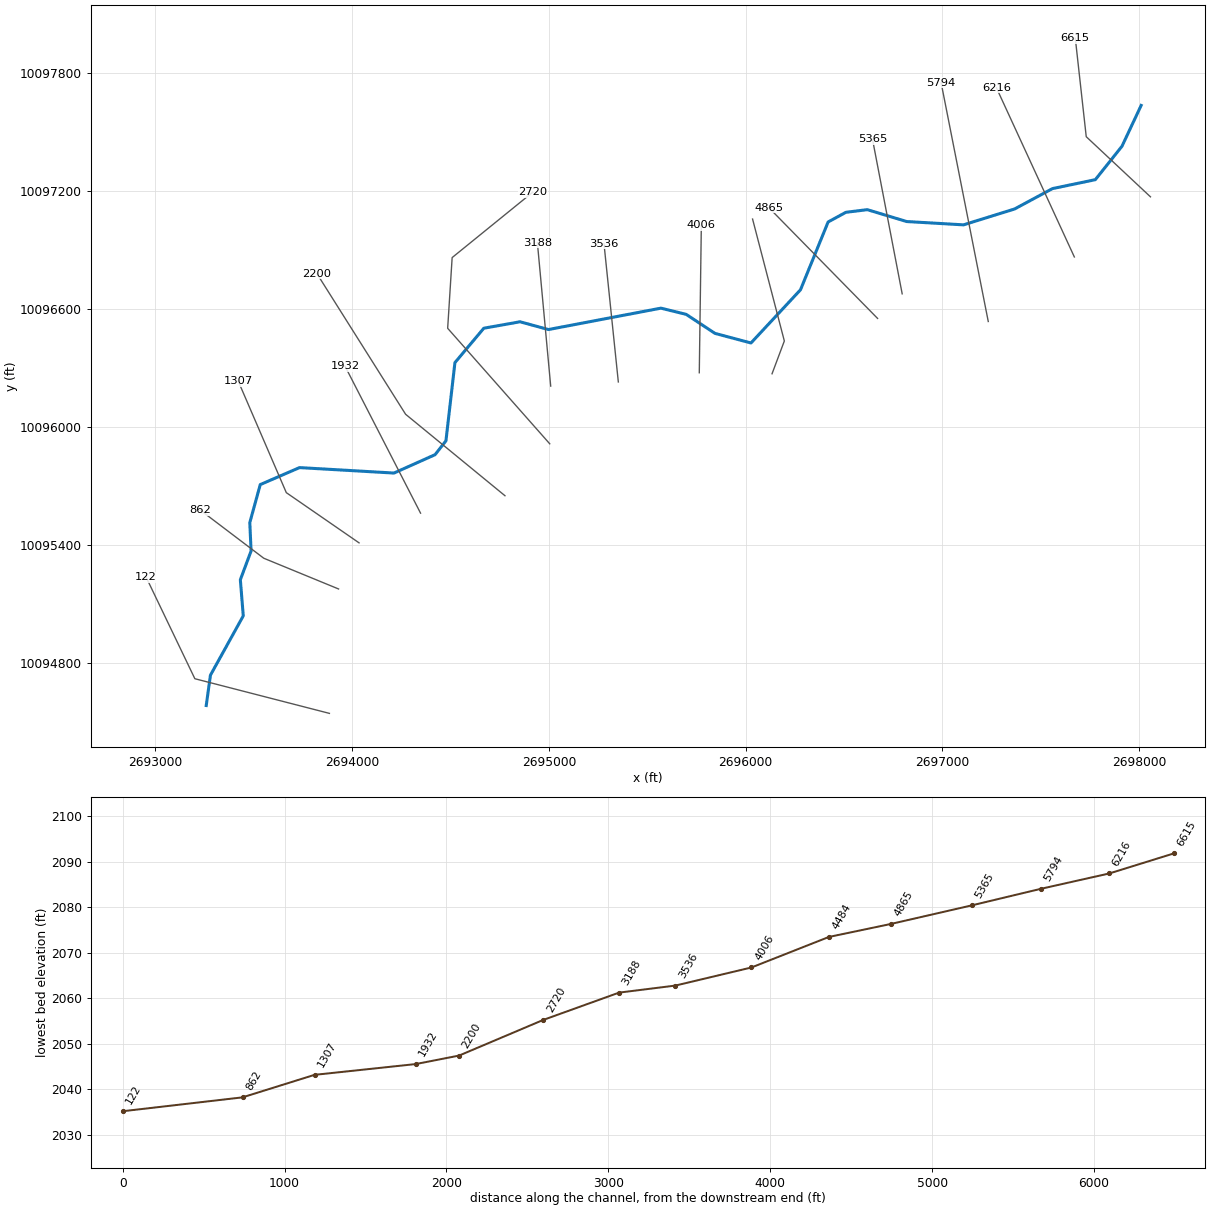
--- ADOBE CREEK.prj (project) ---

Proj Title=ADOBE CREEK Base Level Engineering
Current Plan=p01
Default Exp/Contr=0.3,0.1
English Units
Geom File=g01
Flow File=f01
Plan File=p01
Y Axis Title=Elevation
X Axis Title(PF)=Main Channel Distance
X Axis Title(XS)=Station
BEGIN DESCRIPTION:
ADOBE CREEK
END DESCRIPTION:
DSS Export Rating Curves= 0
DSS Export Rating Curve Sorted= 0
DSS Export Volume Flow Curves= 0
DXF OffsetX= 0
DXF OffsetY= 0
DXF ScaleX= 1
DXF ScaleY= 10

--- ADOBE CREEK.p01 (plan) ---

Plan Title=Multiple Run
Short Identifier=Multiple
Geom File=g01
Flow File=f01
Subcritical Flow
K Sum by GR= 0
Std Step Tol= 0.01
Critical Tol= 0.01
Num of Std Step Trials= 20
Max Error Tol= 0.3
Flow Tol Ratio= 0.001
Split Flow NTrial= 30
Split Flow Tol= 0.02
Split Flow Ratio= 0.02
Log Output Level= 0
Friction Slope Method= 1
Unsteady Friction Slope Method= 2
Unsteady Bridges Friction Slope Method= 1
Parabolic Critical Depth
Global Vel Dist=  1 , 1 , 1
Global Log Level= 0
CheckData=True
Encroach Param= -1, 0, 0, 0
BEGIN DESCRIPTION:
Multiple Run
END DESCRIPTION:

--- ADOBE CREEK.f01 (steady flow) ---

Flow Title=Multiple
Program Version=4.10
Number of Profiles= 7
Profile Names=10-year,25-year,50-year,1pct_min,100-year,1pct_plu,500-year
River Rch & RM=ADOBE CREEK,Reach-1         ,6615
    1225    1787    2273    2106    2849    3852    4473
River Rch & RM=ADOBE CREEK,Reach-1         ,5365
    1928    2877    3716    3490    4719    6382    7619
Boundary for River Rch & Prof#=ADOBE CREEK,Reach-1         , 1
Up Type= 0
Dn Type= 3
Dn Slope=0.004
Boundary for River Rch & Prof#=ADOBE CREEK,Reach-1         , 2
Up Type= 0
Dn Type= 3
Dn Slope=0.004
Boundary for River Rch & Prof#=ADOBE CREEK,Reach-1         , 3
Up Type= 0
Dn Type= 3
Dn Slope=0.004
Boundary for River Rch & Prof#=ADOBE CREEK,Reach-1         , 4
Up Type= 0
Dn Type= 3
Dn Slope=0.004
Boundary for River Rch & Prof#=ADOBE CREEK,Reach-1         , 5
Up Type= 0
Dn Type= 3
Dn Slope=0.004
Boundary for River Rch & Prof#=ADOBE CREEK,Reach-1         , 6
Up Type= 0
Dn Type= 3
Dn Slope=0.004
Boundary for River Rch & Prof#=ADOBE CREEK,Reach-1         , 7
Up Type= 0
Dn Type= 3
Dn Slope=0.004
DSS Import GetInterval= 0
DSS Import GetPeak= 0
DSS Import FillOption= 0

--- ADOBE CREEK.g01 (geometry) ---

Geom Title=Existing Conditions
Program Version=4.10

River Reach=ADOBE CREEK     ,Reach-1
Reach XY= 30
      2698010.28     10097633.83      2697912.85     10097426.47
      2697777.45     10097256.46      2697559.61     10097211.09
      2697366.91     10097107.49      2697107.42     10097026.83
      2696818.47     10097043.73      2696618.45     10097104.02
      2696509.74     10097090.66      2696419.21     10097041.33
      2696278.76     10096696.68      2696027.27     10096426.47
      2695844.14     10096475.35      2695697.75       10096572.
      2695569.41     10096603.45      2694997.84     10096494.72
      2694853.55     10096534.21      2694669.31     10096501.43
      2694522.54     10096326.65      2694476.82     10095929.21
      2694421.34     10095858.59      2694212.76     10095765.35
      2693732.68      10095793.1      2693533.09     10095706.73
      2693479.92     10095513.17       2693486.5     10095369.35
      2693431.88     10095223.12      2693446.79      10095039.5
      2693279.93     10094738.14      2693258.47     10094583.73

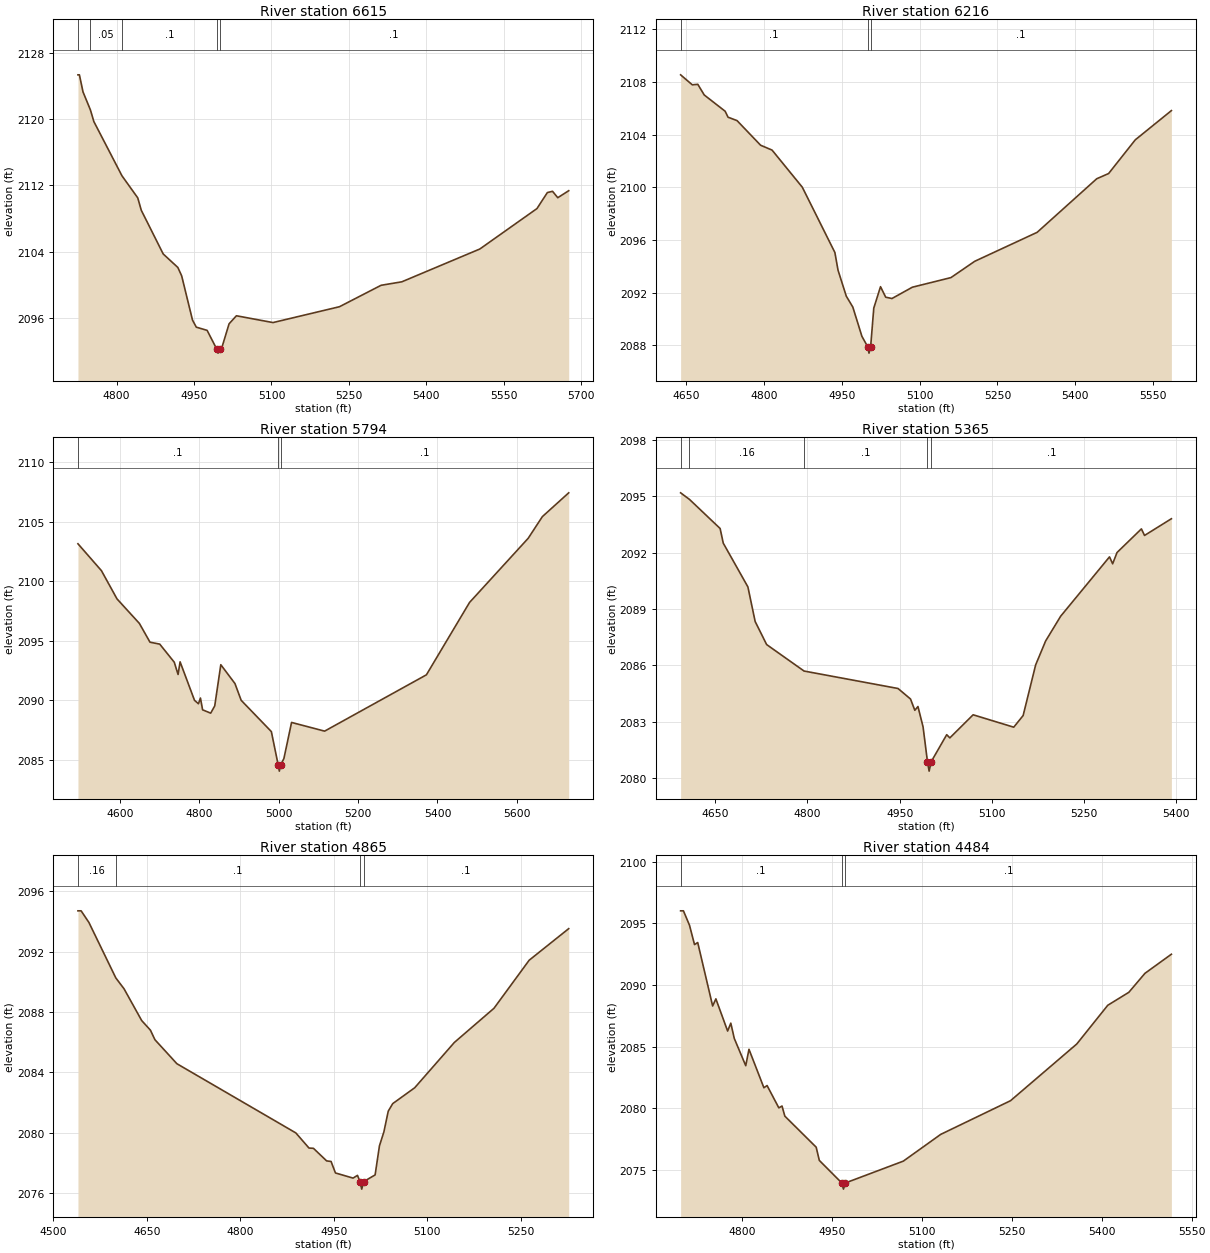
Type RM Length L Ch R = 1 ,6615    ,399,399,399
BEGIN DESCRIPTION:
Mapping XS 1d3842be
END DESCRIPTION:
XS GIS Cut Line= 3
      2698057.59     10097169.25      2697731.19     10097474.82
      2697675.63     10097974.82
#Sta/Elev= 30
  4725.3 2125.33  4728.1 2125.33  4735.1 2123.27  4749.4 2121.11  4756.1  2119.7
  4810.5 2113.17  4841.1 2110.51  4847.9 2109.02  4890.4 2103.75  4918.7 2102.13
  4926.1 2101.12  4947.1 2095.79  4954.4 2094.94  4975.4 2094.55  4993.9 2092.31
  4996.6 2091.81  4999.9 2092.31  5003.7 2092.43  5017.9 2095.34  5032.1 2096.31
  5102.9 2095.49  5231.7  2097.4  5312.2 2099.98  5352.4  2100.4  5503.4 2104.35
    5614 2109.22  5634.2 2111.15  5644.2  2111.3  5654.3 2110.53  5675.5 2111.37
#Mann= 5 ,-1 , 0
  4725.3      .1       0  4749.4     .05       0  4810.5      .1       0
  4993.9     .07       0  4999.9      .1       0
Bank Sta=4993.9,4999.9
XS Rating Curve= 0 ,0
Exp/Cntr=0.3,0.1

Type RM Length L Ch R = 1 ,6216    ,422,422,422
BEGIN DESCRIPTION:
ADOBE CREEK 14.0
END DESCRIPTION:
XS GIS Cut Line= 2
      2697670.73     10096863.64      2697274.88     10097723.06
#Sta/Elev= 30
  4639.1 2108.55  4661.6 2107.79  4672.2 2107.83  4684.6 2107.02    4725 2105.78
  4730.5 2105.33  4747.9 2105.07  4793.3  2103.2  4815.4 2102.83  4873.7 2100.01
  4936.5 2095.05  4942.6  2093.7  4958.5 2091.73  4971.1  2090.9  4988.6 2088.68
  4999.5  2087.9  5002.3  2087.4  5005.5  2087.9  5011.5 2090.82  5024.5 2092.45
  5034.5 2091.65  5046.6 2091.55  5085.9 2092.41  5160.3 2093.14  5206.2 2094.38
  5326.5 2096.58  5441.3 2100.65  5464.3 2101.05  5515.7 2103.61  5585.3 2105.83
#Mann= 3 ,-1 , 0
  4639.1      .1       0  4999.5     .07       0  5005.5      .1       0
Bank Sta=4999.5,5005.5
XS Rating Curve= 0 ,0
Exp/Cntr=0.3,0.1

Type RM Length L Ch R = 1 ,5794    ,429,429,429
BEGIN DESCRIPTION:
ADOBE CREEK 13.0
END DESCRIPTION:
XS GIS Cut Line= 2
       2697233.2     10096535.61      2696993.67     10097748.89
#Sta/Elev= 30
    4494 2103.13  4553.2 2100.87  4592.4  2098.5  4648.8 2096.44  4675.6 2094.86
  4700.1  2094.7  4736.7 2093.18  4746.3 2092.15  4751.4 2093.21  4787.7 2089.98
  4797.6 2089.69  4802.7 2090.17  4808.1 2089.18  4828.5  2088.9  4838.7 2089.51
    4854 2092.97  4889.6 2091.39  4905.3 2089.98  4981.4 2087.35  4998.7 2084.53
  5001.5 2084.03  5004.7 2084.53    5013 2085.09  5032.3 2088.12  5115.6 2087.39
  5372.1 2092.12  5480.8  2098.2  5628.6 2103.59  5664.3 2105.41  5730.7 2107.41
#Mann= 3 ,-1 , 0
    4494      .1       0  4998.7     .07       0  5004.7      .1       0
Bank Sta=4998.7,5004.7
XS Rating Curve= 0 ,0
Exp/Cntr=0.3,0.1

Type RM Length L Ch R = 1 ,5365    ,500,500,500
BEGIN DESCRIPTION:
ADOBE CREEK 12.0
END DESCRIPTION:
XS GIS Cut Line= 2
      2696795.71     10096676.21      2696645.05     10097460.68
#Sta/Elev= 30
  4593.5 2095.19  4607.9 2094.84  4657.8 2093.29  4662.9 2092.51    4703 2090.18
  4714.8 2088.34  4733.5 2087.11  4794.4  2085.7  4947.4 2084.77  4967.7 2084.21
  4974.7 2083.61  4979.8 2083.81  4988.1 2082.73  4995.3 2080.87    4998 2080.37
  5001.3 2080.87  5026.6 2082.31  5031.7 2082.14  5069.6 2083.37  5135.7 2082.71
    5151 2083.33  5171.4 2086.03  5187.6  2087.3  5212.1 2088.62  5291.6 2091.78
  5296.7 2091.41  5303.8 2092.01  5343.5 2093.27  5348.6 2092.92  5392.3 2093.81
#Mann= 5 ,-1 , 0
  4593.5      .1       0  4607.9     .16       0  4794.4      .1       0
  4995.3     .07       0  5001.3      .1       0
Bank Sta=4995.3,5001.3
XS Rating Curve= 0 ,0
Exp/Cntr=0.3,0.1

Type RM Length L Ch R = 1 ,4865    ,381,381,381
BEGIN DESCRIPTION:
ADOBE CREEK 11.0
END DESCRIPTION:
XS GIS Cut Line= 2
      2696670.69     10096551.21      2696118.65     10097113.66
#Sta/Elev= 30
  4539.3  2094.7  4544.4  2094.7  4556.9 2093.93  4600.1 2090.26  4613.3 2089.54
  4641.6 2087.44  4655.7  2086.8  4662.9 2086.17  4698.2 2084.58  4889.2    2080
  4910.3    2079  4917.5 2078.98  4938.6 2078.15  4945.8 2078.11  4952.8 2077.35
  4981.1 2077.01  4988.2 2077.19  4992.2 2076.78    4995 2076.28  4998.2 2076.78
  5016.5 2077.22  5023.5 2079.15  5030.6 2080.07  5037.6 2081.44  5044.8 2081.94
  5080.1 2082.99  5143.8 2085.99  5207.4 2088.25  5263.9 2091.43  5327.4 2093.52
#Mann= 4 ,-1 , 0
  4539.3     .16       0  4600.1      .1       0  4992.2     .07       0
  4998.2      .1       0
Bank Sta=4992.2,4998.2
XS Rating Curve= 0 ,0
Exp/Cntr=0.3,0.1

Type RM Length L Ch R = 1 ,4484    ,478,478,478
BEGIN DESCRIPTION:
ADOBE CREEK 10.0
END DESCRIPTION:
XS GIS Cut Line= 3
      2696134.25     10096269.91      2696196.75      10096436.6
       2696035.3     10097056.39
#Sta/Elev= 30
  4697.7 2096.01  4702.4 2096.01  4712.5 2094.84  4720.9 2093.27  4726.2 2093.44
  4751.1 2088.29  4756.5 2088.87  4776.1 2086.26  4781.4  2086.9  4787.2 2085.66
  4806.3 2083.45  4811.7 2084.78  4836.6 2081.66  4841.9 2081.84  4861.5 2080.03
  4866.8 2080.18  4871.5 2079.36  4923.8 2076.84    4929 2075.77  4966.5 2073.94
  4969.3 2073.44  4972.5 2073.94  5069.1 2075.71  5131.5 2077.88  5247.9 2080.61
  5358.4 2085.21  5410.1 2088.35  5445.2  2089.4  5472.1 2090.94  5516.2 2092.49
#Mann= 3 ,-1 , 0
  4697.7      .1       0  4966.5     .07       0  4972.5      .1       0
Bank Sta=4966.5,4972.5
XS Rating Curve= 0 ,0
Exp/Cntr=0.3,0.1

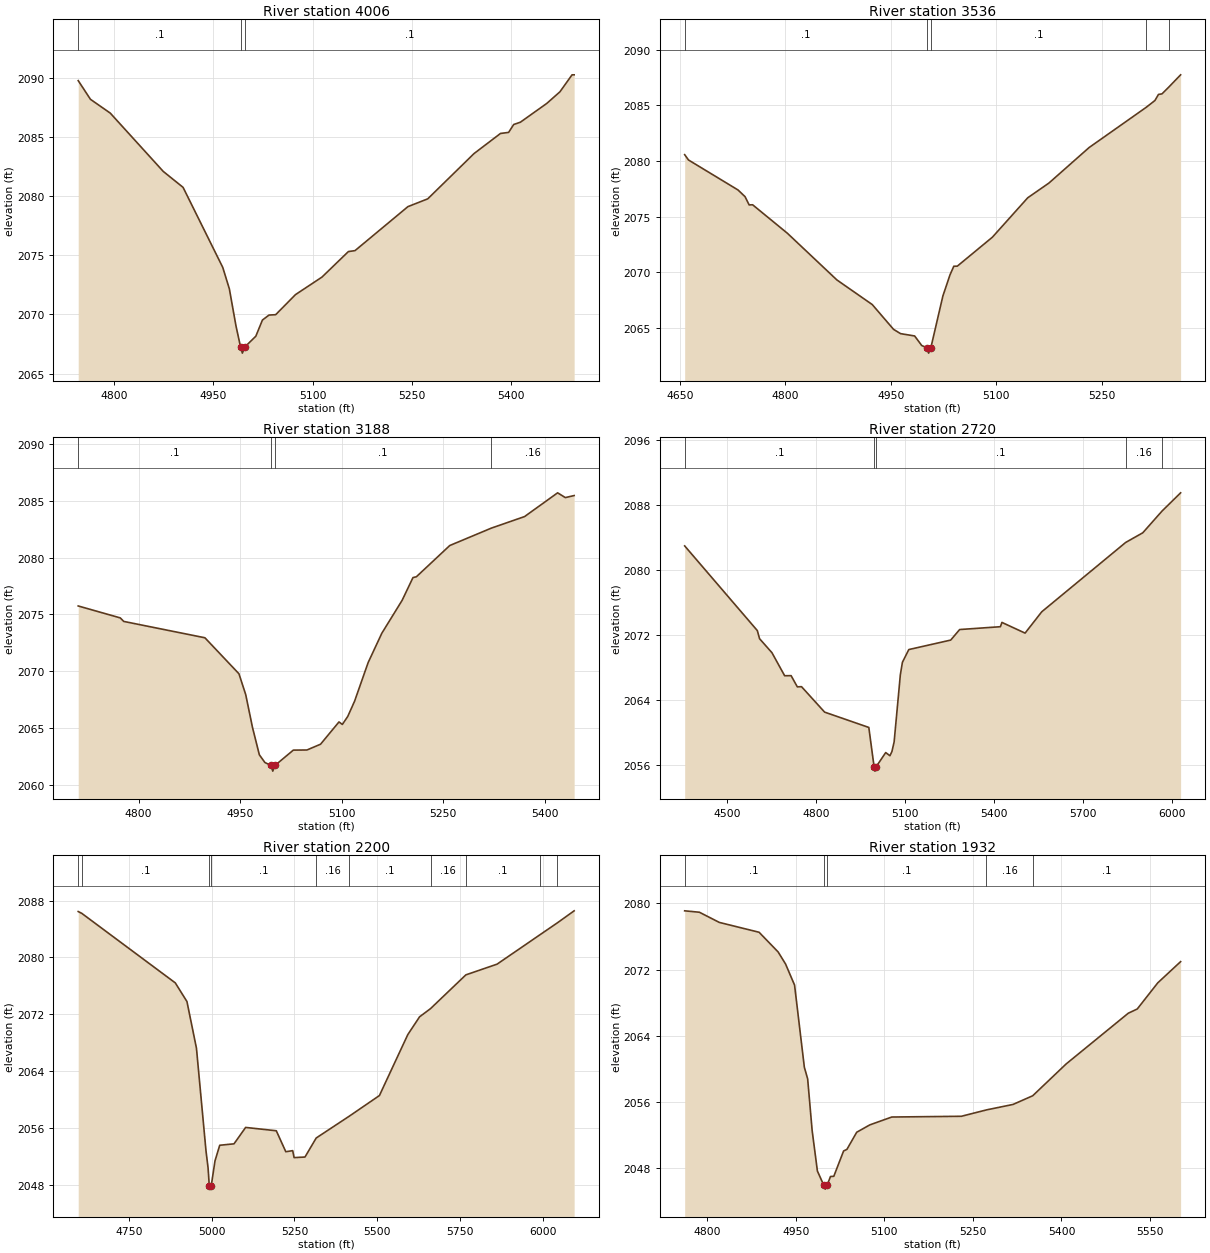
Type RM Length L Ch R = 1 ,4006    ,470,470,470
BEGIN DESCRIPTION:
ADOBE CREEK 9.0
END DESCRIPTION:
XS GIS Cut Line= 2
      2695764.46     10096275.19      2695774.88     10097025.12
#Sta/Elev= 30
  4745.6 2089.78  4764.1  2088.2  4794.1 2087.03  4874.2  2082.1  4904.2 2080.75
  4964.2 2073.98  4974.2 2072.16  4984.2 2069.03  4991.2 2067.23  4993.9 2066.73
  4997.2 2067.23  5014.2 2068.16  5024.2 2069.53  5034.2 2069.95  5044.2 2069.98
  5074.2 2071.68  5114.2 2073.16  5154.2 2075.32  5164.2  2075.4  5244.2 2079.12
  5274.2 2079.78  5344.2 2083.61  5384.2 2085.31  5396.5  2085.4  5404.2 2086.07
  5414.2 2086.26  5454.2 2087.85  5474.2 2088.84  5492.4 2090.27  5495.6 2090.27
#Mann= 3 ,-1 , 0
  4745.6      .1       0  4991.2     .07       0  4997.2      .1       0
Bank Sta=4991.2,4997.2
XS Rating Curve= 0 ,0
Exp/Cntr=0.3,0.1

Type RM Length L Ch R = 1 ,3536    ,348,348,348
BEGIN DESCRIPTION:
ADOBE CREEK 8.0
END DESCRIPTION:
XS GIS Cut Line= 2
        2695353.     10096228.27      2695280.22      10096930.1
#Sta/Elev= 30
  4656.8 2080.57  4662.3 2080.09  4732.7  2077.4  4742.7  2076.8  4748.5 2076.06
  4753.5 2076.07    4803 2073.51  4873.4 2069.32  4923.7 2067.11  4953.9 2064.89
  4963.9  2064.5    4984 2064.29  4994.1 2063.43  5001.1 2063.25  5003.9 2062.75
  5007.1 2063.25  5024.2 2067.89  5034.3 2069.78  5039.7 2070.55  5044.7 2070.56
  5094.6 2073.16  5144.9  2076.7    5175 2078.02  5232.2 2081.21  5313.4 2084.82
  5325.8 2085.43  5330.9 2085.98  5335.9 2086.03  5345.6 2086.64  5362.4 2087.74
#Mann= 5 ,-1 , 0
  4656.8      .1       0  5001.1     .07       0  5007.1      .1       0
  5313.4     .16       0  5345.6      .1       0
Bank Sta=5001.1,5007.1
XS Rating Curve= 0 ,0
Exp/Cntr=0.3,0.1

Type RM Length L Ch R = 1 ,3188    ,468,468,468
BEGIN DESCRIPTION:
ADOBE CREEK 7.0
END DESCRIPTION:
XS GIS Cut Line= 2
      2695009.26     10096207.39      2694941.54     10096936.65
#Sta/Elev= 30
  4710.9 2075.74    4773 2074.69  4778.1 2074.38    4898 2072.94  4948.3 2069.77
  4958.3 2067.93  4968.3 2065.04  4978.4 2062.64  4986.6 2061.96  4995.5  2061.7
  4998.2  2061.2  5001.5  2061.7  5028.6 2063.05  5048.7 2063.06  5068.8 2063.57
    5096 2065.53    5101 2065.31    5109 2066.02    5119 2067.35  5139.1 2070.76
  5159.2 2073.33  5189.3 2076.24  5205.3 2078.24  5210.3 2078.31  5259.6 2081.06
  5320.9 2082.59  5370.1 2083.61  5418.9  2085.7  5430.3 2085.28  5443.3 2085.46
#Mann= 4 ,-1 , 0
  4710.9      .1       0  4995.5     .07       0  5001.5      .1       0
  5320.9     .16       0
Bank Sta=4995.5,5001.5
XS Rating Curve= 0 ,0
Exp/Cntr=0.3,0.1

Type RM Length L Ch R = 1 ,2720    ,520,520,520
BEGIN DESCRIPTION:
ADOBE CREEK 6.0
END DESCRIPTION:
XS GIS Cut Line= 4
       2695004.4     10095914.01      2694485.63     10096501.05
      2694508.38     10096860.53      2694917.88     10097192.69
#Sta/Elev= 30
  4357.8 2082.99  4602.6 2072.54  4610.1 2071.54  4651.9 2069.81  4694.6 2066.97
  4716.4 2066.98  4737.3  2065.6  4751.5 2065.62  4829.3 2062.48  4978.2 2060.59
  4996.1  2055.7  4998.8  2055.2  5002.1  2055.7  5035.1 2057.49  5049.3  2057.1
    5056 2057.61  5063.5 2058.81  5084.4 2067.08  5091.4 2068.63  5112.9  2070.2
  5254.1 2071.37  5284.2 2072.67  5421.6 2073.02  5426.6 2073.55  5504.7 2072.23
  5560.8 2074.86  5843.7 2083.42  5901.3 2084.61  5966.1 2087.29  6028.7 2089.54
#Mann= 5 ,-1 , 0
  4357.8      .1       0  4996.1     .07       0  5002.1      .1       0
  5843.7     .16       0  5966.1      .1       0
Bank Sta=4996.1,5002.1
XS Rating Curve= 0 ,0
Exp/Cntr=0.3,0.1

Type RM Length L Ch R = 1 ,2200    ,268,268,268
BEGIN DESCRIPTION:
ADOBE CREEK 5.0
END DESCRIPTION:
XS GIS Cut Line= 3
      2694776.86     10095650.11      2694271.75      10096064.2
      2693821.28     10096778.59
#Sta/Elev= 30
  4597.1 2086.46    4608  2086.2  4890.3 2076.41  4925.5 2073.78  4954.2 2067.21
  4982.9  2052.8  4989.3 2050.34  4992.9 2047.86  4995.6 2047.36  4998.9 2047.86
  5010.2 2051.35  5024.5 2053.54  5067.6 2053.74  5102.7 2056.05  5195.3 2055.58
    5224 2052.63  5244.8 2052.78  5249.1  2051.8  5281.9 2051.88  5315.8 2054.56
  5416.2 2057.65  5506.7 2060.54  5592.5 2069.13    5628 2071.63  5661.2 2072.79
  5767.8 2077.54  5862.1 2079.05  5992.5 2083.22  6043.9 2084.86  6094.8 2086.56
#Mann= 10 ,-1 , 0
  4597.1     .16       0    4608      .1       0  4992.9     .07       0
  4998.9      .1       0  5315.8     .16       0  5416.2      .1       0
  5661.2     .16       0  5767.8      .1       0  5992.5     .16       0
  6043.9      .1       0
Bank Sta=4992.9,4998.9
XS Rating Curve= 0 ,0
Exp/Cntr=0.3,0.1

Type RM Length L Ch R = 1 ,1932    ,625,625,625
BEGIN DESCRIPTION:
ADOBE CREEK 4.0
END DESCRIPTION:
XS GIS Cut Line= 2
      2694347.79     10095561.61      2693963.67     10096309.09
#Sta/Elev= 30
  4761.5 2079.11  4786.4 2078.94  4820.2 2077.71  4887.6 2076.52  4919.9 2074.14
  4932.5 2072.68  4947.7 2070.14  4964.3 2060.21  4969.9 2058.81  4977.5 2052.57
  4986.4 2047.68    4997 2045.99  4999.7 2045.49    5003 2045.99  5008.6 2047.01
  5014.2 2047.04  5030.8  2050.1  5036.4 2050.29    5053 2052.36  5075.2 2053.25
  5112.4  2054.2  5230.4 2054.29  5272.9 2055.06  5317.9 2055.72  5351.3 2056.77
  5407.9 2060.61  5513.2 2066.74  5528.4 2067.25  5563.2 2070.41  5601.9 2072.97
#Mann= 5 ,-1 , 0
  4761.5      .1       0    4997     .07       0    5003      .1       0
  5272.9     .16       0  5351.3      .1       0
Bank Sta=4997,5003
XS Rating Curve= 0 ,0
Exp/Cntr=0.3,0.1

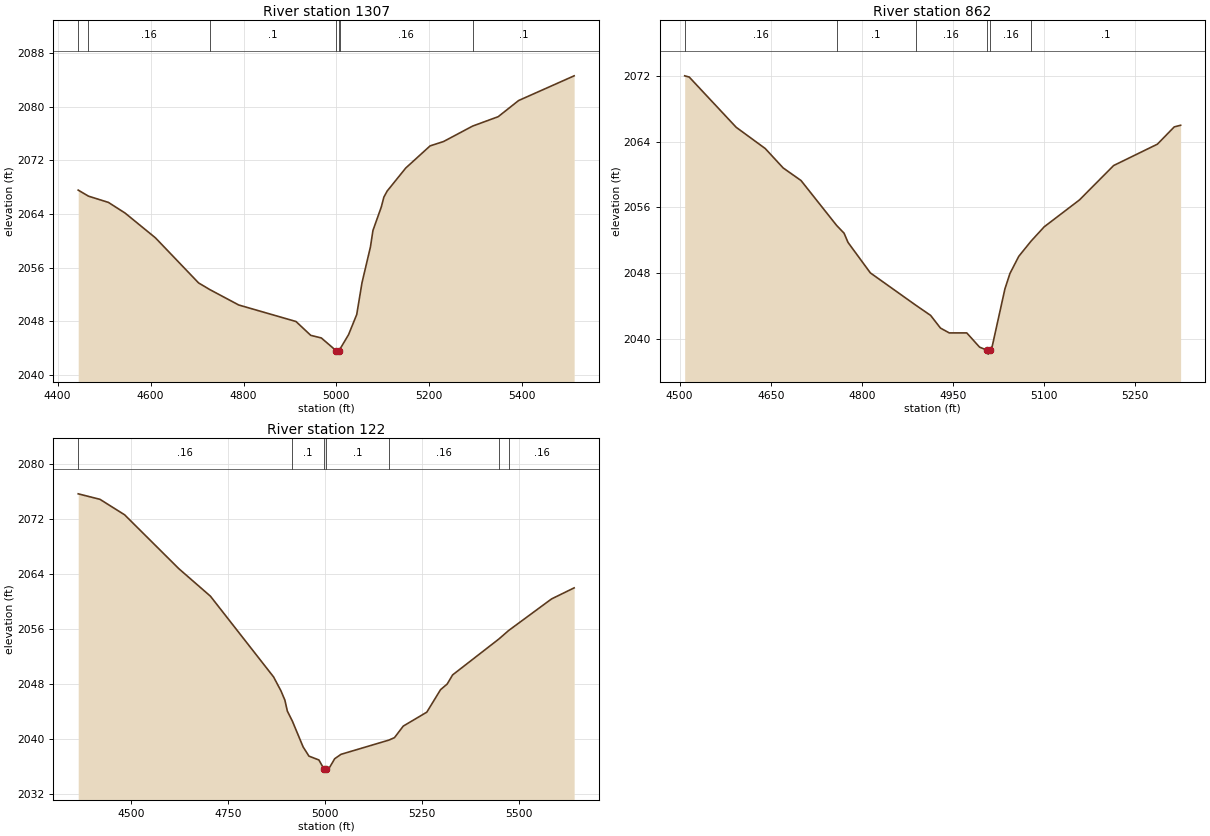
Type RM Length L Ch R = 1 ,1307    ,445,445,445
BEGIN DESCRIPTION:
ADOBE CREEK 3.0
END DESCRIPTION:
XS GIS Cut Line= 3
      2694035.26     10095410.58       2693665.5     10095665.77
      2693420.71     10096233.47
#Sta/Elev= 30
  4444.2 2067.56  4466.3 2066.66  4509.2 2065.73  4545.1 2064.14  4610.4 2060.45
  4703.3 2053.73  4727.4 2052.74  4789.8 2050.44    4913 2047.98  4944.7 2045.92
  4967.5 2045.53  4999.6 2043.62  5002.4 2043.12  5005.6 2043.62  5006.7 2043.76
  5026.1 2046.02  5043.7 2049.02  5055.1 2053.78  5073.2 2059.09  5078.6 2061.54
  5096.7 2065.07  5102.1 2066.51  5109.1 2067.41  5149.2 2070.85  5201.6 2074.15
  5230.6  2074.8  5293.1  2077.1  5348.2  2078.5  5392.2 2080.91  5511.7 2084.59
#Mann= 7 ,-1 , 0
  4444.2      .1       0  4466.3     .16       0  4727.4      .1       0
  4999.6     .07       0  5005.6      .1       0  5006.7     .16       0
  5293.1      .1       0
Bank Sta=4999.6,5005.6
XS Rating Curve= 0 ,0
Exp/Cntr=0.3,0.1

Type RM Length L Ch R = 1 ,862     ,740,740,740
BEGIN DESCRIPTION:
ADOBE CREEK 2.0
END DESCRIPTION:
XS GIS Cut Line= 3
      2693931.13     10095176.18      2693550.92     10095332.43
      2693227.99     10095577.24
#Sta/Elev= 30
  4508.4 2072.01  4515.9 2071.86  4593.2 2065.75    4641 2063.17  4670.5 2060.81
  4699.9 2059.28  4758.6 2053.81  4770.8 2052.87  4777.2 2051.76    4814 2048.05
  4888.4 2044.14  4913.2 2042.88  4929.4 2041.34  4943.9 2040.75  4972.7 2040.75
  4993.8 2039.02  5005.4 2038.67  5008.1 2038.17  5011.4 2038.67  5014.7 2039.15
  5035.5  2046.1  5043.8 2047.98  5058.3 2050.06  5078.3 2051.89    5100 2053.64
  5158.2 2056.92  5214.4  2061.1  5286.5  2063.7  5314.2  2065.8  5324.7    2066
#Mann= 6 ,-1 , 0
  4508.4     .16       0  4758.6      .1       0  4888.4     .16       0
  5005.4     .07       0  5011.4     .16       0  5078.3      .1       0
Bank Sta=5005.4,5011.4
XS Rating Curve= 0 ,0
Exp/Cntr=0.3,0.1

Type RM Length L Ch R = 1 ,122     ,0,0,0
BEGIN DESCRIPTION:
ADOBE CREEK 1.0
END DESCRIPTION:
XS GIS Cut Line= 3
      2693884.51     10094543.91      2693200.69     10094720.08
      2692952.99     10095236.28
#Sta/Elev= 30
    4364 2075.63  4420.1 2074.83  4483.8 2072.57  4623.5 2064.73  4704.9 2060.73
  4867.7 2048.98  4886.6 2046.97  4896.9  2045.6  4903.2 2044.01  4916.3 2042.53
  4943.9 2038.79  4958.9 2037.45  4984.6 2036.89  4997.2 2035.62  4999.9 2035.12
  5003.2 2035.62  5010.5 2035.65  5025.3 2037.07  5041.5 2037.71  5164.9 2039.78
  5179.4 2040.14  5202.1 2041.82  5262.8 2043.85  5298.2 2047.12  5315.3 2047.94
  5329.3 2049.27  5448.7  2054.5  5473.7 2055.73  5584.4 2060.33  5642.7 2061.94
#Mann= 7 ,-1 , 0
    4364     .16       0  4916.3      .1       0  4997.2     .07       0
  5003.2      .1       0  5164.9     .16       0  5448.7      .1       0
  5473.7     .16       0
Bank Sta=4997.2,5003.2
XS Rating Curve= 0 ,0
Exp/Cntr=0.3,0.1

Chan Stop Cuts=-1
Use User Specified Reach Order=0
Composite Channel Slope=5