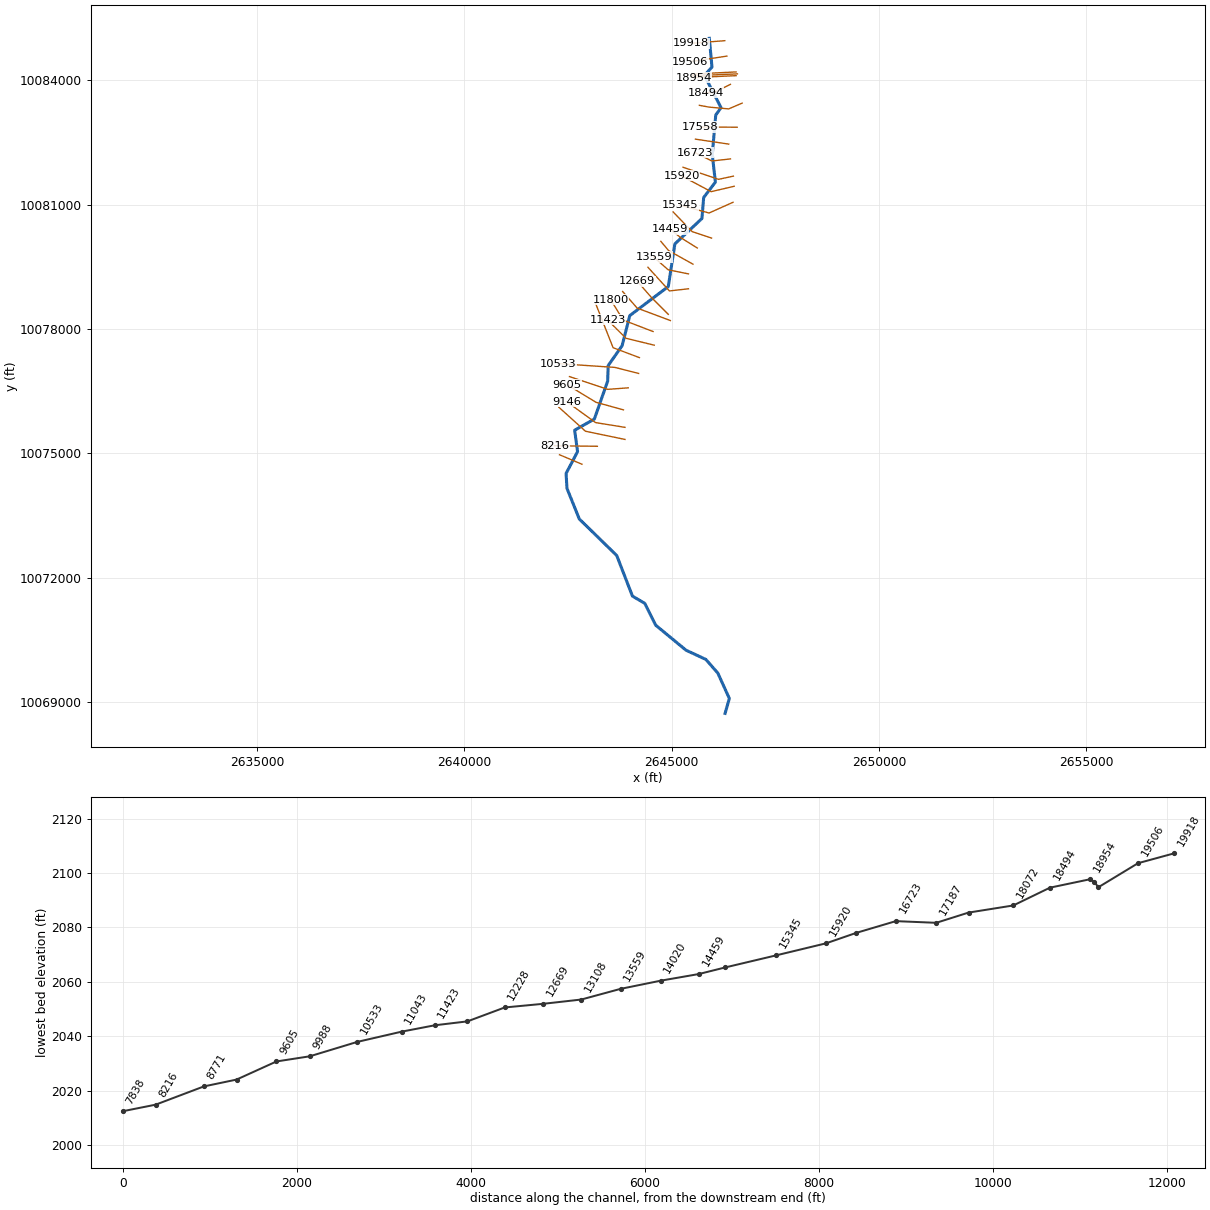
--- BANTA BRANCH.prj (project) ---

Proj Title=BANTA BRANCH Base Level Engineering
Current Plan=p01
Default Exp/Contr=0.3,0.1
English Units
Geom File=g01
Flow File=f01
Plan File=p01
BEGIN DESCRIPTION:
BANTA BRANCH
END DESCRIPTION:

--- BANTA BRANCH.p01 (plan) ---

Plan Title=Multiple Run
Short Identifier=Multiple
Geom File=g01
Flow File=f01
Subcritical Flow
K Sum by GR= 0
Std Step Tol= 0.01
Critical Tol= 0.01
Num of Std Step Trials= 20
Max Error Tol= 0.3
Flow Tol Ratio= 0.001
Split Flow NTrial= 30
Split Flow Tol= 0.02
Split Flow Ratio= 0.02
Log Output Level= 0
Friction Slope Method= 1
Unsteady Friction Slope Method= 2
Unsteady Bridges Friction Slope Method= 1
Parabolic Critical Depth
Global Vel Dist=  1 , 1 , 1
Global Log Level= 0
CheckData=True
Encroach Param= -1, 0, 0, 0
BEGIN DESCRIPTION:
Multiple Run
END DESCRIPTION:

--- BANTA BRANCH.f01 (steady flow) ---

Flow Title=Multiple
Number of Profiles=7
Profile Names=10-year,25-year,50-year,1pct_min,100-year,1pct_plu,500-year
River Rch & RM= BANTA BRANCH,Reach-1,19918
    1819    2705    3483    3261    4410    5964    7078
River Rch & RM= BANTA BRANCH,Reach-1,14760
    2155    3225    4171    3918    5299    7167    8566
River Rch & RM= BANTA BRANCH,Reach-1,10533
    2675    4037    5250    4956    6703    9065   10942
River Rch & RM= BANTA BRANCH,Reach-1,7447
    2783    4213    5491    5195    7026    9502   11519
River Rch & RM= BANTA BRANCH,Reach-1,5542
    2972    4509    5884    5574    7538   10194   12387
River Rch & RM= BANTA BRANCH,Reach-1,518
    3404    5195    6808    6472    8753   11838   14492
Boundary for River Rch & Prof#=BANTA BRANCH,Reach-1,1
Up Type=0
Dn Type=3
Dn Slope=0.005
Boundary for River Rch & Prof#=BANTA BRANCH,Reach-1,2
Up Type=0
Dn Type=3
Dn Slope=0.005
Boundary for River Rch & Prof#=BANTA BRANCH,Reach-1,3
Up Type=0
Dn Type=3
Dn Slope=0.005
Boundary for River Rch & Prof#=BANTA BRANCH,Reach-1,4
Up Type=0
Dn Type=3
Dn Slope=0.005
Boundary for River Rch & Prof#=BANTA BRANCH,Reach-1,5
Up Type=0
Dn Type=3
Dn Slope=0.005
Boundary for River Rch & Prof#=BANTA BRANCH,Reach-1,6
Up Type=0
Dn Type=3
Dn Slope=0.005
Boundary for River Rch & Prof#=BANTA BRANCH,Reach-1,7
Up Type=0
Dn Type=3
Dn Slope=0.005

--- BANTA BRANCH.g01 (geometry) ---

Geom Title=Existing Conditions

River Reach=BANTA BRANCH,Reach-1
Reach XY= 30
      2645908.47     10085013.73      2645972.56     10084319.91
      2645790.09     10084119.00      2646190.87     10083340.41
      2646063.43     10083163.34      2645979.22     10082208.90
      2646055.49     10081544.90      2645772.16     10081172.14
      2645730.43     10080666.14      2645078.47     10080053.73
      2644918.47     10079023.73      2643990.32     10078322.97
      2643804.85     10077595.29      2643469.90     10077118.13
      2643456.80     10076741.60      2643136.44     10075826.96
      2642660.05     10075556.10      2642731.28     10075040.88
      2642454.12     10074513.27      2642475.74     10074152.66
      2642772.35     10073415.27      2643675.85     10072532.65
      2644054.73     10071553.23      2644351.32     10071379.18
      2644615.31     10070851.36      2645345.84     10070248.77
      2645825.10     10070025.63      2646113.50     10069696.22
      2646391.53     10069083.34      2646288.47     10068723.73

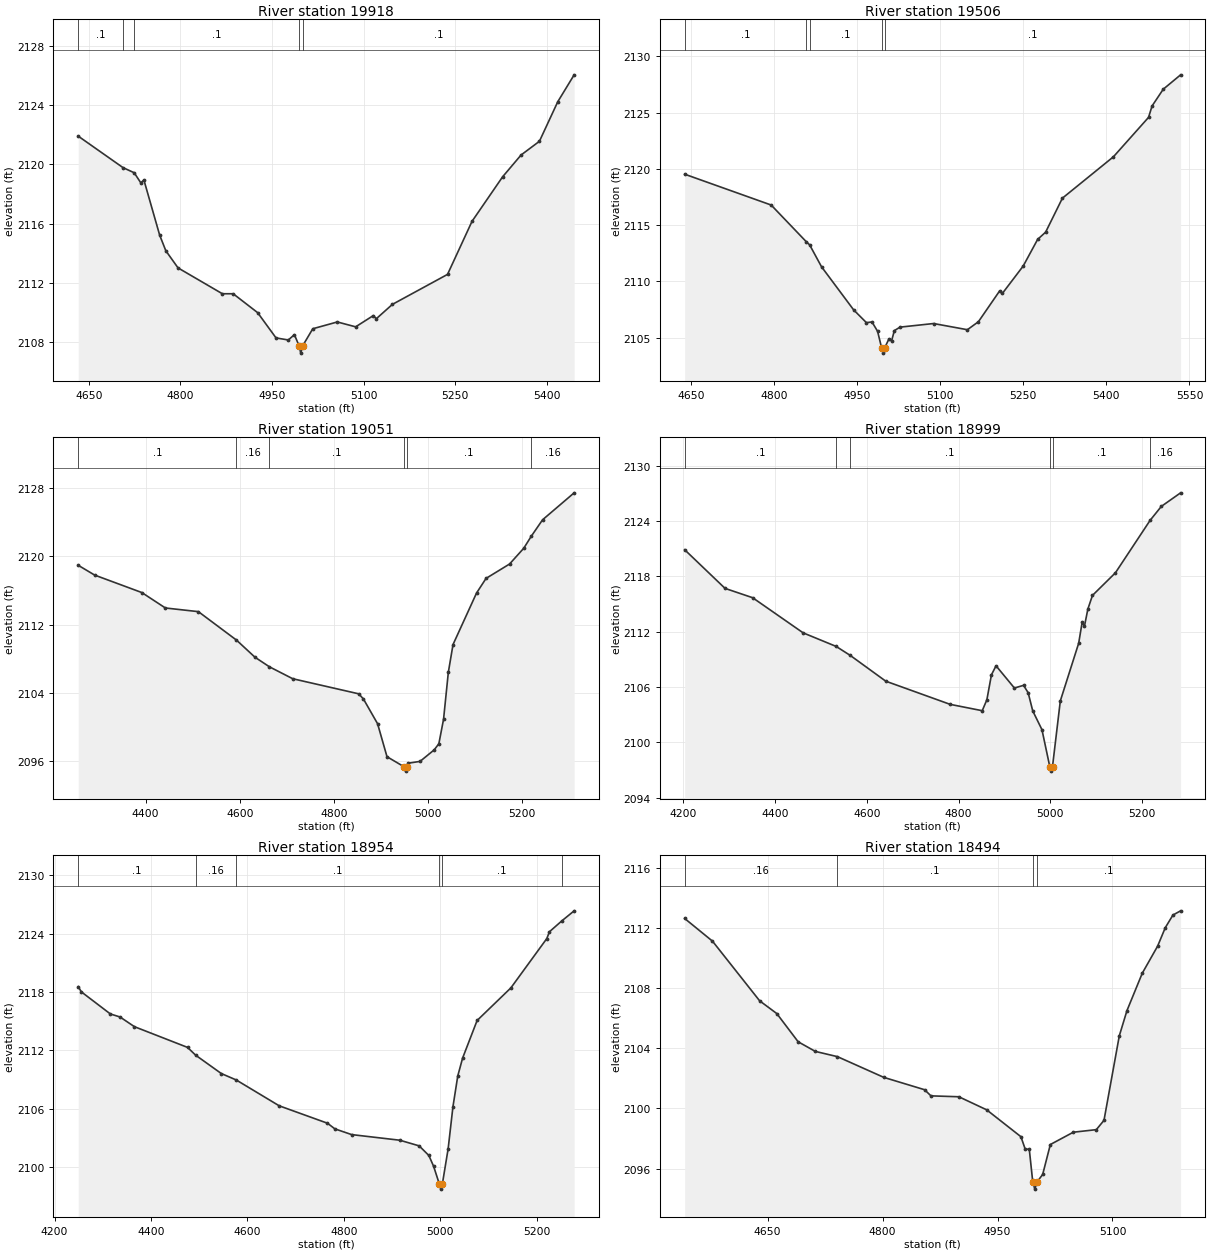
Type RM Length L Ch R = 1,19918,412,412,412
BEGIN DESCRIPTION:
BANTA BRANCH 44.0
END DESCRIPTION:
XS GIS Cut Line= 2
      2646281.50     10084957.15      2645471.73     10084893.07
#Sta/Elev= 30
  4632.5 2121.92  4705.8 2119.79  4724.2 2119.44  4735.0 2118.76  4740.1 2118.95
  4765.9 2115.22  4776.0 2114.16  4796.0 2113.00  4868.6 2111.25  4886.3 2111.25
  4926.4 2109.97  4956.5 2108.26  4976.6 2108.12  4986.6 2108.48  4994.2 2107.73
  4997.0 2107.23  5000.2 2107.73  5016.7 2108.88  5056.9 2109.34  5086.9 2109.01
  5115.8 2109.77  5120.8 2109.56  5147.1 2110.53  5237.4 2112.56  5277.5 2116.15
  5327.7 2119.17  5357.8 2120.64  5387.9 2121.57  5418.0 2124.25  5444.8 2126.07
#Mann=5,-1,0
  4632.5     0.1       0  4705.8    0.16       0  4724.2     0.1       0
  4994.2    0.07       0  5000.2     0.1       0
Bank Sta=4994.2,5000.2
Exp/Cntr=0.3,0.1

Type RM Length L Ch R = 1,19506,455,455,455
BEGIN DESCRIPTION:
BANTA BRANCH 43.0
END DESCRIPTION:
XS GIS Cut Line= 2
      2646332.85     10084585.22      2645447.45     10084449.81
#Sta/Elev= 30
  4638.3 2119.53  4794.5 2116.79  4857.9 2113.53  4864.0 2113.25  4885.5 2111.30
  4943.5 2107.47  4966.5 2106.34  4976.6 2106.40  4986.7 2105.57  4993.8 2104.13
  4996.6 2103.63  4999.8 2104.13  5006.9 2104.86  5012.0 2104.72  5017.0 2105.63
  5027.2 2105.94  5087.9 2106.26  5148.9 2105.71  5168.8 2106.42  5207.3 2109.17
  5212.3 2108.95  5249.7 2111.37  5275.8 2113.74  5290.2 2114.38  5320.5 2117.40
  5412.7 2121.08  5476.1 2124.58  5482.4 2125.59  5502.6 2127.08  5534.0 2128.36
#Mann=5,-1,0
  4638.3     0.1       0  4857.9    0.16       0  4864.0     0.1       0
  4993.8    0.07       0  4999.8     0.1       0
Bank Sta=4993.8,4999.8
Exp/Cntr=0.3,0.1

Type RM Length L Ch R = 1,19051,52,52,52
BEGIN DESCRIPTION:
Mapping XS 2b5c7267
END DESCRIPTION:
XS GIS Cut Line= 2
      2646553.37     10084203.28      2645501.55     10084151.30
#Sta/Elev= 30
  4257.1 2118.95  4292.0 2117.80  4392.2 2115.75  4442.2 2113.94  4512.3 2113.51
  4593.2 2110.17  4632.5 2108.16  4663.1 2107.04  4712.6 2105.64  4852.7 2103.87
  4862.7 2103.27  4892.8 2100.36  4912.8 2096.49  4949.4 2095.30  4952.2 2094.80
  4955.4 2095.30  4957.4 2095.73  4982.9 2095.94  5012.9 2097.29  5022.9 2098.01
  5032.9 2100.89  5043.0 2106.38  5053.0 2109.65  5103.0 2115.70  5123.1 2117.41
  5173.1 2119.10  5203.2 2120.95  5219.2 2122.36  5243.2 2124.29  5310.2 2127.45
#Mann=6,-1,0
  4257.1     0.1       0  4593.2    0.16       0  4663.1     0.1       0
  4949.4    0.07       0  4955.4     0.1       0  5219.2    0.16       0
Bank Sta=4949.4,4955.4
Exp/Cntr=0.3,0.1

Type RM Length L Ch R = 1,18999,45,45,45
BEGIN DESCRIPTION:
BANTA BRANCH 42.0
END DESCRIPTION:
XS GIS Cut Line= 2
      2646586.40     10084156.41      2645506.52     10084109.53
#Sta/Elev= 30
  4202.9 2120.87  4290.9 2116.68  4351.0 2115.67  4461.1 2111.86  4533.0 2110.39
  4563.9 2109.41  4641.2 2106.62  4781.4 2104.11  4851.4 2103.42  4861.5 2104.60
  4871.5 2107.31  4881.5 2108.29  4921.5 2105.88  4941.5 2106.17  4951.5 2105.37
  4961.5 2103.40  4981.6 2101.36  4998.6 2097.37  5001.3 2096.87  5004.6 2097.37
  5021.6 2104.48  5061.6 2110.73  5069.2 2113.01  5074.2 2112.58  5081.7 2114.45
  5091.7 2115.92  5141.7 2118.37  5217.2 2124.05  5241.8 2125.57  5283.8 2127.04
#Mann=6,-1,0
  4202.9     0.1       0  4533.0    0.16       0  4563.9     0.1       0
  4998.6    0.07       0  5004.6     0.1       0  5217.2    0.16       0
Bank Sta=4998.6,5004.6
Exp/Cntr=0.3,0.1

Type RM Length L Ch R = 1,18954,460,460,460
BEGIN DESCRIPTION:
Mapping XS 3c1d4908
END DESCRIPTION:
XS GIS Cut Line= 2
      2646555.07     10084113.00      2645527.33     10084066.13
#Sta/Elev= 30
  4249.1 2118.55  4255.7 2118.01  4315.8 2115.74  4335.8 2115.43  4365.8 2114.43
  4475.9 2112.30  4492.7 2111.50  4546.0 2109.61  4576.9 2108.95  4666.1 2106.29
  4766.2 2104.50  4781.5 2103.92  4816.3 2103.33  4916.4 2102.75  4956.4 2102.17
  4976.5 2101.18  4986.5 2100.05  4998.4 2098.22  5001.1 2097.72  5004.4 2098.22
  5016.5 2101.87  5026.5 2106.21  5036.5 2109.37  5046.5 2111.20  5076.6 2115.07
  5146.6 2118.42  5221.2 2123.50  5226.7 2124.20  5252.2 2125.31  5277.9 2126.35
#Mann=6,-1,0
  4249.1     0.1       0  4492.7    0.16       0  4576.9     0.1       0
  4998.4    0.07       0  5004.4     0.1       0  5252.2    0.16       0
Bank Sta=4998.4,5004.4
Exp/Cntr=0.3,0.1

Type RM Length L Ch R = 1,18494,422,422,422
BEGIN DESCRIPTION:
BANTA BRANCH 41.0
END DESCRIPTION:
XS GIS Cut Line= 3
      2646418.45     10083903.72      2646018.47     10083703.73
      2645818.46     10083703.73
#Sta/Elev= 30
  4541.7 2112.65  4578.0 2111.14  4639.5 2107.17  4661.9 2106.32  4689.8 2104.44
  4712.2 2103.80  4741.1 2103.45  4801.6 2102.07  4854.7 2101.25  4863.1 2100.84
  4899.5 2100.78  4935.8 2099.91  4980.5 2098.12  4986.1 2097.29  4991.4 2097.29
  4995.9 2095.13  4998.6 2094.63  5001.9 2095.13  5008.9 2095.61  5018.9 2097.60
  5048.9 2098.42  5078.9 2098.59  5088.9 2099.21  5108.9 2104.84  5118.9 2106.52
  5138.9 2109.01  5158.9 2110.81  5168.9 2112.04  5178.9 2112.88  5188.9 2113.16
#Mann=4,-1,0
  4541.7    0.16       0  4741.1     0.1       0  4995.9    0.07       0
  5001.9     0.1       0
Bank Sta=4995.9,5001.9
Exp/Cntr=0.3,0.1

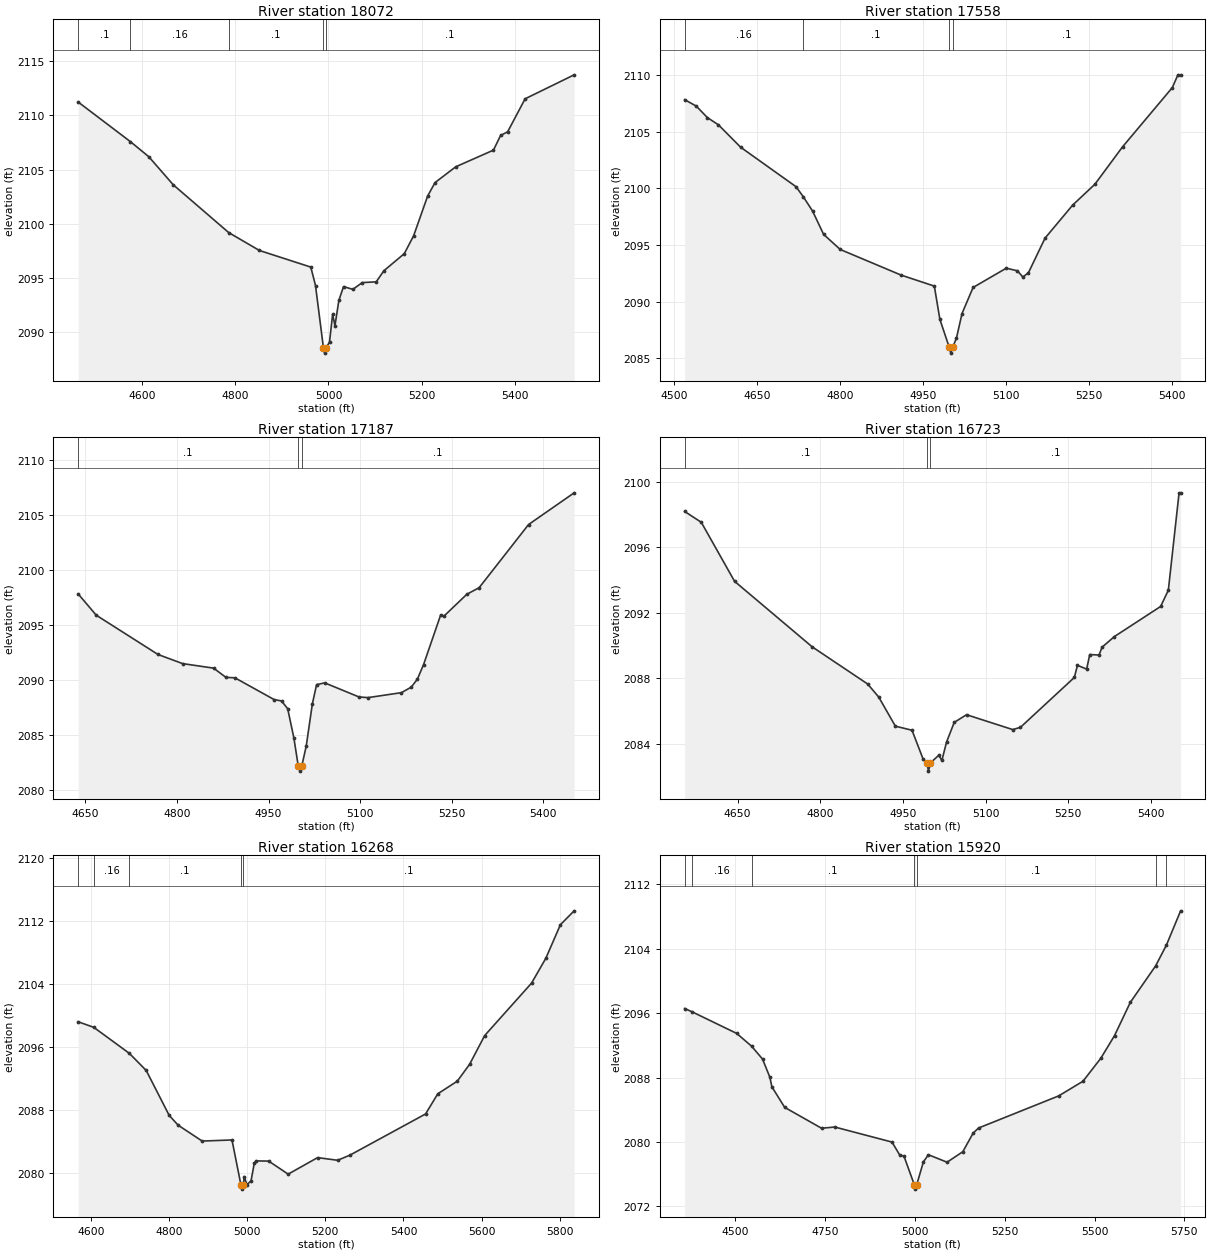
Type RM Length L Ch R = 1,18072,514,514,514
BEGIN DESCRIPTION:
BANTA BRANCH 40.0
END DESCRIPTION:
XS GIS Cut Line= 4
      2646699.21     10083449.81      2646374.56     10083310.92
      2645900.60     10083354.32      2645667.97     10083397.73
#Sta/Elev= 30
  4462.2 2111.22  4574.1 2107.58  4613.7 2106.19  4666.3 2103.60  4785.6 2099.19
  4851.6 2097.54  4962.0 2096.01  4972.1 2094.31  4989.1 2088.58  4991.9 2088.08
  4995.1 2088.58  5002.2 2089.10  5008.9 2091.66  5013.9 2090.61  5022.3 2092.94
  5032.3 2094.21  5052.4 2093.96  5072.5 2094.58  5102.6 2094.65  5119.0 2095.67
  5162.9 2097.25  5182.9 2098.89  5213.1 2102.56  5229.0 2103.80  5273.3 2105.25
  5354.5 2106.79  5369.8 2108.14  5385.0 2108.48  5422.5 2111.52  5527.9 2113.73
#Mann=5,-1,0
  4462.2     0.1       0  4574.1    0.16       0  4785.6     0.1       0
  4989.1    0.07       0  4995.1     0.1       0
Bank Sta=4989.1,4995.1
Exp/Cntr=0.3,0.1

Type RM Length L Ch R = 1,17558,371,371,371
BEGIN DESCRIPTION:
BANTA BRANCH 39.0
END DESCRIPTION:
XS GIS Cut Line= 2
      2646579.45     10082868.21      2645683.58     10082875.16
#Sta/Elev= 30
  4519.2 2107.81  4540.2 2107.24  4560.2 2106.23  4580.2 2105.59  4620.2 2103.62
  4720.2 2100.14  4733.2 2099.27  4750.2 2097.99  4770.2 2095.93  4800.2 2094.60
  4910.2 2092.34  4970.2 2091.37  4980.2 2088.44  4997.2 2085.96  5000.0 2085.46
  5003.2 2085.96  5010.2 2086.79  5020.2 2088.95  5040.2 2091.25  5100.2 2092.95
  5120.2 2092.72  5130.2 2092.17  5140.2 2092.55  5170.2 2095.60  5220.2 2098.52
  5260.2 2100.35  5310.2 2103.65  5400.2 2108.88  5410.2 2110.00  5415.1 2110.00
#Mann=4,-1,0
  4519.2    0.16       0  4733.2     0.1       0  4997.2    0.07       0
  5003.2     0.1       0
Bank Sta=4997.2,5003.2
Exp/Cntr=0.3,0.1

Type RM Length L Ch R = 1,17187,464,464,464
BEGIN DESCRIPTION:
BANTA BRANCH 38.0
END DESCRIPTION:
XS GIS Cut Line= 2
      2646377.63     10082461.09      2645574.65     10082580.45
#Sta/Elev= 30
  4638.5 2097.80  4668.0 2095.87  4769.1 2092.30  4809.5 2091.47  4860.1 2091.06
  4880.3 2090.22  4895.0 2090.18  4959.3 2088.20  4971.3 2088.08  4981.4 2087.37
  4991.5 2084.72  4998.6 2082.20  5001.4 2081.70  5004.6 2082.20  5011.7 2083.96
  5021.8 2087.82  5028.7 2089.56  5042.0 2089.72  5098.1 2088.44  5112.8 2088.38
  5167.5 2088.83  5183.6 2089.33  5193.7 2090.06  5203.8 2091.38  5231.8 2095.89
  5236.9 2095.77  5274.6 2097.77  5294.8 2098.37  5375.7 2104.11  5450.3 2106.99
#Mann=3,-1,0
  4638.5     0.1       0  4998.6    0.07       0  5004.6     0.1       0
Bank Sta=4998.6,5004.6
Exp/Cntr=0.3,0.1

Type RM Length L Ch R = 1,16723,455,455,455
BEGIN DESCRIPTION:
BANTA BRANCH 37.0
END DESCRIPTION:
XS GIS Cut Line= 3
      2646418.43     10082103.73      2645968.47     10082053.73
      2645568.51     10082253.71
#Sta/Elev= 30
  4554.0 2098.20  4584.1 2097.54  4644.5 2093.93  4785.4 2089.92  4886.0 2087.65
  4906.1 2086.85  4936.3 2085.07  4966.5 2084.82  4986.6 2083.06  4993.7 2082.82
  4996.4 2082.32  4999.7 2082.82  5015.1 2083.29  5020.7 2082.97  5029.1 2084.09
  5043.1 2085.30  5065.4 2085.77  5149.3 2084.86  5163.3 2085.00  5261.1 2088.05
  5266.7 2088.79  5283.4 2088.56  5289.0 2089.45  5305.8 2089.42  5311.4 2089.90
  5333.8 2090.55  5417.6 2092.39  5431.6 2093.38  5451.1 2099.34  5453.9 2099.34
#Mann=3,-1,0
  4554.0     0.1       0  4993.7    0.07       0  4999.7     0.1       0
Bank Sta=4993.7,4999.7
Exp/Cntr=0.3,0.1

Type RM Length L Ch R = 1,16268,348,348,348
BEGIN DESCRIPTION:
BANTA BRANCH 36.0
END DESCRIPTION:
XS GIS Cut Line= 3
      2646488.73     10081688.80      2646129.33     10081610.67
      2645275.15     10081902.34
#Sta/Elev= 30
  4566.9 2099.24  4606.9 2098.53  4697.9 2095.23  4741.1 2093.06  4800.0 2087.35
  4823.0 2086.11  4884.4 2084.10  4960.8 2084.24  4983.9 2078.50  4986.6 2078.00
  4989.9 2078.50  4992.2 2079.60  4999.0 2078.56  5009.6 2079.05  5018.2 2081.35
  5023.5 2081.58  5054.8 2081.56  5104.7 2079.90  5180.1 2082.00  5231.5 2081.66
  5263.2 2082.32  5456.7 2087.54  5488.0 2090.10  5537.9 2091.70  5569.6 2093.85
  5608.1 2097.49  5728.1 2104.14  5764.7 2107.29  5802.1 2111.56  5837.3 2113.32
#Mann=5,-1,0
  4566.9     0.1       0  4606.9    0.16       0  4697.9     0.1       0
  4983.9    0.07       0  4989.9     0.1       0
Bank Sta=4983.9,4989.9
Exp/Cntr=0.3,0.1

Type RM Length L Ch R = 1,15920,575,575,575
BEGIN DESCRIPTION:
BANTA BRANCH 35.0
END DESCRIPTION:
XS GIS Cut Line= 3
      2646509.53     10081444.00      2645952.25     10081313.80
      2645238.71     10081694.00
#Sta/Elev= 30
  4358.7 2096.57  4378.0 2096.19  4503.6 2093.48  4544.9 2091.90  4575.4 2090.30
  4596.0 2088.03  4601.4 2086.86  4637.1 2084.30  4739.8 2081.71  4776.6 2081.86
  4936.0 2079.99  4957.5 2078.38  4969.3 2078.24  4998.4 2074.65  5001.2 2074.15
  5004.4 2074.65  5023.4 2077.54  5037.3 2078.42  5089.3 2077.49  5133.2 2078.80
  5161.9 2081.11  5177.1 2081.74  5399.8 2085.72  5467.6 2087.54  5517.2 2090.39
  5555.5 2093.21  5599.4 2097.33  5670.1 2101.88  5700.0 2104.45  5739.5 2108.70
#Mann=7,-1,0
  4358.7     0.1       0  4378.0    0.16       0  4544.9     0.1       0
  4998.4    0.07       0  5004.4     0.1       0  5670.1    0.16       0
  5700.0     0.1       0
Bank Sta=4998.4,5004.4
Exp/Cntr=0.3,0.1

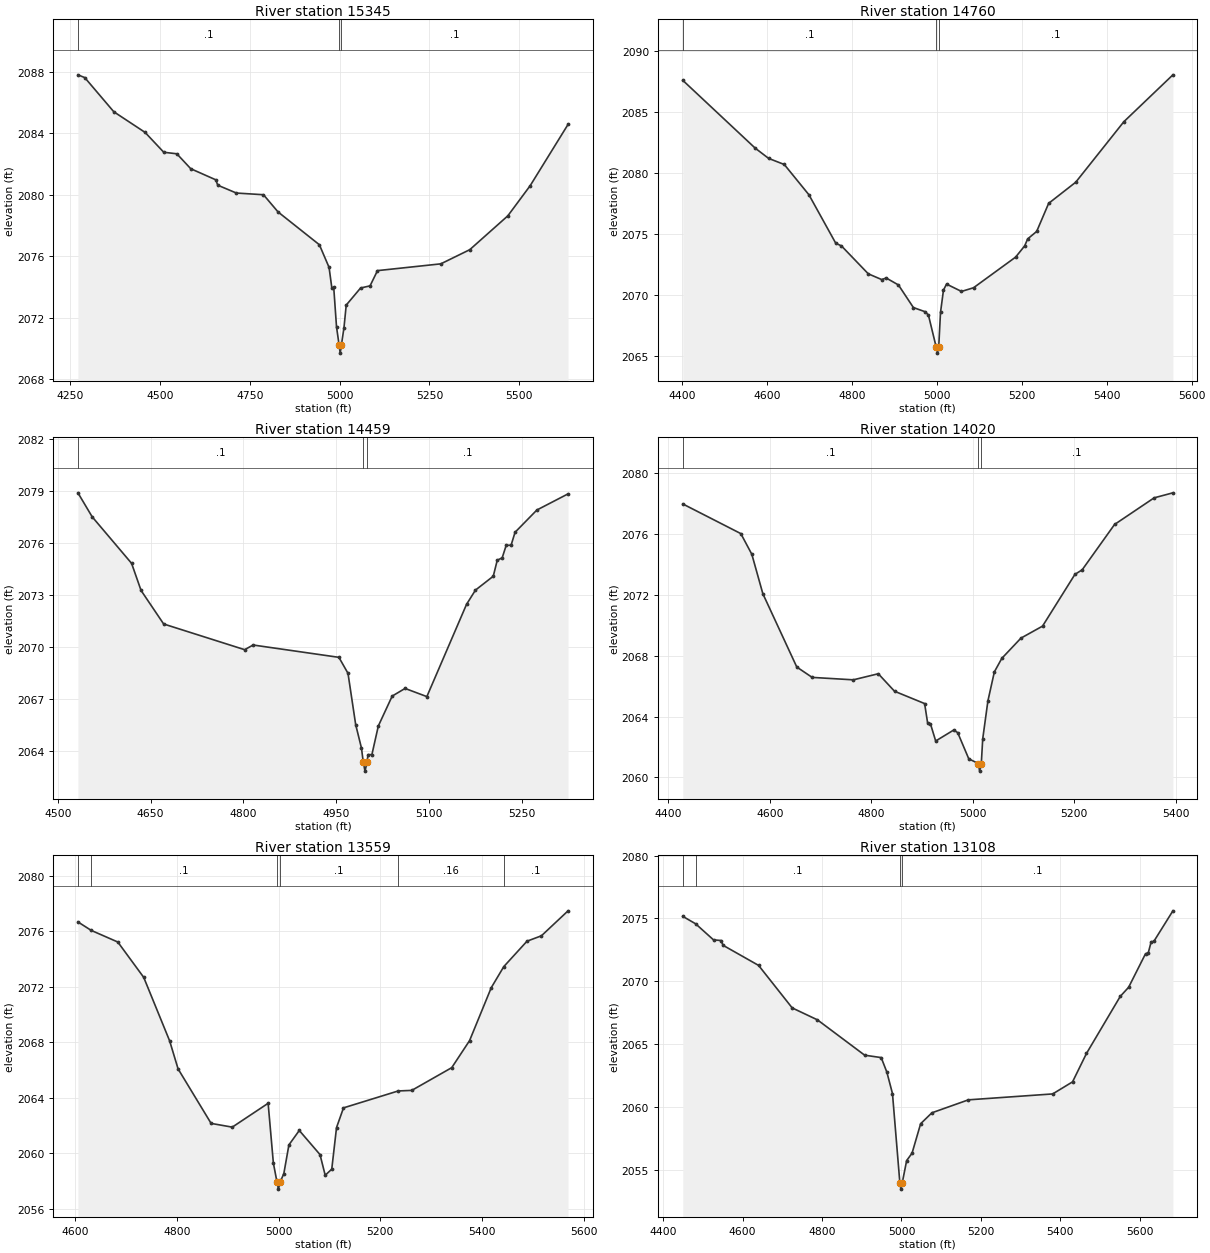
Type RM Length L Ch R = 1,15345,585,585,585
BEGIN DESCRIPTION:
BANTA BRANCH 34.0
END DESCRIPTION:
XS GIS Cut Line= 3
      2646479.58     10081057.01      2645902.34     10080798.77
      2645196.76     10080989.23
#Sta/Elev= 30
  4272.2 2087.79  4291.2 2087.61  4372.0 2085.39  4459.0 2084.05  4510.9 2082.76
  4547.3 2082.66  4586.0 2081.69  4655.6 2080.97  4661.1 2080.62  4712.9 2080.11
  4788.3 2080.00  4828.9 2078.88  4943.8 2076.75  4970.7 2075.28  4978.5 2073.93
  4983.7 2073.98  4991.4 2071.42  4998.8 2070.21  5001.6 2069.71  5004.8 2070.21
  5012.2 2071.37  5018.4 2072.83  5058.3 2073.94  5084.7 2074.08  5105.4 2075.07
  5281.5 2075.51  5362.0 2076.43  5467.9 2078.63  5530.1 2080.59  5635.4 2084.57
#Mann=3,-1,0
  4272.2     0.1       0  4998.8    0.07       0  5004.8     0.1       0
Bank Sta=4998.8,5004.8
Exp/Cntr=0.3,0.1

Type RM Length L Ch R = 1,14760,301,301,301
BEGIN DESCRIPTION:
BANTA BRANCH 33.0
END DESCRIPTION:
XS GIS Cut Line= 3
      2645962.64     10080194.01      2645493.91     10080350.26
      2645035.58     10080824.21
#Sta/Elev= 30
  4402.5 2087.60  4572.9 2082.05  4604.5 2081.21  4641.4 2080.71  4699.4 2078.23
  4762.6 2074.26  4775.8 2074.05  4839.1 2071.76  4870.7 2071.29  4881.2 2071.42
  4910.0 2070.85  4945.2 2069.00  4973.5 2068.65  4980.7 2068.37  4998.8 2065.77
  5001.6 2065.27  5004.8 2065.77  5009.0 2068.60  5016.0 2070.43  5023.2 2070.92
  5058.4 2070.32  5086.7 2070.62  5185.8 2073.13  5207.1 2074.05  5214.1 2074.62
  5235.3 2075.23  5263.5 2077.53  5327.2 2079.26  5440.4 2084.21  5555.9 2088.05
#Mann=3,-1,0
  4402.5     0.1       0  4998.8    0.07       0  5004.8     0.1       0
Bank Sta=4998.8,5004.8
Exp/Cntr=0.3,0.1

Type RM Length L Ch R = 1,14459,439,439,439
BEGIN DESCRIPTION:
BANTA BRANCH 32.0
END DESCRIPTION:
XS GIS Cut Line= 3
      2645618.45     10079953.74      2645218.47     10080203.73
      2644968.50     10080403.71
#Sta/Elev= 30
  4532.6 2078.88  4555.6 2077.50  4619.3 2074.82  4634.6 2073.26  4671.1 2071.33
  4802.0 2069.85  4815.6 2070.12  4954.2 2069.41  4968.9 2068.49  4981.3 2065.54
  4990.7 2064.18  4993.6 2063.36  4996.4 2062.86  4999.6 2063.36  5001.3 2063.81
  5007.5 2063.81  5017.9 2065.46  5040.3 2067.18  5061.1 2067.62  5096.3 2067.15
  5160.4 2072.46  5174.8 2073.28  5203.6 2074.08  5210.0 2075.00  5218.0 2075.14
  5224.4 2075.85  5232.4 2075.87  5238.8 2076.61  5274.0 2077.89  5324.4 2078.82
#Mann=3,-1,0
  4532.6     0.1       0  4993.6    0.07       0  4999.6     0.1       0
Bank Sta=4993.6,4999.6
Exp/Cntr=0.3,0.1

Type RM Length L Ch R = 1,14020,461,461,461
BEGIN DESCRIPTION:
BANTA BRANCH 31.0
END DESCRIPTION:
XS GIS Cut Line= 3
      2645514.76     10079563.79      2644926.21     10079891.92
      2644738.73     10080115.86
#Sta/Elev= 30
  4428.7 2077.97  4543.1 2076.02  4564.8 2074.66  4586.5 2072.07  4653.4 2067.25
  4683.7 2066.57  4764.8 2066.41  4814.0 2066.81  4846.0 2065.66  4905.3 2064.85
  4911.1 2063.60  4916.8 2063.52  4927.1 2062.39  4962.6 2063.11  4970.5 2062.94
  4992.3 2061.22  5011.0 2060.91  5013.7 2060.41  5017.0 2060.91  5019.8 2062.53
  5030.0 2065.02  5042.7 2066.93  5057.4 2067.82  5095.1 2069.15  5137.7 2069.94
  5201.5 2073.34  5215.8 2073.64  5279.6 2076.62  5357.6 2078.37  5394.6 2078.70
#Mann=3,-1,0
  4428.7     0.1       0  5011.0    0.07       0  5017.0     0.1       0
Bank Sta=5011,5017
Exp/Cntr=0.3,0.1

Type RM Length L Ch R = 1,13559,451,451,451
BEGIN DESCRIPTION:
BANTA BRANCH 30.0
END DESCRIPTION:
XS GIS Cut Line= 3
      2645405.39     10079329.42      2644915.79     10079428.38
      2644566.82     10079735.69
#Sta/Elev= 30
  4605.0 2076.67  4631.1 2076.06  4683.5 2075.22  4734.5 2072.67  4785.5 2068.09
  4802.1 2066.07  4867.1 2062.14  4908.7 2061.87  4979.3 2063.59  4989.6 2059.28
  4996.8 2057.90  4999.5 2057.40  5002.8 2057.90  5010.2 2058.52  5020.2 2060.59
  5040.6 2061.63  5081.4 2059.89  5091.6 2058.40  5104.5 2058.84  5113.9 2061.84
  5127.6 2063.26  5235.3 2064.48  5261.9 2064.52  5340.6 2066.16  5375.7 2068.11
  5418.4 2071.93  5443.1 2073.45  5488.7 2075.28  5517.1 2075.67  5569.5 2077.47
#Mann=6,-1,0
  4605.0    0.16       0  4631.1     0.1       0  4996.8    0.07       0
  5002.8     0.1       0  5235.3    0.16       0  5443.1     0.1       0
Bank Sta=4996.8,5002.8
Exp/Cntr=0.3,0.1

Type RM Length L Ch R = 1,13108,439,439,439
BEGIN DESCRIPTION:
BANTA BRANCH 29.0
END DESCRIPTION:
XS GIS Cut Line= 3
      2645405.35     10078970.04      2644947.04     10078917.96
      2644427.17     10079489.82
#Sta/Elev= 30
  4449.4 2075.17  4481.7 2074.58  4526.8 2073.30  4545.7 2073.25  4550.8 2072.87
  4640.3 2071.27  4724.9 2067.89  4788.5 2066.94  4907.4 2064.13  4949.0 2063.94
  4963.2 2062.79  4977.4 2061.08  4996.0 2053.98  4998.7 2053.48  5002.0 2053.98
  5013.1 2055.75  5026.7 2056.34  5048.3 2058.68  5076.7 2059.55  5168.6 2060.58
  5380.8 2061.05  5430.8 2062.01  5465.9 2064.27  5551.0 2068.81  5572.0 2069.53
  5614.6 2072.20  5621.3 2072.25  5628.8 2073.15  5635.5 2073.18  5683.5 2075.61
#Mann=4,-1,0
  4449.4    0.16       0  4481.7     0.1       0  4996.0    0.07       0
  5002.0     0.1       0
Bank Sta=4996,5002
Exp/Cntr=0.3,0.1

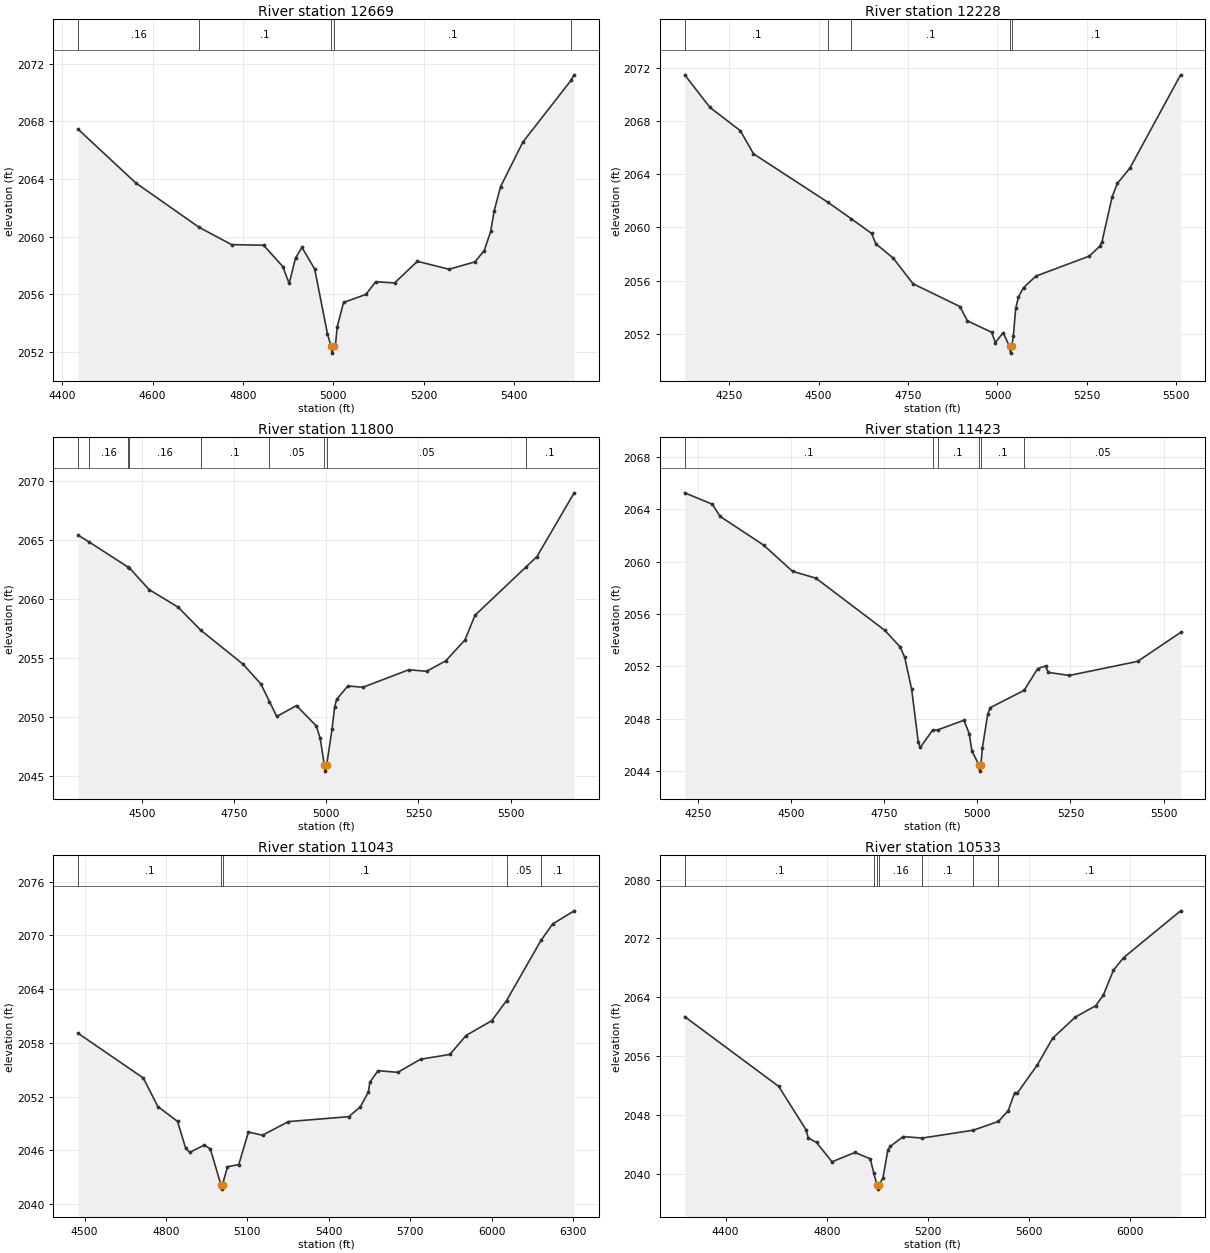
Type RM Length L Ch R = 1,12669,441,441,441
BEGIN DESCRIPTION:
BANTA BRANCH 28.0
END DESCRIPTION:
XS GIS Cut Line= 3
      2644918.46     10078353.74      2644518.47     10078753.73
      2644168.45     10079153.75
#Sta/Elev= 30
  4435.5 2067.45  4562.8 2063.73  4702.6 2060.65  4774.9 2059.44  4845.6 2059.40
  4888.0 2057.92  4902.2 2056.74  4916.3 2058.51  4930.5 2059.25  4958.7 2057.74
  4987.0 2053.23  4994.6 2052.40  4997.4 2051.90  5000.6 2052.40  5004.5 2052.40
  5008.3 2053.70  5022.5 2055.42  5071.9 2055.98  5093.7 2056.86  5135.5 2056.78
  5185.8 2058.28  5256.0 2057.73  5313.0 2058.24  5333.8 2059.03  5348.1 2060.37
  5355.7 2061.78  5369.9 2063.47  5419.3 2066.57  5525.6 2070.85  5532.7 2071.24
#Mann=5,-1,0
  4435.5    0.16       0  4702.6     0.1       0  4994.6    0.07       0
  5000.6     0.1       0  5525.6    0.16       0
Bank Sta=4994.6,5000.6
Exp/Cntr=0.3,0.1

Type RM Length L Ch R = 1,12228,428,428,428
BEGIN DESCRIPTION:
BANTA BRANCH 27.0
END DESCRIPTION:
XS GIS Cut Line= 3
      2644968.46     10078203.73      2644168.47     10078503.73
      2643818.47     10078903.73
#Sta/Elev= 30
  4125.9 2071.46  4196.2 2069.02  4281.6 2067.26  4318.1 2065.53  4526.6 2061.88
  4591.0 2060.66  4648.3 2059.55  4659.9 2058.78  4708.8 2057.69  4764.0 2055.77
  4894.9 2054.06  4916.2 2052.98  4983.6 2052.13  4994.1 2051.35  5015.9 2052.10
  5033.8 2051.06  5036.5 2050.56  5039.8 2051.06  5044.4 2051.88  5051.0 2053.92
  5058.6 2054.78  5072.8 2055.48  5108.0 2056.35  5257.0 2057.85  5285.4 2058.58
  5292.1 2058.93  5320.6 2062.31  5334.8 2063.30  5369.9 2064.45  5511.8 2071.46
#Mann=5,-1,0
  4125.9     0.1       0  4526.6    0.16       0  4591.0     0.1       0
  5033.8    0.07       0  5039.8     0.1       0
Bank Sta=5033.8,5039.8
Exp/Cntr=0.3,0.1

Type RM Length L Ch R = 1,11800,377,377,377
BEGIN DESCRIPTION:
BANTA BRANCH 26.0
END DESCRIPTION:
XS GIS Cut Line= 3
      2644551.17     10077938.81      2643832.46     10078214.84
      2643530.36     10078704.44
#Sta/Elev= 30
  4327.3 2065.39  4355.6 2064.85  4463.1 2062.69  4465.2 2062.66  4520.0 2060.79
  4598.0 2059.32  4659.9 2057.36  4774.1 2054.50  4823.0 2052.81  4846.1 2051.33
  4865.8 2050.07  4919.4 2050.99  4973.4 2049.26  4983.6 2048.22  4995.1 2045.95
  4997.8 2045.45  5001.1 2045.95  5015.8 2049.00  5022.8 2050.86  5028.1 2051.51
  5058.6 2052.65  5099.5 2052.54  5223.9 2054.02  5272.3 2053.89  5324.4 2054.78
  5376.5 2056.55  5403.6 2058.63  5541.9 2062.71  5571.6 2063.59  5672.5 2068.98
#Mann=9,-1,0
  4327.3     0.1       0  4355.6    0.16       0  4463.1     0.1       0
  4465.2    0.16       0  4659.9     0.1       0  4846.1    0.05       0
  4995.1   0.035       0  5001.1    0.05       0  5541.9     0.1       0
Bank Sta=4995.1,5001.1
Exp/Cntr=0.3,0.1

Type RM Length L Ch R = 1,11423,380,380,380
BEGIN DESCRIPTION:
BANTA BRANCH 25.0
END DESCRIPTION:
XS GIS Cut Line= 3
      2644580.70     10077608.67      2643899.30     10077775.77
      2643452.24     10078220.66
#Sta/Elev= 30
  4213.6 2065.27  4288.0 2064.40  4308.6 2063.47  4425.4 2061.28  4503.4 2059.27
  4566.0 2058.75  4751.3 2054.76  4792.5 2053.49  4804.8 2052.69  4823.4 2050.25
  4841.3 2046.19  4846.4 2045.81  4879.6 2047.13  4893.2 2047.15  4963.8 2047.89
  4978.0 2046.87  4985.1 2045.56  5003.3 2044.50  5006.0 2044.00  5009.3 2044.50
  5013.4 2045.78  5027.5 2048.33  5034.5 2048.85  5125.7 2050.18  5161.8 2051.83
  5183.1 2052.04  5190.1 2051.55  5246.7 2051.31  5430.5 2052.39  5545.9 2054.60
#Mann=6,-1,0
  4213.6     0.1       0  4879.6    0.05       0  4893.2     0.1       0
  5003.3    0.07       0  5009.3     0.1       0  5125.7    0.05       0
Bank Sta=5003.3,5009.3
Exp/Cntr=0.3,0.1

Type RM Length L Ch R = 1,11043,510,510,510
BEGIN DESCRIPTION:
BANTA BRANCH 24.0
END DESCRIPTION:
XS GIS Cut Line= 3
      2644223.03     10077308.61      2643587.66     10077548.17
      2643165.78     10078615.91
#Sta/Elev= 30
  4476.7 2059.05  4716.7 2054.06  4770.1 2050.88  4842.6 2049.22  4872.8 2046.20
  4887.7 2045.77  4941.1 2046.58  4963.4 2046.15  5002.3 2042.16  5005.0 2041.66
  5008.3 2042.16  5026.6 2044.16  5068.2 2044.40  5103.7 2048.03  5155.7 2047.68
  5251.0 2049.20  5473.5 2049.75  5516.0 2050.84  5545.8 2052.50  5551.2 2053.60
  5581.1 2054.88  5654.0 2054.70  5737.8 2056.16  5846.0 2056.70  5905.4 2058.81
  6000.4 2060.47  6054.8 2062.71  6181.4 2069.42  6224.6 2071.26  6303.8 2072.73
#Mann=5,-1,0
  4476.7     0.1       0  5002.3    0.07       0  5008.3     0.1       0
  6054.8    0.05       0  6181.4     0.1       0
Bank Sta=5002.3,5008.3
Exp/Cntr=0.3,0.1

Type RM Length L Ch R = 1,10533,545,545,545
BEGIN DESCRIPTION:
BANTA BRANCH 23.0
END DESCRIPTION:
XS GIS Cut Line= 3
      2644203.66     10076926.63      2643634.83     10077072.25
      2642263.40     10077164.52
#Sta/Elev= 30
  4237.9 2061.36  4609.5 2051.88  4718.1 2045.96  4726.8 2044.85  4759.4 2044.24
  4820.6 2041.61  4911.6 2042.88  4971.8 2042.02  4986.1 2040.07  4998.8 2038.39
  5001.6 2037.89  5004.8 2038.39  5021.9 2039.39  5041.9 2043.26  5051.9 2043.73
  5102.1 2045.04  5177.5 2044.84  5379.6 2045.91  5478.8 2047.10  5517.8 2048.57
  5543.1 2051.02  5553.1 2050.93  5633.3 2054.82  5693.4 2058.43  5783.6 2061.31
  5863.8 2062.85  5893.8 2064.29  5933.9 2067.68  5974.0 2069.39  6199.6 2075.76
#Mann=7,-1,0
  4237.9     0.1       0  4986.1    0.16       0  4998.8    0.07       0
  5004.8    0.16       0  5177.5     0.1       0  5379.6    0.05       0
  5478.8     0.1       0
Bank Sta=4998.8,5004.8
Exp/Cntr=0.3,0.1

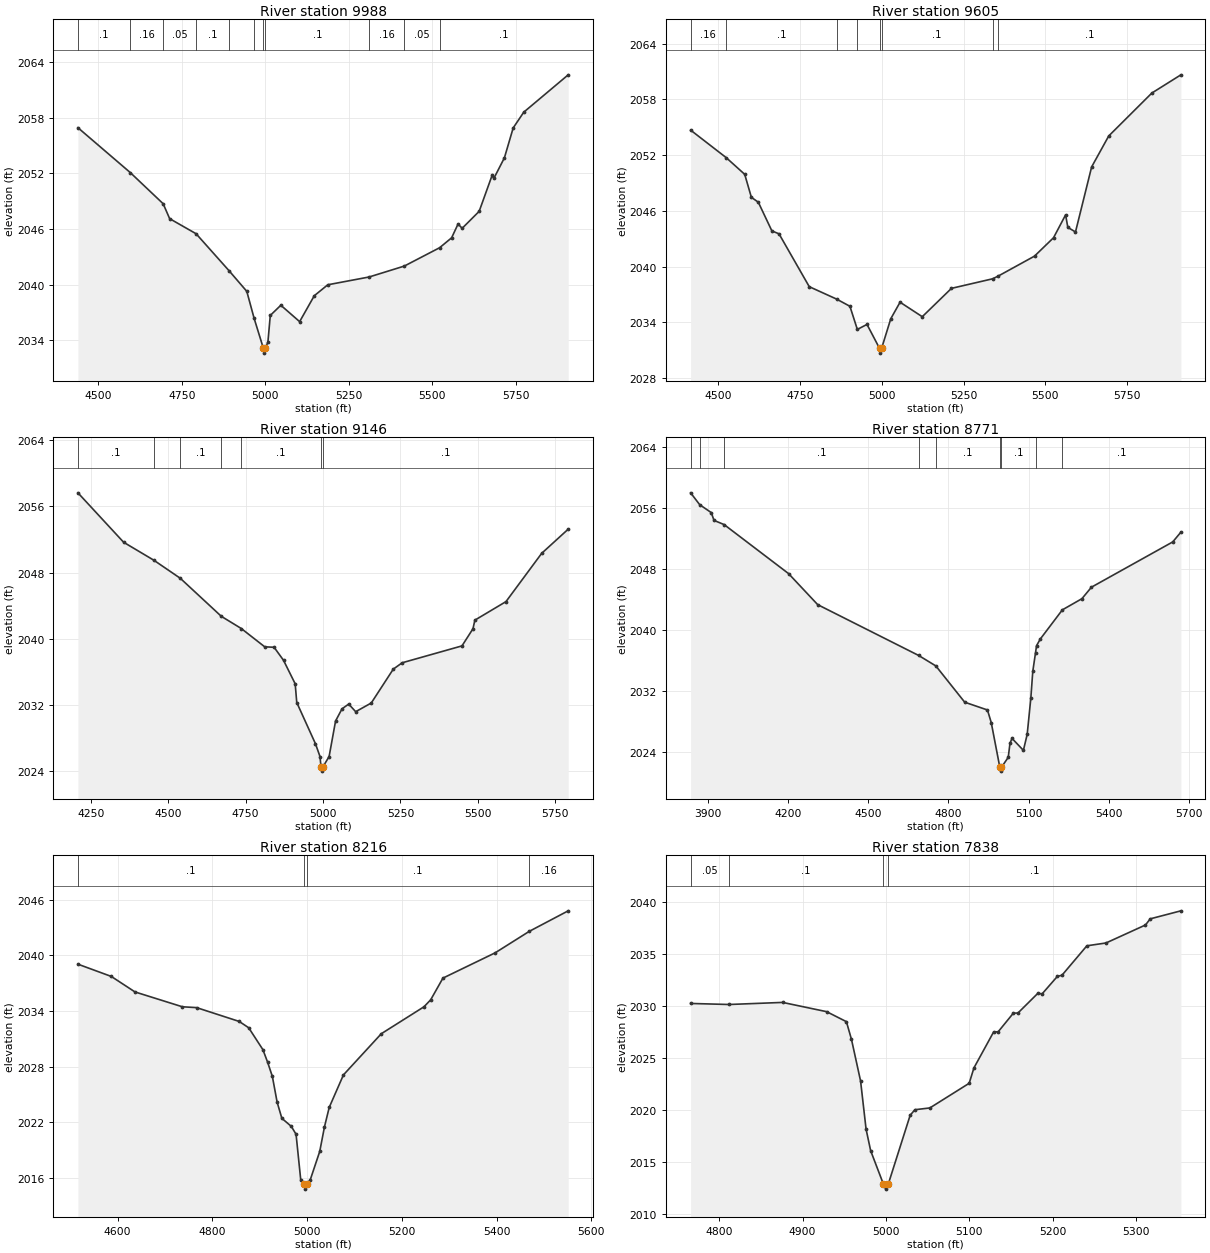
Type RM Length L Ch R = 1,9988,383,383,383
BEGIN DESCRIPTION:
BANTA BRANCH 22.0
END DESCRIPTION:
XS GIS Cut Line= 3
      2643952.29     10076579.43      2643457.46     10076542.96
      2642535.59     10076850.25
#Sta/Elev= 30
  4438.7 2056.94  4595.3 2052.10  4693.9 2048.73  4713.3 2047.12  4792.5 2045.49
  4891.1 2041.50  4944.3 2039.27  4966.2 2036.36  4994.1 2033.10  4996.8 2032.60
  5000.1 2033.10  5007.6 2033.83  5014.6 2036.67  5046.2 2037.77  5102.5 2036.00
  5146.4 2038.80  5186.8 2039.98  5310.4 2040.82  5415.9 2042.00  5521.5 2043.98
  5557.5 2045.05  5576.8 2046.54  5589.1 2046.08  5640.0 2047.91  5678.7 2051.79
  5684.0 2051.47  5715.6 2053.69  5741.9 2056.92  5773.6 2058.62  5906.6 2062.65
#Mann=11,-1,0
  4438.7     0.1       0  4595.3    0.16       0  4693.9    0.05       0
  4792.5     0.1       0  4891.1    0.05       0  4966.2     0.1       0
  4994.1    0.07       0  5000.1     0.1       0  5310.4    0.16       0
  5415.9    0.05       0  5521.5     0.1       0
Bank Sta=4994.1,5000.1
Exp/Cntr=0.3,0.1

Type RM Length L Ch R = 1,9605,459,459,459
BEGIN DESCRIPTION:
BANTA BRANCH 21.0
END DESCRIPTION:
XS GIS Cut Line= 3
      2643837.71     10076048.16      2643176.21     10076230.46
      2642483.52     10076652.32
#Sta/Elev= 30
  4416.6 2054.70  4524.8 2051.75  4581.8 2049.94  4602.1 2047.47  4623.3 2046.94
  4664.8 2043.85  4686.5 2043.54  4778.9 2037.85  4862.1 2036.52  4903.1 2035.74
  4925.7 2033.25  4955.2 2033.79  4993.7 2031.20  4996.4 2030.70  4999.7 2031.20
  5027.8 2034.40  5056.2 2036.18  5124.0 2034.62  5213.1 2037.67  5339.0 2038.70
  5356.3 2039.00  5466.8 2041.14  5524.9 2043.12  5561.7 2045.58  5568.5 2044.23
  5591.9 2043.74  5641.2 2050.74  5693.4 2054.07  5825.1 2058.69  5913.8 2060.65
#Mann=8,-1,0
  4416.6    0.16       0  4524.8     0.1       0  4862.1    0.05       0
  4925.7     0.1       0  4993.7    0.07       0  4999.7     0.1       0
  5339.0    0.16       0  5356.3     0.1       0
Bank Sta=4993.7,4999.7
Exp/Cntr=0.3,0.1

Type RM Length L Ch R = 1,9146,375,375,375
BEGIN DESCRIPTION:
BANTA BRANCH 20.0
END DESCRIPTION:
XS GIS Cut Line= 4
      2643874.16     10075626.29      2643165.79     10075740.88
      2642467.87     10076246.09      2642463.03     10076246.09
#Sta/Elev= 30
  4208.1 2057.65  4355.7 2051.68  4453.3 2049.51  4538.7 2047.33  4671.4 2042.73
  4735.8 2041.26  4811.5 2039.05  4841.9 2038.99  4872.3 2037.42  4910.0 2034.58
  4915.1 2032.32  4975.5 2027.34  4990.2 2025.79  4993.4 2024.53  4996.2 2024.03
  4999.4 2024.53  5019.6 2025.79  5040.5 2030.09  5061.4 2031.56  5082.9 2032.13
  5105.5 2031.21  5155.8 2032.26  5226.9 2036.35  5255.7 2037.12  5448.9 2039.16
  5484.4 2041.23  5490.6 2042.27  5591.1 2044.51  5706.4 2050.34  5792.1 2053.26
#Mann=7,-1,0
  4208.1     0.1       0  4453.3    0.16       0  4538.7     0.1       0
  4671.4    0.16       0  4735.8     0.1       0  4993.4    0.07       0
  4999.4     0.1       0
Bank Sta=4993.4,4999.4
Exp/Cntr=0.3,0.1

Type RM Length L Ch R = 1,8771,555,555,555
BEGIN DESCRIPTION:
BANTA BRANCH 19.0
END DESCRIPTION:
XS GIS Cut Line= 3
      2643874.17     10075334.62      2642921.00     10075532.55
      2642281.43     10076109.72
#Sta/Elev= 30
  3835.0 2057.98  3869.1 2056.42  3912.3 2055.39  3922.5 2054.37  3960.4 2053.82
  4201.5 2047.40  4310.6 2043.33  4688.7 2036.67  4752.9 2035.30  4860.8 2030.55
  4946.0 2029.53  4960.1 2027.89  4992.3 2022.02  4995.1 2021.52  4998.3 2022.02
  5023.7 2023.32  5030.4 2025.18  5037.9 2025.81  5080.5 2024.24  5094.7 2026.34
  5108.3 2031.07  5115.6 2034.58  5125.8 2037.01  5129.8 2037.96  5144.0 2038.84
  5226.4 2042.65  5299.5 2044.11  5335.3 2045.62  5639.5 2051.55  5670.0 2052.83
#Mann=9,-1,0
  3835.0     0.1       0  3869.1    0.16       0  3960.4     0.1       0
  4688.7    0.16       0  4752.9     0.1       0  4992.3    0.07       0
  4998.3     0.1       0  5125.8    0.05       0  5226.4     0.1       0
Bank Sta=4992.3,4998.3
Exp/Cntr=0.3,0.1

Type RM Length L Ch R = 1,8216,378,378,378
BEGIN DESCRIPTION:
BANTA BRANCH 18.0
END DESCRIPTION:
XS GIS Cut Line= 2
      2643208.84     10075168.75      2642174.13     10075182.64
#Sta/Elev= 30
  4516.2 2039.04  4586.6 2037.72  4636.6 2036.05  4736.6 2034.45  4766.6 2034.36
  4856.6 2032.87  4876.6 2032.19  4906.6 2029.83  4916.6 2028.47  4926.6 2026.94
  4936.6 2024.18  4946.6 2022.43  4966.6 2021.56  4976.6 2020.71  4986.6 2015.73
  4993.6 2015.30  4996.4 2014.80  4999.6 2015.30  5006.6 2015.81  5026.6 2018.87
  5036.6 2021.52  5046.6 2023.61  5076.6 2027.11  5156.6 2031.55  5246.6 2034.45
  5260.7 2035.20  5286.6 2037.54  5396.7 2040.26  5468.9 2042.58  5551.0 2044.79
#Mann=4,-1,0
  4516.2     0.1       0  4993.6    0.07       0  4999.6     0.1       0
  5468.9    0.16       0
Bank Sta=4993.6,4999.6
Exp/Cntr=0.3,0.1

Type RM Length L Ch R = 1,7838,278,278,278
BEGIN DESCRIPTION:
BANTA BRANCH 17.0
END DESCRIPTION:
XS GIS Cut Line= 2
      2642836.26     10074736.22      2642294.54     10074965.41
#Sta/Elev= 30
  4765.7 2030.23  4811.7 2030.13  4876.1 2030.33  4928.9 2029.44  4952.6 2028.48
  4958.7 2026.77  4969.6 2022.78  4976.2 2018.15  4981.7 2016.08  4996.9 2012.89
  4999.7 2012.39  5002.9 2012.89  5029.1 2019.49  5034.8 2020.02  5052.7 2020.19
  5099.9 2022.56  5105.6 2024.04  5129.2 2027.49  5134.7 2027.51  5152.9 2029.30
  5158.4 2029.31  5182.1 2031.19  5187.5 2031.16  5205.7 2032.83  5211.2 2032.94
  5241.1 2035.77  5264.0 2036.04  5311.4 2037.77  5317.1 2038.36  5353.9 2039.13
#Mann=4,-1,0
  4765.7    0.05       0  4811.7     0.1       0  4996.9    0.07       0
  5002.9     0.1       0
Bank Sta=4996.9,5002.9
Exp/Cntr=0.3,0.1