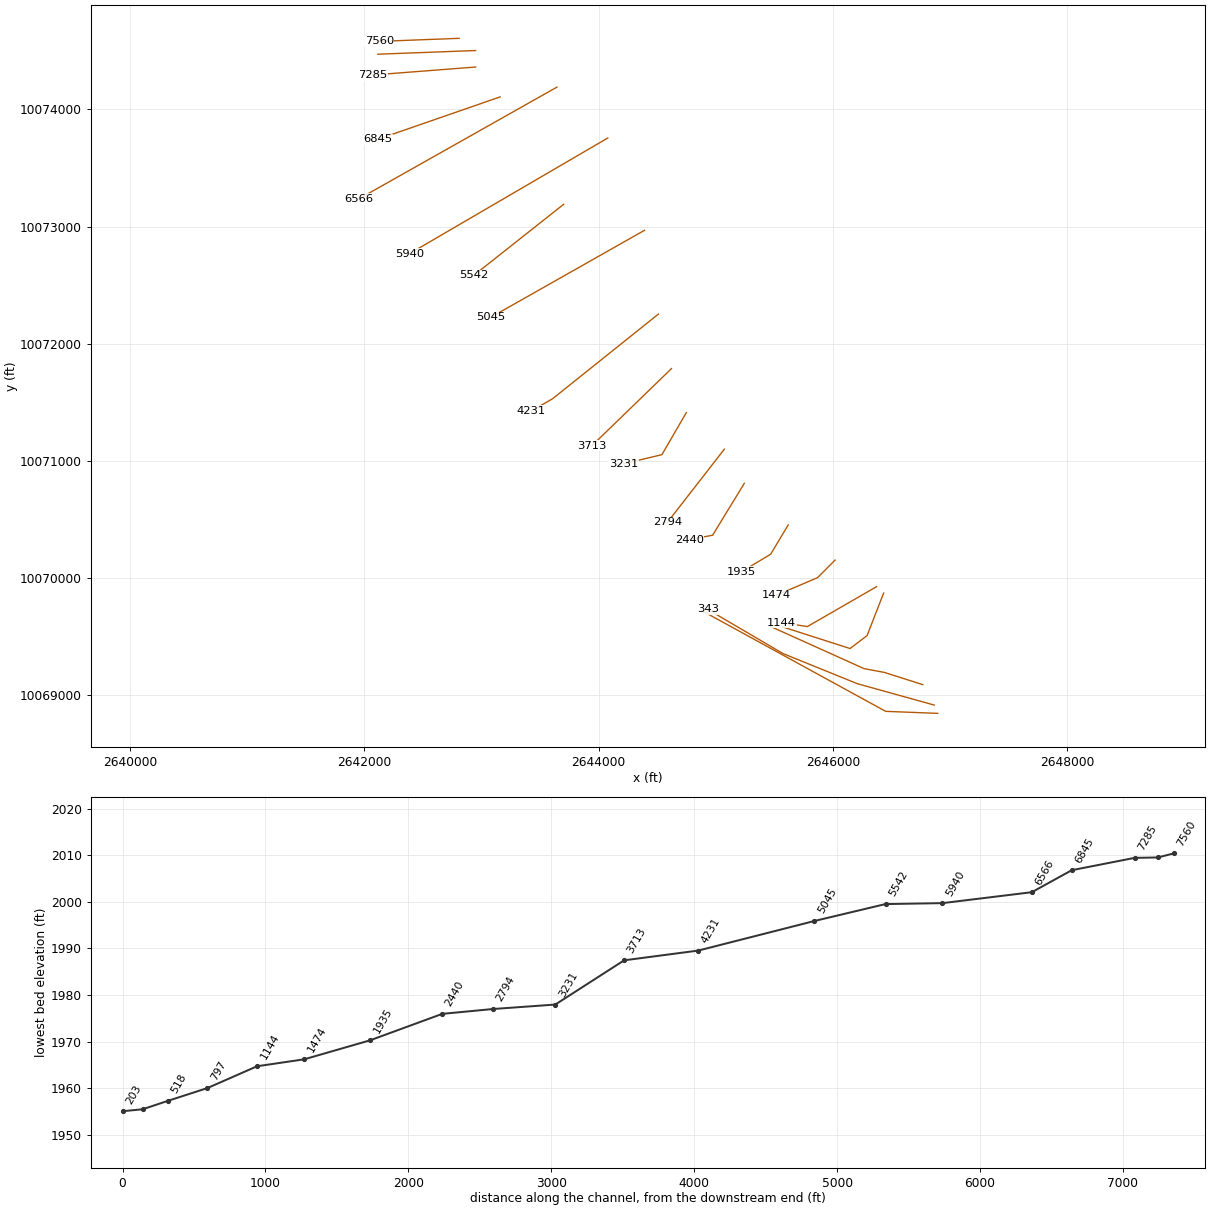
HEC-RAS study BANTA BRANCH.prj: BANTA BRANCH Base Level Engineering

--- BANTA BRANCH.g01 (geometry) --- (continued)

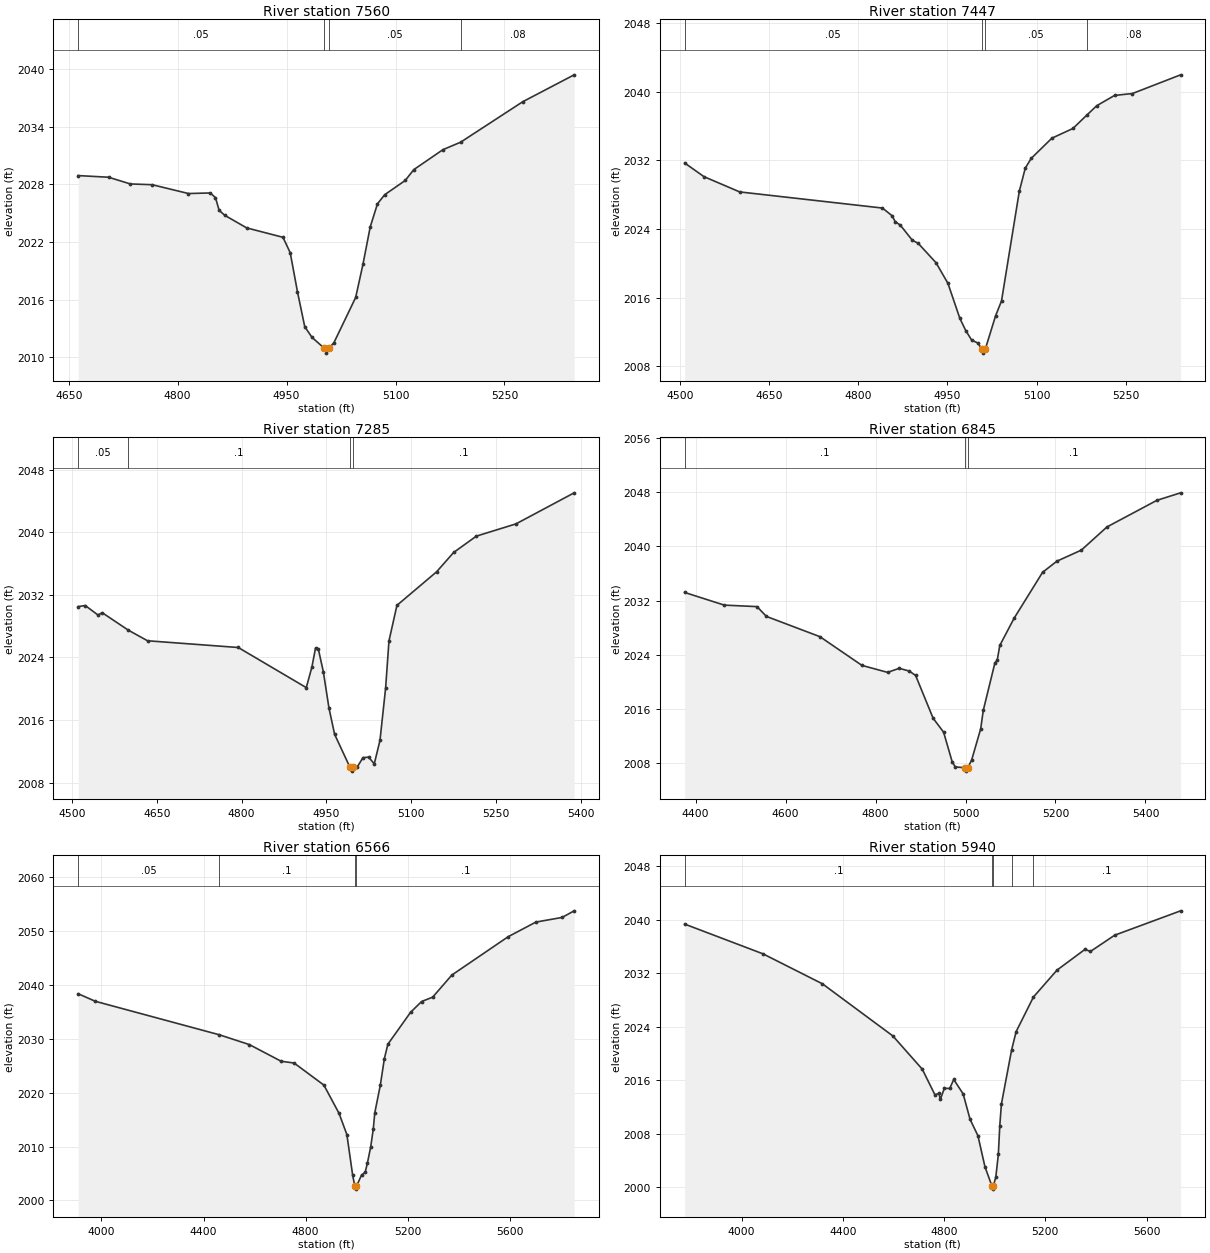
Type RM Length L Ch R = 1,7560,113,113,113
BEGIN DESCRIPTION:
Mapping XS aa31c049
END DESCRIPTION:
XS GIS Cut Line= 2
      2642810.17     10074606.02      2642127.86     10074579.98
#Sta/Elev= 30
  4663.1 2028.92  4704.8 2028.75  4734.9 2028.05  4764.9 2027.97  4814.9 2027.05
  4844.9 2027.11  4852.1 2026.62  4857.1 2025.30  4864.9 2024.78  4895.0 2023.47
  4945.0 2022.49  4955.0 2020.88  4965.0 2016.80  4975.0 2013.17  4985.0 2012.06
  5002.0 2010.92  5004.8 2010.42  5008.0 2010.92  5015.1 2011.50  5045.1 2016.22
  5055.1 2019.66  5065.1 2023.56  5075.1 2025.98  5085.1 2026.93  5113.3 2028.41
  5125.1 2029.54  5165.2 2031.62  5189.6 2032.40  5275.2 2036.62  5345.9 2039.42
#Mann=4,-1,0
  4663.1    0.05       0  5002.0    0.04       0  5008.0    0.05       0
  5189.6    0.08       0
Bank Sta=5002,5008
Exp/Cntr=0.3,0.1

Type RM Length L Ch R = 1,7447,162,162,162
BEGIN DESCRIPTION:
Mapping XS 7af9047d
END DESCRIPTION:
XS GIS Cut Line= 2
      2642950.86     10074501.86      2642117.45     10074470.60
#Sta/Elev= 30
  4508.2 2031.70  4540.6 2030.11  4600.7 2028.33  4840.8 2026.45  4857.1 2025.55
  4862.1 2024.87  4870.8 2024.46  4890.9 2022.71  4900.9 2022.34  4930.9 2020.08
  4950.9 2017.68  4970.9 2013.61  4980.9 2012.17  4990.9 2011.06  5000.9 2010.74
  5007.9 2010.05  5010.7 2009.55  5013.9 2010.05  5031.0 2013.89  5041.0 2015.63
  5071.0 2028.43  5081.0 2031.11  5091.0 2032.24  5125.7 2034.59  5161.1 2035.72
  5184.5 2037.28  5201.1 2038.37  5231.1 2039.57  5261.1 2039.79  5342.2 2041.97
#Mann=4,-1,0
  4508.2    0.05       0  5007.9    0.04       0  5013.9    0.05       0
  5184.5    0.08       0
Bank Sta=5007.9,5013.9
Exp/Cntr=0.3,0.1

Type RM Length L Ch R = 1,7285,440,440,440
BEGIN DESCRIPTION:
BANTA BRANCH 16.0
END DESCRIPTION:
XS GIS Cut Line= 2
      2642950.82     10074361.23      2642075.84     10074293.52
#Sta/Elev= 30
  4511.0 2030.50  4523.4 2030.64  4545.9 2029.43  4553.5 2029.72  4599.6 2027.49
  4633.7 2026.13  4794.2 2025.27  4914.6 2020.14  4924.6 2022.79  4930.9 2025.19
  4935.9 2025.08  4944.7 2022.19  4954.7 2017.54  4964.7 2014.17  4991.8 2009.96
  4994.6 2009.46  4997.8 2009.96  5004.8 2010.00  5014.9 2011.18  5024.9 2011.25
  5034.9 2010.39  5045.0 2013.39  5055.0 2020.10  5060.9 2026.11  5075.0 2030.66
  5145.2 2034.95  5175.3 2037.42  5215.5 2039.51  5285.7 2041.08  5388.6 2045.05
#Mann=4,-1,0
  4511.0    0.05       0  4599.6     0.1       0  4991.8    0.07       0
  4997.8     0.1       0
Bank Sta=4991.8,4997.8
Exp/Cntr=0.3,0.1

Type RM Length L Ch R = 1,6845,279,279,279
BEGIN DESCRIPTION:
BANTA BRANCH 15.0
END DESCRIPTION:
XS GIS Cut Line= 2
      2643160.28     10074106.26      2642118.60     10073745.15
#Sta/Elev= 30
  4375.7 2033.19  4463.7 2031.32  4536.4 2031.10  4557.5 2029.65  4676.4 2026.66
  4769.8 2022.42  4826.8 2021.39  4852.6 2021.99  4875.1 2021.58  4889.1 2020.93
  4928.0 2014.62  4951.3 2012.56  4970.3 2008.21  4977.2 2007.43  4999.1 2007.31
  5001.8 2006.81  5005.1 2007.31  5013.6 2008.44  5033.8 2013.07  5039.5 2015.78
  5065.3 2022.77  5070.6 2023.22  5076.2 2025.36  5107.9 2029.37  5171.4 2036.17
  5203.2 2037.81  5257.5 2039.44  5314.4 2042.86  5425.4 2046.79  5478.2 2047.90
#Mann=3,-1,0
  4375.7     0.1       0  4999.1    0.07       0  5005.1     0.1       0
Bank Sta=4999.1,5005.1
Exp/Cntr=0.3,0.1

Type RM Length L Ch R = 1,6566,626,626,626
BEGIN DESCRIPTION:
BANTA BRANCH 14.0
END DESCRIPTION:
XS GIS Cut Line= 2
      2643645.16     10074189.75      2641952.94     10073235.16
#Sta/Elev= 30
  3908.9 2038.39  3975.9 2036.99  4461.6 2030.77  4579.7 2028.94  4703.9 2025.85
  4754.7 2025.52  4871.4 2021.42  4930.7 2016.17  4961.4 2012.23  4984.2 2004.64
  4992.8 2002.59  4995.6 2002.09  4998.8 2002.59  5018.8 2004.70  5033.2 2005.23
  5041.8 2006.92  5054.9 2009.97  5064.7 2013.20  5070.8 2016.28  5092.4 2021.39
  5108.4 2026.36  5122.1 2029.02  5210.9 2034.94  5254.2 2036.95  5297.5 2037.76
  5372.7 2041.87  5592.9 2048.98  5702.0 2051.71  5804.5 2052.57  5851.8 2053.80
#Mann=4,-1,0
  3908.9    0.05       0  4461.6     0.1       0  4992.8    0.07       0
  4998.8     0.1       0
Bank Sta=4992.8,4998.8
Exp/Cntr=0.3,0.1

Type RM Length L Ch R = 1,5940,398,398,398
BEGIN DESCRIPTION:
BANTA BRANCH 13.0
END DESCRIPTION:
XS GIS Cut Line= 2
      2644079.18     10073755.72      2642386.87     10072768.53
#Sta/Elev= 30
  3775.3 2039.34  4084.9 2034.89  4319.7 2030.41  4597.6 2022.63  4713.9 2017.66
  4763.8 2013.84  4779.5 2014.04  4785.3 2013.15  4801.0 2014.79  4822.5 2014.79
  4838.2 2016.12  4875.4 2013.97  4902.7 2010.17  4933.8 2007.72  4961.4 2003.10
  4988.7 2000.24  4991.5 1999.74  4994.7 2000.24  5004.4 2001.53  5014.4 2004.92
  5020.1 2009.20  5026.5 2012.44  5066.9 2020.54  5084.7 2023.27  5153.2 2028.45
  5246.4 2032.47  5356.7 2035.56  5378.2 2035.25  5474.1 2037.68  5734.5 2041.32
#Mann=5,-1,0
  3775.3     0.1       0  4988.7    0.07       0  4994.7     0.1       0
  5066.9    0.16       0  5153.2     0.1       0
Bank Sta=4988.7,4994.7
Exp/Cntr=0.3,0.1

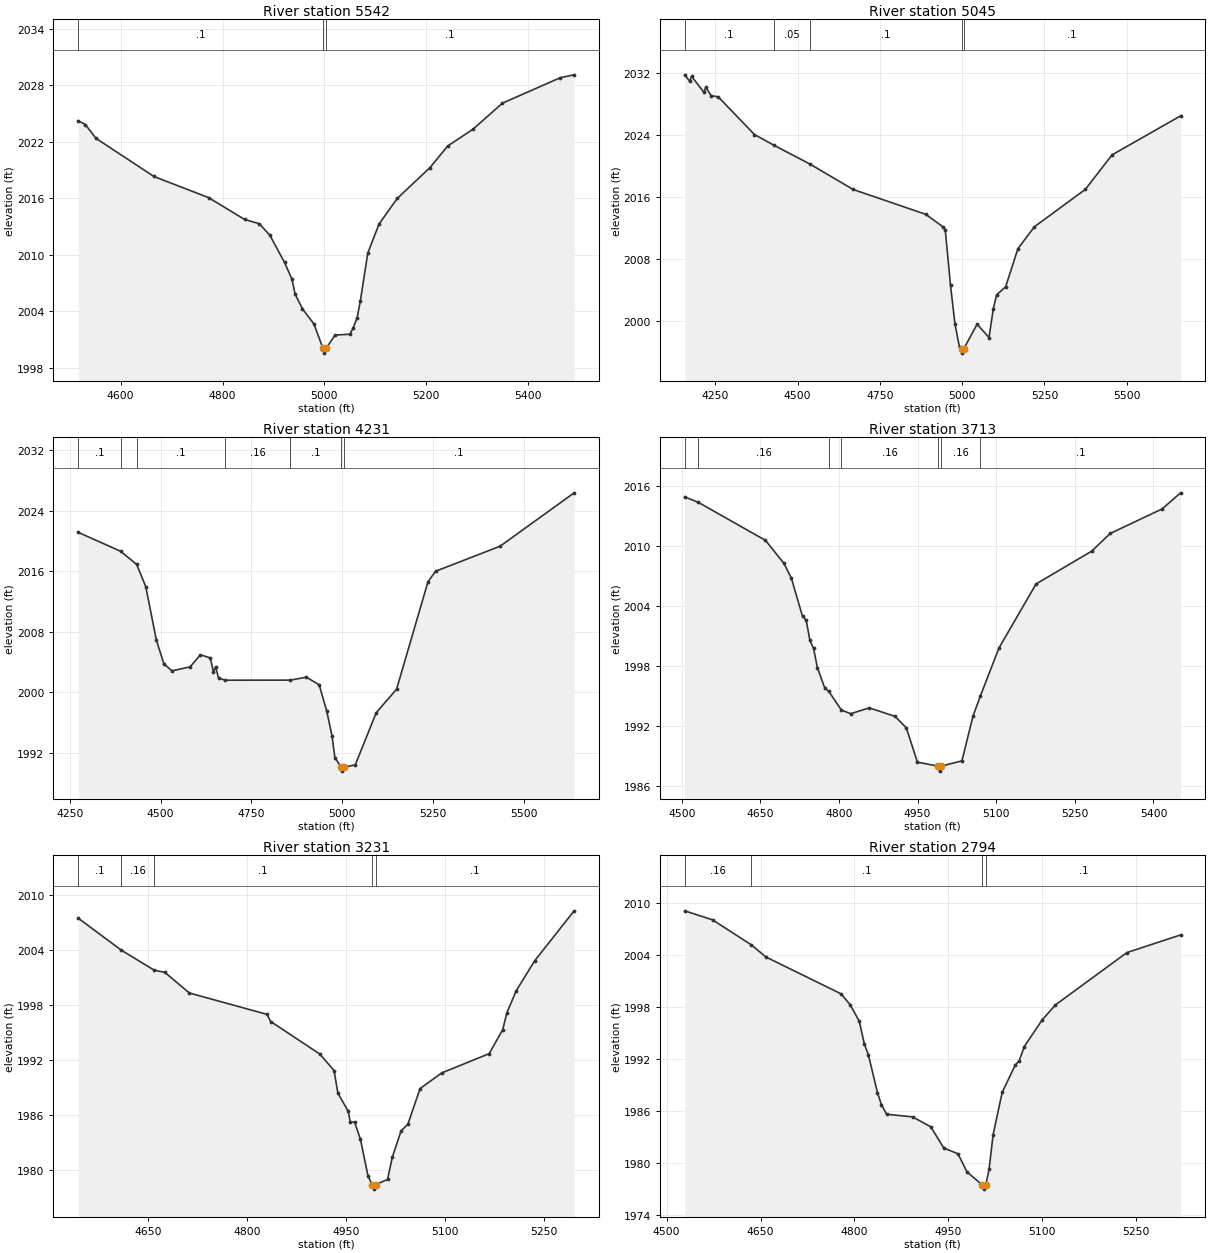
Type RM Length L Ch R = 1,5542,497,497,497
BEGIN DESCRIPTION:
BANTA BRANCH 12.0
END DESCRIPTION:
XS GIS Cut Line= 2
      2643701.89     10073189.56      2642938.02     10072585.42
#Sta/Elev= 30
  4516.6 2024.23  4530.7 2023.82  4551.5 2022.36  4665.3 2018.31  4772.7 2016.06
  4843.2 2013.75  4872.1 2013.29  4892.9 2012.07  4921.8 2009.17  4936.2 2007.41
  4942.6 2005.80  4957.0 2004.24  4979.5 2002.64  4997.3 2000.04  5000.1 1999.54
  5003.3 2000.04  5021.1 2001.46  5050.0 2001.55  5056.4 2002.19  5064.4 2003.32
  5070.8 2005.12  5085.2 2010.17  5107.4 2013.26  5143.0 2015.97  5207.1 2019.24
  5242.3 2021.55  5292.0 2023.34  5349.7 2026.10  5463.5 2028.81  5490.5 2029.11
#Mann=3,-1,0
  4516.6     0.1       0  4997.3    0.07       0  5003.3     0.1       0
Bank Sta=4997.3,5003.3
Exp/Cntr=0.3,0.1

Type RM Length L Ch R = 1,5045,814,814,814
BEGIN DESCRIPTION:
BANTA BRANCH 11.0
END DESCRIPTION:
XS GIS Cut Line= 2
      2644392.96     10072968.37      2643081.97     10072226.18
#Sta/Elev= 30
  4157.2 2031.74  4172.4 2030.91  4178.2 2031.54  4215.7 2029.49  4221.5 2030.15
  4237.4 2029.05  4259.0 2028.91  4369.2 2024.05  4427.2 2022.70  4537.9 2020.25
  4668.8 2016.98  4889.6 2013.78  4943.1 2012.13  4948.8 2011.77  4964.7 2004.64
  4978.2 1999.69  4992.1 1996.64  4998.2 1996.41  5001.0 1995.91  5004.2 1996.41
  5045.5 1999.63  5081.7 1997.92  5094.5 2001.57  5104.7 2003.41  5132.1 2004.45
  5169.6 2009.37  5219.6 2012.18  5374.5 2017.00  5455.3 2021.43  5663.7 2026.46
#Mann=5,-1,0
  4157.2     0.1       0  4427.2    0.05       0  4537.9     0.1       0
  4998.2    0.07       0  5004.2     0.1       0
Bank Sta=4998.2,5004.2
Exp/Cntr=0.3,0.1

Type RM Length L Ch R = 1,4231,518,518,518
BEGIN DESCRIPTION:
BANTA BRANCH 10.0
END DESCRIPTION:
XS GIS Cut Line= 3
      2644511.04     10072253.12      2643608.23     10071530.87
      2643427.68     10071426.71
#Sta/Elev= 30
  4273.4 2021.14  4390.1 2018.64  4434.3 2016.89  4459.4 2013.94  4488.3 2006.91
  4509.1 2003.75  4531.5 2002.82  4581.1 2003.34  4609.7 2004.94  4637.1 2004.53
  4645.1 2002.72  4651.5 2003.32  4659.5 2001.88  4677.5 2001.58  4857.4 2001.59
  4901.3 2001.98  4936.5 2000.97  4957.3 1997.48  4971.7 1994.22  4979.7 1991.33
  4997.5 1990.05  5000.3 1989.55  5003.5 1990.05  5035.7 1990.38  5093.4 1997.28
  5149.4 2000.39  5235.8 2014.60  5256.6 2015.99  5434.4 2019.31  5638.0 2026.37
#Mann=7,-1,0
  4273.4     0.1       0  4390.1    0.16       0  4434.3     0.1       0
  4677.5    0.16       0  4857.4     0.1       0  4997.5    0.07       0
  5003.5     0.1       0
Bank Sta=4997.5,5003.5
Exp/Cntr=0.3,0.1

Type RM Length L Ch R = 1,3713,482,482,482
BEGIN DESCRIPTION:
BANTA BRANCH 8.0
END DESCRIPTION:
XS GIS Cut Line= 2
      2644622.15     10071787.84      2643942.84     10071129.33
#Sta/Elev= 30
  4505.7 2014.93  4531.2 2014.40  4659.8 2010.58  4695.0 2008.27  4709.2 2006.80
  4730.5 2002.96  4737.5 2002.58  4744.6 2000.55  4751.6 1999.75  4758.8 1997.84
  4772.9 1995.79  4780.8 1995.44  4804.5 1993.59  4822.3 1993.21  4857.8 1993.80
  4907.2 1992.94  4928.6 1991.79  4949.7 1988.36  4989.1 1987.96  4991.9 1987.46
  4995.1 1987.96  5034.6 1988.49  5055.7 1992.97  5069.8 1994.99  5105.3 1999.80
  5176.0 2006.21  5282.0 2009.49  5317.5 2011.27  5416.3 2013.72  5451.8 2015.34
#Mann=7,-1,0
  4505.7     0.1       0  4531.2    0.16       0  4780.8     0.1       0
  4804.5    0.16       0  4989.1    0.07       0  4995.1    0.16       0
  5069.8     0.1       0
Bank Sta=4989.1,4995.1
Exp/Cntr=0.3,0.1

Type RM Length L Ch R = 1,3231,437,437,437
BEGIN DESCRIPTION:
BANTA BRANCH 7.0
END DESCRIPTION:
XS GIS Cut Line= 3
      2644749.13     10071412.77      2644540.79     10071053.38
      2644213.07     10070975.35
#Sta/Elev= 30
  4544.1 2007.46  4609.2 2003.99  4659.4 2001.80  4675.5 2001.56  4712.8 1999.31
  4830.4 1996.99  4836.1 1996.21  4910.7 1992.66  4932.2 1990.87  4938.0 1988.41
  4953.8 1986.42  4956.8 1985.26  4963.3 1985.26  4972.2 1983.39  4983.6 1979.43
  4989.7 1978.46  4992.5 1977.96  4995.7 1978.46  5013.3 1979.01  5020.6 1981.44
  5033.9 1984.31  5044.1 1985.01  5062.7 1988.91  5095.5 1990.61  5167.5 1992.71
  5188.1 1995.33  5194.3 1997.15  5208.6 1999.57  5236.5 2002.82  5296.4 2008.26
#Mann=5,-1,0
  4544.1     0.1       0  4609.2    0.16       0  4659.4     0.1       0
  4989.7    0.07       0  4995.7     0.1       0
Bank Sta=4989.7,4995.7
Exp/Cntr=0.3,0.1

Type RM Length L Ch R = 1,2794,354,354,354
BEGIN DESCRIPTION:
BANTA BRANCH 6.0
END DESCRIPTION:
XS GIS Cut Line= 2
      2645073.51     10071100.32      2644587.39     10070475.31
#Sta/Elev= 30
  4528.9 2009.12  4573.4 2008.08  4635.4 2005.19  4658.4 2003.80  4778.8 1999.53
  4793.3 1998.26  4807.7 1996.36  4815.9 1993.71  4822.2 1992.50  4836.7 1988.14
  4843.0 1986.75  4851.2 1985.64  4892.8 1985.34  4921.8 1984.19  4942.6 1981.74
  4965.2 1981.08  4979.7 1978.98  5003.8 1977.50  5006.6 1977.00  5009.8 1977.50
  5015.0 1979.35  5021.3 1983.27  5035.8 1988.16  5056.7 1991.33  5063.0 1991.81
  5071.1 1993.46  5100.0 1996.56  5120.8 1998.26  5234.9 2004.30  5320.7 2006.34
#Mann=4,-1,0
  4528.9    0.16       0  4635.4     0.1       0  5003.8    0.07       0
  5009.8     0.1       0
Bank Sta=5003.8,5009.8
Exp/Cntr=0.3,0.1

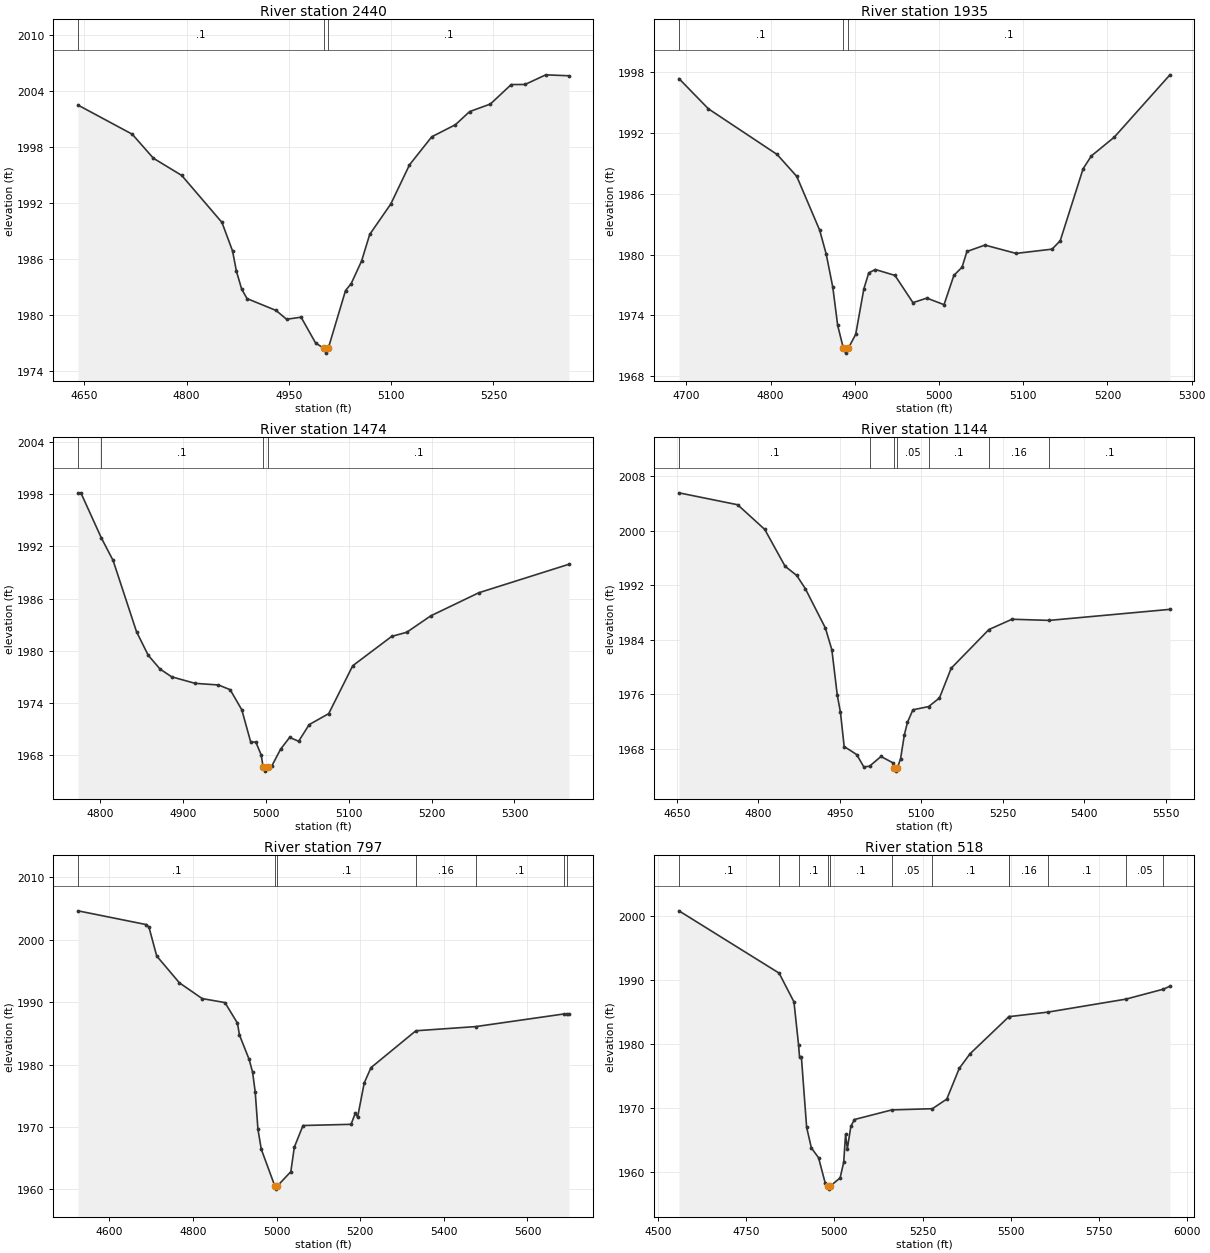
Type RM Length L Ch R = 1,2440,505,505,505
BEGIN DESCRIPTION:
BANTA BRANCH 5.0
END DESCRIPTION:
XS GIS Cut Line= 3
      2645243.90     10070808.56      2644973.08     10070365.88
      2644775.16     10070329.42
#Sta/Elev= 30
  4640.6 2002.47  4720.3 1999.35  4751.2 1996.79  4792.8 1994.95  4851.8 1989.93
  4867.3 1986.89  4873.1 1984.70  4880.7 1982.81  4888.6 1981.79  4931.2 1980.52
  4946.6 1979.58  4967.9 1979.80  4989.2 1977.04  5001.7 1976.46  5004.4 1975.96
  5007.7 1976.46  5033.1 1982.65  5041.4 1983.39  5056.6 1985.80  5068.6 1988.65
  5099.5 1991.90  5126.9 1996.08  5159.6 1999.08  5194.3 2000.37  5215.1 2001.77
  5245.6 2002.58  5276.1 2004.66  5296.4 2004.67  5326.9 2005.70  5360.8 2005.60
#Mann=3,-1,0
  4640.6     0.1       0  5001.7    0.07       0  5007.7     0.1       0
Bank Sta=5001.7,5007.7
Exp/Cntr=0.3,0.1

Type RM Length L Ch R = 1,1935,461,461,461
BEGIN DESCRIPTION:
BANTA BRANCH 4.0
END DESCRIPTION:
XS GIS Cut Line= 3
      2645618.45     10070453.70      2645468.47     10070203.73
      2645218.43     10070053.71
#Sta/Elev= 30
  4691.1 1997.37  4726.0 1994.39  4807.7 1989.88  4831.0 1987.72  4858.2 1982.41
  4866.0 1980.04  4873.8 1976.78  4879.6 1973.01  4886.3 1970.78  4889.1 1970.28
  4892.3 1970.78  4901.0 1972.13  4910.7 1976.63  4916.5 1978.20  4924.3 1978.53
  4947.6 1977.95  4969.0 1975.26  4985.5 1975.71  5005.9 1975.06  5017.6 1977.95
  5027.3 1978.76  5033.1 1980.31  5054.5 1980.94  5091.5 1980.12  5134.2 1980.54
  5143.9 1981.37  5171.1 1988.48  5180.9 1989.74  5208.1 1991.59  5274.2 1997.74
#Mann=3,-1,0
  4691.1     0.1       0  4886.3    0.07       0  4892.3     0.1       0
Bank Sta=4886.3,4892.3
Exp/Cntr=0.3,0.1

Type RM Length L Ch R = 1,1474,330,330,330
BEGIN DESCRIPTION:
BANTA BRANCH 3.0
END DESCRIPTION:
XS GIS Cut Line= 3
      2646018.44     10070153.70      2645868.47     10070003.73
      2645518.45     10069853.72
#Sta/Elev= 30
  4772.9 1998.15  4776.4 1998.15  4801.1 1992.98  4815.3 1990.39  4843.6 1982.21
  4857.7 1979.51  4871.9 1977.93  4886.0 1977.03  4914.3 1976.28  4942.6 1976.09
  4956.7 1975.55  4970.8 1973.23  4981.5 1969.54  4987.7 1969.54  4994.1 1968.07
  4996.5 1966.70  4999.2 1966.20  5002.5 1966.70  5006.8 1966.76  5017.6 1968.72
  5028.5 1970.07  5039.4 1969.63  5052.1 1971.54  5075.7 1972.80  5104.7 1978.30
  5151.8 1981.67  5169.9 1982.14  5199.0 1984.03  5257.0 1986.68  5365.8 1989.95
#Mann=4,-1,0
  4772.9    0.16       0  4801.1     0.1       0  4996.5    0.07       0
  5002.5     0.1       0
Bank Sta=4996.5,5002.5
Exp/Cntr=0.3,0.1

Type RM Length L Ch R = 1,1144,347,347,347
BEGIN DESCRIPTION:
BANTA BRANCH 2.0
END DESCRIPTION:
XS GIS Cut Line= 3
      2646372.09     10069926.69      2645781.84     10069586.43
      2645561.51     10069620.86
#Sta/Elev= 30
  4653.8 2005.55  4761.9 2003.80  4811.8 2000.18  4849.2 1994.78  4870.7 1993.42
  4886.5 1991.49  4923.5 1985.71  4935.4 1982.51  4945.4 1975.85  4951.2 1973.35
  4958.1 1968.32  4981.2 1967.14  4994.3 1965.33  5004.8 1965.43  5025.9 1966.86
  5047.4 1965.95  5050.2 1965.21  5052.9 1964.71  5056.2 1965.21  5062.0 1966.55
  5069.0 1970.06  5074.7 1971.88  5084.7 1973.71  5113.6 1974.18  5133.6 1975.45
  5155.2 1979.81  5224.7 1985.49  5267.2 1987.00  5335.7 1986.83  5558.1 1988.45
#Mann=7,-1,0
  4653.8     0.1       0  5004.8    0.05       0  5050.2    0.07       0
  5056.2    0.05       0  5113.6     0.1       0  5224.7    0.16       0
  5335.7     0.1       0
Bank Sta=5050.2,5056.2
Exp/Cntr=0.3,0.1

Type RM Length L Ch R = 1,797,279,279,279
BEGIN DESCRIPTION:
Mapping XS 50ffb08e
END DESCRIPTION:
XS GIS Cut Line= 4
      2646432.55     10069872.17      2646291.51     10069509.80
      2646146.11     10069399.12      2645572.29     10069583.18
#Sta/Elev= 30
  4525.0 2004.65  4688.8 2002.44  4695.0 2001.98  4713.3 1997.41  4767.7 1993.10
  4822.1 1990.58  4876.5 1989.94  4906.4 1986.65  4911.2 1984.75  4934.3 1980.84
  4942.6 1978.79  4948.9 1975.62  4955.4 1969.64  4963.4 1966.43  4995.8 1960.53
  4998.5 1960.03  5001.8 1960.53  5034.1 1962.83  5042.4 1966.75  5063.2 1970.23
  5178.1 1970.42  5188.5 1972.23  5193.7 1971.54  5209.6 1977.05  5225.8 1979.51
  5333.1 1985.42  5476.4 1986.09  5686.7 1988.11  5693.7 1988.08  5699.2 1988.05
#Mann=7,-1,0
  4525.0     0.1       0  4995.8    0.07       0  5001.8     0.1       0
  5333.1    0.16       0  5476.4     0.1       0  5686.7    0.05       0
  5693.7     0.1       0
Bank Sta=4995.8,5001.8
Exp/Cntr=0.3,0.1

Type RM Length L Ch R = 1,518,175,175,175
BEGIN DESCRIPTION:
Mapping XS 21133b9e
END DESCRIPTION:
XS GIS Cut Line= 4
      2646766.76     10069090.96      2646439.08     10069195.13
      2646265.46     10069227.68      2645472.32     10069585.25
#Sta/Elev= 30
  4560.0 2000.75  4843.5 1991.02  4885.7 1986.52  4898.8 1979.75  4901.5 1977.91
  4906.7 1977.91  4921.6 1966.91  4935.0 1963.70  4955.3 1962.17  4974.1 1958.22
  4982.9 1957.76  4985.6 1957.26  4988.9 1957.76  5016.4 1959.01  5026.6 1961.48
  5031.8 1965.81  5036.9 1963.59  5046.9 1967.10  5057.1 1968.14  5162.9 1969.64
  5277.7 1969.83  5318.5 1971.33  5353.8 1976.13  5384.3 1978.41  5494.2 1984.20
  5495.8 1984.22  5604.7 1984.92  5825.6 1986.95  5932.0 1988.51  5950.5 1988.97
#Mann=12,-1,0
  4560.0     0.1       0  4843.5    0.05       0  4898.8     0.1       0
  4982.9    0.07       0  4988.9     0.1       0  5162.9    0.05       0
  5277.7     0.1       0  5494.2    0.05       0  5495.8    0.16       0
  5604.7     0.1       0  5825.6    0.05       0  5932.0     0.1       0
Bank Sta=4982.9,4988.9
Exp/Cntr=0.3,0.1

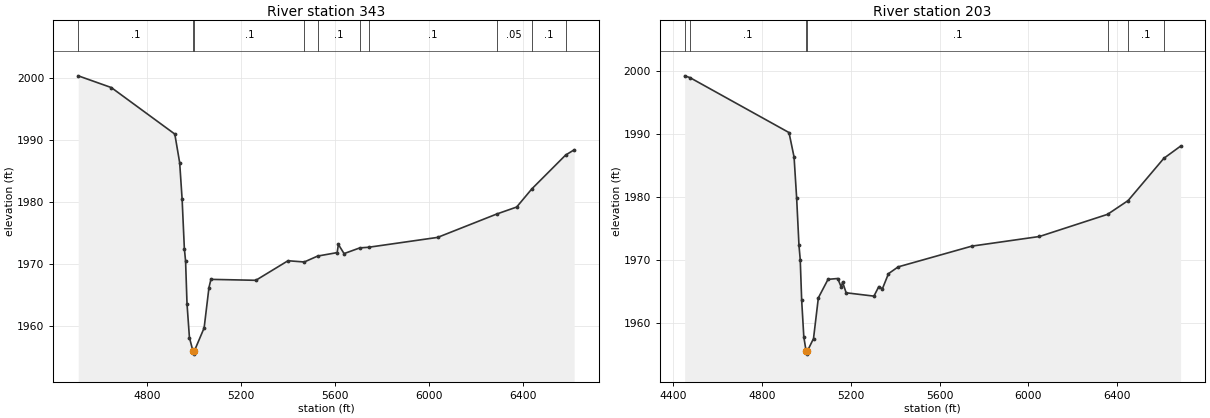
Type RM Length L Ch R = 1,343,140,140,140
BEGIN DESCRIPTION:
Mapping XS 4f5becbd
END DESCRIPTION:
XS GIS Cut Line= 4
      2646864.16     10068916.80      2646207.89     10069099.09
      2645574.21     10069356.04      2644932.62     10069732.32
#Sta/Elev= 30
  4507.7 2000.29  4648.5 1998.40  4918.4 1990.91  4939.1 1986.30  4949.5 1980.42
  4959.0 1972.48  4964.2 1970.47  4970.3 1963.58  4980.6 1958.14  4995.4 1955.97
  4998.2 1955.47  5001.4 1955.97  5043.1 1959.69  5063.7 1966.20  5072.1 1967.51
  5263.0 1967.36  5399.7 1970.51  5468.9 1970.31  5525.5 1971.26  5608.7 1971.82
  5614.0 1973.13  5638.1 1971.66  5705.1 1972.58  5742.4 1972.68  6035.9 1974.27
  6287.0 1978.03  6372.0 1979.16  6436.2 1982.07  6580.1 1987.53  6616.4 1988.37
#Mann=10,-1,0
  4507.7     0.1       0  4995.4    0.07       0  5001.4     0.1       0
  5468.9    0.05       0  5525.5     0.1       0  5705.1    0.05       0
  5742.4     0.1       0  6287.0    0.05       0  6436.2     0.1       0
  6580.1    0.05       0
Bank Sta=4995.4,5001.4
Exp/Cntr=0.3,0.1

Type RM Length L Ch R = 1,203,0,0,0
BEGIN DESCRIPTION:
BANTA BRANCH 1.0
END DESCRIPTION:
XS GIS Cut Line= 3
      2646894.83     10068845.73      2646449.93     10068863.10
      2644882.22     10069721.76
#Sta/Elev= 30
  4452.3 1999.29  4475.8 1999.01  4922.0 1990.27  4944.8 1986.37  4956.4 1979.84
  4966.8 1972.37  4972.5 1970.08  4979.0 1963.62  4988.6 1957.81  4998.8 1955.55
  5001.6 1955.05  5004.8 1955.55  5032.3 1957.52  5054.1 1964.00  5097.7 1966.94
  5141.3 1967.07  5157.4 1965.69  5163.1 1966.50  5179.2 1964.80  5304.4 1964.27
  5326.2 1965.79  5342.3 1965.43  5369.8 1967.84  5413.4 1968.92  5745.3 1972.22
  6049.6 1973.75  6356.0 1977.27  6448.6 1979.46  6609.3 1986.17  6685.0 1988.12
#Mann=7,-1,0
  4452.3    0.05       0  4475.8     0.1       0  4998.8    0.07       0
  5004.8     0.1       0  6356.0    0.05       0  6448.6     0.1       0
  6609.3    0.05       0
Bank Sta=4998.8,5004.8
Exp/Cntr=0.3,0.1

Chan Stop Cuts=-1