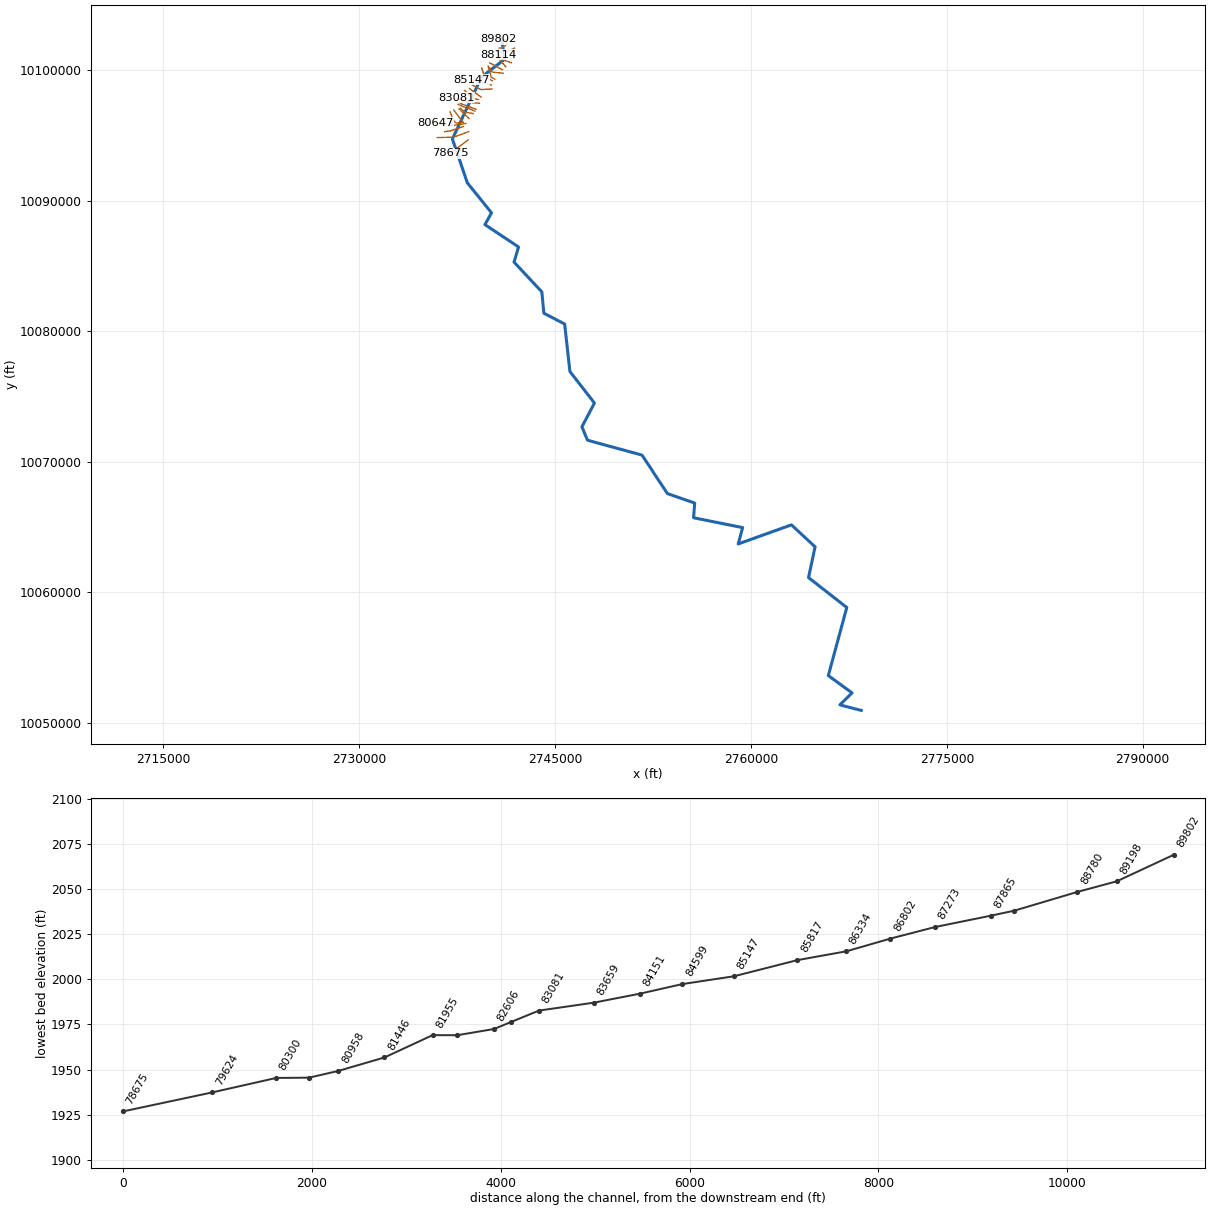
--- BARONS CREEK.prj (project) ---

Proj Title=BARONS CREEK Base Level Engineering
Current Plan=p01
Default Exp/Contr=0.3,0.1
English Units
Geom File=g01
Flow File=f01
Plan File=p01
Y Axis Title=Elevation
X Axis Title(PF)=Main Channel Distance
X Axis Title(XS)=Station
BEGIN DESCRIPTION:
BARONS CREEK
END DESCRIPTION:
DSS Export Rating Curves= 0
DSS Export Rating Curve Sorted= 0
DSS Export Volume Flow Curves= 0
DXF OffsetX= 0
DXF OffsetY= 0
DXF ScaleX= 1
DXF ScaleY= 10

--- BARONS CREEK.p01 (plan) ---

Plan Title=Multiple Run
Short Identifier=Multiple
Geom File=g01
Flow File=f01
Subcritical Flow
K Sum by GR= 0
Std Step Tol= 0.01
Critical Tol= 0.01
Num of Std Step Trials= 20
Max Error Tol= 0.3
Flow Tol Ratio= 0.001
Split Flow NTrial= 30
Split Flow Tol= 0.02
Split Flow Ratio= 0.02
Log Output Level= 0
Friction Slope Method= 1
Unsteady Friction Slope Method= 2
Unsteady Bridges Friction Slope Method= 1
Parabolic Critical Depth
Global Vel Dist=  1 , 1 , 1
Global Log Level= 0
CheckData=True
Encroach Param= -1, 0, 0, 0
BEGIN DESCRIPTION:
Multiple Run
END DESCRIPTION:

--- BARONS CREEK.f01 (steady flow) ---

Flow Title=Multiple
Program Version=4.10
Number of Profiles= 7
Profile Names=10-year,25-year,50-year,1pct_min,100-year,1pct_plu,500-year
River Rch & RM=BARONS CREEK,Reach-1         ,89802
     356     487     595     533     720     974    1060
River Rch & RM=BARONS CREEK,Reach-1         ,88114
    1200    1764    2259    2114    2859    3866    4601
River Rch & RM=BARONS CREEK,Reach-1         ,82606
    1243    1830    2346    2197    2971    4018    4790
River Rch & RM=BARONS CREEK,Reach-1         ,80647
    1982    2987    3888    3693    4995    6755    8286
River Rch & RM=BARONS CREEK,Reach-1         ,78675
    2109    3181    4145    3939    5327    7204    8844
River Rch & RM=BARONS CREEK,Reach-1         ,74571
    2500    3793    4962    4731    6398    8653   10695
River Rch & RM=BARONS CREEK,Reach-1         ,70929
    2870    4365    5718    5457    7380    9981   12358
River Rch & RM=BARONS CREEK,Reach-1         ,62840
    3280    5009    6579    6292    8509   11507   14310
River Rch & RM=BARONS CREEK,Reach-1         ,59969
    3784    5806    7652    7340    9927   13425   16795
River Rch & RM=BARONS CREEK,Reach-1         ,58855
    3784    5806    7652    7340    9927   13425   16795
River Rch & RM=BARONS CREEK,Reach-1         ,57879
    3784    5806    7652    7340    9927   13425   16795
River Rch & RM=BARONS CREEK,Reach-1         ,56866
    3964    6079    8006    7674   10379   14036   17530
River Rch & RM=BARONS CREEK,Reach-1         ,49904
    4065    6234    8213    7872   10646   14397   17981
River Rch & RM=BARONS CREEK,Reach-1         ,46114
    4210    6468    8529    8184   11068   14969   18735
River Rch & RM=BARONS CREEK,Reach-1         ,42726
    4565    7016    9255    8880   12009   16241   20323
River Rch & RM=BARONS CREEK,Reach-1         ,34078
    4697    7222    9530    9145   12367   16726   20936
River Rch & RM=BARONS CREEK,Reach-1         ,32568
    4730    7273    9597    9210   12455   16845   21086
River Rch & RM=BARONS CREEK,Reach-1         ,30082
    4705    7227    9528    9135   12355   16708   20877
River Rch & RM=BARONS CREEK,Reach-1         ,25052
    5264    8111   10718   10296   13924   18831   23621
River Rch & RM=BARONS CREEK,Reach-1         ,22712
    5916    9132   12082   11618   15712   21249   26701
River Rch & RM=BARONS CREEK,Reach-1         ,13437
    6129    9458   12511   12026   16264   21996   27620
River Rch & RM=BARONS CREEK,Reach-1         ,8849
    6323    9756   12905   12403   16773   22684   28473
River Rch & RM=BARONS CREEK,Reach-1         ,7077
    6323    9756   12905   12403   16773   22684   28473
Boundary for River Rch & Prof#=BARONS CREEK,Reach-1         , 1
Up Type= 0
Dn Type= 3
Dn Slope=0.0026
Boundary for River Rch & Prof#=BARONS CREEK,Reach-1         , 2
Up Type= 0
Dn Type= 3
Dn Slope=0.0026
Boundary for River Rch & Prof#=BARONS CREEK,Reach-1         , 3
Up Type= 0
Dn Type= 3
Dn Slope=0.0026
Boundary for River Rch & Prof#=BARONS CREEK,Reach-1         , 4
Up Type= 0
Dn Type= 3
Dn Slope=0.0026
Boundary for River Rch & Prof#=BARONS CREEK,Reach-1         , 5
Up Type= 0
Dn Type= 3
Dn Slope=0.0026
Boundary for River Rch & Prof#=BARONS CREEK,Reach-1         , 6
Up Type= 0
Dn Type= 3
Dn Slope=0.0026
Boundary for River Rch & Prof#=BARONS CREEK,Reach-1         , 7
Up Type= 0
Dn Type= 3
Dn Slope=0.0026
DSS Import GetInterval= 0
DSS Import GetPeak= 0
DSS Import FillOption= 0

--- BARONS CREEK.g01 (geometry) ---

Geom Title=Existing Conditions
Program Version=4.10

River Reach=BARONS CREEK    ,Reach-1
Reach XY= 30
      2740889.45     10102456.49       2741130.6     10100846.07
      2739360.34     10099484.22      2737128.51      10094732.8
      2738270.79     10091374.72      2740125.88     10089072.66
      2739617.33     10088171.22      2742193.77     10086456.91
      2741850.77     10085297.01      2743977.93     10083015.62
      2744133.32     10081380.76      2745723.31     10080556.14
      2746128.47     10076913.73      2748006.12     10074497.76
      2747049.75     10072674.05      2747473.31     10071651.02
      2751652.56     10070506.75      2753594.54     10067558.16
      2755687.65     10066833.34        2755597.     10065707.64
      2759357.79     10064952.95      2759016.97     10063699.69
      2763093.59     10065164.01      2764904.82      10063479.4
      2764403.76     10061121.21       2767333.7     10058829.95
      2765917.16     10053611.73      2767734.19      10052286.7
      2766803.91     10051366.56      2768444.97     10050942.89

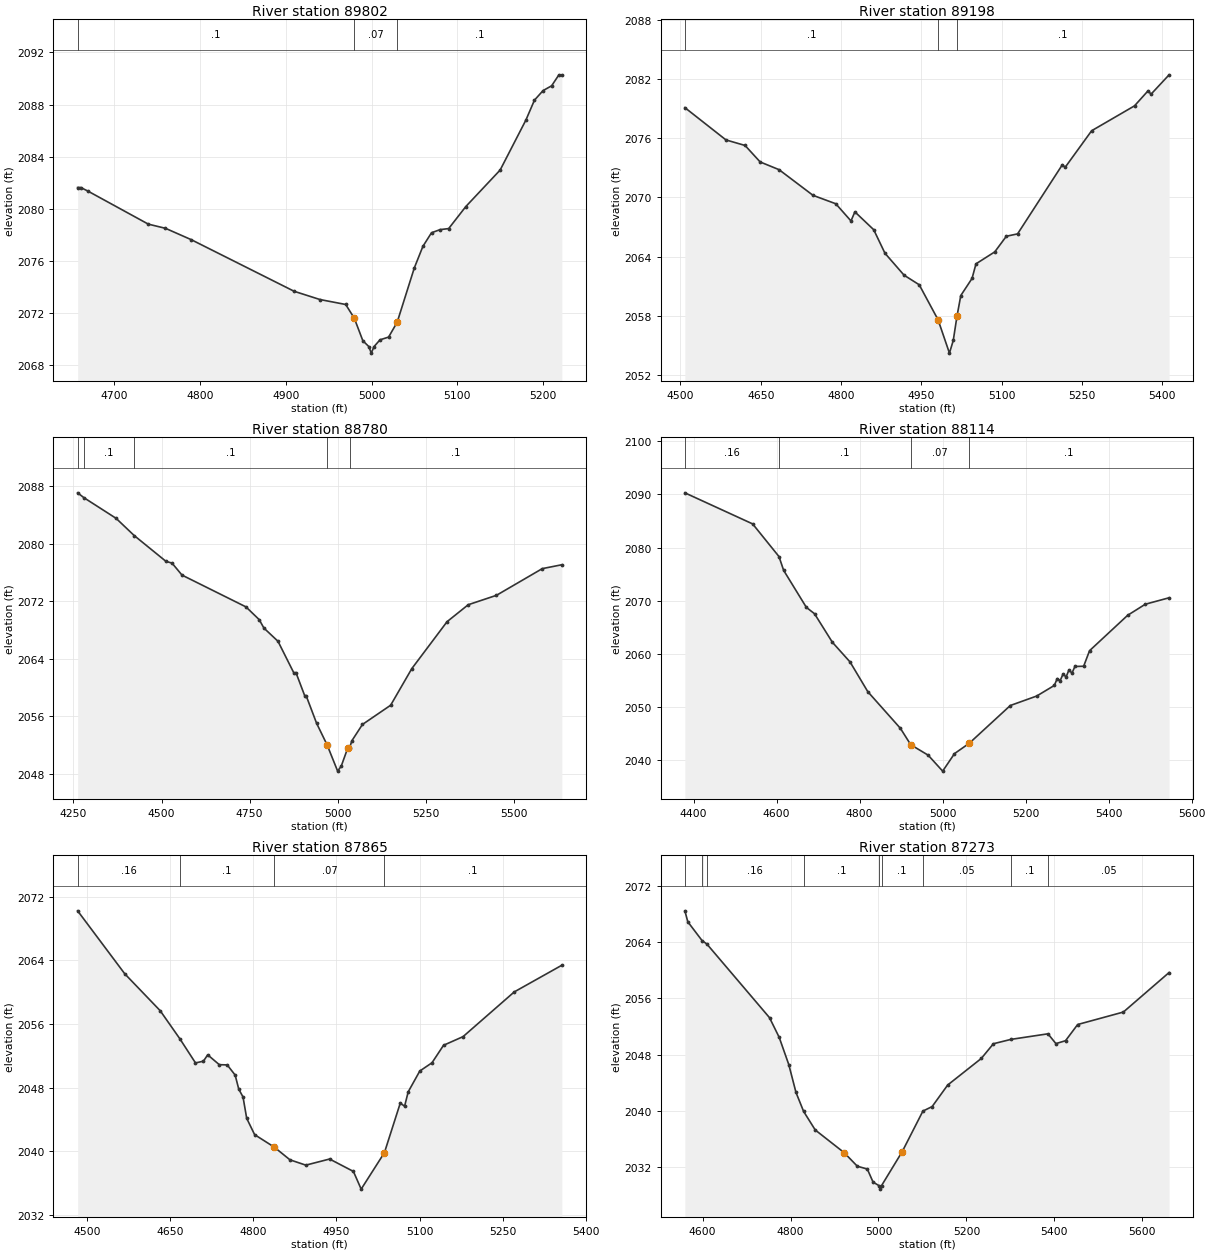
Type RM Length L Ch R = 1 ,89802   ,604,604,604
BEGIN DESCRIPTION:
BARONS CREEK 155.0
END DESCRIPTION:
XS GIS Cut Line= 2
       2741250.9     10102364.74       2740686.6     10102364.74
#Sta/Elev= 30
  4657.5 2081.64  4661.2 2081.64  4669.9 2081.35  4739.9 2078.83  4759.9 2078.51
  4789.9 2077.64  4909.9 2073.68  4939.9 2073.05  4969.9 2072.67  4979.9 2071.62
  4989.9 2069.89  4996.9 2069.44  4999.7 2068.94  5002.9 2069.44  5009.9 2069.96
  5019.9 2070.17  5029.9 2071.31  5049.9 2075.48  5059.9 2077.13  5069.9 2078.17
  5079.9 2078.41  5089.9 2078.49  5109.9 2080.18  5149.9 2082.98  5179.9 2086.81
  5189.9 2088.34  5199.9 2089.07  5209.9 2089.44  5218.4 2090.28  5221.8 2090.28
#Mann= 3 , 0 , 0
  4657.5      .1       0  4979.9     .07       0  5029.9      .1       0
Bank Sta=4979.9,5029.9
XS Rating Curve= 0 ,0
Exp/Cntr=0.3,0.1

Type RM Length L Ch R = 1 ,89198   ,418,418,418
BEGIN DESCRIPTION:
BARONS CREEK 154.0
END DESCRIPTION:
XS GIS Cut Line= 3
      2741441.81     10102139.02      2740981.76     10101713.69
      2740704.03     10101696.34
#Sta/Elev= 30
  4508.3 2079.09  4585.1 2075.82  4620.8 2075.26    4649 2073.59  4684.3 2072.81
  4747.8 2070.21  4790.3 2069.36  4818.7 2067.62    4826 2068.54  4861.2 2066.73
  4882.2 2064.35  4917.9 2062.13  4946.2 2061.16  4981.4 2057.62  5002.7 2054.24
  5009.8 2055.52  5016.7 2057.95  5023.9 2060.07  5044.9  2061.8  5052.3 2063.28
  5087.4 2064.49    5109 2066.07    5130 2066.31  5213.8 2073.32  5218.8 2073.04
  5268.4 2076.75  5348.5 2079.27  5374.1 2080.81  5379.2 2080.44  5413.1 2082.41
#Mann= 3 , 0 , 0
  4508.3      .1       0  4981.4     .07       0  5016.7      .1       0
Bank Sta=4981.4,5016.7
XS Rating Curve= 0 ,0
Exp/Cntr=0.3,0.1

Type RM Length L Ch R = 1 ,88780   ,666,666,666
BEGIN DESCRIPTION:
BARONS CREEK 153.0
END DESCRIPTION:
XS GIS Cut Line= 3
      2741893.21     10101705.01      2741311.62     10101427.24
      2740582.99     10101435.91
#Sta/Elev= 30
  4262.1 2087.11  4280.3 2086.42  4371.1 2083.56  4422.5 2081.16  4512.7 2077.56
  4529.8 2077.32  4558.1 2075.65  4739.5 2071.22  4777.1 2069.44  4790.4 2068.27
  4830.3 2066.43  4875.6 2061.99  4881.2 2062.07  4906.6 2058.78  4910.7 2058.78
  4939.8 2055.01  4969.8 2051.97  4999.5 2048.34  5009.8 2049.05  5028.5 2051.61
  5033.5 2051.59  5039.8 2052.57  5069.8 2054.84  5149.8 2057.52  5209.8 2062.62
  5309.8 2069.16  5369.8 2071.52  5449.8 2072.83  5579.8 2076.55  5635.3 2077.09
#Mann= 5 ,-1 , 0
  4262.1     .16       0  4280.3      .1       0  4422.5      .1       0
  4969.8     .07       0  5033.5      .1       0
Bank Sta=4969.8,5028.5
XS Rating Curve= 0 ,0
Exp/Cntr=0.3,0.1

Type RM Length L Ch R = 1 ,88114   ,249,249,249
BEGIN DESCRIPTION:
BARONS CREEK 152.0
END DESCRIPTION:
XS GIS Cut Line= 3
      2741641.48     10100567.86      2741129.33     10100758.83
       2740686.6     10101192.88
#Sta/Elev= 30
    4379 2090.28  4542.3 2084.44  4605.7 2078.31    4617 2075.71  4671.7 2068.76
  4691.4 2067.56  4734.4  2062.2    4777  2058.5  4819.8 2052.91  4898.3 2046.03
  4923.2 2042.95  4965.1 2040.99  5000.1 2037.99  5028.6 2041.28  5064.1 2043.22
  5163.1 2050.32  5226.7  2052.1  5269.1 2054.09  5276.2 2055.39  5283.2    2055
  5290.4 2056.27  5297.4 2055.66  5304.5 2057.04  5311.5 2056.39  5318.7 2057.65
  5339.8  2057.7    5354 2060.62  5445.8 2067.27  5488.3 2069.35  5545.6 2070.56
#Mann= 4 ,-1 , 0
    4379     .16       0  4605.7      .1       0  4923.2     .07       0
  5064.1      .1       0
Bank Sta=4923.2,5064.1
XS Rating Curve= 0 ,0
Exp/Cntr=0.3,0.1

Type RM Length L Ch R = 1 ,87865   ,592,592,592
BEGIN DESCRIPTION:
BARONS CREEK 151.0
END DESCRIPTION:
XS GIS Cut Line= 2
      2741207.45     10100272.73      2740644.32     10100939.82
#Sta/Elev= 30
  4483.5 2070.25  4568.5 2062.32  4632.3 2057.68    4668 2054.12    4696  2051.1
  4710.3 2051.32    4718 2052.12  4738.9 2050.88  4753.2 2050.85  4767.5 2049.57
    4774  2047.8  4781.7 2046.81  4788.3 2044.13  4802.6 2042.07  4838.2 2040.49
  4866.3  2038.9  4894.9 2038.23  4937.8    2039  4980.7 2037.44  4994.7 2035.21
  5036.6  2039.8  5065.2 2046.04    5073 2045.65  5079.5 2047.46  5100.4 2050.08
  5122.4 2051.12  5143.2 2053.32  5178.4 2054.41  5270.7 2060.04  5356.5  2063.4
#Mann= 4 ,-1 , 0
  4483.5     .16       0    4668      .1       0  4838.2     .07       0
  5036.6      .1       0
Bank Sta=4838.2,5036.6
XS Rating Curve= 0 ,0
Exp/Cntr=0.3,0.1

Type RM Length L Ch R = 1 ,87273   ,471,471,471
BEGIN DESCRIPTION:
BARONS CREEK 150.0
END DESCRIPTION:
XS GIS Cut Line= 2
      2740964.38     10100038.36      2739993.25     10100558.61
#Sta/Elev= 30
  4559.5 2068.42  4566.2 2066.86  4598.6  2064.2  4609.5 2063.71  4752.1 2053.25
  4774.1 2050.46    4796 2046.58  4812.3 2042.64  4829.7 2039.94  4856.1 2037.31
  4921.9 2034.09  4951.9 2032.16  4974.6 2031.76  4987.7 2029.91    5001 2029.41
  5003.7 2028.91    5007 2029.41    5054 2034.23  5101.1 2039.99  5122.1 2040.63
  5157.5 2043.69  5233.9 2047.46  5261.5 2049.55  5301.5 2050.17  5385.6 2050.96
  5403.7 2049.57  5425.6 2049.98  5453.2 2052.28  5557.2 2054.05  5661.2 2059.66
#Mann= 9 ,-1 , 0
  4559.5     .16       0  4598.6      .1       0  4609.5     .16       0
  4829.7      .1       0    5001     .07       0    5007      .1       0
  5101.1     .05       0  5301.5      .1       0  5385.6     .05       0
Bank Sta=4921.9,5054
XS Rating Curve= 0 ,0
Exp/Cntr=0.3,0.1

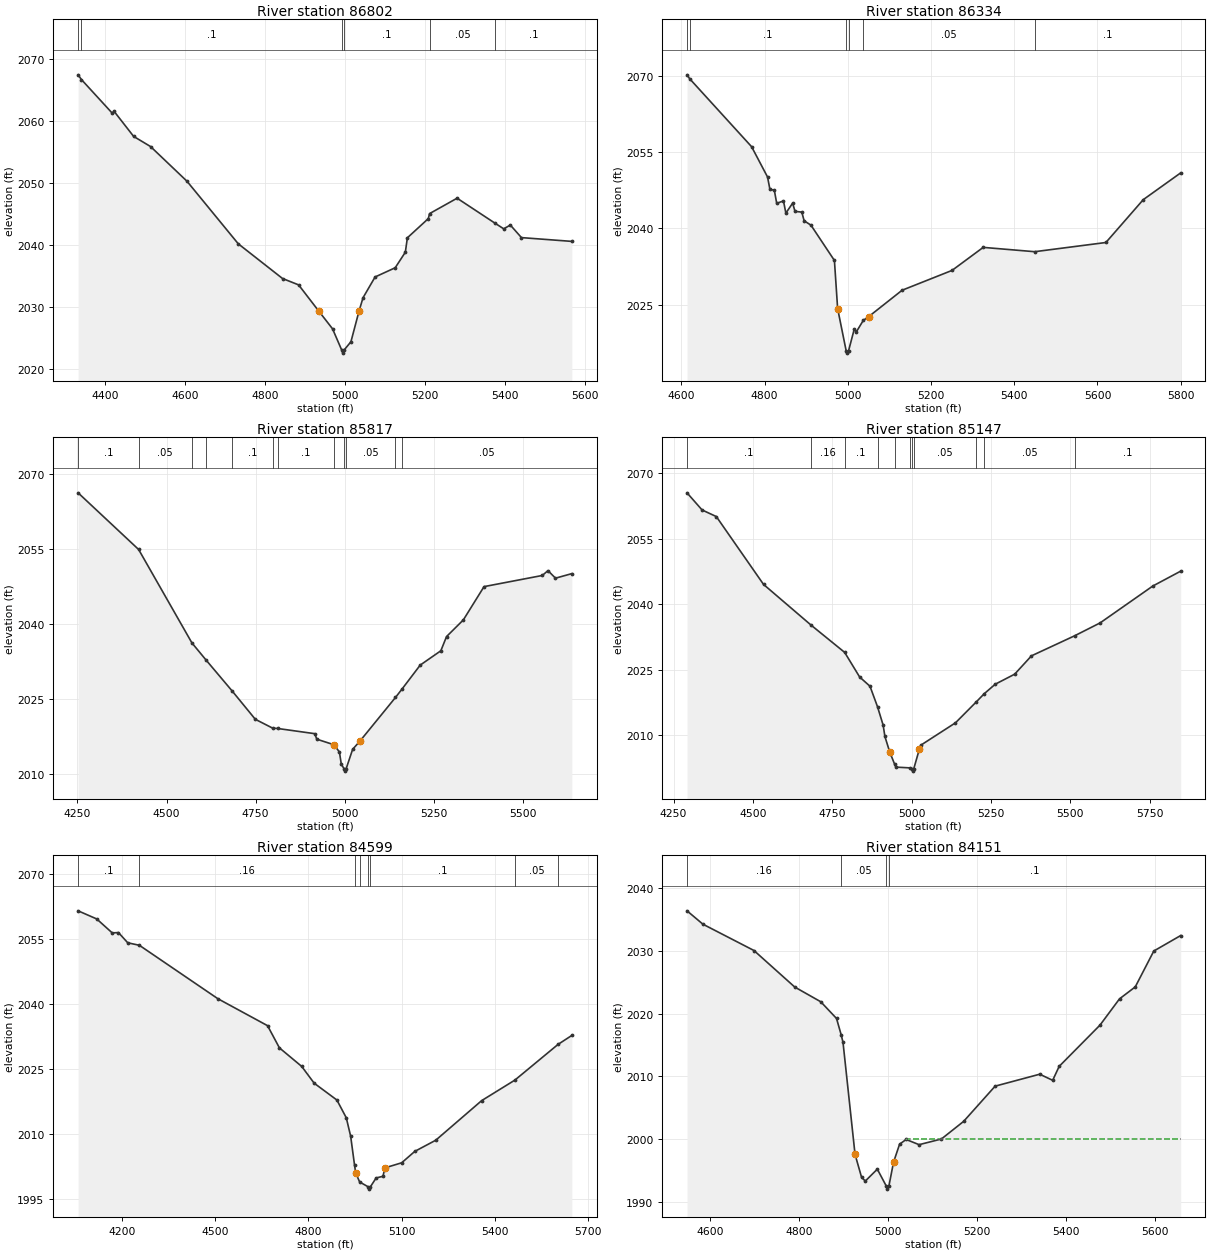
Type RM Length L Ch R = 1 ,86802   ,468,468,468
BEGIN DESCRIPTION:
BARONS CREEK 149.0
END DESCRIPTION:
XS GIS Cut Line= 3
      2741016.47     10099769.25      2740148.43     10099864.74
      2739983.51     10100185.89
#Sta/Elev= 30
    4333 2067.51  4341.4 2066.74  4418.1 2061.33  4423.1  2061.6  4471.8 2057.56
  4514.1 2055.92  4605.1 2050.32  4733.4  2040.2  4844.1 2034.59  4884.3 2033.56
  4934.6 2029.33  4969.1 2026.46    4992 2023.03  4994.7 2022.53    4998 2023.03
  5015.1 2024.37  5035.2 2029.29  5045.3 2031.48  5075.5 2034.84  5125.8 2036.33
  5151.1 2038.84  5156.2 2041.17  5208.5 2044.27  5211.7 2045.08  5280.5 2047.57
    5376  2043.5  5397.1 2042.62  5413.6 2043.23  5441.4  2041.2  5567.3 2040.59
#Mann= 6 ,-1 , 0
    4333     .16       0  4341.4      .1       0    4992     .07       0
    4998      .1       0  5211.7     .05       0    5376      .1       0
Bank Sta=4934.6,5035.2
XS Rating Curve= 0 ,0
Exp/Cntr=0.3,0.1

Type RM Length L Ch R = 1 ,86334   ,517,517,517
BEGIN DESCRIPTION:
BARONS CREEK 148.0
END DESCRIPTION:
XS GIS Cut Line= 3
      2740374.16     10099317.84      2740096.35     10099465.43
      2739870.66     10100307.42
#Sta/Elev= 30
  4613.7 2070.22  4620.3 2069.43  4768.9 2056.08  4807.2 2050.12  4812.9 2047.69
  4823.5 2047.52  4829.2 2044.95  4845.5 2045.41  4851.2 2043.02  4867.5 2044.98
  4873.2 2043.36  4889.5 2043.22  4895.1 2041.51  4911.5 2040.65  4967.9  2033.7
  4975.6 2024.24    4996 2015.98  4998.8 2015.48    5002 2015.98  5015.6 2020.22
  5020.8  2019.7  5037.2 2021.91  5050.4 2022.67  5130.5 2027.85  5250.5 2031.75
  5325.4 2036.28    5449 2035.43  5620.2 2037.24    5710 2045.67    5800 2050.94
#Mann= 6 ,-1 , 0
  4613.7     .16       0  4620.3      .1       0    4996     .07       0
    5002      .1       0  5037.2     .05       0    5449      .1       0
Bank Sta=4975.6,5050.4
XS Rating Curve= 0 ,0
Exp/Cntr=0.3,0.1

Type RM Length L Ch R = 1 ,85817   ,670,670,670
BEGIN DESCRIPTION:
BARONS CREEK 147.0
END DESCRIPTION:
XS GIS Cut Line= 3
      2740191.84     10099196.33      2739592.87     10099500.15
      2739367.19     10100177.21
#Sta/Elev= 30
  4251.8 2066.27  4421.6 2054.94  4571.2 2036.25  4611.4 2032.78  4684.4 2026.61
    4749 2020.98  4797.6 2019.21  4811.6 2019.14  4915.9  2018.1  4921.5    2017
  4968.6 2015.91  4969.4  2015.9    4985 2014.44  4990.4 2011.96    4998 2011.11
  5000.7 2010.61    5004 2011.11  5022.1 2014.97    5043 2016.65  5142.3 2025.34
  5160.2 2026.98  5211.8 2031.82  5269.6 2034.68  5285.6 2037.52  5332.8 2040.86
  5390.8 2047.51  5554.2 2049.74  5570.2 2050.71  5591.3  2049.2  5637.1 2050.11
#Mann= 12 ,-1 , 0
  4251.8      .1       0  4421.6     .05       0  4571.2     .16       0
  4611.4     .05       0  4684.4      .1       0  4797.6     .05       0
  4811.6      .1       0  4968.6     .05       0    4998    .035       0
    5004     .05       0  5142.3      .1       0  5160.2     .05       0
Bank Sta=4969.4,5043
XS Rating Curve= 0 ,0
Exp/Cntr=0.3,0.1

Type RM Length L Ch R = 1 ,85147   ,548,548,548
BEGIN DESCRIPTION:
BARONS CREEK 145.0
END DESCRIPTION:
XS GIS Cut Line= 2
      2740105.04     10098875.15      2738603.37     10099283.12
#Sta/Elev= 30
  4292.3 2065.56  4339.7 2061.63  4384.7 2060.11  4533.5 2044.54  4683.6 2035.18
  4789.2 2028.94  4836.4 2023.29    4869 2021.17  4892.7 2016.47  4910.5 2012.23
    4916 2009.64  4931.2 2006.08  4946.8 2003.25  4950.6 2002.61  4996.2 2002.43
  5000.8 2002.19  5003.5 2001.69  5006.8 2002.19  5024.5 2006.69  5030.2 2007.69
  5138.5 2012.78  5203.2 2017.52  5229.4 2019.48  5263.8 2021.64    5325 2023.94
    5378 2028.15  5513.7 2032.74  5594.4 2035.71  5760.4 2044.17  5848.4 2047.59
#Mann= 11 ,-1 , 0
  4292.3      .1       0  4683.6     .16       0  4789.2      .1       0
  4892.7     .05       0  4946.8      .1       0  4996.2     .05       0
  5000.8    .035       0  5006.8     .05       0  5203.2      .1       0
  5229.4     .05       0  5513.7      .1       0
Bank Sta=4931.2,5024.5
XS Rating Curve= 0 ,0
Exp/Cntr=0.3,0.1

Type RM Length L Ch R = 1 ,84599   ,448,448,448
BEGIN DESCRIPTION:
BARONS CREEK 144.0
END DESCRIPTION:
XS GIS Cut Line= 3
       2740148.4     10098562.65       2739315.1     10098519.25
      2738646.68     10098875.16
#Sta/Elev= 30
  4057.3 2061.49  4117.3 2059.62  4167.4  2056.4  4187.4 2056.48  4217.4 2054.12
  4254.8 2053.55  4507.8 2041.24  4668.1 2035.02  4706.3 2029.91  4778.2 2025.63
  4818.3 2021.77  4891.7 2017.88  4921.9 2013.79    4936 2009.55  4948.7  2002.8
  4952.3 2001.06    4965    1999  4993.3 1997.85    4996 1997.35  4999.3 1997.85
  5018.2 1999.93  5040.2 2000.31  5046.5 2002.25  5100.5 2003.42  5142.8 2006.05
  5210.3 2008.62  5358.4 2017.75  5465.5 2022.48  5604.5  2030.7    5649 2032.77
#Mann= 8 ,-1 , 0
  4057.3      .1       0  4254.8     .16       0  4948.7     .05       0
    4965      .1       0  4993.3     .07       0  4999.3      .1       0
  5465.5     .05       0  5604.5      .1       0
Bank Sta=4952.3,5046.5
XS Rating Curve= 0 ,0
Exp/Cntr=0.3,0.1

Type RM Length L Ch R = 1 ,84151   ,492,492,492
BEGIN DESCRIPTION:
BARONS CREEK 143.0
END DESCRIPTION:
XS GIS Cut Line= 2
      2739332.47     10097937.65      2738438.33      10098597.4
#Sta/Elev= 30
  4547.3 2036.37  4583.1 2034.24    4698 2030.05  4789.8 2024.23  4848.3 2021.89
  4883.8 2019.23  4894.1 2016.67  4898.4 2015.42  4925.5 1997.57  4940.1 1993.95
  4948.5 1993.33  4975.6 1995.23  4995.7 1992.55  4998.4 1992.05  5001.7 1992.55
  5012.1 1996.33  5025.7  1999.2  5040.4 1999.96  5069.6 1999.13  5119.8 2000.03
  5169.9 2002.84  5240.8 2008.45  5341.1 2010.35  5370.3 2009.38  5384.9  2011.6
  5476.8 2018.17  5520.7 2022.35  5556.2 2024.26  5597.9 2029.97  5658.5 2032.44
#Mann= 4 ,-1 , 0
  4547.3     .16       0  4894.1     .05       0  4995.7     .07       0
  5001.7      .1       0
#XS Ineff= 2 , 0
                         5041.14         2000.01
Permanent Ineff=
       T       T
Bank Sta=4925.5,5012.1
XS Rating Curve= 0 ,0
Exp/Cntr=0.3,0.1

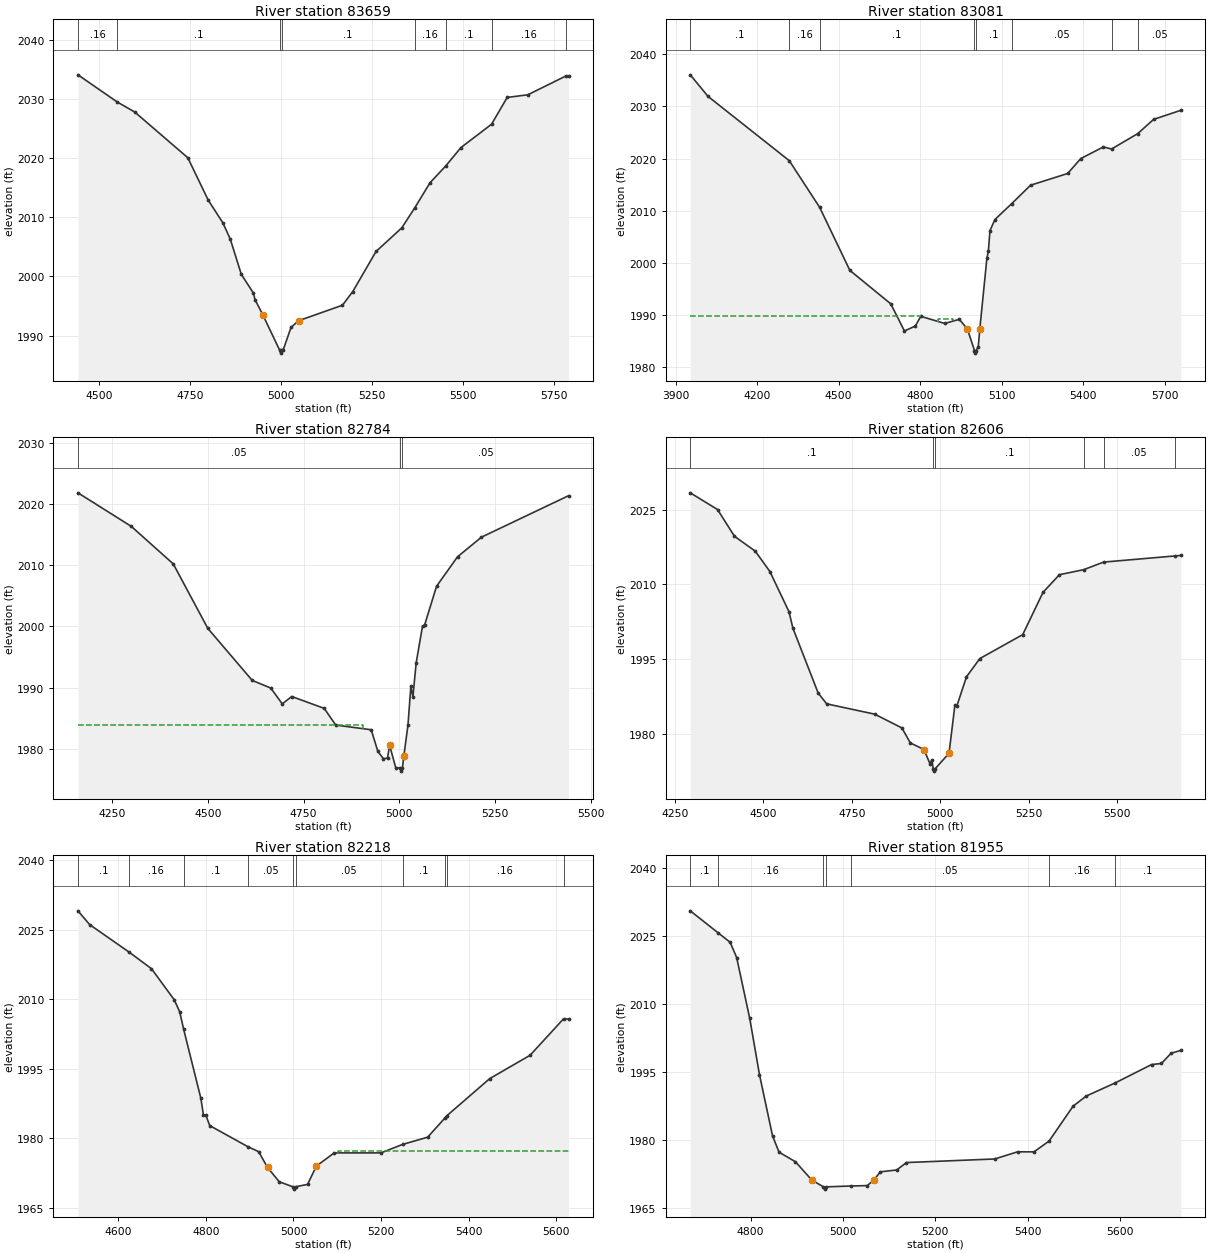
Type RM Length L Ch R = 1 ,83659   ,578,578,578
BEGIN DESCRIPTION:
BARONS CREEK 142.0
END DESCRIPTION:
XS GIS Cut Line= 3
      2739132.82     10097755.36      2738655.37     10097824.81
      2738065.09      10098458.5
#Sta/Elev= 30
  4441.4 2034.05  4549.2 2029.47  4597.4 2027.77  4743.3 2020.05  4799.5 2012.88
  4839.9 2009.03  4860.1  2006.3  4890.4 2000.35  4923.9 1997.16    4928 1996.08
  4949.5 1993.51  4995.8 1987.54  4998.5 1987.04  5001.8 1987.54  5005.6 1987.59
  5027.1 1991.39  5048.1 1992.52  5168.4 1995.13  5196.7 1997.43  5260.7 2004.21
  5331.5  2008.2  5366.7 2011.53  5409.2 2015.83  5451.9 2018.63  5494.2 2021.77
  5578.2  2025.7  5621.2 2030.23  5677.9 2030.68  5781.9 2033.83  5789.9 2033.88
#Mann= 8 ,-1 , 0
  4441.4     .16       0  4549.2      .1       0  4995.8     .07       0
  5001.8      .1       0  5366.7     .16       0  5451.9      .1       0
  5578.2     .16       0  5781.9      .1       0
Bank Sta=4949.5,5048.1
XS Rating Curve= 0 ,0
Exp/Cntr=0.3,0.1

Type RM Length L Ch R = 1 ,83081   ,297,297,297
BEGIN DESCRIPTION:
BARONS CREEK 141.0
END DESCRIPTION:
XS GIS Cut Line= 3
      2739193.59      10097468.9      2738290.79     10097547.03
       2737457.5     10097885.55
#Sta/Elev= 30
  3954.2 2036.05  4019.6 2031.91  4318.3  2019.6  4430.4 2010.64  4541.5 1998.55
  4692.1 1992.13  4742.3 1986.93  4782.4 1987.87  4802.5 1989.74  4890.7 1988.37
  4944.2 1989.16  4973.7 1987.35  5000.2 1983.18  5002.9 1982.68  5006.2 1983.18
    5014  1983.9 5019.76 1987.32  5045.9 2000.88  5051.3 2002.25  5057.2 2006.17
  5075.4  2008.3  5136.8 2011.33  5206.6 2014.88  5343.2 2017.13  5391.3 2019.99
  5474.4 2022.22  5504.8 2021.83  5601.2 2024.78  5659.1  2027.5  5759.8 2029.25
#Mann= 8 ,-1 , 0
  3954.2      .1       0  4318.3     .16       0  4430.4      .1       0
  5000.2     .07       0  5006.2      .1       0  5136.8     .05       0
  5504.8      .1       0  5601.2     .05       0
#XS Ineff= 2 ,-1
  3954.2 4802.59 1989.75 4866.93 4919.82 1989.28
Permanent Ineff=
       T       T
Bank Sta=4973.7,5019.76
XS Rating Curve= 0 ,0
Exp/Cntr=0.3,0.1

Type RM Length L Ch R = 1 ,82784   ,178,178,178
BEGIN DESCRIPTION:
Mapping XS 5bb828ea
END DESCRIPTION:
XS GIS Cut Line= 3
      2738933.13     10097008.84      2738230.03     10097277.93
      2737735.27     10097460.21
#Sta/Elev= 30
  4161.2  2021.8  4300.4 2016.32  4409.9 2010.19    4500 1999.66  4615.9 1991.16
  4664.3 1989.91  4694.3 1987.33    4719 1988.53  4803.8 1986.59  4833.9 1983.86
  4926.4  1983.1  4943.8 1979.55  4958.3 1978.37  4968.9 1978.47  4974.3 1980.58
  4990.3 1976.92  5001.7 1976.84  5004.5 1976.34  5007.7 1976.84  5011.6 1978.85
  5022.3 1983.86  5029.8 1990.19  5035.2 1988.46  5043.6 1993.98  5060.3 2000.06
  5065.6 2000.19  5096.9 2006.54  5151.6 2011.35  5214.1 2014.56  5441.3 2021.33
#Mann= 3 ,-1 , 0
  4161.2     .05       0  5001.7     .04       0  5007.7     .05       0
#XS Ineff= 2 , 0
         4904.55 1983.89
Permanent Ineff=
       T       T
Bank Sta=4974.3,5011.6
XS Rating Curve= 0 ,0
Exp/Cntr=0.3,0.1

Type RM Length L Ch R = 1 ,82606   ,388,388,388
BEGIN DESCRIPTION:
BARONS CREEK 140.0
END DESCRIPTION:
XS GIS Cut Line= 4
      2738846.38     10096869.93      2738238.71     10097121.68
      2737986.97     10097199.81      2737562.52     10097390.37
#Sta/Elev= 30
  4293.1 2028.42  4370.2 2025.06    4418 2019.69  4476.6 2016.71  4518.1 2012.61
  4572.1 2004.53  4583.1 2001.23  4654.6 1988.19  4678.5 1986.02  4814.2 1983.95
  4891.2 1981.18  4915.1 1978.16  4953.6 1976.84  4970.7 1973.96    4976 1974.78
  4979.5    1973  4982.3  1972.5  4985.5    1973  5024.4 1976.09  5041.1 1985.81
  5046.3 1985.54  5073.7 1991.45  5111.5 1995.12  5232.7 1999.93    5290 2008.42
  5336.4 2011.97  5405.1 2012.98  5461.1  2014.5  5663.2 2015.74  5679.7 2015.83
#Mann= 6 ,-1 , 0
  4293.1      .1       0  4979.5     .07       0  4985.5      .1       0
  5405.1     .16       0  5461.1     .05       0  5663.2      .1       0
Bank Sta=4953.6,5024.4
XS Rating Curve= 0 ,0
Exp/Cntr=0.3,0.1

Type RM Length L Ch R = 1 ,82218   ,263,263,263
BEGIN DESCRIPTION:
BARONS CREEK 139.0
END DESCRIPTION:
XS GIS Cut Line= 3
      2738724.78     10096678.98      2738082.46     10096791.82
      2737726.56     10097095.63
#Sta/Elev= 30
  4507.9 2029.12  4534.6 2026.15  4624.4 2020.23  4675.8 2016.63  4727.5 2009.95
  4740.2 2007.33  4749.1 2003.61  4788.5 1988.67  4794.5    1985  4799.6 1985.08
  4808.8 1982.77  4896.2  1978.2  4920.4 1977.15  4940.7 1973.74  4967.5 1970.65
  4998.7 1969.56  5001.4 1969.06  5004.7 1969.56  5032.1 1970.09  5052.4 1974.05
    5093 1976.88  5199.8 1976.88  5249.1 1978.71  5306.3 1980.27  5345.3 1984.36
    5350 1984.89    5448 1992.91  5540.2 1997.95  5616.6 2005.82    5628 2005.76
#Mann= 10 ,-1 , 0
  4507.9      .1       0  4624.4     .16       0  4749.1      .1       0
  4896.2     .05       0  4998.7    .035       0  5004.7     .05       0
  5249.1      .1       0  5345.3     .05       0    5350     .16       0
  5616.6      .1       0
#XS Ineff= 2 , 0
                         5101.59         1977.26
Permanent Ineff=
       T       T
Bank Sta=4940.7,5052.4
XS Rating Curve= 0 ,0
Exp/Cntr=0.3,0.1

Type RM Length L Ch R = 1 ,81955   ,509,509,509
BEGIN DESCRIPTION:
BARONS CREEK 138.0
END DESCRIPTION:
XS GIS Cut Line= 2
      2738403.65     10096297.02      2737639.72      10097034.9
#Sta/Elev= 30
  4669.5 2030.55  4730.1 2025.66  4755.8 2023.61  4769.9 2020.24  4798.2  2006.8
  4819.3 1994.38  4847.6 1980.84  4861.7 1977.24  4897.2 1975.13  4932.5 1971.09
  4957.8 1969.58  4960.5 1969.08  4963.8 1969.58  5016.6 1969.77  5052.6 1969.86
  5066.8 1971.06  5080.9  1972.9  5116.4 1973.31  5137.5 1974.95  5328.6 1975.74
    5378 1977.32  5413.5 1977.31  5446.3  1979.7  5498.2  1987.4  5526.5 1989.63
  5589.6 1992.55    5668 1996.59  5689.3 1996.83  5710.4 1999.09  5731.6 1999.73
#Mann= 7 ,-1 , 0
  4669.5      .1       0  4730.1     .16       0  4957.8     .07       0
  4963.8     .16       0  5016.6     .05       0  5446.3     .16       0
  5589.6      .1       0
#XS Ineff= 2 , 0
                         5137.27         1974.92
Permanent Ineff=
       T       T
Bank Sta=4932.5,5066.8
XS Rating Curve= 0 ,0
Exp/Cntr=0.3,0.1

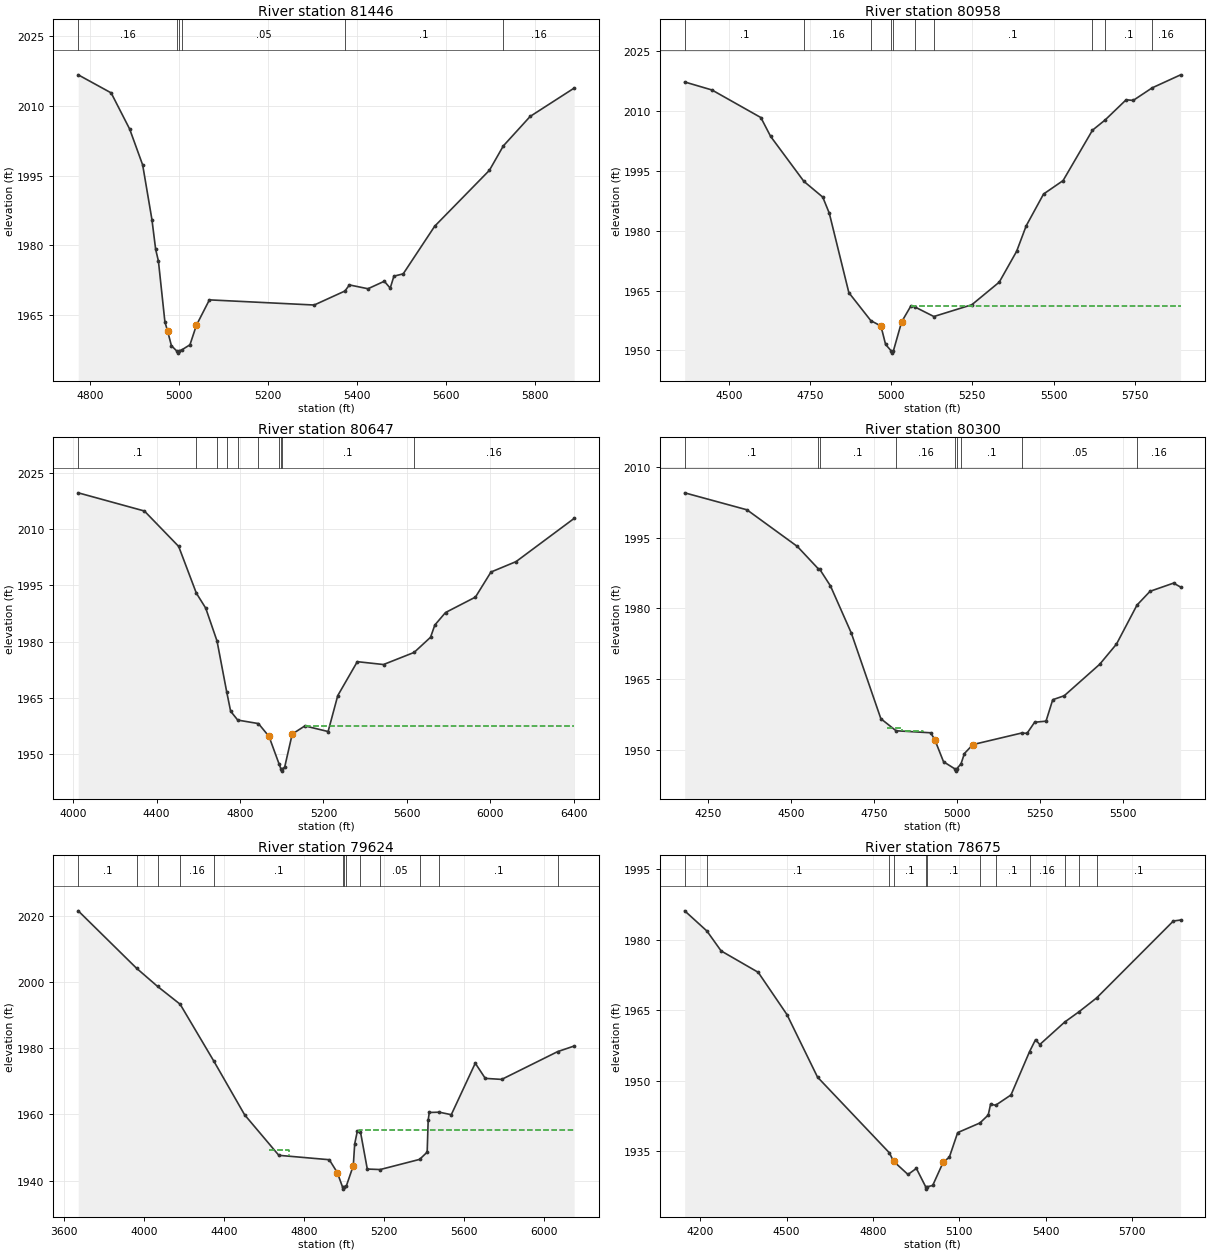
Type RM Length L Ch R = 1 ,81446   ,488,488,488
BEGIN DESCRIPTION:
BARONS CREEK 137.0
END DESCRIPTION:
XS GIS Cut Line= 2
      2737900.17     10096062.64      2737232.62      10096955.6
#Sta/Elev= 30
  4773.9 2016.73  4847.9 2012.84  4889.6 2005.03  4918.8  1997.3  4939.6 1985.54
    4948  1979.1  4954.2  1976.6  4968.8 1963.47    4975 1961.45  4983.4 1958.34
    4995 1957.24  4997.7 1956.74    5001 1957.24    5007 1957.45  5025.1 1958.54
  5039.7 1962.77  5068.8 1968.22  5304.4 1967.11  5373.5 1970.13  5383.6 1971.44
  5425.3 1970.62    5462 1972.23  5475.3 1970.75  5483.6 1973.33  5504.5 1973.83
  5575.3  1984.1  5698.3 1996.15  5729.6 2001.41    5790 2007.77  5888.8 2013.87
#Mann= 6 ,-1 , 0
  4773.9     .16       0    4995     .07       0    5001     .16       0
    5007     .05       0  5373.5      .1       0  5729.6     .16       0
Bank Sta=4975,5039.7
XS Rating Curve= 0 ,0
Exp/Cntr=0.3,0.1

Type RM Length L Ch R = 1 ,80958   ,311,311,311
BEGIN DESCRIPTION:
BARONS CREEK 136.0
END DESCRIPTION:
XS GIS Cut Line= 4
       2737952.2     10096001.89      2737414.05     10095958.49
      2737240.44     10096106.06      2736954.09     10096808.91
#Sta/Elev= 30
  4364.4 2017.28  4448.4 2015.27  4598.9 2008.36    4629 2003.63  4731.3 1992.37
  4789.5 1988.41  4809.6 1984.37  4869.8 1964.46  4937.5 1957.44  4968.6 1956.09
  4982.8  1951.5  5000.7  1949.8  5003.4  1949.3  5006.7  1949.8  5032.3 1957.15
  5060.8 1961.13    5072 1960.92  5131.5 1958.48  5248.4 1961.43  5332.8  1967.1
  5386.3 1974.83  5415.7 1981.21  5469.2 1989.19  5529.2 1992.55  5619.8 2005.19
  5658.4 2007.73  5723.5 2012.82  5745.1 2012.65  5803.4  2015.8  5891.1 2019.07
#Mann= 10 ,-1 , 0
  4364.4      .1       0  4731.3     .16       0  4937.5      .1       0
  5000.7     .07       0  5006.7      .1       0    5072     .16       0
  5131.5      .1       0  5619.8     .16       0  5658.4      .1       0
  5803.4     .16       0
#XS Ineff= 2 , 0
                         5060.79         1961.16
Permanent Ineff=
       T       T
Bank Sta=4968.6,5032.3
XS Rating Curve= 0 ,0
Exp/Cntr=0.3,0.1

Type RM Length L Ch R = 1 ,80647   ,347,347,347
BEGIN DESCRIPTION:
BARONS CREEK 135.0
END DESCRIPTION:
XS GIS Cut Line= 3
       2738151.9     10095923.76      2736893.22     10095724.11
      2735816.83     10095967.17
#Sta/Elev= 30
  4024.4 2019.64  4341.7  2014.8  4506.1 2005.37  4590.8 1992.93  4635.7 1988.95
    4690 1980.19  4736.1 1966.73  4755.2  1961.5  4789.3 1959.14  4888.5 1958.21
  4939.1  1954.8  4987.8 1947.41  4996.9 1946.05  4999.6 1945.55  5002.9 1946.05
  5014.5 1946.65  5050.5 1955.42  5111.3 1957.59  5222.6 1956.09  5268.8 1965.65
  5362.6 1974.69  5488.2 1973.93  5634.9 1977.15  5713.8 1981.19  5734.3 1984.45
  5785.5 1987.77    5929 1991.88  6003.4 1998.55  6123.8 2001.33  6402.3 2012.83
#Mann= 10 ,-1 , 0
  4024.4      .1       0  4590.8     .16       0    4690      .1       0
  4736.1     .05       0  4789.3      .1       0  4888.5     .05       0
  4987.8      .1       0  4996.9     .07       0  5002.9      .1       0
  5634.9     .16       0
#XS Ineff= 2 , 0
                         5110.94         1957.61
Permanent Ineff=
       T       T
Bank Sta=4939.1,5050.5
XS Rating Curve= 0 ,0
Exp/Cntr=0.3,0.1

Type RM Length L Ch R = 1 ,80300   ,676,676,676
BEGIN DESCRIPTION:
BARONS CREEK 134.0
END DESCRIPTION:
XS GIS Cut Line= 3
      2737969.59     10095689.38      2736971.35     10095350.85
      2736537.36     10095290.09
#Sta/Elev= 30
  4180.3 2004.56  4367.7 2000.95  4519.4 1993.16  4581.6 1988.47  4586.9 1988.29
    4619 1984.77  4681.8 1974.74  4770.7 1956.54  4816.4 1953.99  4920.6 1953.56
    4933 1952.08  4959.2  1947.4  4992.9 1945.91  4995.6 1945.41  4998.9 1945.91
  5011.7 1946.94    5022 1949.15  5047.4 1951.05  5194.3 1953.51  5210.4 1953.44
  5233.3  1955.8  5267.6 1956.03  5287.8 1960.59  5322.4 1961.43  5429.1 1968.12
  5479.6 1972.41  5541.3  1980.7  5580.6 1983.63  5651.3 1985.37  5672.6 1984.53
#Mann= 9 ,-1 , 0
  4180.3      .1       0  4581.6     .16       0  4586.9      .1       0
  4816.4     .16       0  4992.9     .07       0  4998.9     .16       0
  5011.7      .1       0  5194.3     .05       0  5541.3     .16       0
#XS Ineff= 2 ,-1
 4790.01 4833.47 1954.49 4842.52 4896.47 1953.89
Permanent Ineff=
       T       T
Bank Sta=4933,5047.4
XS Rating Curve= 0 ,0
Exp/Cntr=0.3,0.1

Type RM Length L Ch R = 1 ,79624   ,949,949,949
BEGIN DESCRIPTION:
BARONS CREEK 132.0
END DESCRIPTION:
XS GIS Cut Line= 3
      2738377.63     10095298.78      2737240.44     10094873.42
      2735973.96     10094838.72
#Sta/Elev= 30
  3669.5 2021.54  3961.1  2004.2  4066.5 1998.69  4179.5  1993.3  4348.5 1976.05
  4502.1 1959.87  4673.1 1947.63  4925.6  1946.3  4965.6 1942.42  4992.7 1937.91
  4995.4 1937.41  4998.7 1937.91  5011.3 1938.44  5045.7 1944.51  5052.7 1951.08
  5065.7  1954.9  5081.7 1954.68  5115.7 1943.48  5180.3 1943.33  5377.5  1946.4
  5415.3  1948.6  5420.3 1958.24  5425.8 1960.58  5476.1 1960.67  5535.9 1959.91
  5655.9 1975.48  5705.9 1970.89    5788 1970.58  6067.7 1978.97  6150.6 1980.67
#Mann= 13 ,-1 , 0
  3669.5      .1       0  3961.1     .16       0  4066.5      .1       0
  4179.5     .16       0  4348.5      .1       0  4992.7     .07       0
  4998.7      .1       0  5011.3     .16       0  5081.7      .1       0
  5180.3     .05       0  5377.5     .16       0  5476.1      .1       0
  6067.7     .05       0
#XS Ineff= 2 ,-1
  4623.3 4722.16 1949.29    5075  6150.6 1955.29
Permanent Ineff=
       T       T
Bank Sta=4965.6,5045.7
XS Rating Curve= 0 ,0
Exp/Cntr=0.3,0.1

Type RM Length L Ch R = 1 ,78675   ,574,574,574
BEGIN DESCRIPTION:
BARONS CREEK 130.0
END DESCRIPTION:
XS GIS Cut Line= 2
      2738334.21      10094665.1      2736963.05     10093623.71
#Sta/Elev= 30
  4146.5 1986.18  4223.8 1981.87  4272.9 1977.64  4401.8 1973.07  4501.6 1964.06
  4607.7 1950.73  4857.1 1934.59  4871.7 1932.79  4921.8 1929.97  4950.9 1931.27
  4983.2 1927.35    4986 1926.85  4989.2 1927.35  5007.6 1927.64  5044.4 1932.64
  5065.2 1933.63  5094.3  1938.9  5171.4 1940.95  5200.4 1942.65  5208.5 1944.96
    5226 1944.73  5279.4 1946.93  5343.8 1956.16  5364.7 1958.72  5379.3 1957.67
  5465.9 1962.47  5516.3  1964.7  5576.8 1967.62  5843.1 1984.01  5868.3 1984.22
#Mann= 12 ,-1 , 0
  4146.5     .16       0  4223.8      .1       0  4857.1     .05       0
  4871.7      .1       0  4983.2     .07       0  4989.2      .1       0
  5171.4     .05       0    5226      .1       0  5343.8     .16       0
  5465.9      .1       0  5516.3     .05       0  5576.8      .1       0
Bank Sta=4871.7,5044.4
XS Rating Curve= 0 ,0
Exp/Cntr=0.3,0.1