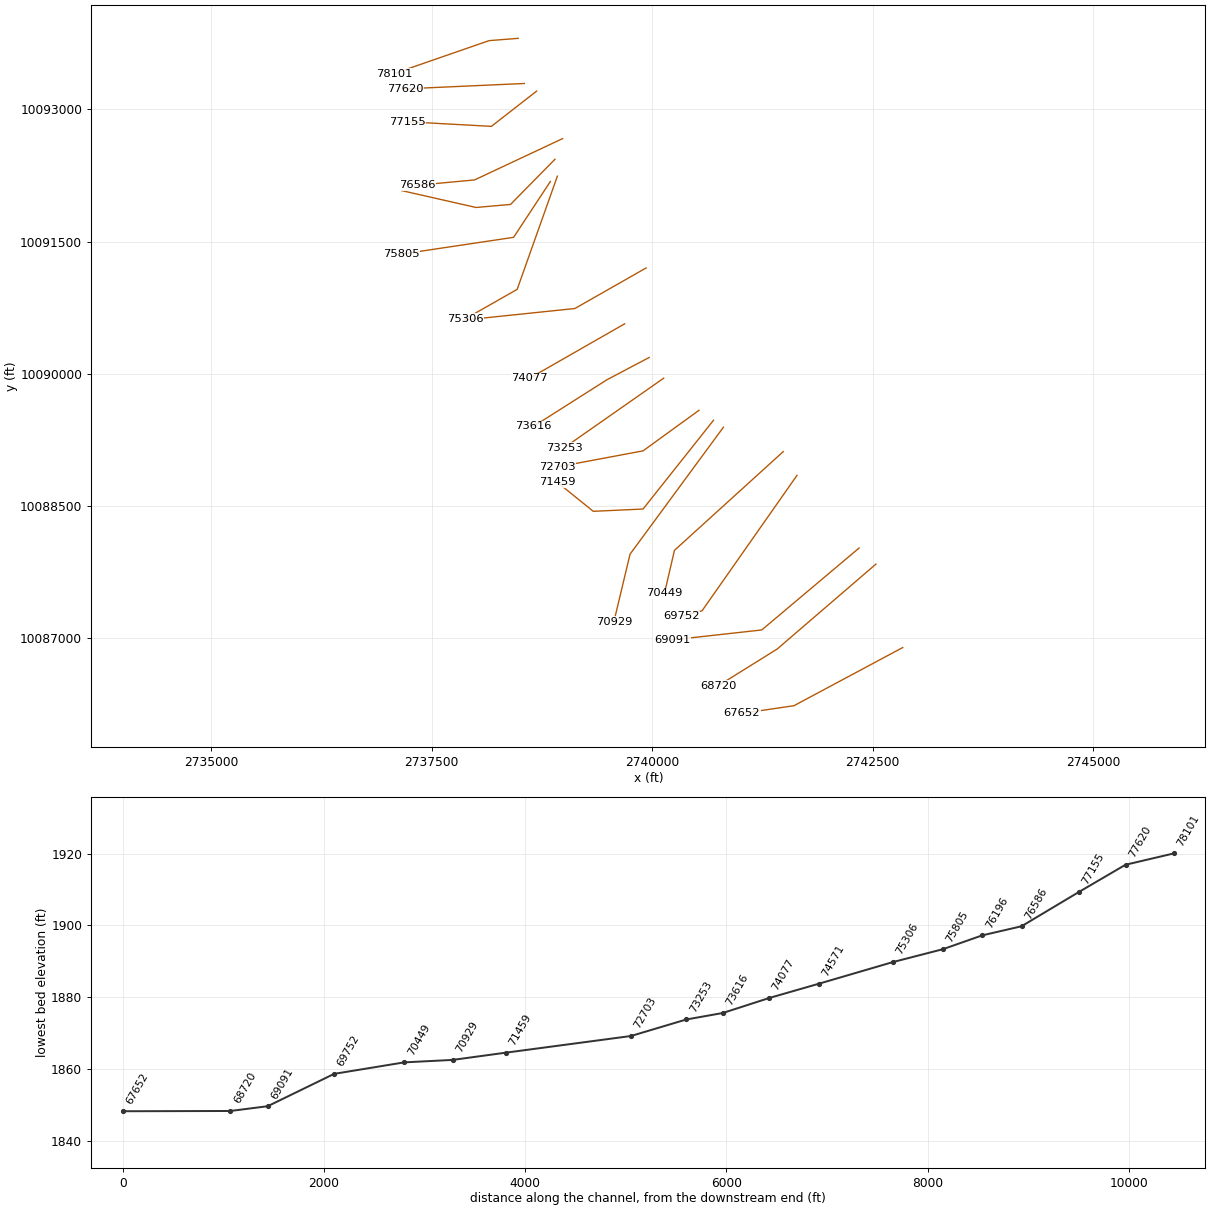
HEC-RAS study BARONS CREEK.prj: BARONS CREEK Base Level Engineering

--- BARONS CREEK.g01 (geometry) --- (continued)

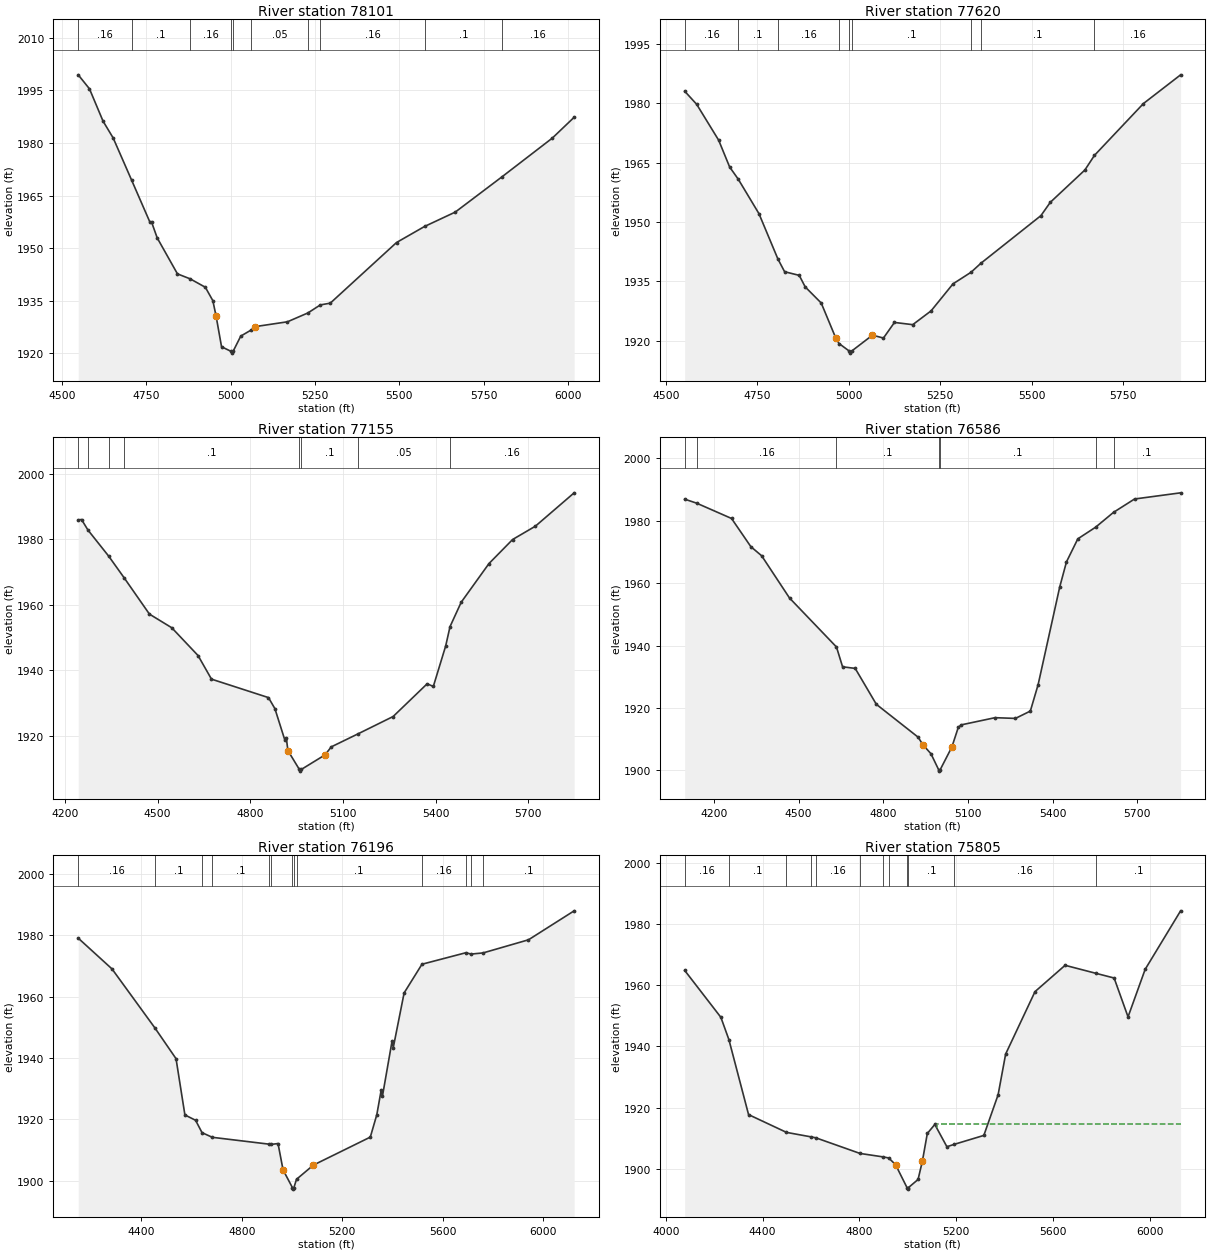
Type RM Length L Ch R = 1 ,78101   ,481,481,481
BEGIN DESCRIPTION:
BARONS CREEK 129.0
END DESCRIPTION:
XS GIS Cut Line= 3
       2738481.8     10093805.71       2738151.9     10093779.67
      2737075.51      10093406.4
#Sta/Elev= 30
  4547.8 1999.45  4581.2 1995.45  4621.4 1986.24  4651.5 1981.42  4705.9 1969.45
  4760.2 1957.45  4765.2 1957.46  4781.9 1952.94    4842 1942.66  4879.8 1941.24
  4924.7 1938.84  4946.9 1935.02  4956.5 1930.63  4972.7 1921.87  5000.9 1920.55
  5003.6 1920.05  5006.9 1920.55  5029.7 1924.91  5059.9 1926.61  5072.9 1927.62
  5168.1 1928.99  5228.6 1931.51  5265.7 1933.81  5295.1 1934.31  5491.5 1951.61
  5574.4 1956.18  5665.6 1960.29  5804.6 1970.39  5953.3  1981.4    6018 1987.34
#Mann= 10 ,-1 , 0
  4547.8     .16       0  4705.9      .1       0  4879.8     .16       0
  5000.9     .07       0  5006.9     .16       0  5059.9     .05       0
  5228.6      .1       0  5265.7     .16       0  5574.4      .1       0
  5804.6     .16       0
Bank Sta=4956.5,5072.9
XS Rating Curve= 0 ,0
Exp/Cntr=0.3,0.1

Type RM Length L Ch R = 1 ,77620   ,465,465,465
BEGIN DESCRIPTION:
BARONS CREEK 128.0
END DESCRIPTION:
XS GIS Cut Line= 2
      2738551.25     10093293.56      2737197.02     10093232.79
#Sta/Elev= 30
  4551.2 1983.05    4584 1979.73  4644.1 1970.67  4674.1  1963.9  4697.7 1960.81
  4754.2 1952.12    4806 1940.67  4824.3 1937.45  4864.3 1936.53  4880.6 1933.62
  4924.4 1929.55  4964.4 1920.66  4973.1 1919.31  5001.4 1917.39  5004.2 1916.89
  5007.4 1917.39  5064.5 1921.43  5094.5  1920.7  5124.6 1924.64  5174.6 1924.08
  5224.7 1927.56  5284.7 1934.39    5334 1937.32  5360.9 1939.59    5525 1951.62
  5550.6 1954.98  5645.1 1963.14  5671.4 1966.85  5805.2 1979.93  5906.8 1987.18
#Mann= 9 ,-1 , 0
  4551.2     .16       0  4697.7      .1       0    4806     .16       0
  4973.1      .1       0  5001.4     .07       0  5007.4      .1       0
    5334     .05       0  5360.9      .1       0  5671.4     .16       0
Bank Sta=4964.4,5064.5
XS Rating Curve= 0 ,0
Exp/Cntr=0.3,0.1

Type RM Length L Ch R = 1 ,77155   ,569,569,569
BEGIN DESCRIPTION:
BARONS CREEK 127.0
END DESCRIPTION:
XS GIS Cut Line= 3
       2738690.1     10093206.75      2738177.94     10092807.44
      2737223.29     10092859.52
#Sta/Elev= 30
  4243.1 1985.92  4253.8 1986.03  4274.7 1982.81  4341.7 1974.86  4392.3 1968.18
  4473.7 1957.17    4546 1953.01  4631.1 1944.53  4674.5 1937.34    4859 1931.71
  4879.8 1928.35  4911.6 1918.88  4916.6 1919.47    4922 1915.54  4959.1 1909.78
  4961.9 1909.28  4965.1 1909.78  5042.2 1914.24  5062.3 1916.68  5149.6 1920.68
  5262.6 1925.94  5372.7 1935.92  5392.7 1935.11  5432.8 1947.49  5446.8 1953.37
  5482.9 1960.79    5573 1972.61  5649.4 1979.93  5723.2    1984  5848.6 1994.17
#Mann= 8 ,-1 , 0
  4243.1     .16       0  4274.7      .1       0  4341.7     .16       0
  4392.3      .1       0  4959.1     .07       0  4965.1      .1       0
  5149.6     .05       0  5446.8     .16       0
Bank Sta=4922,5042.2
XS Rating Curve= 0 ,0
Exp/Cntr=0.3,0.1

Type RM Length L Ch R = 1 ,76586   ,390,390,390
BEGIN DESCRIPTION:
BARONS CREEK 126.0
END DESCRIPTION:
XS GIS Cut Line= 3
      2738985.22     10092668.55      2737986.97     10092199.81
      2737335.93     10092139.04
#Sta/Elev= 30
  4096.7 1986.94    4139 1985.66  4262.7 1980.75  4331.1 1971.71  4369.3  1968.8
    4468 1955.26  4634.4 1939.55    4656  1933.2  4700.7 1932.69  4775.6 1921.18
  4923.5 1910.65  4940.8 1908.18  4969.1 1905.33    4996 1900.26  4998.8 1899.76
    5002 1900.26  5043.2  1907.5  5065.9  1913.8  5076.4 1914.59  5195.9 1916.89
  5268.3 1916.66  5321.1 1919.01  5348.7 1927.49  5425.2 1958.81  5449.1 1966.84
  5489.3 1974.22  5552.3 1977.95  5615.7 1982.71  5690.2 1986.99  5853.4 1988.97
#Mann= 7 ,-1 , 0
  4096.7      .1       0    4139     .16       0  4634.4      .1       0
    4996     .07       0    5002      .1       0  5552.3     .16       0
  5615.7      .1       0
Bank Sta=4940.8,5043.2
XS Rating Curve= 0 ,0
Exp/Cntr=0.3,0.1

Type RM Length L Ch R = 1 ,76196   ,391,391,391
BEGIN DESCRIPTION:
BARONS CREEK 125.0
END DESCRIPTION:
XS GIS Cut Line= 4
      2738898.42     10092434.18      2738394.96     10091922.03
      2738004.33     10091887.31      2737162.84     10092078.16
#Sta/Elev= 30
  4149.4 1979.09    4284 1969.04    4455 1949.75  4538.6 1939.78  4573.9 1921.43
  4616.4 1919.68  4642.1 1915.64    4683 1914.13  4907.3 1911.91  4915.8  1911.8
  4944.4  1912.1  4964.4 1903.52  5001.6 1897.73  5004.4 1897.23  5007.6 1897.73
  5017.9 1900.43  5084.9 1905.06  5311.6  1914.2  5337.5 1921.53  5354.8  1929.5
  5359.9 1927.57  5397.9 1945.42    5403 1943.42  5446.1 1961.23  5517.1 1970.58
  5692.1 1974.34  5712.4 1973.89  5760.2 1974.27  5940.9 1978.55  6122.6    1988
#Mann= 13 ,-1 , 0
  4149.4     .16       0    4455      .1       0  4642.1     .05       0
    4683      .1       0  4907.3     .05       0  4915.8     .16       0
  5001.6     .07       0  5007.6     .16       0  5017.9      .1       0
  5517.1     .16       0  5692.1      .1       0  5712.4     .16       0
  5760.2      .1       0
Bank Sta=4964.4,5084.9
XS Rating Curve= 0 ,0
Exp/Cntr=0.3,0.1

Type RM Length L Ch R = 1 ,75805   ,499,499,499
BEGIN DESCRIPTION:
BARONS CREEK 124.0
END DESCRIPTION:
XS GIS Cut Line= 3
      2738846.37     10092182.48      2738429.68     10091548.76
      2737153.63     10091357.79
#Sta/Elev= 30
  4077.9 1964.84  4227.4 1949.52  4260.6 1942.22  4341.8 1917.73  4498.5 1911.92
  4598.8 1910.47  4619.6 1910.15  4802.2 1905.04  4898.4  1903.9  4920.7 1903.56
  4948.8 1901.39  4996.3 1893.88  4999.1 1893.38  5002.3 1893.88    5042 1896.53
    5060 1902.57  5080.2 1911.56  5111.2 1914.51  5161.1 1907.23  5192.2 1908.03
  5313.7 1910.93  5372.7 1924.21  5403.8 1937.52  5525.1 1957.91  5649.4 1966.51
  5776.8 1963.89  5851.9 1962.36  5909.4 1949.66  5980.1 1965.19  6126.6 1984.31
#Mann= 12 ,-1 , 0
  4077.9     .16       0  4260.6      .1       0  4498.5     .16       0
  4598.8     .05       0  4619.6     .16       0  4802.2      .1       0
  4898.4     .16       0  4920.7      .1       0  4996.3     .07       0
  5002.3      .1       0  5192.2     .16       0  5776.8      .1       0
#XS Ineff= 2 , 0
                         5119.32         1914.69
Permanent Ineff=
       T       T
Bank Sta=4948.8,5060
XS Rating Curve= 0 ,0
Exp/Cntr=0.3,0.1

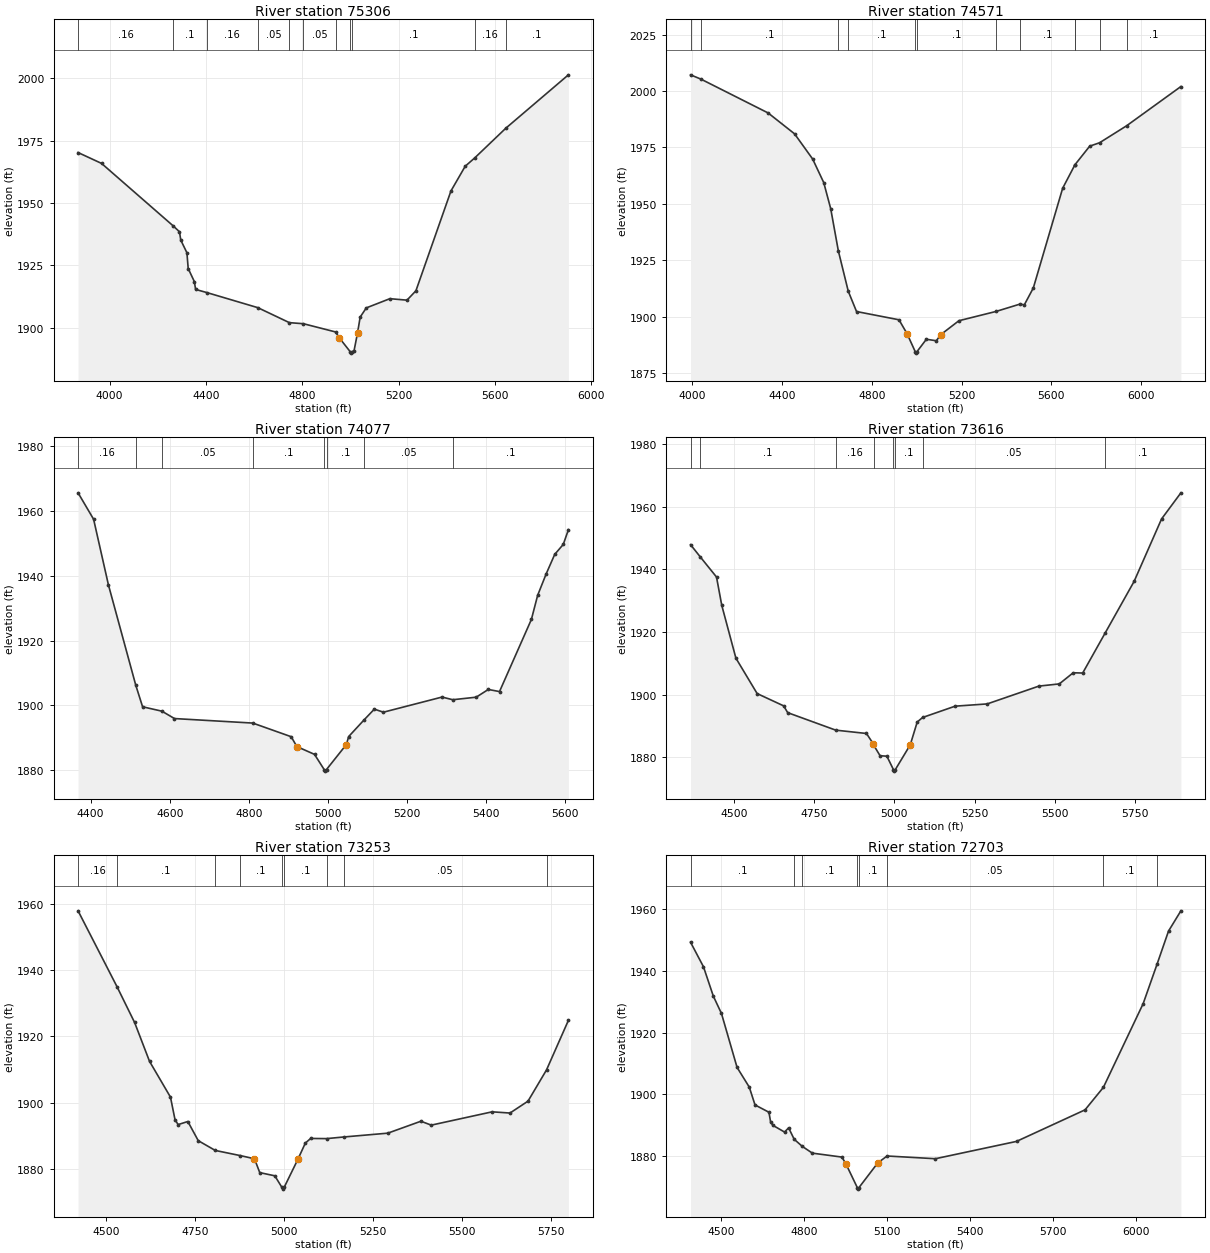
Type RM Length L Ch R = 1 ,75306   ,735,735,735
BEGIN DESCRIPTION:
BARONS CREEK 123.0
END DESCRIPTION:
XS GIS Cut Line= 3
       2738925.6     10092242.23      2738469.86     10090958.35
       2737883.9     10090625.01
#Sta/Elev= 30
  3868.9 1970.21  3966.5 1965.85  4263.7 1940.82  4290.1 1938.44  4295.4 1935.12
    4321 1930.02  4326.3  1923.7  4351.8 1918.47  4357.1 1915.32  4403.5 1914.07
  4615.5 1908.01  4746.5    1902  4804.9 1901.57  4938.4 1898.27  4953.2 1895.99
  4999.7 1890.28  5002.5 1889.78  5005.7 1890.28  5014.9 1890.64 5029.58 1897.87
  5040.5 1904.23    5066 1907.92  5163.9 1911.61  5234.9 1911.02    5272 1914.77
  5417.6 1954.82  5476.7 1964.71  5516.9 1968.11  5645.2 1979.95  5905.4 2001.37
#Mann= 11 ,-1 , 0
  3868.9     .16       0  4263.7      .1       0  4403.5     .16       0
  4615.5     .05       0  4746.5      .1       0  4804.9     .05       0
  4938.4      .1       0  4999.7     .07       0  5005.7      .1       0
  5516.9     .16       0  5645.2      .1       0
Bank Sta=4953.2,5029.58
XS Rating Curve= 0 ,0
Exp/Cntr=0.3,0.1

Type RM Length L Ch R = 1 ,74571   ,494,494,494
BEGIN DESCRIPTION:
BARONS CREEK 122.0
END DESCRIPTION:
XS GIS Cut Line= 3
      2739931.42     10091201.54      2739124.12     10090741.47
      2737874.17     10090611.27
#Sta/Elev= 30
  3991.6 2007.21  4038.9 2005.26  4337.6 1990.29  4455.4 1981.03    4536 1969.86
  4585.4 1959.41  4616.5 1947.82  4650.5 1929.12  4694.7 1911.22  4731.6 1902.21
  4920.8 1898.55  4956.6 1892.42  4993.9 1884.26  4996.6 1883.76  4999.9 1884.26
  5042.9 1889.91  5087.3 1889.25  5107.4 1891.99  5187.9 1898.13  5354.5 1902.28
  5460.9 1905.53  5479.5 1905.17  5519.7 1912.68  5650.4 1956.89  5705.2 1967.32
  5705.8  1967.4    5771 1975.57    5815 1977.08  5935.2 1984.59  6177.5 2002.02
#Mann= 12 ,-1 , 0
  3991.6     .16       0  4038.9      .1       0  4650.5     .05       0
  4694.7      .1       0  4993.9     .07       0  4999.9      .1       0
  5354.5     .05       0  5460.9      .1       0  5705.2     .05       0
  5705.8      .1       0    5815     .16       0  5935.2      .1       0
Bank Sta=4956.6,5107.4
XS Rating Curve= 0 ,0
Exp/Cntr=0.3,0.1

Type RM Length L Ch R = 1 ,74077   ,461,461,461
BEGIN DESCRIPTION:
BARONS CREEK 120.0
END DESCRIPTION:
XS GIS Cut Line= 2
      2739688.36     10090567.86       2738612.7     10089951.96
#Sta/Elev= 30
  4368.2 1965.49  4407.5 1957.35    4445 1937.12  4514.1 1906.23  4531.3  1899.6
  4580.2 1898.24  4611.9 1895.97  4809.8 1894.58  4906.9 1890.38  4921.2 1887.35
  4965.9 1884.94  4990.2 1880.28    4993 1879.78  4996.2 1880.28  5046.4 1887.97
  5052.2 1890.42  5091.4 1895.59  5117.1 1898.87  5140.1 1897.93  5288.2 1902.59
  5315.4 1901.77  5374.5 1902.55  5405.2 1904.93  5433.5 1904.28  5514.1  1926.5
  5529.9 1933.92  5551.5 1940.54  5573.1 1946.54  5594.7 1949.61  5607.7 1954.15
#Mann= 8 ,-1 , 0
  4368.2     .16       0  4514.1      .1       0  4580.2     .05       0
  4809.8      .1       0  4990.2     .07       0  4996.2      .1       0
  5091.4     .05       0  5315.4      .1       0
Bank Sta=4921.2,5046.4
XS Rating Curve= 0 ,0
Exp/Cntr=0.3,0.1

Type RM Length L Ch R = 1 ,73616   ,363,363,363
BEGIN DESCRIPTION:
BARONS CREEK 119.0
END DESCRIPTION:
XS GIS Cut Line= 3
      2739966.11      10090185.9      2739488.71     10089934.18
      2738655.41     10089404.69
#Sta/Elev= 30
  4365.3 1947.85  4395.9 1943.91  4446.2 1937.53  4462.6 1928.47  4506.6 1911.64
  4572.7 1900.35  4655.2 1896.43  4667.9 1894.26  4817.5 1888.68  4913.2 1887.62
  4934.4 1884.31  4936.2  1883.8  4955.5 1880.52  4976.7 1880.38  4997.1 1876.11
  4999.8 1875.61  5003.1 1876.11  5049.5    1884  5071.2 1891.27  5087.9 1892.72
  5189.3 1896.33  5289.2 1897.05  5450.1 1902.73  5513.6 1903.43  5556.9 1906.98
  5586.5  1906.9    5657 1919.77  5746.5 1936.11  5832.1 1956.05  5892.3 1964.38
#Mann= 8 ,-1 , 0
  4365.3     .16       0  4395.9      .1       0  4817.5     .16       0
  4936.2      .1       0  4997.1     .07       0  5003.1      .1       0
  5087.9     .05       0    5657      .1       0
Bank Sta=4934.4,5049.5
XS Rating Curve= 0 ,0
Exp/Cntr=0.3,0.1

Type RM Length L Ch R = 1 ,73253   ,550,550,550
BEGIN DESCRIPTION:
BARONS CREEK 118.0
END DESCRIPTION:
XS GIS Cut Line= 2
      2740131.07     10089951.54      2739002.99     10089161.89
#Sta/Elev= 30
  4422.3 1958.04  4531.4 1935.13  4581.1 1924.24    4623 1912.48  4681.8 1901.65
  4694.5 1894.86  4703.2 1893.33  4730.6 1894.27  4759.8 1888.47  4807.6 1885.51
  4878.3 1883.94  4917.7 1882.99  4932.5  1878.8  4974.8 1877.83  4994.9  1874.3
  4997.6  1873.8  5000.9  1874.3  5039.7 1882.85  5060.6 1887.75  5075.5 1889.14
  5120.2 1889.09    5168 1889.58  5292.1 1890.74    5385 1894.35  5414.2 1893.17
  5585.1  1897.2  5635.2 1896.83  5685.8 1900.43  5737.8 1909.89  5799.3  1924.9
#Mann= 9 ,-1 , 0
  4422.3     .16       0  4531.4      .1       0  4807.6     .16       0
  4878.3      .1       0  4994.9     .07       0  5000.9      .1       0
  5120.2     .16       0    5168     .05       0  5737.8      .1       0
Bank Sta=4917.7,5039.7
XS Rating Curve= 0 ,0
Exp/Cntr=0.3,0.1

Type RM Length L Ch R = 1 ,72703   ,1244,1244,1244
BEGIN DESCRIPTION:
BARONS CREEK 117.0
END DESCRIPTION:
XS GIS Cut Line= 3
      2740530.38     10089586.96      2739896.69     10089126.89
      2738924.52     10088944.61
#Sta/Elev= 30
    4390 1949.34  4436.8 1941.36  4472.4 1931.83  4501.8 1926.21  4558.2  1908.7
  4602.3 1902.31  4623.1 1896.52  4673.4 1894.15  4679.6 1890.91  4688.1 1889.88
  4729.8 1887.72  4744.5 1889.09  4764.6 1885.38  4794.2 1883.05  4830.3 1880.88
    4937  1879.6  4951.7 1877.38  4992.7  1869.7  4995.5  1869.2  4998.7  1869.7
  5066.8 1877.72  5100.4 1879.95  5274.9 1879.07  5568.1 1884.69  5815.8 1894.93
  5882.1 1902.23  6025.9 1929.41  6075.8 1942.14  6117.5 1952.95  6162.2 1959.52
#Mann= 8 ,-1 , 0
    4390      .1       0  4764.6     .05       0  4794.2      .1       0
  4992.7     .07       0  4998.7      .1       0  5100.4     .05       0
  5882.1      .1       0  6075.8     .05       0
Bank Sta=4951.7,5066.8
XS Rating Curve= 0 ,0
Exp/Cntr=0.3,0.1

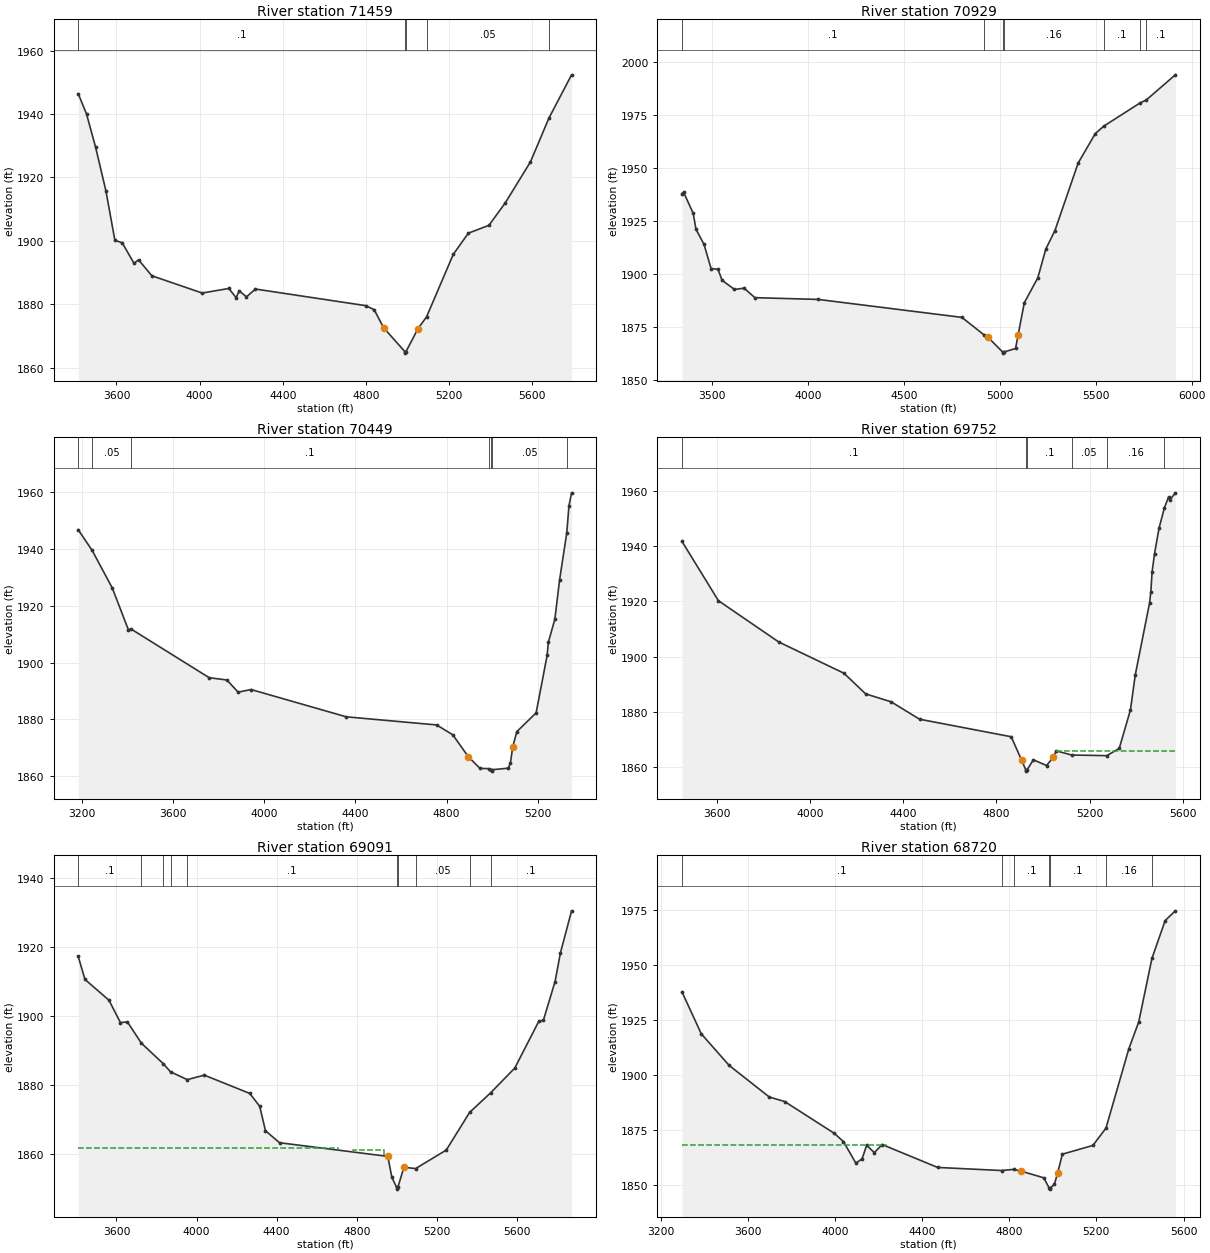
Type RM Length L Ch R = 1 ,71459   ,530,530,530
BEGIN DESCRIPTION:
BARONS CREEK 116.0
END DESCRIPTION:
XS GIS Cut Line= 4
      2740695.29     10089474.09      2739896.69     10088467.17
      2739332.46     10088441.13      2738925.84     10088769.88
#Sta/Elev= 30
  3416.1 1946.43  3456.2    1940  3499.5 1929.59  3549.2 1915.81  3592.5 1900.17
  3627.7 1899.37  3684.6 1892.89  3706.2 1894.01  3770.3 1888.97  4012.3 1883.52
  4140.4 1884.96  4175.7 1882.05  4190.1 1884.21  4225.4 1882.32  4268.6 1884.78
  4799.6 1879.53  4839.6 1878.26  4884.5 1872.62  4986.8 1865.06  4989.6 1864.56
  4992.8 1865.06  5049.9 1872.24  5091.6 1876.01    5220 1895.72  5292.3  1902.4
  5391.5 1904.89  5469.8 1911.94  5591.3 1924.91    5680 1938.71    5789 1952.37
#Mann= 5 ,-1 , 0
  3416.1      .1       0  4986.8     .07       0  4992.8      .1       0
  5091.6     .05       0    5680      .1       0
Bank Sta=4884.5,5049.9
XS Rating Curve= 0 ,0
Exp/Cntr=0.3,0.1

Type RM Length L Ch R = 1 ,70929   ,480,480,480
BEGIN DESCRIPTION:
BARONS CREEK 115.0
END DESCRIPTION:
XS GIS Cut Line= 3
      2740808.13     10089395.96      2739749.12     10087955.01
      2739566.83     10087191.11
#Sta/Elev= 30
  3341.3 1937.78  3349.7 1938.42  3399.9 1928.48  3414.5 1920.92  3456.2 1913.86
    3493 1902.45  3529.5 1902.06  3550.3 1896.92  3615.1 1892.56  3665.3 1893.18
  3721.6  1888.7  4051.4 1887.87  4801.8 1879.39  4916.4 1871.19  4937.6 1870.03
  5014.1 1863.04  5016.8 1862.54  5020.1 1863.04  5081.5 1864.73  5094.3 1870.95
  5127.2 1886.33  5197.3 1898.01  5239.4 1911.64  5286.7 1920.31  5407.9 1952.17
  5497.2 1966.06  5542.3 1969.63  5730.5 1980.51  5763.1 1981.91  5914.9 1993.79
#Mann= 7 ,-1 , 0
  3341.3      .1       0  4916.4     .16       0  5014.1     .07       0
  5020.1     .16       0  5542.3      .1       0  5730.5     .16       0
  5763.1      .1       0
Bank Sta=4937.6,5094.3
XS Rating Curve= 0 ,0
Exp/Cntr=0.3,0.1

Type RM Length L Ch R = 1 ,70449   ,697,697,697
BEGIN DESCRIPTION:
BARONS CREEK 114.0
END DESCRIPTION:
XS GIS Cut Line= 3
      2741485.23      10089118.2       2740252.6     10087998.42
      2740139.74     10087512.26
#Sta/Elev= 30
  3184.3 1946.63  3245.7 1939.33  3333.8 1926.16  3404.7 1911.43    3415 1911.82
  3758.8 1894.67  3836.5 1893.86  3885.8 1889.59  3942.6 1890.51  4360.2 1880.93
  4756.9 1878.08  4827.9 1874.59  4895.5 1866.94  4946.8 1862.82  4985.2 1862.74
  4995.2 1862.36  4997.9 1861.86  5001.2 1862.36    5071  1862.9  5080.3 1864.64
  5090.5 1870.35  5108.5 1875.72  5193.2 1882.33  5241.6 1902.57  5246.7 1907.08
  5275.3 1915.18  5295.9 1928.87  5327.7 1945.58  5337.1 1954.96  5348.7 1959.58
#Mann= 7 ,-1 , 0
  3184.3     .16       0  3245.7     .05       0    3415      .1       0
  4985.2     .05       0  4995.2     .07       0  5001.2     .05       0
  5327.7      .1       0
Bank Sta=4895.5,5090.5
XS Rating Curve= 0 ,0
Exp/Cntr=0.3,0.1

Type RM Length L Ch R = 1 ,69752   ,661,661,661
BEGIN DESCRIPTION:
BARONS CREEK 113.0
END DESCRIPTION:
XS GIS Cut Line= 3
      2741641.49     10088849.11       2740565.1     10087312.65
      2740332.09     10087252.24
#Sta/Elev= 30
  3450.6 1941.65  3606.9 1920.23  3865.8 1905.31  4145.7 1894.02  4238.6 1886.56
  4347.9  1883.7    4470 1877.41  4863.1 1871.08  4907.6 1862.64  4925.5 1859.16
  4928.3 1858.66  4931.5 1859.16  4958.2 1862.76  5014.8 1860.69  5044.4 1863.76
  5056.7 1865.98  5122.5 1864.48  5273.3 1864.25  5326.6 1866.86  5374.8 1880.81
  5395.4 1893.43    5457  1919.5  5462.2 1923.53  5467.7 1930.73  5478.1 1937.26
  5497.6 1946.51  5520.5 1953.78  5538.2  1957.7  5543.3 1956.53  5567.3 1959.19
#Mann= 6 ,-1 , 0
  3450.6      .1       0  4925.5     .07       0  4931.5      .1       0
  5122.5     .05       0  5273.3     .16       0  5520.5      .1       0
#XS Ineff= 2 , 0
                         5056.71            1866
Permanent Ineff=
       T       T
Bank Sta=4907.6,5044.4
XS Rating Curve= 0 ,0
Exp/Cntr=0.3,0.1

Type RM Length L Ch R = 1 ,69091   ,371,371,371
BEGIN DESCRIPTION:
BARONS CREEK 111.0
END DESCRIPTION:
XS GIS Cut Line= 3
       2742344.6     10088024.45      2741242.18     10087095.64
      2740226.57     10086982.79
#Sta/Elev= 30
  3409.2 1917.26    3443 1910.56  3562.7 1904.54  3619.9 1898.05    3655 1898.21
  3724.8 1892.04    3835 1886.03  3870.2 1883.72  3953.8 1881.46  4038.6 1882.77
  4266.2 1877.44  4315.6 1873.68  4344.2  1866.6  4414.5 1863.13  4955.1 1859.16
  4975.2 1853.09  4999.1 1850.15  5001.9 1849.65  5005.1 1850.15  5035.6 1856.02
  5093.5 1855.61  5246.9    1861  5363.6 1871.94  5468.9 1877.65    5589 1884.82
  5709.7 1898.49  5731.6 1898.66  5790.2 1909.96  5817.1 1918.33  5872.6  1930.5
#Mann= 10 ,-1 , 0
  3409.2      .1       0  3724.8     .05       0    3835     .16       0
  3870.2     .05       0  3953.8      .1       0  4999.1     .07       0
  5005.1      .1       0  5093.5     .05       0  5363.6     .16       0
  5468.9      .1       0
#XS Ineff= 2 ,-1
  3409.2  4705.5 1861.54  4782.7 4934.75 1860.88
Permanent Ineff=
       T       T
Bank Sta=4955.1,5035.6
XS Rating Curve= 0 ,0
Exp/Cntr=0.3,0.1

Type RM Length L Ch R = 1 ,68720   ,1068,1068,1068
BEGIN DESCRIPTION:
BARONS CREEK 110.0
END DESCRIPTION:
XS GIS Cut Line= 3
      2742535.56     10087842.15      2741415.79     10086878.63
      2740747.37     10086461.95
#Sta/Elev= 30
  3297.6  1937.9  3386.1 1918.86  3514.5 1904.47  3698.8 1890.13    3769  1888.1
  3996.2  1873.7  4038.9  1869.9    4096 1860.11  4124.5  1862.1  4145.4 1868.22
  4180.5 1864.91  4216.7 1868.57  4471.3 1858.17  4764.5 1856.77  4820.8 1857.29
  4855.2 1856.48    4959 1853.44  4983.1 1848.82  4985.9 1848.32  4989.1 1848.82
  5007.4 1850.55  5022.7 1855.84  5043.9 1864.19  5184.1 1868.17  5244.1 1876.03
  5349.1 1912.08  5394.4 1924.22    5455 1953.06  5515.9  1970.3  5562.5  1974.7
#Mann= 7 ,-1 , 0
  3297.6      .1       0  4764.5     .16       0  4820.8      .1       0
  4983.1     .07       0  4989.1      .1       0  5244.1     .16       0
    5455     .05       0
#XS Ineff= 2 , 0
          4235.8 1868.39
Permanent Ineff=
       T       T
Bank Sta=4855.2,5022.7
XS Rating Curve= 0 ,0
Exp/Cntr=0.3,0.1

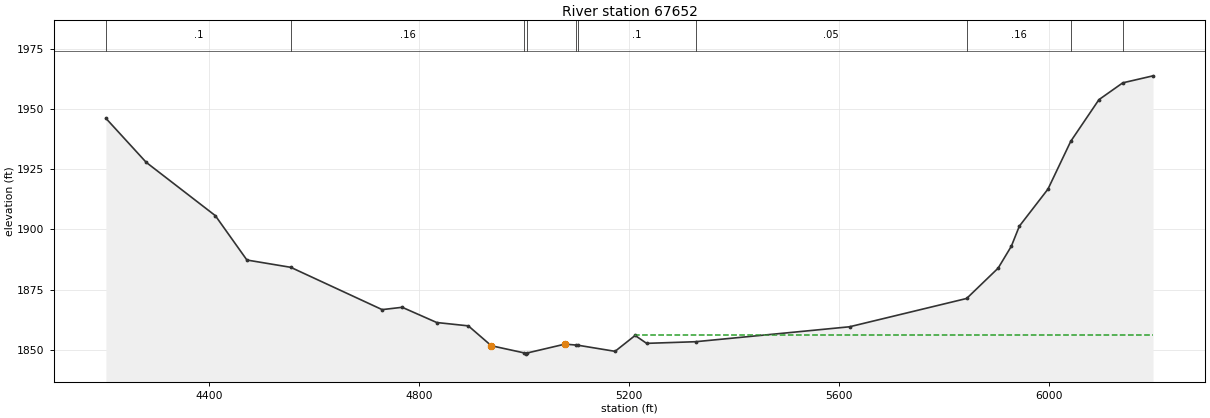
Type RM Length L Ch R = 1 ,67652   ,460,460,460
BEGIN DESCRIPTION:
BARONS CREEK 109.0
END DESCRIPTION:
XS GIS Cut Line= 3
      2742839.37     10086895.97      2741606.76     10086236.26
      2741016.46     10086149.45
#Sta/Elev= 30
  4203.6 1946.13  4280.4 1927.85  4412.1 1905.72  4472.2 1887.31  4555.7 1884.28
  4729.8 1866.72    4768 1867.69  4833.8 1861.37    4894 1859.98  4937.8 1851.73
  5000.6 1848.75  5003.4 1848.25  5006.6 1848.75    5078  1852.4    5100    1852
  5102.6 1851.95  5173.5 1849.41  5211.7    1856  5233.6 1852.72  5326.8  1853.4
  5620.1  1859.6  5843.2 1871.35  5903.2 1883.94  5928.4 1893.06  5943.6 1901.36
  5998.1 1916.74  6041.5 1936.58  6095.2 1953.87  6140.6 1960.85  6198.3 1963.76
#Mann= 10 ,-1 , 0
  4203.6      .1       0  4555.7     .16       0  5000.6     .07       0
  5006.6     .16       0    5100     .05       0  5102.6      .1       0
  5326.8     .05       0  5843.2     .16       0  6041.5      .1       0
  6140.6     .05       0
#XS Ineff= 2 , 0
                         5211.54         1856.02
Permanent Ineff=
       T       T
Bank Sta=4937.8,5078
XS Rating Curve= 0 ,0
Exp/Cntr=0.3,0.1