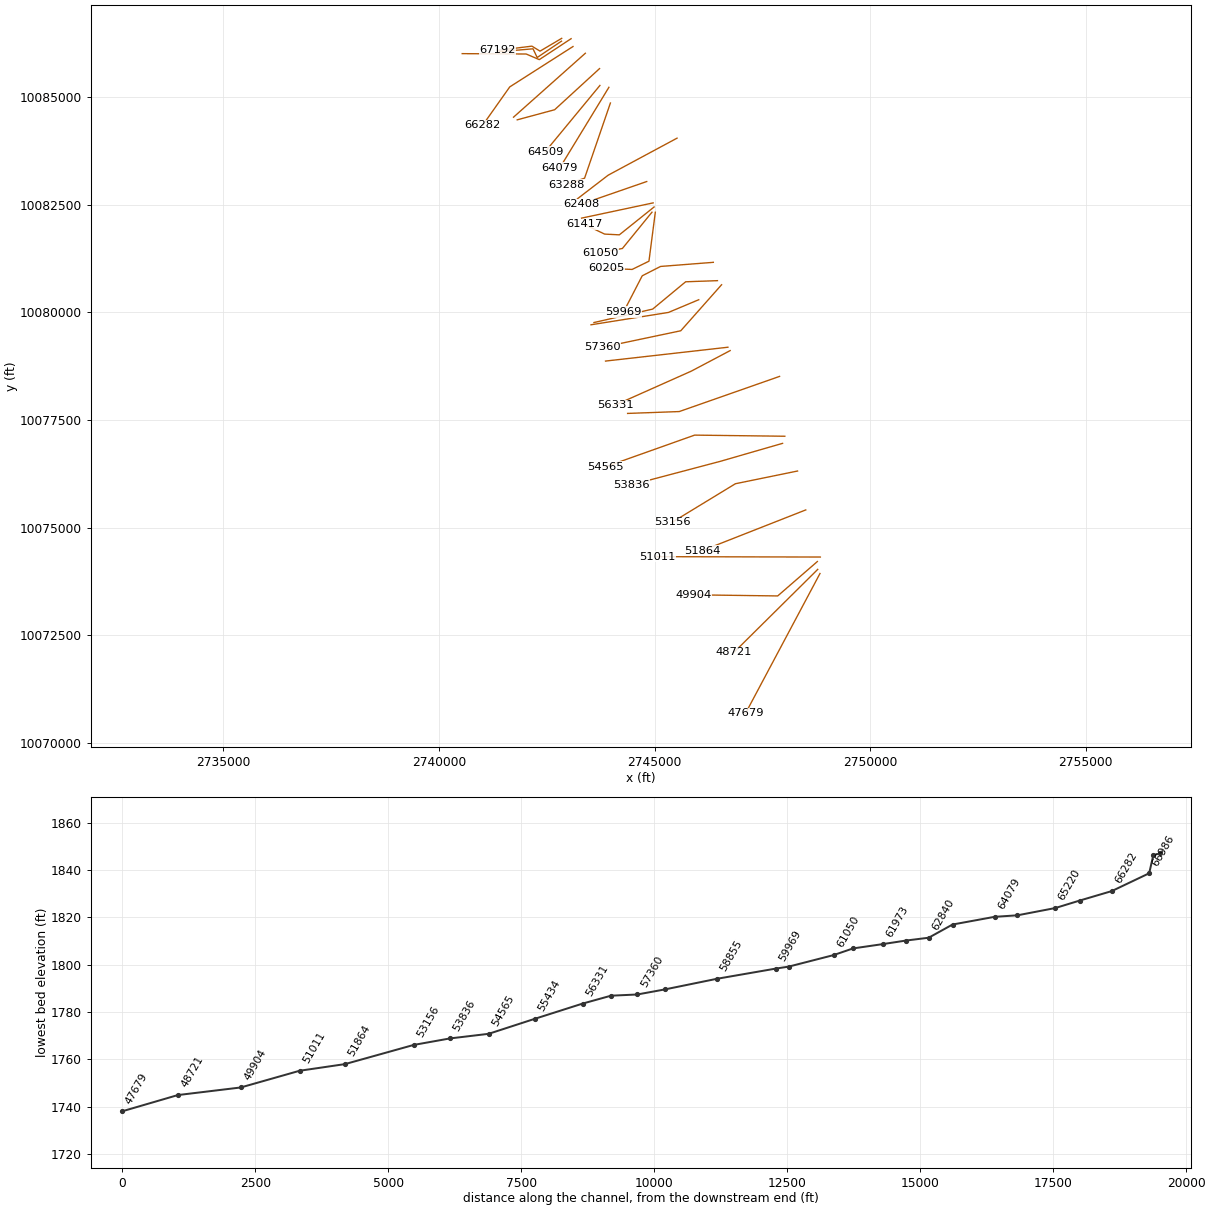
HEC-RAS study BARONS CREEK.prj: BARONS CREEK Base Level Engineering

--- BARONS CREEK.g01 (geometry) --- (continued)

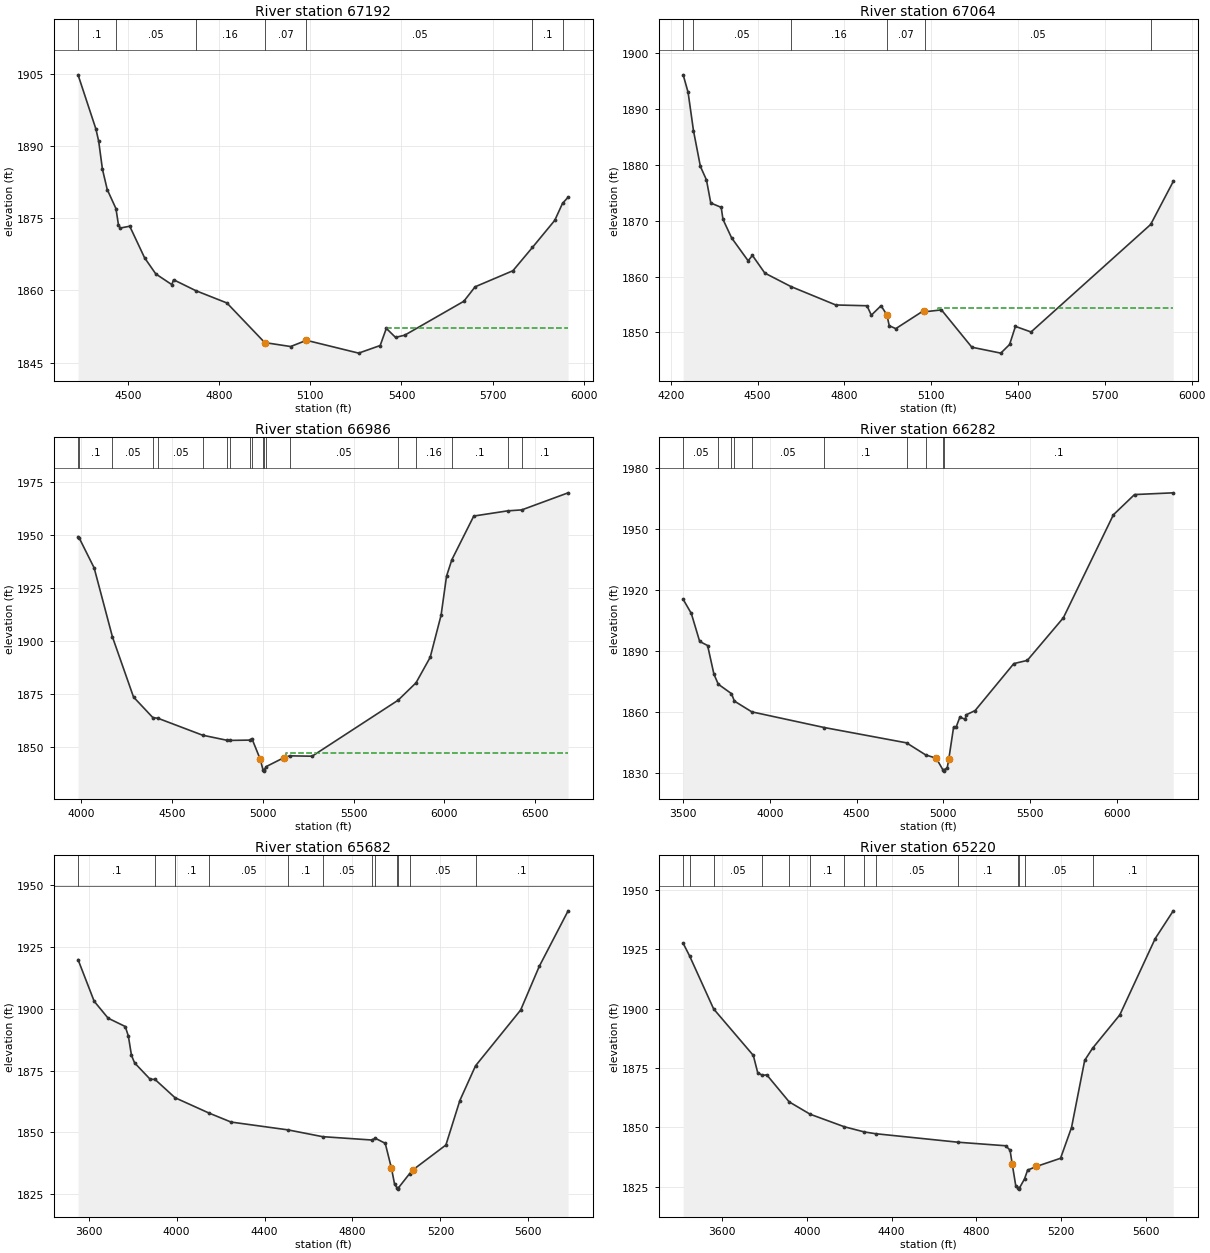
Type RM Length L Ch R = 1 ,67192   ,128,128,128
BEGIN DESCRIPTION:
Mapping XS c66d73a7
END DESCRIPTION:
XS GIS Cut Line= 4
      2742846.89     10086357.11      2742344.48     10086059.78
      2742155.67     10086175.88      2741354.92     10086076.06
#Sta/Elev= 30
  4335.8 1904.74  4394.7 1893.47  4403.7 1890.96  4416.1 1885.14  4431.8 1880.94
  4460.5 1876.98  4468.8  1873.6  4474.6 1872.94  4505.9 1873.32  4554.7 1866.77
  4591.6 1863.42  4644.3  1861.2  4650.1 1862.21  4723.7 1859.93  4825.6 1857.39
    4950 1849.17  5035.2 1848.35  5087.3 1849.64  5259.1 1846.98  5329.9 1848.56
  5350.1 1852.12  5380.3 1850.25  5410.5  1850.7  5605.1 1857.74  5642.3 1860.75
  5766.6 1864.08    5831 1868.93  5904.3 1874.54  5929.9 1878.07  5948.2 1879.34
#Mann= 7 ,-1 , 0
  4335.8      .1       0  4460.5     .05       0  4723.7     .16       0
    4950     .07       0  5087.3     .05       0    5831      .1       0
  5929.9     .16       0
#XS Ineff= 2 , 0
                         5350.09         1852.13
Permanent Ineff=
       T       T
Bank Sta=4950,5087.3
XS Rating Curve= 0 ,0
Exp/Cntr=0.3,0.1

Type RM Length L Ch R = 1 ,67064   ,78,78,78
BEGIN DESCRIPTION:
Mapping XS 4dfa5339
END DESCRIPTION:
XS GIS Cut Line= 4
      2742842.56     10086292.01      2742278.29     10085912.21
      2742181.72     10086114.03      2741395.01     10086046.76
#Sta/Elev= 30
  4242.9 1896.14  4259.9 1892.99  4278.5 1886.13  4302.3 1879.74  4323.3 1877.31
  4338.3 1873.17  4374.3 1872.39  4380.4 1870.24  4410.3 1866.92  4467.3 1862.82
  4482.2 1863.78  4525.1 1860.61  4615.3  1858.2  4770.2  1854.9  4878.1 1854.76
  4893.1 1853.07  4926.7 1854.77  4946.9 1853.11    4955 1851.18  4977.6 1850.66
  5073.8 1853.88    5080 1853.69  5135.4 1854.02  5240.4 1847.33  5340.5 1846.27
  5370.9 1847.82    5391 1851.06    5445 1850.06  5858.3 1869.32  5936.4 1877.03
#Mann= 6 ,-1 , 0
  4242.9      .1       0  4278.5     .05       0  4615.3     .16       0
  4946.9     .07       0    5080     .05       0  5858.3      .1       0
#XS Ineff= 2 , 0
                         5123.52         1854.42
Permanent Ineff=
       T       T
Bank Sta=4946.9,5073.8
XS Rating Curve= 0 ,0
Exp/Cntr=0.3,0.1

Type RM Length L Ch R = 1 ,66986   ,704,704,704
BEGIN DESCRIPTION:
BARONS CREEK 107.0
END DESCRIPTION:
XS GIS Cut Line= 4
      2743065.09     10086349.11      2742327.25       10085863.
      2742023.43     10085993.21      2740539.08     10086001.89
#Sta/Elev= 30
  3982.7 1949.03  3989.2 1948.42  4071.4 1934.33  4172.3 1901.78  4288.2  1873.5
  4394.5 1863.82  4423.6 1863.47  4668.1 1855.53  4804.1  1853.1  4817.3 1853.06
    4929 1853.21    4940 1853.92  4986.2 1844.13  5001.4 1839.09  5004.1 1838.59
  5007.4 1839.09  5019.4 1840.76  5115.2 1844.89  5147.9 1845.79  5271.8 1845.63
  5744.9 1871.99  5843.6 1880.18  5921.8 1892.23  5981.8 1912.06  6011.8 1930.45
    6041 1938.18  6161.8 1958.77  6348.4 1961.22  6426.2 1961.67  6681.2 1969.71
#Mann= 19 ,-1 , 0
  3982.7     .16       0  3989.2      .1       0  4172.3     .05       0
  4394.5      .1       0  4423.6     .05       0  4668.1     .16       0
  4804.1      .1       0  4817.3     .05       0    4929      .1       0
    4940     .16       0  5001.4     .07       0  5007.4     .16       0
  5019.4      .1       0  5147.9     .05       0  5744.9      .1       0
  5843.6     .16       0    6041      .1       0  6348.4     .05       0
  6426.2      .1       0
#XS Ineff= 2 , 0
                          5125.7         1846.97
Permanent Ineff=
       T       T
Bank Sta=4986.2,5115.2
XS Rating Curve= 0 ,0
Exp/Cntr=0.3,0.1

Type RM Length L Ch R = 1 ,66282   ,600,600,600
BEGIN DESCRIPTION:
BARONS CREEK 106.0
END DESCRIPTION:
XS GIS Cut Line= 3
      2743108.53     10086166.84      2741641.48     10085229.32
      2741016.49     10084343.91
#Sta/Elev= 30
  3500.5 1915.41  3547.4 1908.49  3595.6 1894.74  3641.3 1892.75  3677.7 1878.69
  3702.8 1873.75  3778.7 1869.12  3795.7 1865.45    3896 1860.17  4313.9 1852.47
  4787.8 1844.95  4898.5 1839.01  4959.2  1837.4  4998.5 1831.56  5001.3 1831.06
  5004.5 1831.56  5022.7 1832.73  5031.5 1836.94    5059 1852.54  5074.3  1852.8
  5095.4 1857.61  5125.8  1856.5  5131.8  1858.7  5183.4 1860.82  5406.4 1883.87
    5484 1885.44    5692 1906.38  5980.2 1956.94  6102.1 1966.89  6325.3 1967.74
#Mann= 10 ,-1 , 0
  3500.5     .05       0  3702.8      .1       0  3778.7     .05       0
  3795.7      .1       0    3896     .05       0  4313.9      .1       0
  4787.8     .05       0  4898.5      .1       0  4998.5     .07       0
  5004.5      .1       0
Bank Sta=4959.2,5031.5
XS Rating Curve= 0 ,0
Exp/Cntr=0.3,0.1

Type RM Length L Ch R = 1 ,65682   ,462,462,462
BEGIN DESCRIPTION:
BARONS CREEK 105.0
END DESCRIPTION:
XS GIS Cut Line= 2
      2743394.92     10086010.54      2741729.71     10084527.46
#Sta/Elev= 30
  3551.3 1919.82  3624.7 1902.99  3688.2 1896.15    3766 1892.79  3780.2 1888.96
  3794.4 1881.14  3808.7 1878.08  3879.7 1871.45  3901.2 1871.43  3992.7 1864.01
  4148.4 1857.77  4247.6 1854.18  4506.5 1851.02  4663.9 1848.28  4887.1 1846.93
  4904.2 1847.61  4949.1  1845.6  4977.6 1835.44  4991.8 1829.01    5003 1827.58
  5005.7 1827.08    5009 1827.58  5059.6  1833.3  5076.2 1834.94  5225.1  1844.9
  5288.6 1862.88  5359.9  1876.9  5565.3 1899.45  5649.8 1917.07  5781.2 1939.53
#Mann= 12 ,-1 , 0
  3551.3      .1       0  3901.2     .05       0  3992.7      .1       0
  4148.4     .05       0  4506.5      .1       0  4663.9     .05       0
  4887.1      .1       0  4904.2     .05       0    5003    .035       0
    5009     .05       0  5059.6     .05       0  5359.9      .1       0
Bank Sta=4977.6,5076.2
XS Rating Curve= 0 ,0
Exp/Cntr=0.3,0.1

Type RM Length L Ch R = 1 ,65220   ,711,711,711
BEGIN DESCRIPTION:
BARONS CREEK 104.0
END DESCRIPTION:
XS GIS Cut Line= 3
      2743724.81     10085654.66      2742683.15     10084699.81
      2741815.11     10084465.44
#Sta/Elev= 30
  3416.4 1927.53  3446.6 1922.22    3560 1899.88  3747.3 1880.27  3768.2 1872.95
  3790.5 1871.87  3810.8 1872.08  3916.6 1860.68  4015.4 1855.48  4177.2 1850.18
  4271.6    1848  4323.8 1847.27    4714 1843.67  4937.9 1842.18  4958.6 1840.34
    4969 1834.41  4985.8 1825.19  4997.1  1824.4  4999.8  1823.9  5003.1  1824.4
  5026.8 1828.18  5041.5 1831.91  5082.9 1833.45  5196.9 1836.91  5248.7 1849.88
  5310.8  1878.2  5347.7 1883.27  5476.5 1897.36  5643.3  1929.5  5728.6 1941.23
#Mann= 14 ,-1 , 0
  3416.4      .1       0  3446.6     .16       0    3560     .05       0
  3790.5      .1       0  3916.6     .05       0  4015.4      .1       0
  4177.2     .05       0  4271.6      .1       0  4323.8     .05       0
    4714      .1       0  4997.1     .07       0  5003.1      .1       0
  5026.8     .05       0  5347.7      .1       0
Bank Sta=4969,5082.9
XS Rating Curve= 0 ,0
Exp/Cntr=0.3,0.1

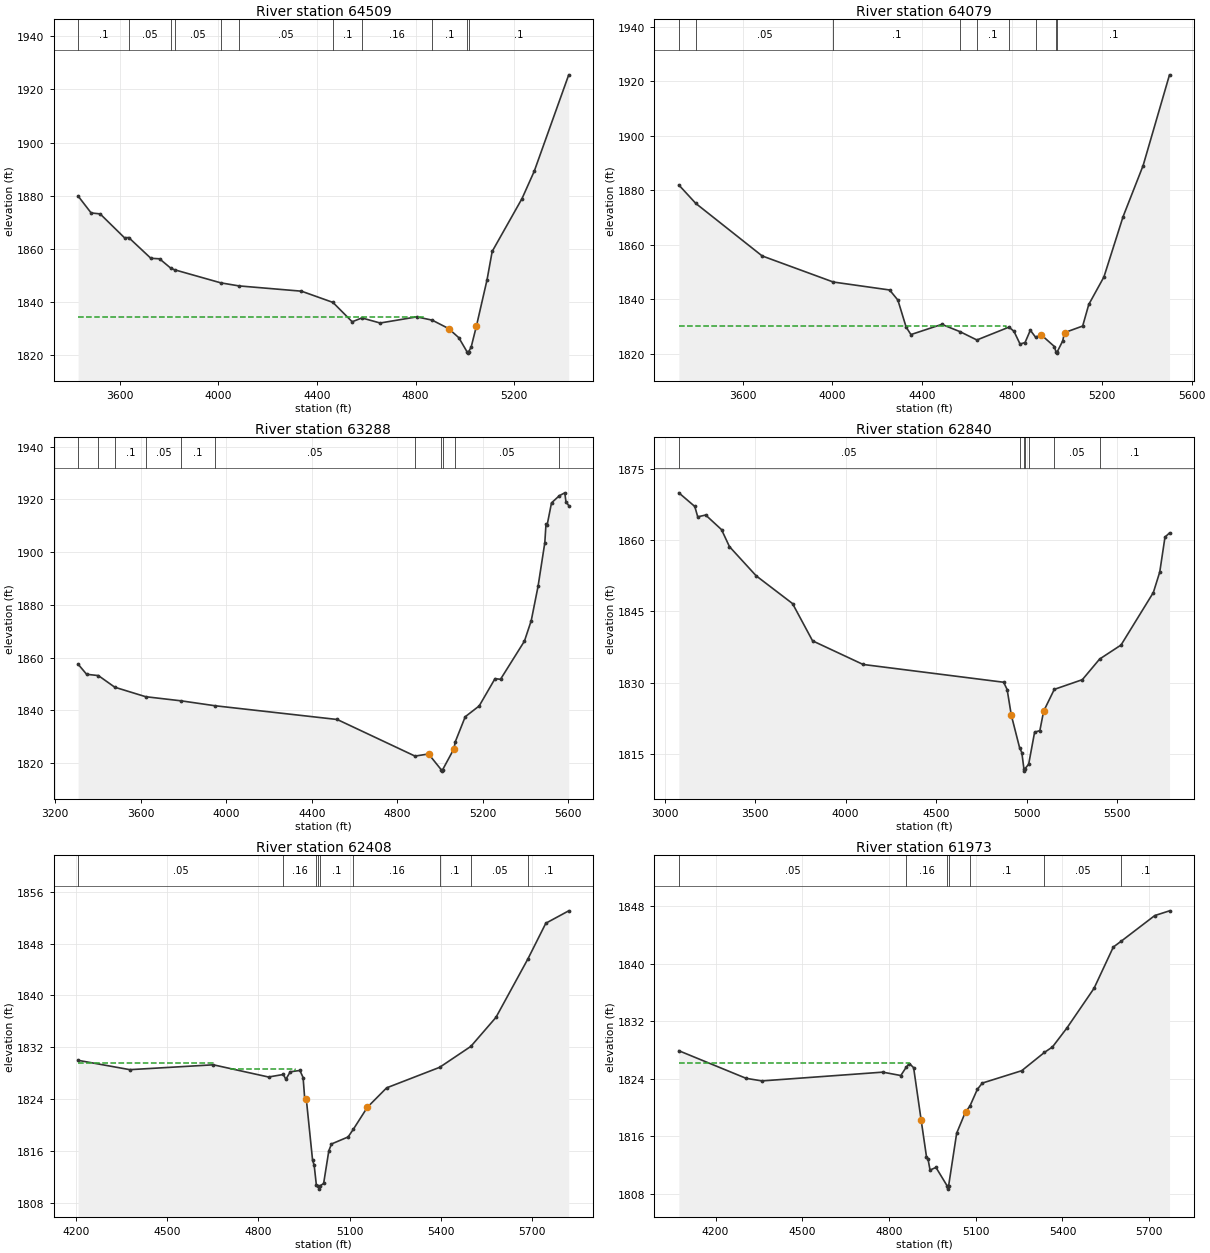
Type RM Length L Ch R = 1 ,64509   ,430,430,430
BEGIN DESCRIPTION:
BARONS CREEK 103.0
END DESCRIPTION:
XS GIS Cut Line= 2
      2743733.53     10085264.07      2742466.62     10083728.16
#Sta/Elev= 30
  3430.2 1879.93  3483.2 1873.56  3519.7  1873.2  3618.7 1864.21  3635.6 1864.31
  3725.6  1856.5  3760.8 1856.31  3807.2 1852.72  3822.2 1852.17  4009.6 1847.26
  4082.7 1846.12  4336.7 1844.13  4464.3 1839.91  4542.5 1832.62  4581.8 1834.07
  4655.9 1832.16  4804.7 1834.47  4867.2 1833.23  4933.4 1830.09  4975.1 1826.64
  5008.6 1821.33  5011.3 1820.83  5014.6 1821.33  5025.1 1823.02  5046.8 1831.07
  5089.8 1848.45  5110.6 1859.08  5231.8 1878.99  5281.3 1889.26  5421.2 1925.51
#Mann= 11 ,-1 , 0
  3430.2      .1       0  3635.6     .05       0  3807.2      .1       0
  3822.2     .05       0  4009.6      .1       0  4082.7     .05       0
  4464.3      .1       0  4581.8     .16       0  4867.2      .1       0
  5008.6     .07       0  5014.6      .1       0
#XS Ineff= 2 , 0
         4832.97 1834.48
Permanent Ineff=
       T       T
Bank Sta=4933.4,5046.8
XS Rating Curve= 0 ,0
Exp/Cntr=0.3,0.1

Type RM Length L Ch R = 1 ,64079   ,791,791,791
BEGIN DESCRIPTION:
BARONS CREEK 102.0
END DESCRIPTION:
XS GIS Cut Line= 2
      2743941.85     10085220.67      2742804.68     10083354.32
#Sta/Elev= 30
  3315.8 1881.93  3391.4 1875.16  3686.9 1855.88  4003.7  1846.3  4254.6 1843.38
  4291.4 1839.67  4328.2 1829.74  4349.5    1827  4487.1 1830.75  4567.7 1828.09
  4643.3 1825.02  4786.2 1829.74  4808.5 1828.21  4835.7 1823.51  4857.9 1824.09
  4881.4  1828.6  4904.5 1826.06  4930.6 1826.86  4988.7  1822.6  4995.3 1820.69
    4998 1820.19  5001.3 1820.69  5025.4 1824.64  5033.6 1827.71  5114.5 1830.14
  5141.7 1838.07  5209.2 1848.17  5294.6 1870.33  5383.7 1889.06  5501.3 1922.39
#Mann= 9 ,-1 , 0
  3315.8      .1       0  3391.4     .05       0  4003.7      .1       0
  4567.7     .16       0  4643.3      .1       0  4786.2     .16       0
  4904.5      .1       0  4995.3     .07       0  5001.3      .1       0
#XS Ineff= 2 , 0
          4771.7 1830.24
Permanent Ineff=
       T       T
Bank Sta=4930.6,5033.6
XS Rating Curve= 0 ,0
Exp/Cntr=0.3,0.1

Type RM Length L Ch R = 1 ,63288   ,448,448,448
BEGIN DESCRIPTION:
BARONS CREEK 101.0
END DESCRIPTION:
XS GIS Cut Line= 3
      2743976.55     10084856.04       2743377.6     10083111.26
      2742952.85      10082963.9
#Sta/Elev= 30
  3307.5  1857.5  3347.4 1853.65  3402.4 1853.16  3479.4 1848.74  3623.6 1845.15
  3789.9 1843.58    3948 1841.72  4519.3 1836.51  4883.1 1822.63  4946.4 1823.44
  5005.9 1817.43  5008.7 1816.93  5011.9 1817.43    5065 1825.39    5071 1827.99
  5117.9 1837.56  5183.1 1841.65  5257.1    1852  5282.8 1851.75  5394.7 1866.23
  5426.5    1874  5458.3 1886.96    5490 1903.56  5495.4 1910.47  5500.7 1910.21
  5521.3 1918.65  5557.9 1921.37  5583.5 1922.46  5588.8 1919.04  5601.8 1917.65
#Mann= 11 ,-1 , 0
  3307.5      .1       0  3402.4     .05       0  3479.4      .1       0
  3623.6     .05       0  3789.9      .1       0    3948     .05       0
  4883.1     .16       0  5005.9     .07       0  5011.9     .16       0
    5071     .05       0  5557.9      .1       0
Bank Sta=4946.4,5065
XS Rating Curve= 0 ,0
Exp/Cntr=0.3,0.1

Type RM Length L Ch R = 1 ,62840   ,432,432,432
BEGIN DESCRIPTION:
BARONS CREEK 100.0
END DESCRIPTION:
XS GIS Cut Line= 3
      2745521.71     10084040.09      2743924.47     10083180.71
      2743213.05     10082634.13
#Sta/Elev= 30
  3078.7 1869.91  3166.8 1867.04    3183 1864.86  3226.8 1865.24  3314.5 1862.17
  3358.3 1858.59  3505.9 1852.45  3706.9 1846.61  3817.5 1838.77  4096.7  1833.8
  4873.2 1830.06  4892.5 1828.53  4915.5 1823.14  4961.7 1816.23  4973.6 1815.27
  4985.1 1811.86  4987.8 1811.36  4991.1 1811.86  5011.5 1812.82  5044.2 1819.54
  5073.3 1819.89  5094.1 1823.96    5153 1828.56    5308  1830.6  5403.5 1834.94
  5521.8 1837.89  5700.4 1848.94  5735.7 1853.25  5764.7  1860.6  5789.6 1861.47
#Mann= 7 ,-1 , 0
  3078.7     .05       0  4961.7     .16       0  4985.1     .07       0
  4991.1     .16       0  5011.5      .1       0    5153     .05       0
  5403.5      .1       0
Bank Sta=4915.5,5094.1
XS Rating Curve= 0 ,0
Exp/Cntr=0.3,0.1

Type RM Length L Ch R = 1 ,62408   ,435,435,435
BEGIN DESCRIPTION:
BARONS CREEK 99.0
END DESCRIPTION:
XS GIS Cut Line= 2
      2744818.54     10083033.13      2743292.12     10082504.09
#Sta/Elev= 30
    4206    1830  4376.4 1828.56  4651.4 1829.31    4833 1827.43  4881.9 1827.82
    4890 1827.07  4904.6 1828.23  4936.3 1828.44  4946.9 1827.35  4952.3 1824.05
  4957.5 1824.02  4978.1 1814.61  4983.4 1813.83  4990.5  1810.8  4996.8 1810.65
  4999.6 1810.15  5002.8 1810.65  5014.5 1811.02  5031.6 1816.06  5040.4 1817.11
  5095.1 1818.19  5112.4 1819.38  5158.6 1822.77    5222 1825.76  5396.4 1828.92
  5499.3 1832.15  5581.9 1836.62  5687.1 1845.63  5746.1 1851.13  5821.5 1853.04
#Mann= 9 ,-1 , 0
    4206     .05       0  4881.9     .16       0  4990.5      .1       0
  4996.8     .07       0  5002.8      .1       0  5112.4     .16       0
  5396.4      .1       0  5499.3     .05       0  5687.1      .1       0
#XS Ineff= 2 ,-1
    4206 4651.02 1829.59 4707.27 4921.02 1828.65
Permanent Ineff=
       T       T
Bank Sta=4957.5,5158.6
XS Rating Curve= 0 ,0
Exp/Cntr=0.3,0.1

Type RM Length L Ch R = 1 ,61973   ,556,556,556
BEGIN DESCRIPTION:
BARONS CREEK 98.0
END DESCRIPTION:
XS GIS Cut Line= 2
      2744968.24     10082537.77      2743308.47     10082184.26
#Sta/Elev= 30
  4073.2 1827.91  4305.8 1824.07  4360.5 1823.71  4778.4 1824.93  4840.8 1824.46
  4859.7 1825.62  4870.5 1826.13  4885.2 1825.55  4911.4 1818.21  4929.7 1813.15
  4934.8 1812.88    4942  1811.3  4962.5 1811.67  5000.4 1809.15  5003.1 1808.65
  5006.4 1809.15  5034.1 1816.44  5064.7 1819.41  5079.5 1820.17  5105.6 1822.54
  5122.8 1823.41    5259 1825.13  5337.8 1827.68  5365.5 1828.44  5415.1 1831.06
  5509.1 1836.59  5575.9 1842.34  5603.4 1843.16  5719.1 1846.72  5770.2 1847.38
#Mann= 7 ,-1 , 0
  4073.2     .05       0  4859.7     .16       0  5000.4     .07       0
  5006.4     .16       0  5079.5      .1       0  5337.8     .05       0
  5603.4      .1       0
#XS Ineff= 2 , 0
         4869.32 1826.16
Permanent Ineff=
       T       T
Bank Sta=4911.4,5064.7
XS Rating Curve= 0 ,0
Exp/Cntr=0.3,0.1

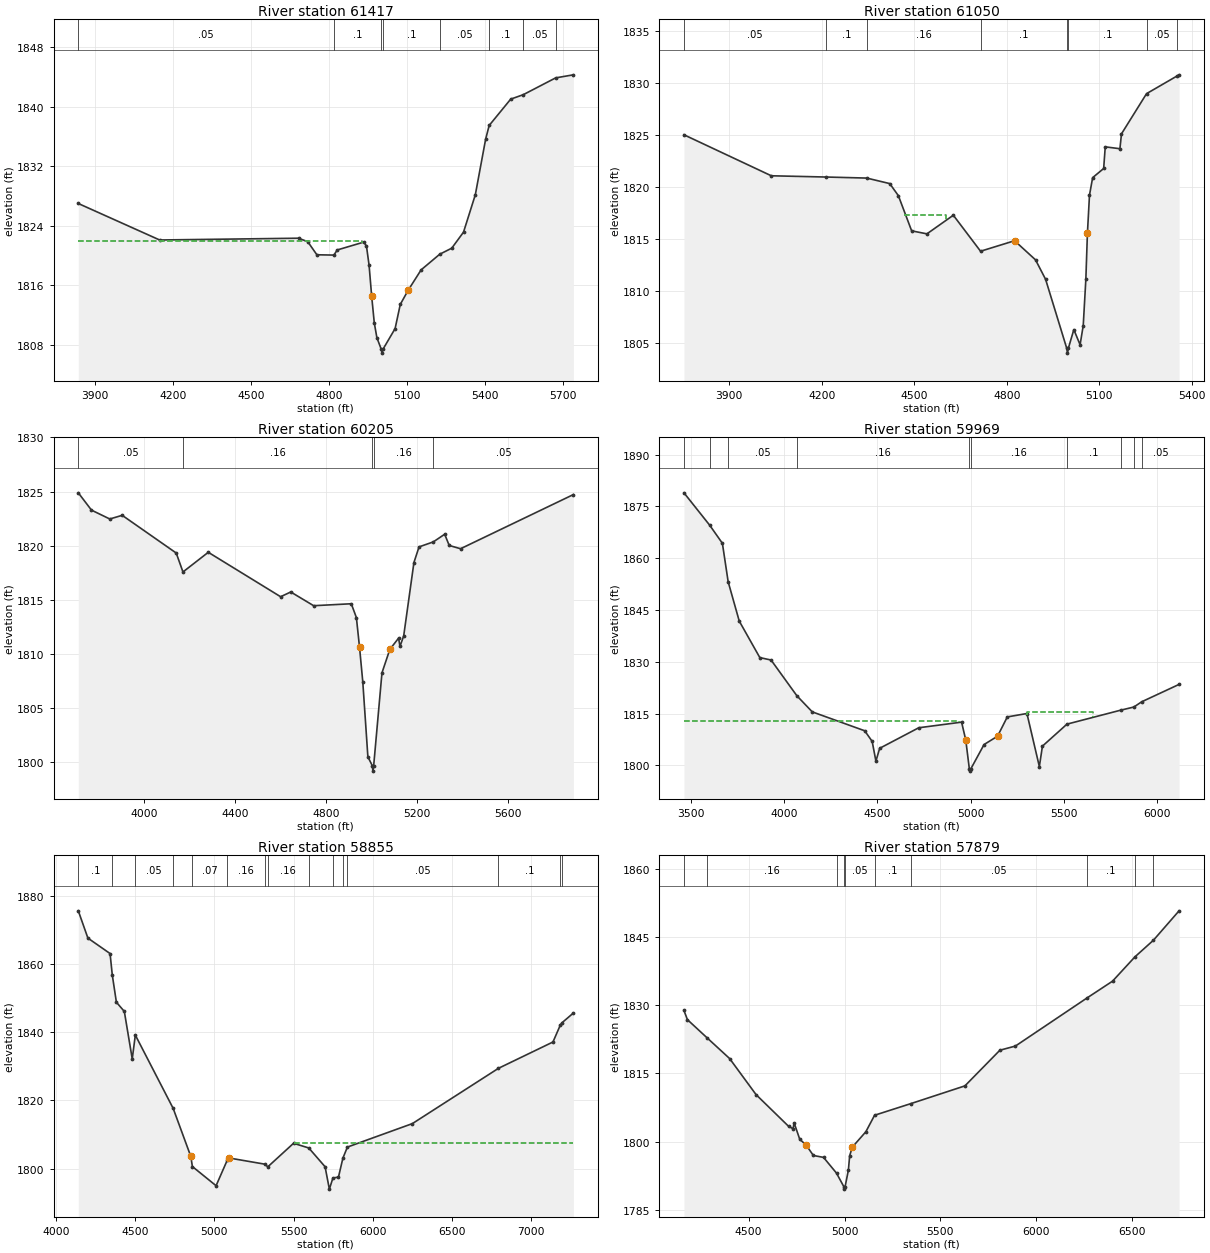
Type RM Length L Ch R = 1 ,61417   ,367,367,367
BEGIN DESCRIPTION:
BARONS CREEK 97.0
END DESCRIPTION:
XS GIS Cut Line= 4
      2744989.82     10082442.95       2744183.6     10081796.24
      2743843.02     10081813.49      2743364.44       10082042.
#Sta/Elev= 30
    3835 1826.97  4148.1 1822.06  4682.6  1822.3  4717.8 1821.83    4753 1820.07
  4818.4 1820.03  4831.4 1820.72  4933.8 1821.78  4943.8 1821.23  4953.8 1818.67
  4963.8 1814.48  4973.8 1810.92  4983.8 1808.92  5000.9 1807.34  5003.6 1806.84
  5006.9 1807.34  5053.9 1810.14  5073.9  1813.4    5104 1815.29    5154 1818.04
  5225.8 1820.15  5271.9 1820.96  5317.2 1823.12  5362.6 1828.15  5402.4 1835.65
  5415.9 1837.47  5498.7 1841.01  5547.1 1841.61  5671.7 1843.87  5739.9 1844.28
#Mann= 8 ,-1 , 0
    3835     .05       0  4818.4      .1       0  5000.9     .07       0
  5006.9      .1       0  5225.8     .05       0  5415.9      .1       0
  5547.1     .05       0  5671.7      .1       0
#XS Ineff= 2 , 0
         4924.72  1821.9
Permanent Ineff=
       T       T
Bank Sta=4963.8,5104
XS Rating Curve= 0 ,0
Exp/Cntr=0.3,0.1

Type RM Length L Ch R = 1 ,61050   ,845,845,845
BEGIN DESCRIPTION:
BARONS CREEK 96.0
END DESCRIPTION:
XS GIS Cut Line= 3
      2744940.11     10082321.35      2744254.33     10081479.32
       2743742.8     10081383.95
#Sta/Elev= 30
  3752.9 1824.99  4036.3 1821.05  4214.3 1820.93  4345.8 1820.83  4420.5  1820.3
  4448.5 1819.14  4491.6 1815.76  4541.2 1815.47  4626.8 1817.26  4715.2  1813.8
  4825.6 1814.81  4893.6 1812.97  4926.2  1811.1  4994.4 1804.51  4997.2 1804.01
  5000.4 1804.51  5017.8 1806.27  5038.1 1804.81  5048.3 1806.66  5056.8 1811.11
  5061.9 1815.53  5068.6 1819.19  5078.8 1820.87  5114.6 1821.75  5119.7 1823.83
  5167.3 1823.65  5172.4 1825.08  5253.7 1828.94  5353.3 1830.65  5359.2 1830.75
#Mann= 8 ,-1 , 0
  3752.9     .05       0  4214.3      .1       0  4345.8     .16       0
  4715.2      .1       0  4994.4     .07       0  5000.4      .1       0
  5253.7     .05       0  5353.3      .1       0
#XS Ineff= 1 ,-1
 4465.23 4604.32  1817.3
Permanent Ineff=
       T
Bank Sta=4825.6,5061.9
XS Rating Curve= 0 ,0
Exp/Cntr=0.3,0.1

Type RM Length L Ch R = 1 ,60205   ,236,236,236
BEGIN DESCRIPTION:
BARONS CREEK 95.0
END DESCRIPTION:
XS GIS Cut Line= 4
      2745018.22     10082321.32      2744870.65     10081184.18
      2744480.03     10080993.21      2743882.28      10081019.2
#Sta/Elev= 30
    3710 1824.88  3768.1 1823.28  3848.7 1822.46  3903.3  1822.8  4141.2 1819.31
  4170.8 1817.56  4282.3 1819.38  4600.8 1815.27  4645.4 1815.71  4746.2 1814.44
  4911.9 1814.62  4934.4 1813.34  4948.2  1810.6  4962.5 1807.41    4985 1800.46
  5004.5 1799.64  5007.3 1799.14  5010.5 1799.64    5047 1808.23  5081.7  1810.4
  5120.1 1811.44  5126.3 1810.68  5142.6 1811.64  5187.7 1818.43  5210.2 1819.88
  5272.9 1820.34  5323.1 1821.05  5343.1 1820.01  5393.1 1819.71  5889.8 1824.72
#Mann= 5 ,-1 , 0
    3710     .05       0  4170.8     .16       0  5004.5     .07       0
  5010.5     .16       0  5272.9     .05       0
Bank Sta=4948.2,5081.7
XS Rating Curve= 0 ,0
Exp/Cntr=0.3,0.1

Type RM Length L Ch R = 1 ,59969   ,1114,1114,1114
BEGIN DESCRIPTION:
BARONS CREEK 94.0
END DESCRIPTION:
XS GIS Cut Line= 4
      2746363.75     10081158.14      2745139.75     10081062.65
       2744714.4     10080845.64      2744280.39     10080003.65
#Sta/Elev= 30
  3463.7 1878.95  3601.8 1869.55  3669.6 1864.33  3700.5 1853.19  3759.9  1841.8
  3870.2 1831.22  3930.4 1830.52  4068.6 1820.17  4151.1  1815.5  4431.9 1810.03
    4472 1806.96  4492.1 1801.24  4512.2 1804.95  4721.5  1810.9  4951.1 1812.53
  4973.5 1807.34    4993 1798.84  4995.7 1798.34    4999 1798.84  5071.5 1806.04
  5143.8 1808.46    5196 1814.04  5301.2 1815.03  5367.7 1799.66  5384.2 1805.58
  5515.6 1811.95  5803.1 1815.99  5873.7  1816.9  5916.2 1818.43  6116.2 1823.46
#Mann= 10 ,-1 , 0
  3463.7     .16       0  3601.8      .1       0  3700.5     .05       0
  4068.6     .16       0    4993     .07       0    4999     .16       0
  5515.6      .1       0  5803.1     .05       0  5873.7     .16       0
  5916.2     .05       0
#XS Ineff= 2 ,-1
  3463.7 4938.92 1812.79 5302.84 5652.84 1815.42
Permanent Ineff=
       T       T
Bank Sta=4973.5,5143.8
XS Rating Curve= 0 ,0
Exp/Cntr=0.3,0.1

Type RM Length L Ch R = 1 ,58855   ,976,976,976
BEGIN DESCRIPTION:
BARONS CREEK 93.0
END DESCRIPTION:
XS GIS Cut Line= 4
      2746459.15     10080732.79      2745721.35     10080706.75
      2744957.46     10080073.07       2743594.6     10079760.57
#Sta/Elev= 30
  4139.6  1875.6  4200.3  1867.6  4340.4 1863.07  4354.5 1856.76  4380.4  1848.8
  4430.5  1846.1  4480.5  1832.2  4500.1 1839.16  4739.4 1817.65  4850.7 1803.58
  4860.7 1800.62  5010.4    1795  5080.7 1802.46    5095 1803.11  5320.7  1801.3
  5336.8 1800.52    5500 1807.44  5596.2 1806.07  5699.3 1800.56  5726.3    1794
  5748.8 1797.26  5783.9 1797.53  5811.9 1803.09  5840.4 1806.33  6250.9 1813.21
  6795.2 1829.43  7139.5 1837.14  7185.4 1842.04  7196.3 1842.77  7268.6 1845.64
#Mann= 15 ,-1 , 0
  4139.6      .1       0  4354.5     .08       0  4500.1     .05       0
  4739.4     .16       0  4860.7     .07       0  5080.7     .16       0
  5320.7      .1       0  5336.8     .16       0  5596.2      .1       0
  5748.8     .16       0  5811.9      .1       0  5840.4     .05       0
  6795.2      .1       0  7185.4     .16       0  7196.3      .1       0
#XS Ineff= 2 , 0
                         5501.42         1807.53
Permanent Ineff=
       T       T
Bank Sta=4850.7,5095
XS Rating Curve= 0 ,0
Exp/Cntr=0.3,0.1

Type RM Length L Ch R = 1 ,57879   ,519,519,519
BEGIN DESCRIPTION:
BARONS CREEK 92.0
END DESCRIPTION:
XS GIS Cut Line= 3
      2746025.15     10080290.08      2745322.04     10079994.94
      2743525.96     10079708.61
#Sta/Elev= 30
  4162.9 1828.86    4181 1826.84  4281.9  1822.9  4401.1 1818.27  4538.9 1810.33
    4708 1803.37  4731.7 1802.82  4737.2 1804.12  4766.6 1800.49  4799.2 1799.26
  4837.6 1796.93  4890.6 1796.51  4958.3 1793.04  4996.9 1790.02  4999.7 1789.52
  5002.9 1790.02  5020.2 1793.72  5026.8 1796.86  5040.4 1798.76  5111.3 1802.16
  5156.7 1805.79  5344.9 1808.34  5627.8 1812.26    5810 1820.11  5891.1 1821.03
  6264.3 1831.62  6397.4 1835.32  6514.1 1840.67  6610.9 1844.35  6744.2 1850.81
#Mann= 10 ,-1 , 0
  4162.9     .05       0  4281.9     .16       0  4958.3     .05       0
  4996.9    .035       0  5002.9     .05       0  5156.7      .1       0
  5344.9     .05       0  6264.3      .1       0  6514.1     .16       0
  6610.9      .1       0
Bank Sta=4799.2,5040.4
XS Rating Curve= 0 ,0
Exp/Cntr=0.3,0.1

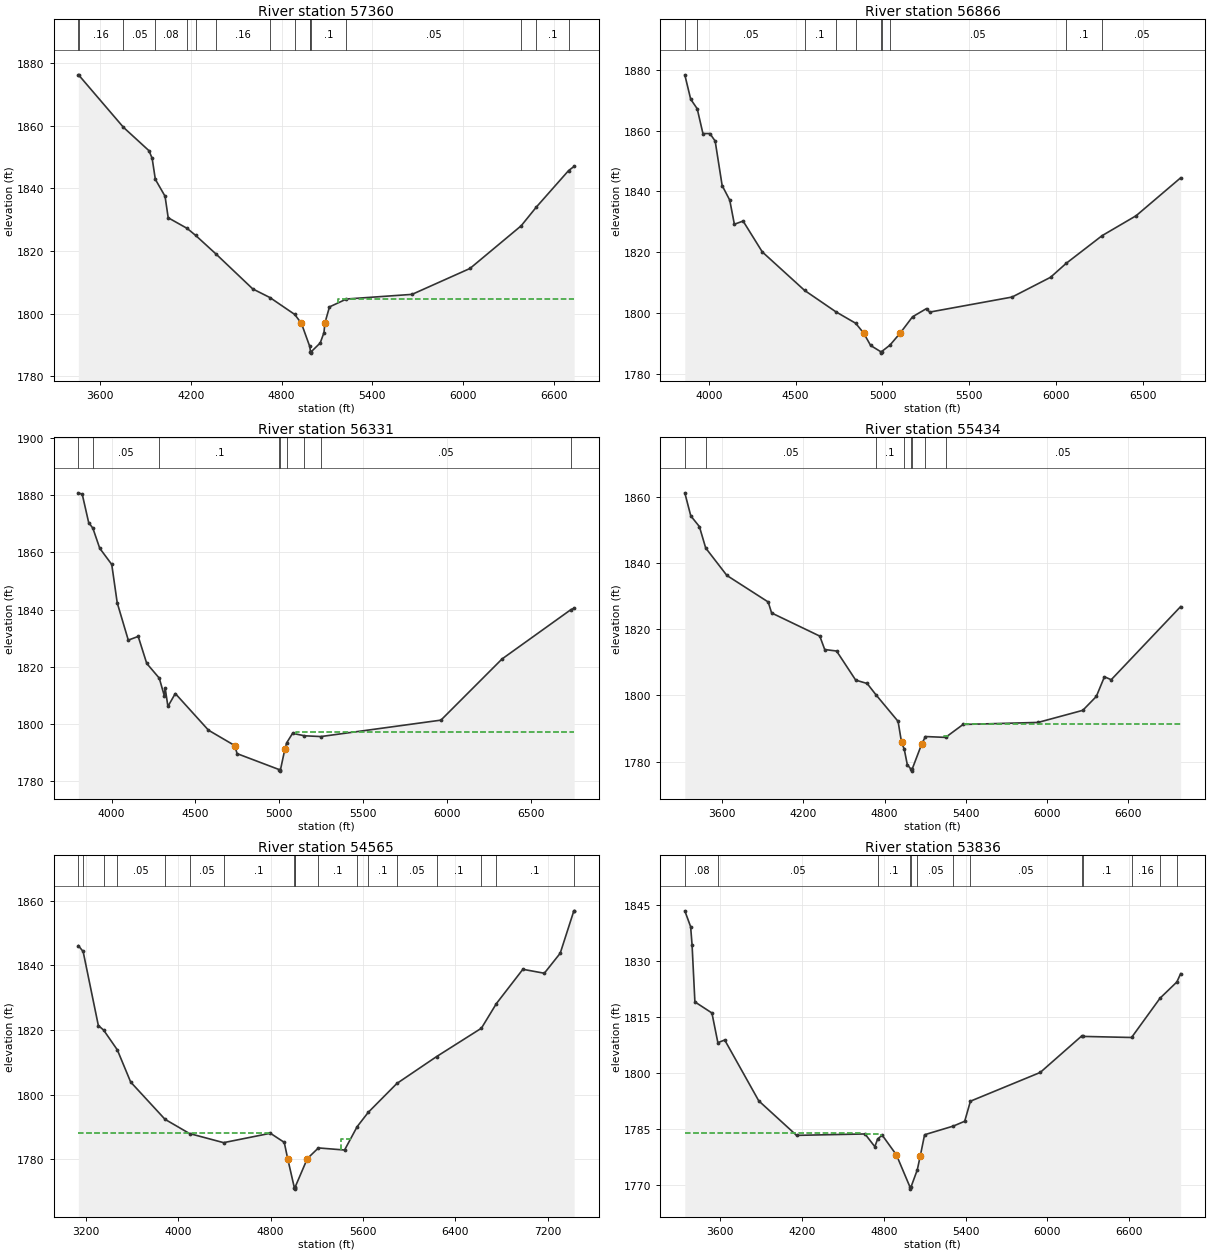
Type RM Length L Ch R = 1 ,57360   ,494,494,494
BEGIN DESCRIPTION:
BARONS CREEK 91.0
END DESCRIPTION:
XS GIS Cut Line= 3
      2746554.67     10080637.29       2745608.5      10079569.6
      2743794.27     10079187.65
#Sta/Elev= 30
  3455.2 1876.24  3460.2 1876.03  3753.7 1859.48  3922.7 1852.01  3943.6 1849.58
  3964.7 1842.87  4028.9 1837.48  4049.8  1830.6  4174.4 1827.23  4230.5 1825.01
  4367.2 1818.98  4609.3 1807.88  4723.1 1805.12  4886.4 1799.75  4931.2  1796.9
  4986.3 1789.51  4991.2 1787.88    4994 1787.38  4997.2 1787.88  5055.6 1790.62
  5080.6 1793.96  5086.2 1796.93  5116.9 1802.14  5229.5 1804.66  5663.1 1806.14
  6046.4 1814.41  6385.3 1828.04  6485.3    1834    6699 1845.67  6735.8 1847.01
#Mann= 16 ,-1 , 0
  3455.2      .1       0  3460.2     .16       0  3753.7     .05       0
  3964.7     .08       0  4174.4     .05       0  4230.5     .08       0
  4367.2     .16       0  4723.1      .1       0  4886.4     .16       0
  4986.3      .1       0  4991.2     .07       0  4997.2      .1       0
  5229.5     .05       0  6385.3     .16       0  6485.3      .1       0
    6699     .16       0
#XS Ineff= 2 , 0
                            5175         1804.78
Permanent Ineff=
       T       T
Bank Sta=4931.2,5086.2
XS Rating Curve= 0 ,0
Exp/Cntr=0.3,0.1

Type RM Length L Ch R = 1 ,56866   ,535,535,535
BEGIN DESCRIPTION:
BARONS CREEK 90.0
END DESCRIPTION:
XS GIS Cut Line= 2
      2746702.28     10079187.66      2743863.69     10078866.47
#Sta/Elev= 30
  3861.3 1878.32  3895.3 1870.31  3932.7 1867.19  3965.8 1859.03    4006 1859.02
  4036.2 1856.56  4076.5 1841.94  4120.2 1837.15  4146.9 1829.22  4197.2 1830.27
  4307.9 1820.12  4551.3 1807.49  4731.2 1800.47  4845.7 1796.69  4891.6 1793.48
  4931.9 1789.39  4989.3 1787.37    4992 1786.87  4995.3 1787.37  5043.4 1789.51
    5103  1793.5  5173.4 1798.81  5253.9 1801.51  5271.9 1800.35  5747.1  1805.3
  5968.5 1811.79  6058.8 1816.38  6265.8 1825.48  6461.6 1832.02    6718 1844.47
#Mann= 10 ,-1 , 0
  3861.3      .1       0  3932.7     .05       0  4551.3      .1       0
  4731.2     .05       0  4845.7      .1       0  4989.3     .07       0
  4995.3      .1       0  5043.4     .05       0  6058.8      .1       0
  6265.8     .05       0
Bank Sta=4891.6,5103
XS Rating Curve= 0 ,0
Exp/Cntr=0.3,0.1

Type RM Length L Ch R = 1 ,56331   ,897,897,897
BEGIN DESCRIPTION:
BARONS CREEK 89.0
END DESCRIPTION:
XS GIS Cut Line= 3
      2746754.34     10079109.53      2745851.55      10078632.1
      2744082.08     10077842.77
#Sta/Elev= 30
  3801.3 1880.78  3824.7 1880.27    3863 1870.39    3888 1868.43    3929 1861.41
  4000.7 1855.75  4033.4 1842.33  4099.4 1829.31  4158.6  1830.6  4209.5 1821.16
  4284.3 1816.02  4313.9 1809.94  4319.5 1812.54  4335.9 1806.13  4379.9 1810.65
    4578 1797.83  4735.6 1792.43  4748.4 1789.65  5001.6 1784.03  5004.4 1783.53
  5007.6 1784.03    5034 1791.26  5044.6 1793.42  5079.8 1796.74  5150.6 1795.88
  5248.8 1795.61  5965.1 1801.35  6329.9 1822.73  6740.6 1839.96  6760.1 1840.47
#Mann= 9 ,-1 , 0
  3801.3      .1       0    3888     .05       0  4284.3      .1       0
  5001.6     .07       0  5007.6      .1       0  5044.6     .05       0
  5150.6      .1       0  5248.8     .05       0  6740.6      .1       0
#XS Ineff= 2 , 0
                          5097.6         1797.08
Permanent Ineff=
       T       T
Bank Sta=4735.6,5034
XS Rating Curve= 0 ,0
Exp/Cntr=0.3,0.1

Type RM Length L Ch R = 1 ,55434   ,869,869,869
BEGIN DESCRIPTION:
BARONS CREEK 87.0
END DESCRIPTION:
XS GIS Cut Line= 3
      2747900.16     10078510.57      2745573.78      10077694.6
      2744375.89      10077651.2
#Sta/Elev= 30
  3323.7 1861.11  3367.9 1854.16  3431.5 1850.92  3478.2 1844.45  3634.7 1836.17
  3940.1 1828.16  3965.2 1824.85  4321.3 1817.86  4357.6 1813.81  4445.3 1813.36
  4586.6 1804.58  4671.3 1803.56    4736 1800.17  4899.8 1792.13  4925.5 1785.76
  4945.1 1783.78  4968.1 1779.04  4996.9 1777.61  4999.6 1777.11  5002.9 1777.61
    5074 1785.24  5101.9 1787.55  5250.7 1787.29  5379.9 1791.19  5934.4 1791.81
  6264.7 1795.46  6364.7 1799.65  6424.8 1805.59  6474.8  1804.7  6987.7 1826.77
#Mann= 8 ,-1 , 0
  3323.7      .1       0  3478.2     .05       0    4736      .1       0
  4945.1     .16       0  4996.9     .07       0  5002.9     .16       0
  5101.9      .1       0  5250.7     .05       0
#XS Ineff= 3 ,-1
 5236.29 5288.97 1787.72 5349.12 5365.81 1790.06 5384.69  6987.7 1791.26
Permanent Ineff=
       T       T       T
Bank Sta=4925.5,5074
XS Rating Curve= 0 ,0
Exp/Cntr=0.3,0.1

Type RM Length L Ch R = 1 ,54565   ,729,729,729
BEGIN DESCRIPTION:
BARONS CREEK 86.0
END DESCRIPTION:
XS GIS Cut Line= 3
      2748021.73     10077121.68      2745929.68     10077147.72
      2743854.99     10076409.86
#Sta/Elev= 30
  3135.1 1846.05  3176.6 1844.24  3308.4 1821.35  3354.2 1819.93  3472.8 1813.82
  3588.4 1803.87  3885.7 1792.35  4098.4 1787.94  4393.3 1785.13  4798.5 1788.03
  4918.5 1785.22  4948.5 1780.15  5005.5 1771.26  5008.3 1770.76  5011.5 1771.26
  5012.9  1771.4  5118.5 1780.21  5214.4  1783.5  5440.9 1782.85  5550.2 1790.09
  5646.2 1794.51  5894.3 1803.44  6238.2 1811.75  6625.9 1820.51    6756 1828.14
  6985.1 1838.73  7170.9 1837.51  7308.4 1843.69  7426.8 1856.81  7429.3 1856.81
#Mann= 18 ,-1 , 0
  3135.1     .16       0  3176.6      .1       0  3354.2     .08       0
  3472.8     .05       0  3885.7      .1       0  4098.4     .05       0
  4393.3      .1       0  5005.5     .07       0  5011.5      .1       0
  5012.9     .05       0  5214.4      .1       0  5550.2     .05       0
  5646.2      .1       0  5894.3     .05       0  6238.2      .1       0
  6625.9     .05       0    6756      .1       0  7426.8     .16       0
#XS Ineff= 2 ,-1
  3135.1 4788.44 1788.03 5408.97 5493.99 1786.31
Permanent Ineff=
       T       T
Bank Sta=4948.5,5118.5
XS Rating Curve= 0 ,0
Exp/Cntr=0.3,0.1

Type RM Length L Ch R = 1 ,53836   ,680,680,680
BEGIN DESCRIPTION:
BARONS CREEK 84.0
END DESCRIPTION:
XS GIS Cut Line= 3
      2747969.62     10076956.75      2746528.64     10076540.08
       2744463.1     10075993.32
#Sta/Elev= 30
  3340.9 1843.56  3383.7  1839.3  3394.2 1834.44    3415  1819.1  3539.9 1816.12
  3583.5 1808.14  3633.6 1808.87  3883.4 1792.52  4160.5 1783.25  4662.4 1783.63
  4734.8 1780.21  4755.5  1782.3    4789  1783.3  4892.8 1778.02  4993.3 1769.31
    4996 1768.81  4999.3 1769.31  5046.1 1773.98  5068.7 1777.84  5099.7 1783.42
  5311.5 1785.76  5393.9 1787.04  5435.9 1792.43  5947.9 1800.15  6251.2 1809.92
  6260.4 1809.83  6617.8 1809.54  6826.7  1820.1  6950.1 1824.45  6977.6 1826.69
#Mann= 13 ,-1 , 0
  3340.9     .08       0  3583.5     .05       0  4755.5      .1       0
  4993.3     .07       0  4999.3      .1       0  5046.1     .05       0
  5311.5      .1       0  5435.9     .05       0  6251.2     .16       0
  6260.4      .1       0  6617.8     .16       0  6826.7      .1       0
  6950.1     .16       0
#XS Ineff= 3 ,-1
  3340.9 4622.41  1783.8 4663.57 4778.35 1783.61 5198.68 5246.96  1783.8
Permanent Ineff=
       T       T       T
Bank Sta=4892.8,5068.7
XS Rating Curve= 0 ,0
Exp/Cntr=0.3,0.1

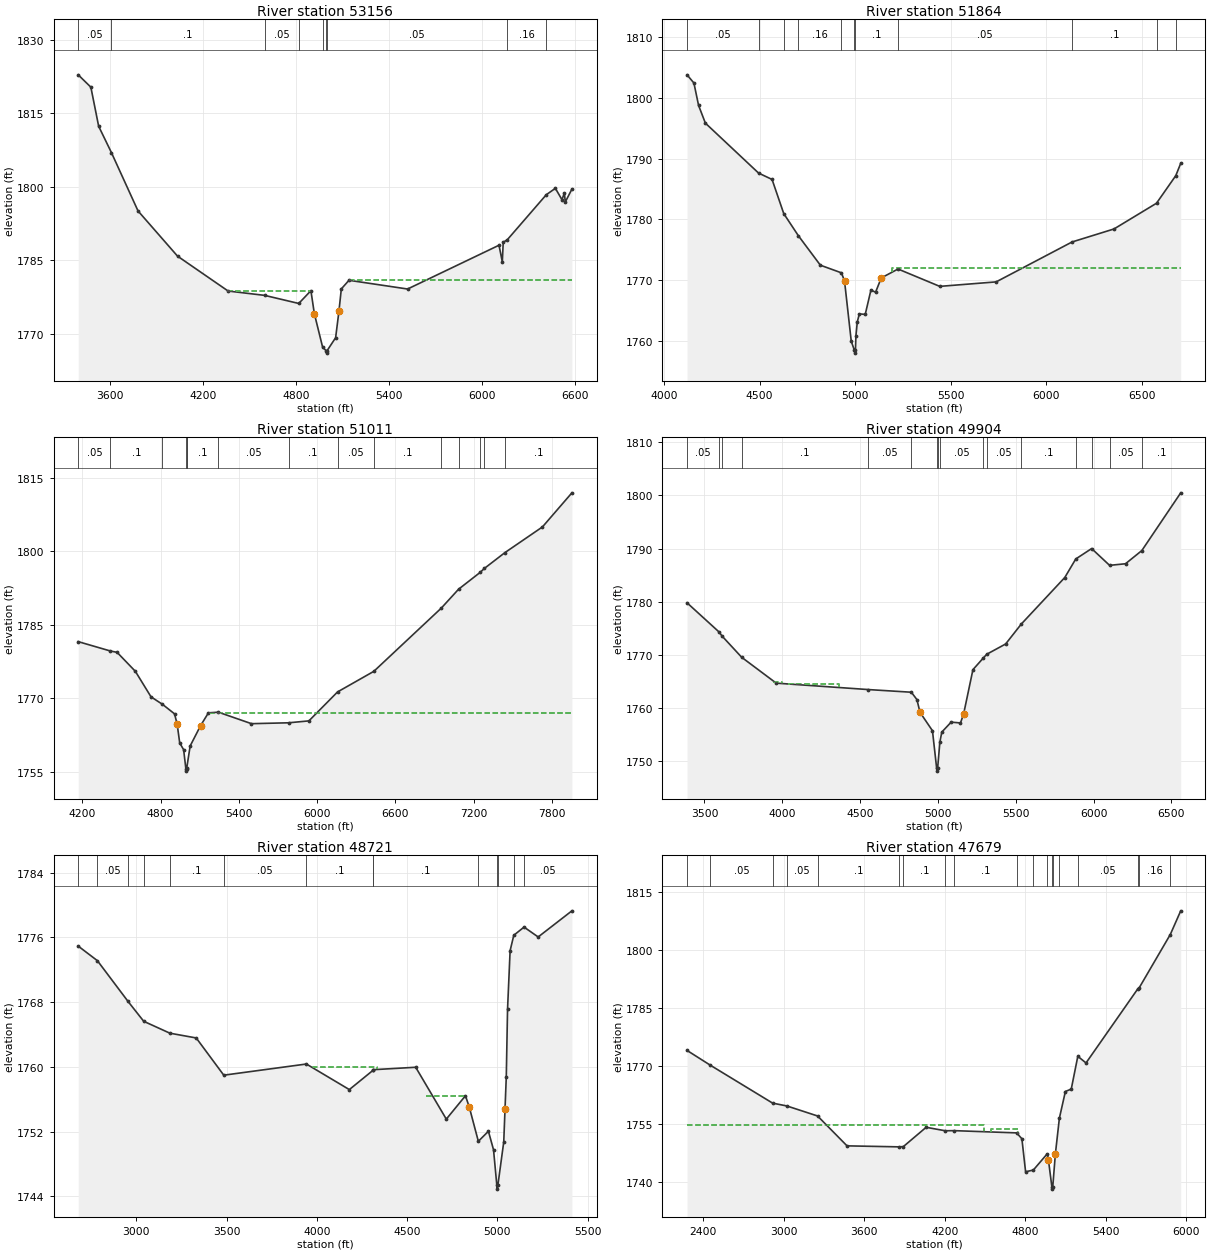
Type RM Length L Ch R = 1 ,53156   ,1292,1292,1292
BEGIN DESCRIPTION:
BARONS CREEK 81.0
END DESCRIPTION:
XS GIS Cut Line= 3
      2748316.88      10076314.4      2746875.86     10076019.25
      2745408.88     10075125.17
#Sta/Elev= 30
  3393.7 1822.89  3475.3 1820.37  3525.7 1812.39  3608.6 1806.98    3780  1795.1
  4035.2 1785.87  4361.8 1778.75    4598 1777.86  4818.1 1776.21  4896.7 1778.82
  4918.8 1774.14  4972.5 1767.26  4995.2 1766.57  4997.9 1766.07  5001.2 1766.57
  5056.3 1769.22  5077.6 1774.58  5093.1 1779.18  5142.6 1780.94  5521.1 1779.16
  6111.7  1788.1    6133  1784.7  6138.9 1788.69  6165.5 1789.23    6417 1798.41
  6475.8 1799.72  6518.4 1797.39  6533.9 1798.79  6539.7 1796.92  6582.6 1799.56
#Mann= 9 ,-1 , 0
  3393.7     .05       0  3608.6      .1       0    4598     .05       0
  4818.1      .1       0  4972.5     .05       0  4995.2     .04       0
  5001.2     .05       0  6165.5     .16       0    6417      .1       0
#XS Ineff= 2 ,-1
 4352.43 4896.56 1778.85 5143.18  6582.6 1781.03
Permanent Ineff=
       T       T
Bank Sta=4918.8,5077.6
XS Rating Curve= 0 ,0
Exp/Cntr=0.3,0.1

Type RM Length L Ch R = 1 ,51864   ,853,853,853
BEGIN DESCRIPTION:
BARONS CREEK 80.0
END DESCRIPTION:
XS GIS Cut Line= 2
      2748507.77      10075411.6      2746103.42     10074465.48
#Sta/Elev= 30
  4119.8 1803.83  4155.8 1802.48  4180.2 1798.79  4215.8 1795.87  4494.2 1787.64
  4564.8 1786.59    4626 1780.96  4702.8  1777.3  4817.6 1772.46  4927.9  1771.2
    4944 1769.87  4979.2 1759.94  4995.2 1758.47    4998 1757.97  5001.2 1758.47
  5003.6  1760.8    5011 1763.15  5021.7 1764.44  5052.4 1764.35  5082.2 1768.36
  5106.6 1768.01  5136.3 1770.36  5224.1 1771.83  5442.4 1768.97  5737.6 1769.71
  6135.1 1776.29  6354.3 1778.43  6576.8 1782.67  6677.8 1787.22  6703.6 1789.25
#Mann= 11 ,-1 , 0
  4119.8     .05       0  4494.2      .1       0    4626     .05       0
  4702.8     .16       0  4927.9      .1       0  4995.2     .07       0
  5001.2      .1       0  5224.1     .05       0  6135.1      .1       0
  6576.8     .16       0  6677.8      .1       0
#XS Ineff= 2 , 0
                          5190.4         1771.98
Permanent Ineff=
       T       T
Bank Sta=4944,5136.3
XS Rating Curve= 0 ,0
Exp/Cntr=0.3,0.1

Type RM Length L Ch R = 1 ,51011   ,1107,1107,1107
BEGIN DESCRIPTION:
BARONS CREEK 79.0
END DESCRIPTION:
XS GIS Cut Line= 2
      2748846.34     10074317.86      2745062.55     10074326.54
#Sta/Elev= 30
    4169 1781.55    4416 1779.64  4466.9 1779.37  4606.9  1775.5  4726.9  1770.3
  4814.4 1768.78  4906.9 1766.84  4926.9  1764.8  4946.9  1760.9  4976.9 1759.52
  4993.9 1755.66  4996.6 1755.16  4999.9 1755.66  5000.8 1755.81  5026.9 1760.29
  5106.9 1764.44  5166.9 1767.04  5243.5 1767.17  5496.9 1764.83    5781 1765.01
  5936.9  1765.4  6156.5  1771.3  6434.7  1775.5  6951.9 1788.39  7084.3 1792.24
  7249.3 1795.66  7281.7 1796.47    7439 1799.69  7726.9 1804.93  7952.8 1811.88
#Mann= 15 ,-1 , 0
    4169     .05       0    4416      .1       0  4814.4     .05       0
  4993.9     .04       0  4999.9     .05       0  5000.8      .1       0
  5243.5     .05       0    5781      .1       0  6156.5     .05       0
  6434.7      .1       0  6951.9     .16       0  7084.3      .1       0
  7249.3     .16       0  7281.7     .05       0    7439      .1       0
#XS Ineff= 2 , 0
                         5167.88         1767.08
Permanent Ineff=
       T       T
Bank Sta=4926.9,5106.9
XS Rating Curve= 0 ,0
Exp/Cntr=0.3,0.1

Type RM Length L Ch R = 1 ,49904   ,1183,1183,1183
BEGIN DESCRIPTION:
BARONS CREEK 83.0
END DESCRIPTION:
XS GIS Cut Line= 3
      2748776.87     10074213.67      2747856.76     10073415.08
      2745903.67     10073441.12
#Sta/Elev= 30
  3388.3 1779.78  3593.2 1774.31  3613.7 1773.51  3739.6 1769.52  3961.2 1764.66
  4553.5 1763.45  4829.3 1762.95    4865 1761.57  4885.1 1759.16    4965  1755.7
    4992  1748.6  4994.7  1748.1    4998  1748.6  5012.8 1753.61    5025 1755.45
    5085 1757.32    5145 1757.17    5165 1758.84    5225  1767.2  5288.9  1769.3
  5313.9  1770.1    5435 1772.03  5535.6 1775.78    5815 1784.54  5885.6 1788.03
  5987.5 1789.99  6102.9 1786.83  6205.1 1787.13  6309.9 1789.61  6559.9 1800.48
#Mann= 16 ,-1 , 0
  3388.3     .05       0  3593.2      .1       0  3613.7     .05       0
  3739.6      .1       0  4553.5     .05       0  4829.3      .1       0
    4992     .07       0    4998      .1       0  5012.8     .05       0
  5288.9      .1       0  5313.9     .05       0  5535.6      .1       0
  5885.6     .05       0  5987.5      .1       0  6102.9     .05       0
  6309.9      .1       0
#XS Ineff= 2 ,-1
 3942.25 3995.45 1764.96 4037.34 4365.87 1764.47
Permanent Ineff=
       T       T
Bank Sta=4885.1,5165
XS Rating Curve= 0 ,0
Exp/Cntr=0.3,0.1

Type RM Length L Ch R = 1 ,48721   ,1042,1042,1042
BEGIN DESCRIPTION:
BARONS CREEK 78.0
END DESCRIPTION:
XS GIS Cut Line= 2
      2748785.55     10074031.38      2746842.33      10072105.5
#Sta/Elev= 30
  2677.6 1774.92  2783.8 1773.12  2953.8 1768.08  3040.5 1765.63  3185.5 1764.16
  3331.5 1763.57  3484.2 1758.97    3942 1760.35    4180 1757.19  4312.3 1759.59
  4313.5 1759.65  4547.7 1759.95  4717.4 1753.54  4823.5 1756.43  4844.7 1755.03
  4894.9  1750.8  4950.8 1752.04  4979.1 1749.75  4997.3 1745.39    5000 1744.89
  5003.3 1745.39  5035.7 1750.72  5042.7 1754.73  5049.8 1758.78  5056.8 1767.14
    5071 1774.36  5091.4 1776.26  5148.2 1777.27  5226.5 1776.05  5413.5 1779.28
#Mann= 14 ,-1 , 0
  2677.6      .1       0  2783.8     .05       0  2953.8      .1       0
  3040.5     .05       0  3185.5      .1       0  3484.2     .05       0
    3942      .1       0  4312.3     .05       0  4313.5      .1       0
  4894.9     .05       0  4997.3    .035       0  5003.3     .05       0
  5091.4      .1       0  5148.2     .05       0
#XS Ineff= 2 ,-1
 3977.84 4332.39 1760.03 4606.82 4821.59 1756.42
Permanent Ineff=
       T       T
Bank Sta=4844.7,5042.7
XS Rating Curve= 0 ,0
Exp/Cntr=0.3,0.1

Type RM Length L Ch R = 1 ,47679   ,1068,1068,1068
BEGIN DESCRIPTION:
BARONS CREEK 77.0
END DESCRIPTION:
XS GIS Cut Line= 2
      2748837.65     10073935.88      2747110.21     10070689.35
#Sta/Elev= 30
  2280.6 1773.99  2454.7 1770.15  2918.2 1760.34  3024.9  1759.6  3252.9 1757.01
  3472.4 1749.27  3861.2 1749.01    3892 1749.08  4061.8 1754.08  4203.9 1753.18
    4272 1753.21  4735.4 1752.63  4774.9 1751.11  4802.5 1742.56  4860.1    1743
  4963.5  1747.2  4972.6 1745.63  4998.6 1738.56  5001.4 1738.06  5004.6 1738.56
  5024.3 1747.17  5054.2 1756.44  5098.8 1763.35  5142.7 1763.99  5191.5 1772.47
  5252.6 1770.75  5636.8 1789.87  5647.7 1790.16  5880.3 1804.02  5958.1 1810.16
#Mann= 19 ,-1 , 0
  2280.6      .1       0  2454.7     .05       0  2918.2      .1       0
  3024.9     .05       0  3252.9      .1       0  3861.2     .05       0
    3892      .1       0  4203.9     .05       0    4272      .1       0
  4735.4     .05       0  4860.1      .1       0  4963.5     .16       0
  4998.6     .07       0  5004.6     .16       0  5054.2      .1       0
  5191.5     .05       0  5636.8      .1       0  5647.7     .16       0
  5880.3      .1       0
#XS Ineff= 2 ,-1
  2280.6  4491.9 1754.62 4541.62  4742.4 1753.68
Permanent Ineff=
       T       T
Bank Sta=4972.6,5024.3
XS Rating Curve= 0 ,0
Exp/Cntr=0.3,0.1