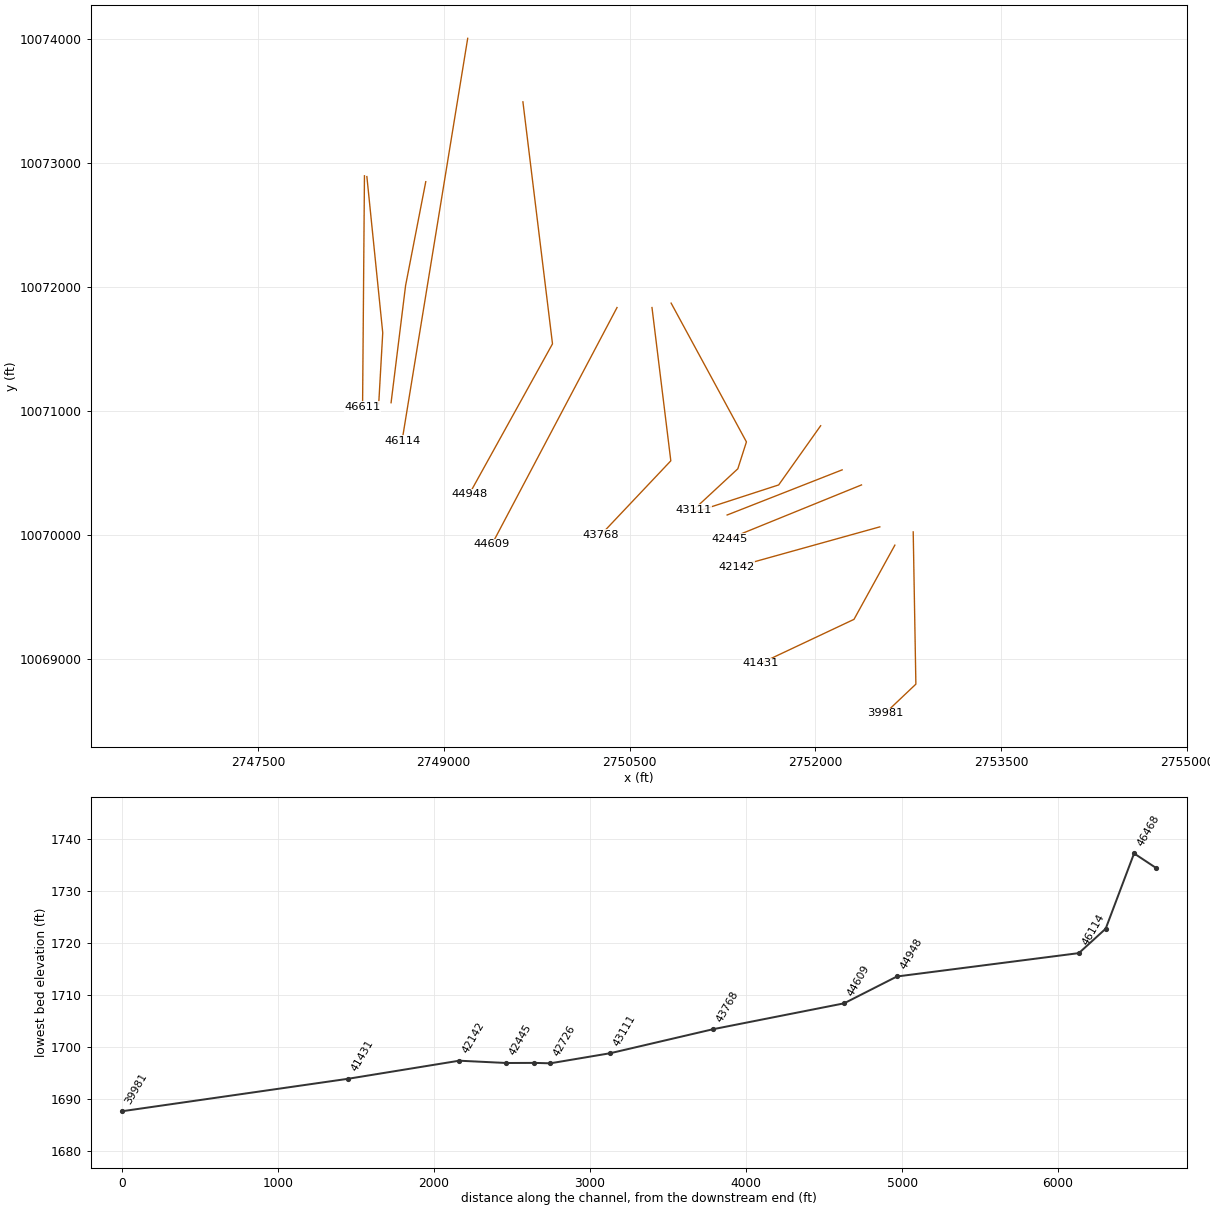
HEC-RAS study BARONS CREEK.prj: BARONS CREEK Base Level Engineering

--- BARONS CREEK.g01 (geometry) --- (continued)

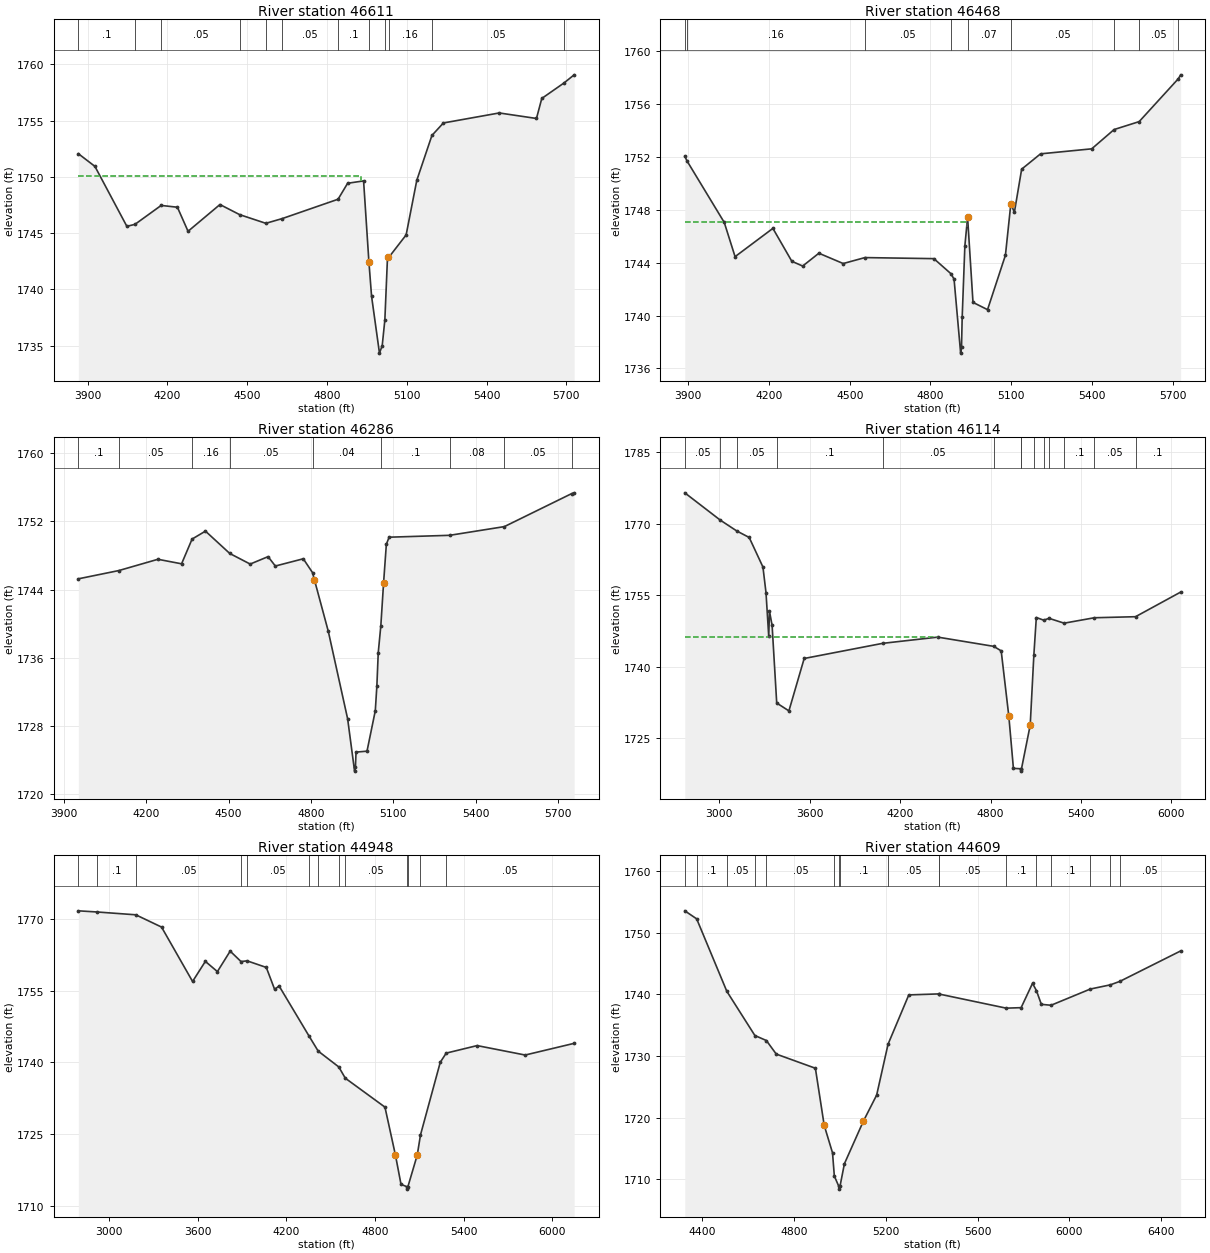
Type RM Length L Ch R = 1 ,46611   ,143,143,143
BEGIN DESCRIPTION:
Mapping XS 8040a8e4
END DESCRIPTION:
XS GIS Cut Line= 2
      2748360.34     10072896.18      2748345.15     10071032.04
#Sta/Elev= 30
  3864.9 1752.06  3927.3 1750.93  4047.4  1745.6    4078 1745.78  4176.3 1747.46
  4237.4  1747.3  4277.4 1745.16  4397.4 1747.54  4471.5 1746.64  4569.9 1745.87
  4631.5 1746.29  4841.4 1748.01  4877.4 1749.43  4937.4 1749.64  4957.4 1742.44
  4967.4 1739.39  4997.1 1734.33  5007.4 1734.99  5017.4 1737.29  5027.4  1742.9
  5031.4 1742.82  5097.4 1744.84  5137.4 1749.69  5194.3 1753.68  5237.4 1754.79
  5447.4 1755.68  5587.4 1755.19  5607.4 1756.97  5690.5 1758.34  5729.1 1759.07
#Mann= 12 ,-1 , 0
  3864.9      .1       0    4078     .16       0  4176.3     .05       0
  4471.5     .16       0  4569.9      .1       0  4631.5     .05       0
  4841.4      .1       0  4957.4     .07       0  5017.4      .1       0
  5031.4     .16       0  5194.3     .05       0  5690.5      .1       0
#XS Ineff= 2 , 0
         4926.14 1750.05
Permanent Ineff=
       T       T
Bank Sta=4957.4,5027.4
XS Rating Curve= 0 ,0
Exp/Cntr=0.3,0.1

Type RM Length L Ch R = 1 ,46468   ,182,182,182
BEGIN DESCRIPTION:
Mapping XS a6f0c7c6
END DESCRIPTION:
XS GIS Cut Line= 3
      2748379.87     10072889.64      2748507.91     10071628.83
      2748475.36     10071053.75
#Sta/Elev= 30
  3886.9 1752.05  3895.8 1751.68  4033.6 1747.05  4073.8 1744.46  4214.4  1746.6
  4284.8 1744.11  4325.1 1743.75  4385.4 1744.72  4475.8 1743.94  4556.5 1744.39
  4812.9 1744.31  4876.3 1743.17  4887.9 1742.76  4912.4 1737.16  4915.7 1737.66
  4918.1 1739.86  4928.1 1745.28  4938.2 1747.44  4958.3    1741  5012.4 1740.45
  5078.9 1744.57    5099 1748.46  5112.2 1747.82  5139.2 1751.08  5209.4 1752.24
  5399.7 1752.62  5482.9 1754.08  5576.1 1754.68  5721.9 1757.93  5730.2 1758.22
#Mann= 9 ,-1 , 0
  3886.9      .1       0  3895.8     .16       0  4556.5     .05       0
  4876.3      .1       0  4938.2     .07       0    5099     .05       0
  5482.9     .08       0  5576.1     .05       0  5721.9      .1       0
#XS Ineff= 2 , 0
         4934.66 1747.11
Permanent Ineff=
       T       T
Bank Sta=4938.2,5099
XS Rating Curve= 0 ,0
Exp/Cntr=0.3,0.1

Type RM Length L Ch R = 1 ,46286   ,172,172,172
BEGIN DESCRIPTION:
Mapping XS 1343be61
END DESCRIPTION:
XS GIS Cut Line= 3
      2748855.13     10072848.43      2748692.37     10072010.77
      2748575.19     10071064.62
#Sta/Elev= 30
  3952.6 1745.26  4100.3 1746.23  4242.6 1747.55  4328.8 1747.02  4367.1 1749.92
  4415.8 1750.85  4504.5 1748.23  4578.8 1746.99    4644 1747.86  4670.5 1746.76
  4772.3 1747.61  4805.9 1745.99    4813 1745.13  4863.4 1739.11  4933.9 1728.85
  4959.2 1722.72  4962.4 1723.22  4964.5 1724.95  5004.5 1725.06  5034.7  1729.8
  5040.4 1732.69  5045.4 1736.59  5054.9 1739.78  5064.9  1744.8    5075 1749.32
  5085.1 1750.14  5305.8 1750.36    5505 1751.38  5750.3 1755.25  5759.3 1755.34
#Mann= 9 ,-1 , 0
  3952.6      .1       0  4100.3     .05       0  4367.1     .16       0
  4504.5     .05       0  4805.9     .04       0  5054.9      .1       0
  5305.8     .08       0    5505     .05       0  5750.3      .1       0
Bank Sta=4813,5064.9
XS Rating Curve= 0 ,0
Exp/Cntr=0.3,0.1

Type RM Length L Ch R = 1 ,46114   ,1166,1166,1166
BEGIN DESCRIPTION:
BARONS CREEK 76.0
END DESCRIPTION:
XS GIS Cut Line= 2
      2749193.57     10074005.38      2748664.06     10070758.88
#Sta/Elev= 30
  2771.4 1776.52  3006.5 1770.79  3116.5  1768.5  3198.6 1767.14  3289.8 1760.93
  3310.1 1755.55  3328.2 1746.37  3333.3 1751.63  3350.6 1748.67  3381.2 1732.35
  3462.1  1730.7  3563.4 1741.71  4083.7 1744.89  4449.6  1746.2    4821 1744.26
  4870.4 1743.31  4921.1 1729.57  4951.5 1718.62  4999.1 1718.54  5001.9 1718.04
  5005.1 1718.54  5062.9  1727.7  5087.3 1742.54  5103.5 1750.32  5152.5 1749.76
  5187.7 1750.15    5288 1749.13  5488.8 1750.27  5761.7 1750.49  6060.8 1755.66
#Mann= 14 ,-1 , 0
  2771.4     .05       0  3006.5      .1       0  3116.5     .05       0
  3381.2      .1       0  4083.7     .05       0    4821      .1       0
  4999.1     .07       0  5005.1      .1       0  5087.3     .05       0
  5152.5      .1       0  5187.7     .08       0    5288      .1       0
  5488.8     .05       0  5761.7      .1       0
#XS Ineff= 2 , 0
            4450 1746.27
Permanent Ineff=
       T       T
Bank Sta=4921.1,5062.9
XS Rating Curve= 0 ,0
Exp/Cntr=0.3,0.1

Type RM Length L Ch R = 1 ,44948   ,339,339,339
BEGIN DESCRIPTION:
BARONS CREEK 74.0
END DESCRIPTION:
XS GIS Cut Line= 3
       2749639.2     10073492.84      2749877.91     10071539.75
      2749205.16     10070324.46
#Sta/Elev= 30
  2791.1 1771.63    2918 1771.39  3180.1  1770.8  3354.4 1768.24  3564.5 1756.89
    3651 1761.08  3732.6 1758.95  3819.1 1763.22  3892.3 1761.05  3933.9 1761.19
  4063.6 1759.82    4120 1755.24  4150.2 1755.95  4352.6 1745.52  4414.9 1742.36
  4554.2 1739.06  4598.4 1736.71  4866.9 1730.67  4937.9 1720.66  4975.7 1714.55
  5016.2 1714.06    5019 1713.56  5022.2 1714.06  5085.6 1720.68  5107.5 1724.87
  5241.4 1740.03  5281.6 1741.94    5491 1743.51  5816.2 1741.54  6147.8 1743.98
#Mann= 13 ,-1 , 0
  2791.1     .05       0    2918      .1       0  3180.1     .05       0
  3892.3      .1       0  3933.9     .05       0  4352.6      .1       0
  4414.9     .05       0  4554.2      .1       0  4598.4     .05       0
  5016.2    .035       0  5022.2     .05       0  5107.5      .1       0
  5281.6     .05       0
Bank Sta=4937.9,5085.6
XS Rating Curve= 0 ,0
Exp/Cntr=0.3,0.1

Type RM Length L Ch R = 1 ,44609   ,841,841,841
BEGIN DESCRIPTION:
BARONS CREEK 73.0
END DESCRIPTION:
XS GIS Cut Line= 2
      2750398.73     10071832.69      2749389.64     10069923.01
#Sta/Elev= 30
  4324.2 1753.56  4375.9 1752.26  4507.3  1740.5  4629.5 1733.33  4679.5 1732.52
  4722.6 1730.32  4893.1 1728.02  4931.5 1718.75  4967.7  1714.3  4975.6 1710.53
  4994.5 1708.91  4997.2 1708.41  5000.5 1708.91  5019.5 1712.53  5101.9 1719.42
    5160 1723.67  5209.6 1731.92    5300 1739.92  5430.2 1740.08    5432 1740.06
  5724.4 1737.77  5789.3 1737.85    5839  1741.8  5855.9 1740.62  5877.4 1738.39
  5919.6 1738.24  6090.6 1740.87  6177.7 1741.55  6219.1 1742.11  6484.1 1747.05
#Mann= 17 ,-1 , 0
  4324.2     .05       0  4375.9      .1       0  4507.3     .05       0
  4629.5      .1       0  4679.5     .05       0  4975.6      .1       0
  4994.5     .07       0  5000.5      .1       0  5209.6     .05       0
  5430.2      .1       0    5432     .05       0  5724.4      .1       0
  5855.9     .05       0  5919.6      .1       0  6090.6     .05       0
  6177.7      .1       0  6219.1     .05       0
Bank Sta=4931.5,5101.9
XS Rating Curve= 0 ,0
Exp/Cntr=0.3,0.1

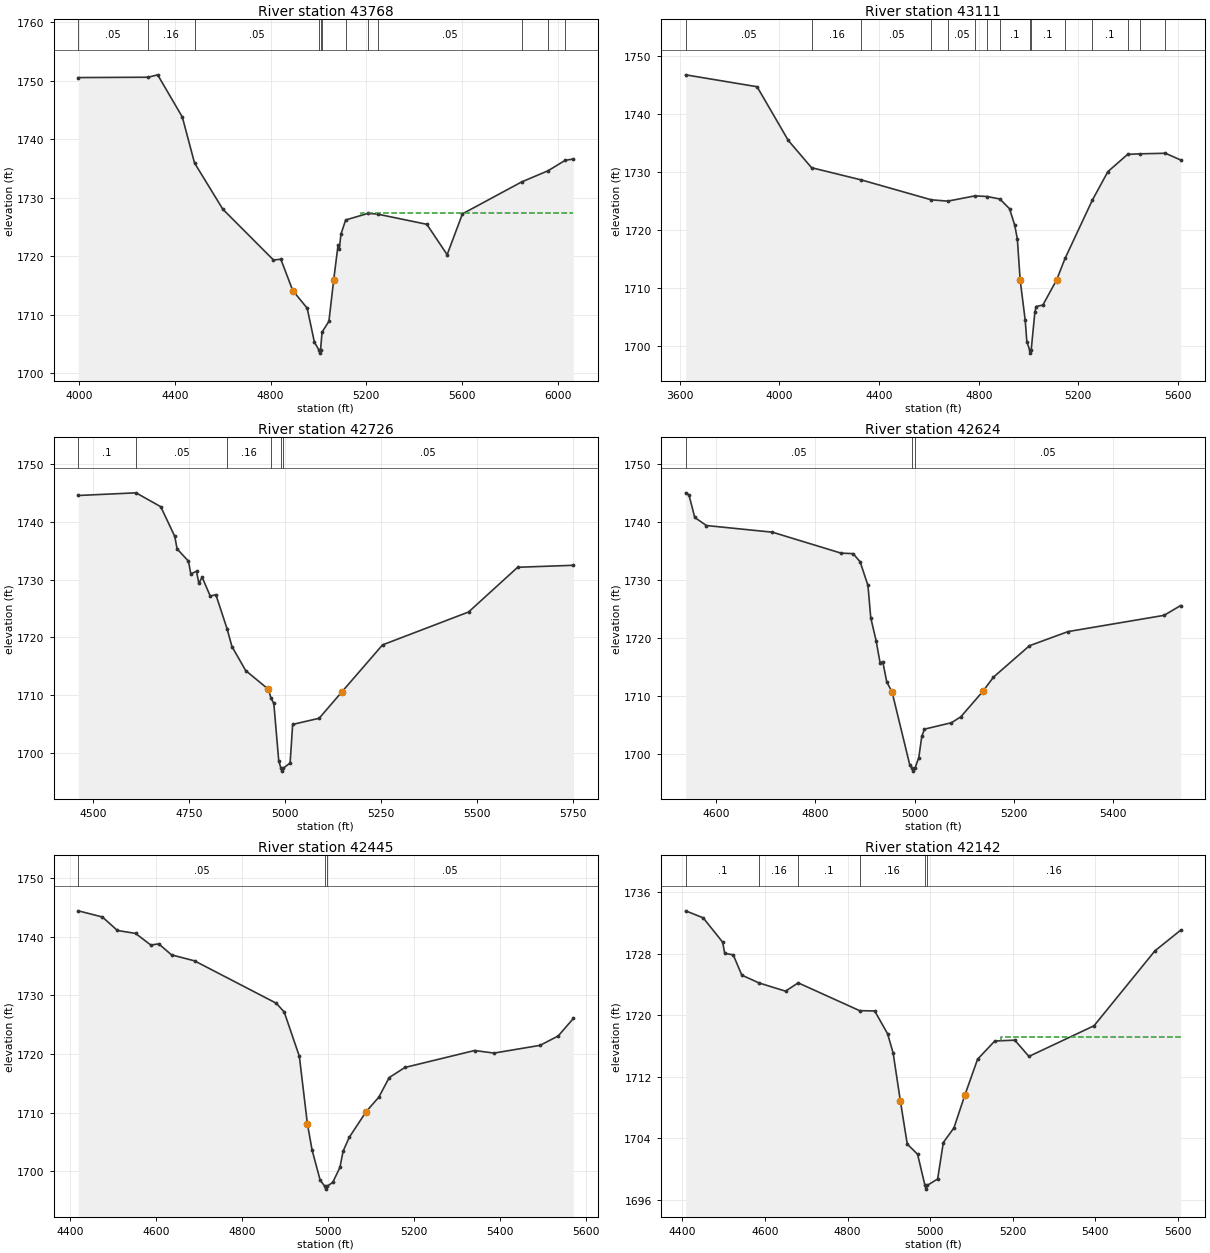
Type RM Length L Ch R = 1 ,43768   ,657,657,657
BEGIN DESCRIPTION:
BARONS CREEK 72.0
END DESCRIPTION:
XS GIS Cut Line= 3
      2750680.86     10071832.72      2750832.77     10070595.74
      2750268.51     10069998.92
#Sta/Elev= 30
  3996.8 1750.52  4288.6 1750.58  4328.3 1750.99  4431.2 1743.79  4482.2 1735.94
  4600.3 1728.04  4811.9 1719.36  4842.8 1719.48  4892.5 1714.14  4952.9 1711.11
  4983.1 1705.29  5002.5 1703.94  5005.2 1703.44  5008.5 1703.94    5015 1707.03
  5043.6 1708.88  5063.7    1716  5081.8 1721.92  5086.8 1721.18    5094 1723.79
  5113.6 1726.19  5207.3 1727.32    5247 1727.19  5452.5 1725.45  5537.4 1720.26
  5601.4 1727.24  5848.5 1732.69  5958.5 1734.59  6030.4 1736.38  6064.4 1736.61
#Mann= 12 ,-1 , 0
  3996.8     .05       0  4288.6     .16       0  4482.2     .05       0
  5002.5    .035       0  5008.5     .05       0    5015     .16       0
  5113.6     .05       0  5207.3      .1       0    5247     .05       0
  5848.5     .08       0  5958.5     .05       0  6030.4     .08       0
#XS Ineff= 2 , 0
                         5177.27         1727.33
Permanent Ineff=
       T       T
Bank Sta=4892.5,5063.7
XS Rating Curve= 0 ,0
Exp/Cntr=0.3,0.1

Type RM Length L Ch R = 1 ,43111   ,385,385,385
BEGIN DESCRIPTION:
BARONS CREEK 71.0
END DESCRIPTION:
XS GIS Cut Line= 4
      2750835.37     10071868.33      2751443.02     10070748.52
      2751373.57     10070531.51      2751017.64     10070201.62
#Sta/Elev= 30
  3623.5 1746.79  3910.3 1744.74  4035.7 1735.48  4129.1 1730.79  4329.4 1728.68
  4609.6 1725.26  4675.7 1725.03    4785 1725.94  4834.5 1725.83  4884.8  1725.4
  4923.6 1723.73  4944.6 1720.88  4955.1 1718.52  4966.3 1711.49  4986.6 1704.53
  4993.2 1700.84  5004.6 1699.35  5007.3 1698.85  5010.6 1699.35  5025.3 1705.86
  5030.6 1706.88  5057.5 1707.13  5112.6 1711.45  5146.9 1715.19  5255.6 1725.16
  5318.6 1730.12  5397.8 1733.09  5446.2 1733.18  5549.6 1733.28  5610.7 1732.12
#Mann= 15 ,-1 , 0
  3623.5     .05       0  4129.1     .16       0  4329.4     .05       0
  4609.6      .1       0  4675.7     .05       0    4785      .1       0
  4834.5     .05       0  4884.8      .1       0  5004.6     .07       0
  5010.6      .1       0  5146.9     .05       0  5255.6      .1       0
  5397.8     .05       0  5446.2      .1       0  5549.6     .05       0
Bank Sta=4966.3,5112.6
XS Rating Curve= 0 ,0
Exp/Cntr=0.3,0.1

Type RM Length L Ch R = 1 ,42726   ,102,102,102
BEGIN DESCRIPTION:
Mapping XS fdb768b1
END DESCRIPTION:
XS GIS Cut Line= 3
        2752042.     10070878.76      2751703.43      10070401.3
        2751035.     10070184.27
#Sta/Elev= 30
  4462.3 1744.53  4612.6 1744.99  4676.9 1742.59  4713.3 1737.47  4719.4 1735.31
    4749 1733.18  4755.1 1730.98  4769.9 1731.44    4776 1729.36  4784.6 1730.41
  4805.6 1727.16  4820.3 1727.39  4849.3 1721.53  4862.1 1718.44  4897.8 1714.29
  4956.9 1711.05  4963.7 1709.52  4971.1 1708.61  4983.9 1698.68  4989.6 1697.41
  4992.3 1696.91  4995.6 1697.41  5013.5 1698.32  5020.1 1704.98    5089 1706.04
  5147.5 1710.55    5254 1718.72  5477.8  1724.4  5605.6 1732.13  5750.4 1732.47
#Mann= 6 ,-1 , 0
  4462.3      .1       0  4612.6     .05       0  4849.3     .16       0
  4963.7     .05       0  4989.6     .04       0  4995.6     .05       0
Bank Sta=4956.9,5147.5
XS Rating Curve= 0 ,0
Exp/Cntr=0.3,0.1

Type RM Length L Ch R = 1 ,42624   ,179,179,179
BEGIN DESCRIPTION:
BARONS CREEK 70.0
END DESCRIPTION:
XS GIS Cut Line= 2
      2752215.56     10070522.81       2751287.4     10070158.49
#Sta/Elev= 30
  4538.6 1744.99  4545.3 1744.62    4557 1740.74  4580.5 1739.35  4713.4  1738.2
  4851.6 1734.59    4876  1734.5    4890  1733.1  4905.8 1729.03  4911.5 1723.42
  4922.2 1719.52  4930.3 1715.65  4935.6 1715.88  4943.7 1712.38  4954.4 1710.63
  4989.9 1698.12  4994.4 1697.49  4997.2 1696.99  5000.4 1697.49  5008.2 1699.31
  5014.3    1703  5019.7 1704.23  5073.9 1705.34  5092.9 1706.36  5137.1 1710.73
  5158.6  1713.2  5231.2 1718.62    5309 1721.06  5502.3 1723.86  5535.7 1725.55
#Mann= 3 ,-1 , 0
  4538.6     .05       0  4994.4     .04       0  5000.4     .05       0
Bank Sta=4954.4,5137.1
XS Rating Curve= 0 ,0
Exp/Cntr=0.3,0.1

Type RM Length L Ch R = 1 ,42445   ,303,303,303
BEGIN DESCRIPTION:
Mapping XS f30d2cad
END DESCRIPTION:
XS GIS Cut Line= 2
      2752371.81     10070401.29      2751305.91       10069968.
#Sta/Elev= 30
  4419.8 1744.43  4475.8 1743.38  4510.7 1741.08  4552.9 1740.58  4588.3  1738.6
  4606.9 1738.79  4636.5 1736.92    4690  1735.9  4880.1 1728.67  4898.4 1727.18
  4933.6 1719.62  4952.3 1708.11  4963.1 1703.68  4981.8 1698.54  4992.5 1697.47
  4995.3 1696.97  4998.5 1697.47  5011.3 1698.13  5027.9 1700.67  5035.3 1703.45
  5049.5 1705.79  5088.9 1710.19  5118.3 1712.65  5142.4 1715.99    5179 1717.72
    5341 1720.61    5386 1720.17  5493.1 1721.49  5535.3 1723.09  5570.4 1726.07
#Mann= 3 ,-1 , 0
  4419.8     .05       0  4992.5     .04       0  4998.5     .05       0
Bank Sta=4952.3,5088.9
XS Rating Curve= 0 ,0
Exp/Cntr=0.3,0.1

Type RM Length L Ch R = 1 ,42142   ,711,711,711
BEGIN DESCRIPTION:
BARONS CREEK 69.0
END DESCRIPTION:
XS GIS Cut Line= 2
      2752519.45     10070062.77      2751364.89     10069741.58
#Sta/Elev= 30
  4408.1 1733.54  4450.6 1732.63  4497.6 1729.48  4502.8 1728.01  4523.3 1727.83
  4544.1 1725.19  4586.1 1724.17    4650 1723.11  4680.5 1724.19  4829.3 1720.58
  4865.8 1720.54    4897 1717.58  4910.4 1715.09  4928.1  1708.8  4944.6 1703.26
  4969.6 1701.94  4987.4 1697.91  4990.1 1697.41  4993.4 1697.91  5018.2 1698.73
  5031.9 1703.46  5057.7 1705.37  5083.8 1709.58  5114.9 1714.28  5156.5 1716.64
  5204.9 1716.75  5239.2 1714.64  5396.8 1718.62  5544.1 1728.34  5606.5 1731.03
#Mann= 6 ,-1 , 0
  4408.1      .1       0  4586.1     .16       0  4680.5      .1       0
  4829.3     .16       0  4987.4     .07       0  4993.4     .16       0
#XS Ineff= 2 , 0
                         5171.59         1717.13
Permanent Ineff=
       T       T
Bank Sta=4928.1,5083.8
XS Rating Curve= 0 ,0
Exp/Cntr=0.3,0.1

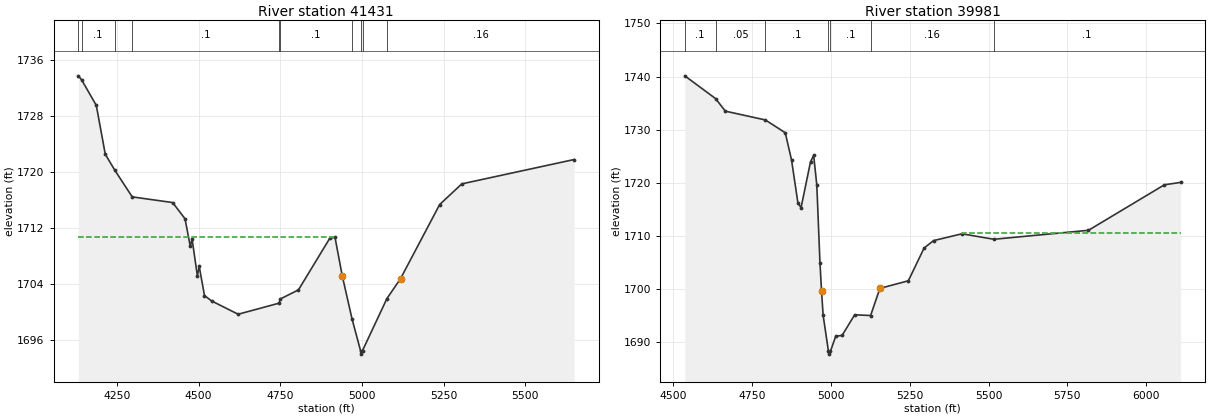
Type RM Length L Ch R = 1 ,41431   ,1450,1450,1450
BEGIN DESCRIPTION:
BARONS CREEK 68.0
END DESCRIPTION:
XS GIS Cut Line= 3
      2752640.96     10069915.23      2752311.07     10069316.23
      2751555.86     10068960.33
#Sta/Elev= 30
  4131.5 1733.72  4141.5 1733.15  4186.5  1729.5    4214 1722.52  4243.1 1720.24
  4296.6 1716.42  4420.4 1715.61  4458.3 1713.29  4474.3 1709.38    4480 1710.37
  4496.1 1705.15  4501.8 1706.48  4517.9 1702.32  4539.7 1701.55  4621.1 1699.65
  4746.1 1701.23  4750.5 1701.84  4805.7 1703.13  4902.2 1710.54  4917.7 1710.64
  4939.8 1705.16  4969.8 1698.99  4995.9 1694.45  4998.6 1693.95  5001.9 1694.45
  5076.7 1701.89  5118.3 1704.73  5238.3 1715.33  5306.1 1718.28  5650.2 1721.76
#Mann= 10 ,-1 , 0
  4131.5     .05       0  4141.5      .1       0  4243.1     .05       0
  4296.6      .1       0  4746.1     .12       0  4750.5      .1       0
  4969.8     .12       0  4995.9     .07       0  5001.9     .12       0
  5076.7     .16       0
#XS Ineff= 2 , 0
         4917.39 1710.71
Permanent Ineff=
       T       T
Bank Sta=4939.8,5118.3
XS Rating Curve= 0 ,0
Exp/Cntr=0.3,0.1

Type RM Length L Ch R = 1 ,39981   ,948,948,948
BEGIN DESCRIPTION:
BARONS CREEK 67.0
END DESCRIPTION:
XS GIS Cut Line= 3
      2752789.03     10070022.18      2752810.58     10068793.47
      2752561.76     10068557.52
#Sta/Elev= 30
  4537.2 1740.13  4634.8 1735.84  4665.7 1733.48  4792.6 1731.82  4855.7 1729.41
  4875.7 1724.24  4895.7 1716.22  4905.7 1715.29  4935.7 1723.93  4945.7 1725.16
  4955.7 1719.54  4965.7 1704.92 4970.69 1699.58  4975.7 1695.05  4992.7 1688.22
  4995.5 1687.72  4998.7 1688.22  5015.7 1691.11  5035.7 1691.23  5075.7 1695.13
  5126.2 1694.99  5155.7  1700.1  5245.8 1701.53  5295.8  1707.7  5325.8  1709.1
  5415.8 1710.38  5516.8 1709.35  5816.9 1711.04  6057.6 1719.61    6109 1720.06
#Mann= 7 ,-1 , 0
  4537.2      .1       0  4634.8     .05       0  4792.6      .1       0
  4992.7     .07       0  4998.7      .1       0  5126.2     .16       0
  5516.8      .1       0
#XS Ineff= 2 , 0
                         5415.57         1710.58
Permanent Ineff=
       T       T
Bank Sta=4970.69,5155.7
XS Rating Curve= 0 ,0
Exp/Cntr=0.3,0.1