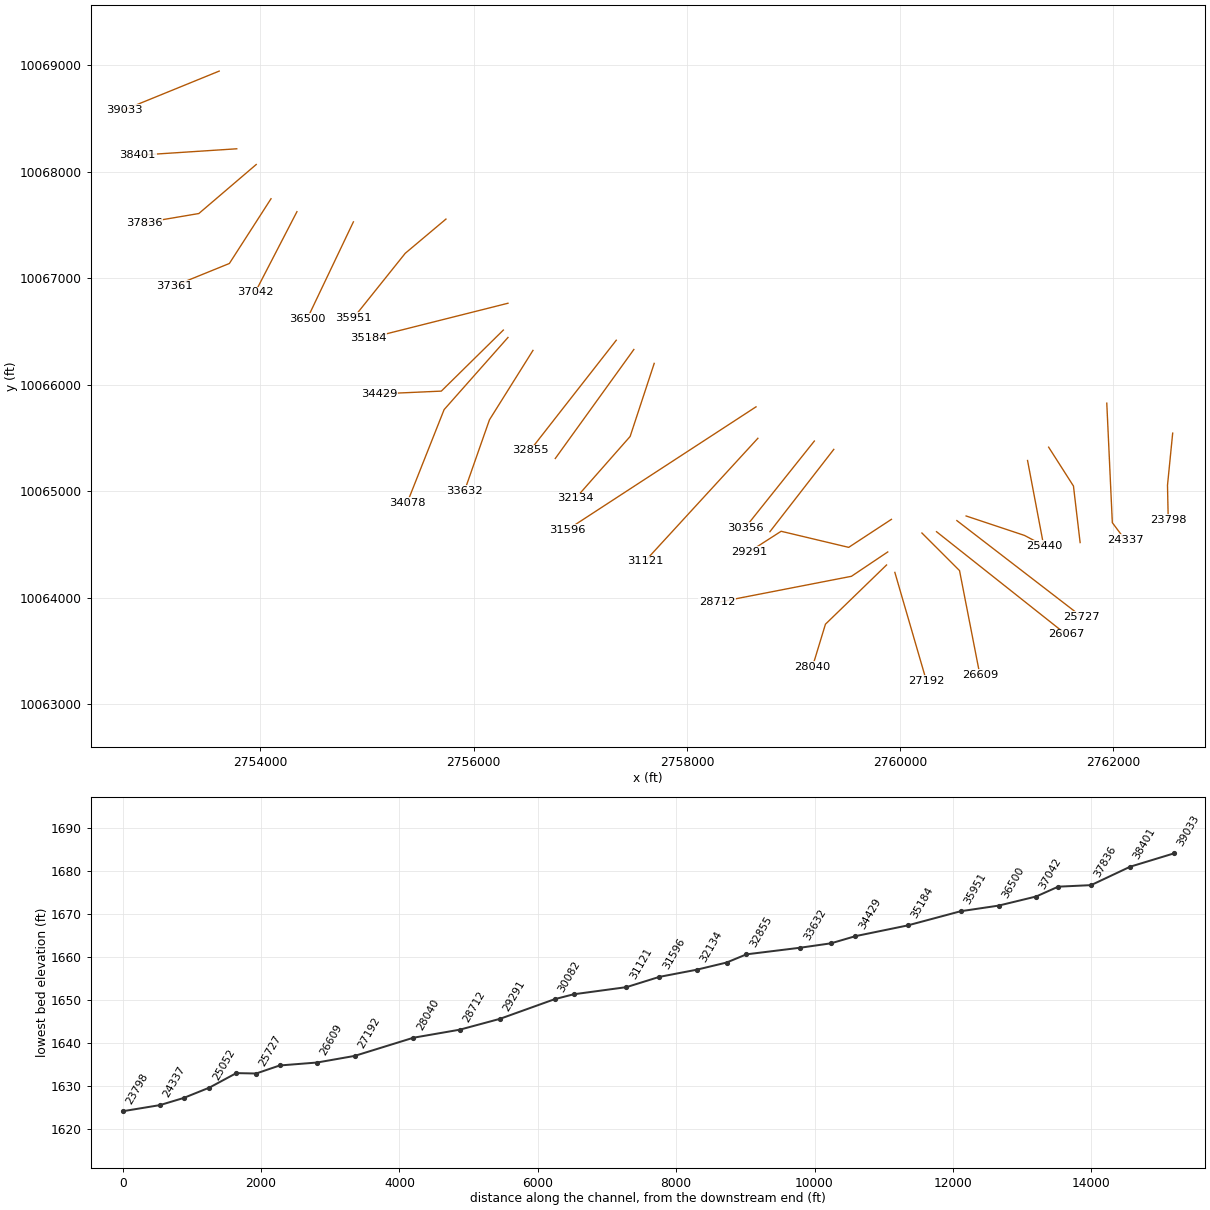
HEC-RAS study BARONS CREEK.prj: BARONS CREEK Base Level Engineering

--- BARONS CREEK.g01 (geometry) --- (continued)

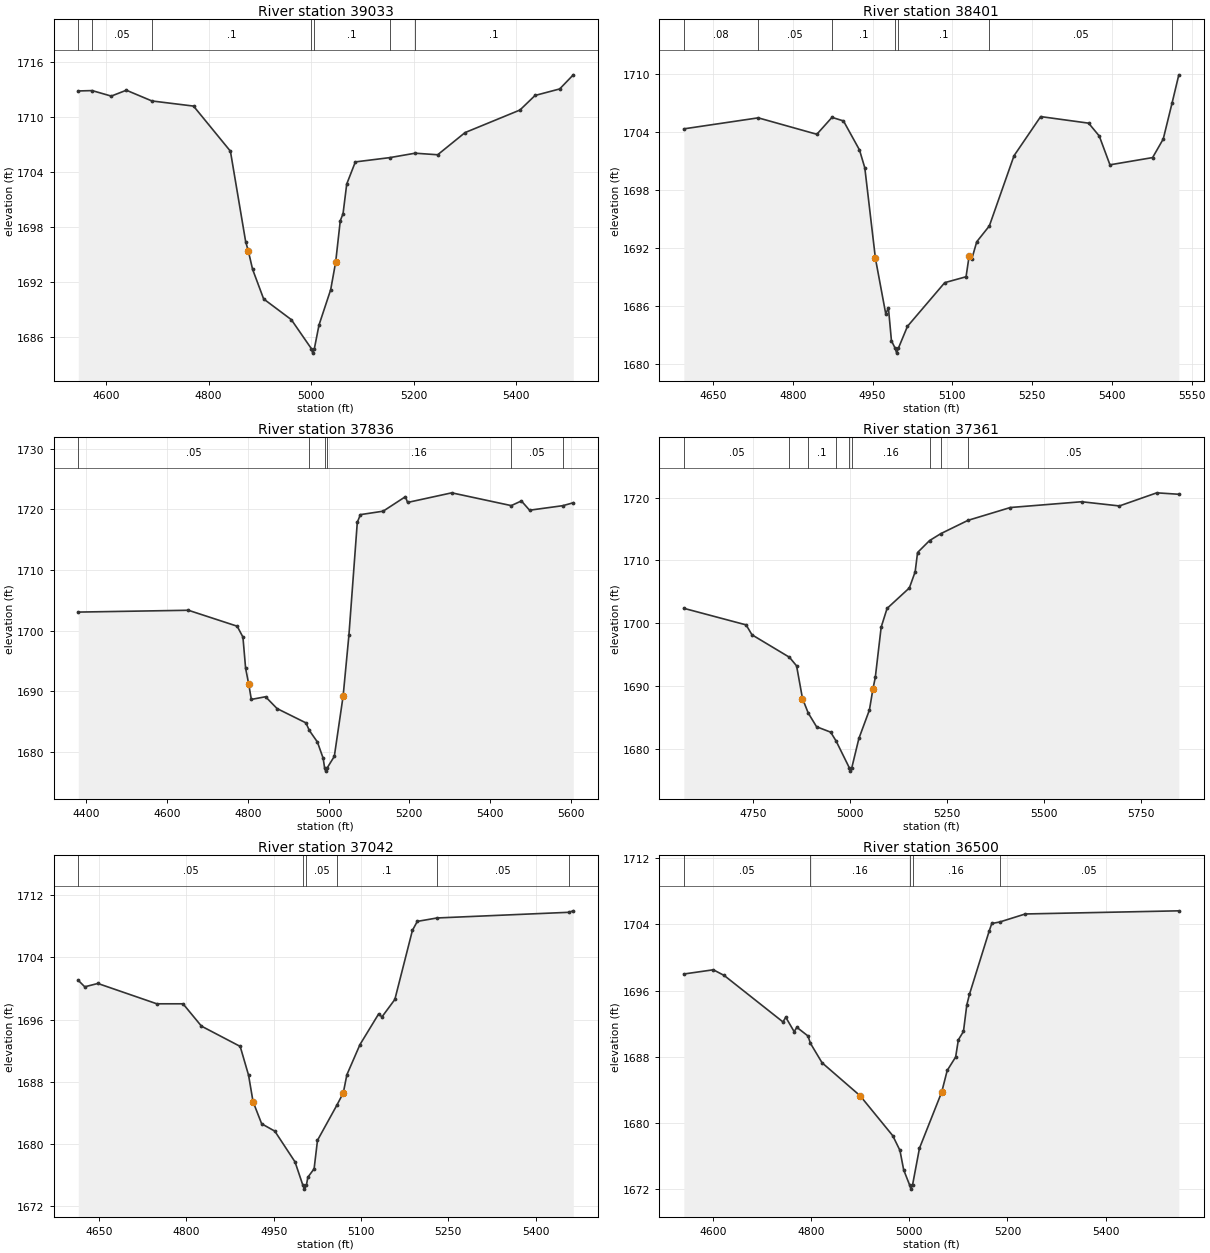
Type RM Length L Ch R = 1 ,39033   ,632,632,632
BEGIN DESCRIPTION:
BARONS CREEK 66.0
END DESCRIPTION:
XS GIS Cut Line= 2
      2753613.11     10068942.95      2752719.45     10068578.54
#Sta/Elev= 30
    4546 1712.79    4573 1712.83  4610.3 1712.23  4639.7 1712.87  4689.5  1711.7
  4770.7 1711.14  4842.6 1706.22  4872.3 1696.36  4877.7 1695.29  4885.8 1693.34
  4907.4  1690.1  4961.4 1687.84  5000.3 1684.69    5003 1684.19  5006.3 1684.69
  5015.4 1687.27  5038.1 1691.11  5047.8 1694.11  5056.8 1698.63  5062.2  1699.4
  5069.4 1702.64  5086.2 1705.05  5153.6 1705.52  5202.7    1706  5246.7 1705.83
  5300.1 1708.25  5407.1 1710.71  5436.6  1712.3  5484.6 1713.01  5511.1 1714.55
#Mann= 7 ,-1 , 0
    4546     .08       0    4573     .05       0  4689.5      .1       0
  5000.3     .07       0  5006.3      .1       0  5153.6     .05       0
  5202.7      .1       0
Bank Sta=4877.7,5047.8
XS Rating Curve= 0 ,0
Exp/Cntr=0.3,0.1

Type RM Length L Ch R = 1 ,38401   ,565,565,565
BEGIN DESCRIPTION:
BARONS CREEK 65.0
END DESCRIPTION:
XS GIS Cut Line= 2
      2753778.05     10068213.79      2752849.23     10068153.03
#Sta/Elev= 30
  4595.1 1704.29    4735 1705.43  4845.2 1703.73  4873.7 1705.48  4895.3 1705.11
  4925.4 1702.11  4935.4 1700.26  4955.4 1690.88  4974.8 1685.15  4979.8 1685.78
  4985.5 1682.37  4992.5 1681.59  4995.3 1681.09  4998.5 1681.59  5015.6 1683.86
  5085.7 1688.38  5125.8 1688.99  5131.5  1691.1  5136.5 1690.81  5145.9 1692.61
  5169.6 1694.25    5216 1701.51  5266.1 1705.56  5356.3 1704.88  5376.3 1703.55
  5396.4 1700.57  5476.6 1701.32  5496.6 1703.24  5513.2 1706.96  5525.9 1709.88
#Mann= 7 ,-1 , 0
  4595.1     .08       0    4735     .05       0  4873.7      .1       0
  4992.5     .07       0  4998.5      .1       0  5169.6     .05       0
  5513.2      .1       0
Bank Sta=4955.4,5131.5
XS Rating Curve= 0 ,0
Exp/Cntr=0.3,0.1

Type RM Length L Ch R = 1 ,37836   ,475,475,475
BEGIN DESCRIPTION:
BARONS CREEK 64.0
END DESCRIPTION:
XS GIS Cut Line= 3
      2753960.35      10068066.2      2753422.18     10067606.16
      2752911.76     10067519.65
#Sta/Elev= 30
  4380.2 1703.06  4652.8 1703.36  4773.6 1700.73  4787.9 1698.93  4794.5 1693.79
  4802.2 1691.17  4808.7 1688.64  4843.9 1689.08  4872.4 1687.13  4943.8 1684.77
  4952.4 1683.51  4972.3 1681.61  4986.6 1678.91  4990.2  1677.3  4992.9  1676.8
  4996.2  1677.3  5014.2 1679.24    5036  1689.2  5050.3 1699.22  5071.1 1717.89
  5078.8 1719.15  5135.1 1719.72  5190.4 1722.12  5195.5 1721.16    5305 1722.75
  5452.3 1720.64  5477.4 1721.41  5497.7 1719.88  5580.1 1720.63  5605.9 1721.11
#Mann= 6 ,-1 , 0
  4380.2     .05       0  4952.4     .16       0  4990.2     .07       0
  4996.2     .16       0  5452.3     .05       0  5580.1      .1       0
Bank Sta=4802.2,5036
XS Rating Curve= 0 ,0
Exp/Cntr=0.3,0.1

Type RM Length L Ch R = 1 ,37361   ,319,319,319
BEGIN DESCRIPTION:
BARONS CREEK 63.0
END DESCRIPTION:
XS GIS Cut Line= 3
      2754099.28     10067745.07      2753708.64     10067137.41
      2753196.48     10066929.07
#Sta/Elev= 30
  4572.4 1702.38  4732.8 1699.74    4748 1698.16  4844.5 1694.58  4862.9 1693.21
  4878.1 1688.01  4892.8 1685.71  4914.4 1683.51  4950.7 1682.65  4964.8 1681.23
    4999 1676.94  5001.7 1676.44    5005 1676.94  5023.4 1681.64  5050.5 1686.17
  5059.7 1689.57  5065.7 1691.37  5080.8 1699.37    5096 1702.36  5153.5 1705.63
  5168.4  1708.2  5174.6 1711.27  5205.4 1713.17  5234.6 1714.28  5304.7  1716.4
  5413.7 1718.44  5597.3 1719.36  5694.6 1718.69  5790.9 1720.78  5847.7 1720.55
#Mann= 9 ,-1 , 0
  4572.4     .05       0  4844.5     .16       0  4892.8      .1       0
  4964.8     .16       0    4999     .07       0    5005     .16       0
  5205.4      .1       0  5234.6     .16       0  5304.7     .05       0
Bank Sta=4878.1,5059.7
XS Rating Curve= 0 ,0
Exp/Cntr=0.3,0.1

Type RM Length L Ch R = 1 ,37042   ,542,542,542
BEGIN DESCRIPTION:
BARONS CREEK 62.0
END DESCRIPTION:
XS GIS Cut Line= 2
      2754342.34     10067623.55      2753951.69      10066868.3
#Sta/Elev= 30
  4614.3 1701.05  4625.4 1700.22  4647.9 1700.65  4749.2 1698.03  4794.2 1698.03
  4825.9 1695.15  4892.4 1692.54  4906.8 1688.83  4914.5 1685.42  4929.3 1682.57
  4951.9 1681.62  4986.6 1677.66  5000.1 1674.65  5002.8 1674.15  5006.1 1674.65
  5008.7 1675.69  5019.4 1676.77  5025.2 1680.44  5058.3 1684.94  5069.5 1686.55
  5075.7 1688.89  5098.2 1692.78  5130.3 1696.73  5135.9 1696.34  5158.1 1698.59
  5188.3  1707.5  5196.7 1708.65  5230.6 1709.09  5456.8 1709.82  5464.6 1710.01
#Mann= 6 ,-1 , 0
  4614.3     .05       0  5000.1     .04       0  5006.1     .05       0
  5058.3      .1       0  5230.6     .05       0  5456.8     .08       0
Bank Sta=4914.5,5069.5
XS Rating Curve= 0 ,0
Exp/Cntr=0.3,0.1

Type RM Length L Ch R = 1 ,36500   ,549,549,549
BEGIN DESCRIPTION:
BARONS CREEK 61.0
END DESCRIPTION:
XS GIS Cut Line= 2
      2754871.82       10067528.      2754438.32     10066617.64
#Sta/Elev= 30
  4540.7 1698.01  4600.8 1698.52    4623 1697.83  4742.7 1692.22  4748.3 1692.79
  4765.4 1691.05    4771 1691.57  4793.7 1690.52  4798.5 1689.65  4822.3 1687.29
  4899.9  1683.3  4966.3 1678.48  4980.9 1676.71  4988.5 1674.36  5000.6 1672.53
  5003.3 1672.03  5006.6 1672.53  5020.7 1676.97    5066 1683.75  5077.2 1686.36
  5094.4 1687.99  5099.9 1690.06  5110.3 1691.07  5117.1 1694.27  5122.6 1695.57
  5162.5 1703.16    5168 1704.11  5184.1 1704.29  5236.2 1705.26    5549 1705.64
#Mann= 5 ,-1 , 0
  4540.7     .05       0  4798.5     .16       0  5000.6     .07       0
  5006.6     .16       0  5184.1     .05       0
Bank Sta=4899.9,5066
XS Rating Curve= 0 ,0
Exp/Cntr=0.3,0.1

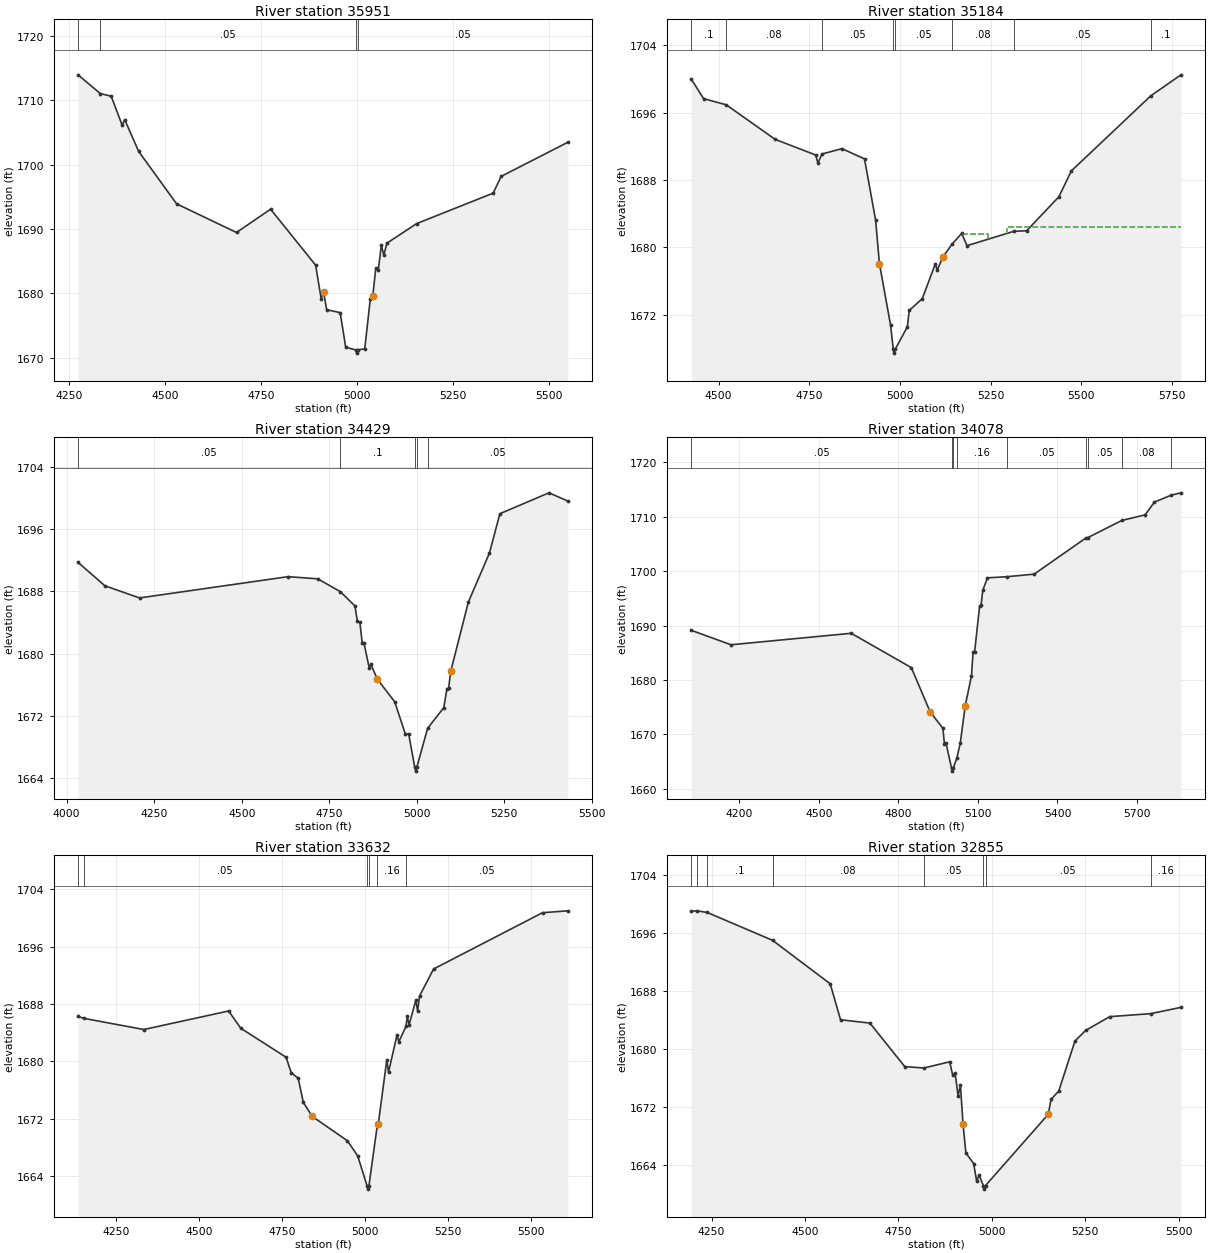
Type RM Length L Ch R = 1 ,35951   ,767,767,767
BEGIN DESCRIPTION:
BARONS CREEK 60.0
END DESCRIPTION:
XS GIS Cut Line= 3
      2755739.92      10067554.1      2755357.95     10067232.89
      2754872.67      10066626.3
#Sta/Elev= 30
  4272.3 1713.93  4330.2 1711.02  4358.7 1710.61  4387.3  1706.1  4393.9 1706.97
  4430.2 1702.05  4529.1  1693.9  4685.2 1689.45    4774 1693.07  4891.3 1684.38
  4905.7  1679.2  4912.1 1680.23  4920.1 1677.47  4955.3    1677  4969.7 1671.63
  4995.5 1671.22  4998.3 1670.72  5001.5 1671.22  5019.3 1671.39  5033.8 1679.15
  5040.2 1679.57  5048.2 1683.96  5054.6 1683.62  5062.6 1687.47    5069 1685.93
    5077 1687.79  5154.5 1690.83  5353.9 1695.56  5374.7 1698.16  5548.2 1703.45
#Mann= 4 ,-1 , 0
  4272.3     .08       0  4330.2     .05       0  4995.5     .04       0
  5001.5     .05       0
Bank Sta=4912.1,5040.2
XS Rating Curve= 0 ,0
Exp/Cntr=0.3,0.1

Type RM Length L Ch R = 1 ,35184   ,755,755,755
BEGIN DESCRIPTION:
BARONS CREEK 59.0
END DESCRIPTION:
XS GIS Cut Line= 2
      2756321.49     10066764.15      2755012.12     10066434.63
#Sta/Elev= 30
  4424.4 1700.02  4458.5 1697.68  4521.3 1696.94  4655.5 1692.84  4767.8 1690.97
  4773.7    1690  4784.8 1691.09    4840 1691.73  4902.2 1690.51  4932.8 1683.24
  4943.3 1678.06    4974 1670.75  4981.4 1667.91  4984.1 1667.41  4987.4 1667.91
  5020.3 1670.54  5025.6 1672.49  5061.5 1673.89  5097.4 1678.02  5102.6 1677.29
  5118.4 1678.84  5143.2 1680.35    5170 1681.65  5184.8 1680.19  5313.9  1681.9
  5349.2 1681.96  5438.1 1686.01  5472.6 1689.09  5691.7 1698.02  5774.6 1700.51
#Mann= 8 ,-1 , 0
  4424.4      .1       0  4521.3     .08       0  4784.8     .05       0
  4981.4     .04       0  4987.4     .05       0  5143.2     .08       0
  5313.9     .05       0  5691.7      .1       0
#XS Ineff= 2 ,-1
 5170.08 5243.65  1681.6  5293.8  5774.6 1682.37
Permanent Ineff=
       T       T
Bank Sta=4943.3,5118.4
XS Rating Curve= 0 ,0
Exp/Cntr=0.3,0.1

Type RM Length L Ch R = 1 ,34429   ,351,351,351
BEGIN DESCRIPTION:
BARONS CREEK 58.0
END DESCRIPTION:
XS GIS Cut Line= 3
      2756278.09     10066512.41      2755696.49     10065939.49
      2755114.86     10065913.45
#Sta/Elev= 30
  4032.4 1691.71    4109  1688.7    4208 1687.14  4632.3 1689.87  4717.1 1689.59
  4781.8 1687.94  4823.2 1686.11  4830.3 1684.12  4837.3 1684.02  4843.9 1681.39
  4848.8 1681.39  4863.8 1678.21  4868.8 1678.63  4886.9 1676.73  4936.9  1673.8
  4966.9 1669.71  4976.9 1669.64    4994 1665.41  4996.7 1664.91    5000 1665.41
  5030.7  1670.4    5077 1673.06  5085.7  1675.4  5090.7 1675.57  5097.1 1677.77
  5147.1  1686.6  5207.2 1692.88  5237.2 1697.95  5377.3 1700.63    5431 1699.58
#Mann= 5 ,-1 , 0
  4032.4     .05       0  4781.8      .1       0    4994     .07       0
    5000      .1       0  5030.7     .05       0
Bank Sta=4886.9,5097.1
XS Rating Curve= 0 ,0
Exp/Cntr=0.3,0.1

Type RM Length L Ch R = 1 ,34078   ,446,446,446
BEGIN DESCRIPTION:
BARONS CREEK 57.0
END DESCRIPTION:
XS GIS Cut Line= 3
       2756321.5     10066442.98      2755722.53     10065765.88
      2755375.31     10064889.14
#Sta/Elev= 30
  4018.7 1689.13  4168.9 1686.47  4622.3 1688.58    4849 1682.27  4920.1 1674.11
    4968 1671.12  4973.9 1668.18  4979.3  1668.5  5000.7 1663.75  5003.4 1663.25
  5006.7 1663.75  5020.3 1665.62  5033.4 1668.36  5052.3 1675.28  5075.6 1680.73
    5082 1685.21  5087.4 1685.07  5106.4 1693.54  5111.8 1693.75  5118.6 1696.52
  5136.1 1698.77  5211.1 1698.98  5312.2 1699.45  5506.6 1706.07  5514.9 1706.17
  5643.1 1709.32  5730.6 1710.34  5765.7 1712.68  5829.5 1713.97  5865.7 1714.39
#Mann= 9 ,-1 , 0
  4018.7     .05       0  5000.7    .035       0  5006.7     .05       0
  5020.3     .16       0  5211.1     .05       0  5506.6     .08       0
  5514.9     .05       0  5643.1     .08       0  5829.5     .05       0
Bank Sta=4920.1,5052.3
XS Rating Curve= 0 ,0
Exp/Cntr=0.3,0.1

Type RM Length L Ch R = 1 ,33632   ,777,777,777
BEGIN DESCRIPTION:
BARONS CREEK 56.0
END DESCRIPTION:
XS GIS Cut Line= 3
      2756555.88     10066321.46      2756147.88     10065670.39
      2755913.52     10065002.03
#Sta/Elev= 30
  4134.5 1686.27  4151.3 1686.01  4332.8 1684.45  4588.6 1687.03  4625.1 1684.63
  4761.8 1680.59  4777.2 1678.45  4798.4 1677.65  4813.7 1674.31  4840.8 1672.34
  4946.7 1668.96  4977.7 1666.85  5005.7 1662.72  5008.5 1662.22  5011.7 1662.72
  5036.9 1671.13  5039.7 1671.23  5065.4 1680.19  5070.7 1678.51  5096.4 1683.71
  5101.7 1682.73  5123.4 1684.89  5127.4 1686.28  5132.7 1685.11  5153.1 1688.53
  5158.4 1687.01  5164.2 1689.12  5206.6 1692.88  5535.1 1700.72  5611.1 1700.98
#Mann= 6 ,-1 , 0
  4134.5     .08       0  4151.3     .05       0  5005.7     .04       0
  5011.7     .05       0  5036.9     .16       0  5123.4     .05       0
Bank Sta=4840.8,5039.7
XS Rating Curve= 0 ,0
Exp/Cntr=0.3,0.1

Type RM Length L Ch R = 1 ,32855   ,287,287,287
BEGIN DESCRIPTION:
BARONS CREEK 55.0
END DESCRIPTION:
XS GIS Cut Line= 2
      2757337.13     10066416.94      2756529.85     10065383.97
#Sta/Elev= 30
  4195.4 1699.02  4210.9 1699.08  4238.5 1698.85  4413.2 1695.01  4567.5 1689.01
  4595.2 1684.05  4673.8 1683.59    4767 1677.59  4818.1 1677.39  4887.3 1678.25
  4895.4 1676.42  4901.8 1676.72  4909.9 1673.57  4916.2 1675.02  4922.9 1669.73
  4930.7 1665.68  4951.5 1664.21  4959.6 1661.76    4966 1662.63  4977.4 1661.18
  4980.2 1660.68  4983.4 1661.18  5151.3 1671.01  5158.6 1673.05  5179.4 1674.23
  5222.8 1681.12  5251.7 1682.59  5315.9 1684.48  5425.3 1684.89  5506.4 1685.76
#Mann= 8 ,-1 , 0
  4195.4     .15       0  4210.9     .08       0  4238.5      .1       0
  4413.2     .08       0  4818.1     .05       0  4977.4     .04       0
  4983.4     .05       0  5425.3     .16       0
Bank Sta=4922.9,5151.3
XS Rating Curve= 0 ,0
Exp/Cntr=0.3,0.1

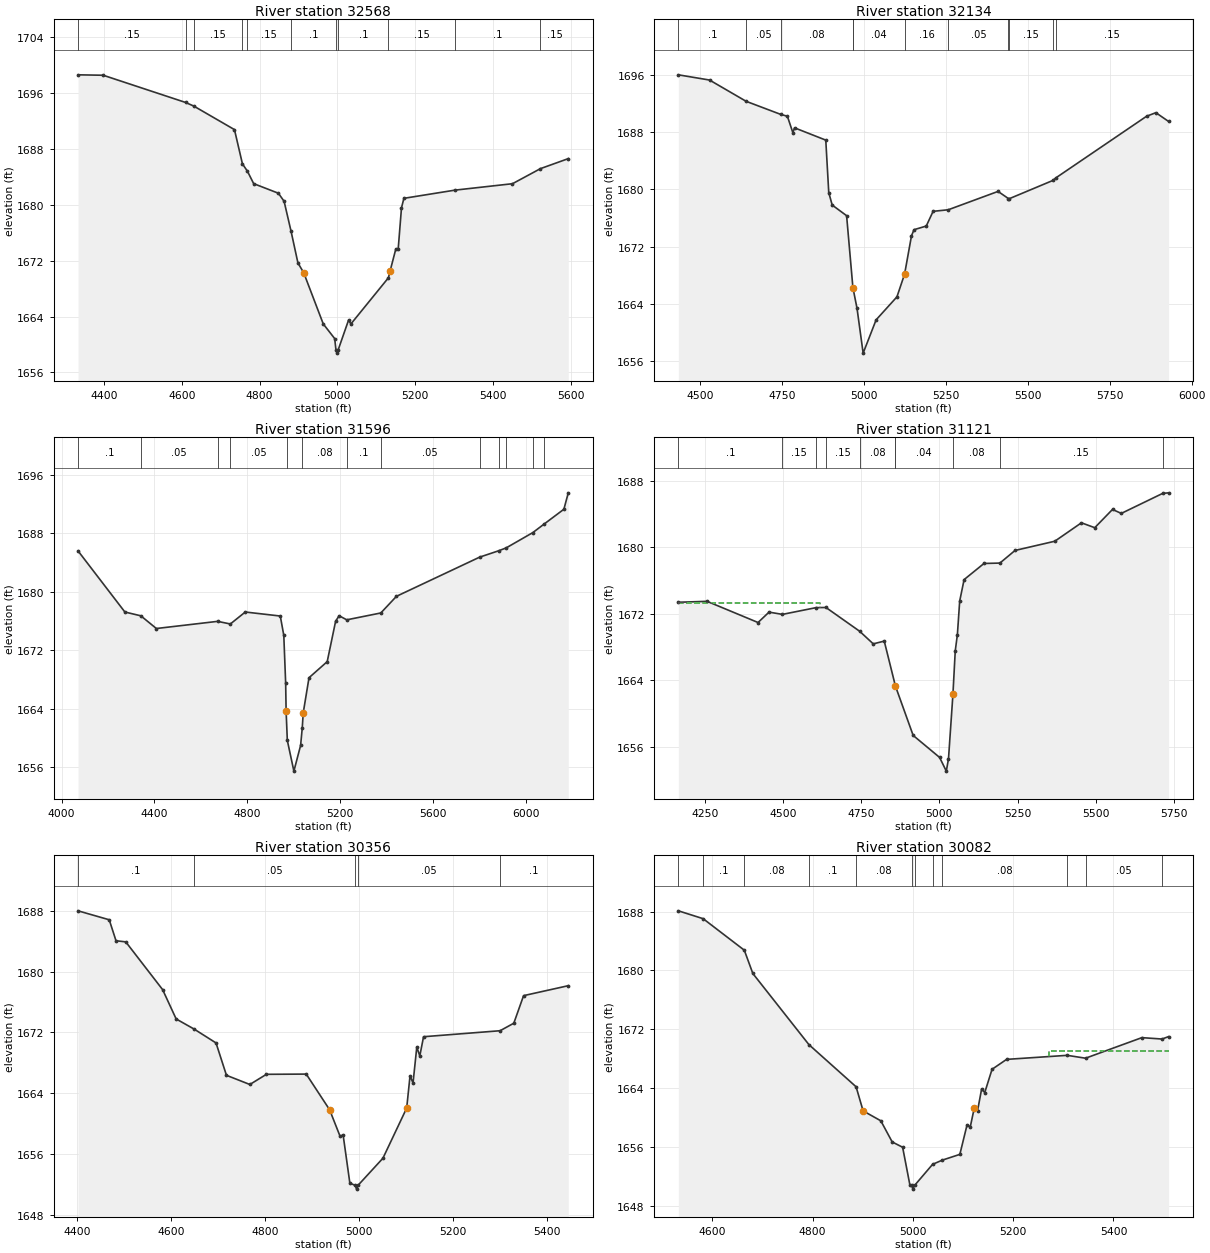
Type RM Length L Ch R = 1 ,32568   ,434,434,434
BEGIN DESCRIPTION:
BARONS CREEK 54.0
END DESCRIPTION:
XS GIS Cut Line= 2
      2757502.07     10066330.15      2756765.27      10065307.3
#Sta/Elev= 30
  4333.4 1698.59  4398.1 1698.53  4609.7 1694.64    4631 1694.12  4735.6 1690.75
  4756.1 1685.85  4768.9  1684.8    4785 1683.02  4848.5 1681.65  4863.2  1680.5
  4881.2 1676.19  4898.8 1671.67  4913.6 1670.28  4963.9 1662.95  4993.3 1660.85
  4996.5 1659.27  4999.2 1658.77  5002.5 1659.27  5028.9 1663.48  5035.1 1662.95
  5131.5 1669.55  5135.7  1670.5  5150.4 1673.65  5156.6 1673.65  5165.1 1679.57
  5171.3 1680.92  5302.4 1682.09  5450.5 1683.01  5522.5 1685.17    5594  1686.6
#Mann= 11 ,-1 , 0
  4333.4     .15       0  4609.7      .1       0    4631     .15       0
  4756.1      .1       0  4768.9     .15       0  4881.2      .1       0
  4996.5     .07       0  5002.5      .1       0  5131.5     .15       0
  5302.4      .1       0  5522.5     .15       0
Bank Sta=4913.6,5135.7
XS Rating Curve= 0 ,0
Exp/Cntr=0.3,0.1

Type RM Length L Ch R = 1 ,32134   ,538,538,538
BEGIN DESCRIPTION:
BARONS CREEK 53.0
END DESCRIPTION:
XS GIS Cut Line= 3
      2757693.01      10066199.9      2757467.32     10065514.14
      2756955.17     10064932.54
#Sta/Elev= 30
  4432.7 1696.05  4527.9 1695.32  4639.7 1692.34  4744.7 1690.52  4765.6 1690.25
  4782.2 1687.96  4787.5 1688.63  4882.8 1686.91  4891.9 1679.56  4902.4 1677.82
  4946.4 1676.33  4965.6 1666.27  4978.2 1663.36  4996.9 1657.09  5036.5 1661.75
  5100.1 1664.97  5123.5 1668.16  5144.5 1673.51  5152.2 1674.37  5189.6 1674.88
  5210.5 1676.94  5256.8 1677.16  5408.8 1679.73  5440.4 1678.73  5442.6  1678.7
  5576.6 1681.27  5584.9 1681.61  5862.3 1690.25  5890.7 1690.75  5929.6 1689.52
#Mann= 11 ,-1 , 0
  4432.7      .1       0  4639.7     .05       0  4744.7     .08       0
  4965.6     .05       0  4965.6     .04       0  5123.5     .16       0
  5256.8     .05       0  5440.4      .1       0  5442.6     .15       0
  5576.6      .1       0  5584.9     .15       0
Bank Sta=4965.6,5123.5
XS Rating Curve= 0 ,0
Exp/Cntr=0.3,0.1

Type RM Length L Ch R = 1 ,31596   ,475,475,475
BEGIN DESCRIPTION:
BARONS CREEK 52.0
END DESCRIPTION:
XS GIS Cut Line= 2
      2758647.91     10065791.94      2756878.03     10064638.05
#Sta/Elev= 30
    4071  1685.6  4272.8 1677.23  4341.5 1676.71  4408.5 1674.97  4672.6 1675.95
  4727.3 1675.59  4791.8 1677.23  4942.6 1676.68  4957.7 1674.03  4965.7 1667.52
 4967.74 1663.61  4972.9 1659.64  5001.2 1655.43  5030.2 1658.96  5037.3 1661.37
 5041.47 1663.42  5066.4 1668.23  5144.8 1670.43    5181 1675.96  5196.1 1676.72
  5229.1 1676.16  5375.9  1677.1  5443.2 1679.38  5801.9 1684.75  5884.6 1685.63
  5916.4 1686.02  6030.9 1688.11  6077.5 1689.23  6164.8 1691.31  6183.8 1693.56
#Mann= 13 ,-1 , 0
    4071      .1       0  4341.5     .05       0  4672.6     .08       0
  4727.3     .05       0  4972.9     .05       0  5037.3     .08       0
  5229.1      .1       0  5375.9     .05       0  5801.9      .1       0
  5884.6     .05       0  5916.4      .1       0  6030.9     .15       0
  6077.5      .1       0
Bank Sta=4967.74,5041.47
XS Rating Curve= 0 ,0
Exp/Cntr=0.3,0.1

Type RM Length L Ch R = 1 ,31121   ,765,765,765
BEGIN DESCRIPTION:
BARONS CREEK 51.0
END DESCRIPTION:
XS GIS Cut Line= 2
      2758665.21     10065496.75      2757606.22     10064342.28
#Sta/Elev= 30
  4165.9 1673.38  4257.7 1673.49  4420.5 1670.94  4455.6 1672.19  4498.5 1671.92
  4605.7 1672.73  4637.5 1672.75  4745.1 1669.89  4788.6 1668.37  4823.8  1668.7
  4859.5 1663.29  4916.2 1657.34  5000.7 1654.69  5022.1 1653.04  5029.1 1654.52
  5043.3  1662.3  5050.7 1667.53  5057.5 1669.47  5064.9 1673.53    5079 1676.11
  5142.5 1678.05  5193.4  1678.1  5241.8 1679.62  5368.8 1680.73  5453.9 1682.95
  5496.5 1682.36  5553.2 1684.56  5581.3 1684.08  5713.4 1686.49  5732.5 1686.56
#Mann= 10 ,-1 , 0
  4165.9      .1       0  4498.5     .15       0  4605.7     .08       0
  4637.5     .15       0  4745.1     .08       0  4859.5     .05       0
  4859.5     .04       0  5043.3     .08       0  5193.4     .15       0
  5713.4     .05       0
#XS Ineff= 2 , 0
         4617.73 1673.23
Permanent Ineff=
       T       T
Bank Sta=4859.5,5043.3
XS Rating Curve= 0 ,0
Exp/Cntr=0.3,0.1

Type RM Length L Ch R = 1 ,30356   ,274,274,274
BEGIN DESCRIPTION:
BARONS CREEK 50.0
END DESCRIPTION:
XS GIS Cut Line= 2
      2759194.77     10065470.76      2758543.71     10064654.77
#Sta/Elev= 30
    4402 1688.02  4468.4 1686.84  4482.8 1684.08  4503.6 1683.93  4582.1 1677.64
  4610.9 1673.78  4649.1 1672.45  4695.8 1670.62    4718 1666.36  4767.8 1665.15
  4803.1 1666.49  4887.9 1666.52  4937.6 1661.83    4960 1658.32  4966.4 1658.52
  4980.8 1652.15  4992.2 1651.87    4995 1651.37  4998.2 1651.87  5051.2 1655.44
  5101.8 1662.05  5108.9 1666.28  5115.3 1665.35  5123.3 1670.08  5129.7 1668.91
  5137.7 1671.44  5300.7 1672.23  5329.9 1673.22  5350.7 1676.85  5445.9 1678.16
#Mann= 5 ,-1 , 0
    4402      .1       0  4649.1     .05       0  4992.2     .04       0
  4998.2     .05       0  5300.7      .1       0
Bank Sta=4937.6,5101.8
XS Rating Curve= 0 ,0
Exp/Cntr=0.3,0.1

Type RM Length L Ch R = 1 ,30082   ,791,791,791
BEGIN DESCRIPTION:
BARONS CREEK 49.0
END DESCRIPTION:
XS GIS Cut Line= 2
      2759377.07     10065392.66      2758778.09     10064620.05
#Sta/Elev= 30
  4532.4 1688.11  4581.8 1687.04  4663.9 1682.75  4680.9 1679.58  4792.7  1669.9
  4886.8 1664.16  4900.8 1660.88  4936.1 1659.53  4958.8 1656.65  4979.6 1655.93
  4994.1 1650.79  4997.4 1650.73  5000.2 1650.23  5003.4 1650.73  5039.3  1653.6
  5058.4 1654.17  5093.7 1654.96  5108.1 1658.98  5114.5  1658.7  5122.6 1661.32
    5129  1660.9  5137.1 1663.85  5143.4 1663.38  5157.9 1666.54  5186.9 1667.89
  5307.8 1668.44  5344.3 1668.05  5456.7 1670.85  5496.8 1670.66    5510 1670.99
#Mann= 12 ,-1 , 0
  4532.4     .15       0  4581.8      .1       0  4663.9     .08       0
  4792.7      .1       0  4886.8     .08       0  4997.4     .07       0
  5003.4     .08       0  5039.3     .05       0  5058.4     .08       0
  5307.8      .1       0  5344.3     .05       0  5496.8      .1       0
#XS Ineff= 2 , 0
                         5272.05         1668.97
Permanent Ineff=
       T       T
Bank Sta=4900.8,5122.6
XS Rating Curve= 0 ,0
Exp/Cntr=0.3,0.1

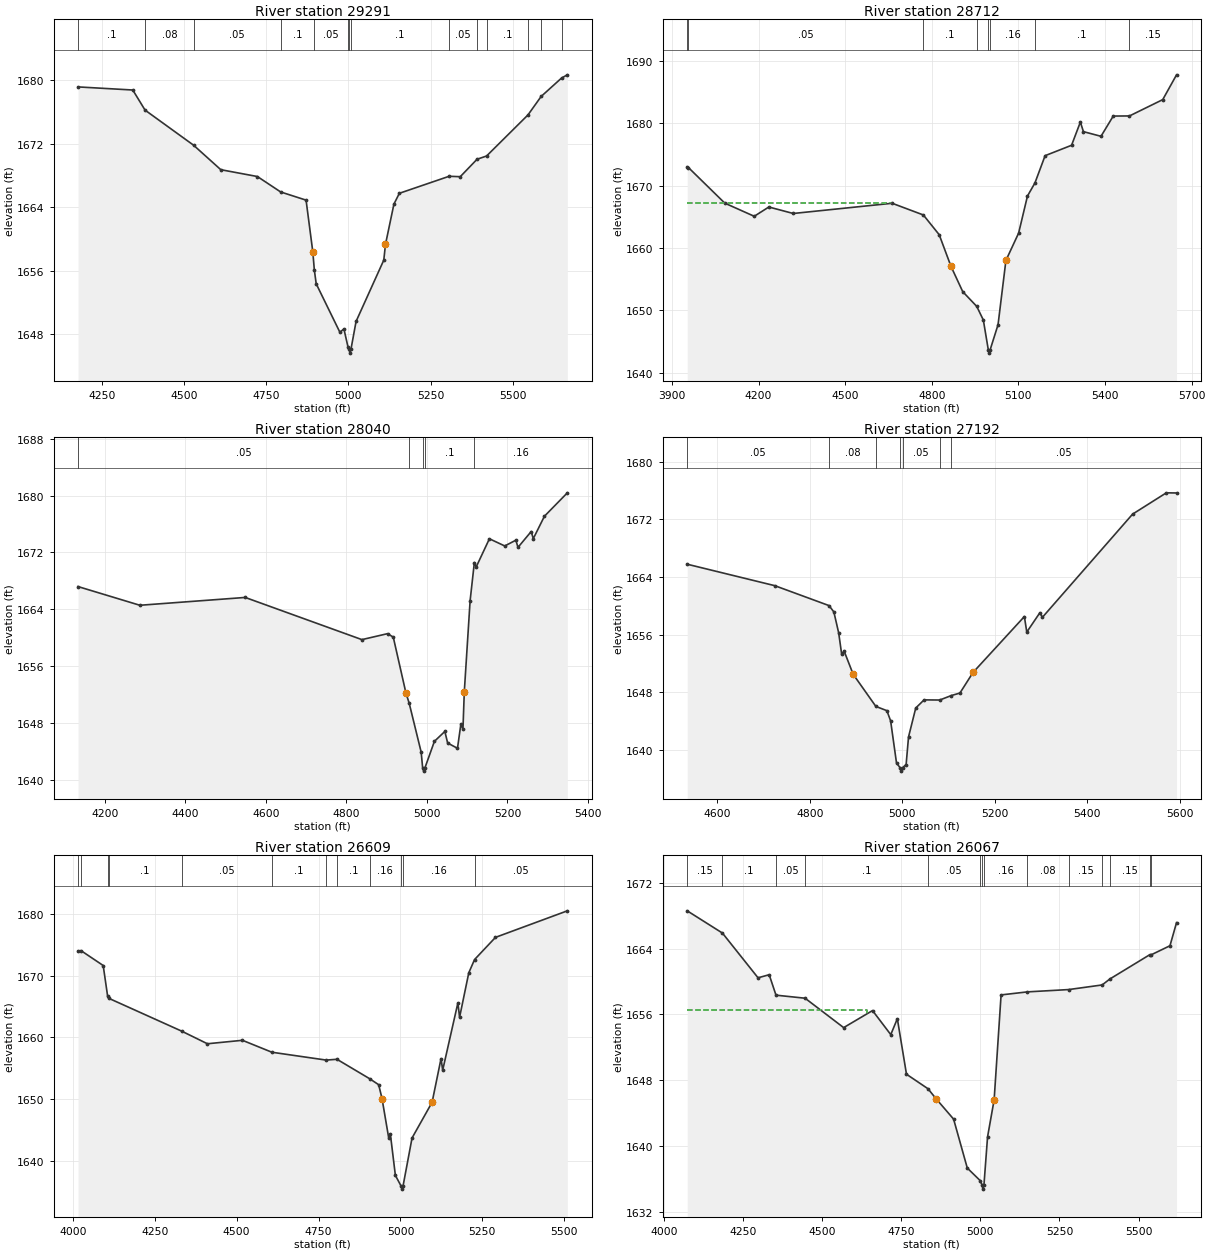
Type RM Length L Ch R = 1 ,29291   ,579,579,579
BEGIN DESCRIPTION:
BARONS CREEK 48.0
END DESCRIPTION:
XS GIS Cut Line= 4
      2759917.77     10064736.14      2759516.86     10064473.18
      2758883.12     10064624.07      2758582.41     10064430.76
#Sta/Elev= 30
  4177.7 1679.13  4344.3 1678.74  4381.7 1676.21  4529.2  1671.8    4612 1668.72
  4723.3 1667.86  4794.1 1665.92  4871.4 1664.89  4891.9 1658.38  4896.5 1656.12
  4902.2 1654.37  4974.2 1648.28  4986.5 1648.69    4999 1646.41    5002 1646.15
  5004.8 1645.65    5008 1646.15  5023.5 1649.64  5107.8 1657.35  5112.9 1659.32
  5138.6 1664.39  5155.1 1665.75  5306.5 1667.89  5340.4 1667.84  5391.4 1670.03
  5420.4 1670.44  5546.4 1675.61  5586.4 1677.93  5648.6 1680.25  5666.1 1680.65
#Mann= 14 ,-1 , 0
  4177.7      .1       0  4381.7     .08       0  4529.2     .05       0
  4794.1      .1       0  4896.5     .05       0    4999      .1       0
    5002     .07       0    5008      .1       0  5306.5     .05       0
  5391.4     .16       0  5420.4      .1       0  5546.4     .15       0
  5586.4      .1       0  5648.6     .15       0
Bank Sta=4891.9,5112.9
XS Rating Curve= 0 ,0
Exp/Cntr=0.3,0.1

Type RM Length L Ch R = 1 ,28712   ,672,672,672
BEGIN DESCRIPTION:
BARONS CREEK 47.0
END DESCRIPTION:
XS GIS Cut Line= 3
      2759883.35     10064430.09      2759542.73     10064201.57
      2758281.54     10063956.22
#Sta/Elev= 30
  3952.7 1673.03    3957 1672.92  4082.9 1667.21  4184.9  1665.1  4235.5 1666.59
    4320 1665.55  4662.6 1667.19  4770.7 1665.31  4825.6 1662.14  4866.4 1657.06
  4907.1    1653  4955.7 1650.63  4978.5 1648.44  4995.8 1643.63  4998.6 1643.13
  5001.8 1643.63  5029.4 1647.69  5056.7 1658.01  5100.7  1662.4  5131.3 1668.35
  5157.2 1670.45  5192.4 1674.83  5284.1  1676.5  5314.6 1680.23  5325.1 1678.69
    5386 1677.94  5428.4 1681.19  5484.7 1681.21  5599.9 1683.83  5647.7 1687.81
#Mann= 8 ,-1 , 0
  3952.7     .08       0    3957     .05       0  4770.7      .1       0
  4955.7     .16       0  4995.8     .07       0  5001.8     .16       0
  5157.2      .1       0  5484.7     .15       0
#XS Ineff= 2 , 0
         4661.36 1667.28
Permanent Ineff=
       T       T
Bank Sta=4866.4,5056.7
XS Rating Curve= 0 ,0
Exp/Cntr=0.3,0.1

Type RM Length L Ch R = 1 ,28040   ,848,848,848
BEGIN DESCRIPTION:
BARONS CREEK 46.0
END DESCRIPTION:
XS GIS Cut Line= 3
      2759871.86     10064307.57      2759298.92     10063751.99
      2759177.38     10063352.65
#Sta/Elev= 30
  4133.4  1667.2  4287.1 1664.57  4548.7 1665.67  4838.6 1659.74  4902.4 1660.58
  4916.5 1660.09  4947.8 1652.28  4956.2 1650.76  4985.8 1643.92  4989.4 1641.75
  4992.1 1641.25  4995.4 1641.75  5018.7 1645.44  5044.6 1646.83  5051.6  1645.2
    5076 1644.46  5084.4 1647.85  5089.6 1647.15  5092.9 1652.38  5107.4 1665.23
  5117.9 1670.58  5122.5 1669.96  5155.3 1673.92  5193.4 1672.91    5221 1673.72
  5226.3 1672.71  5259.1 1674.94  5264.3 1673.94    5292 1677.09  5348.9 1680.38
#Mann= 5 ,-1 , 0
  4133.4     .05       0  4956.2      .1       0  4989.4     .07       0
  4995.4      .1       0  5117.9     .16       0
Bank Sta=4947.8,5092.9
XS Rating Curve= 0 ,0
Exp/Cntr=0.3,0.1

Type RM Length L Ch R = 1 ,27192   ,542,542,542
BEGIN DESCRIPTION:
BARONS CREEK 45.0
END DESCRIPTION:
XS GIS Cut Line= 2
      2759949.95     10064238.15       2760245.1     10063222.47
#Sta/Elev= 30
    4535 1665.77  4724.3 1662.79  4841.6 1660.02    4852 1659.14  4862.4 1656.23
  4868.9 1653.25  4874.1 1653.71  4893.7 1650.48  4942.8 1646.01  4966.6 1645.42
  4974.7    1644  4987.4 1638.16  4994.8 1637.52  4997.6 1637.02  5000.8 1637.52
  5008.2 1637.94  5013.4 1641.77    5029 1645.79    5047 1646.92  5080.8  1646.9
  5105.8 1647.52  5124.5 1647.87  5152.8 1650.73  5263.8  1658.5    5269 1656.34
  5297.4 1659.04  5302.6 1658.38  5497.7 1672.73  5570.6 1675.69  5592.7 1675.67
#Mann= 7 ,-1 , 0
    4535     .05       0  4841.6     .08       0  4942.8     .05       0
  4994.8     .04       0  5000.8     .05       0  5080.8      .1       0
  5105.8     .05       0
Bank Sta=4893.7,5152.8
XS Rating Curve= 0 ,0
Exp/Cntr=0.3,0.1

Type RM Length L Ch R = 1 ,26609   ,542,542,542
BEGIN DESCRIPTION:
BARONS CREEK 44.0
END DESCRIPTION:
XS GIS Cut Line= 3
      2760203.77     10064607.84      2760556.45     10064255.16
      2760746.94     10063278.43
#Sta/Elev= 30
  4015.6 1673.99  4024.9 1674.03  4092.5 1671.63    4106 1666.68  4109.5 1666.33
  4332.1 1661.02  4410.7 1658.98  4517.6 1659.54  4607.5 1657.61  4773.3 1656.34
  4806.2 1656.47  4905.6 1653.34  4933.5 1652.36  4943.7 1650.13    4964  1643.8
  4969.1 1644.41  4984.5  1637.7  5001.9 1635.98  5004.6 1635.48  5007.9 1635.98
  5035.4 1643.75  5096.6 1649.52  5123.9 1656.58  5128.9 1654.71  5175.4  1665.6
  5180.5 1663.26  5208.6 1670.45  5226.2 1672.59  5290.1 1676.18  5509.5 1680.47
#Mann= 12 ,-1 , 0
  4015.6      .1       0  4024.9     .15       0    4106     .08       0
  4109.5      .1       0  4332.1     .05       0  4607.5      .1       0
  4773.3     .05       0  4806.2      .1       0  4905.6     .16       0
  5001.9     .07       0  5007.9     .16       0  5226.2     .05       0
Bank Sta=4943.7,5096.6
XS Rating Curve= 0 ,0
Exp/Cntr=0.3,0.1

Type RM Length L Ch R = 1 ,26067   ,340,340,340
BEGIN DESCRIPTION:
BARONS CREEK 43.0
END DESCRIPTION:
XS GIS Cut Line= 2
       2760340.6     10064620.03      2761553.29     10063658.55
#Sta/Elev= 30
  4072.7 1668.58  4184.1 1665.88  4296.7 1660.45    4332 1660.82  4353.5 1658.34
  4445.5 1657.97  4567.5  1654.4  4658.8 1656.47  4716.5 1653.55  4737.3 1655.48
  4766.2 1648.74  4834.2 1646.98  4859.2 1645.79  4915.2 1643.29  4958.5 1637.35
  4999.1 1635.83  5005.2 1635.29  5007.9 1634.79  5011.2 1635.29  5022.6 1641.13
  5043.4 1645.63  5065.4 1658.37  5148.9 1658.74  5279.3 1659.02    5385 1659.58
  5409.7 1660.31  5535.1 1663.24  5540.1 1663.24  5599.5 1664.34  5620.3 1667.15
#Mann= 14 ,-1 , 0
  4072.7     .15       0  4184.1      .1       0  4353.5     .05       0
  4445.5      .1       0  4834.2     .05       0  4999.1     .16       0
  5005.2     .07       0  5011.2     .16       0  5148.9     .08       0
  5279.3     .15       0    5385     .08       0  5409.7     .15       0
  5535.1     .08       0  5540.1     .15       0
#XS Ineff= 2 , 0
         4642.27 1656.58
Permanent Ineff=
       T       T
Bank Sta=4859.2,5043.4
XS Rating Curve= 0 ,0
Exp/Cntr=0.3,0.1

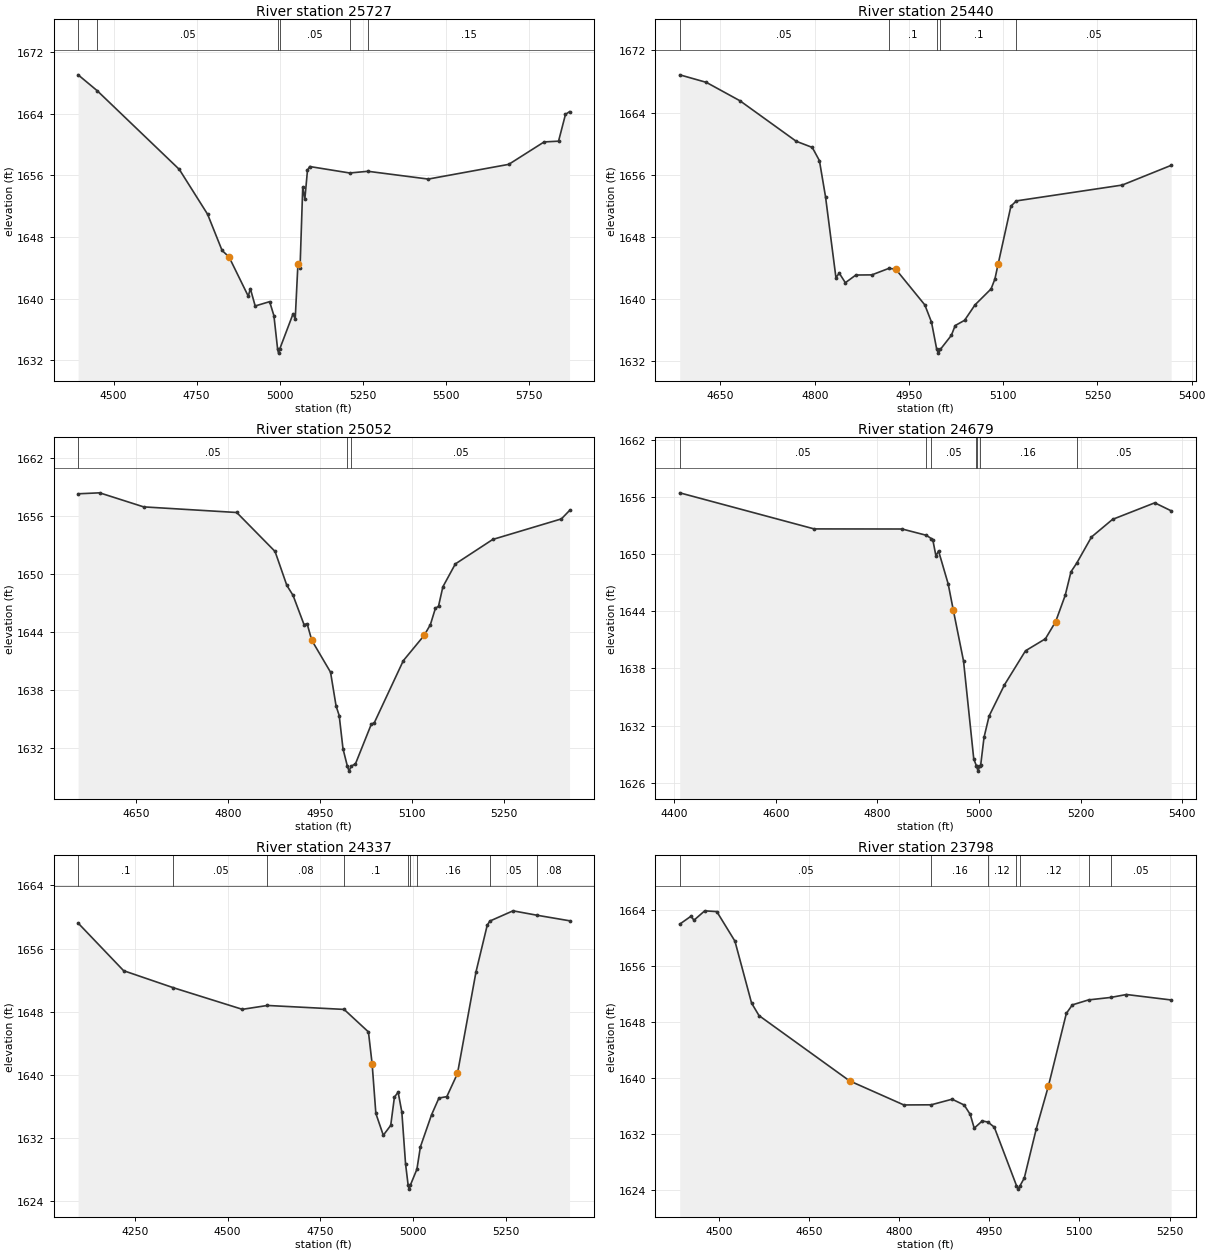
Type RM Length L Ch R = 1 ,25727   ,287,287,287
BEGIN DESCRIPTION:
BARONS CREEK 42.0
END DESCRIPTION:
XS GIS Cut Line= 2
      2760531.52     10064724.24      2761703.41     10063821.46
#Sta/Elev= 30
  4393.3 1669.04  4450.2    1667    4698 1656.76  4783.1 1650.94  4826.7 1646.24
  4847.5 1645.41  4905.5 1640.31  4911.8 1641.29  4926.3 1639.04  4969.8  1639.6
  4982.7 1637.78  4993.9 1633.42  4996.7 1632.92  4999.9 1633.42  5040.5 1638.04
  5046.8 1637.32    5055  1644.5  5061.3 1643.91  5069.5 1654.51  5075.8 1652.91
  5083.7 1656.64  5090.3 1657.14  5210.8  1656.3  5265.7 1656.52  5447.3 1655.51
  5689.6 1657.42    5796 1660.33  5839.5 1660.43  5860.4 1663.91  5872.6 1664.26
#Mann= 6 ,-1 , 0
  4393.3     .15       0  4450.2     .05       0  4993.9     .04       0
  4999.9     .05       0  5210.8     .08       0  5265.7     .15       0
Bank Sta=4847.5,5055
XS Rating Curve= 0 ,0
Exp/Cntr=0.3,0.1

Type RM Length L Ch R = 1 ,25440   ,388,388,388
BEGIN DESCRIPTION:
Mapping XS 4b7a4af3
END DESCRIPTION:
XS GIS Cut Line= 3
      2760618.37     10064767.61      2761165.24     10064585.33
       2761347.5     10064489.85
#Sta/Elev= 30
  4585.2 1668.86  4627.5 1667.89    4681 1665.52  4770.6  1660.3  4796.1 1659.51
  4807.5 1657.81  4817.2 1653.17  4833.8 1642.74  4839.1 1643.31  4848.8 1642.08
  4865.5 1643.07    4891 1643.09  4917.8 1643.92  4928.7 1643.85  4975.3 1639.22
  4985.9 1637.01  4994.2 1633.51    4997 1633.01  5000.2 1633.51  5017.5  1635.3
  5023.6 1636.56  5038.6 1637.24  5055.2 1639.23  5080.7 1641.28  5086.8 1642.55
  5092.1 1644.53  5112.3 1651.94    5121 1652.62  5289.5 1654.66  5367.4  1657.2
#Mann= 5 ,-1 , 0
  4585.2     .05       0  4917.8      .1       0  4994.2     .07       0
  5000.2      .1       0    5121     .05       0
Bank Sta=4928.7,5092.1
XS Rating Curve= 0 ,0
Exp/Cntr=0.3,0.1

Type RM Length L Ch R = 1 ,25052   ,373,373,373
BEGIN DESCRIPTION:
BARONS CREEK 41.0
END DESCRIPTION:
XS GIS Cut Line= 2
      2761194.43      10065288.2       2761343.6     10064500.71
#Sta/Elev= 30
    4555 1658.26  4590.1 1658.36  4661.9 1656.91  4813.7 1656.33  4876.2 1652.31
  4895.4 1648.81  4905.6 1647.77  4923.4 1644.77  4928.5 1644.85  4936.1 1643.14
  4966.7 1639.85  4975.7 1636.37  4980.8 1635.38    4987 1631.95  4994.2 1630.14
  4996.9 1629.64  5000.2 1630.14  5007.4  1630.4  5033.1 1634.47  5038.2 1634.65
  5085.4 1641.04  5119.3 1643.64  5129.5 1644.75  5137.7 1646.44  5142.8 1646.66
  5149.9 1648.66  5170.2 1651.02  5231.3 1653.55  5343.2 1655.67  5356.5 1656.54
#Mann= 3 ,-1 , 0
    4555     .05       0  4994.2    .035       0  5000.2     .05       0
Bank Sta=4936.1,5119.3
XS Rating Curve= 0 ,0
Exp/Cntr=0.3,0.1

Type RM Length L Ch R = 1 ,24679   ,342,342,342
BEGIN DESCRIPTION:
Mapping XS a245c2db
END DESCRIPTION:
XS GIS Cut Line= 3
      2761392.32     10065413.24      2761624.98     10065048.63
       2761687.4     10064518.01
#Sta/Elev= 30
  4411.1 1656.45  4675.5 1652.66  4848.6 1652.65  4896.3 1651.99  4905.8 1651.65
    4909  1651.5  4915.1 1649.82  4920.2 1650.35  4939.2 1646.88  4949.2 1644.15
  4969.4 1638.78  4989.5  1628.5  4994.8 1627.77  4995.2 1627.72  4997.9 1627.22
  5001.2 1627.72  5003.2 1627.88  5009.7 1630.76  5019.7 1633.01  5049.9 1636.28
  5091.3 1639.86  5130.5 1641.12  5150.6 1642.92  5169.4 1645.68  5180.8 1648.16
  5191.9 1649.05  5221.1 1651.81  5262.5 1653.66  5345.6  1655.4  5377.9 1654.56
#Mann= 7 ,-1 , 0
  4411.1     .05       0  4896.3      .1       0  4905.8     .05       0
  4994.8     .16       0  4995.2     .07       0  5001.2     .16       0
  5191.9     .05       0
Bank Sta=4949.2,5150.6
XS Rating Curve= 0 ,0
Exp/Cntr=0.3,0.1

Type RM Length L Ch R = 1 ,24337   ,539,539,539
BEGIN DESCRIPTION:
BARONS CREEK 40.0
END DESCRIPTION:
XS GIS Cut Line= 3
      2761937.48     10065826.41      2761989.56     10064704.88
      2762111.08     10064541.69
#Sta/Elev= 30
  4096.4 1659.24  4219.2 1653.21  4353.8 1651.05  4539.6 1648.32  4607.3 1648.81
  4814.2 1648.31  4879.9 1645.46  4889.9 1641.39  4899.9 1635.14    4920 1632.38
    4940 1633.63    4950  1637.2    4960 1637.84    4970 1635.33    4980 1628.78
    4987 1626.06  4989.8 1625.56    4993 1626.06  5010.7 1628.08  5020.1 1630.91
  5050.1 1634.96  5070.1 1637.09  5091.4 1637.27  5120.2  1640.2  5170.2 1653.07
  5200.3 1658.94  5207.3 1659.49  5270.1 1660.79    5335 1660.23  5422.6 1659.53
#Mann= 9 ,-1 , 0
  4096.4      .1       0  4353.8     .05       0  4607.3     .08       0
  4814.2      .1       0    4987     .07       0    4993      .1       0
  5010.7     .16       0  5207.3     .05       0    5335     .08       0
Bank Sta=4889.9,5120.2
XS Rating Curve= 0 ,0
Exp/Cntr=0.3,0.1

Type RM Length L Ch R = 1 ,23798   ,445,445,445
BEGIN DESCRIPTION:
BARONS CREEK 39.0
END DESCRIPTION:
XS GIS Cut Line= 3
      2762555.53     10065545.14      2762506.92     10065055.57
      2762513.87     10064729.22
#Sta/Elev= 30
  4434.4 1661.97  4453.1  1663.1  4458.1 1662.53    4476 1663.87  4496.1 1663.76
  4526.3 1659.54    4554  1650.7  4566.4 1648.91  4717.2 1639.59  4807.6 1636.15
  4853.1 1636.17    4888 1636.97  4908.1 1636.14  4918.2 1634.79  4924.8 1632.83
  4938.2 1633.87  4947.7  1633.7  4958.2 1632.98  4995.2 1624.63    4998 1624.13
  5001.2 1624.63  5008.2 1625.72  5028.2 1632.76  5048.2  1638.8  5078.2 1649.22
  5088.2 1650.44  5115.2 1651.15    5152  1651.5  5178.3 1651.92  5252.8 1651.14
#Mann= 7 ,-1 , 0
  4434.4     .05       0  4853.1     .16       0  4947.7     .12       0
  4995.2     .07       0  5001.2     .12       0  5115.2     .16       0
    5152     .05       0
Bank Sta=4717.2,5048.2
XS Rating Curve= 0 ,0
Exp/Cntr=0.3,0.1