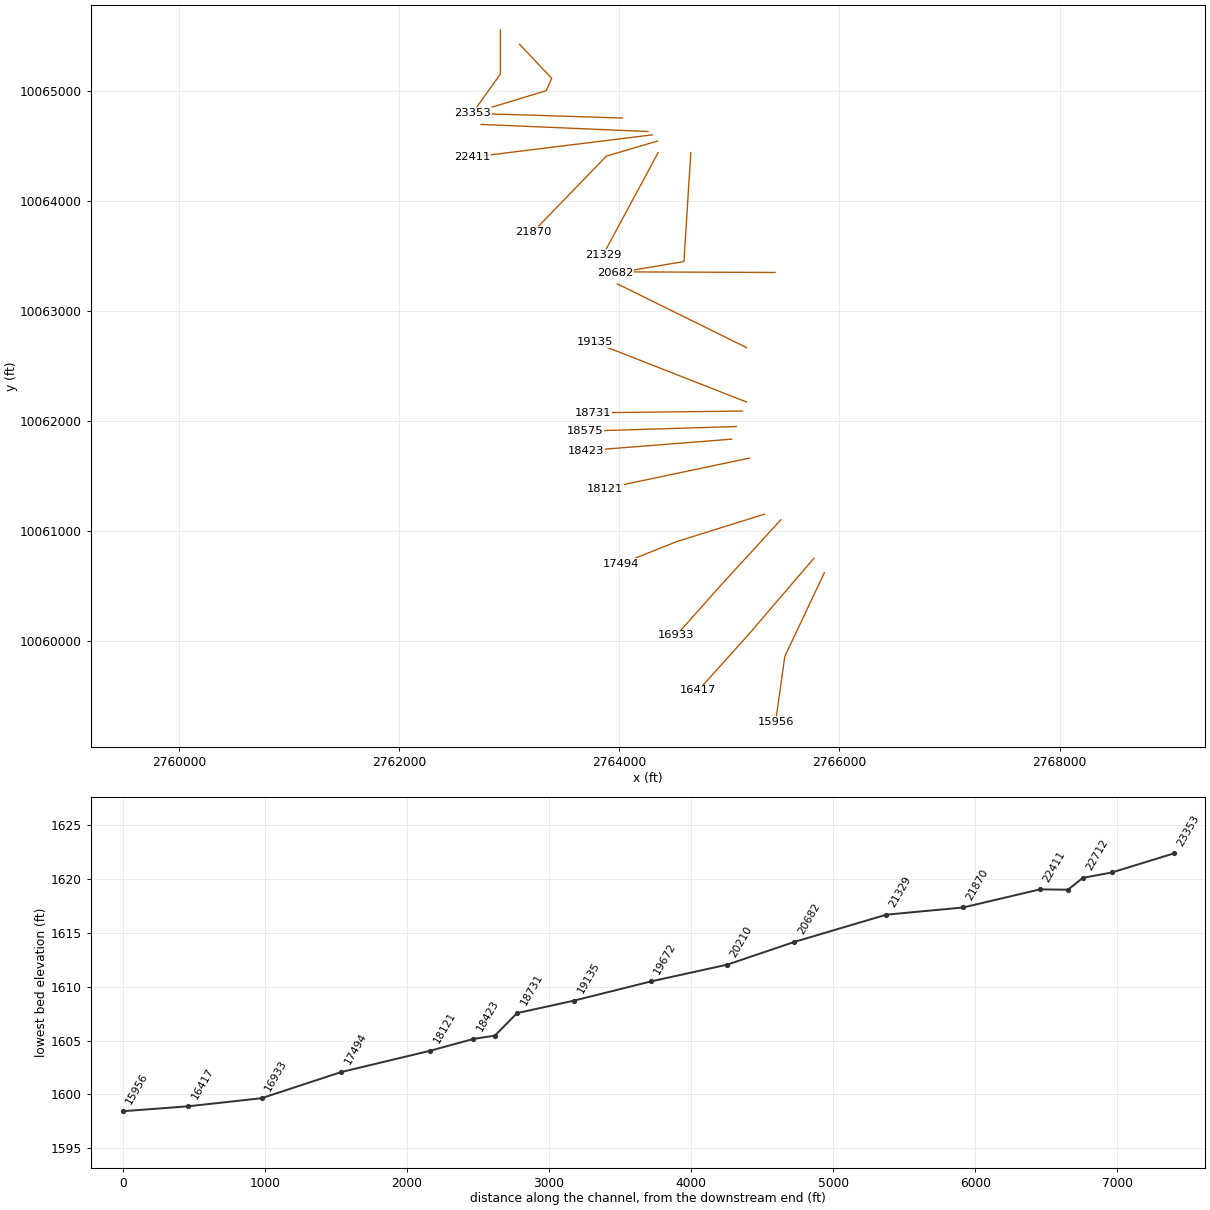
HEC-RAS study BARONS CREEK.prj: BARONS CREEK Base Level Engineering

--- BARONS CREEK.g01 (geometry) --- (continued)

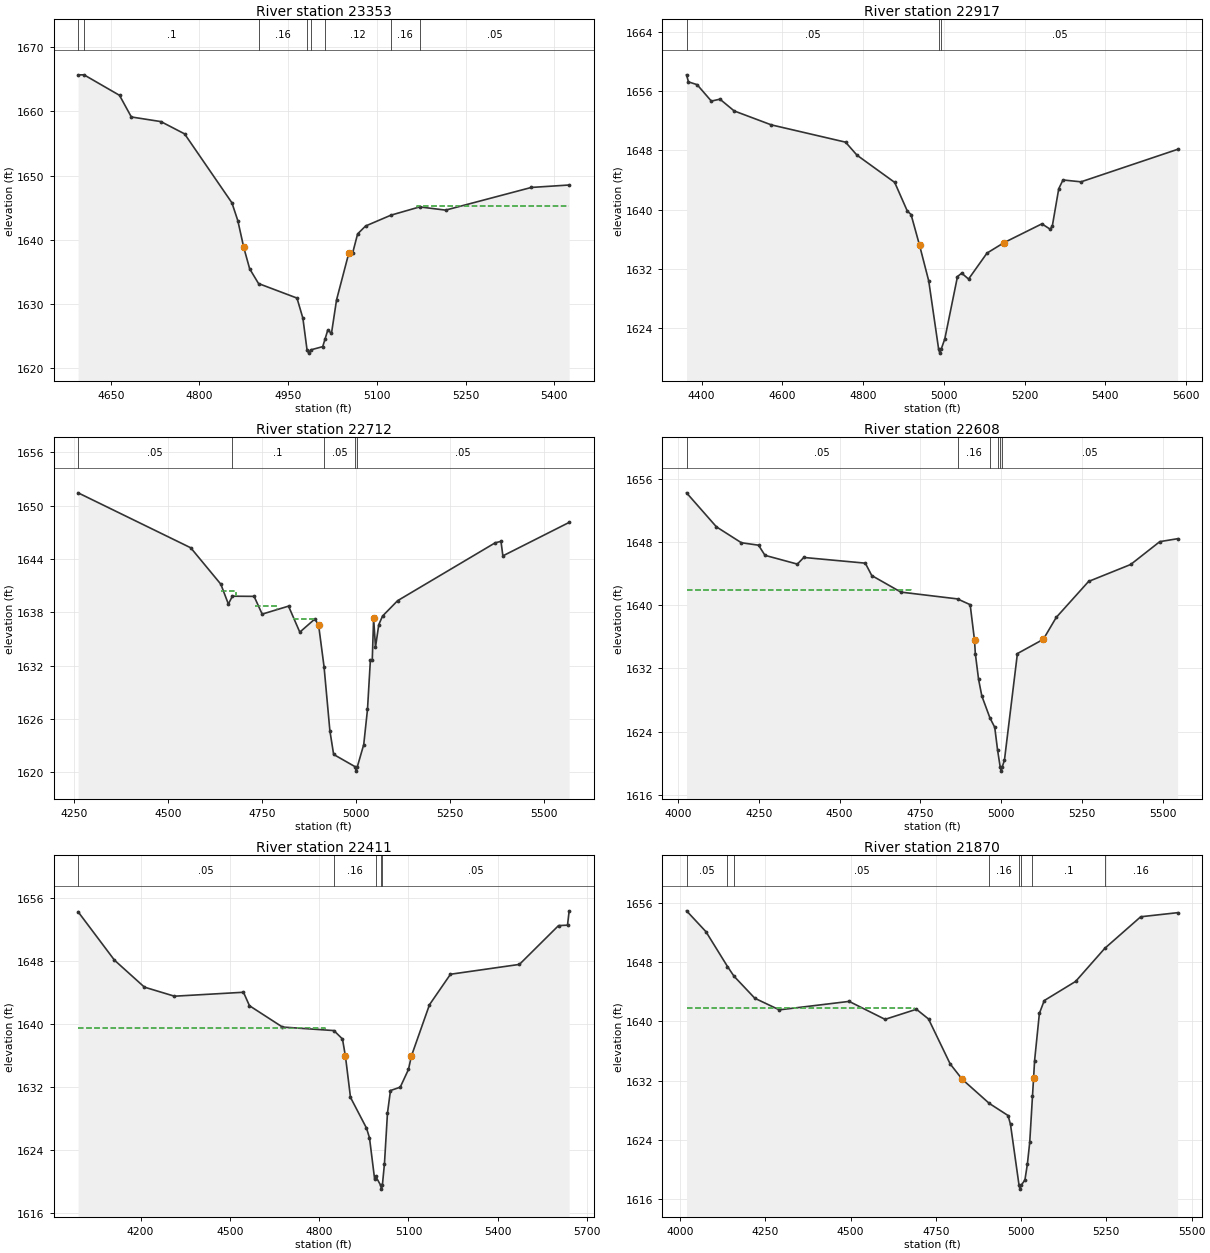
Type RM Length L Ch R = 1 ,23353   ,436,436,436
BEGIN DESCRIPTION:
BARONS CREEK 38.0
END DESCRIPTION:
XS GIS Cut Line= 3
      2762918.47     10065553.76      2762918.47     10065153.73
      2762668.49     10064803.77
#Sta/Elev= 30
  4594.9 1665.69  4604.9  1665.7  4664.9 1662.51  4684.9 1659.14  4734.9 1658.42
  4774.9 1656.51  4854.9 1645.78  4864.9    1643  4874.9 1638.84  4884.9 1635.51
  4899.9 1633.21  4964.9 1630.95  4974.9 1627.81  4981.9 1622.88  4984.7 1622.38
  4987.9 1622.88  5008.4 1623.39  5012.3 1624.56    5017 1625.98  5023.2 1625.45
  5031.8 1630.67  5052.7 1638.02  5058.8  1637.9  5067.4 1640.94  5080.9 1642.17
  5123.9 1643.86  5172.3 1645.14  5216.1 1644.64  5361.1 1648.17    5425 1648.55
#Mann= 8 ,-1 , 0
  4594.9     .05       0  4604.9      .1       0  4899.9     .16       0
  4981.9     .07       0  4987.9     .16       0  5012.3     .12       0
  5123.9     .16       0  5172.3     .05       0
#XS Ineff= 2 , 0
                         5167.73         1645.34
Permanent Ineff=
       T       T
Bank Sta=4874.9,5052.7
XS Rating Curve= 0 ,0
Exp/Cntr=0.3,0.1

Type RM Length L Ch R = 1 ,22917   ,205,205,205
BEGIN DESCRIPTION:
Mapping XS 927b56d6
END DESCRIPTION:
XS GIS Cut Line= 4
      2763092.55     10065424.65      2763385.68     10065114.28
      2763333.95     10065002.18      2762696.81     10064808.46
#Sta/Elev= 30
  4362.6 1658.22  4367.3 1657.27  4388.8 1656.89    4424 1654.67  4445.4 1654.93
  4480.6 1653.34  4572.4 1651.46  4756.5 1649.12  4784.8 1647.36  4878.2 1643.68
  4909.4 1639.81  4918.7 1639.34  4939.6 1635.21  4962.5 1630.36  4987.1 1621.11
  4989.9 1620.61  4993.1 1621.11  5002.3 1622.54  5033.7 1630.96  5044.1 1631.42
  5061.1 1630.62  5106.8 1634.13  5148.6 1635.53  5242.7 1638.08  5263.5 1637.35
  5268.7 1637.83  5284.5 1642.83    5295 1644.01  5339.7 1643.76  5578.9 1648.15
#Mann= 3 ,-1 , 0
  4362.6     .05       0  4987.1    .035       0  4993.1     .05       0
Bank Sta=4939.6,5148.6
XS Rating Curve= 0 ,0
Exp/Cntr=0.3,0.1

Type RM Length L Ch R = 1 ,22712   ,104,104,104
BEGIN DESCRIPTION:
Mapping XS 18321617
END DESCRIPTION:
XS GIS Cut Line= 3
      2764028.05     10064753.78       2763248.1     10064778.52
      2762722.08      10064794.1
#Sta/Elev= 30
  4259.6 1651.45  4559.3 1645.26  4639.4 1641.16  4659.4 1638.93  4670.2 1639.81
  4727.9 1639.79  4749.4 1637.79  4819.5 1638.69  4849.5 1635.76  4889.5 1637.24
  4899.5 1636.56    4914 1631.87  4929.5 1624.67  4939.5 1621.99  4996.6 1620.61
  4999.3 1620.11  5002.6 1620.61  5019.6  1623.1  5029.6 1627.06  5037.3 1632.62
  5042.3 1632.62  5045.9 1637.33  5050.9 1634.07  5059.6  1636.6  5069.6 1637.57
  5109.6  1639.3  5369.7 1645.83  5384.8 1645.98  5389.8 1644.35  5566.2 1648.12
#Mann= 5 ,-1 , 0
  4259.6     .05       0  4670.2      .1       0    4914     .05       0
  4996.6     .04       0  5002.6     .05       0
#XS Ineff= 3 ,-1
 4640.13 4679.44 1640.38 4729.21 4789.62 1638.68    4832 4889.35 1637.29
Permanent Ineff=
       T       T       T
Bank Sta=4899.5,5045.9
XS Rating Curve= 0 ,0
Exp/Cntr=0.3,0.1

Type RM Length L Ch R = 1 ,22608   ,197,197,197
BEGIN DESCRIPTION:
Mapping XS 59cef412
END DESCRIPTION:
XS GIS Cut Line= 2
      2764260.83     10064631.42       2762743.4     10064696.09
#Sta/Elev= 30
  4026.6 1654.19    4119 1649.89  4196.2 1647.88  4249.2 1647.57  4269.2 1646.29
  4369.3 1645.18  4389.3 1646.02  4579.5  1645.3  4599.5 1643.73  4689.6 1641.64
  4864.7 1640.78  4903.8 1640.05 4917.23 1635.57  4919.8 1633.85  4929.8 1630.62
  4939.8 1628.52  4964.9 1625.74  4979.8 1624.55  4988.7 1621.63  4996.8 1619.51
  4999.6 1619.01  5002.8 1619.51  5009.9 1620.42  5049.9 1633.87    5130 1635.67
    5170 1638.44  5270.1 1642.99  5400.2 1645.13  5490.3 1648.02  5545.4 1648.39
#Mann= 6 ,-1 , 0
  4026.6     .05       0  4864.7     .16       0  4964.9      .1       0
  4988.7     .05       0  4996.8     .04       0  5002.8     .05       0
#XS Ineff= 2 , 0
            4720 1641.88
Permanent Ineff=
       T       T
Bank Sta=4917.23,5130
XS Rating Curve= 0 ,0
Exp/Cntr=0.3,0.1

Type RM Length L Ch R = 1 ,22411   ,541,541,541
BEGIN DESCRIPTION:
BARONS CREEK 36.0
END DESCRIPTION:
XS GIS Cut Line= 2
      2764299.62     10064601.24      2762662.89      10064398.8
#Sta/Elev= 30
  3990.4 1654.29  4112.5 1648.14  4213.2 1644.71    4314 1643.56  4545.8 1644.06
  4565.9 1642.35  4676.7 1639.64  4849.5 1639.19  4878.3 1638.12  4888.3 1635.91
  4905.2  1630.7  4958.9  1626.8    4969 1625.56  4986.3  1620.3  4990.1 1620.65
  5006.3 1619.54    5009 1619.04  5012.3 1619.54  5019.3 1622.29  5029.4  1628.7
  5039.5 1631.57  5072.3    1632  5099.9 1634.25    5110 1635.98  5170.5 1642.48
    5241 1646.35  5472.5  1647.6  5603.8 1652.53    5634 1652.59  5639.6 1654.41
#Mann= 5 ,-1 , 0
  3990.4     .05       0  4849.5     .16       0  4990.1     .05       0
  5006.3     .04       0  5012.3     .05       0
#XS Ineff= 2 , 0
         4817.94 1639.58
Permanent Ineff=
       T       T
Bank Sta=4888.3,5110
XS Rating Curve= 0 ,0
Exp/Cntr=0.3,0.1

Type RM Length L Ch R = 1 ,21870   ,541,541,541
BEGIN DESCRIPTION:
BARONS CREEK 35.0
END DESCRIPTION:
XS GIS Cut Line= 3
      2764347.03     10064545.19      2763881.47     10064407.24
      2763217.52     10063721.74
#Sta/Elev= 30
    4019 1654.88  4075.9 1652.07  4139.1 1647.37  4158.1 1646.07  4219.3 1643.09
    4291 1641.53  4495.7 1642.67  4601.1 1640.25    4693 1641.61  4728.5  1640.3
    4792 1634.24  4827.5 1632.16  4906.6 1628.92  4961.8 1627.28  4968.9 1626.08
    4994 1617.86  4996.8 1617.36    5000 1617.86  5011.2  1618.6  5018.4 1620.73
  5025.3 1623.69  5033.3 1629.85 5036.68  1632.4  5039.5 1634.67  5053.6 1641.05
  5067.8 1642.78  5159.8 1645.36  5245.3 1649.82  5350.7 1654.08  5458.9 1654.63
#Mann= 8 ,-1 , 0
    4019     .05       0  4139.1     .16       0  4158.1     .05       0
  4906.6     .16       0    4994     .07       0    5000     .16       0
  5033.3      .1       0  5245.3     .16       0
#XS Ineff= 2 , 0
         4686.01 1641.73
Permanent Ineff=
       T       T
Bank Sta=4827.5,5036.68
XS Rating Curve= 0 ,0
Exp/Cntr=0.3,0.1

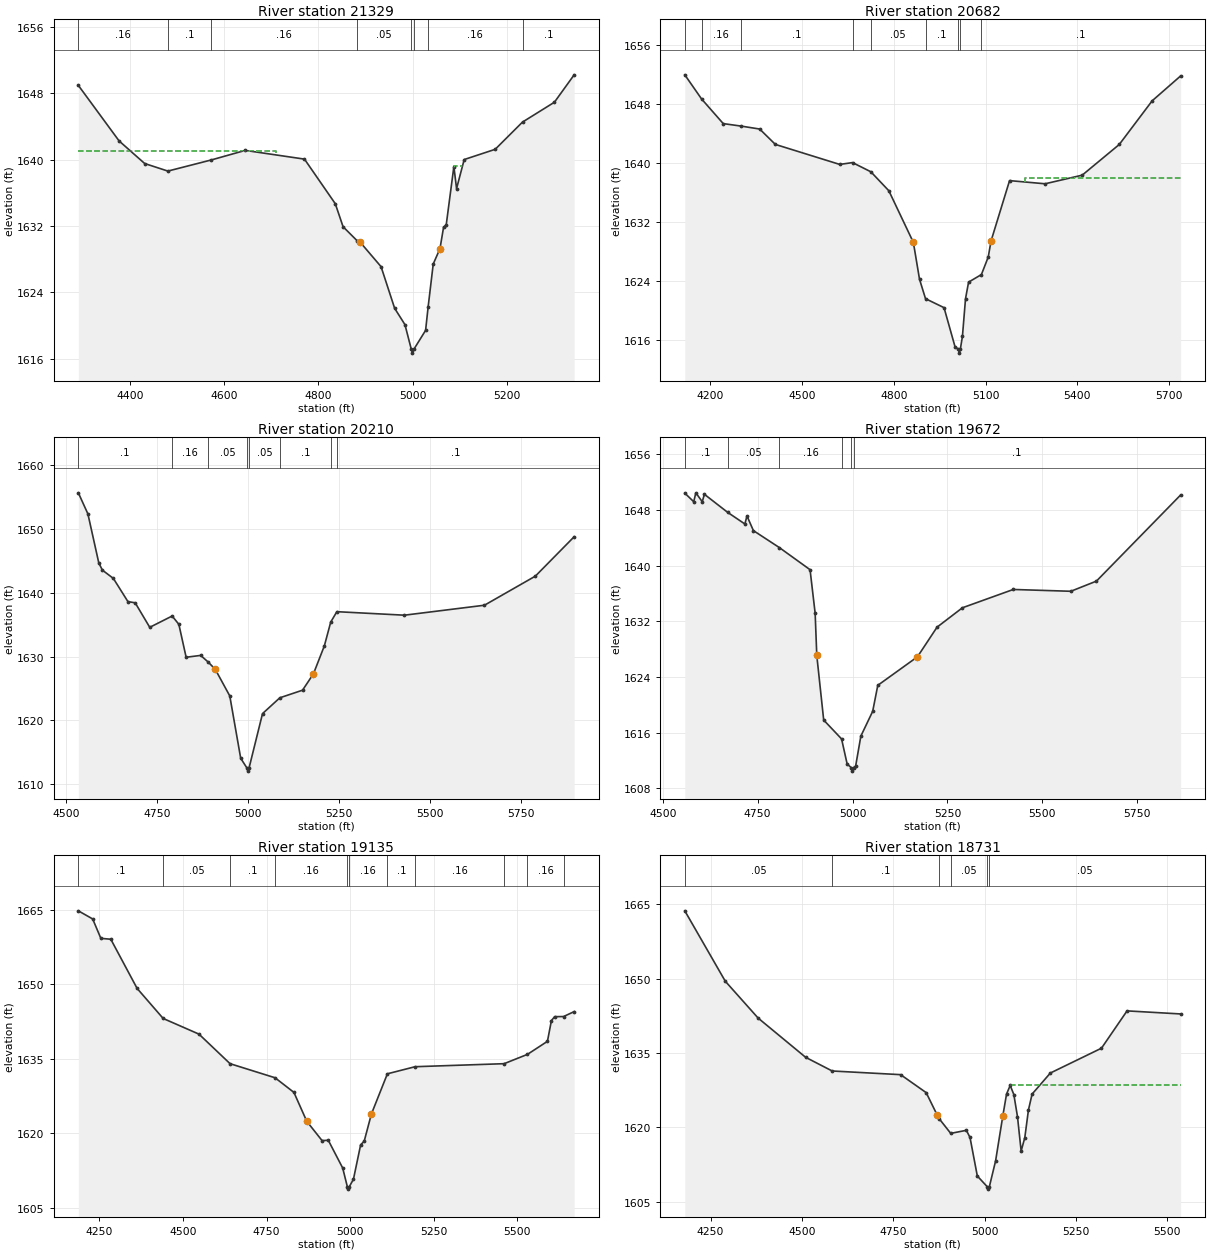
Type RM Length L Ch R = 1 ,21329   ,647,647,647
BEGIN DESCRIPTION:
BARONS CREEK 34.0
END DESCRIPTION:
XS GIS Cut Line= 2
      2764352.26     10064439.05      2763852.89     10063513.13
#Sta/Elev= 30
  4290.6 1648.93  4377.1 1642.24  4431.4 1639.52  4480.6 1638.61  4572.7 1639.95
  4644.7  1641.1  4770.4 1640.05  4835.8 1634.68  4852.3 1631.91  4881.8 1630.24
  4887.5 1630.12  4932.9  1627.1  4961.7 1622.09  4983.6 1620.12  4996.9 1617.19
  4999.6 1616.69  5002.9 1617.19  5027.4 1619.43  5032.8 1622.26  5043.6 1627.42
  5057.9 1629.27  5065.5 1631.83  5071.2 1632.15  5087.4 1639.16  5093.1  1636.5
  5109.3    1640    5175 1641.23    5233 1644.51  5300.7  1646.9  5342.6  1650.2
#Mann= 8 ,-1 , 0
  4290.6     .16       0  4480.6      .1       0  4572.7     .16       0
  4881.8     .05       0  4996.9    .035       0  5002.9     .05       0
  5032.8     .16       0    5233      .1       0
#XS Ineff= 2 ,-1
  4290.6    4710 1641.03 5087.73 5106.82 1639.23
Permanent Ineff=
       T       T
Bank Sta=4887.5,5057.9
XS Rating Curve= 0 ,0
Exp/Cntr=0.3,0.1

Type RM Length L Ch R = 1 ,20682   ,472,472,472
BEGIN DESCRIPTION:
BARONS CREEK 33.0
END DESCRIPTION:
XS GIS Cut Line= 3
      2764649.14     10064439.06      2764586.64     10063449.48
      2763966.88     10063345.32
#Sta/Elev= 30
  4117.2 1651.99    4172 1648.71  4242.8 1645.36  4301.4 1645.02  4361.9 1644.62
  4413.1 1642.53  4623.5 1639.81  4665.2 1640.06  4725.1 1638.81  4783.9 1636.23
    4864 1629.21  4884.1  1624.2  4903.7 1621.56  4964.2 1620.34  4999.9 1615.06
  5011.3 1614.66  5014.1 1614.16  5017.3 1614.66  5024.3 1616.43  5034.4 1621.56
  5044.4 1623.81  5086.3 1624.84  5108.7 1627.23  5117.7 1629.39  5178.3 1637.61
  5294.4 1637.18  5415.6 1638.35  5536.7 1642.52  5644.3 1648.46  5737.2 1651.84
#Mann= 9 ,-1 , 0
  4117.2     .05       0    4172     .16       0  4301.4      .1       0
  4665.2     .16       0  4725.1     .05       0  4903.7      .1       0
  5011.3     .07       0  5017.3      .1       0  5086.3      .1       0
#XS Ineff= 2 , 0
                          5228.3         1637.97
Permanent Ineff=
       T       T
Bank Sta=4864,5117.7
XS Rating Curve= 0 ,0
Exp/Cntr=0.3,0.1

Type RM Length L Ch R = 1 ,20210   ,538,538,538
BEGIN DESCRIPTION:
BARONS CREEK 32.0
END DESCRIPTION:
XS GIS Cut Line= 2
      2765414.75     10063350.52      2764051.86     10063355.72
#Sta/Elev= 30
  4533.2 1655.65  4559.5 1652.35  4589.5 1644.65  4599.5 1643.53  4629.5 1642.24
  4669.5 1638.61  4689.5 1638.42  4729.5 1634.58  4791.1 1636.35  4809.5 1635.05
  4829.5 1629.89  4869.5 1630.18  4889.7 1629.16  4909.5 1628.01  4949.5 1623.83
  4979.5 1614.07  4996.5 1612.55  4999.2 1612.05  5002.5 1612.55  5039.5 1621.06
  5087.1 1623.54  5149.5 1624.73  5179.5  1627.3  5209.5 1631.68  5226.9 1635.39
  5243.8 1637.03  5429.5 1636.48  5649.5 1638.04  5789.5  1642.6  5896.1 1648.77
#Mann= 8 ,-1 , 0
  4533.2      .1       0  4791.1     .16       0  4889.7     .05       0
  4996.5    .035       0  5002.5     .05       0  5087.1      .1       0
  5226.9     .16       0  5243.8      .1       0
Bank Sta=4909.5,5179.5
XS Rating Curve= 0 ,0
Exp/Cntr=0.3,0.1

Type RM Length L Ch R = 1 ,19672   ,537,537,537
BEGIN DESCRIPTION:
BARONS CREEK 31.0
END DESCRIPTION:
XS GIS Cut Line= 2
      2765154.38     10062668.22      2763982.97     10063246.11
#Sta/Elev= 30
  4558.1 1650.45  4581.6 1649.21  4587.2 1650.49  4604.1 1649.21  4609.7 1650.28
  4671.1 1647.68  4716.4 1646.01  4721.9 1647.17  4738.8 1645.06  4807.5 1642.61
  4888.1 1639.44  4901.5 1633.18 4905.81 1627.11    4924 1617.83  4971.1 1615.12
  4985.8 1611.51  4996.6 1610.99  4999.3 1610.49  5002.6 1610.99  5008.2 1611.23
  5021.9 1615.52  5053.1 1619.09  5066.5 1622.82    5171 1626.92  5222.6 1631.18
  5289.5 1633.97  5423.5  1636.6  5575.1 1636.34  5642.5  1637.8  5864.3 1650.18
#Mann= 6 ,-1 , 0
  4558.1      .1       0  4671.1     .05       0  4807.5     .16       0
  4971.1      .1       0  4996.6     .07       0  5002.6      .1       0
Bank Sta=4905.81,5171
XS Rating Curve= 0 ,0
Exp/Cntr=0.3,0.1

Type RM Length L Ch R = 1 ,19135   ,404,404,404
BEGIN DESCRIPTION:
BARONS CREEK 30.0
END DESCRIPTION:
XS GIS Cut Line= 2
      2765154.32     10062173.45       2763774.1     10062715.12
#Sta/Elev= 30
  4187.3 1664.85  4230.2 1663.21  4254.6  1659.3  4284.4 1659.12    4363 1649.21
    4441 1643.14  4548.1 1639.98    4641 1634.02  4775.6 1631.18    4832 1628.23
  4870.4  1622.4  4916.1 1618.51  4934.8 1618.57  4977.8 1612.98  4991.7 1609.22
  4994.5 1608.72  4997.7 1609.22    5010 1610.72  5031.5 1617.65  5042.2  1618.4
  5063.7 1623.87  5111.5 1631.98  5194.4 1633.41  5460.6 1634.02  5530.4  1635.9
  5590.1 1638.53    5602 1642.71  5611.6  1643.5  5638.3 1643.53    5670 1644.52
#Mann= 11 ,-1 , 0
  4187.3      .1       0    4441     .05       0    4641      .1       0
  4775.6     .16       0  4991.7     .07       0  4997.7     .16       0
  5111.5      .1       0  5194.4     .16       0  5460.6     .05       0
  5530.4     .16       0  5638.3     .05       0
Bank Sta=4870.4,5063.7
XS Rating Curve= 0 ,0
Exp/Cntr=0.3,0.1

Type RM Length L Ch R = 1 ,18731   ,156,156,156
BEGIN DESCRIPTION:
Mapping XS 8558bfde
END DESCRIPTION:
XS GIS Cut Line= 2
      2765119.38     10062090.79      2763761.77     10062075.19
#Sta/Elev= 30
  4179.3 1663.71  4290.2  1649.5  4380.2 1642.06  4510.2 1634.15  4582.9 1631.39
  4770.3 1630.65  4840.3 1627.02  4870.3 1622.51  4876.1 1621.74  4907.5  1618.8
  4950.3 1619.42  4960.3 1617.97  4980.3  1610.2  5007.3 1608.05    5010 1607.55
  5013.3 1608.05  5030.3 1613.23  5050.3  1622.4  5060.3 1626.72  5070.3 1628.48
  5080.3 1626.64  5090.3 1622.17  5100.3 1615.23  5110.3 1617.93  5120.3 1623.52
  5130.3 1626.73  5180.3 1630.98  5320.3 1635.99  5390.3 1643.52    5537  1642.9
#Mann= 6 ,-1 , 0
  4179.3     .05       0  4582.9      .1       0  4876.1     .16       0
  4907.5     .05       0  5007.3     .04       0  5013.3     .05       0
#XS Ineff= 2 , 0
                          5070.2         1628.48
Permanent Ineff=
       T       T
Bank Sta=4870.3,5050.3
XS Rating Curve= 0 ,0
Exp/Cntr=0.3,0.1

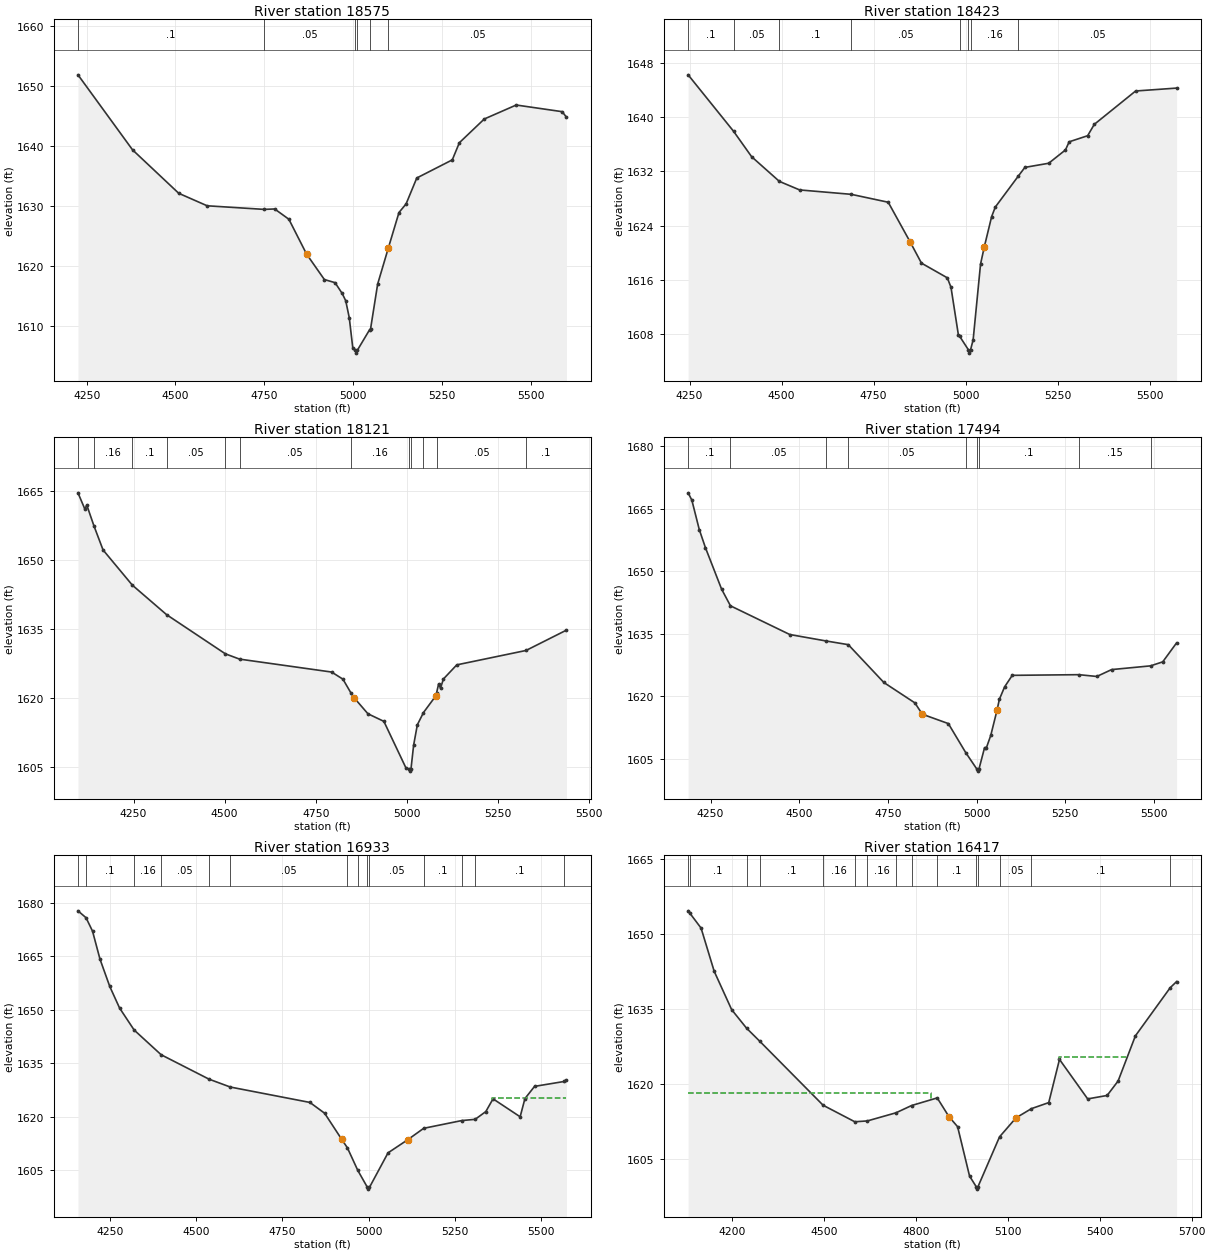
Type RM Length L Ch R = 1 ,18575   ,152,152,152
BEGIN DESCRIPTION:
Mapping XS 36b81fb6
END DESCRIPTION:
XS GIS Cut Line= 2
      2765062.09     10061950.16      2763687.12      10061908.5
#Sta/Elev= 30
  4225.5 1651.83  4379.2 1639.33  4509.3 1632.09  4589.3 1630.01  4749.6 1629.41
  4779.4 1629.48  4819.4 1627.77  4869.4 1621.95  4919.4 1617.72  4949.5  1617.2
  4969.5 1615.41  4979.5  1614.2  4989.5 1611.36  4999.5 1606.29  5006.5 1605.96
  5009.2 1605.46  5012.5 1605.96  5046.6 1609.34  5049.5 1609.51  5069.5 1616.98
  5099.2 1622.91  5129.5 1628.89  5149.5 1630.32  5179.6 1634.64  5279.6 1637.66
  5299.6 1640.52  5369.7 1644.47  5459.7  1646.8  5589.1 1645.69  5601.1 1644.77
#Mann= 6 ,-1 , 0
  4225.5      .1       0  4749.6     .05       0  5006.5    .035       0
  5012.5     .05       0  5046.6     .16       0  5099.2     .05       0
Bank Sta=4869.4,5099.2
XS Rating Curve= 0 ,0
Exp/Cntr=0.3,0.1

Type RM Length L Ch R = 1 ,18423   ,302,302,302
BEGIN DESCRIPTION:
BARONS CREEK 29.0
END DESCRIPTION:
XS GIS Cut Line= 2
      2765020.41     10061835.58       2763697.5     10061731.41
#Sta/Elev= 30
  4246.2 1646.28  4369.9 1637.92  4418.7 1634.18  4494.1 1630.53  4549.1 1629.27
  4689.2 1628.62  4789.8 1627.45    4850 1621.52  4880.1 1618.45  4950.3 1616.28
  4960.3 1614.88  4980.4 1607.84  4983.7 1607.65  5007.5 1605.65  5010.3 1605.15
  5013.5 1605.65  5020.5 1607.12  5040.6 1618.31  5050.6 1620.81  5070.7 1625.32
  5080.7 1626.74  5143.4 1631.33    5161  1632.6  5225.7 1633.21  5271.3 1635.18
  5281.3 1636.38  5331.5 1637.28  5349.6 1638.96  5461.9 1643.89  5573.2 1644.32
#Mann= 8 ,-1 , 0
  4246.2      .1       0  4369.9     .05       0  4494.1      .1       0
  4689.2     .05       0  4983.7     .16       0  5007.5     .07       0
  5013.5     .16       0  5143.4     .05       0
Bank Sta=4850,5050.6
XS Rating Curve= 0 ,0
Exp/Cntr=0.3,0.1

Type RM Length L Ch R = 1 ,18121   ,627,627,627
BEGIN DESCRIPTION:
BARONS CREEK 28.0
END DESCRIPTION:
XS GIS Cut Line= 2
      2765180.36     10061663.02      2763867.88     10061386.98
#Sta/Elev= 30
  4097.2 1664.56  4116.2 1661.01  4121.4  1661.9    4141 1657.39  4166.1 1652.14
  4246.5 1644.49  4340.6 1638.07  4501.9 1629.56  4540.9 1628.41  4793.6  1625.6
  4824.7 1624.05    4846 1621.15  4855.3 1620.02  4893.3 1616.53  4937.1 1614.88
  4998.4 1604.64  5005.6 1604.56  5008.4 1604.06  5011.6 1604.56  5018.8  1609.7
    5029 1614.13  5045.9  1616.8  5080.1 1620.46  5081.9 1621.09  5087.5 1623.04
  5092.6 1622.08  5100.6 1624.09  5137.3 1627.16  5327.4 1630.29  5438.4 1634.71
#Mann= 12 ,-1 , 0
  4097.2      .1       0    4141     .16       0  4246.5      .1       0
  4340.6     .05       0  4501.9      .1       0  4540.9     .05       0
    4846     .16       0  5005.6     .07       0  5011.6     .16       0
  5045.9      .1       0  5081.9     .05       0  5327.4      .1       0
Bank Sta=4855.3,5080.1
XS Rating Curve= 0 ,0
Exp/Cntr=0.3,0.1

Type RM Length L Ch R = 1 ,17494   ,561,561,561
BEGIN DESCRIPTION:
BARONS CREEK 27.0
END DESCRIPTION:
XS GIS Cut Line= 3
      2765318.47     10061153.73      2764518.47     10060903.73
      2764018.44     10060703.72
#Sta/Elev= 30
  4186.9 1668.76  4197.4 1667.01  4218.3 1659.97  4235.6 1655.64  4281.2 1645.69
  4306.2 1641.69  4473.4 1634.81  4576.1 1633.26  4638.3 1632.38  4738.5 1623.32
    4826 1618.43  4846.9 1615.72  4920.3 1613.47  4969.2 1606.53  5000.6 1602.58
  5003.3 1602.08  5006.6 1602.58  5022.4 1607.71  5027.7 1607.71  5039.9 1610.66
  5057.4 1616.63  5064.1 1619.29  5078.9 1622.27  5100.4 1625.03  5288.3 1625.19
  5338.7 1624.76  5380.5 1626.41  5490.1  1627.3  5524.5 1628.26  5563.6 1632.81
#Mann= 9 ,-1 , 0
  4186.9      .1       0  4306.2     .05       0  4576.1      .1       0
  4638.3     .05       0  4969.2      .1       0  5000.6     .07       0
  5006.6      .1       0  5288.3     .15       0  5490.1      .1       0
Bank Sta=4846.9,5057.4
XS Rating Curve= 0 ,0
Exp/Cntr=0.3,0.1

Type RM Length L Ch R = 1 ,16933   ,516,516,516
BEGIN DESCRIPTION:
BARONS CREEK 26.0
END DESCRIPTION:
XS GIS Cut Line= 3
      2765468.47     10061103.74      2764918.47     10060503.73
      2764518.48     10060053.75
#Sta/Elev= 30
  4157.4 1677.76  4180.8 1675.82  4199.6 1672.06  4221.2 1664.21  4249.6 1656.53
    4278 1650.48  4320.2 1644.31  4398.5 1637.37  4537.4 1630.51  4599.1  1628.3
  4829.8 1623.98  4872.4 1620.95  4921.7 1613.66  4938.5 1611.23  4968.5 1604.92
  4996.4 1600.15  4999.1 1599.65  5002.4 1600.15  5056.2 1609.83  5113.1  1613.5
  5159.6 1616.72  5269.7 1618.89  5308.8 1619.24  5339.7 1621.42  5360.6 1624.99
  5439.2 1619.95    5453 1625.05    5481 1628.49  5566.5 1629.86  5573.4 1630.15
#Mann= 14 ,-1 , 0
  4157.4     .16       0  4180.8      .1       0  4320.2     .16       0
  4398.5     .05       0  4537.4     .16       0  4599.1     .05       0
  4938.5      .1       0  4968.5     .05       0  4996.4    .035       0
  5002.4     .05       0  5159.6      .1       0  5269.7     .05       0
  5308.8      .1       0  5566.5     .15       0
#XS Ineff= 2 , 0
                         5358.18         1625.18
Permanent Ineff=
       T       T
Bank Sta=4921.7,5113.1
XS Rating Curve= 0 ,0
Exp/Cntr=0.3,0.1

Type RM Length L Ch R = 1 ,16417   ,461,461,461
BEGIN DESCRIPTION:
BARONS CREEK 25.0
END DESCRIPTION:
XS GIS Cut Line= 3
      2765768.47     10060753.73      2765168.47     10060053.73
      2764718.49     10059553.76
#Sta/Elev= 30
  4056.3 1654.64  4062.3 1654.14  4098.6 1651.18  4141.4 1642.53  4198.4 1634.85
    4247 1631.14  4289.8 1628.54    4497  1615.7  4600.4 1612.39  4641.3 1612.56
    4735 1614.19  4785.6 1615.64  4869.5 1617.17  4907.5 1613.44    4936  1611.4
    4975 1601.52  4996.6  1599.4  4999.3  1598.9  5002.6  1599.4  5072.9 1609.37
  5126.6 1613.17    5177 1615.02  5233.5 1616.23  5268.6 1624.88  5360.6 1616.97
  5424.1 1617.66    5460 1620.56  5516.4  1629.6    5630 1639.24  5650.9 1640.47
#Mann= 15 ,-1 , 0
  4056.3     .05       0  4062.3      .1       0    4247     .16       0
  4289.8      .1       0    4497     .16       0  4600.4      .1       0
  4641.3     .16       0    4735      .1       0  4785.6     .16       0
  4869.5      .1       0  4996.6     .07       0  5002.6      .1       0
  5072.9     .05       0    5177      .1       0    5630     .15       0
#XS Ineff= 2 ,-1
  4056.3 4849.89 1618.12 5268.18 5493.18 1625.39
Permanent Ineff=
       T       T
Bank Sta=4907.5,5126.6
XS Rating Curve= 0 ,0
Exp/Cntr=0.3,0.1

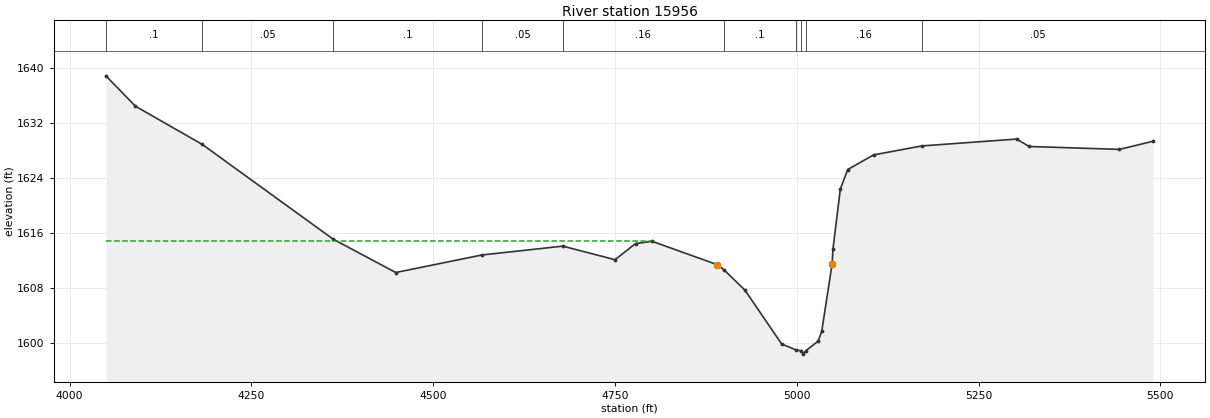
Type RM Length L Ch R = 1 ,15956   ,590,590,590
BEGIN DESCRIPTION:
BARONS CREEK 24.0
END DESCRIPTION:
XS GIS Cut Line= 3
      2765862.69     10060621.38      2765503.31     10059860.94
      2765420.08     10059267.94
#Sta/Elev= 30
    4050 1638.85  4090.6 1634.44  4182.7 1628.88  4362.5 1615.13  4448.6 1610.29
  4567.3 1612.84  4678.3 1614.12    4750 1612.15  4778.3 1614.49  4801.1 1614.82
  4890.9 1611.42  4899.5 1610.72  4928.7 1607.73  4979.2 1599.91  4999.4 1599.03
  5006.4 1598.94  5009.2 1598.44  5012.4 1598.94  5029.2  1600.3  5034.3 1601.75
 5048.48 1611.46  5049.8 1613.74  5059.9 1622.41    5070 1625.24  5105.6 1627.37
  5171.8 1628.67  5302.3 1629.67  5319.5 1628.59  5443.7 1628.17  5489.9 1629.35
#Mann= 10 ,-1 , 0
    4050      .1       0  4182.7     .05       0  4362.5      .1       0
  4567.3     .05       0  4678.3     .16       0  4899.5      .1       0
  4999.4     .16       0  5006.4     .07       0  5012.4     .16       0
  5171.8     .05       0
#XS Ineff= 2 , 0
         4801.11 1614.82
Permanent Ineff=
       T       T
Bank Sta=4890.9,5048.48
XS Rating Curve= 0 ,0
Exp/Cntr=0.3,0.1