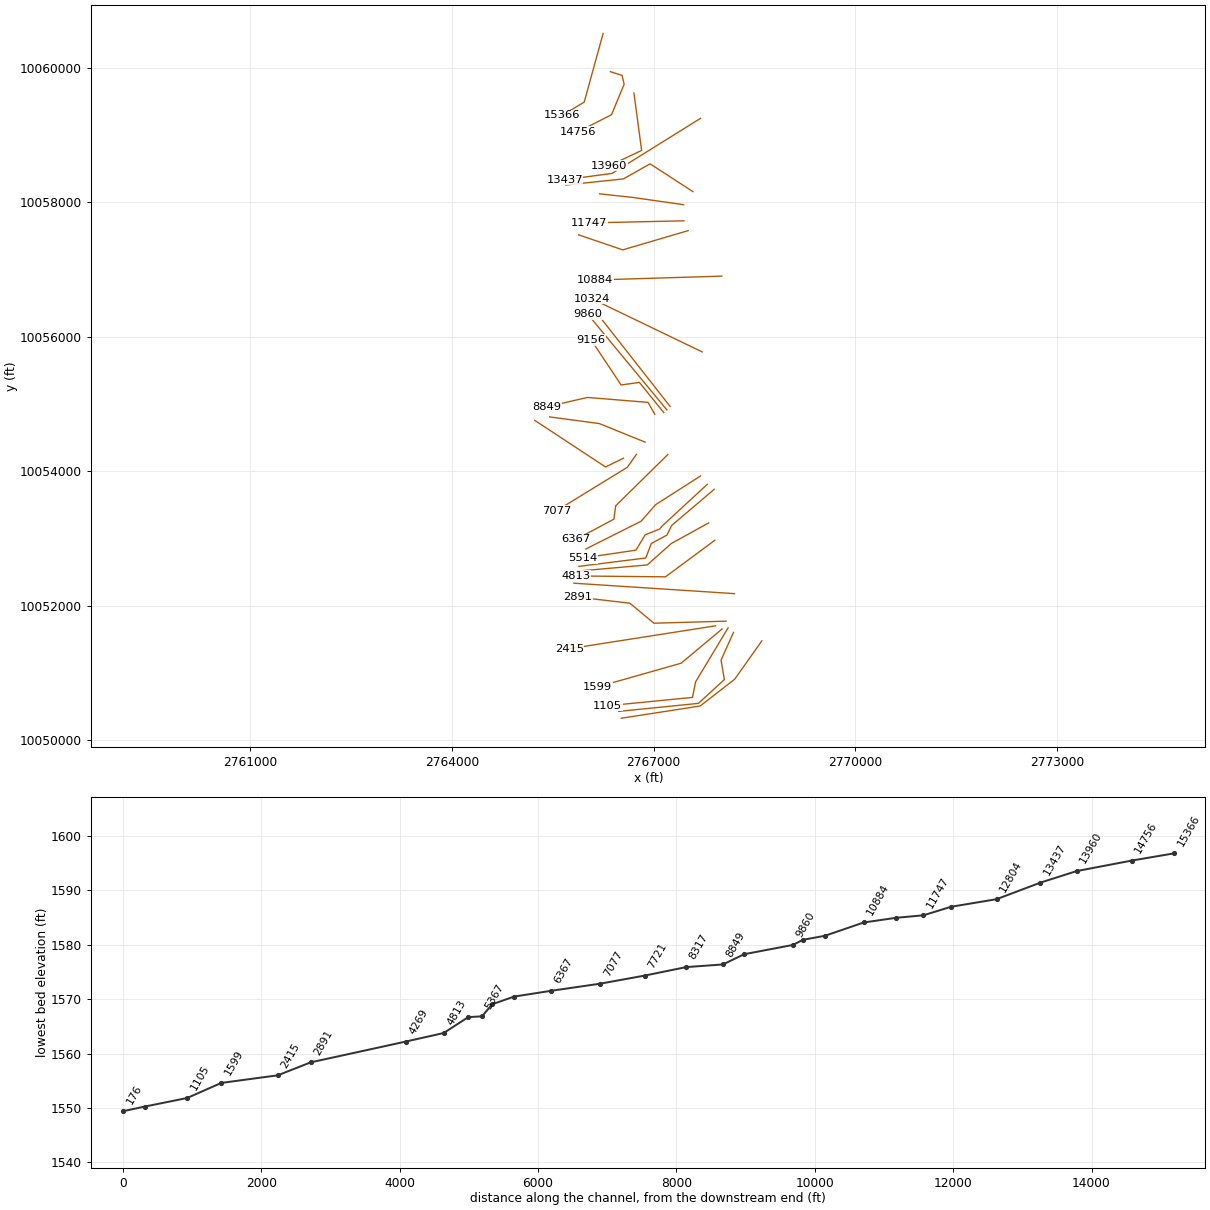
HEC-RAS study BARONS CREEK.prj: BARONS CREEK Base Level Engineering

--- BARONS CREEK.g01 (geometry) --- (continued)

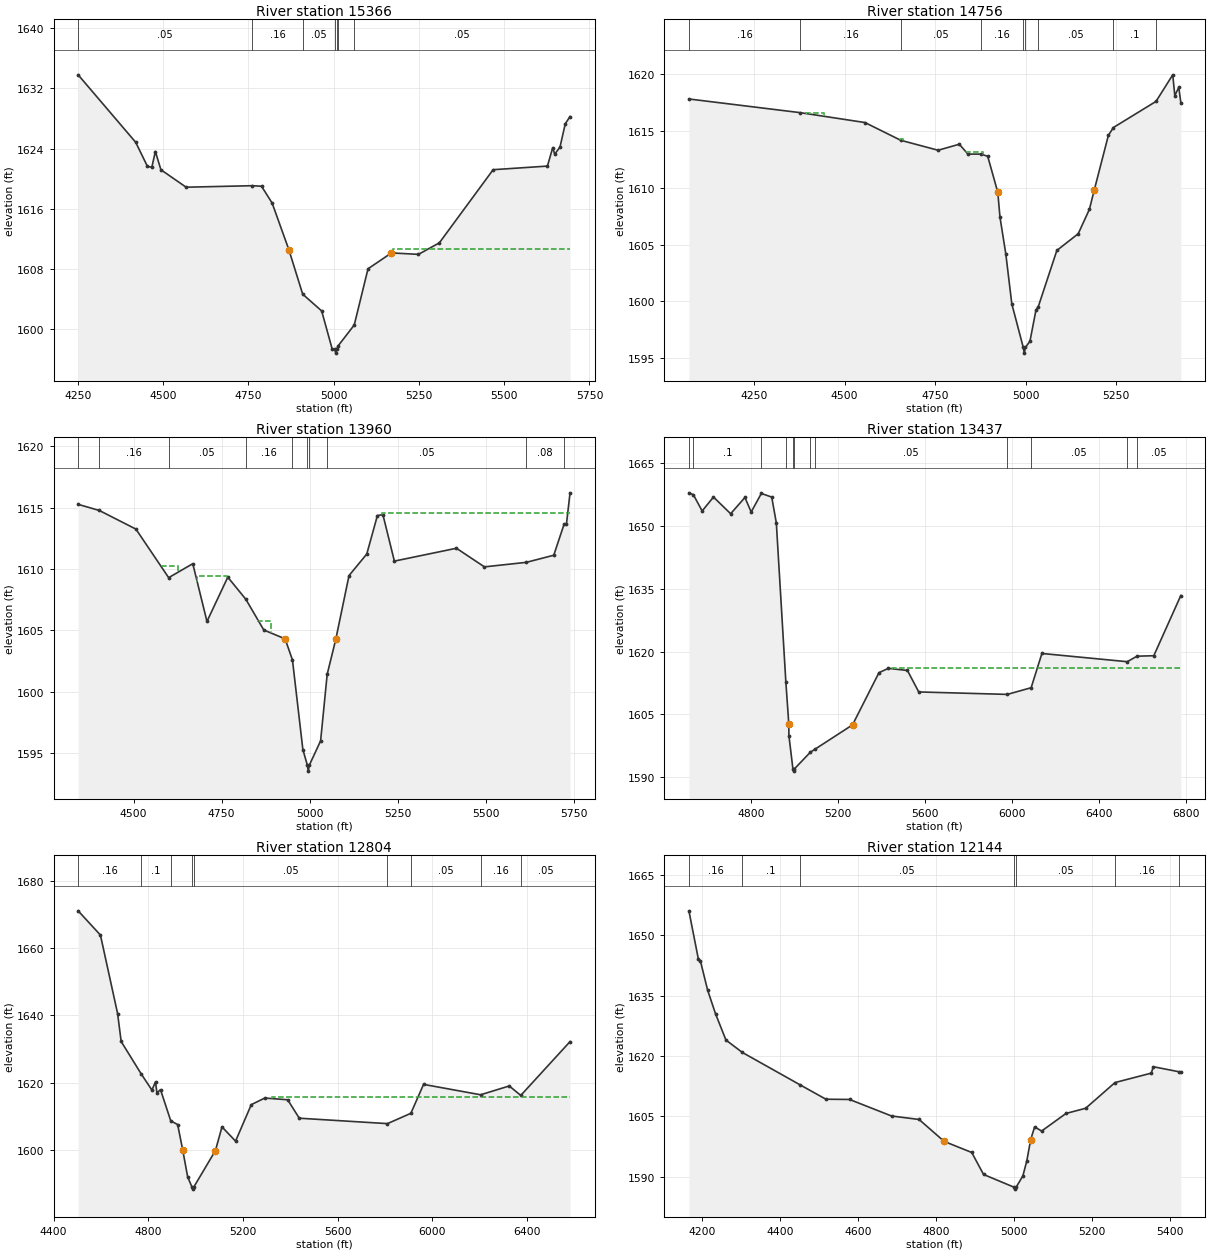
Type RM Length L Ch R = 1 ,15366   ,610,610,610
BEGIN DESCRIPTION:
BARONS CREEK 23.0
END DESCRIPTION:
XS GIS Cut Line= 3
       2766248.1       10060512.      2765966.85     10059491.15
      2765638.71     10059293.22
#Sta/Elev= 30
  4250.9 1633.82  4419.6 1624.84    4454 1621.64  4466.9 1621.51  4477.3 1623.61
  4493.6 1621.18  4567.5 1618.86  4761.5 1619.06  4788.5 1618.99  4819.6 1616.75
  4868.5 1610.56  4909.2 1604.62  4964.8 1602.39  4995.9 1597.28  5003.3 1597.27
  5006.1 1596.77  5009.3 1597.27  5012.5  1597.7  5060.4 1600.52  5100.7    1608
  5169.5 1610.11  5248.6 1609.92  5309.8 1611.45  5467.5 1621.19  5626.7 1621.67
  5642.2 1624.13    5648 1623.26  5663.5  1624.2    5679 1627.31    5693 1628.27
#Mann= 7 ,-1 , 0
  4250.9     .05       0  4761.5     .16       0  4909.2     .05       0
  5003.3    .035       0  5009.3     .05       0  5012.5      .1       0
  5060.4     .05       0
#XS Ineff= 2 , 0
                         5174.73         1610.66
Permanent Ineff=
       T       T
Bank Sta=4868.5,5169.5
XS Rating Curve= 0 ,0
Exp/Cntr=0.3,0.1

Type RM Length L Ch R = 1 ,14756   ,796,796,796
BEGIN DESCRIPTION:
BARONS CREEK 22.0
END DESCRIPTION:
XS GIS Cut Line= 5
     2766356.036    10059943.798     2766529.647    10059888.242
      2766560.62     10059756.81       2766373.1     10059303.65
      2765873.54     10059048.66
#Sta/Elev= 30
4070.1491617.824  4377.6 1616.62  4556.4 1615.75  4655.1 1614.19  4758.4 1613.31
    4817 1613.84  4840.9 1612.97  4876.5 1612.97  4895.5 1612.78  4923.3 1609.61
  4929.4 1607.42  4945.5 1604.18  4962.1 1599.78  4993.7 1595.95  4996.5 1595.45
  4999.7 1595.95  5012.2  1596.5  5028.8 1599.24  5035.3 1599.55  5086.5 1604.49
  5145.5 1605.96  5176.4 1608.11    5190 1609.83  5228.8 1614.62  5242.7 1615.31
  5360.4 1617.61  5406.6 1619.95  5412.3 1618.12  5423.3 1618.85  5428.9 1617.51
#Mann= 9 ,-1 , 0
4070.149     .16       0  4377.6     .16       0  4655.1     .05       0
  4876.5     .16       0  4993.7     .07       0  4999.7     .16       0
  5035.3     .05       0  5242.7      .1       0  5360.4     .05       0
#XS Ineff= 3 ,-1
 4394.89 4444.01 1616.55 4652.81 4662.56 1614.26 4832.39  4883.3 1613.15
Permanent Ineff=
       T       T       T
Bank Sta=4923.3,5190
XS Rating Curve= 0 ,0
Exp/Cntr=0.3,0.1

Type RM Length L Ch R = 1 ,13960   ,523,523,523
BEGIN DESCRIPTION:
BARONS CREEK 21.0
END DESCRIPTION:
XS GIS Cut Line= 3
      2766706.44     10059626.52      2766821.02      10058772.4
      2766336.66     10058543.24
#Sta/Elev= 30
  4342.4 1615.28  4402.6 1614.78  4506.6 1613.26  4599.6  1609.3  4668.1 1610.44
  4708.4 1605.73  4767.6 1609.34  4818.8 1607.54  4869.9 1605.03  4930.4 1604.31
  4951.3 1602.59  4980.9 1595.28  4993.5 1594.02  4996.2 1593.52  4999.5 1594.02
  5031.3 1595.99    5050 1601.42  5074.4 1604.27    5112 1609.47  5162.5 1611.23
  5192.7 1614.37  5208.3 1614.44  5240.9 1610.65  5417.2  1611.7  5496.7 1610.18
  5615.8 1610.55  5693.7 1611.13  5722.8 1613.64  5729.8 1613.68    5740 1616.22
#Mann= 10 ,-1 , 0
  4342.4      .1       0  4402.6     .16       0  4599.6     .05       0
  4818.8     .16       0  4951.3      .1       0  4993.5     .07       0
  4999.5      .1       0    5050     .05       0  5615.8     .08       0
  5722.8     .05       0
#XS Ineff= 5 ,-1
 4578.18 4626.36 1610.28 4680.91 4766.36 1609.41 4770.91 4779.09 1608.55
 4851.82 4889.09 1605.73 5204.55    5740 1614.56
Permanent Ineff=
       T       T       T       T       T
Bank Sta=4930.4,5074.4
XS Rating Curve= 0 ,0
Exp/Cntr=0.3,0.1

Type RM Length L Ch R = 1 ,13437   ,633,633,633
BEGIN DESCRIPTION:
BARONS CREEK 20.0
END DESCRIPTION:
XS GIS Cut Line= 3
      2767697.16     10059249.84      2766382.27     10058430.74
      2765675.25     10058335.89
#Sta/Elev= 30
  4515.2 1657.96  4535.6 1657.52  4576.2 1653.62  4628.2 1656.95  4707.2 1652.96
  4772.9 1656.85  4801.6 1653.37  4848.4 1657.81  4896.1 1656.94  4917.3 1650.77
    4961  1612.8 4974.65  1602.7  4975.1 1599.92  4993.7  1591.9  4996.5  1591.4
  4999.7  1591.9  5074.2 1595.94  5096.2 1596.68  5267.7 1602.46  5389.3 1614.94
  5432.6 1615.98  5520.3 1615.47  5572.3 1610.34  5979.7 1609.75  6089.3 1611.35
  6138.8 1619.54  6531.2 1617.57  6576.3 1618.89  6653.4    1619  6777.7  1633.4
#Mann= 12 ,-1 , 0
  4515.2     .05       0  4535.6      .1       0  4848.4     .16       0
    4961     .05       0  4993.7    .035       0  4999.7     .05       0
  5074.2      .1       0  5096.2     .05       0  5979.7     .08       0
  6089.3     .05       0  6531.2     .16       0  6576.3     .05       0
#XS Ineff= 2 , 0
                         5447.44         1616.02
Permanent Ineff=
       T       T
Bank Sta=4974.65,5267.7
XS Rating Curve= 0 ,0
Exp/Cntr=0.3,0.1

Type RM Length L Ch R = 1 ,12804   ,660,660,660
BEGIN DESCRIPTION:
BARONS CREEK 19.0
END DESCRIPTION:
XS GIS Cut Line= 4
      2767585.05     10058159.16      2766947.04     10058573.01
      2766550.41     10058348.83      2765692.95     10058258.34
#Sta/Elev= 30
  4503.7 1671.04  4597.9 1663.84  4670.4 1640.53  4685.5 1632.22  4770.4 1622.56
  4815.4 1617.78  4830.6 1620.23  4836.5 1616.95  4851.7 1617.91    4895 1608.65
  4924.2 1607.53  4945.3 1600.07  4966.4 1592.01  4985.3 1588.86  4988.1 1588.36
  4991.3 1588.86  5083.7  1599.8  5111.4 1606.85  5168.8 1602.62  5235.3 1613.46
  5292.2 1615.42  5388.9 1614.91    5438 1609.43  5810.6 1607.82  5909.4 1610.88
  5963.1 1619.48  6204.1 1616.39  6325.1 1619.01  6373.8  1616.2    6582 1632.19
#Mann= 9 ,-1 , 0
  4503.7     .16       0  4770.4      .1       0    4895     .05       0
  4985.3    .035       0  4991.3     .05       0  5810.6     .08       0
  5909.4     .05       0  6204.1     .16       0  6373.8     .05       0
#XS Ineff= 2 , 0
                         5321.02         1615.79
Permanent Ineff=
       T       T
Bank Sta=4945.3,5083.7
XS Rating Curve= 0 ,0
Exp/Cntr=0.3,0.1

Type RM Length L Ch R = 1 ,12144   ,397,397,397
BEGIN DESCRIPTION:
BARONS CREEK 18.0
END DESCRIPTION:
XS GIS Cut Line= 3
      2767446.02     10057965.11      2766680.39     10058074.48
      2766195.98     10058126.57
#Sta/Elev= 30
  4166.5 1656.05  4190.7  1644.1  4195.8 1643.67  4214.5 1636.35  4234.7  1630.5
  4261.4 1623.97  4303.5 1620.89  4450.1 1612.92  4517.6 1609.28  4578.2 1609.22
  4685.7 1605.12  4756.4 1604.25  4820.6 1598.81  4891.3 1596.06  4921.6  1590.6
  4999.2 1587.46  5001.9 1586.96  5005.2 1587.46  5022.3 1590.23  5032.4 1593.97
  5042.4 1599.27  5052.5 1602.41  5070.4 1601.38  5132.9 1605.75  5183.2 1607.03
  5258.5 1613.42  5351.5 1615.76  5356.5 1617.35  5422.3  1616.1  5427.1 1616.09
#Mann= 7 ,-1 , 0
  4166.5     .16       0  4303.5      .1       0  4450.1     .05       0
  4999.2    .035       0  5005.2     .05       0  5258.5     .16       0
  5422.3     .05       0
Bank Sta=4820.6,5042.4
XS Rating Curve= 0 ,0
Exp/Cntr=0.3,0.1

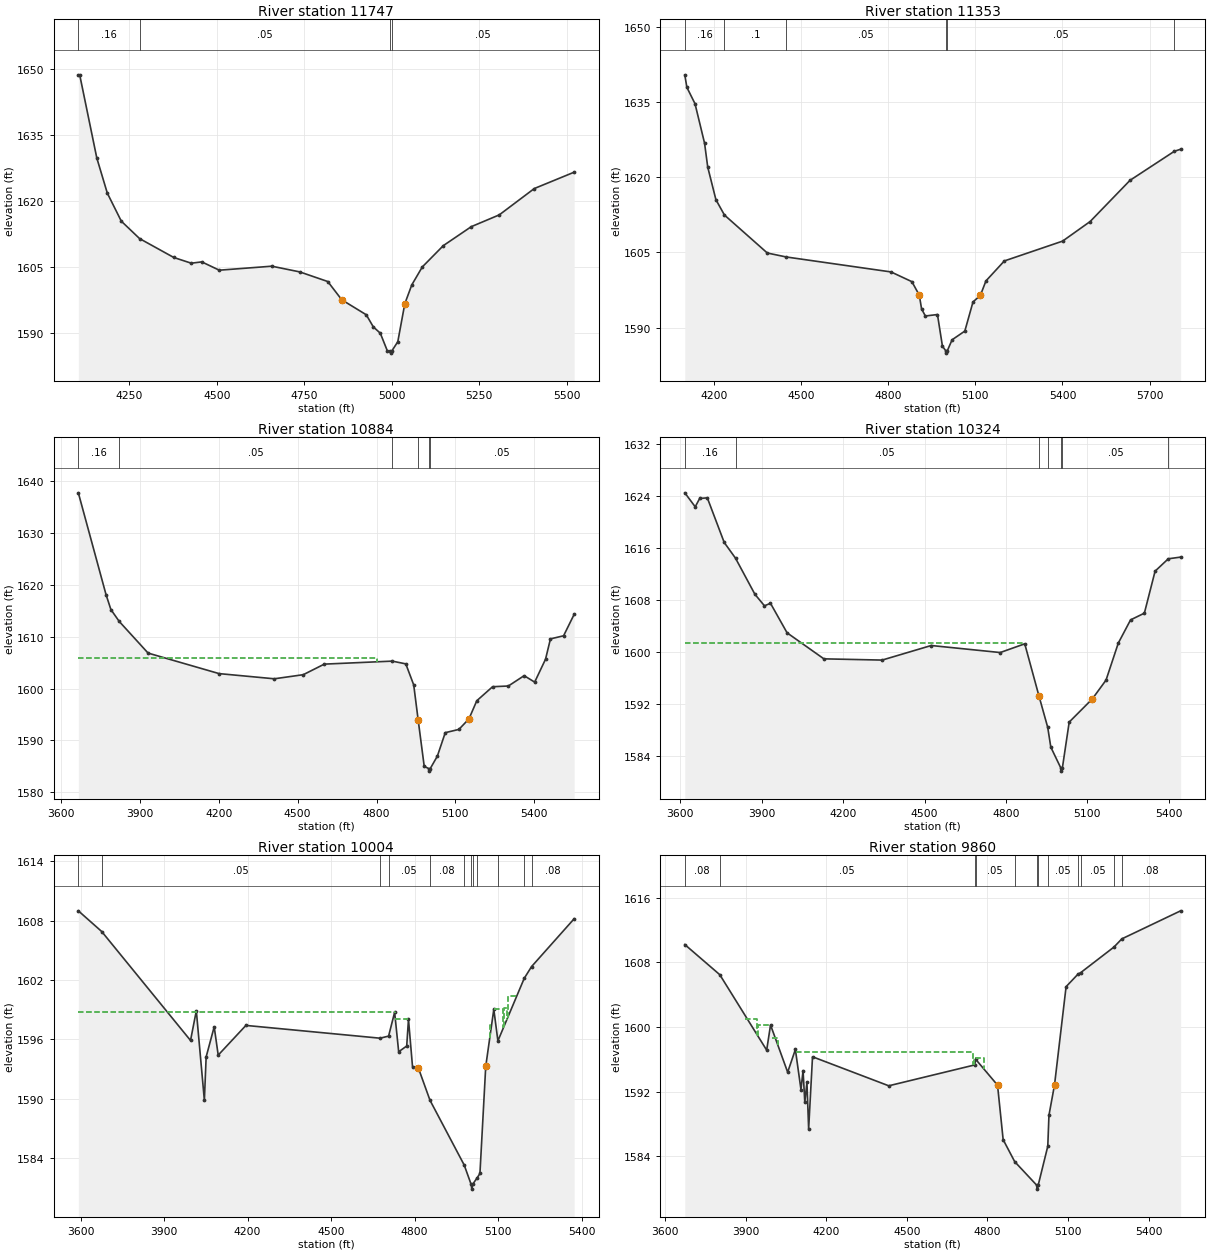
Type RM Length L Ch R = 1 ,11747   ,394,394,394
BEGIN DESCRIPTION:
BARONS CREEK 17.0
END DESCRIPTION:
XS GIS Cut Line= 2
      2767451.22     10057725.52      2766034.56     10057694.27
#Sta/Elev= 30
  4104.4 1648.69  4108.3 1648.69  4157.2 1629.77  4187.2 1621.79  4227.2 1615.41
  4279.4 1611.45  4377.2 1607.15  4427.2 1605.85  4457.2 1606.15  4507.2 1604.26
  4657.3 1605.17  4737.3 1603.87  4817.3 1601.68  4857.3 1597.53  4927.3 1594.12
  4947.4 1591.37  4967.4 1589.93  4987.4 1585.94  4994.4  1585.9  4997.1  1585.4
  5000.4  1585.9  5017.4    1588  5037.4 1596.63  5057.4 1600.92  5087.4    1605
  5147.4 1609.84  5227.4 1614.16  5307.4 1616.84  5407.5 1622.83  5521.4 1626.55
#Mann= 4 ,-1 , 0
  4104.4     .16       0  4279.4     .05       0  4994.4     .04       0
  5000.4     .05       0
Bank Sta=4857.3,5037.4
XS Rating Curve= 0 ,0
Exp/Cntr=0.3,0.1

Type RM Length L Ch R = 1 ,11353   ,469,469,469
BEGIN DESCRIPTION:
BARONS CREEK 16.0
END DESCRIPTION:
XS GIS Cut Line= 3
      2767513.77      10057579.7      2766539.77     10057293.23
      2765883.48      10057517.2
#Sta/Elev= 30
  4098.5  1640.4  4105.6 1637.91  4133.7 1634.64  4166.6 1626.78  4177.5 1622.02
  4205.7 1615.52  4235.1 1612.46  4382.9 1604.89  4448.3  1604.1  4809.2 1601.12
  4881.1 1599.18  4906.6 1596.49  4914.5 1593.75  4927.5 1592.34  4969.2 1592.63
  4986.4 1586.32  4997.4 1585.44  5000.2 1584.94  5003.4 1585.44  5019.7  1587.6
  5063.5 1589.33  5091.7 1595.14  5117.1 1596.45  5136.3 1599.33  5199.7 1603.31
  5400.4 1607.26  5495.5 1611.17  5632.9 1619.38  5785.5 1625.16  5807.2 1625.57
#Mann= 6 ,-1 , 0
  4098.5     .16       0  4235.1      .1       0  4448.3     .05       0
  4997.4    .035       0  5003.4     .05       0  5785.5      .1       0
Bank Sta=4906.6,5117.1
XS Rating Curve= 0 ,0
Exp/Cntr=0.3,0.1

Type RM Length L Ch R = 1 ,10884   ,560,560,560
BEGIN DESCRIPTION:
BARONS CREEK 15.0
END DESCRIPTION:
XS GIS Cut Line= 2
      2768013.73     10056902.61       2766128.3     10056845.31
#Sta/Elev= 30
  3665.5 1637.79  3770.8 1618.16  3789.4 1615.26  3821.1 1612.97  3930.9 1606.86
    4201  1602.9  4411.1  1601.9  4521.2 1602.69  4601.2 1604.73  4859.7 1605.31
  4911.3 1604.78  4941.4 1600.72  4958.3 1593.97  4981.4    1585  4998.4 1584.58
  5001.1 1584.08  5004.4 1584.58  5031.4 1586.98  5061.4  1591.5  5113.2 1592.13
  5151.4 1594.15  5181.5 1597.67  5241.5 1600.37  5301.5 1600.51  5361.5  1602.5
  5401.6 1601.26  5442.9 1605.68  5461.6  1609.6  5511.6  1610.2  5551.8 1614.34
#Mann= 6 ,-1 , 0
  3665.5     .16       0  3821.1     .05       0  4859.7      .1       0
  4958.3     .05       0  4998.4    .035       0  5004.4     .05       0
#XS Ineff= 2 , 0
         4802.56 1605.83
Permanent Ineff=
       T       T
Bank Sta=4958.3,5151.4
XS Rating Curve= 0 ,0
Exp/Cntr=0.3,0.1

Type RM Length L Ch R = 1 ,10324   ,320,320,320
BEGIN DESCRIPTION:
BARONS CREEK 14.0
END DESCRIPTION:
XS GIS Cut Line= 2
      2767723.08     10055775.04      2766076.17     10056568.31
#Sta/Elev= 30
  3616.2 1624.42  3654.6 1622.27    3671 1623.55  3699.2 1623.65  3761.5 1616.79
  3803.2 1614.37  3874.6 1608.83  3909.9 1607.05  3932.1 1607.44  3993.3  1602.9
    4129  1598.9  4343.7 1598.71  4524.7 1600.95  4779.1 1599.87  4869.5 1601.21
  4921.8 1593.21  4954.2 1588.37  4965.6 1585.33  5002.3 1582.14    5005 1581.64
  5008.3 1582.14  5033.4 1589.18  5118.4 1592.73  5169.2 1595.63  5214.4 1601.32
  5259.7 1604.89  5310.5 1605.92  5350.1 1612.38  5398.7 1614.28  5444.2 1614.54
#Mann= 7 ,-1 , 0
  3616.2     .16       0  3803.2     .05       0  4921.8      .1       0
  4954.2     .05       0  5002.3     .03       0  5008.3     .05       0
  5398.7     .08       0
#XS Ineff= 2 , 0
         4863.64 1601.28
Permanent Ineff=
       T       T
Bank Sta=4921.8,5118.4
XS Rating Curve= 0 ,0
Exp/Cntr=0.3,0.1

Type RM Length L Ch R = 1 ,10004   ,144,144,144
BEGIN DESCRIPTION:
Mapping XS dbab3a07
END DESCRIPTION:
XS GIS Cut Line= 2
       2767244.5     10054964.57      2766145.17     10056365.67
#Sta/Elev= 30
    3592 1608.99    3676  1606.9    3995  1595.9  4015.8  1598.9  4044.7 1589.86
  4051.1 1594.24    4080 1597.28  4094.4 1594.42  4193.9 1597.42  4675.6 1596.13
  4706.4 1596.34  4728.1 1598.75  4742.6 1594.76  4771.5 1595.34  4777.8 1598.04
  4792.3 1593.26  4813.1 1593.14  4855.1 1589.86    4978 1583.32  5002.6 1581.39
  5005.4 1580.89  5008.6 1581.39  5024.3 1582.02  5034.5 1582.47  5055.3 1593.28
  5084.3 1599.04    5099 1595.86  5193.5 1602.17  5219.9 1603.36  5372.9 1608.19
#Mann= 12 ,-1 , 0
    3592     .08       0    3676     .05       0  4675.6     .08       0
  4706.4     .05       0  4855.1     .08       0    4978     .05       0
  5002.6     .04       0  5008.6     .05       0  5024.3      .1       0
    5099     .05       0  5193.5      .1       0  5219.9     .08       0
#XS Ineff= 6 ,-1
    3592 4728.48 1598.78 4730.34 4777.78 1598.04 5069.75 5081.26 1597.49
 5084.28 5118.89 1599.04  5119.5 5130.48 1599.21 5134.03 5166.22 1600.35
Permanent Ineff=
       T       T       T       T       T       T
Bank Sta=4813.1,5055.3
XS Rating Curve= 0 ,0
Exp/Cntr=0.3,0.1

Type RM Length L Ch R = 1 ,9860    ,704,704,704
BEGIN DESCRIPTION:
Mapping XS 58b652fc
END DESCRIPTION:
XS GIS Cut Line= 2
      2767197.06     10054912.85      2766020.12     10056335.52
#Sta/Elev= 30
  3672.8  1610.2  3803.1 1606.47  3977.7 1597.14  3992.1 1600.25  4055.9 1594.41
  4084.6 1597.22  4105.4 1592.27  4113.2 1594.61  4119.7 1590.68  4127.6 1593.17
    4134  1587.4  4148.4 1596.32  4432.3 1592.73  4752.3 1595.31    4756 1596.01
  4837.4 1592.81  4858.3 1586.07  4901.3 1583.35  4982.9 1580.45  4985.7 1579.95
  4988.9 1580.45  5024.5 1585.25  5028.9 1589.09  5049.7 1592.86  5092.7 1604.99
  5136.8 1606.53  5147.7 1606.74    5271 1609.89  5300.2  1610.9  5519.2 1614.37
#Mann= 12 ,-1 , 0
  3672.8     .08       0  3803.1     .05       0  4752.3     .08       0
    4756     .05       0  4901.3     .08       0  4982.9     .07       0
  4988.9     .08       0  5024.5     .05       0  5136.8     .08       0
  5147.7     .05       0    5271      .1       0  5300.2     .08       0
#XS Ineff= 6 ,-1
 3897.44 3942.18 1600.99 3944.91 3991.28 1600.28 3996.74  4020.2 1598.66
 4025.11 4084.58 1597.16 4085.67 4744.19  1596.9 4748.01 4787.29 1596.17
Permanent Ineff=
       T       T       T       T       T       T
Bank Sta=4837.4,5049.7
XS Rating Curve= 0 ,0
Exp/Cntr=0.3,0.1

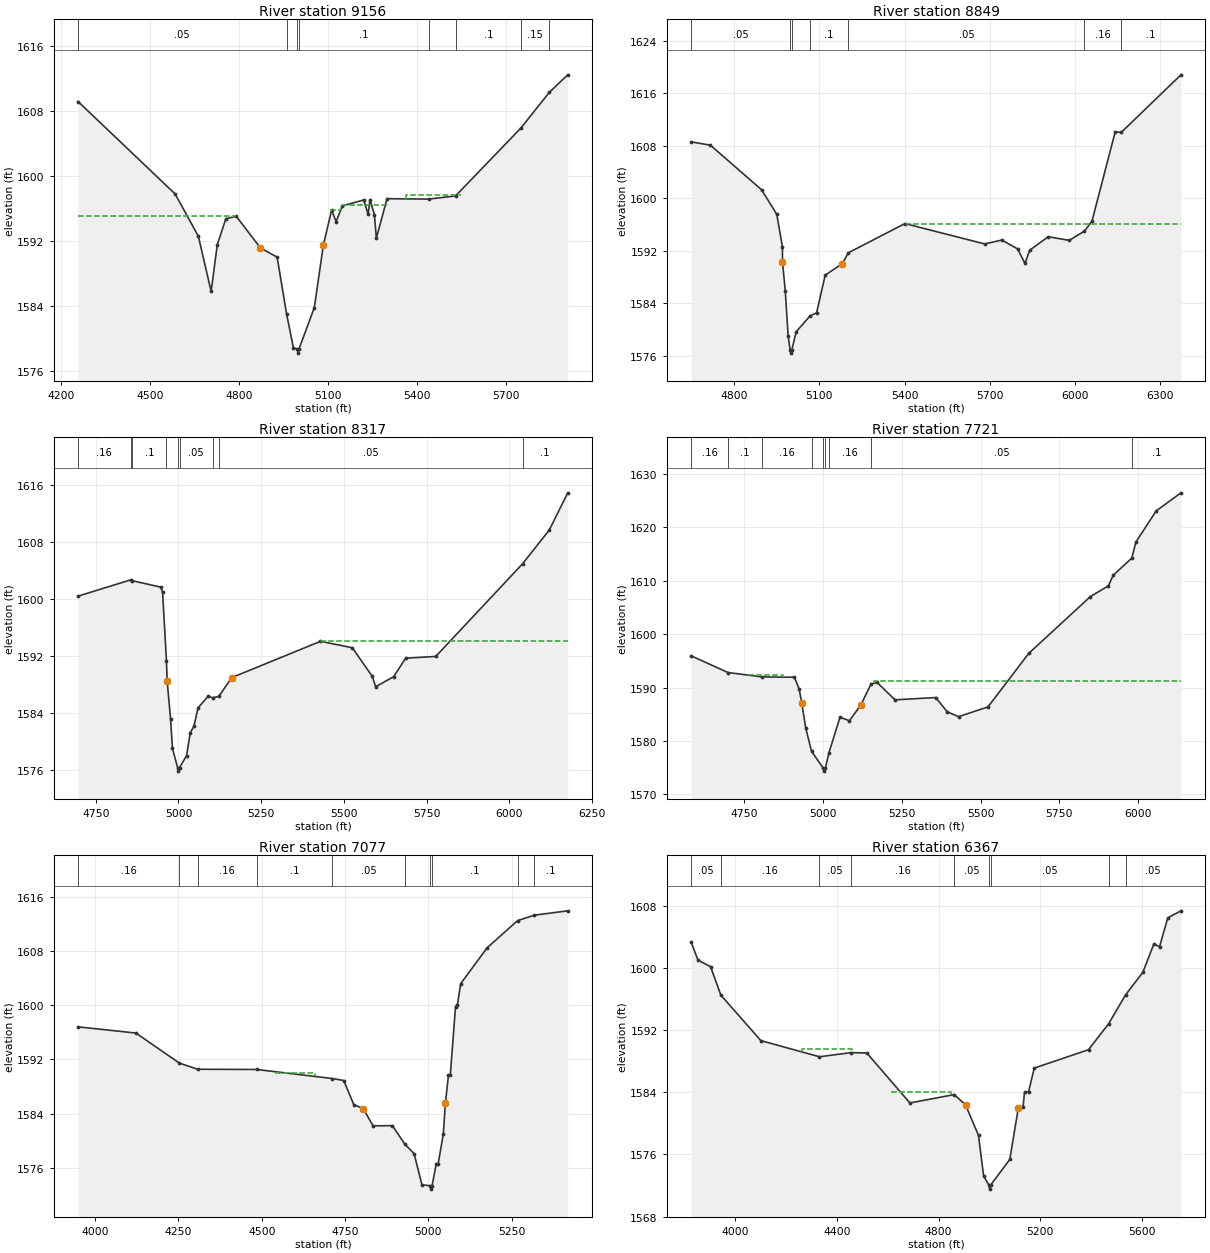
Type RM Length L Ch R = 1 ,9156    ,307,307,307
BEGIN DESCRIPTION:
Mapping XS 40db944e
END DESCRIPTION:
XS GIS Cut Line= 4
      2767149.68     10054873.99      2766787.53     10055322.38
      2766515.92     10055283.58      2766071.85     10055951.85
#Sta/Elev= 30
  4256.5 1609.19  4584.3 1597.82  4662.7 1592.62  4705.8 1585.83  4726.6 1591.59
  4755.4 1594.77  4790.6 1595.08  4872.3 1591.18  4928.6 1590.05  4960.4 1583.08
  4983.4 1578.93  4996.3 1578.75  4999.1 1578.25  5002.3 1578.75  5054.2 1583.86
  5084.5 1591.51  5112.5 1595.84  5127.6 1594.42  5148.6 1596.36  5220.8 1597.08
  5235.8 1595.31  5241.8 1597.14  5256.9 1595.28  5263.5 1592.39  5299.5 1597.24
    5440 1597.19  5530.9 1597.58  5752.4 1605.97  5847.1 1610.31  5909.6 1612.47
#Mann= 8 ,-1 , 0
  4256.5     .05       0  4960.4      .1       0  4996.3     .07       0
  5002.3      .1       0    5440     .08       0  5530.9      .1       0
  5752.4     .15       0  5847.1      .1       0
#XS Ineff= 4 ,-1
  4256.5 4790.11 1595.13 5111.93 5146.31 1595.85 5148.82 5301.69 1596.41
 5364.53 5550.86 1597.73
Permanent Ineff=
       T       T       T       T
Bank Sta=4872.3,5084.5
XS Rating Curve= 0 ,0
Exp/Cntr=0.3,0.1

Type RM Length L Ch R = 1 ,8849    ,532,532,532
BEGIN DESCRIPTION:
BARONS CREEK 13.0
END DESCRIPTION:
XS GIS Cut Line= 4
      2767016.04     10054848.11      2766916.86     10055024.91
      2766015.82      10055098.2       2765412.9     10054960.39
#Sta/Elev= 30
  4648.3 1608.57  4716.3 1608.05  4896.4 1601.26  4949.7 1597.53  4969.8 1592.55
 4969.95 1590.23  4979.8 1585.87  4989.9 1578.96  4996.9 1576.87  4999.7 1576.37
  5002.9 1576.87  5018.2 1579.63  5066.7 1582.03  5090.2 1582.52  5120.3 1588.25
  5180.5    1590  5201.9 1591.66  5401.2 1596.11  5682.1 1593.01  5742.3  1593.6
    5798 1592.26  5824.1 1590.04    5841 1592.06  5906.2 1594.11  5980.1 1593.55
  6033.8 1594.97  6060.1 1596.48  6142.1 1610.11    6163    1610  6373.5 1618.78
#Mann= 7 ,-1 , 0
  4648.3     .05       0  4996.9    .035       0  5002.9     .05       0
  5066.7      .1       0  5201.9     .05       0  6033.8     .16       0
    6163      .1       0
#XS Ineff= 2 , 0
                         5401.17         1596.11
Permanent Ineff=
       T       T
Bank Sta=4969.95,5180.5
XS Rating Curve= 0 ,0
Exp/Cntr=0.3,0.1

Type RM Length L Ch R = 1 ,8317    ,596,596,596
BEGIN DESCRIPTION:
BARONS CREEK 12.0
END DESCRIPTION:
XS GIS Cut Line= 3
      2766873.09     10054433.86      2766190.81      10054709.9
      2765452.79     10054808.65
#Sta/Elev= 30
  4696.3  1600.4  4855.2 1602.68  4860.9 1602.56  4946.6 1601.66    4952 1600.92
  4963.6 1591.37 4965.71 1588.53  4976.1 1583.17  4981.8 1579.07  4997.3 1576.38
    5000 1575.88  5003.3 1576.38  5024.4 1578.05  5035.7 1581.28  5046.5 1582.14
  5059.3 1584.75  5089.6 1586.38    5103 1586.16  5121.8 1586.35  5161.2 1588.99
  5429.3 1594.07  5525.5 1593.17    5586 1589.15  5596.1 1587.71  5650.7 1589.12
  5686.9 1591.71  5777.7 1591.95  6040.1 1604.93  6120.7 1609.65  6176.9 1614.88
#Mann= 9 ,-1 , 0
  4696.3     .16       0  4855.2     .05       0  4860.9      .1       0
  4963.6     .05       0  4997.3    .035       0  5003.3     .05       0
    5103      .1       0  5121.8     .05       0  6040.1      .1       0
#XS Ineff= 2 , 0
                         5429.31         1594.08
Permanent Ineff=
       T       T
Bank Sta=4965.71,5161.2
XS Rating Curve= 0 ,0
Exp/Cntr=0.3,0.1

Type RM Length L Ch R = 1 ,7721    ,644,644,644
BEGIN DESCRIPTION:
BARONS CREEK 11.0
END DESCRIPTION:
XS GIS Cut Line= 3
       2766550.2     10054194.28      2766284.56     10054064.06
      2765232.97     10054756.45
#Sta/Elev= 30
    4581 1595.93  4698.2  1592.8  4805.8 1591.99  4908.8 1591.92  4923.9 1589.71
    4932 1587.09  4944.9 1582.35  4963.2 1578.04  5000.9 1574.83  5003.6 1574.33
  5006.9 1574.83  5017.8 1577.68  5053.4 1584.42  5083.5 1583.78  5119.7 1586.73
  5151.6  1590.6  5170.9 1590.97  5228.1 1587.69  5357.6 1588.12  5393.7 1585.45
  5429.9 1584.54  5523.2 1586.36  5652.7 1596.39  5848.5 1607.04  5905.7 1609.06
  5920.8 1611.03  5979.8 1614.24  5993.1 1617.27  6057.5  1623.1  6135.9 1626.48
#Mann= 9 ,-1 , 0
    4581     .16       0  4698.2      .1       0  4805.8     .16       0
  4963.2     .05       0  5000.9    .035       0  5006.9     .05       0
  5017.8     .16       0  5151.6     .05       0  5979.8      .1       0
#XS Ineff= 2 ,-1
 4760.29 4871.97 1592.35 5161.78  6135.9 1591.13
Permanent Ineff=
       T       T
Bank Sta=4932,5119.7
XS Rating Curve= 0 ,0
Exp/Cntr=0.3,0.1

Type RM Length L Ch R = 1 ,7077    ,710,710,710
BEGIN DESCRIPTION:
BARONS CREEK 10.0
END DESCRIPTION:
XS GIS Cut Line= 3
      2766742.89     10054251.56      2766607.47     10054058.86
       2765555.4     10053413.03
#Sta/Elev= 30
  3948.5 1596.82  4122.2  1595.9  4252.8 1591.46  4307.3 1590.55  4484.7 1590.52
  4711.8 1589.18  4746.1 1588.89  4776.1 1585.34  4804.7 1584.72  4834.1 1582.19
  4892.1 1582.22  4929.4 1579.49  4957.3 1578.07  4980.8 1573.48  5005.1 1573.34
  5007.9 1572.84  5011.1 1573.34  5023.6 1576.51  5029.4 1576.55  5044.9 1580.97
  5051.2 1585.56  5060.3 1589.64  5066.1 1589.77  5081.6 1599.81  5087.4 1600.11
    5097 1603.19  5176.3 1608.49  5267.7 1612.51  5318.6 1613.32  5418.5 1613.96
#Mann= 10 ,-1 , 0
  3948.5     .16       0  4252.8     .05       0  4307.3     .16       0
  4484.7      .1       0  4711.8     .05       0  4929.4      .1       0
  5005.1     .07       0  5011.1      .1       0  5267.7     .05       0
  5318.6      .1       0
#XS Ineff= 1 ,-1
 4540.45 4660.11 1590.03
Permanent Ineff=
       T
Bank Sta=4804.7,5051.2
XS Rating Curve= 0 ,0
Exp/Cntr=0.3,0.1

Type RM Length L Ch R = 1 ,6367    ,538,538,538
BEGIN DESCRIPTION:
BARONS CREEK 9.0
END DESCRIPTION:
XS GIS Cut Line= 4
      2767210.65     10054249.59      2766434.63     10053486.51
      2766408.77     10053288.19      2765843.99      10052986.4
#Sta/Elev= 30
  3825.7 1603.34  3852.6 1601.02  3902.1 1600.19  3942.5 1596.52  4100.1 1590.66
  4330.9 1588.58  4454.2 1589.11  4517.3 1589.07    4687 1582.63  4861.8 1583.71
  4906.3 1582.38  4957.2 1578.45  4977.4 1573.21  4998.5 1572.03  5001.2 1571.53
  5004.5 1572.03  5080.5 1575.36  5113.8 1581.94  5132.8 1582.16  5138.4    1584
  5154.7  1584.1  5176.6 1587.12  5390.5 1589.49  5470.1 1592.85  5536.8 1596.58
  5604.3 1599.45  5648.2 1603.14  5670.1 1602.74  5702.7 1606.48  5754.4 1607.38
#Mann= 9 ,-1 , 0
  3825.7     .05       0  3942.5     .16       0  4330.9     .05       0
  4454.2     .16       0  4861.8     .05       0  4998.5    .035       0
  5004.5     .05       0  5470.1      .1       0  5536.8     .05       0
#XS Ineff= 2 ,-1
 4262.78 4458.81 1589.52 4612.22 4848.01 1584.07
Permanent Ineff=
       T       T
Bank Sta=4906.3,5113.8
XS Rating Curve= 0 ,0
Exp/Cntr=0.3,0.1

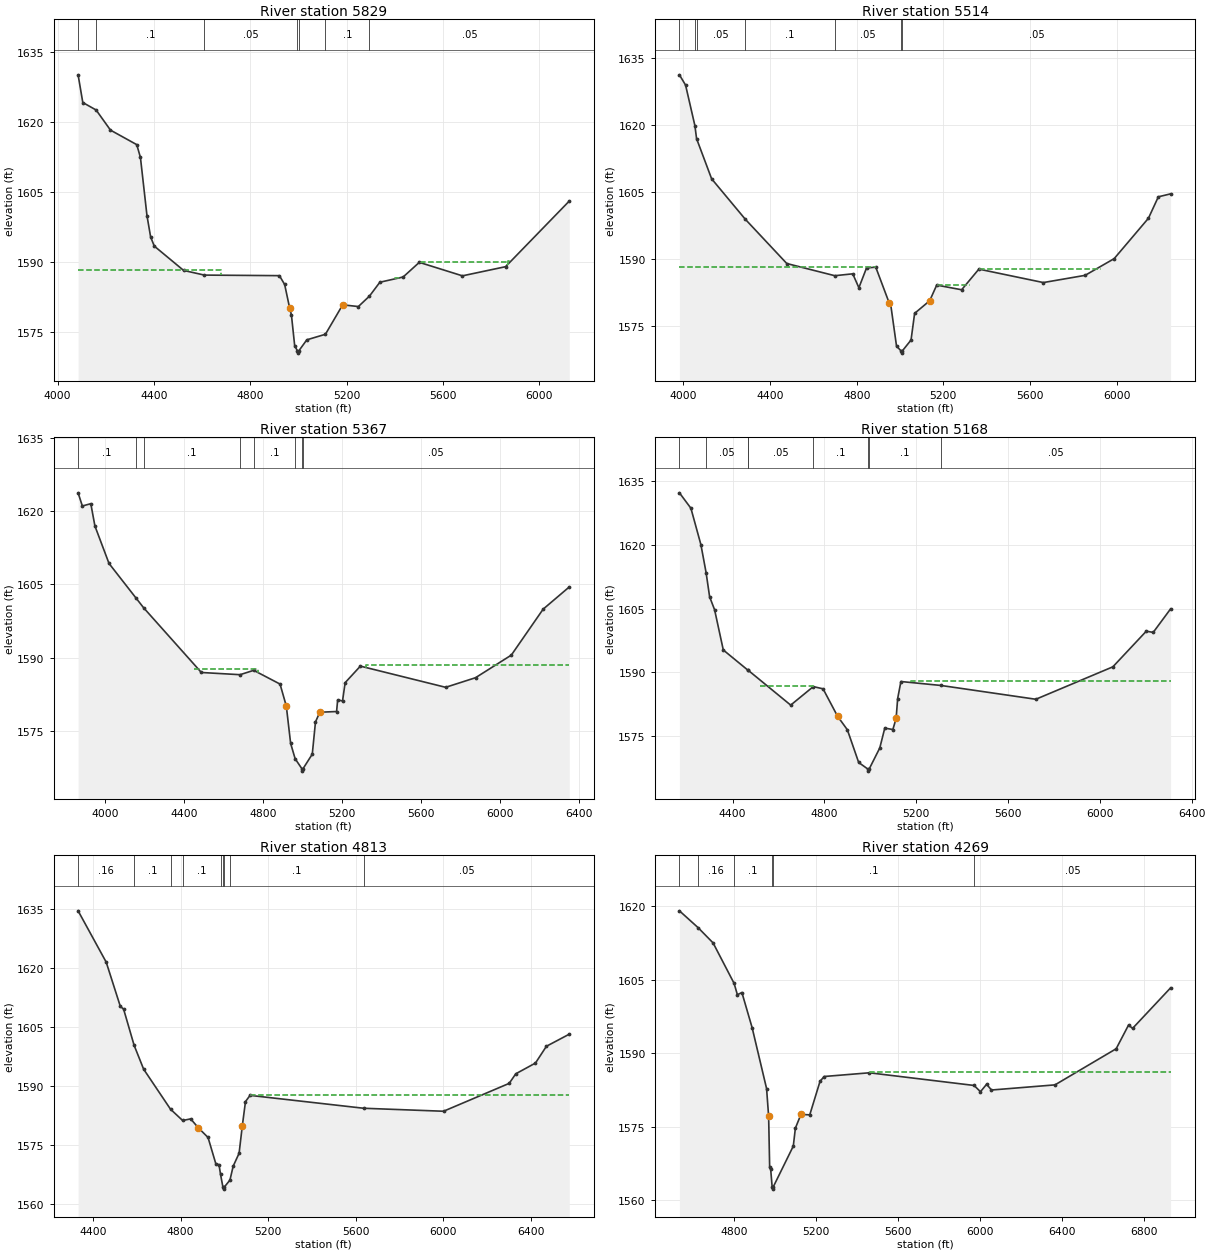
Type RM Length L Ch R = 1 ,5829    ,315,315,315
BEGIN DESCRIPTION:
Mapping XS dd967f27
END DESCRIPTION:
XS GIS Cut Line= 4
      2767697.78     10053930.54      2767029.58     10053503.75
      2766814.02     10053258.01      2765992.05     10052844.88
#Sta/Elev= 30
  4085.3 1630.09  4104.8 1624.16  4160.2 1622.55  4219.8 1618.24  4328.9 1615.13
  4344.2 1612.38  4371.3 1599.93  4386.5 1595.35  4401.7 1593.39  4523.5 1588.18
  4609.7 1587.18  4921.3 1587.06  4943.1 1585.17    4964 1580.08  4971.3  1578.6
  4984.8 1572.02  4996.1 1570.96  4998.8 1570.46  5002.1 1570.96  5035.1 1573.31
  5112.4  1574.5  5184.1 1580.81  5249.2 1580.44  5295.3 1582.68  5338.5 1585.65
  5435.1 1586.77  5502.3 1589.91  5681.3 1587.02  5860.4 1588.98    6125 1603.04
#Mann= 7 ,-1 , 0
  4085.3     .05       0  4160.2      .1       0  4609.7     .05       0
  4996.1    .035       0  5002.1     .05       0  5112.4      .1       0
  5295.3     .05       0
#XS Ineff= 5 ,-1
  4085.3 4678.98 1588.31 5400.61 5420.88 1586.51  5472.6 5493.22 1588.35
 5511.04 5867.14 1589.93 5868.54 5876.23 1590.13
Permanent Ineff=
       T       T       T       T       T
Bank Sta=4964,5184.1
XS Rating Curve= 0 ,0
Exp/Cntr=0.3,0.1

Type RM Length L Ch R = 1 ,5514    ,147,147,147
BEGIN DESCRIPTION:
Mapping XS c1a4c243
END DESCRIPTION:
XS GIS Cut Line= 6
      2767796.99     10053805.55      2767120.11     10053180.41
      2767089.93     10053141.61      2766874.37     10053055.39
      2766736.42      10052826.9      2765947.48      10052710.5
#Sta/Elev= 30
  3981.7  1631.2  4010.1  1628.9  4053.2 1619.83  4060.8 1616.95  4130.3 1607.98
  4285.7 1598.95  4477.3 1589.06  4698.9 1586.34  4781.8 1586.76    4810 1583.65
  4845.3 1588.07  4887.9 1588.25  4949.4 1580.33  4955.7 1580.33  4983.8 1570.62
  5004.7 1569.55  5007.4 1569.05  5010.7 1569.55  5050.8 1571.98  5067.3 1577.93
  5136.9 1580.75  5169.2 1584.24  5284.3  1583.2  5363.9 1587.81  5661.5 1584.81
  5854.2 1586.42  5988.4 1590.15  6146.7 1599.18  6192.3 1603.96  6248.8 1604.62
#Mann= 7 ,-1 , 0
  3981.7     .05       0  4053.2      .1       0  4060.8     .05       0
  4285.7      .1       0  4698.9     .05       0  5004.7     .04       0
  5010.7     .05       0
#XS Ineff= 3 ,-1
  3981.7 4887.81 1588.25  5169.6 5321.19 1584.26 5364.66 5927.54 1587.84
Permanent Ineff=
       T       T       T
Bank Sta=4949.4,5136.9
XS Rating Curve= 0 ,0
Exp/Cntr=0.3,0.1

Type RM Length L Ch R = 1 ,5367    ,199,199,199
BEGIN DESCRIPTION:
Mapping XS b423c8af
END DESCRIPTION:
XS GIS Cut Line= 6
      2767900.42     10053732.23      2767266.69     10053193.35
      2767197.71     10053051.08      2766964.91     10052926.05
        2766883.     10052710.49      2765887.14     10052585.47
#Sta/Elev= 30
  3863.8 1623.72  3885.3 1621.03  3928.2  1621.5    3949 1616.94  4020.4 1609.29
  4158.3 1602.16  4196.3  1600.2  4488.3    1587  4684.4 1586.55  4753.7 1587.44
    4887 1584.63  4918.7 1580.14  4940.7  1572.5  4963.4 1569.38  4997.5 1567.34
  5000.2 1566.84  5003.5 1567.34  5050.3 1570.31  5066.5 1576.89  5088.4 1578.88
  5173.5 1579.02  5178.9  1581.4  5203.6 1581.18  5216.8 1584.92    5294  1588.3
  5726.1 1583.97  5877.3 1585.93  6058.7 1590.55  6219.9 1599.94  6352.3 1604.48
#Mann= 8 ,-1 , 0
  3863.8      .1       0  4158.3     .05       0  4196.3      .1       0
  4684.4     .05       0  4753.7      .1       0  4963.4     .05       0
  4997.5     .04       0  5003.5     .05       0
#XS Ineff= 2 ,-1
 4449.95 4775.56 1587.76  5324.2  6352.3 1588.47
Permanent Ineff=
       T       T
Bank Sta=4918.7,5088.4
XS Rating Curve= 0 ,0
Exp/Cntr=0.3,0.1

Type RM Length L Ch R = 1 ,5168    ,355,355,355
BEGIN DESCRIPTION:
BARONS CREEK 8.0
END DESCRIPTION:
XS GIS Cut Line= 4
      2767818.56     10053232.17      2767262.38     10052926.05
      2766904.55     10052607.03       2765883.1     10052516.52
#Sta/Elev= 30
  4168.5 1632.25  4218.5 1628.62  4262.1 1620.03  4284.7 1613.44    4300 1607.76
  4321.7  1604.7  4359.6 1595.23  4467.8 1590.43  4468.9 1590.41  4653.2 1582.24
  4751.7  1586.6  4794.2 1586.08  4857.5 1579.61  4900.1 1576.43  4949.4 1568.73
  4989.1 1567.19  4991.8 1566.69  4995.1 1567.19  5041.4 1572.16  5063.1 1576.83
  5098.3 1576.49  5112.5 1579.09  5119.2 1583.78  5133.4  1587.8  5307.8 1586.87
  5721.1 1583.62  6056.7 1591.26  6202.4 1599.66  6232.5 1599.37  6308.2 1604.91
#Mann= 8 ,-1 , 0
  4168.5      .1       0  4284.7     .05       0  4467.8      .1       0
  4468.9     .05       0  4751.7      .1       0  4989.1     .07       0
  4995.1      .1       0  5307.8     .05       0
#XS Ineff= 2 ,-1
 4520.33 4750.91 1586.68 5176.13  6308.2 1588.03
Permanent Ineff=
       T       T
Bank Sta=4857.5,5112.5
XS Rating Curve= 0 ,0
Exp/Cntr=0.3,0.1

Type RM Length L Ch R = 1 ,4813    ,544,544,544
BEGIN DESCRIPTION:
BARONS CREEK 7.0
END DESCRIPTION:
XS GIS Cut Line= 3
      2767909.03     10052973.45      2767176.16     10052430.27
      2765844.04      10052443.2
#Sta/Elev= 30
  4331.9 1634.45  4460.3 1621.42    4525 1610.16  4539.7 1609.51  4587.8 1600.31
  4631.4 1594.23  4754.2 1584.07  4809.6  1581.2  4846.4 1581.61  4881.9 1579.31
  4925.7 1576.89  4961.2 1570.22  4975.8 1569.97  4982.8 1567.52  4993.7 1564.27
  4996.4 1563.77  4999.7 1564.27  5025.8 1566.07  5040.5 1569.59  5067.6 1572.88
  5082.2  1579.8  5096.8 1586.01  5117.7 1587.58  5636.6 1584.31  6001.8 1583.55
  6301.9 1590.63  6331.9 1593.06  6421.9 1595.79  6471.9 1600.05  6576.3 1603.12
#Mann= 9 ,-1 , 0
  4331.9     .16       0  4587.8      .1       0  4754.2     .05       0
  4809.6      .1       0  4982.8     .05       0  4993.7    .035       0
  4999.7     .05       0  5025.8      .1       0  5636.6     .05       0
#XS Ineff= 2 , 0
                         5117.79         1587.58
Permanent Ineff=
       T       T
Bank Sta=4881.9,5082.2
XS Rating Curve= 0 ,0
Exp/Cntr=0.3,0.1

Type RM Length L Ch R = 1 ,4269    ,1378,1378,1378
BEGIN DESCRIPTION:
BARONS CREEK 6.0
END DESCRIPTION:
XS GIS Cut Line= 2
      2768202.23     10052180.22      2765813.87     10052335.42
#Sta/Elev= 30
  4535.2 1619.07    4626 1615.64  4699.3 1612.51  4801.7 1604.24  4817.6 1601.93
  4839.6 1602.38  4889.7 1595.16  4959.9 1582.75  4969.9 1577.08  4974.9 1566.68
  4979.9 1566.27  4986.9 1562.71  4989.7 1562.21  4992.9 1562.71  5090.1    1571
  5100.2 1574.66  5127.2 1577.46  5170.3 1577.39  5220.4 1584.24  5240.5 1585.22
  5460.9 1585.98  5971.2 1583.39  6002.1 1582.11  6032.1 1583.64  6055.8 1582.46
  6365.3 1583.51  6663.4 1590.89  6723.6 1595.72  6743.6 1595.06  6928.6 1603.33
#Mann= 6 ,-1 , 0
  4535.2      .1       0    4626     .16       0  4801.7      .1       0
  4986.9     .07       0  4992.9      .1       0  5971.2     .05       0
#XS Ineff= 2 , 0
                         5461.65         1586.21
Permanent Ineff=
       T       T
Bank Sta=4969.9,5127.2
XS Rating Curve= 0 ,0
Exp/Cntr=0.3,0.1

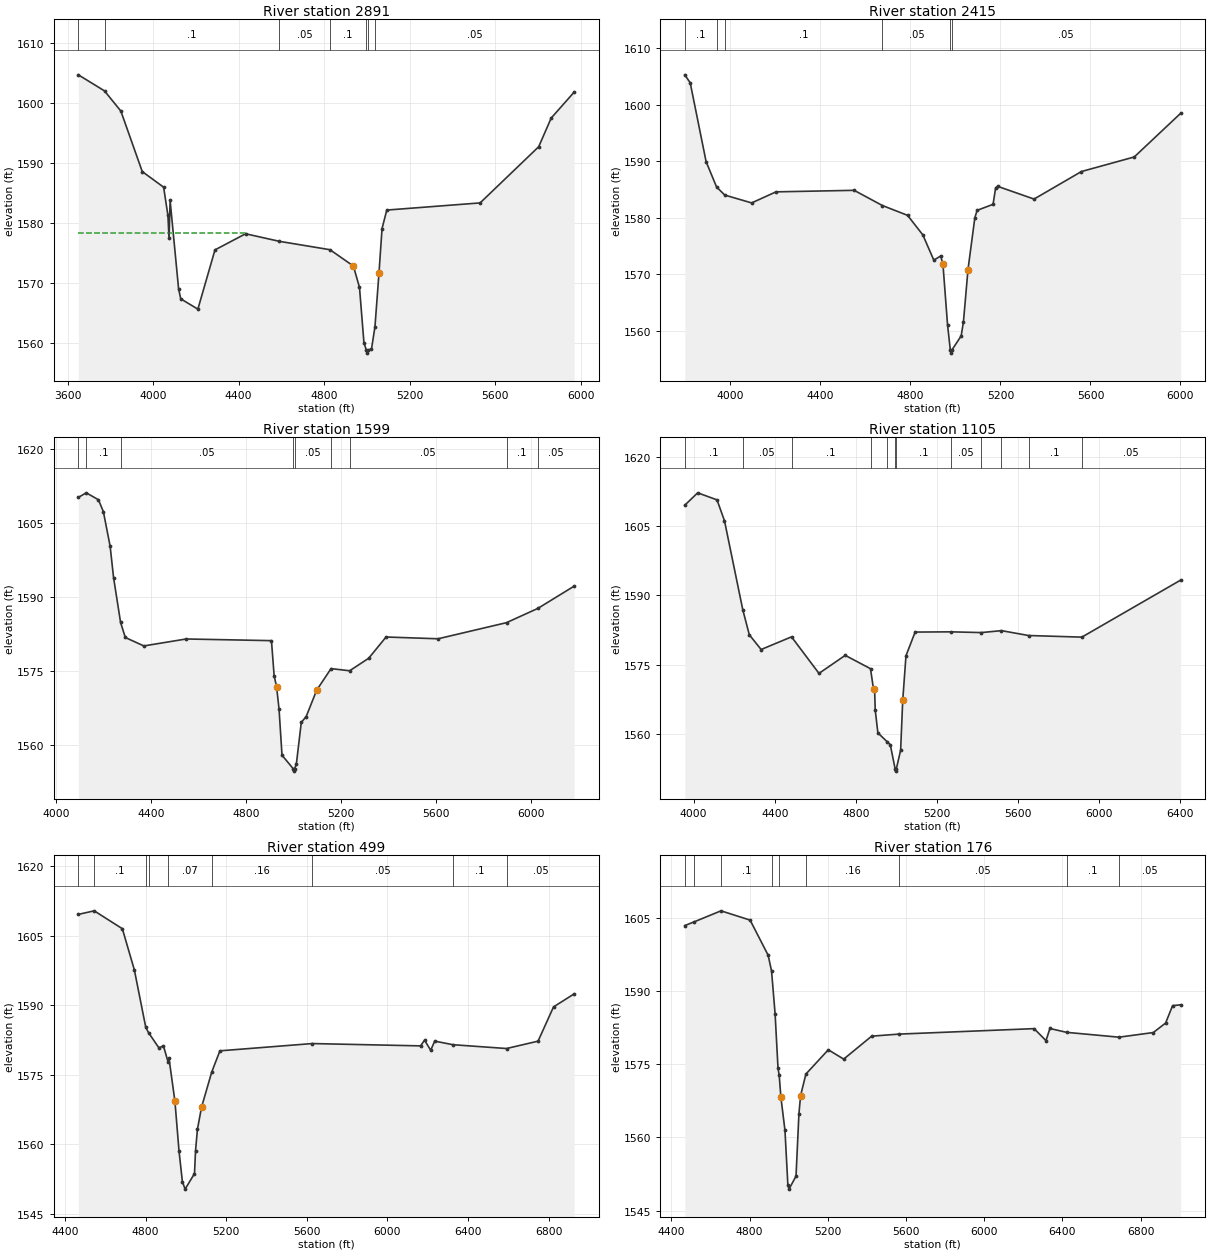
Type RM Length L Ch R = 1 ,2891    ,476,476,476
BEGIN DESCRIPTION:
BARONS CREEK 5.0
END DESCRIPTION:
XS GIS Cut Line= 4
       2768077.2     10051770.66      2767003.71     10051740.48
      2766645.88     10052037.95      2765871.68     10052128.27
#Sta/Elev= 30
  3650.6 1604.64    3773 1601.97  3849.4 1598.62  3949.5 1588.56  4049.5 1585.96
  4069.5 1581.28  4074.8 1577.44  4079.8 1583.77  4119.5 1569.05  4129.5 1567.41
  4209.6 1565.69  4289.6 1575.54  4432.8 1578.22  4591.3 1576.96  4827.4 1575.57
  4936.8 1572.86  4965.4 1569.31  4986.3 1560.09  4997.6 1558.88  5000.4 1558.38
  5003.6 1558.88  5021.5 1559.03  5037.8 1562.78  5056.6 1571.69  5070.9 1579.09
  5093.1 1582.16  5529.5 1583.35  5803.5 1592.69  5861.8 1597.45  5969.3 1601.77
#Mann= 7 ,-1 , 0
  3650.6     .05       0    3773      .1       0  4591.3     .05       0
  4827.4      .1       0  4997.6     .07       0  5003.6      .1       0
  5037.8     .05       0
#XS Ineff= 2 , 0
         4433.24 1578.31
Permanent Ineff=
       T       T
Bank Sta=4936.8,5056.6
XS Rating Curve= 0 ,0
Exp/Cntr=0.3,0.1

Type RM Length L Ch R = 1 ,2415    ,816,816,816
BEGIN DESCRIPTION:
BARONS CREEK 4.0
END DESCRIPTION:
XS GIS Cut Line= 2
      2767921.99     10051701.68      2765744.87      10051361.1
#Sta/Elev= 30
    3797  1605.3    3821 1603.89  3891.7 1589.92  3938.1 1585.44  3974.6    1584
  4094.1 1582.61  4202.3 1584.57  4549.6 1584.84  4675.1 1582.15    4787 1580.41
  4854.8 1576.95  4903.8 1572.47  4934.2 1573.21  4944.3 1571.76  4964.6 1561.07
  4977.2  1556.5    4980    1556  4983.2  1556.5  5025.3 1559.05  5035.4 1561.55
  5055.6  1570.8    5086 1579.97  5096.1 1581.29    5167 1582.36  5178.5 1585.28
  5187.2 1585.55  5349.2 1583.29  5559.8 1588.17  5794.5 1590.75  6000.6 1598.48
#Mann= 6 ,-1 , 0
    3797      .1       0  3938.1     .05       0  3974.6      .1       0
  4675.1     .05       0  4977.2     .04       0  4983.2     .05       0
Bank Sta=4944.3,5055.6
XS Rating Curve= 0 ,0
Exp/Cntr=0.3,0.1

Type RM Length L Ch R = 1 ,1599    ,494,494,494
BEGIN DESCRIPTION:
BARONS CREEK 3.0
END DESCRIPTION:
XS GIS Cut Line= 3
      2768016.81     10051654.24      2767408.96     10051145.54
      2766163.26     10050792.09
#Sta/Elev= 30
  4094.7 1610.13    4128 1611.06  4179.2 1609.66  4200.1 1607.25  4228.7 1600.19
    4243 1593.88  4272.6 1584.76  4292.5 1581.71  4370.5    1580  4548.8 1581.41
  4907.8 1581.07    4919 1573.98  4929.4  1571.7  4939.8 1567.14  4952.2 1557.83
  4999.2  1555.1  5001.9  1554.6  5005.2  1555.1  5012.6 1556.03  5033.4 1564.49
  5053.9 1565.66  5098.2 1571.03  5158.7  1575.4  5236.9 1574.96  5317.2  1577.5
  5390.3 1581.81  5609.3 1581.45  5897.4 1584.72  6029.6 1587.62  6182.2 1592.13
#Mann= 9 ,-1 , 0
  4094.7     .05       0    4128      .1       0  4272.6     .05       0
  4999.2    .035       0  5005.2     .05       0  5158.7      .1       0
  5236.9     .05       0  5897.4      .1       0  6029.6     .05       0
Bank Sta=4929.4,5098.2
XS Rating Curve= 0 ,0
Exp/Cntr=0.3,0.1

Type RM Length L Ch R = 1 ,1105    ,606,606,606
BEGIN DESCRIPTION:
BARONS CREEK 2.0
END DESCRIPTION:
XS GIS Cut Line= 4
      2768107.39     10051671.54      2767624.52     10050869.62
       2767577.1     10050636.82       2766311.5     10050511.98
#Sta/Elev= 30
  3956.2 1609.63  4019.9 1612.31  4115.1 1610.78    4152 1606.23  4242.2  1586.9
  4274.3 1581.47  4332.6 1578.26  4482.6 1581.01    4618 1573.07  4747.4 1576.99
  4872.1 1574.09    4887 1569.63  4892.3 1569.63  4895.4  1565.1  4908.5 1560.14
    4954 1558.23  4969.7 1557.56  4993.5 1552.33  4996.2 1551.83  4999.5 1552.33
  5020.7 1556.38    5031  1567.2  5047.1 1576.91  5092.2 1582.05    5270  1582.1
  5419.2 1581.94  5517.9 1582.36  5651.8  1581.3  5914.4 1580.95  6401.6 1593.34
#Mann= 12 ,-1 , 0
  3956.2      .1       0  4242.2     .05       0  4482.6      .1       0
  4872.1     .05       0    4954      .1       0  4993.5     .07       0
  4999.5      .1       0    5270     .05       0  5419.2      .1       0
  5517.9     .05       0  5651.8      .1       0  5914.4     .05       0
Bank Sta=4887,5031
XS Rating Curve= 0 ,0
Exp/Cntr=0.3,0.1

Type RM Length L Ch R = 1 ,499     ,323,323,323
BEGIN DESCRIPTION:
Mapping XS f8739683
END DESCRIPTION:
XS GIS Cut Line= 5
      2768187.09     10051602.87      2768002.21     10051191.46
      2768051.69     10050902.39      2767666.27     10050548.23
      2766480.23     10050428.58
#Sta/Elev= 30
  4466.7 1609.59  4545.4 1610.36    4685  1606.5  4744.6 1597.61  4801.3 1585.19
    4815 1584.06  4865.9  1580.8  4889.1 1581.18  4912.2 1577.69  4916.2 1578.59
  4945.9 1569.25  4966.2 1558.48  4982.9 1551.89  4996.4 1550.27    5043 1553.63
  5048.1 1558.54  5057.5 1563.16  5077.8 1567.94  5128.5 1575.55  5169.1 1580.13
  5626.9  1581.7  6164.4  1581.2  6184.5 1582.44  6214.7 1580.25  6234.8 1582.23
  6325.2 1581.45  6591.2 1580.63  6747.4 1582.22  6824.1 1589.61  6926.5 1592.43
#Mann= 9 ,-1 , 0
  4466.7     .05       0  4545.4      .1       0  4801.3     .05       0
    4815      .1       0  4912.2     .07       0  5128.5     .16       0
  5626.9     .05       0  6325.2      .1       0  6591.2     .05       0
Bank Sta=4945.9,5077.8
XS Rating Curve= 0 ,0
Exp/Cntr=0.3,0.1

Type RM Length L Ch R = 1 ,176     ,0,0,0
BEGIN DESCRIPTION:
BARONS CREEK 1.0
END DESCRIPTION:
XS GIS Cut Line= 4
      2768608.97      10051477.9      2768205.33      10050907.6
      2767692.31     10050509.17      2766517.83     10050326.87
#Sta/Elev= 30
  4468.1 1603.38    4517 1604.16  4653.3  1606.4  4802.2  1604.5  4894.5 1597.31
    4912 1594.07  4930.1 1585.31  4944.9 1574.24  4951.1 1572.71  4959.7 1568.25
  4980.6 1561.43  4995.4 1550.28  5001.3  1549.4  5037.2 1552.07    5052 1564.83
  5060.6 1568.57  5087.7 1572.97  5202.3 1577.94  5281.1 1576.03  5424.1 1580.73
  5563.3 1581.15  6255.4 1582.27  6316.1 1579.81    6336  1582.3  6421.7 1581.51
  6689.5 1580.52    6865 1581.47    6928 1583.41  6963.8 1586.98  7004.9 1587.15
#Mann= 9 ,-1 , 0
  4468.1      .1       0    4517     .05       0  4653.3      .1       0
    4912     .16       0  4951.1     .07       0  5087.7     .16       0
  5563.3     .05       0  6421.7      .1       0  6689.5     .05       0
Bank Sta=4959.7,5060.6
XS Rating Curve= 0 ,0
Exp/Cntr=0.3,0.1

Chan Stop Cuts=-1
Use User Specified Reach Order=0
Composite Channel Slope=5