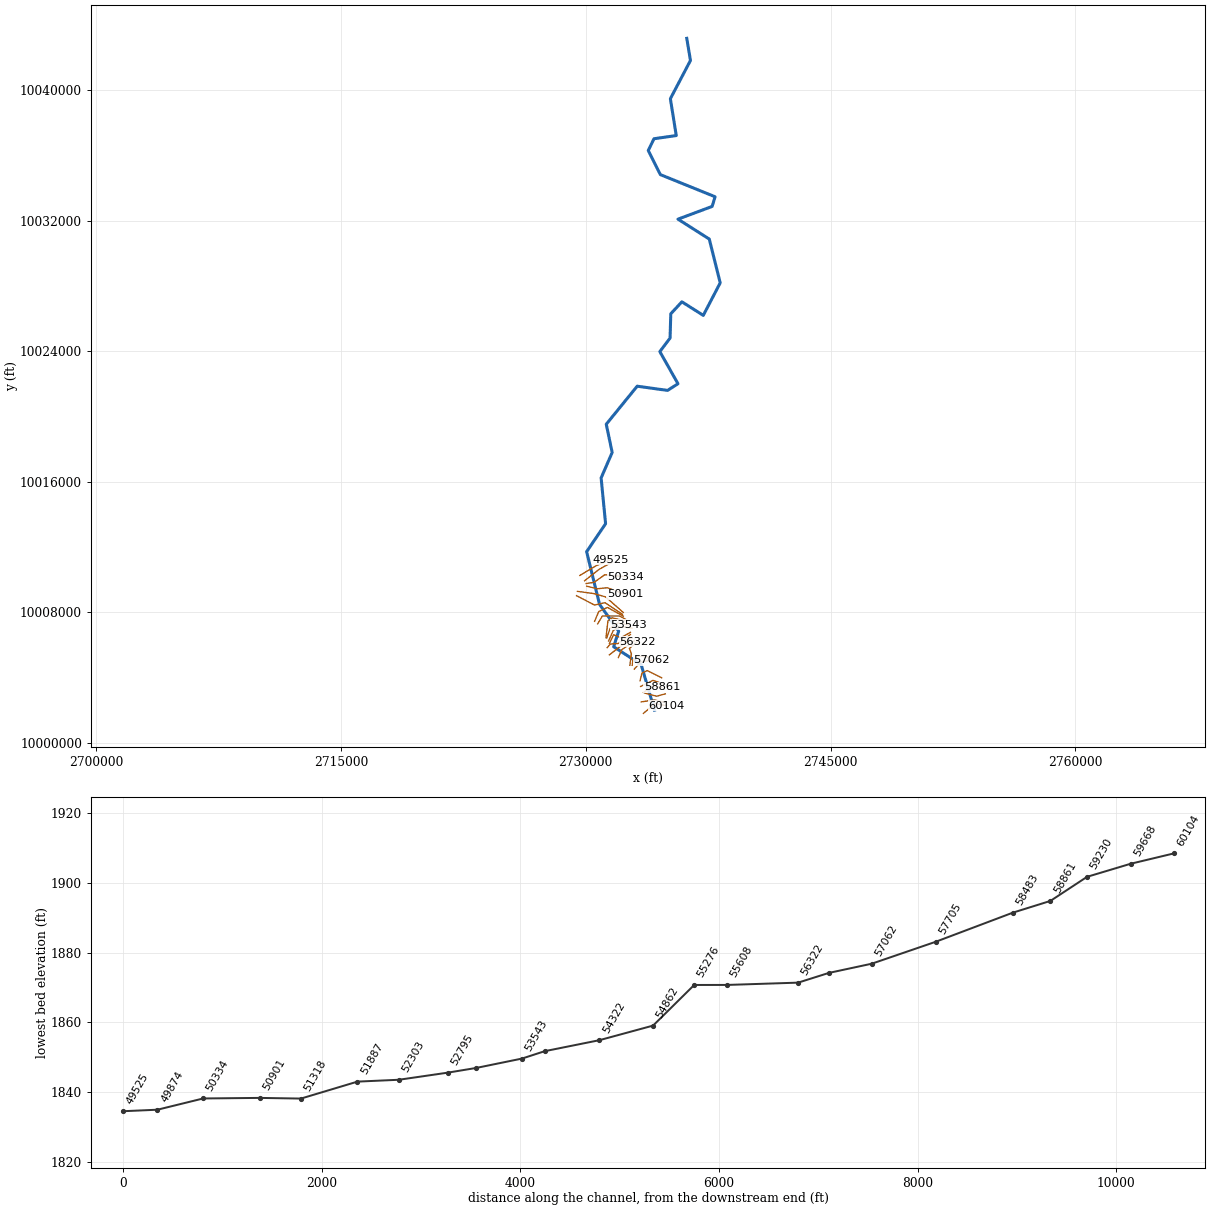
--- BEAR CREEK.prj (project) ---

Proj Title=BEAR CREEK Base Level Engineering
Current Plan=p01
Default Exp/Contr=0.3,0.1
English Units
Geom File=g01
Flow File=f01
Plan File=p01
Y Axis Title=Elevation
X Axis Title(PF)=Main Channel Distance
X Axis Title(XS)=Station
BEGIN DESCRIPTION:
BEAR CREEK
END DESCRIPTION:
DSS Export Rating Curves= 0
DSS Export Rating Curve Sorted= 0
DSS Export Volume Flow Curves= 0
DXF OffsetX= 0
DXF OffsetY= 0
DXF ScaleX= 1
DXF ScaleY= 10

--- BEAR CREEK.p01 (plan) ---

Plan Title=Multiple Run
Short Identifier=Multiple
Geom File=g01
Flow File=f01
Subcritical Flow
K Sum by GR= 0
Std Step Tol= 0.01
Critical Tol= 0.01
Num of Std Step Trials= 20
Max Error Tol= 0.3
Flow Tol Ratio= 0.001
Split Flow NTrial= 30
Split Flow Tol= 0.02
Split Flow Ratio= 0.02
Log Output Level= 0
Friction Slope Method= 1
Unsteady Friction Slope Method= 2
Unsteady Bridges Friction Slope Method= 1
Parabolic Critical Depth
Global Vel Dist=  1 , 1 , 1
Global Log Level= 0
CheckData=True
Encroach Param= -1, 0, 0, 0
BEGIN DESCRIPTION:
Multiple Run
END DESCRIPTION:

--- BEAR CREEK.f01 (steady flow) ---

Flow Title=Multiple
Program Version=4.10
Number of Profiles= 7
Profile Names=10-year,25-year,50-year,1pct_min,100-year,1pct_plu,500-year
River Rch & RM=BEAR CREEK,Reach-1         ,60104
    1261    1851    2369    2216    2997    4053    4816
River Rch & RM=BEAR CREEK,Reach-1         ,56322
    2194    3298    4288    4067    5500    7438    9089
River Rch & RM=BEAR CREEK,Reach-1         ,55608
    2194    3298    4288    4067    5500    7438    9089
River Rch & RM=BEAR CREEK,Reach-1         ,51887
    2810    4271    5594    5339    7221    9765   12090
River Rch & RM=BEAR CREEK,Reach-1         ,51318
    2810    4271    5594    5339    7221    9765   12090
River Rch & RM=BEAR CREEK,Reach-1         ,49874
    2990    4546    5954    5680    7682   10389   12853
River Rch & RM=BEAR CREEK,Reach-1         ,44602
    3838    5884    7750    7430   10049   13589   16974
River Rch & RM=BEAR CREEK,Reach-1         ,43938
    3838    5884    7750    7430   10049   13589   16974
River Rch & RM=BEAR CREEK,Reach-1         ,40414
    4071    6253    8248    7917   10707   14479   18130
River Rch & RM=BEAR CREEK,Reach-1         ,39201
    4205    6463    8527    8187   11071   14973   18756
River Rch & RM=BEAR CREEK,Reach-1         ,37001
    4436    6815    8988    8623   11662   15771   19729
River Rch & RM=BEAR CREEK,Reach-1         ,30105
    4464    6845    9015    8636   11680   15795   19699
River Rch & RM=BEAR CREEK,Reach-1         ,22867
    6572   10203   13555   13088   17699   23936   30318
River Rch & RM=BEAR CREEK,Reach-1         ,22411
    6572   10203   13555   13088   17699   23936   30318
River Rch & RM=BEAR CREEK,Reach-1         ,22005
    6669   10343   13730   13246   17914   24226   30634
River Rch & RM=BEAR CREEK,Reach-1         ,21343
    6669   10343   13730   13246   17914   24226   30634
River Rch & RM=BEAR CREEK,Reach-1         ,14902
    6626   10253   13588   13085   17696   23932   30155
River Rch & RM=BEAR CREEK,Reach-1         ,7438
    7101   10991   14571   14033   18978   25665   32339
Boundary for River Rch & Prof#=BEAR CREEK,Reach-1         , 1
Up Type= 0
Dn Type= 3
Dn Slope=0.003
Boundary for River Rch & Prof#=BEAR CREEK,Reach-1         , 2
Up Type= 0
Dn Type= 3
Dn Slope=0.003
Boundary for River Rch & Prof#=BEAR CREEK,Reach-1         , 3
Up Type= 0
Dn Type= 3
Dn Slope=0.003
Boundary for River Rch & Prof#=BEAR CREEK,Reach-1         , 4
Up Type= 0
Dn Type= 3
Dn Slope=0.003
Boundary for River Rch & Prof#=BEAR CREEK,Reach-1         , 5
Up Type= 0
Dn Type= 3
Dn Slope=0.003
Boundary for River Rch & Prof#=BEAR CREEK,Reach-1         , 6
Up Type= 0
Dn Type= 3
Dn Slope=0.003
Boundary for River Rch & Prof#=BEAR CREEK,Reach-1         , 7
Up Type= 0
Dn Type= 3
Dn Slope=0.003
DSS Import GetInterval= 0
DSS Import GetPeak= 0
DSS Import FillOption= 0

--- BEAR CREEK.g01 (geometry) ---

Geom Title=Existing Conditions
Program Version=4.10

River Reach=BEAR CREEK      ,Reach-1
Reach XY= 30
      2734212.05     10001997.01      2733393.84     10004789.12
      2731709.22     10005881.31      2732016.54     10006837.83
      2730843.87     10008485.38      2730053.08     10011708.66
      2731215.24     10013425.07      2730941.34     10016232.64
      2731618.57      10017793.8      2731256.65     10019525.89
      2733151.94     10021858.01      2735011.46     10021598.71
      2735651.02     10022007.39      2734539.03     10023978.41
      2735166.23     10024809.44      2735209.97     10026298.12
       2735889.6      10027031.5      2737201.05     10026199.43
      2738237.33     10028192.95      2737568.33     10030878.67
      2735650.78     10032099.48       2737741.9     10032878.56
      2737925.04     10033472.31      2734571.56     10034830.31
      2733830.37     10036309.49      2734181.26     10037031.29
       2735544.7     10037225.36      2735184.09     10039483.83
      2736415.99     10041829.76      2736188.65     10043186.23

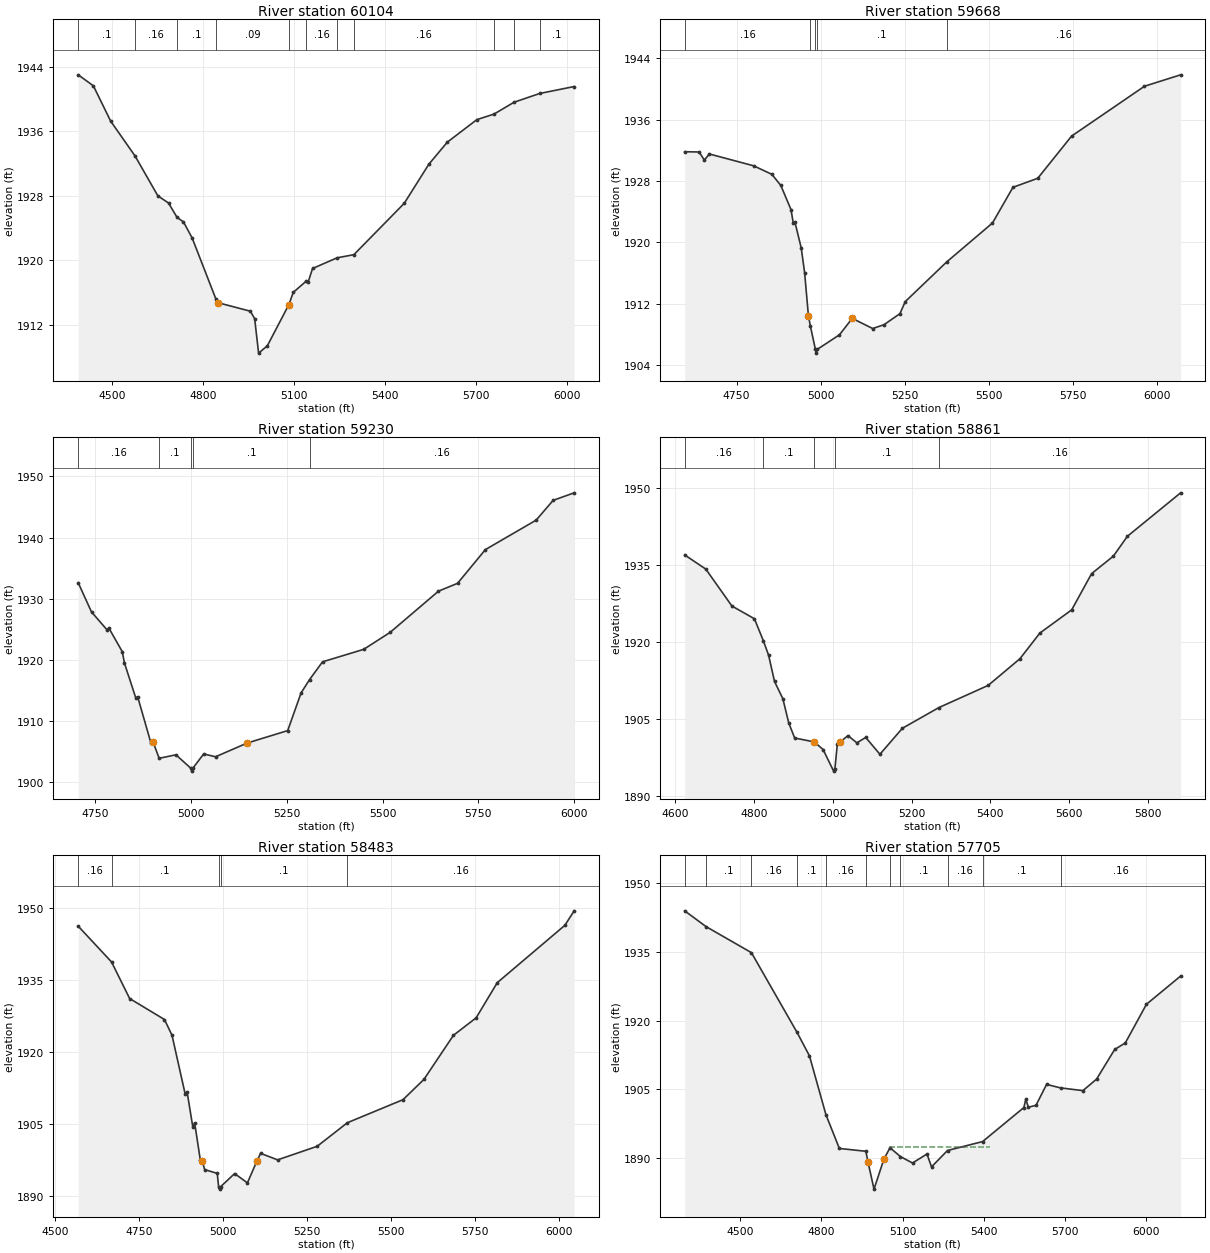
Type RM Length L Ch R = 1 ,60104   ,436,436,436
BEGIN DESCRIPTION:
BEAR CREEK 109.0
END DESCRIPTION:
XS GIS Cut Line= 3
      2733534.95     10001796.76      2734238.09     10002395.74
      2734941.19     10002274.22
#Sta/Elev= 30
  4387.7 1942.98  4437.7 1941.62  4494.8 1937.25  4575.7 1932.91  4650.7 1927.99
  4685.8 1927.11  4713.9 1925.33  4735.2 1924.77  4763.8 1922.78  4841.7 1915.27
  4849.5 1914.76    4956 1913.71  4970.2 1912.79  4983.2 1908.52  5011.9 1909.42
  5083.3 1914.54  5097.6 1916.04  5140.5 1917.44    5147 1917.34  5161.3    1919
  5242.2 1920.32  5297.7 1920.71    5464 1927.07  5545.2 1931.91  5606.1 1934.64
  5703.6 1937.43  5760.4 1938.12  5826.7 1939.59  5911.2 1940.67  6024.9 1941.53
#Mann= 11 ,-1 , 0
  4387.7      .1       0  4575.7     .16       0  4713.9      .1       0
  4841.7     .09       0  5083.3      .1       0  5140.5     .16       0
  5242.2      .1       0  5297.7     .16       0  5760.4      .1       0
  5826.7     .16       0  5911.2      .1       0
Bank Sta=4849.5,5083.3
XS Rating Curve= 0 ,0
Exp/Cntr=0.3,0.1

Type RM Length L Ch R = 1 ,59668   ,438,438,438
BEGIN DESCRIPTION:
BEAR CREEK 108.0
END DESCRIPTION:
XS GIS Cut Line= 3
      2733396.04      10002499.9      2734194.69     10002621.43
      2734844.57     10002474.13
#Sta/Elev= 30
  4595.7  1931.8  4638.6 1931.77  4654.1 1930.71    4669 1931.51  4800.5 1929.97
    4855 1928.85  4881.4 1927.41  4911.7 1924.26  4918.5 1922.51  4923.6  1922.6
  4942.1 1919.26  4952.2 1916.05 4963.52 1910.41    4969 1909.14  4984.2 1906.04
  4986.9 1905.54  4990.2 1906.04  5055.8 1907.93  5093.8 1910.07  5154.5 1908.75
    5188 1909.24  5235.4 1910.68  5251.6 1912.27    5374 1917.41  5510.7 1922.51
  5571.5 1927.16  5645.2 1928.34  5745.8 1933.84  5962.4 1940.34  6069.9 1941.83
#Mann= 5 ,-1 , 0
  4595.7     .16       0    4969      .1       0  4984.2     .07       0
  4990.2      .1       0    5374     .16       0
Bank Sta=4963.52,5093.8
XS Rating Curve= 0 ,0
Exp/Cntr=0.3,0.1

Type RM Length L Ch R = 1 ,59230   ,369,369,369
BEGIN DESCRIPTION:
BEAR CREEK 107.0
END DESCRIPTION:
XS GIS Cut Line= 3
      2733621.79     10003038.09      2734342.26     10002847.13
      2734871.73     10002994.68
#Sta/Elev= 30
  4705.1 1932.61  4739.8 1927.83    4780 1924.93  4785.1  1925.2  4820.2 1921.33
  4825.8 1919.49  4855.2  1913.8  4860.4 1913.94  4895.4 1906.31  4900.6 1906.56
  4916.4 1903.89  4960.3 1904.46  4998.7 1902.29  5001.4 1901.79  5004.7 1902.29
  5032.7  1904.6  5063.7 1904.14  5146.5 1906.39  5252.1 1908.42  5287.1 1914.59
  5309.2 1916.77  5343.1 1919.67  5450.4 1921.71  5519.2 1924.47  5645.8 1931.23
  5695.7 1932.52  5768.3 1938.03  5900.8 1942.85  5945.3 1946.09  6000.1 1947.32
#Mann= 5 ,-1 , 0
  4705.1     .16       0  4916.4      .1       0  4998.7     .07       0
  5004.7      .1       0  5309.2     .16       0
Bank Sta=4900.6,5146.5
XS Rating Curve= 0 ,0
Exp/Cntr=0.3,0.1

Type RM Length L Ch R = 1 ,58861   ,378,378,378
BEGIN DESCRIPTION:
BEAR CREEK 106.0
END DESCRIPTION:
XS GIS Cut Line= 3
      2733534.99     10003081.52      2734107.88     10003463.45
      2734672.17     10003385.31
#Sta/Elev= 30
  4624.3 1936.97    4678  1934.2  4744.1 1927.02  4801.2 1924.54    4824 1920.24
  4837.2 1917.44  4852.2 1912.33  4873.3 1908.99  4888.3 1904.26  4903.3 1901.32
    4953 1900.56  4975.4 1899.08  5002.2 1894.87  5005.5 1895.37  5011.5 1900.08
  5017.5 1900.46  5038.5 1901.79  5061.1 1900.38  5083.6 1901.43  5119.6 1898.15
  5176.7 1903.22  5269.1 1907.24  5394.2 1911.56  5474.9 1916.76  5525.4 1921.75
  5606.2 1926.28  5656.7 1933.33    5712 1936.74  5747.5  1940.6  5882.5 1949.06
#Mann= 5 ,-1 , 0
  4624.3     .16       0    4824      .1       0    4953     .07       0
  5005.5      .1       0  5269.1     .16       0
Bank Sta=4953,5017.5
XS Rating Curve= 0 ,0
Exp/Cntr=0.3,0.1

Type RM Length L Ch R = 1 ,58483   ,778,778,778
BEGIN DESCRIPTION:
BEAR CREEK 105.0
END DESCRIPTION:
XS GIS Cut Line= 3
      2733361.32     10003446.07      2734116.57     10003819.35
      2734714.48     10003611.38
#Sta/Elev= 30
  4568.9 1946.13  4668.1 1938.69  4721.9  1931.1  4825.5 1926.74  4847.9 1923.48
  4887.2 1911.23  4892.8 1911.73  4909.7 1904.47  4915.3 1905.28  4932.1 1897.59
  4937.7 1897.44    4945 1895.56  4982.6 1894.77  4986.6    1892  4989.3  1891.5
  4992.6    1892  5034.2 1894.73  5072.3  1892.8  5101.1 1897.42  5111.6 1898.93
  5162.1 1897.58  5279.9  1900.4  5369.8  1905.3  5535.1 1910.08  5597.3 1914.28
  5685.3 1923.46  5752.8 1927.09  5815.7  1934.4  6016.8 1946.31  6044.4 1949.32
#Mann= 5 ,-1 , 0
  4568.9     .16       0  4668.1      .1       0  4986.6     .07       0
  4992.6      .1       0  5369.8     .16       0
Bank Sta=4937.7,5101.1
XS Rating Curve= 0 ,0
Exp/Cntr=0.3,0.1

Type RM Length L Ch R = 1 ,57705   ,643,643,643
BEGIN DESCRIPTION:
BEAR CREEK 104.0
END DESCRIPTION:
XS GIS Cut Line= 4
      2733325.47     10003792.69      2733436.59     10004258.01
      2733762.98      10004421.2      2734651.89     10003980.22
#Sta/Elev= 30
  4293.7 1944.01  4372.8 1940.56  4540.7 1934.86  4709.6 1917.42  4755.5 1912.28
  4816.5 1899.41  4866.2 1892.02  4964.3  1891.4  4972.4    1889  4994.5 1883.12
  5031.3 1889.71  5053.7 1892.17  5092.5 1890.23    5137 1888.84  5190.5  1890.8
  5207.3 1887.99  5266.5 1891.57  5396.5 1893.53  5549.1 1900.97  5556.2 1902.78
  5565.9 1901.04  5593.9 1901.45  5633.2 1906.03  5684.8 1905.27  5767.6 1904.67
  5818.1 1907.18  5885.3 1913.68  5924.5  1915.1  6002.9 1923.57  6129.3 1929.74
#Mann= 11 ,-1 , 0
  4293.7     .16       0  4372.8      .1       0  4540.7     .16       0
  4709.6      .1       0  4816.5     .16       0  4964.3     .09       0
  5053.7     .16       0  5092.5      .1       0  5266.5     .16       0
  5396.5      .1       0  5684.8     .16       0
#XS Ineff= 1 ,-1
  5055.4 5424.72 1892.44
Permanent Ineff=
       T
Bank Sta=4972.4,5031.3
XS Rating Curve= 0 ,0
Exp/Cntr=0.3,0.1

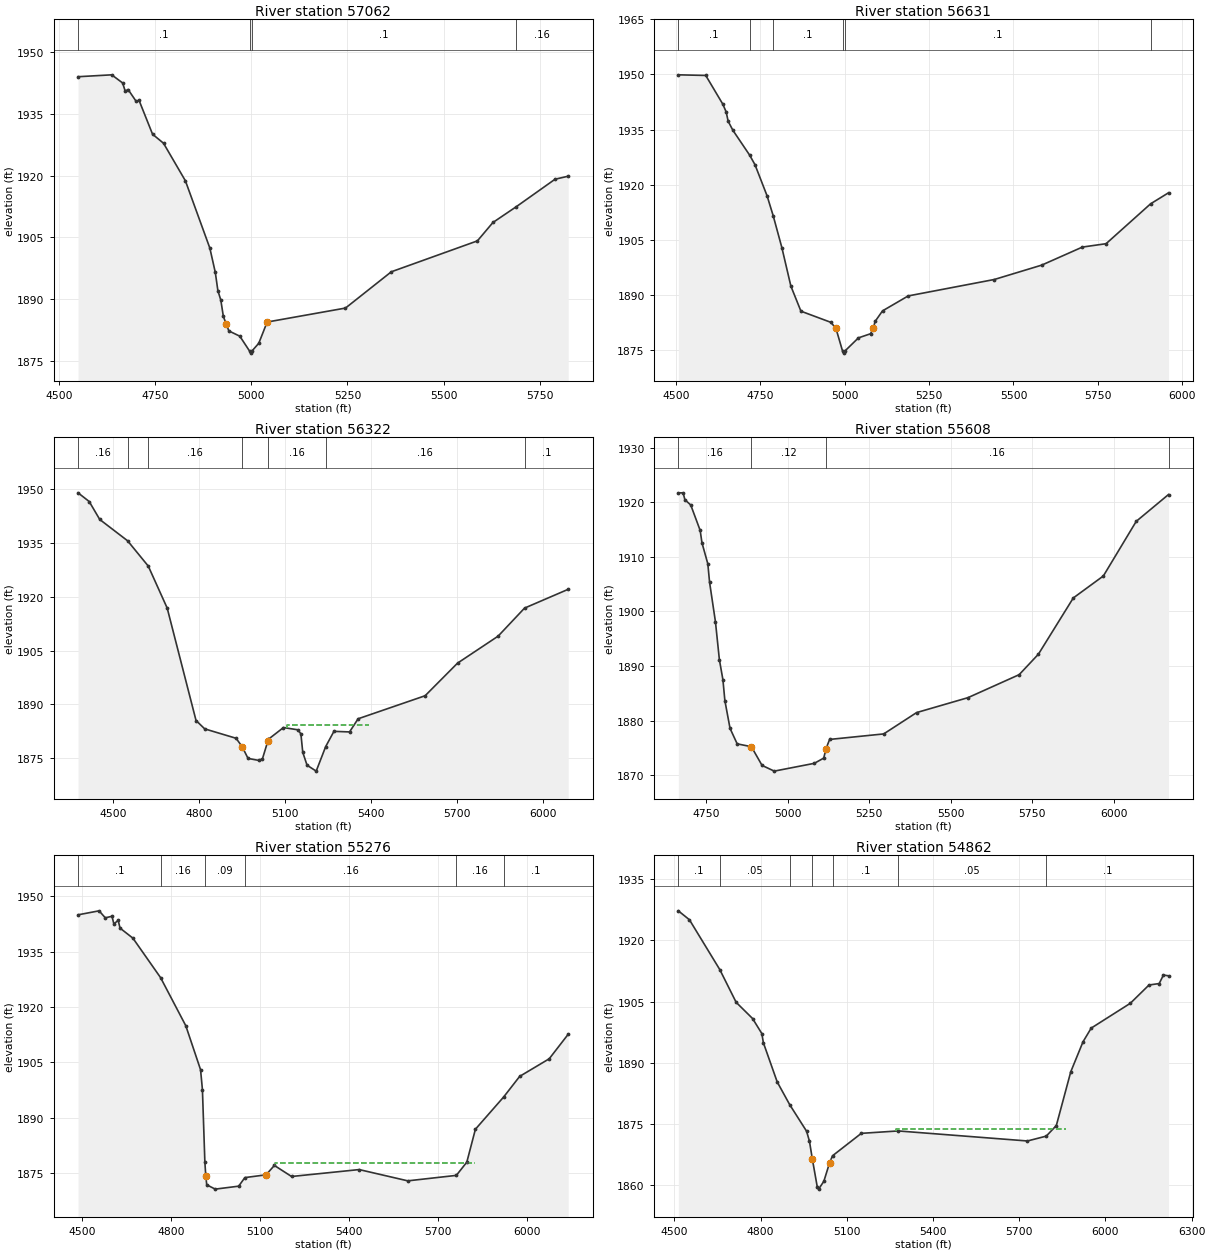
Type RM Length L Ch R = 1 ,57062   ,431,431,431
BEGIN DESCRIPTION:
BEAR CREEK 102.0
END DESCRIPTION:
XS GIS Cut Line= 3
      2732974.78     10004514.08      2733375.82       10004962.
      2734042.51     10005045.34
#Sta/Elev= 30
  4550.2 1944.05  4637.6 1944.51    4666 1942.53  4672.7 1940.54  4680.2 1940.94
  4701.1 1938.06  4708.6 1938.31  4743.7 1930.07  4772.2 1927.87    4829 1918.74
  4892.5 1902.37  4906.7 1896.44  4913.4    1892  4920.9 1889.76  4927.6 1885.75
  4935.1 1883.89  4941.9 1882.23  4970.3 1880.95  4995.7 1877.33  4998.4 1876.83
  5001.7 1877.33  5019.6 1879.23  5041.3 1884.39  5244.8 1887.79  5363.8 1896.61
  5587.4 1904.13  5627.7  1908.6  5688.4 1912.44    5789 1919.12  5823.3 1919.86
#Mann= 4 ,-1 , 0
  4550.2      .1       0  4995.7     .07       0  5001.7      .1       0
  5688.4     .16       0
Bank Sta=4935.1,5041.3
XS Rating Curve= 0 ,0
Exp/Cntr=0.3,0.1

Type RM Length L Ch R = 1 ,56631   ,309,309,309
BEGIN DESCRIPTION:
BEAR CREEK 101.0
END DESCRIPTION:
XS GIS Cut Line= 4
      2732844.57     10004743.21      2732891.45     10005107.83
      2733256.03     10005305.75      2733922.74     10005253.66
#Sta/Elev= 30
  4507.7  1949.9  4588.9 1949.73  4639.3 1941.94  4649.4 1939.81  4655.2 1937.27
  4669.5 1934.78  4718.6 1928.09  4734.7 1925.45  4770.4    1917  4788.7 1911.53
  4814.2 1902.91  4840.9 1892.43  4870.7  1885.6  4959.2 1882.57  4974.3 1880.94
  4994.1 1874.69  4996.8 1874.19  5000.1 1874.69  5040.9 1878.34  5076.7 1879.46
  5084.6 1880.91  5090.3 1882.81  5112.2 1885.68  5188.2 1889.75  5443.1 1894.22
  5583.5 1898.13  5703.9 1903.04  5774.1 1903.96  5905.9 1914.81  5958.9 1917.81
#Mann= 6 ,-1 , 0
  4507.7      .1       0  4718.6     .16       0  4788.7      .1       0
  4994.1     .07       0  5000.1      .1       0  5905.9     .16       0
Bank Sta=4974.3,5084.6
XS Rating Curve= 0 ,0
Exp/Cntr=0.3,0.1

Type RM Length L Ch R = 1 ,56322   ,714,714,714
BEGIN DESCRIPTION:
BEAR CREEK 100.0
END DESCRIPTION:
XS GIS Cut Line= 4
      2732703.77     10004745.14      2732794.91     10005465.65
      2732673.39     10005778.15      2733167.93     10006198.95
#Sta/Elev= 30
  4378.7 1948.92  4417.6  1946.5  4454.4  1941.5  4551.5 1935.57  4623.8 1928.51
  4689.8 1916.82  4790.5  1885.5  4820.8 1883.17  4930.3 1880.55  4951.8 1878.17
    4972 1874.94  5010.5 1874.37  5022.4 1874.86  5040.9 1879.71  5042.5 1880.24
  5095.7 1883.54  5145.8 1882.91  5156.5 1881.78    5163 1876.64    5178 1873.05
  5209.9  1871.4  5243.1 1878.25  5271.8 1882.48  5326.3 1882.32  5356.2 1885.98
  5590.1  1892.4  5703.2 1901.48  5844.9    1909  5937.1 1916.81  6089.6 1922.05
#Mann= 7 ,-1 , 0
  4378.7     .16       0  4551.5      .1       0  4623.8     .16       0
  4951.8     .12       0  5042.5     .16       0  5243.1     .16       0
  5937.1      .1       0
#XS Ineff= 1 ,-1
 5106.82 5394.32 1884.28
Permanent Ineff=
       T
Bank Sta=4951.8,5040.9
XS Rating Curve= 0 ,0
Exp/Cntr=0.3,0.1

Type RM Length L Ch R = 1 ,55608   ,332,332,332
BEGIN DESCRIPTION:
BEAR CREEK 99.0
END DESCRIPTION:
XS GIS Cut Line= 3
       2731996.3     10005218.25      2732204.64     10005697.42
      2733003.21     10006266.84
#Sta/Elev= 30
  4664.4 1921.74  4679.1 1921.75  4684.6 1920.48  4702.5 1919.52  4731.4 1914.86
  4736.9  1912.6  4754.9 1908.73  4760.3 1905.34  4778.3  1898.1  4790.3 1891.19
  4801.2 1887.48  4807.2 1883.66    4823 1878.58  4844.9 1875.74  4888.5 1875.22
  4921.2 1871.79  4958.6 1870.74  5081.5 1872.17  5110.4 1873.13  5117.5 1874.88
  5128.4 1876.55  5294.3 1877.56  5395.1 1881.47  5552.4  1884.2  5709.7 1888.42
  5768.8 1892.18  5875.7 1902.48  5967.9 1906.51  6068.7 1916.52  6167.7 1921.44
#Mann= 4 ,-1 , 0
  4664.4     .16       0  4888.5     .12       0  5117.5     .16       0
  6167.7      .1       0
Bank Sta=4888.5,5117.5
XS Rating Curve= 0 ,0
Exp/Cntr=0.3,0.1

Type RM Length L Ch R = 1 ,55276   ,414,414,414
BEGIN DESCRIPTION:
BEAR CREEK 98.0
END DESCRIPTION:
XS GIS Cut Line= 2
      2731447.71     10005384.94      2732753.18     10006398.76
#Sta/Elev= 30
  4486.9 1944.95  4557.9 1946.03  4578.7 1944.14  4601.3 1944.55  4607.7 1942.48
  4622.2 1943.46  4628.5 1941.35  4671.9 1938.63  4765.2 1927.95  4850.2 1914.94
    4900 1903.04  4906.3 1897.64  4914.5 1878.11  4917.5 1874.39  4920.8  1871.9
  4949.5 1870.73  5028.5 1871.53  5049.4 1873.85  5120.9  1874.6  5148.9 1877.14
  5206.8 1874.15  5434.9 1876.02  5598.7 1872.97  5762.5 1874.45  5797.8 1878.03
  5826.8 1886.94  5921.9 1895.65  5976.1 1901.24  6075.7    1906  6139.8 1912.65
#Mann= 6 ,-1 , 0
  4486.9      .1       0  4765.2     .16       0  4914.5     .09       0
  5049.4     .16       0  5762.5     .16       0  5921.9      .1       0
#XS Ineff= 1 ,-1
  5151.7 5824.66 1877.77
Permanent Ineff=
       T
Bank Sta=4917.5,5120.9
XS Rating Curve= 0 ,0
Exp/Cntr=0.3,0.1

Type RM Length L Ch R = 1 ,54862   ,540,540,540
BEGIN DESCRIPTION:
BEAR CREEK 97.0
END DESCRIPTION:
XS GIS Cut Line= 4
      2731315.76     10005822.44      2731503.25     10006044.65
      2731982.41     10006079.37      2732739.35     10006627.97
#Sta/Elev= 30
  4513.4 1927.26  4552.1 1925.07  4657.9 1912.84  4714.7 1904.84  4771.8 1900.87
  4804.1 1897.18  4809.4 1894.94  4857.6 1885.32  4901.2 1879.74  4959.8 1873.25
  4969.8  1870.8  4979.8 1866.46    4997  1859.6  5001.7 1859.06  5019.9 1860.98
    5040 1865.54    5050 1867.23  5150.3 1872.73  5278.7 1873.32  5728.5 1870.86
  5793.9 1872.05    5829 1874.65  5879.3 1887.83  5921.9 1895.17  5950.4 1898.52
  6086.5  1904.6  6151.5 1909.08    6187 1909.44  6201.7 1911.52  6219.4 1911.34
#Mann= 7 ,-1 , 0
  4513.4      .1       0  4657.9     .05       0  4901.2      .1       0
  4979.8     .07       0    5050      .1       0  5278.7     .05       0
  5793.9      .1       0
#XS Ineff= 1 ,-1
 5269.32 5863.64 1873.73
Permanent Ineff=
       T
Bank Sta=4979.8,5040
XS Rating Curve= 0 ,0
Exp/Cntr=0.3,0.1

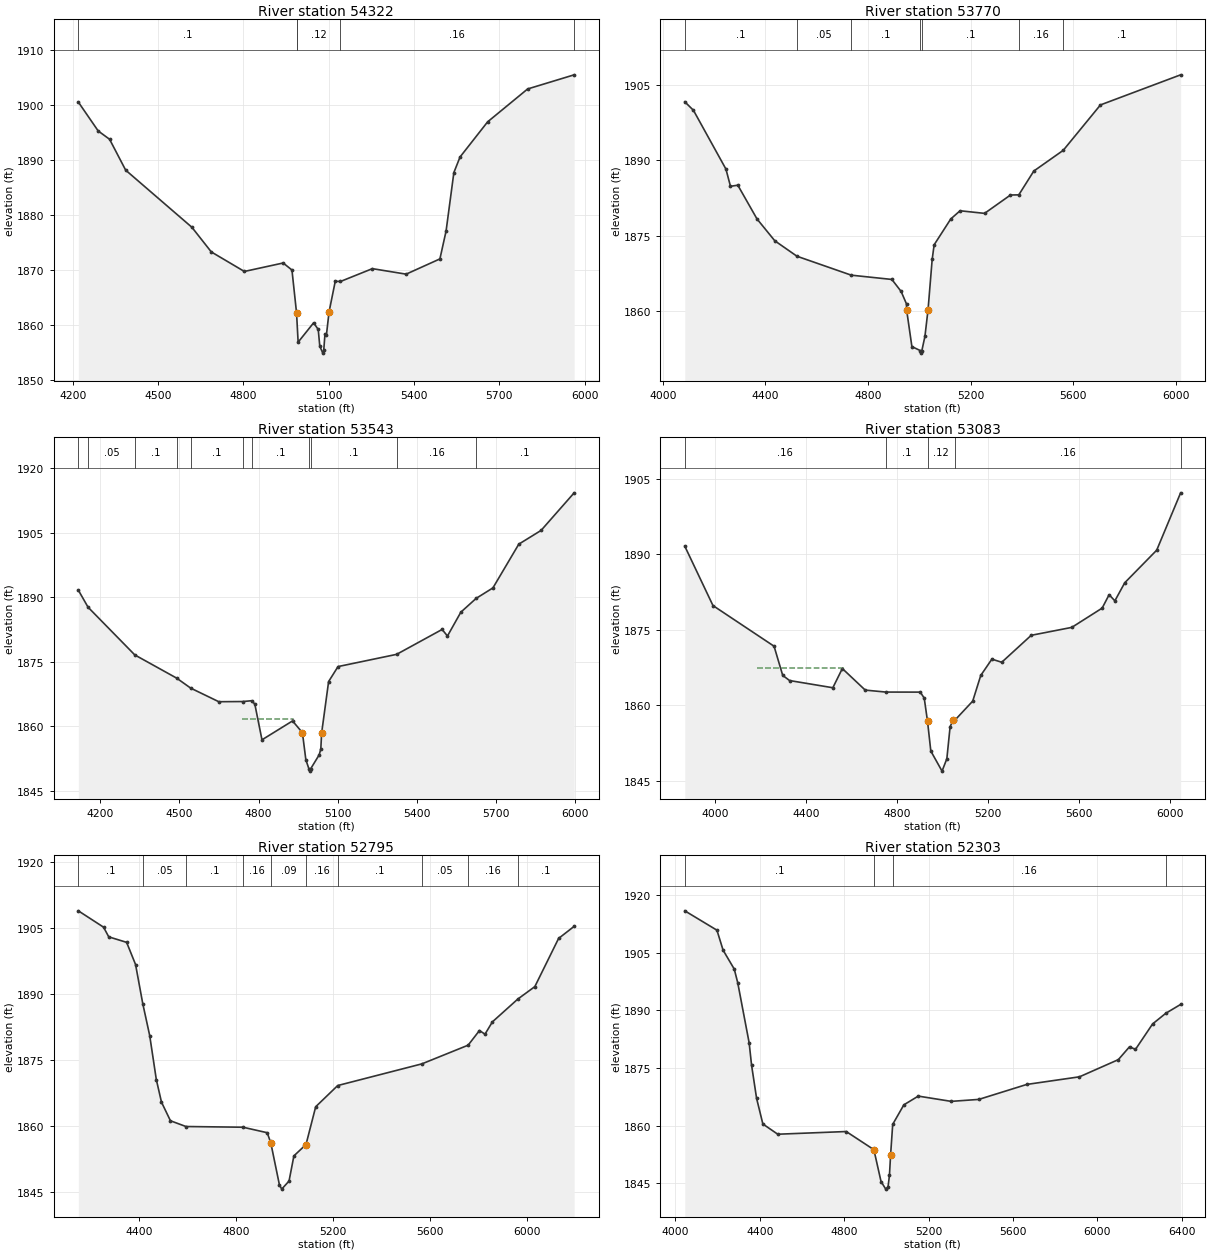
Type RM Length L Ch R = 1 ,54322   ,552,552,552
BEGIN DESCRIPTION:
BEAR CREEK 96.0
END DESCRIPTION:
XS GIS Cut Line= 4
      2731454.62     10006093.23      2731704.64     10006621.03
      2732142.14     10006433.53      2732739.39     10006766.89
#Sta/Elev= 30
  4219.2 1900.49  4289.1 1895.24  4329.1 1893.73  4385.7 1888.12  4618.6 1877.74
  4686.9 1873.26  4803.2 1869.71  4939.7 1871.25  4970.6 1869.97  4986.8 1862.16
  4992.3 1856.86  5046.7 1860.37    5063 1859.18  5068.5 1856.13  5079.1 1854.87
  5082.4 1855.37  5086.6 1858.26    5092 1858.25  5101.1 1862.36  5122.9 1867.92
  5141.3 1867.89  5253.5 1870.22  5372.2 1869.22    5491 1871.99  5512.7 1877.05
  5540.1 1887.68  5561.8 1890.51  5658.9  1896.9  5799.5 1902.87  5963.2 1905.44
#Mann= 5 ,-1 , 0
  4219.2      .1       0  4986.8     .05       0  4986.8     .12       0
  5141.3     .16       0  5963.2      .1       0
Bank Sta=4986.8,5101.1
XS Rating Curve= 0 ,0
Exp/Cntr=0.3,0.1

Type RM Length L Ch R = 1 ,53770   ,227,227,227
BEGIN DESCRIPTION:
BEAR CREEK 95.0
END DESCRIPTION:
XS GIS Cut Line= 4
      2731399.09     10006239.11       2731683.8     10006871.03
      2732072.69     10007134.92        2732835.     10007024.04
#Sta/Elev= 30
  4085.5 1901.64  4119.2 1899.95  4245.9 1888.27  4263.6 1884.85  4292.2 1885.07
  4367.1 1878.36  4436.5 1874.02    4523 1870.95  4734.7 1867.19    4893 1866.34
    4929 1863.96    4950 1861.47 4950.28 1860.36    4971    1853  5003.9  1852.2
  5006.7  1851.7  5009.9  1852.2  5021.9 1855.04 5034.09 1860.36  5050.1 1870.32
  5057.8 1873.23  5122.6 1878.36  5158.9 1879.99  5254.4 1879.47  5355.5 1883.12
  5387.9 1883.15  5446.4 1887.88  5561.2    1892  5706.3 1901.02  6018.9    1907
#Mann= 7 ,-1 , 0
  4085.5      .1       0    4523     .05       0  4734.7      .1       0
  5003.9     .07       0  5009.9      .1       0  5387.9     .16       0
  5561.2      .1       0
Bank Sta=4950.28,5034.09
XS Rating Curve= 0 ,0
Exp/Cntr=0.3,0.1

Type RM Length L Ch R = 1 ,53543   ,460,460,460
BEGIN DESCRIPTION:
BEAR CREEK 94.0
END DESCRIPTION:
XS GIS Cut Line= 4
      2731287.97     10006426.59      2731489.36     10007002.98
      2731961.58     10007336.31       2732642.1     10007225.21
#Sta/Elev= 30
  4117.1 1891.62  4153.9 1887.66  4330.9 1876.58  4489.5 1871.19  4542.6 1868.87
  4649.1 1865.71  4739.9 1865.75  4773.3 1865.94  4785.6 1865.16  4812.7 1856.86
  4928.5 1861.25 4965.91 1858.52  4978.9 1852.23  4990.7 1850.09  4993.5 1849.59
  4996.7 1850.09  5029.4 1853.37  5035.6 1854.74 5038.64 1858.42  5065.1 1870.39
  5100.8 1873.87  5322.8 1876.71    5495 1882.49  5515.3 1880.97    5566  1886.5
    5624 1889.71  5687.5 1892.14  5785.5  1902.3  5869.9 1905.49  5995.2 1914.22
#Mann= 11 ,-1 , 0
  4117.1      .1       0  4153.9     .05       0  4330.9      .1       0
  4489.5     .05       0  4542.6      .1       0  4739.9     .05       0
  4773.3      .1       0  4990.7     .07       0  4996.7      .1       0
  5322.8     .16       0    5624      .1       0
#XS Ineff= 1 ,-1
  4737.5 4928.41 1861.63
Permanent Ineff=
       T
Bank Sta=4965.91,5038.64
XS Rating Curve= 0 ,0
Exp/Cntr=0.3,0.1

Type RM Length L Ch R = 1 ,53083   ,288,288,288
BEGIN DESCRIPTION:
BEAR CREEK 93.0
END DESCRIPTION:
XS GIS Cut Line= 4
      2731239.36      10006426.6      2731357.41     10007461.31
      2731600.47     10007655.76      2732404.73     10007475.49
#Sta/Elev= 30
  3867.9 1891.65  3991.6 1879.84  4259.8 1871.75  4297.8 1865.95    4328 1864.92
  4517.9 1863.49  4559.5 1867.31  4660.1 1863.02  4750.7 1862.63  4901.7 1862.62
  4919.1 1861.43  4933.5 1856.84    4948  1850.9  4997.3  1846.9  5018.4 1849.36
  5032.8 1855.77  5047.2 1857.11  5053.6 1857.03    5132 1860.83  5167.3 1865.94
  5216.1 1869.18  5259.5 1868.56  5388.8 1873.92    5567  1875.5  5700.2 1879.33
  5730.9    1882  5756.1 1880.78  5799.5 1884.38  5939.8 1890.86  6044.8 1902.27
#Mann= 5 ,-1 , 0
  3867.9     .16       0  4750.7      .1       0  4933.5     .12       0
  5053.6     .16       0  6044.8      .1       0
#XS Ineff= 1 ,-1
 4185.23 4565.34 1867.42
Permanent Ineff=
       T
Bank Sta=4933.5,5047.2
XS Rating Curve= 0 ,0
Exp/Cntr=0.3,0.1

Type RM Length L Ch R = 1 ,52795   ,492,492,492
BEGIN DESCRIPTION:
BEAR CREEK 92.0
END DESCRIPTION:
XS GIS Cut Line= 4
      2730729.29     10007290.55      2731015.73     10007767.95
      2732066.07     10007767.95      2732452.38      10007559.6
#Sta/Elev= 30
  4150.3 1908.84  4254.4 1905.12  4275.8 1902.92  4349.6 1901.67  4386.5 1896.62
  4416.1 1887.75  4444.8 1880.47  4472.1 1870.46  4493.4 1865.33  4530.4 1861.09
  4594.4 1859.78  4829.8 1859.62  4929.8 1858.37  4944.6 1856.03  4979.8 1846.59
  4989.5 1845.54  5019.8 1847.38  5039.8  1853.1  5089.8 1855.69  5129.8 1864.28
  5220.6  1869.1  5567.9 1874.03  5758.8 1878.28  5805.6 1881.62  5828.3 1880.78
  5858.9 1883.58  5963.8 1888.77    6034  1891.6  6132.1 1902.56  6196.3 1905.31
#Mann= 10 ,-1 , 0
  4150.3      .1       0  4416.1     .05       0  4594.4      .1       0
  4829.8     .16       0  4944.6     .09       0  5089.8     .16       0
  5220.6      .1       0  5567.9     .05       0  5758.8     .16       0
  5963.8      .1       0
Bank Sta=4944.6,5089.8
XS Rating Curve= 0 ,0
Exp/Cntr=0.3,0.1

Type RM Length L Ch R = 1 ,52303   ,416,416,416
BEGIN DESCRIPTION:
BEAR CREEK 91.0
END DESCRIPTION:
XS GIS Cut Line= 4
      2730542.64     10007442.45      2730794.37     10008041.39
      2731328.23     10008293.13      2732300.48     10007754.92
#Sta/Elev= 30
  4044.1 1915.93  4196.5 1910.89  4225.7 1905.69  4278.6 1900.77    4295 1897.24
  4349.2 1881.59  4360.7 1875.77  4384.5 1867.13  4414.3 1860.45  4484.9 1857.79
  4809.6 1858.49  4940.7 1853.77  4974.7 1845.47  4997.1  1843.5  5007.9  1844.1
  5014.6 1847.11  5020.1 1852.47    5030 1860.36  5082.9 1865.44  5151.3 1867.71
  5307.2 1866.34  5438.1 1866.85    5666 1870.75  5915.6 1872.73  6099.9  1877.2
    6153 1880.55  6181.2 1879.87  6262.5  1886.5  6325.1 1889.27  6395.3 1891.57
#Mann= 4 ,-1 , 0
  4044.1      .1       0  4940.7     .09       0    5030     .16       0
  6325.1      .1       0
Bank Sta=4940.7,5020.1
XS Rating Curve= 0 ,0
Exp/Cntr=0.3,0.1

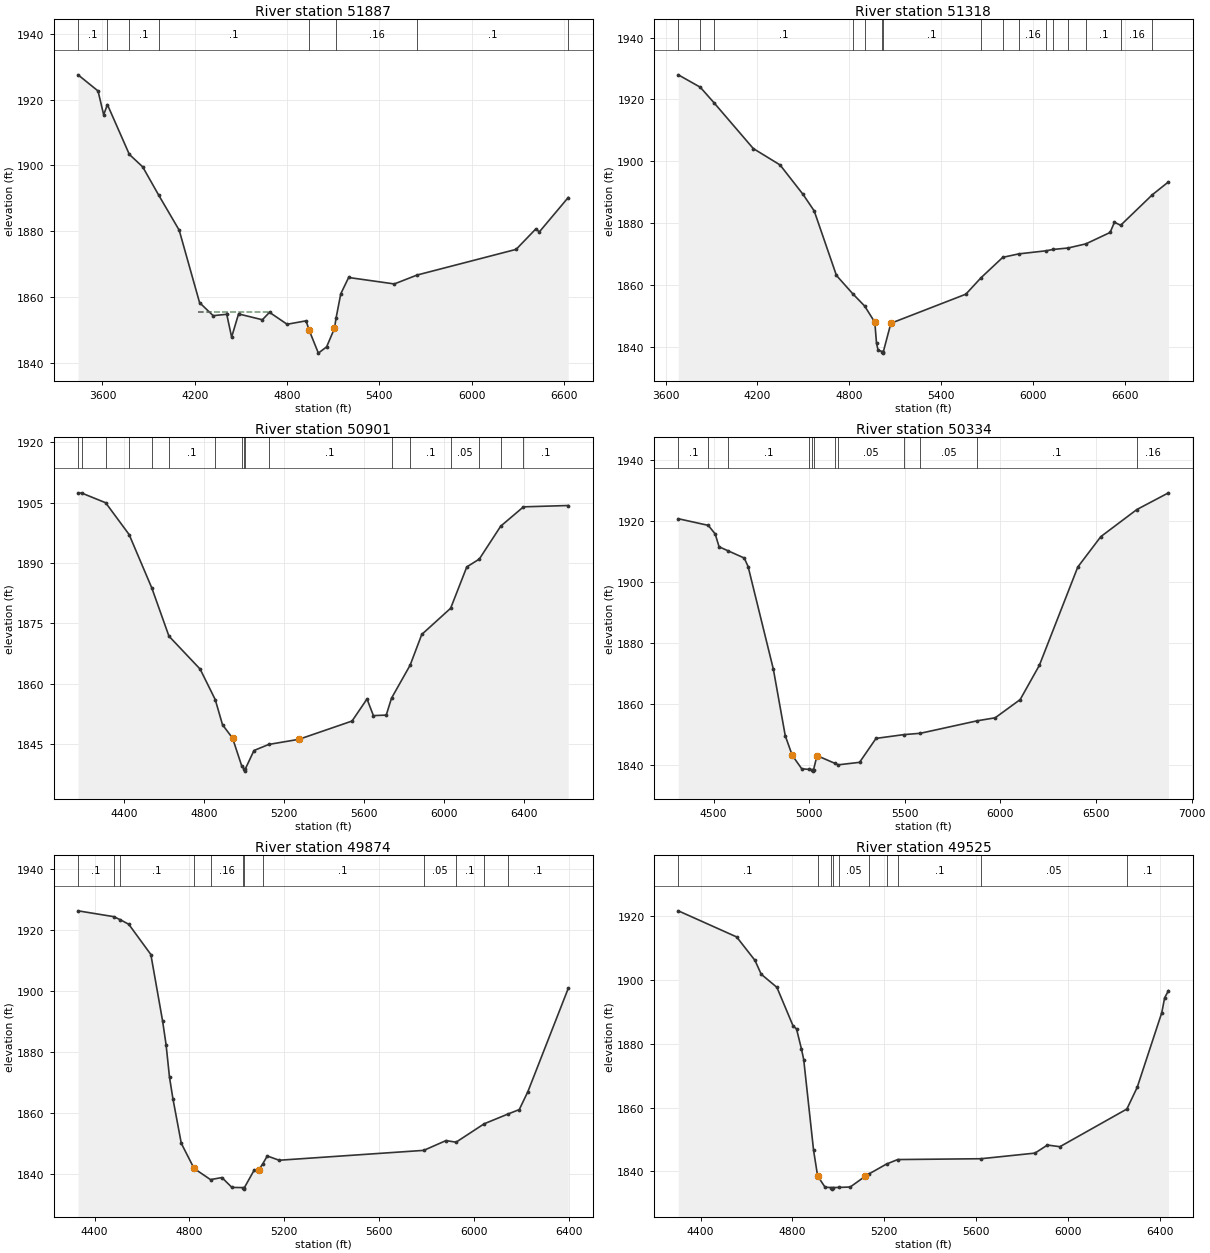
Type RM Length L Ch R = 1 ,51887   ,569,569,569
BEGIN DESCRIPTION:
BEAR CREEK 90.0
END DESCRIPTION:
XS GIS Cut Line= 4
       2729433.3     10009014.46      2730537.43     10008438.09
      2731183.26     10008583.92      2732244.57     10007869.45
#Sta/Elev= 30
  3441.4 1927.52  3571.3 1922.62  3607.9 1915.38  3632.3 1918.48  3774.8 1903.35
  3861.7 1899.56  3966.1 1890.94    4099 1880.32  4231.5 1858.31  4319.8 1854.35
  4408.2 1854.77  4439.9 1847.83    4485 1854.88  4639.8 1853.11  4686.2 1855.37
  4800.7 1851.74  4923.8 1852.78  4944.3 1849.89  5003.9 1842.97  5057.6 1844.88
  5108.3 1850.46  5118.6 1853.52  5149.3 1860.96  5200.6 1865.95  5497.7 1863.99
    5646  1866.7  6289.5 1874.49  6418.5 1880.74  6440.2 1879.78  6628.4 1890.25
#Mann= 8 ,-1 , 0
  3441.4      .1       0  3632.3     .05       0  3774.8      .1       0
  3966.1      .1       0  4944.3     .09       0  5118.6     .16       0
    5646      .1       0  6628.4      .1       0
#XS Ineff= 1 ,-1
 4222.52  4686.8 1855.45
Permanent Ineff=
       T
Bank Sta=4944.3,5108.3
XS Rating Curve= 0 ,0
Exp/Cntr=0.3,0.1

Type RM Length L Ch R = 1 ,51318   ,417,417,417
BEGIN DESCRIPTION:
BEAR CREEK 89.0
END DESCRIPTION:
XS GIS Cut Line= 4
      2729493.19      10009277.5      2730520.93     10009138.61
      2731215.38     10008937.22      2732298.69     10007985.85
#Sta/Elev= 30
  3683.5 1927.96    3827 1923.96  3917.3 1918.91  4173.2 1904.16  4348.1 1898.87
  4498.4 1889.35  4571.1 1884.03  4716.4 1863.19  4822.3 1857.31    4901 1853.29
  4967.1 1848.07  4978.3 1841.27  4988.7 1839.03    5017  1838.6  5019.7  1838.1
    5023  1838.6    5072 1847.74  5561.7 1857.13  5660.9 1862.44    5803 1869.03
  5906.7 1870.14  6087.1 1871.15  6129.9 1871.57  6229.2 1872.04  6346.5 1873.39
    6504 1877.06  6532.5 1880.37  6572.7 1879.37  6780.2 1889.25  6885.4  1893.4
#Mann= 16 ,-1 , 0
  3683.5      .1       0    3827     .05       0  3917.3      .1       0
  4822.3     .05       0    4901      .1       0    5017     .07       0
    5023      .1       0  5660.9     .16       0    5803      .1       0
  5906.7     .16       0  6087.1     .05       0  6129.9     .16       0
  6229.2     .05       0  6346.5      .1       0  6572.7     .16       0
  6780.2      .1       0
Bank Sta=4967.1,5072
XS Rating Curve= 0 ,0
Exp/Cntr=0.3,0.1

Type RM Length L Ch R = 1 ,50901   ,567,567,567
BEGIN DESCRIPTION:
BEAR CREEK 88.0
END DESCRIPTION:
XS GIS Cut Line= 4
      2730055.69     10009596.94      2730701.49     10009437.22
      2731326.49     10009499.72      2732409.82       10009090.
#Sta/Elev= 30
  4168.5 1907.42  4187.6 1907.35  4306.7 1904.95  4423.9 1897.06  4537.7 1883.75
  4623.1 1871.82  4779.1 1863.63  4854.7 1856.05    4891 1849.81  4941.3 1846.49
  4986.9 1839.61  4998.6 1838.79  5001.3 1838.29  5004.6 1838.79  5048.4 1843.41
  5122.2 1844.92  5272.9 1846.19  5538.8 1850.73  5613.7 1856.21  5645.7 1852.08
  5709.9 1852.21  5736.3 1856.42  5829.4 1864.61  5887.5 1872.24    6032 1878.75
  6112.8 1889.02  6175.2 1890.96  6282.4 1899.14  6396.3 1903.94  6620.1 1904.27
#Mann= 17 ,-1 , 0
  4168.5     .05       0  4187.6      .1       0  4306.7     .05       0
  4423.9      .1       0  4537.7     .05       0  4623.1      .1       0
  4854.7     .05       0  4986.9     .16       0  4998.6     .07       0
  5004.6     .16       0  5122.2      .1       0  5736.3     .05       0
  5829.4      .1       0    6032     .05       0  6175.2      .1       0
  6282.4     .16       0  6396.3      .1       0
Bank Sta=4941.3,5272.9
XS Rating Curve= 0 ,0
Exp/Cntr=0.3,0.1

Type RM Length L Ch R = 1 ,50334   ,460,460,460
BEGIN DESCRIPTION:
BEAR CREEK 87.0
END DESCRIPTION:
XS GIS Cut Line= 4
      2730027.87     10009756.67      2730513.99     10009833.06
      2731166.77     10010298.33      2732430.66     10010180.28
#Sta/Elev= 30
  4315.7 1920.75  4472.4 1918.58  4508.6 1915.76  4528.9 1911.57  4574.8 1910.28
  4660.5 1907.89  4680.7 1905.09  4812.7  1871.5    4875  1849.7  4911.5 1843.29
  4961.1  1838.9  4998.5  1838.7  5017.1 1838.63  5019.9 1838.13  5023.1 1838.63
    5041 1843.21  5132.6 1840.73  5152.7  1840.2  5263.5 1841.01  5349.6 1848.85
  5495.2 1850.08  5581.6 1850.52  5879.8 1854.62  5972.7 1855.59  6103.2 1861.55
  6203.7 1872.78  6404.6 1904.95  6525.1  1914.9  6713.3 1923.76  6878.8 1929.23
#Mann= 12 ,-1 , 0
  4315.7      .1       0  4472.4     .05       0  4574.8      .1       0
  4998.5     .16       0  5017.1     .07       0  5023.1     .16       0
  5132.6      .1       0  5152.7     .05       0  5495.2      .1       0
  5581.6     .05       0  5879.8      .1       0  6713.3     .16       0
Bank Sta=4911.5,5041
XS Rating Curve= 0 ,0
Exp/Cntr=0.3,0.1

Type RM Length L Ch R = 1 ,49874   ,349,349,349
BEGIN DESCRIPTION:
BEAR CREEK 86.0
END DESCRIPTION:
XS GIS Cut Line= 3
      2729930.68      10009930.3      2730826.49     10010631.67
      2731639.01     10011083.07
#Sta/Elev= 30
  4330.5 1926.15  4480.9 1924.24  4509.2 1923.21  4544.4 1921.74  4637.5 1911.83
  4687.2 1889.97  4701.7 1882.28  4716.2 1871.55  4730.6 1864.54  4765.9 1849.92
  4819.8 1841.68  4889.1 1838.02  4937.3  1838.7  4979.3 1835.46    5026  1835.4
  5028.8  1834.9    5032  1835.4  5072.4 1841.01  5093.2 1841.32  5108.8  1843.1
  5128.5 1845.77  5178.6 1844.37  5788.5 1847.61  5882.3 1850.82  5924.7 1850.29
  6043.4 1856.33  6144.5 1859.55  6191.2 1860.98  6227.6 1866.88  6397.7 1900.71
#Mann= 12 ,-1 , 0
  4330.5      .1       0  4480.9     .05       0  4509.2      .1       0
  4819.8     .05       0  4889.1     .16       0    5026     .07       0
    5032     .16       0  5108.8      .1       0  5788.5     .05       0
  5924.7      .1       0  6043.4     .05       0  6144.5      .1       0
Bank Sta=4819.8,5093.2
XS Rating Curve= 0 ,0
Exp/Cntr=0.3,0.1

Type RM Length L Ch R = 1 ,49525   ,653,653,653
BEGIN DESCRIPTION:
BEAR CREEK 85.0
END DESCRIPTION:
XS GIS Cut Line= 3
      2729639.02     10010256.68      2730632.05     10010846.95
      2731533.94     10011228.52
#Sta/Elev= 30
  4303.3  1921.7  4557.3 1913.52  4637.1 1906.17  4664.3 1901.83  4732.6 1897.72
  4802.9 1885.66  4818.2 1884.66  4839.7 1878.34  4849.4 1875.07  4892.3 1846.64
    4910 1838.57  4942.5 1835.05  4969.1 1834.96  4971.9 1834.46  4975.1 1834.96
  5002.2 1834.99    5052 1835.13    5117 1838.48  5133.7 1839.23  5209.9 1842.32
  5258.6 1843.73  5621.5 1843.99  5856.4 1845.75  5910.7 1848.28    5965 1847.76
  6256.6 1859.57  6301.6 1866.37  6408.7 1889.81    6421 1894.43  6437.8 1896.69
#Mann= 10 ,-1 , 0
  4303.3      .1       0    4910     .16       0  4969.1     .07       0
  4975.1     .16       0  5002.2     .05       0  5133.7     .16       0
  5209.9     .05       0  5258.6      .1       0  5621.5     .05       0
  6256.6      .1       0
Bank Sta=4910,5117
XS Rating Curve= 0 ,0
Exp/Cntr=0.3,0.1