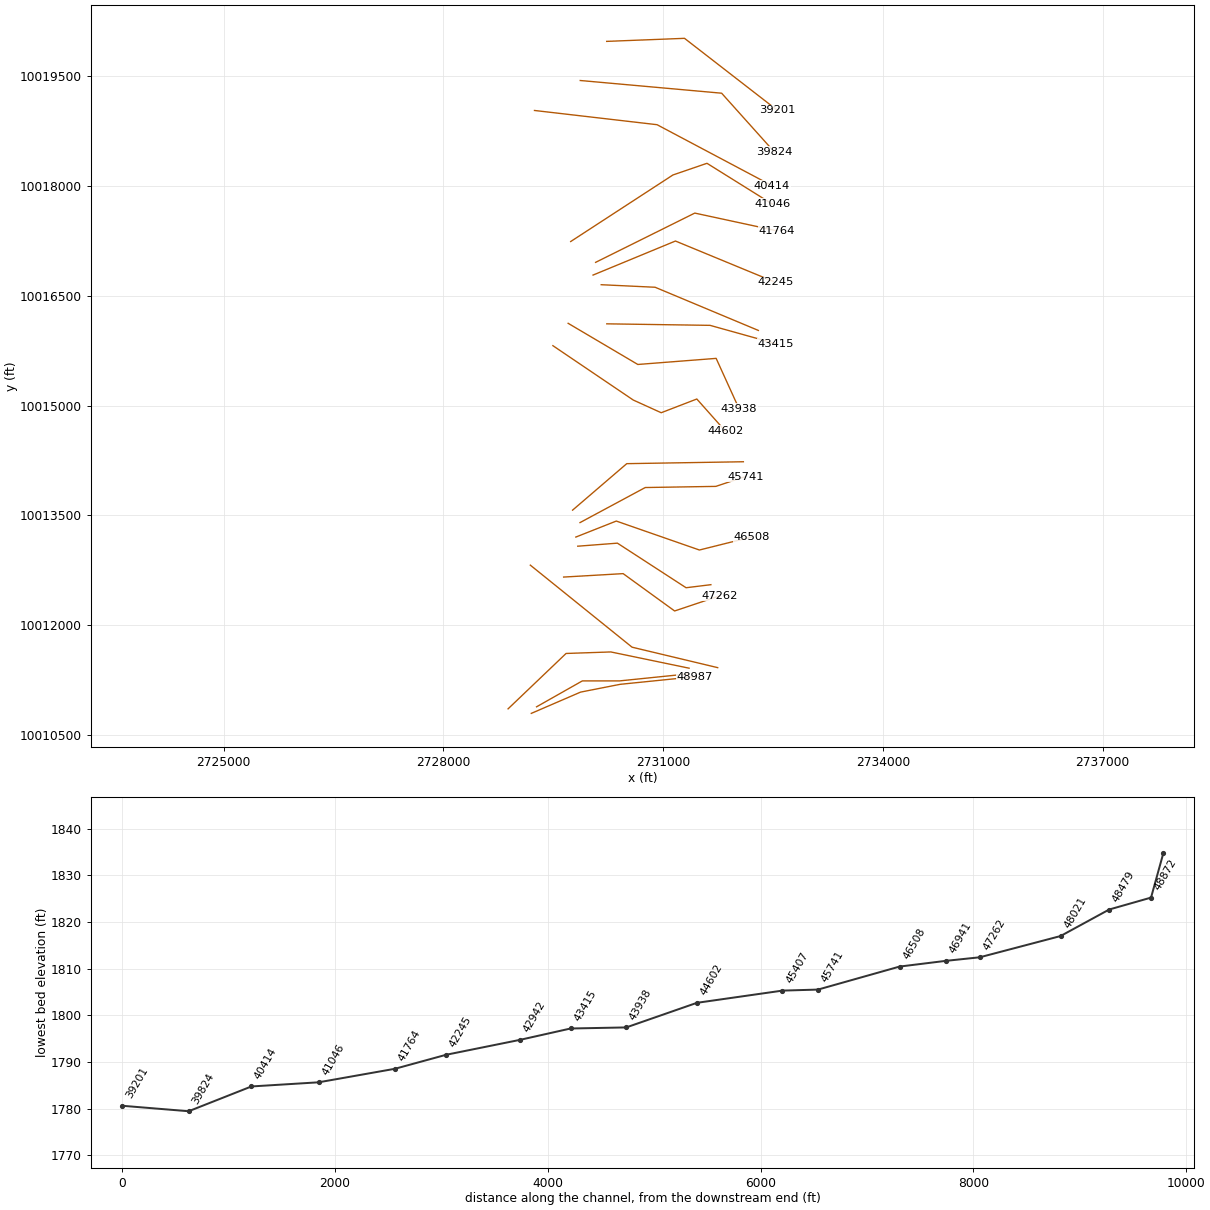
HEC-RAS study BEAR CREEK.prj: BEAR CREEK Base Level Engineering

--- BEAR CREEK.g01 (geometry) --- (continued)

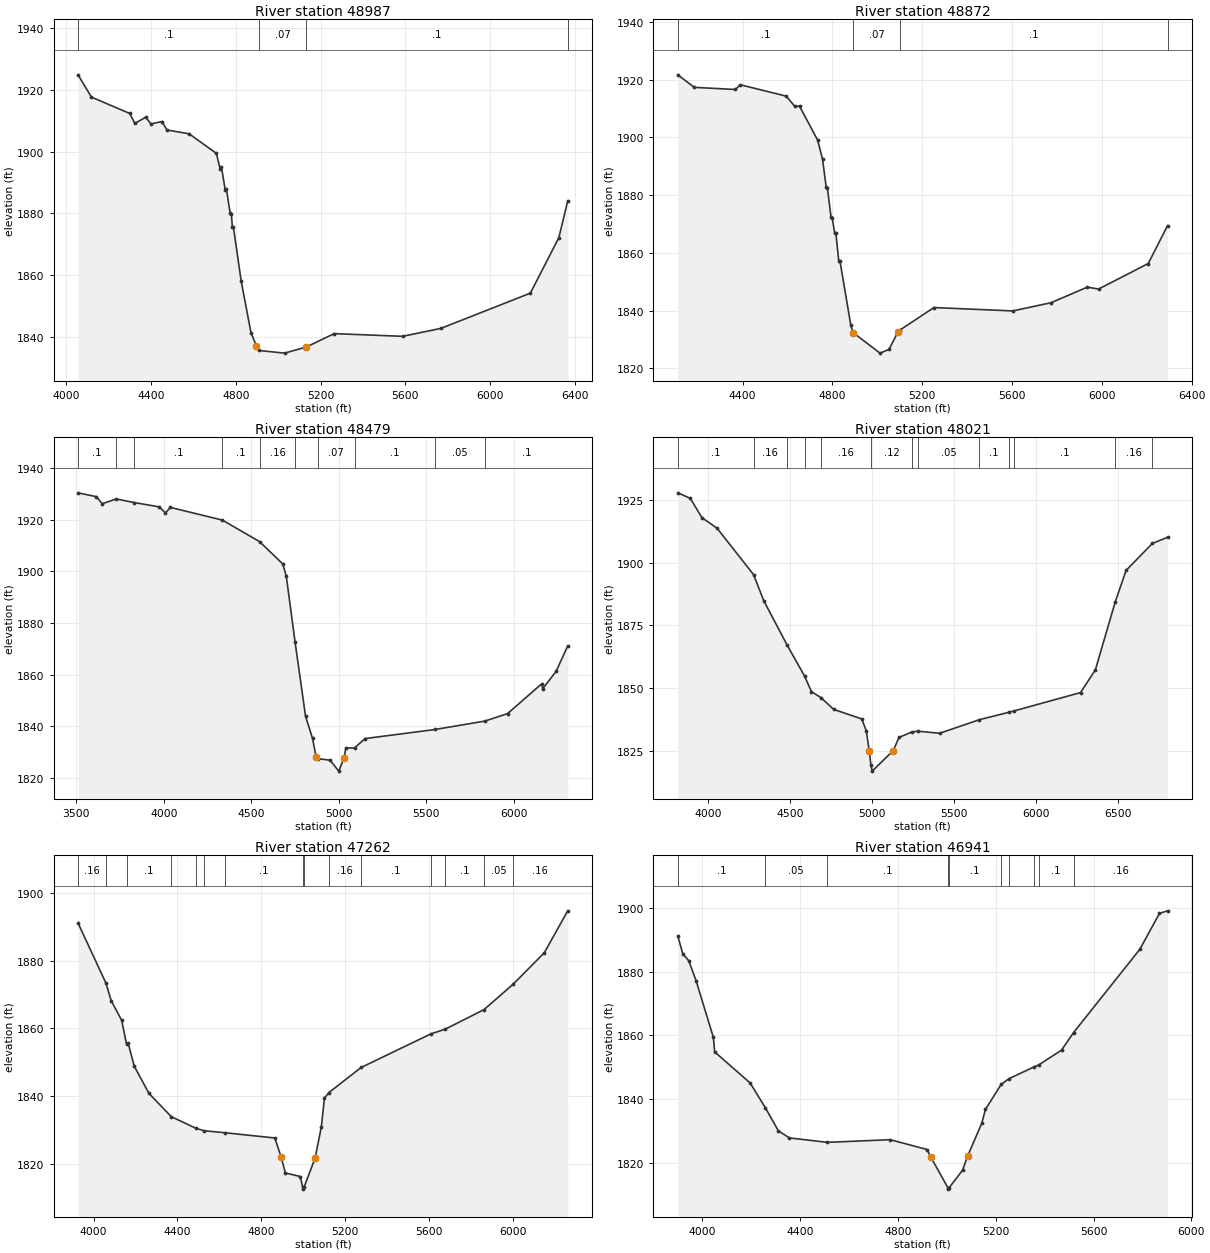
Type RM Length L Ch R = 1 ,48987   ,115,115,115
BEGIN DESCRIPTION:
Mapping XS 543d61bb
END DESCRIPTION:
XS GIS Cut Line= 4
      2729199.28     10010791.89      2729871.99     10011082.67
      2730412.36     10011189.01      2731433.96     10011293.12
#Sta/Elev= 30
  4055.8 1924.87  4119.1 1917.65    4300 1912.35  4323.5 1909.14  4375.9 1911.15
  4399.4 1908.96  4451.8 1909.74  4475.3 1907.01  4580.2 1905.77  4708.6 1899.42
  4726.6 1894.34  4732.1 1895.15  4750.1 1887.66  4755.6 1888.02  4773.6 1879.97
  4779.1 1879.82    4784 1875.61  4788.7 1875.61  4825.8 1857.97  4871.8 1841.36
  4897.2 1837.09  4907.4  1835.6  5030.7 1834.73  5133.7 1836.74  5264.1 1841.05
  5586.8 1840.17  5767.7 1842.74  6189.9 1854.16  6324.3 1872.13  6366.3 1884.06
#Mann= 4 ,-1 , 0
  4055.8      .1       0  4907.4     .07       0  5133.7      .1       0
  6366.3      .1       0
Bank Sta=4897.2,5133.7
XS Rating Curve= 0 ,0
Exp/Cntr=0.3,0.1

Type RM Length L Ch R = 1 ,48872   ,393,393,393
BEGIN DESCRIPTION:
BEAR CREEK 84.0
END DESCRIPTION:
XS GIS Cut Line= 4
      2729270.93     10010881.66      2729895.93     10011235.83
      2730402.88     10011235.83       2731353.9     10011333.02
#Sta/Elev= 30
  4111.1 1921.67  4184.6 1917.33  4367.9 1916.59  4389.5 1918.23  4594.4 1914.28
  4631.9 1910.78  4653.5  1910.8  4734.3    1899    4756 1892.37  4771.8 1882.96
  4777.6 1882.37  4793.5 1872.54  4799.2 1872.04  4809.4 1866.98  4815.1 1866.86
  4828.1 1857.26  4833.2 1857.26    4882 1834.85    4892 1832.37  5011.8 1825.26
    5052 1826.54    5092 1832.65    5102 1833.33    5252 1841.05  5603.4 1839.88
  5774.3 1842.74  5935.1 1848.12  5985.4 1847.46  6206.5 1856.29  6292.4  1869.4
#Mann= 4 ,-1 , 0
  4111.1      .1       0    4892     .07       0    5102      .1       0
  6292.4      .1       0
Bank Sta=4892,5092
XS Rating Curve= 0 ,0
Exp/Cntr=0.3,0.1

Type RM Length L Ch R = 1 ,48479   ,458,458,458
BEGIN DESCRIPTION:
BEAR CREEK 83.0
END DESCRIPTION:
XS GIS Cut Line= 4
      2728882.02     10010853.86      2729673.71     10011610.83
      2730284.82     10011631.67      2731353.88     10011409.53
#Sta/Elev= 30
  3510.1  1930.4  3613.7 1928.93  3648.9 1926.21  3728.9 1928.02    3831 1926.64
  3974.4 1924.96  4009.7  1922.6    4038 1924.76  4335.2 1919.84  4548.2 1911.49
  4680.2 1902.87  4700.3 1898.14  4750.6  1872.6  4810.3 1843.96  4850.3 1835.35
  4870.4 1828.28  4880.4 1827.53  4950.4 1826.95  5000.2 1822.71  5030.4 1827.86
  5040.5 1831.63  5090.5  1831.7  5150.5 1835.31  5550.9 1838.82  5835.4 1842.08
  5964.9 1844.96  6160.2 1856.53  6165.3 1854.56    6242 1861.28  6308.8 1871.16
#Mann= 10 ,-1 , 0
  3510.1      .1       0  3728.9     .16       0    3831      .1       0
  4335.2      .1       0  4548.2     .16       0  4750.6      .1       0
  4880.4     .07       0  5090.5      .1       0  5550.9     .05       0
  5835.4      .1       0
Bank Sta=4870.4,5030.4
XS Rating Curve= 0 ,0
Exp/Cntr=0.3,0.1

Type RM Length L Ch R = 1 ,48021   ,759,759,759
BEGIN DESCRIPTION:
BEAR CREEK 82.0
END DESCRIPTION:
XS GIS Cut Line= 3
      2729185.66     10012818.31      2730574.97     10011696.64
      2731744.13     10011417.12
#Sta/Elev= 30
  3813.4 1927.76    3890 1925.55  3960.4  1917.9  4053.1 1913.67  4275.5 1895.24
  4337.8 1884.84  4479.6 1867.29    4587 1854.82  4628.9 1848.65  4686.1  1846.3
  4764.8 1841.58  4935.2  1837.8  4963.1 1833.16 4981.53 1825.06  4991.9  1819.3
  4999.2 1817.02  5127.8 1825.16    5163 1830.45  5244.1 1832.66  5280.6 1832.89
  5410.9 1832.08  5652.6 1837.47  5834.6 1840.46  5864.9 1840.97  6270.9 1848.29
  6361.2 1857.35  6481.1 1884.13  6548.5  1896.9  6708.9 1907.63  6801.1 1910.06
#Mann= 13 ,-1 , 0
  3813.4      .1       0  4275.5     .16       0  4479.6      .1       0
    4587     .05       0  4686.1     .16       0  4991.9     .12       0
  5244.1     .16       0  5280.6     .05       0  5652.6      .1       0
  5834.6     .05       0  5864.9      .1       0  6481.1     .16       0
  6708.9      .1       0
Bank Sta=4981.53,5127.8
XS Rating Curve= 0 ,0
Exp/Cntr=0.3,0.1

Type RM Length L Ch R = 1 ,47262   ,321,321,321
BEGIN DESCRIPTION:
BEAR CREEK 81.0
END DESCRIPTION:
XS GIS Cut Line= 4
      2729640.52     10012655.28      2730453.05     10012702.15
      2731156.18     10012191.74      2731774.73     10012399.65
#Sta/Elev= 30
  3925.7 1891.19  4058.5 1873.46  4083.9 1868.21    4134 1862.38  4157.1 1855.32
  4164.2 1855.73  4194.1 1848.79  4264.2 1840.77  4370.4 1833.91  4486.6 1830.51
  4526.5 1829.74  4626.8 1829.15  4864.1  1827.6  4893.5 1822.11  4914.4 1817.26
  4985.5  1816.2  4997.2 1812.97  4999.9 1812.47  5003.2 1812.97  5056.6 1821.74
    5086 1830.94  5100.7 1839.35  5122.1 1841.04    5276 1848.47  5607.2 1858.36
  5677.9 1859.82  5861.5 1865.57  5999.8 1873.04  6148.9 1882.37    6261  1894.8
#Mann= 15 ,-1 , 0
  3925.7     .16       0  4058.5     .05       0  4157.1      .1       0
  4370.4     .05       0  4486.6      .1       0  4526.5     .05       0
  4626.8      .1       0  4997.2     .07       0  5003.2      .1       0
  5122.1     .16       0    5276      .1       0  5607.2     .05       0
  5677.9      .1       0  5861.5     .05       0  5999.8     .16       0
Bank Sta=4893.5,5056.6
XS Rating Curve= 0 ,0
Exp/Cntr=0.3,0.1

Type RM Length L Ch R = 1 ,46941   ,433,433,433
BEGIN DESCRIPTION:
BEAR CREEK 80.0
END DESCRIPTION:
XS GIS Cut Line= 4
      2729833.29     10013077.16      2730374.93     10013118.82
      2731312.43     10012509.45        2731651.     10012551.12
#Sta/Elev= 30
  3899.7 1891.19  3920.1  1885.6    3945 1883.37  3975.1    1877  4045.3 1859.32
  4050.5 1854.79  4195.7 1845.02  4257.9 1837.24  4311.2 1829.98  4356.2 1827.78
  4510.8 1826.39  4768.3 1827.22  4919.2 1824.14  4934.4 1821.74  5003.8  1812.2
  5006.6  1811.7  5009.8  1812.2  5064.2 1817.64  5085.3 1822.18  5142.6 1832.35
  5157.8 1836.73  5221.7 1844.56    5254 1846.39    5357 1850.09  5375.1 1850.67
  5468.8 1855.34  5518.1 1860.86  5788.8 1886.98  5869.4 1898.27  5902.2 1899.08
#Mann= 10 ,-1 , 0
  3899.7      .1       0  4257.9     .05       0  4510.8      .1       0
  5003.8     .07       0  5009.8      .1       0  5221.7     .16       0
    5254      .1       0    5357     .05       0  5375.1      .1       0
  5518.1     .16       0
Bank Sta=4934.4,5085.3
XS Rating Curve= 0 ,0
Exp/Cntr=0.3,0.1

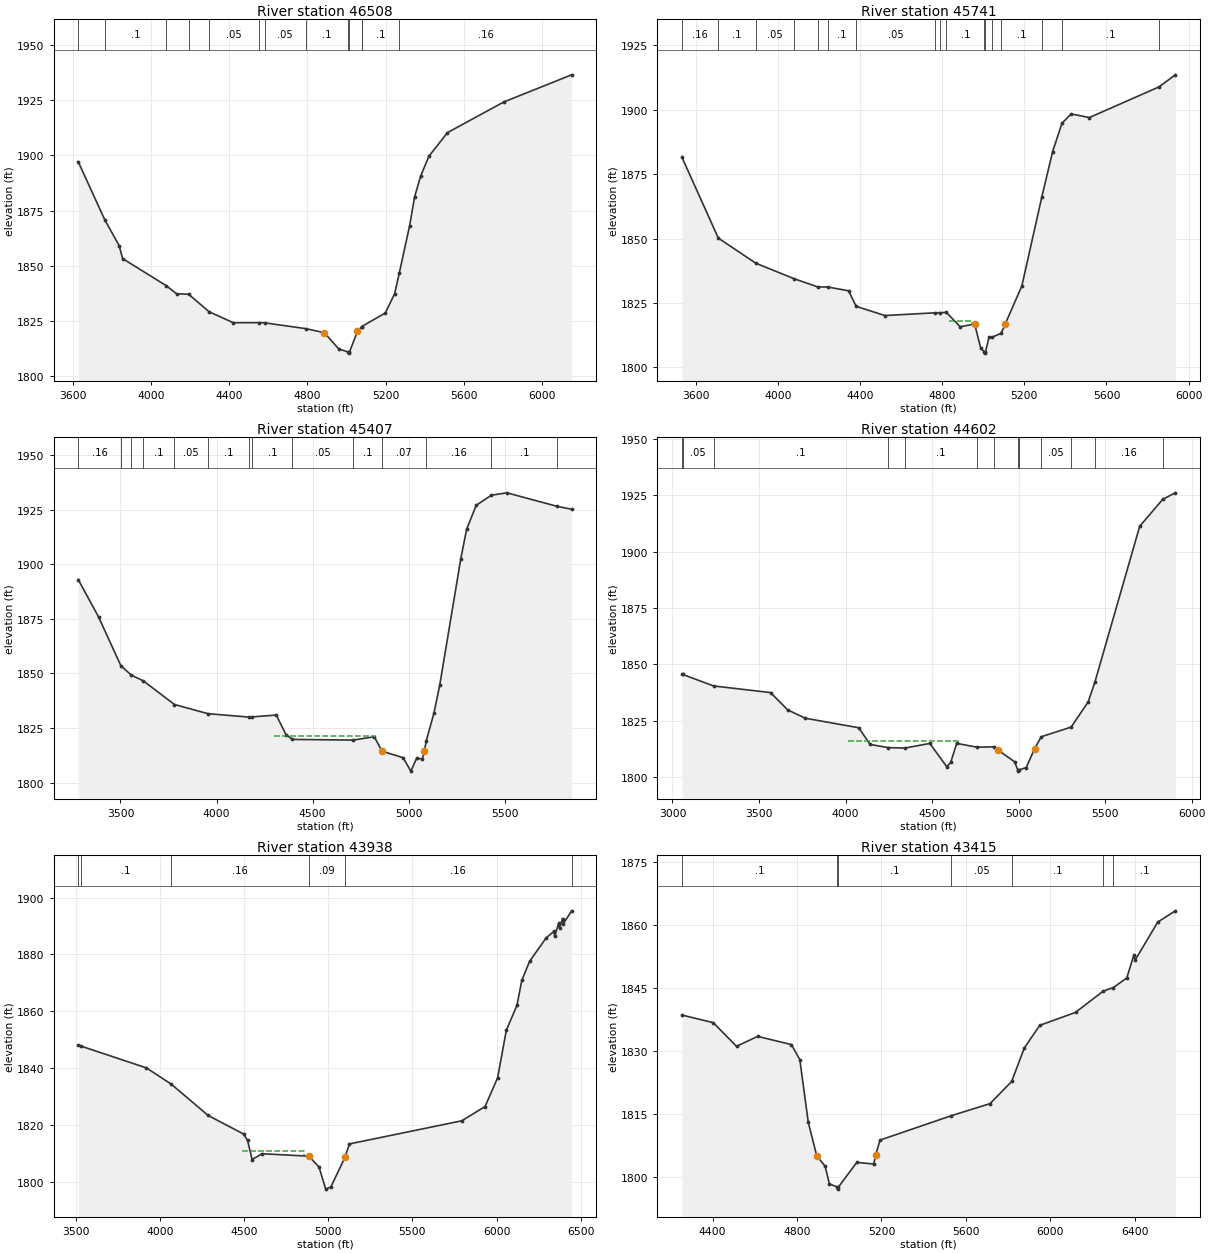
Type RM Length L Ch R = 1 ,46508   ,767,767,767
BEGIN DESCRIPTION:
BEAR CREEK 78.0
END DESCRIPTION:
XS GIS Cut Line= 4
      2729807.23     10013202.16       2730359.3      10013420.9
      2731494.72     10013025.07      2732203.05     10013202.15
#Sta/Elev= 30
    3626 1897.17  3762.1 1870.81  3835.5 1859.18  3853.2  1853.3  4076.2 1841.04
    4130 1837.34    4191 1837.16  4296.5  1829.2  4420.2 1824.24  4553.3 1824.27
  4579.9 1824.21  4790.2 1821.58  4886.1 1819.74  4960.5 1812.35  5009.1 1810.98
  5011.8 1810.48  5015.1 1810.98  5055.6 1820.32  5076.8 1822.36  5077.9 1822.51
  5198.5 1828.65  5246.2 1837.38  5269.8 1846.62  5322.8 1868.07  5348.6 1881.28
  5379.7 1890.69  5421.6 1899.62  5516.8 1910.31  5805.4  1924.2  6152.4 1936.48
#Mann= 13 ,-1 , 0
    3626     .16       0  3762.1      .1       0  4076.2     .05       0
    4191      .1       0  4296.5     .05       0  4553.3      .1       0
  4579.9     .05       0  4790.2      .1       0  5009.1     .07       0
  5015.1      .1       0  5076.8     .16       0  5077.9      .1       0
  5269.8     .16       0
Bank Sta=4886.1,5055.6
XS Rating Curve= 0 ,0
Exp/Cntr=0.3,0.1

Type RM Length L Ch R = 1 ,45741   ,334,334,334
BEGIN DESCRIPTION:
BEAR CREEK 77.0
END DESCRIPTION:
XS GIS Cut Line= 4
      2729864.48     10013400.05      2730755.14     10013879.24
      2731718.68     10013894.86      2732124.19     10014030.03
#Sta/Elev= 30
    3533 1881.53  3709.8  1850.2  3892.4 1840.45  4079.8  1834.4  4193.3 1831.27
  4242.9  1831.2  4343.8 1829.76  4381.1  1823.7    4521 1820.14  4766.7 1821.21
  4791.7 1821.23  4820.4 1821.36  4887.8 1815.77  4957.8 1816.88  4987.8 1807.47
  5004.8 1806.05  5007.5 1805.55  5010.8 1806.05  5027.8 1811.63  5043.1 1811.74
  5087.4 1813.25  5107.8 1817.02  5187.8 1831.61  5284.6 1865.99  5337.8 1883.79
  5383.2 1894.77  5427.8  1898.4  5516.7 1896.99  5855.6 1908.88  5935.5 1913.57
#Mann= 17 ,-1 , 0
    3533     .16       0  3709.8      .1       0  3892.4     .05       0
  4079.8      .1       0  4193.3     .05       0  4242.9      .1       0
  4381.1     .05       0  4766.7      .1       0  4791.7     .05       0
  4820.4      .1       0  5004.8     .07       0  5010.8      .1       0
  5043.1     .05       0  5087.4      .1       0  5284.6     .16       0
  5383.2      .1       0  5855.6     .16       0
#XS Ineff= 1 ,-1
 4833.81 4947.44 1818.17
Permanent Ineff=
       T
Bank Sta=4957.8,5107.8
XS Rating Curve= 0 ,0
Exp/Cntr=0.3,0.1

Type RM Length L Ch R = 1 ,45407   ,805,805,805
BEGIN DESCRIPTION:
BEAR CREEK 76.0
END DESCRIPTION:
XS GIS Cut Line= 3
      2729762.98     10013570.24      2730502.53     10014205.63
      2732094.91     10014231.65
#Sta/Elev= 30
    3280 1892.98  3385.6 1875.94  3502.1 1853.54  3556.7 1849.24  3618.7 1846.64
  3780.9 1835.81  3955.7 1831.61  4167.8 1830.05  4185.1 1830.15    4311 1830.98
    4361 1822.08  4395.1 1819.84  4709.5 1819.53    4821 1821.05    4861 1814.46
    4971 1811.47  5010.8 1805.33  5041.1 1811.17  5071.1 1810.94  5081.1 1814.37
  5091.1 1819.11  5131.1 1831.84  5161.1 1844.55  5271.1 1902.57  5301.1 1915.91
  5351.1 1926.95  5430.7 1931.59  5511.1 1932.66  5773.5 1926.45  5847.6 1925.16
#Mann= 14 ,-1 , 0
    3280     .16       0  3502.1      .1       0  3556.7     .05       0
  3618.7      .1       0  3780.9     .05       0  3955.7      .1       0
  4167.8     .05       0  4185.1      .1       0  4395.1     .05       0
  4709.5      .1       0    4861     .07       0  5091.1     .16       0
  5430.7      .1       0  5773.5     .16       0
#XS Ineff= 1 ,-1
 4297.16 4822.16 1821.38
Permanent Ineff=
       T
Bank Sta=4861,5081.1
XS Rating Curve= 0 ,0
Exp/Cntr=0.3,0.1

Type RM Length L Ch R = 1 ,44602   ,664,664,664
BEGIN DESCRIPTION:
BEAR CREEK 75.0
END DESCRIPTION:
XS GIS Cut Line= 5
      2729493.83     10015818.49      2730591.07     10015075.42
      2730973.02     10014901.81      2731459.13     10015089.31
      2731848.02     10014651.81
#Sta/Elev= 30
    3055 1845.55  3059.4 1845.55  3238.2 1840.45  3566.8 1837.52  3665.7 1829.84
  3767.5 1826.16  4076.1 1821.94    4142 1814.55  4245.6 1813.14  4342.2 1812.93
  4487.2 1814.98  4585.1 1804.65    4608 1806.65  4642.2 1815.02    4758 1813.33
  4856.2 1813.46  4880.6 1812.08  4977.1 1806.83  4995.5 1803.21  4998.2 1802.71
  5001.5 1803.21    5044  1804.3  5093.2 1812.72    5131 1817.95  5303.8 1822.24
  5402.2 1833.38  5441.3 1842.25  5699.9 1911.22  5833.5 1923.22  5906.1 1926.05
#Mann= 13 ,-1 , 0
    3055      .1       0  3059.4     .05       0  3238.2      .1       0
  4245.6     .05       0  4342.2      .1       0    4758     .05       0
  4856.2      .1       0  4995.5     .07       0  5001.5      .1       0
    5131     .05       0  5303.8      .1       0  5441.3     .16       0
  5833.5      .1       0
#XS Ineff= 1 ,-1
  4012.5    4650 1815.94
Permanent Ineff=
       T
Bank Sta=4880.6,5093.2
XS Rating Curve= 0 ,0
Exp/Cntr=0.3,0.1

Type RM Length L Ch R = 1 ,43938   ,523,523,523
BEGIN DESCRIPTION:
BEAR CREEK 74.0
END DESCRIPTION:
XS GIS Cut Line= 4
      2729702.17     10016124.04      2730653.57     10015561.53
      2731723.02     10015644.86      2732035.22     10014958.03
#Sta/Elev= 30
  3513.8 1848.06  3529.4 1847.78  3919.6 1840.08  4067.1 1834.36  4286.3 1823.35
    4497 1816.82  4520.2 1814.56  4547.6 1807.84  4606.1  1809.9  4884.8 1809.03
  4944.9 1805.23  4984.8 1797.44  5015.1 1798.19  5099.2 1808.62  5125.5 1813.34
  5793.4 1821.48  5931.8  1826.5  6006.5  1836.6  6058.1 1853.33  6121.4 1862.11
  6150.4 1870.93  6196.5 1877.58  6294.3 1885.79  6340.4  1888.1  6345.9 1886.38
    6369 1890.93  6374.5 1889.19  6392.1 1892.65  6397.6 1890.86  6446.2 1895.36
#Mann= 6 ,-1 , 0
  3513.8     .05       0  3529.4      .1       0  4067.1     .16       0
  4884.8     .09       0  5099.2     .16       0  6446.2     .16       0
#XS Ineff= 1 ,-1
 4488.64 4855.11 1810.79
Permanent Ineff=
       T
Bank Sta=4884.8,5099.2
XS Rating Curve= 0 ,0
Exp/Cntr=0.3,0.1

Type RM Length L Ch R = 1 ,43415   ,473,473,473
BEGIN DESCRIPTION:
BEAR CREEK 72.0
END DESCRIPTION:
XS GIS Cut Line= 3
      2730229.95     10016117.08      2731639.68     10016096.25
       2732534.5     10015846.54
#Sta/Elev= 30
  4254.8 1838.61  4403.3 1836.79  4513.3 1831.17  4613.4 1833.54  4773.4 1831.59
  4813.4    1828  4853.4 1813.09  4893.4 1805.15  4933.4 1802.63  4953.4 1798.49
  4990.4 1797.71  4993.2 1797.21  4996.4 1797.71  5083.4 1803.57  5163.4 1803.18
  5173.4  1805.4  5193.4 1808.87  5531.7 1814.68  5715.3 1817.55  5817.5 1822.81
  5877.5 1830.79    5951 1836.17  6120.2 1839.24  6251.2 1844.29  6299.6 1845.15
  6363.3 1847.44  6397.4 1852.99  6402.6 1851.66  6510.3 1860.74  6593.7  1863.4
#Mann= 7 ,-1 , 0
  4254.8      .1       0  4990.4     .07       0  4996.4      .1       0
  5531.7     .05       0  5817.5      .1       0  6251.2     .16       0
  6299.6      .1       0
Bank Sta=4893.4,5173.4
XS Rating Curve= 0 ,0
Exp/Cntr=0.3,0.1

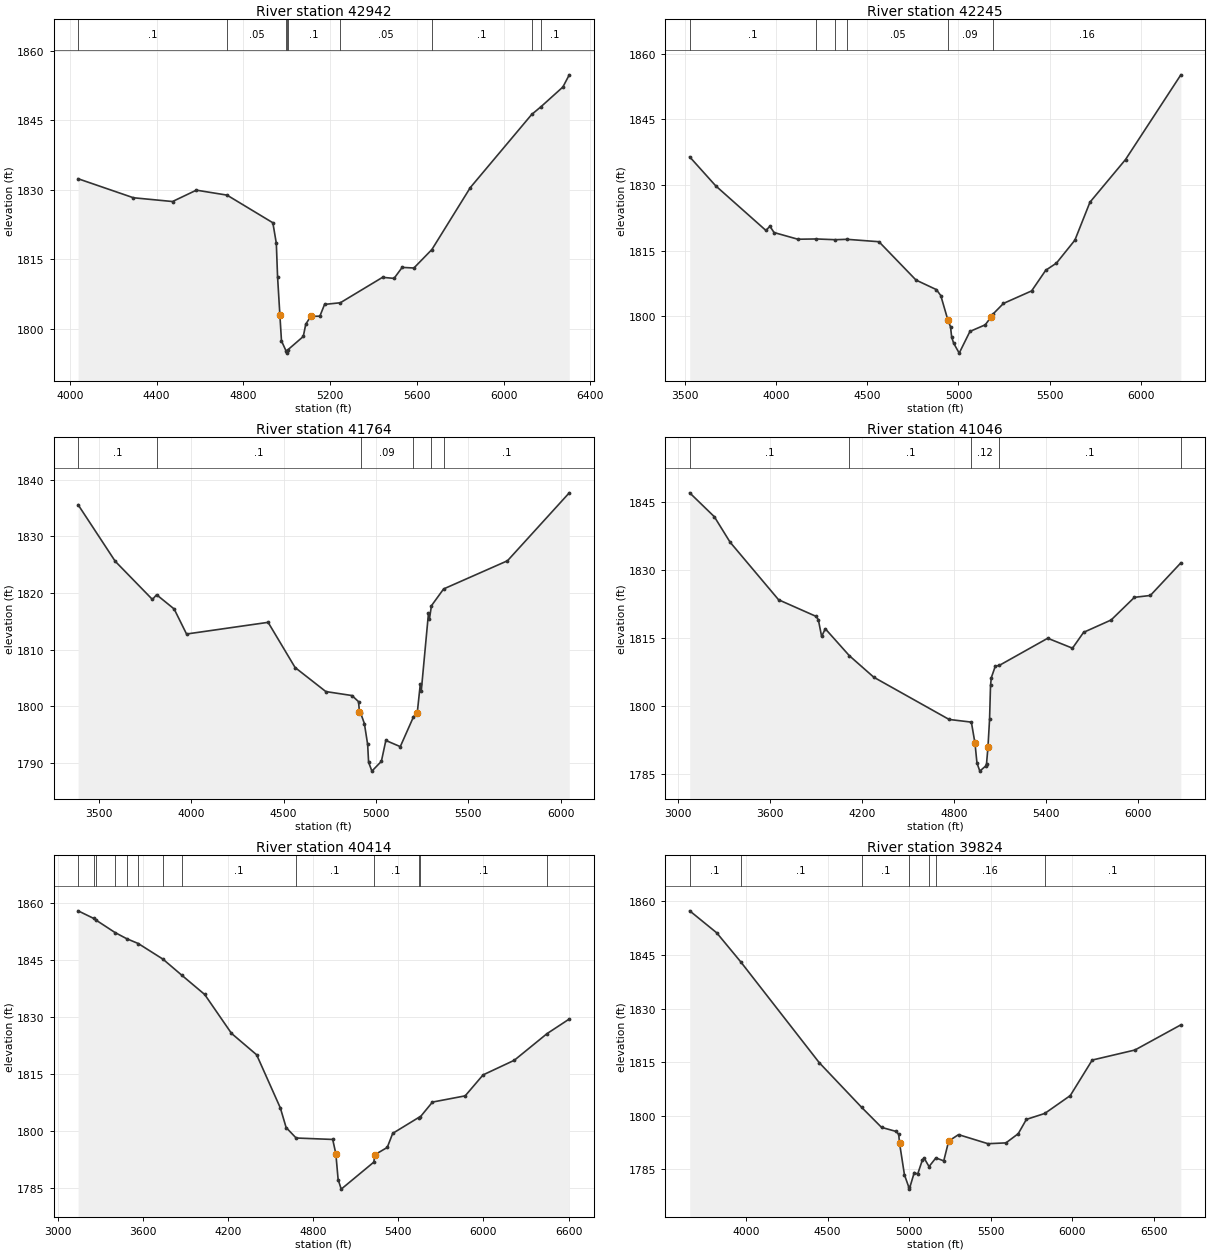
Type RM Length L Ch R = 1 ,42942   ,697,697,697
BEGIN DESCRIPTION:
BEAR CREEK 71.0
END DESCRIPTION:
XS GIS Cut Line= 3
      2730153.59     10016651.81      2730889.68     10016617.08
      2732299.38     10016026.82
#Sta/Elev= 30
  4037.7 1832.38  4292.9 1828.28  4473.1 1827.47  4583.2 1829.92  4724.5 1828.85
  4935.9 1822.89  4951.9 1818.46  4957.6 1811.27  4968.4 1802.92  4975.7 1797.42
  4996.5 1795.29  4999.2 1794.79  5002.5 1795.29  5005.7 1795.53  5076.2 1798.38
  5087.7 1801.04  5110.9 1802.71  5152.7 1802.76  5174.4 1805.29  5247.2 1805.65
  5441.8 1811.13  5494.8  1810.9  5532.2 1813.27  5586.4 1813.14  5669.3 1817.12
  5846.6 1830.48  6129.5 1846.23  6173.5 1847.95  6273.4 1852.15  6302.9 1854.78
#Mann= 9 ,-1 , 0
  4037.7      .1       0  4724.5     .05       0  4996.5    .035       0
  5002.5     .05       0  5005.7      .1       0  5247.2     .05       0
  5669.3      .1       0  6129.5     .16       0  6173.5      .1       0
Bank Sta=4968.4,5110.9
XS Rating Curve= 0 ,0
Exp/Cntr=0.3,0.1

Type RM Length L Ch R = 1 ,42245   ,481,481,481
BEGIN DESCRIPTION:
BEAR CREEK 70.0
END DESCRIPTION:
XS GIS Cut Line= 3
      2730042.48     10016783.76      2731167.46     10017249.03
      2732528.61     10016686.51
#Sta/Elev= 30
  3527.9 1836.43  3670.7  1829.8  3945.6 1819.61  3967.2 1820.58    3990 1819.14
  4120.4 1817.61  4222.1 1817.67  4325.8  1817.5  4389.4 1817.59  4564.6 1817.04
  4767.4 1808.28  4879.3 1806.09  4903.2 1804.73  4941.2 1799.26  4956.5 1797.59
  4962.8 1795.25  4973.6 1793.86    5004 1791.58  5062.9 1796.54  5146.7 1798.05
  5179.2 1799.87  5187.9 1800.45  5246.5 1802.94  5400.8  1805.8    5478 1810.52
  5536.6 1812.15  5637.7  1817.4  5720.2 1826.07    5915 1835.82  6218.1 1855.18
#Mann= 6 ,-1 , 0
  3527.9      .1       0  4222.1     .05       0  4325.8      .1       0
  4389.4     .05       0  4941.2     .09       0  5187.9     .16       0
Bank Sta=4941.2,5179.2
XS Rating Curve= 0 ,0
Exp/Cntr=0.3,0.1

Type RM Length L Ch R = 1 ,41764   ,718,718,718
BEGIN DESCRIPTION:
BEAR CREEK 69.0
END DESCRIPTION:
XS GIS Cut Line= 3
       2730077.2     10016957.37      2731431.35     10017630.97
      2732553.03     10017388.63
#Sta/Elev= 30
  3387.2 1835.56  3588.2 1825.59  3789.8 1818.85  3812.2 1819.69  3907.3 1817.18
  3974.5 1812.76  4416.2 1814.82  4562.4 1806.85  4728.9 1802.61  4870.3 1801.91
    4906 1800.83  4911.1 1798.92  4917.1 1798.85  4937.6 1796.97  4955.3 1793.29
  4960.4 1790.16  4978.3 1788.58  5029.7 1790.31  5053.8 1793.99    5132  1792.9
  5203.6 1798.16  5224.1  1798.9  5240.6 1803.98  5245.7 1802.73  5284.7 1816.41
  5289.8 1815.38  5300.8 1817.75  5366.7 1820.71  5712.6 1825.68  6047.2 1837.66
#Mann= 6 ,-1 , 0
  3387.2      .1       0  3812.2      .1       0  4917.1     .09       0
  5203.6      .1       0  5300.8     .16       0  5366.7      .1       0
Bank Sta=4911.1,5224.1
XS Rating Curve= 0 ,0
Exp/Cntr=0.3,0.1

Type RM Length L Ch R = 1 ,41046   ,632,632,632
BEGIN DESCRIPTION:
BEAR CREEK 68.0
END DESCRIPTION:
XS GIS Cut Line= 4
      2729736.87     10017242.06      2731132.74     10018151.81
      2731598.02     10018311.53       2732486.9     10017755.98
#Sta/Elev= 30
  3074.8 1846.96  3235.7  1841.7  3338.4  1836.1  3655.2 1823.41  3900.3 1819.75
  3914.7 1819.01  3936.1 1815.33    3960 1817.03  4116.9  1811.1  4276.9 1806.35
  4768.2 1797.06  4913.6 1796.47  4937.3 1791.79  4950.1 1787.48  4968.8 1785.68
  5007.4 1786.82  5012.7 1787.35  5021.9 1790.95  5032.5 1797.19  5038.6 1804.54
  5043.9 1806.27  5069.9 1808.79  5095.9 1808.96  5412.1 1814.94  5573.6 1812.75
  5646.2 1816.24    5826 1818.96  5978.1 1823.95  6081.9 1824.36  6281.1 1831.54
#Mann= 5 ,-1 , 0
  3074.8      .1       0  4116.9      .1       0  4913.6     .12       0
  5095.9      .1       0  6281.1      .1       0
Bank Sta=4937.3,5021.9
XS Rating Curve= 0 ,0
Exp/Cntr=0.3,0.1

Type RM Length L Ch R = 1 ,40414   ,590,590,590
BEGIN DESCRIPTION:
BEAR CREEK 66.0
END DESCRIPTION:
XS GIS Cut Line= 3
      2729242.45     10019033.75      2730916.07     10018839.31
       2732484.5     10018006.51
#Sta/Elev= 30
  3144.5 1858.07  3254.5 1856.07    3269 1855.67  3404.5 1852.36    3487 1850.73
  3568.3 1849.46  3742.3 1845.35  3876.2 1841.08  4036.5 1836.04  4225.3  1825.8
  4402.5 1820.16  4569.7 1806.15  4610.3    1801  4680.8 1798.25  4938.4 1797.87
  4960.4 1794.14  4976.7 1787.31  4998.5 1784.79  5228.4 1791.91  5234.9 1793.84
  5322.8 1795.77  5361.1 1799.47  5543.3 1803.63  5553.8 1803.73  5641.3 1807.71
  5871.8 1809.35    5998 1814.87  6217.9 1818.72  6449.1 1825.75  6605.2 1829.58
#Mann= 13 ,-1 , 0
  3144.5     .05       0  3254.5      .1       0    3269     .05       0
  3404.5      .1       0    3487     .05       0  3568.3      .1       0
  3742.3     .05       0  3876.2      .1       0  4680.8      .1       0
  5228.4      .1       0  5543.3     .05       0  5553.8      .1       0
  6449.1     .05       0
Bank Sta=4960.4,5234.9
XS Rating Curve= 0 ,0
Exp/Cntr=0.3,0.1

Type RM Length L Ch R = 1 ,39824   ,623,623,623
BEGIN DESCRIPTION:
BEAR CREEK 65.0
END DESCRIPTION:
XS GIS Cut Line= 3
      2729867.49     10019443.47      2731798.02     10019269.86
      2732513.28     10018471.27
#Sta/Elev= 30
  3655.3 1857.36  3820.9 1851.21  3967.5 1843.12  4449.5 1814.86  4709.3 1802.36
    4831 1796.77  4921.4 1795.61  4936.4 1794.79  4941.4  1792.4  4971.6 1783.48
  4998.7 1779.98  5001.4 1779.48  5031.8 1784.13  5052.5 1783.67    5082  1787.7
  5092.1 1788.18  5122.2 1785.79  5164.2 1788.21  5212.5 1787.39  5242.7 1792.93
  5302.9 1794.73  5483.6 1792.19  5593.6 1792.42    5669 1794.99  5718.8 1798.99
  5831.7 1800.66    5988 1805.66  6122.5  1815.6  6384.2 1818.41  6665.7 1825.45
#Mann= 7 ,-1 , 0
  3655.3      .1       0  3967.5      .1       0  4709.3      .1       0
  4998.7     .09       0  5122.2      .1       0  5164.2     .16       0
  5831.7      .1       0
Bank Sta=4941.4,5242.7
XS Rating Curve= 0 ,0
Exp/Cntr=0.3,0.1

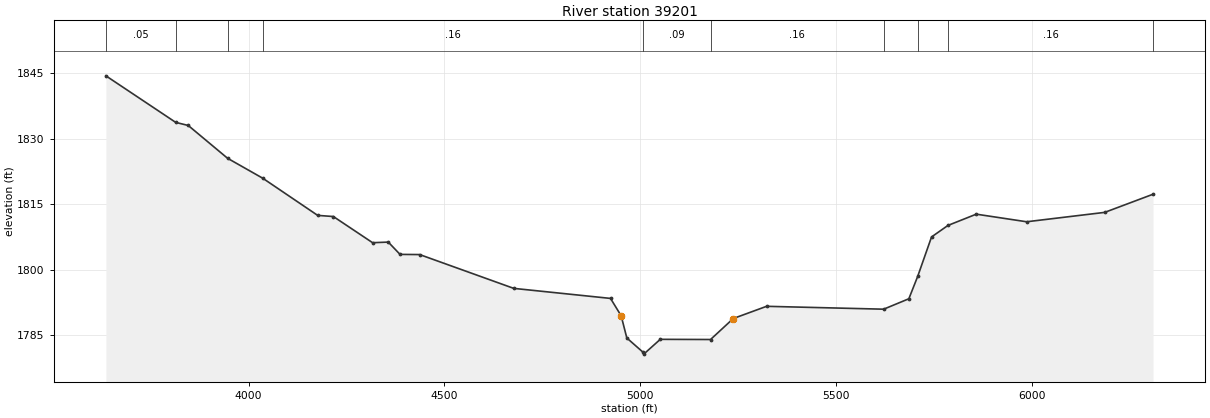
Type RM Length L Ch R = 1 ,39201   ,1193,1193,1193
BEGIN DESCRIPTION:
BEAR CREEK 64.0
END DESCRIPTION:
XS GIS Cut Line= 3
      2730228.52     10019978.19      2731291.07     10020019.86
      2732561.89     10019033.76
#Sta/Elev= 30
  3636.1 1844.44  3814.2 1833.77  3846.2 1833.06  3946.6 1825.54  4036.3 1820.97
  4176.5 1812.45  4216.5 1812.19  4316.6 1806.19  4356.6 1806.33  4386.6 1803.51
  4436.7 1803.47  4676.8 1795.72  4923.7 1793.42  4950.8 1789.44  4965.3 1784.35
  5005.8 1781.15  5008.5 1780.65  5050.6 1784.04  5178.9    1784  5236.9 1788.81
  5321.9 1791.61  5620.6 1790.95  5684.9 1793.34  5707.5 1798.48  5742.8 1807.51
  5784.7 1810.15  5856.9 1812.73  5985.4 1810.99  6184.6 1813.14    6308  1817.3
#Mann= 10 ,-1 , 0
  3636.1     .05       0  3814.2      .1       0  3946.6     .05       0
  4036.3     .16       0  5005.8     .09       0  5178.9     .16       0
  5620.6      .1       0  5707.5      .1       0  5784.7     .16       0
    6308      .1       0
Bank Sta=4950.8,5236.9
XS Rating Curve= 0 ,0
Exp/Cntr=0.3,0.1