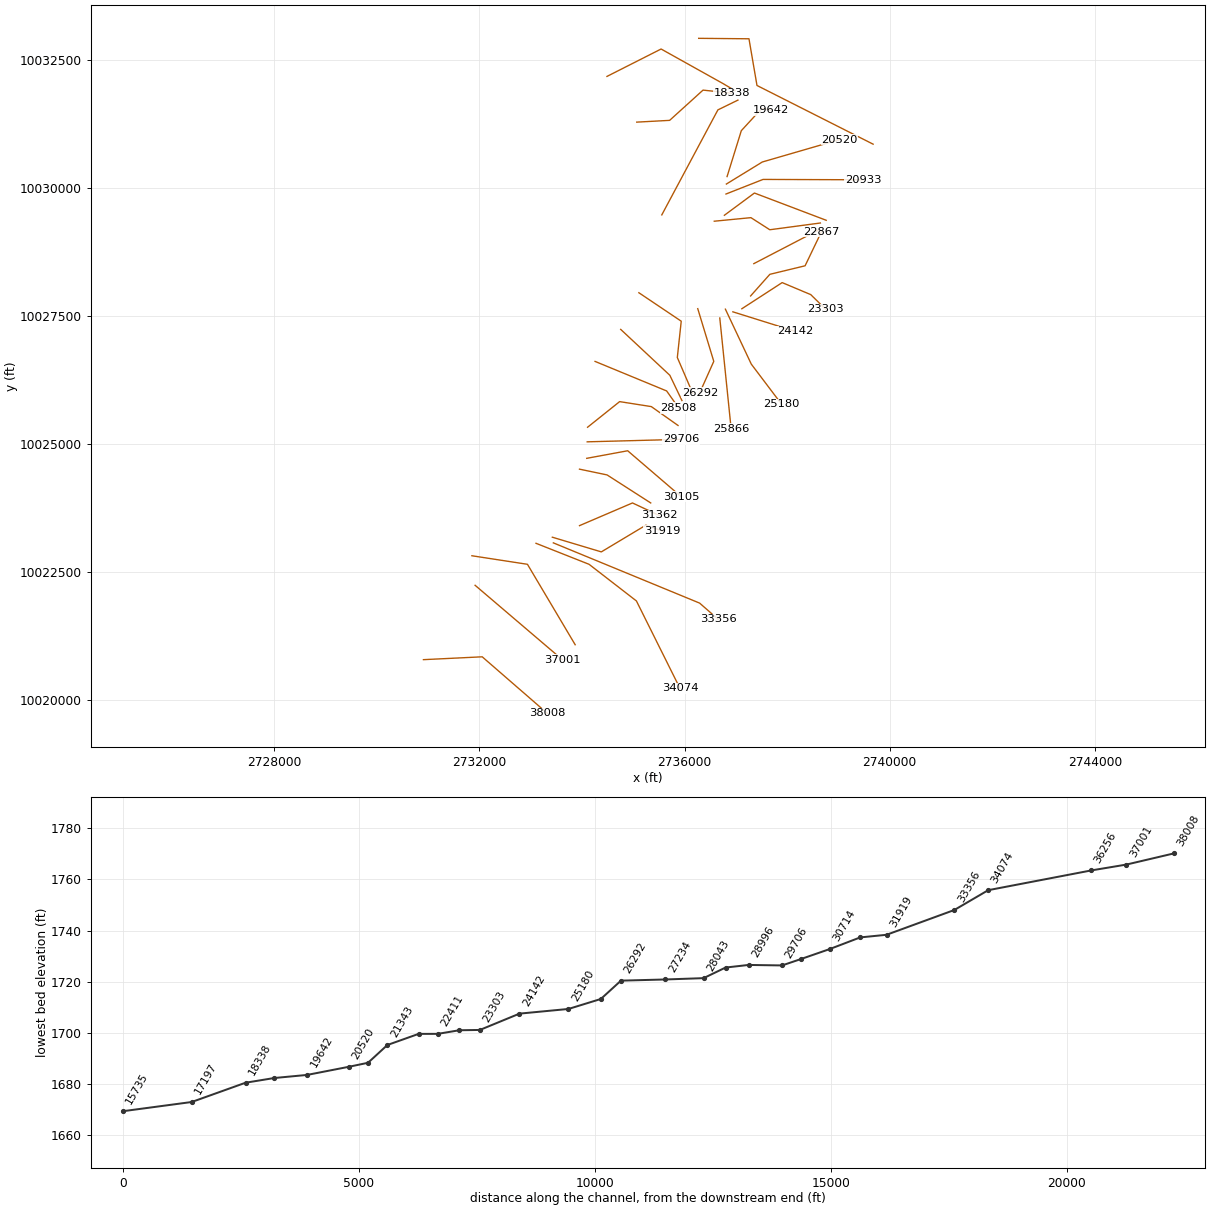
HEC-RAS study BEAR CREEK.prj: BEAR CREEK Base Level Engineering

--- BEAR CREEK.g01 (geometry) --- (continued)

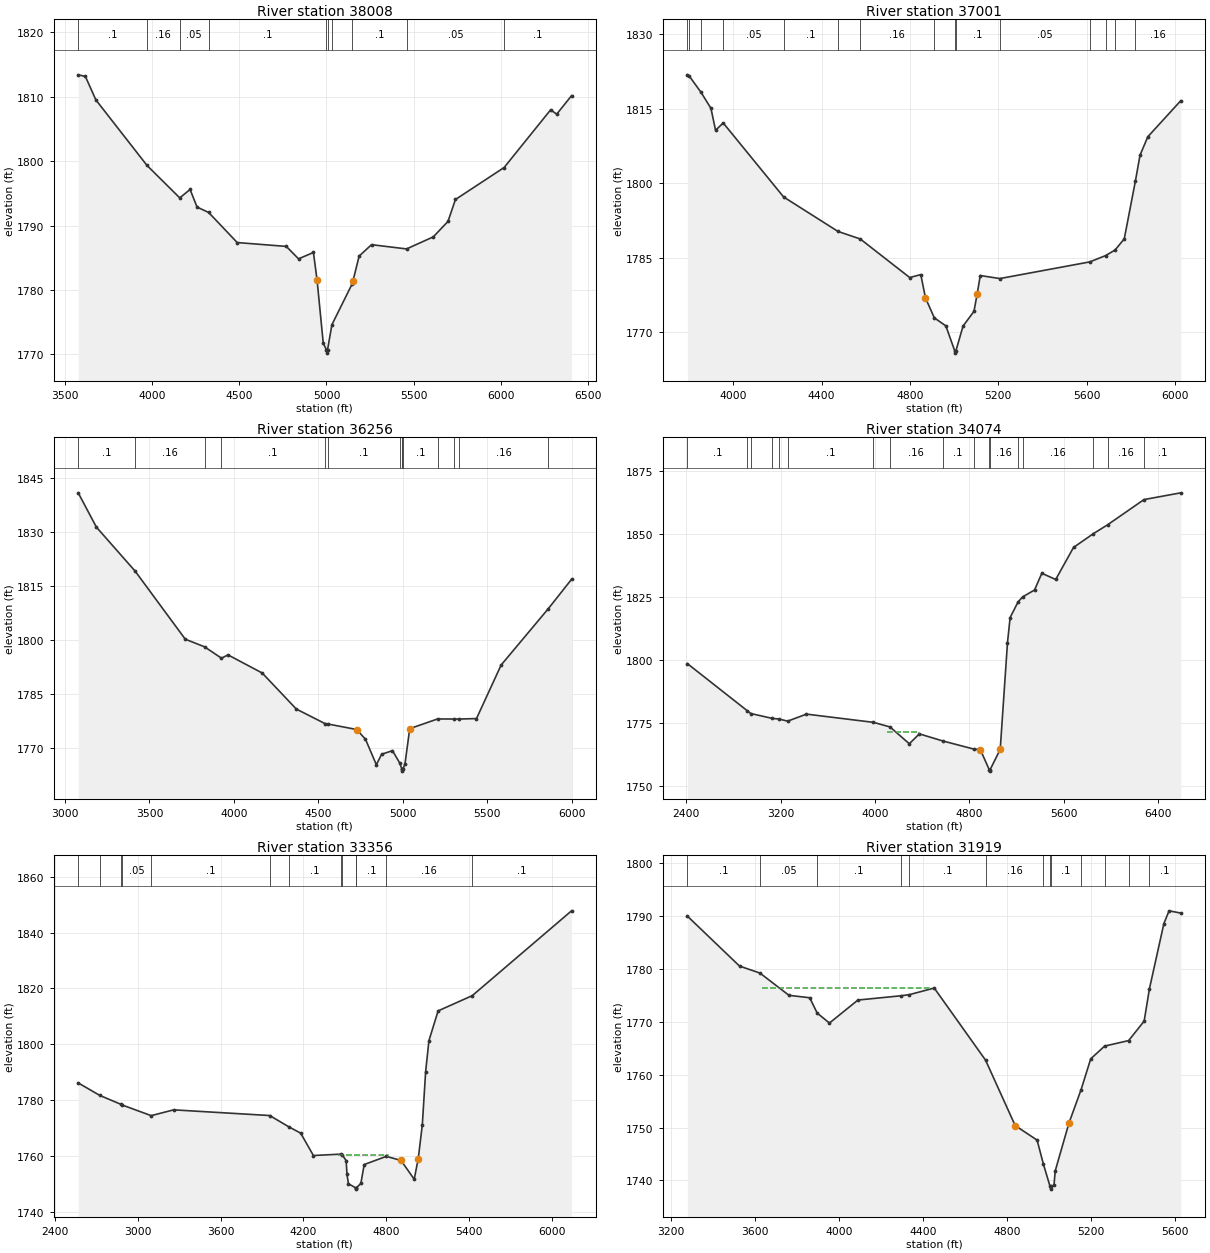
Type RM Length L Ch R = 1 ,38008   ,1007,1007,1007
BEGIN DESCRIPTION:
BEAR CREEK 62.0
END DESCRIPTION:
XS GIS Cut Line= 3
      2730907.36     10020788.09      2732053.23     10020843.65
      2733323.74     10019739.76
#Sta/Elev= 30
  3575.5 1813.42  3616.7 1813.17  3676.7 1809.53    3970 1799.35  4158.1  1794.3
  4217.4 1795.61  4257.4 1792.87  4324.1 1792.03  4487.7 1787.36  4769.4 1786.76
  4839.6 1784.83  4925.1 1785.82    4946 1781.51  4981.4 1771.72  4999.9 1770.68
  5002.7 1770.18  5005.9 1770.68  5031.1  1774.6  5147.1 1780.93    5152  1781.4
  5187.2 1785.26  5258.4 1787.03  5459.3 1786.37  5612.6 1788.24    5697 1790.64
  5739.8 1794.05  6019.1 1799.02  6285.8 1807.98  6320.9 1807.31  6405.8 1810.18
#Mann= 10 ,-1 , 0
  3575.5      .1       0    3970     .16       0  4158.1     .05       0
  4324.1      .1       0  4999.9     .07       0  5005.9      .1       0
  5031.1     .16       0  5147.1      .1       0  5459.3     .05       0
  6019.1      .1       0
Bank Sta=4946,5152
XS Rating Curve= 0 ,0
Exp/Cntr=0.3,0.1

Type RM Length L Ch R = 1 ,37001   ,745,745,745
BEGIN DESCRIPTION:
BEAR CREEK 60.0
END DESCRIPTION:
XS GIS Cut Line= 2
      2731914.31      10022239.5      2733614.22     10020789.38
#Sta/Elev= 30
  3792.2 1821.79  3800.7 1821.53  3853.9 1818.26  3898.7 1815.05  3919.6 1810.64
  3954.3 1812.11  4227.9 1797.22  4474.1 1790.29  4575.1 1788.77  4799.1 1781.01
  4849.2 1781.61  4870.4 1776.91  4910.6  1772.9  4962.7 1771.29  5002.5 1766.31
  5005.3 1765.81  5008.5 1766.31  5040.6 1771.26    5090 1774.21  5104.3 1777.66
  5118.6 1781.42  5207.2 1780.81  5614.7 1784.16  5686.2 1785.43  5729.1 1786.55
  5770.8  1788.8  5820.9 1800.35  5842.1 1805.61  5877.3 1809.33  6026.6 1816.58
#Mann= 15 ,-1 , 0
  3792.2      .1       0  3800.7     .16       0  3853.9      .1       0
  3954.3     .05       0  4227.9      .1       0  4474.1     .05       0
  4575.1     .16       0  4910.6      .1       0  5002.5     .07       0
  5008.5      .1       0  5207.2     .05       0  5614.7      .1       0
  5686.2     .05       0  5729.1      .1       0  5820.9     .16       0
Bank Sta=4870.4,5104.3
XS Rating Curve= 0 ,0
Exp/Cntr=0.3,0.1

Type RM Length L Ch R = 1 ,36256   ,2182,2182,2182
BEGIN DESCRIPTION:
BEAR CREEK 59.0
END DESCRIPTION:
XS GIS Cut Line= 3
      2731851.85     10022815.87      2732935.17      10022649.2
       2733865.7     10021079.79
#Sta/Elev= 30
  3078.1 1840.83  3185.8  1831.3  3415.1 1819.08    3712 1800.17  3825.9 1798.06
  3926.4 1794.89    3965 1795.81  4167.4 1790.78  4369.6 1780.76    4539 1776.73
  4556.3 1776.61  4726.9 1775.08  4778.9 1772.38  4843.2  1765.3  4874.5 1768.21
  4938.8 1769.21  4980.5 1765.86  4993.7 1764.23  4994.2 1764.02    4997 1763.52
  5000.2 1764.02  5012.8 1765.56  5040.8 1775.32  5206.2 1778.02    5305 1777.99
  5329.6 1777.98  5436.1 1778.12    5582    1793  5861.7 1808.67  5998.7  1816.8
#Mann= 14 ,-1 , 0
  3078.1      .1       0  3415.1     .16       0  3825.9     .05       0
  3926.4      .1       0    4539     .05       0  4556.3      .1       0
  4980.5     .16       0  4993.7      .1       0  4994.2     .07       0
  5000.2      .1       0  5206.2     .16       0    5305      .1       0
  5329.6     .16       0  5861.7      .1       0
Bank Sta=4726.9,5040.8
XS Rating Curve= 0 ,0
Exp/Cntr=0.3,0.1

Type RM Length L Ch R = 1 ,34074   ,718,718,718
BEGIN DESCRIPTION:
BEAR CREEK 58.0
END DESCRIPTION:
XS GIS Cut Line= 4
       2733101.8     10023058.94      2734136.56      10022649.2
      2735060.17     10021933.92       2735907.4     10020232.53
#Sta/Elev= 30
    2410 1798.42  2915.6 1779.81  2947.7 1778.63  3129.5 1776.71  3188.5 1776.45
  3259.4 1775.62  3419.2 1778.41  3987.2 1775.14  4127.3 1773.32  4290.9 1766.66
    4376 1770.57  4572.7 1767.79  4837.4 1764.54  4892.4 1764.37    4969  1756.3
  4971.7  1755.8    4975  1756.3  5061.5 1764.44  5123.1 1806.77  5145.5 1816.72
  5213.4 1822.94  5251.5 1824.89  5352.6 1827.64  5414.2 1834.27  5531.7 1831.79
  5682.8  1844.5  5851.2 1849.97    5972 1853.49  6280.1 1863.48  6591.8 1866.16
#Mann= 17 ,-1 , 0
    2410      .1       0  2915.6     .05       0  2947.7      .1       0
  3129.5     .05       0  3188.5     .16       0  3259.4      .1       0
  3987.2     .05       0  4127.3     .16       0  4572.7      .1       0
  4837.4     .16       0    4969     .07       0    4975     .16       0
  5213.4      .1       0  5251.5     .16       0  5851.2      .1       0
    5972     .16       0  6280.1      .1       0
#XS Ineff= 1 ,-1
 4102.27 4372.16 1771.36
Permanent Ineff=
       T
Bank Sta=4892.4,5061.5
XS Rating Curve= 0 ,0
Exp/Cntr=0.3,0.1

Type RM Length L Ch R = 1 ,33356   ,1437,1437,1437
BEGIN DESCRIPTION:
BEAR CREEK 57.0
END DESCRIPTION:
XS GIS Cut Line= 3
      2733439.87     10023067.58      2736293.29     10021891.57
      2736657.94      10021572.5
#Sta/Elev= 30
  2569.8 1786.12  2726.6 1781.63  2882.1 1778.39  2885.4 1778.26  3098.1 1774.39
  3260.5 1776.47    3956 1774.43  4094.9 1770.36  4179.9 1768.13  4272.2  1760.1
  4474.9  1760.6  4482.4 1760.22  4509.3 1758.28  4515.2  1753.3    4526 1749.97
  4577.1 1748.55  4579.8 1748.05  4583.1 1748.55  4615.8 1750.07  4639.8 1756.86
  4799.8 1759.79  4906.2 1758.35  5001.9 1751.59  5031.3 1759.02  5060.6 1771.12
  5084.6 1790.15  5108.5 1801.29  5174.9 1811.94  5422.5 1817.42  6140.6 1847.81
#Mann= 13 ,-1 , 0
  2569.8      .1       0  2726.6     .05       0  2882.1      .1       0
  2885.4     .05       0  3098.1      .1       0    3956     .16       0
  4094.9      .1       0  4474.9     .16       0  4482.4      .1       0
  4577.1     .07       0  4583.1      .1       0  4799.8     .16       0
  5422.5      .1       0
#XS Ineff= 1 ,-1
 4452.27 4809.091760.121
Permanent Ineff=
       T
Bank Sta=4906.2,5031.3
XS Rating Curve= 0 ,0
Exp/Cntr=0.3,0.1

Type RM Length L Ch R = 1 ,31919   ,557,557,557
BEGIN DESCRIPTION:
BEAR CREEK 55.0
END DESCRIPTION:
XS GIS Cut Line= 4
       2733420.8     10023177.86      2734375.71     10022891.39
      2735243.76     10023412.22      2735564.19     10023299.64
#Sta/Elev= 30
    3277 1789.97  3525.1 1780.53  3622.3 1779.21  3760.6    1775  3859.2 1774.54
  3894.9 1771.64  3953.2 1769.76  4088.9 1774.11  4295.1 1774.92    4334 1775.13
  4452.1 1776.38  4696.7 1762.73  4837.6 1750.37  4941.9 1747.62  4972.3 1743.03
  5003.7 1738.85  5006.5 1738.35  5009.7 1738.85  5022.3 1739.05  5028.1 1741.78
  5093.5 1750.83  5151.3 1757.15  5197.2 1762.99  5263.4  1765.4  5377.7 1766.44
  5451.6 1770.12    5477 1776.28  5545.6 1788.57  5570.2 1790.98  5625.9 1790.56
#Mann= 13 ,-1 , 0
    3277      .1       0  3622.3     .05       0  3894.9      .1       0
  4295.1     .16       0    4334      .1       0  4696.7     .16       0
  4972.3      .1       0  5003.7     .07       0  5009.7      .1       0
  5151.3     .05       0  5263.4      .1       0  5377.7     .05       0
    5477      .1       0
#XS Ineff= 1 ,-1
 3634.09 4438.64 1776.35
Permanent Ineff=
       T
Bank Sta=4837.6,5093.5
XS Rating Curve= 0 ,0
Exp/Cntr=0.3,0.1

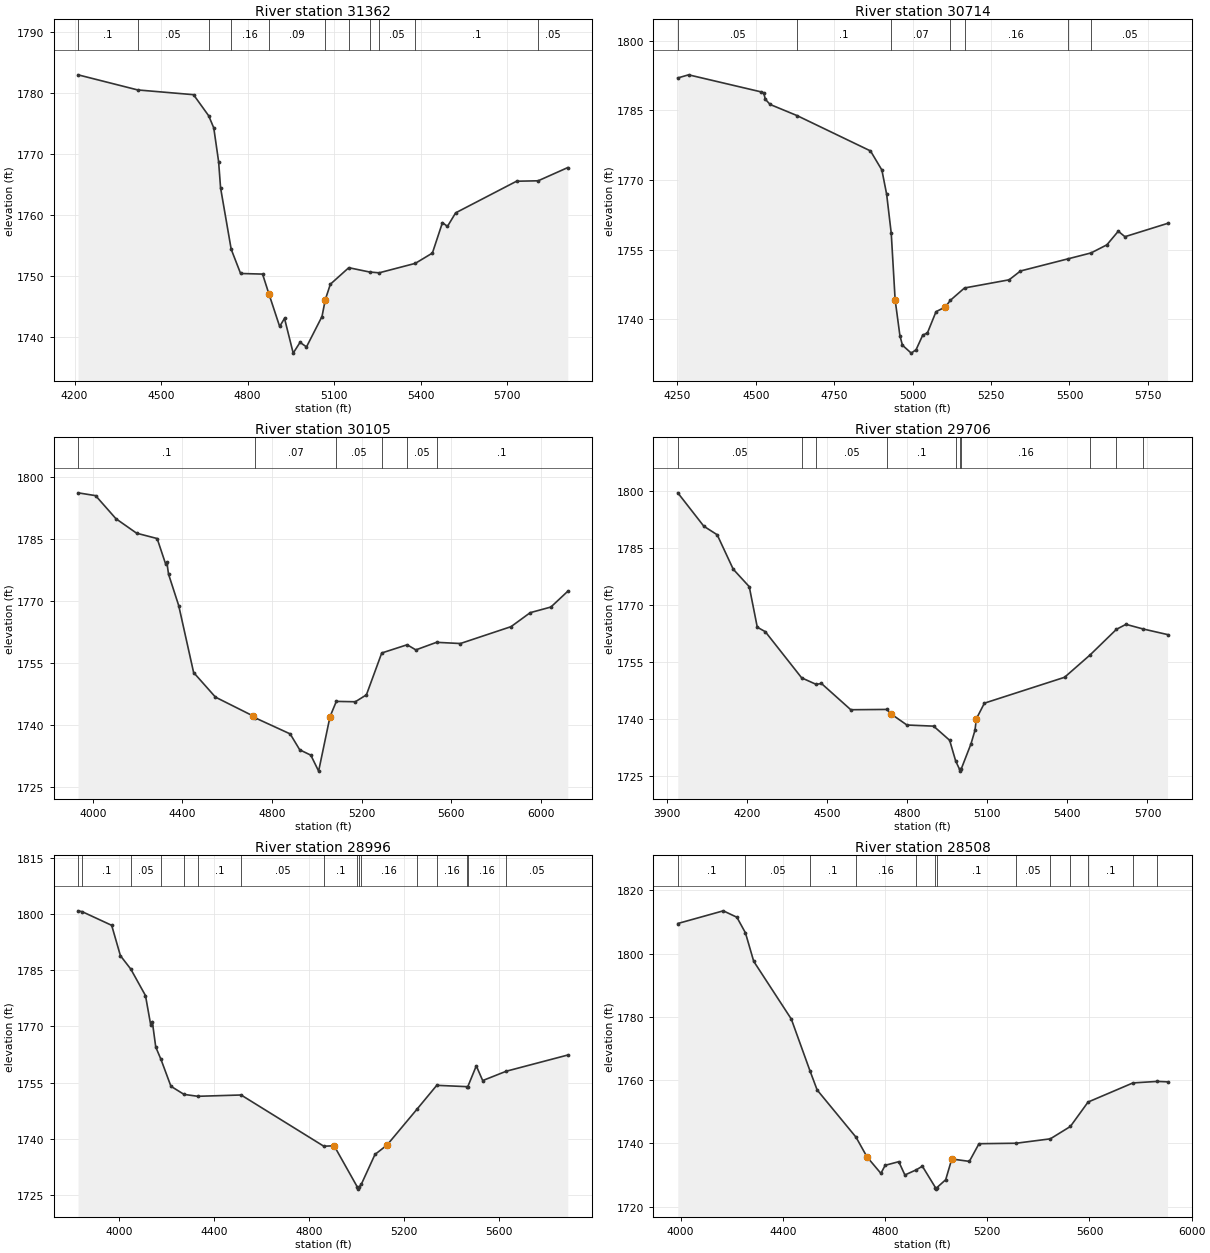
Type RM Length L Ch R = 1 ,31362   ,648,648,648
BEGIN DESCRIPTION:
BEAR CREEK 54.0
END DESCRIPTION:
XS GIS Cut Line= 3
      2733950.34     10023403.53      2734983.35     10023846.25
      2735503.79     10023603.38
#Sta/Elev= 30
    4212    1783    4419 1780.52  4612.5 1779.74  4665.2 1776.27  4682.7 1774.29
  4699.5 1768.76  4706.3 1764.45  4743.1 1754.38  4775.7  1750.4  4851.9  1750.3
  4873.6  1747.1  4911.2  1741.7    4928 1743.04  4958.1 1737.33  4981.9  1739.1
  5004.2 1738.35    5058 1743.34  5069.5 1746.11    5087 1748.64  5150.9 1751.35
  5223.2 1750.64  5256.2 1750.51  5381.5 1752.06  5440.8 1753.75  5475.7 1758.75
    5493 1758.12  5521.4 1760.35  5732.6 1765.54  5807.5 1765.61  5910.2 1767.78
#Mann= 11 ,-1 , 0
    4212      .1       0    4419     .05       0  4665.2      .1       0
  4743.1     .16       0  4873.6     .09       0  5069.5      .1       0
  5150.9     .05       0  5223.2      .1       0  5256.2     .05       0
  5381.5      .1       0  5807.5     .05       0
Bank Sta=4873.6,5069.5
XS Rating Curve= 0 ,0
Exp/Cntr=0.3,0.1

Type RM Length L Ch R = 1 ,30714   ,609,609,609
BEGIN DESCRIPTION:
BEAR CREEK 53.0
END DESCRIPTION:
XS GIS Cut Line= 3
      2733950.38     10024505.97      2734488.56     10024393.13
      2735339.26     10023846.25
#Sta/Elev= 30
  4251.3 1791.99  4285.8 1792.66    4515 1789.02  4525.2  1788.8  4530.3  1787.4
  4545.7 1786.28    4631  1783.9  4865.6 1776.28  4901.9 1772.17  4917.1 1766.96
  4931.8 1758.53  4944.2 1744.22  4959.4 1736.52  4967.5 1734.46  4995.5 1732.76
  5010.9 1733.49  5032.1 1736.62  5047.2 1737.12  5074.5 1741.68  5104.7 1742.71
  5119.9 1744.11  5165.3 1746.78  5307.5 1748.54  5343.8 1750.44    5495 1753.05
  5568.9 1754.33  5619.2 1756.07  5655.5    1759  5676.7 1757.82  5812.5 1760.68
#Mann= 7 ,-1 , 0
  4251.3     .05       0    4631      .1       0  4931.8     .07       0
  5119.9      .1       0  5165.3     .16       0    5495      .1       0
  5568.9     .05       0
Bank Sta=4944.2,5104.7
XS Rating Curve= 0 ,0
Exp/Cntr=0.3,0.1

Type RM Length L Ch R = 1 ,30105   ,399,399,399
BEGIN DESCRIPTION:
BEAR CREEK 52.0
END DESCRIPTION:
XS GIS Cut Line= 3
      2734091.38     10024717.19      2734890.03     10024864.77
      2735931.67     10023970.69
#Sta/Elev= 30
  3934.1 1796.14  4012.5 1795.46  4103.3 1789.88  4195.5 1786.38  4287.1 1785.09
  4325.2 1778.89  4330.3 1779.39  4337.9 1776.48  4383.3 1768.88  4449.8  1752.7
  4547.2 1746.75  4716.1 1742.17  4724.3 1741.74  4880.5 1737.86  4923.3 1734.01
  4972.7 1732.72  5007.5 1728.86  5058.3 1742.03  5086.5 1745.72  5171.3 1745.63
  5220.7  1747.3  5289.1 1757.42  5402.5 1759.41  5441.3 1758.17  5533.5    1760
  5639.9 1759.71    5866 1763.79  5951.6 1767.17  6043.8 1768.53    6119 1772.34
#Mann= 6 ,-1 , 0
  3934.1      .1       0  4724.3     .07       0  5086.5     .05       0
  5289.1      .1       0  5402.5     .05       0  5533.5      .1       0
Bank Sta=4716.1,5058.3
XS Rating Curve= 0 ,0
Exp/Cntr=0.3,0.1

Type RM Length L Ch R = 1 ,29706   ,710,710,710
BEGIN DESCRIPTION:
BEAR CREEK 51.0
END DESCRIPTION:
XS GIS Cut Line= 2
      2734100.99     10025039.25      2735933.85     10025087.85
#Sta/Elev= 30
  3941.6 1799.63  4039.1 1790.84  4089.1 1788.59  4149.1 1779.53  4209.2 1774.92
  4239.2 1764.26  4269.2 1763.08  4405.4 1750.92  4459.9  1749.2  4479.3 1749.45
  4589.3 1742.53  4724.4 1742.61  4739.4 1741.46  4799.4 1738.51  4899.4 1738.21
  4959.4 1734.49    4982 1729.03  4996.4 1726.87  4999.2 1726.37  5002.4 1726.87
  5039.5 1733.59  5054.2 1737.11  5059.5 1740.15  5089.5 1744.26  5389.6 1751.07
  5485.4 1756.97    5584 1763.71  5619.7 1765.01  5682.5 1763.81  5775.1 1762.32
#Mann= 10 ,-1 , 0
  3941.6     .05       0  4405.4      .1       0  4459.9     .05       0
  4724.4      .1       0    4982     .16       0  4996.4     .07       0
  5002.4     .16       0  5485.4     .05       0    5584      .1       0
  5682.5     .05       0
Bank Sta=4739.4,5059.5
XS Rating Curve= 0 ,0
Exp/Cntr=0.3,0.1

Type RM Length L Ch R = 1 ,28996   ,488,488,488
BEGIN DESCRIPTION:
BEAR CREEK 50.0
END DESCRIPTION:
XS GIS Cut Line= 4
      2734107.92     10025323.97      2734732.91     10025823.97
      2735350.97     10025726.75       2735871.8     10025358.69
#Sta/Elev= 30
  3827.2 1800.88  3845.1 1800.64    3969 1797.01  4005.8  1788.9  4049.6 1785.32
  4111.5 1778.24  4133.9 1770.26  4140.3  1771.3  4154.7 1764.51  4176.9 1761.18
  4218.7 1754.03  4273.8 1751.86    4332 1751.35  4514.4  1751.7  4862.9 1738.02
  4906.5 1738.14  5004.8 1727.06  5007.5 1726.56  5010.8 1727.06  5020.6  1727.8
  5078.6 1735.82  5129.2 1738.32  5256.9    1748  5338.9 1754.28  5464.9 1753.93
  5469.3 1753.85  5505.5 1759.48  5532.5 1755.55    5632 1758.05    5891 1762.37
#Mann= 16 ,-1 , 0
  3827.2     .05       0  3845.1      .1       0  4049.6     .05       0
  4176.9      .1       0  4273.8     .05       0    4332      .1       0
  4514.4     .05       0  4862.9      .1       0  5004.8     .07       0
  5010.8      .1       0  5020.6     .16       0  5256.9      .1       0
  5338.9     .16       0  5464.9      .1       0  5469.3     .16       0
    5632     .05       0
Bank Sta=4906.5,5129.2
XS Rating Curve= 0 ,0
Exp/Cntr=0.3,0.1

Type RM Length L Ch R = 1 ,28508   ,465,465,465
BEGIN DESCRIPTION:
BEAR CREEK 49.0
END DESCRIPTION:
XS GIS Cut Line= 3
      2734253.75     10026608.69      2735649.58      10026032.3
      2735884.57     10025700.56
#Sta/Elev= 30
  3988.8 1809.52  4166.9 1813.53  4220.1  1811.5  4253.6 1806.56    4286 1797.56
  4433.1 1779.31    4506 1762.98  4534.2 1756.89  4686.5 1741.94  4729.6  1735.7
  4783.7 1730.52  4800.4 1733.07  4853.7 1734.22  4877.6 1730.01  4922.1 1731.64
    4946 1732.79  4997.1 1726.04  4999.8 1725.54  5003.1 1726.04  5037.3 1728.51
  5061.2 1735.07  5129.9 1734.31  5167.7  1739.9    5313 1740.05  5446.8 1741.44
  5525.3 1745.35  5594.5 1753.07  5770.2 1759.12  5866.1  1759.6  5905.5 1759.46
#Mann= 13 ,-1 , 0
  3988.8      .1       0  4253.6     .05       0    4506      .1       0
  4686.5     .16       0  4922.1      .1       0  4997.1     .07       0
  5003.1      .1       0    5313     .05       0  5446.8      .1       0
  5525.3     .05       0  5594.5      .1       0  5770.2     .16       0
  5866.1      .1       0
Bank Sta=4729.6,5061.2
XS Rating Curve= 0 ,0
Exp/Cntr=0.3,0.1

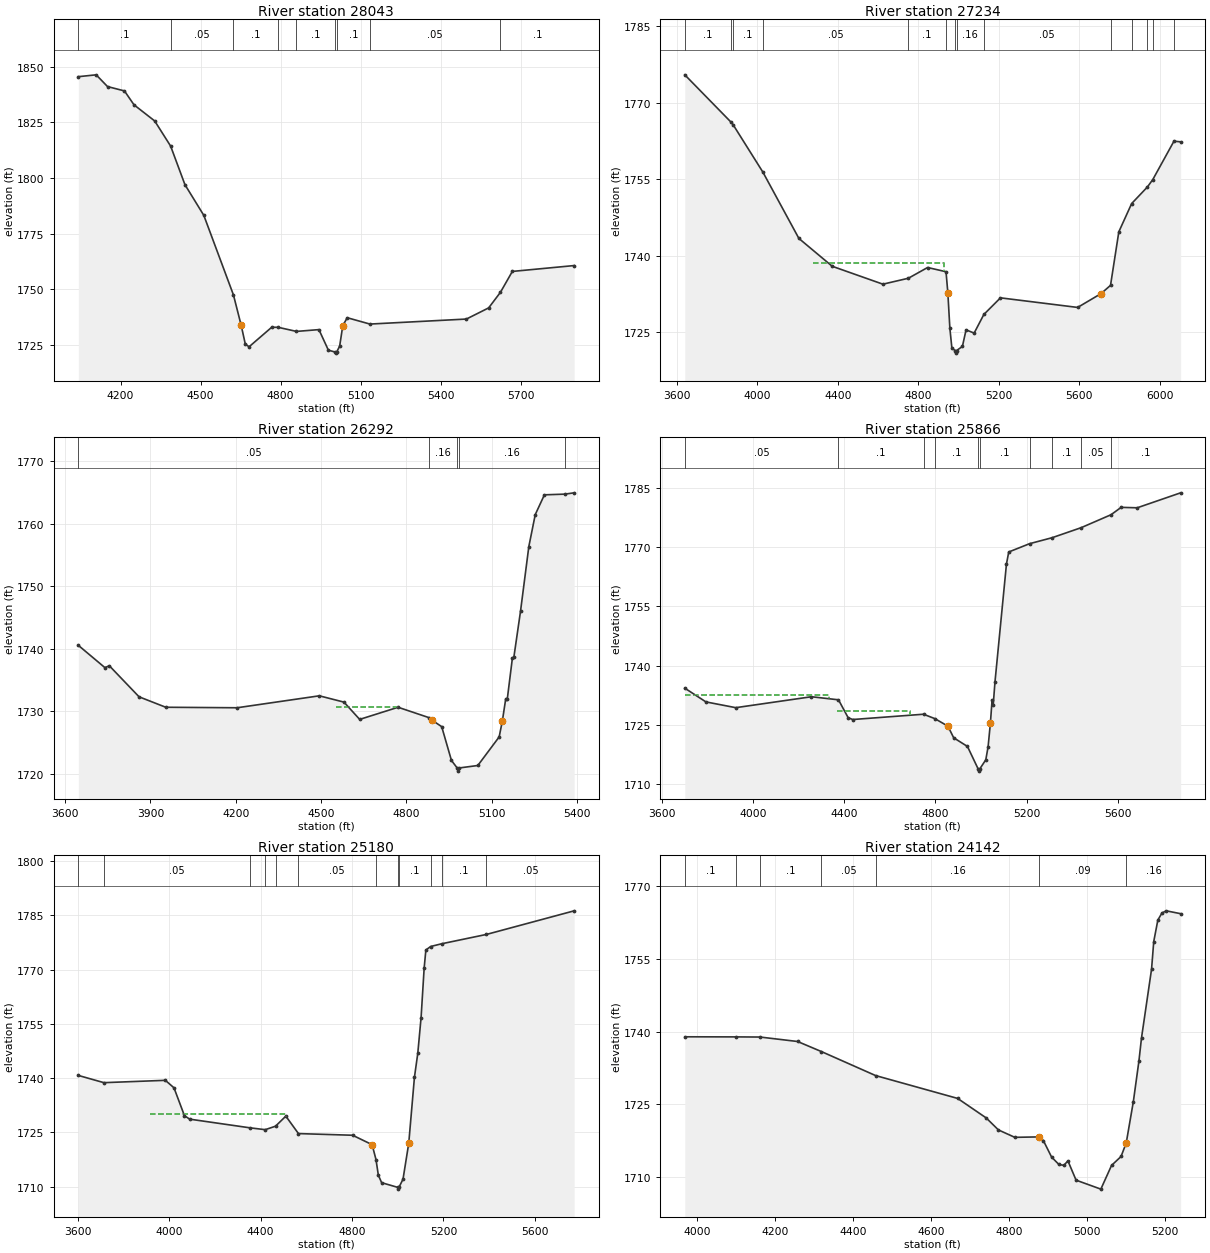
Type RM Length L Ch R = 1 ,28043   ,809,809,809
BEGIN DESCRIPTION:
BEAR CREEK 48.0
END DESCRIPTION:
XS GIS Cut Line= 3
      2734753.77     10027233.68      2735712.08     10026337.86
       2735948.2     10025844.79
#Sta/Elev= 30
  4041.8 1845.54  4108.7 1846.37  4151.2  1841.1  4214.7 1839.14  4250.4 1832.91
  4328.1 1825.65  4387.7 1814.38  4441.4 1797.05  4512.2 1783.25  4623.3  1747.5
 4652.27 1733.84  4667.6 1725.49  4681.7 1724.24  4766.7 1733.02    4791 1732.99
  4859.5 1731.15  4943.6 1731.96  4979.1 1722.72  5004.1  1721.9  5006.8  1721.4
  5010.1  1721.9  5021.3 1724.52 5032.95 1733.67  5049.6  1737.3  5134.8 1734.45
  5496.3  1736.7  5579.9 1741.72  5624.1 1748.74  5668.6 1758.09  5900.3 1760.72
#Mann= 9 ,-1 , 0
  4041.8      .1       0  4387.7     .05       0  4623.3      .1       0
    4791     .16       0  4859.5      .1       0  5004.1     .07       0
  5010.1      .1       0  5134.8     .05       0  5624.1      .1       0
Bank Sta=4652.27,5032.95
XS Rating Curve= 0 ,0
Exp/Cntr=0.3,0.1

Type RM Length L Ch R = 1 ,27234   ,942,942,942
BEGIN DESCRIPTION:
BEAR CREEK 47.0
END DESCRIPTION:
XS GIS Cut Line= 4
      2735107.92     10027948.97       2735934.3     10027393.42
      2735857.91     10026685.08      2736156.51     10025990.67
#Sta/Elev= 30
  3639.6 1775.45  3869.9 1766.15    3880 1765.65  4027.7 1756.37  4206.6 1743.37
  4372.1 1737.91  4624.1  1734.4  4750.5 1735.56  4846.3 1737.67  4937.8 1736.84
  4946.8 1732.74  4956.9 1725.76    4967 1721.83  4984.1 1721.38  4986.8 1720.88
  4990.1 1721.38  5019.2 1722.19  5037.4 1725.44  5077.6 1724.81  5125.8 1728.46
  5208.4 1731.72  5591.9 1729.84  5708.5 1732.56  5755.3 1734.17  5796.6 1744.67
  5860.4 1750.21  5938.4 1753.45  5965.5 1754.92  6070.6 1762.44  6103.7 1762.31
#Mann= 14 ,-1 , 0
  3639.6      .1       0  3869.9     .05       0    3880      .1       0
  4027.7     .05       0  4750.5      .1       0  4937.8     .16       0
  4984.1     .07       0  4990.1     .16       0  5125.8     .05       0
  5755.3     .16       0  5860.4      .1       0  5938.4     .16       0
  5965.5     .05       0  6070.6      .1       0
#XS Ineff= 1 ,-1
 4278.98  4926.7 1738.55
Permanent Ineff=
       T
Bank Sta=4946.8,5708.5
XS Rating Curve= 0 ,0
Exp/Cntr=0.3,0.1

Type RM Length L Ch R = 1 ,26292   ,426,426,426
BEGIN DESCRIPTION:
BEAR CREEK 46.0
END DESCRIPTION:
XS GIS Cut Line= 3
      2736256.36     10027638.17      2736568.85     10026609.56
      2736295.67     10025998.15
#Sta/Elev= 30
  3646.1 1740.53  3739.5 1736.97  3755.3 1737.26  3859.8  1732.3  3953.8 1730.63
  4204.7 1730.55  4494.1 1732.46  4580.9 1731.45  4636.1 1728.69  4771.3 1730.63
  4880.7 1728.96  4891.8 1728.53  4924.7 1727.53    4959 1722.13  4979.2 1720.92
  4981.9 1720.42  4985.2 1720.92  5051.8 1721.32  5126.9 1725.89 5138.18 1728.45
  5150.1    1732  5155.6 1731.98  5173.3 1738.43  5178.8 1738.68    5202 1745.96
  5231.3 1756.32  5253.9 1761.43  5286.1 1764.59  5357.8  1764.7  5390.8 1764.91
#Mann= 5 ,-1 , 0
  3646.1     .05       0  4880.7     .16       0  4979.2     .07       0
  4985.2     .16       0  5357.8     .05       0
#XS Ineff= 1 ,-1
 4553.18 4773.07 1730.64
Permanent Ineff=
       T
Bank Sta=4891.8,5138.18
XS Rating Curve= 0 ,0
Exp/Cntr=0.3,0.1

Type RM Length L Ch R = 1 ,25866   ,686,686,686
BEGIN DESCRIPTION:
BEAR CREEK 45.0
END DESCRIPTION:
XS GIS Cut Line= 2
      2736686.04     10027455.88      2736907.39     10025294.49
#Sta/Elev= 30
  3701.6 1734.26  3794.2 1730.78  3924.9 1729.32  4256.6 1732.09  4375.1 1731.31
  4417.5 1726.77  4437.6 1726.32  4747.6 1727.66  4797.5 1726.54  4854.5 1724.64
  4879.9 1721.69  4940.2  1719.5  4987.5 1713.75  4990.2 1713.25  4993.5 1713.75
  5020.6 1716.12  5030.7 1719.44  5040.7 1725.39  5048.1 1731.22  5053.2  1730.1
  5060.8 1735.83  5111.1 1765.69  5121.1 1768.75  5212.4 1770.85  5310.9 1772.36
  5438.7 1774.91  5569.2 1778.18  5613.7 1780.05  5684.1 1779.94  5874.3 1783.73
#Mann= 10 ,-1 , 0
  3701.6     .05       0  4375.1      .1       0  4747.6     .05       0
  4797.5      .1       0  4987.5     .07       0  4993.5      .1       0
  5212.4     .05       0  5310.9      .1       0  5438.7     .05       0
  5569.2      .1       0
#XS Ineff= 2 ,-1
 3677.56 4333.81 1732.43 4366.92 4689.02  1728.4
Permanent Ineff=
       T       T
Bank Sta=4854.5,5040.7
XS Rating Curve= 0 ,0
Exp/Cntr=0.3,0.1

Type RM Length L Ch R = 1 ,25180   ,1038,1038,1038
BEGIN DESCRIPTION:
BEAR CREEK 44.0
END DESCRIPTION:
XS GIS Cut Line= 3
      2736795.43     10027628.41      2737300.62     10026555.52
      2737893.95     10025769.63
#Sta/Elev= 30
  3601.8 1740.77  3713.8 1738.77  3982.8 1739.42  4020.6 1737.34  4066.2 1729.67
    4089 1728.69  4353.2 1726.29  4419.9 1725.78    4465 1726.74  4510.2 1729.52
  4565.4  1724.7  4802.5 1724.24  4887.9 1721.64  4904.9 1717.52  4915.2  1713.2
  4929.6 1711.13  4999.4 1709.85  5002.2 1709.35  5005.4 1709.85  5023.2  1712.1
  5048.3 1722.03  5073.2 1740.26  5087.8 1746.86  5102.3 1756.77  5115.7 1770.41
  5123.2 1775.43  5144.1  1776.4  5191.9 1777.15  5388.6 1779.74  5772.4 1786.26
#Mann= 12 ,-1 , 0
  3601.8      .1       0  3713.8     .05       0  4353.2      .1       0
  4419.9     .05       0    4465      .1       0  4565.4     .05       0
  4904.9      .1       0  4999.4     .07       0  5005.4      .1       0
  5144.1     .16       0  5191.9      .1       0  5388.6     .05       0
#XS Ineff= 1 ,-1
 3916.19 4511.36 1730.04
Permanent Ineff=
       T
Bank Sta=4887.9,5048.3
XS Rating Curve= 0 ,0
Exp/Cntr=0.3,0.1

Type RM Length L Ch R = 1 ,24142   ,839,839,839
BEGIN DESCRIPTION:
BEAR CREEK 42.0
END DESCRIPTION:
XS GIS Cut Line= 2
      2736941.21     10027576.37      2738154.17     10027196.34
#Sta/Elev= 30
  3968.2 1738.96  4100.5 1738.94  4161.1 1738.91  4257.4 1737.99  4318.5 1735.91
  4457.3 1730.96  4667.7 1726.24  4740.8 1722.22  4772.2 1719.74  4814.2 1718.21
    4877  1718.3  4887.5 1717.53  4908.5 1714.14  4927.2 1712.61  4939.9 1712.43
  4950.4 1713.35  4971.3 1709.37  5034.8 1707.52  5062.2 1712.41  5086.6 1714.26
  5099.9 1717.07  5118.1 1725.58  5132.4 1733.96    5139 1738.72  5164.8 1752.93
  5170.4 1758.62  5180.9 1763.05  5191.4 1764.51  5202.5 1764.96  5239.3 1764.37
#Mann= 7 ,-1 , 0
  3968.2      .1       0  4100.5     .05       0  4161.1      .1       0
  4318.5     .05       0  4457.3     .16       0    4877     .09       0
  5099.9     .16       0
Bank Sta=4877,5099.9
XS Rating Curve= 0 ,0
Exp/Cntr=0.3,0.1

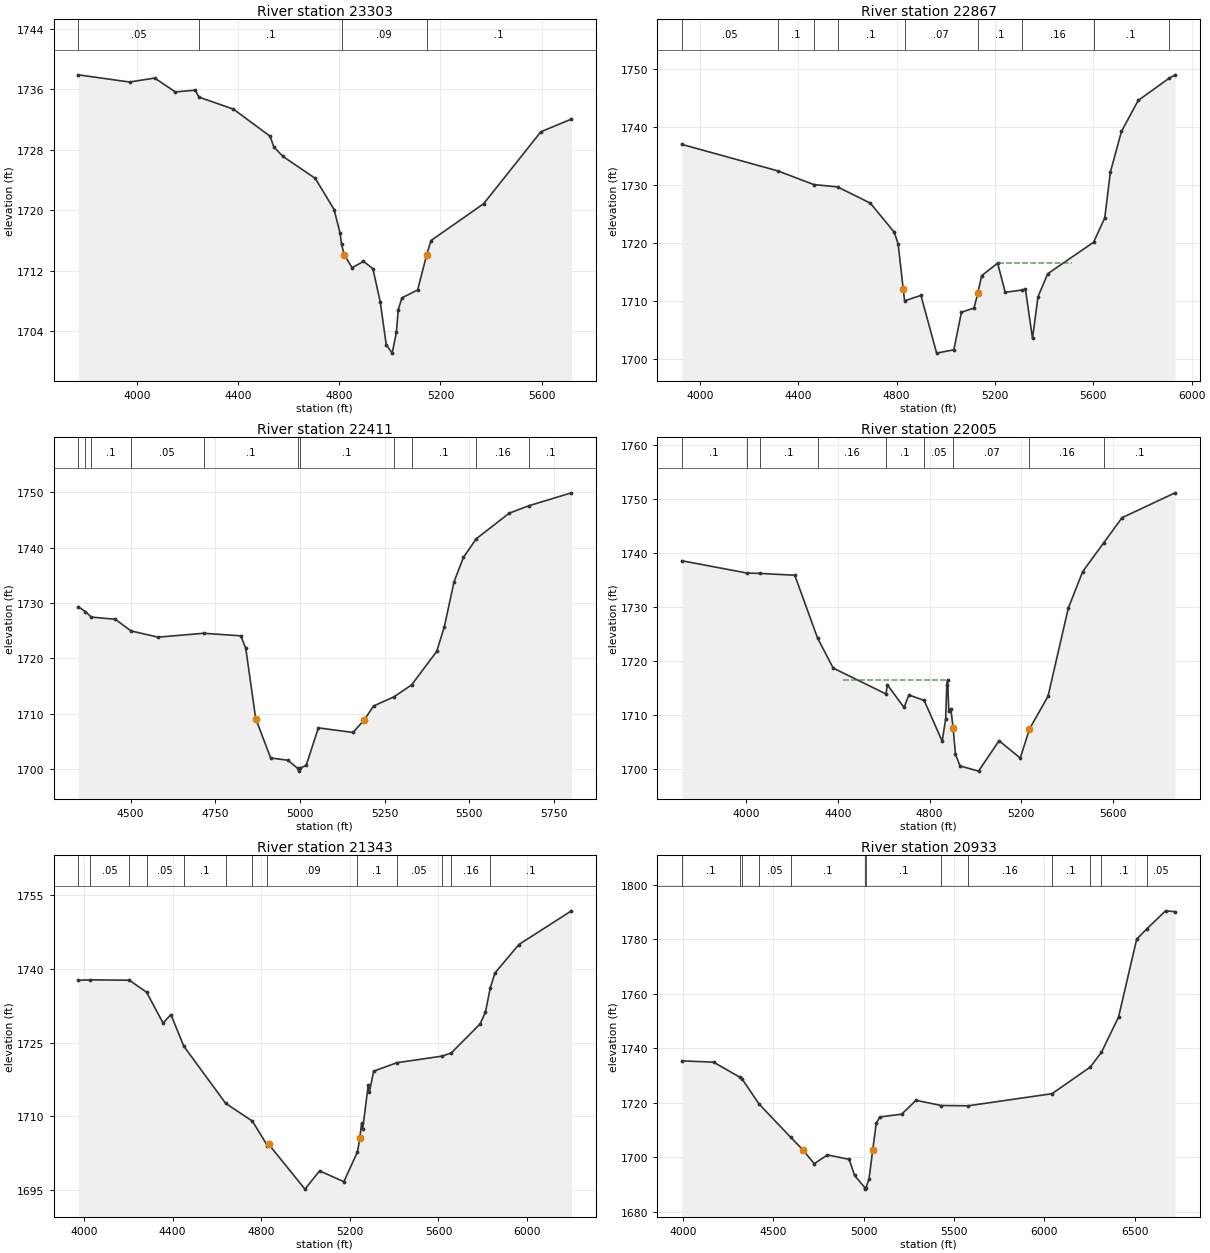
Type RM Length L Ch R = 1 ,23303   ,436,436,436
BEGIN DESCRIPTION:
BEAR CREEK 41.0
END DESCRIPTION:
XS GIS Cut Line= 4
      2737116.14     10027636.31      2737902.57     10028146.71
      2738459.87     10027912.34      2738751.52      10027625.9
#Sta/Elev= 30
  3767.4 1737.92  3970.4 1736.97    4070 1737.49  4151.6 1735.66  4230.1 1735.89
  4245.2 1734.97  4381.1 1733.39  4526.1 1729.81  4541.2 1728.39  4577.5 1727.13
  4704.9 1724.24  4779.5 1720.12  4803.2    1717    4809  1715.5  4819.8 1714.13
  4850.7 1712.42  4895.8 1713.27  4932.8 1712.31    4962 1707.93  4985.7 1702.26
  5009.2 1701.14  5025.9 1703.88  5033.2 1706.86  5047.6 1708.44  5109.9 1709.49
  5145.3 1714.09  5162.8 1716.02  5371.2 1720.89  5597.5  1730.4  5718.3 1732.07
#Mann= 4 ,-1 , 0
  3767.4     .05       0  4245.2      .1       0    4809     .09       0
  5145.3      .1       0
Bank Sta=4819.8,5145.3
XS Rating Curve= 0 ,0
Exp/Cntr=0.3,0.1

Type RM Length L Ch R = 1 ,22867   ,456,456,456
BEGIN DESCRIPTION:
BEAR CREEK 40.0
END DESCRIPTION:
XS GIS Cut Line= 4
      2737287.16     10027886.33      2737662.12     10028308.17
      2738349.62     10028474.84      2738667.32     10029136.28
#Sta/Elev= 30
    3927 1736.95    4317 1732.39  4463.9 1730.03  4560.3 1729.63  4693.4 1726.84
    4791 1721.81  4806.6  1719.8  4827.2 1712.03  4832.8 1710.02  4899.2 1710.95
  4963.1 1701.02    5033 1701.59  5063.9 1708.06  5115.3 1708.79  5130.6 1711.38
  5146.2 1714.35    5211  1716.5    5242 1711.49  5308.5 1711.87  5324.2 1712.01
  5352.9 1703.54  5375.1 1710.72  5414.7 1714.68  5601.1  1720.1  5646.7 1724.29
  5669.3 1732.14  5714.6 1739.18  5782.6 1744.51  5907.5 1748.31  5932.6 1748.92
#Mann= 9 ,-1 , 0
    3927     .05       0    4317      .1       0  4463.9     .05       0
  4560.3      .1       0  4832.8     .07       0  5130.6      .1       0
  5308.5     .16       0  5601.1      .1       0  5907.5     .16       0
#XS Ineff= 1 ,-1
 5210.56 5512.08 1716.54
Permanent Ineff=
       T
Bank Sta=4827.2,5130.6
XS Rating Curve= 0 ,0
Exp/Cntr=0.3,0.1

Type RM Length L Ch R = 1 ,22411   ,406,406,406
BEGIN DESCRIPTION:
BEAR CREEK 39.0
END DESCRIPTION:
XS GIS Cut Line= 2
       2737349.6     10028516.49       2738641.3     10029188.38
#Sta/Elev= 30
  4345.2 1729.36  4366.5 1728.44  4383.8 1727.46  4454.7 1727.06  4500.9 1724.96
  4580.6 1723.83  4715.4 1724.53  4824.9 1724.07  4839.9 1721.81  4869.1 1709.12
  4913.3 1701.99  4963.9 1701.58  4993.1 1700.11  4995.9 1699.61  4999.1 1700.11
  5018.2 1700.65  5054.1 1707.43  5156.5  1706.6  5189.3 1708.85  5217.2 1711.39
  5276.9 1713.03  5329.5 1715.21  5403.5 1721.26    5426 1725.72  5454.7 1733.86
  5482.5 1738.27  5520.3 1741.62  5617.7 1746.25  5676.8 1747.61  5801.2 1749.92
#Mann= 11 ,-1 , 0
  4345.2      .1       0  4366.5     .05       0  4383.8      .1       0
  4500.9     .05       0  4715.4      .1       0  4993.1     .07       0
  4999.1      .1       0  5276.9     .16       0  5329.5      .1       0
  5520.3     .16       0  5676.8      .1       0
Bank Sta=4869.1,5189.3
XS Rating Curve= 0 ,0
Exp/Cntr=0.3,0.1

Type RM Length L Ch R = 1 ,22005   ,662,662,662
BEGIN DESCRIPTION:
BEAR CREEK 38.0
END DESCRIPTION:
XS GIS Cut Line= 4
      2736578.23     10029344.81      2737293.46     10029414.25
      2737661.52     10029178.14      2738647.65     10029310.09
#Sta/Elev= 30
  3719.7 1738.61  4001.9 1736.34  4058.5 1736.26  4212.2 1735.92  4311.4 1724.29
  4379.6 1718.71  4609.9 1713.91  4615.9 1715.62  4688.5  1711.4  4709.7 1713.72
  4776.4 1712.71    4855 1705.14  4870.2  1709.3    4875 1715.64  4878.8 1716.47
  4883.8 1710.78  4892.7 1711.17  4902.8 1707.57  4912.9 1702.71    4933 1700.56
  5013.5  1699.6  5102.9 1705.24  5195.4 1702.03  5235.7 1707.42  5316.4 1713.47
    5405 1729.84  5467.8 1736.61  5559.1 1741.92  5639.3 1746.59  5870.5  1751.2
#Mann= 9 ,-1 , 0
  3719.7      .1       0  4001.9     .16       0  4058.5      .1       0
  4311.4     .16       0  4609.9      .1       0  4776.4     .05       0
  4902.8     .07       0  5235.7     .16       0  5559.1      .1       0
#XS Ineff= 1 ,-1
 4424.17 4878.84 1716.52
Permanent Ineff=
       T
Bank Sta=4902.8,5235.7
XS Rating Curve= 0 ,0
Exp/Cntr=0.3,0.1

Type RM Length L Ch R = 1 ,21343   ,410,410,410
BEGIN DESCRIPTION:
BEAR CREEK 37.0
END DESCRIPTION:
XS GIS Cut Line= 3
      2736775.69     10029460.71       2737361.6     10029894.72
      2738761.38     10029363.02
#Sta/Elev= 30
  3973.8 1737.66  4029.1 1737.75  4204.6 1737.68  4282.6 1735.23  4356.8 1728.98
  4392.3  1730.7  4450.1 1724.31  4639.4 1712.67  4760.3 1709.06  4827.5 1704.11
  4832.9  1704.4  4997.3 1695.25  5063.3 1698.96    5173 1696.76  5234.4 1702.81
  5245.1  1705.6  5252.7 1708.59    5258 1707.47  5282.8  1716.3  5288.2    1715
  5307.6  1719.2  5411.7 1720.92  5615.1 1722.25  5657.3 1722.89  5787.6 1728.78
  5812.1 1731.19  5833.5 1736.06  5854.9 1739.14  5963.1 1744.93  6200.3 1751.77
#Mann= 13 ,-1 , 0
  3973.8      .1       0  4029.1     .05       0  4204.6      .1       0
  4282.6     .05       0  4450.1      .1       0  4639.4     .05       0
  4760.3      .1       0  4827.5     .09       0  5234.4      .1       0
  5411.7     .05       0  5615.1      .1       0  5657.3     .16       0
  5833.5      .1       0
Bank Sta=4832.9,5245.1
XS Rating Curve= 0 ,0
Exp/Cntr=0.3,0.1

Type RM Length L Ch R = 1 ,20933   ,413,413,413
BEGIN DESCRIPTION:
BEAR CREEK 36.0
END DESCRIPTION:
XS GIS Cut Line= 3
      2736807.32     10029875.61      2737529.57     10030160.34
        2739481.      10030153.4
#Sta/Elev= 30
  3994.7 1735.38  4170.1 1734.89  4318.6 1729.27  4329.6 1728.56  4421.4 1719.57
  4595.7 1707.38  4662.7 1702.83  4726.9 1697.63  4799.9 1700.86    4920 1699.24
    4950 1693.34    5007  1688.8  5009.7  1688.3    5013  1688.8    5030 1692.11
    5050  1702.5    5070 1712.49    5090  1714.8    5210  1715.8    5290 1720.89
  5430.5 1718.99    5579 1718.89  6042.2 1723.33  6253.5 1733.11  6314.9 1738.48
    6410 1751.49    6510 1780.02  6566.4 1783.83    6670 1790.44  6722.5 1790.13
#Mann= 13 ,-1 , 0
  3994.7      .1       0  4318.6     .16       0  4329.6      .1       0
  4421.4     .05       0  4595.7      .1       0    5007     .07       0
    5013      .1       0  5430.5     .05       0    5579     .16       0
  6042.2      .1       0  6253.5     .16       0  6314.9      .1       0
  6566.4     .05       0
Bank Sta=4662.7,5050
XS Rating Curve= 0 ,0
Exp/Cntr=0.3,0.1

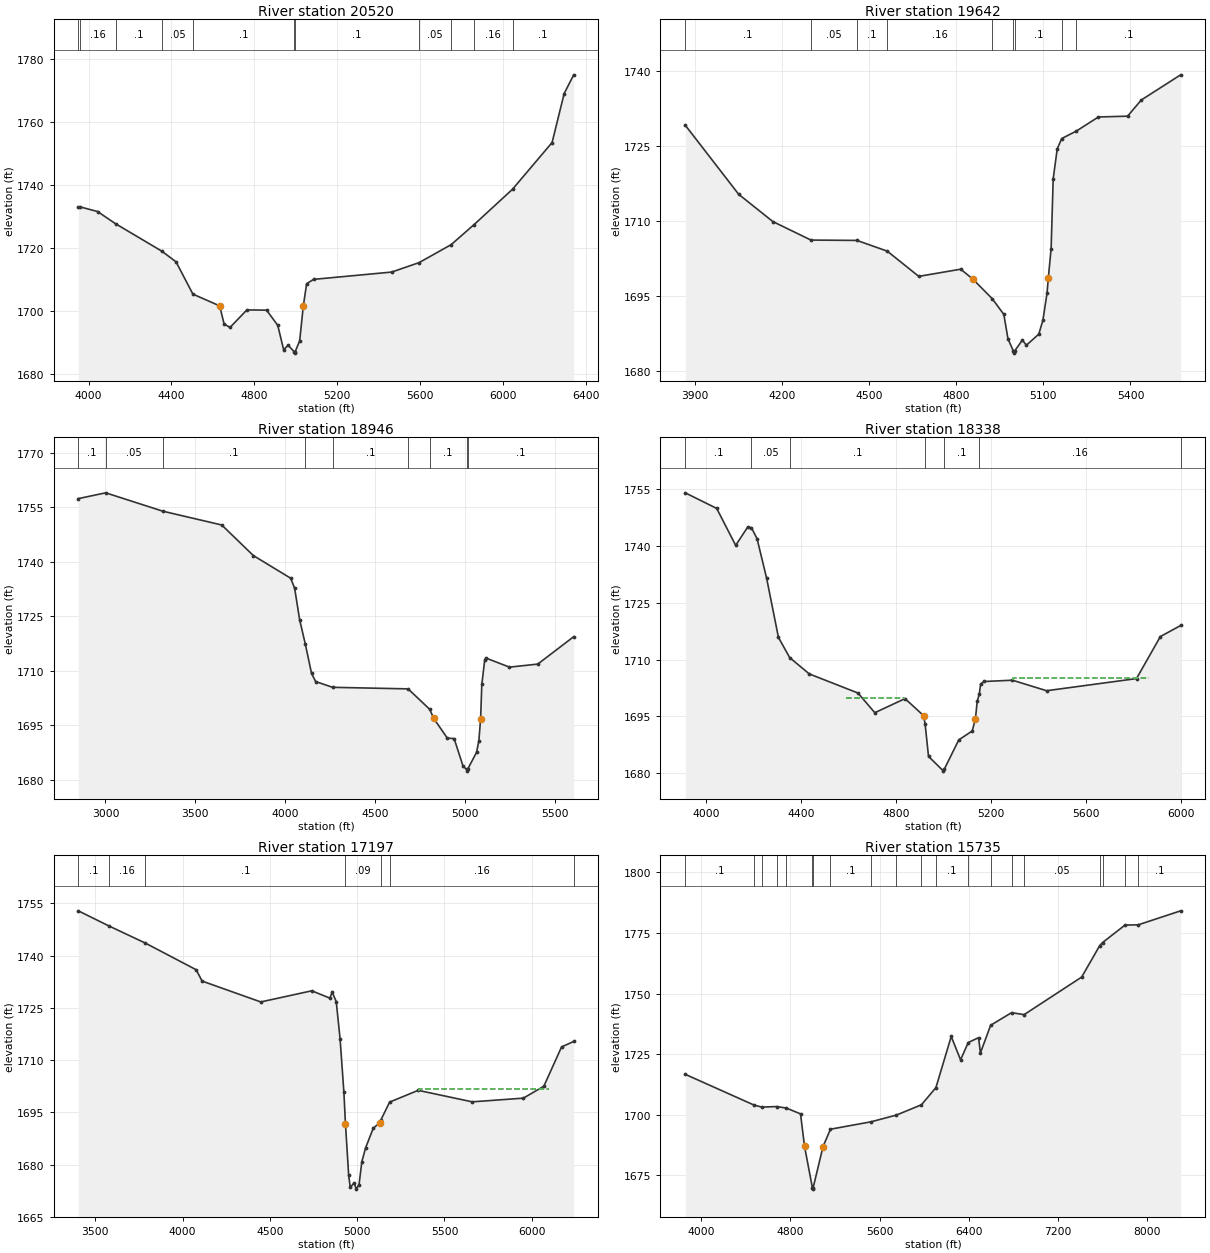
Type RM Length L Ch R = 1 ,20520   ,878,878,878
BEGIN DESCRIPTION:
BEAR CREEK 35.0
END DESCRIPTION:
XS GIS Cut Line= 3
      2736814.26     10030070.04      2737515.68     10030500.62
      2739022.62     10030938.12
#Sta/Elev= 30
  3950.1 1733.15  3958.8 1733.17  4043.1 1731.69  4129.9 1727.82  4353.9 1719.08
    4422 1715.71  4503.5 1705.45  4632.7 1701.72    4654 1695.99  4682.5 1694.86
  4764.2 1700.44  4859.3 1700.36  4913.2 1695.54  4941.6 1687.79  4963.5 1689.23
  4991.7 1687.21  4994.5 1686.71  4997.7 1687.21  5019.1 1690.65  5036.4 1701.56
  5052.6 1708.76  5086.2 1710.14  5463.3 1712.46  5595.7 1715.46  5750.7 1721.18
  5861.4 1727.55  6046.8 1738.77    6238 1753.62  6296.3 1769.18  6342.3 1775.12
#Mann= 11 ,-1 , 0
  3950.1      .1       0  3958.8     .16       0  4129.9      .1       0
  4353.9     .05       0  4503.5      .1       0  4991.7     .07       0
  4997.7      .1       0  5595.7     .05       0  5750.7      .1       0
  5861.4     .16       0  6046.8      .1       0
Bank Sta=4632.7,5036.4
XS Rating Curve= 0 ,0
Exp/Cntr=0.3,0.1

Type RM Length L Ch R = 1 ,19642   ,696,696,696
BEGIN DESCRIPTION:
BEAR CREEK 34.0
END DESCRIPTION:
XS GIS Cut Line= 4
      2736828.17     10030215.85      2737105.96     10031111.73
      2737501.79     10031542.29      2737682.35     10031514.51
#Sta/Elev= 30
  3867.3 1729.19  4051.2 1715.36  4168.7  1709.9  4300.1 1706.19  4458.4 1706.12
  4562.8 1703.97  4671.2 1698.92  4815.6 1700.36  4858.1 1698.34  4924.6 1694.42
  4964.1  1691.3  4978.3 1686.42  4996.3 1684.05    4999 1683.55  5002.3 1684.05
  5027.7 1686.16  5041.8 1685.14  5084.4 1687.35  5098.6 1690.14  5112.7  1695.5
 5117.27 1698.62  5126.9  1704.5    5134 1718.46  5147.9 1724.44  5163.3 1726.52
  5213.5 1728.01  5289.7 1730.84  5390.1    1731  5437.3 1734.24  5572.8 1739.28
#Mann= 9 ,-1 , 0
  3867.3      .1       0  4300.1     .05       0  4458.4      .1       0
  4562.8     .16       0  4924.6      .1       0  4996.3     .07       0
  5002.3      .1       0  5163.3     .16       0  5213.5      .1       0
Bank Sta=4858.1,5117.27
XS Rating Curve= 0 ,0
Exp/Cntr=0.3,0.1

Type RM Length L Ch R = 1 ,18946   ,608,608,608
BEGIN DESCRIPTION:
BEAR CREEK 33.0
END DESCRIPTION:
XS GIS Cut Line= 3
      2735555.24     10029468.51      2736649.01     10031517.16
      2737039.68     10031708.15
#Sta/Elev= 30
  2848.9 1757.32  3001.4 1758.91    3319 1753.86  3647.3 1750.06  3822.9 1741.66
  4031.1 1735.41  4053.1 1732.61  4080.7 1724.01  4112.8 1717.21  4147.1 1709.21
  4169.8 1706.99    4264  1705.4  4684.4 1704.97  4804.9 1699.34  4827.3 1696.83
  4902.8 1691.41  4940.6  1691.3  4990.6 1683.66  5009.6 1682.84  5012.3 1682.34
  5015.6 1682.84  5065.3  1687.5  5078.4 1690.71    5088 1696.77  5094.7 1706.18
  5110.7 1712.85  5116.7 1713.47  5248.6 1710.95  5406.2 1711.79  5606.1 1719.33
#Mann= 9 ,-1 , 0
  2848.9      .1       0  3001.4     .05       0    3319      .1       0
  4112.8     .16       0    4264      .1       0  4684.4     .05       0
  4804.9      .1       0  5009.6     .07       0  5015.6      .1       0
Bank Sta=4827.3,5088
XS Rating Curve= 0 ,0
Exp/Cntr=0.3,0.1

Type RM Length L Ch R = 1 ,18338   ,1141,1141,1141
BEGIN DESCRIPTION:
BEAR CREEK 31.0
END DESCRIPTION:
XS GIS Cut Line= 4
      2735066.04      10031278.4      2735708.39     10031313.12
      2736359.43      10031903.4      2736923.59     10031842.64
#Sta/Elev= 30
  3910.5 1754.09  4043.1 1749.97  4123.2 1740.19  4173.3 1744.99  4189.6 1744.88
  4213.4 1741.95  4253.4 1731.59  4303.5 1715.87  4350.9 1710.52  4433.7  1706.2
  4639.1 1701.15  4710.1 1695.95  4837.4 1699.67  4915.5 1695.19  4922.3 1692.93
  4936.5  1684.4  4999.7  1680.5    5003    1681  5064.2 1688.76  5120.8 1691.12
  5134.5 1694.36  5141.9 1698.95    5151 1700.92  5156.1 1703.49  5170.3  1704.2
  5290.6 1704.54  5434.6 1701.76  5813.8 1704.97  5914.4 1716.08    6000 1719.01
#Mann= 7 ,-1 , 0
  3910.5      .1       0  4189.6     .05       0  4350.9      .1       0
  4922.3     .09       0    5003      .1       0    5151     .16       0
    6000     .16       0
#XS Ineff= 2 ,-1
 4588.07 4835.23 1699.92 5292.61 5865.06 1705.23
Permanent Ineff=
       T       T
Bank Sta=4915.5,5134.5
XS Rating Curve= 0 ,0
Exp/Cntr=0.3,0.1

Type RM Length L Ch R = 1 ,17197   ,1462,1462,1462
BEGIN DESCRIPTION:
BEAR CREEK 29.0
END DESCRIPTION:
XS GIS Cut Line= 4
      2734486.17     10032170.76      2735541.72     10032705.48
      2736753.53      10032028.4       2736982.7     10031892.98
#Sta/Elev= 30
  3402.8 1752.83  3576.5 1748.53  3786.5 1743.58    4078 1735.92  4111.8 1732.67
  4447.9 1726.68  4740.2 1729.88    4843 1727.79  4857.3 1729.47  4880.2 1726.79
  4902.4 1716.02  4924.1 1700.74 4932.95 1691.79  4951.5 1676.88  4960.4  1673.5
  4983.3 1674.74  4994.7 1672.96  5010.9 1674.26  5026.9 1680.85  5048.6 1684.83
    5092 1690.41  5129.7 1692.06  5135.4 1692.76  5186.2 1697.94  5349.8 1701.31
  5659.1 1698.01  5952.1 1699.07  6069.4 1702.49  6170.9 1713.77  6240.4 1715.34
#Mann= 7 ,-1 , 0
  3402.8      .1       0  3576.5     .16       0  3786.5      .1       0
 4932.95     .09       0  5135.4      .1       0  5186.2     .16       0
  6240.4     .16       0
#XS Ineff= 1 ,-1
 5356.53  6098.3  1701.8
Permanent Ineff=
       T
Bank Sta=4932.95,5129.7
XS Rating Curve= 0 ,0
Exp/Cntr=0.3,0.1

Type RM Length L Ch R = 1 ,15735   ,833,833,833
BEGIN DESCRIPTION:
BEAR CREEK 26.0
END DESCRIPTION:
XS GIS Cut Line= 4
      2736274.38     10032913.81      2737255.27     10032905.13
      2737411.52     10031993.68      2739676.27     10030848.28
#Sta/Elev= 30
  3856.1 1716.71    4475 1703.99  4544.2 1703.19  4676.6 1703.41  4762.9 1702.79
  4889.9  1700.4 4926.14 1686.98  4996.8 1669.85  4999.6 1669.35  5002.8 1669.85
  5092.1 1686.92  5158.6 1694.07  5522.7 1697.13  5748.6 1699.88  5974.8 1704.14
  6104.6 1711.25  6241.9 1732.33  6325.5 1722.69  6394.7 1729.83  6487.1 1731.83
  6503.7 1725.53  6595.5 1736.96  6782.9 1742.14    6896 1741.34  7411.8 1756.83
  7574.3 1769.84  7599.2 1771.07  7800.4 1778.27  7918.7 1778.38  8299.7 1784.16
#Mann= 20 ,-1 , 0
  3856.1      .1       0    4475     .16       0  4544.2      .1       0
  4676.6     .16       0  4762.9      .1       0  4996.8     .07       0
  5002.8     .16       0  5158.6      .1       0  5522.7     .05       0
  5748.6      .1       0  5974.8     .16       0  6104.6      .1       0
  6394.7     .16       0  6595.5      .1       0  6782.9     .16       0
    6896     .05       0  7574.3      .1       0  7599.2     .05       0
  7800.4     .05       0  7918.7      .1       0
Bank Sta=4926.14,5092.1
XS Rating Curve= 0 ,0
Exp/Cntr=0.3,0.1