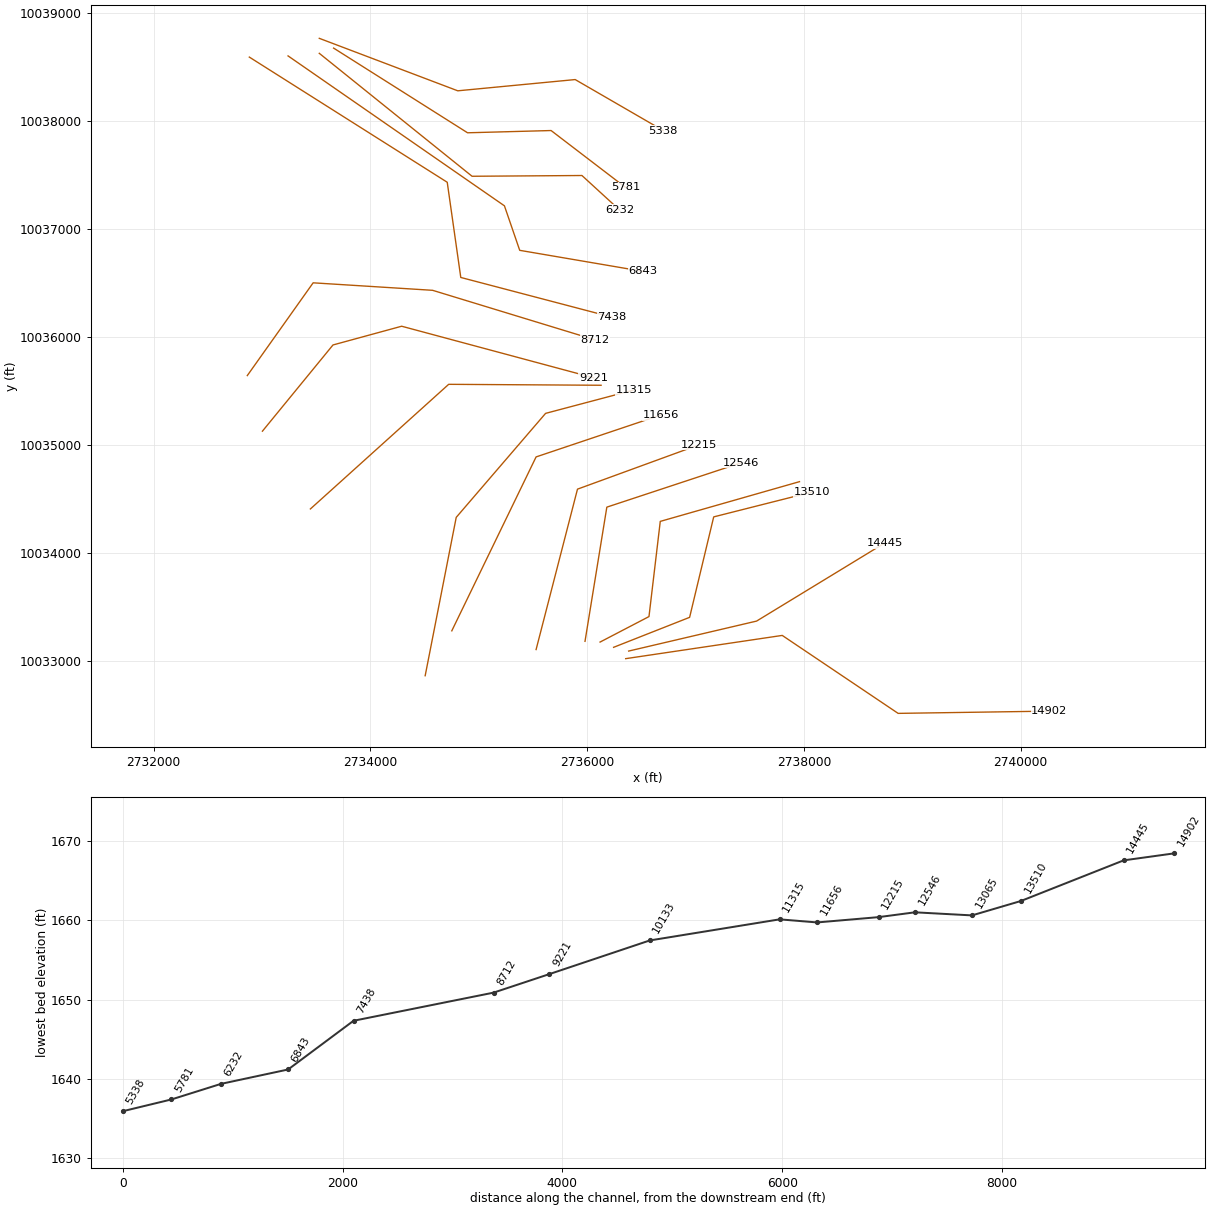
HEC-RAS study BEAR CREEK.prj: BEAR CREEK Base Level Engineering

--- BEAR CREEK.g01 (geometry) --- (continued)

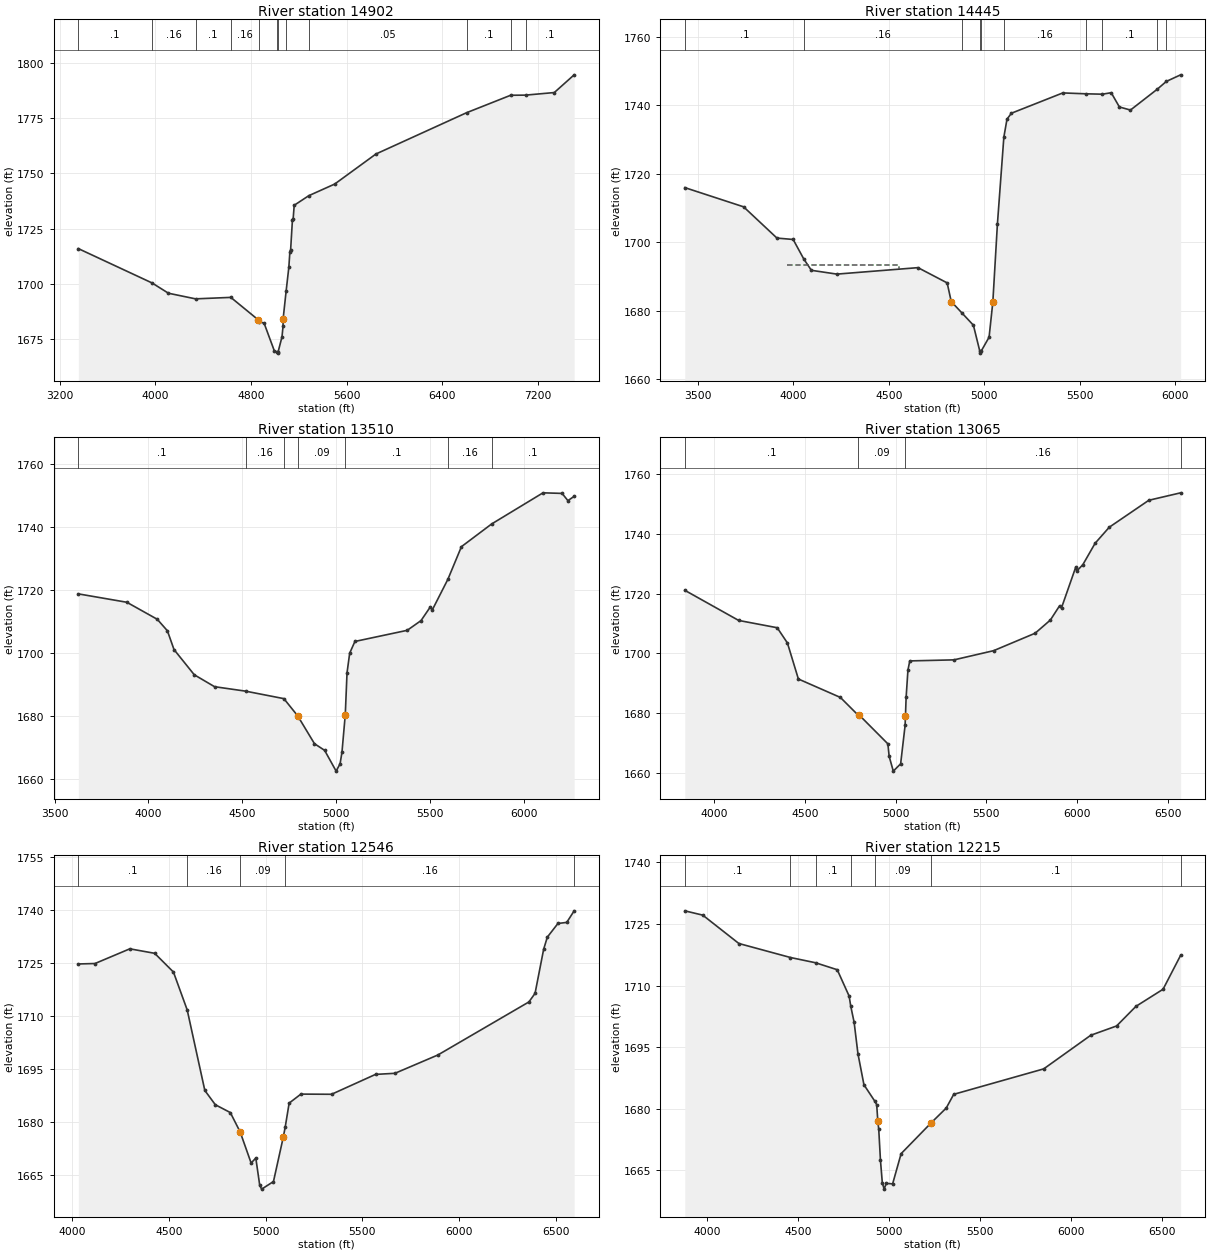
Type RM Length L Ch R = 1 ,14902   ,457,457,457
BEGIN DESCRIPTION:
BEAR CREEK 25.0
END DESCRIPTION:
XS GIS Cut Line= 4
      2736355.93     10033017.98       2737800.4     10033233.26
      2738869.85     10032511.04      2740264.59     10032531.85
#Sta/Elev= 30
  3355.8  1715.9  3972.2 1700.32  4109.4 1695.65    4336  1693.1  4630.9 1693.77
  4858.1 1683.67  4869.4 1682.73    4909 1682.08  4994.9 1669.47    5020 1668.98
  5022.7 1668.48    5026 1668.98  5058.9  1675.9  5067.3 1680.61 5068.18 1684.01
  5093.7 1696.82  5115.9 1707.43  5124.8 1714.56  5130.9 1715.35  5145.8 1728.78
  5151.9 1729.31  5160.8 1735.56  5283.2 1739.92  5499.5 1745.19  5844.2 1758.82
    6602 1777.55  6970.5 1785.47    7095 1785.53  7335.5  1786.7  7501.6 1794.74
#Mann= 12 ,-1 , 0
  3355.8      .1       0  3972.2     .16       0    4336      .1       0
  4630.9     .16       0  4869.4      .1       0    5020     .07       0
    5026      .1       0  5093.7     .16       0  5283.2     .05       0
    6602      .1       0  6970.5     .05       0    7095      .1       0
Bank Sta=4858.1,5068.18
XS Rating Curve= 0 ,0
Exp/Cntr=0.3,0.1

Type RM Length L Ch R = 1 ,14445   ,935,935,935
BEGIN DESCRIPTION:
BEAR CREEK 24.0
END DESCRIPTION:
XS GIS Cut Line= 3
      2736383.32      10033088.3      2737563.86     10033366.07
      2738743.97     10034088.02
#Sta/Elev= 30
  3431.4 1715.99  3739.3 1710.37    3914 1701.23  3998.7 1700.83  4054.8 1695.08
  4094.2 1691.81  4227.7  1690.7  4652.4 1692.59  4805.2 1688.13  4826.5 1682.68
  4882.1 1679.37  4942.6 1675.75  4976.4  1668.1  4979.1  1667.6  4982.4  1668.1
  5024.7 1672.26 5044.32 1682.53  5068.3 1705.36    5102 1730.73  5118.5 1736.01
  5141.8 1737.74  5410.7 1743.67  5532.2 1743.41  5617.8  1743.3  5664.2 1743.73
  5706.9 1739.57  5764.9 1738.66  5906.3  1744.8  5952.7 1747.03  6027.6 1748.96
#Mann= 10 ,-1 , 0
  3431.4      .1       0  4054.8     .16       0  4882.1      .1       0
  4976.4     .07       0  4982.4      .1       0    5102     .16       0
  5532.2     .05       0  5617.8      .1       0  5906.3     .05       0
  5952.7      .1       0
#XS Ineff= 1 ,-1
 3966.48 4551.14 1693.29
Permanent Ineff=
       T
Bank Sta=4826.5,5044.32
XS Rating Curve= 0 ,0
Exp/Cntr=0.3,0.1

Type RM Length L Ch R = 1 ,13510   ,445,445,445
BEGIN DESCRIPTION:
BEAR CREEK 23.0
END DESCRIPTION:
XS GIS Cut Line= 4
      2736244.42     10033123.02       2736945.8     10033400.79
      2737168.03     10034331.35      2738070.78     10034560.51
#Sta/Elev= 30
  3626.7 1718.68  3885.2 1716.02  4047.4 1710.62  4101.4 1706.97  4136.6 1701.02
  4244.6 1693.02  4352.7 1689.24  4517.8 1687.83  4722.2 1685.45  4795.4 1680.02
  4885.2 1671.16  4939.3 1669.05  5000.7 1662.46  5021.7 1664.79  5031.8 1668.48
 5049.43  1680.4  5058.7 1693.65  5072.9 1699.88  5100.8 1703.59  5379.5 1707.12
    5453  1710.2  5503.3  1714.6  5513.7 1713.66  5596.2  1723.3  5668.4 1733.65
  5829.6 1740.86  6103.1 1750.73  6204.9 1750.55  6235.9 1748.25  6269.2 1749.62
#Mann= 7 ,-1 , 0
  3626.7      .1       0  4517.8     .16       0  4722.2      .1       0
  4795.4     .09       0 5049.43      .1       0  5596.2     .16       0
  5829.6      .1       0
Bank Sta=4795.4,5049.43
XS Rating Curve= 0 ,0
Exp/Cntr=0.3,0.1

Type RM Length L Ch R = 1 ,13065   ,519,519,519
BEGIN DESCRIPTION:
BEAR CREEK 22.0
END DESCRIPTION:
XS GIS Cut Line= 4
      2736119.38     10033171.61       2736570.8     10033407.74
      2736674.97     10034289.68      2737959.66     10034657.73
#Sta/Elev= 30
    3837 1721.08  4133.9 1711.01  4346.5 1708.57  4402.8 1703.48  4463.3 1691.43
  4694.9 1685.27    4793 1679.34    4798 1679.42  4956.7 1669.76  4963.8 1665.58
  4986.6 1660.64  5027.1 1663.08  5051.8 1675.94  5053.6 1678.96  5057.4 1685.34
  5067.4 1694.43  5077.5 1697.48  5321.4 1697.83  5539.8  1700.9  5768.7 1706.73
  5852.7 1711.14  5903.9 1715.94  5914.3 1715.26    5993 1728.89  5998.2  1727.5
  6031.9 1729.66  6099.4  1736.8  6177.4 1742.16  6395.5 1751.17  6570.9 1753.66
#Mann= 4 ,-1 , 0
    3837      .1       0    4793     .09       0  5051.8     .16       0
  6570.9      .1       0
Bank Sta=4798,5053.6
XS Rating Curve= 0 ,0
Exp/Cntr=0.3,0.1

Type RM Length L Ch R = 1 ,12546   ,331,331,331
BEGIN DESCRIPTION:
BEAR CREEK 21.0
END DESCRIPTION:
XS GIS Cut Line= 3
      2735980.53     10033178.61      2736181.92     10034421.63
      2737418.05     10034831.36
#Sta/Elev= 30
  4032.6 1724.79  4118.8 1724.92  4298.6 1729.08    4427 1727.81    4524  1722.5
    4595 1711.78  4686.1 1688.97  4740.3 1684.93  4817.8 1682.71  4868.7 1677.21
  4925.3 1668.42  4949.5 1669.83  4969.8 1662.08  4979.7 1661.03  5040.7 1663.18
  5091.4 1675.75  5101.5 1678.64  5121.7 1685.39  5182.5 1687.94  5340.9 1687.89
    5568 1693.52  5668.4 1693.83  5890.2 1699.02  6360.4 1714.04  6392.1 1716.47
  6436.5 1728.96  6455.5 1732.39  6510.3 1736.26  6555.8 1736.56  6594.1 1739.84
#Mann= 5 ,-1 , 0
  4032.6      .1       0    4595     .16       0  4868.7     .09       0
  5101.5     .16       0  6594.1     .16       0
Bank Sta=4868.7,5091.4
XS Rating Curve= 0 ,0
Exp/Cntr=0.3,0.1

Type RM Length L Ch R = 1 ,12215   ,559,559,559
BEGIN DESCRIPTION:
BEAR CREEK 20.0
END DESCRIPTION:
XS GIS Cut Line= 3
      2735529.15     10033102.22      2735911.08     10034588.29
      2737029.11     10034998.01
#Sta/Elev= 30
  3878.9 1728.21  3977.6 1727.16  4176.1 1720.25  4459.6 1716.84  4597.6 1715.56
  4716.8 1713.86    4782 1707.45  4790.9 1705.01  4809.7 1701.02  4830.4 1693.43
  4863.5 1685.84  4922.9 1681.86  4933.6 1680.98  4939.8 1676.93  4944.9 1674.97
  4954.3  1667.4  4964.6  1661.9  4974.7 1660.42  4985.7 1661.81  5021.2 1661.71
  5067.8 1669.06    5233 1676.57  5315.6 1680.16  5356.9 1683.51  5851.5 1689.71
  6110.1  1697.9  6251.9 1700.16  6358.4 1704.94  6507.5 1709.11    6604 1717.37
#Mann= 7 ,-1 , 0
  3878.9      .1       0  4459.6     .16       0  4597.6      .1       0
  4790.9     .16       0  4922.9     .09       0    5233      .1       0
    6604      .1       0
Bank Sta=4939.8,5233
XS Rating Curve= 0 ,0
Exp/Cntr=0.3,0.1

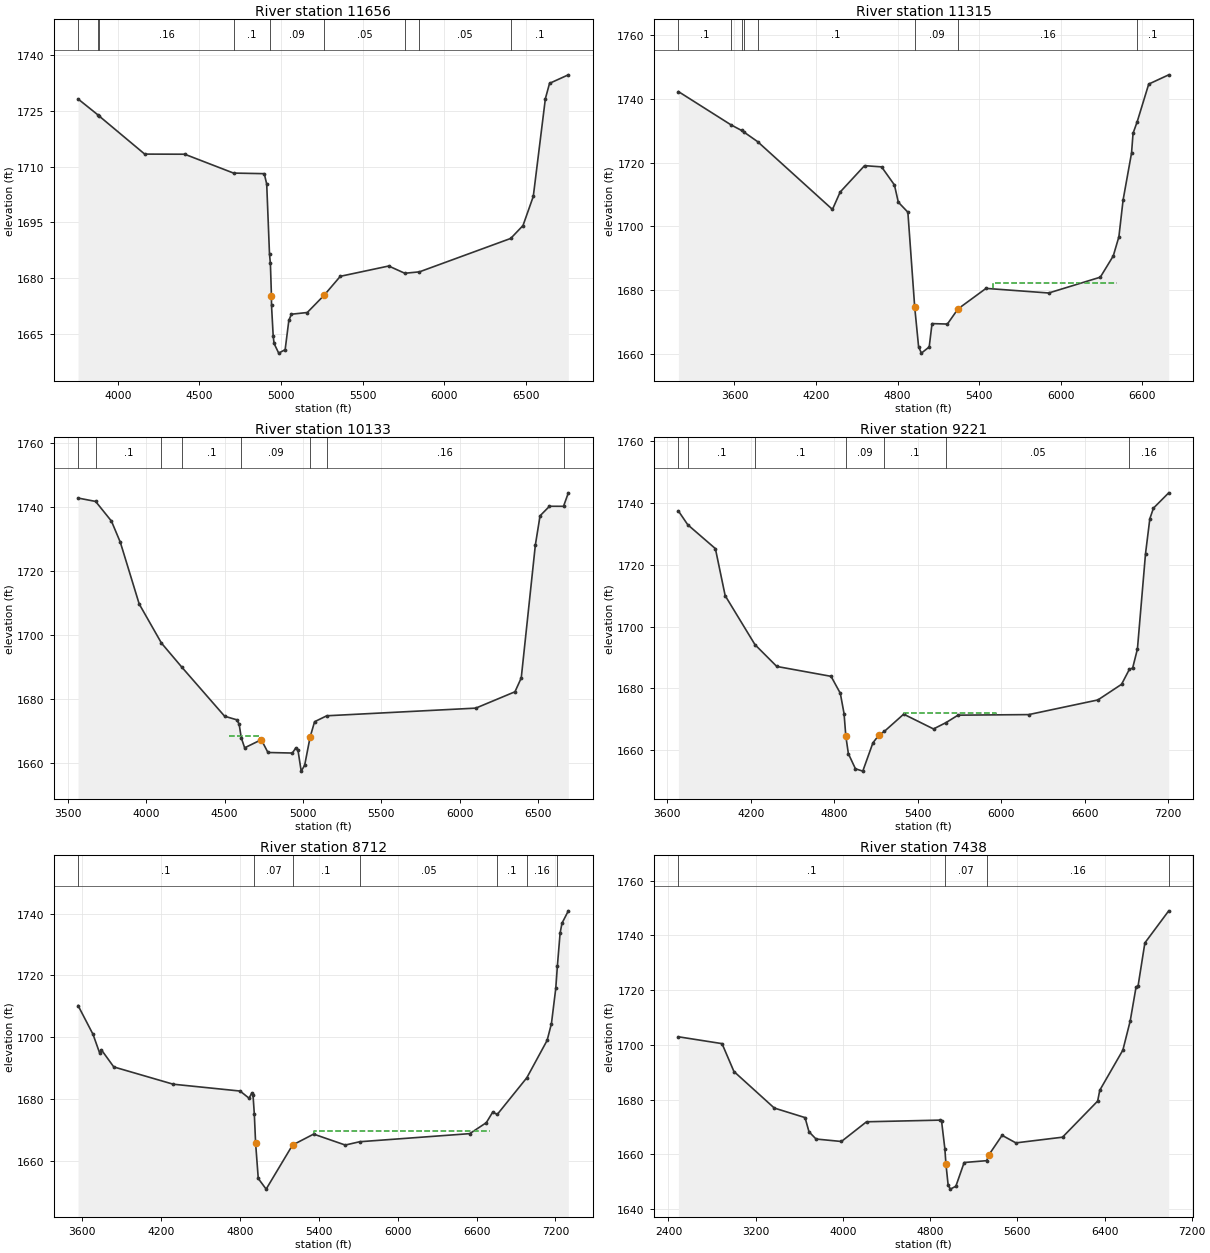
Type RM Length L Ch R = 1 ,11656   ,341,341,341
BEGIN DESCRIPTION:
BEAR CREEK 19.0
END DESCRIPTION:
XS GIS Cut Line= 3
      2734751.36      10033275.8      2735529.14     10034886.91
      2736681.89     10035275.78
#Sta/Elev= 30
  3756.1  1728.2  3877.9 1723.91  3886.9 1723.55  4164.7 1713.35  4409.8 1713.32
  4709.2 1708.24  4897.6 1708.08  4912.6 1705.28  4929.7 1686.38  4935.2 1683.89
 4941.76 1675.04    4942 1672.64  4952.3  1664.4  4957.8 1662.35  4986.1 1659.75
  5025.6 1660.68  5048.3 1668.57  5064.1 1670.23  5161.3 1670.69    5264 1675.31
  5363.9 1680.44  5660.5 1683.21  5759.1 1681.26  5848.9 1681.64  6408.4 1690.64
  6483.7 1694.11  6546.8 1701.96  6620.9 1728.29  6646.5 1732.41  6761.7  1734.7
#Mann= 9 ,-1 , 0
  3756.1     .16       0  3877.9      .1       0  3886.9     .16       0
  4709.2      .1       0  4935.2     .09       0    5264     .05       0
  5759.1      .1       0  5848.9     .05       0  6408.4      .1       0
Bank Sta=4941.76,5264
XS Rating Curve= 0 ,0
Exp/Cntr=0.3,0.1

Type RM Length L Ch R = 1 ,11315   ,1182,1182,1182
BEGIN DESCRIPTION:
BEAR CREEK 18.0
END DESCRIPTION:
XS GIS Cut Line= 4
      2734505.65     10032859.84       2734792.1     10034326.82
      2735616.75     10035290.36      2736432.74     10035507.38
#Sta/Elev= 30
  3187.7 1742.34    3575 1731.87  3652.2 1730.13  3668.9 1729.64    3770 1726.62
  4320.9  1705.3  4377.6 1710.77    4557 1719.06  4682.4 1718.68  4776.9 1712.99
  4805.4 1707.58  4875.8 1704.44  4926.2 1674.53  4954.7 1662.14  4975.3 1660.14
  5032.7 1662.08  5053.5 1669.42  5166.6 1669.28  5244.5 1674.03  5450.9 1680.49
  5911.9 1679.04  6291.6 1684.01    6387 1690.69  6428.4 1696.73  6459.4  1708.3
  6521.5 1723.05  6532.5 1729.23  6562.7 1732.83  6647.8  1744.7    6795 1747.61
#Mann= 8 ,-1 , 0
  3187.7      .1       0    3575     .16       0  3652.2      .1       0
  3668.9     .16       0    3770      .1       0  4926.2     .09       0
  5244.5     .16       0  6562.7      .1       0
#XS Ineff= 1 ,-1
 5503.16  6413.4 1682.16
Permanent Ineff=
       T
Bank Sta=4926.2,5244.5
XS Rating Curve= 0 ,0
Exp/Cntr=0.3,0.1

Type RM Length L Ch R = 1 ,10133   ,912,912,912
BEGIN DESCRIPTION:
BEAR CREEK 17.0
END DESCRIPTION:
XS GIS Cut Line= 3
      2733446.61     10034404.94      2734722.66     10035559.46
      2736128.91     10035550.78
#Sta/Elev= 30
  3565.1 1742.78  3677.2 1741.72    3778 1735.58  3834.8 1728.95  3955.1 1709.68
    4097 1697.47    4225 1690.06  4499.9 1674.62  4578.3 1673.49  4592.5 1672.13
    4606 1667.92  4627.6 1664.75  4733.7 1667.29  4776.3 1663.29  4931.8 1663.12
  4953.4 1664.68  4967.6 1664.04  4988.3 1657.47  5010.2 1659.27  5045.3 1668.13
  5073.7 1672.91  5151.4 1674.76  6101.7 1677.15  6351.8 1682.26  6391.8 1686.58
  6481.8 1728.12  6511.8 1737.24  6571.8 1740.21  6661.5  1740.2  6692.2 1744.41
#Mann= 8 ,-1 , 0
  3565.1     .05       0  3677.2      .1       0    4097     .16       0
    4225      .1       0    4606     .09       0  5045.3      .1       0
  5151.4     .16       0  6661.5      .1       0
#XS Ineff= 1 ,-1
 4528.12 4723.01 1668.39
Permanent Ineff=
       T
Bank Sta=4733.7,5045.3
XS Rating Curve= 0 ,0
Exp/Cntr=0.3,0.1

Type RM Length L Ch R = 1 ,9221    ,509,509,509
BEGIN DESCRIPTION:
BEAR CREEK 16.0
END DESCRIPTION:
XS GIS Cut Line= 4
      2733003.89     10035125.41      2733654.95     10035924.04
      2734288.63     10036097.65      2736059.48     10035620.22
#Sta/Elev= 30
  3681.3 1737.44  3748.2 1732.99  3946.7 1725.26    4017 1710.03    4231 1694.17
  4387.6 1687.11  4777.5 1683.91    4844 1678.42  4870.9 1671.84  4883.6 1664.52
    4902 1658.85  4952.6 1653.98  5005.4 1653.22  5078.2 1662.38  5119.7 1664.79
  5161.2 1666.12  5299.1 1671.66  5513.3 1666.88    5602  1668.9  5689.6 1671.34
  6197.1 1671.52  6694.3 1676.27    6864 1681.33  6919.9 1686.16  6943.8 1686.61
    6978 1692.77    7036 1723.57  7067.1 1734.93  7093.1 1738.37  7202.8 1743.32
#Mann= 7 ,-1 , 0
  3681.3     .05       0  3748.2      .1       0    4231      .1       0
  4883.6     .09       0  5161.2      .1       0    5602     .05       0
  6919.9     .16       0
#XS Ineff= 1 ,-1
 5298.79 5963.67 1672.08
Permanent Ineff=
       T
Bank Sta=4883.6,5119.7
XS Rating Curve= 0 ,0
Exp/Cntr=0.3,0.1

Type RM Length L Ch R = 1 ,8712    ,1274,1274,1274
BEGIN DESCRIPTION:
BEAR CREEK 15.0
END DESCRIPTION:
XS GIS Cut Line= 4
      2732864.31     10035640.46      2733471.93      10036499.8
      2734574.36     10036430.36      2736074.76      10035970.7
#Sta/Elev= 30
  3571.4 1710.27  3685.3 1700.93  3734.6    1695  3748.1 1695.98  3842.9  1690.4
  4294.6 1684.81  4802.8  1682.6  4870.9 1680.29  4890.9 1681.86  4900.9 1681.47
    4911 1675.18    4921 1665.65    4941 1654.31  5000.9 1650.87  5201.5 1665.13
  5361.9 1668.67  5602.3 1665.13  5711.6  1666.2  6548.3 1668.82  6674.1 1672.36
  6722.6 1675.77  6757.6 1675.04  6982.3 1686.91  7136.6    1699  7169.3 1704.45
  7202.1 1715.81  7214.6  1723.2  7234.9 1733.64  7249.3 1736.89  7297.7  1740.9
#Mann= 7 ,-1 , 0
  3571.4      .1       0    4911     .07       0  5201.5      .1       0
  5711.6     .05       0  6757.6      .1       0  6982.3     .16       0
  7214.6      .1       0
#XS Ineff= 1 ,-1
 5360.94 6701.01 1669.69
Permanent Ineff=
       T
Bank Sta=4921,5201.5
XS Rating Curve= 0 ,0
Exp/Cntr=0.3,0.1

Type RM Length L Ch R = 1 ,7438    ,595,595,595
BEGIN DESCRIPTION:
BEAR CREEK 14.0
END DESCRIPTION:
XS GIS Cut Line= 4
      2732882.81     10038591.15       2734709.2     10037431.42
       2734834.2     10036549.48      2736230.04     10036181.42
#Sta/Elev= 30
  2491.2 1702.98  2891.1 1700.48  3000.4 1690.29  3370.5 1676.94  3652.6 1673.45
    3689 1668.26  3753.5 1665.62  3986.3 1664.72  4216.7 1671.92  4894.3 1672.53
  4904.9 1672.23  4935.2  1662.1  4945.3 1656.42  4965.3 1648.84  4985.4 1647.31
  5036.2 1648.36  5112.3 1657.04    5319 1657.71  5339.2 1659.84  5460.4 1666.97
  5586.8 1664.21  6014.5 1666.29  6336.9 1679.48  6356.5 1683.45  6568.3 1698.11
  6635.7 1708.79  6689.2 1721.13  6708.1 1721.64  6770.2 1737.29    6989 1749.01
#Mann= 4 ,-1 , 0
  2491.2      .1       0  4935.2     .07       0    5319     .16       0
    6989      .1       0
Bank Sta=4945.3,5339.2
XS Rating Curve= 0 ,0
Exp/Cntr=0.3,0.1

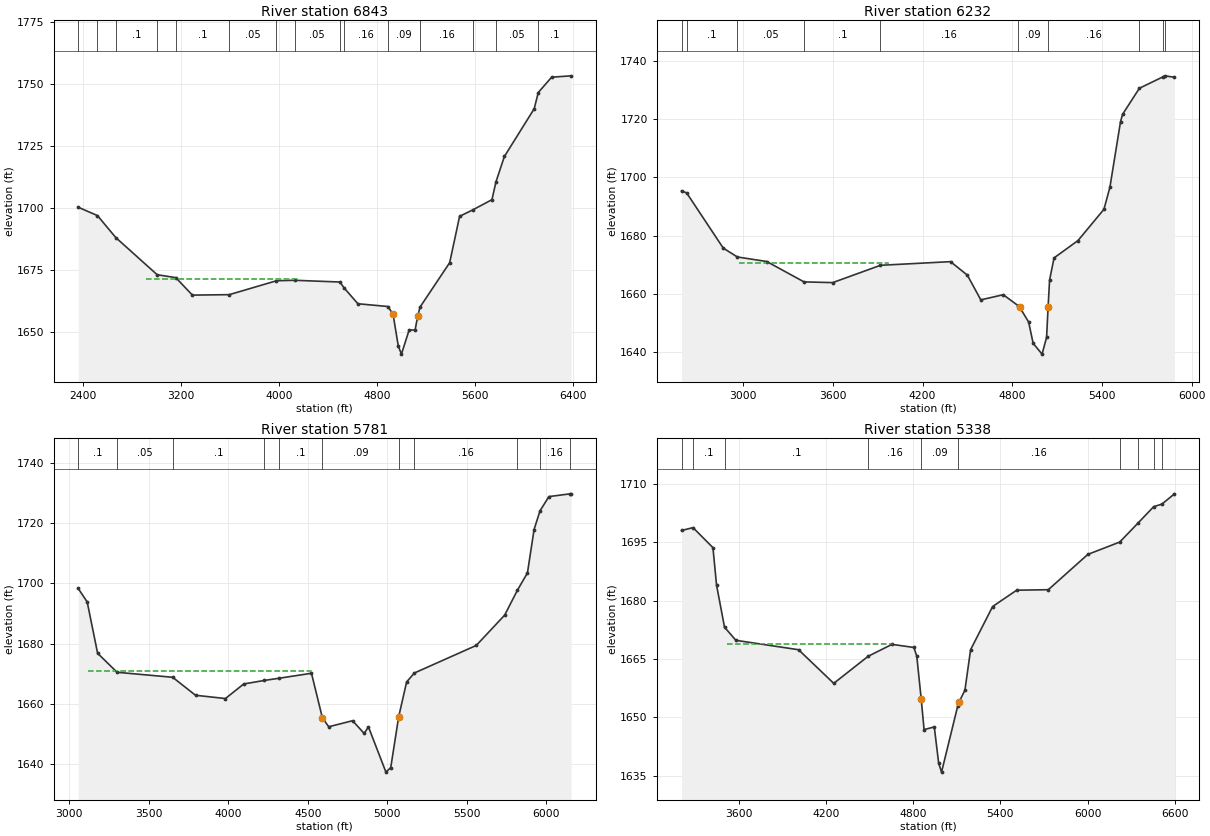
Type RM Length L Ch R = 1 ,6843    ,611,611,611
BEGIN DESCRIPTION:
BEAR CREEK 13.0
END DESCRIPTION:
XS GIS Cut Line= 4
      2733240.43     10038602.01      2735236.98     10037213.11
      2735378.04     10036800.78      2736515.42      10036605.8
#Sta/Elev= 30
  2360.2 1700.44  2517.7 1697.06  2666.7  1688.2  3004.5  1673.2  3156.7 1672.02
  3291.9 1664.97  3592.7 1665.15    3978 1670.76  4126.2 1670.95  4495.6 1670.25
  4528.1 1667.97  4642.1 1661.48  4886.8 1660.37  4929.1 1657.27  4971.7 1644.44
  4997.5 1641.15  5060.4 1650.93  5108.7 1650.84  5129.9 1656.41    5149 1660.12
  5390.9 1678.05    5472 1696.77    5583 1699.45  5735.9 1703.49  5768.7 1710.68
  5837.3 1720.92  6080.8 1740.21  6113.6 1746.73  6222.9 1752.92  6382.1 1753.47
#Mann= 15 ,-1 , 0
  2360.2      .1       0  2517.7     .05       0  2666.7      .1       0
  3004.5     .05       0  3156.7      .1       0  3592.7     .05       0
    3978      .1       0  4126.2     .05       0  4495.6      .1       0
  4528.1     .16       0  4886.8     .09       0    5149     .16       0
    5583      .1       0  5768.7     .05       0  6113.6      .1       0
#XS Ineff= 1 ,-1
 2914.77 4153.41 1671.39
Permanent Ineff=
       T
Bank Sta=4929.1,5129.9
XS Rating Curve= 0 ,0
Exp/Cntr=0.3,0.1

Type RM Length L Ch R = 1 ,6232    ,451,451,451
BEGIN DESCRIPTION:
BEAR CREEK 12.0
END DESCRIPTION:
XS GIS Cut Line= 4
      2733528.68     10038625.84      2734938.37     10037486.98
      2735952.26     10037493.92       2736299.5     10037174.46
#Sta/Elev= 30
  2587.1 1695.42  2621.5  1694.7  2866.1 1675.76  2960.4  1672.7  3157.1 1671.14
  3406.7 1664.14  3598.5 1663.89  3918.3 1669.84  4386.8 1671.09  4499.4 1666.46
  4589.4 1657.97  4739.5 1659.73  4839.5 1655.96  4849.5 1655.44  4909.5 1650.34
  4939.5 1643.05  4999.2 1639.33  5029.5 1645.08  5039.5  1655.4  5049.5 1664.78
  5079.5 1672.38  5239.5 1678.33  5413.3 1689.08  5453.1 1696.64    5524 1719.12
  5538.1 1721.71  5650.4 1730.64  5810.5 1734.62  5820.5 1734.91  5885.1 1734.41
#Mann= 10 ,-1 , 0
  2587.1     .05       0  2621.5      .1       0  2960.4     .05       0
  3406.7      .1       0  3918.3     .16       0  4839.5     .09       0
  5039.5     .16       0  5650.4      .1       0  5810.5     .16       0
  5820.5      .1       0
#XS Ineff= 1 ,-1
  2973.3 3965.62 1670.76
Permanent Ineff=
       T
Bank Sta=4849.5,5039.5
XS Rating Curve= 0 ,0
Exp/Cntr=0.3,0.1

Type RM Length L Ch R = 1 ,5781    ,443,443,443
BEGIN DESCRIPTION:
BEAR CREEK 11.0
END DESCRIPTION:
XS GIS Cut Line= 4
      2733660.62     10038674.46       2734896.7     10037889.76
      2735667.53     10037910.59      2736354.27     10037383.39
#Sta/Elev= 30
    3056 1698.35  3112.7 1693.86  3178.2 1676.82  3300.7 1670.51  3650.3 1668.85
  3794.1 1662.88  3982.1 1661.79  4097.3 1666.63  4227.8 1667.81  4321.8 1668.55
  4523.5 1670.18  4591.9 1655.43  4631.9 1652.42    4782 1654.43  4854.7 1650.22
    4882 1652.37  4991.8 1637.36  5022.1 1638.88  5072.1 1655.76  5122.1 1667.31
  5170.8 1670.27  5560.2 1679.43  5738.8 1689.49  5818.3  1697.7  5882.1 1703.51
  5923.7 1717.88  5960.8  1724.1  6017.1 1728.84  6150.7 1729.76    6157 1729.68
#Mann= 11 ,-1 , 0
    3056      .1       0  3300.7     .05       0  3650.3      .1       0
  4227.8     .16       0  4321.8      .1       0  4591.9     .09       0
  5072.1      .1       0  5170.8     .16       0  5818.3      .1       0
  5960.8     .16       0  6150.7      .1       0
#XS Ineff= 1 ,-1
 3117.33 4521.31 1670.91
Permanent Ineff=
       T
Bank Sta=4591.9,5072.1
XS Rating Curve= 0 ,0
Exp/Cntr=0.3,0.1

Type RM Length L Ch R = 1 ,5338    ,465,465,465
BEGIN DESCRIPTION:
BEAR CREEK 10.0
END DESCRIPTION:
XS GIS Cut Line= 4
      2733528.63     10038764.76      2734806.42     10038278.64
      2735889.76     10038382.81      2736702.23      10037910.6
#Sta/Elev= 30
  3203.7 1698.07    3283 1698.81  3420.2 1693.65    3445 1684.03  3499.8 1673.19
    3578  1669.8  4009.7 1667.38  4252.1 1658.72  4489.5  1665.7  4653.3 1668.76
    4804 1667.96    4824 1665.74  4854.2 1654.81  4874.3 1646.82  4944.6  1647.5
  4974.7  1638.2  4994.6 1635.87  5105.3 1652.78  5115.4 1653.94  5155.6 1656.95
  5194.7 1667.38  5346.4  1678.5  5512.1  1682.7  5729.9 1682.83  6002.2 1691.92
  6221.6 1695.09  6346.5 1699.93  6455.7 1704.21  6512.3 1704.86  6598.9 1707.51
#Mann= 10 ,-1 , 0
  3203.7     .05       0    3283      .1       0  3499.8      .1       0
  4489.5     .16       0  4854.2     .09       0  5105.3     .16       0
  6221.6     .05       0  6346.5      .1       0  6455.7     .05       0
  6512.3      .1       0
#XS Ineff= 1 ,-1
 3513.64 4659.09 1668.95
Permanent Ineff=
       T
Bank Sta=4854.2,5115.4
XS Rating Curve= 0 ,0
Exp/Cntr=0.3,0.1