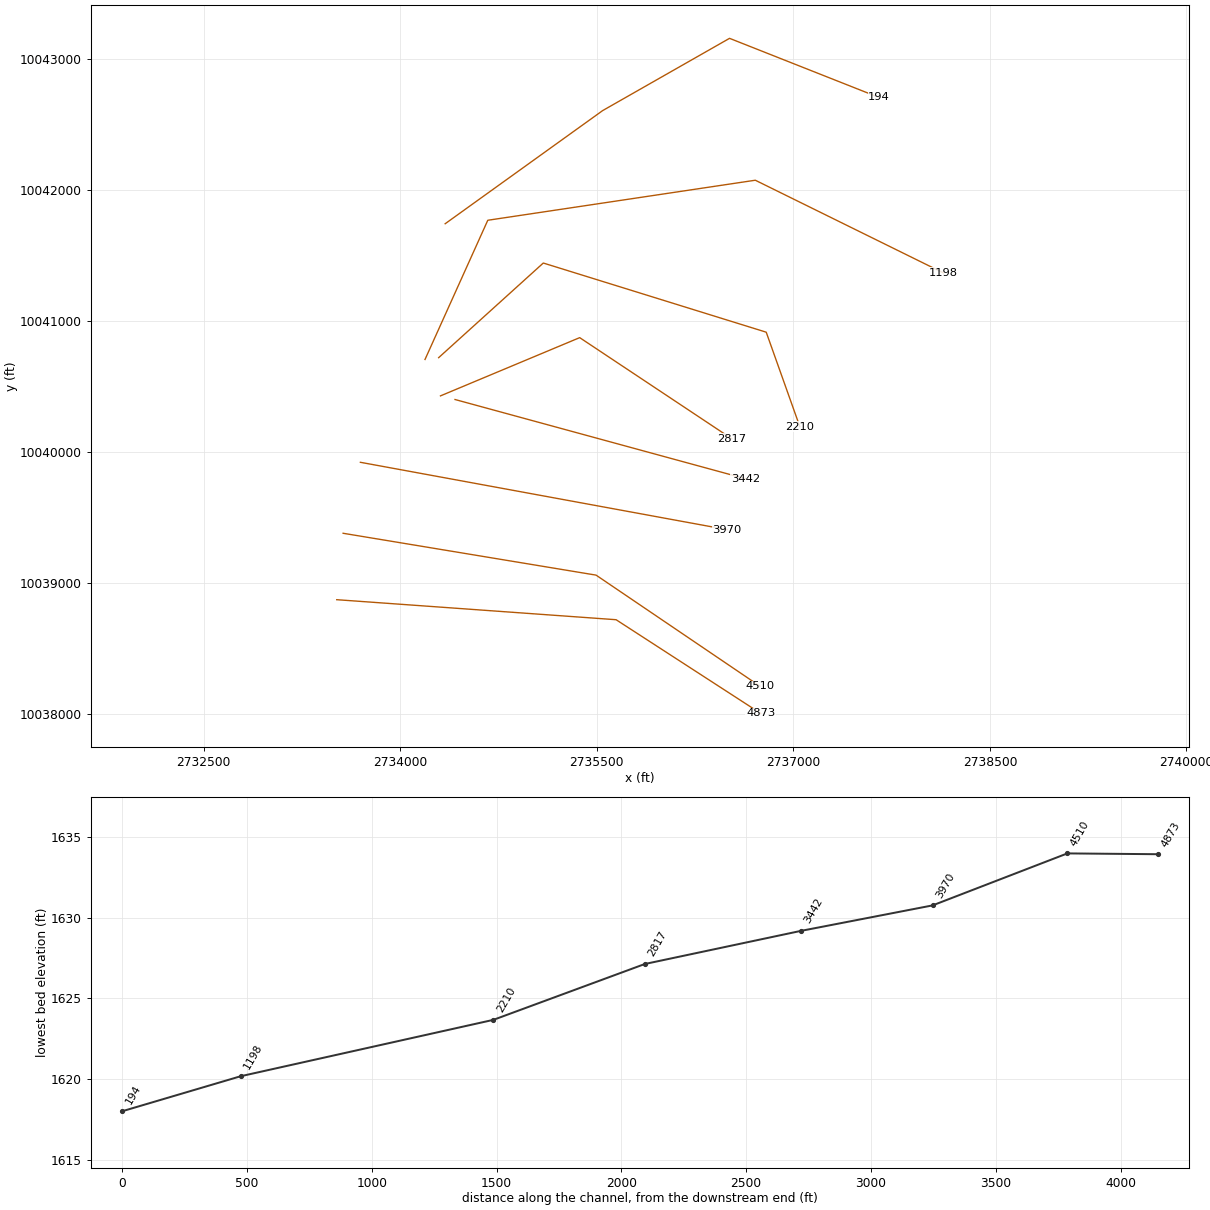
HEC-RAS study BEAR CREEK.prj: BEAR CREEK Base Level Engineering

--- BEAR CREEK.g01 (geometry) --- (continued)

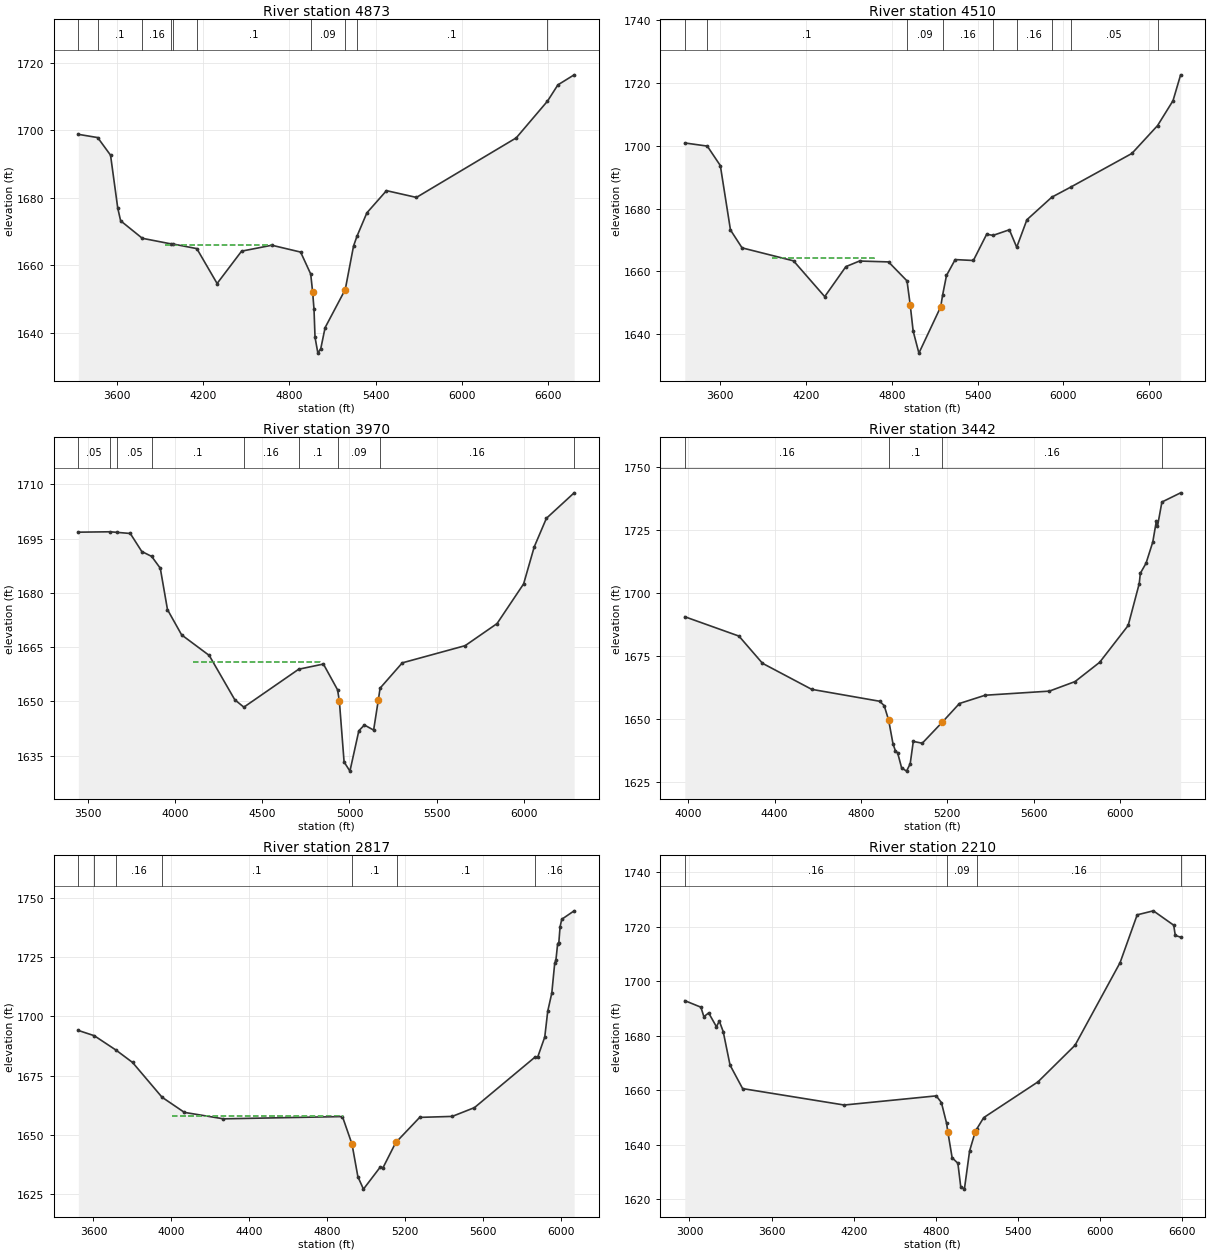
Type RM Length L Ch R = 1 ,4873    ,363,363,363
BEGIN DESCRIPTION:
BEAR CREEK 9.0
END DESCRIPTION:
XS GIS Cut Line= 3
      2733514.72     10038875.87       2735646.7     10038723.09
      2736750.16     10038008.27
#Sta/Elev= 30
    3330 1698.81  3464.7 1697.85  3554.3 1692.63  3604.4 1676.94  3624.5 1673.17
  3775.4 1667.98  3973.9 1666.33  3987.2  1666.3  4154.9 1664.92  4296.2 1654.57
  4466.6 1664.16  4677.2 1665.92  4877.7 1663.89  4947.9 1657.38 4961.36 1652.04
  4970.9 1646.93    4978 1638.62  4997.8 1633.92  5018.1 1635.27  5048.1 1641.48
  5188.5 1652.79  5246.1 1665.67  5269.6 1668.54  5338.9 1675.52  5475.5 1682.11
    5684  1680.1  6378.9 1697.76  6596.5 1708.66    6669 1713.48  6782.2 1716.46
#Mann= 10 ,-1 , 0
    3330     .05       0  3464.7      .1       0  3775.4     .16       0
  3973.9      .1       0  3987.2     .16       0  4154.9      .1       0
  4947.9     .09       0  5188.5     .16       0  5269.6      .1       0
  6596.5      .1       0
#XS Ineff= 1 ,-1
 3936.36 4681.82 1666.06
Permanent Ineff=
       T
Bank Sta=4961.36,5188.5
XS Rating Curve= 0 ,0
Exp/Cntr=0.3,0.1

Type RM Length L Ch R = 1 ,4510    ,540,540,540
BEGIN DESCRIPTION:
BEAR CREEK 8.0
END DESCRIPTION:
XS GIS Cut Line= 3
      2733563.42      10039382.8      2735493.92     10039063.37
      2736743.66     10038216.32
#Sta/Elev= 30
  3352.5 1700.88  3509.7 1699.88  3600.9 1693.68  3671.8 1673.18  3752.9 1667.48
  4112.6 1663.35  4330.7 1651.96  4478.8 1661.51  4573.9 1663.29  4776.7 1663.01
  4906.1 1656.97  4928.7 1649.24    4949    1641  4989.3 1633.97  5141.6 1648.72
  5155.3 1652.53  5182.1 1658.69  5242.9 1663.75    5370 1663.46  5462.9 1671.81
  5507.8 1671.46  5621.7 1673.24    5673 1667.68  5744.4 1676.44  5918.4 1683.62
  6050.8 1686.83  6478.3 1697.54  6657.6  1706.4  6765.8 1714.34    6819 1722.57
#Mann= 9 ,-1 , 0
  3352.5      .1       0  3509.7      .1       0  4906.1     .09       0
  5155.3     .16       0  5507.8      .1       0    5673     .16       0
  5918.4      .1       0  6050.8     .05       0  6657.6      .1       0
#XS Ineff= 1 ,-1
 3963.64 4677.27 1664.16
Permanent Ineff=
       T
Bank Sta=4928.7,5141.6
XS Rating Curve= 0 ,0
Exp/Cntr=0.3,0.1

Type RM Length L Ch R = 1 ,3970    ,528,528,528
BEGIN DESCRIPTION:
BEAR CREEK 7.0
END DESCRIPTION:
XS GIS Cut Line= 2
       2733695.3     10039924.48      2736493.71     10039410.63
#Sta/Elev= 30
  3444.1 1696.76  3626.3 1696.87  3666.1 1696.71  3742.2  1696.4  3808.2 1691.42
  3864.8 1690.07  3914.4  1686.8  3955.7 1675.36    4037 1668.38  4195.2 1662.71
    4342 1650.46    4394 1648.42  4708.6  1658.9  4850.4 1660.33  4931.7 1653.21
  4941.9 1650.13  4969.1 1633.28  5002.6 1630.75  5053.7  1641.9  5085.5 1643.49
  5138.6 1642.09  5165.6 1650.42  5175.7 1653.67    5303 1660.66  5663.8 1665.41
  5846.8 1671.51  5999.3 1682.48  6060.3 1692.71    6130 1700.59  6289.3 1707.63
#Mann= 9 ,-1 , 0
  3444.1     .05       0  3626.3      .1       0  3666.1     .05       0
  3864.8      .1       0    4394     .16       0  4708.6      .1       0
  4931.7     .09       0  5175.7     .16       0  6289.3     .05       0
#XS Ineff= 1 ,-1
  4101.7 4831.53  1660.8
Permanent Ineff=
       T
Bank Sta=4941.9,5165.6
XS Rating Curve= 0 ,0
Exp/Cntr=0.3,0.1

Type RM Length L Ch R = 1 ,3442    ,625,625,625
BEGIN DESCRIPTION:
BEAR CREEK 6.0
END DESCRIPTION:
XS GIS Cut Line= 2
      2734417.52     10040403.65      2736632.81     10039799.48
#Sta/Elev= 30
  3984.4 1690.54  4235.2 1682.85  4344.1 1672.04  4572.1 1661.68  4887.2 1656.94
  4907.9 1655.19  4928.6 1649.37  4948.7 1639.96  4959.7 1637.27  4970.1 1636.42
  4988.4 1630.49  5011.3 1629.17  5028.2 1632.09  5042.6 1640.99  5084.1 1640.26
  5176.7 1648.62  5256.2 1656.05  5375.4 1659.34  5672.5 1660.97  5791.7 1664.77
  5905.7 1672.43  6037.7 1687.07  6088.9 1703.71  6094.1 1707.82  6120.6 1711.84
  6151.7 1720.26  6168.3 1728.64  6173.5  1726.5  6193.9 1736.14  6280.6  1739.8
#Mann= 4 ,-1 , 0
  3984.4     .16       0  4928.6      .1       0  5176.7     .16       0
  6193.9      .1       0
Bank Sta=4928.6,5176.7
XS Rating Curve= 0 ,0
Exp/Cntr=0.3,0.1

Type RM Length L Ch R = 1 ,2817    ,607,607,607
BEGIN DESCRIPTION:
BEAR CREEK 5.0
END DESCRIPTION:
XS GIS Cut Line= 3
      2734306.39     10040431.41      2735368.92     10040875.87
      2736528.66     10040105.02
#Sta/Elev= 30
  3522.2 1694.05  3603.9 1691.83  3714.5 1685.82  3800.6 1680.54  3951.6 1665.89
  4066.4 1659.49  4266.9 1656.77  4877.5 1657.73  4926.6 1646.09  4956.7 1632.35
  4985.3 1627.12  5070.9 1636.36    5086 1636.21  5152.1 1646.95  5158.1 1647.37
  5273.8 1657.38  5440.7 1657.79    5555  1661.5  5864.6 1682.73  5879.6 1682.86
  5915.7  1691.3  5930.8  1702.1  5951.8 1709.85  5966.8 1722.48  5972.8 1723.64
  5981.9  1730.7  5987.9 1731.14  5994.2 1737.76  6002.9 1740.94  6066.5  1744.5
#Mann= 7 ,-1 , 0
  3522.2     .05       0  3603.9      .1       0  3714.5     .16       0
  3951.6      .1       0  4926.6      .1       0  5158.1      .1       0
  5864.6     .16       0
#XS Ineff= 1 ,-1
 4004.55 4878.98 1657.85
Permanent Ineff=
       T
Bank Sta=4926.6,5152.1
XS Rating Curve= 0 ,0
Exp/Cntr=0.3,0.1

Type RM Length L Ch R = 1 ,2210    ,1012,1012,1012
BEGIN DESCRIPTION:
BEAR CREEK 3.0
END DESCRIPTION:
XS GIS Cut Line= 4
      2734292.54      10040723.1      2735091.15     10041445.31
      2736792.53     10040917.53      2737048.88     10040196.98
#Sta/Elev= 30
  2966.2 1692.88  3083.9 1690.48  3105.5    1687  3140.7 1688.36  3197.4  1683.3
  3218.4 1685.38  3246.8 1681.52  3296.8 1669.21  3388.7 1660.58  4130.9 1654.55
  4803.5 1657.91  4841.3 1655.45  4879.1 1647.83  4888.2 1644.67  4919.6 1635.17
  4961.5 1633.17  4982.4 1624.55  5009.2 1623.66  5047.2 1637.69  5087.1 1644.48
  5097.6 1645.59  5150.2 1649.92  5546.4 1663.04  5817.5 1676.49  6146.8 1706.85
  6271.7  1724.4  6389.8 1725.87  6538.6 1720.59  6550.1 1716.83  6589.1  1716.2
#Mann= 4 ,-1 , 0
  2966.2     .16       0  4879.1     .09       0  5097.6     .16       0
  6589.1     .16       0
Bank Sta=4888.2,5087.1
XS Rating Curve= 0 ,0
Exp/Cntr=0.3,0.1

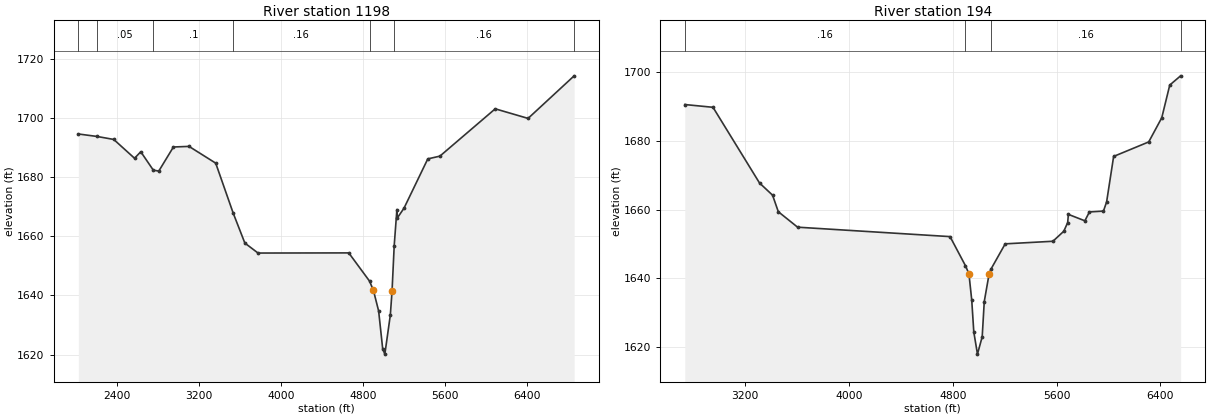
Type RM Length L Ch R = 1 ,1198    ,475,475,475
BEGIN DESCRIPTION:
BEAR CREEK 2.0
END DESCRIPTION:
XS GIS Cut Line= 4
      2734188.38     10040709.22      2734667.53      10041771.7
       2736709.2     10042077.26      2738145.11      10041369.7
#Sta/Elev= 30
    2026 1694.57  2208.6 1693.73    2371 1692.72  2573.7 1686.36  2634.3 1688.56
  2756.5 1682.34  2809.8 1682.03  2952.4 1690.17  3104.6 1690.37  3364.4 1684.71
  3534.8 1667.82  3648.5  1657.7  3776.7 1654.33  4660.8 1654.38  4863.2 1644.84
  4901.3 1641.68  4951.8 1634.75  4991.4 1621.93  5012.3 1620.17  5065.7 1633.37
 5082.39  1641.4  5103.5 1656.87  5129.8 1669.04  5134.8 1666.23    5199  1669.5
  5430.7 1686.15  5548.6 1687.08  6087.7 1703.07  6407.7 1699.83  6856.7 1714.22
#Mann= 7 ,-1 , 0
    2026      .1       0  2208.6     .05       0  2756.5      .1       0
  3534.8     .16       0  4863.2      .1       0  5103.5     .16       0
  6856.7      .1       0
Bank Sta=4901.3,5082.39
XS Rating Curve= 0 ,0
Exp/Cntr=0.3,0.1

Type RM Length L Ch R = 1 ,194     ,0,0,0
BEGIN DESCRIPTION:
BEAR CREEK 1.0
END DESCRIPTION:
XS GIS Cut Line= 4
      2734342.35     10041745.26       2735544.6     10042608.97
      2736512.49     10043160.19      2737653.71      10042708.9
#Sta/Elev= 30
  2734.5 1690.49  2951.8 1689.69  3310.3 1667.71    3411 1664.16  3455.2 1659.36
  3603.9 1654.87  4778.8 1652.13    4897 1643.72  4924.3 1641.35  4945.9 1633.73
  4961.8 1624.46  4990.1    1618  5026.6 1623.03  5042.5 1633.26  5079.9 1641.31
  5093.9 1642.67  5203.9 1650.03  5571.7 1650.78  5655.7  1653.7  5685.4 1656.22
  5690.8 1658.59  5817.9 1656.72    5853  1659.3  5961.1 1659.54  5985.5  1662.2
  6039.6 1675.42    6310 1679.63  6410.5 1686.65  6472.2 1696.15  6555.9 1698.83
#Mann= 4 ,-1 , 0
  2734.5     .16       0    4897     .09       0  5093.9     .16       0
  6555.9     .05       0
Bank Sta=4924.3,5079.9
XS Rating Curve= 0 ,0
Exp/Cntr=0.3,0.1

Chan Stop Cuts=-1
Use User Specified Reach Order=0
Composite Channel Slope=5