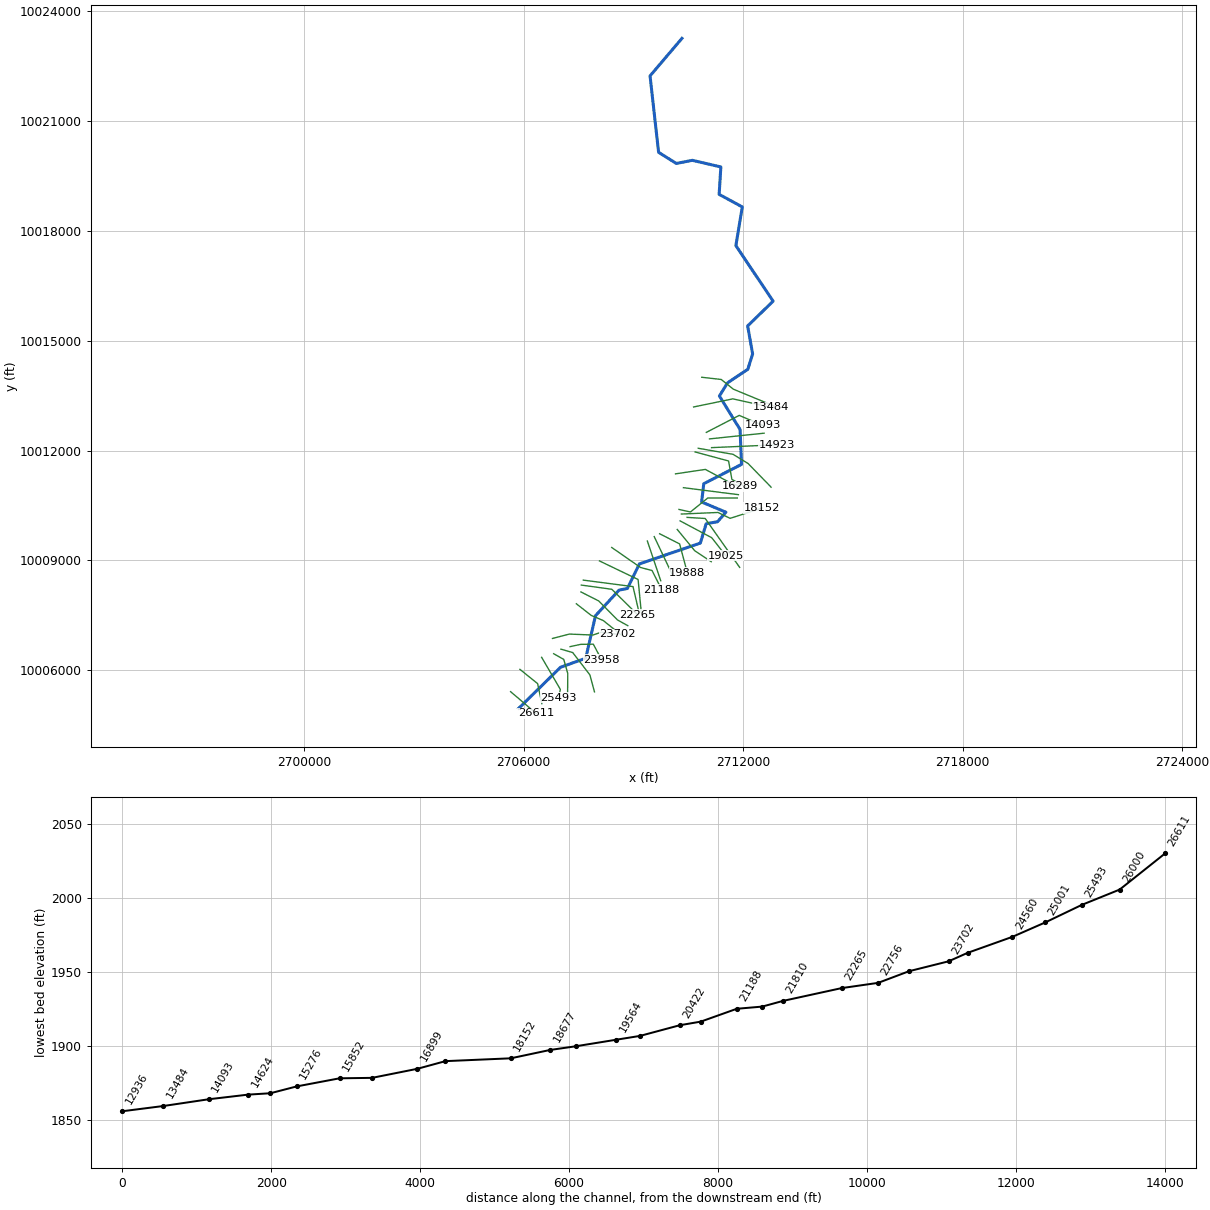
--- BURR OAK CREEK.prj (project) ---

Proj Title=BURR OAK CREEK Base Level Engineering
Current Plan=p01
Default Exp/Contr=0.3,0.1
English Units
Geom File=g01
Flow File=f01
Plan File=p01
Y Axis Title=Elevation
X Axis Title(PF)=Main Channel Distance
X Axis Title(XS)=Station
BEGIN DESCRIPTION:
BURR OAK CREEK
END DESCRIPTION:
DSS Export Rating Curves= 0
DSS Export Rating Curve Sorted= 0
DSS Export Volume Flow Curves= 0
DXF OffsetX= 0
DXF OffsetY= 0
DXF ScaleX= 1
DXF ScaleY= 10

--- BURR OAK CREEK.p01 (plan) ---

Plan Title=Multiple Run
Short Identifier=Multiple
Geom File=g01
Flow File=f01
Subcritical Flow
K Sum by GR= 0
Std Step Tol= 0.01
Critical Tol= 0.01
Num of Std Step Trials= 20
Max Error Tol= 0.3
Flow Tol Ratio= 0.001
Split Flow NTrial= 30
Split Flow Tol= 0.02
Split Flow Ratio= 0.02
Log Output Level= 0
Friction Slope Method= 1
Unsteady Friction Slope Method= 2
Unsteady Bridges Friction Slope Method= 1
Parabolic Critical Depth
Global Vel Dist=  1 , 1 , 1
Global Log Level= 0
CheckData=True
Encroach Param= -1, 0, 0, 0
BEGIN DESCRIPTION:
Multiple Run
END DESCRIPTION:

--- BURR OAK CREEK.f01 (steady flow) ---

Flow Title=Multiple
Program Version=4.10
Number of Profiles= 7
Profile Names=10-year,25-year,50-year,1pct_min,100-year,1pct_plu,500-year
River Rch & RM=BURR OAK CREEK,Reach-1         ,26611
     650     915    1138    1036    1401    1894    2115
River Rch & RM=BURR OAK CREEK,Reach-1         ,23702
    1488    2204    2836    2660    3598    4866    5786
River Rch & RM=BURR OAK CREEK,Reach-1         ,23171
    1488    2204    2836    2660    3598    4866    5786
River Rch & RM=BURR OAK CREEK,Reach-1         ,21188
    2565    3905    5116    4877    6596    8920   10961
River Rch & RM=BURR OAK CREEK,Reach-1         ,20705
    2565    3905    5116    4877    6596    8920   10961
River Rch & RM=BURR OAK CREEK,Reach-1         ,17274
    2889    4394    5750    5469    7396   10003   12242
River Rch & RM=BURR OAK CREEK,Reach-1         ,9811
    3547    5424    7122    6792    9185   12422   15281
River Rch & RM=BURR OAK CREEK,Reach-1         ,3239
    4812    7453    9873    9487   12830   17352   21679
River Rch & RM=BURR OAK CREEK,Reach-1         ,2277
    4812    7453    9873    9487   12830   17352   21679
Boundary for River Rch & Prof#=BURR OAK CREEK,Reach-1         , 1
Up Type= 0
Dn Type= 3
Dn Slope=0.0058
Boundary for River Rch & Prof#=BURR OAK CREEK,Reach-1         , 2
Up Type= 0
Dn Type= 3
Dn Slope=0.0058
Boundary for River Rch & Prof#=BURR OAK CREEK,Reach-1         , 3
Up Type= 0
Dn Type= 3
Dn Slope=0.0058
Boundary for River Rch & Prof#=BURR OAK CREEK,Reach-1         , 4
Up Type= 0
Dn Type= 3
Dn Slope=0.0058
Boundary for River Rch & Prof#=BURR OAK CREEK,Reach-1         , 5
Up Type= 0
Dn Type= 3
Dn Slope=0.0058
Boundary for River Rch & Prof#=BURR OAK CREEK,Reach-1         , 6
Up Type= 0
Dn Type= 3
Dn Slope=0.0058
Boundary for River Rch & Prof#=BURR OAK CREEK,Reach-1         , 7
Up Type= 0
Dn Type= 3
Dn Slope=0.0058
DSS Import GetInterval= 0
DSS Import GetPeak= 0
DSS Import FillOption= 0

--- BURR OAK CREEK.g01 (geometry) ---

Geom Title=Existing Conditions
Program Version=4.10

River Reach=BURR OAK CREEK  ,Reach-1
Reach XY= 30
      2705870.08      10004961.9      2707009.98     10006081.38
      2707699.03     10006329.19      2707965.87     10007490.24
      2708611.34     10008190.92      2708837.72     10008234.34
      2709164.62     10008905.03      2710830.67     10009475.05
      2710989.26     10010002.95      2711301.08     10010058.68
      2711528.31     10010318.18      2710865.72      10010597.2
      2710923.63     10011096.34      2711955.58     10011624.87
      2711916.16     10012577.68      2711351.11     10013492.69
      2711571.82     10013850.38      2712127.43     10014223.35
      2712258.64     10014640.86      2712122.75     10015406.69
      2712818.47     10016083.73      2711800.86     10017600.71
      2711976.68     10018658.01      2711344.17     10019001.33
      2711390.64     10019750.11      2710612.93     10019931.38
      2710174.23     10019845.52      2709690.16     10020149.09
      2709456.91     10022238.08      2710328.47     10023263.73

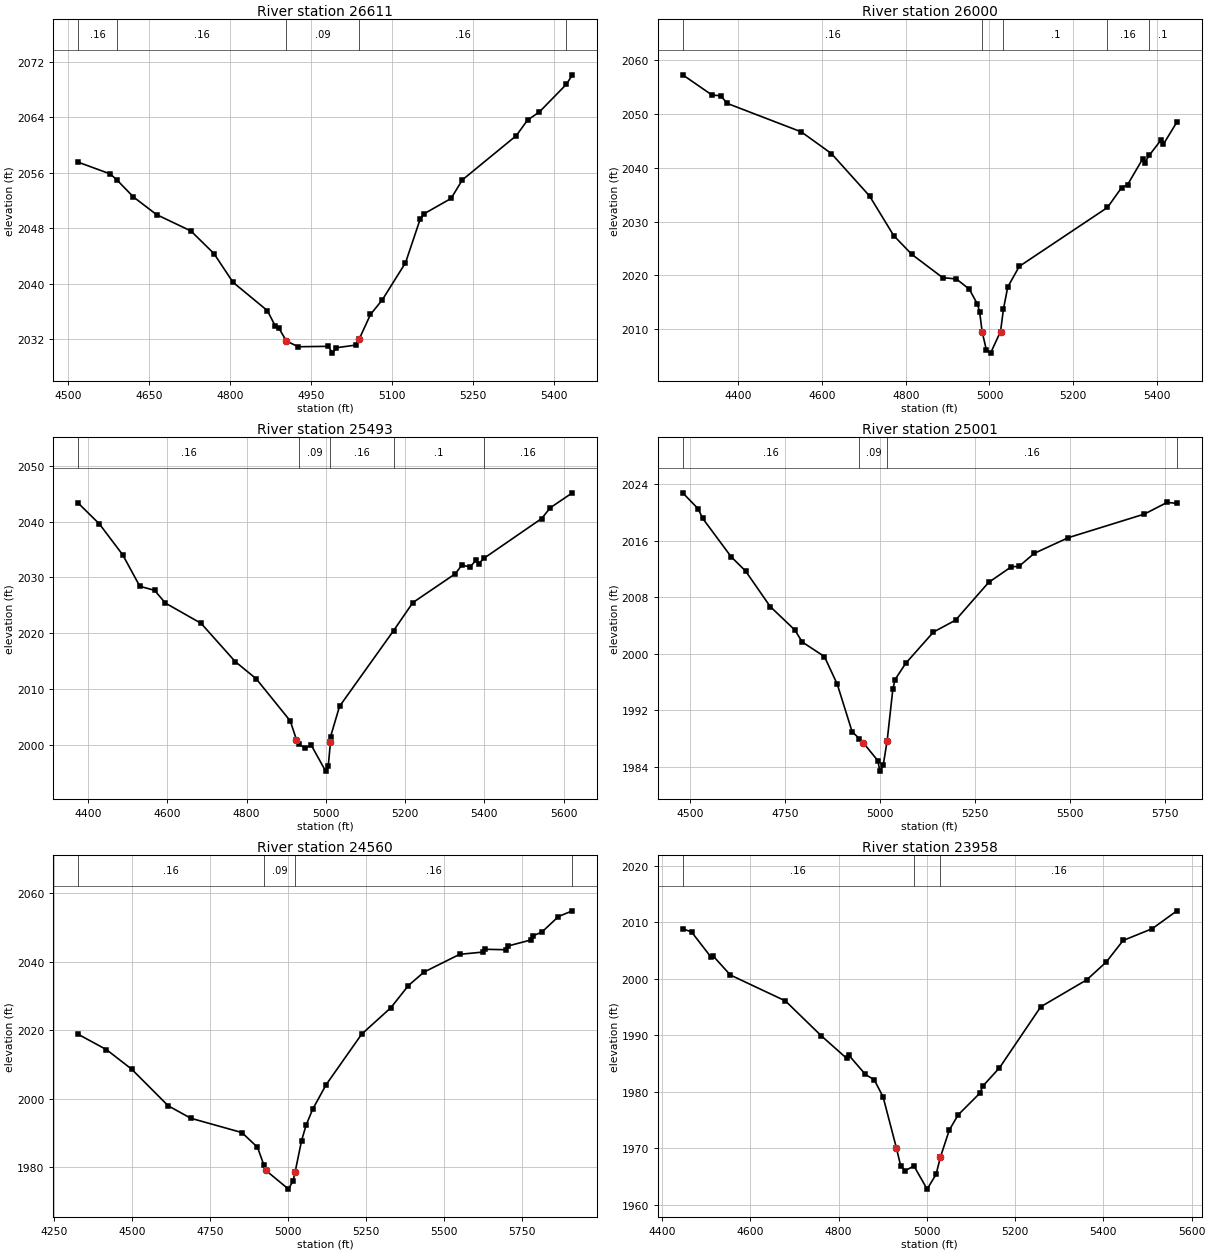
Type RM Length L Ch R = 1 ,26611   ,611,611,611
BEGIN DESCRIPTION:
BURR OAK CREEK 56.0
END DESCRIPTION:
XS GIS Cut Line= 2
      2705646.25     10005415.82      2706343.77      10004822.4
#Sta/Elev= 30
  4518.5 2057.51  4578.1 2055.81  4590.6 2054.93    4621 2052.49  4663.8 2049.95
  4727.5 2047.59  4770.3 2044.32  4805.5 2040.19  4869.1 2036.11  4883.4 2033.95
    4890 2033.65  4904.3 2031.73  4926.3  2030.9  4982.2 2030.96  4989.7 2029.98
  4996.5 2030.75  5032.8 2031.14  5039.4 2032.02  5060.2 2035.55  5082.2 2037.67
  5125.1    2043  5152.5 2049.34  5160.2  2050.1  5209.6 2052.28  5230.4 2054.95
  5330.4 2061.33  5351.2 2063.57  5373.2 2064.75  5423.3 2068.74  5434.3  2070.1
#Mann= 5 ,-1 , 0
  4518.5     .16       0  4590.6     .16       0  4904.3     .09       0
  5039.4     .16       0  5423.3      .1       0
Bank Sta=4904.3,5039.4
XS Rating Curve= 0 ,0
Exp/Cntr=0.3,0.1

Type RM Length L Ch R = 1 ,26000   ,507,507,507
BEGIN DESCRIPTION:
BURR OAK CREEK 55.0
END DESCRIPTION:
XS GIS Cut Line= 3
      2705901.44     10006025.21       2706385.8      10005634.6
      2706500.28     10005088.21
#Sta/Elev= 30
  4267.3 2057.26  4337.7 2053.48  4358.6 2053.38  4372.9 2051.97  4550.5 2046.66
  4622.4 2042.63  4713.6 2034.74  4771.2 2027.39  4814.4  2023.9    4888 2019.58
  4921.1 2019.31  4951.7 2017.43  4971.4 2014.63  4976.5 2013.21  4982.4 2009.55
  4992.6 2006.12  5002.6 2005.54  5026.4 2009.55  5033.5 2013.79  5043.7 2017.84
  5071.2 2021.66  5281.9 2032.61  5315.7 2036.31  5329.8 2036.83  5365.7 2041.61
  5370.8 2040.93  5381.5 2042.29  5410.5 2045.22  5415.6 2044.39  5447.8 2048.49
#Mann= 5 ,-1 , 0
  4267.3     .16       0  4982.4     .09       0  5033.5      .1       0
  5281.9     .16       0  5381.5      .1       0
Bank Sta=4982.4,5026.4
XS Rating Curve= 0 ,0
Exp/Cntr=0.3,0.1

Type RM Length L Ch R = 1 ,25493   ,492,492,492
BEGIN DESCRIPTION:
BURR OAK CREEK 54.0
END DESCRIPTION:
XS GIS Cut Line= 3
      2706495.17     10006353.36      2707005.59     10005478.35
      2706958.72      10005249.2
#Sta/Elev= 30
  4375.2 2043.35  4429.1 2039.57  4487.8 2034.04  4530.8 2028.41    4568 2027.68
  4595.3  2025.4  4685.5 2021.75  4771.5 2014.89  4824.4 2011.81  4910.4 2004.24
  4926.1 2000.85  4931.9 2000.09  4947.6 1999.36  4963.3 1999.89  4999.7 1995.23
  5006.3 1996.19 5011.82 2000.44  5012.1 2001.42  5034.7 2006.86  5171.3 2020.47
  5219.7 2025.48  5327.2 2030.67  5342.9 2032.19  5364.4 2031.89  5380.1 2033.19
  5385.9 2032.45  5398.4  2033.4  5544.7 2040.57  5566.4  2042.5  5622.1 2045.18
#Mann= 5 ,-1 , 0
  4375.2     .16       0  4931.9     .09       0 5011.82     .16       0
  5171.3      .1       0  5398.4     .16       0
Bank Sta=4926.1,5011.82
XS Rating Curve= 0 ,0
Exp/Cntr=0.3,0.1

Type RM Length L Ch R = 1 ,25001   ,441,441,441
BEGIN DESCRIPTION:
BURR OAK CREEK 53.0
END DESCRIPTION:
XS GIS Cut Line= 4
      2706823.33     10006452.29      2707099.34     10006296.06
      2707208.72     10005910.64      2707203.52     10005328.06
#Sta/Elev= 30
  4480.5 2022.78  4520.9 2020.53  4533.2 2019.15  4608.3  2013.7  4645.8 2011.71
  4710.7 2006.67  4775.7 2003.34  4794.9 2001.65  4853.3 1999.59  4887.2 1995.66
  4926.3 1988.93  4945.6 1987.95    4955 1987.41  4994.1 1984.83  4999.1 1983.36
    5008  1984.2  5018.4 1987.65  5033.3 1994.94  5039.2 1996.33  5067.2 1998.63
  5140.2 2003.06  5198.3 2004.74  5285.2 2010.08  5345.2 2012.31  5365.2 2012.36
  5405.2  2014.2  5495.2 2016.43  5695.2 2019.77  5755.2 2021.43  5780.9 2021.28
#Mann= 4 ,-1 , 0
  4480.5     .16       0  4945.6     .09       0  5018.4     .16       0
  5780.9      .1       0
Bank Sta=4955,5018.4
XS Rating Curve= 0 ,0
Exp/Cntr=0.3,0.1

Type RM Length L Ch R = 1 ,24560   ,602,602,602
BEGIN DESCRIPTION:
BURR OAK CREEK 52.0
END DESCRIPTION:
XS GIS Cut Line= 4
      2707021.22     10006577.31      2707344.13     10006483.56
      2707812.88     10005874.18      2707937.89      10005410.6
#Sta/Elev= 30
  4325.8 2018.87  4416.7 2014.38  4497.4 2008.68  4614.5 1997.99  4687.1 1994.34
  4851.1 1990.15  4901.1 1985.86  4921.9 1980.58  4928.2 1979.08  5000.5 1973.63
  5015.1 1976.05  5021.6 1978.56  5042.4 1987.77  5056.9  1992.3  5078.2 1996.99
  5121.3 2004.15  5235.4 2018.92  5328.8 2026.62  5384.9 2033.08  5434.8 2037.02
  5549.4 2042.22    5624 2042.88  5629.2  2043.7  5698.7 2043.56  5703.9 2044.64
  5778.5 2046.43  5783.7 2047.59  5813.3 2048.72  5866.3 2053.26    5911 2054.93
#Mann= 4 ,-1 , 0
  4325.8     .16       0  4921.9     .09       0  5021.6     .16       0
    5911     .16       0
Bank Sta=4928.2,5021.6
XS Rating Curve= 0 ,0
Exp/Cntr=0.3,0.1

Type RM Length L Ch R = 1 ,23958   ,256,256,256
BEGIN DESCRIPTION:
BURR OAK CREEK 51.0
END DESCRIPTION:
XS GIS Cut Line= 4
      2707271.19     10006645.01      2707557.68     10006707.51
      2707906.63     10006712.72      2708130.61     10006290.81
#Sta/Elev= 30
  4446.8 2008.83  4466.9 2008.26  4510.9 2003.82    4516    2004  4554.8 2000.65
  4679.4 1996.08  4760.8 1989.91  4818.7  1985.9  4823.7 1986.43  4860.8 1983.08
  4880.8 1982.13  4900.8 1979.12  4930.8 1970.15  4940.8 1966.89  4950.8 1966.08
  4970.8  1966.9  5000.6 1962.81  5020.9 1965.42  5030.9 1968.51  5050.9 1973.26
  5070.9 1975.93  5120.6 1979.81  5126.2 1980.97  5164.5 1984.24  5258.1 1995.04
  5362.4 1999.81  5406.4 2002.94  5444.7 2006.76  5510.6 2008.84  5566.7    2012
#Mann= 3 ,-1 , 0
  4446.8     .16       0  4970.8      .1       0  5030.9     .16       0
Bank Sta=4930.8,5030.9
XS Rating Curve= 0 ,0
Exp/Cntr=0.3,0.1

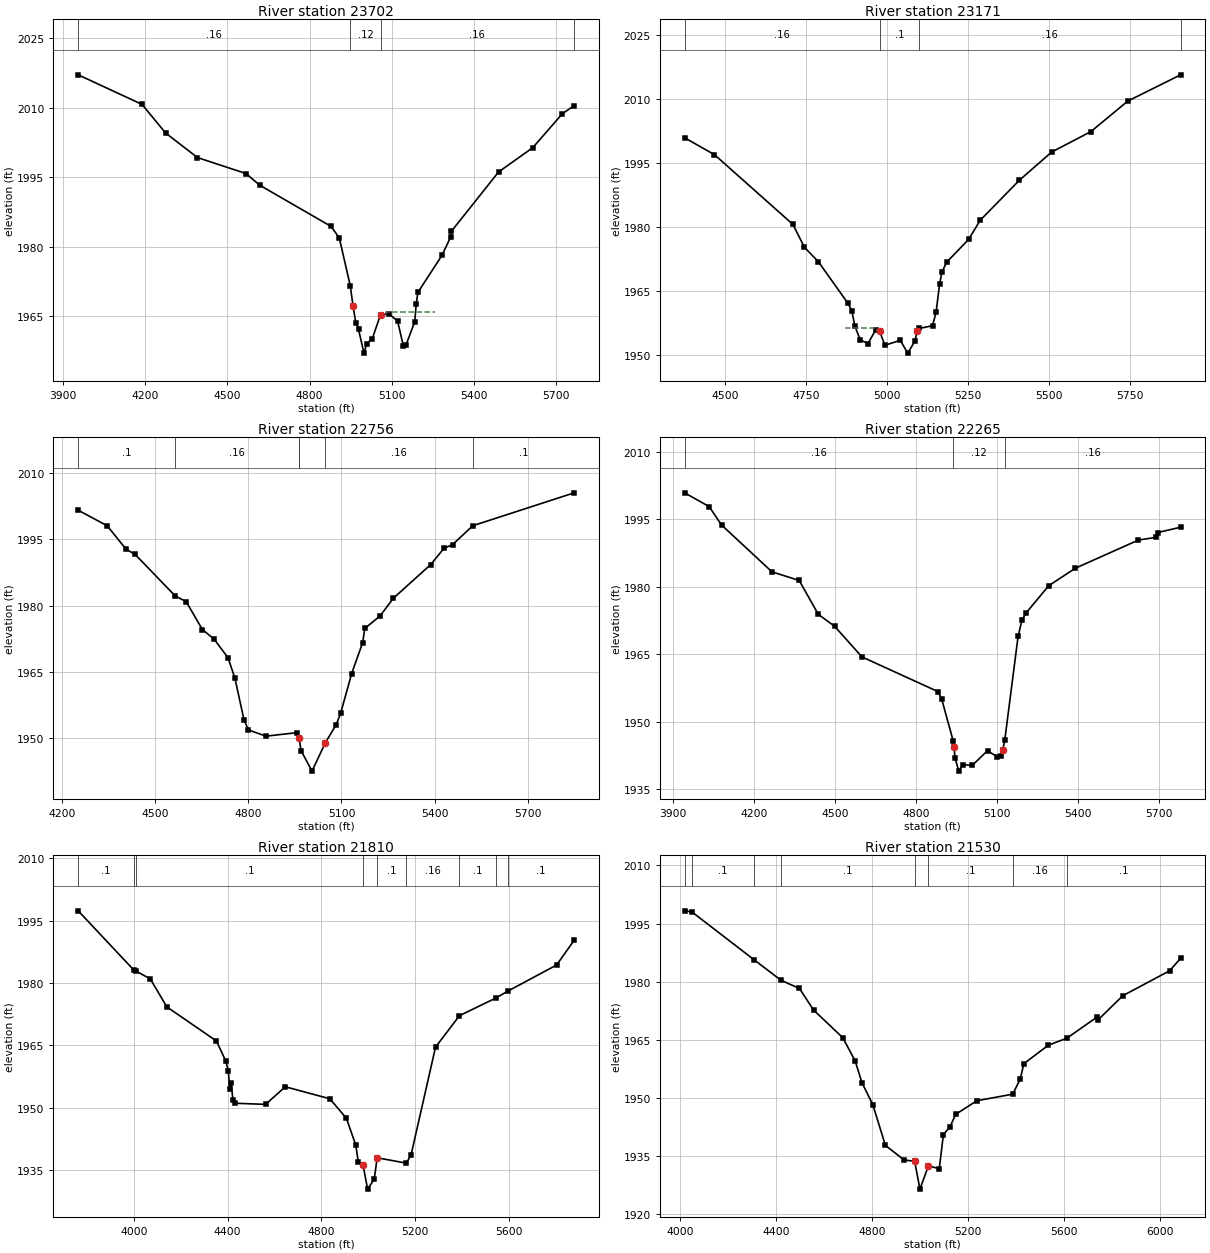
Type RM Length L Ch R = 1 ,23702   ,531,531,531
BEGIN DESCRIPTION:
BURR OAK CREEK 50.0
END DESCRIPTION:
XS GIS Cut Line= 5
      2706792.02     10006868.96      2707250.38     10006988.76
      2707896.22     10006962.72      2708125.38     10007040.85
      2708568.05     10006983.56
#Sta/Elev= 30
  3956.1 2017.06  4188.7 2010.69  4274.8 2004.53  4390.9 1999.23  4568.1 1995.78
  4618.1 1993.27  4878.3 1984.39  4908.3 1981.89  4948.4 1971.55  4958.4 1967.18
  4968.4 1963.62  4978.4 1962.18  4998.2 1957.08  5008.4 1959.14  5028.4 1960.16
  5058.5 1965.34  5089.2 1965.53  5120.7 1964.01    5142  1958.6    5152 1958.91
  5183.4 1963.85  5188.7 1967.66  5194.8 1970.16  5282.7 1978.16    5314 1982.06
  5317.3 1983.36  5489.2 1996.13  5613.9 2001.37  5722.1  2008.7  5764.7  2010.4
#Mann= 4 ,-1 , 0
  3956.1     .16       0  4948.4     .12       0  5058.5     .16       0
  5764.7      .1       0
#XS Ineff= 1 ,-1
 5078.12  5257.1 1965.94
Permanent Ineff=
       T
Bank Sta=4958.4,5058.5
XS Rating Curve= 0 ,0
Exp/Cntr=0.3,0.1

Type RM Length L Ch R = 1 ,23171   ,415,415,415
BEGIN DESCRIPTION:
BURR OAK CREEK 49.0
END DESCRIPTION:
XS GIS Cut Line= 4
      2707443.06     10007816.92      2707849.34     10007499.18
      2708177.47     10007358.56      2708692.05     10006947.93
#Sta/Elev= 30
  4375.9  2000.9  4467.8 1996.96  4710.2 1980.58  4745.4 1975.25  4788.8 1971.83
  4880.2 1962.06  4891.7 1960.37  4901.6 1956.66  4918.1 1953.51  4941.6 1952.65
  4965.2 1955.79  4977.8 1955.51  4994.2 1952.24  5041.4 1953.41  5064.5  1950.4
  5086.6 1953.21  5093.9 1955.61  5099.4 1956.18    5141 1956.83    5152 1959.95
  5162.7  1966.5  5170.1  1969.4  5184.5 1971.71  5252.5 1977.08  5288.3 1981.57
  5409.3 1990.96  5508.6 1997.55  5630.3 2002.38  5743.9 2009.52    5907 2015.68
#Mann= 4 ,-1 , 0
  4375.9     .16       0  4977.8      .1       0  5099.4     .16       0
    5907     .16       0
#XS Ineff= 1 ,-1
 4870.91 4970.11 1956.31
Permanent Ineff=
       T
Bank Sta=4977.8,5093.9
XS Rating Curve= 0 ,0
Exp/Cntr=0.3,0.1

Type RM Length L Ch R = 1 ,22756   ,491,491,491
BEGIN DESCRIPTION:
BURR OAK CREEK 48.0
END DESCRIPTION:
XS GIS Cut Line= 4
      2707568.12     10008139.79      2708052.47     10007895.01
      2708568.09     10007374.18      2708848.62     10007218.33
#Sta/Elev= 30
  4252.6 2001.61  4345.9 1998.09  4407.2 1992.74  4435.1 1991.66  4564.8  1982.2
  4600.3  1980.9  4652.4 1974.58    4690 1972.43  4734.8  1968.2  4757.2 1963.54
  4786.1 1954.19  4800.4 1951.87    4857 1950.44    4956 1951.24  4963.1 1950.13
  4970.1 1947.14  5005.3 1942.53    5048 1948.94  5083.3 1953.08  5097.4 1955.64
  5132.8 1964.61  5168.1 1971.59  5175.2 1974.84  5224.7  1977.7  5267.1 1981.68
  5387.4 1989.31  5429.8 1992.96  5458.1 1993.84  5522.5 1998.09  5849.1 2005.55
#Mann= 6 ,-1 , 0
  4252.6      .1       0  4564.8     .16       0  4963.1      .1       0
  4963.1     .12       0    5048     .16       0  5522.5      .1       0
Bank Sta=4963.1,5048
XS Rating Curve= 0 ,0
Exp/Cntr=0.3,0.1

Type RM Length L Ch R = 1 ,22265   ,786,786,786
BEGIN DESCRIPTION:
BURR OAK CREEK 47.0
END DESCRIPTION:
XS GIS Cut Line= 3
      2707578.52      10008327.3      2708411.84     10008212.72
      2709120.21     10007514.78
#Sta/Elev= 30
  3943.4 2000.91  4034.2 1997.84  4079.7 1993.76  4266.4 1983.33  4367.3 1981.41
    4438 1973.87  4498.5  1971.2  4599.5  1964.4  4880.4 1956.69  4894.6 1955.03
    4937 1945.76 4940.34 1944.32  4944.1 1941.92    4958 1938.98  4972.4 1940.42
  5007.7 1940.25  5064.3 1943.54  5099.7 1942.17  5113.8  1942.4  5120.9 1943.76
    5128 1945.82  5177.4 1968.94  5191.6 1972.55  5205.7 1974.07  5290.6 1980.23
  5389.6 1984.14  5622.9  1990.4  5686.6 1990.99  5693.6 1992.07    5779 1993.25
#Mann= 3 ,-1 , 0
  3943.4     .16       0    4937     .12       0    5128     .16       0
Bank Sta=4940.34,5120.9
XS Rating Curve= 0 ,0
Exp/Cntr=0.3,0.1

Type RM Length L Ch R = 1 ,21810   ,280,280,280
BEGIN DESCRIPTION:
Mapping XS 65c3d446
END DESCRIPTION:
XS GIS Cut Line= 3
      2707633.45     10008462.56      2708991.05     10008285.48
      2709160.91     10007557.53
#Sta/Elev= 30
  3762.4 1997.37  4001.3 1983.01  4007.2 1982.91    4070 1980.98  4140.6 1974.24
  4352.4 1966.02  4392.7 1961.12  4402.8  1958.8  4409.2 1954.58  4414.2 1955.88
    4423  1951.9    4433 1951.03  4562.1 1950.76  4646.2    1955  4836.4 1952.11
    4907 1947.41    4947 1940.95  4957.4 1936.99  4977.6 1936.26  4997.5 1930.35
    5026 1932.77  5038.1  1937.9  5162.4 1936.61  5182.8 1938.55  5287.3 1964.53
  5389.4 1972.12  5544.3 1976.35  5596.9 1978.06  5804.1 1984.32    5879 1990.28
#Mann= 9 ,-1 , 0
  3762.4      .1       0  4001.3     .16       0  4007.2      .1       0
  4977.6     .09       0  5038.1      .1       0  5162.4     .16       0
  5389.4      .1       0  5544.3     .16       0  5596.9      .1       0
Bank Sta=4977.6,5038.1
XS Rating Curve= 0 ,0
Exp/Cntr=0.3,0.1

Type RM Length L Ch R = 1 ,21530   ,342,342,342
BEGIN DESCRIPTION:
Mapping XS 6cf37cfa
END DESCRIPTION:
XS GIS Cut Line= 3
      2708074.35     10008986.89      2709129.94     10008479.92
      2709216.69     10007588.16
#Sta/Elev= 30
  4018.4 1998.28  4048.3 1998.01  4307.5 1985.66  4419.3 1980.39  4496.8 1978.25
  4555.5  1972.7  4677.5 1965.55  4728.8 1959.59    4757 1953.99  4802.3 1948.31
    4855 1937.78  4932.6 1934.04    4977 1933.67  4998.9  1926.5  5034.3  1932.5
  5079.5 1931.76  5096.6 1940.57  5124.8 1942.62  5147.5 1945.77  5235.8 1949.29
  5385.9    1951  5416.7 1954.87  5432.1 1958.86  5533.9 1963.62  5611.1 1965.42
  5737.7 1970.91  5742.7 1970.24  5844.6 1976.39  6039.6 1982.82  6085.4 1986.04
#Mann= 8 ,-1 , 0
  4018.4     .16       0  4048.3      .1       0  4307.5     .16       0
  4419.3      .1       0    4977     .09       0  5034.3      .1       0
  5385.9     .16       0  5611.1      .1       0
Bank Sta=4977,5034.3
XS Rating Curve= 0 ,0
Exp/Cntr=0.3,0.1

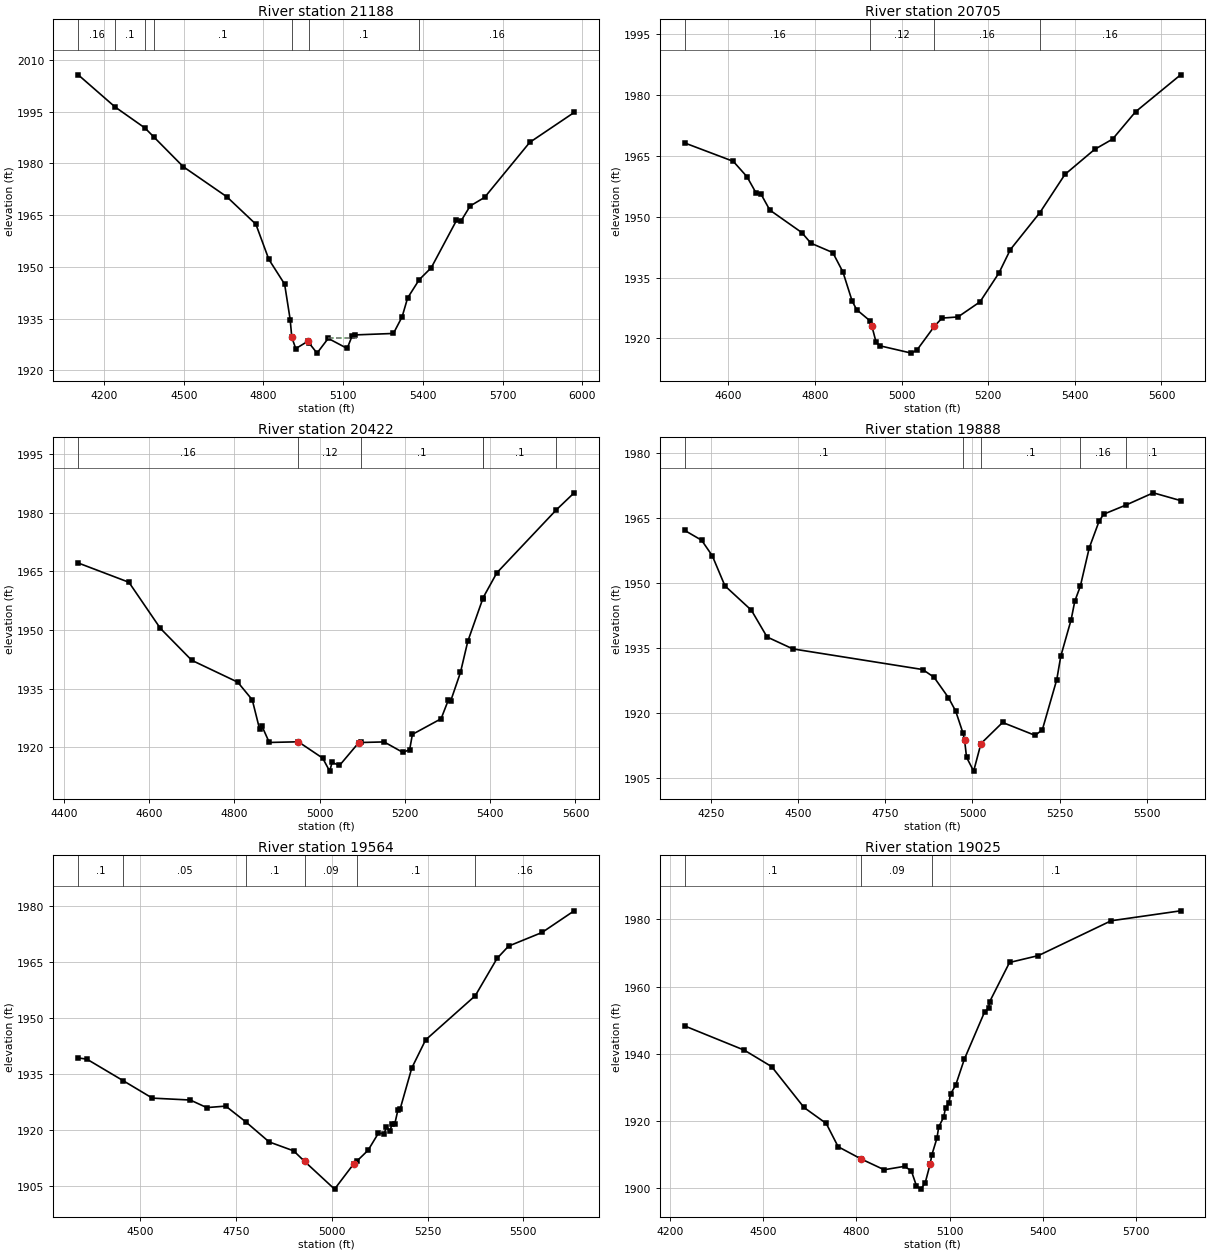
Type RM Length L Ch R = 1 ,21188   ,483,483,483
BEGIN DESCRIPTION:
BURR OAK CREEK 45.0
END DESCRIPTION:
XS GIS Cut Line= 4
      2708409.44     10009354.94      2709195.92     10008808.05
      2709511.02     10008724.72      2709773.75     10008204.46
#Sta/Elev= 30
  4102.6 2005.65  4241.3 1996.34  4353.7 1990.25  4386.7 1987.69    4498 1979.03
  4662.1 1970.31  4771.3 1962.37  4820.1 1952.18  4879.5 1945.01  4900.4 1934.76
  4906.5 1929.62  4921.4 1926.32  4965.9 1928.41    4972  1927.9  5001.5 1925.02
  5043.6 1929.29  5114.9 1926.38  5133.2 1929.93  5145.9  1930.3    5289 1930.72
  5321.8 1935.55  5342.4 1940.99  5386.1  1946.3  5431.5 1949.77  5526.3 1963.45
    5543 1963.25    5578 1967.66  5632.2 1970.14  5802.1 1986.08  5969.3 1994.75
#Mann= 7 ,-1 , 0
  4102.6     .16       0  4241.3      .1       0  4353.7     .16       0
  4386.7      .1       0  4906.5     .09       0    4972      .1       0
  5386.1     .16       0
#XS Ineff= 1 ,-1
 5043.38  5153.8 1929.51
Permanent Ineff=
       F
Bank Sta=4906.5,4965.9
XS Rating Curve= 0 ,0
Exp/Cntr=0.3,0.1

Type RM Length L Ch R = 1 ,20705   ,283,283,283
BEGIN DESCRIPTION:
BURR OAK CREEK 44.0
END DESCRIPTION:
XS GIS Cut Line= 2
      2709383.64     10009529.98      2709748.23     10008444.89
#Sta/Elev= 30
  4499.5 1968.18  4611.6 1963.65  4643.2 1959.87  4664.3 1955.84  4674.9 1955.71
    4696 1951.63  4769.8 1946.08  4790.9 1943.46  4841.4 1941.14  4864.8 1936.35
  4885.9 1929.23  4896.4 1927.07  4928.1 1924.24 4931.36 1923.12  4941.2 1919.07
  4949.2 1918.18  5022.8 1916.35  5035.8 1917.13  5075.8 1922.96  5093.5 1924.99
  5130.3 1925.27  5181.2    1929  5224.9 1936.12  5251.2 1941.88  5319.5 1951.02
  5377.2 1960.42  5445.6 1966.58  5487.2 1969.13  5540.1 1975.86  5644.2 1984.98
#Mann= 4 ,-1 , 0
  4499.5     .16       0  4928.1     .12       0  5075.8     .16       0
  5319.5     .16       0
Bank Sta=4931.36,5075.8
XS Rating Curve= 0 ,0
Exp/Cntr=0.3,0.1

Type RM Length L Ch R = 1 ,20422   ,534,534,534
BEGIN DESCRIPTION:
BURR OAK CREEK 43.0
END DESCRIPTION:
XS GIS Cut Line= 2
      2709570.28      10009651.5       2710069.4     10008601.16
#Sta/Elev= 30
    4434 1967.12  4552.9 1962.19  4626.6 1950.41  4700.2 1942.24    4808 1936.65
  4842.1 1932.14  4859.3 1924.63  4864.8 1925.41    4882 1921.23  4950.2  1921.4
  5007.3 1917.22  5023.6  1913.9  5029.4 1916.13  5046.6 1915.34    5092 1921.21
  5097.6 1921.22  5151.2 1921.37  5195.5 1918.68  5211.2 1919.41  5217.6  1923.3
  5284.9 1927.29  5302.1 1932.14  5307.6 1931.89  5330.3 1939.13  5347.5 1947.09
  5382.7 1957.98  5383.3 1958.22  5415.7 1964.62  5555.3 1980.73  5596.9 1985.06
#Mann= 6 ,-1 , 0
    4434     .16       0  4950.2     .12       0  5097.6      .1       0
  5382.7     .16       0  5383.3      .1       0  5555.3     .16       0
Bank Sta=4950.2,5092
XS Rating Curve= 0 ,0
Exp/Cntr=0.3,0.1

Type RM Length L Ch R = 1 ,19888   ,324,324,324
BEGIN DESCRIPTION:
BURR OAK CREEK 42.0
END DESCRIPTION:
XS GIS Cut Line= 3
      2709717.87     10009729.63      2710264.71     10009451.87
      2710473.04     10008670.61
#Sta/Elev= 30
  4174.9 1962.23  4223.5 1959.96  4254.1 1956.37  4290.3 1949.44  4366.2 1943.81
  4411.1 1937.64    4485 1934.89  4857.3 1930.13  4889.8 1928.35  4931.2 1923.64
  4951.9 1920.54  4972.5 1915.55  4977.6 1913.77    4983 1909.89  5003.4 1906.69
  5024.3 1913.04  5086.4 1917.92  5179.6 1914.94  5200.3 1916.22  5241.7  1927.8
  5253.2  1933.2  5282.9 1941.63  5293.4  1945.9  5309.3 1949.36  5334.8 1958.19
  5363.1 1964.36  5376.2 1965.97  5439.5 1968.06  5518.4  1970.9  5596.8 1969.11
#Mann= 5 ,-1 , 0
  4174.9      .1       0  4972.5     .09       0  5024.3      .1       0
  5309.3     .16       0  5439.5      .1       0
Bank Sta=4977.6,5024.3
XS Rating Curve= 0 ,0
Exp/Cntr=0.3,0.1

Type RM Length L Ch R = 1 ,19564   ,539,539,539
BEGIN DESCRIPTION:
BURR OAK CREEK 41.0
END DESCRIPTION:
XS GIS Cut Line= 3
      2710199.63      10009846.8      2710677.03     10009265.24
      2711128.41     10008965.77
#Sta/Elev= 30
  4338.3 1939.26  4360.9 1938.93  4455.7 1933.15  4531.7 1928.48  4630.7 1927.97
  4673.7 1925.94  4723.3 1926.34  4775.3 1922.14  4836.6 1916.73  4900.5 1914.34
  4929.2 1911.49  5007.2 1904.08  5056.9 1910.81  5064.8 1911.53  5094.6 1914.49
  5121.5 1919.06  5136.5 1918.99  5142.5 1920.62  5151.6 1919.72  5157.6 1921.55
  5164.4 1921.61  5172.6 1925.33  5178.6 1925.66  5208.7 1936.55  5244.8 1944.09
  5374.4 1955.94  5431.3 1965.95  5461.3 1969.24  5548.5 1972.89  5632.4  1978.7
#Mann= 6 ,-1 , 0
  4338.3      .1       0  4455.7     .05       0  4775.3      .1       0
  4929.2     .09       0  5064.8      .1       0  5374.4     .16       0
Bank Sta=4929.2,5056.9
XS Rating Curve= 0 ,0
Exp/Cntr=0.3,0.1

Type RM Length L Ch R = 1 ,19025   ,348,348,348
BEGIN DESCRIPTION:
BURR OAK CREEK 40.0
END DESCRIPTION:
XS GIS Cut Line= 3
      2710277.76     10010081.19      2711141.44     10009621.14
       2711523.4     10009135.02
#Sta/Elev= 30
  4247.1 1948.28  4439.3 1941.06  4527.2 1936.16  4631.3    1924  4702.9 1919.24
  4741.2 1912.32  4814.4 1908.71  4889.3 1905.46  4955.2 1906.48  4977.1 1905.09
  4993.4 1900.64  5006.8 1899.69  5021.1 1901.42  5037.4 1907.13    5043 1909.92
  5059.3 1914.85    5065 1918.18  5081.3  1921.2  5086.9 1923.96  5097.6 1925.33
  5103.2 1928.04  5119.5 1930.61  5147.2 1938.29  5213.1 1952.53  5225.7 1953.66
  5228.8 1955.45    5293 1967.18  5386.1 1969.23  5620.2  1979.6  5843.9 1982.56
#Mann= 3 ,-1 , 0
  4247.1      .1       0  4814.4     .09       0    5043      .1       0
Bank Sta=4814.4,5037.4
XS Rating Curve= 0 ,0
Exp/Cntr=0.3,0.1

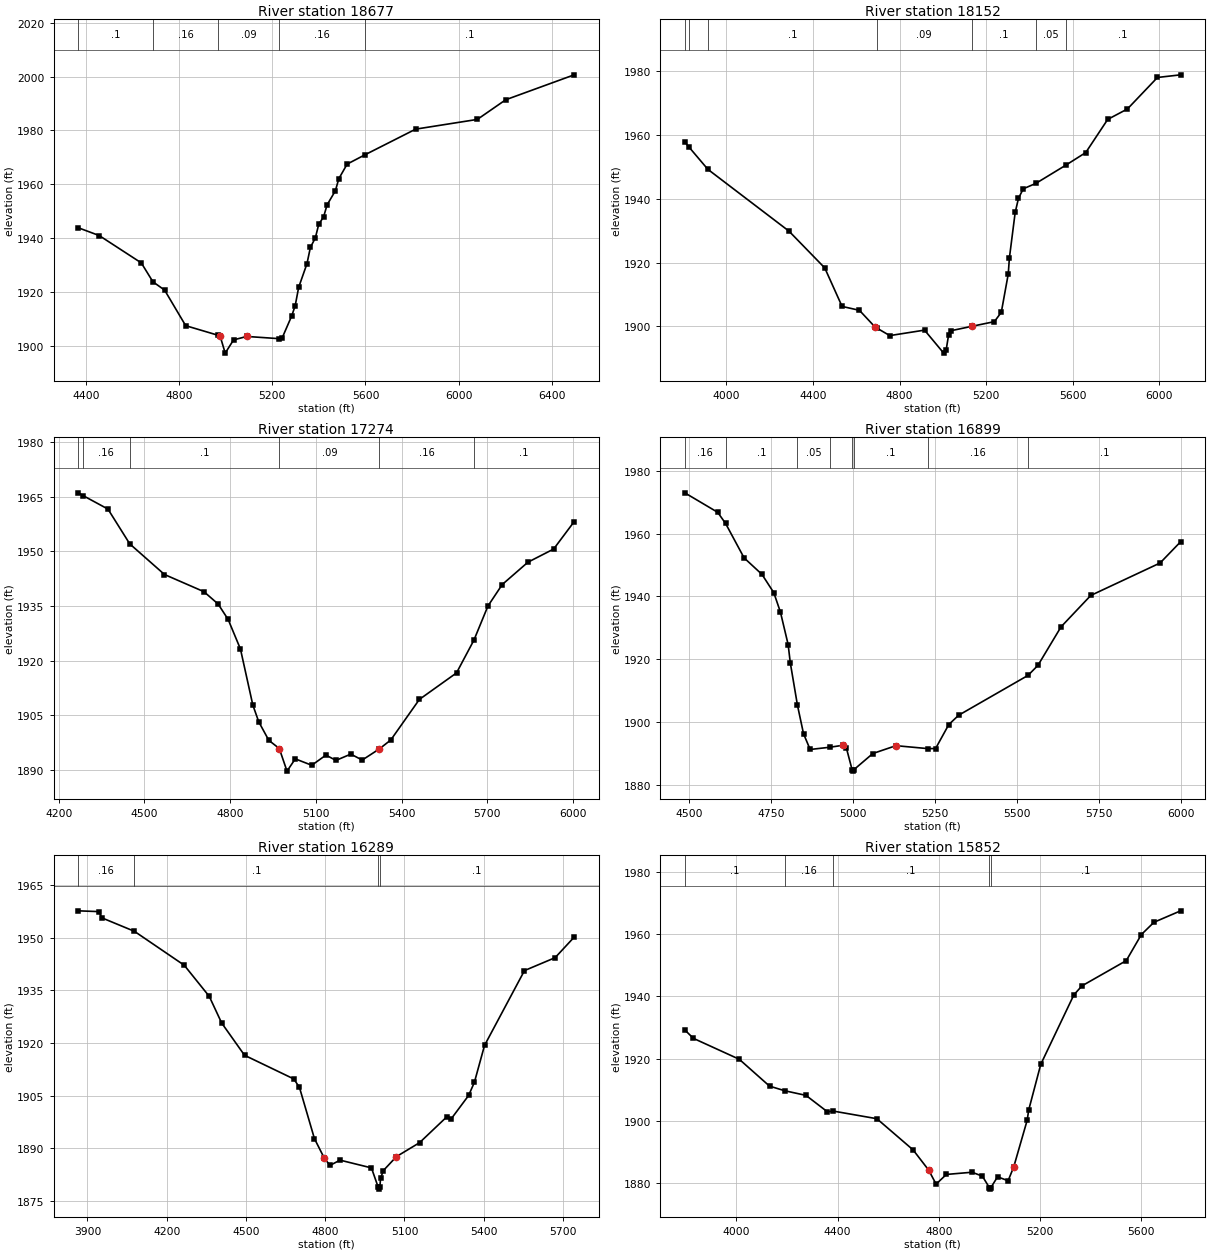
Type RM Length L Ch R = 1 ,18677   ,525,525,525
BEGIN DESCRIPTION:
BURR OAK CREEK 39.0
END DESCRIPTION:
XS GIS Cut Line= 3
      2710468.71      10010176.7      2710963.49     10010146.32
      2711904.42     10008810.81
#Sta/Elev= 30
  4366.9 1943.77  4456.8 1940.87  4637.2 1930.72  4687.3 1923.68  4737.4  1920.6
  4827.9 1907.38  4968.2 1903.78  4975.9  1903.5  4997.6 1897.17  5033.6 1902.09
  5090.2 1903.37  5226.9 1902.56  5241.7  1902.7  5283.5 1911.05  5298.3 1914.83
  5313.1 1921.61  5348.8 1930.42  5363.6 1936.51  5384.6 1939.95  5399.4 1945.07
  5420.3 1947.84  5435.1 1952.27  5470.8 1957.52  5485.6 1962.02  5521.3 1967.44
  5599.7 1970.98  5815.7 1980.44  6080.4 1984.05  6202.4 1991.36  6496.3 2000.63
#Mann= 5 ,-1 , 0
  4366.9      .1       0  4687.3     .16       0  4968.2     .09       0
  5226.9     .16       0  5599.7      .1       0
Bank Sta=4975.9,5090.2
XS Rating Curve= 0 ,0
Exp/Cntr=0.3,0.1

Type RM Length L Ch R = 1 ,18152   ,878,878,878
BEGIN DESCRIPTION:
BURR OAK CREEK 38.0
END DESCRIPTION:
XS GIS Cut Line= 4
      2710312.41     10010267.84      2711310.71     10010311.25
      2711644.92     10010150.66      2712521.61     10010432.76
#Sta/Elev= 30
  3807.7 1957.85  3826.2  1956.3  3914.4 1949.24  4288.9 1929.86  4454.4  1918.3
  4534.4 1906.22  4614.5    1905  4684.6 1899.91  4694.6 1899.45  4754.7 1897.06
  4915.4 1898.78  5003.9 1891.56  5015.1 1892.45  5026.3 1897.17  5037.4 1898.59
  5133.9 1899.97    5238 1901.44  5270.1 1904.37  5302.2 1916.38  5307.5 1921.41
  5334.2  1935.7  5349.5 1940.15  5371.6 1943.14  5429.7 1944.83  5568.2 1950.55
  5660.3 1954.51  5761.8 1964.92  5852.8 1968.19  5991.6 1978.08  6098.7 1978.91
#Mann= 7 ,-1 , 0
  3807.7      .1       0  3826.2     .16       0  3914.4      .1       0
  4694.6     .09       0  5133.9      .1       0  5429.7     .05       0
  5568.2      .1       0
Bank Sta=4684.6,5133.9
XS Rating Curve= 0 ,0
Exp/Cntr=0.3,0.1

Type RM Length L Ch R = 1 ,17274   ,375,375,375
BEGIN DESCRIPTION:
BURR OAK CREEK 36.0
END DESCRIPTION:
XS GIS Cut Line= 4
      2710247.31     10010393.72      2710559.85     10010324.27
      2711032.94     10010706.21      2711840.25     10010706.21
#Sta/Elev= 30
  4268.5 1966.08  4284.5 1965.34  4372.1 1961.62  4448.5 1952.06    4570 1943.65
  4708.1 1938.93  4757.7 1935.55  4792.9  1931.3    4836 1923.17  4879.2 1907.82
    4900 1903.19  4935.2 1898.11  4971.9 1895.86  4998.9 1889.65  5027.9 1893.02
  5085.5 1891.26  5135.1 1894.05  5170.3  1892.6  5222.2 1894.32  5262.2 1892.69
  5322.2 1895.75  5362.2 1898.21  5462.2 1909.34  5592.2 1916.62  5653.3 1925.65
  5702.2 1934.99  5752.2 1940.89  5842.2 1947.03  5932.2 1950.64    6004 1958.17
#Mann= 6 ,-1 , 0
  4268.5      .1       0  4284.5     .16       0  4448.5      .1       0
  4971.9     .09       0  5322.2     .16       0  5653.3      .1       0
Bank Sta=4971.9,5322.2
XS Rating Curve= 0 ,0
Exp/Cntr=0.3,0.1

Type RM Length L Ch R = 1 ,16899   ,610,610,610
BEGIN DESCRIPTION:
BURR OAK CREEK 35.0
END DESCRIPTION:
XS GIS Cut Line= 2
      2710368.84     10010988.33      2711870.64     10010797.35
#Sta/Elev= 30
  4485.9 1972.94  4586.3 1966.75  4610.4 1963.21    4667 1952.26  4721.5 1947.02
  4757.7 1941.19  4777.9 1935.03  4801.4 1924.73  4808.1 1918.87  4829.9 1905.41
  4848.4 1896.38  4868.6 1891.37  4929.9  1892.1  4969.4 1892.71  4979.5 1891.75
  4996.6 1884.99  4999.4 1884.49  5002.6 1884.99  5060.1 1890.09  5130.7 1892.58
  5228.5 1891.64  5251.6 1891.67    5292  1899.3  5322.2 1902.26  5533.9 1914.92
  5564.1  1918.1  5634.7 1930.35  5725.4 1940.32  5937.1 1950.64  5999.8 1957.39
#Mann= 8 ,-1 , 0
  4485.9     .16       0  4610.4      .1       0  4829.9     .05       0
  4929.9      .1       0  4996.6     .07       0  5002.6      .1       0
  5228.5     .16       0  5533.9      .1       0
Bank Sta=4969.4,5130.7
XS Rating Curve= 0 ,0
Exp/Cntr=0.3,0.1

Type RM Length L Ch R = 1 ,16289   ,437,437,437
BEGIN DESCRIPTION:
BURR OAK CREEK 34.0
END DESCRIPTION:
XS GIS Cut Line= 4
      2710151.87     10011365.94      2710967.83     10011487.46
       2711653.6     10011118.54      2711909.71     10011023.04
#Sta/Elev= 30
  3865.4 1957.66  3942.8 1957.44  3955.1 1955.64  4077.5 1951.83  4266.4 1942.15
    4361 1933.29  4407.9 1925.71  4494.6  1916.5  4680.9 1909.76  4702.4 1907.37
  4759.2 1892.75  4796.1 1887.25    4818 1885.12  4856.1 1886.62    4975 1884.41
  5000.8 1878.86  5003.6 1878.36  5006.8 1878.86  5009.5 1881.44  5020.1 1883.65
  5069.5 1887.62  5157.2  1891.6  5261.1 1899.02  5277.3 1898.42    5343 1905.06
  5364.9 1908.84  5403.1 1919.31  5554.3 1940.63  5670.3 1944.31  5742.4 1950.16
#Mann= 4 ,-1 , 0
  3865.4     .16       0  4077.5      .1       0  5000.8     .07       0
  5006.8      .1       0
Bank Sta=4796.1,5069.5
XS Rating Curve= 0 ,0
Exp/Cntr=0.3,0.1

Type RM Length L Ch R = 1 ,15852   ,576,576,576
BEGIN DESCRIPTION:
BURR OAK CREEK 33.0
END DESCRIPTION:
XS GIS Cut Line= 4
      2710685.72     10011964.89      2711601.51      10011717.5
      2711692.66     10011214.02      2712131.01     10010975.32
#Sta/Elev= 30
  3796.1 1929.21    3830 1926.51  4011.4 1919.78    4131 1911.15  4191.5 1909.66
    4275 1908.18    4360 1902.88  4381.6 1903.15  4555.1 1900.68  4698.3 1890.66
  4759.7 1884.18  4789.2 1879.66  4829.8 1882.77  4931.5 1883.48  4972.1 1882.21
  4999.6 1878.55  5002.4 1878.05  5005.6 1878.55  5032.2 1882.01  5073.7 1880.74
  5095.8 1885.15  5149.3 1900.24    5155 1903.44  5202.8 1918.16  5333.6 1940.48
  5365.5 1943.37  5540.6 1951.48  5600.4 1959.87  5650.1 1963.81  5755.5 1967.49
#Mann= 5 ,-1 , 0
  3796.1      .1       0  4191.5     .16       0  4381.6      .1       0
  4999.6     .07       0  5005.6      .1       0
Bank Sta=4759.7,5095.8
XS Rating Curve= 0 ,0
Exp/Cntr=0.3,0.1

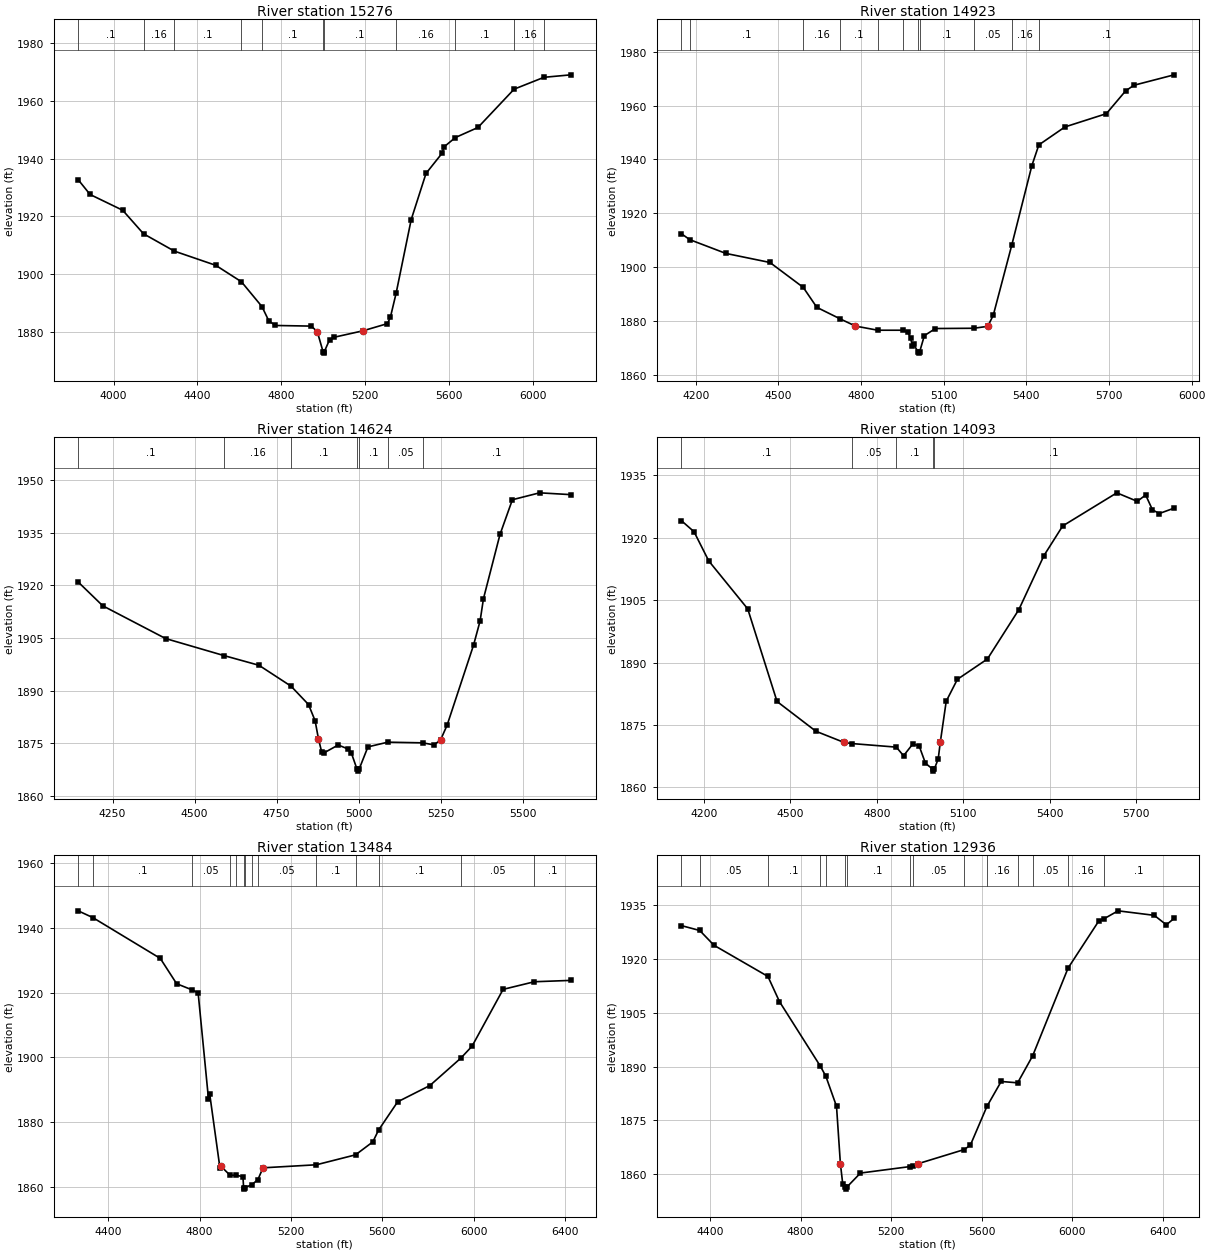
Type RM Length L Ch R = 1 ,15276   ,353,353,353
BEGIN DESCRIPTION:
BURR OAK CREEK 32.0
END DESCRIPTION:
XS GIS Cut Line= 4
       2710772.5     10012064.72      2711723.04     10011899.79
      2712135.37     10011648.05      2712764.07     10011002.01
#Sta/Elev= 30
  3831.6 1932.71  3888.4 1927.58  4043.9 1922.11    4143 1913.96  4290.1 1907.94
  4487.2 1903.03  4609.8 1897.32  4707.7 1888.71    4740 1883.81  4771.4 1882.16
  4943.3 1881.94  4971.8 1879.95  4998.9 1873.07  5001.6 1872.57  5004.9 1873.07
  5029.9 1877.19  5051.2 1878.07  5189.3 1880.31  5305.9  1882.8    5320 1885.02
  5347.1 1893.29  5419.1 1918.87  5489.8 1934.89  5567.5 1941.99  5574.7 1944.03
  5629.5 1947.32  5737.3 1950.82  5909.8 1964.11  6052.1 1968.22  6180.9 1969.08
#Mann= 11 ,-1 , 0
  3831.6      .1       0    4143     .16       0  4290.1      .1       0
  4609.8     .16       0  4707.7      .1       0  4998.9     .07       0
  5004.9      .1       0  5347.1     .16       0  5629.5      .1       0
  5909.8     .16       0  6052.1      .1       0
Bank Sta=4971.8,5189.3
XS Rating Curve= 0 ,0
Exp/Cntr=0.3,0.1

Type RM Length L Ch R = 1 ,14923   ,299,299,299
BEGIN DESCRIPTION:
BURR OAK CREEK 31.0
END DESCRIPTION:
XS GIS Cut Line= 2
      2711137.06     10012082.08      2712924.35     10012160.16
#Sta/Elev= 30
  4147.4  1912.4  4177.8 1910.18    4309 1905.05  4469.1 1901.68    4590 1892.41
  4639.3 1884.99    4725 1880.65 4779.55 1878.02  4860.4 1876.48  4952.4 1876.48
  4969.6  1875.7  4979.6 1873.68  4985.9 1870.63  4990.9 1871.21  5006.6 1868.46
  5009.4 1867.96  5012.6 1868.46  5029.6 1874.45  5069.7 1877.11  5209.4 1877.21
  5259.9 1877.93  5279.9 1882.08  5346.7 1908.04    5420 1937.73  5445.2 1945.41
  5540.1  1952.1  5690.3 1957.03  5760.3 1965.51  5790.4  1967.6  5936.4 1971.48
#Mann= 11 ,-1 , 0
  4147.4     .16       0  4177.8      .1       0    4590     .16       0
    4725      .1       0  4860.4     .05       0  4952.4      .1       0
  5006.6     .07       0  5012.6      .1       0  5209.4     .05       0
  5346.7     .16       0  5445.2      .1       0
Bank Sta=4779.55,5259.9
XS Rating Curve= 0 ,0
Exp/Cntr=0.3,0.1

Type RM Length L Ch R = 1 ,14624   ,531,531,531
BEGIN DESCRIPTION:
BURR OAK CREEK 30.0
END DESCRIPTION:
XS GIS Cut Line= 2
      2711080.64     10012320.79      2712573.59     10012477.03
#Sta/Elev= 30
  4145.4    1921  4220.2 1914.21  4411.7 1904.86  4588.8 1900.02  4696.2 1897.23
  4793.9 1891.26    4847 1886.03  4867.1  1881.4  4877.2 1876.26  4887.3 1872.43
  4893.3 1872.19  4937.5 1874.49  4967.7 1873.33  4977.7 1872.15  4994.9 1867.53
  4997.6 1867.03  5000.9 1867.53    5028 1873.95  5088.4 1875.29  5195.4  1875.1
  5229.1 1874.51  5249.2 1875.92  5269.3 1880.18  5349.8 1903.02  5369.7 1909.91
  5379.9 1916.25  5430.2 1934.55    5468 1944.47  5550.9 1946.44  5646.5 1945.92
#Mann= 7 ,-1 , 0
  4145.4      .1       0  4588.8     .16       0  4793.9      .1       0
  4994.9     .07       0  5000.9      .1       0  5088.4     .05       0
  5195.4      .1       0
Bank Sta=4877.2,5249.2
XS Rating Curve= 0 ,0
Exp/Cntr=0.3,0.1

Type RM Length L Ch R = 1 ,14093   ,609,609,609
BEGIN DESCRIPTION:
BURR OAK CREEK 29.0
END DESCRIPTION:
XS GIS Cut Line= 3
      2710993.87     10012498.75      2711892.31     10012963.16
      2712534.11     10012689.96
#Sta/Elev= 30
  4122.5 1924.15  4166.5 1921.48  4217.7 1914.44  4352.8 1902.91  4454.4 1880.64
  4589.2 1873.48  4686.8 1870.79  4712.7 1870.53  4868.1 1869.66  4893.1 1867.59
  4924.8 1870.39  4946.9 1870.01  4969.1 1865.78  4993.8 1864.39  4996.6 1863.89
  4999.8 1864.39  5013.3 1866.83 5020.45 1870.81  5041.1 1880.71  5079.8 1885.97
    5184 1890.87  5292.7 1902.71    5380 1915.74  5444.9 1922.86  5632.7 1930.83
  5703.6 1928.78  5732.6 1930.31  5756.3 1926.74  5779.9 1925.85  5831.4 1927.15
#Mann= 5 ,-1 , 0
  4122.5      .1       0  4712.7     .05       0  4868.1      .1       0
  4993.8     .07       0  4999.8      .1       0
Bank Sta=4686.8,5020.45
XS Rating Curve= 0 ,0
Exp/Cntr=0.3,0.1

Type RM Length L Ch R = 1 ,13484   ,548,548,548
BEGIN DESCRIPTION:
BURR OAK CREEK 28.0
END DESCRIPTION:
XS GIS Cut Line= 3
      2710646.66     10013193.19       2711718.7     10013414.55
      2712754.78     10013184.79
#Sta/Elev= 30
    4269 1945.27  4333.1 1943.18  4628.2 1930.58  4699.7 1922.76  4766.9 1920.87
  4793.8 1919.92    4839 1887.22  4844.1 1888.83  4889.2 1865.85  4894.3 1866.35
  4933.6 1863.59  4961.3 1863.63  4989.7 1863.14  4992.8 1859.83  4995.6 1859.33
  4998.8 1859.83  5028.2 1860.67  5055.2 1862.27  5077.5 1865.91  5311.1 1866.85
  5482.4 1869.92    5558 1873.92  5582.9 1877.54  5666.6 1886.29  5807.6 1891.32
  5943.4 1899.81  5992.2 1903.48    6128 1921.02  6264.8 1923.37  6424.9 1923.79
#Mann= 14 ,-1 , 0
    4269     .05       0  4333.1      .1       0  4766.9     .05       0
  4933.6      .1       0  4961.3     .05       0  4992.8    .035       0
  4998.8     .05       0  5028.2      .1       0  5055.2     .05       0
  5311.1      .1       0  5482.4     .05       0  5582.9      .1       0
  5943.4     .05       0  6264.8      .1       0
Bank Sta=4894.3,5077.5
XS Rating Curve= 0 ,0
Exp/Cntr=0.3,0.1

Type RM Length L Ch R = 1 ,12936   ,619,619,619
BEGIN DESCRIPTION:
BURR OAK CREEK 26.0
END DESCRIPTION:
XS GIS Cut Line= 4
      2710868.02     10014004.82      2711401.86     10013944.06
      2711731.72      10013679.3      2712854.71     10013215.37
#Sta/Elev= 30
  4273.7 1929.29  4354.9 1927.93    4418  1923.8  4655.9 1915.12  4706.9  1908.1
  4887.6 1890.07  4911.5  1887.3  4958.7 1878.91 4975.85  1862.9  4986.2 1857.25
  4997.3 1856.31  5000.1 1855.81  5003.3 1856.31  5064.3 1860.29    5281 1862.08
  5296.2 1862.22  5318.2 1862.89  5522.8 1866.85  5549.7 1868.09  5622.5 1878.85
  5685.5 1885.83  5758.2 1885.45  5824.5 1892.98  5980.8 1917.44  6117.7  1930.7
  6140.8 1931.24  6201.6 1933.41  6361.4 1932.15  6414.6 1929.51    6449 1931.31
#Mann= 15 ,-1 , 0
  4273.7      .1       0  4354.9     .05       0  4655.9      .1       0
  4887.6     .05       0  4911.5      .1       0  4997.3     .07       0
  5003.3      .1       0    5281     .16       0  5296.2     .05       0
  5522.8      .1       0  5622.5     .16       0  5758.2      .1       0
  5824.5     .05       0  5980.8     .16       0  6140.8      .1       0
Bank Sta=4975.85,5318.2
XS Rating Curve= 0 ,0
Exp/Cntr=0.3,0.1