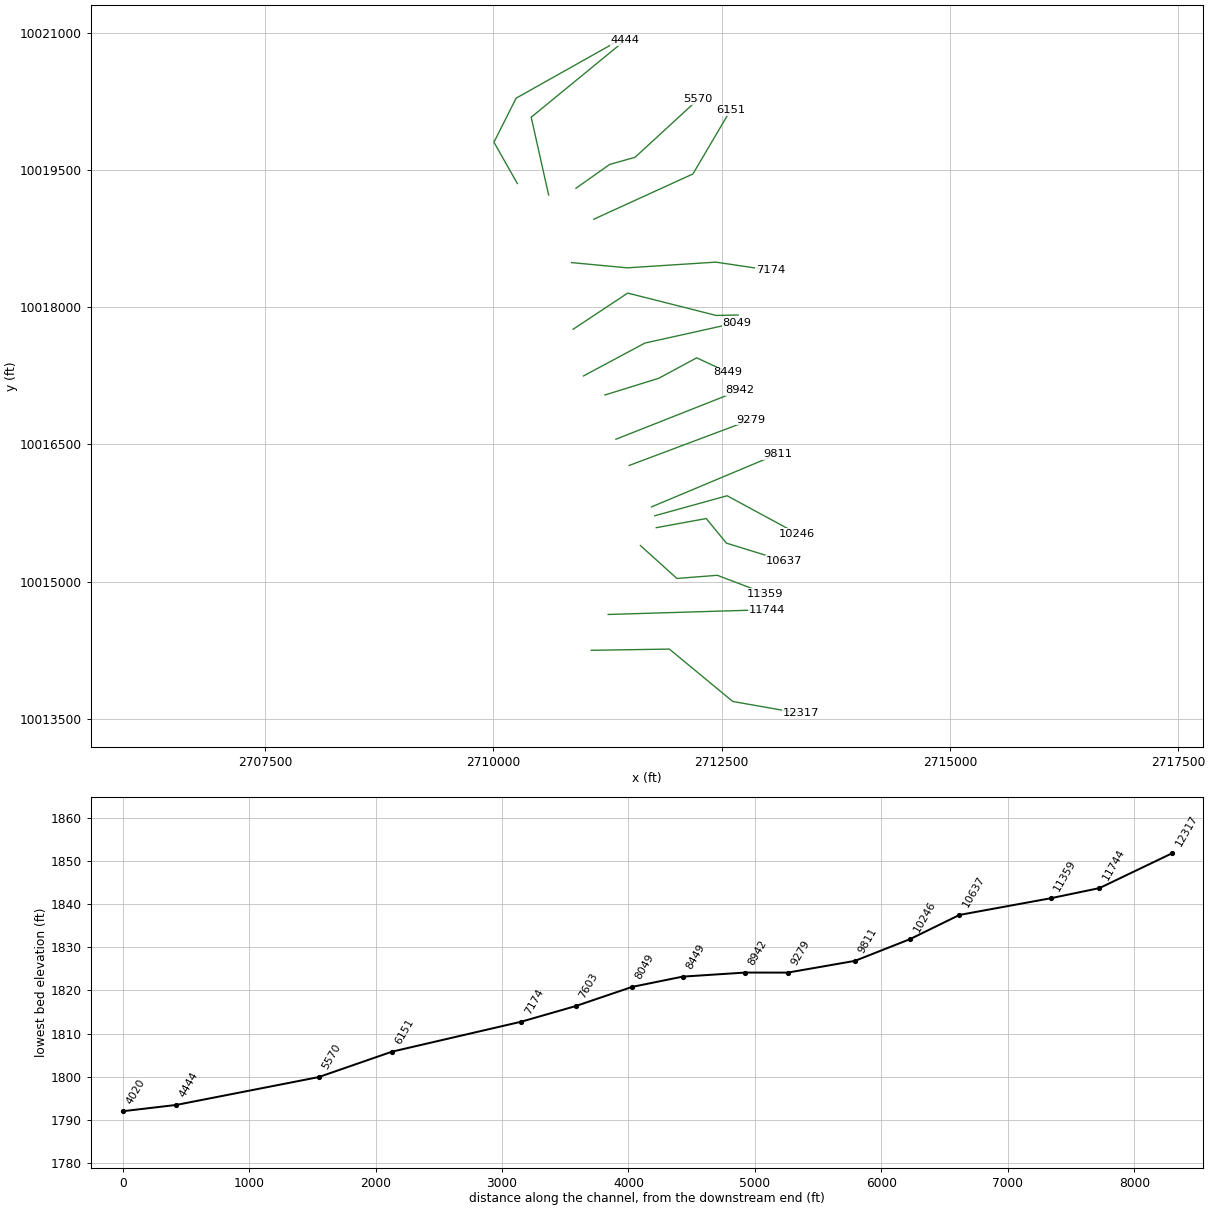
HEC-RAS study BURR OAK CREEK.prj: BURR OAK CREEK Base Level Engineering

--- BURR OAK CREEK.g01 (geometry) --- (continued)

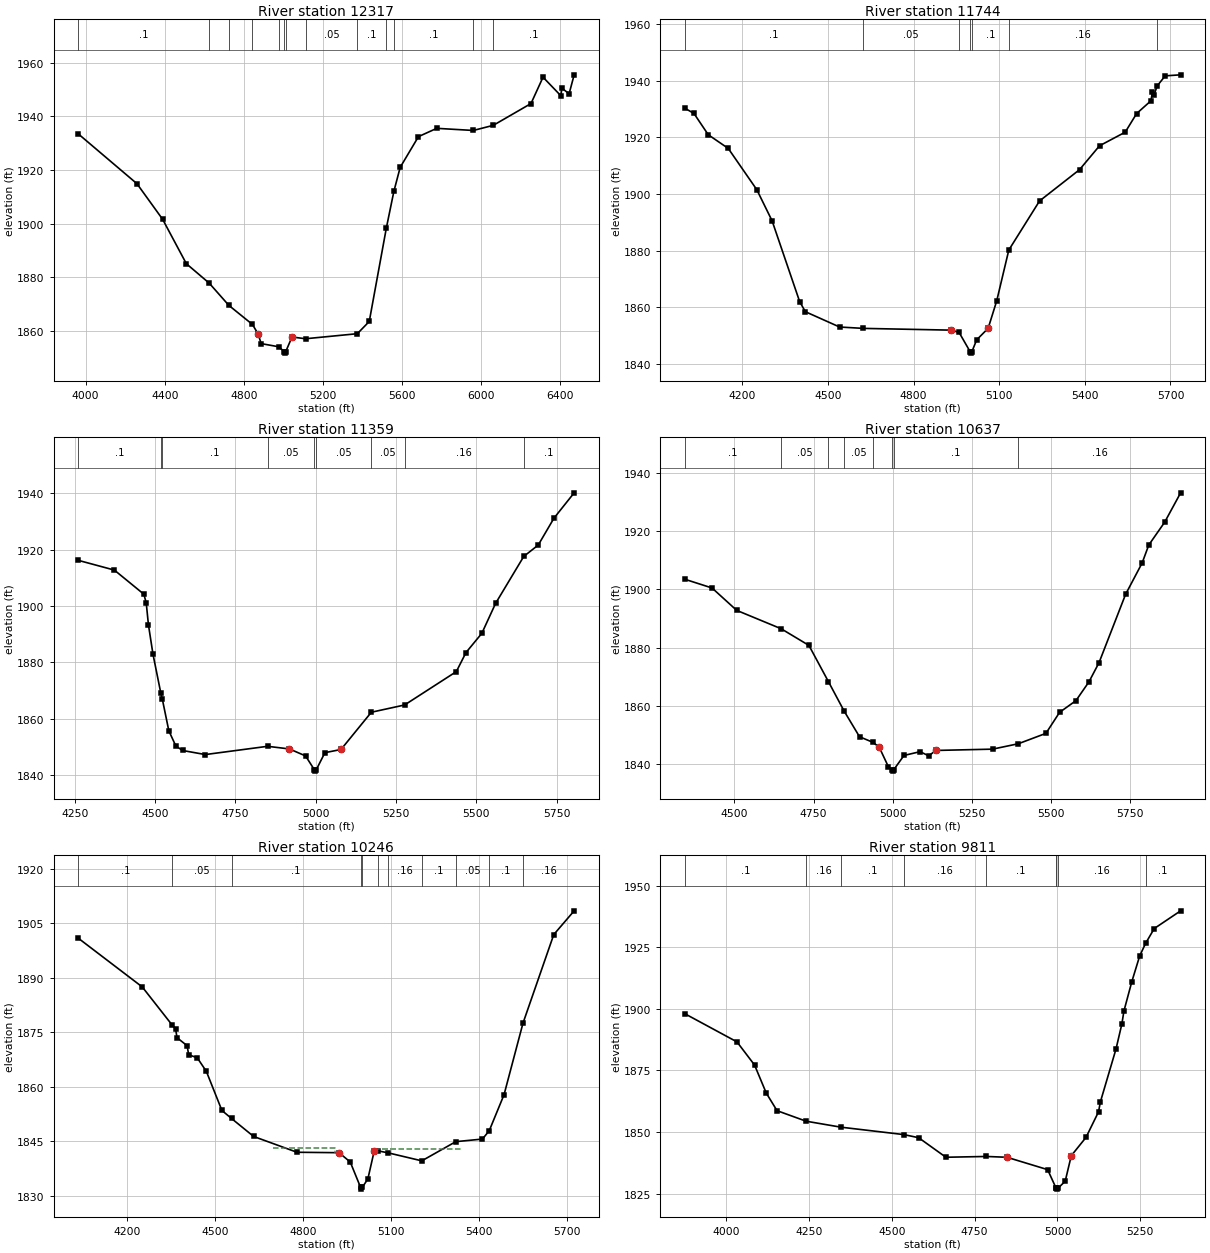
Type RM Length L Ch R = 1 ,12317   ,573,573,573
BEGIN DESCRIPTION:
BURR OAK CREEK 25.0
END DESCRIPTION:
XS GIS Cut Line= 4
      2711071.95     10014247.88      2711927.03      10014260.9
      2712621.48     10013687.98      2713363.59     10013557.79
#Sta/Elev= 30
  3962.8 1933.44  4259.4 1914.89  4389.4 1901.62  4509.4 1885.08    4625 1877.84
  4724.6 1869.54  4843.9 1862.44  4873.4 1858.78  4887.7 1855.31  4976.6 1854.13
  5005.9 1852.26  5008.6 1851.76  5011.9 1852.26    5044 1857.77  5112.5 1857.12
  5374.6    1859  5434.9 1863.56  5521.4 1898.39  5559.6 1912.09  5591.3 1920.97
  5683.8 1932.43  5776.5 1935.52  5961.5 1934.73  6062.4 1936.64  6253.3 1944.76
  6314.2 1954.58  6404.4 1947.66  6409.5 1950.47  6446.2 1948.42  6471.7 1955.46
#Mann= 13 ,-1 , 0
  3962.8      .1       0    4625     .05       0  4724.6      .1       0
  4843.9     .16       0  4976.6      .1       0  5005.9     .07       0
  5011.9      .1       0  5112.5     .05       0  5374.6      .1       0
  5521.4     .16       0  5559.6      .1       0  5961.5     .05       0
  6062.4      .1       0
Bank Sta=4873.4,5044
XS Rating Curve= 0 ,0
Exp/Cntr=0.3,0.1

Type RM Length L Ch R = 1 ,11744   ,385,385,385
BEGIN DESCRIPTION:
BURR OAK CREEK 24.0
END DESCRIPTION:
XS GIS Cut Line= 2
      2711256.35      10014639.6      2712992.47     10014691.68
#Sta/Elev= 30
  3998.7 1930.35  4030.8 1928.49  4080.9 1920.96  4150.9 1916.12  4250.9 1901.53
  4304.6 1890.49    4401 1861.96    4421 1858.37  4541.1 1852.95  4624.3 1852.47
  4931.2 1851.85  4959.5 1851.05  4998.3 1844.22    5001 1843.72  5004.3 1844.22
  5021.3 1848.44  5061.3 1852.49  5091.3 1862.18  5133.7 1880.18  5241.4 1897.54
  5381.4  1908.6  5451.5 1917.05  5541.5 1921.87  5581.5 1928.45  5631.6 1932.97
  5636.9 1936.07  5641.9 1934.84  5653.2  1938.2  5681.6 1941.79  5735.6 1942.15
#Mann= 7 ,-1 , 0
  3998.7      .1       0  4624.3     .05       0  4959.5      .1       0
  4998.3     .07       0  5004.3      .1       0  5133.7     .16       0
  5653.2      .1       0
Bank Sta=4931.2,5061.3
XS Rating Curve= 0 ,0
Exp/Cntr=0.3,0.1

Type RM Length L Ch R = 1 ,11359   ,722,722,722
BEGIN DESCRIPTION:
BURR OAK CREEK 23.0
END DESCRIPTION:
XS GIS Cut Line= 4
      2711610.19     10015393.72       2712009.5     10015033.47
      2712452.21     10015068.19      2712977.09     10014868.65
#Sta/Elev= 30
    4261 1916.18  4373.1 1912.73    4465 1904.16  4472.4 1901.03  4479.2 1893.33
  4493.4 1882.84  4517.6 1869.16  4522.6 1866.84  4542.7 1855.69  4564.4 1850.31
  4585.3  1848.7  4656.3 1847.25  4850.2 1850.18  4918.1 1849.24  4968.3 1846.77
  4995.7 1841.87  4998.5 1841.37  5001.7 1841.87  5028.5 1847.92  5078.6 1849.05
    5173 1862.27  5276.6 1864.85  5437.6 1876.69  5467.7 1883.46    5517 1890.28
  5559.8  1900.9  5647.5 1917.57  5692.6 1921.62  5741.7 1931.18  5804.4 1940.15
#Mann= 9 ,-1 , 0
    4261      .1       0  4517.6     .05       0  4522.6      .1       0
  4850.2     .05       0  4995.7     .07       0  5001.7     .05       0
    5173     .05       0  5276.6     .16       0  5647.5      .1       0
Bank Sta=4918.1,5078.6
XS Rating Curve= 0 ,0
Exp/Cntr=0.3,0.1

Type RM Length L Ch R = 1 ,10637   ,391,391,391
BEGIN DESCRIPTION:
BURR OAK CREEK 21.0
END DESCRIPTION:
XS GIS Cut Line= 4
       2711783.8     10015589.02      2712330.68     10015688.85
      2712552.03     10015419.75      2713184.61     10015224.78
#Sta/Elev= 30
    4343 1903.49  4429.1 1900.48  4506.9 1892.79  4647.3 1886.47  4735.1 1880.74
  4796.8 1868.26  4846.3 1858.16  4894.9 1849.33    4938 1847.37  4957.3  1845.7
  4985.9 1839.06  4997.2    1838    5000  1837.5  5003.2    1838  5035.4 1842.89
  5086.3 1844.19  5113.6 1842.75  5135.8 1844.61  5315.2 1845.06  5396.7 1846.92
  5483.8 1850.49  5526.9 1857.71  5578.5 1861.73  5619.7  1868.2  5651.7 1874.84
  5735.4 1898.29  5787.8 1909.11  5808.7 1915.27  5858.9 1923.11  5909.3 1933.21
#Mann= 8 ,-1 , 0
    4343      .1       0  4647.3     .05       0  4796.8      .1       0
  4846.3     .05       0    4938      .1       0  4997.2     .07       0
  5003.2      .1       0  5396.7     .16       0
Bank Sta=4957.3,5135.8
XS Rating Curve= 0 ,0
Exp/Cntr=0.3,0.1

Type RM Length L Ch R = 1 ,10246   ,435,435,435
BEGIN DESCRIPTION:
BURR OAK CREEK 20.0
END DESCRIPTION:
XS GIS Cut Line= 3
      2711767.89     10015719.49      2712559.51     10015938.22
      2713323.43     10015525.01
#Sta/Elev= 30
  4033.8  1900.9  4251.7  1887.5  4353.6 1877.02    4365 1876.05  4370.2 1873.54
  4404.6 1871.34  4409.8 1868.85  4438.9 1868.03  4470.1 1864.28  4523.1 1853.53
  4555.9 1851.32  4631.3 1846.37    4779 1842.03  4922.4 1841.91  4960.5 1839.35
  4995.6 1832.39  4998.3 1831.89  5001.6 1832.39  5020.5 1834.68  5042.3 1842.42
  5055.5 1842.41  5089.6 1841.87  5204.4 1839.67  5320.3 1844.95    5411 1845.66
  5434.2 1847.96  5484.7 1857.88  5549.1 1877.51  5654.1 1901.91  5723.6 1908.44
#Mann= 11 ,-1 , 0
  4033.8      .1       0  4353.6     .05       0  4555.9      .1       0
  4995.6     .07       0  5001.6      .1       0  5055.5     .05       0
  5089.6     .16       0  5204.4      .1       0  5320.3     .05       0
  5434.2      .1       0  5549.1     .16       0
#XS Ineff= 2 ,-1
 4696.48 4907.16 1843.28 5047.27  5340.8 1843.03
Permanent Ineff=
       T       T
Bank Sta=4922.4,5042.3
XS Rating Curve= 0 ,0
Exp/Cntr=0.3,0.1

Type RM Length L Ch R = 1 ,9811    ,532,532,532
BEGIN DESCRIPTION:
BURR OAK CREEK 19.0
END DESCRIPTION:
XS GIS Cut Line= 2
      2711731.68     10015816.44      2713111.89     10016394.56
#Sta/Elev= 30
  3875.3 1898.02  4032.8 1886.58  4085.8 1877.21  4121.2 1865.81  4153.7 1858.68
  4241.5 1854.41  4346.5 1851.99  4536.4 1848.98    4581 1847.72  4663.3 1839.79
  4785.7 1840.11  4847.6 1839.78  4970.3 1834.77    4995  1827.5  4996.5 1827.36
  4999.3 1826.86  5002.5 1827.36  5023.3 1830.04  5041.7 1840.42  5086.1 1847.84
  5123.9  1858.2  5129.5 1862.23  5176.8 1883.76  5194.5 1893.95  5200.6 1899.12
  5224.4 1911.02  5248.2 1921.47  5266.1 1926.58  5292.1 1932.57  5371.7 1939.75
#Mann= 9 ,-1 , 0
  3875.3      .1       0  4241.5     .16       0  4346.5      .1       0
  4536.4     .16       0  4785.7      .1       0    4995     .16       0
  4996.5     .07       0  5002.5     .16       0  5266.1      .1       0
Bank Sta=4847.6,5041.7
XS Rating Curve= 0 ,0
Exp/Cntr=0.3,0.1

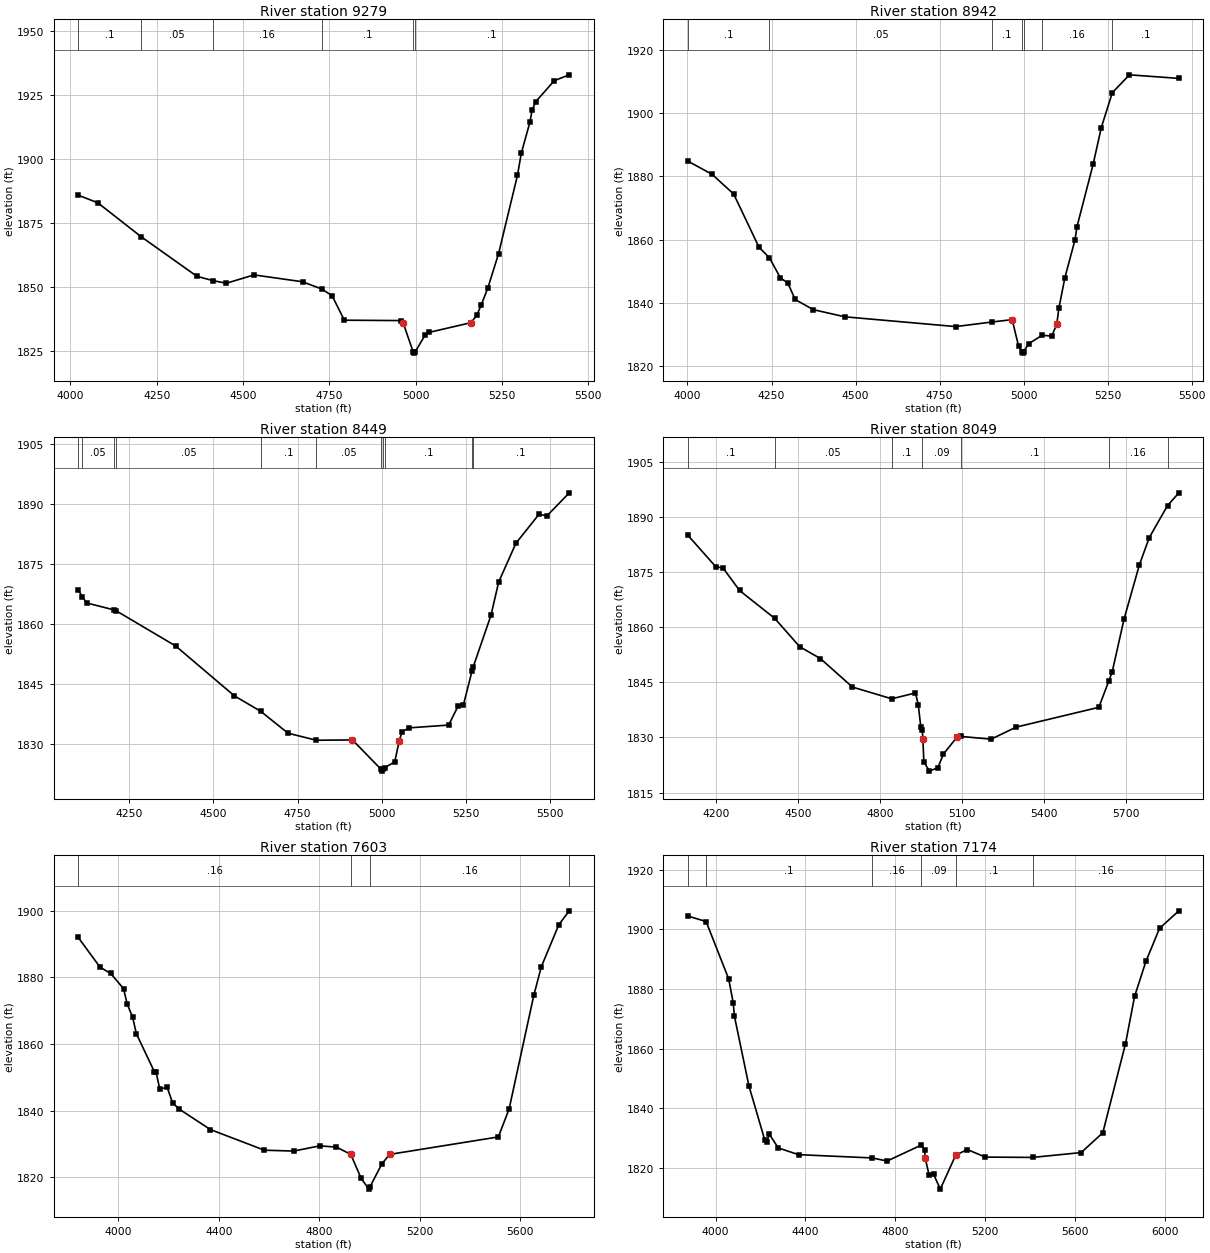
Type RM Length L Ch R = 1 ,9279    ,337,337,337
BEGIN DESCRIPTION:
BURR OAK CREEK 18.0
END DESCRIPTION:
XS GIS Cut Line= 2
      2711486.94     10016269.58      2712819.15     10016769.16
#Sta/Elev= 30
  4022.1 1885.83  4079.6 1882.77  4205.2 1869.53  4366.1 1854.14  4412.6 1852.43
  4451.6 1851.42  4531.7 1854.67  4672.3 1851.99  4727.7 1849.16  4757.7 1846.58
  4793.3 1836.99  4958.9 1836.84  4964.2 1835.76  4992.6 1824.64  4995.4 1824.14
  4998.6 1824.64  5027.6 1831.27  5038.3 1832.22    5160 1836.02  5177.2 1838.95
  5190.3 1843.11  5209.2 1849.64  5240.1 1862.97  5294.7 1893.47    5306 1902.21
  5330.9  1914.3  5337.4 1919.06  5348.1 1922.34  5401.5 1930.48  5444.9 1932.76
#Mann= 6 ,-1 , 0
  4022.1      .1       0  4205.2     .05       0  4412.6     .16       0
  4727.7      .1       0  4992.6     .07       0  4998.6      .1       0
Bank Sta=4964.2,5160
XS Rating Curve= 0 ,0
Exp/Cntr=0.3,0.1

Type RM Length L Ch R = 1 ,8942    ,493,493,493
BEGIN DESCRIPTION:
BURR OAK CREEK 17.0
END DESCRIPTION:
XS GIS Cut Line= 2
       2711341.1     10016556.04      2712700.48      10017092.5
#Sta/Elev= 30
  4000.6 1884.87    4073 1880.68  4137.5 1874.43  4212.8 1857.62  4243.8 1854.31
  4276.1 1848.01  4298.8 1846.25  4320.3 1841.12    4374  1837.9  4468.2 1835.63
  4798.3 1832.54  4904.6 1833.97    4966 1834.74    4985 1826.41  4994.6 1824.65
  4997.3 1824.15  5000.6 1824.65  5014.8 1827.11  5055.5  1829.8  5083.6 1829.53
  5098.6 1833.22  5105.1 1838.37    5123 1848.04  5152.8 1859.87  5158.8 1864.08
  5206.9 1883.82  5231.3 1895.46    5264 1906.48  5315.1 1912.12    5462 1910.99
#Mann= 7 ,-1 , 0
  4000.6      .1       0  4243.8     .05       0  4904.6      .1       0
  4994.6     .07       0  5000.6      .1       0  5055.5     .16       0
    5264      .1       0
Bank Sta=4966,5098.6
XS Rating Curve= 0 ,0
Exp/Cntr=0.3,0.1

Type RM Length L Ch R = 1 ,8449    ,400,400,400
BEGIN DESCRIPTION:
BURR OAK CREEK 16.0
END DESCRIPTION:
XS GIS Cut Line= 4
      2711221.33     10017040.42      2711809.85     10017222.71
      2712226.51     10017446.66      2712564.24     10017290.79
#Sta/Elev= 30
  4097.3 1868.68  4109.3 1866.92  4122.9 1865.31  4203.1  1863.6  4211.2 1863.32
  4387.4 1854.55  4562.5 1842.04  4640.3  1838.2  4721.8 1832.71  4805.8 1830.94
  4913.4 1831.02    4998 1823.71  5000.8 1823.21    5004 1823.71  5008.9 1824.05
  5039.2 1825.53  5052.4 1830.75  5061.1  1833.1    5083 1834.05  5199.6 1834.74
  5228.2  1839.6  5243.7 1839.86  5269.4 1848.36  5272.4 1849.25  5325.5 1862.23
  5348.4 1870.56  5399.8 1880.28  5468.7 1887.55  5491.6 1887.09  5558.4 1892.89
#Mann= 11 ,-1 , 0
  4097.3      .1       0  4109.3     .05       0  4203.1      .1       0
  4211.2     .05       0  4640.3      .1       0  4805.8     .05       0
    4998    .035       0    5004     .05       0  5008.9      .1       0
  5269.4     .05       0  5272.4      .1       0
Bank Sta=4913.4,5052.4
XS Rating Curve= 0 ,0
Exp/Cntr=0.3,0.1

Type RM Length L Ch R = 1 ,8049    ,446,446,446
BEGIN DESCRIPTION:
BURR OAK CREEK 15.0
END DESCRIPTION:
XS GIS Cut Line= 3
      2710986.93     10017248.75       2711658.8     10017608.12
      2712669.23     10017832.08
#Sta/Elev= 30
  4096.4 1885.18  4198.5 1876.59  4226.1 1876.17  4286.2 1870.06  4414.8 1862.46
  4506.4 1854.73  4582.1  1851.5  4699.2 1843.74  4843.1 1840.54  4929.7 1842.14
  4939.9 1838.97  4949.3 1832.86  4954.5 1832.01 4956.82 1829.61  4960.4 1823.37
  4980.7 1820.83  5011.6 1821.76  5032.1 1825.48  5083.3 1830.25  5095.5 1830.29
  5206.3 1829.54  5298.4 1832.83  5600.6 1838.22  5636.4 1845.28  5649.3 1847.84
  5692.9 1862.29  5749.1  1877.1  5785.2 1884.49  5851.8  1893.2  5893.3 1896.68
#Mann= 7 ,-1 , 0
  4096.4      .1       0  4414.8     .05       0  4843.1      .1       0
  4954.5     .09       0  5095.5      .1       0  5636.4     .16       0
  5851.8      .1       0
Bank Sta=4956.82,5083.3
XS Rating Curve= 0 ,0
Exp/Cntr=0.3,0.1

Type RM Length L Ch R = 1 ,7603    ,429,429,429
BEGIN DESCRIPTION:
BURR OAK CREEK 14.0
END DESCRIPTION:
XS GIS Cut Line= 4
      2710872.34     10017759.16       2711471.3       10018155.
      2712440.05     10017910.21      2712679.65     10017915.41
#Sta/Elev= 30
  3839.5 1892.09  3927.1 1883.09  3969.2 1881.22  4020.4 1876.68  4035.4 1871.95
  4056.5 1868.15  4071.6  1863.1  4143.8 1851.62  4149.8 1851.67  4164.8 1846.48
  4194.5 1846.95    4216 1842.33  4243.1 1840.41  4366.5  1834.3  4581.7 1828.09
  4698.9 1827.83  4802.1  1829.4  4868.9 1829.02  4925.8 1826.84  4967.1 1819.63
  4997.8 1816.39    5001 1816.89  5049.6 1823.95  5080.6 1826.83  5513.8 1832.08
  5556.7 1840.51  5655.1 1874.68  5685.1 1883.27  5755.1 1895.93  5796.3 1900.04
#Mann= 4 ,-1 , 0
  3839.5     .16       0  4925.8     .09       0    5001     .16       0
  5796.3      .1       0
Bank Sta=4925.8,5080.6
XS Rating Curve= 0 ,0
Exp/Cntr=0.3,0.1

Type RM Length L Ch R = 1 ,7174    ,1023,1023,1023
BEGIN DESCRIPTION:
BURR OAK CREEK 13.0
END DESCRIPTION:
XS GIS Cut Line= 4
       2710856.7     10018488.33       2711466.1     10018431.04
      2712434.85     10018493.54      2713033.59     10018405.03
#Sta/Elev= 30
  3875.3 1904.51  3957.4 1902.66  4057.9 1883.39    4078  1875.4  4083.8 1870.76
  4148.3 1847.38  4218.6 1829.32  4228.6 1828.55  4238.7 1831.27  4278.8 1826.61
  4369.2 1824.36  4696.5 1823.26  4763.8 1822.22  4916.6  1827.6  4930.7 1826.01
 4933.52 1823.13  4950.7 1817.56  4970.8 1817.77  5000.6 1812.78  5069.4  1824.2
  5121.1 1826.08  5201.2 1823.54  5411.7 1823.43  5628.2 1825.06  5724.6 1831.71
  5825.7 1861.61  5866.2 1877.52  5916.7 1889.28  5977.4 1900.38  6063.4 1906.25
#Mann= 6 ,-1 , 0
  3875.3     .16       0  3957.4      .1       0  4696.5     .16       0
  4916.6     .09       0  5069.4      .1       0  5411.7     .16       0
Bank Sta=4933.52,5069.4
XS Rating Curve= 0 ,0
Exp/Cntr=0.3,0.1

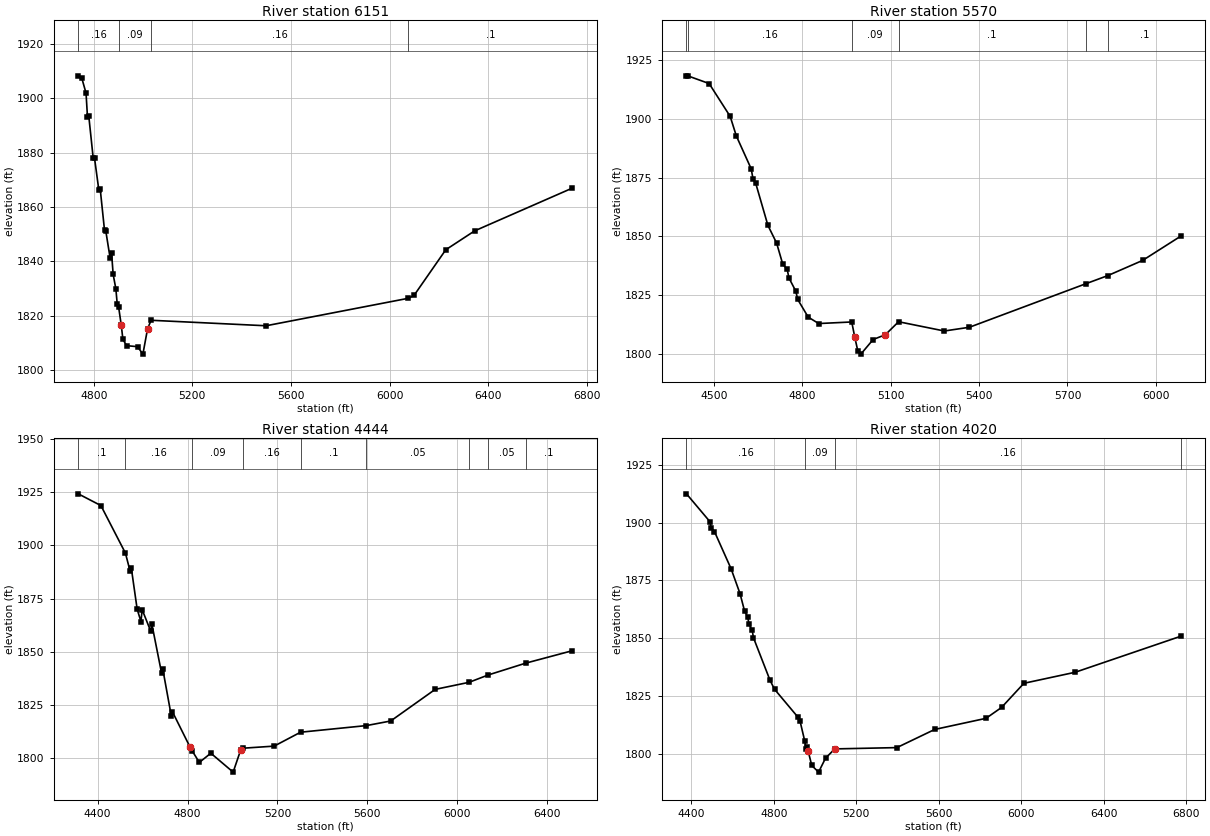
Type RM Length L Ch R = 1 ,6151    ,581,581,581
BEGIN DESCRIPTION:
BURR OAK CREEK 11.0
END DESCRIPTION:
XS GIS Cut Line= 3
      2711099.74     10018963.14      2712184.85     10019457.95
      2712597.19     10020156.76
#Sta/Elev= 30
  4737.4 1908.27  4751.7 1907.44    4769 1901.89  4774.7 1893.27  4780.2 1893.36
  4797.8 1878.18  4803.3 1878.03  4820.8 1866.27  4826.3 1866.74  4843.9  1851.4
  4849.3 1851.05  4866.9 1841.03  4872.4 1843.15  4878.9 1835.22  4889.9 1829.85
  4895.4  1824.3  4900.9 1823.29  4911.9 1816.42  4918.5 1811.23  4933.8 1808.94
  4977.8 1808.58  4999.5 1805.83 5018.47 1815.17  5032.8 1818.29    5499 1816.27
  6076.1 1826.39  6098.9 1827.44  6227.6 1844.24  6344.7  1851.2  6741.4 1866.97
#Mann= 4 ,-1 , 0
  4737.4     .16       0  4900.9     .09       0  5032.8     .16       0
  6076.1      .1       0
Bank Sta=4911.9,5018.47
XS Rating Curve= 0 ,0
Exp/Cntr=0.3,0.1

Type RM Length L Ch R = 1 ,5570    ,1126,1126,1126
BEGIN DESCRIPTION:
BURR OAK CREEK 9.0
END DESCRIPTION:
XS GIS Cut Line= 4
      2710904.45     10019301.69      2711273.39     10019562.11
      2711551.17     10019640.24       2712241.3     10020273.95
#Sta/Elev= 30
  4407.1 1918.32  4411.3 1918.32    4484 1915.03  4555.4 1901.06  4576.3 1892.74
  4626.8 1878.73  4632.9 1874.45  4641.6 1872.82  4683.4 1854.71    4713 1847.16
  4733.9 1838.16  4748.7 1836.09  4754.8 1832.34  4778.3 1826.66  4784.4 1823.23
  4820.1 1815.68  4855.8 1812.94  4967.9 1813.61  4978.2 1807.15  4988.6 1801.23
  4998.8 1799.93  5040.6 1806.15  5082.1 1808.19  5126.8 1813.71  5282.1 1809.77
  5367.2 1811.36  5762.2 1829.87  5836.9 1833.34  5954.8 1839.78  6084.2  1850.1
#Mann= 6 ,-1 , 0
  4407.1      .1       0  4411.3     .16       0  4967.9     .09       0
  5126.8      .1       0  5762.2     .16       0  5836.9      .1       0
Bank Sta=4978.2,5082.1
XS Rating Curve= 0 ,0
Exp/Cntr=0.3,0.1

Type RM Length L Ch R = 1 ,4444    ,424,424,424
BEGIN DESCRIPTION:
BURR OAK CREEK 8.0
END DESCRIPTION:
XS GIS Cut Line= 3
      2710604.98     10019227.92      2710414.01     10020078.61
      2711441.51     10020919.69
#Sta/Elev= 30
  4313.7 1924.15  4414.5 1918.64  4523.7 1896.31  4544.4 1887.85  4549.6  1889.5
  4575.9 1869.96  4592.9 1864.14    4598 1869.81  4636.2 1859.65  4641.3 1862.99
  4684.7 1839.89  4689.8 1841.94    4728 1819.77  4733.1 1821.77  4811.6 1805.17
  4819.8 1803.63  4852.6 1798.04  4903.8 1802.36  5003.1 1793.48  5037.1 1804.02
  5046.6 1804.71  5185.6 1805.69  5303.1 1812.22  5596.1 1815.33  5704.3 1817.49
  5902.4 1832.34  6053.2 1835.65  6138.1 1839.09  6305.5 1844.66  6513.4 1850.51
#Mann= 9 ,-1 , 0
  4313.7      .1       0  4523.7     .16       0  4819.8     .09       0
  5046.6     .16       0  5303.1      .1       0  5596.1     .05       0
  6053.2      .1       0  6138.1     .05       0  6305.5      .1       0
Bank Sta=4811.6,5037.1
XS Rating Curve= 0 ,0
Exp/Cntr=0.3,0.1

Type RM Length L Ch R = 1 ,4020    ,781,781,781
BEGIN DESCRIPTION:
BURR OAK CREEK 6.0
END DESCRIPTION:
XS GIS Cut Line= 4
       2710262.1     10019353.79      2710006.03     10019805.17
      2710249.08     10020286.94      2711415.07     10020941.46
#Sta/Elev= 30
  4376.5 1912.45  4490.5 1900.37  4496.2 1897.79  4512.1 1896.13  4592.9 1879.99
  4636.2 1869.23  4657.8 1861.84  4673.7 1859.06  4679.4 1856.02  4695.3 1853.32
    4701 1850.23  4781.8  1831.7  4803.4 1827.88  4916.9  1815.8  4927.4 1813.95
  4949.9 1805.42  4955.9 1801.96  4961.5 1802.95  4966.9 1800.95  4983.8 1794.91
  5016.8 1792.02  5050.7 1798.08  5095.5 1802.07  5396.3 1802.63  5579.7 1810.49
  5828.4  1815.3  5903.7    1820  6012.1 1830.46  6260.8 1835.24  6772.2 1850.81
#Mann= 4 ,-1 , 0
  4376.5     .16       0  4949.9     .09       0  5095.5     .16       0
  6772.2      .1       0
Bank Sta=4966.9,5095.5
XS Rating Curve= 0 ,0
Exp/Cntr=0.3,0.1