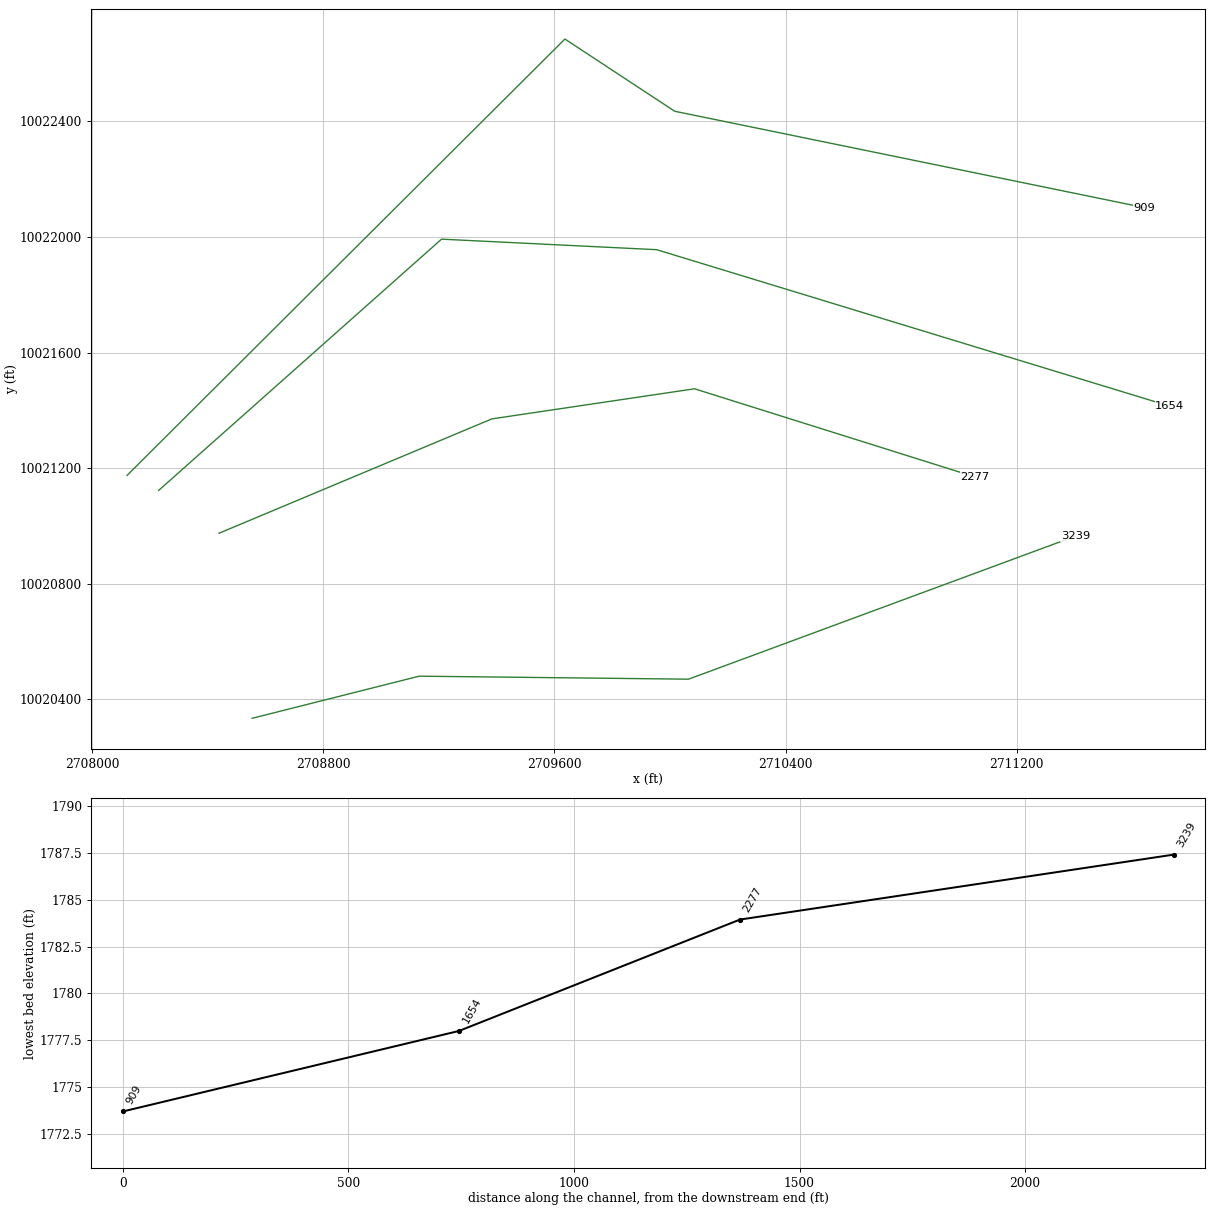
HEC-RAS study BURR OAK CREEK.prj: BURR OAK CREEK Base Level Engineering

--- BURR OAK CREEK.g01 (geometry) --- (continued)

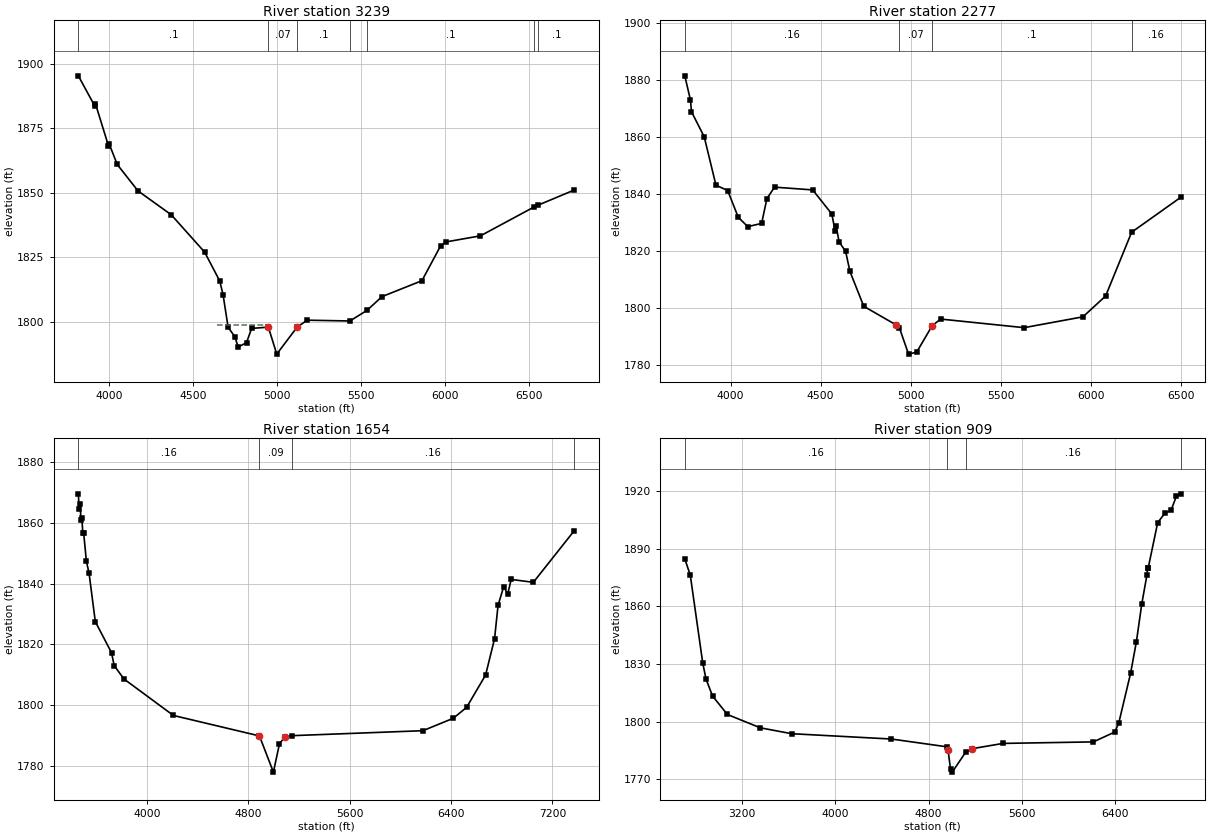
Type RM Length L Ch R = 1 ,3239    ,962,962,962
BEGIN DESCRIPTION:
BURR OAK CREEK 4.0
END DESCRIPTION:
XS GIS Cut Line= 4
      2708553.67     10020333.88      2709131.82     10020479.72
      2710064.11     10020469.31      2711402.68     10020964.11
#Sta/Elev= 30
  3816.2 1895.39  3913.3 1883.79  3918.5 1884.51  3995.4 1868.32  4000.6  1868.9
    4048    1861  4171.8 1850.75  4370.2 1841.47  4569.1 1826.99  4659.1  1815.8
  4679.1 1810.43  4709.1 1797.81  4749.1  1794.2  4769.1 1790.15  4819.1  1791.9
  4849.1 1797.39  4949.1 1797.88  4998.9 1787.41  5119.1 1797.76  5179.2 1800.58
  5435.4 1800.27  5536.7 1804.38  5626.4 1809.72  5864.4  1815.9  5975.4 1829.37
  6005.8 1830.92  6213.4 1833.31  6530.5 1844.42    6559 1845.27  6771.9 1851.06
#Mann= 7 ,-1 , 0
  3816.2      .1       0  4949.1     .07       0  5119.1      .1       0
  5435.4     .16       0  5536.7      .1       0  6530.5     .05       0
    6559      .1       0
#XS Ineff= 1 ,-1
 4641.48 4941.76 1798.62
Permanent Ineff=
       T
Bank Sta=4949.1,5119.1
XS Rating Curve= 0 ,0
Exp/Cntr=0.3,0.1

Type RM Length L Ch R = 1 ,2277    ,623,623,623
BEGIN DESCRIPTION:
BURR OAK CREEK 2.0
END DESCRIPTION:
XS GIS Cut Line= 4
      2708439.09      10020974.5      2709383.56     10021370.35
      2710084.95     10021474.51       2711055.3     10021169.54
#Sta/Elev= 30
  3746.4 1881.54    3778 1872.97  3783.4 1868.96  3854.1 1860.16  3919.2 1843.19
  3984.3 1841.31  4042.9 1831.94  4095.9 1828.64  4172.6  1829.8  4201.8 1838.47
    4244  1842.5  4455.9 1841.53  4561.8 1833.09  4580.2 1827.16  4585.6 1828.91
  4602.3 1823.31  4638.6 1819.94  4662.4 1812.94  4739.1 1800.71    4917 1794.24
  4937.2 1793.09  4987.5 1783.94  5032.5 1784.62  5119.2 1793.97  5166.3 1796.23
  5628.5 1793.22  5954.9 1797.02  6080.7 1804.33  6224.9 1826.69  6496.7  1838.9
#Mann= 4 ,-1 , 0
  3746.4     .16       0  4937.2     .07       0  5119.2      .1       0
  6224.9     .16       0
Bank Sta=4917,5119.2
XS Rating Curve= 0 ,0
Exp/Cntr=0.3,0.1

Type RM Length L Ch R = 1 ,1654    ,745,745,745
BEGIN DESCRIPTION:
Mapping XS e6befdad
END DESCRIPTION:
XS GIS Cut Line= 4
      2708230.06     10021122.66      2709209.22     10021992.45
      2709954.01     10021955.99      2711730.07     10021414.32
#Sta/Elev= 30
  3458.9 1869.55  3465.7 1864.54  3472.4 1866.22    3480 1861.02  3486.7 1861.63
  3494.2  1856.6  3500.9 1856.66  3522.6 1847.33  3543.5 1843.44  3592.9 1827.49
  3720.8 1817.28  3741.7 1813.03  3819.5 1808.61  4209.2 1796.63    4888  1789.9
  4997.9 1777.99  5046.1 1787.33  5088.2 1789.54  5148.3 1789.99  6177.6 1791.62
    6418 1795.72  6522.6 1799.31  6672.3 1809.93  6743.1  1821.9  6770.7 1832.89
  6815.3 1839.03  6846.8 1836.57  6874.4 1841.39    7049 1840.43  7371.1 1857.38
#Mann= 4 ,-1 , 0
  3458.9     .16       0    4888     .09       0  5148.3     .16       0
  7371.1      .1       0
Bank Sta=4888,5088.2
XS Rating Curve= 0 ,0
Exp/Cntr=0.3,0.1

Type RM Length L Ch R = 1 ,909     ,0,0,0
BEGIN DESCRIPTION:
BURR OAK CREEK 1.0
END DESCRIPTION:
XS GIS Cut Line= 4
      2708120.67     10021174.74       2709636.3     10022685.16
      2710016.51     10022435.16      2711641.49     10022101.83
#Sta/Elev= 30
  2709.2 1884.72  2756.4 1876.19  2862.5 1830.74  2890.8 1822.21  2947.3 1813.31
  3074.6 1803.69  3357.5 1796.75  3626.2 1793.69  4481.8 1790.92  4959.2 1786.86
  4967.5 1785.12  4988.6 1775.43  5003.4 1773.69  5118.1 1784.01  5175.4 1785.91
  5439.6 1788.64  6214.5 1789.43  6398.3 1794.58  6432.4 1799.34  6533.2 1825.05
  6583.6 1841.67  6628.9 1861.02  6673.9 1876.35  6679.3 1880.07  6684.4 1879.89
  6765.8  1903.5  6825.4 1908.33  6880.9 1910.02  6926.2 1917.27  6962.8 1918.56
#Mann= 4 ,-1 , 0
  2709.2     .16       0  4959.2     .09       0  5118.1     .16       0
  6962.8      .1       0
Bank Sta=4967.5,5175.4
XS Rating Curve= 0 ,0
Exp/Cntr=0.3,0.1

Chan Stop Cuts=-1
Use User Specified Reach Order=0
Composite Channel Slope=5