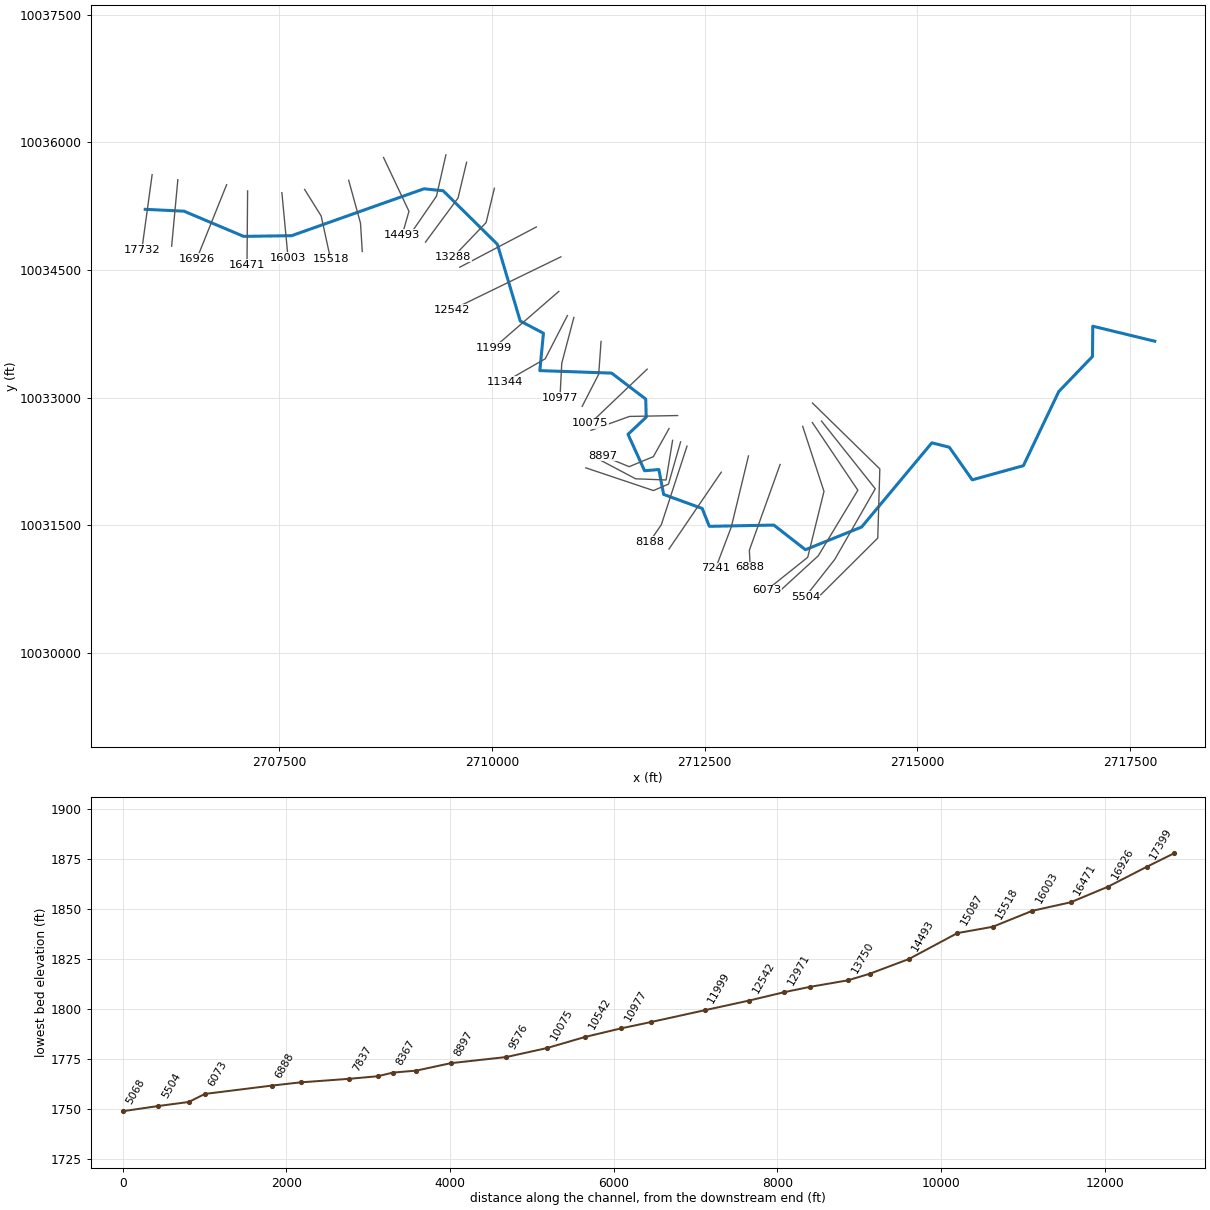
--- DELAWARE CREEK.prj (project) ---

Proj Title=DELAWARE CREEK Base Level Engineering
Current Plan=p01
Default Exp/Contr=0.3,0.1
English Units
Geom File=g01
Flow File=f01
Plan File=p01
Y Axis Title=Elevation
X Axis Title(PF)=Main Channel Distance
X Axis Title(XS)=Station
BEGIN DESCRIPTION:
DELAWARE CREEK
END DESCRIPTION:
DSS Export Rating Curves= 0
DSS Export Rating Curve Sorted= 0
DSS Export Volume Flow Curves= 0
DXF OffsetX= 0
DXF OffsetY= 0
DXF ScaleX= 1
DXF ScaleY= 10

--- DELAWARE CREEK.p01 (plan) ---

Plan Title=Multiple Run
Short Identifier=Multiple
Geom File=g01
Flow File=f01
Subcritical Flow
K Sum by GR= 0
Std Step Tol= 0.01
Critical Tol= 0.01
Num of Std Step Trials= 20
Max Error Tol= 0.3
Flow Tol Ratio= 0.001
Split Flow NTrial= 30
Split Flow Tol= 0.02
Split Flow Ratio= 0.02
Log Output Level= 0
Friction Slope Method= 1
Unsteady Friction Slope Method= 2
Unsteady Bridges Friction Slope Method= 1
Parabolic Critical Depth
Global Vel Dist=  1 , 1 , 1
Global Log Level= 0
CheckData=True
Encroach Param= -1, 0, 0, 0
BEGIN DESCRIPTION:
Multiple Run
END DESCRIPTION:

--- DELAWARE CREEK.f01 (steady flow) ---

Flow Title=Multiple
Number of Profiles=7
Profile Names=10-year,25-year,50-year,1pct_min,100-year,1pct_plu,500-year
River Rch & RM= DELAWARE CREEK,Reach-1,17732
    1268    1858    2373    2211    2990    4044    4742
River Rch & RM= DELAWARE CREEK,Reach-1,16003
    1901    2839    3670    3455    4672    6319    7570
River Rch & RM= DELAWARE CREEK,Reach-1,8188
    2795    4254    5570    5303    7171    9698   11888
River Rch & RM= DELAWARE CREEK,Reach-1,5504
    2988    4549    5958    5669    7667   10369   12703
Boundary for River Rch & Prof#=DELAWARE CREEK,Reach-1,1
Up Type=0
Dn Type=3
Dn Slope=0.005
Boundary for River Rch & Prof#=DELAWARE CREEK,Reach-1,2
Up Type=0
Dn Type=3
Dn Slope=0.005
Boundary for River Rch & Prof#=DELAWARE CREEK,Reach-1,3
Up Type=0
Dn Type=3
Dn Slope=0.005
Boundary for River Rch & Prof#=DELAWARE CREEK,Reach-1,4
Up Type=0
Dn Type=3
Dn Slope=0.005
Boundary for River Rch & Prof#=DELAWARE CREEK,Reach-1,5
Up Type=0
Dn Type=3
Dn Slope=0.005
Boundary for River Rch & Prof#=DELAWARE CREEK,Reach-1,6
Up Type=0
Dn Type=3
Dn Slope=0.005
Boundary for River Rch & Prof#=DELAWARE CREEK,Reach-1,7
Up Type=0
Dn Type=3
Dn Slope=0.005

--- DELAWARE CREEK.g01 (geometry) ---

Geom Title=Existing Conditions
Program Version=4.10

River Reach=DELAWARE CREEK  ,Reach-1
Reach XY= 30
      2705928.09     10035213.36      2706382.86     10035191.69
      2707084.23     10034895.52      2707648.28     10034903.74
      2709203.16     10035454.64      2709427.71     10035431.45
      2710065.15     10034802.53      2710333.56     10033901.33
      2710606.32     10033757.78      2710564.03     10033318.52
       2711407.5     10033289.16      2711808.23     10032983.76
      2711813.44     10032771.12      2711599.88     10032569.66
      2711794.59     10032142.33      2711962.39     10032156.15
      2712018.47     10031863.73      2712471.55     10031698.78
      2712555.28     10031489.17      2713313.09     10031503.68
      2713684.13     10031214.52      2714344.54     10031481.22
      2715169.86     10032470.53      2715375.03     10032417.84
      2715644.03     10032035.22      2716244.75     10032201.47
      2716660.89     10033072.76      2717056.61      10033484.5
      2717060.14     10033840.28      2717788.47     10033663.73

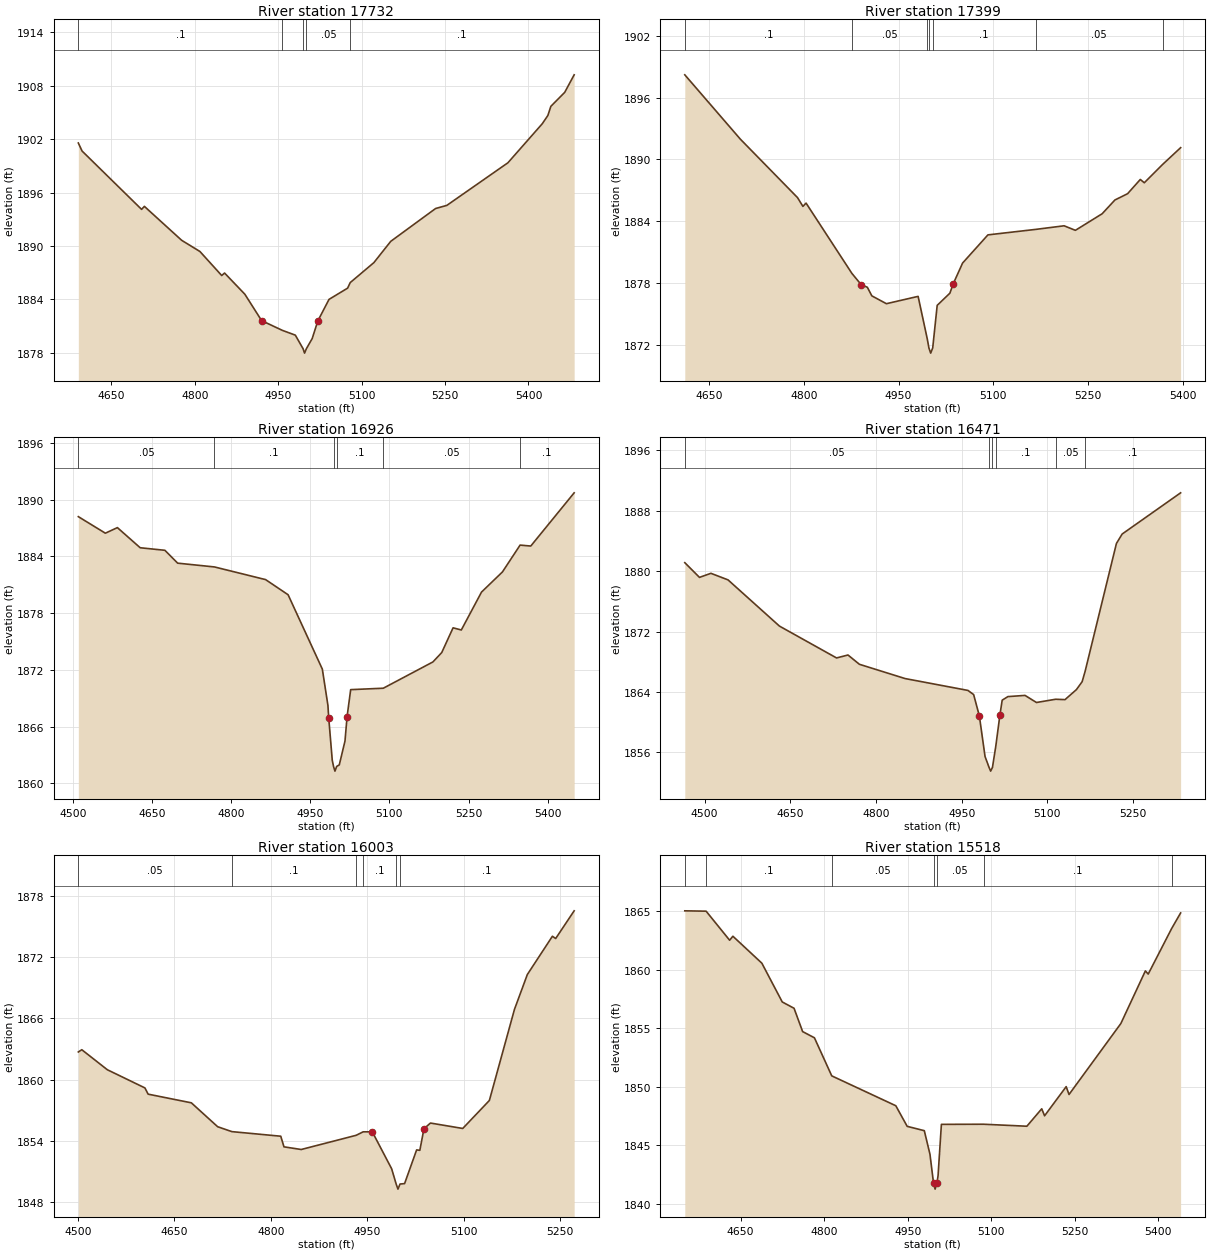
Type RM Length L Ch R = 1 ,17732   ,333,333,333
BEGIN DESCRIPTION:
DELAWARE CREEK 32.0
END DESCRIPTION:
XS GIS Cut Line= 2
      2706009.07      10035620.4      2705887.81     10034736.88
#Sta/Elev= 30
  4590.4 1901.57  4597.1 1900.67  4704.2 1894.11  4709.2 1894.45  4776.2 1890.64
  4809.1 1889.38  4848.3 1886.68  4853.4 1886.96  4889.9 1884.58  4920.1 1881.61
  4957.3 1880.52  4980.7 1879.98  4994.6 1878.46  4997.3 1877.96  5000.6 1878.46
    5011 1879.59  5021.1 1881.57  5041.3    1884  5074.7 1885.26  5079.5 1885.89
    5122 1888.13  5152.3 1890.52    5233 1894.21  5253.2 1894.56  5363.1 1899.35
  5424.8 1903.73  5434.9 1904.66  5440.3 1905.69  5465.2 1907.26  5482.2 1909.23
#Mann= 5 ,-1 , 0
  4590.4      .1       0  4957.3     .05       0  4994.6     .04       0
  5000.6     .05       0  5079.5      .1       0
Bank Sta=4920.1,5021.1
XS Rating Curve= 0 ,0
Exp/Cntr=0.3,0.1

Type RM Length L Ch R = 1 ,17399   ,473,473,473
BEGIN DESCRIPTION:
DELAWARE CREEK 31.0
END DESCRIPTION:
XS GIS Cut Line= 2
      2706311.16     10035561.38      2706238.25     10034780.18
#Sta/Elev= 30
  4611.8  1898.2  4699.8 1891.96  4790.2  1886.3  4798.7 1885.45  4803.7 1885.77
  4876.2 1878.96  4890.7 1877.88  4900.7 1877.61  4907.8 1876.78  4930.8 1876.02
    4981 1876.73  4995.6 1872.58  4998.1 1871.73  5000.9 1871.23  5004.1 1871.73
  5011.2 1875.86  5031.3 1877.04 5036.36 1877.92  5051.4 1879.96  5091.5 1882.69
    5167 1883.22    5212 1883.57  5229.9 1883.13  5272.3 1884.74  5292.4 1886.07
  5312.5 1886.68  5332.6 1888.06  5338.9 1887.74    5368 1889.52  5396.4 1891.14
#Mann= 7 ,-1 , 0
  4611.8      .1       0  4876.2     .05       0  4995.6      .1       0
  4998.1     .07       0  5004.1      .1       0    5167     .05       0
    5368      .1       0
Bank Sta=4890.7,5036.36
XS Rating Curve= 0 ,0
Exp/Cntr=0.3,0.1

Type RM Length L Ch R = 1 ,16926   ,455,455,455
BEGIN DESCRIPTION:
DELAWARE CREEK 30.0
END DESCRIPTION:
XS GIS Cut Line= 2
       2706884.1     10035502.42      2706533.42     10034630.93
#Sta/Elev= 30
  4510.6 1888.21  4561.8 1886.46  4584.6 1887.05  4627.8 1884.92  4674.6 1884.65
  4698.8 1883.29  4768.5 1882.89  4865.4 1881.55    4908 1879.95  4972.9 1872.08
  4983.5 1868.24    4985 1866.92  4991.7 1862.44  4994.1 1861.79  4996.8 1861.29
  5000.1 1861.79    5005 1861.95  5015.8 1864.47 5019.77 1867.05  5026.6 1869.91
  5088.4 1870.06  5182.4 1872.84  5199.1 1873.83  5220.6 1876.45  5236.2 1876.22
  5274.5 1880.23  5314.1 1882.36  5347.6  1885.2  5367.8  1885.1    5450 1890.73
#Mann= 6 ,-1 , 0
  4510.6     .05       0  4768.5      .1       0  4994.1     .07       0
  5000.1      .1       0  5088.4     .05       0  5347.6      .1       0
Bank Sta=4985,5019.77
XS Rating Curve= 0 ,0
Exp/Cntr=0.3,0.1

Type RM Length L Ch R = 1 ,16471   ,468,468,468
BEGIN DESCRIPTION:
DELAWARE CREEK 29.0
END DESCRIPTION:
XS GIS Cut Line= 2
      2707130.61     10035429.44      2707123.66     10034561.36
#Sta/Elev= 30
  4465.3 1881.13    4491 1879.18    4511 1879.72    4541 1878.85    4631 1872.73
    4731 1868.51    4751  1868.9    4771 1867.67    4851 1865.78    4961 1864.21
    4971 1863.66    4981 1860.84    4991 1855.45    4998 1854.02  5000.8 1853.52
    5004 1854.02  5009.9 1856.88 5017.05 1860.98    5021 1862.92    5031 1863.39
    5061 1863.55    5081 1862.61  5114.6 1863.04    5131 1862.99    5151 1864.32
    5161 1865.37  5166.2 1866.74    5221 1883.67    5231 1884.92  5333.4 1890.38
#Mann= 6 ,-1 , 0
  4465.3     .05       0    4998    .035       0    5004     .05       0
  5009.9      .1       0  5114.6     .05       0  5166.2      .1       0
Bank Sta=4981,5017.05
XS Rating Curve= 0 ,0
Exp/Cntr=0.3,0.1

Type RM Length L Ch R = 1 ,16003   ,485,485,485
BEGIN DESCRIPTION:
DELAWARE CREEK 28.0
END DESCRIPTION:
XS GIS Cut Line= 2
      2707533.38     10035408.65       2707606.3      10034641.3
#Sta/Elev= 30
  4500.8  1862.7  4506.2 1862.92  4545.9 1860.96  4604.3 1859.18  4609.3 1858.57
  4676.5 1857.72  4717.4 1855.38  4739.5  1854.9  4815.5 1854.45  4820.5 1853.41
  4847.3 1853.15  4932.7 1854.54  4943.6 1854.88  4957.8 1854.88  4987.9 1851.26
  4994.9 1849.77  4997.7 1849.27  5000.9 1849.77    5008 1849.81  5026.7 1853.11
  5031.7 1853.07  5038.1 1855.18  5048.2 1855.74  5098.4 1855.21  5139.8 1857.95
  5178.8 1866.87  5198.8 1870.28  5237.8 1874.03  5242.9 1873.81  5271.6 1876.52
#Mann= 6 ,-1 , 0
  4500.8     .05       0  4739.5      .1       0  4932.7     .05       0
  4943.6      .1       0  4994.9     .07       0  5000.9      .1       0
Bank Sta=4957.8,5038.1
XS Rating Curve= 0 ,0
Exp/Cntr=0.3,0.1

Type RM Length L Ch R = 1 ,15518   ,431,431,431
BEGIN DESCRIPTION:
DELAWARE CREEK 27.0
END DESCRIPTION:
XS GIS Cut Line= 3
      2707800.74     10035446.83      2707995.19     10035134.32
      2708106.29     10034623.94
#Sta/Elev= 30
  4549.8 1865.02  4588.1 1864.99  4630.3 1862.51  4636.2 1862.85  4688.2 1860.55
  4724.8 1857.24    4746  1856.7  4761.4 1854.71  4782.6 1854.18  4813.7 1850.93
  4928.7 1848.38  4949.2 1846.62  4979.9 1846.25  4990.1 1844.23  4996.5 1841.76
  4999.3 1841.26  5002.5 1841.76  5004.6  1842.4  5010.6 1846.79  5086.5  1846.8
  5164.1 1846.63  5190.8 1848.12  5195.9 1847.52  5234.7 1850.01  5239.8 1849.34
  5332.9  1855.4  5376.9 1859.89    5382 1859.62  5424.1 1863.51  5440.2 1864.84
#Mann= 7 ,-1 , 0
  4549.8     .05       0  4588.1      .1       0  4813.7     .05       0
  4996.5    .035       0  5002.5     .05       0  5086.5      .1       0
  5424.1     .16       0
Bank Sta=4996.5,5002.5
XS Rating Curve= 0 ,0
Exp/Cntr=0.3,0.1

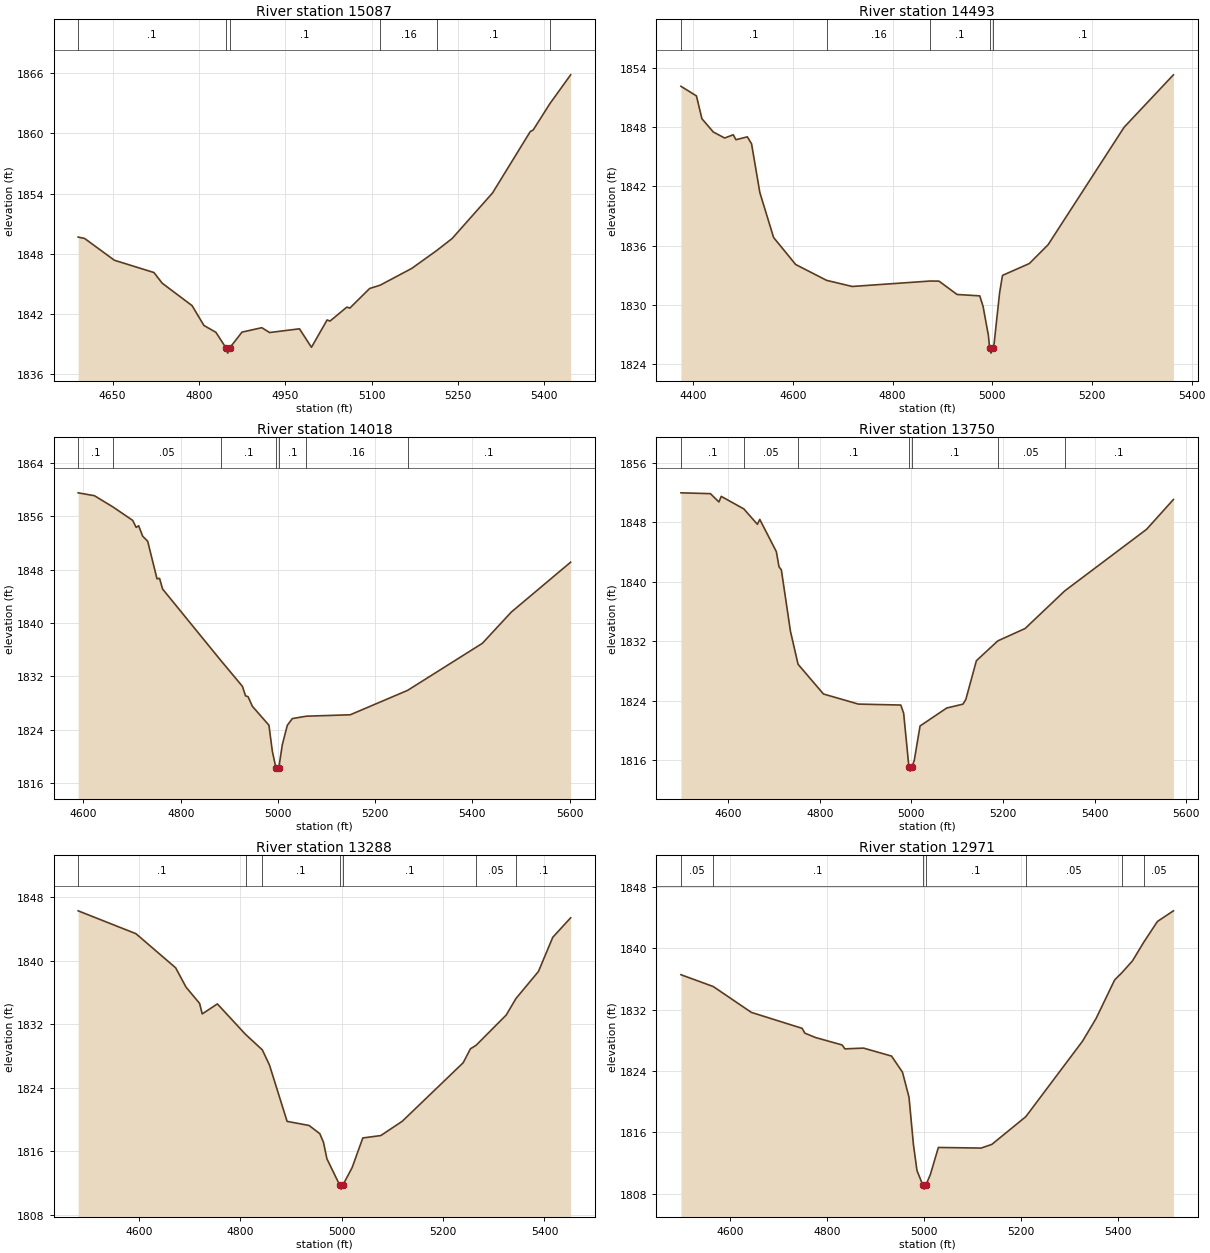
Type RM Length L Ch R = 1 ,15087   ,594,594,594
BEGIN DESCRIPTION:
DELAWARE CREEK 26.0
END DESCRIPTION:
XS GIS Cut Line= 3
       2708318.1      10035554.5        2708457.     10035050.99
       2708477.8     10034718.15
#Sta/Elev= 30
  4590.1 1849.67  4601.3 1849.53  4653.1 1847.36  4721.8 1846.14  4736.1 1845.08
    4788 1842.85  4808.7 1840.87  4829.5 1840.19  4847.2 1838.62    4850 1838.12
  4853.2 1838.62  4874.8 1840.21  4909.2 1840.65  4922.8 1840.17  4974.7 1840.54
  4995.5  1838.7  5022.7 1841.42  5027.8 1841.31    5057  1842.7  5062.2  1842.6
  5096.6 1844.55  5114.9 1844.88  5169.8 1846.55  5213.2 1848.33  5239.9 1849.52
  5310.1 1854.05  5375.8 1860.17  5380.8 1860.32  5409.8 1862.94  5445.9 1865.81
#Mann= 6 ,-1 , 0
  4590.1      .1       0  4847.2     .07       0  4853.2      .1       0
  5114.9     .16       0  5213.2      .1       0  5409.8     .05       0
Bank Sta=4847.2,4853.2
XS Rating Curve= 0 ,0
Exp/Cntr=0.3,0.1

Type RM Length L Ch R = 1 ,14493   ,475,475,475
BEGIN DESCRIPTION:
DELAWARE CREEK 25.0
END DESCRIPTION:
XS GIS Cut Line= 3
      2708727.82     10035821.84      2709026.44     10035189.88
      2708946.58     10034912.09
#Sta/Elev= 30
  4375.4  1852.1  4406.5 1851.13  4417.5 1848.82  4440.3 1847.48  4463.1 1846.87
  4480.3  1847.2  4485.8  1846.7  4508.6 1846.99  4517.1 1846.28  4533.7 1841.36
  4561.3 1836.81  4605.6 1834.08  4667.6 1832.48    4719 1831.86  4875.5 1832.41
  4893.1  1832.4  4929.4 1831.05  4974.9 1830.91  4981.6 1829.83  4992.2 1826.92
  4994.7 1825.62  4997.4 1825.12  5000.7 1825.62  5003.7 1826.09  5014.8 1831.26
  5020.5 1832.98  5074.4 1834.18    5112 1836.08  5264.5 1847.96  5363.4 1853.26
#Mann= 5 ,-1 , 0
  4375.4      .1       0  4667.6     .16       0  4875.5      .1       0
  4994.7     .07       0  5000.7      .1       0
Bank Sta=4994.7,5000.7
XS Rating Curve= 0 ,0
Exp/Cntr=0.3,0.1

Type RM Length L Ch R = 1 ,14018   ,268,268,268
BEGIN DESCRIPTION:
DELAWARE CREEK 24.0
END DESCRIPTION:
XS GIS Cut Line= 3
      2709460.48     10035853.11      2709349.36     10035366.96
      2709057.69     10034943.35
#Sta/Elev= 30
  4589.1 1859.51  4622.5 1859.08  4660.6  1857.4  4701.3 1855.38  4708.4 1854.33
  4713.5 1854.58  4721.8 1853.01  4732.1 1852.26  4751.3 1846.63  4756.5  1846.7
  4762.8  1845.1  4882.4 1834.41    4927 1830.52  4933.4 1829.09  4938.5 1828.98
  4947.5 1827.53  4981.5  1824.7  4988.5 1820.81  4995.8 1818.32  4998.5 1817.82
  5001.8 1818.32    5009 1821.77  5019.3 1824.68  5029.6 1825.69  5058.6 1826.05
  5148.7 1826.26  5266.8 1829.92  5420.6 1836.97  5480.1 1841.65  5602.1 1849.12
#Mann= 7 ,-1 , 0
  4589.1      .1       0  4660.6     .05       0  4882.4      .1       0
  4995.8     .07       0  5001.8      .1       0  5058.6     .16       0
  5266.8      .1       0
Bank Sta=4995.8,5001.8
XS Rating Curve= 0 ,0
Exp/Cntr=0.3,0.1

Type RM Length L Ch R = 1 ,13750   ,462,462,462
BEGIN DESCRIPTION:
DELAWARE CREEK 23.0
END DESCRIPTION:
XS GIS Cut Line= 3
      2709703.52     10035766.27      2709602.83     10035346.13
      2709220.89     10034828.78
#Sta/Elev= 30
    4497 1851.99  4561.3 1851.88  4579.9 1850.76    4585 1851.51  4634.4 1849.82
  4663.9 1847.75  4669.1 1848.41  4705.3 1844.07  4711.1 1842.03  4716.2 1841.62
  4736.1 1833.34  4752.7  1828.9  4808.1  1824.9  4884.3 1823.54    4977 1823.41
  4983.2  1822.3  4994.8 1815.01  4997.6 1814.51  5000.8 1815.01  5006.3 1815.93
    5019 1820.59  5077.2 1823.01  5112.7 1823.53  5118.9 1824.16    5142 1829.38
  5188.7 1832.05  5248.4 1833.72  5334.8 1838.78  5513.6 1847.08  5572.1 1851.09
#Mann= 7 ,-1 , 0
    4497      .1       0  4634.4     .05       0  4752.7      .1       0
  4994.8     .07       0  5000.8      .1       0  5188.7     .05       0
  5334.8      .1       0
Bank Sta=4994.8,5000.8
XS Rating Curve= 0 ,0
Exp/Cntr=0.3,0.1

Type RM Length L Ch R = 1 ,13288   ,317,317,317
BEGIN DESCRIPTION:
DELAWARE CREEK 22.0
END DESCRIPTION:
XS GIS Cut Line= 3
      2710029.92     10035460.72      2709932.69     10035057.93
      2709547.29     10034655.18
#Sta/Elev= 30
  4479.9 1846.32  4593.9 1843.44  4672.3 1839.14  4692.8  1836.7  4719.5 1834.66
  4724.7 1833.33  4754.6 1834.59  4810.2 1830.75  4843.3  1828.8  4857.4 1826.89
  4892.2 1819.79  4935.6 1819.27  4956.7 1818.24  4963.9 1817.17  4970.8 1815.07
  4996.1 1811.75  4998.9 1811.25  5002.1 1811.75  5020.5 1813.96  5041.6  1817.7
  5077.1    1818  5119.6 1819.81  5239.7 1827.18  5253.9 1828.93  5265.2 1829.38
  5324.6 1833.19  5343.8 1835.27  5388.2 1838.68  5416.5 1842.99  5451.7 1845.44
#Mann= 7 ,-1 , 0
  4479.9      .1       0  4810.2     .16       0  4843.3      .1       0
  4996.1     .07       0  5002.1      .1       0  5265.2     .05       0
  5343.8      .1       0
Bank Sta=4996.1,5002.1
XS Rating Curve= 0 ,0
Exp/Cntr=0.3,0.1

Type RM Length L Ch R = 1 ,12971   ,429,429,429
BEGIN DESCRIPTION:
DELAWARE CREEK 21.0
END DESCRIPTION:
XS GIS Cut Line= 2
      2710522.96     10035005.85       2709623.7     10034533.65
#Sta/Elev= 30
  4498.2 1836.57  4564.8 1835.03  4643.5 1831.65  4748.1 1829.57  4753.8 1828.94
  4775.8 1828.37  4830.7  1827.4  4836.3 1826.89  4874.8 1826.99  4932.5 1825.95
  4955.1 1823.85  4968.6 1820.58  4977.7  1814.4    4985 1811.01  4997.2 1809.08
    5000 1808.58  5003.2 1809.08  5012.7  1810.5  5029.1 1814.02  5117.3 1813.94
  5139.4 1814.42  5209.5 1818.04  5326.5  1827.9  5354.2 1830.83  5392.7 1835.89
  5407.3 1836.81  5429.4 1838.37  5452.7 1840.81  5480.9 1843.52  5513.9 1844.91
#Mann= 7 ,-1 , 0
  4498.2     .05       0  4564.8      .1       0  4997.2     .07       0
  5003.2      .1       0  5209.5     .05       0  5407.3      .1       0
  5452.7     .05       0
Bank Sta=4997.2,5003.2
XS Rating Curve= 0 ,0
Exp/Cntr=0.3,0.1

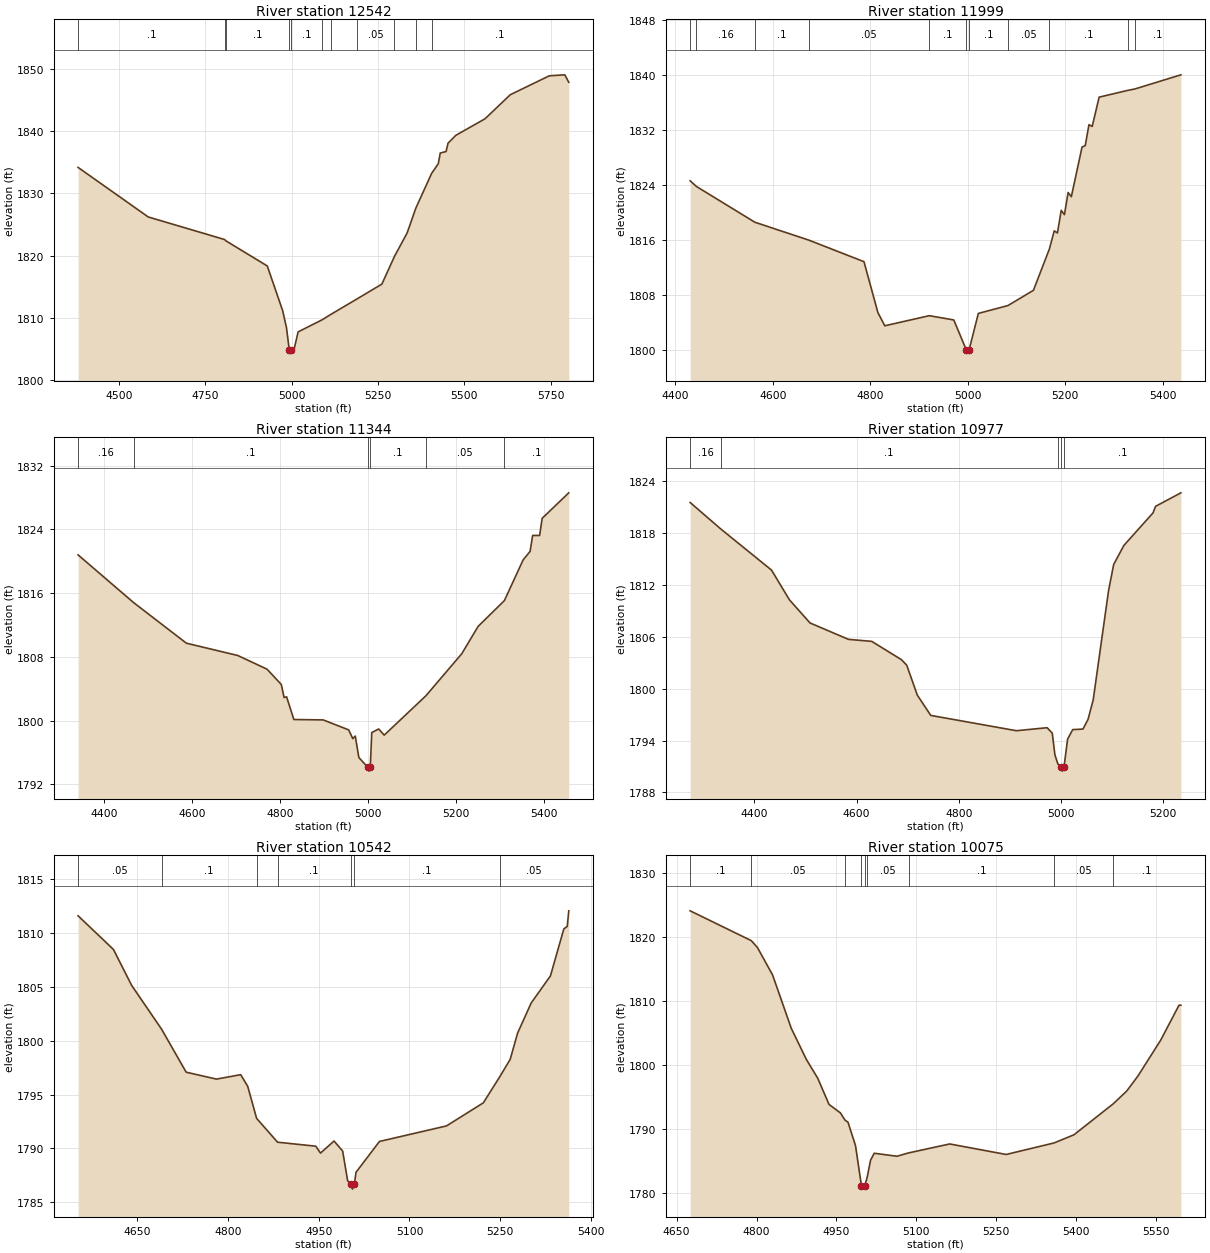
Type RM Length L Ch R = 1 ,12542   ,543,543,543
BEGIN DESCRIPTION:
DELAWARE CREEK 20.0
END DESCRIPTION:
XS GIS Cut Line= 2
      2710811.16     10034655.16       2709533.4     10034033.64
#Sta/Elev= 30
  4381.4 1834.17  4584.6 1826.22  4805.7  1822.6    4809 1822.41  4929.3 1818.36
  4973.8  1811.2  4984.9 1808.46    4993 1804.88  4995.8 1804.38    4999 1804.88
  5007.1 1805.04  5018.6 1807.79    5087 1809.69  5112.4 1810.56  5190.2 1813.11
  5261.1 1815.45  5297.6  1819.9  5334.3 1823.66  5359.4 1827.63    5405 1833.19
  5424.5 1834.77  5430.1 1836.47  5447.1 1836.72  5452.6 1838.05  5475.2 1839.31
  5559.8 1841.97    5633 1845.83  5745.8 1848.86  5790.9 1849.02  5802.3 1847.83
#Mann= 11 ,-1 , 0
  4381.4      .1       0  4805.7     .05       0    4809      .1       0
    4993     .07       0    4999      .1       0    5087     .05       0
  5112.4      .1       0  5190.2     .05       0  5297.6      .1       0
  5359.4     .05       0    5405      .1       0
Bank Sta=4993,4999
XS Rating Curve= 0 ,0
Exp/Cntr=0.3,0.1

Type RM Length L Ch R = 1 ,11999   ,655,655,655
BEGIN DESCRIPTION:
DELAWARE CREEK 19.0
END DESCRIPTION:
XS GIS Cut Line= 2
      2710786.84     10034248.89      2710026.43     10033589.17
#Sta/Elev= 30
  4430.6 1824.62  4443.4  1823.8  4563.4 1818.59  4673.6    1816  4787.2 1812.85
  4815.7 1805.44  4829.9 1803.52  4921.1 1804.99  4971.4 1804.37  4996.9 1800.04
  4999.6 1799.54  5002.9 1800.04  5021.8 1805.32  5082.4 1806.46  5134.8 1808.68
  5167.6 1814.71  5177.5 1817.34  5184.1 1817.03  5191.8 1820.32  5198.4  1819.7
    5206 1822.92  5212.6 1822.31  5234.5 1829.53  5241.1 1829.74  5248.7 1832.79
  5255.4 1832.54  5269.6  1836.8  5327.9 1837.78  5343.4    1838  5437.3 1840.05
#Mann= 11 ,-1 , 0
  4430.6      .1       0  4443.4     .16       0  4563.4      .1       0
  4673.6     .05       0  4921.1      .1       0  4996.9     .07       0
  5002.9      .1       0  5082.4     .05       0  5167.6      .1       0
  5327.9     .05       0  5343.4      .1       0
Bank Sta=4996.9,5002.9
XS Rating Curve= 0 ,0
Exp/Cntr=0.3,0.1

Type RM Length L Ch R = 1 ,11344   ,367,367,367
BEGIN DESCRIPTION:
DELAWARE CREEK 18.0
END DESCRIPTION:
XS GIS Cut Line= 3
      2710887.57     10033964.22      2710627.13     10033457.24
      2710154.94     10033186.42
#Sta/Elev= 30
  4341.2  1820.8  4467.1 1814.82  4587.2 1809.71  4703.7 1808.17  4770.3 1806.45
  4802.7 1804.53    4809 1802.89  4814.7 1802.98  4831.2 1800.13  4897.8 1800.08
  4955.7 1798.83    4965 1797.73  4970.7 1798.05  4978.8 1795.36  4998.8 1794.15
  5001.6 1793.65  5004.8 1794.15  5008.1 1798.49  5023.9 1798.94  5036.4 1798.17
  5130.9  1803.1  5212.4 1808.38  5249.8 1811.83  5309.3 1815.06  5351.9 1820.17
  5367.7 1821.24  5373.5 1823.24  5389.3 1823.24  5395.1 1825.39  5455.5 1828.59
#Mann= 6 ,-1 , 0
  4341.2     .16       0  4467.1      .1       0  4998.8     .07       0
  5004.8      .1       0  5130.9     .05       0  5309.3      .1       0
Bank Sta=4998.8,5004.8
XS Rating Curve= 0 ,0
Exp/Cntr=0.3,0.1

Type RM Length L Ch R = 1 ,10977   ,435,435,435
BEGIN DESCRIPTION:
DELAWARE CREEK 17.0
END DESCRIPTION:
XS GIS Cut Line= 3
      2710963.95     10033943.37      2710821.58     10033405.16
      2710800.75     10033002.42
#Sta/Elev= 30
  4274.4 1821.52  4333.9 1818.48  4433.5 1813.71  4468.6 1810.27  4508.8  1807.6
  4584.1  1805.7  4629.6 1805.47  4687.8 1803.35  4698.1 1802.71  4718.8 1799.25
  4745.1 1796.91  4912.7 1795.14  4972.7 1795.49  4982.8 1794.86    4988 1792.34
  4993.8  1791.3  4999.8 1790.97  5002.5 1790.47  5005.8 1790.97  5012.8 1794.17
  5022.8 1795.27  5042.8 1795.33  5052.8 1796.45  5062.9 1798.72  5092.9 1811.33
  5102.9 1814.35  5122.9 1816.56  5179.9 1820.32  5184.9 1821.08  5234.4 1822.64
#Mann= 5 ,-1 , 0
  4274.4     .16       0  4333.9      .1       0  4993.8     .05       0
  4999.8    .035       0  5005.8      .1       0
Bank Sta=4999.8,5005.8
XS Rating Curve= 0 ,0
Exp/Cntr=0.3,0.1

Type RM Length L Ch R = 1 ,10542   ,467,467,467
BEGIN DESCRIPTION:
DELAWARE CREEK 16.0
END DESCRIPTION:
XS GIS Cut Line= 3
      2711283.38     10033662.06      2711255.61     10033276.68
      2711061.29     10032898.45
#Sta/Elev= 30
  4551.9 1811.57  4610.4 1808.45  4640.5 1805.12    4690 1801.06  4730.7 1797.07
  4780.8 1796.43  4820.9 1796.84  4832.5 1795.76  4847.2 1792.79  4881.9 1790.58
  4945.1 1790.21  4952.8 1789.57  4975.3 1790.69  4989.5 1789.76  4997.8    1787
    5003 1786.73  5005.8 1786.23    5009 1786.73  5011.6 1787.79  5050.4 1790.65
  5161.3 1792.09  5222.2 1794.23  5249.4 1796.65  5266.6 1798.26  5278.9  1800.7
  5301.4 1803.49  5333.2    1806  5355.3 1810.35    5361 1810.59  5363.5 1812.03
#Mann= 7 ,-1 , 0
  4551.9     .05       0    4690      .1       0  4847.2     .05       0
  4881.9      .1       0    5003     .07       0    5009      .1       0
  5249.4     .05       0
Bank Sta=5003,5009
XS Rating Curve= 0 ,0
Exp/Cntr=0.3,0.1

Type RM Length L Ch R = 1 ,10075   ,499,499,499
BEGIN DESCRIPTION:
DELAWARE CREEK 15.0
END DESCRIPTION:
XS GIS Cut Line= 2
      2711825.06     10033335.72      2711158.38     10032700.29
#Sta/Elev= 30
  4675.4  1824.1  4790.2 1819.44  4801.7 1818.37    4830  1814.1  4865.2 1805.75
  4893.5  1800.9  4914.9 1797.96    4936 1793.88  4957.4 1792.56  4965.9 1791.44
  4971.6 1791.11  4985.7 1787.46  4996.9 1781.16  4999.6 1780.66  5002.9 1781.16
  5007.4 1782.43    5014 1785.19  5020.9 1786.26  5063.4 1785.79  5085.2 1786.31
  5162.5 1787.71  5268.5 1786.07  5358.5 1787.87  5395.9 1789.15  5469.6 1793.99
  5494.9 1795.98    5516 1798.34  5558.5 1803.91  5592.9 1809.37  5596.4 1809.37
#Mann= 9 ,-1 , 0
  4675.4      .1       0  4790.2     .05       0  4965.9      .1       0
  4996.9     .07       0  5002.9      .1       0  5007.4     .05       0
  5085.2      .1       0  5358.5     .05       0  5469.6      .1       0
Bank Sta=4996.9,5002.9
XS Rating Curve= 0 ,0
Exp/Cntr=0.3,0.1

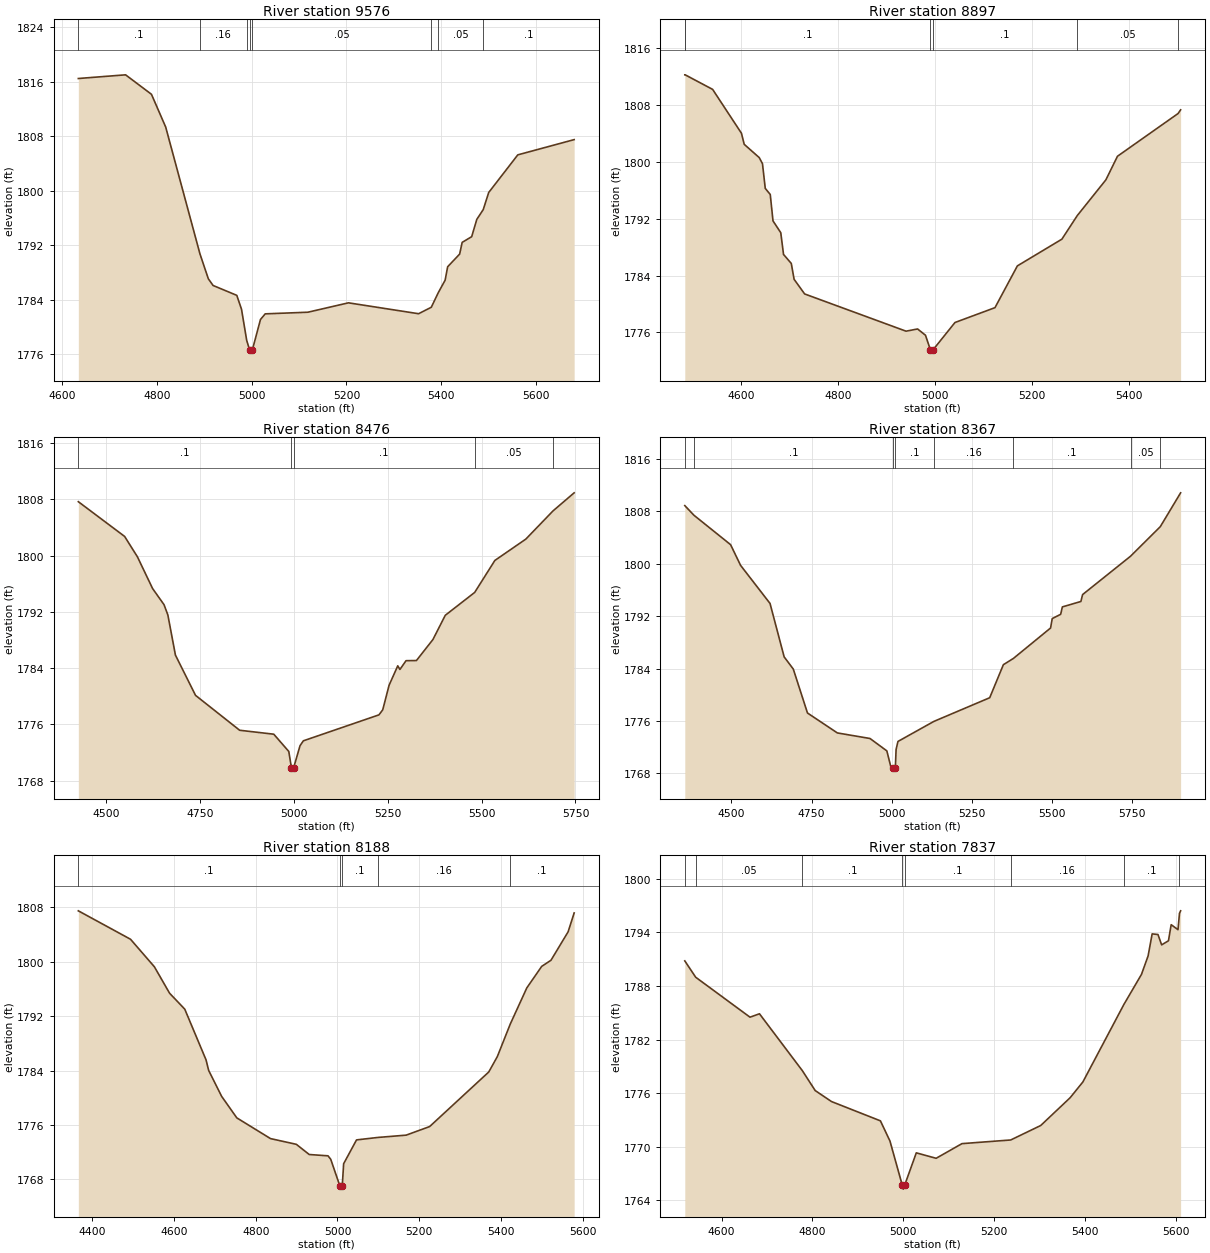
Type RM Length L Ch R = 1 ,9576    ,679,679,679
BEGIN DESCRIPTION:
DELAWARE CREEK 14.0
END DESCRIPTION:
XS GIS Cut Line= 3
      2712182.71     10032790.57      2711616.72     10032780.16
       2711165.3     10032616.95
#Sta/Elev= 30
  4634.3  1816.5    4734 1817.04  4788.6 1814.18  4818.6 1809.37    4891 1790.71
  4908.6 1787.07  4918.6 1786.09  4968.6 1784.64  4978.6  1782.6  4989.6    1778
  4995.6 1776.65  4998.4 1776.15  5001.6 1776.65  5018.6 1781.09  5028.6 1781.92
  5118.6 1782.16  5204.2 1783.54  5352.2 1781.94    5379 1782.89  5393.7 1785.03
  5408.2 1786.87  5413.5 1788.84  5438.8  1790.7  5444.1 1792.42  5464.2 1793.26
    5475  1795.8  5488.6 1797.24  5500.1 1799.75  5561.5 1805.28  5680.4 1807.52
#Mann= 8 ,-1 , 0
  4634.3      .1       0    4891     .16       0  4989.6     .05       0
  4995.6    .035       0  5001.6     .05       0    5379      .1       0
  5393.7     .05       0  5488.6      .1       0
Bank Sta=4995.6,5001.6
XS Rating Curve= 0 ,0
Exp/Cntr=0.3,0.1

Type RM Length L Ch R = 1 ,8897    ,421,421,421
BEGIN DESCRIPTION:
DELAWARE CREEK 13.0
END DESCRIPTION:
XS GIS Cut Line= 4
      2712081.99     10032637.79      2711897.97     10032307.93
      2711613.25     10032189.88      2711302.06     10032317.81
#Sta/Elev= 30
  4483.3 1812.25  4484.1 1812.25  4540.7  1810.2  4600.1 1804.03  4605.8 1802.47
  4636.8  1800.6  4643.5 1799.74  4649.2 1796.27  4659.5 1795.41  4665.2 1791.69
  4681.2 1790.03  4686.9 1786.97  4702.9  1785.7  4708.7 1783.47  4730.4 1781.41
  4939.5 1776.17  4963.3 1776.48  4979.6  1775.6  4989.6 1773.58  4992.4 1773.08
  4995.6 1773.58  5040.4 1777.39  5122.9 1779.48  5169.1 1785.36  5260.9 1789.12
  5292.5 1792.43  5351.6 1797.47  5375.5 1800.79  5500.4  1806.8  5505.7 1807.32
#Mann= 6 ,-1 , 0
  4483.3     .16       0  4484.1      .1       0  4989.6     .07       0
  4995.6      .1       0  5292.5     .05       0  5500.4      .1       0
Bank Sta=4989.6,4995.6
XS Rating Curve= 0 ,0
Exp/Cntr=0.3,0.1

Type RM Length L Ch R = 1 ,8476    ,288,288,288
BEGIN DESCRIPTION:
DELAWARE CREEK 12.0
END DESCRIPTION:
XS GIS Cut Line= 4
      2712123.67     10032498.95      2712047.27     10032033.63
      2711689.63     10032047.52      2711255.58      10032276.7
#Sta/Elev= 30
  4426.2 1807.66  4549.5 1802.72  4583.5 1799.83    4624 1795.31  4654.4 1793.02
  4664.6 1791.56  4684.8 1785.85  4738.3 1780.13  4855.8 1775.17  4946.6 1774.61
  4986.6 1772.16  4993.6 1769.86  4996.4 1769.36  4999.6 1769.86  5016.6 1772.98
  5025.5 1773.67  5226.8 1777.36  5236.8 1778.08  5253.7 1781.57  5276.8 1784.33
  5282.5 1783.81  5298.8 1785.06  5326.5 1785.08  5370.5 1788.07  5403.3 1791.51
  5481.6 1794.76  5535.4 1799.31  5617.8 1802.34  5690.4 1806.36  5746.5 1808.92
#Mann= 5 ,-1 , 0
  4426.2      .1       0  4993.6     .07       0  4999.6      .1       0
  5481.6     .05       0  5690.4      .1       0
Bank Sta=4993.6,4999.6
XS Rating Curve= 0 ,0
Exp/Cntr=0.3,0.1

Type RM Length L Ch R = 1 ,8367    ,179,179,179
BEGIN DESCRIPTION:
Mapping XS 86d39bc0
END DESCRIPTION:
XS GIS Cut Line= 4
      2712217.71     10032480.99      2712075.47     10031985.43
      2711899.12     10031909.35      2711104.01     10032176.13
#Sta/Elev= 30
  4354.7 1808.88  4383.2 1807.41  4497.5 1802.92  4528.7 1799.76  4620.5 1793.95
  4664.6 1785.79  4693.1 1783.93  4737.3 1777.23  4830.4 1774.19  4932.3 1773.34
  4984.8 1771.45  4997.7 1768.94  5005.3 1768.86    5008 1768.36  5011.3 1768.86
  5013.7 1771.68  5019.5 1772.89  5131.6 1775.95  5305.6 1779.56  5348.2  1784.6
  5379.3 1785.55  5495.4  1790.2  5500.6 1791.64  5526.9 1792.29  5532.2 1793.42
    5590 1794.25  5595.3  1795.3  5744.9 1801.16  5837.5 1805.66    5901 1810.83
#Mann= 8 ,-1 , 0
  4354.7     .16       0  4383.2      .1       0  5005.3     .07       0
  5011.3      .1       0  5131.6     .16       0  5379.3      .1       0
  5744.9     .05       0  5837.5      .1       0
Bank Sta=5005.3,5011.3
XS Rating Curve= 0 ,0
Exp/Cntr=0.3,0.1

Type RM Length L Ch R = 1 ,8188    ,351,351,351
BEGIN DESCRIPTION:
DELAWARE CREEK 11.0
END DESCRIPTION:
XS GIS Cut Line= 3
      2712292.93     10032430.75      2711990.85     10031507.15
      2711853.76     10031308.38
#Sta/Elev= 30
    4366  1807.5  4493.7 1803.32  4552.1 1799.27  4589.3 1795.38  4626.4 1793.04
  4678.5 1785.58  4684.9 1784.03  4716.7 1780.21  4753.8 1777.05  4836.3    1774
  4899.4 1773.16    4931 1771.66  4976.9 1771.47  4983.6 1770.96  5005.8 1767.07
  5008.5 1766.57  5011.8 1767.07  5015.2 1770.31  5046.7 1773.81  5098.9 1774.17
  5168.1 1774.51  5225.6 1775.77  5370.3  1783.8  5391.3 1786.07  5422.9 1790.85
  5463.4 1796.17  5499.8 1799.33  5522.5 1800.23  5564.4 1804.41  5579.2 1807.19
#Mann= 5 ,-1 , 0
    4366      .1       0  5005.8     .07       0  5011.8      .1       0
  5098.9     .16       0  5422.9      .1       0
Bank Sta=5005.8,5011.8
XS Rating Curve= 0 ,0
Exp/Cntr=0.3,0.1

Type RM Length L Ch R = 1 ,7837    ,596,596,596
BEGIN DESCRIPTION:
DELAWARE CREEK 10.0
END DESCRIPTION:
XS GIS Cut Line= 2
      2712695.73     10032125.23      2712081.16     10031222.47
#Sta/Elev= 30
  4518.8  1790.8  4542.8 1788.97  4662.4  1784.5  4683.3 1784.88  4777.8 1778.51
    4806 1776.29  4841.9 1775.06  4949.7  1772.9  4970.7 1770.64  4997.5 1765.76
  5000.3 1765.26  5003.5 1765.76  5028.7 1769.32  5072.4 1768.71  5129.3 1770.35
  5236.7 1770.76  5302.8 1772.38  5367.4 1775.48  5395.6 1777.25  5485.9 1785.92
  5524.7 1789.29  5539.3 1791.36  5548.2 1793.82    5561 1793.75  5569.1 1792.59
  5584.1 1793.05  5590.1 1794.85  5605.1 1794.29  5608.4 1796.12  5610.9  1796.4
#Mann= 8 ,-1 , 0
  4518.8      .1       0  4542.8     .05       0  4777.8      .1       0
  4997.5     .07       0  5003.5      .1       0  5236.7     .16       0
  5485.9      .1       0  5608.4     .05       0
Bank Sta=4997.5,5003.5
XS Rating Curve= 0 ,0
Exp/Cntr=0.3,0.1

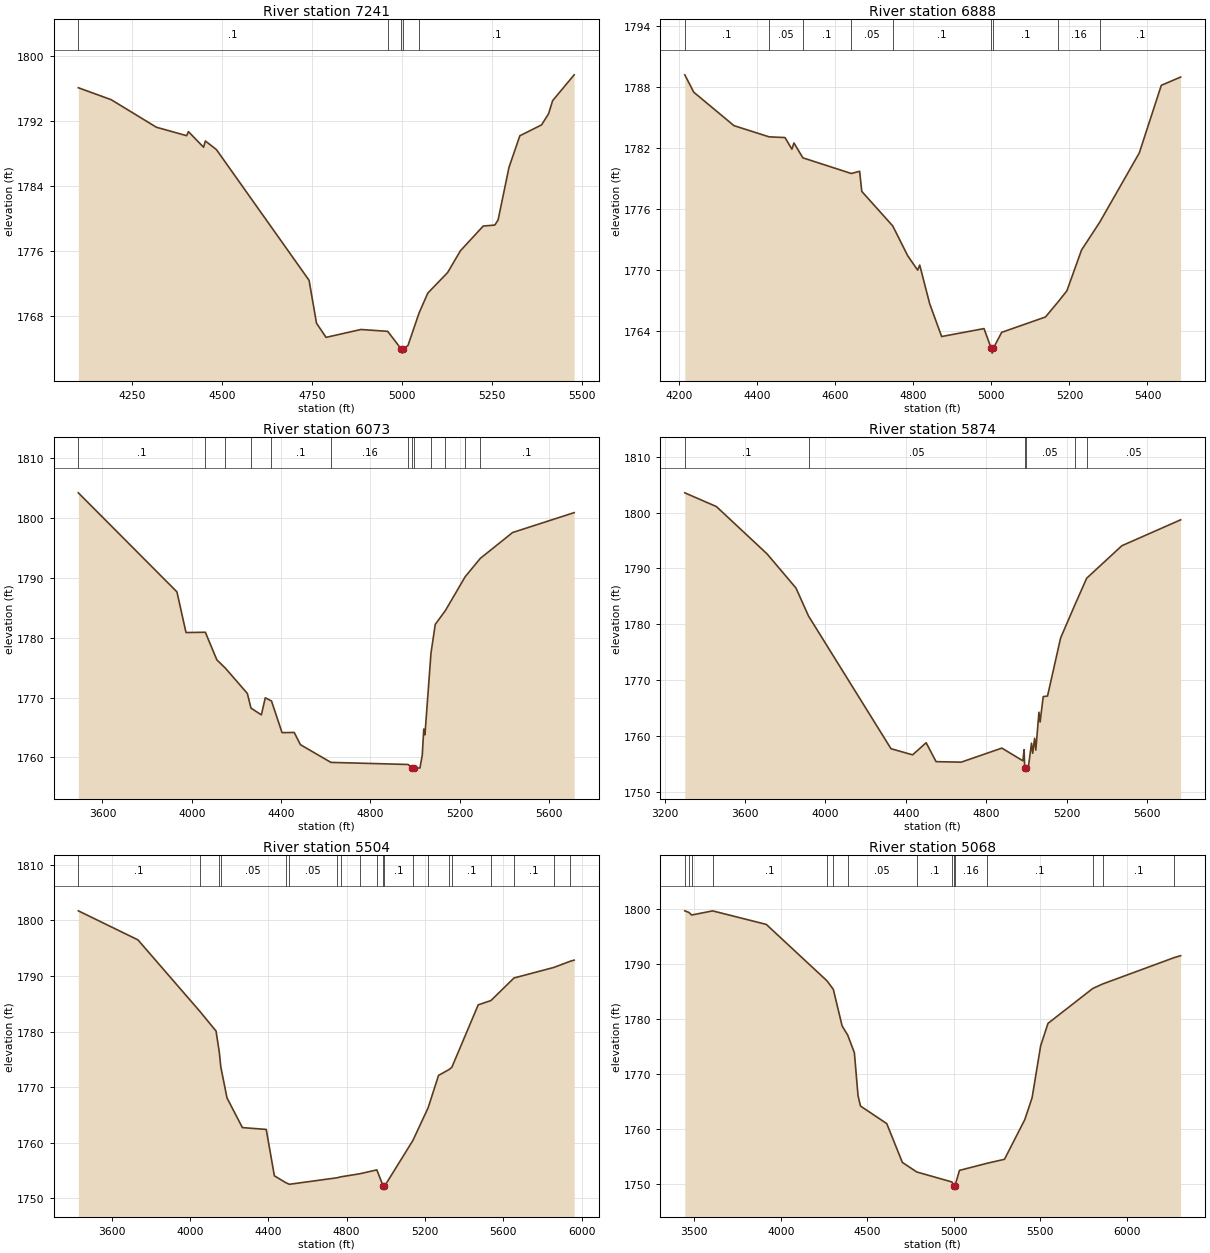
Type RM Length L Ch R = 1 ,7241    ,353,353,353
BEGIN DESCRIPTION:
DELAWARE CREEK 9.0
END DESCRIPTION:
XS GIS Cut Line= 3
      2713015.16     10032316.19      2712813.77     10031482.85
      2712630.13     10030997.78
#Sta/Elev= 30
  4101.7 1796.15  4192.9 1794.68  4318.4 1791.29  4402.2 1790.25  4407.3 1790.75
  4449.2 1788.83  4454.3  1789.6  4484.9 1788.54  4742.1 1772.45  4762.7 1767.17
  4789.2 1765.43  4886.1  1766.4  4960.3 1766.17  4997.9 1763.99  5000.6 1763.49
  5003.9 1763.99  5016.6 1764.44  5047.4 1768.44  5071.6 1770.88  5126.6 1773.41
  5162.1 1776.09  5225.4 1779.13  5257.5 1779.25  5266.7 1779.89  5296.9 1786.36
    5327 1790.24  5387.3 1791.58  5406.8 1792.96  5417.9 1794.56  5477.7 1797.74
#Mann= 5 ,-1 , 0
  4101.7      .1       0  4960.3     .16       0  4997.9     .07       0
  5003.9     .16       0  5047.4      .1       0
Bank Sta=4997.9,5003.9
XS Rating Curve= 0 ,0
Exp/Cntr=0.3,0.1

Type RM Length L Ch R = 1 ,6888    ,815,815,815
BEGIN DESCRIPTION:
DELAWARE CREEK 8.0
END DESCRIPTION:
XS GIS Cut Line= 3
      2713386.68     10032215.48      2713025.57     10031208.54
      2713035.95     10031007.94
#Sta/Elev= 30
  4214.3 1789.19  4237.4 1787.48  4340.3  1784.2  4430.3  1783.1  4471.1 1783.03
  4488.7 1781.89  4494.1  1782.5  4516.8 1781.04  4641.1  1779.5  4662.3 1779.72
  4667.9 1777.74  4747.2 1774.35  4785.6 1771.42    4811 1770.01  4816.3 1770.51
  4841.8 1766.72  4872.5 1763.49  4981.1 1764.27  4999.3 1762.36  5002.1 1761.86
  5005.3 1762.36  5026.3  1763.9  5138.6 1765.41  5171.9 1766.94  5193.5 1767.98
  5230.9 1771.98  5278.1 1774.75    5379 1781.52  5435.4 1788.16  5484.9 1788.97
#Mann= 9 ,-1 , 0
  4214.3      .1       0  4430.3     .05       0  4516.8      .1       0
  4641.1     .05       0  4747.2      .1       0  4999.3     .07       0
  5005.3      .1       0  5171.9     .16       0  5278.1      .1       0
Bank Sta=4999.3,5005.3
XS Rating Curve= 0 ,0
Exp/Cntr=0.3,0.1

Type RM Length L Ch R = 1 ,6073    ,199,199,199
BEGIN DESCRIPTION:
DELAWARE CREEK 7.0
END DESCRIPTION:
XS GIS Cut Line= 4
      2713652.14     10032663.59      2713902.14     10031899.69
      2713711.17     10031125.39      2713226.46     10030737.62
#Sta/Elev= 30
  3491.7  1804.2  3933.5 1787.66  3974.3 1780.86  4060.9 1780.91  4112.3 1776.31
  4150.7 1774.91  4249.1 1770.69  4265.5 1768.24  4311.9 1767.11  4329.5 1769.96
  4357.3 1769.43  4404.6 1764.14  4459.1 1764.17    4487 1762.13  4623.6 1759.17
  4969.6 1758.82  4988.7 1758.21  4991.4 1757.71  4994.7 1758.21  5022.6 1758.23
  5032.9 1760.34  5039.8 1764.74    5045 1763.77    5072  1777.4  5091.2 1782.22
  5136.8 1784.54  5225.4 1790.19  5293.1 1793.25  5437.8 1797.57  5713.7 1800.89
#Mann= 13 ,-1 , 0
  3491.7      .1       0  4060.9     .05       0  4150.7      .1       0
  4265.5     .05       0  4357.3      .1       0  4623.6     .16       0
  4969.6      .1       0  4988.7     .07       0  4994.7      .1       0
    5072     .16       0  5136.8      .1       0  5225.4     .05       0
  5293.1      .1       0
Bank Sta=4988.7,4994.7
XS Rating Curve= 0 ,0
Exp/Cntr=0.3,0.1

Type RM Length L Ch R = 1 ,5874    ,370,370,370
BEGIN DESCRIPTION:
DELAWARE CREEK 6.0
END DESCRIPTION:
XS GIS Cut Line= 4
      2713765.33     10032708.33      2714300.03     10031913.23
      2713834.75      10031142.4      2713386.82     10030732.66
#Sta/Elev= 30
  3300.9 1803.56    3458  1801.1  3709.9 1792.62  3853.9 1786.49  3916.1 1781.48
  4326.3 1757.69  4433.7 1756.59    4501 1758.76  4550.5 1755.37  4675.6 1755.28
  4877.5  1757.8  4982.3 1755.52  4988.1 1757.51  4991.3 1754.17  4994.1 1753.67
  4997.3 1754.17  5009.5 1754.43    5025 1758.68  5030.8 1756.87  5040.5 1759.55
  5046.4 1757.44  5061.9 1764.23  5067.7 1762.47  5083.2 1767.03  5104.6 1767.13
  5169.8 1777.55    5239 1783.33  5299.3 1788.25  5474.4 1794.08  5766.5 1798.72
#Mann= 6 ,-1 , 0
  3300.9      .1       0  3916.1     .05       0  4991.3     .04       0
  4997.3     .05       0    5239     .16       0  5299.3     .05       0
Bank Sta=4991.3,4997.3
XS Rating Curve= 0 ,0
Exp/Cntr=0.3,0.1

Type RM Length L Ch R = 1 ,5504    ,436,436,436
BEGIN DESCRIPTION:
Mapping XS 22f0c876
END DESCRIPTION:
XS GIS Cut Line= 4
      2713872.94     10032725.73      2714504.89     10031930.59
      2714029.19     10031100.73       2713682.7     10030660.68
#Sta/Elev= 30
  3429.8 1801.69  3734.3 1796.47    4052 1783.56  4133.2 1780.08  4150.1  1776.2
  4157.6  1773.6  4189.2 1768.06  4267.7 1762.73  4389.5  1762.4  4431.1 1754.06
  4489.3 1752.83  4507.7 1752.54  4751.3 1753.71    4770 1753.88  4867.5 1754.43
  4954.3 1755.13  4987.3 1752.17  4990.1 1751.67  4993.3 1752.17  5138.6 1760.42
  5216.4  1766.3  5269.4 1772.11    5323 1773.16  5337.3 1773.56  5472.1 1784.79
    5537 1785.56  5654.8 1789.62  5857.9 1791.51  5941.6 1792.62  5962.1 1792.83
#Mann= 20 ,-1 , 0
  3429.8      .1       0    4052     .05       0  4150.1      .1       0
  4157.6     .05       0  4489.3      .1       0  4507.7     .05       0
  4751.3      .1       0    4770     .05       0  4867.5     .16       0
  4954.3     .05       0  4987.3     .07       0  4993.3      .1       0
  5138.6     .05       0  5216.4      .1       0    5323     .05       0
  5337.3      .1       0    5537     .05       0  5654.8      .1       0
  5857.9     .05       0  5941.6      .1       0
Bank Sta=4987.3,4993.3
XS Rating Curve= 0 ,0
Exp/Cntr=0.3,0.1

Type RM Length L Ch R = 1 ,5068    ,455,455,455
BEGIN DESCRIPTION:
DELAWARE CREEK 5.0
END DESCRIPTION:
XS GIS Cut Line= 4
      2713766.75     10032937.86      2714558.39     10032163.58
      2714534.08     10031351.08      2713863.92     10030684.39
#Sta/Elev= 30
  3445.1 1799.72  3468.8 1799.43  3484.8 1798.96  3606.1 1799.71    3916 1797.25
  4267.1 1786.97  4303.5 1785.42  4354.4 1778.76  4386.7 1777.09  4425.2 1773.88
  4446.3 1766.06  4460.4 1764.18  4612.3 1760.98  4702.4 1753.92  4785.3 1752.18
  4989.4 1750.35  4999.5 1749.55  5002.2 1749.05  5005.5 1749.55  5032.5 1752.46
  5192.3 1753.76  5292.6 1754.48  5409.8 1761.69  5452.3  1765.7  5501.7 1775.15
  5544.2 1779.23  5802.8 1785.58  5860.5 1786.41  6273.2  1791.2  6310.6 1791.55
#Mann= 15 ,-1 , 0
  3445.1     .05       0  3468.8      .1       0  3484.8     .05       0
  3606.1      .1       0  4267.1     .05       0  4303.5      .1       0
  4386.7     .05       0  4785.3      .1       0  4989.4     .16       0
  4999.5     .07       0  5005.5     .16       0  5192.3      .1       0
  5802.8     .05       0  5860.5      .1       0  6273.2     .05       0
Bank Sta=4999.5,5005.5
XS Rating Curve= 0 ,0
Exp/Cntr=0.3,0.1