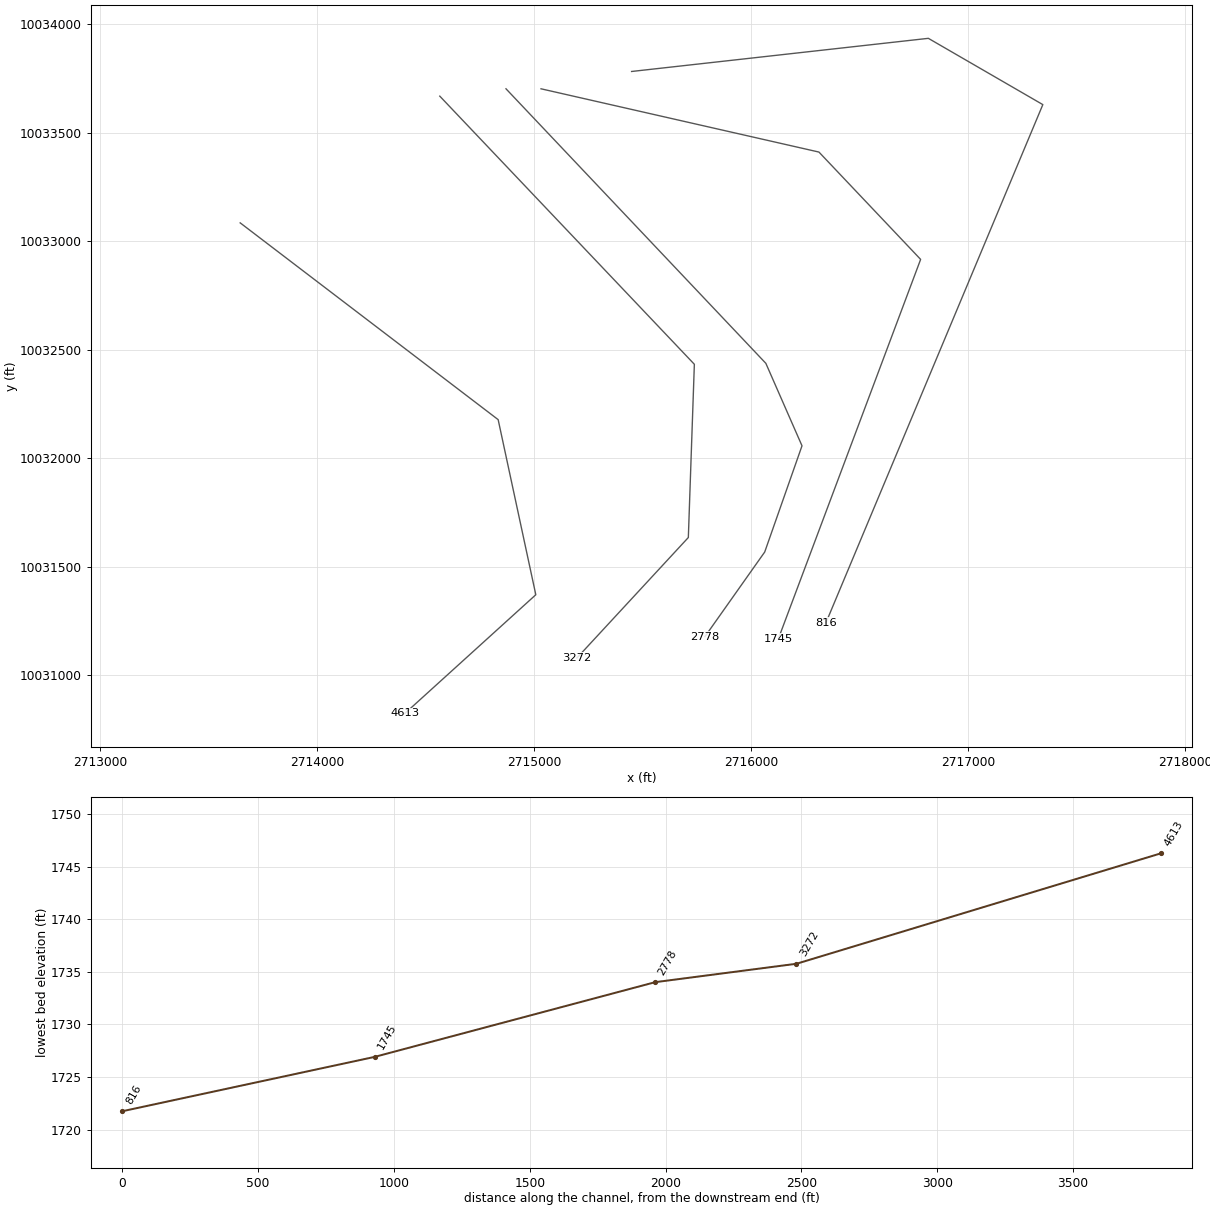
HEC-RAS study DELAWARE CREEK.prj: DELAWARE CREEK Base Level Engineering

--- DELAWARE CREEK.g01 (geometry) --- (continued)

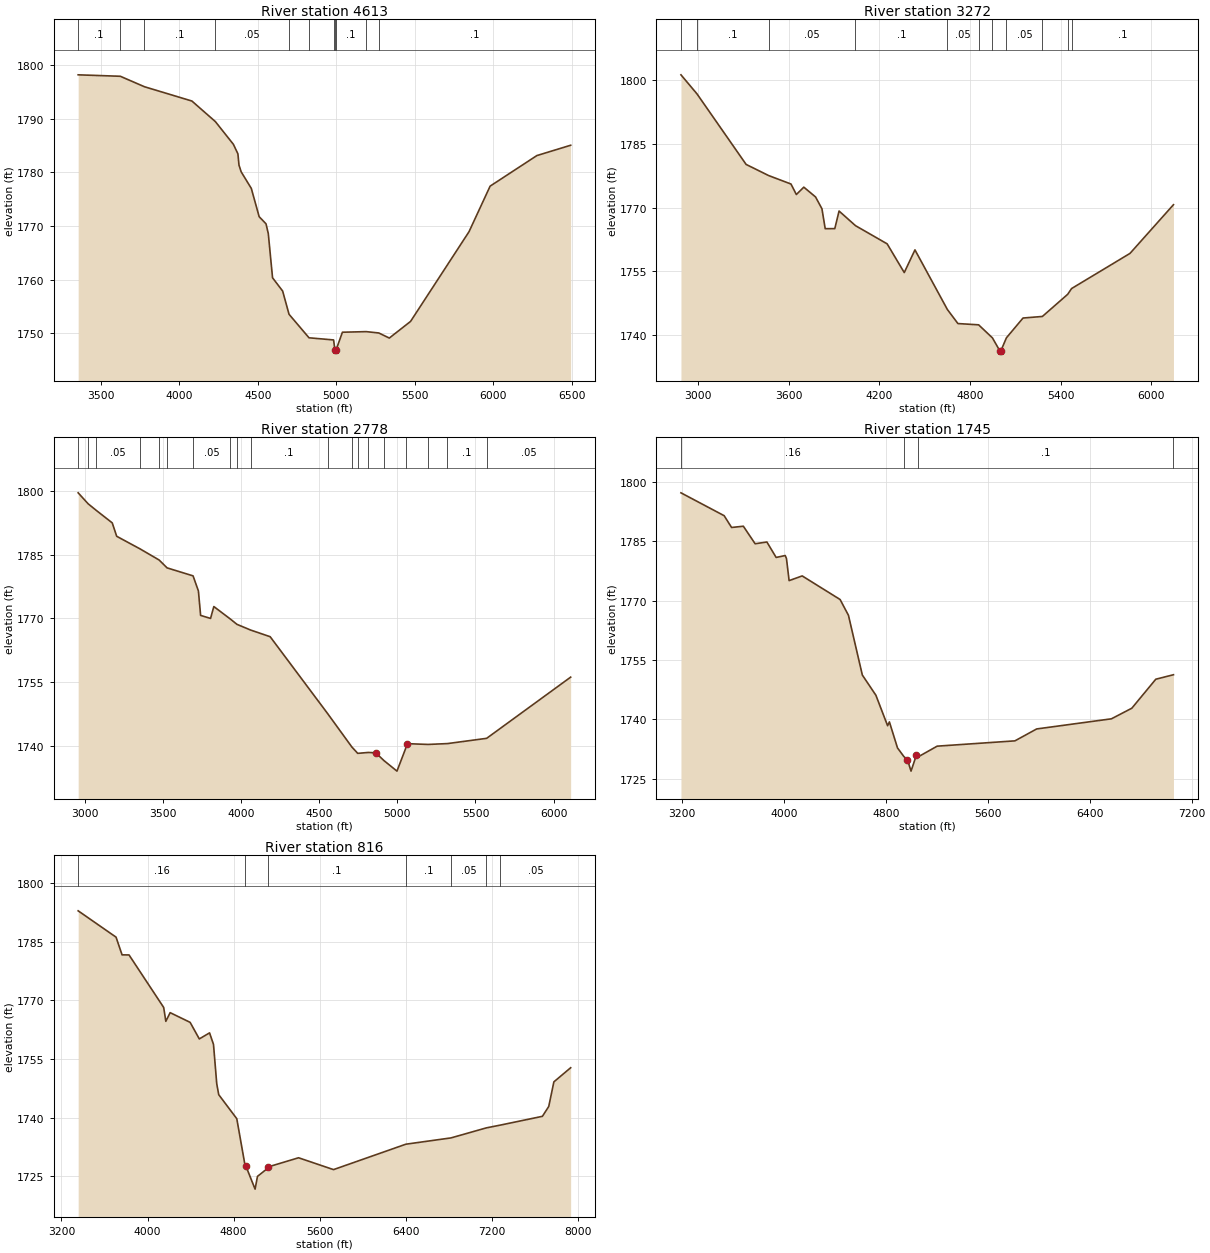
Type RM Length L Ch R = 1 ,4613    ,1341,1341,1341
BEGIN DESCRIPTION:
DELAWARE CREEK 4.0
END DESCRIPTION:
XS GIS Cut Line= 4
      2713644.35     10033085.44      2714833.56     10032178.34
      2715007.17     10031371.05      2714403.88     10030824.17
#Sta/Elev= 30
  3356.9  1798.2  3625.3 1797.93  3778.8 1795.98  4081.1 1793.31  4230.3 1789.48
  4345.1 1785.24  4374.1 1783.45  4380.8 1781.36    4395 1780.09  4459.4    1777
  4509.3 1771.73  4552.9  1770.4  4567.4 1768.59  4594.6 1760.33  4658.9 1757.85
  4699.5 1753.52  4826.7 1749.13  4983.2 1748.73  4992.1 1746.77  4994.8 1746.27
  4998.1 1746.77  5039.3 1750.17    5191 1750.28  5271.2 1750.03    5338 1749.08
  5473.3 1752.19  5845.4 1768.92  5979.9 1777.43  6277.3 1783.13  6492.6 1785.06
#Mann= 11 ,-1 , 0
  3356.9      .1       0  3625.3     .05       0  3778.8      .1       0
  4230.3     .05       0  4699.5      .1       0  4826.7     .05       0
  4983.2      .1       0  4992.1     .07       0  4998.1      .1       0
    5191     .16       0  5271.2      .1       0
Bank Sta=4992.1,4998.1
XS Rating Curve= 0 ,0
Exp/Cntr=0.3,0.1

Type RM Length L Ch R = 1 ,3272    ,520,520,520
BEGIN DESCRIPTION:
DELAWARE CREEK 3.0
END DESCRIPTION:
XS GIS Cut Line= 4
      2714564.49      10033669.6      2715738.09      10032433.5
      2715710.32     10031634.89      2715196.41     10031079.31
#Sta/Elev= 30
  2885.9 1801.27  2992.2 1796.78  3317.3 1780.18  3466.5 1777.56  3614.3 1775.57
  3649.8  1773.1  3699.2 1774.83  3776.9 1772.53  3819.3 1769.74  3840.8 1765.06
  3904.3 1765.07  3932.6 1769.21  4041.3 1765.77  4250.9 1761.49  4364.2 1754.73
    4435 1760.07  4649.3 1746.06  4719.4 1742.73  4856.5 1742.43  4948.1 1739.35
  4997.4 1736.27  5000.2 1735.77  5003.4 1736.27  5040.4 1739.37  5150.5 1744.03
  5278.6  1744.4  5446.1 1749.61    5472 1750.97  5858.6 1759.24  6146.3  1770.7
#Mann= 11 ,-1 , 0
  2885.9     .16       0  2992.2      .1       0  3466.5     .05       0
  4041.3      .1       0  4649.3     .05       0  4856.5      .1       0
  4948.1     .07       0  5040.4     .05       0  5278.6      .1       0
  5446.1     .05       0    5472      .1       0
Bank Sta=4997.4,5003.4
XS Rating Curve= 0 ,0
Exp/Cntr=0.3,0.1

Type RM Length L Ch R = 1 ,2778    ,1033,1033,1033
BEGIN DESCRIPTION:
Mapping XS 7e136263
END DESCRIPTION:
XS GIS Cut Line= 5
      2714869.71     10033703.54      2716067.66     10032437.88
      2716234.33     10032057.67      2716062.45     10031568.09
      2715786.88     10031178.13
#Sta/Elev= 30
  2955.5 1799.61  3019.3 1797.03  3069.4 1795.53  3173.9 1792.52  3202.2 1789.37
  3352.7 1786.38  3473.9 1783.78  3525.1 1781.92  3691.4 1780.04  3725.7 1776.47
  3739.8 1770.72  3803.4 1770.01  3824.4 1772.81    3930 1769.87  3972.2 1768.62
  4060.1 1767.27  4185.2  1765.7  4553.7 1747.56  4708.2 1739.72    4746 1738.21
  4813.6 1738.42  4861.6 1738.34  4913.8 1736.51  4997.3 1734.02  5052.1 1739.28
  5059.5  1740.5    5196 1740.31  5320.8 1740.51  5571.8 1741.75  6109.7 1756.17
#Mann= 19 ,-1 , 0
  2955.5      .1       0  3019.3     .16       0  3069.4     .05       0
  3352.7      .1       0  3473.9     .05       0  3525.1      .1       0
  3691.4     .05       0    3930      .1       0  3972.2     .05       0
  4060.1      .1       0  4553.7     .05       0  4708.2      .1       0
    4746     .05       0  4813.6      .1       0  4913.8     .07       0
  5052.1      .1       0    5196     .05       0  5320.8      .1       0
  5571.8     .05       0
Bank Sta=4861.6,5059.5
XS Rating Curve= 0 ,0
Exp/Cntr=0.3,0.1

Type RM Length L Ch R = 1 ,1745    ,929,929,929
BEGIN DESCRIPTION:
DELAWARE CREEK 2.0
END DESCRIPTION:
XS GIS Cut Line= 4
      2715031.16     10033703.51      2716312.45     10033411.84
       2716781.2     10032917.05      2716125.29     10031167.93
#Sta/Elev= 30
    3193 1797.25  3531.9 1791.47  3590.2 1788.49  3682.5 1788.81  3774.8 1784.38
  3867.1 1784.82  3939.7 1780.92  4010.7  1781.4  4020.7 1780.65  4041.5 1775.06
    4144 1776.25  4441.4 1770.29  4507.1 1766.29  4615.9  1751.2  4722.3 1746.09
  4814.1 1738.39  4828.3 1739.35  4891.8 1732.78  4941.6  1730.6  4969.9 1729.83
  4997.9 1726.91  5040.7 1731.01  5054.8 1730.53  5202.9 1733.22  5812.9 1734.56
  5983.7 1737.57  6569.9 1740.13  6730.1 1742.81  6918.2 1750.14  7056.7 1751.27
#Mann= 4 ,-1 , 0
    3193     .16       0  4941.6     .09       0  5054.8      .1       0
  7056.7     .05       0
Bank Sta=4969.9,5040.7
XS Rating Curve= 0 ,0
Exp/Cntr=0.3,0.1

Type RM Length L Ch R = 1 ,816     ,0,0,0
BEGIN DESCRIPTION:
DELAWARE CREEK 1.0
END DESCRIPTION:
XS GIS Cut Line= 4
      2715448.78     10033783.37      2716816.79     10033936.14
      2717344.57     10033630.59      2716344.58     10031241.71
#Sta/Elev= 30
  3355.1 1792.91    3707 1786.18  3763.1 1781.65  3827.7 1781.63  4149.7  1768.2
  4169.8 1764.65  4209.7 1766.87  4395.4 1764.39  4480.7 1760.15    4576  1761.7
  4612.6 1758.75  4642.7  1748.7  4661.3 1745.89    4829 1739.75  4903.6 1728.14
  4913.2 1727.66  4999.1 1721.74  5021.2    1725  5114.9 1727.05  5123.1 1727.44
  5403.1 1729.76  5727.8 1726.73  6400.1 1733.23  6819.6 1734.84  7148.6 1737.41
  7277.5 1738.11  7668.8 1740.36  7727.7 1742.88  7775.3 1749.17  7931.2 1752.78
#Mann= 7 ,-1 , 0
  3355.1     .16       0  4903.6     .09       0  5114.9      .1       0
  6400.1      .1       0  6819.6     .05       0  7148.6      .1       0
  7277.5     .05       0
Bank Sta=4913.2,5123.1
XS Rating Curve= 0 ,0
Exp/Cntr=0.3,0.1

Chan Stop Cuts=-1
Use User Specified Reach Order=0
Composite Channel Slope=5