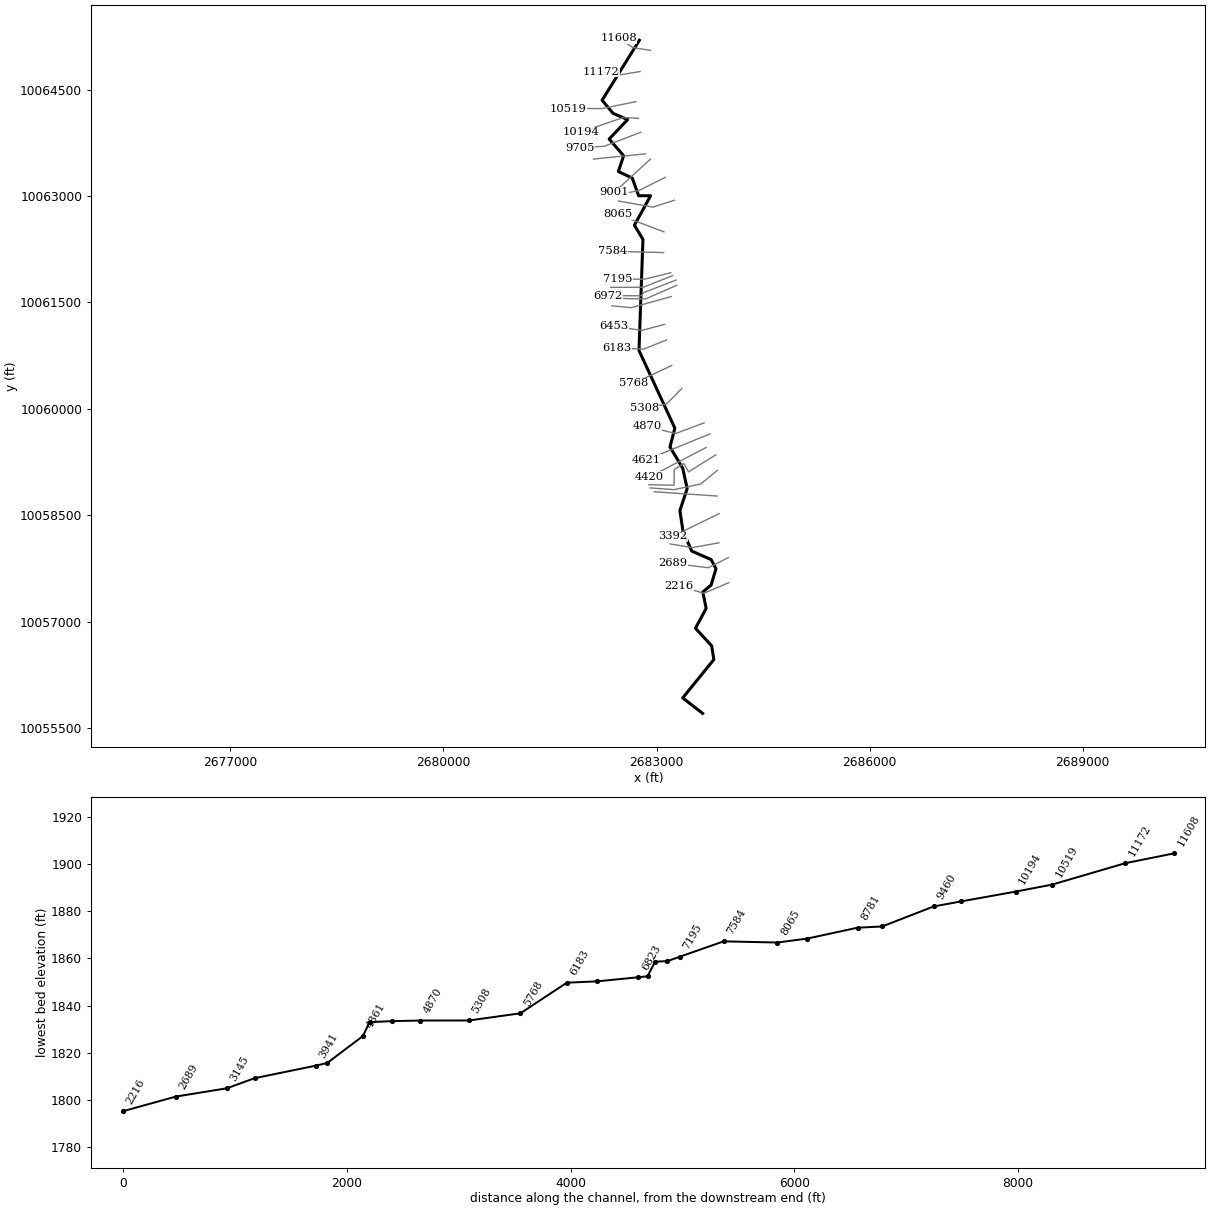
--- DEVILS CREEK.prj (project) ---

Proj Title=DEVILS CREEK Base Level Engineering
Current Plan=p01
Default Exp/Contr=0.3,0.1
English Units
Geom File=g01
Flow File=f01
Plan File=p01
BEGIN DESCRIPTION:
DEVILS CREEK
END DESCRIPTION:

--- DEVILS CREEK.p01 (plan) ---

Plan Title=Multiple Run
Short Identifier=Multiple
Geom File=g01
Flow File=f01
Subcritical Flow
K Sum by GR= 0
Std Step Tol= 0.01
Critical Tol= 0.01
Num of Std Step Trials= 20
Max Error Tol= 0.3
Flow Tol Ratio= 0.001
Split Flow NTrial= 30
Split Flow Tol= 0.02
Split Flow Ratio= 0.02
Log Output Level= 0
Friction Slope Method= 1
Unsteady Friction Slope Method= 2
Unsteady Bridges Friction Slope Method= 1
Parabolic Critical Depth
Global Vel Dist=  1 , 1 , 1
Global Log Level= 0
CheckData=True
Encroach Param= -1, 0, 0, 0
BEGIN DESCRIPTION:
Multiple Run
END DESCRIPTION:

--- DEVILS CREEK.f01 (steady flow) ---

Flow Title=Multiple
Number of Profiles=7
Profile Names=10-year,25-year,50-year,1pct_min,100-year,1pct_plu,500-year
River Rch & RM= DEVILS CREEK,Reach-1,11608
    1847    2762    3572    3362    4547    6150    7373
River Rch & RM= DEVILS CREEK,Reach-1,3392
    2319    3503    4563    4322    5845    7905    9598
Boundary for River Rch & Prof#=DEVILS CREEK,Reach-1,1
Up Type=0
Dn Type=3
Dn Slope=0.005
Boundary for River Rch & Prof#=DEVILS CREEK,Reach-1,2
Up Type=0
Dn Type=3
Dn Slope=0.005
Boundary for River Rch & Prof#=DEVILS CREEK,Reach-1,3
Up Type=0
Dn Type=3
Dn Slope=0.005
Boundary for River Rch & Prof#=DEVILS CREEK,Reach-1,4
Up Type=0
Dn Type=3
Dn Slope=0.005
Boundary for River Rch & Prof#=DEVILS CREEK,Reach-1,5
Up Type=0
Dn Type=3
Dn Slope=0.005
Boundary for River Rch & Prof#=DEVILS CREEK,Reach-1,6
Up Type=0
Dn Type=3
Dn Slope=0.005
Boundary for River Rch & Prof#=DEVILS CREEK,Reach-1,7
Up Type=0
Dn Type=3
Dn Slope=0.005

--- DEVILS CREEK.g01 (geometry) ---

Geom Title=Existing Conditions

River Reach=DEVILS CREEK,Reach-1
Reach XY= 30
      2682758.47     10065193.73      2682233.97     10064349.41
      2682388.57     10064163.76      2682594.07     10064076.99
      2682332.72     10063802.65      2682536.61     10063567.72
      2682462.99     10063344.19      2682657.88     10063253.28
      2682748.21     10063004.19      2682916.31     10063003.10
      2682688.52     10062588.35      2682808.79     10062388.83
      2682753.06     10060824.11      2683257.95     10059729.38
      2683189.34     10059464.28      2683368.59     10059165.04
      2683431.21     10058877.74      2683329.12     10058569.12
      2683372.49     10058275.40      2683496.23     10057997.80
      2683769.28     10057877.45      2683836.85     10057748.37
      2683768.31     10057518.70      2683651.73     10057422.27
      2683698.65     10057190.33      2683548.03     10056910.99
      2683776.15     10056662.97      2683806.59     10056469.57
      2683368.51     10055929.39      2683648.74     10055711.63

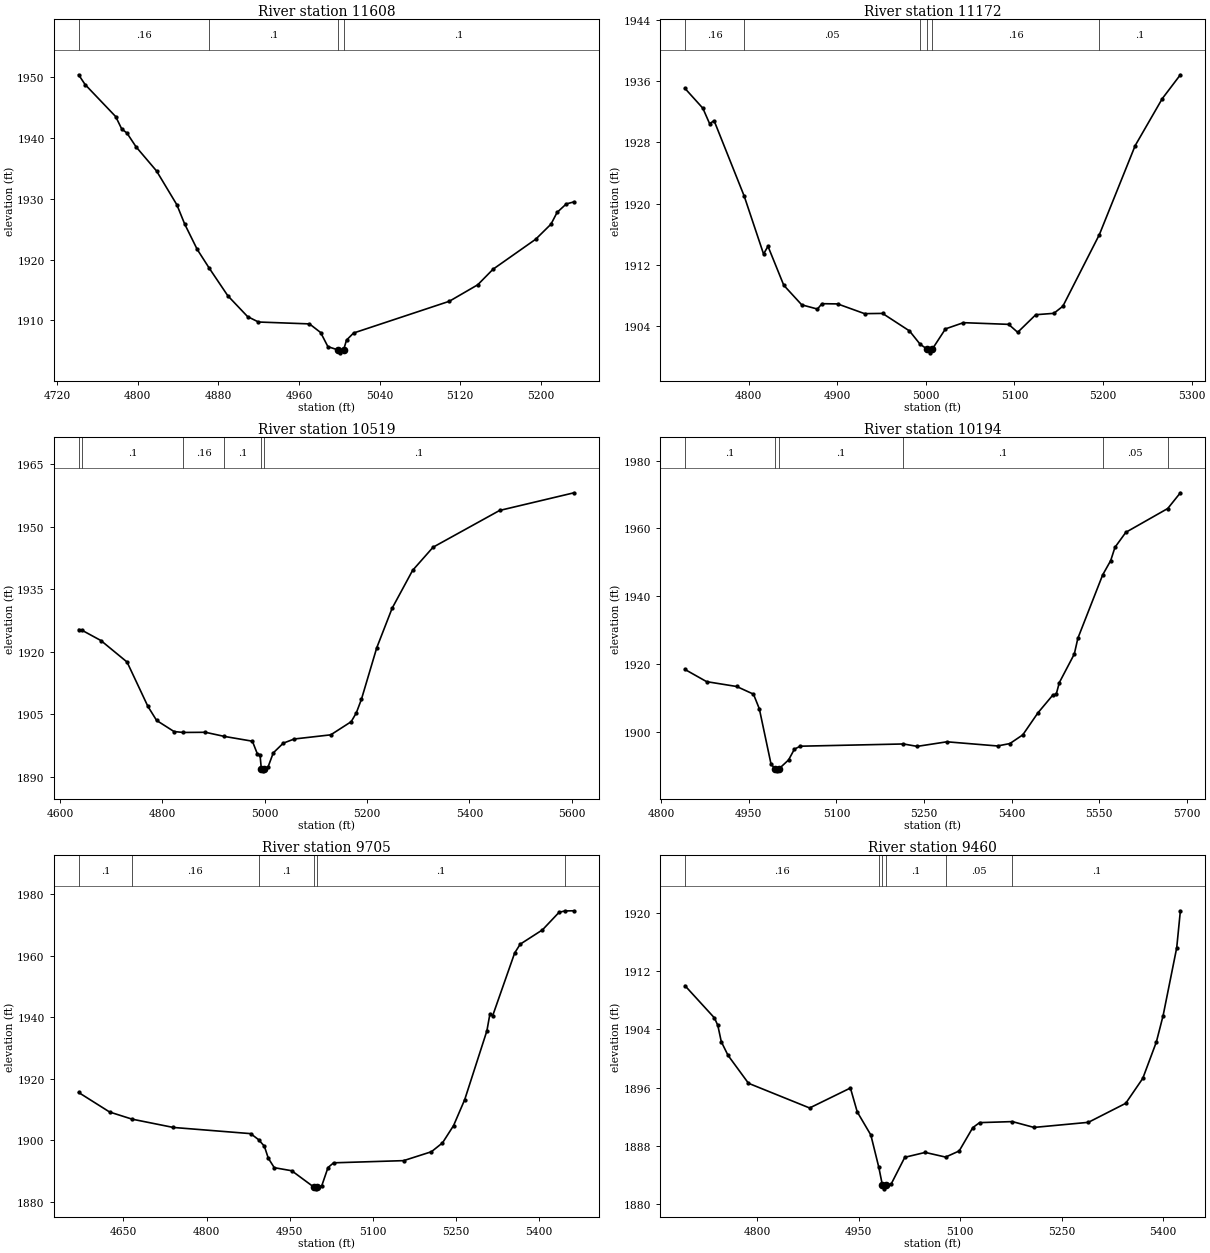
Type RM Length L Ch R = 1,11608,436,436,436
BEGIN DESCRIPTION:
DEVILS CREEK 26.0
END DESCRIPTION:
XS GIS Cut Line= 3
      2682914.78     10065051.90      2682667.37     10065090.96
      2682464.28     10065221.14
#Sta/Elev= 30
  4741.2 1950.41  4747.6 1948.81  4778.0 1943.53  4784.0 1941.49  4789.1 1940.84
  4798.2 1938.56  4818.5 1934.60  4838.7 1929.03  4846.5 1925.85  4858.9 1921.69
  4870.9 1918.59  4889.3 1914.06  4908.9 1910.64  4919.7 1909.75  4970.3 1909.44
  4981.4 1908.02  4988.6 1905.70  4998.2 1905.18  5000.9 1904.68  5004.2 1905.18
  5007.1 1906.78  5014.1 1907.94  5109.1 1913.16  5137.3 1915.87  5152.5 1918.43
  5194.8 1923.36  5210.0 1925.84  5216.1 1927.78  5225.2 1929.17  5232.9 1929.51
#Mann=4,-1,0
  4741.2    0.16       0  4870.9     0.1       0  4998.2    0.07       0
  5004.2     0.1       0
Bank Sta=4998.2,5004.2
Exp/Cntr=0.3,0.1

Type RM Length L Ch R = 1,11172,653,653,653
BEGIN DESCRIPTION:
DEVILS CREEK 25.0
END DESCRIPTION:
XS GIS Cut Line= 3
      2682768.43     10064753.73      2682468.47     10064703.73
      2682218.42     10064753.74
#Sta/Elev= 30
  4728.2 1935.04  4748.4 1932.45  4756.0 1930.44  4761.1 1930.82  4795.1 1920.96
  4816.9 1913.41  4821.9 1914.42  4839.7 1909.33  4860.0 1906.77  4877.7 1906.22
  4882.8 1906.92  4900.5 1906.89  4930.9 1905.62  4951.2 1905.65  4981.6 1903.36
  4993.7 1901.61  5001.4 1901.00  5004.2 1900.50  5007.4 1901.00  5022.2 1903.63
  5042.5 1904.44  5093.5 1904.22  5103.7 1903.18  5124.1 1905.48  5144.5 1905.66
  5154.7 1906.59  5195.9 1915.95  5236.3 1927.57  5266.9 1933.71  5287.3 1936.82
#Mann=6,-1,0
  4728.2    0.16       0  4795.1    0.05       0  4993.7    0.16       0
  5001.4    0.07       0  5007.4    0.16       0  5195.9     0.1       0
Bank Sta=5001.4,5007.4
Exp/Cntr=0.3,0.1

Type RM Length L Ch R = 1,10519,325,325,325
BEGIN DESCRIPTION:
DEVILS CREEK 24.0
END DESCRIPTION:
XS GIS Cut Line= 3
      2682711.11     10064329.59      2682233.23     10064231.96
      2681753.08     10064231.96
#Sta/Elev= 30
  4636.4 1925.32  4642.4 1925.18  4679.9 1922.68  4731.0 1917.52  4771.8 1906.86
  4788.8 1903.50  4822.8 1900.84  4840.8 1900.62  4884.1 1900.66  4920.7 1899.68
  4975.9 1898.52  4985.7 1895.44  4990.8 1895.26  4993.3 1891.91  4996.1 1891.41
  4999.3 1891.91  5006.5 1892.35  5016.7 1895.72  5036.2 1898.05  5057.6 1899.05
  5129.0 1900.05  5168.9 1903.20  5178.9 1905.31  5188.9 1908.57  5218.9 1920.96
  5248.9 1930.43  5288.9 1939.51  5328.9 1945.07  5458.9 1953.89  5604.3 1958.13
#Mann=6,-1,0
  4636.4    0.16       0  4642.4     0.1       0  4840.8    0.16       0
  4920.7     0.1       0  4993.3    0.07       0  4999.3     0.1       0
Bank Sta=4993.3,4999.3
Exp/Cntr=0.3,0.1

Type RM Length L Ch R = 1,10194,489,489,489
BEGIN DESCRIPTION:
DEVILS CREEK 23.0
END DESCRIPTION:
XS GIS Cut Line= 3
      2682745.53     10064093.56      2682531.95     10064106.59
      2681932.65     10063899.04
#Sta/Elev= 30
  4840.6 1918.36  4877.7 1914.76  4929.2 1913.33  4957.9 1911.07  4967.9 1906.77
  4987.9 1890.50  4995.0 1888.94  4997.7 1888.44  5001.0 1888.94  5018.0 1891.66
  5028.0 1894.84  5038.0 1895.71  5214.7 1896.37  5238.2 1895.66  5289.1 1897.01
  5375.7 1895.78  5396.9 1896.49  5419.0 1899.06  5444.9 1905.55  5470.8 1910.88
  5476.1 1910.98  5481.6 1914.50  5507.2 1922.91  5513.3 1927.57  5555.8 1946.28
  5569.5 1950.49  5576.8 1954.40  5595.4 1958.83  5667.2 1965.86  5688.8 1970.50
#Mann=6,-1,0
  4840.6     0.1       0  4995.0    0.07       0  5001.0     0.1       0
  5214.7     0.1       0  5555.8    0.05       0  5667.2     0.1       0
Bank Sta=4995,5001
Exp/Cntr=0.3,0.1

Type RM Length L Ch R = 1,9705,245,245,245
BEGIN DESCRIPTION:
DEVILS CREEK 22.0
END DESCRIPTION:
XS GIS Cut Line= 3
      2682777.97     10063897.95      2682261.50     10063700.10
      2681921.58     10063679.65
#Sta/Elev= 30
  4569.1 1915.59  4625.1 1909.23  4665.5 1906.92  4739.9 1904.22  4879.4 1902.21
  4893.6 1900.26  4904.1 1898.13  4911.2 1894.22  4922.0 1891.14  4953.5 1890.14
  4993.9 1884.76  4996.7 1884.26  4999.9 1884.76  5007.6 1885.23  5018.9 1891.18
  5029.0 1892.72  5155.3 1893.43  5205.4 1896.32  5225.4 1899.20  5245.4 1904.83
  5265.5 1913.27  5305.5 1935.63  5311.0 1941.17  5316.0 1940.58  5355.6 1960.95
  5365.6 1963.81  5405.7 1968.46  5435.8 1974.19  5446.5 1974.62  5462.7 1974.67
#Mann=6,-1,0
  4569.1     0.1       0  4665.5    0.16       0  4893.6     0.1       0
  4993.9    0.07       0  4999.9     0.1       0  5446.5    0.05       0
Bank Sta=4993.9,4999.9
Exp/Cntr=0.3,0.1

Type RM Length L Ch R = 1,9460,459,459,459
BEGIN DESCRIPTION:
Mapping XS 8c74608f
END DESCRIPTION:
XS GIS Cut Line= 2
      2682841.88     10063593.57      2682113.12     10063520.69
#Sta/Elev= 30
  4693.2 1910.00  4736.8 1905.57  4741.8 1904.54  4746.9 1902.31  4756.9 1900.43
  4787.1 1896.60  4877.5 1893.21  4937.8 1895.95  4947.9 1892.67  4968.0 1889.50
  4979.8 1885.06  4985.1 1882.61  4987.8 1882.11  4991.1 1882.61  4998.1 1882.78
  5018.2 1886.44  5048.4 1887.11  5078.5 1886.47  5098.6 1887.31  5118.7 1890.51
  5128.8 1891.20  5177.2 1891.34  5209.2 1890.54  5289.6 1891.24  5344.8 1893.85
  5370.0 1897.27  5390.1 1902.27  5400.1 1905.90  5420.2 1915.21  5425.6 1920.28
#Mann=6,-1,0
  4693.2    0.16       0  4979.8     0.1       0  4985.1    0.07       0
  4991.1     0.1       0  5078.5    0.05       0  5177.2     0.1       0
Bank Sta=4985.1,4991.1
Exp/Cntr=0.3,0.1

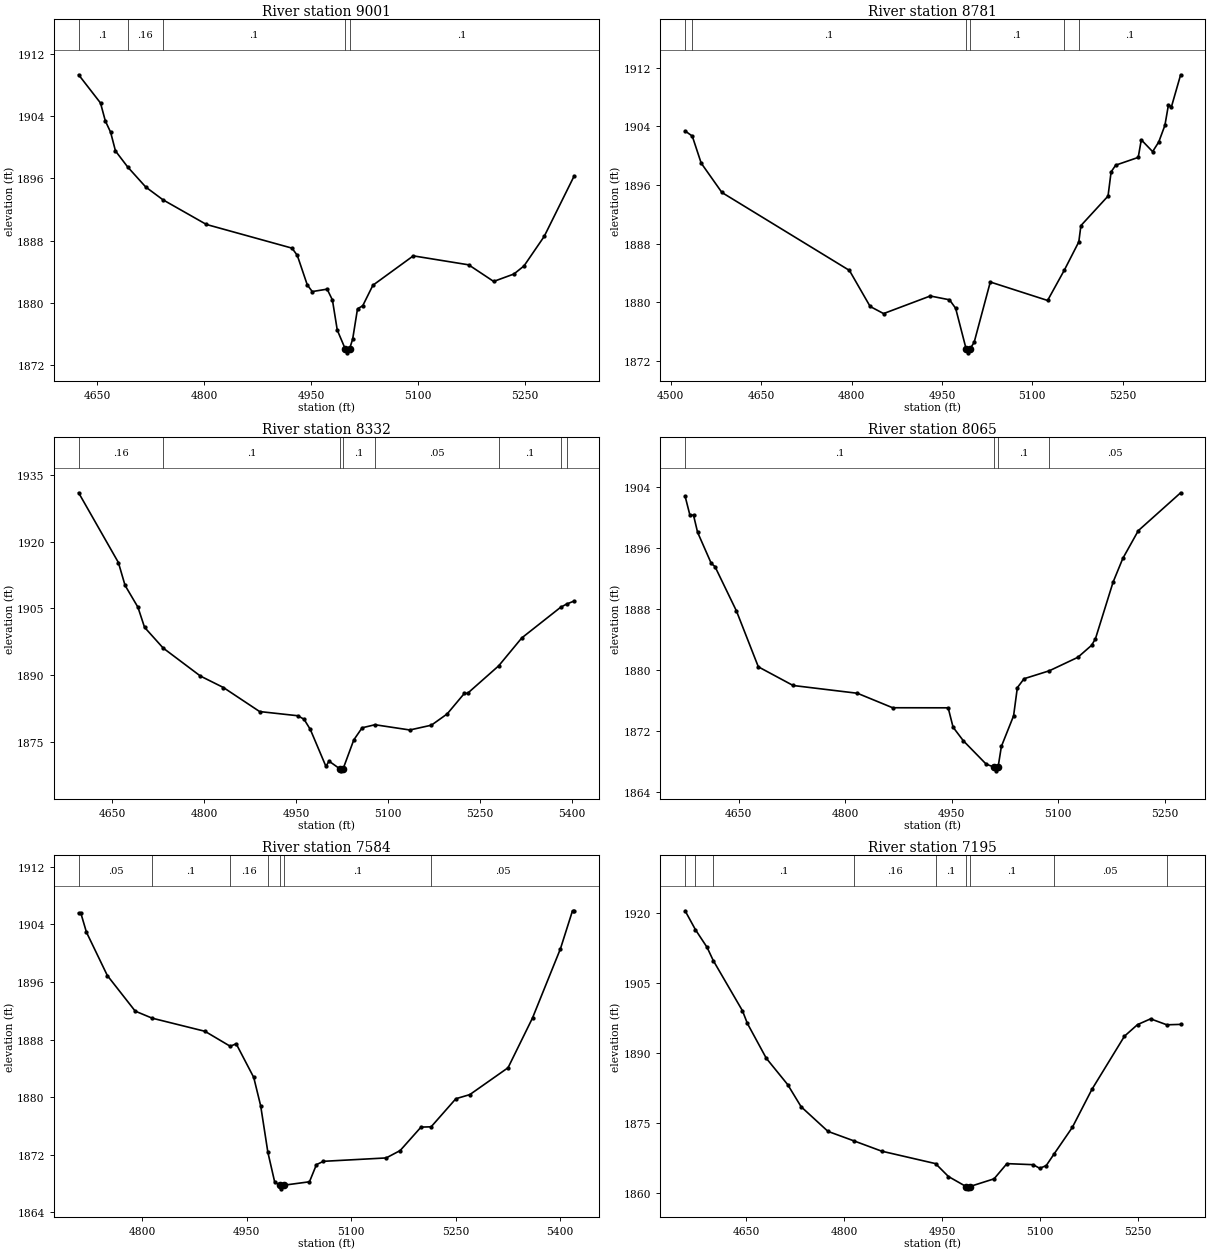
Type RM Length L Ch R = 1,9001,220,220,220
BEGIN DESCRIPTION:
DEVILS CREEK 21.0
END DESCRIPTION:
XS GIS Cut Line= 2
      2682914.79     10063520.67      2682402.64     10063050.12
#Sta/Elev= 30
  4624.0 1909.28  4654.7 1905.66  4661.5 1903.35  4668.9 1901.91  4675.7 1899.51
  4692.7 1897.47  4718.2 1894.88  4742.4 1893.24  4803.3 1890.08  4923.5 1887.04
  4930.9 1886.11  4944.9 1882.33  4951.9 1881.47  4972.8 1881.78  4980.2 1880.39
  4987.0 1876.53  4998.2 1874.11  5001.0 1873.61  5004.2 1874.11  5008.6 1875.36
  5015.4 1879.25  5022.8 1879.66  5037.0 1882.28  5093.7 1886.05  5171.4 1884.90
  5206.5 1882.77  5234.9 1883.72  5249.1 1884.76  5277.4 1888.54  5319.5 1896.30
#Mann=5,-1,0
  4624.0     0.1       0  4692.7    0.16       0  4742.4     0.1       0
  4998.2    0.07       0  5004.2     0.1       0
Bank Sta=4998.2,5004.2
Exp/Cntr=0.3,0.1

Type RM Length L Ch R = 1,8781,449,449,449
BEGIN DESCRIPTION:
DEVILS CREEK 20.0
END DESCRIPTION:
XS GIS Cut Line= 3
      2683123.10     10063262.84      2682753.31     10063077.94
      2682352.90     10062994.74
#Sta/Elev= 30
  4523.7 1903.38  4535.6 1902.68  4550.4 1898.99  4584.8 1894.98  4796.4 1884.34
  4830.8 1879.42  4853.1 1878.45  4930.6 1880.85  4962.5 1880.33  4972.7 1879.17
  4990.2 1873.59  4992.9 1873.09  4996.2 1873.59  5003.4 1874.52  5030.2 1882.76
  5125.3 1880.24  5153.2 1884.40  5177.1 1888.24  5180.6 1890.46  5225.6 1894.49
  5230.7 1897.79  5238.3 1898.71  5275.7 1899.77  5280.8 1902.17  5299.6 1900.56
  5309.8 1901.88  5320.0 1904.15  5325.8 1906.91  5330.9 1906.70  5346.1 1911.05
#Mann=6,-1,0
  4523.7    0.16       0  4535.6     0.1       0  4990.2    0.07       0
  4996.2     0.1       0  5153.2    0.05       0  5177.1     0.1       0
Bank Sta=4990.2,4996.2
Exp/Cntr=0.3,0.1

Type RM Length L Ch R = 1,8332,267,267,267
BEGIN DESCRIPTION:
DEVILS CREEK 19.0
END DESCRIPTION:
XS GIS Cut Line= 3
      2683250.69     10062939.92      2682948.62     10062843.57
      2682464.25     10062929.50
#Sta/Elev= 30
  4594.9 1930.95  4659.8 1915.28  4670.7 1910.14  4691.7 1905.24  4702.5 1900.72
  4732.9 1896.06  4793.8 1889.76  4831.3 1887.19  4890.4 1881.79  4952.7 1880.85
  4962.9 1880.06  4973.1 1877.78  4998.6 1869.48  5003.7 1870.65  5020.8 1868.97
  5023.6 1868.47  5026.8 1868.97  5044.1 1875.42  5057.7 1878.14  5078.7 1878.83
  5135.6 1877.65  5170.8 1878.73  5196.5 1881.25  5224.8 1885.90  5229.9 1885.89
  5280.7 1892.07  5318.4 1898.34  5381.7 1905.21  5391.5 1905.94  5403.9 1906.63
#Mann=8,-1,0
  4594.9    0.16       0  4732.9     0.1       0  5020.8    0.07       0
  5026.8     0.1       0  5078.7    0.05       0  5280.7     0.1       0
  5381.7    0.05       0  5391.5     0.1       0
Bank Sta=5020.8,5026.8
Exp/Cntr=0.3,0.1

Type RM Length L Ch R = 1,8065,481,481,481
BEGIN DESCRIPTION:
DEVILS CREEK 18.0
END DESCRIPTION:
XS GIS Cut Line= 2
      2683104.89     10062494.60      2682452.37     10062741.57
#Sta/Elev= 30
  4574.7 1902.83  4581.3 1900.41  4586.6 1900.32  4592.3 1898.09  4611.5 1894.02
  4616.8 1893.59  4647.0 1887.77  4677.8 1880.44  4726.8 1877.99  4817.3 1876.97
  4866.9 1875.07  4945.1 1875.06  4952.0 1872.52  4966.5 1870.73  4998.6 1867.67
  5009.4 1867.29  5012.1 1866.79  5015.4 1867.29  5020.0 1869.99  5037.2 1874.01
  5042.5 1877.71  5052.0 1878.88  5087.5 1879.92  5127.7 1881.69  5147.1 1883.27
  5152.5 1884.14  5177.3 1891.56  5191.0 1894.67  5212.8 1898.31  5272.4 1903.28
#Mann=4,-1,0
  4574.7     0.1       0  5009.4    0.07       0  5015.4     0.1       0
  5087.5    0.05       0
Bank Sta=5009.4,5015.4
Exp/Cntr=0.3,0.1

Type RM Length L Ch R = 1,7584,389,389,389
BEGIN DESCRIPTION:
DEVILS CREEK 17.0
END DESCRIPTION:
XS GIS Cut Line= 2
      2683099.69     10062202.94      2682388.72     10062221.17
#Sta/Elev= 30
  4709.0 1905.57  4712.1 1905.57  4720.2 1902.91  4750.2 1896.89  4790.2 1891.95
  4814.6 1890.97  4890.3 1889.15  4926.6 1887.07  4935.1 1887.42  4960.3 1882.75
  4970.3 1878.79  4980.6 1872.35  4990.3 1868.26  4997.3 1867.78  5000.1 1867.28
  5003.3 1867.78  5040.3 1868.26  5050.3 1870.64  5060.3 1871.10  5150.4 1871.57
  5170.4 1872.59  5200.4 1875.85  5214.9 1875.89  5250.4 1879.79  5270.4 1880.36
  5325.3 1884.09  5360.4 1891.00  5400.5 1900.61  5417.8 1905.88  5420.2 1905.88
#Mann=7,-1,0
  4709.0    0.05       0  4814.6     0.1       0  4926.6    0.16       0
  4980.6     0.1       0  4997.3    0.07       0  5003.3     0.1       0
  5214.9    0.05       0
Bank Sta=4997.3,5003.3
Exp/Cntr=0.3,0.1

Type RM Length L Ch R = 1,7195,113,113,113
BEGIN DESCRIPTION:
DEVILS CREEK 16.0
END DESCRIPTION:
XS GIS Cut Line= 3
      2683201.24     10061919.09      2682828.83     10061827.94
      2682452.34     10061830.54
#Sta/Elev= 30
  4556.2 1920.56  4572.1 1916.49  4589.9 1912.70  4599.4 1909.86  4644.2 1899.06
  4651.7 1896.35  4680.7 1888.86  4713.5 1883.20  4734.1 1878.44  4775.3 1873.14
  4814.9 1871.11  4857.6 1868.89  4940.3 1866.21  4960.0 1863.44  4987.0 1861.29
  4989.7 1860.79  4993.0 1861.29  5030.0 1862.94  5049.7 1866.21  5090.0 1865.98
  5100.0 1865.20  5110.0 1865.79  5121.7 1868.22  5150.0 1874.00  5180.0 1882.16
  5230.0 1893.61  5250.0 1896.09  5270.0 1897.33  5294.9 1896.05  5316.1 1896.14
#Mann=9,-1,0
  4556.2     0.1       0  4572.1    0.16       0  4599.4     0.1       0
  4814.9    0.16       0  4940.3     0.1       0  4987.0    0.07       0
  4993.0     0.1       0  5121.7    0.05       0  5294.9     0.1       0
Bank Sta=4987,4993
Exp/Cntr=0.3,0.1

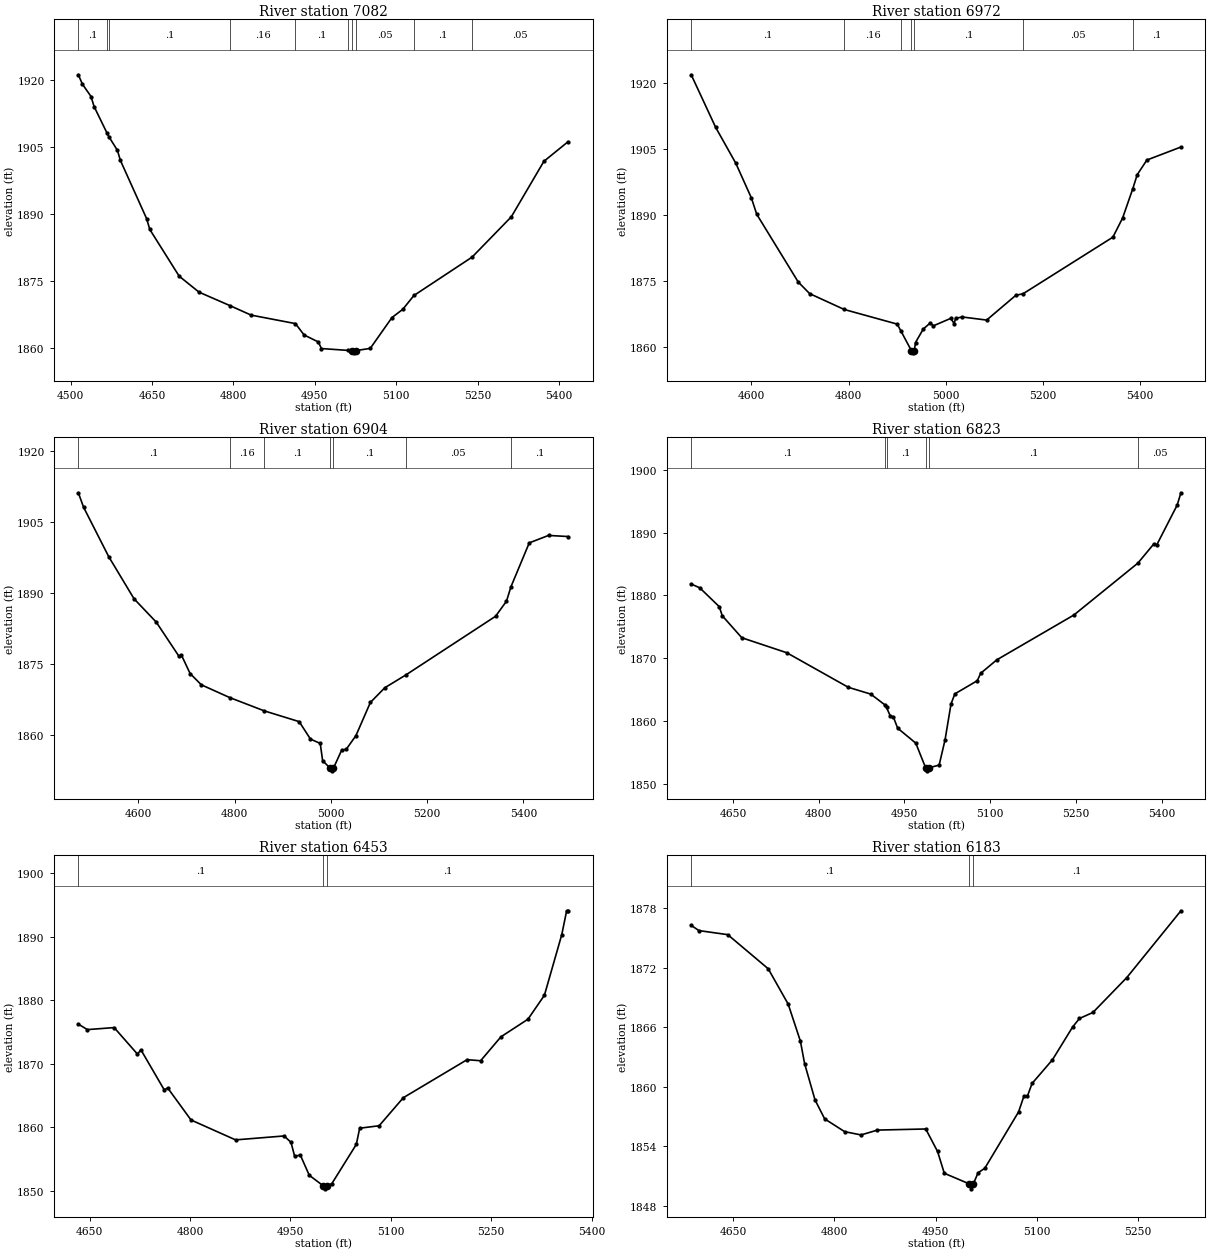
Type RM Length L Ch R = 1,7082,110,110,110
BEGIN DESCRIPTION:
Mapping XS 3fa0ce27
END DESCRIPTION:
XS GIS Cut Line= 3
      2683225.48     10061877.23      2682814.01     10061714.90
      2682353.95     10061713.16
#Sta/Elev= 30
  4514.4 1921.10  4521.9 1919.00  4537.8 1916.24  4543.4 1914.00  4567.6 1907.97
  4570.8 1907.22  4586.4 1904.20  4591.9 1901.94  4640.2 1888.92  4646.1 1886.49
  4700.2 1876.04  4736.9 1872.46  4793.3 1869.48  4832.8 1867.33  4914.5 1865.43
  4930.4 1862.89  4956.7 1861.32  4962.3 1859.85  5010.8 1859.44  5019.3 1859.39
  5022.0 1858.89  5025.3 1859.39  5052.3 1859.88  5092.3 1866.78  5112.3 1868.63
  5132.8 1871.72  5240.0 1880.31  5312.3 1889.33  5372.3 1901.74  5416.8 1906.12
#Mann=10,-1,0
  4514.4     0.1       0  4567.6    0.16       0  4570.8     0.1       0
  4793.3    0.16       0  4914.5     0.1       0  5010.8    0.05       0
  5019.3    0.07       0  5025.3    0.05       0  5132.8     0.1       0
  5240.0    0.05       0
Bank Sta=5019.3,5025.3
Exp/Cntr=0.3,0.1

Type RM Length L Ch R = 1,6972,68,68,68
BEGIN DESCRIPTION:
Mapping XS 016b1448
END DESCRIPTION:
XS GIS Cut Line= 4
      2683274.04     10061815.58      2682823.56     10061641.11
      2682779.29     10061594.24      2682318.35     10061595.97
#Sta/Elev= 30
  4475.9 1921.94  4526.3 1909.95  4567.7 1901.80  4599.8 1893.90  4610.8 1890.18
  4696.3 1874.75  4719.8 1872.11  4791.1 1868.50  4900.1 1865.17  4907.6 1863.64
  4929.3 1859.13  4932.0 1858.63  4935.3 1859.13  4937.8 1860.98  4953.7 1864.04
  4968.0 1865.42  4974.8 1864.79  5010.4 1866.48  5017.3 1865.30  5020.4 1866.50
  5034.3 1866.79  5084.3 1866.09  5144.3 1871.72  5159.6 1872.10  5344.3 1884.97
  5364.3 1889.33  5385.3 1896.01  5394.3 1899.18  5414.3 1902.53  5484.4 1905.49
#Mann=7,-1,0
  4475.9     0.1       0  4791.1    0.16       0  4907.6     0.1       0
  4929.3    0.07       0  4935.3     0.1       0  5159.6    0.05       0
  5385.3     0.1       0
Bank Sta=4929.3,4935.3
Exp/Cntr=0.3,0.1

Type RM Length L Ch R = 1,6904,81,81,81
BEGIN DESCRIPTION:
Mapping XS 8838a526
END DESCRIPTION:
XS GIS Cut Line= 3
      2683284.46     10061742.66      2682840.92     10061548.23
      2682307.89     10061562.12
#Sta/Elev= 30
  4475.4 1911.25  4486.3 1908.19  4538.5 1897.75  4591.1 1888.84  4637.4 1883.89
  4684.2 1876.72  4689.7 1876.91  4707.6 1873.04  4730.9 1870.65  4789.7 1867.96
  4862.0 1865.13  4934.3 1862.86  4957.7 1859.17  4978.0 1858.26  4983.0 1854.60
  4999.2 1852.96  5001.9 1852.46  5005.2 1852.96  5022.2 1856.77  5032.2 1857.04
  5052.2 1859.91  5082.2 1866.92  5112.2 1870.03  5155.7 1872.72  5342.3 1885.14
  5365.0 1888.33  5374.2 1891.36  5412.3 1900.66  5452.3 1902.23  5492.9 1902.00
#Mann=7,-1,0
  4475.4     0.1       0  4789.7    0.16       0  4862.0     0.1       0
  4999.2    0.07       0  5005.2     0.1       0  5155.7    0.05       0
  5374.2     0.1       0
Bank Sta=4999.2,5005.2
Exp/Cntr=0.3,0.1

Type RM Length L Ch R = 1,6823,370,370,370
BEGIN DESCRIPTION:
Mapping XS 051525d7
END DESCRIPTION:
XS GIS Cut Line= 3
      2683206.42     10061583.15      2682646.54     10061426.90
      2682371.93     10061452.80
#Sta/Elev= 30
  4576.8 1881.81  4591.7 1881.21  4625.9 1878.20  4631.1 1876.76  4665.3 1873.25
  4744.0 1870.86  4851.7 1865.35  4891.1 1864.26  4915.4 1862.57  4918.6 1862.13
  4925.3 1860.76  4930.5 1860.64  4938.1 1858.83  4969.8 1856.45  4987.0 1852.53
  4989.7 1852.03  4993.0 1852.53  5010.7 1852.94  5021.1 1856.99  5031.5 1862.69
  5038.2 1864.30  5077.5 1866.40  5083.4 1867.58  5111.7 1869.73  5246.5 1876.87
  5358.6 1885.15  5386.3 1888.19  5391.4 1888.02  5427.3 1894.39  5433.9 1896.36
#Mann=6,-1,0
  4576.8     0.1       0  4915.4    0.16       0  4918.6     0.1       0
  4987.0    0.07       0  4993.0     0.1       0  5358.6    0.05       0
Bank Sta=4987,4993
Exp/Cntr=0.3,0.1

Type RM Length L Ch R = 1,6453,270,270,270
BEGIN DESCRIPTION:
DEVILS CREEK 15.0
END DESCRIPTION:
XS GIS Cut Line= 3
      2683115.33     10061192.54      2682794.97     10061106.59
      2682399.18     10061163.87
#Sta/Elev= 30
  4633.1 1876.25  4646.6 1875.38  4686.6 1875.70  4721.4 1871.52  4726.6 1872.19
  4761.4 1865.88  4766.6 1866.18  4801.4 1861.13  4868.0 1857.99  4940.5 1858.61
  4950.8 1857.60  4956.2 1855.43  4964.8 1855.58  4978.1 1852.41  4998.7 1850.77
  5001.4 1850.27  5004.7 1850.77  5011.8 1851.09  5048.4 1857.28  5053.4 1859.83
  5082.5 1860.22  5118.6 1864.64  5213.9 1870.64  5234.1 1870.47  5264.4 1874.24
  5304.8 1877.02  5329.4 1880.80  5355.3 1890.35  5362.6 1894.12  5364.7 1894.12
#Mann=3,-1,0
  4633.1     0.1       0  4998.7    0.07       0  5004.7     0.1       0
Bank Sta=4998.7,5004.7
Exp/Cntr=0.3,0.1

Type RM Length L Ch R = 1,6183,415,415,415
BEGIN DESCRIPTION:
DEVILS CREEK 14.0
END DESCRIPTION:
XS GIS Cut Line= 3
      2683138.73     10060971.17      2682818.41     10060843.57
      2682438.23     10060856.59
#Sta/Elev= 30
  4588.0 1876.29  4599.5 1875.77  4642.1 1875.36  4702.0 1871.92  4731.6 1868.35
  4749.7 1864.61  4755.9 1862.35  4771.3 1858.69  4785.6 1856.77  4815.2 1855.48
  4839.5 1855.15  4863.8 1855.64  4935.3 1855.75  4952.8 1853.48  4962.8 1851.28
  4999.8 1850.21  5002.5 1849.71  5005.8 1850.21  5012.8 1851.33  5022.8 1851.79
  5072.8 1857.48  5080.8 1859.09  5085.8 1859.06  5092.8 1860.35  5122.9 1862.73
  5152.9 1866.05  5162.9 1866.90  5182.9 1867.51  5232.9 1871.02  5313.2 1877.77
#Mann=3,-1,0
  4588.0     0.1       0  4999.8    0.07       0  5005.8     0.1       0
Bank Sta=4999.8,5005.8
Exp/Cntr=0.3,0.1

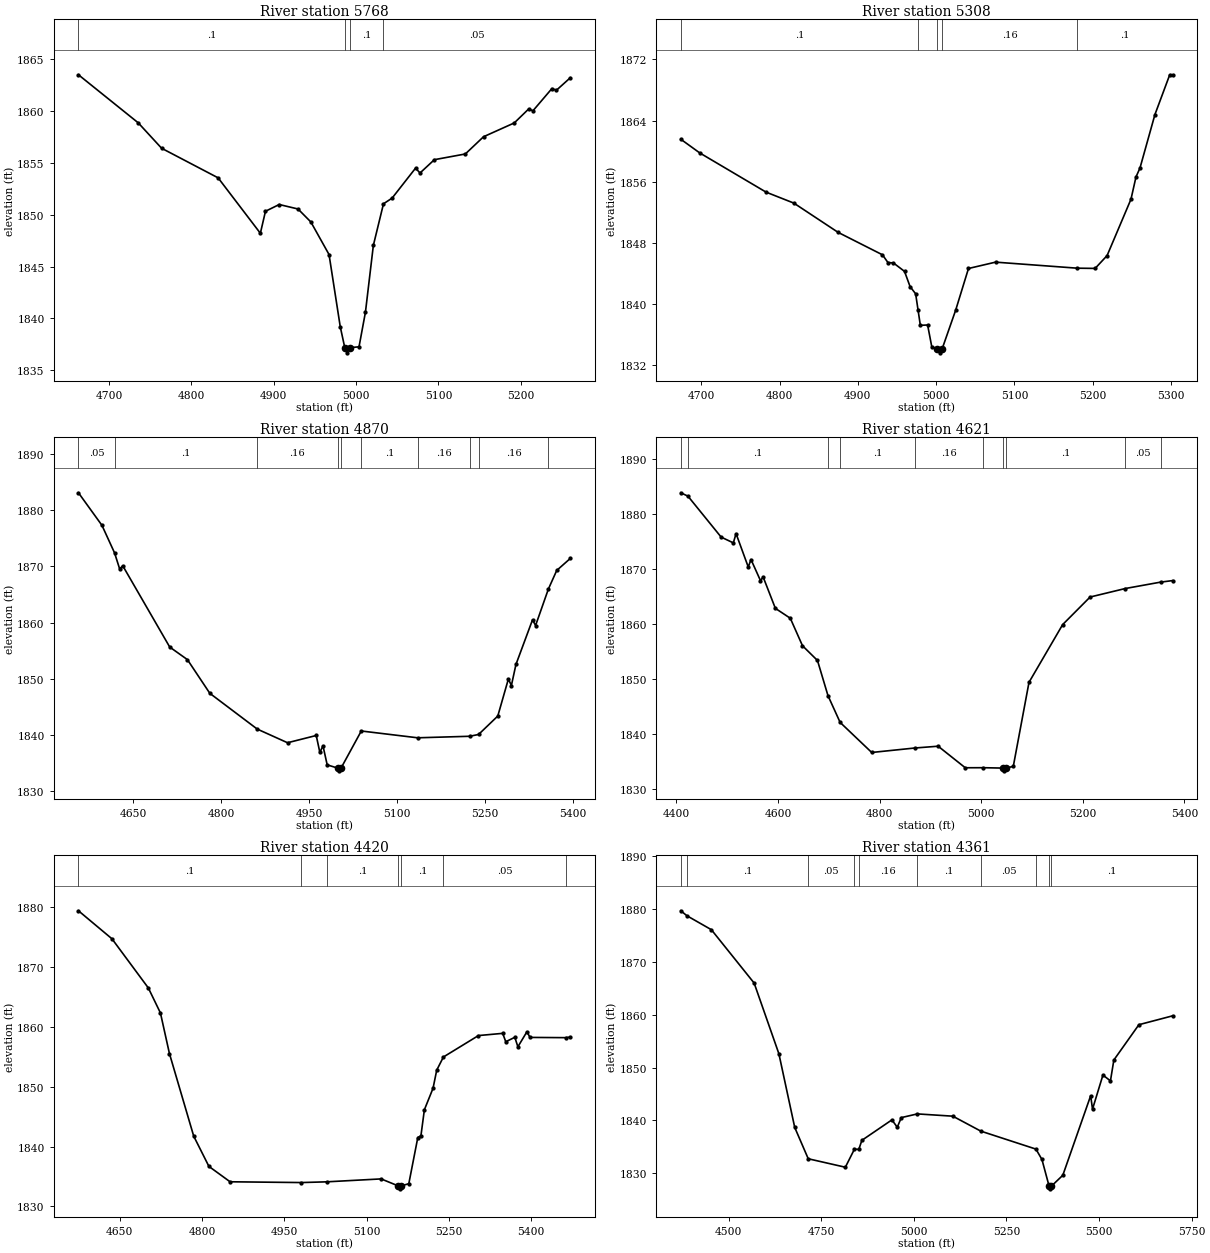
Type RM Length L Ch R = 1,5768,460,460,460
BEGIN DESCRIPTION:
DEVILS CREEK 13.0
END DESCRIPTION:
XS GIS Cut Line= 2
      2683214.26     10060611.80      2682673.03     10060359.40
#Sta/Elev= 30
  4662.9 1863.48  4735.5 1858.85  4763.9 1856.40  4832.5 1853.55  4883.8 1848.21
  4890.0 1850.33  4906.7 1850.98  4929.5 1850.55  4945.1 1849.30  4967.2 1846.16
  4980.8 1839.21  4986.3 1837.19  4989.0 1836.69  4992.3 1837.19  5003.6 1837.27
  5011.4 1840.61  5021.0 1847.04  5033.3 1851.05  5043.8 1851.60  5072.2 1854.48
  5077.7 1854.02  5095.1 1855.30  5132.7 1855.85  5154.8 1857.51  5192.1 1858.84
  5209.4 1860.17  5214.9 1860.02  5237.8 1862.15  5243.3 1861.99  5260.1 1863.19
#Mann=4,-1,0
  4662.9     0.1       0  4986.3    0.07       0  4992.3     0.1       0
  5033.3    0.05       0
Bank Sta=4986.3,4992.3
Exp/Cntr=0.3,0.1

Type RM Length L Ch R = 1,5308,438,438,438
BEGIN DESCRIPTION:
DEVILS CREEK 12.0
END DESCRIPTION:
XS GIS Cut Line= 3
      2683357.50     10060288.90      2683141.33     10060070.13
      2682826.23     10060010.23
#Sta/Elev= 30
  4673.8 1861.57  4698.0 1859.78  4782.8 1854.65  4818.2 1853.22  4874.8 1849.39
  4931.4 1846.46  4938.4 1845.45  4945.5 1845.39  4959.6 1844.29  4966.7 1842.30
  4973.8 1841.36  4976.8 1839.30  4979.8 1837.24  4989.1 1837.28  4994.4 1834.44
  5001.6 1834.14  5004.4 1833.64  5007.6 1834.14  5025.0 1839.24  5041.3 1844.67
  5075.9 1845.50  5180.3 1844.71  5203.1 1844.68  5218.4 1846.36  5248.9 1853.73
  5255.3 1856.64  5260.4 1857.81  5279.5 1864.80  5298.4 1870.00  5302.1 1870.00
#Mann=5,-1,0
  4673.8     0.1       0  4976.8    0.16       0  5001.6    0.07       0
  5007.6    0.16       0  5180.3     0.1       0
Bank Sta=5001.6,5007.6
Exp/Cntr=0.3,0.1

Type RM Length L Ch R = 1,4870,249,249,249
BEGIN DESCRIPTION:
DEVILS CREEK 11.0
END DESCRIPTION:
XS GIS Cut Line= 3
      2683668.50     10059803.74      2683268.47     10059653.73
      2682868.51     10059753.72
#Sta/Elev= 30
  4556.1 1883.10  4596.2 1877.31  4617.8 1872.39  4626.4 1869.56  4631.8 1870.10
  4711.9 1855.65  4742.1 1853.41  4780.4 1847.41  4861.3 1841.05  4913.0 1838.62
  4962.0 1839.91  4968.2 1836.89  4973.5 1838.08  4980.7 1834.68  4998.4 1834.12
  5001.1 1833.62  5004.4 1834.12  5038.9 1840.71  5135.0 1839.50  5223.8 1839.77
  5239.1 1840.09  5271.9 1843.37  5290.0 1849.97  5295.1 1848.80  5302.9 1852.55
  5331.2 1860.50  5336.4 1859.48  5358.3 1865.98  5372.5 1869.28  5395.6 1871.41
#Mann=10,-1,0
  4556.1    0.05       0  4617.8     0.1       0  4861.3    0.16       0
  4998.4    0.07       0  5004.4    0.16       0  5038.9     0.1       0
  5135.0    0.16       0  5223.8     0.1       0  5239.1    0.16       0
  5358.3     0.1       0
Bank Sta=4998.4,5004.4
Exp/Cntr=0.3,0.1

Type RM Length L Ch R = 1,4621,201,201,201
BEGIN DESCRIPTION:
Mapping XS f7e8b65d
END DESCRIPTION:
XS GIS Cut Line= 2
      2683754.38     10059649.85      2682858.11     10059283.10
#Sta/Elev= 30
  4408.5 1883.93  4422.6 1883.31  4487.9 1875.87  4511.9 1874.82  4517.3 1876.50
  4541.3 1870.43  4546.7 1871.79  4565.3 1867.97  4570.7 1868.60  4594.7 1862.91
  4624.1 1861.11  4648.1 1856.11  4677.6 1853.43  4698.3 1847.03  4722.2 1842.17
  4784.4 1836.70  4869.0 1837.51  4915.2 1837.84  4968.6 1833.92  5004.0 1833.93
  5043.1 1833.86  5045.8 1833.36  5049.1 1833.86  5063.2 1834.18  5094.1 1849.46
  5160.4 1859.96  5214.4 1864.97  5283.8 1866.52  5353.2 1867.68  5376.9 1867.96
#Mann=10,-1,0
  4408.5    0.05       0  4422.6     0.1       0  4698.3    0.05       0
  4722.2     0.1       0  4869.0    0.16       0  5004.0     0.1       0
  5043.1    0.07       0  5049.1     0.1       0  5283.8    0.05       0
  5353.2     0.1       0
Bank Sta=5043.1,5049.1
Exp/Cntr=0.3,0.1

Type RM Length L Ch R = 1,4420,59,59,59
BEGIN DESCRIPTION:
DEVILS CREEK 10.0
END DESCRIPTION:
XS GIS Cut Line= 2
      2683697.99     10059456.73      2682902.48     10059042.72
#Sta/Elev= 30
  4574.5 1879.40  4635.6 1874.72  4701.9 1866.51  4724.0 1862.33  4740.4 1855.55
  4784.7 1841.74  4812.4 1836.69  4851.0 1834.12  4981.2 1833.99  5027.0 1834.11
  5126.4 1834.60  5157.4 1833.44  5160.2 1832.94  5163.4 1833.44  5176.9 1833.80
  5193.3 1841.51  5199.0 1841.81  5205.3 1846.15  5221.1 1849.75  5227.8 1852.77
  5240.0 1854.97  5303.9 1858.55  5348.1 1858.92  5353.7 1857.52  5370.2 1858.26
  5375.8 1856.67  5392.3 1859.19  5397.9 1858.24  5463.1 1858.20  5471.3 1858.30
#Mann=7,-1,0
  4574.5     0.1       0  4981.2    0.16       0  5027.0     0.1       0
  5157.4    0.07       0  5163.4     0.1       0  5240.0    0.05       0
  5463.1     0.1       0
Bank Sta=5157.4,5163.4
Exp/Cntr=0.3,0.1

Type RM Length L Ch R = 1,4361,319,319,319
BEGIN DESCRIPTION:
DEVILS CREEK 9.0
END DESCRIPTION:
XS GIS Cut Line= 6
      2683832.75     10059353.00      2683450.81     10059113.42
      2683384.83     10059231.47      2683249.42     10059148.14
      2683245.95     10058925.92      2682892.58     10058932.74
#Sta/Elev= 30
  4370.6 1879.66  4387.3 1878.71  4453.1 1876.08  4568.6 1865.98  4635.4 1852.61
  4678.2 1838.66  4714.7 1832.73  4814.9 1831.13  4839.5 1834.56  4851.2 1834.50
  4859.5 1836.22  4940.6 1840.09  4955.1 1838.70  4966.0 1840.52  5009.3 1841.22
  5105.1 1840.79  5180.7 1837.96  5329.5 1834.56  5345.7 1832.60  5365.1 1827.54
  5367.8 1827.04  5371.1 1827.54  5402.1 1829.61  5477.3 1844.66  5482.3 1842.12
  5510.4 1848.57  5530.7 1847.47  5539.9 1851.42  5607.5 1858.10  5698.6 1859.78
#Mann=10,-1,0
  4370.6    0.05       0  4387.3     0.1       0  4714.7    0.05       0
  4839.5     0.1       0  4851.2    0.16       0  5009.3     0.1       0
  5180.7    0.05       0  5329.5     0.1       0  5365.1    0.07       0
  5371.1     0.1       0
Bank Sta=5365.1,5371.1
Exp/Cntr=0.3,0.1

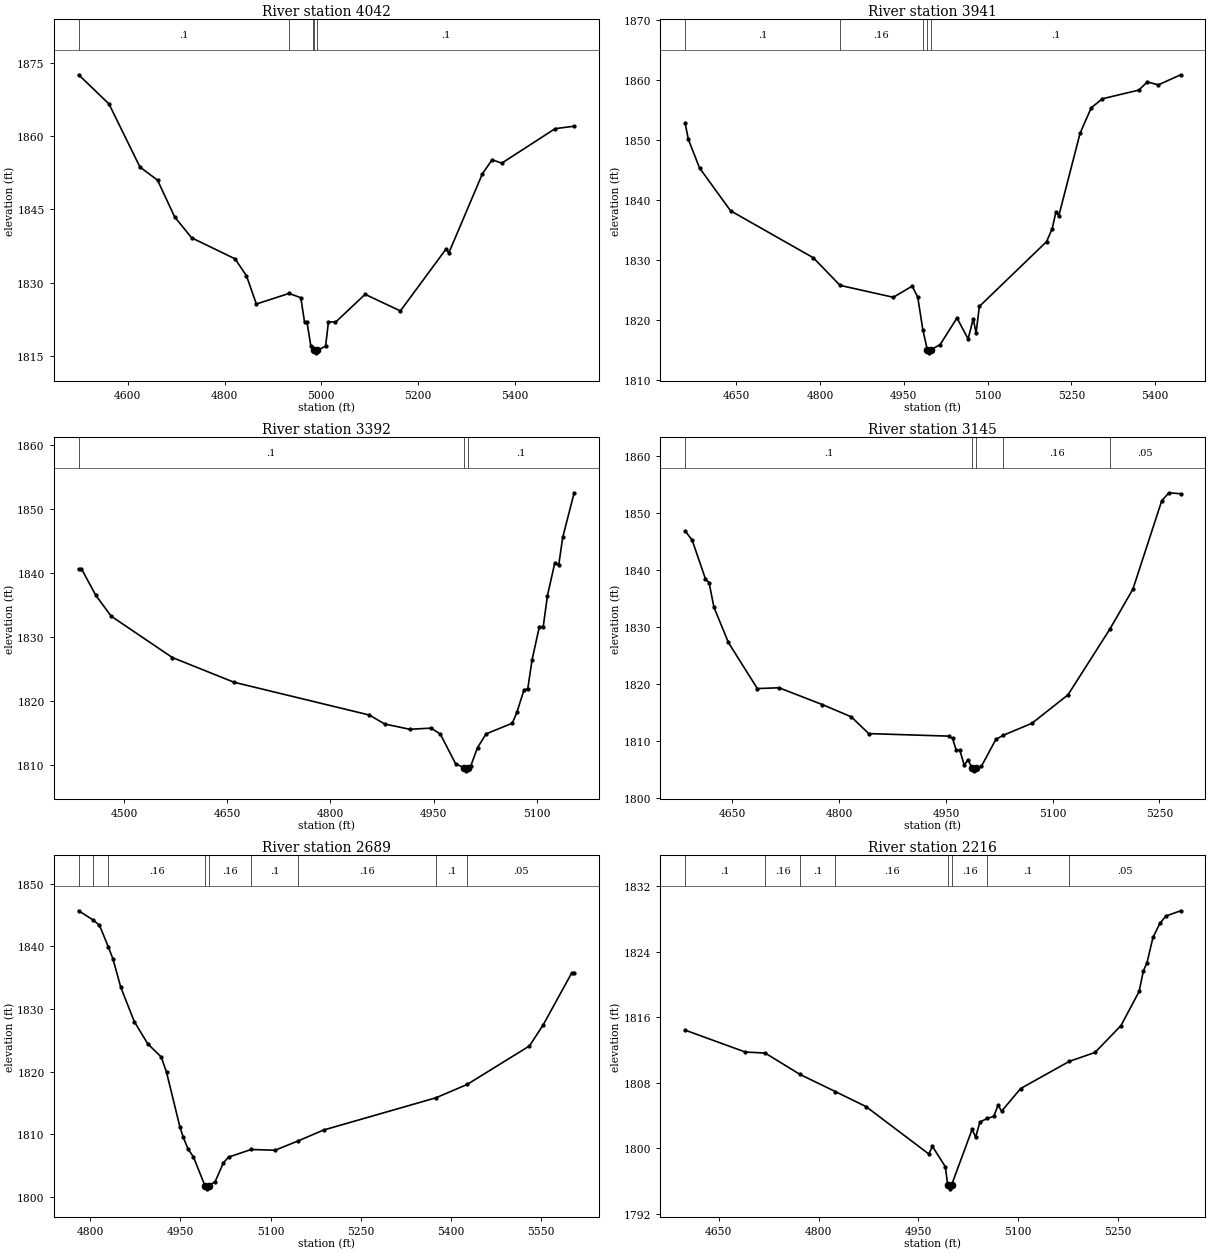
Type RM Length L Ch R = 1,4042,101,101,101
BEGIN DESCRIPTION:
DEVILS CREEK 8.0
END DESCRIPTION:
XS GIS Cut Line= 4
      2683857.02     10059134.22      2683620.95     10058943.28
      2683245.95     10058863.42      2682909.16     10058887.72
#Sta/Elev= 30
  4498.2 1872.59  4560.9 1866.62  4625.0 1853.68  4661.5 1850.96  4696.7 1843.46
  4731.9 1839.16  4821.7 1834.85  4845.3 1831.37  4865.7 1825.59  4933.3 1827.76
  4957.7 1826.88  4965.3 1821.90  4970.4 1821.89  4978.2 1817.08  4982.1 1816.54
  4985.4 1816.08  4988.2 1815.58  4991.4 1816.08  5008.9 1816.94  5014.8 1821.96
  5029.3 1821.85  5090.6 1827.58  5163.5 1824.17  5258.5 1836.94  5263.5 1836.02
  5333.1 1852.28  5353.2 1855.17  5373.2 1854.47  5483.5 1861.54  5522.9 1862.05
#Mann=5,-1,0
  4498.2     0.1       0  4933.3    0.16       0  4982.1     0.1       0
  4985.4    0.07       0  4991.4     0.1       0
Bank Sta=4985.4,4991.4
Exp/Cntr=0.3,0.1

Type RM Length L Ch R = 1,3941,549,549,549
BEGIN DESCRIPTION:
Mapping XS c03407ab
END DESCRIPTION:
XS GIS Cut Line= 2
      2683854.21     10058773.12      2682968.80     10058833.88
#Sta/Elev= 30
  4558.3 1852.80  4564.1 1850.08  4584.1 1845.31  4639.8 1838.15  4788.0 1830.31
  4835.8 1825.71  4931.2 1823.72  4965.0 1825.58  4975.0 1823.74  4984.0 1818.34
  4992.1 1814.95  4994.8 1814.45  4998.1 1814.95  5015.1 1815.82  5045.2 1820.27
  5065.2 1816.76  5074.4 1820.15  5079.4 1817.74  5085.3 1822.19  5205.6 1833.00
  5215.6 1835.12  5222.6 1838.00  5227.6 1837.32  5265.7 1851.10  5285.8 1855.36
  5305.8 1856.85  5370.8 1858.29  5386.0 1859.65  5406.0 1859.17  5445.8 1860.85
#Mann=5,-1,0
  4558.3     0.1       0  4835.8    0.16       0  4984.0     0.1       0
  4992.1    0.07       0  4998.1     0.1       0
Bank Sta=4992.1,4998.1
Exp/Cntr=0.3,0.1

Type RM Length L Ch R = 1,3392,247,247,247
BEGIN DESCRIPTION:
Mapping XS defccbc6
END DESCRIPTION:
XS GIS Cut Line= 2
      2683880.91     10058525.86      2683233.54     10058208.67
#Sta/Elev= 30
  4433.7 1840.65  4437.8 1840.65  4458.7 1836.50  4481.0 1833.25  4570.0 1826.79
  4659.6 1822.93  4856.5 1817.81  4879.0 1816.41  4915.3 1815.58  4946.5 1815.76
  4959.8 1814.84  4982.1 1810.20  4994.1 1809.59  4996.8 1809.09  5000.1 1809.59
  5004.3 1809.89  5014.0 1812.72  5026.6 1814.87  5064.6 1816.53  5071.2 1818.21
  5081.5 1821.70  5087.1 1821.92  5093.4 1826.46  5104.0 1831.62  5109.6 1831.61
  5115.7 1836.45  5126.5 1841.60  5132.1 1841.22  5138.0 1845.59  5154.6 1852.52
#Mann=3,-1,0
  4433.7     0.1       0  4994.1    0.07       0  5000.1     0.1       0
Bank Sta=4994.1,5000.1
Exp/Cntr=0.3,0.1

Type RM Length L Ch R = 1,3145,456,456,456
BEGIN DESCRIPTION:
DEVILS CREEK 7.0
END DESCRIPTION:
XS GIS Cut Line= 3
      2683878.34     10058114.40      2683503.31     10058046.69
      2683192.29     10058098.53
#Sta/Elev= 30
  4583.4 1846.90  4593.4 1845.25  4612.0 1838.47  4617.1 1837.81  4623.9 1833.52
  4644.2 1827.33  4684.9 1819.24  4715.4 1819.38  4776.3 1816.43  4817.0 1814.28
  4841.4 1811.34  4953.6 1810.90  4959.3 1810.49  4964.4 1808.43  4969.5 1808.43
  4975.7 1805.78  4980.8 1806.76  4986.7 1805.31  4989.4 1804.81  4992.7 1805.31
  4999.8 1805.60  5020.1 1810.32  5030.6 1811.05  5070.8 1813.15  5121.5 1818.14
  5180.2 1829.64  5212.7 1836.67  5253.3 1852.20  5263.4 1853.58  5279.8 1853.41
#Mann=5,-1,0
  4583.4     0.1       0  4986.7    0.07       0  4992.7     0.1       0
  5030.6    0.16       0  5180.2    0.05       0
Bank Sta=4986.7,4992.7
Exp/Cntr=0.3,0.1

Type RM Length L Ch R = 1,2689,473,473,473
BEGIN DESCRIPTION:
DEVILS CREEK 6.0
END DESCRIPTION:
XS GIS Cut Line= 3
      2684011.10     10057906.06      2683727.27     10057762.84
      2683224.66     10057825.34
#Sta/Elev= 30
  4780.8 1845.66  4805.0 1844.19  4815.5 1843.35  4829.9 1839.96  4837.8 1838.01
  4851.0 1833.43  4873.4 1827.98  4895.8 1824.43  4918.2 1822.33  4927.0 1819.91
  4949.3 1811.16  4954.9 1809.51  4963.0 1807.61  4971.6 1806.43  4990.9 1801.79
  4993.7 1801.29  4996.9 1801.79  5007.8 1802.42  5021.8 1805.47  5030.2 1806.35
  5067.8 1807.57  5107.6 1807.45  5145.5 1808.92  5188.2 1810.67  5375.0 1815.81
  5427.0 1817.94  5530.8 1824.09  5553.8 1827.48  5600.8 1835.68  5605.2 1835.68
#Mann=9,-1,0
  4780.8     0.1       0  4805.0    0.05       0  4829.9    0.16       0
  4990.9    0.07       0  4996.9    0.16       0  5067.8     0.1       0
  5145.5    0.16       0  5375.0     0.1       0  5427.0    0.05       0
Bank Sta=4990.9,4996.9
Exp/Cntr=0.3,0.1

Type RM Length L Ch R = 1,2216,178,178,178
BEGIN DESCRIPTION:
DEVILS CREEK 5.0
END DESCRIPTION:
XS GIS Cut Line= 3
      2684018.42     10057553.71      2683668.47     10057403.73
      2683318.51     10057503.72
#Sta/Elev= 30
  4599.5 1814.44  4690.1 1811.76  4719.8 1811.64  4771.9 1809.04  4825.1 1806.94
  4871.4 1805.10  4965.7 1799.31  4971.2 1800.24  4990.6 1797.75  4994.1 1795.55
  4996.9 1795.05  5000.1 1795.55  5030.9 1802.33  5036.1 1801.36  5042.6 1803.22
  5053.7 1803.65  5063.4 1803.91  5069.9 1805.29  5075.1 1804.53  5103.7 1807.30
  5176.8 1810.62  5215.5 1811.71  5254.5 1814.99  5281.8 1819.16  5288.3 1821.72
  5293.5 1822.62  5302.6 1825.76  5313.0 1827.48  5322.1 1828.38  5344.2 1829.02
#Mann=8,-1,0
  4599.5     0.1       0  4719.8    0.16       0  4771.9     0.1       0
  4825.1    0.16       0  4994.1    0.07       0  5000.1    0.16       0
  5053.7     0.1       0  5176.8    0.05       0
Bank Sta=4994.1,5000.1
Exp/Cntr=0.3,0.1