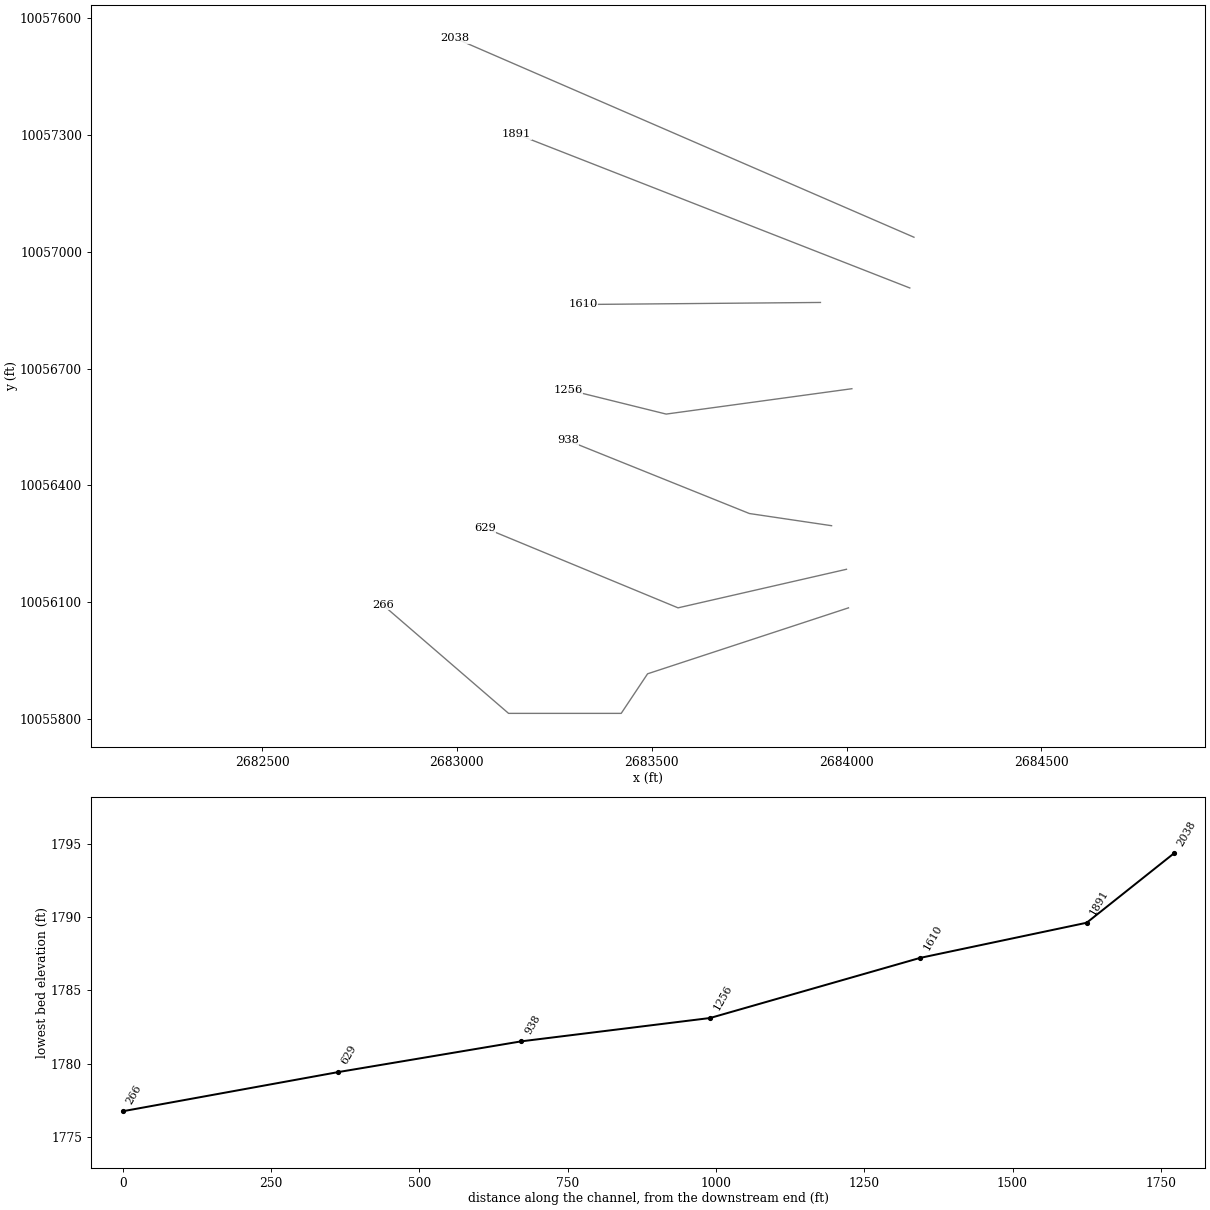
HEC-RAS study DEVILS CREEK.prj: DEVILS CREEK Base Level Engineering

--- DEVILS CREEK.g01 (geometry) --- (continued)

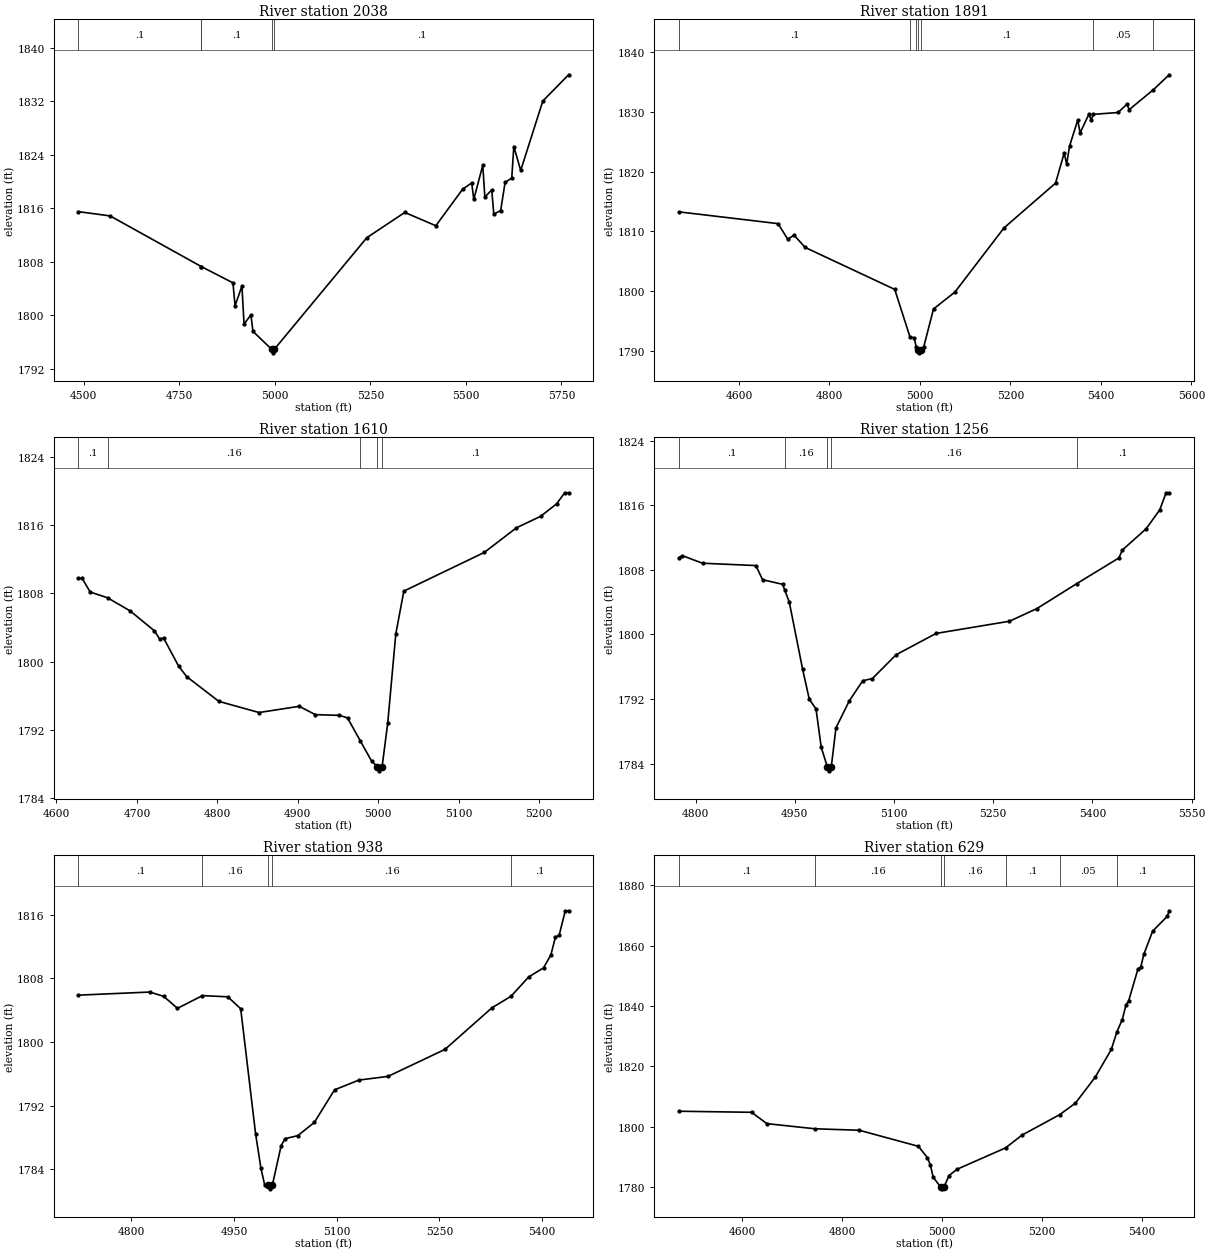
Type RM Length L Ch R = 1,2038,147,147,147
BEGIN DESCRIPTION:
Mapping XS 21f050bc
END DESCRIPTION:
XS GIS Cut Line= 2
      2684173.04     10057037.02      2682995.94     10057547.45
#Sta/Elev= 30
  4485.6 1815.49  4568.8 1814.85  4807.3 1807.27  4807.5 1807.26  4890.2 1804.83
  4895.7 1801.40  4913.7 1804.35  4919.2 1798.67  4937.2 1800.02  4942.6 1797.56
  4992.0 1794.85  4994.8 1794.35  4998.0 1794.85  5240.6 1811.59  5339.9 1815.37
  5421.2 1813.38  5491.6 1818.87  5515.1 1819.78  5520.5 1817.32  5544.0 1822.43
  5549.5 1817.67  5567.5 1818.74  5572.9 1815.12  5590.9 1815.65  5602.4 1819.86
  5619.9 1820.51  5625.3 1825.24  5643.3 1821.66  5701.2 1832.05  5768.6 1835.98
#Mann=5,-1,0
  4485.6     0.1       0  4807.3    0.16       0  4807.5     0.1       0
  4992.0    0.07       0  4998.0     0.1       0
Bank Sta=4992,4998
Exp/Cntr=0.3,0.1

Type RM Length L Ch R = 1,1891,281,281,281
BEGIN DESCRIPTION:
Mapping XS 9dfc881b
END DESCRIPTION:
XS GIS Cut Line= 2
      2684162.37     10056906.79      2683153.40     10057301.70
#Sta/Elev= 30
  4467.4 1813.24  4686.4 1811.27  4707.8 1808.66  4721.8 1809.34  4746.3 1807.28
  4944.3 1800.25  4977.9 1792.31  4987.0 1792.13  4992.2 1790.53  4995.6 1790.12
  4998.3 1789.62  5001.6 1790.12  5008.5 1790.65  5030.0 1796.97  5077.3 1799.80
  5185.9 1810.56  5299.8 1818.06  5318.9 1823.11  5324.3 1821.23  5330.7 1824.26
  5348.7 1828.60  5354.1 1826.48  5373.2 1829.58  5378.6 1828.66  5383.3 1829.58
  5438.2 1829.89  5457.3 1831.27  5462.7 1830.38  5516.0 1833.71  5550.9 1836.21
#Mann=7,-1,0
  4467.4     0.1       0  4977.9    0.16       0  4992.2     0.1       0
  4995.6    0.07       0  5001.6     0.1       0  5383.3    0.05       0
  5516.0     0.1       0
Bank Sta=4995.6,5001.6
Exp/Cntr=0.3,0.1

Type RM Length L Ch R = 1,1610,354,354,354
BEGIN DESCRIPTION:
DEVILS CREEK 4.0
END DESCRIPTION:
XS GIS Cut Line= 2
      2683933.04     10056869.61      2683323.66     10056864.40
#Sta/Elev= 30
  4627.2 1809.76  4632.0 1809.76  4641.8 1808.17  4663.5 1807.49  4691.8 1805.94
  4721.8 1803.61  4728.2 1802.67  4733.2 1802.77  4751.8 1799.49  4761.8 1798.26
  4801.8 1795.36  4851.8 1794.05  4901.8 1794.78  4921.8 1793.80  4951.8 1793.72
  4961.8 1793.42  4977.8 1790.71  4991.8 1788.35  4998.8 1787.72  5001.5 1787.22
  5004.8 1787.72  5011.8 1792.82  5021.8 1803.25  5031.8 1808.27  5131.8 1812.80
  5171.8 1815.69  5201.8 1817.03  5221.8 1818.50  5231.7 1819.79  5236.6 1819.79
#Mann=5,-1,0
  4627.2     0.1       0  4663.5    0.16       0  4977.8     0.1       0
  4998.8    0.07       0  5004.8     0.1       0
Bank Sta=4998.8,5004.8
Exp/Cntr=0.3,0.1

Type RM Length L Ch R = 1,1256,318,318,318
BEGIN DESCRIPTION:
DEVILS CREEK 3.0
END DESCRIPTION:
XS GIS Cut Line= 3
      2684013.72     10056648.25      2683537.16     10056583.15
      2683284.56     10056645.65
#Sta/Elev= 30
  4774.8 1809.52  4780.1 1809.75  4810.4 1808.82  4891.1 1808.53  4901.2 1806.78
  4931.5 1806.21  4934.7 1805.51  4941.6 1804.00  4961.8 1795.68  4971.9 1791.97
  4982.0 1790.79  4989.9 1786.04  4999.1 1783.62  5001.9 1783.12  5005.1 1783.62
  5012.2 1788.45  5032.4 1791.79  5052.6 1794.27  5067.3 1794.55  5103.1 1797.49
  5163.6 1800.13  5274.5 1801.64  5315.9 1803.20  5376.0 1806.28  5439.9 1809.47
  5445.3 1810.46  5481.1 1813.08  5501.7 1815.42  5511.4 1817.54  5516.0 1817.54
#Mann=5,-1,0
  4774.8     0.1       0  4934.7    0.16       0  4999.1    0.07       0
  5005.1    0.16       0  5376.0     0.1       0
Bank Sta=4999.1,5005.1
Exp/Cntr=0.3,0.1

Type RM Length L Ch R = 1,938,309,309,309
BEGIN DESCRIPTION:
DEVILS CREEK 2.0
END DESCRIPTION:
XS GIS Cut Line= 3
      2683961.63     10056296.69      2683750.70     10056327.94
      2683284.53     10056515.45
#Sta/Elev= 30
  4722.9 1805.89  4827.2 1806.28  4847.4 1805.74  4867.6 1804.23  4904.0 1805.83
  4941.1 1805.68  4959.9 1804.18  4981.7 1788.42  4989.4 1784.14  4994.8 1782.06
  5000.2 1782.03  5003.0 1781.53  5006.2 1782.03  5019.0 1786.97  5024.8 1787.84
  5043.2 1788.22  5067.4 1789.88  5096.9 1793.98  5132.6 1795.21  5174.9 1795.67
  5258.2 1799.07  5326.6 1804.29  5354.6 1805.75  5380.5 1808.19  5402.0 1809.32
  5412.8 1810.95  5419.4 1813.20  5424.8 1813.42  5433.8 1816.50  5438.6 1816.50
#Mann=5,-1,0
  4722.9     0.1       0  4904.0    0.16       0  5000.2    0.07       0
  5006.2    0.16       0  5354.6     0.1       0
Bank Sta=5000.2,5006.2
Exp/Cntr=0.3,0.1

Type RM Length L Ch R = 1,629,363,363,363
BEGIN DESCRIPTION:
Mapping XS 23e4e0e0
END DESCRIPTION:
XS GIS Cut Line= 3
      2683999.87     10056184.84      2683567.56     10056085.88
      2683071.78     10056290.94
#Sta/Elev= 30
  4473.8 1805.13  4618.9 1804.78  4649.6 1801.02  4745.8 1799.32  4834.3 1798.83
  4952.6 1793.50  4970.4 1789.76  4976.5 1787.31  4981.9 1783.33  4997.4 1779.93
  5000.1 1779.43  5003.4 1779.93  5013.7 1783.84  5029.7 1785.91  5126.7 1792.99
  5160.0 1797.27  5234.8 1803.98  5266.4 1807.81  5305.9 1816.41  5338.2 1825.62
  5349.2 1831.38  5360.0 1835.48  5367.5 1840.34  5372.9 1841.77  5391.4 1852.25
  5396.8 1852.77  5403.3 1857.19  5420.7 1864.76  5450.0 1869.68  5453.8 1871.52
#Mann=7,-1,0
  4473.8     0.1       0  4745.8    0.16       0  4997.4    0.07       0
  5003.4    0.16       0  5126.7     0.1       0  5234.8    0.05       0
  5349.2     0.1       0
Bank Sta=4997.4,5003.4
Exp/Cntr=0.3,0.1

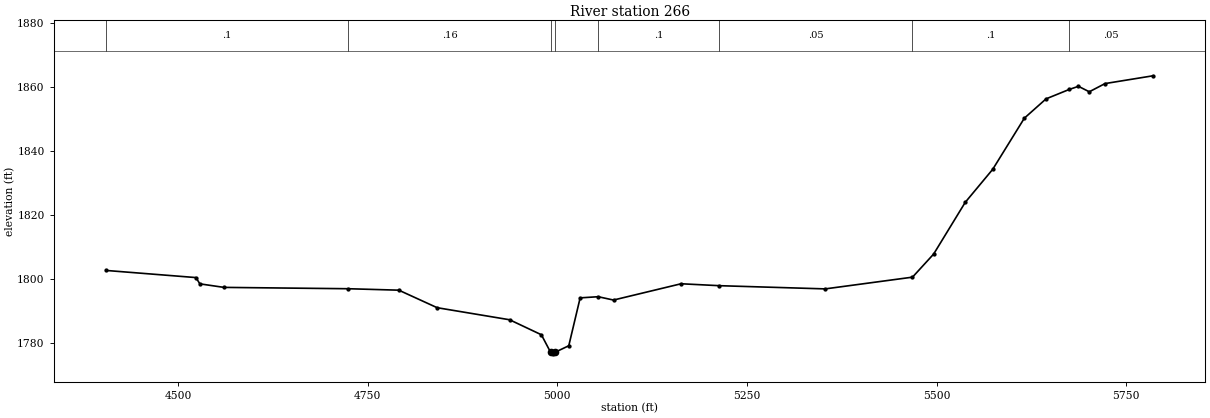
Type RM Length L Ch R = 1,266,0,0,0
BEGIN DESCRIPTION:
DEVILS CREEK 1.0
END DESCRIPTION:
XS GIS Cut Line= 5
      2684005.04     10056085.87      2683489.43     10055916.61
      2683421.72     10055815.05      2683132.66     10055815.05
      2682809.77     10056093.67
#Sta/Elev= 30
  4405.2 1802.77  4523.5 1800.55  4528.7 1798.59  4560.5 1797.49  4724.5 1797.07
  4791.0 1796.62  4841.6 1791.15  4937.1 1787.39  4979.0 1782.71  4991.1 1777.26
  4993.8 1776.76  4997.1 1777.26  5015.1 1779.28  5030.1 1794.22  5053.9 1794.58
  5074.1 1793.54  5163.2 1798.62  5213.6 1798.02  5353.2 1797.02  5468.3 1800.68
  5496.2 1807.89  5537.9 1824.04  5574.1 1834.33  5615.8 1850.28  5644.4 1856.30
  5675.2 1859.26  5687.1 1860.21  5701.4 1858.51  5722.2 1861.07  5785.5 1863.50
#Mann=8,-1,0
  4405.2     0.1       0  4724.5    0.16       0  4991.1    0.07       0
  4997.1    0.16       0  5053.9     0.1       0  5213.6    0.05       0
  5468.3     0.1       0  5675.2    0.05       0
Bank Sta=4991.1,4997.1
Exp/Cntr=0.3,0.1

Chan Stop Cuts=-1