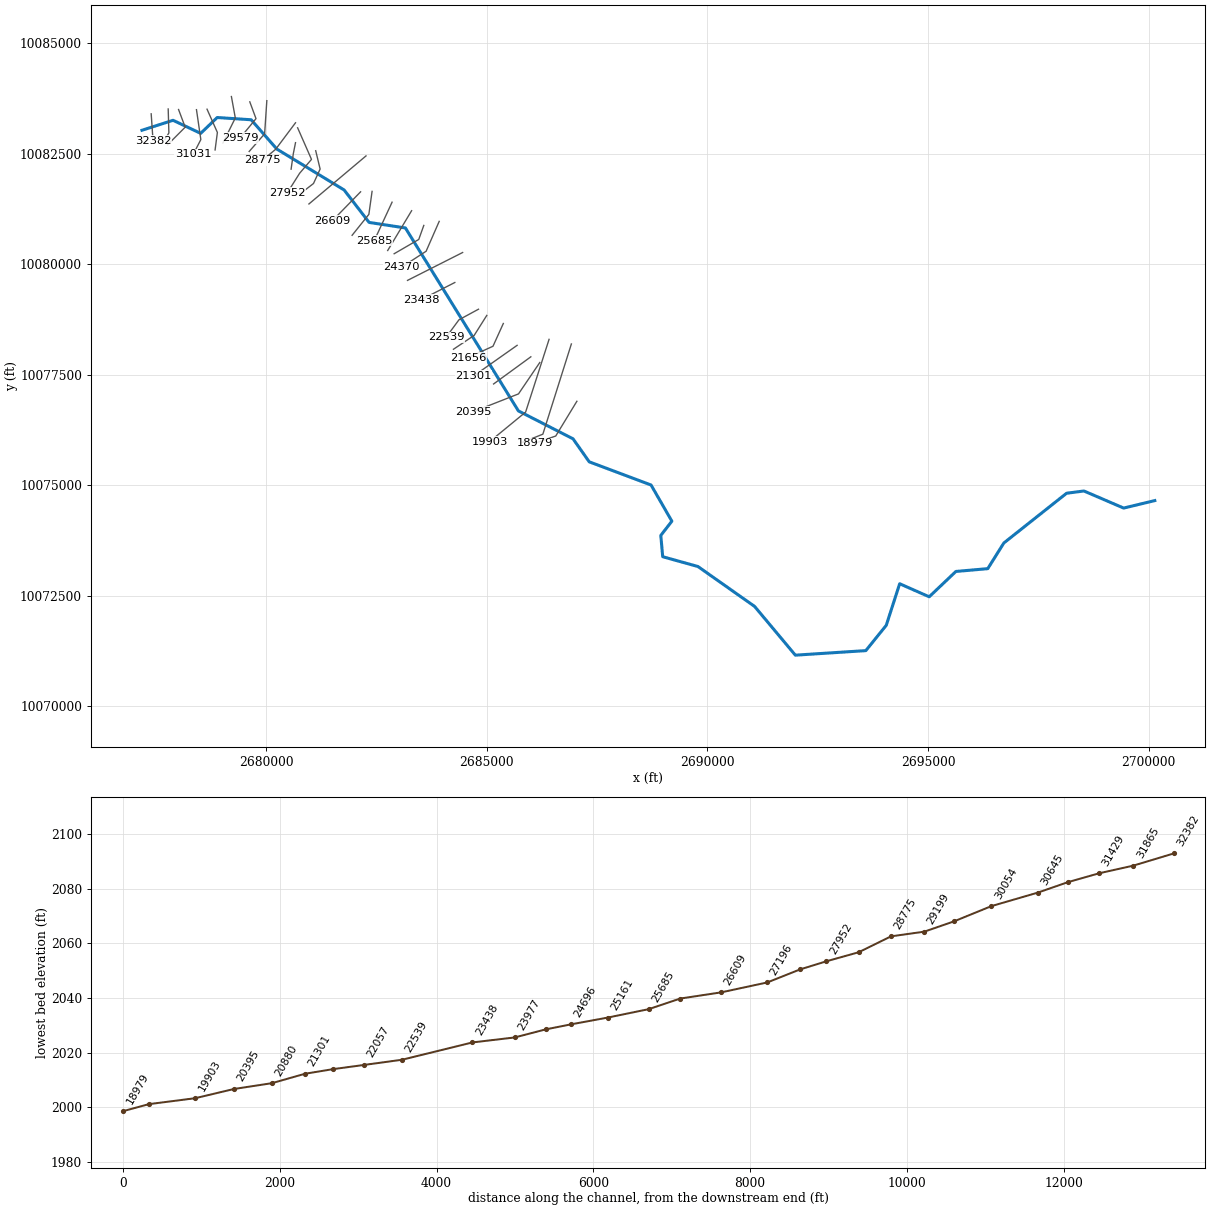
--- DITTMAR CREEK.prj (project) ---

Proj Title=DITTMAR CREEK Base Level Engineering
Current Plan=p01
Default Exp/Contr=0.3,0.1
English Units
Geom File=g01
Flow File=f01
Plan File=p01
Y Axis Title=Elevation
X Axis Title(PF)=Main Channel Distance
X Axis Title(XS)=Station
BEGIN DESCRIPTION:
DITTMAR CREEK
END DESCRIPTION:
DSS Export Rating Curves= 0
DSS Export Rating Curve Sorted= 0
DSS Export Volume Flow Curves= 0
DXF OffsetX= 0
DXF OffsetY= 0
DXF ScaleX= 1
DXF ScaleY= 10

--- DITTMAR CREEK.p01 (plan) ---

Plan Title=Multiple Run
Short Identifier=Multiple
Geom File=g01
Flow File=f01
Subcritical Flow
K Sum by GR= 0
Std Step Tol= 0.01
Critical Tol= 0.01
Num of Std Step Trials= 20
Max Error Tol= 0.3
Flow Tol Ratio= 0.001
Split Flow NTrial= 30
Split Flow Tol= 0.02
Split Flow Ratio= 0.02
Log Output Level= 0
Friction Slope Method= 1
Unsteady Friction Slope Method= 2
Unsteady Bridges Friction Slope Method= 1
Parabolic Critical Depth
Global Vel Dist=  1 , 1 , 1
Global Log Level= 0
CheckData=True
Encroach Param= -1, 0, 0, 0
BEGIN DESCRIPTION:
Multiple Run
END DESCRIPTION:

--- DITTMAR CREEK.f01 (steady flow) ---

Flow Title=Multiple
Program Version=4.10
Number of Profiles= 7
Profile Names=10-year,25-year,50-year,1pct_min,100-year,1pct_plu,500-year
River Rch & RM=DITTMAR CREEK,Reach-1         ,32382
    1032    1496    1894    1748    2364    3198    3685
River Rch & RM=DITTMAR CREEK,Reach-1         ,31865
    1306    1911    2435    2260    3056    4133    4816
River Rch & RM=DITTMAR CREEK,Reach-1         ,27196
    2754    4179    5456    5175    6998    9464   11524
River Rch & RM=DITTMAR CREEK,Reach-1         ,23977
    3222    4910    6429    6110    8263   11175   13667
River Rch & RM=DITTMAR CREEK,Reach-1         ,19903
    3488    5326    6983    6643    8983   12149   14886
River Rch & RM=DITTMAR CREEK,Reach-1         ,17054
    3735    5719    7512    7158    9681   13092   16097
River Rch & RM=DITTMAR CREEK,Reach-1         ,14131
    4401    6774    8930    8537   11545   15613   19315
River Rch & RM=DITTMAR CREEK,Reach-1         ,7718
    4789    7395    9770    9358   12655   17115   21256
River Rch & RM=DITTMAR CREEK,Reach-1         ,3756
    4927    7607   10049    9623   13014   17600   21850
Boundary for River Rch & Prof#=DITTMAR CREEK,Reach-1         , 1
Up Type= 0
Dn Type= 3
Dn Slope=0.007
Boundary for River Rch & Prof#=DITTMAR CREEK,Reach-1         , 2
Up Type= 0
Dn Type= 3
Dn Slope=0.007
Boundary for River Rch & Prof#=DITTMAR CREEK,Reach-1         , 3
Up Type= 0
Dn Type= 3
Dn Slope=0.007
Boundary for River Rch & Prof#=DITTMAR CREEK,Reach-1         , 4
Up Type= 0
Dn Type= 3
Dn Slope=0.007
Boundary for River Rch & Prof#=DITTMAR CREEK,Reach-1         , 5
Up Type= 0
Dn Type= 3
Dn Slope=0.007
Boundary for River Rch & Prof#=DITTMAR CREEK,Reach-1         , 6
Up Type= 0
Dn Type= 3
Dn Slope=0.007
Boundary for River Rch & Prof#=DITTMAR CREEK,Reach-1         , 7
Up Type= 0
Dn Type= 3
Dn Slope=0.007
DSS Import GetInterval= 0
DSS Import GetPeak= 0
DSS Import FillOption= 0

--- DITTMAR CREEK.g01 (geometry) ---

Geom Title=Existing Conditions
Program Version=4.10

River Reach=DITTMAR CREEK   ,Reach-1
Reach XY= 30
      2677188.47     10083033.73      2677893.55     10083259.91
      2678519.27     10082963.98      2678893.77     10083322.37
      2679662.94     10083272.02      2680245.64     10082608.48
      2681769.37     10081683.51      2682335.82     10080948.73
      2683158.53     10080823.38      2685718.47     10076683.73
      2686957.45     10076051.28      2687322.72     10075531.68
       2688724.8     10075006.04      2689196.36     10074187.61
      2688945.49     10073865.17      2688988.47     10073383.73
       2689787.5     10073161.39      2691071.27     10072258.55
      2691994.24     10071155.59      2693591.36     10071258.66
      2694053.92      10071830.9      2694358.27     10072772.16
      2695027.26     10072476.53      2695631.78     10073049.94
      2696353.81     10073113.55      2696719.03     10073694.62
      2698140.15      10074819.7      2698532.94     10074871.14
      2699433.42     10074484.38      2700138.47     10074653.73

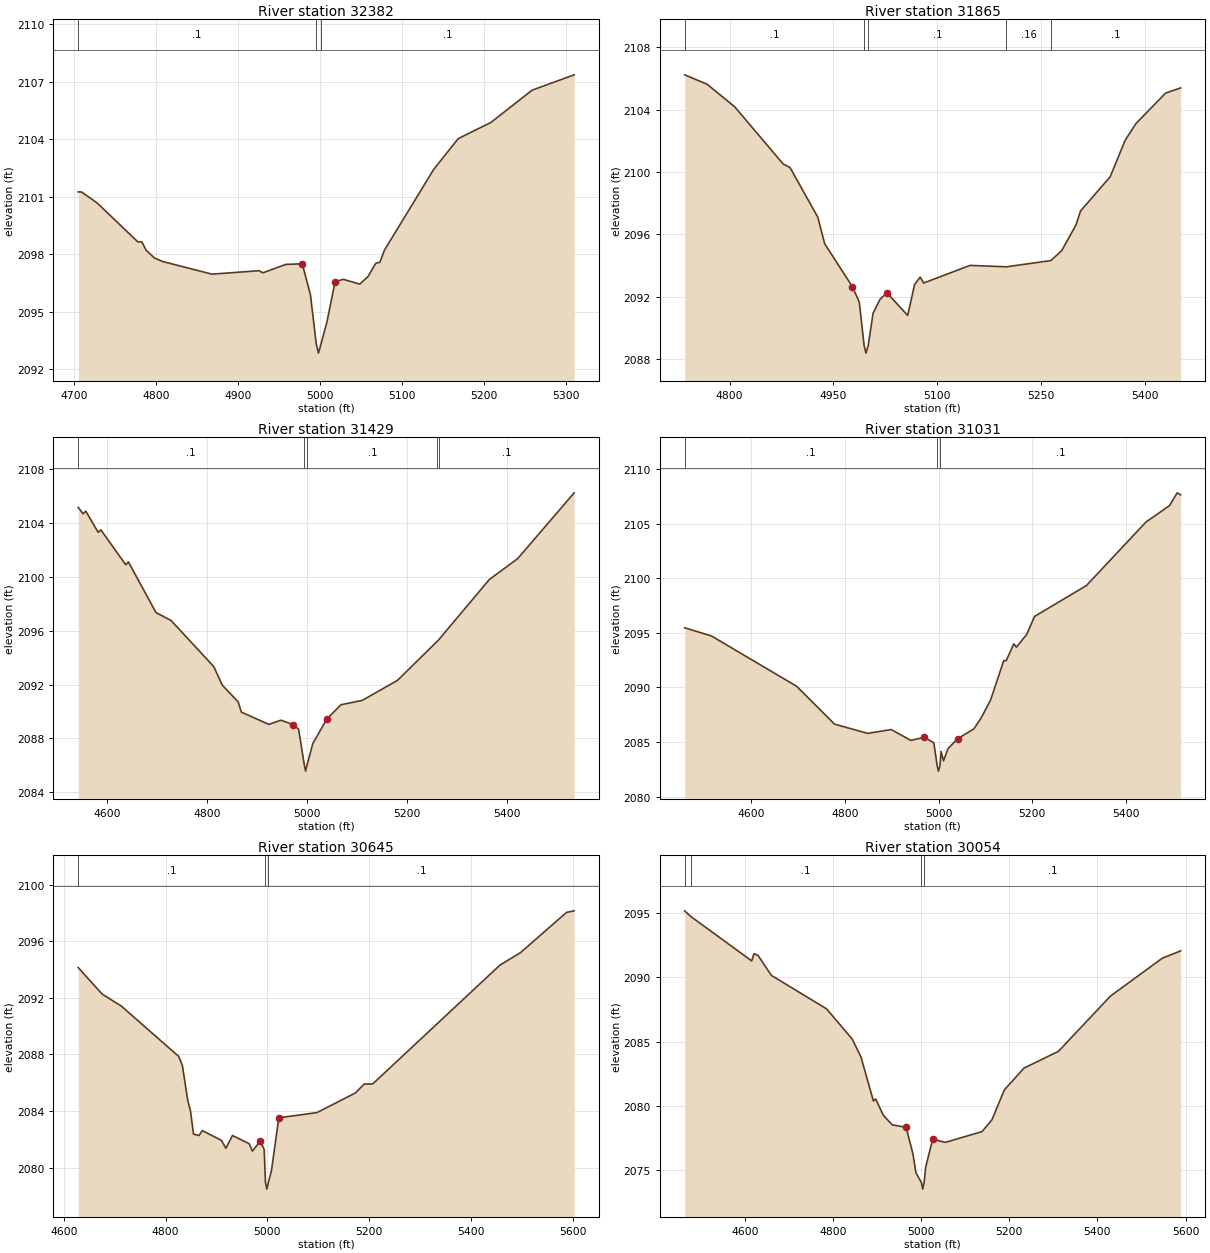
Type RM Length L Ch R = 1 ,32382   ,517,517,517
BEGIN DESCRIPTION:
DITTMAR CREEK 71.0
END DESCRIPTION:
XS GIS Cut Line= 2
      2677398.14     10083406.67      2677439.81     10082802.51
#Sta/Elev= 30
  4704.9 2101.25  4708.9 2101.25  4727.9 2100.68  4777.6 2098.65  4782.7 2098.64
    4788  2098.2  4798.1  2097.8  4808.1 2097.62  4868.2 2096.96  4925.5 2097.14
  4930.5 2097.03  4958.4 2097.47  4978.5  2097.5  4988.5 2095.88  4995.5 2093.34
  4998.3 2092.84  5001.5 2093.34  5008.6 2094.46  5018.6 2096.57  5028.6 2096.69
  5048.7 2096.44  5058.7 2096.83  5068.3 2097.53  5073.3 2097.58  5078.7  2098.2
  5138.9 2102.42  5168.9 2104.03    5209 2104.88  5259.2 2106.56  5310.5 2107.36
#Mann= 3 ,-1 , 0
  4704.9      .1       0  4995.5     .07       0  5001.5      .1       0
Bank Sta=4978.5,5018.6
XS Rating Curve= 0 ,0
Exp/Cntr=0.3,0.1

Type RM Length L Ch R = 1 ,31865   ,436,436,436
BEGIN DESCRIPTION:
DITTMAR CREEK 70.0
END DESCRIPTION:
XS GIS Cut Line= 3
      2677783.56     10083516.02      2677799.18     10082974.36
      2677710.62     10082823.29
#Sta/Elev= 30
  4735.2 2106.23  4767.5 2105.63  4807.5 2104.18  4877.5 2100.51  4887.5 2100.28
  4927.6  2097.1  4937.6 2095.39  4977.6 2092.64  4987.6 2091.65  4994.6 2088.87
  4997.3 2088.37  5000.6 2088.87  5007.6 2090.93  5017.6 2091.82  5027.6 2092.24
  5057.6 2090.79  5067.6 2092.77  5075.7 2093.25  5080.7 2092.87  5147.7    2094
  5200.4 2093.91  5264.7 2094.31  5280.3 2094.95    5301  2096.6  5307.5 2097.49
  5350.4 2099.69  5371.9 2102.02  5387.6  2103.1  5430.5 2105.06  5452.2 2105.39
#Mann= 5 ,-1 , 0
  4735.2      .1       0  4994.6     .07       0  5000.6      .1       0
  5200.4     .16       0  5264.7      .1       0
Bank Sta=4977.6,5027.6
XS Rating Curve= 0 ,0
Exp/Cntr=0.3,0.1

Type RM Length L Ch R = 1 ,31429   ,398,398,398
BEGIN DESCRIPTION:
DITTMAR CREEK 69.0
END DESCRIPTION:
XS GIS Cut Line= 3
      2678018.47     10083503.71      2678168.47     10083103.73
      2677768.44     10082703.71
#Sta/Elev= 30
  4542.5 2105.15  4552.3 2104.67  4557.6 2104.87  4582.5  2103.3  4587.9 2103.48
  4637.7 2100.89    4643  2101.1  4698.2 2097.34  4728.5 2096.75  4813.9 2093.33
  4830.8 2091.96  4862.9  2090.7  4869.1 2089.95  4924.3 2089.04  4948.3 2089.35
  4973.2 2089.02  4983.8 2088.68    4995 2086.07  4997.7 2085.57    5001 2086.07
  5012.1 2087.61  5040.4 2089.45  5068.7  2090.5  5111.1 2090.82  5181.8 2092.31
  5261.8 2095.23  5264.9 2095.35  5365.7  2099.8  5422.2 2101.34  5535.4 2106.23
#Mann= 5 ,-1 , 0
  4542.5      .1       0    4995     .07       0    5001      .1       0
  5261.8     .16       0  5264.9      .1       0
Bank Sta=4973.2,5040.4
XS Rating Curve= 0 ,0
Exp/Cntr=0.3,0.1

Type RM Length L Ch R = 1 ,31031   ,386,386,386
BEGIN DESCRIPTION:
DITTMAR CREEK 68.0
END DESCRIPTION:
XS GIS Cut Line= 3
      2678424.19     10083500.37      2678523.14     10082823.32
      2678351.26     10082489.96
#Sta/Elev= 30
  4457.6 2095.47  4514.8 2094.72  4696.7 2090.11  4777.6 2086.64  4848.3 2085.79
  4898.9 2086.14  4940.5 2085.15  4969.6 2085.43  4989.8 2084.92  4996.9 2082.83
  4999.7 2082.33  5002.9 2082.83  5005.4 2084.14  5010.4 2083.27  5020.1 2084.39
  5040.4  2085.3  5075.3  2086.2  5090.9 2087.21  5111.1 2088.86  5139.1 2092.46
  5144.4 2092.46  5160.6    2094  5166.2 2093.69  5188.4 2094.88  5204.9 2096.51
  5315.7 2099.34  5443.1 2105.17    5493 2106.66  5509.6 2107.84  5516.9 2107.65
#Mann= 3 ,-1 , 0
  4457.6      .1       0  4996.9     .07       0  5002.9      .1       0
Bank Sta=4969.6,5040.4
XS Rating Curve= 0 ,0
Exp/Cntr=0.3,0.1

Type RM Length L Ch R = 1 ,30645   ,591,591,591
BEGIN DESCRIPTION:
DITTMAR CREEK 67.0
END DESCRIPTION:
XS GIS Cut Line= 3
      2678663.78     10083510.79      2678898.14     10082984.78
      2678846.06     10082588.95
#Sta/Elev= 30
  4628.1 2094.14  4675.3 2092.26  4712.5 2091.43  4825.7 2087.86  4832.9 2087.22
  4843.4 2084.77  4848.9 2083.99  4854.8 2082.37  4865.7 2082.27  4872.1 2082.62
  4909.5 2081.93  4918.6 2081.37  4931.4 2082.27  4964.3 2081.69  4970.5 2081.17
  4986.2 2081.87  4993.8 2081.28  4996.2 2078.98    4999 2078.48  5002.2 2078.98
  5008.1  2079.8  5022.5 2083.52  5097.6 2083.89  5172.8 2085.27  5190.6 2085.91
    5207 2085.91  5457.2 2094.31  5497.5 2095.19  5588.3 2098.04  5603.2 2098.15
#Mann= 3 ,-1 , 0
  4628.1      .1       0  4996.2     .07       0  5002.2      .1       0
Bank Sta=4986.2,5022.5
XS Rating Curve= 0 ,0
Exp/Cntr=0.3,0.1

Type RM Length L Ch R = 1 ,30054   ,475,475,475
BEGIN DESCRIPTION:
DITTMAR CREEK 66.0
END DESCRIPTION:
XS GIS Cut Line= 3
      2679215.85     10083797.31      2679304.39      10083312.9
      2679023.14     10082745.18
#Sta/Elev= 30
  4462.9 2095.16  4476.4 2094.73  4615.2 2091.27  4620.3 2091.83  4629.2 2091.71
  4659.7 2090.15    4785 2087.55  4843.3  2085.2    4863 2083.82  4891.5 2080.39
  4896.6 2080.55  4913.8 2079.29  4934.2 2078.54  4965.6 2078.35  4981.1  2076.3
  4987.9 2074.83  5000.5 2074.05  5003.3 2073.55  5006.5 2074.05  5010.2 2075.27
    5026 2077.43  5054.8 2077.18  5138.1 2078.02  5160.5 2078.93  5188.8 2081.26
  5233.4 2082.95  5311.5 2084.25  5429.6 2088.54  5547.3 2091.48  5588.9 2092.05
#Mann= 4 ,-1 , 0
  4462.9     .16       0  4476.4      .1       0  5000.5     .07       0
  5006.5      .1       0
Bank Sta=4965.6,5026
XS Rating Curve= 0 ,0
Exp/Cntr=0.3,0.1

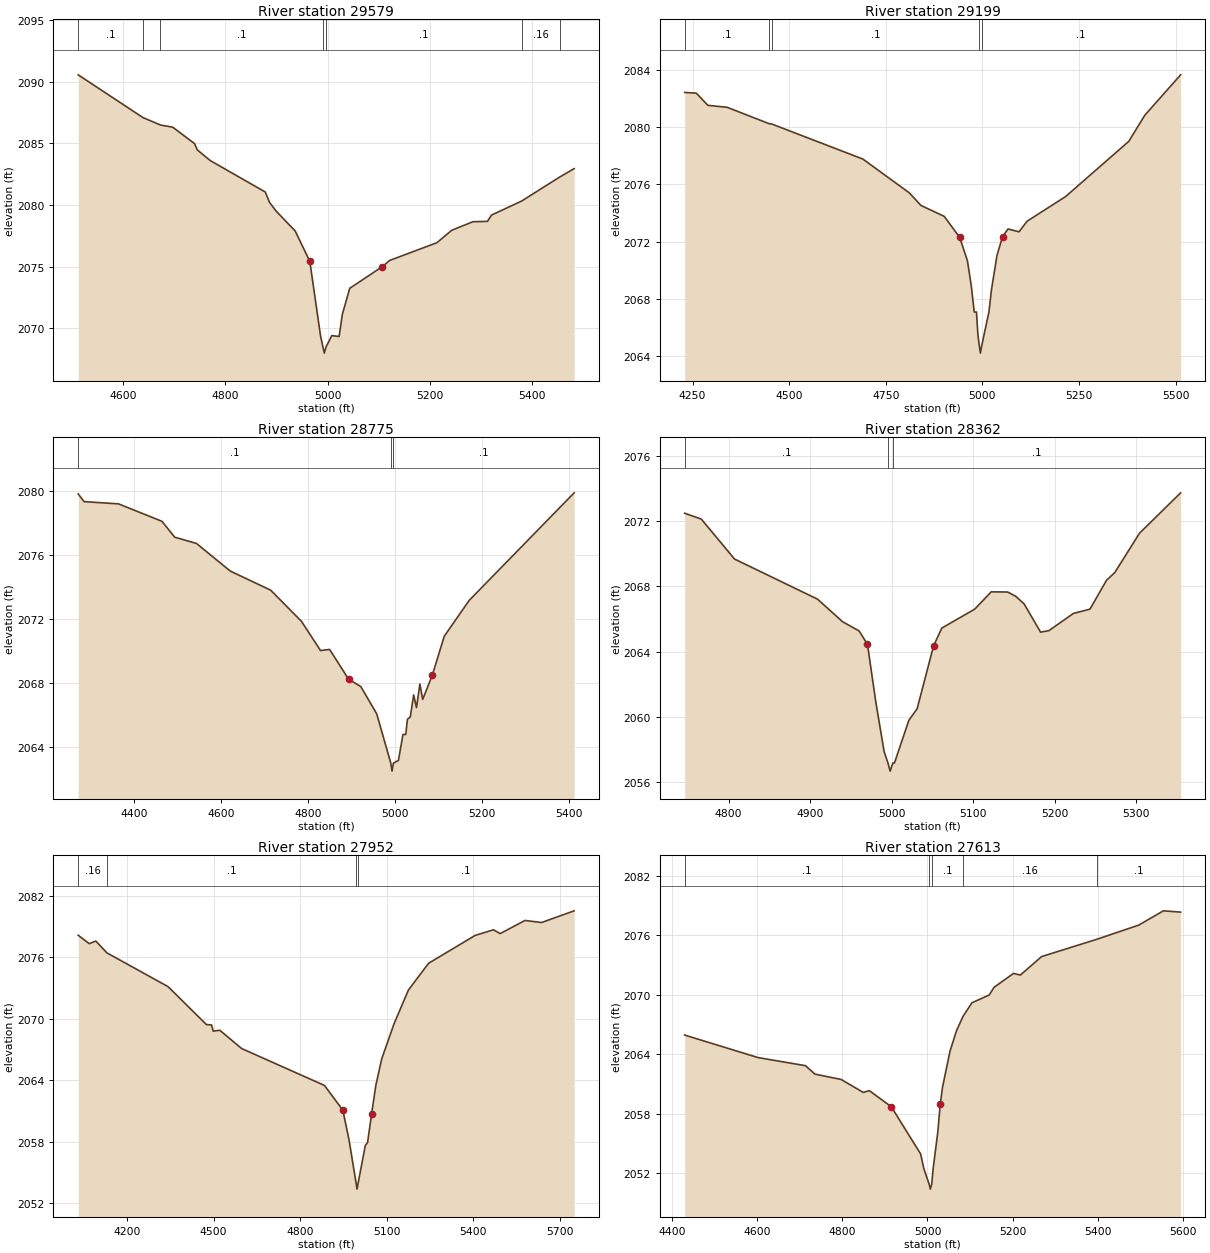
Type RM Length L Ch R = 1 ,29579   ,380,380,380
BEGIN DESCRIPTION:
DITTMAR CREEK 65.0
END DESCRIPTION:
XS GIS Cut Line= 3
      2679632.52     10083677.47      2679773.14     10083297.28
      2679413.79     10082859.81
#Sta/Elev= 30
  4511.6 2090.57  4638.5  2087.1  4672.6  2086.5  4696.8 2086.32  4739.5 2084.99
  4744.9 2084.48    4770 2083.62  4878.1 2081.06  4886.2 2080.23  4899.4 2079.51
  4936.6  2077.9  4965.3 2075.44  4986.3 2069.39    4991 2068.49  4993.7 2067.99
    4997 2068.49  5008.3 2069.41  5022.7 2069.34  5029.1 2071.15  5043.5 2073.25
  5107.4 2075.01  5121.7 2075.51  5214.3 2076.95    5243 2077.95  5284.6 2078.65
  5313.3 2078.68  5321.2 2079.19  5380.3 2080.33  5454.5 2082.27  5483.1 2082.96
#Mann= 7 ,-1 , 0
  4511.6      .1       0  4638.5     .16       0  4672.6      .1       0
    4991     .07       0    4997      .1       0  5380.3     .16       0
  5454.5      .1       0
Bank Sta=4965.3,5107.4
XS Rating Curve= 0 ,0
Exp/Cntr=0.3,0.1

Type RM Length L Ch R = 1 ,29199   ,424,424,424
BEGIN DESCRIPTION:
DITTMAR CREEK 64.0
END DESCRIPTION:
XS GIS Cut Line= 3
      2680018.47     10083703.73      2679968.47     10082953.73
      2679618.45     10082553.71
#Sta/Elev= 30
  4229.7 2082.41  4259.8 2082.36  4289.8 2081.51  4339.9 2081.37  4448.1 2080.23
  4454.6 2080.21  4690.7 2077.76    4811  2075.4  4841.1 2074.52  4901.2 2073.76
  4941.3 2072.29  4961.3 2070.66  4971.3  2068.9  4978.9 2067.08  4984.7 2067.08
  4988.5 2065.46  4992.1 2064.71  4994.9 2064.21  4998.1 2064.71    5017 2067.09
  5023.6 2068.65  5037.8 2071.04  5052.1 2072.33  5066.3 2072.88  5094.8 2072.68
  5115.7 2073.42  5215.3 2075.14  5378.6 2078.99  5420.3 2080.82  5512.9 2083.64
#Mann= 5 ,-1 , 0
  4229.7      .1       0  4448.1     .16       0  4454.6      .1       0
  4992.1     .07       0  4998.1      .1       0
Bank Sta=4941.3,5052.1
XS Rating Curve= 0 ,0
Exp/Cntr=0.3,0.1

Type RM Length L Ch R = 1 ,28775   ,413,413,413
BEGIN DESCRIPTION:
DITTMAR CREEK 63.0
END DESCRIPTION:
XS GIS Cut Line= 3
      2680668.49     10083203.76      2680218.47     10082603.73
      2679918.43      10082353.7
#Sta/Elev= 30
  4271.3 2079.81  4284.9 2079.33    4364 2079.19    4464  2078.1  4493.2 2077.11
  4543.2 2076.72  4621.3 2074.99    4714  2073.8  4784.9 2071.85  4828.6 2070.03
  4849.5  2070.1  4893.2 2068.24  4921.3 2067.78  4957.8 2066.08  4990.2    2063
    4993  2062.5  4996.2    2063  5007.8 2063.17  5018.2 2064.79  5024.6 2064.79
  5028.5 2065.74    5035 2065.88  5042.8 2067.26  5049.3 2066.47  5057.1 2067.94
  5063.6 2066.98  5085.8  2068.5  5113.1 2070.92  5170.4 2073.16  5411.9 2079.88
#Mann= 3 ,-1 , 0
  4271.3      .1       0  4990.2     .07       0  4996.2      .1       0
Bank Sta=4893.2,5085.8
XS Rating Curve= 0 ,0
Exp/Cntr=0.3,0.1

Type RM Length L Ch R = 1 ,28362   ,410,410,410
BEGIN DESCRIPTION:
DITTMAR CREEK 62.0
END DESCRIPTION:
XS GIS Cut Line= 3
      2680668.46     10082753.69      2680618.47     10082503.73
      2680568.46      10082153.7
#Sta/Elev= 30
  4746.2 2072.49  4766.6 2072.13  4807.4 2069.68  4909.3 2067.22  4939.9 2065.84
  4960.3 2065.27  4970.5 2064.45  4980.7 2060.92  4990.9 2057.88  4995.6 2057.18
  4998.3 2056.68  5001.6 2057.18  5003.6 2057.18  5021.3  2059.8  5031.4  2060.5
  5051.6 2064.36  5061.7 2065.45  5102.1 2066.61  5122.3 2067.67  5142.5 2067.66
  5152.6 2067.39  5162.7 2066.93  5182.9  2065.2    5193 2065.29  5223.3 2066.35
  5243.5 2066.61  5263.8 2068.38  5273.9 2068.85  5304.2 2071.26  5354.7 2073.74
#Mann= 3 ,-1 , 0
  4746.2      .1       0  4995.6     .07       0  5001.6      .1       0
Bank Sta=4970.5,5051.6
XS Rating Curve= 0 ,0
Exp/Cntr=0.3,0.1

Type RM Length L Ch R = 1 ,27952   ,339,339,339
BEGIN DESCRIPTION:
DITTMAR CREEK 61.0
END DESCRIPTION:
XS GIS Cut Line= 4
      2680716.46     10083089.72      2681030.43     10082375.32
      2680761.96     10082061.34      2680480.88     10081617.05
#Sta/Elev= 30
  4030.9 2078.15    4069 2077.33  4092.1 2077.58  4130.4 2076.43  4342.2 2073.14
  4475.3 2069.44  4493.2  2069.4  4498.7  2068.8    4522 2068.88  4597.5  2067.1
  4884.6  2063.5  4948.3 2061.09  4970.2 2058.12  4994.7 2053.89  4997.4 2053.39
  5000.7 2053.89  5026.2 2057.65  5033.9 2057.92  5048.2 2060.76  5062.5 2063.49
  5083.3 2066.12  5126.1 2069.54  5175.5  2072.8  5245.7 2075.42  5406.8 2078.13
  5470.3 2078.68  5493.7 2078.31  5579.7 2079.59  5637.3 2079.39  5750.1 2080.53
#Mann= 4 ,-1 , 0
  4030.9     .16       0  4130.4      .1       0  4994.7     .07       0
  5000.7      .1       0
Bank Sta=4948.3,5048.2
XS Rating Curve= 0 ,0
Exp/Cntr=0.3,0.1

Type RM Length L Ch R = 1 ,27613   ,417,417,417
BEGIN DESCRIPTION:
DITTMAR CREEK 60.0
END DESCRIPTION:
XS GIS Cut Line= 4
      2681125.98     10082571.03       2681226.1      10082156.9
      2681075.94     10081829.27      2680776.57     10081597.94
#Sta/Elev= 30
  4429.8 2065.93  4601.9 2063.66  4713.5 2062.84  4735.7 2061.99  4797.2 2061.45
  4849.3 2060.14  4863.5 2060.32    4915  2058.7    4984 2053.93  4991.4 2052.47
    5004 2050.88  5006.8 2050.38    5010 2050.88  5013.4 2052.46  5024.4 2056.18
    5030 2058.94  5035.5 2060.69    5053 2064.31  5068.4 2066.39  5083.5 2067.81
  5104.5 2069.19    5145 2069.97  5156.4 2070.75    5202 2072.15  5218.3 2071.99
  5268.1 2073.85  5398.7 2075.61  5496.3 2077.03  5554.3 2078.47  5594.6 2078.34
#Mann= 5 ,-1 , 0
  4429.8      .1       0    5004     .07       0    5010      .1       0
  5083.5     .16       0  5398.7      .1       0
Bank Sta=4915,5030
XS Rating Curve= 0 ,0
Exp/Cntr=0.3,0.1

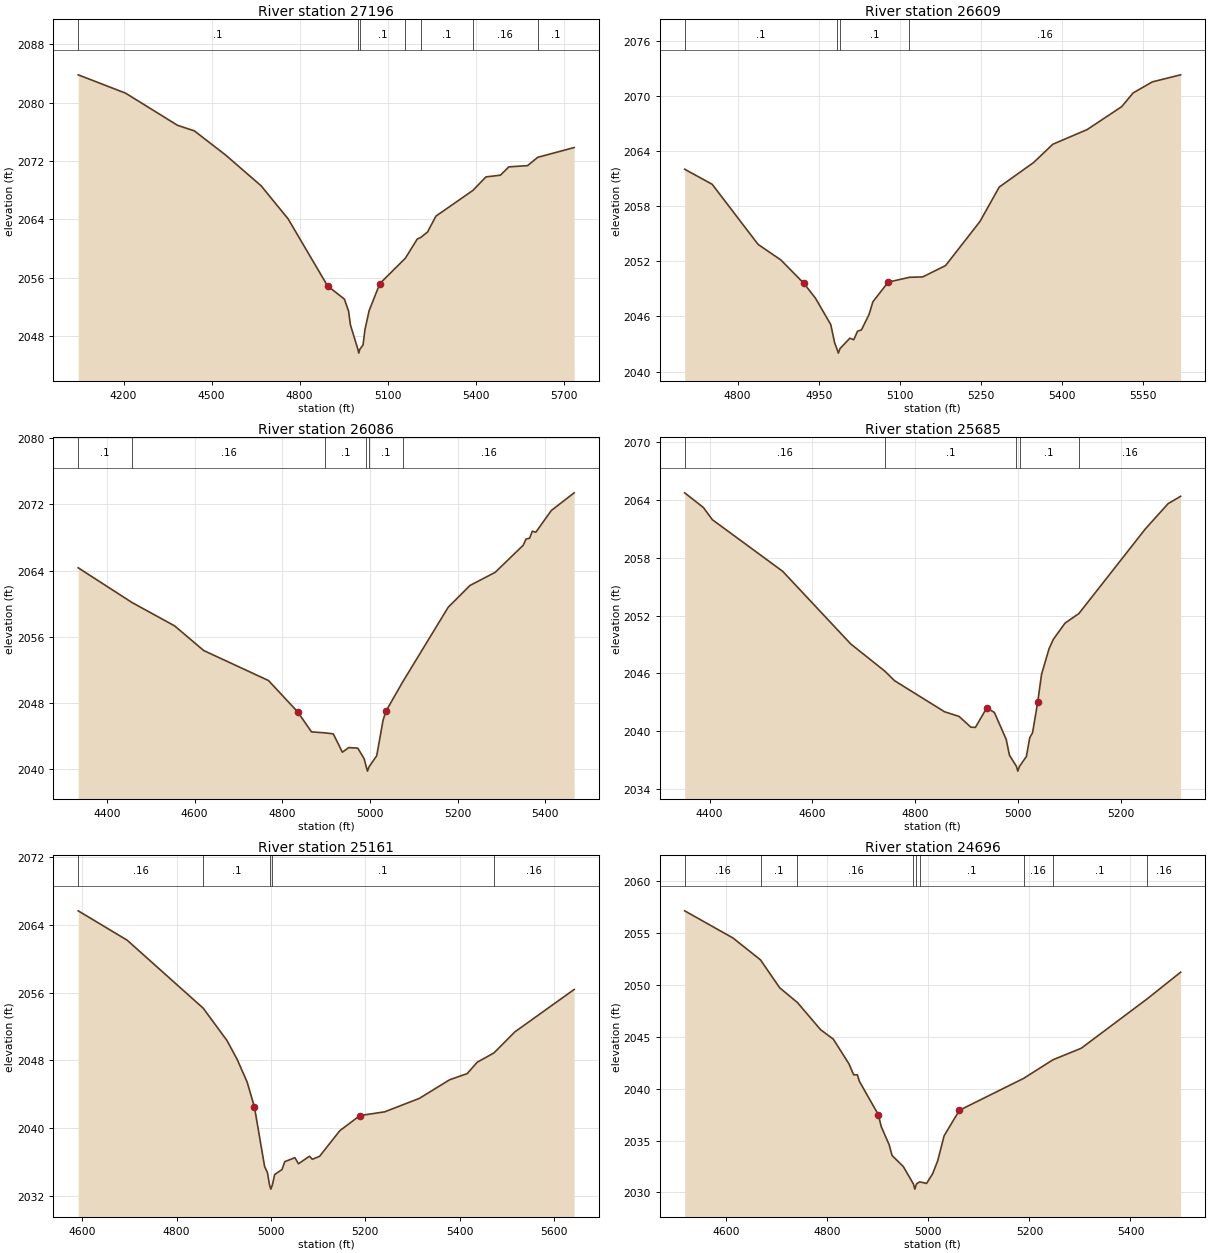
Type RM Length L Ch R = 1 ,27196   ,587,587,587
BEGIN DESCRIPTION:
DITTMAR CREEK 59.0
END DESCRIPTION:
XS GIS Cut Line= 2
      2682265.88     10082453.96      2680972.36     10081366.03
#Sta/Elev= 30
  4045.4 2083.82  4207.1  2081.3    4384 2076.89  4441.2 2076.13  4547.9 2072.81
  4668.8 2068.59  4760.7 2064.06  4895.2 2054.86  4952.4 2053.05  4966.7 2051.41
  4973.2  2049.5  4998.8 2046.13  5001.6 2045.63  5004.8 2046.13  5016.1 2046.75
  5022.7 2048.88    5037 2051.47  5073.3 2055.17  5160.4 2058.66  5200.8 2061.28
  5212.6  2061.5  5235.9 2062.25  5264.5 2064.43  5390.3 2067.95  5434.9 2069.81
  5484.4 2070.05    5513 2071.19  5576.7 2071.36  5611.6  2072.5  5735.6 2073.84
#Mann= 7 ,-1 , 0
  4045.4      .1       0  4998.8     .07       0  5004.8      .1       0
  5160.4     .16       0  5212.6      .1       0  5390.3     .16       0
  5611.6      .1       0
Bank Sta=4895.2,5073.3
XS Rating Curve= 0 ,0
Exp/Cntr=0.3,0.1

Type RM Length L Ch R = 1 ,26609   ,523,523,523
BEGIN DESCRIPTION:
DITTMAR CREEK 58.0
END DESCRIPTION:
XS GIS Cut Line= 2
      2682142.92     10081641.02      2681502.86     10080985.34
#Sta/Elev= 30
  4702.4 2062.04  4753.2  2060.4  4838.1 2053.85  4880.3 2052.15  4922.8  2049.6
  4944.1 2047.99  4972.4 2045.11  4979.4 2043.15  4983.5 2042.51  4986.3 2042.01
  4989.5 2042.51  5007.6 2043.64  5014.8 2043.47  5021.8  2044.4    5029 2044.54
  5043.1 2046.23  5050.1  2047.6  5078.4 2049.74  5117.7 2050.27  5142.1 2050.31
  5184.5 2051.55  5248.1 2056.36  5283.6  2060.1  5347.1 2062.77  5382.6 2064.76
  5446.1 2066.36  5509.7 2068.85    5531 2070.35  5566.3 2071.55  5618.7 2072.32
#Mann= 4 ,-1 , 0
  4702.4      .1       0  4983.5     .07       0  4989.5      .1       0
  5117.7     .16       0
Bank Sta=4922.8,5078.4
XS Rating Curve= 0 ,0
Exp/Cntr=0.3,0.1

Type RM Length L Ch R = 1 ,26086   ,401,401,401
BEGIN DESCRIPTION:
DITTMAR CREEK 57.0
END DESCRIPTION:
XS GIS Cut Line= 3
      2682403.35     10081651.41      2682330.43     10081130.61
      2681951.03     10080657.66
#Sta/Elev= 30
  4334.1 2064.34  4456.9 2060.14  4554.3 2057.31  4620.6 2054.33  4768.5  2050.7
  4834.8 2046.93  4866.7 2044.49  4897.2 2044.37  4916.4 2044.25  4937.2 2042.03
  4951.6 2042.59  4972.4 2042.52  4986.8 2041.25  4991.8 2040.24  4994.5 2039.74
  4997.8 2040.24  5015.6 2041.61    5030 2045.88  5036.4 2046.97  5075.1 2050.55
  5178.8 2059.57  5228.4  2062.2    5286 2063.79    5350 2067.07  5356.5 2067.82
  5364.4 2067.91  5370.9 2068.77  5378.8 2068.64  5414.1 2071.27  5466.3 2073.41
#Mann= 6 ,-1 , 0
  4334.1      .1       0  4456.9     .16       0  4897.2      .1       0
  4991.8     .07       0  4997.8      .1       0  5075.1     .16       0
Bank Sta=4834.8,5036.4
XS Rating Curve= 0 ,0
Exp/Cntr=0.3,0.1

Type RM Length L Ch R = 1 ,25685   ,524,524,524
BEGIN DESCRIPTION:
DITTMAR CREEK 56.0
END DESCRIPTION:
XS GIS Cut Line= 2
      2682856.48     10081406.66      2682450.23     10080531.67
#Sta/Elev= 30
  4351.7 2064.73  4388.1 2063.21  4405.4 2061.95  4542.4 2056.59  4674.7 2049.06
    4741 2046.24  4759.9 2045.25  4857.1 2042.03  4885.5 2041.54  4908.4 2040.43
  4917.2  2040.4  4939.3 2042.43  4954.2 2041.95  4977.1 2039.17  4983.4 2037.53
    4997 2036.37  4999.7 2035.87    5003 2036.37  5016.4 2037.39  5022.9 2039.33
  5028.4 2039.85  5038.5 2043.05  5045.8 2045.89  5060.5 2048.57  5068.7 2049.53
  5091.6 2051.22  5118.5 2052.21    5248    2061  5292.1 2063.61  5316.4 2064.37
#Mann= 5 ,-1 , 0
  4351.7     .16       0    4741      .1       0    4997     .07       0
    5003      .1       0  5118.5     .16       0
Bank Sta=4939.3,5038.5
XS Rating Curve= 0 ,0
Exp/Cntr=0.3,0.1

Type RM Length L Ch R = 1 ,25161   ,465,465,465
BEGIN DESCRIPTION:
DITTMAR CREEK 55.0
END DESCRIPTION:
XS GIS Cut Line= 2
      2683299.16     10081213.91      2682757.51     10080312.89
#Sta/Elev= 30
  4591.4 2065.69  4695.1 2062.22  4856.3 2054.18  4906.6 2050.37  4928.3 2048.13
  4949.6 2045.43    4965 2042.48  4986.6 2035.44  4992.4 2034.76    4997 2033.28
  4999.7 2032.78    5003 2033.28  5007.9 2034.51  5023.3 2035.09  5029.3 2036.03
  5050.7  2036.5  5058.3 2035.78  5081.7 2036.67  5087.6 2036.31  5103.1 2036.66
  5145.9 2039.69  5188.6 2041.48  5241.1 2041.92  5314.9 2043.52    5379 2045.72
  5415.9 2046.44  5437.3 2047.79  5472.8 2048.89  5516.9 2051.37  5642.7 2056.39
#Mann= 5 ,-1 , 0
  4591.4     .16       0  4856.3      .1       0    4997     .07       0
    5003      .1       0  5472.8     .16       0
Bank Sta=4965,5188.6
XS Rating Curve= 0 ,0
Exp/Cntr=0.3,0.1

Type RM Length L Ch R = 1 ,24696   ,326,326,326
BEGIN DESCRIPTION:
DITTMAR CREEK 54.0
END DESCRIPTION:
XS GIS Cut Line= 3
      2683575.23     10080880.61      2683460.64      10080562.9
      2682903.37       10080240.
#Sta/Elev= 30
  4517.5 2057.17  4613.1 2054.55  4667.6 2052.44  4705.5 2049.75  4740.8 2048.32
  4786.6  2045.7  4811.8 2044.79  4842.7 2042.41  4852.1 2041.35  4859.4 2041.35
  4863.5 2040.71  4900.8 2037.51  4906.6 2036.36  4922.4 2034.59  4928.1 2033.56
  4950.2 2032.51  4970.3 2030.82  4973.1 2030.32  4976.3 2030.82  4982.6 2031.02
  4996.4 2030.87  5008.5 2031.82  5018.5 2033.07  5031.1 2035.47  5061.5 2037.93
  5188.3    2041  5246.6  2042.8  5302.5 2043.91  5432.9 2048.67  5499.3 2051.25
#Mann= 9 ,-1 , 0
  4517.5     .16       0  4667.6      .1       0  4740.8     .16       0
  4970.3     .07       0  4976.3     .16       0  4982.6      .1       0
  5188.3     .16       0  5246.6      .1       0  5432.9     .16       0
Bank Sta=4900.8,5061.5
XS Rating Curve= 0 ,0
Exp/Cntr=0.3,0.1

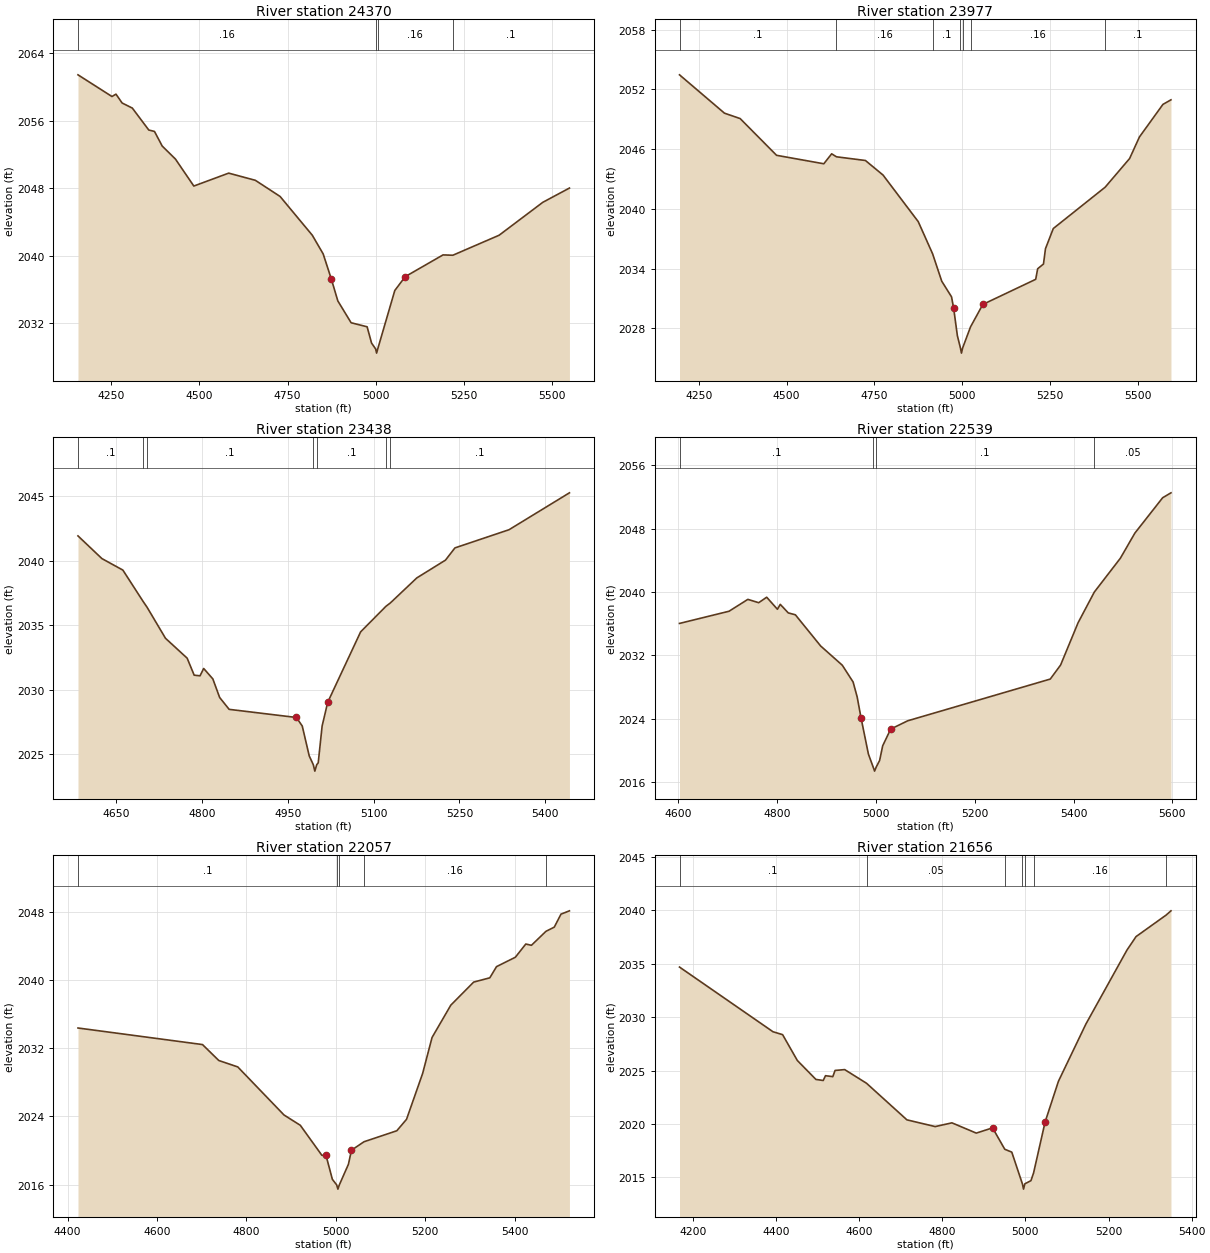
Type RM Length L Ch R = 1 ,24370   ,393,393,393
BEGIN DESCRIPTION:
DITTMAR CREEK 53.0
END DESCRIPTION:
XS GIS Cut Line= 3
      2683924.17     10080972.48      2683627.56     10080296.13
      2683077.77     10079939.05
#Sta/Elev= 30
  4155.6 2061.44    4252 2058.87  4263.4 2059.15  4280.8  2058.1  4309.7  2057.5
  4356.4  2054.9  4372.6 2054.73  4394.5    2053    4432 2051.46  4484.2 2048.26
  4583.1 2049.79  4658.7 2048.94  4728.8 2047.03  4820.3 2042.43  4851.1 2040.22
  4874.4 2037.22  4892.7 2034.65  4930.4 2032.06  4975.8 2031.58  4988.4 2029.65
  4999.9 2028.96  5002.7 2028.46  5005.9 2028.96  5054.3 2035.88  5083.8 2037.52
  5191.1  2040.1    5219 2040.06  5350.2 2042.43  5474.1 2046.33  5549.7 2048.02
#Mann= 4 ,-1 , 0
  4155.6     .16       0  4999.9     .07       0  5005.9     .16       0
    5219      .1       0
Bank Sta=4874.4,5083.8
XS Rating Curve= 0 ,0
Exp/Cntr=0.3,0.1

Type RM Length L Ch R = 1 ,23977   ,539,539,539
BEGIN DESCRIPTION:
DITTMAR CREEK 52.0
END DESCRIPTION:
XS GIS Cut Line= 2
      2684455.08     10080267.81      2683206.25     10079636.78
#Sta/Elev= 30
  4195.2 2053.46  4323.2 2049.61  4367.8 2049.07  4471.5 2045.38    4606 2044.53
  4628.4 2045.53  4642.1 2045.23  4724.5 2044.86  4774.6  2043.4  4874.9 2038.72
  4915.7  2035.5  4941.8 2032.74  4969.7 2031.17  4975.7 2030.03  4986.3 2027.27
  4995.1 2026.02  4997.9 2025.52  5001.1 2026.02  5023.8 2028.16  5058.8 2030.41
  5209.3 2032.93  5214.9 2033.99  5231.5 2034.47  5237.1    2036  5259.4 2038.03
  5407.1 2042.18  5476.7 2045.06  5504.6 2047.22  5571.5 2050.49  5594.4 2050.95
#Mann= 7 ,-1 , 0
  4195.2      .1       0  4642.1     .16       0  4915.7      .1       0
  4995.1     .07       0  5001.1      .1       0  5023.8     .16       0
  5407.1      .1       0
Bank Sta=4975.7,5058.8
XS Rating Curve= 0 ,0
Exp/Cntr=0.3,0.1

Type RM Length L Ch R = 1 ,23438   ,899,899,899
BEGIN DESCRIPTION:
DITTMAR CREEK 50.0
END DESCRIPTION:
XS GIS Cut Line= 2
      2684278.33     10079588.94      2683513.52     10079198.73
#Sta/Elev= 30
  4583.6 2041.94  4625.4 2040.18    4662 2039.29  4697.5 2036.85  4704.4  2036.4
  4736.5    2034  4774.3 2032.46  4786.6 2031.14  4796.8 2031.09  4803.2 2031.66
  4819.2 2030.85  4831.1 2029.41  4847.7 2028.49  4965.1 2027.86  4975.4  2027.2
  4987.6 2024.88  4994.7  2024.2  4997.4  2023.7  5000.7  2024.2  5003.3 2024.34
  5010.1 2027.19  5019.9 2029.04  5077.4  2034.5  5121.6 2036.48  5129.3 2036.74
  5175.5 2038.68  5225.6 2040.06  5242.2 2041.01  5336.7 2042.42  5442.2 2045.28
#Mann= 7 ,-1 , 0
  4583.6      .1       0  4697.5     .05       0  4704.4      .1       0
  4994.7     .07       0  5000.7      .1       0  5121.6     .16       0
  5129.3      .1       0
Bank Sta=4965.1,5019.9
XS Rating Curve= 0 ,0
Exp/Cntr=0.3,0.1

Type RM Length L Ch R = 1 ,22539   ,482,482,482
BEGIN DESCRIPTION:
DITTMAR CREEK 49.0
END DESCRIPTION:
XS GIS Cut Line= 3
      2684814.83     10078984.79       2684372.1      10078745.2
      2684080.43     10078349.35
#Sta/Elev= 30
  4602.1 2036.02  4702.4 2037.56  4740.5 2039.06  4762.4 2038.64  4778.6 2039.33
  4800.4 2037.81  4806.1 2038.43  4822.3 2037.35  4836.7 2037.11  4887.9 2033.17
  4931.7 2030.74  4953.6 2028.62  4961.8 2026.74  4969.8 2024.04  4984.6 2019.51
  4994.3 2017.86  4997.1 2017.36  5000.3 2017.86  5007.3 2018.71  5013.5 2020.56
  5029.7 2022.67  5064.2 2023.72  5352.8 2028.99  5373.7 2030.76  5409.1  2036.1
    5442 2039.98  5494.8 2044.26    5524 2047.42  5580.4  2051.9  5597.2 2052.52
#Mann= 4 ,-1 , 0
  4602.1      .1       0  4994.3     .07       0  5000.3      .1       0
    5442     .05       0
Bank Sta=4969.8,5029.7
XS Rating Curve= 0 ,0
Exp/Cntr=0.3,0.1

Type RM Length L Ch R = 1 ,22057   ,401,401,401
BEGIN DESCRIPTION:
DITTMAR CREEK 48.0
END DESCRIPTION:
XS GIS Cut Line= 3
      2685002.31     10078844.15      2684715.85     10078391.03
      2684247.22     10078078.61
#Sta/Elev= 30
  4423.1 2034.35  4701.6 2032.41  4738.1 2030.54  4780.5 2029.79  4883.9 2024.16
  4920.4 2022.95  4968.7 2019.43  4977.7 2019.46  4992.1 2016.62  5001.7 2015.97
  5004.5 2015.47  5007.7 2015.97  5028.1 2018.39  5034.8 2020.03  5062.8 2021.02
  5136.3 2022.31    5158 2023.65    5194 2029.02  5215.1 2033.24  5257.1 2037.03
  5308.2 2039.73  5344.3 2040.23  5359.3 2041.54  5401.4 2042.64  5424.8 2044.19
  5437.4 2044.04  5469.9 2045.68  5488.5 2046.17  5503.5 2047.69  5522.4 2048.08
#Mann= 5 ,-1 , 0
  4423.1      .1       0  5001.7     .07       0  5007.7      .1       0
  5062.8     .16       0  5469.9      .1       0
Bank Sta=4977.7,5034.8
XS Rating Curve= 0 ,0
Exp/Cntr=0.3,0.1

Type RM Length L Ch R = 1 ,21656   ,355,355,355
BEGIN DESCRIPTION:
DITTMAR CREEK 47.0
END DESCRIPTION:
XS GIS Cut Line= 3
      2685377.29     10078661.83      2685142.93     10078146.24
      2684581.93     10077891.71
#Sta/Elev= 30
  4167.8 2034.68  4392.7 2028.63  4415.8 2028.36  4451.3 2025.94    4496 2024.17
  4513.6 2024.07    4519 2024.52  4536.6 2024.43  4542.1 2025.01  4565.2 2025.09
  4617.8 2023.81  4714.9 2020.39    4783 2019.76  4823.2 2020.11  4881.8 2019.15
    4921 2019.64  4950.3 2017.64  4967.2 2017.37  4992.7 2014.41  4995.5 2013.91
  4998.7 2014.41  5013.3  2014.7  5019.7 2015.43  5047.4 2020.19  5079.5    2024
  5145.4 2029.34  5244.2 2036.26  5266.2 2037.53  5338.5 2039.54  5350.2 2039.94
#Mann= 7 ,-1 , 0
  4167.8      .1       0  4617.8     .05       0  4950.3      .1       0
  4992.7     .07       0  4998.7      .1       0  5019.7     .16       0
  5338.5      .1       0
Bank Sta=4921,5047.4
XS Rating Curve= 0 ,0
Exp/Cntr=0.3,0.1

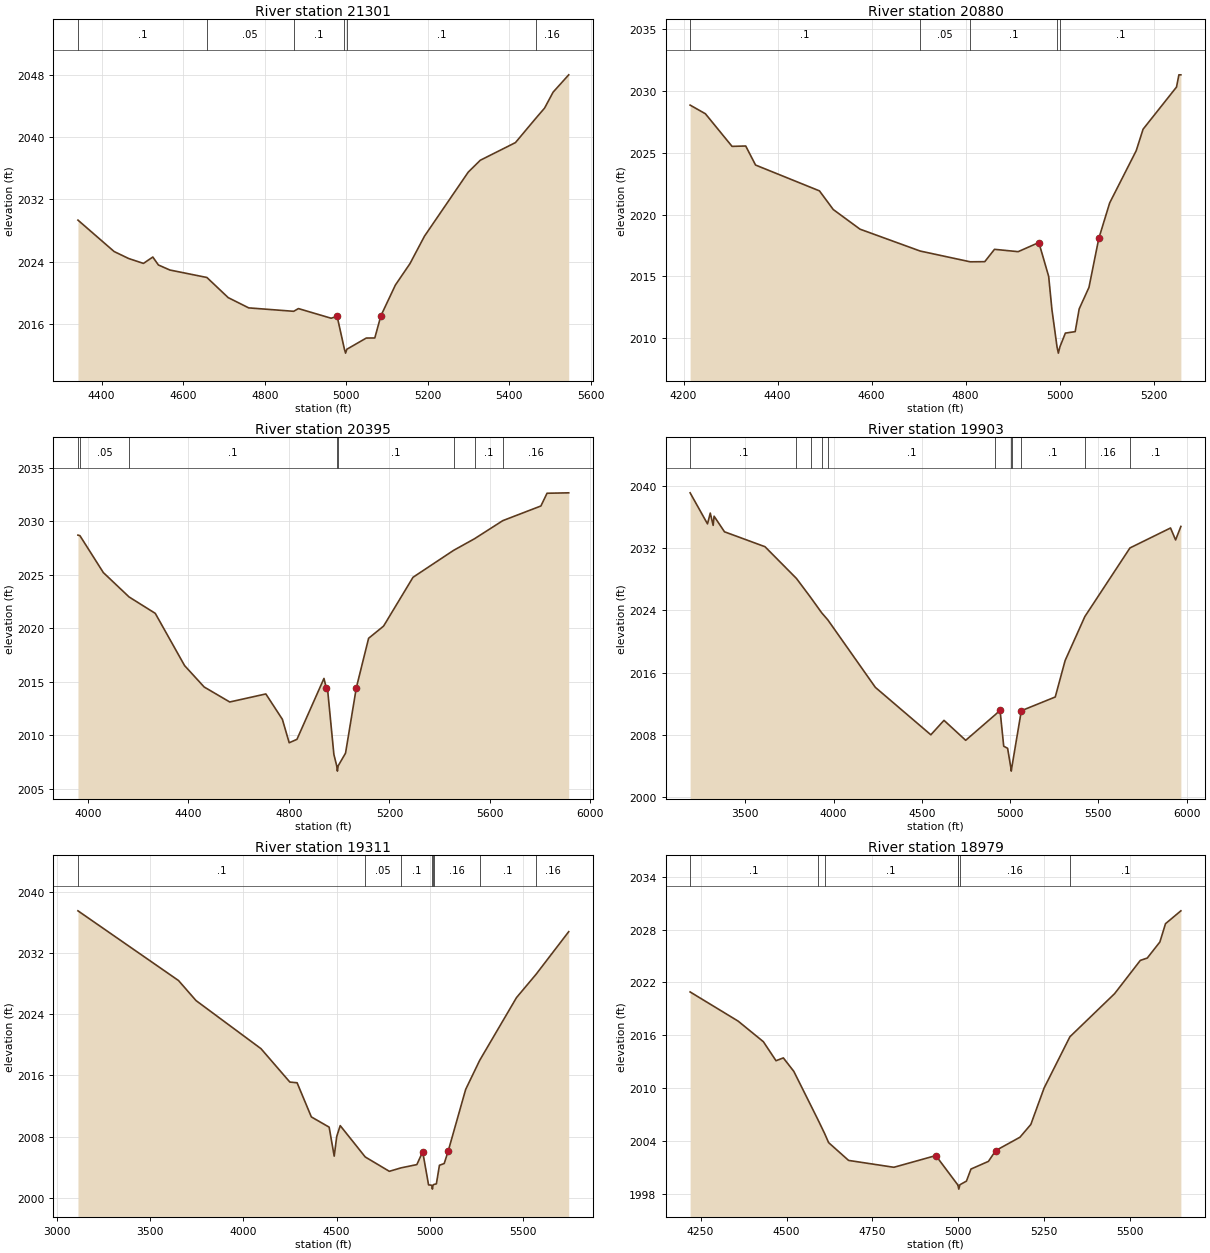
Type RM Length L Ch R = 1 ,21301   ,421,421,421
BEGIN DESCRIPTION:
DITTMAR CREEK 46.0
END DESCRIPTION:
XS GIS Cut Line= 2
      2685689.83     10078167.08      2684705.43     10077474.36
#Sta/Elev= 30
  4341.9 2029.34  4430.6  2025.3  4466.3  2024.4  4502.5 2023.77  4525.5 2024.59
  4539.2 2023.57  4567.4 2022.92  4658.2 2021.96  4710.4 2019.37  4760.7 2018.05
    4871 2017.61  4882.7 2017.96  4962.8 2016.72  4977.6 2016.96  4995.5 2012.73
  4998.3 2012.23  5001.5 2012.73  5049.1 2014.17    5070 2014.18  5084.8 2017.02
  5120.5 2020.99  5156.2 2023.74  5191.9 2027.28  5299.1 2035.51  5328.7 2037.04
  5414.9 2039.31  5464.6 2042.42  5486.4 2043.75  5507.3  2045.8  5545.6 2048.03
#Mann= 6 ,-1 , 0
  4341.9      .1       0  4658.2     .05       0    4871      .1       0
  4995.5     .07       0  5001.5      .1       0  5464.6     .16       0
Bank Sta=4977.6,5084.8
XS Rating Curve= 0 ,0
Exp/Cntr=0.3,0.1

Type RM Length L Ch R = 1 ,20880   ,485,485,485
BEGIN DESCRIPTION:
DITTMAR CREEK 45.0
END DESCRIPTION:
XS GIS Cut Line= 2
      2686000.55     10077907.31      2685156.76      10077292.7
#Sta/Elev= 30
    4214 2028.86  4246.5 2028.16  4303.2 2025.52  4332.3 2025.55  4353.2 2024.01
  4489.1 2021.92  4518.5 2020.41  4575.4 2018.82  4703.4 2017.05  4809.8 2016.18
  4840.7 2016.19  4861.5 2017.19  4911.8    2017  4955.8 2017.74  4976.7    2015
  4983.6 2012.32  4994.5 2009.29  4997.3 2008.79  5000.5 2009.29  5012.2 2010.41
  5033.1 2010.53  5041.6 2012.37  5062.4 2014.11  5083.3 2018.07  5106.5 2020.95
  5162.9 2025.17  5177.5 2026.91  5248.6 2030.32  5253.7 2031.31  5257.9 2031.31
#Mann= 5 ,-1 , 0
    4214      .1       0  4703.4     .05       0  4809.8      .1       0
  4994.5     .07       0  5000.5      .1       0
Bank Sta=4955.8,5083.3
XS Rating Curve= 0 ,0
Exp/Cntr=0.3,0.1

Type RM Length L Ch R = 1 ,20395   ,492,492,492
BEGIN DESCRIPTION:
DITTMAR CREEK 44.0
END DESCRIPTION:
XS GIS Cut Line= 3
      2686203.17     10077777.99      2685721.06     10077068.11
       2684701.8     10076667.69
#Sta/Elev= 30
  3960.2 2028.71    3968 2028.66  4061.2 2025.21  4163.8 2022.93  4267.9  2021.4
  4384.6 2016.52  4462.5 2014.52  4564.3 2013.12    4708 2013.87  4773.8  2011.5
  4800.9 2009.31  4831.8 2009.63  4939.3 2015.32    4949  2014.4  4954.4 2014.12
  4978.8 2008.22    4990 2007.16  4992.8 2006.66    4996 2007.16  5025.2 2008.34
  5068.2 2014.46    5117 2019.07  5176.6 2020.21  5293.8 2024.77  5454.9 2027.28
  5538.5 2028.37  5650.9 2030.06  5802.7 2031.43  5827.1 2032.62  5913.4 2032.66
#Mann= 8 ,-1 , 0
  3960.2      .1       0    3968     .05       0  4163.8      .1       0
    4990     .07       0    4996      .1       0  5454.9     .16       0
  5538.5      .1       0  5650.9     .16       0
Bank Sta=4949,5068.2
XS Rating Curve= 0 ,0
Exp/Cntr=0.3,0.1

Type RM Length L Ch R = 1 ,19903   ,592,592,592
BEGIN DESCRIPTION:
DITTMAR CREEK 43.0
END DESCRIPTION:
XS GIS Cut Line= 3
      2686413.75     10078302.45      2685882.52     10076656.65
      2685070.02     10075989.99
#Sta/Elev= 30
  3187.6 2039.15  3286.1 2035.15  3301.8 2036.54  3318.2 2034.96  3323.4 2036.14
  3382.3 2034.13  3611.8 2032.21    3790 2028.12    3871 2025.66  3932.9  2023.7
  3967.6 2022.79  4237.1 2014.09  4551.4 2007.98    4626 2009.84  4748.9 2007.27
    4917 2010.58  4943.5 2011.14  4964.3 2006.51  4986.5 2006.24  5004.3  2003.8
  5007.1  2003.3  5010.3  2003.8  5064.1 2011.08  5256.3 2012.85  5312.3 2017.55
    5424 2023.21  5679.5 2032.05  5909.4 2034.62  5938.1 2033.08    5968 2034.82
#Mann= 11 ,-1 , 0
  3187.6      .1       0    3790     .05       0    3871      .1       0
  3932.9     .05       0  3967.6      .1       0    4917     .16       0
  5004.3     .07       0  5010.3     .16       0  5064.1      .1       0
    5424     .16       0  5679.5      .1       0
Bank Sta=4943.5,5064.1
XS Rating Curve= 0 ,0
Exp/Cntr=0.3,0.1

Type RM Length L Ch R = 1 ,19311   ,332,332,332
BEGIN DESCRIPTION:
DITTMAR CREEK 42.0
END DESCRIPTION:
XS GIS Cut Line= 3
      2686918.99     10078198.35      2686273.14     10076156.65
      2685814.78     10075974.35
#Sta/Elev= 30
  3111.4 2037.54  3651.2 2028.42  3745.5 2025.79  4094.1  2019.5    4249 2015.13
  4287.9 2015.04  4364.4 2010.57    4460 2009.23  4487.1 2005.44  4500.7 2008.02
  4519.4 2009.43  4653.7 2005.33  4783.1 2003.45  4845.4  2003.9  4930.7 2004.33
  4962.2    2006  4993.7 2001.68  5011.5 2001.62  5014.3 2001.12  5017.5 2001.62
    5022 2001.73  5035.6 2001.81  5052.1 2004.24  5077.6 2004.47  5098.5 2006.05
  5192.9 2014.17  5268.1 2017.97  5465.7 2026.18  5570.7 2029.23  5746.1 2034.81
#Mann= 8 ,-1 , 0
  3111.4      .1       0  4653.7     .05       0  4845.4      .1       0
  5011.5     .07       0  5017.5      .1       0    5022     .16       0
  5268.1      .1       0  5570.7     .16       0
Bank Sta=4962.2,5098.5
XS Rating Curve= 0 ,0
Exp/Cntr=0.3,0.1

Type RM Length L Ch R = 1 ,18979   ,412,412,412
BEGIN DESCRIPTION:
DITTMAR CREEK 41.0
END DESCRIPTION:
XS GIS Cut Line= 3
      2687043.96     10076901.42      2686564.81     10076114.99
      2686086.23     10075948.53
#Sta/Elev= 30
  4219.5 2020.92  4359.1 2017.61  4432.6 2015.27  4469.4 2013.11  4490.7 2013.43
  4521.2  2011.9    4591 2006.44  4610.6 2004.86  4622.4 2003.81  4680.5 2001.79
  4812.2 2001.01  4934.3 2002.34  4997.8 1999.03  4998.4 1999.03  5001.1 1998.53
  5004.4 1999.03  5023.3 1999.44  5036.5 2000.81  5087.3 2001.68  5108.6 2002.91
  5178.9 2004.42  5210.6 2005.87  5249.2 2010.01  5324.3 2015.83  5454.2 2020.72
  5529.1  2024.5  5549.4 2024.77    5586 2026.59  5602.4 2028.67  5647.1 2030.13
#Mann= 7 ,-1 , 0
  4219.5      .1       0    4591     .05       0  4610.6      .1       0
  4997.8     .16       0  4998.4     .07       0  5004.4     .16       0
  5324.3      .1       0
Bank Sta=4934.3,5108.6
XS Rating Curve= 0 ,0
Exp/Cntr=0.3,0.1