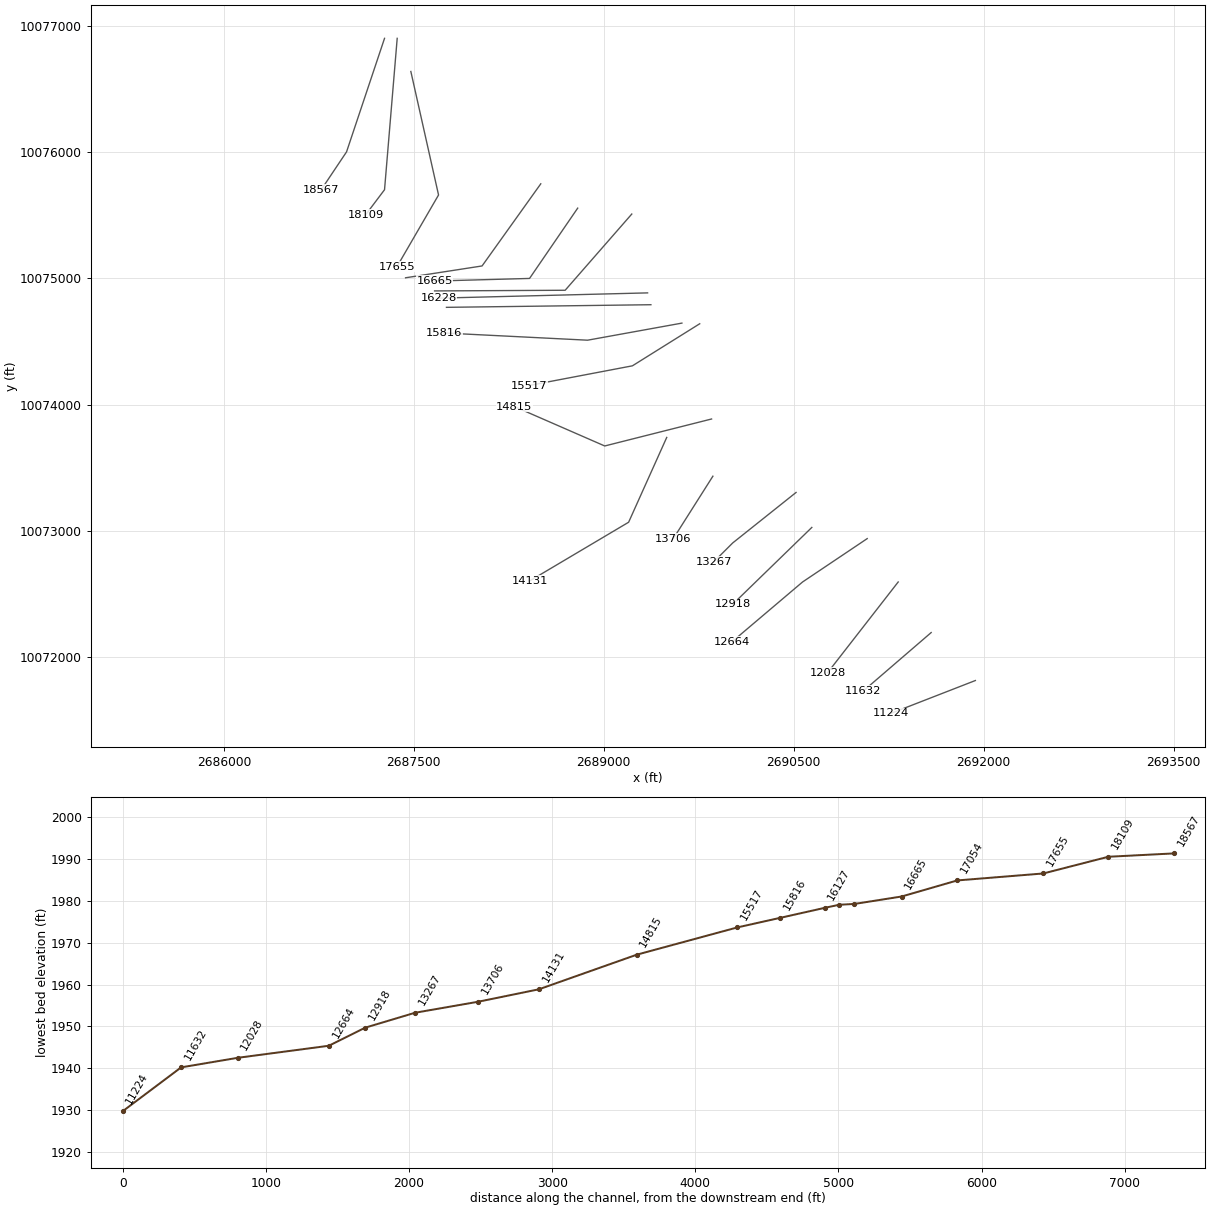
HEC-RAS study DITTMAR CREEK.prj: DITTMAR CREEK Base Level Engineering

--- DITTMAR CREEK.g01 (geometry) --- (continued)

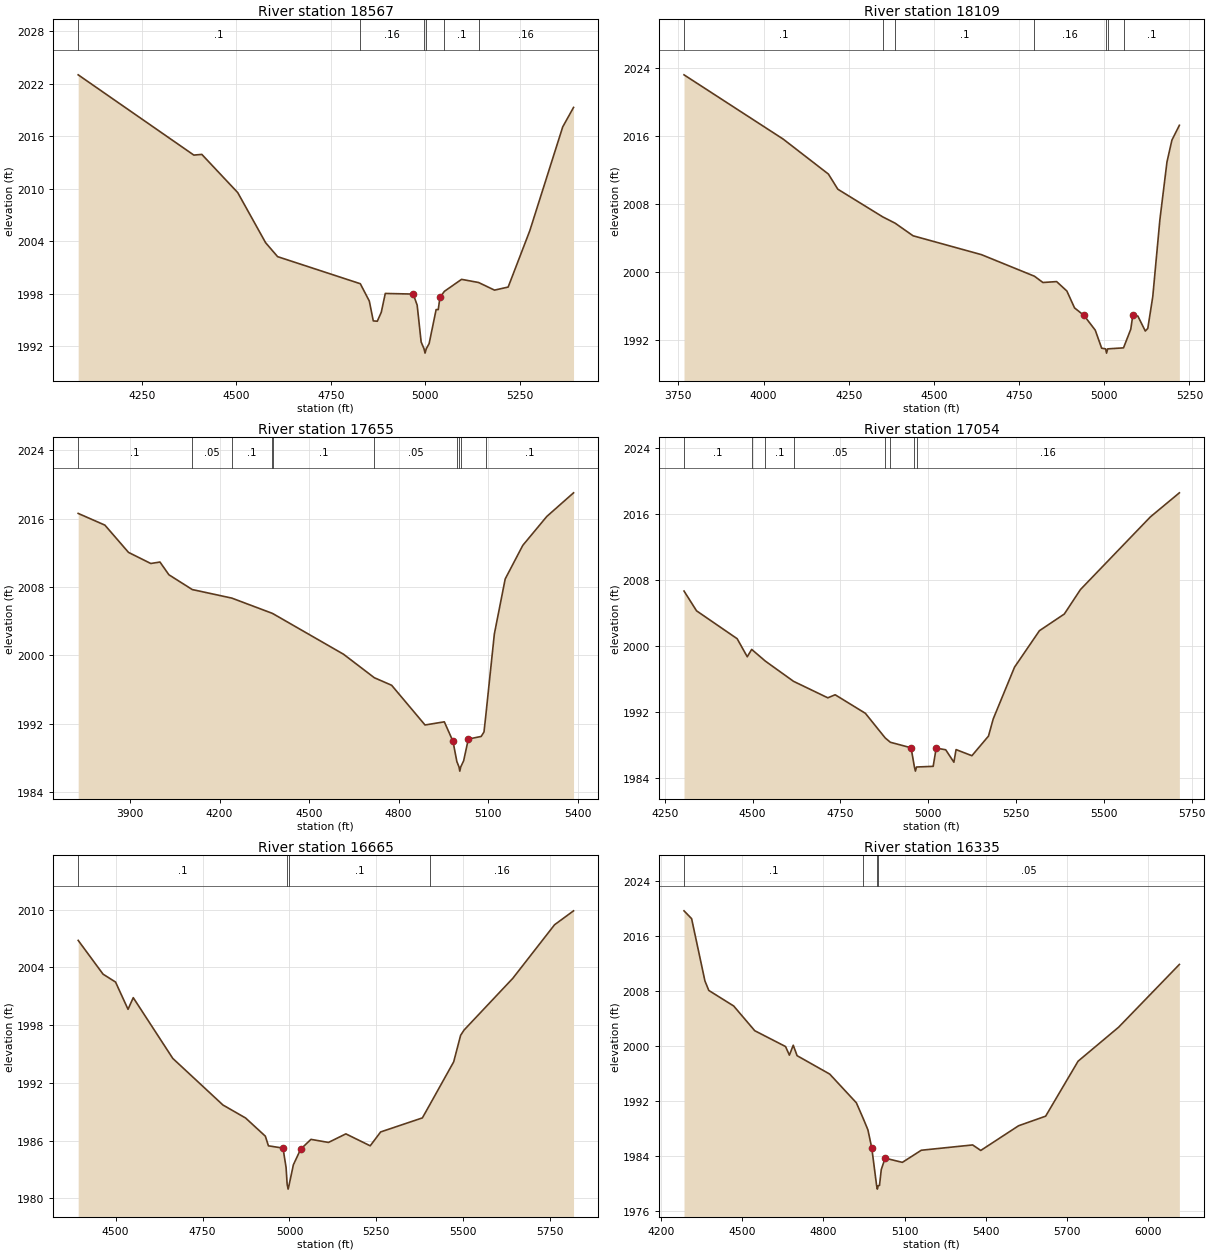
Type RM Length L Ch R = 1 ,18567   ,458,458,458
BEGIN DESCRIPTION:
DITTMAR CREEK 40.0
END DESCRIPTION:
XS GIS Cut Line= 3
      2687268.47     10076903.75      2686968.47     10076003.73
      2686768.44      10075703.7
#Sta/Elev= 30
  4082.2    2023  4387.9 2013.84    4409 2013.92  4503.9 2009.56  4577.6 2003.84
  4609.3 2002.25  4827.9 1999.16  4851.7 1997.18  4862.2 1994.92  4872.8 1994.88
  4883.3  1995.9  4893.9 1998.05  4967.7 1997.98  4978.2 1996.71  4988.7 1992.51
  4996.3 1991.74    4999 1991.24  5002.3 1991.74  5009.8 1992.33  5028.3 1996.21
  5033.9 1996.21  5038.4  1997.6  5050.1 1998.29  5095.5 1999.66  5140.5  1999.3
  5182.6 1998.43  5218.7 1998.78  5275.8  2005.2  5362.9 2017.06  5391.5 2019.28
#Mann= 6 ,-1 , 0
  4082.2      .1       0  4827.9     .16       0  4996.3     .07       0
  5002.3     .16       0  5050.1      .1       0  5140.5     .16       0
Bank Sta=4967.7,5038.4
XS Rating Curve= 0 ,0
Exp/Cntr=0.3,0.1

Type RM Length L Ch R = 1 ,18109   ,454,454,454
BEGIN DESCRIPTION:
DITTMAR CREEK 39.0
END DESCRIPTION:
XS GIS Cut Line= 3
      2687368.46     10076903.69      2687268.47     10075703.73
      2687118.48     10075503.74
#Sta/Elev= 30
  3766.5 2023.19  4057.5 2015.63  4190.4 2011.51    4218 2009.73    4350 2006.47
  4386.3 2005.73  4438.8 2004.25  4639.5 2002.03  4795.2 1999.49  4820.1 1998.75
  4860.2 1998.86  4890.3 1997.75  4912.9 1995.76  4940.5 1994.88  4973.7 1993.14
  4992.5 1991.02  5004.1 1990.94  5006.8 1990.44  5010.1 1990.94  5056.6 1991.06
  5077.9 1993.25  5084.2 1994.98  5098.7  1994.8  5120.6 1993.04  5127.9 1993.35
  5142.5 1997.09  5163.3 2006.11  5184.2 2012.94  5198.7 2015.51  5220.6 2017.25
#Mann= 7 ,-1 , 0
  3766.5      .1       0    4350     .05       0  4386.3      .1       0
  4795.2     .16       0  5004.1     .07       0  5010.1     .16       0
  5056.6      .1       0
Bank Sta=4940.5,5084.2
XS Rating Curve= 0 ,0
Exp/Cntr=0.3,0.1

Type RM Length L Ch R = 1 ,17655   ,601,601,601
BEGIN DESCRIPTION:
DITTMAR CREEK 38.0
END DESCRIPTION:
XS GIS Cut Line= 3
      2687476.26     10076641.06      2687695.02     10075661.86
      2687366.87     10075094.11
#Sta/Elev= 30
  3726.6 2016.62  3816.1 2015.25  3895.1 2012.06  3969.8 2010.76  4000.5 2010.93
  4030.5 2009.44  4108.7 2007.71  4241.1 2006.71  4374.2 2004.96  4379.3 2004.88
  4615.3 2000.14  4718.5 1997.39  4776.4 1996.51  4888.3 1991.86  4952.9 1992.23
  4981.9 1989.95  4994.9 1987.58    5002 1986.96  5004.7 1986.46    5008 1986.96
  5017.6 1987.67  5033.3 1990.21  5076.4 1990.52  5085.8 1991.05  5091.4 1992.83
  5120.5 2002.52  5156.8 2008.95  5215.7 2012.88    5296 2016.26  5385.7 2019.03
#Mann= 10 ,-1 , 0
  3726.6      .1       0  4108.7     .05       0  4241.1      .1       0
  4374.2     .05       0  4379.3      .1       0  4718.5     .05       0
  4994.9     .16       0    5002     .07       0    5008     .16       0
  5091.4      .1       0
Bank Sta=4981.9,5033.3
XS Rating Curve= 0 ,0
Exp/Cntr=0.3,0.1

Type RM Length L Ch R = 1 ,17054   ,389,389,389
BEGIN DESCRIPTION:
DITTMAR CREEK 37.0
END DESCRIPTION:
XS GIS Cut Line= 3
      2688502.34     10075750.44      2688038.77     10075099.36
      2687434.65     10075005.62
#Sta/Elev= 30
  4304.5 2006.64  4340.2 2004.24  4455.8 2000.86  4484.6 1998.67  4497.2 1999.56
  4536.2 1998.14  4616.4 1995.69    4714 1993.69  4734.9 1994.06    4821 1991.81
  4877.5 1988.82  4892.1  1988.3  4951.1 1987.63  4960.6  1985.3  4963.4  1984.8
  4966.6  1985.3    5014 1985.38  5022.6 1987.59  5049.7 1987.39    5073 1985.88
  5079.2 1987.41  5124.3 1986.67  5171.5 1989.05    5185 1991.13  5245.7 1997.41
  5316.6 2001.83  5387.4 2003.85  5433.4 2006.82  5632.5 2015.63  5715.1 2018.55
#Mann= 8 ,-1 , 0
  4304.5      .1       0  4497.2     .05       0  4536.2      .1       0
  4616.4     .05       0  4877.5      .1       0  4892.1     .16       0
  4960.6     .07       0  4966.6     .16       0
Bank Sta=4951.1,5022.6
XS Rating Curve= 0 ,0
Exp/Cntr=0.3,0.1

Type RM Length L Ch R = 1 ,16665   ,330,330,330
BEGIN DESCRIPTION:
DITTMAR CREEK 36.0
END DESCRIPTION:
XS GIS Cut Line= 3
      2688793.97     10075557.69      2688413.77      10075000.4
      2687663.79     10074979.57
#Sta/Elev= 30
  4392.3 2006.81  4463.9  2003.3  4499.8 2002.48  4535.7 1999.65  4550.7 2000.86
  4664.4 1994.55  4808.7 1989.71  4873.8 1988.36  4930.7 1986.47  4939.5 1985.47
  4981.5 1985.23  4990.3 1983.22  4993.4 1981.47  4996.2 1980.97  4999.4 1981.47
  5011.3  1983.5  5032.3 1985.12  5061.9 1986.14  5112.2 1985.82  5162.3 1986.71
  5232.3 1985.47  5262.3 1986.91  5382.4 1988.37  5405.7 1989.87  5472.4 1994.19
  5492.4 1996.95  5502.4  1997.5  5642.5 2002.87  5762.5 2008.43  5817.2 2009.88
#Mann= 4 ,-1 , 0
  4392.3      .1       0  4993.4     .07       0  4999.4      .1       0
  5405.7     .16       0
Bank Sta=4981.5,5032.3
XS Rating Curve= 0 ,0
Exp/Cntr=0.3,0.1

Type RM Length L Ch R = 1 ,16335   ,107,107,107
BEGIN DESCRIPTION:
DITTMAR CREEK 35.0
END DESCRIPTION:
XS GIS Cut Line= 3
      2689221.09     10075510.85      2688695.02     10074906.65
      2687663.76     10074901.45
#Sta/Elev= 30
  4284.2 2019.64  4312.3  2018.5  4361.6 2009.45  4375.9 2008.07    4468 2005.81
  4545.8 2002.22  4659.8 1999.92    4674 1998.67  4688.3 2000.11  4702.5 1998.59
  4823.1 1995.92  4921.8 1991.74    4947 1989.47  4964.5 1987.81  4978.8 1985.17
  4996.7  1979.7  4999.4  1979.2  5002.7  1979.7  5007.3 1979.74  5013.9 1982.05
  5028.2  1983.7  5091.9 1983.09  5161.9 1984.85  5351.9 1985.62  5381.9 1984.82
  5521.9 1988.41  5621.9  1989.8  5741.9 1997.79  5891.9 2002.73  6116.6 2011.85
#Mann= 4 ,-1 , 0
  4284.2      .1       0    4947     .05       0  4996.7     .04       0
  5002.7     .05       0
Bank Sta=4978.8,5028.2
XS Rating Curve= 0 ,0
Exp/Cntr=0.3,0.1

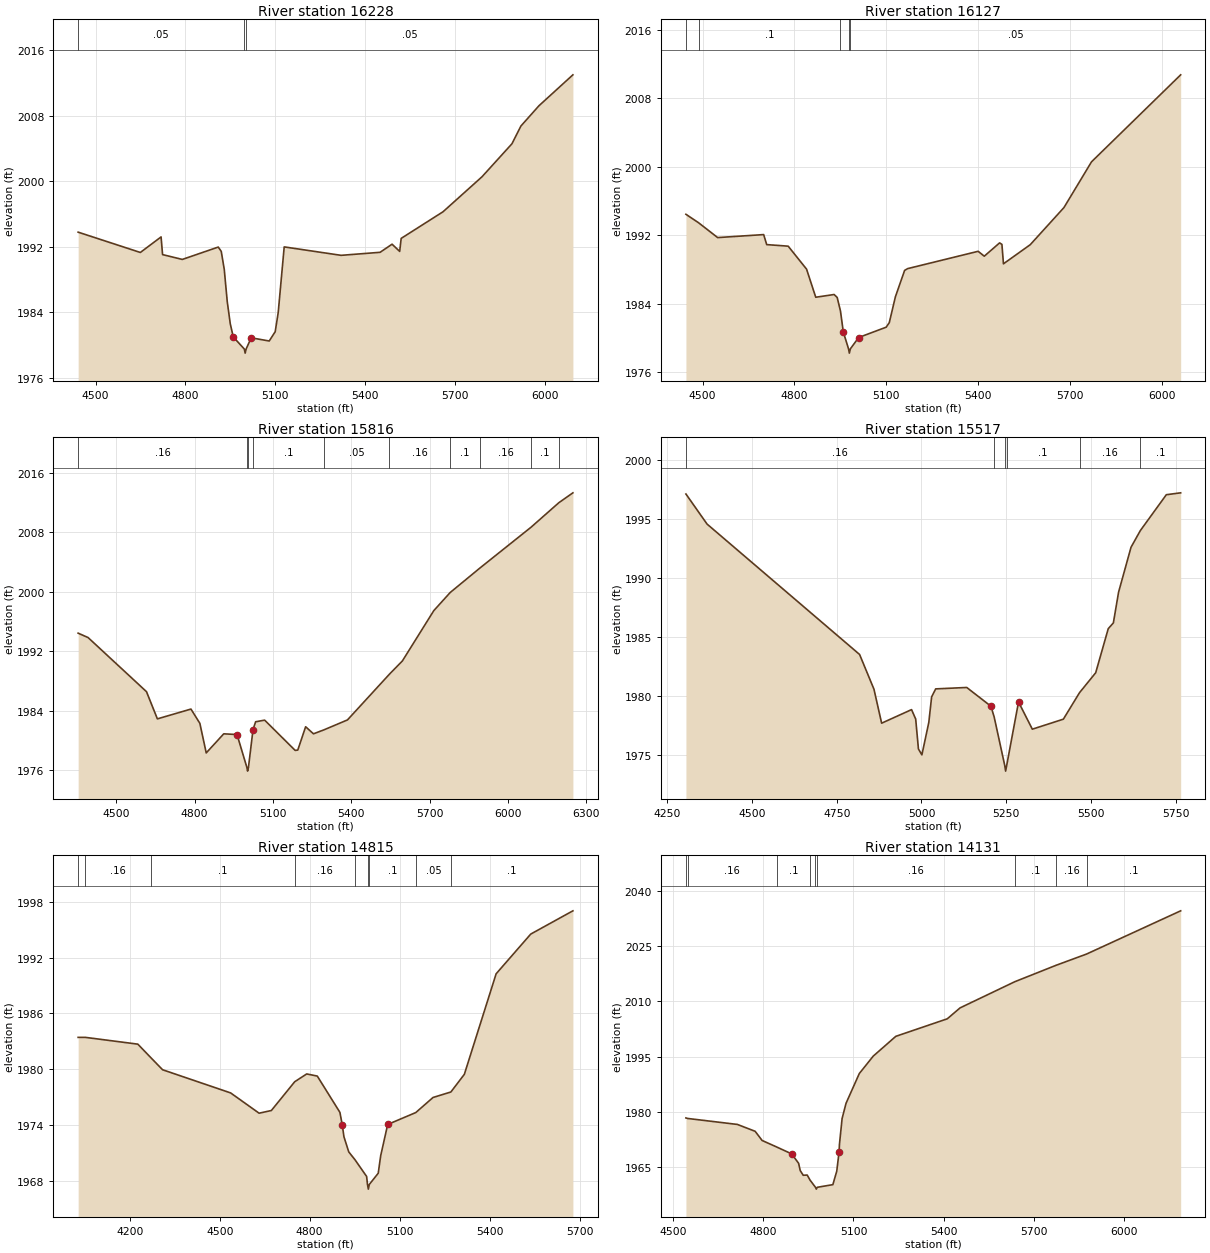
Type RM Length L Ch R = 1 ,16228   ,101,101,101
BEGIN DESCRIPTION:
Mapping XS 9a11bcd3
END DESCRIPTION:
XS GIS Cut Line= 2
      2689346.03     10074885.82      2687695.06     10074844.15
#Sta/Elev= 30
  4441.8 1993.77  4649.4 1991.29  4718.6 1993.19  4723.6 1991.03  4789.5 1990.44
  4909.5 1991.95  4919.5 1991.42  4929.5 1989.23  4939.5 1985.29  4949.5  1982.6
  4959.5 1980.98  4996.5  1979.5  4999.3    1979  5002.5  1979.5  5019.5 1980.87
  5079.6 1980.48  5099.6 1981.62  5109.6 1983.95  5129.6 1991.97  5319.6 1990.94
  5449.7 1991.31  5489.7  1992.3  5515.1 1991.42  5520.1 1993.01  5659.8 1996.26
  5789.8 2000.53  5889.8 2004.56  5919.8 2006.73  5979.9  2009.2  6093.3 2012.98
#Mann= 3 ,-1 , 0
  4441.8     .05       0  4996.5     .04       0  5002.5     .05       0
Bank Sta=4959.5,5019.5
XS Rating Curve= 0 ,0
Exp/Cntr=0.3,0.1

Type RM Length L Ch R = 1 ,16127   ,311,311,311
BEGIN DESCRIPTION:
Mapping XS b81f07e1
END DESCRIPTION:
XS GIS Cut Line= 2
       2689372.1     10074792.07      2687757.54     10074771.24
#Sta/Elev= 30
  4445.8 1994.46  4487.1 1993.47  4549.4 1991.74  4699.5 1992.09  4709.5 1990.92
  4779.5 1990.74  4839.5 1988.06  4869.5 1984.78  4929.5  1985.1  4939.5 1984.75
  4950.2 1983.17  4959.5 1980.72  4976.5 1978.76  4979.2 1978.26  4982.5 1978.76
  5009.5 1980.08  5099.5 1981.29  5109.5 1981.82  5129.5 1984.84  5159.5 1987.91
  5169.5 1988.12  5399.5 1990.14  5419.5 1989.57  5469.5 1991.12  5477.1 1990.95
  5482.1 1988.68  5569.5 1990.91  5679.5 1995.24  5769.5 2000.58  6060.5 2010.73
#Mann= 5 ,-1 , 0
  4445.8     .05       0  4487.1      .1       0  4950.2     .05       0
  4976.5     .04       0  4982.5     .05       0
Bank Sta=4959.5,5009.5
XS Rating Curve= 0 ,0
Exp/Cntr=0.3,0.1

Type RM Length L Ch R = 1 ,15816   ,299,299,299
BEGIN DESCRIPTION:
DITTMAR CREEK 34.0
END DESCRIPTION:
XS GIS Cut Line= 3
      2689616.89     10074646.24       2688872.1     10074510.82
      2687736.65     10074568.11
#Sta/Elev= 30
  4354.1 1994.44  4392.1 1993.85  4615.7 1986.57  4657.4 1982.91  4785.9 1984.23
    4820 1982.31  4844.4 1978.33  4911.5  1980.9  4962.3  1980.8    5000 1976.38
  5002.7 1975.88    5006 1976.38  5021.8 1980.96  5023.3 1981.44  5033.5 1982.52
    5068 1982.74  5184.8 1978.67  5194.8 1978.71  5224.9 1981.85  5254.9  1980.9
  5295.5 1981.44  5385.1 1982.77  5545.9 1988.93  5595.4 1990.71  5715.5 1997.47
  5778.3 1999.91  5893.4 2003.24  6087.7 2008.69  6194.2 2011.99    6248 2013.32
#Mann= 10 ,-1 , 0
  4354.1     .16       0    5000     .07       0    5006     .16       0
  5021.8      .1       0  5295.5     .05       0  5545.9     .16       0
  5778.3      .1       0  5893.4     .16       0  6087.7      .1       0
  6194.2     .05       0
Bank Sta=4962.3,5023.3
XS Rating Curve= 0 ,0
Exp/Cntr=0.3,0.1

Type RM Length L Ch R = 1 ,15517   ,702,702,702
BEGIN DESCRIPTION:
DITTMAR CREEK 33.0
END DESCRIPTION:
XS GIS Cut Line= 3
      2689757.52     10074641.03      2689226.27      10074307.7
      2688408.53     10074151.44
#Sta/Elev= 30
    4305 1997.12  4367.3 1994.57  4817.4  1983.5  4859.8 1980.55  4882.4 1977.67
  4970.7 1978.82  4982.9 1978.02    4991 1975.48  5001.2 1974.98  5021.6 1977.74
  5029.9  1979.9  5041.9 1980.58  5133.5  1980.7  5204.8 1979.11  5214.4  1978.2
  5245.5  1974.1  5248.2  1973.6  5251.5  1974.1  5286.3 1979.47    5327 1977.16
  5418.6 1978.01  5466.3 1980.26    5514 1981.95    5551 1985.69  5566.1 1986.18
  5581.5 1988.79  5618.2  1992.6  5645.8 1994.02  5722.4 1997.06  5764.7 1997.22
#Mann= 6 ,-1 , 0
    4305     .16       0  5214.4      .1       0  5245.5     .07       0
  5251.5      .1       0  5466.3     .16       0  5645.8      .1       0
Bank Sta=5204.8,5286.3
XS Rating Curve= 0 ,0
Exp/Cntr=0.3,0.1

Type RM Length L Ch R = 1 ,14815   ,684,684,684
BEGIN DESCRIPTION:
DITTMAR CREEK 32.0
END DESCRIPTION:
XS GIS Cut Line= 3
      2689851.32     10073886.18      2689007.52     10073672.28
      2688293.95     10073984.79
#Sta/Elev= 30
  4028.1 1983.42  4052.4 1983.42  4227.1 1982.69  4271.3 1981.21  4309.6 1979.94
  4536.5 1977.45  4631.4 1975.27  4672.3 1975.56  4750.1 1978.65  4790.1 1979.49
  4825.4 1979.26  4900.8 1975.36  4908.5 1974.04  4914.3 1972.73  4930.3 1971.11
  4950.8 1970.28  4989.9 1968.47  4992.8 1967.61  4995.6 1967.11  4998.8 1967.61
  5028.6 1968.82  5036.7 1970.69  5060.1 1974.06  5153.8 1975.34  5211.3 1976.96
  5270.8 1977.55  5315.7 1979.45  5421.6 1990.25    5537 1994.52  5677.6 1997.02
#Mann= 9 ,-1 , 0
  4028.1      .1       0  4052.4     .16       0  4271.3      .1       0
  4750.1     .16       0  4950.8      .1       0  4992.8     .07       0
  4998.8      .1       0  5153.8     .05       0  5270.8      .1       0
Bank Sta=4908.5,5060.1
XS Rating Curve= 0 ,0
Exp/Cntr=0.3,0.1

Type RM Length L Ch R = 1 ,14131   ,425,425,425
BEGIN DESCRIPTION:
DITTMAR CREEK 31.0
END DESCRIPTION:
XS GIS Cut Line= 3
      2689497.09     10073739.95      2689196.25     10073067.78
      2688414.52     10072602.38
#Sta/Elev= 30
  4542.5 1978.26  4547.9 1978.12  4713.7 1976.49  4772.8 1974.62    4796 1972.12
  4845.1 1970.32  4894.2 1968.47  4917.4 1965.91  4922.9 1963.91  4932.8 1962.64
  4946.1 1962.69  4955.8 1961.28  4973.6 1959.36  4976.3 1958.86  4979.6 1959.36
  5031.4 1960.08  5044.4 1963.77 5051.98 1968.92  5053.3 1971.03  5062.1 1978.09
  5075.2 1982.24  5119.4 1990.36  5165.8 1995.11  5240.9  2000.5    5412 2005.27
  5454.9 2008.26  5636.7 2015.38  5775.2 2019.89  5875.8 2022.93  6188.7  2034.7
#Mann= 9 ,-1 , 0
  4542.5      .1       0  4547.9     .16       0  4845.1      .1       0
  4955.8     .16       0  4973.6     .07       0  4979.6     .16       0
  5636.7      .1       0  5775.2     .16       0  5875.8      .1       0
Bank Sta=4894.2,5051.98
XS Rating Curve= 0 ,0
Exp/Cntr=0.3,0.1

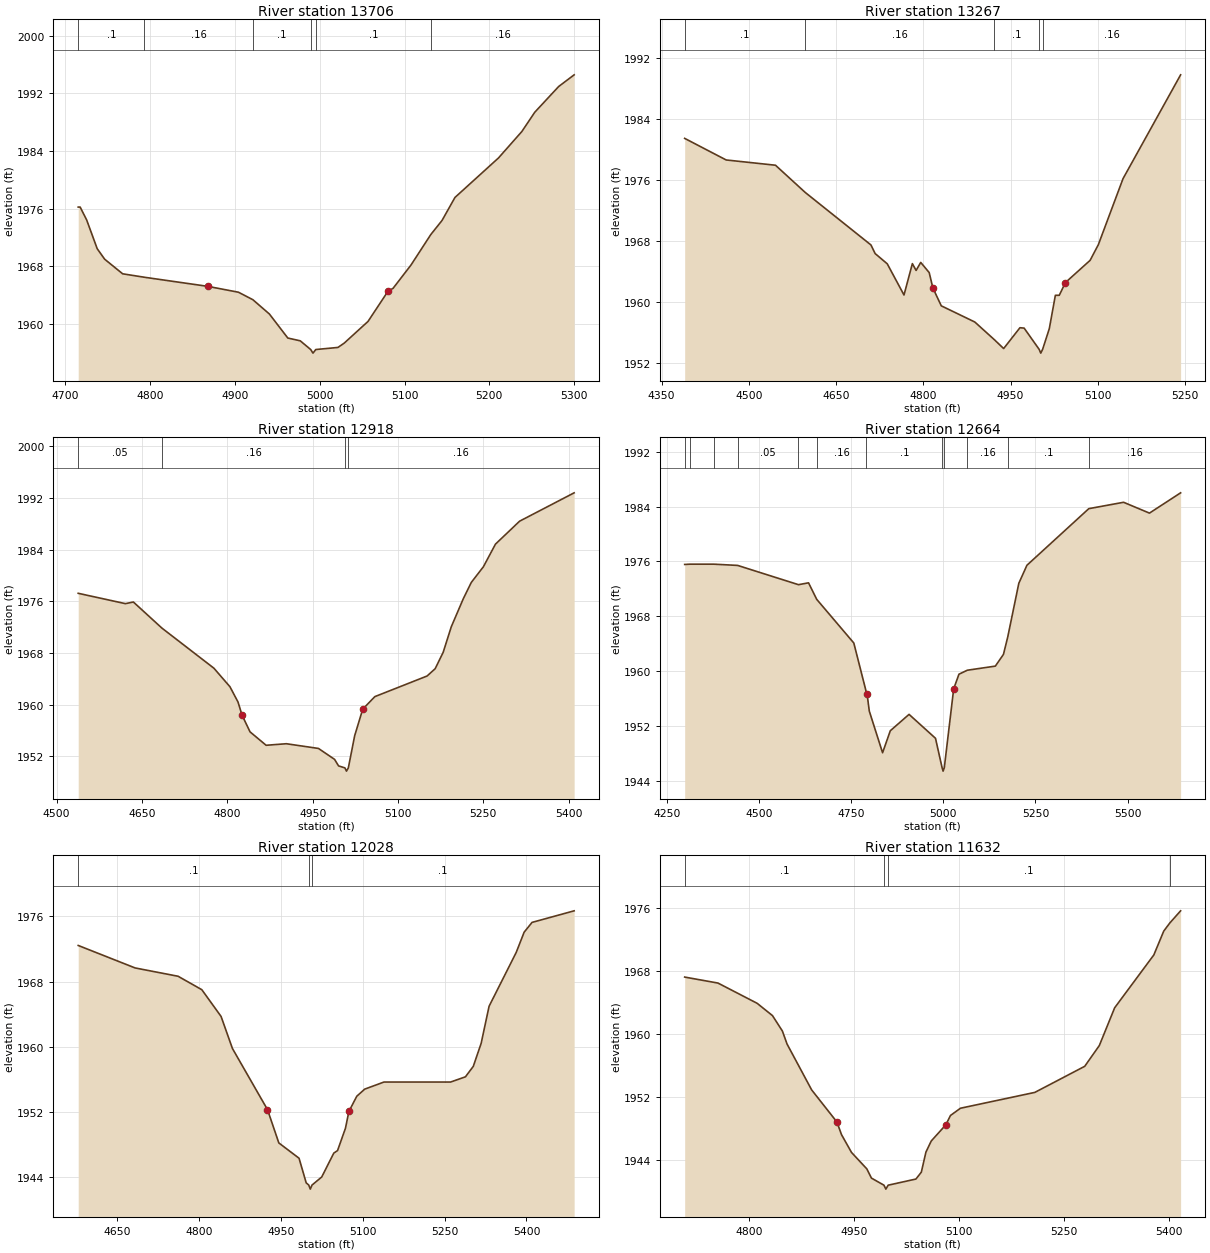
Type RM Length L Ch R = 1 ,13706   ,439,439,439
BEGIN DESCRIPTION:
DITTMAR CREEK 30.0
END DESCRIPTION:
XS GIS Cut Line= 2
      2689861.66     10073432.66      2689549.43      10072938.3
#Sta/Elev= 30
  4715.3  1976.2  4717.6  1976.2  4725.3  1974.4  4737.7 1970.41  4746.5 1968.95
  4767.7 1966.92  4793.4 1966.44  4867.8 1965.18  4904.2 1964.36  4921.2 1963.32
  4940.7 1961.33  4962.4 1957.99  4977.1  1957.6  4989.4 1956.39  4992.1 1955.89
  4995.4 1956.39  5021.5 1956.68  5028.9 1957.28    5057  1960.3  5080.6 1964.51
  5086.5  1964.9  5107.7 1968.15    5131 1972.38  5144.2 1974.33  5159.5 1977.54
  5210.8 1983.03  5238.3  1986.7  5253.6 1989.39  5281.7 1992.96    5300 1994.59
#Mann= 6 ,-1 , 0
  4715.3      .1       0  4793.4     .16       0  4921.2      .1       0
  4989.4     .07       0  4995.4      .1       0    5131     .16       0
Bank Sta=4867.8,5080.6
XS Rating Curve= 0 ,0
Exp/Cntr=0.3,0.1

Type RM Length L Ch R = 1 ,13267   ,349,349,349
BEGIN DESCRIPTION:
DITTMAR CREEK 29.0
END DESCRIPTION:
XS GIS Cut Line= 3
       2690518.5     10073303.76      2690018.47     10072903.73
      2689868.46     10072753.73
#Sta/Elev= 30
  4389.8 1981.43  4461.1  1978.6  4545.9 1977.91  4597.2 1974.33    4710 1967.46
  4717.2 1966.33    4738 1964.99  4766.8  1960.9  4781.2 1965.01  4787.6 1964.12
  4795.6 1965.17  4810.1 1963.84  4816.5 1961.81  4830.9 1959.48  4888.5 1957.36
  4922.3 1955.03  4938.1 1953.88  4966.1 1956.61  4973.3 1956.56  4999.1 1953.78
  5001.9 1953.28  5005.1 1953.78  5016.6 1956.49    5027 1960.86  5033.7 1960.86
  5044.3 1962.53  5086.7 1965.44  5100.9  1967.5  5143.3 1976.15  5242.3 1989.76
#Mann= 5 ,-1 , 0
  4389.8      .1       0  4597.2     .16       0  4922.3      .1       0
  4999.1     .07       0  5005.1     .16       0
Bank Sta=4816.5,5044.3
XS Rating Curve= 0 ,0
Exp/Cntr=0.3,0.1

Type RM Length L Ch R = 1 ,12918   ,254,254,254
BEGIN DESCRIPTION:
DITTMAR CREEK 28.0
END DESCRIPTION:
XS GIS Cut Line= 2
      2690642.93     10073026.44      2690018.79      10072417.9
#Sta/Elev= 30
  4537.9 1977.24  4620.8 1975.64  4634.9 1975.89  4685.1 1971.85  4776.4 1965.65
  4804.6 1962.78  4818.8 1960.41  4825.8  1958.4  4839.9  1955.8  4868.2 1953.72
  4903.7 1953.96  4960.2 1953.23  4988.5 1951.54  4995.5 1950.53  5006.7 1950.22
  5009.4 1949.72  5012.7 1950.22  5023.8 1955.19    5038 1959.31  5059.3 1961.25
  5151.1 1964.44  5165.3 1965.57  5179.4 1968.11  5193.6 1972.05  5214.7 1976.39
  5228.8 1978.92  5250.1 1981.35  5271.3 1984.85  5313.7  1988.4  5409.6 1992.79
#Mann= 4 ,-1 , 0
  4537.9     .05       0  4685.1     .16       0  5006.7     .07       0
  5012.7     .16       0
Bank Sta=4825.8,5038
XS Rating Curve= 0 ,0
Exp/Cntr=0.3,0.1

Type RM Length L Ch R = 1 ,12664   ,636,636,636
BEGIN DESCRIPTION:
DITTMAR CREEK 27.0
END DESCRIPTION:
XS GIS Cut Line= 3
      2691080.45     10072937.92      2690570.02     10072594.15
      2690013.09     10072120.51
#Sta/Elev= 30
  4297.7 1975.56  4311.7  1975.6  4377.2  1975.6  4441.5 1975.42  4606.7 1972.61
    4634 1972.88  4656.2 1970.47  4756.9  1964.1  4791.1 1956.88  4792.9 1956.66
    4799 1954.16    4835 1948.09    4856  1951.3  4906.9 1953.69  4978.7  1950.2
  4996.6 1945.91  4999.3 1945.41  5002.6 1945.91  5028.1 1957.42  5042.4 1959.55
  5065.1 1960.13  5141.2 1960.73  5163.2 1962.44  5174.8 1964.97  5204.9 1972.81
  5226.9 1975.44  5394.9  1983.7  5489.4 1984.63  5559.6 1983.05  5644.2 1986.01
#Mann= 12 ,-1 , 0
  4297.7      .1       0  4311.7     .05       0  4377.2      .1       0
  4441.5     .05       0  4606.7      .1       0  4656.2     .16       0
  4791.1      .1       0  4996.6     .07       0  5002.6      .1       0
  5065.1     .16       0  5174.8      .1       0  5394.9     .16       0
Bank Sta=4792.9,5028.1
XS Rating Curve= 0 ,0
Exp/Cntr=0.3,0.1

Type RM Length L Ch R = 1 ,12028   ,396,396,396
BEGIN DESCRIPTION:
DITTMAR CREEK 26.0
END DESCRIPTION:
XS GIS Cut Line= 2
      2691325.23     10072594.15      2690767.93      10071875.4
#Sta/Elev= 30
    4578 1972.44  4682.4 1969.68  4761.2 1968.66  4804.7 1967.01    4840 1963.73
  4860.8  1959.8  4925.1  1952.3  4945.9 1948.21    4983 1946.33  4996.1 1943.31
  5000.8 1943.04  5003.6 1942.54  5006.8 1943.04  5024.6 1944.03  5046.7 1946.96
  5053.6 1947.27  5068.1 1950.01  5074.4 1952.07  5088.9 1953.94  5103.4 1954.81
  5138.7 1955.68  5260.9 1955.68  5288.1 1956.32  5302.5  1957.6    5317 1960.44
  5331.5 1964.98  5381.3 1971.59  5395.8 1974.07  5410.3 1975.27  5487.5 1976.69
#Mann= 3 ,-1 , 0
    4578      .1       0  5000.8     .07       0  5006.8      .1       0
Bank Sta=4925.1,5074.4
XS Rating Curve= 0 ,0
Exp/Cntr=0.3,0.1

Type RM Length L Ch R = 1 ,11632   ,408,408,408
BEGIN DESCRIPTION:
DITTMAR CREEK 25.0
END DESCRIPTION:
XS GIS Cut Line= 2
      2691585.67     10072193.14       2691049.2     10071729.58
#Sta/Elev= 30
  4707.6 1967.18  4755.2 1966.42  4811.2 1963.85  4833.1 1962.29  4847.3 1960.33
  4853.9 1958.69  4889.1 1952.86  4925.2 1948.79  4931.8 1947.18  4946.1 1944.92
    4968 1942.83  4974.6 1941.66  4992.5 1940.76  4995.2 1940.26  4998.5 1940.76
  5038.2 1941.54  5045.9 1942.41  5052.5 1944.96  5060.1 1946.37    5081 1948.43
  5087.6 1949.61  5101.9 1950.53  5208.2 1952.54  5279.5 1955.85  5300.4 1958.49
  5322.3 1963.28  5378.3 1969.99  5392.5 1973.02  5401.1 1974.04  5416.6 1975.59
#Mann= 4 ,-1 , 0
  4707.6      .1       0  4992.5     .07       0  4998.5      .1       0
  5401.1     .16       0
Bank Sta=4925.2,5081
XS Rating Curve= 0 ,0
Exp/Cntr=0.3,0.1

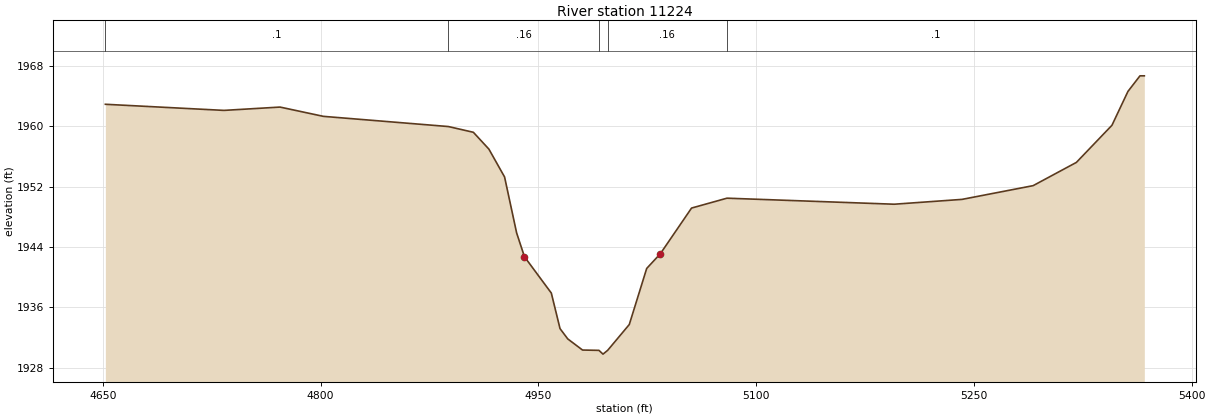
Type RM Length L Ch R = 1 ,11224   ,486,486,486
BEGIN DESCRIPTION:
DITTMAR CREEK 24.0
END DESCRIPTION:
XS GIS Cut Line= 2
      2691934.59      10071812.9      2691267.95     10071552.49
#Sta/Elev= 30
  4651.7 1962.91  4733.4  1962.1    4772 1962.54  4801.9 1961.31    4888 1959.96
  4905.2  1959.2  4915.9 1956.97  4926.7 1953.28    4935 1945.87  4940.4 1942.71
  4958.9  1937.9  4964.9 1933.19  4970.2 1931.83  4980.4 1930.35  4991.7 1930.31
  4994.5 1929.81  4997.7 1930.31  5012.6 1933.73  5024.6 1941.16    5034 1943.11
  5055.5 1949.16  5079.9 1950.47  5195.1 1949.67  5241.8 1950.31  5290.8 1952.13
  5320.6 1955.21  5345.1 1960.13  5356.1 1964.61  5364.4 1966.68  5367.4 1966.68
#Mann= 5 ,-1 , 0
  4651.7      .1       0    4888     .16       0  4991.7     .07       0
  4997.7     .16       0  5079.9      .1       0
Bank Sta=4940.4,5034
XS Rating Curve= 0 ,0
Exp/Cntr=0.3,0.1