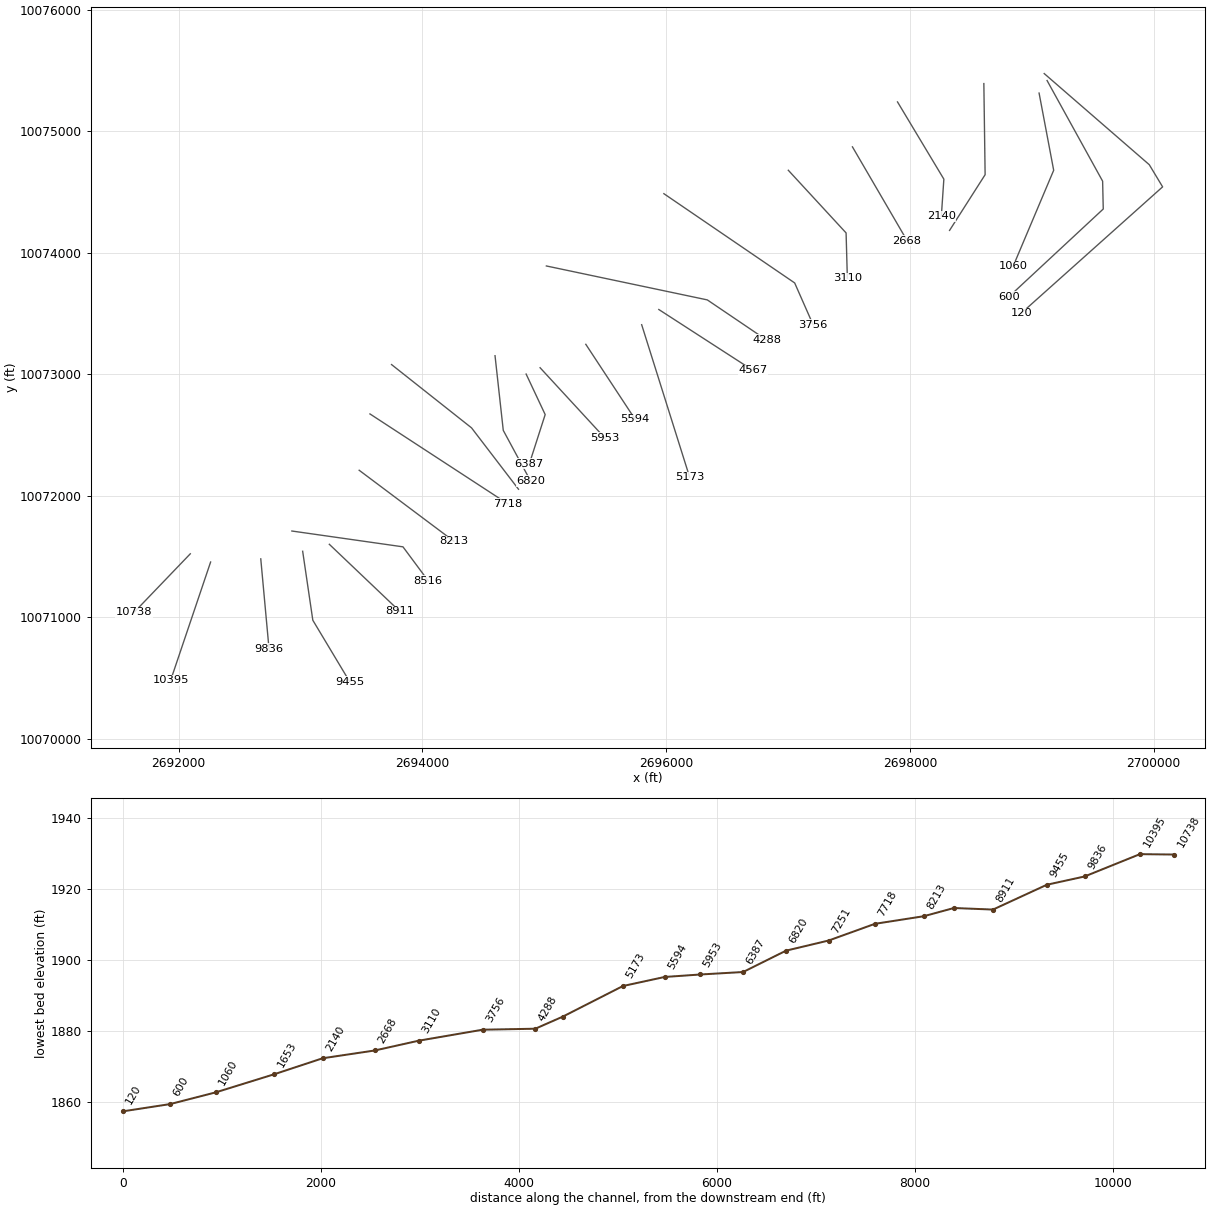
HEC-RAS study DITTMAR CREEK.prj: DITTMAR CREEK Base Level Engineering

--- DITTMAR CREEK.g01 (geometry) --- (continued)

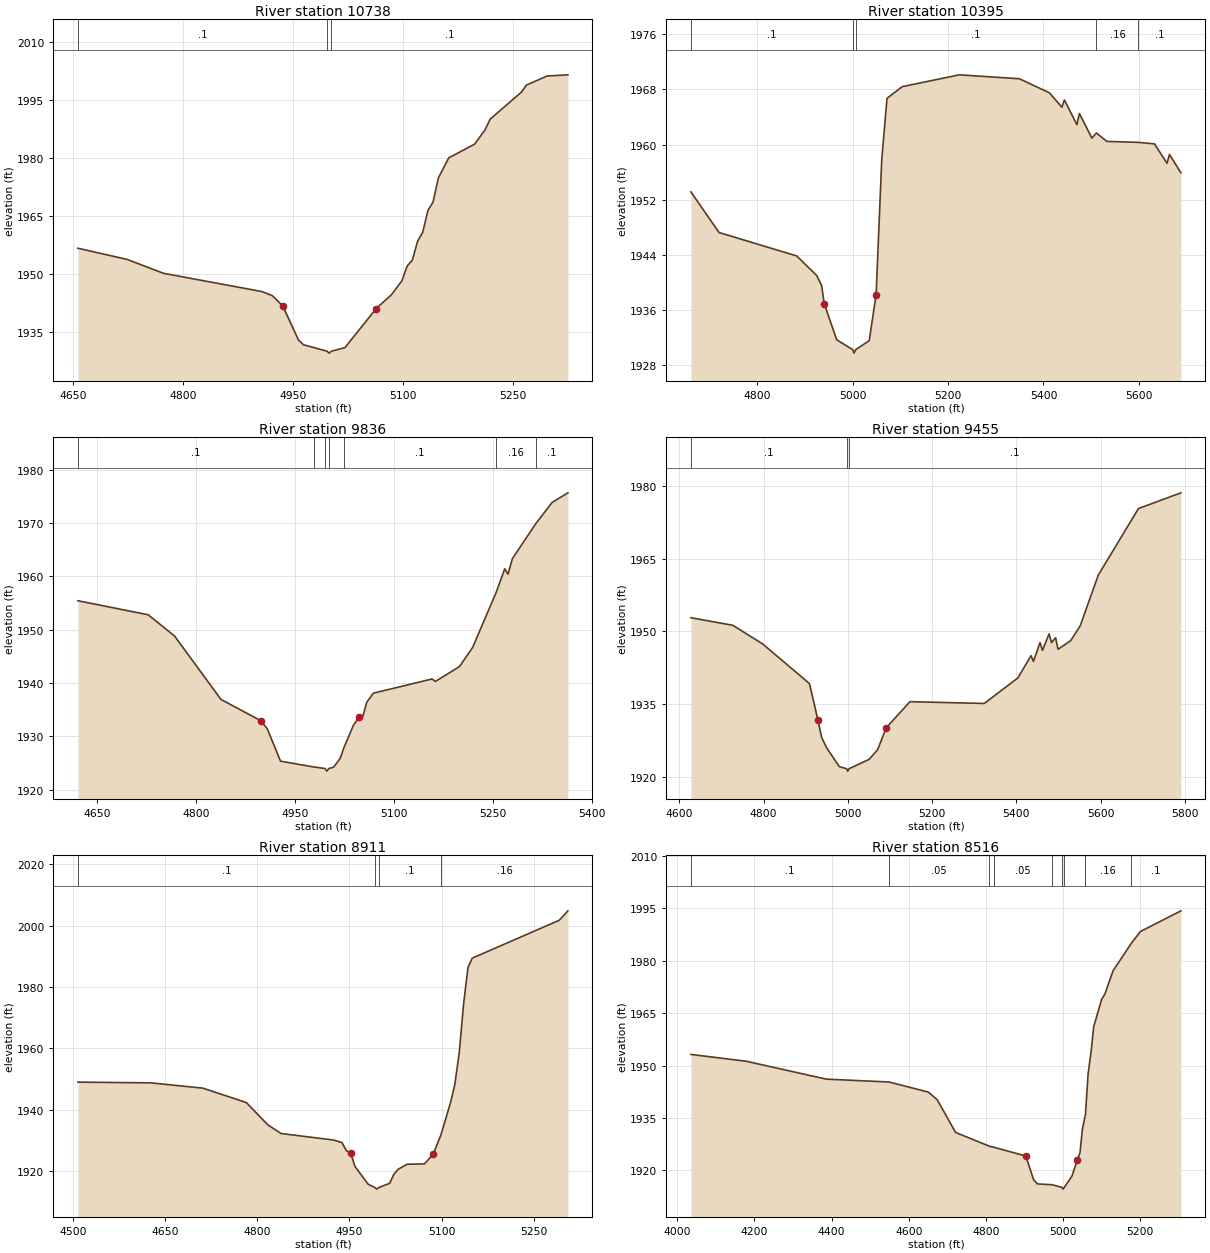
Type RM Length L Ch R = 1 ,10738   ,343,343,343
BEGIN DESCRIPTION:
DITTMAR CREEK 23.0
END DESCRIPTION:
XS GIS Cut Line= 2
      2692096.03     10071521.21       2691633.9     10071038.31
#Sta/Elev= 30
  4656.8 1956.77  4723.9 1953.88  4773.6 1950.29  4907.9 1945.57    4922 1944.51
  4936.2 1941.87  4957.6 1933.08  4964.5 1931.82  4996.7 1930.16  4999.5 1929.66
  5002.7 1930.16  5021.1 1931.09  5063.6 1941.16  5084.6 1944.77  5098.8 1948.38
    5106 1952.19  5112.9 1953.66  5120.2  1958.6  5127.1 1960.88  5134.3 1966.56
  5141.2  1968.7  5148.5 1974.95  5162.6 1980.12  5197.9 1983.67    5212 1987.31
  5219.2 1990.15  5261.7  1997.1  5268.6 1998.94  5296.9 2001.29  5325.2 2001.59
#Mann= 3 ,-1 , 0
  4656.8      .1       0  4996.7     .07       0  5002.7      .1       0
Bank Sta=4936.2,5063.6
XS Rating Curve= 0 ,0
Exp/Cntr=0.3,0.1

Type RM Length L Ch R = 1 ,10395   ,559,559,559
BEGIN DESCRIPTION:
DITTMAR CREEK 22.0
END DESCRIPTION:
XS GIS Cut Line= 2
      2692262.73     10071453.53      2691934.62     10070479.62
#Sta/Elev= 30
  4660.6 1953.14  4719.7 1947.25  4882.4 1943.86  4924.2 1941.04  4934.7 1939.59
  4940.1 1936.96  4966.3 1931.71  5000.1 1930.27  5002.8 1929.77  5006.1 1930.27
  5034.6 1931.58 5049.03 1938.26  5060.8 1957.77  5071.9  1966.7  5103.6 1968.39
  5223.5 1970.11  5349.5 1969.54  5412.4 1967.51  5438.7 1965.42  5443.9 1966.47
  5470.1 1962.89  5475.4 1964.51  5501.6 1960.93  5510.9 1961.68  5533.1 1960.46
  5599.3 1960.32  5632.9  1960.1  5659.1 1957.29  5664.4 1958.57  5688.3 1955.91
#Mann= 5 ,-1 , 0
  4660.6      .1       0  5000.1     .07       0  5006.1      .1       0
  5510.9     .16       0  5599.3      .1       0
Bank Sta=4940.1,5049.03
XS Rating Curve= 0 ,0
Exp/Cntr=0.3,0.1

Type RM Length L Ch R = 1 ,9836    ,381,381,381
BEGIN DESCRIPTION:
DITTMAR CREEK 21.0
END DESCRIPTION:
XS GIS Cut Line= 2
      2692674.18     10071479.58      2692741.89     10070739.98
#Sta/Elev= 30
  4621.2 1955.44  4727.8  1952.8  4767.7 1948.81    4838 1936.93  4898.2 1932.94
  4908.2 1931.43  4928.3 1925.34  4978.5 1924.25  4995.6 1923.97  4998.4 1923.47
  5001.6 1923.97  5008.7  1924.2  5018.7 1925.86  5024.8    1928  5038.8 1932.07
  5047.9 1933.65    5053 1933.69  5058.9 1936.37  5068.9 1938.09    5158 1940.76
    5163 1940.29  5199.5 1943.08  5219.5 1946.67  5255.2 1957.01  5268.1 1961.43
  5273.1 1960.42  5279.8 1963.35  5316.1 1970.05    5340 1973.88  5363.9 1975.68
#Mann= 7 ,-1 , 0
  4621.2      .1       0  4978.5     .16       0  4995.6     .07       0
  5001.6     .16       0  5024.8      .1       0  5255.2     .16       0
  5316.1      .1       0
Bank Sta=4898.2,5047.9
XS Rating Curve= 0 ,0
Exp/Cntr=0.3,0.1

Type RM Length L Ch R = 1 ,9455    ,544,544,544
BEGIN DESCRIPTION:
DITTMAR CREEK 20.0
END DESCRIPTION:
XS GIS Cut Line= 3
      2693017.93     10071542.08      2693101.27     10070974.36
      2693403.33     10070469.18
#Sta/Elev= 30
  4627.8 1952.79  4727.2 1951.23  4797.9 1947.39  4909.1  1939.2  4929.3 1931.61
  4937.9 1928.11  4949.6 1925.98  4979.9 1922.06  4997.1 1921.64  4999.8 1921.14
  5003.1 1921.64  5050.6 1923.57  5070.8 1925.58  5091.1 1930.07  5147.3 1935.47
  5323.7  1935.1  5403.5 1940.38  5434.6 1944.95  5440.4 1943.79    5456 1947.67
  5461.8 1946.05  5477.4 1949.47  5483.2 1947.66    5493 1948.65  5498.8 1946.28
  5528.6 1948.05  5551.3 1951.12  5594.1 1961.57  5689.4 1975.31  5790.2 1978.56
#Mann= 3 ,-1 , 0
  4627.8      .1       0  4997.1     .07       0  5003.1      .1       0
Bank Sta=4929.3,5091.1
XS Rating Curve= 0 ,0
Exp/Cntr=0.3,0.1

Type RM Length L Ch R = 1 ,8911    ,395,395,395
BEGIN DESCRIPTION:
DITTMAR CREEK 19.0
END DESCRIPTION:
XS GIS Cut Line= 2
      2693236.69     10071599.36      2693813.37     10071048.65
#Sta/Elev= 30
  4508.1 1949.01  4626.5 1948.77  4711.4 1947.05  4782.2 1942.35  4817.4 1935.05
  4838.8 1932.26  4923.7 1930.15  4937.8 1929.32  4944.8 1926.71    4952 1925.93
  4958.9 1921.55  4980.3 1915.76  4991.5 1914.64  4994.2 1914.14  4997.5 1914.64
  5015.5 1916.04  5022.4 1919.05  5029.7 1920.66  5043.8 1922.25  5072.1 1922.37
  5086.3 1925.51  5098.9 1931.85  5114.6 1942.38  5121.5 1948.29  5128.7 1958.68
  5135.7 1974.42  5142.9 1986.35  5149.8 1989.41  5291.3 2001.74  5305.5 2004.83
#Mann= 4 ,-1 , 0
  4508.1      .1       0  4991.5     .07       0  4997.5      .1       0
  5098.9     .16       0
Bank Sta=4952,5086.3
XS Rating Curve= 0 ,0
Exp/Cntr=0.3,0.1

Type RM Length L Ch R = 1 ,8516    ,303,303,303
BEGIN DESCRIPTION:
DITTMAR CREEK 18.0
END DESCRIPTION:
XS GIS Cut Line= 3
      2692929.41     10071708.73      2693840.85     10071578.53
      2694048.65       10071298.
#Sta/Elev= 30
  4035.5 1953.18    4179 1951.22  4386.1  1946.1  4548.7 1945.28  4650.7 1942.39
  4673.9 1940.18  4721.4 1930.82  4808.8 1926.89  4821.1 1926.56  4903.3 1924.07
  4923.5 1917.31  4933.6 1916.08  4971.6 1915.83    4997 1915.08  4999.7 1914.58
    5003 1915.08    5023 1918.31  5036.8 1922.94  5043.8 1925.02    5050 1931.71
    5058 1936.05  5064.7 1947.53  5073.1 1954.49  5079.3 1961.12  5100.1 1969.03
  5108.5 1970.53  5129.4 1977.13  5176.6    1985  5200.3 1988.39  5305.3 1994.33
#Mann= 9 ,-1 , 0
  4035.5      .1       0  4548.7     .05       0  4808.8      .1       0
  4821.1     .05       0  4971.6      .1       0    4997     .07       0
    5003      .1       0    5058     .16       0  5176.6      .1       0
Bank Sta=4903.3,5036.8
XS Rating Curve= 0 ,0
Exp/Cntr=0.3,0.1

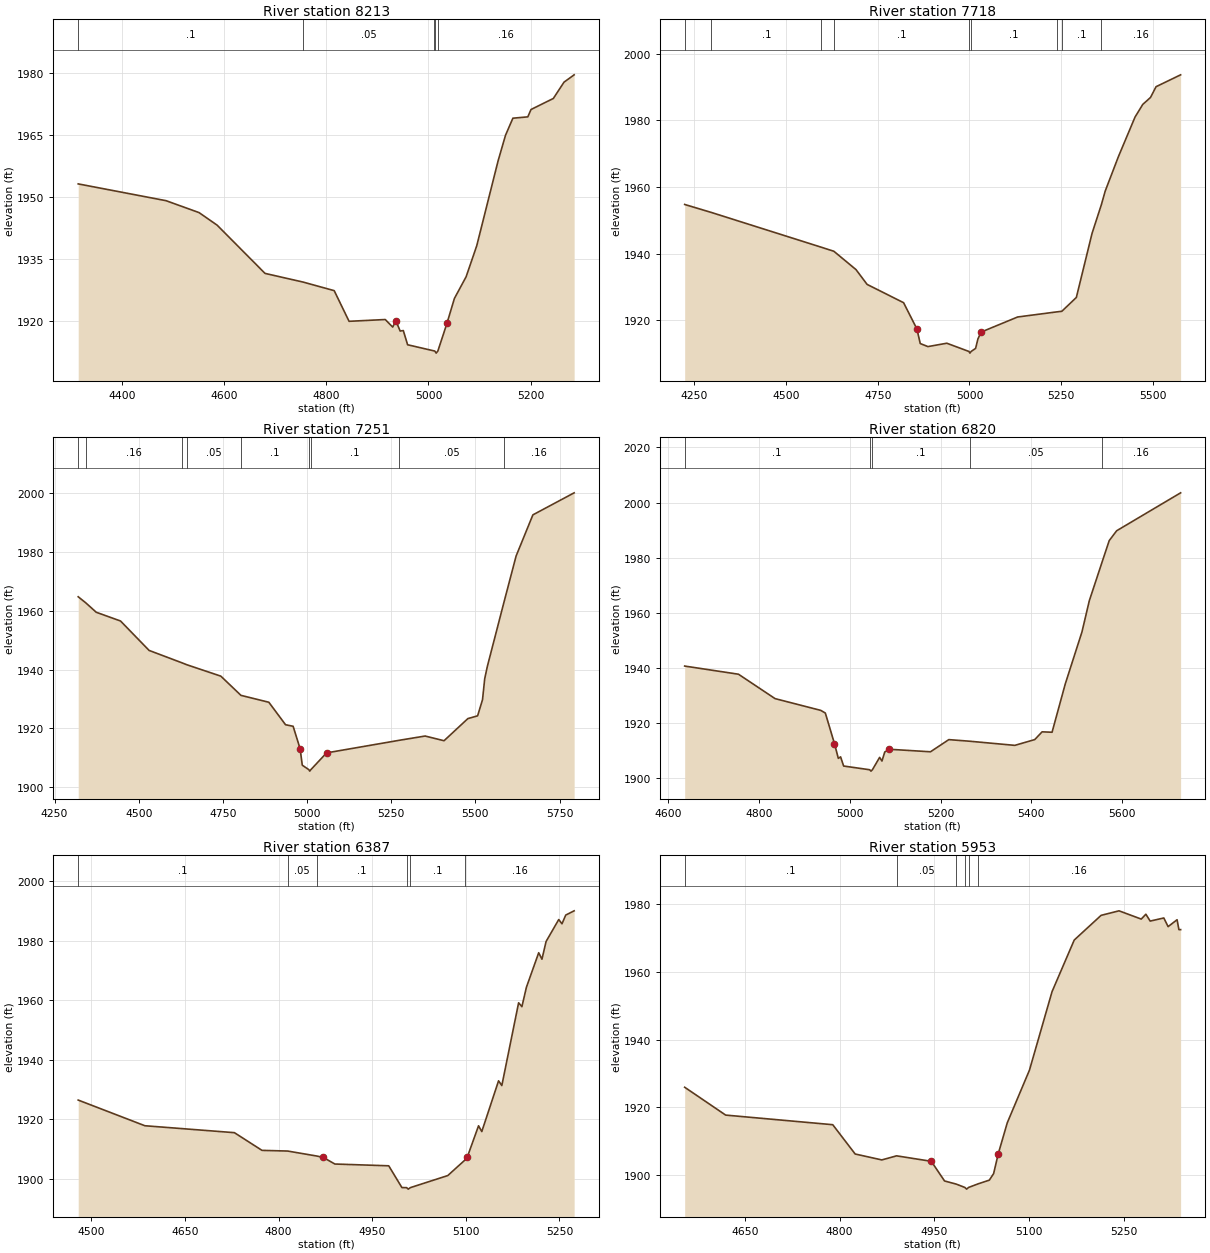
Type RM Length L Ch R = 1 ,8213    ,495,495,495
BEGIN DESCRIPTION:
DITTMAR CREEK 17.0
END DESCRIPTION:
XS GIS Cut Line= 2
      2693481.51     10072208.71      2694257.52      10071625.4
#Sta/Elev= 30
  4314.4 1953.17  4486.4 1949.11    4551 1946.23  4586.4 1943.19  4680.1 1931.54
  4754.7 1929.44  4815.5 1927.37  4844.6 1919.96  4915.4 1920.39    4930 1918.57
  4936.3 1920.06  4944.6 1917.61  4950.8 1917.72  4959.2 1914.29    5010 1912.84
  5012.4 1912.77  5015.1 1912.27  5018.4 1912.77  5036.2 1919.46  5050.8 1925.48
  5073.7 1930.72  5094.5 1938.21  5136.3 1958.73  5150.8 1964.91  5165.3 1969.05
  5194.5 1969.37  5200.8 1971.15  5244.5 1973.82  5265.3 1977.75  5285.2 1979.53
#Mann= 5 ,-1 , 0
  4314.4      .1       0  4754.7     .05       0    5010     .16       0
  5012.4    .035       0  5018.4     .16       0
Bank Sta=4936.3,5036.2
XS Rating Curve= 0 ,0
Exp/Cntr=0.3,0.1

Type RM Length L Ch R = 1 ,7718    ,467,467,467
BEGIN DESCRIPTION:
DITTMAR CREEK 16.0
END DESCRIPTION:
XS GIS Cut Line= 2
      2693570.04     10072672.26      2694700.26     10071932.67
#Sta/Elev= 30
  4224.3 1954.72  4297.3 1952.31  4596.4 1941.89  4630.6 1940.68  4690.9 1935.18
  4721.1 1930.74  4820.5 1925.25  4856.7 1917.39  4865.9 1912.99  4886.9 1912.08
  4938.2 1913.09  4998.5 1910.62  5001.2 1910.12  5004.5 1910.62  5016.6 1911.54
  5023.1 1914.42  5031.7 1916.44  5131.1 1920.96  5237.6 1922.49  5251.5 1922.67
    5291 1926.82  5333.8 1946.05    5359 1954.59  5369.7 1958.76  5405.5 1969.05
  5450.9 1980.95  5471.9 1984.73    5493 1986.82  5508.1 1990.05    5575 1993.61
#Mann= 9 ,-1 , 0
  4224.3     .16       0  4297.3      .1       0  4596.4     .05       0
  4630.6      .1       0  4998.5     .07       0  5004.5      .1       0
  5237.6     .05       0  5251.5      .1       0    5359     .16       0
Bank Sta=4856.7,5031.7
XS Rating Curve= 0 ,0
Exp/Cntr=0.3,0.1

Type RM Length L Ch R = 1 ,7251    ,431,431,431
BEGIN DESCRIPTION:
DITTMAR CREEK 15.0
END DESCRIPTION:
XS GIS Cut Line= 3
      2693747.11     10073078.52      2694403.35      10072557.7
      2694788.74     10072052.52
#Sta/Elev= 30
  4320.3 1964.78  4343.1 1962.68  4373.9  1959.5    4446 1956.53  4530.9 1946.51
  4629.8 1942.23    4643 1941.63    4744 1937.75  4803.7 1931.21  4886.6 1928.86
  4936.2 1921.21  4958.7 1920.68  4979.5 1913.01  4985.9 1907.43  5005.4 1905.91
  5008.1 1905.41  5011.4 1905.91    5058 1911.62  5274.1 1915.91  5350.8 1917.36
    5407 1915.76  5477.7 1923.29  5506.7 1924.24  5521.3 1929.73  5527.8 1936.86
  5535.8 1941.14    5585 1962.92  5621.1 1978.66  5670.9 1992.66  5793.5 2000.17
#Mann= 9 ,-1 , 0
  4320.3      .1       0  4343.1     .16       0  4629.8      .1       0
    4643     .05       0  4803.7      .1       0  5005.4     .07       0
  5011.4      .1       0  5274.1     .05       0    5585     .16       0
Bank Sta=4979.5,5058
XS Rating Curve= 0 ,0
Exp/Cntr=0.3,0.1

Type RM Length L Ch R = 1 ,6820    ,433,433,433
BEGIN DESCRIPTION:
DITTMAR CREEK 14.0
END DESCRIPTION:
XS GIS Cut Line= 3
      2694596.06      10073151.4      2694663.77     10072536.86
      2694887.73     10072120.19
#Sta/Elev= 30
    4637 1940.67  4755.4 1937.71  4835.9 1928.86  4936.5 1924.59  4946.5 1923.63
  4966.6 1912.54  4975.1 1907.18  4980.1 1907.73  4986.8  1904.4  5044.1 1903.05
  5046.9 1902.55  5050.1 1903.05    5066 1907.55  5071.1  1906.2  5077.3  1909.5
  5087.4 1910.48  5177.9 1909.57  5218.2 1913.98  5264.2  1913.4  5363.4  1911.9
  5407.3 1913.99  5423.5 1916.81  5445.4 1916.66  5474.5  1934.2  5511.2 1953.05
  5527.4 1964.39  5555.4 1978.36  5571.2 1986.19  5587.5 1989.76  5728.3 2003.53
#Mann= 5 ,-1 , 0
    4637      .1       0  5044.1     .07       0  5050.1      .1       0
  5264.2     .05       0  5555.4     .16       0
Bank Sta=4966.6,5087.4
XS Rating Curve= 0 ,0
Exp/Cntr=0.3,0.1

Type RM Length L Ch R = 1 ,6387    ,434,434,434
BEGIN DESCRIPTION:
DITTMAR CREEK 13.0
END DESCRIPTION:
XS GIS Cut Line= 3
      2694851.27      10073000.4      2695007.52     10072667.07
      2694877.32     10072260.86
#Sta/Elev= 30
  4478.9 1926.47  4585.7 1917.84  4729.2 1915.51  4773.4 1909.56  4814.6 1909.33
  4861.3 1907.65  4871.5 1907.19  4890.2 1904.97  4976.5 1904.37  4997.6 1897.05
  5005.1 1897.03  5007.8 1896.53  5011.1 1897.03  5071.1 1901.09  5099.4 1906.46
  5102.6 1907.43  5120.4 1917.82  5125.6 1915.88  5152.5 1932.95  5157.7 1931.34
  5184.6 1959.17  5189.9 1957.88  5197.1 1964.39  5216.8    1976    5222 1973.83
  5228.6 1979.77  5248.9 1987.16  5254.1 1985.73  5260.1 1988.66  5273.6 1990.09
#Mann= 6 ,-1 , 0
  4478.9      .1       0  4814.6     .05       0  4861.3      .1       0
  5005.1     .07       0  5011.1      .1       0  5099.4     .16       0
Bank Sta=4871.5,5102.6
XS Rating Curve= 0 ,0
Exp/Cntr=0.3,0.1

Type RM Length L Ch R = 1 ,5953    ,359,359,359
BEGIN DESCRIPTION:
DITTMAR CREEK 12.0
END DESCRIPTION:
XS GIS Cut Line= 2
      2694965.87     10073052.47      2695497.08     10072474.38
#Sta/Elev= 30
  4554.7 1925.94  4619.6 1917.71  4789.1 1914.87  4824.6 1906.21  4866.8 1904.46
  4890.2 1905.67  4945.1 1904.05  4966.1 1898.24  4984.5 1897.32  4998.2 1896.33
    5001 1895.83  5004.2 1896.33  5019.1 1897.38    5037 1898.49  5043.8 1900.44
  5051.2 1906.33  5065.4 1915.44  5100.5 1930.99  5136.3 1954.21  5171.4 1969.45
  5213.9 1976.74  5242.3 1978.08  5277.5 1975.64  5284.8 1977.08  5291.6 1975.05
  5313.2 1975.97    5320 1973.41  5334.2 1975.45  5337.1 1972.52  5339.8 1972.52
#Mann= 6 ,-1 , 0
  4554.7      .1       0  4890.2     .05       0  4984.5      .1       0
  4998.2     .07       0  5004.2      .1       0  5019.1     .16       0
Bank Sta=4945.1,5051.2
XS Rating Curve= 0 ,0
Exp/Cntr=0.3,0.1

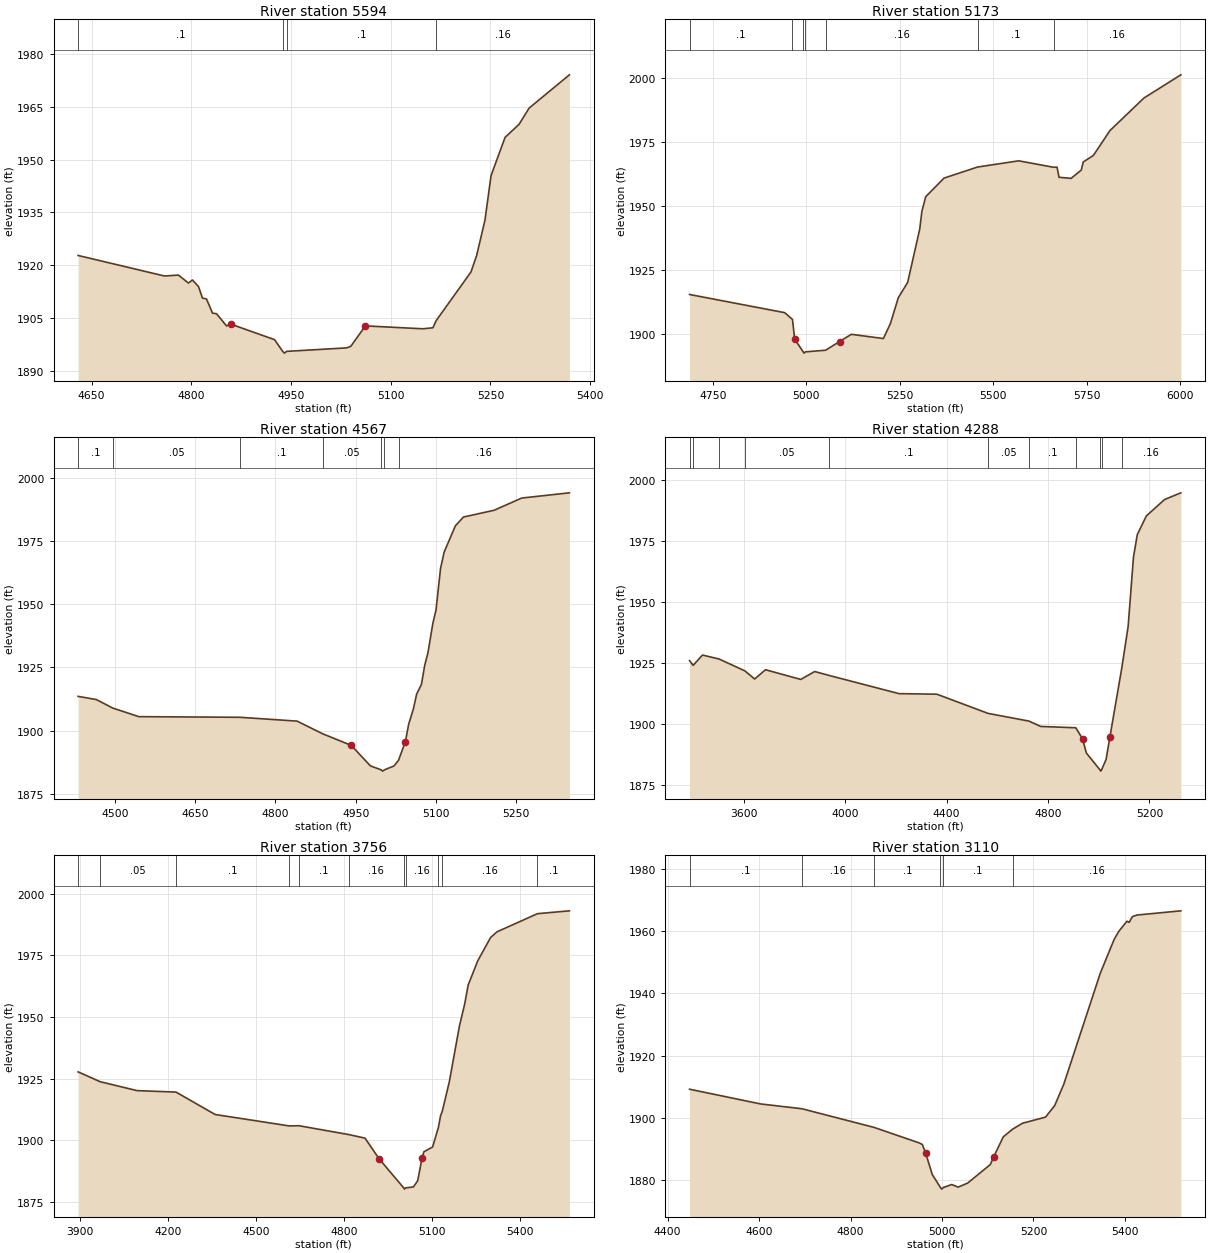
Type RM Length L Ch R = 1 ,5594    ,421,421,421
BEGIN DESCRIPTION:
DITTMAR CREEK 11.0
END DESCRIPTION:
XS GIS Cut Line= 2
      2695340.86     10073245.18      2695746.03     10072627.03
#Sta/Elev= 30
  4629.7 1922.81  4759.6 1916.99  4780.6 1917.25  4795.7 1914.99  4801.7 1915.86
  4810.8    1914  4816.8 1910.73  4822.8  1910.5  4831.9 1906.46  4837.9  1906.3
    4853 1902.84    4859 1903.38  4925.3 1898.94  4937.4 1895.63  4940.2 1895.13
  4943.4 1895.63  5033.9 1896.62  5039.9 1897.06  5061.9 1902.85  5148.4 1902.03
  5163.5 1902.32  5168.1 1904.27  5220.7 1918.13  5229.3 1922.84  5241.8 1932.86
  5250.9 1945.44    5272 1956.28  5293.1 1959.99  5308.2 1964.59  5368.8 1974.01
#Mann= 4 ,-1 , 0
  4629.7      .1       0  4937.4     .07       0  4943.4      .1       0
  5168.1     .16       0
Bank Sta=4859,5061.9
XS Rating Curve= 0 ,0
Exp/Cntr=0.3,0.1

Type RM Length L Ch R = 1 ,5173    ,606,606,606
BEGIN DESCRIPTION:
DITTMAR CREEK 10.0
END DESCRIPTION:
XS GIS Cut Line= 2
      2695799.19     10073406.63      2696192.52     10072152.56
#Sta/Elev= 30
  4687.8 1915.51  4942.4  1908.4  4963.2 1905.75    4969  1898.1  4991.8 1893.08
  4994.5 1892.58  4997.8 1893.08  5051.7 1893.71  5089.1  1897.1  5120.5 1899.93
  5206.5 1898.29  5225.3  1904.2  5246.3 1914.26  5271.3 1920.23  5303.7 1941.14
  5309.2 1947.92  5319.7 1953.76  5368.6 1961.02  5458.4 1965.35  5568.4 1967.77
  5661.8 1965.25  5670.9 1965.32  5676.2 1961.33  5708.6 1960.92  5735.8 1964.17
    5741 1967.33  5768.2 1969.88  5812.2 1979.56  5903.2 1992.31  6002.1  2001.4
#Mann= 7 ,-1 , 0
  4687.8      .1       0  4963.2     .05       0  4991.8    .035       0
  4997.8     .05       0  5051.7     .16       0  5458.4      .1       0
  5661.8     .16       0
Bank Sta=4969,5089.1
XS Rating Curve= 0 ,0
Exp/Cntr=0.3,0.1

Type RM Length L Ch R = 1 ,4567    ,279,279,279
BEGIN DESCRIPTION:
DITTMAR CREEK 9.0
END DESCRIPTION:
XS GIS Cut Line= 2
      2695939.84     10073531.63      2696710.68     10073031.63
#Sta/Elev= 30
  4430.9 1913.54    4465 1912.27  4495.8  1908.9  4544.5 1905.51  4733.6 1905.26
  4840.5 1903.74  4888.1 1898.75  4941.8 1894.14  4977.6 1886.04  4997.7 1884.47
  5000.4 1883.97  5003.7 1884.47  5021.8 1886.03  5030.2 1888.29  5042.9 1895.64
  5049.1 1902.52    5058 1908.64    5064 1914.44  5072.9 1918.22  5079.1  1925.8
  5085.1 1930.72  5094.3 1942.37  5100.2 1947.65  5108.7 1964.12  5115.4 1970.57
  5136.5 1980.99  5151.6 1984.45    5209 1987.13  5260.4 1991.95  5349.7 1994.02
#Mann= 7 ,-1 , 0
  4430.9      .1       0  4495.8     .05       0  4733.6      .1       0
  4888.1     .05       0  4997.7    .035       0  5003.7     .05       0
  5030.2     .16       0
Bank Sta=4941.8,5042.9
XS Rating Curve= 0 ,0
Exp/Cntr=0.3,0.1

Type RM Length L Ch R = 1 ,4288    ,532,532,532
BEGIN DESCRIPTION:
DITTMAR CREEK 8.0
END DESCRIPTION:
XS GIS Cut Line= 3
      2695017.23     10073890.05      2696337.62     10073610.74
      2696823.55     10073280.74
#Sta/Elev= 30
  3386.9 1925.92  3401.2 1923.96  3437.9 1928.19    3503 1926.58  3604.8 1921.72
  3643.7 1918.36  3686.4 1922.16  3825.4 1918.18  3880.2 1921.43  3938.7 1919.78
  4212.8 1912.35    4362 1912.12  4564.2 1904.23  4724.7 1901.09  4771.7 1898.88
  4909.7 1898.34  4936.4 1893.79  4951.4 1887.98  5005.3 1881.04    5008 1880.54
  5011.3 1881.04  5029.3 1885.39  5044.2 1894.55  5091.1 1922.89  5116.1 1939.92
  5137.1 1968.32    5152 1977.59    5188 1985.32  5259.8 1992.04  5323.9 1994.79
#Mann= 11 ,-1 , 0
  3386.9      .1       0  3401.2     .05       0    3503      .1       0
  3604.8     .05       0  3938.7      .1       0  4564.2     .05       0
  4724.7      .1       0  4909.7     .05       0  5005.3    .035       0
  5011.3     .05       0  5091.1     .16       0
Bank Sta=4936.4,5044.2
XS Rating Curve= 0 ,0
Exp/Cntr=0.3,0.1

Type RM Length L Ch R = 1 ,3756    ,646,646,646
BEGIN DESCRIPTION:
DITTMAR CREEK 7.0
END DESCRIPTION:
XS GIS Cut Line= 3
      2695981.44     10074484.81      2697054.39      10073750.4
        2697205.     10073407.65
#Sta/Elev= 30
  3892.6 1927.76    3968 1923.76  4093.5 1920.16  4226.3 1919.57  4359.6 1910.49
    4612 1905.87  4645.3 1905.94  4815.2 1902.36  4870.6 1900.91    4919 1892.46
  5002.5 1880.76  5005.2 1880.26  5008.5 1880.76  5035.3 1881.13  5050.2 1883.67
  5064.5 1892.69  5071.2 1895.39  5100.8 1897.31  5120.6 1905.25    5128 1909.96
  5134.1 1911.91  5157.9 1923.76  5192.3 1946.29  5210.5 1955.39    5222 1962.88
  5254.7 1972.72  5298.4 1982.16  5320.3 1984.48  5458.2 1991.83  5567.2 1992.99
#Mann= 11 ,-1 , 0
  3892.6      .1       0    3968     .05       0  4226.3      .1       0
    4612     .05       0  4645.3      .1       0  4815.2     .16       0
  5002.5     .07       0  5008.5     .16       0  5120.6      .1       0
  5134.1     .16       0  5458.2      .1       0
Bank Sta=4919,5064.5
XS Rating Curve= 0 ,0
Exp/Cntr=0.3,0.1

Type RM Length L Ch R = 1 ,3110    ,442,442,442
BEGIN DESCRIPTION:
DITTMAR CREEK 6.0
END DESCRIPTION:
XS GIS Cut Line= 3
      2697002.28     10074677.52      2697476.27     10074161.86
      2697486.66     10073787.81
#Sta/Elev= 30
  4447.8 1909.22  4603.2 1904.49  4693.7 1902.95  4851.5 1896.96  4950.3 1891.98
  4957.1 1891.47  4964.5 1888.62  4978.7 1881.84  4996.7 1877.66  4999.4 1877.16
  5002.7 1877.66  5021.2 1878.64  5035.4  1877.8  5056.4 1879.13  5105.7 1885.05
  5113.1 1887.55  5134.1 1893.95  5154.7 1896.43  5176.3 1898.31  5226.4 1900.26
  5246.4 1903.94  5266.4 1910.84  5346.4 1946.51  5376.4 1957.25  5386.4 1959.81
  5404.4  1963.1  5409.4 1962.77  5416.4 1964.59  5426.4  1965.1  5522.4 1966.45
#Mann= 6 ,-1 , 0
  4447.8      .1       0  4693.7     .16       0  4851.5      .1       0
  4996.7     .07       0  5002.7      .1       0  5154.7     .16       0
Bank Sta=4964.5,5113.1
XS Rating Curve= 0 ,0
Exp/Cntr=0.3,0.1

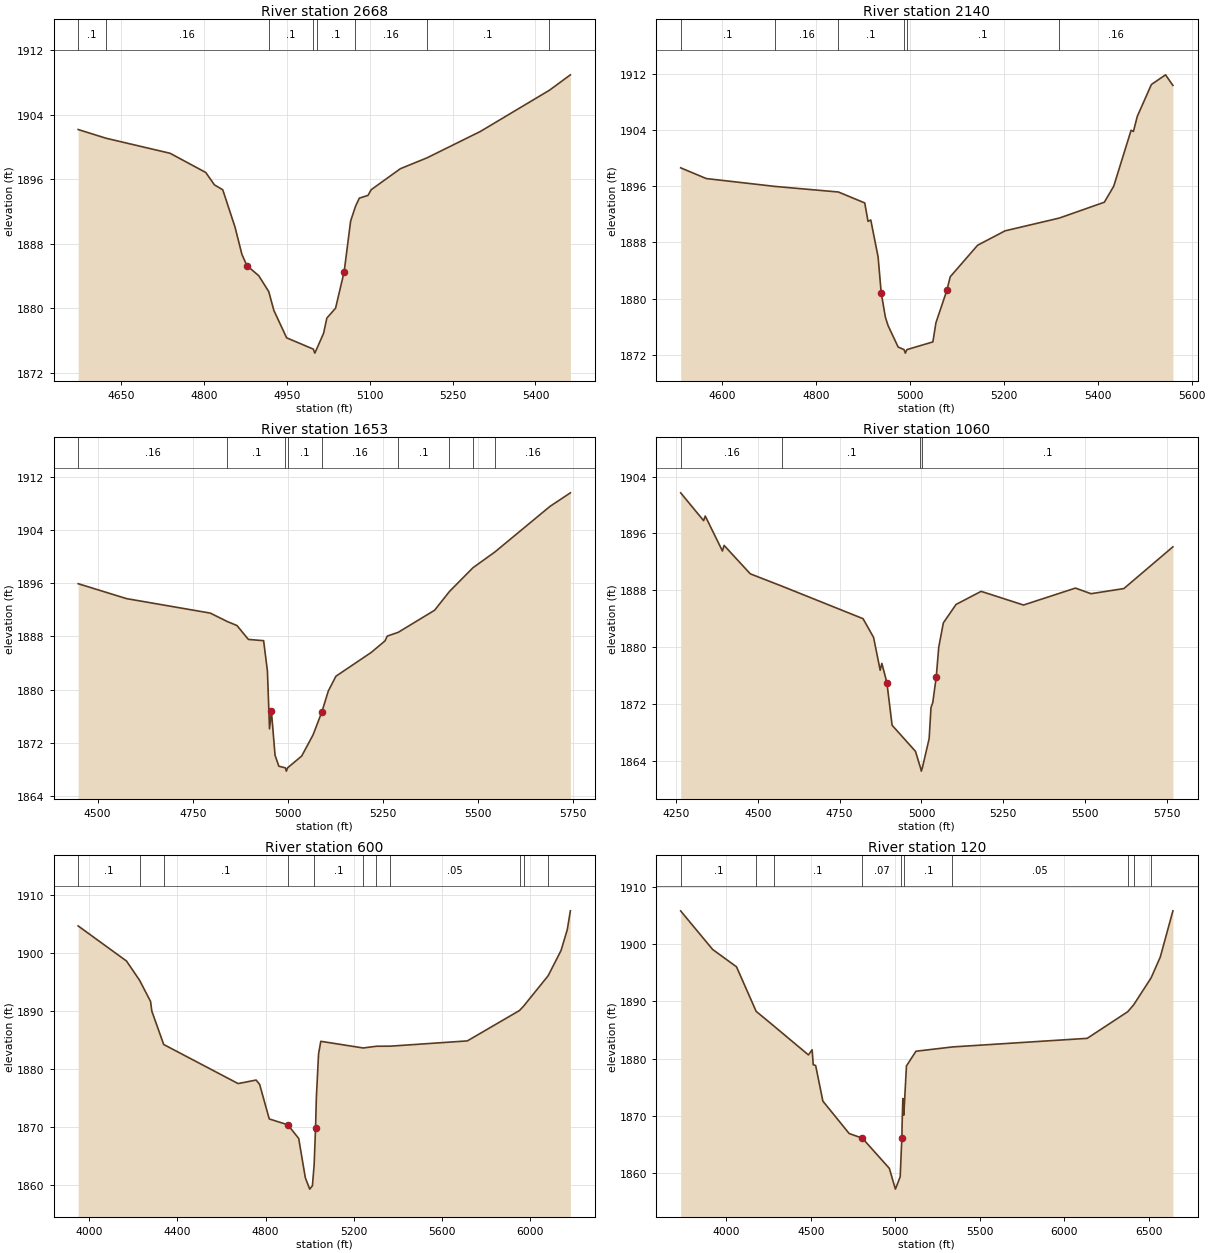
Type RM Length L Ch R = 1 ,2668    ,528,528,528
BEGIN DESCRIPTION:
DITTMAR CREEK 5.0
END DESCRIPTION:
XS GIS Cut Line= 2
      2697528.34     10074870.21      2697976.25      10074099.4
#Sta/Elev= 30
  4571.8 1902.17  4622.2 1901.09  4738.3 1899.22  4802.9 1896.84  4818.6  1895.3
  4833.7 1894.69  4855.9 1890.06  4868.4 1886.67  4877.4 1885.28  4898.9 1884.02
    4917 1882.05  4926.3 1879.71  4949.4 1876.31  4997.7 1874.91  5000.5 1874.41
  5003.7 1874.91  5016.4 1876.89  5022.2 1878.76    5038 1879.99  5053.5 1884.49
  5065.3 1890.81  5074.1 1892.63    5081 1893.65  5096.7 1893.99  5102.5  1894.7
  5155.5 1897.31  5203.5 1898.65  5300.3 1901.93  5425.4 1907.05  5463.3 1908.96
#Mann= 8 ,-1 , 0
  4571.8      .1       0  4622.2     .16       0    4917      .1       0
  4997.7     .07       0  5003.7      .1       0  5074.1     .16       0
  5203.5      .1       0  5425.4     .16       0
Bank Sta=4877.4,5053.5
XS Rating Curve= 0 ,0
Exp/Cntr=0.3,0.1

Type RM Length L Ch R = 1 ,2140    ,487,487,487
BEGIN DESCRIPTION:
DITTMAR CREEK 4.0
END DESCRIPTION:
XS GIS Cut Line= 3
      2697898.15     10075239.97      2698278.35     10074604.57
      2698257.57     10074298.03
#Sta/Elev= 30
  4512.4 1898.65  4566.9 1897.12  4712.8    1896  4848.1  1895.2  4904.2 1893.64
  4911.2 1891.01    4917 1891.21  4932.6 1885.95  4939.2 1880.83  4948.1 1877.35
  4953.9 1876.13  4975.3 1873.08  4987.9 1872.71  4990.6 1872.21  4993.9 1872.71
  5049.2 1873.81  5055.7 1876.54    5079 1881.18  5086.2 1883.11  5144.5 1887.61
  5202.9 1889.66  5318.2 1891.48  5414.1 1893.74  5434.1 1896.02  5471.1 1904.01
  5476.1 1903.84  5484.2 1905.98  5514.3 1910.54  5544.4 1911.92  5560.1 1910.41
#Mann= 6 ,-1 , 0
  4512.4      .1       0  4712.8     .16       0  4848.1      .1       0
  4987.9     .07       0  4993.9      .1       0  5318.2     .16       0
Bank Sta=4939.2,5079
XS Rating Curve= 0 ,0
Exp/Cntr=0.3,0.1

Type RM Length L Ch R = 1 ,1653    ,593,593,593
BEGIN DESCRIPTION:
DITTMAR CREEK 3.0
END DESCRIPTION:
XS GIS Cut Line= 3
      2698606.48     10075390.98      2698616.89     10074641.03
      2698325.22     10074182.69
#Sta/Elev= 30
  4448.7 1895.94    4576 1893.69    4796 1891.51  4840.3 1890.25    4866 1889.64
    4896 1887.55    4936 1887.36    4946 1882.79  4951.5 1874.09  4956.5 1876.74
    4966 1870.12    4976 1868.46    4993 1868.22  4995.8 1867.72    4999 1868.22
    5036 1869.99    5066 1873.19  5088.9 1876.62    5106 1879.79    5126 1882.01
  5218.5 1885.58  5254.8 1887.32  5260.8 1888.05  5289.7 1888.62  5385.2 1891.94
  5424.3 1894.77    5486 1898.34  5544.2 1900.74  5688.4 1907.58    5742 1909.62
#Mann= 9 ,-1 , 0
  4448.7     .16       0  4840.3      .1       0    4993     .07       0
    4999      .1       0  5088.9     .16       0  5289.7      .1       0
  5424.3     .16       0    5486      .1       0  5544.2     .16       0
Bank Sta=4956.5,5088.9
XS Rating Curve= 0 ,0
Exp/Cntr=0.3,0.1

Type RM Length L Ch R = 1 ,1060    ,460,460,460
BEGIN DESCRIPTION:
DITTMAR CREEK 2.0
END DESCRIPTION:
XS GIS Cut Line= 3
       2699059.6     10075312.89      2699179.39     10074677.49
      2698846.67     10073887.27
#Sta/Elev= 30
  4264.3 1901.71  4334.4  1897.8  4339.4 1898.45  4391.9 1893.54    4397 1894.32
  4477.1 1890.32  4574.9 1888.57  4821.5 1884.02  4853.7 1881.39  4873.9 1876.77
    4879 1877.74  4894.4 1875.02  4910.3 1869.04  4981.6 1865.38  4996.9 1863.09
  4999.7 1862.59  5002.9 1863.09  5023.5 1867.16  5029.1 1871.52  5034.5 1872.21
  5045.2 1875.83  5052.8 1880.01  5066.9 1883.43  5105.7 1886.02  5182.3 1887.86
  5311.9 1885.94  5470.5 1888.32    5518 1887.53  5618.4 1888.25  5768.3 1894.12
#Mann= 4 ,-1 , 0
  4264.3     .16       0  4574.9      .1       0  4996.9     .07       0
  5002.9      .1       0
Bank Sta=4894.4,5045.2
XS Rating Curve= 0 ,0
Exp/Cntr=0.3,0.1

Type RM Length L Ch R = 1 ,600     ,480,480,480
BEGIN DESCRIPTION:
Mapping XS 0d575401
END DESCRIPTION:
XS GIS Cut Line= 4
      2699125.16     10075416.03      2699580.89      10074587.9
       2699586.1     10074358.74      2698813.82     10073638.46
#Sta/Elev= 30
  3950.5 1904.68  4169.7 1898.62  4228.6 1895.32  4278.6 1891.66  4284.3 1889.99
  4338.2 1884.23  4675.4 1877.49  4756.9  1878.1  4772.9 1877.35  4816.5 1871.39
  4900.3 1870.39  4949.9 1868.03  4979.9 1861.26  4999.7 1859.29    5012 1859.86
  5019.9 1863.51  5026.2 1869.82  5029.9  1875.1  5039.9 1882.61    5050 1884.78
  5242.3 1883.63  5302.2 1883.93  5364.3 1883.94    5714 1884.85  5950.4 1890.09
  5969.3 1890.86  6080.1 1896.08  6138.5 1900.43  6166.9 1904.04    6181 1907.28
#Mann= 11 ,-1 , 0
  3950.5      .1       0  4228.6     .05       0  4338.2      .1       0
  4900.3     .07       0  5019.9      .1       0  5242.3     .05       0
  5302.2      .1       0  5364.3     .05       0  5950.4      .1       0
  5969.3     .05       0  6080.1      .1       0
Bank Sta=4900.3,5026.2
XS Rating Curve= 0 ,0
Exp/Cntr=0.3,0.1

Type RM Length L Ch R = 1 ,120     ,0,0,0
BEGIN DESCRIPTION:
DITTMAR CREEK 1.0
END DESCRIPTION:
XS GIS Cut Line= 4
      2699101.74     10075473.31       2699963.7     10074723.32
      2700073.08     10074541.03      2698914.24     10073501.98
#Sta/Elev= 30
  3730.4 1905.77  3919.2 1899.06  4060.7 1896.02  4176.9 1888.25  4280.7 1885.72
  4486.1 1880.65  4507.9 1881.54  4514.5 1878.94  4528.8  1878.8  4571.5 1872.59
  4727.2 1866.93  4805.1 1866.12  4964.8 1860.85  5000.5 1857.23    5029  1859.4
  5035.8 1864.32  5039.2 1866.22    5040  1868.4  5044.5 1873.04  5050.3 1870.14
  5051.7 1870.93  5065.9 1878.73  5122.1 1881.29    5338 1882.04  6135.1 1883.54
  6374.9 1888.19  6409.7 1889.38  6513.2  1894.1  6567.2 1897.72    6642 1905.79
#Mann= 10 ,-1 , 0
  3730.4      .1       0  4176.9     .05       0  4280.7      .1       0
  4805.1     .07       0  5035.8     .16       0  5051.7      .1       0
    5338     .05       0  6374.9      .1       0  6409.7     .05       0
  6513.2      .1       0
Bank Sta=4805.1,5039.2
XS Rating Curve= 0 ,0
Exp/Cntr=0.3,0.1

Chan Stop Cuts=-1
Use User Specified Reach Order=0
Composite Channel Slope=5