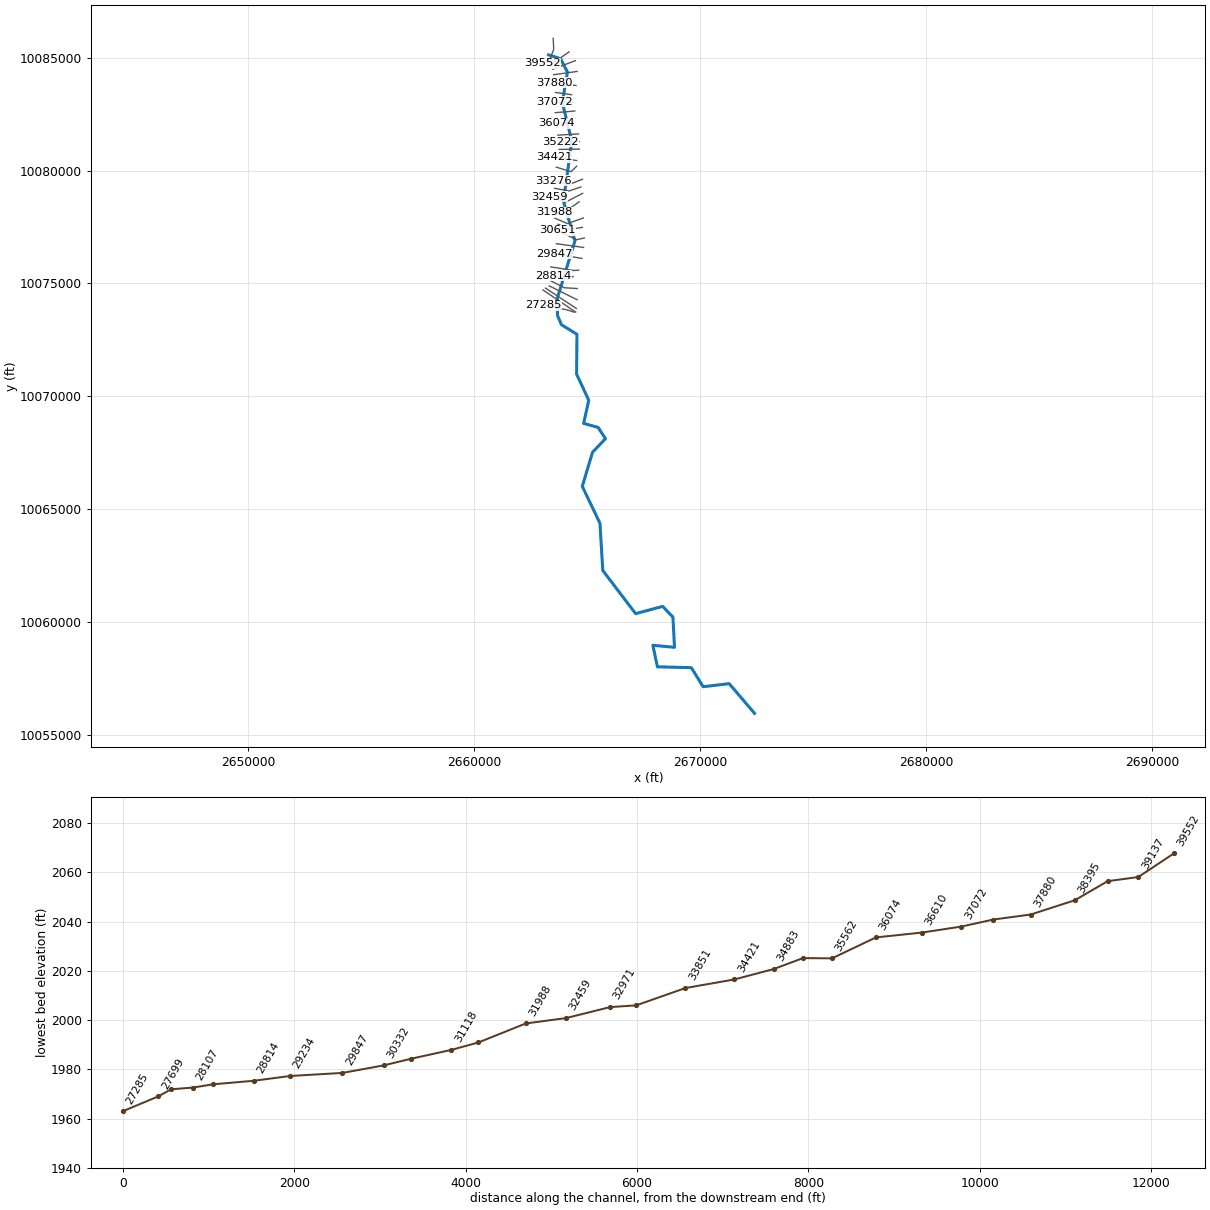
--- FLAG CREEK.prj (project) ---

Proj Title=FLAG CREEK Base Level Engineering
Current Plan=p01
Default Exp/Contr=0.3,0.1
English Units
Geom File=g01
Flow File=f01
Plan File=p01
Y Axis Title=Elevation
X Axis Title(PF)=Main Channel Distance
X Axis Title(XS)=Station
BEGIN DESCRIPTION:
FLAG CREEK
END DESCRIPTION:
DSS Export Rating Curves= 0
DSS Export Rating Curve Sorted= 0
DSS Export Volume Flow Curves= 0
DXF OffsetX= 0
DXF OffsetY= 0
DXF ScaleX= 1
DXF ScaleY= 10

--- FLAG CREEK.p01 (plan) ---

Plan Title=Multiple Run
Short Identifier=Multiple
Geom File=g01
Flow File=f01
Subcritical Flow
K Sum by GR= 0
Std Step Tol= 0.01
Critical Tol= 0.01
Num of Std Step Trials= 20
Max Error Tol= 0.3
Flow Tol Ratio= 0.001
Split Flow NTrial= 30
Split Flow Tol= 0.02
Split Flow Ratio= 0.02
Log Output Level= 0
Friction Slope Method= 1
Unsteady Friction Slope Method= 2
Unsteady Bridges Friction Slope Method= 1
Parabolic Critical Depth
Global Vel Dist=  1 , 1 , 1
Global Log Level= 0
CheckData=True
Encroach Param= -1, 0, 0, 0
BEGIN DESCRIPTION:
Multiple Run
END DESCRIPTION:

--- FLAG CREEK.f01 (steady flow) ---

Flow Title=Multiple
Number of Profiles=7
Profile Names=10-year,25-year,50-year,1pct_min,100-year,1pct_plu,500-year
River Rch & RM= FLAG CREEK,Reach-1,39552
    1006    1461    1855    1717    2322    3140    3638
River Rch & RM= FLAG CREEK,Reach-1,39137
    1739    2602    3366    3169    4286    5796    6956
River Rch & RM= FLAG CREEK,Reach-1,35222
    2135    3223    4195    3970    5370    7262    8807
River Rch & RM= FLAG CREEK,Reach-1,33276
    3367    5185    6839    6549    8857   11978   14876
River Rch & RM= FLAG CREEK,Reach-1,29234
    3844    5951    7876    7566   10232   13837   17293
River Rch & RM= FLAG CREEK,Reach-1,27699
    4164    6462    8566    8239   11142   15068   18879
River Rch & RM= FLAG CREEK,Reach-1,23436
    4376    6785    8989    8637   11681   15797   19756
River Rch & RM= FLAG CREEK,Reach-1,16861
    6217    9726   12962   12515   16925   22889   28896
River Rch & RM= FLAG CREEK,Reach-1,9834
    6207    9679   12870   12397   16765   22673   28484
Boundary for River Rch & Prof#=FLAG CREEK,Reach-1,1
Up Type=0
Dn Type=3
Dn Slope=0.005
Boundary for River Rch & Prof#=FLAG CREEK,Reach-1,2
Up Type=0
Dn Type=3
Dn Slope=0.005
Boundary for River Rch & Prof#=FLAG CREEK,Reach-1,3
Up Type=0
Dn Type=3
Dn Slope=0.005
Boundary for River Rch & Prof#=FLAG CREEK,Reach-1,4
Up Type=0
Dn Type=3
Dn Slope=0.005
Boundary for River Rch & Prof#=FLAG CREEK,Reach-1,5
Up Type=0
Dn Type=3
Dn Slope=0.005
Boundary for River Rch & Prof#=FLAG CREEK,Reach-1,6
Up Type=0
Dn Type=3
Dn Slope=0.005
Boundary for River Rch & Prof#=FLAG CREEK,Reach-1,7
Up Type=0
Dn Type=3
Dn Slope=0.005

--- FLAG CREEK.g01 (geometry) ---

Geom Title=Existing Conditions
Program Version=4.10

River Reach=FLAG CREEK      ,Reach-1
Reach XY= 30
      2663282.04     10085123.68      2663811.72     10084950.13
      2664116.69     10084358.19      2663888.51     10083023.72
      2664307.97      10081298.4      2663938.64     10078638.81
      2664447.74     10076887.99      2663663.06     10074332.94
      2663673.53     10073594.73      2663849.33     10073174.66
      2664535.73      10072752.6      2664520.25     10070989.05
      2665057.94     10069828.45      2664831.76     10068805.19
      2665475.04     10068625.65      2665797.76     10068128.76
       2665224.2      10067526.4      2664772.81     10066017.18
       2665553.3     10064386.71      2665679.76     10062293.84
      2667131.69      10060381.8      2668329.37     10060703.66
      2668781.49     10060230.29      2668853.09     10058891.31
      2667894.36     10058980.95      2668095.57     10058028.44
      2669597.03      10057990.1      2670119.69     10057146.42
      2671273.27     10057283.26      2672393.52     10055966.53

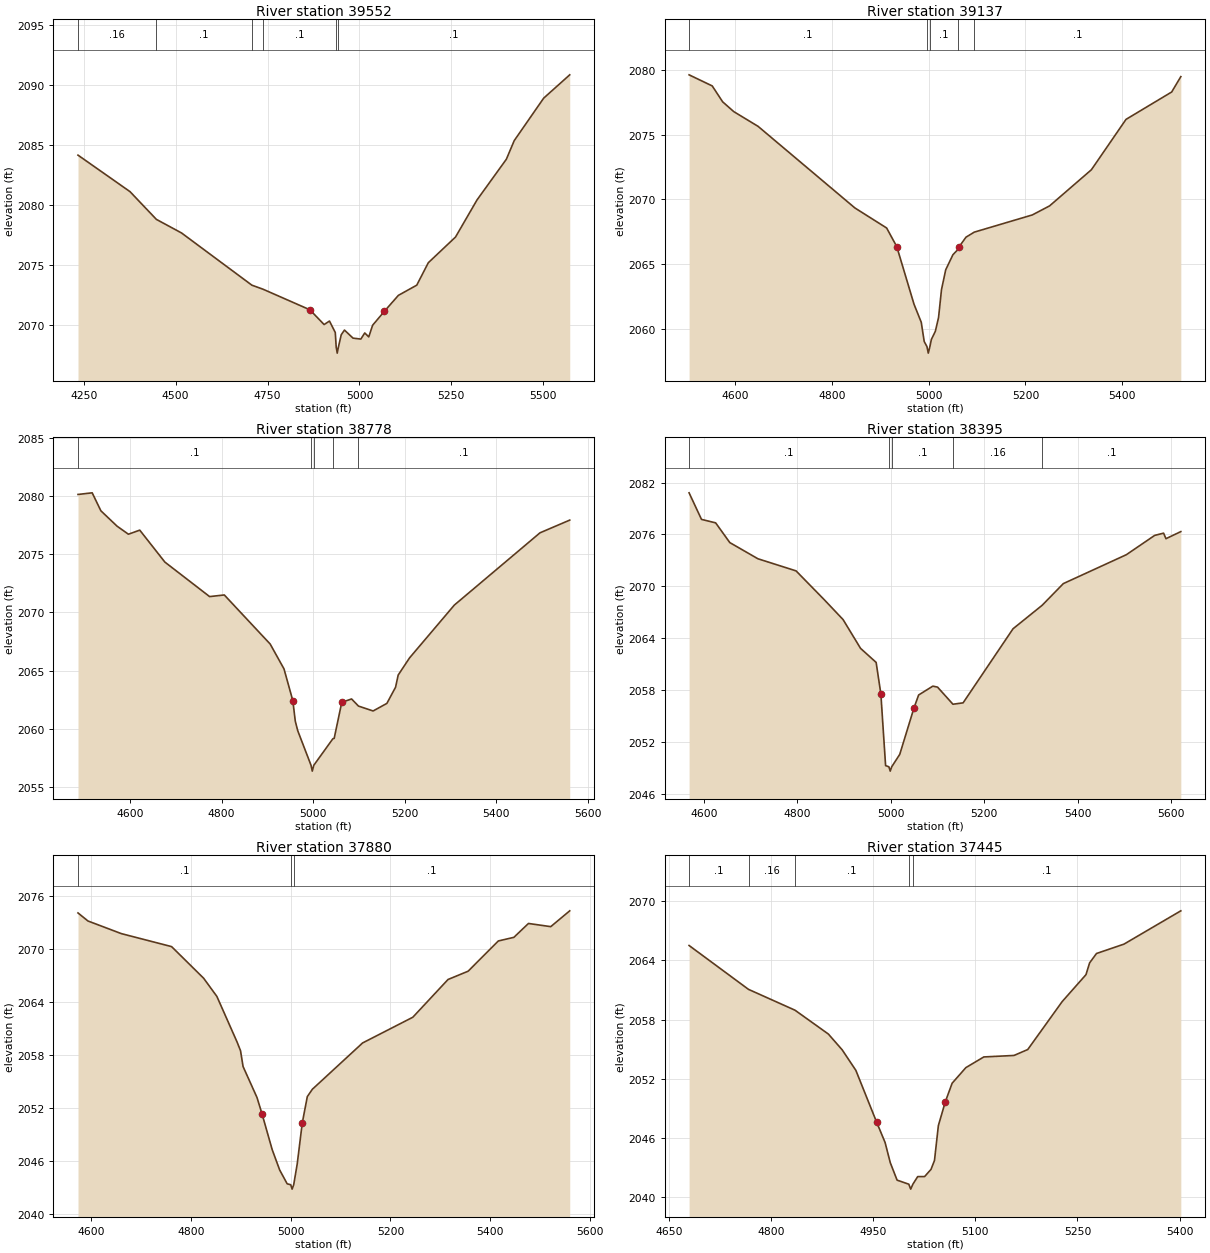
Type RM Length L Ch R = 1 ,39552   ,415,415,415
BEGIN DESCRIPTION:
FLAG CREEK 73.0
END DESCRIPTION:
XS GIS Cut Line= 4
      2663484.48     10085855.03      2663507.24     10085368.09
      2663357.07      10084963.1      2662997.59     10084749.23
#Sta/Elev= 30
  4234.3 2084.17  4375.8 2081.13  4447.5 2078.82  4515.9 2077.69  4707.3 2073.34
  4737.9    2073  4865.1 2071.29  4903.8 2070.06  4918.4 2070.35  4934.2  2069.4
  4936.7 2068.18  4939.5 2067.68  4942.7 2068.18  4950.4 2069.21  4959.2  2069.6
  4982.4 2068.93  5003.7 2068.85  5014.4 2069.36  5025.3 2069.03  5035.7    2070
  5067.7 2071.16  5105.8 2072.49  5155.8 2073.34  5187.3 2075.21  5261.3 2077.35
  5319.8 2080.44  5399.6 2083.83    5421 2085.38  5501.2 2088.92    5572 2090.86
#Mann= 6 ,-1 , 0
  4234.3     .16       0  4447.5      .1       0  4707.3     .16       0
  4737.9      .1       0  4936.7     .07       0  4942.7      .1       0
Bank Sta=4865.1,5067.7
XS Rating Curve= 0 ,0
Exp/Cntr=0.3,0.1

Type RM Length L Ch R = 1 ,39137   ,359,359,359
BEGIN DESCRIPTION:
FLAG CREEK 72.0
END DESCRIPTION:
XS GIS Cut Line= 2
      2664185.24     10085254.32      2663353.01     10084672.21
#Sta/Elev= 30
  4505.3 2079.65  4553.1 2078.79  4574.6 2077.56  4597.6  2076.8  4647.8 2075.66
  4847.8 2069.34  4913.3 2067.79  4934.2 2066.35  4969.9 2061.88  4984.8 2060.49
  4990.9    2059  4996.6  2058.6  4999.3  2058.1  5002.6  2058.6  5005.7 2059.16
  5013.9 2059.79  5020.5 2060.85  5026.6 2063.02  5035.3 2064.55  5050.2 2065.72
  5059.7 2066.09  5062.7 2066.32  5077.2 2067.08  5094.4 2067.47  5214.1  2068.8
  5249.8  2069.5  5336.2  2072.3  5407.7  2076.2    5502 2078.32  5520.9 2079.51
#Mann= 5 ,-1 , 0
  4505.3      .1       0  4996.6     .07       0  5002.6      .1       0
  5059.7     .16       0  5094.4      .1       0
Bank Sta=4934.2,5062.7
XS Rating Curve= 0 ,0
Exp/Cntr=0.3,0.1

Type RM Length L Ch R = 1 ,38778   ,383,383,383
BEGIN DESCRIPTION:
FLAG CREEK 71.0
END DESCRIPTION:
XS GIS Cut Line= 2
       2664467.4     10084867.55      2663462.64     10084485.64
#Sta/Elev= 30
  4486.2 2080.12  4517.2 2080.26  4536.2 2078.72  4571.6  2077.4  4596.4 2076.71
  4621.2 2077.06  4676.1 2074.32  4773.9 2071.36    4806  2071.5  4906.3 2067.29
  4936.5 2065.16  4955.8 2062.43  4961.2 2060.67  4966.6 2059.85  4995.6 2056.89
  4998.3 2056.39  5001.6 2056.89  5043.4 2059.17  5046.2  2059.2  5062.8 2062.29
  5084.2 2062.58  5099.3 2061.97  5131.3 2061.55  5161.4  2062.2  5180.4 2063.59
  5186.1 2064.63  5210.9  2066.1  5308.8 2070.63  5496.1 2076.83  5561.1 2077.92
#Mann= 5 ,-1 , 0
  4486.2      .1       0  4995.6     .07       0  5001.6      .1       0
  5043.4     .16       0  5099.3      .1       0
Bank Sta=4955.8,5062.8
XS Rating Curve= 0 ,0
Exp/Cntr=0.3,0.1

Type RM Length L Ch R = 1 ,38395   ,515,515,515
BEGIN DESCRIPTION:
FLAG CREEK 70.0
END DESCRIPTION:
XS GIS Cut Line= 2
      2664544.74     10084389.74      2663503.06     10084244.18
#Sta/Elev= 30
  4568.6 2080.81  4595.1 2077.74  4625.4 2077.34  4655.7 2075.06  4715.8 2073.19
  4797.4 2071.79  4857.7 2068.46    4898 2066.16  4935.3 2062.84  4968.7 2061.21
  4978.8 2057.57  4988.9 2049.29    4996 2049.15  4998.8 2048.65    5002 2049.15
  5019.2 2050.59  5049.5 2055.93  5059.6 2057.45  5089.9 2058.47    5100 2058.36
    5133 2056.38  5154.7 2056.54  5261.5  2065.1  5323.7 2067.81  5369.1 2070.32
  5503.9 2073.66  5564.5 2075.89  5583.5 2076.15  5588.6 2075.51  5620.4 2076.33
#Mann= 5 ,-1 , 0
  4568.6      .1       0    4996     .07       0    5002      .1       0
    5133     .16       0  5323.7      .1       0
Bank Sta=4978.8,5049.5
XS Rating Curve= 0 ,0
Exp/Cntr=0.3,0.1

Type RM Length L Ch R = 1 ,37880   ,435,435,435
BEGIN DESCRIPTION:
FLAG CREEK 69.0
END DESCRIPTION:
XS GIS Cut Line= 2
      2664494.69     10083766.33      2663516.35     10083893.74
#Sta/Elev= 30
  4573.1 2074.11  4593.1  2073.2  4660.1 2071.77  4760.9  2070.3  4825.2 2066.72
  4851.7 2064.67    4892 2059.54  4899.2 2058.52  4904.3 2056.73  4932.3 2053.22
  4942.4 2051.36  4962.6 2047.35  4977.7 2045.03  4992.8 2043.46  4999.9 2043.36
  5002.7 2042.86  5005.9 2043.36    5013 2045.74  5023.1 2050.36  5033.2 2053.33
  5043.3 2054.16  5144.1  2059.4  5244.9 2062.31  5315.5 2066.58  5355.9 2067.52
  5416.4 2070.94  5447.6 2071.35  5476.9 2072.92  5521.6 2072.56  5559.7 2074.35
#Mann= 3 ,-1 , 0
  4573.1      .1       0  4999.9     .07       0  5005.9      .1       0
Bank Sta=4942.4,5023.1
XS Rating Curve= 0 ,0
Exp/Cntr=0.3,0.1

Type RM Length L Ch R = 1 ,37445   ,373,373,373
BEGIN DESCRIPTION:
FLAG CREEK 68.0
END DESCRIPTION:
XS GIS Cut Line= 2
      2664301.03     10083360.31      2663585.81     10083457.53
#Sta/Elev= 30
  4679.9  2065.5  4767.1 2061.06  4835.4 2058.95  4884.3 2056.54  4904.5 2054.95
  4924.7 2052.86    4955 2047.65  4967.6 2045.56  4975.2 2043.52  4985.2 2041.75
  5002.4 2041.34  5005.2 2040.84  5008.4 2041.34  5015.5 2042.11  5025.6 2042.11
    5035 2042.84  5040.1 2043.74  5045.8 2047.27  5055.9 2049.66    5066 2051.56
  5086.2 2053.14  5112.5 2054.22  5156.8 2054.37    5177 2054.97  5227.5 2059.82
  5262.5 2062.55  5267.8 2063.74  5277.9 2064.69  5318.3 2065.64  5401.7 2069.01
#Mann= 5 ,-1 , 0
  4679.9      .1       0  4767.1     .16       0  4835.4      .1       0
  5002.4     .07       0  5008.4      .1       0
Bank Sta=4955,5055.9
XS Rating Curve= 0 ,0
Exp/Cntr=0.3,0.1

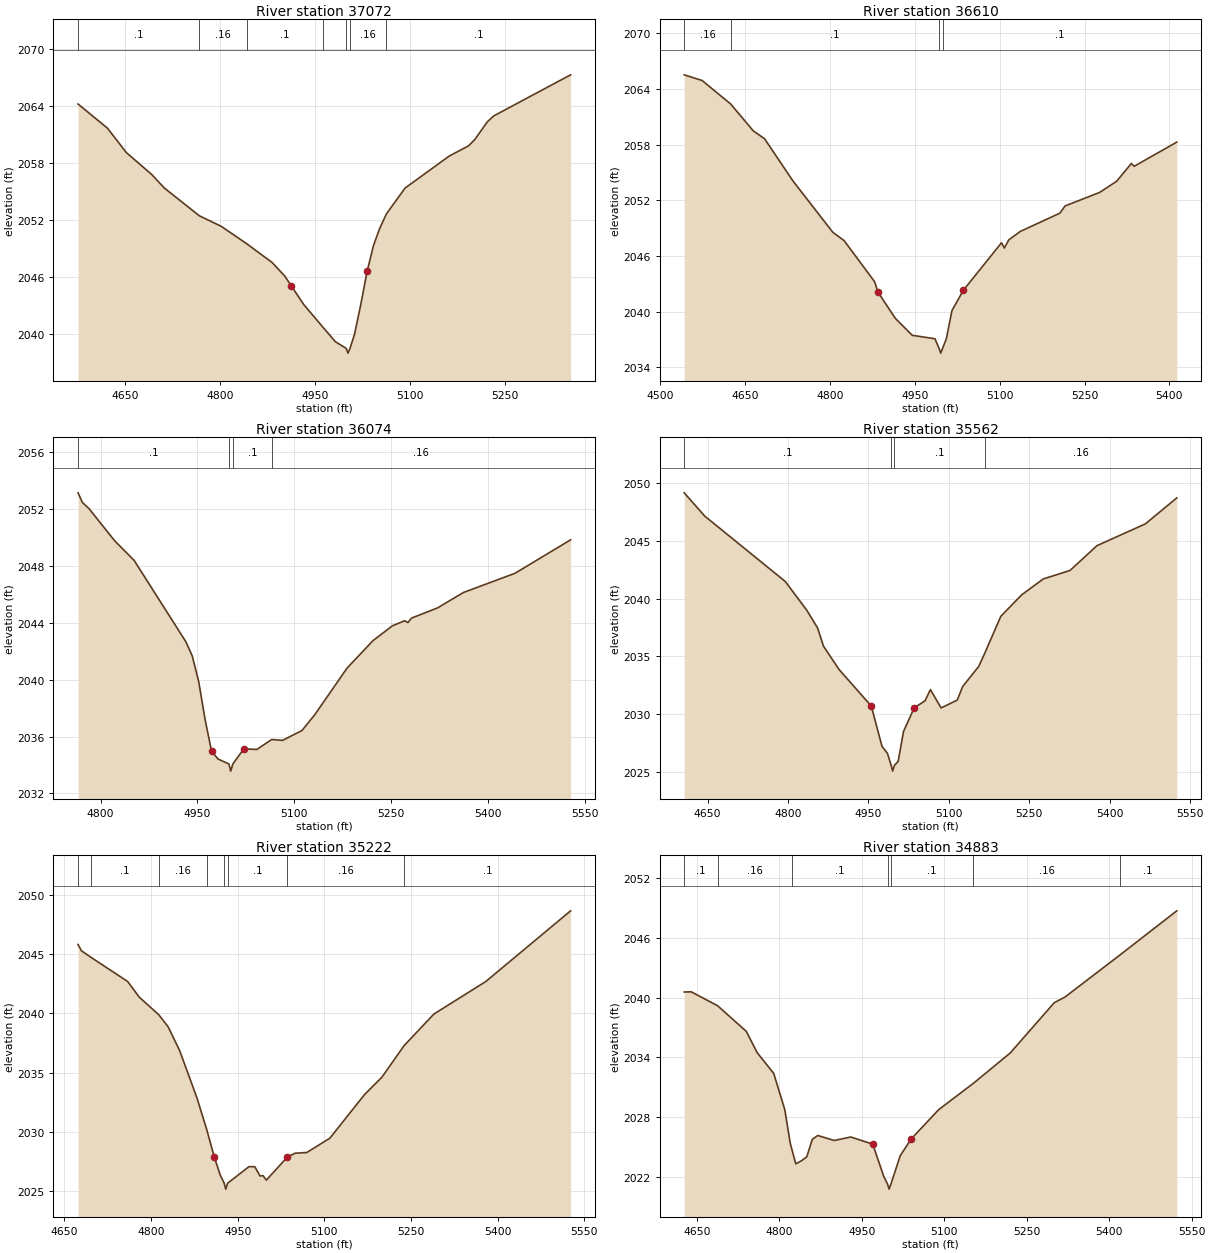
Type RM Length L Ch R = 1 ,37072   ,462,462,462
BEGIN DESCRIPTION:
FLAG CREEK 67.0
END DESCRIPTION:
XS GIS Cut Line= 2
       2664314.9     10083047.81       2663537.2     10083047.81
#Sta/Elev= 30
  4575.4 2064.19  4621.8 2061.65  4651.8 2059.07  4691.8 2056.77  4711.8 2055.34
  4766.9 2052.43  4801.8 2051.31  4841.5  2049.5  4881.8 2047.52  4901.8 2046.09
  4911.8 2045.09  4931.8 2043.09  4961.8 2040.73  4981.8 2039.18  4998.8 2038.48
  5001.6 2037.98  5004.8 2038.48  5011.8 2039.93  5021.8 2043.08  5031.8 2046.58
  5041.8 2049.28  5051.8 2051.12  5062.3 2052.63  5091.8 2055.35  5161.8 2058.73
  5191.8 2059.78  5201.8 2060.45  5221.8 2062.33  5231.8 2062.94  5353.1 2067.26
#Mann= 7 ,-1 , 0
  4575.4      .1       0  4766.9     .16       0  4841.5      .1       0
  4961.8     .16       0  4998.8     .07       0  5004.8     .16       0
  5062.3      .1       0
Bank Sta=4911.8,5031.8
XS Rating Curve= 0 ,0
Exp/Cntr=0.3,0.1

Type RM Length L Ch R = 1 ,36610   ,536,536,536
BEGIN DESCRIPTION:
FLAG CREEK 66.0
END DESCRIPTION:
XS GIS Cut Line= 2
      2664439.98     10082638.09      2663572.63     10082561.76
#Sta/Elev= 30
  4542.3 2065.52  4573.9 2064.91  4624.4 2062.38  4664.3 2059.49  4684.4 2058.63
  4734.6 2054.08  4804.8 2048.57  4824.9 2047.66  4878.7 2043.25  4885.1 2042.09
  4915.3  2039.3  4945.4 2037.46  4985.5 2037.09  4992.9 2036.04  4995.7 2035.54
  4998.9 2036.04  5005.6 2037.07  5015.6 2040.13  5035.7 2042.31  5103.2 2047.43
  5108.2 2046.86    5116 2047.74  5136.1 2048.64  5206.4 2050.62  5215.4 2051.39
  5276.6 2052.85  5306.8 2054.06  5332.7 2055.97  5337.7 2055.67    5413 2058.27
#Mann= 4 ,-1 , 0
  4542.3     .16       0  4624.4      .1       0  4992.9     .07       0
  4998.9      .1       0
Bank Sta=4885.1,5035.7
XS Rating Curve= 0 ,0
Exp/Cntr=0.3,0.1

Type RM Length L Ch R = 1 ,36074   ,512,512,512
BEGIN DESCRIPTION:
FLAG CREEK 65.0
END DESCRIPTION:
XS GIS Cut Line= 2
      2664405.22     10082103.37      2663642.35     10082096.43
#Sta/Elev= 30
    4765 2053.11  4771.8 2052.43  4781.8 2052.01  4821.8 2049.74  4851.8 2048.37
  4931.8 2042.67  4941.8 2041.67  4951.8 2039.88  4961.8 2037.19  4971.8 2034.97
  4981.8 2034.42  4998.8 2034.07  5001.5 2033.57  5004.8 2034.07  5021.8 2035.14
  5041.8 2035.09    5065 2035.79  5081.8 2035.73  5111.8 2036.42  5131.8 2037.54
  5181.8 2040.81  5221.8 2042.73  5251.8 2043.77  5270.8 2044.13  5275.8    2044
  5281.8 2044.32  5321.8 2045.03  5361.8 2046.11  5441.8 2047.46  5527.9 2049.81
#Mann= 4 ,-1 , 0
    4765      .1       0  4998.8     .07       0  5004.8      .1       0
    5065     .16       0
Bank Sta=4971.8,5021.8
XS Rating Curve= 0 ,0
Exp/Cntr=0.3,0.1

Type RM Length L Ch R = 1 ,35562   ,340,340,340
BEGIN DESCRIPTION:
FLAG CREEK 64.0
END DESCRIPTION:
XS GIS Cut Line= 2
      2664606.63      10081624.2      2663689.91     10081568.64
#Sta/Elev= 30
  4606.6 2049.15  4644.8 2047.14  4795.1 2041.48  4835.2 2038.99  4855.2 2037.47
  4866.3 2035.89  4895.3 2033.87  4955.4 2030.71  4975.4 2027.22  4985.5 2026.62
  4992.5 2025.58  4995.2 2025.08  4998.5 2025.58  5005.5 2025.92  5015.5 2028.51
  5035.5 2030.56  5055.6 2031.16  5065.6 2032.13  5085.6 2030.55  5115.7 2031.22
  5125.7 2032.39  5155.8 2034.14  5166.9 2035.27  5196.9 2038.47  5235.9 2040.33
    5276  2041.7  5326.1 2042.44  5376.2 2044.58  5466.3 2046.46    5525 2048.71
#Mann= 4 ,-1 , 0
  4606.6      .1       0  4992.5     .07       0  4998.5      .1       0
  5166.9     .16       0
Bank Sta=4955.4,5035.5
XS Rating Curve= 0 ,0
Exp/Cntr=0.3,0.1

Type RM Length L Ch R = 1 ,35222   ,339,339,339
BEGIN DESCRIPTION:
FLAG CREEK 63.0
END DESCRIPTION:
XS GIS Cut Line= 2
      2664634.39     10081283.92       2663781.8     10081270.06
#Sta/Elev= 30
  4673.5 2045.81  4679.4 2045.28  4696.7  2044.7  4759.4 2042.69  4779.4 2041.37
  4813.3 2039.88  4829.4 2038.87  4849.4 2036.86  4879.4 2032.86  4895.9 2030.26
  4909.5 2027.86  4919.5 2026.38  4926.5 2025.67  4929.2 2025.17  4932.5 2025.67
  4969.5 2027.07  4979.5 2027.06  4988.6 2026.28  4993.6 2026.31  4999.5 2025.93
  5036.1 2027.89  5049.5  2028.2  5069.5 2028.26  5109.5 2029.47  5169.5 2033.15
  5199.5 2034.61    5238 2037.28  5289.5 2039.94  5379.5 2042.69  5526.2 2048.65
#Mann= 8 ,-1 , 0
  4673.5     .16       0  4696.7      .1       0  4813.3     .16       0
  4895.9      .1       0  4926.5     .07       0  4932.5      .1       0
  5036.1     .16       0    5238      .1       0
Bank Sta=4909.5,5036.1
XS Rating Curve= 0 ,0
Exp/Cntr=0.3,0.1

Type RM Length L Ch R = 1 ,34883   ,462,462,462
BEGIN DESCRIPTION:
FLAG CREEK 62.0
END DESCRIPTION:
XS GIS Cut Line= 2
       2664641.3     10080950.59       2663745.5      10080936.7
#Sta/Elev= 30
  4627.1 2040.56  4639.9 2040.58  4687.9 2039.18  4739.9 2036.61  4759.9 2034.46
  4789.9 2032.38    4810 2028.75    4820 2025.35  4823.7 2024.59    4830 2023.29
    4840 2023.59    4850 2023.99    4860 2025.75    4870 2026.14    4900 2025.64
    4930 2025.99    4970 2025.27    4990 2022.03    4997 2021.25  4999.7 2020.75
    5003 2021.25    5020 2024.11    5040  2025.8    5090 2028.74  5153.2 2031.39
    5220 2034.43    5300 2039.48    5320 2040.07  5418.9 2044.25    5523 2048.72
#Mann= 7 ,-1 , 0
  4627.1      .1       0  4687.9     .16       0  4823.7      .1       0
    4997     .07       0    5003      .1       0  5153.2     .16       0
  5418.9      .1       0
Bank Sta=4970,5040
XS Rating Curve= 0 ,0
Exp/Cntr=0.3,0.1

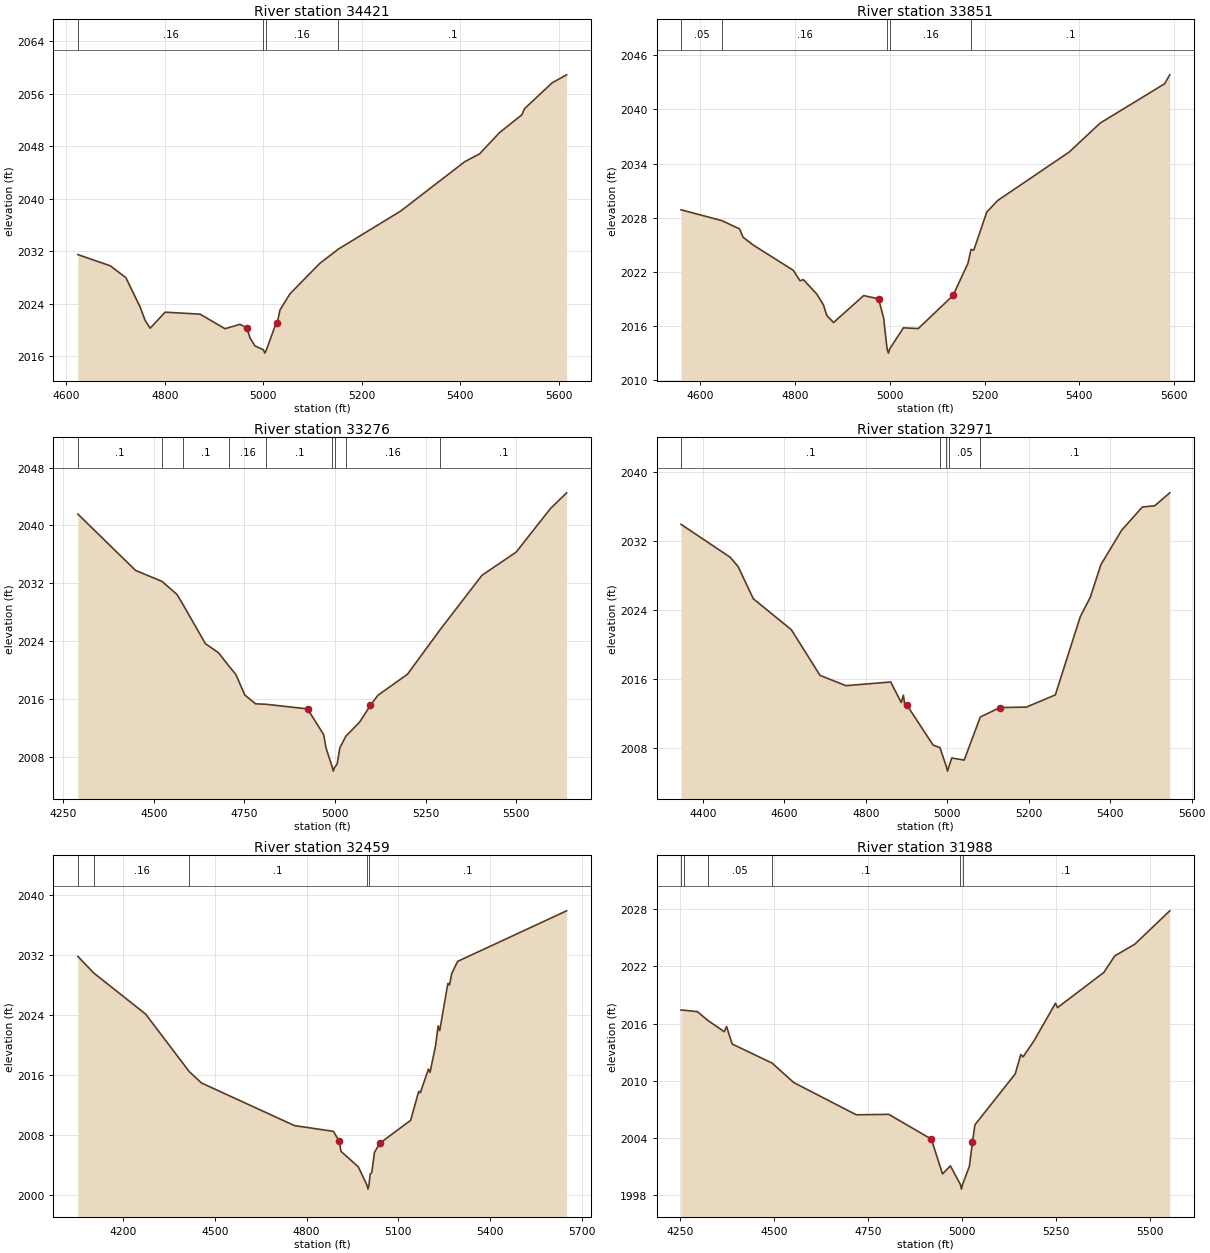
Type RM Length L Ch R = 1 ,34421   ,570,570,570
BEGIN DESCRIPTION:
FLAG CREEK 61.0
END DESCRIPTION:
XS GIS Cut Line= 2
      2664523.31     10080443.64      2663544.15     10080603.36
#Sta/Elev= 30
  4623.6 2031.51  4689.3 2029.81  4721.1    2028  4750.1 2023.51  4760.2 2021.48
  4770.4  2020.3  4800.8 2022.74  4871.7 2022.44  4922.3 2020.22  4952.7 2020.89
  4966.9 2020.32    4973 2018.83  4983.1  2017.6  5000.4    2017  5003.1  2016.5
  5006.4    2017  5023.3 2020.51  5028.3 2021.07  5033.8 2023.06  5054.1 2025.53
  5114.8 2030.18  5152.3 2032.34  5279.2 2038.16  5408.7 2045.65  5439.1 2046.86
  5479.6  2050.1    5525 2052.81  5530.3 2053.74  5586.5 2057.69  5615.7  2058.9
#Mann= 4 ,-1 , 0
  4623.6     .16       0  5000.4     .07       0  5006.4     .16       0
  5152.3      .1       0
Bank Sta=4966.9,5028.3
XS Rating Curve= 0 ,0
Exp/Cntr=0.3,0.1

Type RM Length L Ch R = 1 ,33851   ,575,575,575
BEGIN DESCRIPTION:
FLAG CREEK 60.0
END DESCRIPTION:
XS GIS Cut Line= 3
      2664523.28     10080193.64      2664273.28     10079950.59
      2663621.95     10080151.53
#Sta/Elev= 30
  4560.2 2028.89  4646.3 2027.69  4683.7 2026.77  4690.9 2025.86    4712    2025
  4796.9 2022.19  4811.1 2021.03    4818 2021.16  4846.3 2019.57  4860.5 2018.36
  4867.6 2017.18  4881.8 2016.41  4945.3 2019.39  4976.7 2019.03  4987.2 2016.95
  4994.6 2013.52  4997.4 2013.02  5000.6 2013.52    5029 2015.82  5060.4 2015.74
  5133.7 2019.41  5165.1 2022.96  5171.6  2024.5  5177.4 2024.42  5204.8 2028.64
  5227.9 2029.92  5378.5 2035.28  5443.9 2038.49  5579.7 2042.84  5590.5 2043.83
#Mann= 5 ,-1 , 0
  4560.2     .05       0  4646.3     .16       0  4994.6     .07       0
  5000.6     .16       0  5171.6      .1       0
Bank Sta=4976.7,5133.7
XS Rating Curve= 0 ,0
Exp/Cntr=0.3,0.1

Type RM Length L Ch R = 1 ,33276   ,305,305,305
BEGIN DESCRIPTION:
FLAG CREEK 59.0
END DESCRIPTION:
XS GIS Cut Line= 3
      2664780.26     10079617.27      2664210.78     10079395.03
      2663488.57     10079547.81
#Sta/Elev= 30
    4290 2041.58  4449.3 2033.78  4522.3 2032.26  4563.4 2030.47    4581    2029
  4642.2 2023.64  4678.4 2022.38  4706.5 2020.57  4726.4 2019.37  4750.9 2016.54
  4780.7 2015.31  4810.7 2015.24  4924.2 2014.61  4968.8 2011.04  4975.2 2009.23
  4992.7 2006.49  4995.4 2005.99  4998.7 2006.49  5005.9 2006.95  5013.4  2009.2
  5029.9 2010.82  5068.2 2012.79  5097.9  2015.1  5118.3 2016.48  5200.1  2019.4
    5291 2025.62    5406 2033.11  5500.3 2036.31  5594.6 2042.32  5639.5 2044.52
#Mann= 9 ,-1 , 0
    4290      .1       0  4522.3     .05       0    4581      .1       0
  4706.5     .16       0  4810.7      .1       0  4992.7     .07       0
  4998.7      .1       0  5029.9     .16       0    5291      .1       0
Bank Sta=4924.2,5097.9
XS Rating Curve= 0 ,0
Exp/Cntr=0.3,0.1

Type RM Length L Ch R = 1 ,32971   ,512,512,512
BEGIN DESCRIPTION:
FLAG CREEK 58.0
END DESCRIPTION:
XS GIS Cut Line= 3
       2664710.8     10079276.98      2664189.95     10079096.42
       2663552.3     10079214.25
#Sta/Elev= 30
  4346.5 2033.96    4467 2030.14  4486.6 2029.06    4524 2025.31  4617.4 2021.71
  4687.7 2016.41  4751.2 2015.21  4861.2 2015.64  4887.1 2013.25  4892.4  2014.1
  4895.9 2012.95  4901.1 2012.95  4965.4  2008.3  4982.2 2008.01    4998 2005.78
  5000.7 2005.28    5004 2005.78  5011.1 2006.81  5041.6 2006.56  5081.2 2011.57
  5129.3 2012.67  5194.2 2012.72  5265.4 2014.14  5326.4  2023.2  5351.3  2025.5
  5377.2 2029.27  5428.1 2033.27  5478.9 2035.97  5509.4 2036.12  5546.2 2037.62
#Mann= 5 ,-1 , 0
  4346.5      .1       0  4982.2     .05       0    4998    .035       0
    5004     .05       0  5081.2      .1       0
Bank Sta=4901.1,5129.3
XS Rating Curve= 0 ,0
Exp/Cntr=0.3,0.1

Type RM Length L Ch R = 1 ,32459   ,471,471,471
BEGIN DESCRIPTION:
FLAG CREEK 57.0
END DESCRIPTION:
XS GIS Cut Line= 3
      2664787.14     10078992.24      2664037.17     10078603.37
      2663321.93     10078839.47
#Sta/Elev= 30
    4052 2031.79  4103.7 2029.59  4273.5 2024.12  4416.5 2016.45  4456.2 2014.95
  4760.3 2009.28  4887.4 2008.52    4906 2007.26  4912.6 2005.85  4969.1 2003.79
  4997.7 2001.33  5000.5 2000.83  5003.7 2001.33  5007.8 2002.83  5013.1 2003.04
  5021.8 2005.72  5039.6 2006.94  5140.1 2009.98  5166.5 2013.83  5171.8 2013.65
  5198.3 2016.79  5203.6 2016.37  5221.9 2019.97    5230 2022.55  5235.3 2021.92
  5261.8 2028.19  5267.1 2027.99  5274.5  2029.5  5293.5 2031.12    5650 2037.85
#Mann= 5 ,-1 , 0
    4052      .1       0  4103.7     .16       0  4416.5      .1       0
  4997.7     .07       0  5003.7      .1       0
Bank Sta=4906,5039.6
XS Rating Curve= 0 ,0
Exp/Cntr=0.3,0.1

Type RM Length L Ch R = 1 ,31988   ,552,552,552
BEGIN DESCRIPTION:
FLAG CREEK 56.0
END DESCRIPTION:
XS GIS Cut Line= 3
      2664634.38     10078617.24      2663849.67     10078068.64
      2663516.39     10078151.97
#Sta/Elev= 30
  4252.7 2017.41  4261.6 2017.39  4296.4 2017.24  4324.6 2016.31  4367.9 2015.14
    4374 2015.68  4388.9 2013.85  4495.2 2011.85  4552.8 2009.81  4719.4 2006.43
  4805.7 2006.48  4919.1 2003.88  4948.8 2000.23  4969.7 2001.08  4996.3 1999.14
  4999.1 1998.64  5002.3 1999.14  5020.3 2001.03  5028.6 2003.59  5035.1 2005.38
  5142.4 2010.72  5157.2 2012.75  5163.3  2012.5  5192.9 2014.22  5249.6 2018.13
  5254.8 2017.66  5378.5 2021.36  5407.2 2023.08  5460.9 2024.32  5553.7 2027.81
#Mann= 6 ,-1 , 0
  4252.7     .05       0  4261.6      .1       0  4324.6     .05       0
  4495.2      .1       0  4996.3     .07       0  5002.3      .1       0
Bank Sta=4919.1,5028.6
XS Rating Curve= 0 ,0
Exp/Cntr=0.3,0.1

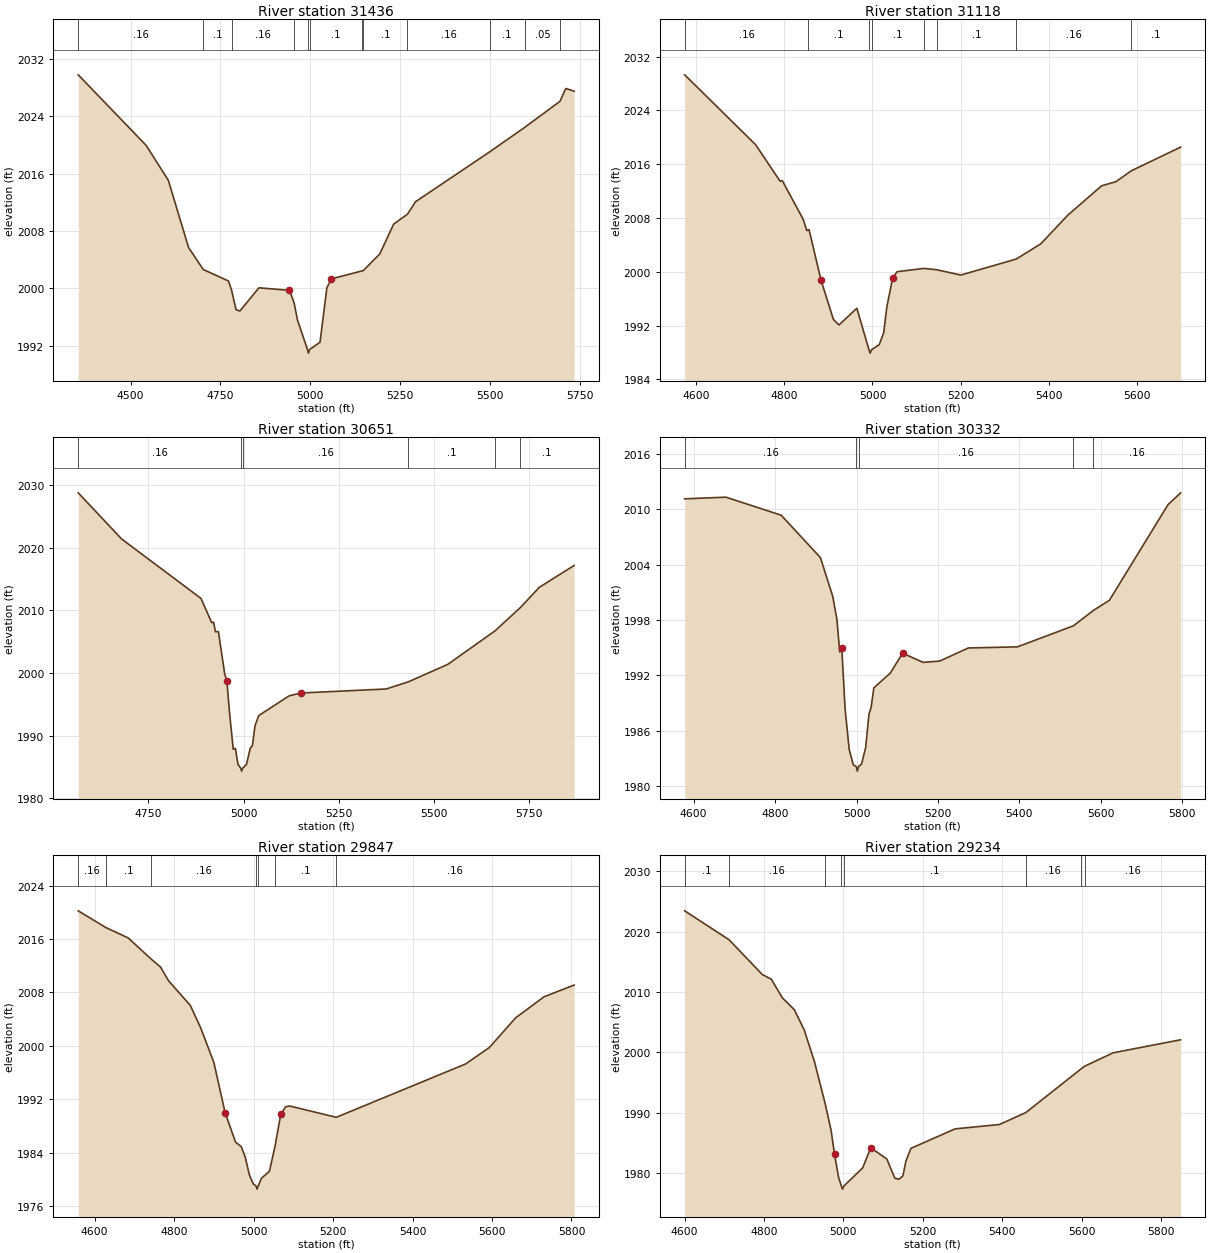
Type RM Length L Ch R = 1 ,31436   ,318,318,318
BEGIN DESCRIPTION:
FLAG CREEK 55.0
END DESCRIPTION:
XS GIS Cut Line= 3
      2664821.93     10077901.99       2664120.5     10077651.98
      2663537.17     10077901.98
#Sta/Elev= 30
  4354.4  2029.8  4543.3 2019.95    4605 2015.08  4661.3 2005.69  4702.2 2002.61
  4772.1 2001.02  4780.8 1999.77  4793.3 1997.01    4804 1996.82    4857 2000.06
    4942 1999.71  4954.9 1997.95  4964.2 1995.57  4992.1 1991.44  4994.8 1990.94
  4998.1 1991.44  5026.9 1992.46    5046 2000.07  5058.8 2001.31    5143 2002.41
    5147 2002.45  5193.1 2004.79  5231.8 2008.96  5270.1 2010.34  5292.8 2012.09
  5498.7 2019.04  5596.1 2022.46  5694.2  2026.1  5710.5 2027.89  5733.7 2027.52
#Mann= 12 ,-1 , 0
  4354.4     .16       0  4702.2      .1       0  4780.8     .16       0
  4954.9      .1       0  4992.1     .07       0  4998.1      .1       0
    5143     .16       0    5147      .1       0  5270.1     .16       0
  5498.7      .1       0  5596.1     .05       0  5694.2      .1       0
Bank Sta=4942,5058.8
XS Rating Curve= 0 ,0
Exp/Cntr=0.3,0.1

Type RM Length L Ch R = 1 ,31118   ,467,467,467
BEGIN DESCRIPTION:
FLAG CREEK 54.0
END DESCRIPTION:
XS GIS Cut Line= 3
      2664773.25      10077485.3      2664238.56     10077395.03
      2663703.85     10077624.19
#Sta/Elev= 30
  4574.4 2029.29  4735.2  2018.9  4790.6 2013.47  4795.7 2013.54  4842.9 2007.81
  4851.1 2006.13  4854.7 2006.24  4856.2 2006.28  4883.5 1998.73  4911.5 1992.91
  4924.1 1992.09  4964.6 1994.57  4992.1  1988.4  4994.8  1987.9  4998.1  1988.4
  5015.3 1989.16  5025.5 1990.93  5032.5 1994.73  5045.8 1999.09  5055.9 2000.01
  5116.5  2000.5  5145.5  2000.3  5200.3 1999.51  5325.8 2001.89  5381.6 2004.16
  5443.1 2008.44  5519.3 2012.78  5551.9  2013.4  5586.5 2015.01  5698.4 2018.54
#Mann= 8 ,-1 , 0
  4574.4     .16       0  4854.7      .1       0  4992.1     .07       0
  4998.1      .1       0  5116.5     .16       0  5145.5      .1       0
  5325.8     .16       0  5586.5      .1       0
Bank Sta=4883.5,5045.8
XS Rating Curve= 0 ,0
Exp/Cntr=0.3,0.1

Type RM Length L Ch R = 1 ,30651   ,319,319,319
BEGIN DESCRIPTION:
FLAG CREEK 53.0
END DESCRIPTION:
XS GIS Cut Line= 3
      2664863.56     10077013.09      2664509.39      10076936.7
      2663670.66     10077359.53
#Sta/Elev= 30
  4565.8 2028.72  4679.9 2021.35  4888.1 2011.88  4916.1 2008.02  4921.2 2008.09
    4926 2006.56  4933.7  2006.6  4950.4 1999.79    4956 1998.72  4962.7 1993.79
  4972.7 1987.82  4978.3 1987.98  4985.1 1985.43    4992 1984.84  4994.8 1984.34
    4998 1984.84  5007.5 1985.41  5017.3 1987.99  5022.9 1988.39  5029.9  1991.6
  5039.6  1993.2  5119.5 1996.35  5151.1  1996.8  5374.2 1997.44  5432.3 1998.58
  5535.9 2001.37  5659.8 2006.71  5726.1 2010.41  5775.7 2013.64  5867.4 2017.14
#Mann= 6 ,-1 , 0
  4565.8     .16       0    4992     .07       0    4998     .16       0
  5432.3      .1       0  5659.8     .16       0  5726.1      .1       0
Bank Sta=4956,5151.1
XS Rating Curve= 0 ,0
Exp/Cntr=0.3,0.1

Type RM Length L Ch R = 1 ,30332   ,485,485,485
BEGIN DESCRIPTION:
FLAG CREEK 52.0
END DESCRIPTION:
XS GIS Cut Line= 2
      2664828.85     10076596.42      2663621.98     10076762.88
#Sta/Elev= 30
  4577.9 2011.11  4679.2 2011.29  4814.9 2009.34  4911.4 2004.75  4941.7 2000.54
  4951.8 1998.07  4958.8 1994.53  4963.8 1995.02    4972 1988.36  4982.1 1983.98
  4992.2  1982.3  4999.3 1982.14    5002 1981.64  5005.3 1982.14  5012.4 1982.42
  5022.5 1984.19  5030.7 1987.82  5035.8 1988.52  5042.6 1990.65    5083 1992.25
  5113.3  1994.4  5163.8 1993.41  5204.2 1993.55  5274.8 1994.97  5395.4 1995.09
    5533 1997.37  5581.8 1999.03  5621.3 2000.13  5765.1 2010.47  5796.2 2011.76
#Mann= 5 ,-1 , 0
  4577.9     .16       0  4999.3     .07       0  5005.3     .16       0
    5533      .1       0  5581.8     .16       0
Bank Sta=4963.8,5113.3
XS Rating Curve= 0 ,0
Exp/Cntr=0.3,0.1

Type RM Length L Ch R = 1 ,29847   ,613,613,613
BEGIN DESCRIPTION:
FLAG CREEK 51.0
END DESCRIPTION:
XS GIS Cut Line= 2
      2664752.48      10076110.3      2663523.39     10076325.57
#Sta/Elev= 30
  4558.9 2020.22  4628.1 2017.73  4684.8 2016.16  4742.2 2013.01    4766 2011.81
  4786.5 2009.73  4840.9 2006.07  4867.5 2002.64  4900.3  1997.5  4928.5    1990
  4954.7 1985.61  4969.1 1984.93  4979.2 1983.35  4989.4 1980.73  4999.5 1979.32
  5006.1 1979.07  5008.8 1978.57  5012.1 1979.07  5019.8 1980.18  5040.1 1981.26
    5054 1984.96  5068.5 1989.76  5080.7 1990.88  5090.9 1991.01  5208.3 1989.32
  5533.9 1997.31  5593.3 1999.76  5659.4  2004.2  5730.5 2007.34  5806.7 2009.11
#Mann= 7 ,-1 , 0
  4558.9     .16       0  4628.1      .1       0  4742.2     .16       0
  5006.1     .07       0  5012.1     .16       0    5054      .1       0
  5208.3     .16       0
Bank Sta=4928.5,5068.5
XS Rating Curve= 0 ,0
Exp/Cntr=0.3,0.1

Type RM Length L Ch R = 1 ,29234   ,420,420,420
BEGIN DESCRIPTION:
FLAG CREEK 50.0
END DESCRIPTION:
XS GIS Cut Line= 3
      2664613.52     10075589.47      2664398.28     10075575.59
      2663377.49      10075735.3
#Sta/Elev= 30
  4600.4 2023.45  4712.1 2018.66  4795.9 2012.89  4818.5 2012.12  4846.3 2009.03
  4876.6 2007.05  4901.5 2003.69  4927.2 1998.44    4954 1991.54  4969.3 1986.98
  4977.8 1983.07    4988 1979.27  4995.1 1977.81  4997.8 1977.31  5001.1 1977.81
  5048.7 1980.84  5068.9 1984.17  5109.4 1982.31  5129.7 1979.12  5139.8 1978.95
  5149.9 1979.49  5157.4 1981.93  5170.2 1984.07  5281.5  1987.3  5392.8 1988.02
  5459.5    1990    5598 1997.21  5608.1  1997.7  5679.4 1999.91  5849.3 2002.07
#Mann= 8 ,-1 , 0
  4600.4      .1       0  4712.1     .16       0    4954      .1       0
  4995.1     .07       0  5001.1      .1       0  5459.5     .16       0
    5598      .1       0  5608.1     .16       0
Bank Sta=4977.8,5068.9
XS Rating Curve= 0 ,0
Exp/Cntr=0.3,0.1

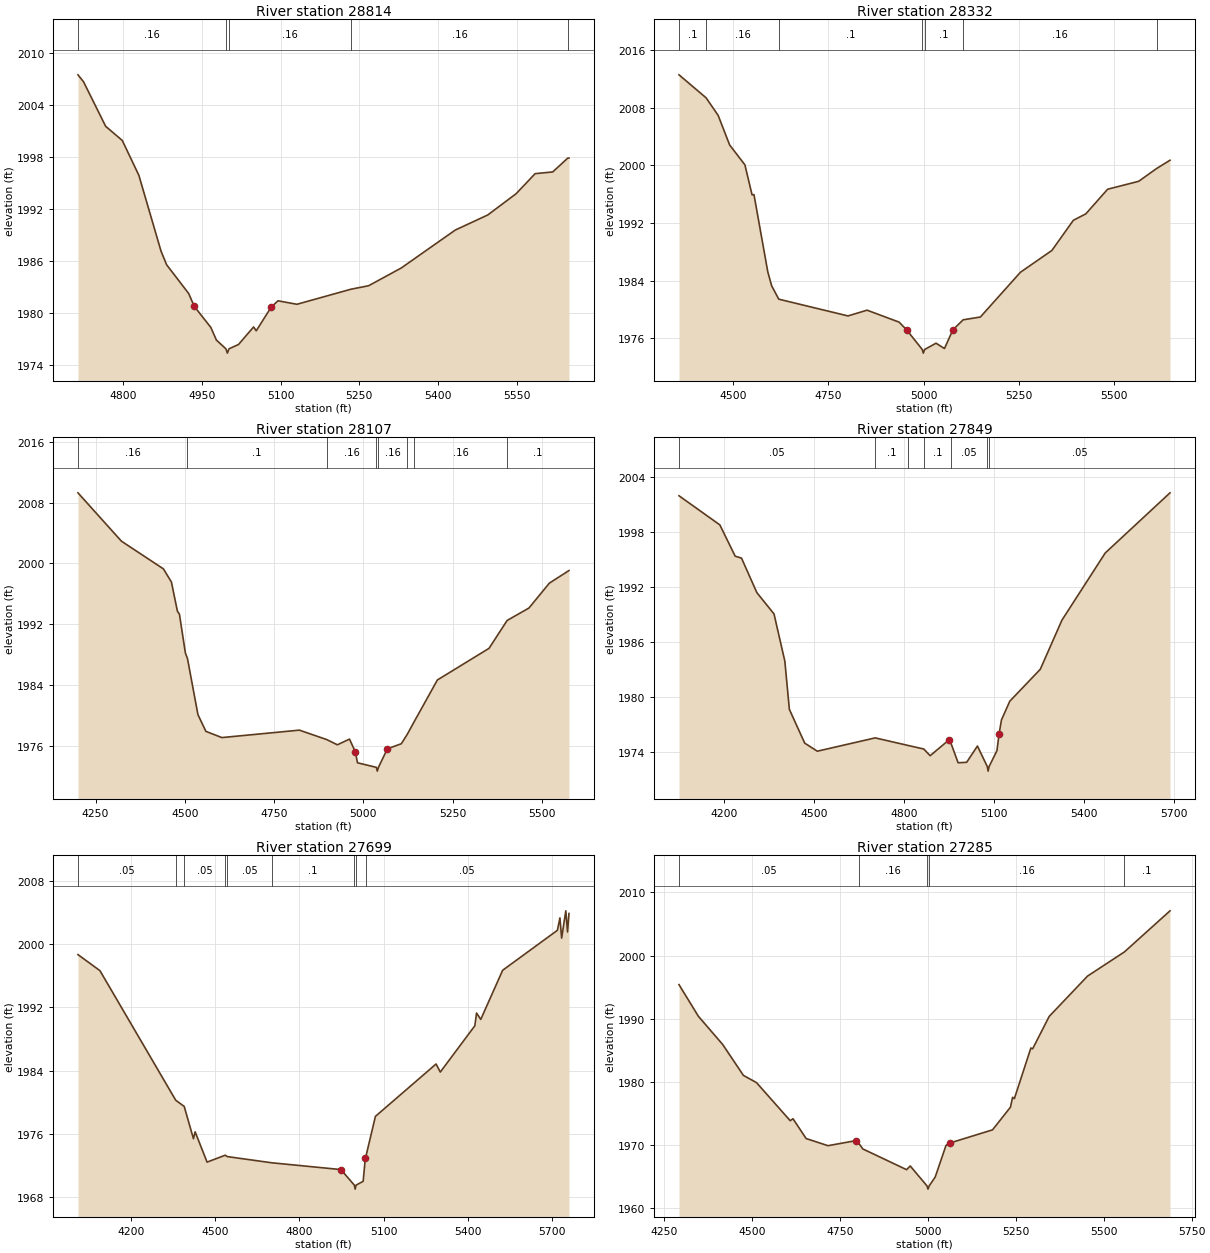
Type RM Length L Ch R = 1 ,28814   ,482,482,482
BEGIN DESCRIPTION:
FLAG CREEK 49.0
END DESCRIPTION:
XS GIS Cut Line= 3
      2664368.49     10075303.74      2664068.47     10075203.73
      2663468.49     10075353.73
#Sta/Elev= 30
  4714.3 2007.51  4724.9 2006.71    4767 2001.57  4798.7 1999.93  4830.3  1995.9
  4872.4 1987.16    4883 1985.59  4925.1 1982.26  4935.7 1980.78  4967.3 1978.34
  4977.8 1976.89  4995.9 1975.88  4998.7 1975.38  5001.9 1975.88    5020 1976.38
  5048.6  1978.4  5053.7 1977.96  5082.1 1980.69    5095 1981.42  5131.1 1981.02
  5234.1 1982.76  5267.6 1983.16  5329.5  1985.2  5432.6 1989.59  5494.4 1991.33
  5548.5 1993.79  5584.6  1996.1  5618.1  1996.3  5646.8  1997.9    5649  1997.9
#Mann= 5 ,-1 , 0
  4714.3     .16       0  4995.9     .07       0  5001.9     .16       0
  5234.1     .16       0  5646.8      .1       0
Bank Sta=4935.7,5082.1
XS Rating Curve= 0 ,0
Exp/Cntr=0.3,0.1

Type RM Length L Ch R = 1 ,28332   ,225,225,225
BEGIN DESCRIPTION:
FLAG CREEK 48.0
END DESCRIPTION:
XS GIS Cut Line= 3
      2664551.02     10074776.98      2663974.67      10074811.7
      2663343.13     10075137.88
#Sta/Elev= 30
  4358.3  2012.6  4429.3 2009.41    4461 2006.97  4491.1 2002.86  4531.2 2000.09
    4550 1995.92    4555 1995.95  4591.3 1985.21  4601.3 1983.29    4620 1981.42
  4801.7 1979.09  4851.7 1979.89  4935.7 1978.23  4955.3 1977.17  4996.6 1974.42
  4999.3 1973.92  5002.6 1974.42  5032.6  1975.3  5054.8 1974.56  5076.9 1977.16
  5103.8 1978.55    5149 1978.94  5254.1 1985.16  5336.6 1988.19  5392.9 1992.38
  5425.7 1993.28  5482.9  1996.7  5564.3  1997.8  5611.4 1999.58  5646.5 2000.73
#Mann= 7 ,-1 , 0
  4358.3      .1       0  4429.3     .16       0    4620      .1       0
  4996.6     .07       0  5002.6      .1       0  5103.8     .16       0
  5611.4      .1       0
Bank Sta=4955.3,5076.9
XS Rating Curve= 0 ,0
Exp/Cntr=0.3,0.1

Type RM Length L Ch R = 1 ,28107   ,258,258,258
BEGIN DESCRIPTION:
FLAG CREEK 47.0
END DESCRIPTION:
XS GIS Cut Line= 2
      2664539.37     10074283.07      2663308.05     10074895.01
#Sta/Elev= 30
  4200.9  2009.3  4322.6 2002.93  4440.2 1999.28  4462.6 1997.55  4479.4  1993.7
    4485 1993.32  4501.8 1988.18  4507.6 1987.46  4536.9 1980.07  4559.2 1977.87
  4603.9 1977.05    4821 1978.03  4897.4 1976.79  4927.4  1976.1  4961.3 1976.85
  4977.8 1975.16  4983.6 1973.73  5036.4 1973.13  5039.2 1972.63  5042.4 1973.13
  5067.4 1975.57  5106.4 1976.24  5122.7 1977.45  5142.4 1979.14  5207.4 1984.64
  5352.1 1988.81  5402.7 1992.48  5463.8 1994.12    5521  1997.4  5575.9 1999.06
#Mann= 8 ,-1 , 0
  4200.9     .16       0  4507.6      .1       0  4897.4     .16       0
  5036.4     .07       0  5042.4     .16       0  5122.7      .1       0
  5142.4     .16       0  5402.7      .1       0
Bank Sta=4977.8,5067.4
XS Rating Curve= 0 ,0
Exp/Cntr=0.3,0.1

Type RM Length L Ch R = 1 ,27849   ,150,150,150
BEGIN DESCRIPTION:
Mapping XS b8cbb64f
END DESCRIPTION:
XS GIS Cut Line= 2
      2664509.23     10073895.05      2663142.37     10074797.13
#Sta/Elev= 30
  4048.5 2001.91  4184.7 1998.74  4235.9 1995.33    4257 1995.12  4308.2 1991.36
  4365.4 1989.04  4401.5  1983.9  4416.6 1978.65  4467.8 1974.97  4509.9 1974.09
    4703 1975.54  4813.3 1974.71  4864.9 1974.33  4886.2  1973.6  4949.4 1975.33
  4955.6 1974.96  4979.5 1972.83  5007.9 1972.88  5043.9 1974.65  5076.8 1972.42
  5079.6 1971.92  5082.8 1972.42    5109 1974.15  5115.8 1975.91    5124 1977.49
  5151.7 1979.53  5253.5 1983.01  5325.7 1988.36  5470.2 1995.68  5686.2 2002.23
#Mann= 7 ,-1 , 0
  4048.5     .05       0    4703      .1       0  4813.3     .05       0
  4864.9      .1       0  4955.6     .05       0  5076.8     .04       0
  5082.8     .05       0
Bank Sta=4949.4,5115.8
XS Rating Curve= 0 ,0
Exp/Cntr=0.3,0.1

Type RM Length L Ch R = 1 ,27699   ,414,414,414
BEGIN DESCRIPTION:
Mapping XS fb87e5bf
END DESCRIPTION:
XS GIS Cut Line= 2
      2664479.06     10073735.53      2663031.85     10074713.38
#Sta/Elev= 30
  4012.4 1998.67  4090.6 1996.64  4360.2 1980.27  4390.3 1979.49  4423.2 1975.41
  4429.2 1976.28  4471.7 1972.45  4536.4 1973.33  4543.6 1973.15  4701.3 1972.37
  4947.7 1971.51  4995.6 1969.54  4998.4 1969.04  5001.6 1969.54  5026.9 1970.03
  5034.6 1972.97  5035.3 1972.97  5070.5 1978.23  5286.3 1984.85  5301.3 1983.83
  5424.2 1989.68  5430.2 1991.29  5445.2 1990.48  5523.1 1996.69  5717.9 2001.74
  5726.8 2003.31  5732.9 2000.75  5747.8  2004.2  5753.9 2001.53    5759 2003.86
#Mann= 9 ,-1 , 0
  4012.4     .05       0  4360.2      .1       0  4390.3     .05       0
  4536.4      .1       0  4543.6     .05       0  4701.3      .1       0
  4995.6     .07       0  5001.6      .1       0  5035.3     .05       0
Bank Sta=4947.7,5034.6
XS Rating Curve= 0 ,0
Exp/Cntr=0.3,0.1

Type RM Length L Ch R = 1 ,27285   ,316,316,316
BEGIN DESCRIPTION:
FLAG CREEK 46.0
END DESCRIPTION:
XS GIS Cut Line= 3
      2664414.36     10073731.23      2664108.29     10073830.38
      2663052.77     10074032.87
#Sta/Elev= 30
  4291.9  1995.4    4347 1990.39  4416.3 1985.91    4475 1981.03  4512.3 1979.88
  4608.2 1973.85  4616.1 1974.16  4653.5 1971.02  4715.7 1969.89  4796.7 1970.71
  4804.2  1970.2  4814.6 1969.38  4939.3 1966.09  4949.5 1966.68  4997.4 1963.51
  5000.1 1963.01  5003.4 1963.51  5020.7 1964.94  5051.3 1969.93  5061.5  1970.3
  5183.7  1972.4  5234.6 1975.99  5240.7 1977.55  5245.8 1977.35  5292.7 1985.36
  5297.8 1985.24  5344.7 1990.36  5453.8 1996.75  5558.7 2000.58  5688.4 2007.09
#Mann= 5 ,-1 , 0
  4291.9     .05       0  4804.2     .16       0  4997.4     .07       0
  5003.4     .16       0  5558.7      .1       0
Bank Sta=4796.7,5061.5
XS Rating Curve= 0 ,0
Exp/Cntr=0.3,0.1