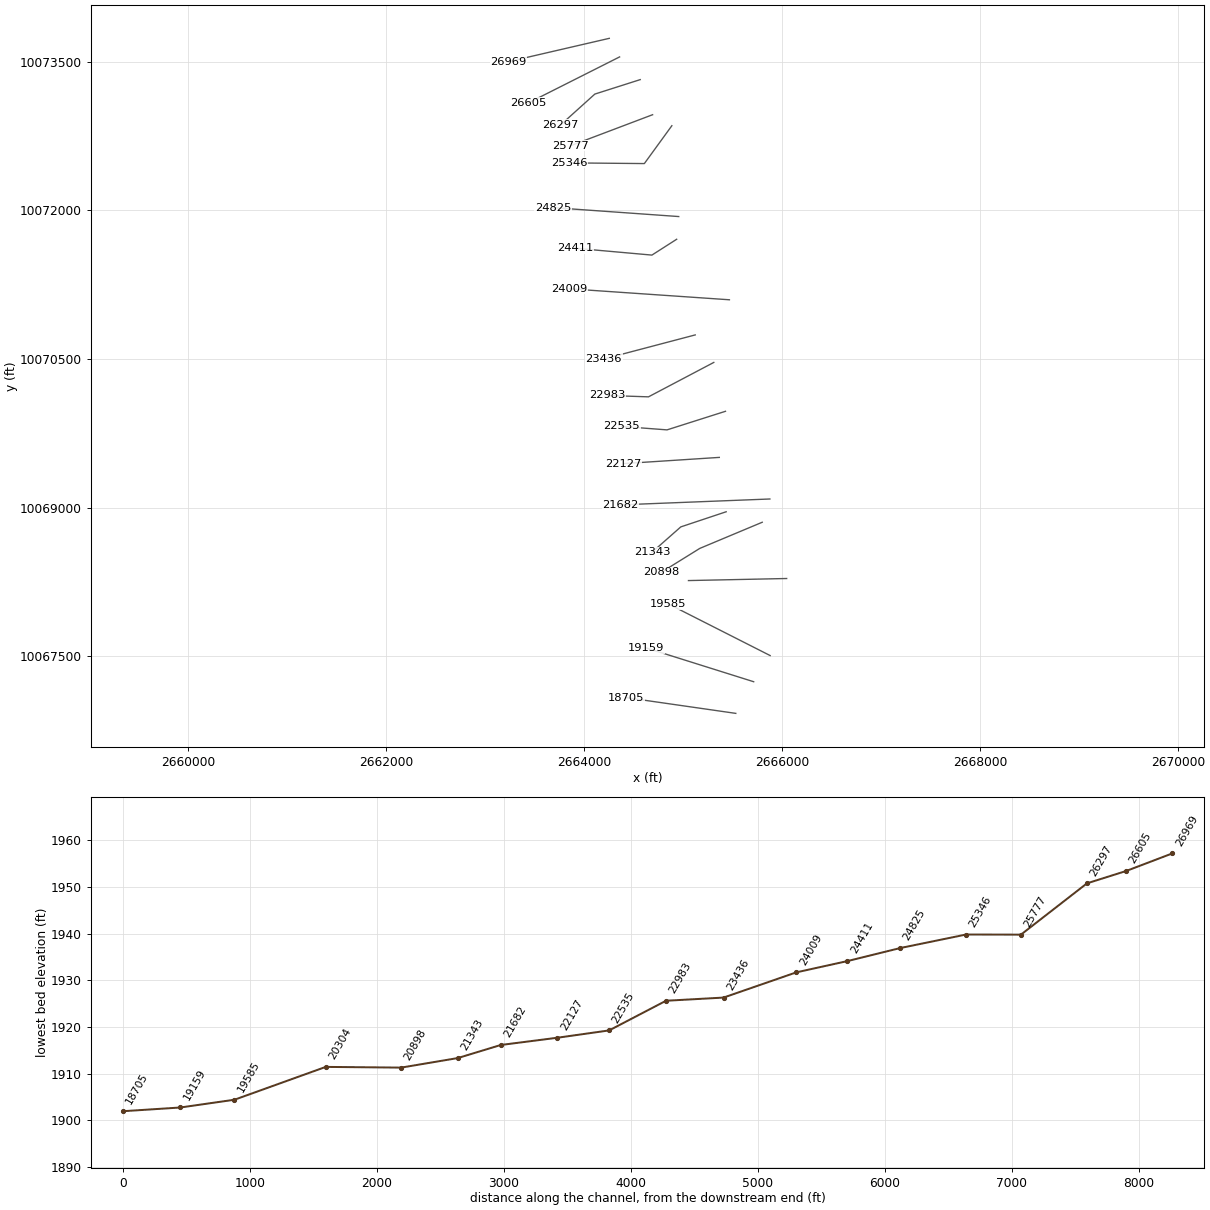
HEC-RAS study FLAG CREEK.prj: FLAG CREEK Base Level Engineering

--- FLAG CREEK.g01 (geometry) --- (continued)

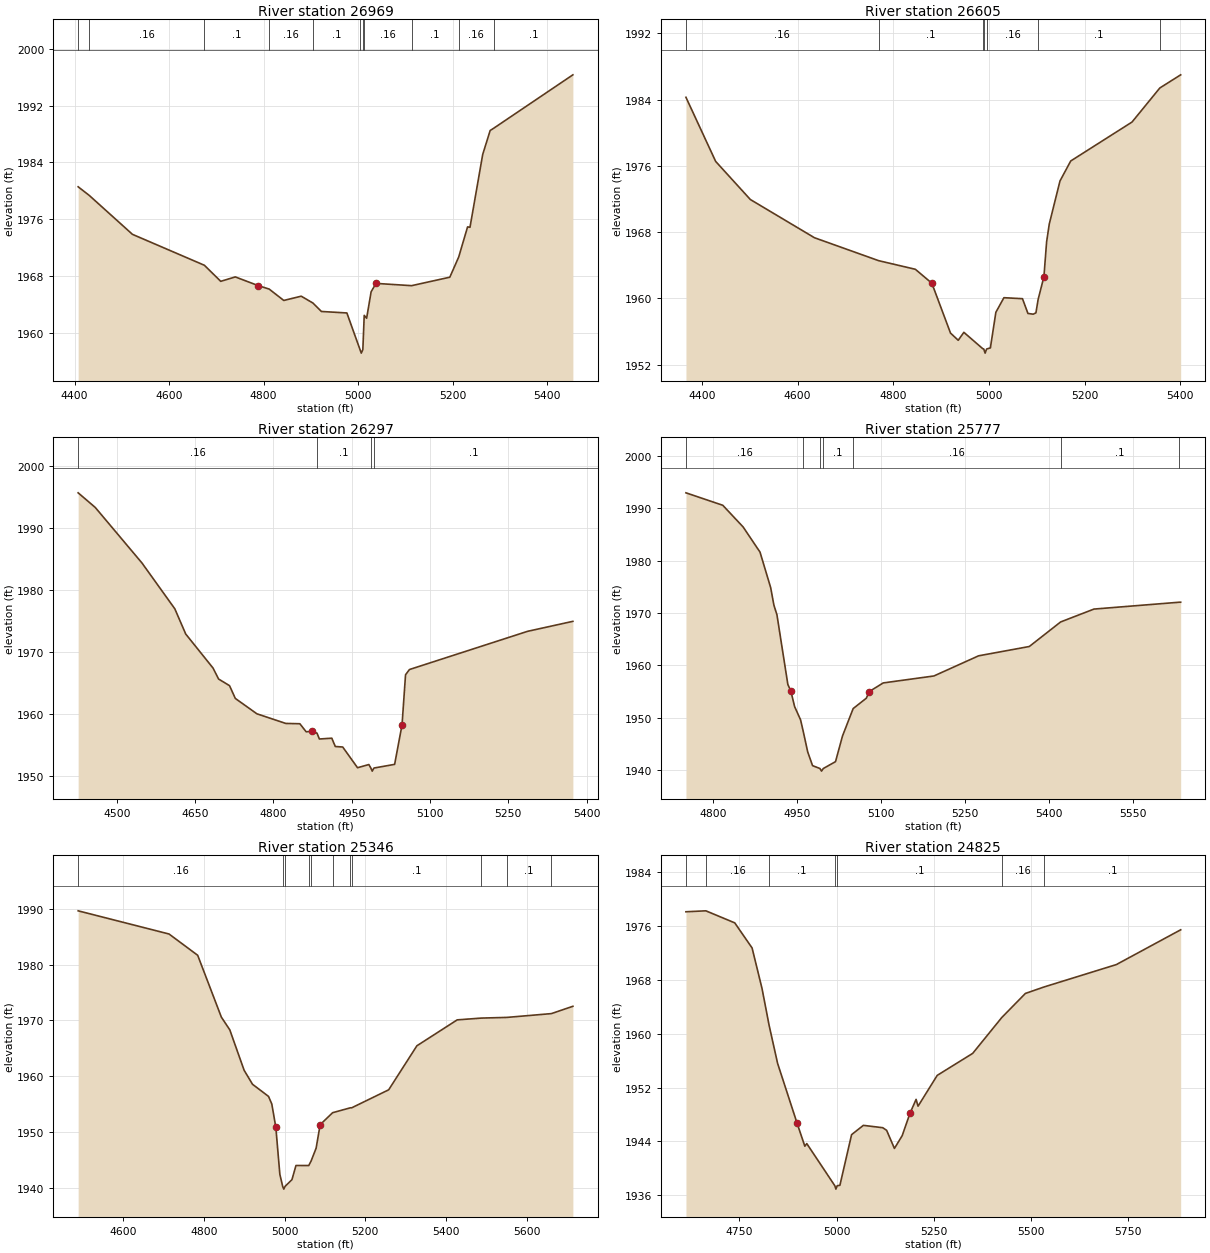
Type RM Length L Ch R = 1 ,26969   ,364,364,364
BEGIN DESCRIPTION:
FLAG CREEK 45.0
END DESCRIPTION:
XS GIS Cut Line= 2
      2664252.42      10073735.3      2663232.55     10073499.41
#Sta/Elev= 30
  4407.5 1980.57  4431.1 1979.35  4522.4 1973.88  4674.6 1969.53  4709.2 1967.27
    4740 1967.89  4788.9 1966.66  4811.7 1966.18  4842.6 1964.58  4879.5 1965.18
  4904.2 1964.22  4922.2 1963.03  4976.1 1962.82  5003.9 1957.67  5006.6 1957.17
  5009.9 1957.67  5012.2 1961.48  5012.8 1962.48  5017.9 1962.08  5027.4  1965.8
  5037.7 1966.98    5113 1966.66  5193.9 1967.85  5212.7 1970.69  5231.5 1974.93
  5236.6 1974.87  5263.5 1985.12  5279.3 1988.49  5286.9 1988.81  5454.3 1996.32
#Mann= 11 ,-1 , 0
  4407.5     .05       0  4431.1     .16       0  4674.6      .1       0
  4811.7     .16       0  4904.2      .1       0  5003.9     .07       0
  5009.9      .1       0  5012.2     .16       0    5113      .1       0
  5212.7     .16       0  5286.9      .1       0
Bank Sta=4788.9,5037.7
XS Rating Curve= 0 ,0
Exp/Cntr=0.3,0.1

Type RM Length L Ch R = 1 ,26605   ,308,308,308
BEGIN DESCRIPTION:
FLAG CREEK 44.0
END DESCRIPTION:
XS GIS Cut Line= 2
       2664356.6      10073547.8      2663433.25     10073082.66
#Sta/Elev= 30
  4366.7 1984.28  4428.8 1976.54  4501.3 1971.94  4635.2 1967.33  4769.4 1964.56
  4846.1 1963.52  4880.6 1961.84  4919.6 1955.82  4935.7 1954.95  4947.5 1955.91
  4986.9 1953.94  4989.1  1953.9  4991.9  1953.4  4995.1  1953.9  5002.9 1954.03
  5014.4 1958.33  5031.2 1960.09    5070 1959.97  5081.4 1958.19  5092.4  1958.1
  5098.1 1958.26  5102.7 1959.88  5114.8 1962.62  5120.4 1966.82    5126 1968.99
  5148.4 1974.18  5170.8 1976.59  5298.9 1981.29    5357  1985.4  5400.6 1986.99
#Mann= 7 ,-1 , 0
  4366.7     .16       0  4769.4      .1       0  4986.9     .16       0
  4989.1     .07       0  4995.1     .16       0  5102.7      .1       0
    5357     .16       0
Bank Sta=4880.6,5114.8
XS Rating Curve= 0 ,0
Exp/Cntr=0.3,0.1

Type RM Length L Ch R = 1 ,26297   ,520,520,520
BEGIN DESCRIPTION:
FLAG CREEK 43.0
END DESCRIPTION:
XS GIS Cut Line= 3
      2664564.93     10073318.64      2664106.62     10073172.81
      2663759.39     10072860.31
#Sta/Elev= 30
  4425.8 1995.63  4458.6 1993.27    4548 1984.33    4611 1976.94    4632 1972.86
  4684.3 1967.38  4694.9 1965.61  4715.9 1964.54    4727 1962.48  4768.4    1960
  4823.7 1958.45  4850.7  1958.4  4862.8  1957.1  4873.3 1957.18  4883.5 1956.89
  4888.1 1955.94  4911.9 1956.07  4918.6 1954.73  4932.8 1954.65  4961.2 1951.31
  4982.9 1951.82  4986.7 1951.26  4989.4 1950.76  4992.7 1951.26  5032.3 1951.85
  5046.5 1958.22  5053.2 1966.29  5060.7 1967.14  5287.1  1973.3  5373.9 1974.91
#Mann= 4 ,-1 , 0
  4425.8     .16       0  4883.5      .1       0  4986.7     .07       0
  4992.7      .1       0
Bank Sta=4873.3,5046.5
XS Rating Curve= 0 ,0
Exp/Cntr=0.3,0.1

Type RM Length L Ch R = 1 ,25777   ,431,431,431
BEGIN DESCRIPTION:
FLAG CREEK 42.0
END DESCRIPTION:
XS GIS Cut Line= 2
      2664689.97     10072964.49      2663863.58     10072651.99
#Sta/Elev= 30
  4751.2 1992.95    4817 1990.57  4853.3 1986.43  4883.5 1981.62  4902.5 1974.84
  4908.3 1971.48  4913.7 1969.66  4933.2 1956.33  4938.5  1955.1  4945.2 1952.13
  4955.9 1949.58  4960.5 1947.45  4968.7 1943.43  4977.3 1940.83  4990.5 1940.28
  4993.3 1939.78  4996.5 1940.28  5018.3 1941.59  5030.8  1946.5  5049.8 1951.73
  5073.3 1953.71  5078.7 1954.99  5103.5 1956.63    5194 1957.96  5273.8 1961.81
  5364.4 1963.59  5420.3 1968.28  5479.8 1970.74  5632.2 1972.05  5634.7 1972.05
#Mann= 7 ,-1 , 0
  4751.2     .16       0  4960.5      .1       0  4990.5     .07       0
  4996.5      .1       0  5049.8     .16       0  5420.3      .1       0
  5632.2     .05       0
Bank Sta=4938.5,5078.7
XS Rating Curve= 0 ,0
Exp/Cntr=0.3,0.1

Type RM Length L Ch R = 1 ,25346   ,521,521,521
BEGIN DESCRIPTION:
FLAG CREEK 41.0
END DESCRIPTION:
XS GIS Cut Line= 3
       2664884.4     10072853.37      2664606.62     10072471.42
      2663851.53     10072478.35
#Sta/Elev= 30
  4487.5 1989.63    4713 1985.48  4784.1 1981.67  4842.8  1970.6  4863.7 1968.33
  4899.2  1961.1  4920.1 1958.58  4959.8 1956.41  4967.9 1955.06  4977.9 1950.91
  4987.9 1942.46  4994.9 1940.31  4997.7 1939.81  5000.9 1940.31  5017.9  1941.5
  5027.9 1944.04  5059.6 1944.03  5065.3 1944.82  5077.9 1947.14  5087.9 1951.35
  5118.8 1953.49  5162.9 1954.37  5165.9 1954.36  5257.9 1957.59  5327.9 1965.47
  5427.9 1970.11    5488 1970.43  5551.3 1970.55  5661.6 1971.23  5714.9 1972.54
#Mann= 11 ,-1 , 0
  4487.5     .16       0  4994.9     .07       0  5000.9     .16       0
  5059.6      .1       0  5065.3     .16       0  5118.8      .1       0
  5162.9     .16       0  5165.9      .1       0    5488     .05       0
  5551.3      .1       0  5661.6     .05       0
Bank Sta=4977.9,5087.9
XS Rating Curve= 0 ,0
Exp/Cntr=0.3,0.1

Type RM Length L Ch R = 1 ,24825   ,414,414,414
BEGIN DESCRIPTION:
FLAG CREEK 40.0
END DESCRIPTION:
XS GIS Cut Line= 2
      2664953.87      10071936.7      2663683.27     10072026.96
#Sta/Elev= 30
  4612.2 1978.13  4663.5 1978.27  4737.9 1976.48  4782.5 1972.75  4808.1 1966.72
  4826.4 1961.23  4848.2 1955.59  4898.3 1946.71  4918.3 1943.28  4923.3 1943.67
  4995.6  1937.4  4998.3  1936.9  5001.6  1937.4  5008.6 1937.47  5038.7    1945
    5069 1946.38  5118.9 1946.03  5128.9 1945.64    5149 1942.95    5169 1944.85
  5189.1 1948.19  5204.8 1950.24  5209.8 1949.23  5259.2 1953.81  5350.5 1957.08
  5425.4 1962.41  5486.2 1965.99  5534.7 1966.96  5720.4 1970.28    5886 1975.45
#Mann= 7 ,-1 , 0
  4612.2      .1       0  4663.5     .16       0  4826.4      .1       0
  4995.6     .07       0  5001.6      .1       0  5425.4     .16       0
  5534.7      .1       0
Bank Sta=4898.3,5189.1
XS Rating Curve= 0 ,0
Exp/Cntr=0.3,0.1

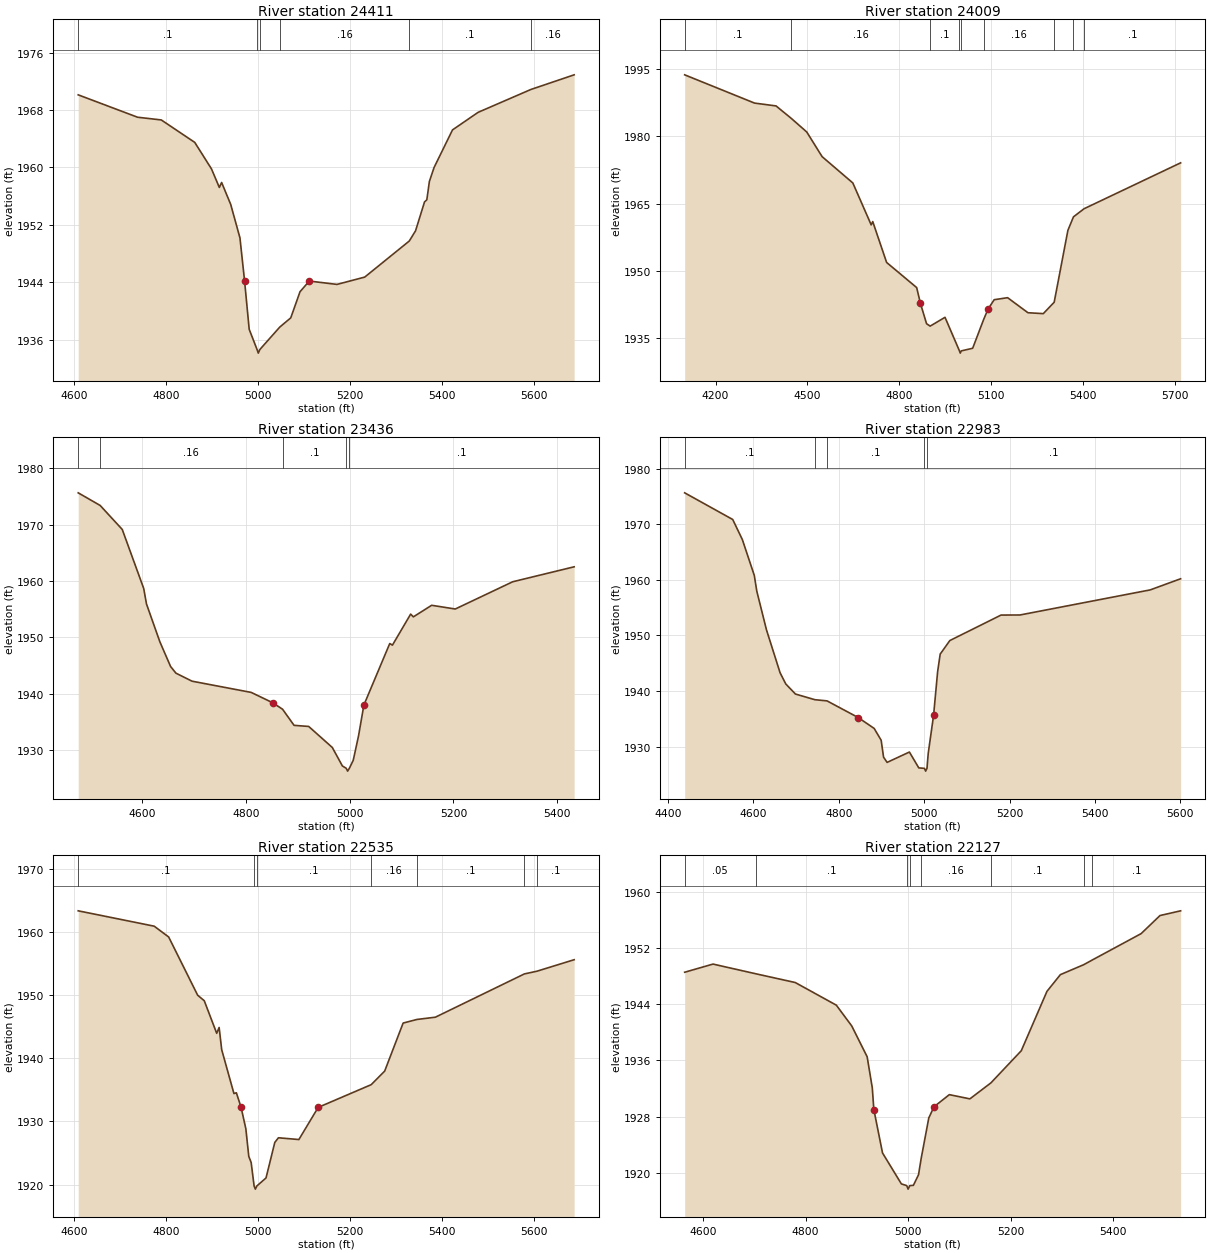
Type RM Length L Ch R = 1 ,24411   ,402,402,402
BEGIN DESCRIPTION:
FLAG CREEK 39.0
END DESCRIPTION:
XS GIS Cut Line= 3
      2664932.99     10071707.52        2664683.     10071547.81
      2663905.25     10071617.25
#Sta/Elev= 30
  4608.8 1970.13  4737.7 1967.01  4789.3 1966.63    4862  1963.5  4898.4  1959.8
  4915.4 1957.22  4920.4 1957.91  4940.1 1954.86  4960.2 1950.19  4970.2 1944.22
  4980.3 1937.44  4997.4 1934.62  5000.1 1934.12  5003.4 1934.62  5046.7 1937.75
  5070.6 1939.04  5090.7 1942.68  5110.8 1944.17    5171  1943.7  5231.3 1944.72
  5328.1 1949.75  5341.7 1951.17  5361.2  1955.2  5366.2 1955.49  5371.8 1958.06
  5381.9 1959.99    5422 1965.24  5477.6 1967.69  5592.4 1970.88  5686.3 1972.92
#Mann= 6 ,-1 , 0
  4608.8      .1       0  4997.4     .07       0  5003.4      .1       0
  5046.7     .16       0  5328.1      .1       0  5592.4     .16       0
Bank Sta=4970.2,5110.8
XS Rating Curve= 0 ,0
Exp/Cntr=0.3,0.1

Type RM Length L Ch R = 1 ,24009   ,573,573,573
BEGIN DESCRIPTION:
FLAG CREEK 38.0
END DESCRIPTION:
XS GIS Cut Line= 2
      2665465.86     10071096.82      2663851.54      10071207.4
#Sta/Elev= 30
  4099.3 1993.65  4327.2 1987.36  4397.4 1986.73    4447 1983.96  4497.6 1980.93
  4547.7 1975.44    4648 1969.58  4707.8 1960.26  4712.9 1960.99  4758.2 1951.89
  4856.2  1946.3  4868.5 1942.79  4888.5 1938.26  4900.2 1937.72  4948.7 1939.68
  4995.8 1932.21  4998.5 1931.71  5001.8 1932.21  5038.9 1932.79    5075 1939.24
    5089 1941.49  5109.1  1943.6  5152.9 1944.05  5219.3  1940.7  5269.4  1940.5
  5304.9 1943.04  5349.6 1959.03  5367.8 1962.04  5402.2 1963.84  5717.4 1974.06
#Mann= 9 ,-1 , 0
  4099.3      .1       0    4447     .16       0  4900.2      .1       0
  4995.8     .07       0  5001.8      .1       0    5075     .16       0
  5304.9      .1       0  5367.8     .16       0  5402.2      .1       0
Bank Sta=4868.5,5089
XS Rating Curve= 0 ,0
Exp/Cntr=0.3,0.1

Type RM Length L Ch R = 1 ,23436   ,453,453,453
BEGIN DESCRIPTION:
FLAG CREEK 37.0
END DESCRIPTION:
XS GIS Cut Line= 2
      2665120.46     10070742.24      2664196.91      10070499.2
#Sta/Elev= 30
  4477.5 1975.63  4519.8 1973.39  4562.3 1969.14  4603.6 1958.69    4609 1955.93
  4634.7 1949.24  4655.4 1944.85  4665.7 1943.67  4696.7 1942.25  4810.6 1940.26
  4851.8 1938.44    4871 1937.28  4893.2 1934.42  4921.3 1934.23  4966.8  1930.5
  4986.2 1927.23  4993.6 1926.81  4996.3 1926.31  4999.6 1926.81  5007.1 1928.23
  5017.3 1932.55  5027.6 1938.02  5077.4 1948.92  5082.6 1948.64  5117.7 1954.14
  5122.9 1953.65  5158.1  1955.7  5203.6 1955.04  5314.2 1959.87  5432.5 1962.52
#Mann= 5 ,-1 , 0
  4477.5      .1       0  4519.8     .16       0    4871      .1       0
  4993.6     .07       0  4999.6      .1       0
Bank Sta=4851.8,5027.6
XS Rating Curve= 0 ,0
Exp/Cntr=0.3,0.1

Type RM Length L Ch R = 1 ,22983   ,448,448,448
BEGIN DESCRIPTION:
FLAG CREEK 36.0
END DESCRIPTION:
XS GIS Cut Line= 3
      2665308.01     10070464.48      2664648.28     10070117.25
      2664232.54     10070131.11
#Sta/Elev= 30
    4439 1975.63  4551.5 1970.84  4574.1 1967.23    4602  1960.8    4608 1957.93
  4630.6 1951.01  4662.4 1943.31  4675.8 1941.29  4698.4 1939.48  4744.1 1938.46
  4772.4 1938.25  4845.3 1935.26  4882.8  1933.3  4899.2 1931.17  4904.8 1928.14
  4913.1  1927.2  4965.3 1929.06  4987.3 1926.21  5000.5 1926.13  5003.3 1925.63
  5006.5 1926.13  5009.4 1928.83 5021.94 1935.65  5031.4 1943.48  5037.4 1946.65
    5060 1949.09    5180 1953.67  5224.1 1953.68  5529.3 1958.19  5600.5 1960.19
#Mann= 5 ,-1 , 0
    4439      .1       0  4744.1     .16       0  4772.4      .1       0
  5000.5     .07       0  5006.5      .1       0
Bank Sta=4845.3,5021.94
XS Rating Curve= 0 ,0
Exp/Cntr=0.3,0.1

Type RM Length L Ch R = 1 ,22535   ,408,408,408
BEGIN DESCRIPTION:
FLAG CREEK 35.0
END DESCRIPTION:
XS GIS Cut Line= 3
      2665426.05     10069971.42      2664835.78     10069783.92
      2664377.43     10069818.65
#Sta/Elev= 30
  4608.3 1963.34  4773.6 1960.91  4805.1  1959.2  4868.1 1949.99  4882.6  1949.1
  4909.6 1943.95  4914.9 1944.87  4920.5 1941.35  4947.1 1934.41  4952.4 1934.53
  4962.5 1932.27    4973 1928.85  4979.4 1924.47  4984.6 1923.49    4991 1919.78
  4993.7 1919.28    4997 1919.78  5016.9 1921.05    5036 1926.67  5043.9 1927.41
  5088.4 1927.13  5130.4 1932.22  5245.8 1935.82  5275.1 1937.97  5315.2 1945.57
  5345.1 1946.14  5385.4  1946.5    5579 1953.35  5606.3 1953.78  5687.3  1955.6
#Mann= 7 ,-1 , 0
  4608.3      .1       0    4991     .07       0    4997      .1       0
  5245.8     .16       0  5345.1      .1       0    5579     .05       0
  5606.3      .1       0
Bank Sta=4962.5,5130.4
XS Rating Curve= 0 ,0
Exp/Cntr=0.3,0.1

Type RM Length L Ch R = 1 ,22127   ,445,445,445
BEGIN DESCRIPTION:
FLAG CREEK 34.0
END DESCRIPTION:
XS GIS Cut Line= 2
      2665363.61     10069506.15      2664398.33     10069443.65
#Sta/Elev= 30
  4564.1 1948.54  4619.4  1949.7  4702.9 1948.32  4779.7 1947.08  4859.9 1943.86
  4889.9 1940.91    4920 1936.53    4930 1932.12 4933.09    1929    4950 1922.85
  4986.8 1918.45  4997.2 1918.21  4999.9 1917.71  5003.2 1918.21  5010.2 1918.25
  5020.2 1919.75  5025.2    1922  5040.2 1927.82  5050.3 1929.41  5080.3 1931.14
  5120.4 1930.54  5161.5 1932.82  5220.6 1937.38  5270.7 1945.82  5296.9  1948.2
  5342.3 1949.61  5359.1 1950.28  5454.4 1954.03  5491.2  1956.6  5531.4 1957.27
#Mann= 8 ,-1 , 0
  4564.1     .05       0  4702.9      .1       0  4997.2     .07       0
  5003.2      .1       0  5025.2     .16       0  5161.5      .1       0
  5342.3     .05       0  5359.1      .1       0
Bank Sta=4933.09,5050.3
XS Rating Curve= 0 ,0
Exp/Cntr=0.3,0.1

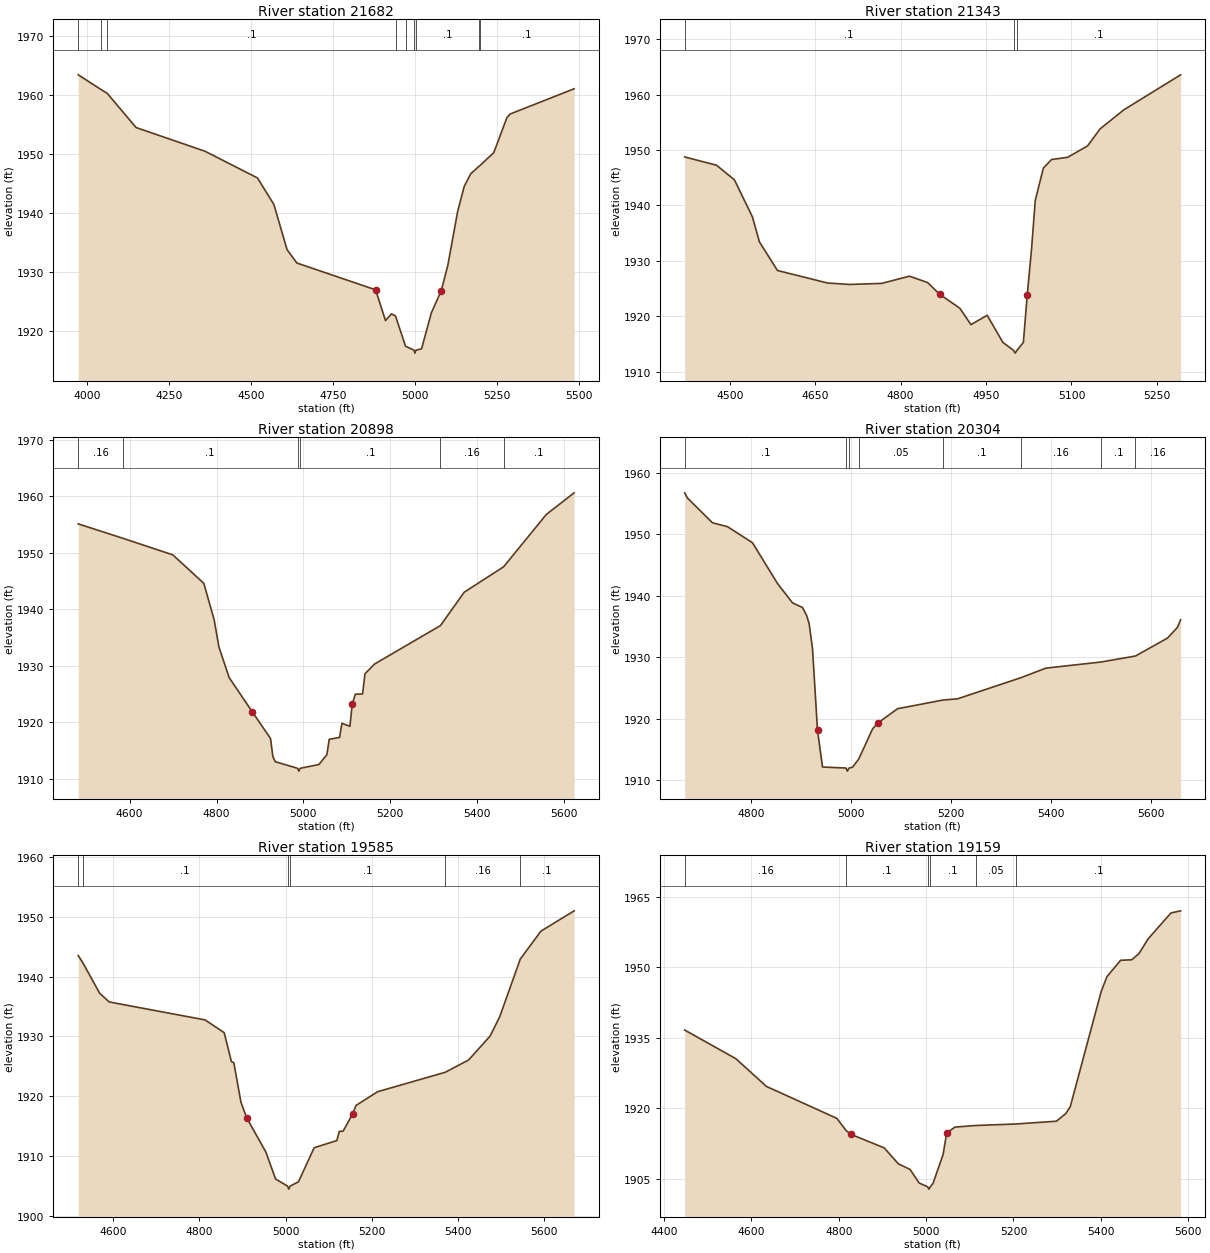
Type RM Length L Ch R = 1 ,21682   ,339,339,339
BEGIN DESCRIPTION:
FLAG CREEK 33.0
END DESCRIPTION:
XS GIS Cut Line= 2
      2665874.78      10069086.4      2664363.55     10069026.98
#Sta/Elev= 30
    3972 1963.47    4041 1960.99  4060.7 1960.31  4148.5 1954.51  4358.6 1950.48
  4518.7 1945.94  4568.8 1941.42  4608.8 1933.76  4638.8 1931.48    4879 1926.92
    4909  1921.7  4927.4 1922.83  4939.7 1922.46  4970.3 1917.33  4996.1 1916.66
  4998.9 1916.16  5002.1 1916.66  5019.1  1916.9  5049.1 1923.03  5079.2 1926.79
  5099.2  1931.1  5129.2 1940.25  5149.2 1944.51  5169.2 1946.66  5194.6 1947.94
  5196.2    1948  5239.3 1950.24  5279.3 1956.19  5289.3 1956.81  5484.4  1961.1
#Mann= 9 ,-1 , 0
    3972      .1       0    4041     .16       0  4060.7      .1       0
  4939.7     .16       0  4970.3      .1       0  4996.1     .07       0
  5002.1      .1       0  5194.6     .16       0  5196.2      .1       0
Bank Sta=4879,5079.2
XS Rating Curve= 0 ,0
Exp/Cntr=0.3,0.1

Type RM Length L Ch R = 1 ,21343   ,445,445,445
BEGIN DESCRIPTION:
FLAG CREEK 32.0
END DESCRIPTION:
XS GIS Cut Line= 3
      2665432.97     10068957.52      2664974.67     10068804.75
      2664683.75     10068548.47
#Sta/Elev= 30
  4420.8 1948.75  4476.6 1947.27  4508.2 1944.62  4539.8 1937.93    4552 1933.44
  4583.7 1928.27  4671.6 1926.01  4710.2 1925.75  4766.5 1925.94  4815.6 1927.24
  4847.2  1926.1  4868.3    1924  4903.9 1921.46  4923.5  1918.5  4951.9 1920.19
  4979.5  1915.3  4998.3 1913.86    5001 1913.36  5004.3 1913.86  5015.5 1915.29
  5022.2 1923.76  5029.7 1931.96  5036.4 1940.92  5050.6 1946.74  5064.9 1948.29
  5093.3 1948.69  5128.4 1950.76  5150.2 1953.82    5192 1957.26  5291.6 1963.57
#Mann= 3 ,-1 , 0
  4420.8      .1       0  4998.3     .07       0  5004.3      .1       0
Bank Sta=4868.3,5022.2
XS Rating Curve= 0 ,0
Exp/Cntr=0.3,0.1

Type RM Length L Ch R = 1 ,20898   ,594,594,594
BEGIN DESCRIPTION:
FLAG CREEK 31.0
END DESCRIPTION:
XS GIS Cut Line= 3
      2665797.32     10068851.65      2665166.38     10068587.64
      2664777.11     10068346.03
#Sta/Elev= 30
  4481.5 1955.12  4584.3 1952.57  4699.4 1949.63  4770.8 1944.58  4794.6 1938.12
  4805.5 1933.32  4829.2 1927.88  4882.2 1921.84  4924.4  1917.1  4929.8 1913.87
  4935.5 1912.98  4986.7 1911.82  4989.5 1911.32  4992.7 1911.82  5035.8 1912.49
  5054.2 1914.24  5059.6 1916.96  5083.4 1917.29  5088.8 1919.79  5107.2 1919.26
  5112.6 1923.23  5119.8 1924.95  5136.4 1924.99  5141.8 1928.56    5164 1930.29
  5315.8 1937.11  5370.5 1943.02  5461.1 1947.51  5559.4 1956.78  5623.6 1960.62
#Mann= 6 ,-1 , 0
  4481.5     .16       0  4584.3      .1       0  4986.7     .07       0
  4992.7      .1       0  5315.8     .16       0  5461.1      .1       0
Bank Sta=4882.2,5112.6
XS Rating Curve= 0 ,0
Exp/Cntr=0.3,0.1

Type RM Length L Ch R = 1 ,20304   ,719,719,719
BEGIN DESCRIPTION:
FLAG CREEK 30.0
END DESCRIPTION:
XS GIS Cut Line= 2
      2666044.07     10068283.92      2665052.29     10068263.11
#Sta/Elev= 30
  4667.6 1956.71  4673.2 1955.86  4723.2 1951.84  4753.2 1951.21  4803.2  1948.6
  4853.2 1941.98  4883.3 1938.82  4903.3 1938.07  4911.6 1936.76  4916.6 1935.41
  4923.3 1931.37  4933.3  1918.1  4943.3 1912.14  4990.3 1911.97    4993 1911.47
  4996.3 1911.97  5003.3  1912.1  5015.6 1913.41  5043.3 1918.31  5053.3 1919.25
  5093.3 1921.61  5183.8 1923.02  5213.3 1923.22  5339.9 1926.65  5390.1 1928.21
  5500.6 1929.21  5569.3 1930.18  5633.4  1933.1  5653.4 1934.85  5659.6 1936.08
#Mann= 8 ,-1 , 0
  4667.6      .1       0  4990.3     .07       0  4996.3      .1       0
  5015.6     .05       0  5183.8      .1       0  5339.9     .16       0
  5500.6      .1       0  5569.3     .16       0
Bank Sta=4933.3,5053.3
XS Rating Curve= 0 ,0
Exp/Cntr=0.3,0.1

Type RM Length L Ch R = 1 ,19585   ,426,426,426
BEGIN DESCRIPTION:
FLAG CREEK 29.0
END DESCRIPTION:
XS GIS Cut Line= 2
      2665877.49     10067506.12      2664849.64     10068026.99
#Sta/Elev= 30
  4518.2 1943.52  4528.6 1942.37  4567.9 1937.23  4590.2 1935.76  4812.9 1932.76
  4857.4 1930.62  4874.1 1925.78  4879.7 1925.61  4896.4 1918.96  4909.5  1916.4
  4954.3 1910.63  4976.7 1906.14  5004.7 1904.94  5007.5 1904.44  5010.7 1904.94
    5030 1905.67  5066.4 1911.37  5119.1 1912.56  5124.7  1914.1  5133.7 1914.14
  5156.1 1917.06  5163.6 1918.44  5213.8 1920.74  5371.3    1924  5425.2 1926.05
  5475.4 1930.07  5497.7 1933.31  5545.3 1942.93  5593.3 1947.61  5670.5 1951.01
#Mann= 6 ,-1 , 0
  4518.2     .16       0  4528.6      .1       0  5004.7     .07       0
  5010.7      .1       0  5371.3     .16       0  5545.3      .1       0
Bank Sta=4909.5,5156.1
XS Rating Curve= 0 ,0
Exp/Cntr=0.3,0.1

Type RM Length L Ch R = 1 ,19159   ,454,454,454
BEGIN DESCRIPTION:
FLAG CREEK 28.0
END DESCRIPTION:
XS GIS Cut Line= 2
      2665710.82     10067242.24      2664627.41     10067582.54
#Sta/Elev= 30
  4447.2 1936.66  4564.3 1930.56  4634.4 1924.65  4795.6 1917.85  4816.8 1915.26
    4827 1914.48  4904.1 1911.56  4936.6 1908.16  4963.3 1906.98  4984.2 1904.07
  5003.6 1903.28  5006.4 1902.78  5009.6 1903.28  5015.7 1903.97    5039 1910.16
  5047.1 1914.75  5066.2 1915.99  5113.9 1916.33  5205.7 1916.65  5298.3 1917.24
  5319.7 1918.85  5330.1 1920.33  5400.7 1944.79    5414 1948.01  5445.4 1951.51
  5470.8 1951.61  5487.4 1952.93  5508.5 1956.08  5560.7 1961.59  5582.8 1962.04
#Mann= 6 ,-1 , 0
  4447.2     .16       0  4816.8      .1       0  5003.6     .07       0
  5009.6      .1       0  5113.9     .05       0  5205.7      .1       0
Bank Sta=4827,5047.1
XS Rating Curve= 0 ,0
Exp/Cntr=0.3,0.1

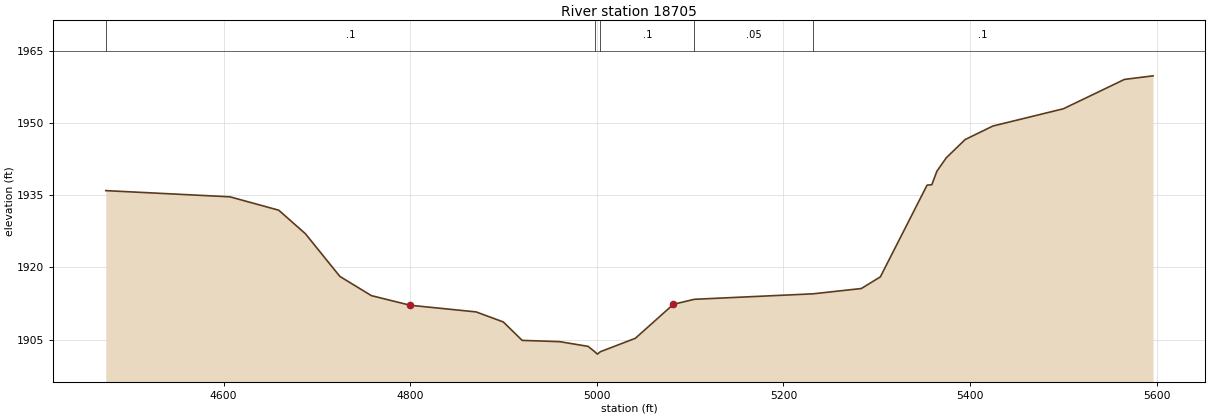
Type RM Length L Ch R = 1 ,18705   ,398,398,398
BEGIN DESCRIPTION:
FLAG CREEK 27.0
END DESCRIPTION:
XS GIS Cut Line= 2
      2665530.24     10066922.81      2664419.16     10067082.53
#Sta/Elev= 30
  4473.7 1935.98  4606.8 1934.69  4659.1 1931.91  4687.7 1927.01  4724.6 1918.14
  4758.4 1914.14  4800.1 1912.14  4870.6 1910.76  4899.8 1908.67    4920 1904.84
  4960.4 1904.57  4990.7 1903.59  4997.8 1902.48  5000.6 1901.98  5003.8 1902.48
  5041.3 1905.27  5082.1 1912.34  5104.5 1913.38  5231.8 1914.52  5283.5 1915.62
  5303.9 1918.04    5354 1937.12  5359.1 1937.21  5364.5 1940.01  5374.6 1942.81
  5394.8  1946.6  5424.5 1949.41  5500.1    1953  5565.5  1959.1  5596.2 1959.85
#Mann= 5 ,-1 , 0
  4473.7      .1       0  4997.8     .07       0  5003.8      .1       0
  5104.5     .05       0  5231.8      .1       0
Bank Sta=4800.1,5082.1
XS Rating Curve= 0 ,0
Exp/Cntr=0.3,0.1