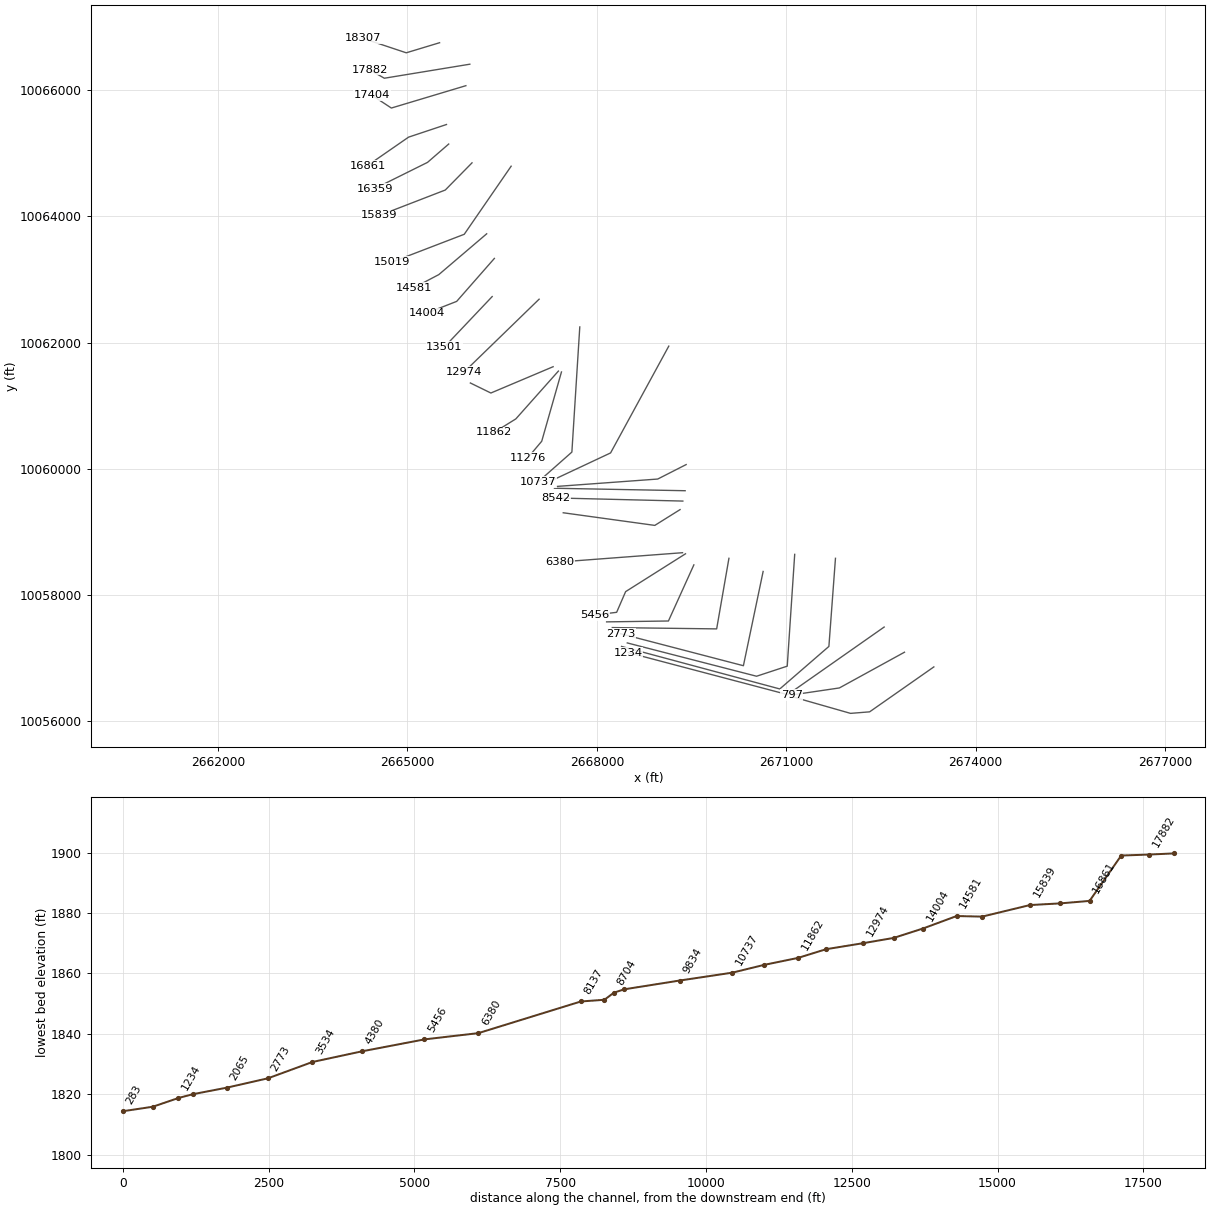
HEC-RAS study FLAG CREEK.prj: FLAG CREEK Base Level Engineering

--- FLAG CREEK.g01 (geometry) --- (continued)

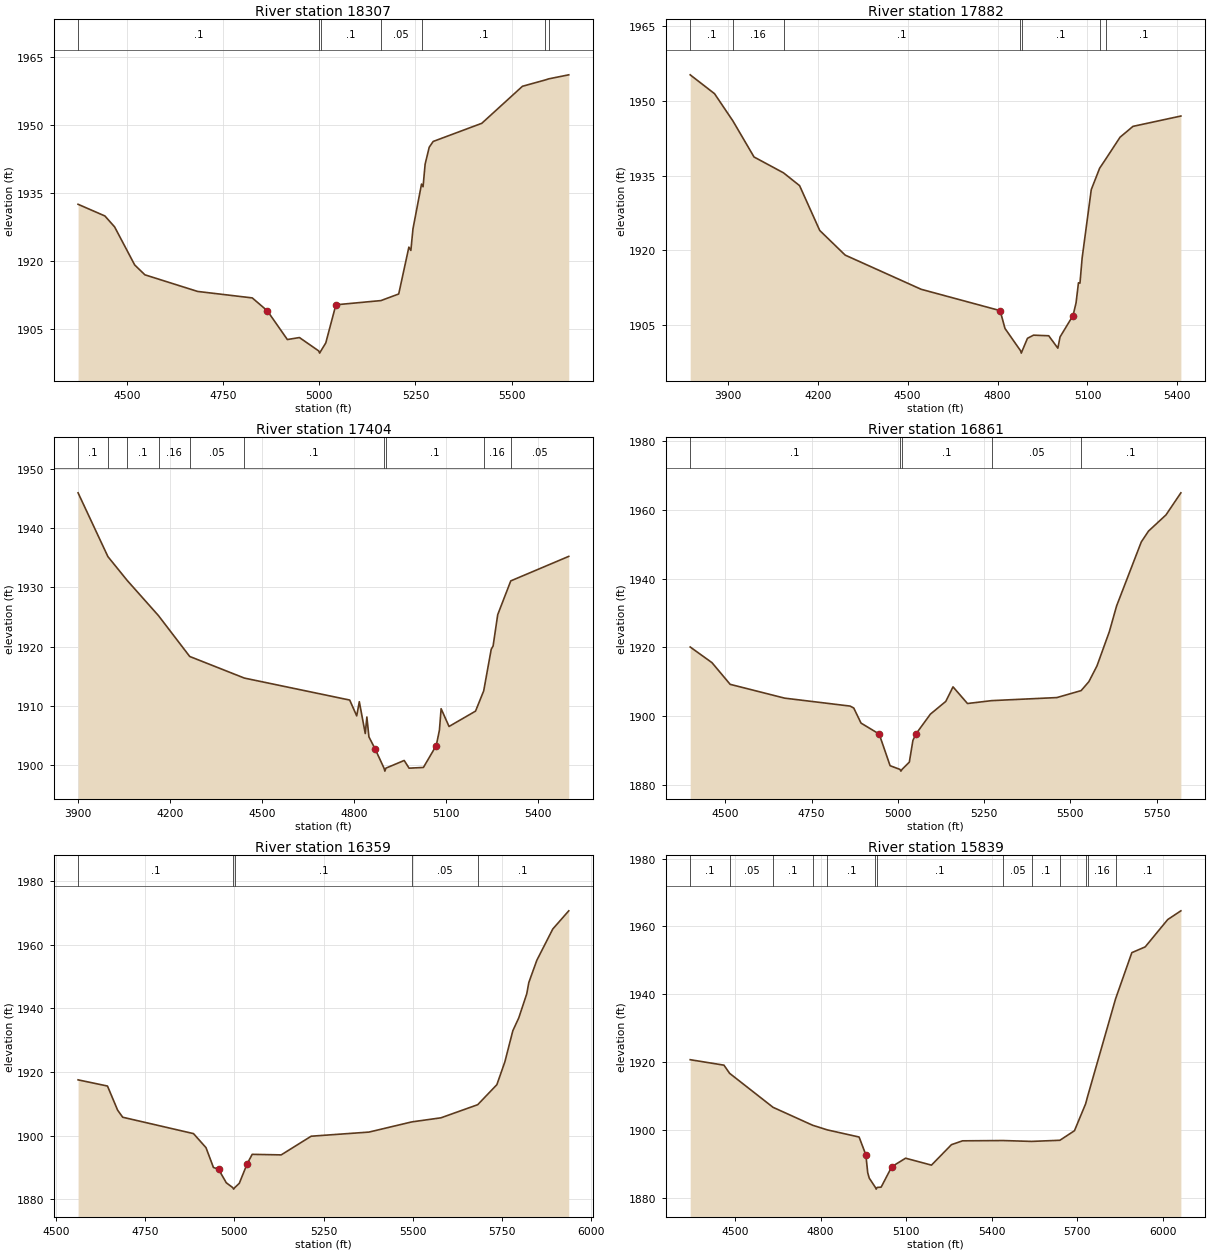
Type RM Length L Ch R = 1 ,18307   ,425,425,425
BEGIN DESCRIPTION:
FLAG CREEK 26.0
END DESCRIPTION:
XS GIS Cut Line= 3
      2665509.43     10066749.21      2664981.62     10066589.48
      2664294.16     10066818.63
#Sta/Elev= 30
  4372.5 1932.56  4442.3 1929.98  4467.5 1927.57  4519.8 1919.16  4546.3 1916.99
  4683.3 1913.32  4825.5 1911.89  4864.6 1909.05  4916.8  1902.7  4948.2 1903.14
  4998.1  1900.2  5000.8  1899.7  5004.1  1900.2  5016.7 1901.95    5043 1910.37
  5160.2  1911.3  5206.4 1912.76  5232.8  1923.1    5238 1922.37  5243.5 1927.16
  5265.7 1937.02  5269.7 1936.43  5275.1 1941.43  5285.7 1945.15    5296 1946.43
  5422.5 1950.44  5528.1 1958.61  5587.3    1960  5596.4 1960.25  5648.6 1961.14
#Mann= 7 ,-1 , 0
  4372.5      .1       0  4998.1     .07       0  5004.1      .1       0
  5160.2     .05       0  5265.7      .1       0  5587.3     .16       0
  5596.4      .1       0
Bank Sta=4864.6,5043
XS Rating Curve= 0 ,0
Exp/Cntr=0.3,0.1

Type RM Length L Ch R = 1 ,17882   ,478,478,478
BEGIN DESCRIPTION:
FLAG CREEK 25.0
END DESCRIPTION:
XS GIS Cut Line= 3
      2665988.57     10066408.92      2664634.39      10066186.7
      2664405.25     10066318.63
#Sta/Elev= 30
  3774.8 1955.25    3856 1951.46  3917.4 1945.97  3987.7 1938.74  4086.1 1935.55
  4139.7 1932.98  4206.9 1923.97  4291.7 1919.02  4545.1 1912.15  4808.6 1907.86
  4824.8 1904.28  4876.5 1899.82  4879.2 1899.32  4882.5 1899.82  4899.8  1902.3
    4920 1902.93  4970.7 1902.81  5001.1 1900.32  5008.6 1902.59  5051.8 1906.88
  5061.9 1909.43  5069.9 1913.46  5074.9 1913.38  5082.2 1918.47  5112.6 1932.18
  5140.5 1936.48    5161 1938.33  5208.6 1942.71  5251.7 1944.89  5411.5 1946.97
#Mann= 7 ,-1 , 0
  3774.8      .1       0  3917.4     .16       0  4086.1      .1       0
  4876.5     .07       0  4882.5      .1       0  5140.5     .16       0
    5161      .1       0
Bank Sta=4808.6,5051.8
XS Rating Curve= 0 ,0
Exp/Cntr=0.3,0.1

Type RM Length L Ch R = 1 ,17404   ,543,543,543
BEGIN DESCRIPTION:
FLAG CREEK 24.0
END DESCRIPTION:
XS GIS Cut Line= 3
      2665926.04     10066068.64       2664745.5     10065714.48
      2664439.92     10065915.88
#Sta/Elev= 30
  3901.4 1945.98  3998.6 1935.21  4061.7 1931.17  4163.4 1925.24  4265.1 1918.35
  4443.2  1914.7  4786.3 1910.99  4809.1 1908.32  4817.6 1910.71    4837 1905.34
  4842.2 1908.13  4848.9 1904.78  4869.8 1902.66  4898.1 1899.49  4900.9 1898.99
  4904.1 1899.49  4963.8 1900.79  4979.7 1899.49  5026.4 1899.61  5068.2 1903.31
  5078.6 1905.91  5084.1 1909.53  5109.9 1906.53  5196.2 1909.12  5222.8 1912.54
  5247.4 1919.58  5253.4 1920.11  5268.5 1925.41    5311 1931.11  5499.9 1935.25
#Mann= 10 ,-1 , 0
  3901.4      .1       0  3998.6     .16       0  4061.7      .1       0
  4163.4     .16       0  4265.1     .05       0  4443.2      .1       0
  4898.1     .07       0  4904.1      .1       0  5222.8     .16       0
    5311     .05       0
Bank Sta=4869.8,5068.2
XS Rating Curve= 0 ,0
Exp/Cntr=0.3,0.1

Type RM Length L Ch R = 1 ,16861   ,502,502,502
BEGIN DESCRIPTION:
FLAG CREEK 23.0
END DESCRIPTION:
XS GIS Cut Line= 3
      2665618.44     10065453.72      2665018.47     10065253.73
      2664368.46     10064803.73
#Sta/Elev= 30
  4397.7  1920.1  4460.9 1915.54  4513.6 1909.23  4671.7 1905.21  4861.5  1902.9
    4872 1902.34  4893.1 1897.95  4945.8 1894.76  4977.4 1885.55    5006 1884.47
  5008.8 1883.97    5012 1884.47  5033.2 1886.59  5043.6 1892.91  5052.4 1894.79
  5094.3 1900.56  5138.9 1904.26  5159.9  1908.5  5201.8 1903.65  5272.3 1904.49
  5461.2 1905.38  5531.5 1907.41  5553.8    1910  5577.4  1914.6  5613.3 1924.58
  5634.2 1932.03  5705.8 1950.66  5726.8 1953.83  5777.5 1958.54  5820.7 1964.97
#Mann= 5 ,-1 , 0
  4397.7      .1       0    5006     .07       0    5012      .1       0
  5272.3     .05       0  5531.5      .1       0
Bank Sta=4945.8,5052.4
XS Rating Curve= 0 ,0
Exp/Cntr=0.3,0.1

Type RM Length L Ch R = 1 ,16359   ,520,520,520
BEGIN DESCRIPTION:
FLAG CREEK 22.0
END DESCRIPTION:
XS GIS Cut Line= 3
        2665654.     10065144.35      2665318.47     10064853.73
      2664482.92       10064439.
#Sta/Elev= 30
  4561.3 1917.49  4643.8 1915.55  4672.3 1907.96  4686.6 1905.74  4885.1  1900.6
  4920.2 1896.19  4941.1 1889.96  4955.3 1889.41  4977.2 1885.14  4995.1 1883.65
  4997.8 1883.15  5001.1 1883.65  5013.6 1884.97    5036 1891.19  5049.8 1894.08
  5131.2 1893.91  5215.3 1899.78  5377.7 1901.08  5497.7 1904.28  5579.4 1905.56
  5682.5 1909.68  5736.3 1915.97  5758.7 1923.13  5781.1 1932.93  5797.8 1936.98
  5820.2 1944.55  5825.9 1948.06  5848.4 1955.06  5893.2  1964.9    5938 1970.61
#Mann= 5 ,-1 , 0
  4561.3      .1       0  4995.1     .07       0  5001.1      .1       0
  5497.7     .05       0  5682.5      .1       0
Bank Sta=4955.3,5036
XS Rating Curve= 0 ,0
Exp/Cntr=0.3,0.1

Type RM Length L Ch R = 1 ,15839   ,820,820,820
BEGIN DESCRIPTION:
FLAG CREEK 21.0
END DESCRIPTION:
XS GIS Cut Line= 3
      2666023.27     10064846.41      2665599.67     10064415.87
      2664558.02     10064013.09
#Sta/Elev= 30
  4342.6 1920.73    4461 1919.12  4480.8 1916.72  4633.2  1906.7    4772 1901.42
  4823.6 1900.05  4934.9 1897.95  4958.6 1892.72  4965.2 1887.42  4970.5 1885.85
  4992.1  1883.1  4994.9  1882.6  4998.1  1883.1  5012.2 1883.18  5049.6 1889.21
    5098 1891.71  5188.7 1889.67  5258.8  1895.7  5297.7 1896.83  5440.3 1896.91
  5539.7 1896.66  5639.1 1896.99  5690.2 1899.81  5729.3 1907.72  5736.3 1909.91
  5834.3 1938.64  5891.4 1952.27  5938.2 1953.96  6017.4 1962.03  6063.4 1964.59
#Mann= 13 ,-1 , 0
  4342.6      .1       0  4480.8     .05       0  4633.2      .1       0
    4772     .05       0  4823.6      .1       0  4992.1     .07       0
  4998.1      .1       0  5440.3     .05       0  5539.7      .1       0
  5639.1     .16       0  5729.3      .1       0  5736.3     .16       0
  5834.3      .1       0
Bank Sta=4958.6,5049.6
XS Rating Curve= 0 ,0
Exp/Cntr=0.3,0.1

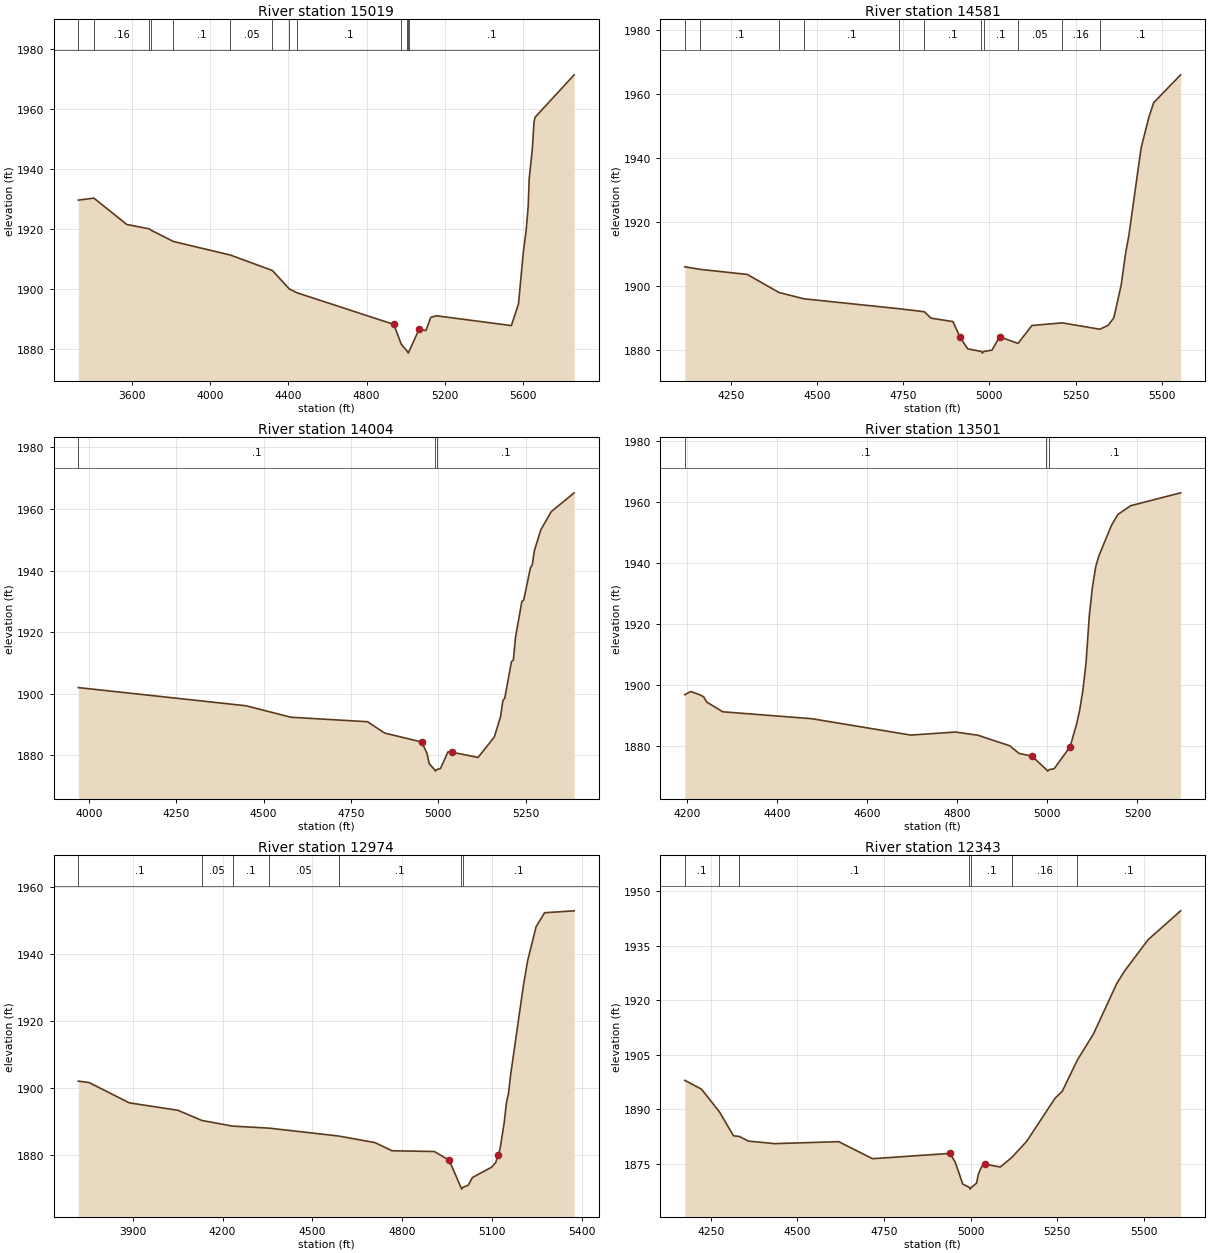
Type RM Length L Ch R = 1 ,15019   ,438,438,438
BEGIN DESCRIPTION:
FLAG CREEK 20.0
END DESCRIPTION:
XS GIS Cut Line= 3
        2666643.     10064793.29       2665900.2      10063714.9
      2664759.22      10063276.4
#Sta/Elev= 30
  3328.4 1929.77  3407.7 1930.44  3575.6 1921.66  3690.6 1920.19  3700.3 1919.73
  3813.8 1915.98  4104.8 1911.46  4319.6  1906.3  4406.2 1900.14  4445.7 1898.87
  4939.7 1888.33  4977.4 1881.72  5007.5  1879.4  5010.4 1879.27  5013.1 1878.77
  5016.4 1879.27    5068 1886.66  5103.4 1886.31  5128.1 1890.71  5158.1 1891.21
  5539.6 1887.95    5576 1895.18  5600.7 1912.47  5614.6 1919.35  5625.3 1927.48
  5630.7 1936.95  5646.7 1946.87  5655.3 1955.89  5660.7 1957.38  5860.2 1971.53
#Mann= 13 ,-1 , 0
  3328.4      .1       0  3407.7     .16       0  3690.6      .1       0
  3700.3     .05       0  3813.8      .1       0  4104.8     .05       0
  4319.6      .1       0  4406.2     .05       0  4445.7      .1       0
  4977.4     .05       0  5007.5      .1       0  5010.4    .035       0
  5016.4      .1       0
Bank Sta=4939.7,5068
XS Rating Curve= 0 ,0
Exp/Cntr=0.3,0.1

Type RM Length L Ch R = 1 ,14581   ,577,577,577
BEGIN DESCRIPTION:
FLAG CREEK 19.0
END DESCRIPTION:
XS GIS Cut Line= 3
      2666255.56     10063722.47      2665497.72     10063076.61
       2665107.1     10062870.89
#Sta/Elev= 30
  4117.1 1905.95  4160.7 1905.16  4298.1 1903.56  4390.3 1897.91  4462.6 1895.94
  4737.6 1892.85  4811.6  1891.9  4830.7 1889.89  4894.4 1888.82  4915.2 1883.85
  4937.2  1880.3    4977 1879.46  4979.8 1878.96    4983 1879.46  5007.5 1879.89
  5029.5 1884.06  5082.9    1882  5123.3  1887.6  5211.3 1888.42  5320.3 1886.43
    5344 1887.65  5360.4 1889.94    5366 1892.51  5382.4 1900.49  5394.5 1909.98
  5404.4 1915.82  5439.7 1943.08  5462.3 1952.71  5476.2 1957.25  5554.3 1965.96
#Mann= 11 ,-1 , 0
  4117.1     .05       0  4160.7      .1       0  4390.3     .05       0
  4462.6      .1       0  4737.6     .05       0  4811.6      .1       0
    4977     .07       0    4983      .1       0  5082.9     .05       0
  5211.3     .16       0  5320.3      .1       0
Bank Sta=4915.2,5029.5
XS Rating Curve= 0 ,0
Exp/Cntr=0.3,0.1

Type RM Length L Ch R = 1 ,14004   ,503,503,503
BEGIN DESCRIPTION:
FLAG CREEK 18.0
END DESCRIPTION:
XS GIS Cut Line= 3
      2666377.48     10063332.57      2665780.23     10062651.98
       2665302.3     10062464.96
#Sta/Elev= 30
    3970 1901.97  4450.1 1896.06  4578.2 1892.34  4797.4 1890.88  4846.7 1887.19
  4952.5 1884.29  4967.7 1880.57    4974 1877.23  4989.1 1875.33  4991.9 1874.83
  4995.1 1875.33  5006.2 1875.68  5027.7 1881.09  5038.5 1880.99  5113.6 1879.27
  5160.4 1885.94  5178.1 1892.55  5184.8 1897.73  5190.2 1898.57  5209.3 1910.41
  5214.7 1910.88    5221 1918.39  5239.1 1929.93  5244.5 1930.48  5263.6 1940.86
    5269 1941.92  5274.7 1946.36  5293.4 1953.26  5323.2 1959.13  5388.7 1965.24
#Mann= 3 ,-1 , 0
    3970      .1       0  4989.1     .07       0  4995.1      .1       0
Bank Sta=4952.5,5038.5
XS Rating Curve= 0 ,0
Exp/Cntr=0.3,0.1

Type RM Length L Ch R = 1 ,13501   ,527,527,527
BEGIN DESCRIPTION:
FLAG CREEK 17.0
END DESCRIPTION:
XS GIS Cut Line= 2
      2666342.73     10062728.37      2665585.82     10061929.79
#Sta/Elev= 30
  4195.5 1896.76  4208.9 1897.81  4229.9 1896.66  4237.2 1896.09  4244.1 1894.36
  4279.7 1891.16  4477.5 1888.89  4697.1 1883.52  4795.8 1884.52  4845.6 1883.49
  4916.4 1880.03  4937.4 1877.51  4965.7 1876.64    4998 1872.21  5000.8 1871.71
    5004 1872.21  5015.1 1872.48  5050.7 1879.76  5064.8 1887.08  5071.7 1891.61
    5079 1898.28  5085.9 1907.21  5093.1 1922.59    5100 1931.89  5107.3 1938.67
  5114.2 1942.22  5142.5 1952.31  5156.7 1955.86    5185 1958.71  5295.8 1962.93
#Mann= 3 ,-1 , 0
  4195.5      .1       0    4998     .07       0    5004      .1       0
Bank Sta=4965.7,5050.7
XS Rating Curve= 0 ,0
Exp/Cntr=0.3,0.1

Type RM Length L Ch R = 1 ,12974   ,631,631,631
BEGIN DESCRIPTION:
FLAG CREEK 16.0
END DESCRIPTION:
XS GIS Cut Line= 2
      2667085.81     10062686.73      2665898.32     10061533.95
#Sta/Elev= 30
  3718.6 1902.11  3754.3  1901.7  3888.6 1895.65  4051.1 1893.43  4130.7 1890.41
  4233.2 1888.72  4356.6 1888.11  4587.5 1885.77  4708.9 1883.81  4765.4 1881.38
  4906.9 1881.16  4956.3 1878.58  4995.8 1870.46  4998.5 1869.96  5001.8 1870.46
  5020.1 1871.13  5034.2 1873.43  5097.8 1876.48  5111.9  1877.9  5119.1    1880
  5126.1 1881.83  5140.2 1889.82  5147.4  1895.6  5154.4 1898.46  5161.6 1904.01
    5204 1930.46  5218.1 1937.87  5246.4 1948.03  5274.7 1952.25  5373.6 1952.82
#Mann= 7 ,-1 , 0
  3718.6      .1       0  4130.7     .05       0  4233.2      .1       0
  4356.6     .05       0  4587.5      .1       0  4995.8     .07       0
  5001.8      .1       0
Bank Sta=4956.3,5119.1
XS Rating Curve= 0 ,0
Exp/Cntr=0.3,0.1

Type RM Length L Ch R = 1 ,12343   ,481,481,481
BEGIN DESCRIPTION:
FLAG CREEK 15.0
END DESCRIPTION:
XS GIS Cut Line= 3
      2667308.01     10061617.26      2666321.89     10061200.59
      2665997.13     10061359.51
#Sta/Elev= 30
  4174.6 1897.94  4222.6 1895.53  4274.6 1889.27  4315.2 1882.67    4332 1882.49
  4358.7  1881.2  4434.7 1880.51  4619.2 1881.05  4716.9 1876.36  4940.5 1877.82
  4955.7 1875.39  4977.5 1869.36  4996.2 1868.48  4998.9 1867.98  5002.2 1868.48
  5017.1  1869.6  5022.5 1872.09  5031.7 1874.16  5040.8 1874.88    5086 1874.07
  5119.3 1876.72    5162 1881.14  5244.3 1893.05  5264.7 1894.89  5308.6 1903.56
  5354.7 1910.67  5422.2 1924.59  5444.7 1928.03  5512.3 1936.62  5606.7 1944.62
#Mann= 7 ,-1 , 0
  4174.6      .1       0  4274.6     .05       0    4332      .1       0
  4996.2     .07       0  5002.2      .1       0  5119.3     .16       0
  5308.6      .1       0
Bank Sta=4940.5,5040.8
XS Rating Curve= 0 ,0
Exp/Cntr=0.3,0.1

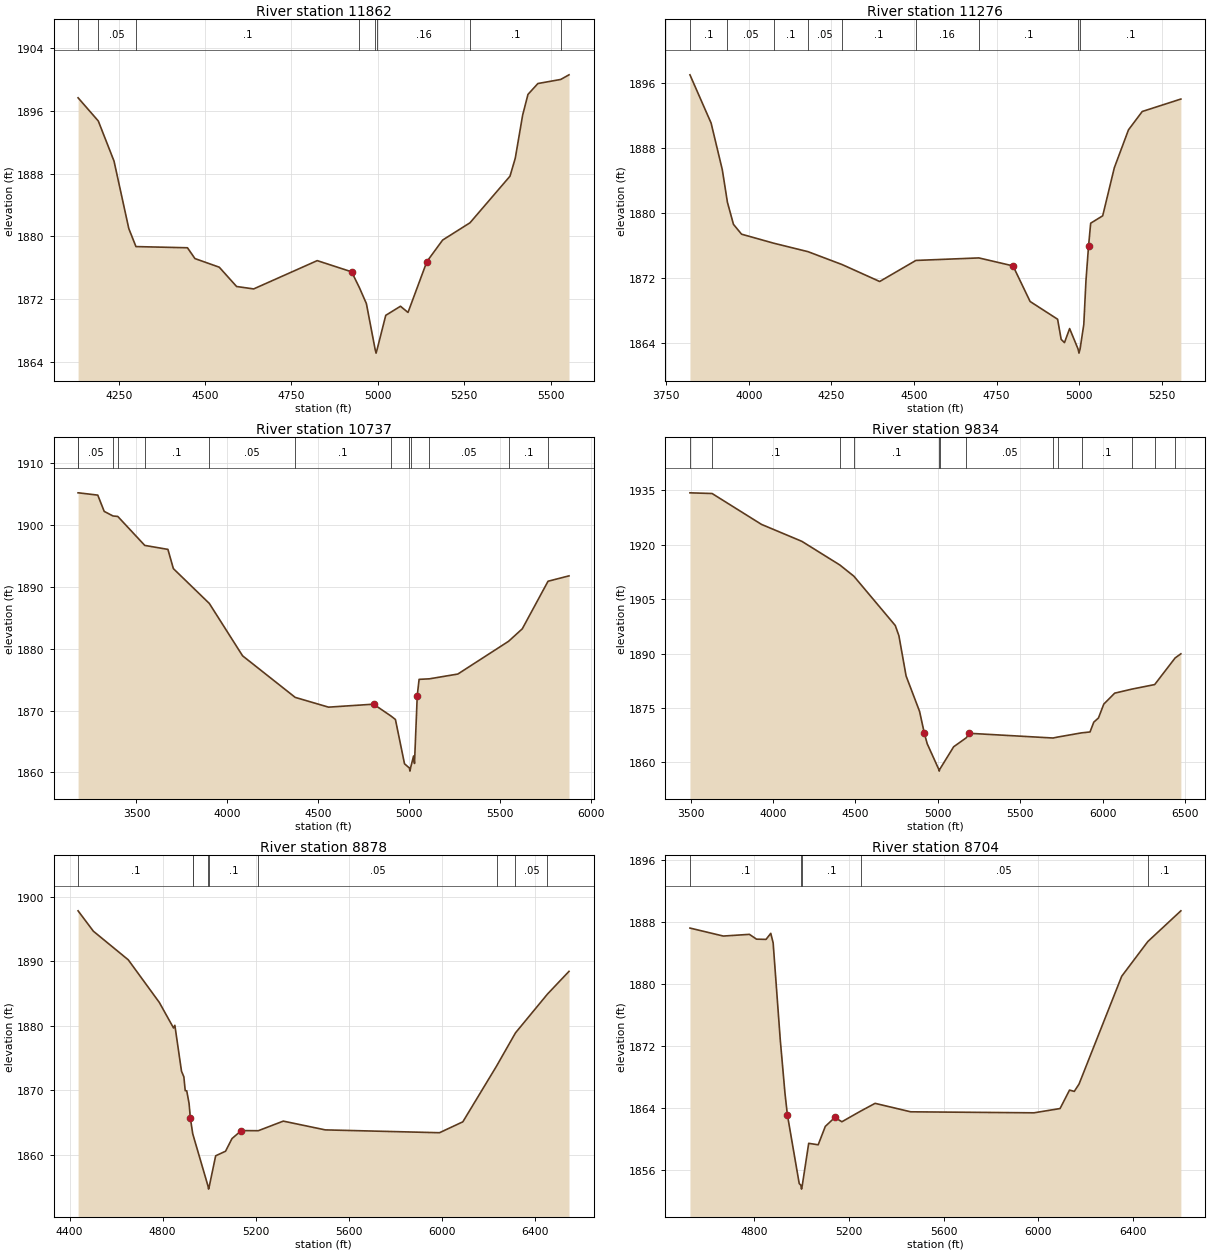
Type RM Length L Ch R = 1 ,11862   ,586,586,586
BEGIN DESCRIPTION:
FLAG CREEK 14.0
END DESCRIPTION:
XS GIS Cut Line= 3
      2667391.36     10061547.83      2666717.73     10060790.87
      2666371.99     10060576.51
#Sta/Elev= 30
  4132.7 1897.67  4191.2 1894.71  4236.7 1889.59  4279.4 1880.99  4300.1 1878.69
  4449.1 1878.54  4470.8 1877.16  4541.1 1876.06  4591.2  1873.6  4640.6 1873.29
  4824.5  1876.9    4924 1875.47  4946.5 1873.45  4966.7 1871.42  4991.9  1865.6
  4994.7  1865.1  4997.9  1865.6  5022.7 1869.92  5065.3 1871.08  5087.1 1870.29
  5141.7 1876.78  5187.2 1879.52  5266.5 1881.73  5382.1 1887.67  5397.4 1889.97
  5418.7 1895.46  5434.1  1898.1  5462.8 1899.49  5528.9 1900.01  5552.8  1900.6
#Mann= 8 ,-1 , 0
  4132.7      .1       0  4191.2     .05       0  4300.1      .1       0
  4946.5     .16       0  4991.9     .07       0  4997.9     .16       0
  5266.5      .1       0  5528.9     .16       0
Bank Sta=4924,5141.7
XS Rating Curve= 0 ,0
Exp/Cntr=0.3,0.1

Type RM Length L Ch R = 1 ,11276   ,539,539,539
BEGIN DESCRIPTION:
FLAG CREEK 13.0
END DESCRIPTION:
XS GIS Cut Line= 3
      2667439.96     10061533.95      2667127.45      10060436.7
      2666905.21     10060172.79
#Sta/Elev= 30
  3822.1    1897  3886.1 1891.07    3920 1885.33  3935.5 1881.33  3953.8 1878.61
  3978.3  1877.4  4075.7 1876.29  4179.3 1875.25  4282.8 1873.66  4396.4 1871.58
  4505.9 1874.17  4696.6 1874.48  4799.9  1873.5  4851.7 1869.12  4934.9 1866.94
  4945.7 1864.46  4955.7 1864.06  4971.3 1865.79  4996.9 1863.27  4999.6 1862.77
  5002.9 1863.27  5014.2  1866.3  5020.7 1871.65  5028.5  1875.9    5035 1878.75
  5071.4 1879.66  5106.5 1885.56  5149.4 1890.23  5191.1 1892.49    5308 1894.02
#Mann= 9 ,-1 , 0
  3822.1      .1       0  3935.5     .05       0  4075.7      .1       0
  4179.3     .05       0  4282.8      .1       0  4505.9     .16       0
  4696.6      .1       0  4996.9     .07       0  5002.9      .1       0
Bank Sta=4799.9,5028.5
XS Rating Curve= 0 ,0
Exp/Cntr=0.3,0.1

Type RM Length L Ch R = 1 ,10737   ,903,903,903
BEGIN DESCRIPTION:
FLAG CREEK 12.0
END DESCRIPTION:
XS GIS Cut Line= 3
      2667730.28     10062247.26      2667604.99     10060265.05
      2667068.04     10059790.74
#Sta/Elev= 30
  3178.5  1905.2  3180.4  1905.2  3286.9 1904.83  3322.3  1902.2  3370.6 1901.46
  3397.1 1901.38  3545.6  1896.7    3673 1896.06  3703.1 1892.95    3901 1887.32
    4084 1878.86  4373.7 1872.14  4557.3 1870.56  4805.3 1871.04  4900.4 1869.14
  4925.5 1868.57  4975.6  1861.4  5002.7 1860.72  5005.4 1860.22  5008.7 1860.72
  5025.5 1862.67  5030.5 1861.46  5045.7 1872.41  5055.8 1875.05  5112.8 1875.14
  5269.1 1875.91  5548.7 1881.21  5623.9 1883.22  5765.7 1890.91  5881.1 1891.78
#Mann= 13 ,-1 , 0
  3178.5      .1       0  3180.4     .05       0  3370.6      .1       0
  3397.1     .05       0  3545.6      .1       0    3901     .05       0
  4373.7      .1       0  4900.4     .16       0  5002.7     .07       0
  5008.7     .16       0  5112.8     .05       0  5548.7      .1       0
  5765.7     .05       0
Bank Sta=4805.3,5045.7
XS Rating Curve= 0 ,0
Exp/Cntr=0.3,0.1

Type RM Length L Ch R = 1 ,9834    ,956,956,956
BEGIN DESCRIPTION:
FLAG CREEK 11.0
END DESCRIPTION:
XS GIS Cut Line= 3
      2669139.75     10061942.99        2668218.     10060251.63
      2667264.93     10059804.17
#Sta/Elev= 30
  3496.4 1934.35  3630.8 1934.16  3930.7 1925.64  4175.7 1920.97  4406.1 1914.45
  4491.2 1911.36  4742.5 1897.76  4764.4 1894.95  4808.1 1883.85  4889.7  1874.1
  4919.1 1867.99  4936.2 1865.16  5006.3 1858.11  5009.1 1857.61  5012.3 1858.11
  5096.7 1864.33  5172.8 1866.79  5192.4 1868.04  5699.9 1866.74  5729.9 1867.02
  5872.7 1868.16  5924.2 1868.41    5947 1871.11  5975.3 1872.26  6007.6 1876.08
  6073.9 1879.11  6178.7 1880.23  6316.6 1881.48  6440.7 1888.82  6475.5 1889.96
#Mann= 13 ,-1 , 0
  3496.4     .16       0  3630.8      .1       0  4406.1     .16       0
  4491.2      .1       0  5006.3     .07       0  5012.3      .1       0
  5172.8     .05       0  5699.9      .1       0  5729.9     .05       0
  5872.7      .1       0  6178.7     .05       0  6316.6      .1       0
  6440.7     .05       0
Bank Sta=4919.1,5192.4
XS Rating Curve= 0 ,0
Exp/Cntr=0.3,0.1

Type RM Length L Ch R = 1 ,8878    ,174,174,174
BEGIN DESCRIPTION:
FLAG CREEK 10.0
END DESCRIPTION:
XS GIS Cut Line= 3
      2669414.86     10060067.08      2668964.38     10059837.93
      2667363.18     10059720.77
#Sta/Elev= 30
  4436.4 1897.86  4502.1  1894.7  4652.2 1890.26  4785.7 1883.65  4846.8 1879.69
  4852.5  1880.1  4881.1 1872.98  4891.3  1872.1    4897 1869.97  4903.6 1869.94
  4913.6 1867.98  4919.2 1865.72  4929.2 1863.31  4930.7 1863.11  4994.9 1855.19
  4997.6 1854.69  5000.9 1855.19    5028 1859.86  5070.5 1860.57  5098.1 1862.53
  5138.3 1863.77  5211.2 1863.75  5318.7 1865.24  5499.2 1863.88  5990.5 1863.44
  6090.8 1865.13    6236 1873.79  6317.2 1878.93  6454.3 1884.93  6547.3 1888.47
#Mann= 9 ,-1 , 0
  4436.4      .1       0  4929.2     .16       0  4930.7      .1       0
  4994.9     .07       0  5000.9      .1       0  5211.2     .05       0
    6236      .1       0  6317.2     .05       0  6454.3      .1       0
Bank Sta=4919.2,5138.3
XS Rating Curve= 0 ,0
Exp/Cntr=0.3,0.1

Type RM Length L Ch R = 1 ,8704    ,162,162,162
BEGIN DESCRIPTION:
Mapping XS 76035b88
END DESCRIPTION:
XS GIS Cut Line= 2
      2669399.27     10059653.04      2667328.93      10059692.1
#Sta/Elev= 30
    4530 1887.21  4670.8 1886.18  4780.8  1886.4  4810.8 1885.78  4850.9 1885.75
  4870.9 1886.53  4880.9  1885.3  4910.9 1872.83  4930.9  1865.9  4940.9 1863.17
  4990.9  1854.3  4997.9 1854.08  5000.6 1853.58  5003.9 1854.08  5030.9 1859.48
  5070.9 1859.29  5100.9 1861.66  5140.9 1862.81  5170.9 1862.26  5249.4 1863.62
  5310.9 1864.63    5461 1863.54  5981.1 1863.41  6091.1 1863.96  6131.1 1866.34
  6151.1 1866.17  6171.1 1867.11  6351.1    1881  6461.2 1885.47  6600.7 1889.43
#Mann= 5 ,-1 , 0
    4530      .1       0  4997.9     .07       0  5003.9      .1       0
  5249.4     .05       0  6461.2      .1       0
Bank Sta=4940.9,5140.9
XS Rating Curve= 0 ,0
Exp/Cntr=0.3,0.1

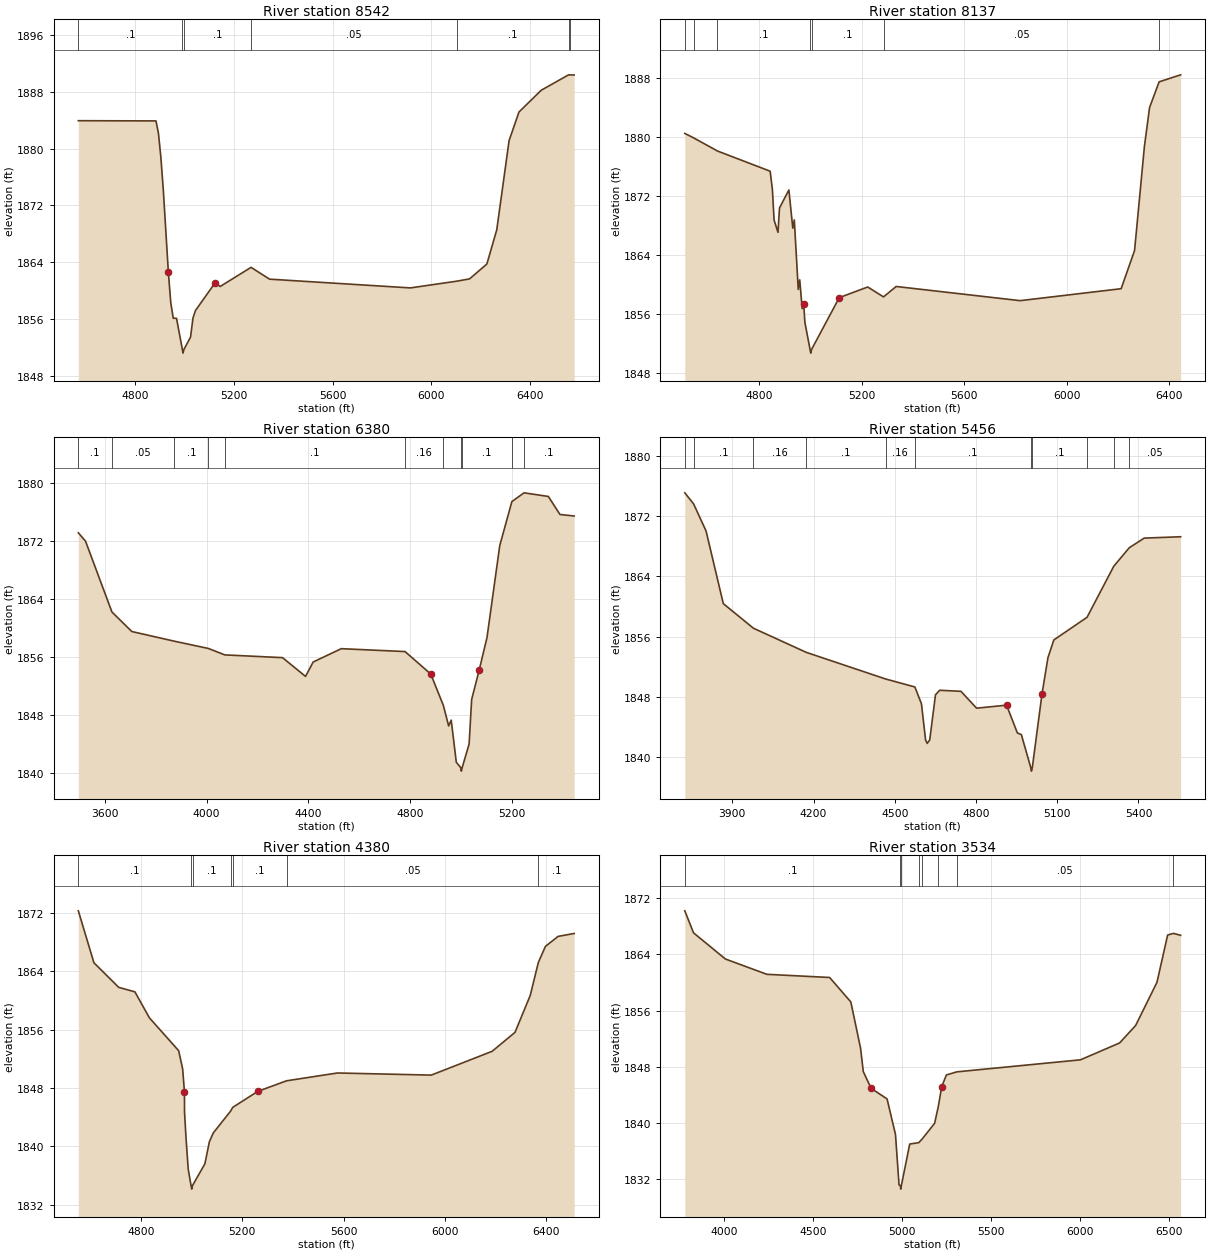
Type RM Length L Ch R = 1 ,8542    ,405,405,405
BEGIN DESCRIPTION:
Mapping XS 1a3f53f2
END DESCRIPTION:
XS GIS Cut Line= 2
      2669362.83     10059488.97      2667355.04     10059538.45
#Sta/Elev= 30
  4570.4 1883.92  4884.9 1883.89  4894.9 1882.16  4904.9  1878.7  4914.9 1874.05
  4934.9  1862.7  4944.9 1858.31  4954.9 1856.15  4968.2 1856.13  4991.9 1851.74
  4994.6 1851.24  4997.9 1851.74  5024.9 1853.49  5034.9 1856.19  5044.9 1857.23
  5124.9 1861.15  5144.9 1860.61  5270.1  1863.3    5345 1861.64  5915.2 1860.41
  6102.3 1861.35  6155.2 1861.68  6225.3 1863.77  6265.3 1868.58  6315.3 1881.13
  6355.3 1885.14  6445.3  1888.2  6556.3 1890.37  6560.8 1890.36  6578.8 1890.35
#Mann= 7 ,-1 , 0
  4570.4      .1       0  4991.9     .07       0  4997.9      .1       0
  5270.1     .05       0  6102.3      .1       0  6556.3     .05       0
  6560.8      .1       0
Bank Sta=4934.9,5124.9
XS Rating Curve= 0 ,0
Exp/Cntr=0.3,0.1

Type RM Length L Ch R = 1 ,8137    ,1757,1757,1757
BEGIN DESCRIPTION:
FLAG CREEK 9.0
END DESCRIPTION:
XS GIS Cut Line= 3
       2669318.5     10059353.76      2668918.47     10059103.73
      2667468.44     10059303.74
#Sta/Elev= 30
  4508.5 1880.44  4542.9 1879.84  4635.9 1878.06  4841.7 1875.32  4850.5 1872.84
    4857 1868.71  4872.3 1867.04  4878.2 1870.34  4914.8 1872.78  4930.1  1867.6
    4936 1868.72  4951.4  1859.3  4957.2  1860.6  4966.7  1856.7  4972.6 1857.35
  4977.3 1854.84  4997.4 1851.17  5000.2 1850.67  5003.4 1851.17  5111.5 1858.19
  5222.5 1859.63  5284.2 1858.29  5333.6  1859.7  5817.5 1857.78  6211.8  1859.4
  6264.2 1864.57  6302.6 1878.66  6322.8 1883.95  6360.1 1887.43    6444 1888.38
#Mann= 7 ,-1 , 0
  4508.5      .1       0  4542.9     .16       0  4635.9      .1       0
  4997.4     .07       0  5003.4      .1       0  5284.2     .05       0
  6360.1      .1       0
Bank Sta=4972.6,5111.5
XS Rating Curve= 0 ,0
Exp/Cntr=0.3,0.1

Type RM Length L Ch R = 1 ,6380    ,924,924,924
BEGIN DESCRIPTION:
Mapping XS d8c82d09
END DESCRIPTION:
XS GIS Cut Line= 2
      2669357.46     10058671.17      2667417.39     10058524.59
#Sta/Elev= 30
    3497  1873.1  3525.2 1871.95  3628.8 1862.17  3706.6 1859.47  3873.9 1858.13
  4007.3 1857.13  4071.8 1856.24  4298.3 1855.86  4388.5 1853.27  4418.6 1855.26
  4528.9  1857.1    4779  1856.7  4879.9  1853.6  4929.4 1849.26  4950.1 1846.43
  4960.2 1847.23  4980.2 1841.41  4997.3 1840.69    5000 1840.19  5003.3 1840.69
  5030.4 1843.93  5040.4 1850.08  5070.5 1854.22  5100.6 1858.64  5150.7 1871.34
  5198.2 1877.41    5246 1878.62  5341.2 1878.12    5387 1875.63  5442.6 1875.42
#Mann= 11 ,-1 , 0
    3497      .1       0  3628.8     .05       0  3873.9      .1       0
  4007.3     .16       0  4071.8      .1       0    4779     .16       0
  4929.4      .1       0  4997.3     .07       0  5003.3      .1       0
  5198.2     .05       0    5246      .1       0
Bank Sta=4879.9,5070.5
XS Rating Curve= 0 ,0
Exp/Cntr=0.3,0.1

Type RM Length L Ch R = 1 ,5456    ,1076,1076,1076
BEGIN DESCRIPTION:
FLAG CREEK 8.0
END DESCRIPTION:
XS GIS Cut Line= 4
      2669404.84     10058653.93      2668456.38     10058054.67
      2668314.11     10057727.02      2667964.88     10057683.91
#Sta/Elev= 30
  3724.6 1875.12  3757.1 1873.65  3803.1 1870.05  3866.8 1860.39  3977.9 1857.12
  4173.2 1853.91  4466.2 1850.37  4574.2 1849.31  4598.5 1847.08  4613.8 1842.27
  4619.7 1841.81  4629.1 1842.26  4650.3 1848.26  4665.6 1848.87  4744.4 1848.73
  4802.1 1846.49  4912.9 1846.89  4952.7  1843.2  4967.5 1842.97    5002 1838.62
  5004.8 1838.12    5008 1838.62  5043.8  1848.4  5065.6 1853.19  5087.4 1855.56
    5210 1858.57  5308.9 1865.37    5366 1867.82    5421  1869.1  5555.6 1869.28
#Mann= 11 ,-1 , 0
  3724.6     .05       0  3757.1      .1       0  3977.9     .16       0
  4173.2      .1       0  4466.2     .16       0  4574.2      .1       0
    5002     .07       0    5008      .1       0    5210     .05       0
  5308.9      .1       0    5366     .05       0
Bank Sta=4912.9,5043.8
XS Rating Curve= 0 ,0
Exp/Cntr=0.3,0.1

Type RM Length L Ch R = 1 ,4380    ,846,846,846
BEGIN DESCRIPTION:
FLAG CREEK 7.0
END DESCRIPTION:
XS GIS Cut Line= 3
      2669537.17     10058478.37      2669134.39     10057589.48
      2668155.18     10057575.59
#Sta/Elev= 30
  4553.9 1872.25  4615.4 1865.14  4713.2 1861.77    4777 1861.16  4834.2  1857.6
  4949.6  1853.1  4965.2 1850.61 4972.35 1847.49  4972.7 1844.69  4978.2 1841.35
  4987.2  1836.9  4998.3 1834.65  5001.1 1834.15  5004.3 1834.65    5053 1837.62
  5070.6 1840.63    5086 1841.84  5154.4 1844.83  5162.7 1845.34  5260.8 1847.52
  5374.8 1848.98  5575.7 1850.05  5945.8 1849.76  6185.8 1853.02  6275.8 1855.61
  6335.8 1860.65  6367.9 1865.18  6395.8 1867.38  6445.8 1868.75  6509.1 1869.15
#Mann= 7 ,-1 , 0
  4553.9      .1       0  4998.3     .07       0  5004.3      .1       0
  5154.4     .16       0  5162.7      .1       0  5374.8     .05       0
  6367.9      .1       0
Bank Sta=4972.35,5260.8
XS Rating Curve= 0 ,0
Exp/Cntr=0.3,0.1

Type RM Length L Ch R = 1 ,3534    ,761,761,761
BEGIN DESCRIPTION:
FLAG CREEK 6.0
END DESCRIPTION:
XS GIS Cut Line= 3
      2670092.72     10058582.49      2669898.28     10057464.48
      2668245.51     10057485.31
#Sta/Elev= 30
  3777.8 1870.21    3827 1867.08  4005.9 1863.36  4239.4 1861.18  4592.1 1860.73
  4711.3 1857.25  4765.9 1850.69  4781.4 1847.34  4825.5 1844.96    4915 1843.46
  4962.4  1838.4  4982.4 1831.22  4989.4 1831.13  4992.2 1830.63  4995.4 1831.13
  5042.4 1837.04  5093.4 1837.24    5114 1837.81  5182.4 1839.99  5203.2 1842.39
  5222.4 1845.22  5248.8 1846.87  5307.7 1847.31  6002.5 1849.02  6222.5 1851.42
  6312.5  1853.9  6432.5 1860.04  6492.5 1866.77  6525.1    1867  6565.5 1866.73
#Mann= 8 ,-1 , 0
  3777.8      .1       0  4989.4     .07       0  4995.4      .1       0
  5093.4     .16       0    5114      .1       0  5203.2     .16       0
  5307.7     .05       0  6525.1      .1       0
Bank Sta=4825.5,5222.4
XS Rating Curve= 0 ,0
Exp/Cntr=0.3,0.1

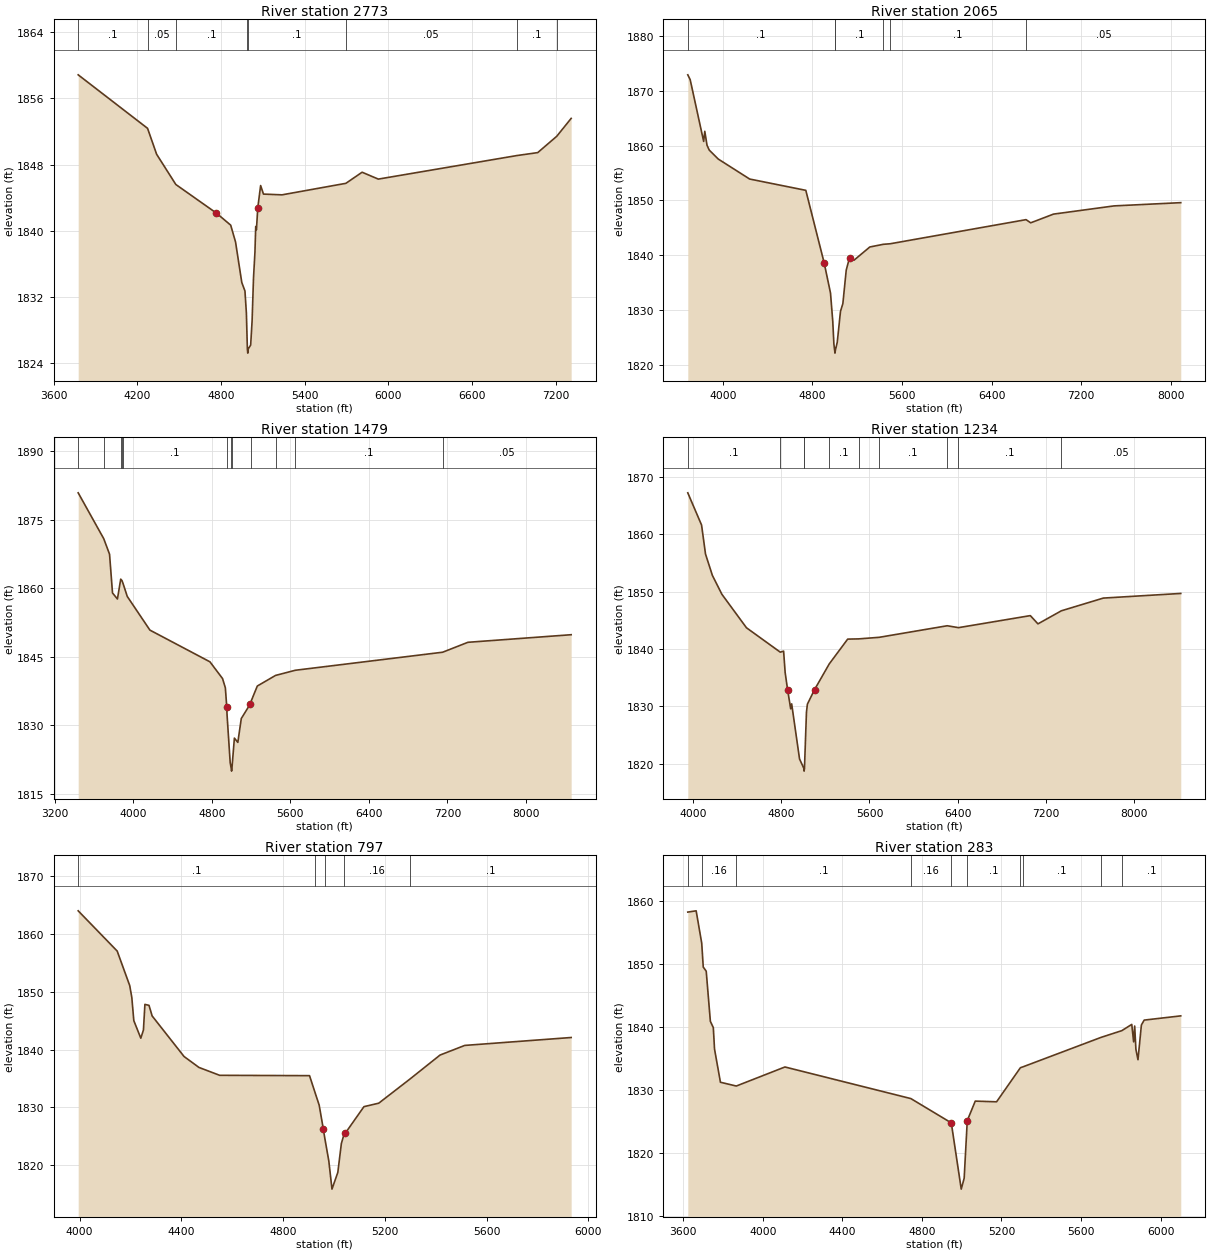
Type RM Length L Ch R = 1 ,2773    ,708,708,708
BEGIN DESCRIPTION:
FLAG CREEK 5.0
END DESCRIPTION:
XS GIS Cut Line= 3
      2670634.39     10058374.18      2670321.89     10056881.14
      2668377.48     10057388.08
#Sta/Elev= 30
  3775.5 1858.84  4272.9 1852.38  4337.9 1849.25  4475.7  1845.6    4767 1842.14
  4869.1 1840.69  4903.8 1838.66  4948.6 1833.77  4971.3 1832.74  4981.5 1830.09
  4988.7 1825.74  4991.5 1825.24  4994.7 1825.74  5012.2 1826.21  5022.4  1829.1
  5032.6 1834.31  5042.8 1837.39  5048.5 1840.53  5053.6 1840.14  5063.3  1842.8
  5083.7 1845.47  5104.1 1844.44  5236.9 1844.35    5695 1845.74  5811.3 1847.08
  5927.6 1846.25  6919.9 1849.09  7070.7 1849.45  7206.9 1851.42  7310.3 1853.58
#Mann= 8 ,-1 , 0
  3775.5      .1       0  4272.9     .05       0  4475.7      .1       0
  4988.7     .07       0  4994.7      .1       0    5695     .05       0
  6919.9      .1       0  7206.9     .05       0
Bank Sta=4767,5063.3
XS Rating Curve= 0 ,0
Exp/Cntr=0.3,0.1

Type RM Length L Ch R = 1 ,2065    ,586,586,586
BEGIN DESCRIPTION:
FLAG CREEK 4.0
END DESCRIPTION:
XS GIS Cut Line= 4
      2671134.39     10058645.02      2671016.34      10056874.2
      2670530.23     10056714.48      2668482.52     10057242.02
#Sta/Elev= 30
  3687.4 1872.92  3708.7 1872.04    3829 1860.77    3839 1862.61  3859.1 1860.06
  3879.1 1859.18  3959.3 1857.55  4239.9  1853.9    4741 1851.84  4905.2 1838.57
  4961.5 1833.09  4981.6 1827.94  4991.6 1823.81  4998.6 1822.63  5001.3 1822.13
  5004.6 1822.63  5021.6  1824.1  5050.5 1829.75  5071.8 1831.17  5101.8 1837.28
  5131.9 1839.58    5172  1839.1  5312.3  1841.5  5433.1 1841.99  5494.5 1842.09
  6707.2 1846.49  6748.7 1845.91  6952.2  1847.5  7493.6    1849  8088.4 1849.59
#Mann= 6 ,-1 , 0
  3687.4      .1       0  4998.6     .07       0  5004.6      .1       0
  5433.1     .05       0  5494.5      .1       0  6707.2     .05       0
Bank Sta=4905.2,5131.9
XS Rating Curve= 0 ,0
Exp/Cntr=0.3,0.1

Type RM Length L Ch R = 1 ,1479    ,245,245,245
BEGIN DESCRIPTION:
FLAG CREEK 3.0
END DESCRIPTION:
XS GIS Cut Line= 4
      2671780.22     10058582.49      2671676.06      10057186.7
      2670898.28     10056513.09      2668392.37     10057186.42
#Sta/Elev= 30
  3438.3 1880.87  3698.5 1870.84  3757.9 1867.43    3788 1858.95  3838.2 1857.63
  3871.6 1861.97  3884.9 1861.65  3895.7 1861.01  3938.4 1858.19  4169.1 1850.82
  4780.8 1843.88  4909.4 1840.21  4937.9 1838.19  4952.2 1834.03    4955 1832.37
  4987.3 1821.78  4998.5 1820.45  5001.3 1819.95  5004.5 1820.45    5030 1827.18
  5065.1 1826.24  5100.3 1831.46  5192.4 1834.67    5204 1835.44  5263.7 1838.58
  5449.5  1840.9  5651.1 1842.03  7152.6 1845.98  7409.6 1848.15  8461.7 1849.81
#Mann= 12 ,-1 , 0
  3438.3      .1       0  3698.5     .05       0  3871.6      .1       0
  3884.9     .05       0  3895.7      .1       0    4955     .16       0
  4998.5     .07       0  5004.5     .16       0    5204      .1       0
  5449.5     .05       0  5651.1      .1       0  7152.6     .05       0
Bank Sta=4952.2,5192.4
XS Rating Curve= 0 ,0
Exp/Cntr=0.3,0.1

Type RM Length L Ch R = 1 ,1234    ,437,437,437
BEGIN DESCRIPTION:
FLAG CREEK 2.0
END DESCRIPTION:
XS GIS Cut Line= 3
      2672551.35     10057493.74      2671023.28     10056422.81
      2668496.95      10057089.1
#Sta/Elev= 30
  3949.6 1867.26  4074.7 1861.64  4110.5 1856.58  4173.2 1852.84  4259.5 1849.55
  4482.7 1843.71    4790 1839.45  4820.1 1839.63    4834 1835.91  4856.8 1832.83
  4884.5 1829.56  4893.3 1830.43  4964.7 1820.82  5003.6 1819.19  5006.3 1818.69
  5009.6 1819.19  5027.7 1828.97  5036.2 1830.38    5101 1832.91  5234.7  1837.4
  5402.3 1841.73    5502 1841.77  5687.3 1842.04  6306.3 1844.06  6408.9 1843.73
  7061.6 1845.83  7130.8 1844.39  7343.4 1846.67  7724.8 1848.89  8428.3  1849.7
#Mann= 10 ,-1 , 0
  3949.6      .1       0    4790     .16       0  5003.6     .07       0
  5009.6     .16       0  5234.7      .1       0    5502     .05       0
  5687.3      .1       0  6306.3     .16       0  6408.9      .1       0
  7343.4     .05       0
Bank Sta=4856.8,5101
XS Rating Curve= 0 ,0
Exp/Cntr=0.3,0.1

Type RM Length L Ch R = 1 ,797     ,514,514,514
BEGIN DESCRIPTION:
Mapping XS a12dde4a
END DESCRIPTION:
XS GIS Cut Line= 3
      2672873.29     10057094.97      2671842.04       10056529.
      2671088.53     10056417.88
#Sta/Elev= 30
  3994.5 1864.04  4147.8 1857.07  4197.1 1851.09  4205.3 1849.04  4213.2 1845.01
  4240.7 1841.97    4251 1843.39  4256.8 1847.83  4272.9 1847.66  4285.2 1845.83
  4410.7  1838.8  4469.1 1836.91  4550.6 1835.54    4904 1835.48  4926.7 1832.41
  4941.9 1830.37    4958 1826.29  4963.7 1824.72  4979.8  1820.7  4992.2 1815.82
  5015.2 1818.72  5029.1 1823.71    5038 1825.08  5045.2 1825.55  5117.9 1830.11
  5176.1 1830.71  5298.1 1834.87  5417.1 1839.05  5514.2 1840.72  5932.5 1842.09
#Mann= 5 ,-1 , 0
  3994.5      .1       0  4926.7     .16       0  4963.7     .07       0
    5038     .16       0  5298.1      .1       0
Bank Sta=4958,5045.2
XS Rating Curve= 0 ,0
Exp/Cntr=0.3,0.1

Type RM Length L Ch R = 1 ,283     ,0,0,0
BEGIN DESCRIPTION:
FLAG CREEK 1.0
END DESCRIPTION:
XS GIS Cut Line= 4
      2673338.56     10056862.33      2672321.21     10056150.53
      2672019.13     10056126.22      2671121.63     10056382.65
#Sta/Elev= 30
  3623.4 1858.24  3665.4 1858.44  3693.4 1853.32  3701.1 1849.53    3716 1848.87
  3736.9 1840.92  3751.7 1839.93  3757.8 1836.52  3787.5 1831.27  3867.2 1830.67
  4111.7 1833.69  4744.8 1828.68    4948 1824.83    4998 1814.33  5012.7 1816.06
  5028.3 1825.19  5068.4 1828.28  5175.6 1828.17  5295.3 1833.57    5308 1833.71
  5701.5 1838.39  5805.3 1839.45  5855.2 1840.44  5864.6 1837.67  5869.8 1840.18
    5876 1836.49  5886.4 1834.84  5903.6 1840.35  5917.6 1841.12  6101.5 1841.79
#Mann= 10 ,-1 , 0
  3623.4      .1       0  3693.4     .16       0  3867.2      .1       0
  4744.8     .16       0    4948     .07       0  5028.3      .1       0
  5295.3     .16       0    5308      .1       0  5701.5     .16       0
  5805.3      .1       0
Bank Sta=4948,5028.3
XS Rating Curve= 0 ,0
Exp/Cntr=0.3,0.1

Chan Stop Cuts=-1
Use User Specified Reach Order=0
Composite Channel Slope=5