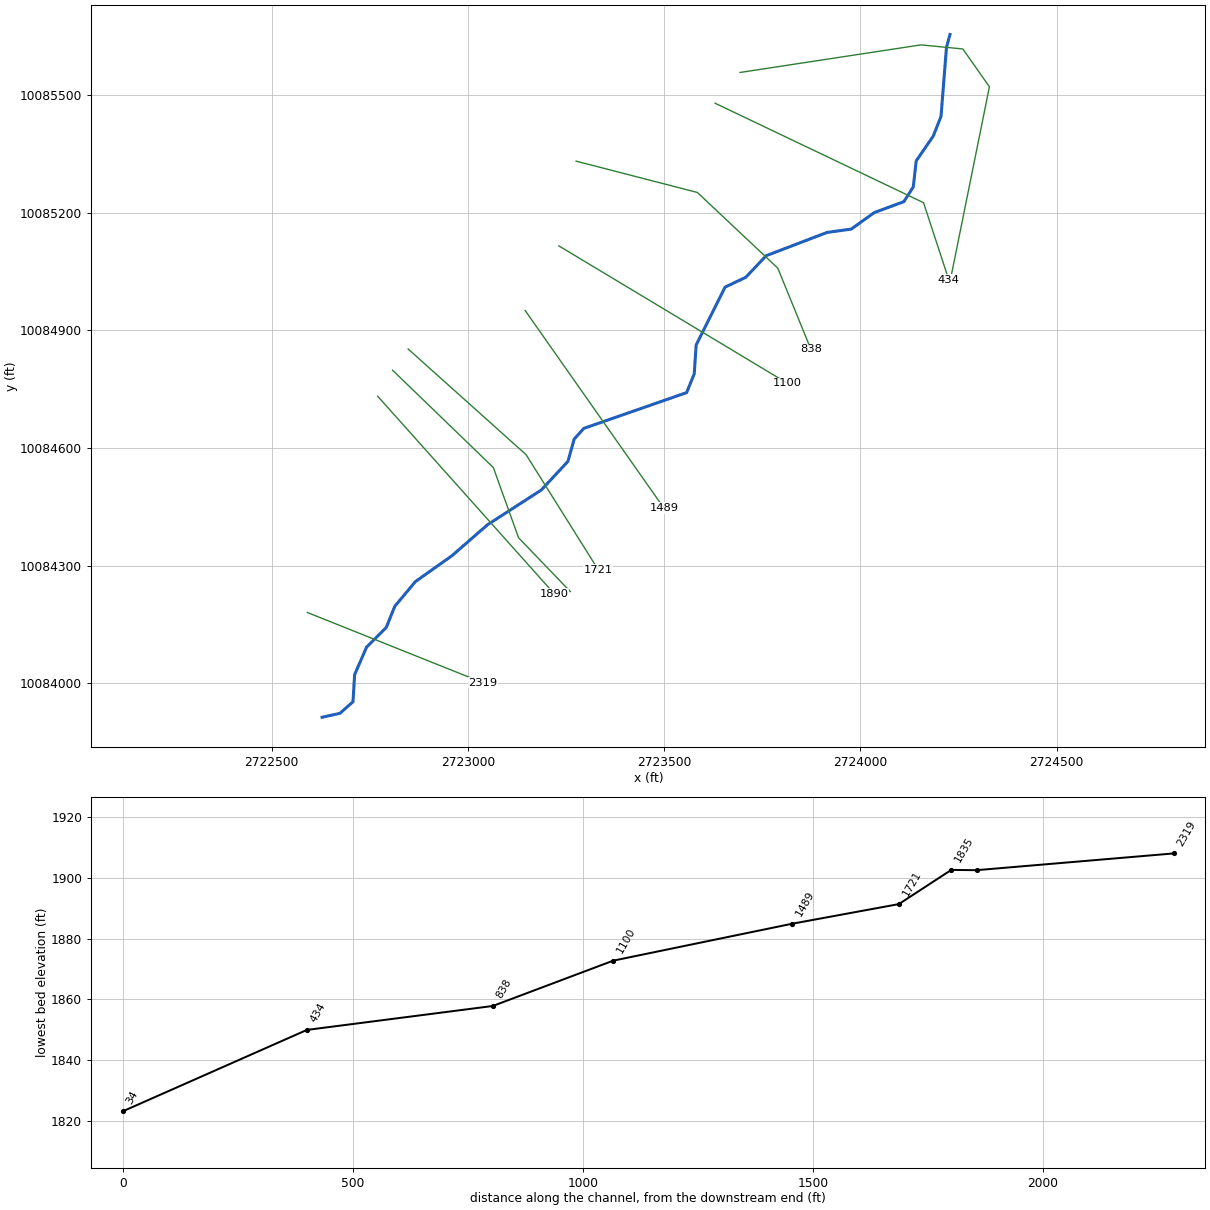
--- GARDEN CREEK.prj (project) ---

Proj Title=GARDEN CREEK Base Level Engineering
Current Plan=p01
Default Exp/Contr=0.3,0.1
English Units
Geom File=g01
Flow File=f01
Plan File=p01
BEGIN DESCRIPTION:
GARDEN CREEK
END DESCRIPTION:

--- GARDEN CREEK.p01 (plan) ---

Plan Title=Multiple Run
Short Identifier=Multiple
Geom File=g01
Flow File=f01
Subcritical Flow
K Sum by GR= 0
Std Step Tol= 0.01
Critical Tol= 0.01
Num of Std Step Trials= 20
Max Error Tol= 0.3
Flow Tol Ratio= 0.001
Split Flow NTrial= 30
Split Flow Tol= 0.02
Split Flow Ratio= 0.02
Log Output Level= 0
Friction Slope Method= 1
Unsteady Friction Slope Method= 2
Unsteady Bridges Friction Slope Method= 1
Parabolic Critical Depth
Global Vel Dist=  1 , 1 , 1
Global Log Level= 0
CheckData=True
Encroach Param= -1, 0, 0, 0
BEGIN DESCRIPTION:
Multiple Run
END DESCRIPTION:

--- GARDEN CREEK.f01 (steady flow) ---

Flow Title=Multiple
Number of Profiles=7
Profile Names=10-year,25-year,50-year,1pct_min,100-year,1pct_plu,500-year
River Rch & RM= GARDEN CREEK,Reach-1,2319
     466     656     817     747    1011    1367    1551
Boundary for River Rch & Prof#=GARDEN CREEK,Reach-1,1
Up Type=0
Dn Type=3
Dn Slope=0.005
Boundary for River Rch & Prof#=GARDEN CREEK,Reach-1,2
Up Type=0
Dn Type=3
Dn Slope=0.005
Boundary for River Rch & Prof#=GARDEN CREEK,Reach-1,3
Up Type=0
Dn Type=3
Dn Slope=0.005
Boundary for River Rch & Prof#=GARDEN CREEK,Reach-1,4
Up Type=0
Dn Type=3
Dn Slope=0.005
Boundary for River Rch & Prof#=GARDEN CREEK,Reach-1,5
Up Type=0
Dn Type=3
Dn Slope=0.005
Boundary for River Rch & Prof#=GARDEN CREEK,Reach-1,6
Up Type=0
Dn Type=3
Dn Slope=0.005
Boundary for River Rch & Prof#=GARDEN CREEK,Reach-1,7
Up Type=0
Dn Type=3
Dn Slope=0.005

--- GARDEN CREEK.g01 (geometry) ---

Geom Title=Existing Conditions

River Reach=GARDEN CREEK,Reach-1
Reach XY= 30
      2722628.52     10083913.79      2722673.85     10083923.77
      2722707.14     10083953.27      2722711.38     10084022.40
      2722741.79     10084092.43      2722792.01     10084142.64
      2722813.55     10084196.30      2722866.36     10084259.58
      2722958.95     10084325.06      2723050.18     10084404.47
      2723187.14     10084492.92      2723254.85     10084565.78
      2723270.89     10084622.63      2723295.31     10084649.83
      2723557.39     10084741.09      2723576.74     10084788.93
      2723581.64     10084862.41      2723655.41     10085009.89
      2723707.99     10085034.84      2723760.13     10085089.93
      2723915.58     10085149.33      2723976.84     10085157.67
      2724035.43     10085199.77      2724110.96     10085227.66
      2724134.92     10085265.04      2724142.40     10085331.48
      2724185.82     10085394.75      2724205.61     10085444.90
      2724219.55     10085620.85      2724228.47     10085653.73

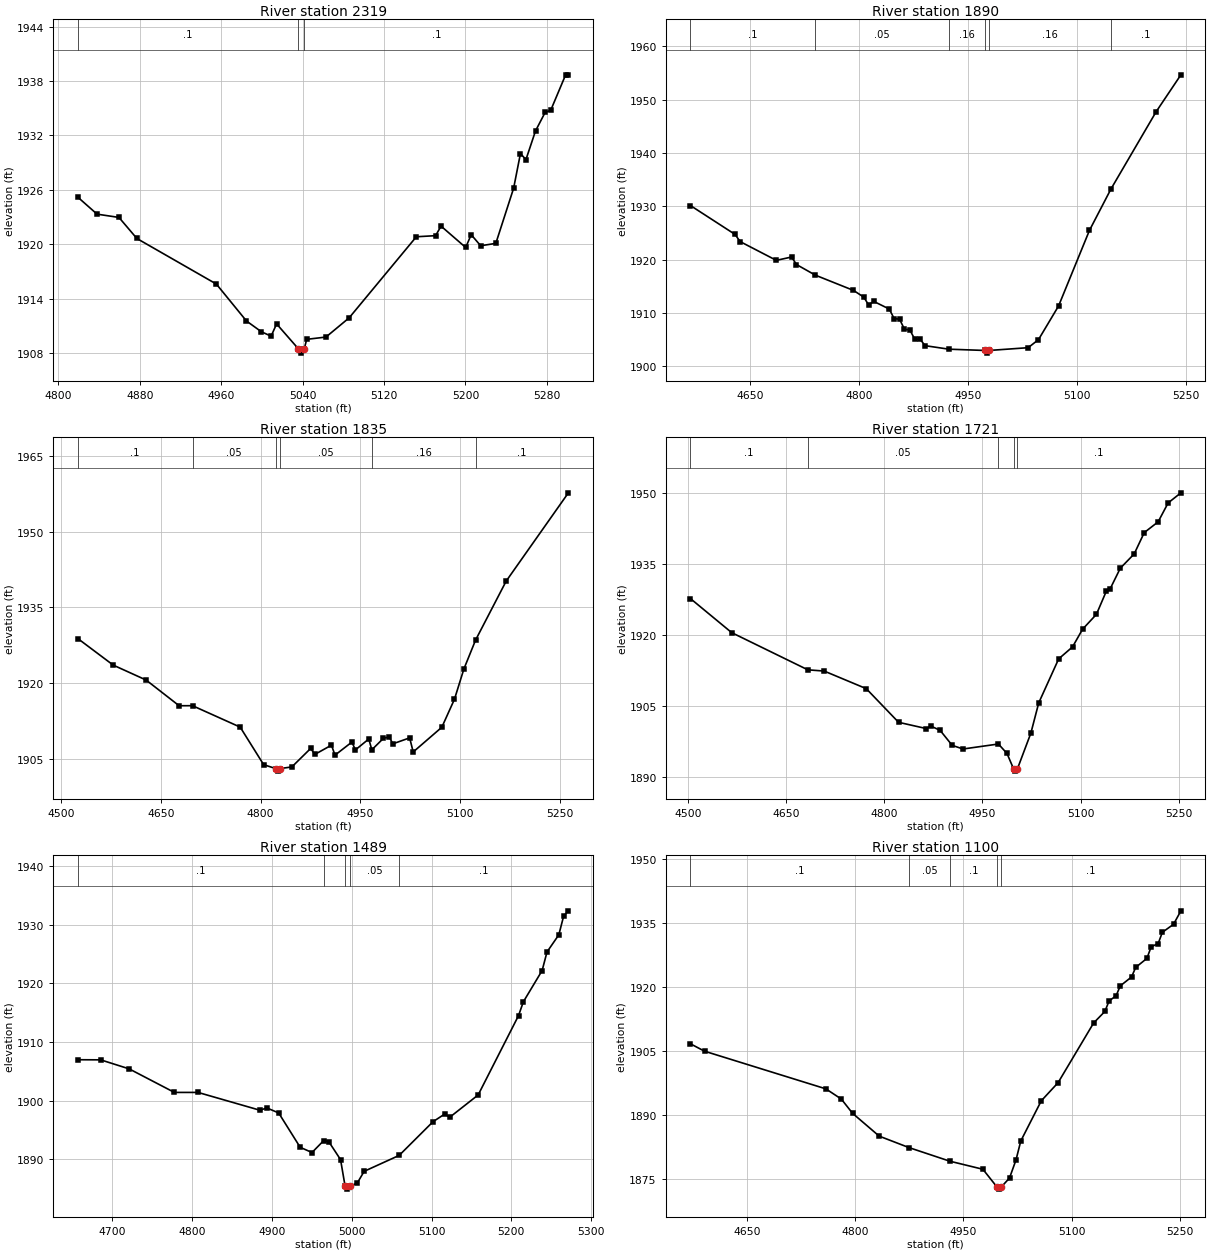
Type RM Length L Ch R = 1,2319,429,429,429
BEGIN DESCRIPTION:
GARDEN CREEK 5.0
END DESCRIPTION:
XS GIS Cut Line= 2
      2722591.02     10084180.74      2723038.46     10084001.77
#Sta/Elev= 30
  4819.3 1925.19  4838.1 1923.33  4859.6 1922.97  4877.2 1920.65  4955.3 1915.63
  4984.9 1911.56  4999.6 1910.37  5009.1 1909.89  5014.5 1911.24  5035.7 1908.52
  5038.5 1908.02  5041.7 1908.52  5044.1 1909.54  5063.0 1909.79  5085.8 1911.91
  5151.8 1920.84  5170.7 1920.96  5176.1 1922.01  5200.3 1919.66  5205.7 1921.07
  5215.0 1919.85  5229.9 1920.11  5247.4 1926.19  5254.1 1930.01  5259.5 1929.34
  5268.9 1932.50  5278.4 1934.55  5283.8 1934.76  5298.5 1938.68  5301.2 1938.68
#Mann=3,-1,0
  4819.3     0.1       0  5035.7    0.07       0  5041.7     0.1       0
Bank Sta=5035.7,5041.7
Exp/Cntr=0.3,0.1

Type RM Length L Ch R = 1,1890,55,55,55
BEGIN DESCRIPTION:
GARDEN CREEK 4.0
END DESCRIPTION:
XS GIS Cut Line= 2
      2722769.98     10084732.01      2723220.36     10084228.02
#Sta/Elev= 30
  4567.6 1930.15  4629.2 1924.73  4636.0 1923.40  4686.0 1919.88  4707.0 1920.51
  4713.7 1919.10  4739.7 1917.11  4792.3 1914.25  4806.5 1912.99  4813.2 1911.52
  4820.1 1912.20  4841.6 1910.76  4848.3 1908.97  4855.8 1908.86  4862.5 1906.98
  4870.0 1906.83  4876.7 1905.12  4884.2 1905.10  4890.9 1903.90  4923.7 1903.24
  4973.2 1903.00  4975.9 1902.50  4979.2 1903.00  5033.0 1903.52  5047.2 1905.02
  5074.9 1911.33  5117.5 1925.50  5147.0 1933.22  5209.4 1947.73  5243.5 1954.64
#Mann=6,-1,0
  4567.6     0.1       0  4739.7    0.05       0  4923.7    0.16       0
  4973.2    0.07       0  4979.2    0.16       0  5147.0     0.1       0
Bank Sta=4973.2,4979.2
Exp/Cntr=0.3,0.1

Type RM Length L Ch R = 1,1835,114,114,114
BEGIN DESCRIPTION:
Mapping XS 91ffce3f
END DESCRIPTION:
XS GIS Cut Line= 4
      2722807.94     10084798.25      2723064.86     10084550.01
      2723129.09     10084371.19      2723261.06     10084234.02
#Sta/Elev= 30
  4525.4 1928.81  4578.5 1923.57  4627.9 1920.62  4677.6 1915.53  4697.7 1915.54
  4769.4 1911.30  4804.7 1903.87  4823.0 1903.09  4825.8 1902.59  4829.0 1903.09
  4847.1 1903.42  4875.4 1907.08  4881.7 1905.90  4906.7 1907.73  4912.0 1905.75
  4937.4 1908.34  4942.7 1906.79  4962.8 1908.95  4967.4 1906.81  4984.9 1909.09
  4993.6 1909.38  4998.9 1907.99  5024.3 1909.17  5029.6 1906.38  5072.7 1911.28
  5091.7 1916.83  5105.8 1922.79  5123.4 1928.52  5169.4 1940.19  5263.0 1957.67
#Mann=6,-1,0
  4525.4     0.1       0  4697.7    0.05       0  4823.0    0.07       0
  4829.0    0.05       0  4967.4    0.16       0  5123.4     0.1       0
Bank Sta=4823,4829
Exp/Cntr=0.3,0.1

Type RM Length L Ch R = 1,1721,232,232,232
BEGIN DESCRIPTION:
Mapping XS a232e9dd
END DESCRIPTION:
XS GIS Cut Line= 3
      2722847.83     10084852.10      2723148.19     10084583.00
      2723332.21     10084289.61
#Sta/Elev= 30
  4503.7 1927.74  4566.8 1920.55  4683.1 1912.71  4708.1 1912.45  4772.4 1908.74
  4821.8 1901.64  4864.4 1900.31  4871.1 1900.85  4885.3 1899.94  4903.8 1896.77
  4920.4 1896.01  4974.4 1897.06  4987.5 1895.07  4997.5 1891.84  5000.3 1891.34
  5003.5 1891.84  5024.0 1899.36  5036.0 1905.73  5066.5 1915.02  5087.7 1917.55
  5103.0 1921.27  5124.2 1924.42  5139.5 1929.36  5145.4 1929.86  5160.7 1934.15
  5181.9 1937.16  5197.3 1941.66  5218.5 1943.93  5233.8 1947.92  5253.3 1950.05
#Mann=5,-1,0
  4503.7     0.1       0  4683.1    0.05       0  4974.4     0.1       0
  4997.5    0.07       0  5003.5     0.1       0
Bank Sta=4997.5,5003.5
Exp/Cntr=0.3,0.1

Type RM Length L Ch R = 1,1489,389,389,389
BEGIN DESCRIPTION:
GARDEN CREEK 3.0
END DESCRIPTION:
XS GIS Cut Line= 2
      2723145.86     10084950.33      2723499.15     10084447.17
#Sta/Elev= 30
  4656.7 1906.97  4685.2 1906.95  4720.9 1905.41  4777.6 1901.39  4807.2 1901.39
  4884.8 1898.35  4893.5 1898.74  4908.3 1897.89  4935.3 1892.02  4950.1 1891.13
  4964.8 1893.17  4971.1 1892.99  4985.9 1889.92  4991.6 1885.38  4994.3 1884.88
  4997.6 1885.38  5006.9 1885.93  5015.5 1887.92  5059.4 1890.64  5101.8 1896.39
  5116.6 1897.71  5122.7 1897.14  5158.4 1900.96  5209.0 1914.50  5215.1 1916.87
  5238.6 1922.20  5244.7 1925.37  5259.5 1928.29  5265.6 1931.51  5271.5 1932.39
#Mann=5,-1,0
  4656.7     0.1       0  4964.8    0.05       0  4991.6   0.035       0
  4997.6    0.05       0  5059.4     0.1       0
Bank Sta=4991.6,4997.6
Exp/Cntr=0.3,0.1

Type RM Length L Ch R = 1,1100,262,262,262
BEGIN DESCRIPTION:
GARDEN CREEK 2.0
END DESCRIPTION:
XS GIS Cut Line= 2
      2723231.79     10085115.00      2723814.32     10084764.78
#Sta/Elev= 30
  4571.7 1906.76  4591.2 1905.03  4759.4 1896.21  4780.8 1893.82  4796.4 1890.48
  4833.3 1885.14  4874.5 1882.46  4931.2 1879.27  4977.0 1877.38  4996.5 1873.23
  4999.3 1872.73  5002.5 1873.23  5013.9 1875.34  5022.9 1879.58  5029.5 1884.00
  5057.9 1893.41  5081.2 1897.66  5130.5 1911.65  5146.0 1914.33  5151.9 1916.80
  5161.6 1918.01  5167.4 1920.33  5183.0 1922.41  5188.8 1924.66  5204.3 1926.76
  5210.2 1929.48  5219.9 1930.23  5225.7 1932.87  5241.2 1934.75  5251.4 1937.90
#Mann=5,-1,0
  4571.7     0.1       0  4874.5    0.05       0  4931.2     0.1       0
  4996.5    0.07       0  5002.5     0.1       0
Bank Sta=4996.5,5002.5
Exp/Cntr=0.3,0.1

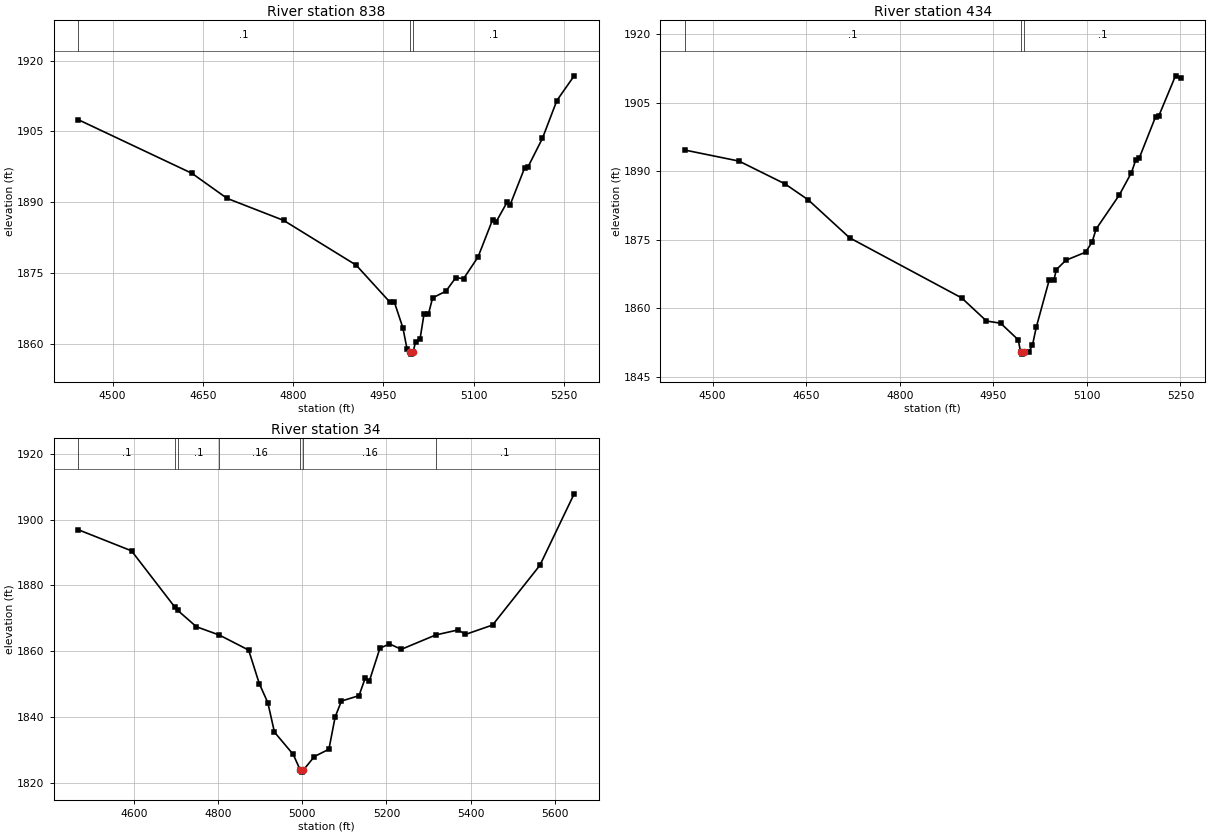
Type RM Length L Ch R = 1,838,404,404,404
BEGIN DESCRIPTION:
Mapping XS 936639aa
END DESCRIPTION:
XS GIS Cut Line= 4
      2723275.68     10085330.94      2723584.72     10085251.08
      2723789.58     10085058.37      2723874.05     10084851.49
#Sta/Elev= 30
  4443.1 1907.50  4631.9 1896.13  4690.2 1890.83  4784.2 1886.16  4904.7 1876.68
  4961.0 1868.81  4968.3 1868.80  4982.4 1863.39  4989.3 1858.91  4993.6 1858.31
  4996.3 1857.81  4999.6 1858.31  5003.5 1860.48  5010.8 1860.92  5017.6 1866.38
  5024.9 1866.33  5031.8 1869.74  5053.9 1871.15  5070.2 1874.01  5083.3 1873.81
  5107.3 1878.41  5131.4 1886.28  5136.8 1885.72  5155.4 1889.98  5160.8 1889.52
  5184.8 1897.31  5190.2 1897.47  5214.3 1903.55  5238.3 1911.57  5267.0 1916.80
#Mann=3,-1,0
  4443.1     0.1       0  4993.6    0.07       0  4999.6     0.1       0
Bank Sta=4993.6,4999.6
Exp/Cntr=0.3,0.1

Type RM Length L Ch R = 1,434,400,400,400
BEGIN DESCRIPTION:
Mapping XS 7d00a070
END DESCRIPTION:
XS GIS Cut Line= 3
      2723629.90     10085478.49      2724161.10     10085225.04
      2724225.34     10085028.86
#Sta/Elev= 30
  4455.4 1894.65  4542.3 1892.23  4615.9 1887.25  4653.3 1883.74  4719.7 1875.42
  4899.3 1862.26  4939.1 1857.20  4961.8 1856.71  4990.1 1853.07  4993.7 1850.44
  4996.5 1849.94  4999.7 1850.44  5007.2 1850.50  5012.8 1851.87  5018.9 1855.81
  5039.7 1866.18  5047.3 1866.18  5051.1 1868.45  5066.4 1870.50  5098.0 1872.27
  5108.5 1874.50  5114.8 1877.32  5151.9 1884.76  5171.6 1889.72  5178.5 1892.51
  5183.8 1892.80  5210.3 1901.96  5215.6 1902.19  5242.2 1910.91  5250.4 1910.36
#Mann=3,-1,0
  4455.4     0.1       0  4993.7    0.07       0  4999.7     0.1       0
Bank Sta=4993.7,4999.7
Exp/Cntr=0.3,0.1

Type RM Length L Ch R = 1,34,0,0,0
BEGIN DESCRIPTION:
GARDEN CREEK 1.0
END DESCRIPTION:
XS GIS Cut Line= 5
      2723693.59     10085556.86      2724154.50     10085627.17
      2724261.27     10085616.75      2724328.98     10085520.40
      2724232.62     10085043.82
#Sta/Elev= 30
  4468.4 1896.93  4594.7 1890.51  4697.4 1873.42  4704.5 1872.38  4748.8 1867.42
  4803.6 1864.87  4872.9 1860.31  4898.2 1850.08  4918.4 1844.32  4934.1 1835.36
  4978.8 1828.55  4995.9 1823.68  4998.7 1823.18  5001.9 1823.68  5029.1 1827.93
  5063.5 1830.15  5078.3 1839.98  5093.2 1844.80  5135.0 1846.45  5149.8 1851.85
  5159.7 1850.98  5184.6 1860.87  5207.3 1862.20  5235.4 1860.54  5317.5 1864.93
  5370.5 1866.45  5387.6 1865.07  5452.1 1867.94  5564.4 1886.08  5645.9 1907.86
#Mann=7,-1,0
  4468.4     0.1       0  4697.4    0.16       0  4704.5     0.1       0
  4803.6    0.16       0  4995.9    0.07       0  5001.9    0.16       0
  5317.5     0.1       0
Bank Sta=4995.9,5001.9
Exp/Cntr=0.3,0.1

Chan Stop Cuts=-1