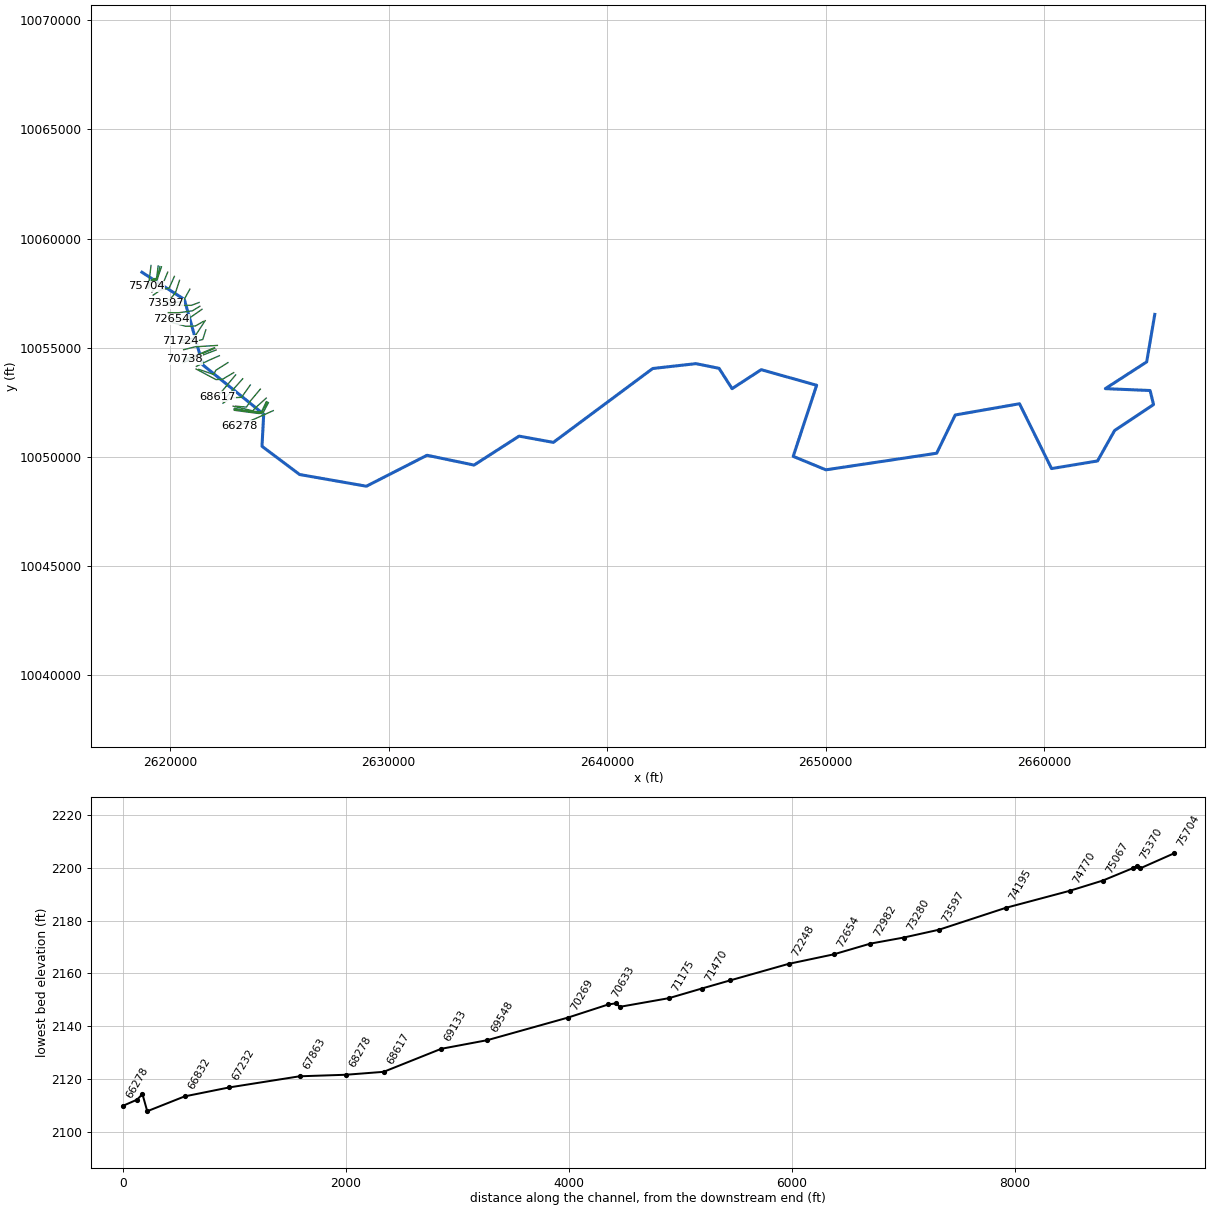
--- KLEIN BRANCH.prj (project) ---

Proj Title=KLEIN BRANCH Base Level Engineering
Current Plan=p01
Default Exp/Contr=0.3,0.1
English Units
Geom File=g01
Flow File=f01
Plan File=p01
Y Axis Title=Elevation
X Axis Title(PF)=Main Channel Distance
X Axis Title(XS)=Station
BEGIN DESCRIPTION:
KLEIN BRANCH
END DESCRIPTION:
DSS Export Rating Curves= 0
DSS Export Rating Curve Sorted= 0
DSS Export Volume Flow Curves= 0
DXF OffsetX= 0
DXF OffsetY= 0
DXF ScaleX= 1
DXF ScaleY= 10

--- KLEIN BRANCH.p01 (plan) ---

Plan Title=Multiple Run
Short Identifier=Multiple
Geom File=g01
Flow File=f01
Subcritical Flow
K Sum by GR= 0
Std Step Tol= 0.01
Critical Tol= 0.01
Num of Std Step Trials= 20
Max Error Tol= 0.3
Flow Tol Ratio= 0.001
Split Flow NTrial= 30
Split Flow Tol= 0.02
Split Flow Ratio= 0.02
Log Output Level= 0
Friction Slope Method= 1
Unsteady Friction Slope Method= 2
Unsteady Bridges Friction Slope Method= 1
Parabolic Critical Depth
Global Vel Dist=  1 , 1 , 1
Global Log Level= 0
CheckData=True
Encroach Param= -1, 0, 0, 0
BEGIN DESCRIPTION:
Multiple Run
END DESCRIPTION:

--- KLEIN BRANCH.f01 (steady flow) ---

Flow Title=Multiple
Program Version=4.10
Number of Profiles= 7
Profile Names=10-year,25-year,50-year,1pct_min,100-year,1pct_plu,500-year
River Rch & RM=KLEIN BRANCH,Reach-1         ,75704
     950    1368    1725    1586    2145    2900    3314
River Rch & RM=KLEIN BRANCH,Reach-1         ,68617
    2221    3320    4289    4026    5444    7363    8781
River Rch & RM=KLEIN BRANCH,Reach-1         ,61244
    3304    5030    6582    6248    8450   11427   13945
River Rch & RM=KLEIN BRANCH,Reach-1         ,59040
    3304    5030    6582    6248    8450   11427   13945
River Rch & RM=KLEIN BRANCH,Reach-1         ,56706
    4170    6408    8436    8053   10890   14728   18175
River Rch & RM=KLEIN BRANCH,Reach-1         ,55275
    4301    6603    8685    8282   11200   15147   18652
River Rch & RM=KLEIN BRANCH,Reach-1         ,49696
    5145    7940   10483   10027   13560   18339   22721
River Rch & RM=KLEIN BRANCH,Reach-1         ,45092
    5426    8387   11084   10612   14351   19408   24090
River Rch & RM=KLEIN BRANCH,Reach-1         ,42686
    5677    8783   11614   11124   15043   20344   25272
River Rch & RM=KLEIN BRANCH,Reach-1         ,40406
    5809    8985   11880   11375   15383   20804   25829
River Rch & RM=KLEIN BRANCH,Reach-1         ,35015
    5891    9108   12039   11524   15584   21076   26147
River Rch & RM=KLEIN BRANCH,Reach-1         ,29894
    8184   12782   17016   16392   22169   29981   37664
River Rch & RM=KLEIN BRANCH,Reach-1         ,26026
    8251   12872   17122   16480   22287   30141   37796
River Rch & RM=KLEIN BRANCH,Reach-1         ,19696
    8375   13059   17365   16707   22594   30555   38283
River Rch & RM=KLEIN BRANCH,Reach-1         ,13764
   10544   16538   22083   21327   28842   39006   49227
River Rch & RM=KLEIN BRANCH,Reach-1         ,12115
   10873   17026   22708   21901   29619   40056   50412
Boundary for River Rch & Prof#=KLEIN BRANCH,Reach-1         , 1
Up Type= 0
Dn Type= 3
Dn Slope=0.0075
Boundary for River Rch & Prof#=KLEIN BRANCH,Reach-1         , 2
Up Type= 0
Dn Type= 3
Dn Slope=0.0075
Boundary for River Rch & Prof#=KLEIN BRANCH,Reach-1         , 3
Up Type= 0
Dn Type= 3
Dn Slope=0.0075
Boundary for River Rch & Prof#=KLEIN BRANCH,Reach-1         , 4
Up Type= 0
Dn Type= 3
Dn Slope=0.0075
Boundary for River Rch & Prof#=KLEIN BRANCH,Reach-1         , 5
Up Type= 0
Dn Type= 3
Dn Slope=0.0075
Boundary for River Rch & Prof#=KLEIN BRANCH,Reach-1         , 6
Up Type= 0
Dn Type= 3
Dn Slope=0.0075
Boundary for River Rch & Prof#=KLEIN BRANCH,Reach-1         , 7
Up Type= 0
Dn Type= 3
Dn Slope=0.0075
DSS Import GetInterval= 0
DSS Import GetPeak= 0
DSS Import FillOption= 0

--- KLEIN BRANCH.g01 (geometry) ---

Geom Title=Existing Conditions
Program Version=4.10

River Reach=KLEIN BRANCH    ,Reach-1
Reach XY= 30
      2618703.47     10058458.73      2620645.76     10057212.45
      2621485.71     10054217.19      2624278.11     10051953.73
       2624199.5     10050484.88      2625921.78     10049191.29
      2628979.14     10048655.13      2631753.78     10050073.21
      2633907.54     10049623.79      2635969.83     10050950.44
      2637538.47     10050663.73      2642086.25     10054048.04
      2644066.04     10054270.85      2645125.06     10054056.09
      2645718.89     10053124.83      2647053.39     10053994.12
      2649591.52     10053280.01      2648518.47     10050023.73
      2650014.26     10049406.18      2655087.08     10050166.61
      2655935.59     10051918.73      2658878.47     10052433.73
      2660344.99     10049463.81      2662450.66     10049812.63
      2663231.61     10051207.32      2665014.37     10052395.43
      2664856.97     10053039.95      2662807.95     10053125.54
      2664700.98     10054350.96      2665071.08     10056527.12

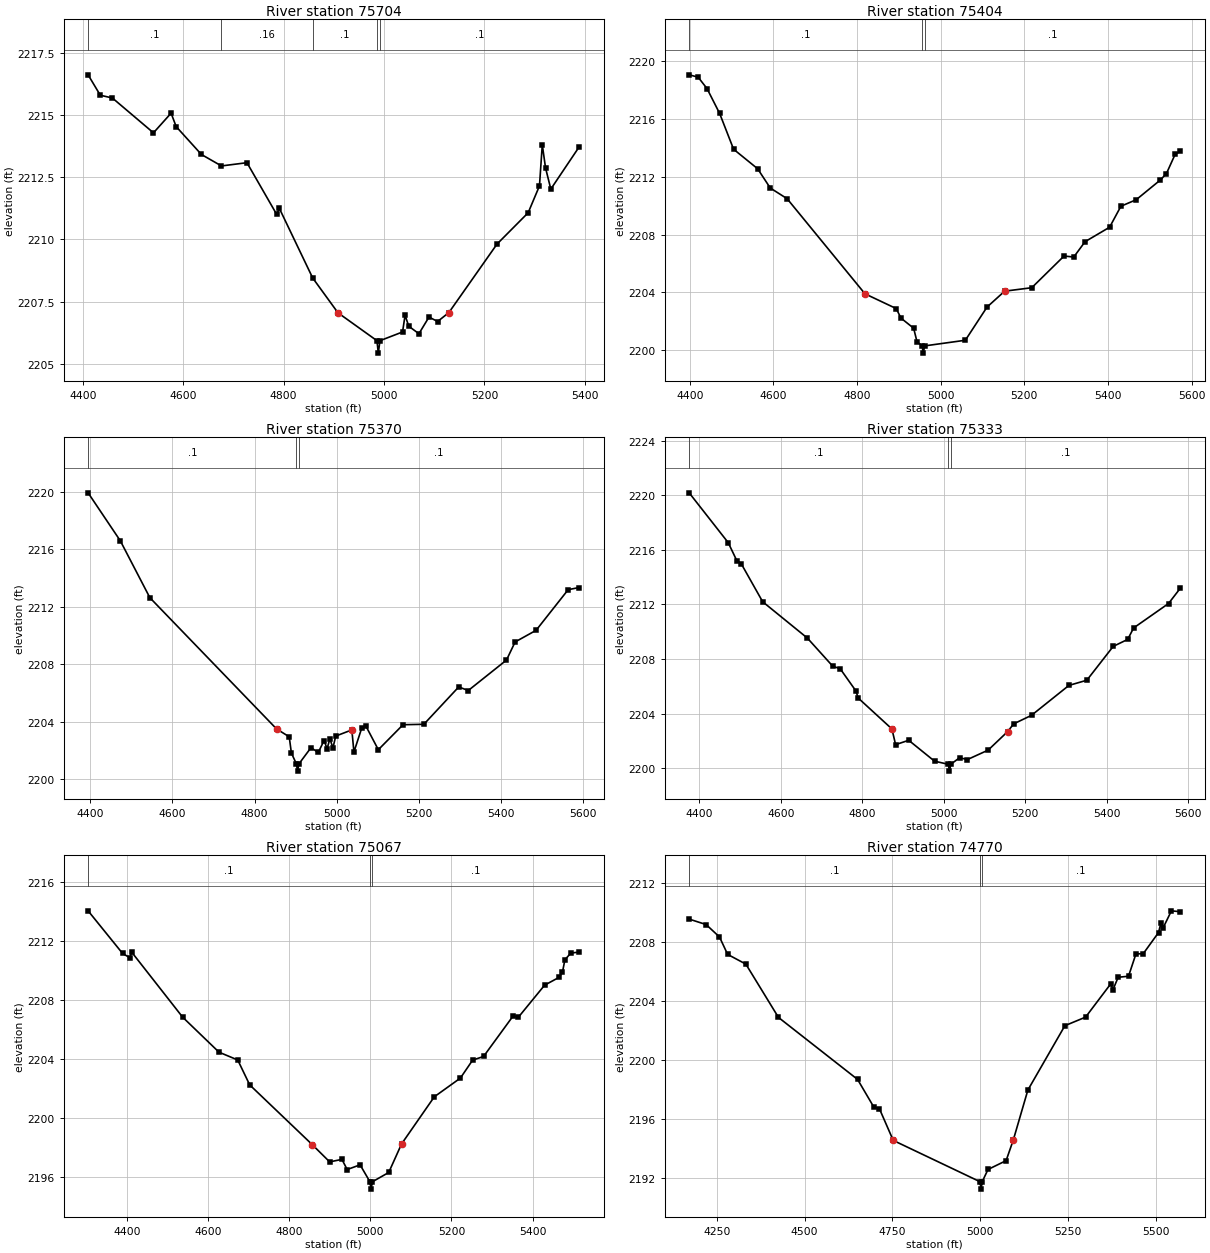
Type RM Length L Ch R = 1 ,75704   ,300,300,300
BEGIN DESCRIPTION:
KLEIN BRANCH 71.0
END DESCRIPTION:
XS GIS Cut Line= 3
      2619119.15     10058767.81      2619035.82     10058080.34
      2618910.84     10057823.43
#Sta/Elev= 30
  4410.5 2216.61  4434.8 2215.79  4458.8 2215.68  4540.7 2214.28  4575.8 2215.07
  4585.9 2214.53  4636.2 2213.41  4676.1 2212.95  4726.9 2213.08  4786.2    2211
  4791.3 2211.25  4857.8 2208.45  4908.2 2207.05  4985.8 2205.93  4988.5 2205.43
  4991.8 2205.93  5036.8 2206.28  5041.8 2206.95  5049.2 2206.51  5069.4 2206.21
  5089.5 2206.88  5106.6  2206.7  5129.1 2207.06  5224.9 2209.81    5287 2211.07
  5309.5 2212.15  5315.1  2213.8  5321.6 2212.87  5332.1 2212.02  5388.7 2213.72
#Mann= 5 ,-1 , 0
  4410.5      .1       0  4676.1     .16       0  4857.8      .1       0
  4985.8     .07       0  4991.8      .1       0
Bank Sta=4908.2,5129.1
XS Rating Curve= 0 ,0
Exp/Cntr=0.3,0.1

Type RM Length L Ch R = 1 ,75404   ,34,34,34
BEGIN DESCRIPTION:
Mapping XS 00f1f4cd
END DESCRIPTION:
XS GIS Cut Line= 6
      2619446.68     10058746.08      2619377.23     10058202.65
      2619335.57      10058166.2      2619262.65      10058166.2
      2619177.58     10058138.42      2618936.34     10057808.66
#Sta/Elev= 30
  4398.7 2219.04  4420.1 2218.88  4441.4 2218.09  4471.6 2216.37  4504.9  2213.9
  4562.4 2212.55  4592.6 2211.22  4632.9 2210.48    4819 2203.91  4893.7 2202.89
  4905.1 2202.23  4935.4 2201.53  4943.5 2200.59  4955.7 2200.31  4958.4 2199.81
  4961.7 2200.31    5059  2200.7  5110.8 2202.99  5152.9 2204.09  5217.8 2204.33
    5295 2206.52  5318.2 2206.45  5345.2 2207.51  5403.9 2208.51  5430.9 2209.96
  5467.5 2210.41  5525.1 2211.77  5539.8 2212.22  5560.6 2213.55  5572.9 2213.75
#Mann= 3 ,-1 , 0
  4398.7      .1       0  4955.7     .07       0  4961.7      .1       0
Bank Sta=4819,5152.9
XS Rating Curve= 0 ,0
Exp/Cntr=0.3,0.1

Type RM Length L Ch R = 1 ,75370   ,37,37,37
BEGIN DESCRIPTION:
Mapping XS 78adbf7e
END DESCRIPTION:
XS GIS Cut Line= 5
      2619526.55     10058720.05       2619399.8     10058180.08
      2619345.98     10058129.74      2619200.15     10058119.32
      2618965.78     10057770.36
#Sta/Elev= 30
    4395 2219.93  4473.4 2216.59  4545.3 2212.63  4853.4  2203.5  4884.3 2202.95
  4889.6 2201.82  4901.8 2201.06  4904.6 2200.56  4907.8 2201.06  4937.2 2202.19
    4955 2201.86  4969.1 2202.69  4976.5 2202.12  4983.3 2202.82  4990.6 2202.17
  4997.5    2203  5036.7 2203.43  5041.7 2201.89  5060.9 2203.57    5071 2203.69
  5101.1 2202.05  5161.2 2203.79  5211.9 2203.82  5296.7 2206.42  5319.9 2206.17
  5412.9 2208.29  5433.9 2209.55  5484.9 2210.36    5563 2213.19  5589.9 2213.34
#Mann= 3 ,-1 , 0
    4395      .1       0  4901.8     .07       0  4907.8      .1       0
Bank Sta=4853.4,5036.7
XS Rating Curve= 0 ,0
Exp/Cntr=0.3,0.1

Type RM Length L Ch R = 1 ,75333   ,266,266,266
BEGIN DESCRIPTION:
Mapping XS 7ff4656e
END DESCRIPTION:
XS GIS Cut Line= 6
      2619597.71     10058704.35      2619431.05     10058221.75
      2619415.43     10058140.15      2619366.82     10058101.96
      2619262.65     10058091.54      2618998.77     10057732.17
#Sta/Elev= 30
    4375 2220.18  4470.9 2216.53    4492 2215.21  4502.6    2215  4555.5  2212.2
  4665.2 2209.54  4727.5 2207.48  4745.9 2207.29  4784.6 2205.66  4789.9 2205.15
  4872.9 2202.88  4881.9 2201.73  4914.1 2202.05  4977.5 2200.52  5011.4 2200.29
  5014.1 2199.79  5017.4 2200.29  5038.9 2200.77  5058.4 2200.64  5109.2 2201.33
  5157.2 2202.69  5171.7 2203.25  5215.7 2203.88  5307.5 2206.07  5351.5 2206.45
  5416.3 2208.93  5451.8 2209.44  5466.4 2210.28  5552.1 2212.07    5581 2213.19
#Mann= 3 ,-1 , 0
    4375      .1       0  5011.4     .07       0  5017.4      .1       0
Bank Sta=4872.9,5157.2
XS Rating Curve= 0 ,0
Exp/Cntr=0.3,0.1

Type RM Length L Ch R = 1 ,75067   ,297,297,297
BEGIN DESCRIPTION:
Mapping XS e80cfea6
END DESCRIPTION:
XS GIS Cut Line= 4
      2619883.03     10058462.26       2619688.6     10057990.07
      2619334.43     10057788.68      2619160.85     10057552.61
#Sta/Elev= 30
  4304.1 2214.05    4389 2211.16  4406.6 2210.87    4412 2211.23  4537.2 2206.83
  4626.9 2204.45  4673.1 2203.92  4702.6 2202.23  4856.5 2198.18  4899.8    2197
    4930 2197.17    4943 2196.48  4974.8  2196.8  4999.1 2195.65  5001.9 2195.15
  5005.1 2195.65  5045.4 2196.28  5077.1 2198.22  5157.8 2201.42  5222.1 2202.69
  5252.3 2203.91  5279.3 2204.16  5352.4 2206.92    5365 2206.82  5429.8    2209
  5465.3 2209.53  5473.7 2209.87  5479.9 2210.73  5494.5 2211.18  5515.2 2211.25
#Mann= 3 ,-1 , 0
  4304.1      .1       0  4999.1     .07       0  5005.1      .1       0
Bank Sta=4856.5,5077.1
XS Rating Curve= 0 ,0
Exp/Cntr=0.3,0.1

Type RM Length L Ch R = 1 ,74770   ,575,575,575
BEGIN DESCRIPTION:
Mapping XS 93f9c158
END DESCRIPTION:
XS GIS Cut Line= 4
       2620188.6     10058267.83      2619952.49     10057740.07
      2619542.77      10057635.9       2619217.8     10057407.73
#Sta/Elev= 30
  4171.3 2209.55  4219.6 2209.18  4257.6 2208.34  4280.8 2207.16  4332.7  2206.5
  4425.5 2202.89  4650.7 2198.69  4697.1 2196.81  4712.6 2196.72  4752.2 2194.56
  4999.4 2191.76  5002.2 2191.26  5005.4 2191.76  5021.9 2192.59  5073.5 2193.19
  5094.1  2194.6  5135.4 2197.97  5240.8 2202.33  5299.7 2202.91  5371.5 2205.17
  5377.6 2204.76  5392.4 2205.61  5421.9 2205.68    5443 2207.19  5463.9 2207.21
  5507.4 2208.64  5514.4 2209.31  5520.5 2208.96    5544 2210.11  5569.3 2210.05
#Mann= 3 ,-1 , 0
  4171.3      .1       0  4999.4     .07       0  5005.4      .1       0
Bank Sta=4752.2,5094.1
XS Rating Curve= 0 ,0
Exp/Cntr=0.3,0.1

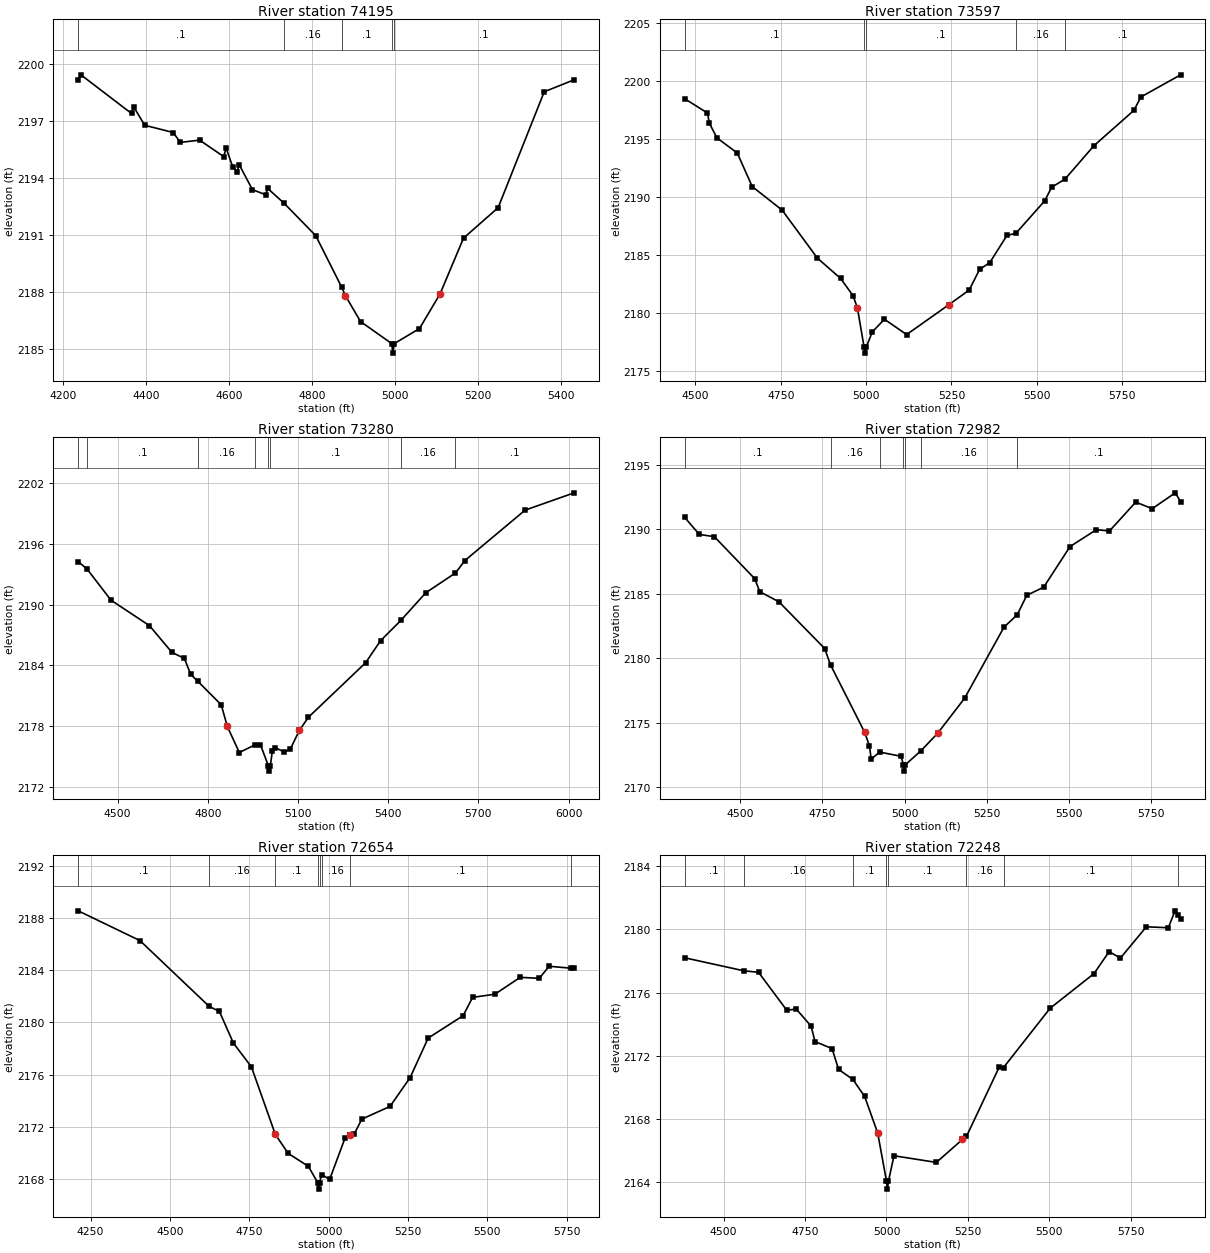
Type RM Length L Ch R = 1 ,74195   ,598,598,598
BEGIN DESCRIPTION:
Mapping XS be07284d
END DESCRIPTION:
XS GIS Cut Line= 4
      2620424.72     10058087.33      2620237.21     10057517.84
      2620014.99     10057247.01      2619793.15     10057143.02
#Sta/Elev= 30
  4236.6 2199.14  4243.1 2199.41    4365 2197.38  4370.3 2197.73  4396.8 2196.76
  4465.6 2196.38  4482.5 2195.86  4529.1 2195.98  4587.4 2195.11  4592.7 2195.58
  4608.9 2194.57  4619.2 2194.31  4624.5 2194.69  4656.3 2193.38    4688 2193.11
  4693.3 2193.44  4732.3 2192.67  4808.9 2190.96  4871.5 2188.25  4880.3 2187.81
  4916.8 2186.45    4992 2185.29  4994.7 2184.79    4998 2185.29  5058.8 2186.08
  5108.4  2187.9  5164.9 2190.83  5248.3 2192.43  5359.4 2198.52  5431.5 2199.15
#Mann= 5 ,-1 , 0
  4236.6      .1       0  4732.3     .16       0  4871.5      .1       0
    4992     .07       0    4998      .1       0
Bank Sta=4880.3,5108.4
XS Rating Curve= 0 ,0
Exp/Cntr=0.3,0.1

Type RM Length L Ch R = 1 ,73597   ,317,317,317
BEGIN DESCRIPTION:
Mapping XS 3fda3f26
END DESCRIPTION:
XS GIS Cut Line= 4
      2620896.92     10057684.49      2620681.66     10057288.68
      2620556.66     10057115.07      2619772.66     10057031.81
#Sta/Elev= 30
  4468.4 2198.44  4535.1 2197.21  4540.8 2196.33  4562.7 2195.07  4622.5 2193.76
  4666.2 2190.87  4753.8 2188.84  4857.2  2184.7  4925.1 2182.95  4961.5 2181.47
  4974.3 2180.42  4994.1 2177.01  4996.9 2176.51  5000.1 2177.01    5018 2178.34
  5053.6 2179.43  5118.6 2178.11  5241.7 2180.67    5302 2181.95  5332.2 2183.72
  5362.4 2184.32  5412.6 2186.66  5438.4 2186.83  5523.3 2189.64  5543.4 2190.81
  5582.5 2191.51  5667.7  2194.4  5784.7 2197.44  5804.8 2198.59  5921.3  2200.5
#Mann= 5 ,-1 , 0
  4468.4      .1       0  4994.1     .07       0  5000.1      .1       0
  5438.4     .16       0  5582.5      .1       0
Bank Sta=4974.3,5241.7
XS Rating Curve= 0 ,0
Exp/Cntr=0.3,0.1

Type RM Length L Ch R = 1 ,73280   ,298,298,298
BEGIN DESCRIPTION:
Mapping XS 389b042f
END DESCRIPTION:
XS GIS Cut Line= 4
      2621320.59     10057073.41      2620966.38     10056941.45
      2620362.21     10056941.45      2619695.57     10056976.18
#Sta/Elev= 30
    4369 2194.25  4398.3 2193.52    4478 2190.44    4606 2187.92  4680.7 2185.28
  4722.1 2184.68  4743.2 2183.11  4765.9 2182.45  4844.9 2180.09  4864.9 2177.96
  4904.9 2175.38  4958.5 2176.16  4974.9 2176.17  5001.9 2174.04  5004.7 2173.54
  5007.9 2174.04  5014.9 2175.52  5024.9 2175.86  5054.9 2175.42  5074.9 2175.74
  5104.9 2177.58  5134.9 2178.87  5324.9 2184.25  5374.9 2186.44    5442 2188.43
  5525.1 2191.17    5624 2193.13  5655.3 2194.36  5855.6 2199.34  6018.7 2201.05
#Mann= 8 ,-1 , 0
    4369     .16       0  4398.3      .1       0  4765.9     .16       0
  4958.5      .1       0  5001.9     .07       0  5007.9      .1       0
    5442     .16       0    5624      .1       0
Bank Sta=4864.9,5104.9
XS Rating Curve= 0 ,0
Exp/Cntr=0.3,0.1

Type RM Length L Ch R = 1 ,72982   ,328,328,328
BEGIN DESCRIPTION:
Mapping XS e30023d5
END DESCRIPTION:
XS GIS Cut Line= 4
       2621355.3     10056899.81      2621014.99     10056691.45
       2620376.1     10056601.18      2619912.12      10056608.1
#Sta/Elev= 30
  4331.2 2190.93  4375.9 2189.61  4421.3 2189.44  4544.2 2186.18  4559.6 2185.17
  4617.7 2184.39    4757 2180.76  4774.8 2179.49  4878.2 2174.28    4893 2173.23
  4898.4 2172.18  4924.1 2172.73  4989.3  2172.4  4996.4 2171.75  4999.2 2171.25
  5002.4 2171.75    5049 2172.81  5100.4 2174.18  5182.4  2176.9  5302.4 2182.42
  5342.5 2183.38  5371.7 2184.89  5423.1 2185.52  5503.1 2188.67  5583.1 2189.98
  5623.1 2189.88  5703.1 2192.12  5753.1 2191.61  5823.2 2192.84  5839.5 2192.15
#Mann= 7 ,-1 , 0
  4331.2      .1       0  4774.8     .16       0  4924.1      .1       0
  4996.4     .07       0  5002.4      .1       0    5049     .16       0
  5342.5      .1       0
Bank Sta=4878.2,5100.4
XS Rating Curve= 0 ,0
Exp/Cntr=0.3,0.1

Type RM Length L Ch R = 1 ,72654   ,406,406,406
BEGIN DESCRIPTION:
Mapping XS ccca7718
END DESCRIPTION:
XS GIS Cut Line= 4
      2621452.46     10056760.88       2620938.6     10056399.79
      2620633.04     10056274.79      2620028.86     10056302.57
#Sta/Elev= 30
    4211 2188.58  4405.7 2186.29  4623.9 2181.23  4655.9 2180.85  4700.2 2178.41
  4756.8 2176.59  4832.2  2171.4  4872.6 2169.94  4936.4 2168.94  4965.7 2167.69
  4968.4 2167.19  4971.7 2167.69    4978 2168.31  5003.5 2167.94  5051.5 2171.09
  5066.1 2171.36  5066.9 2171.38  5080.9 2171.43  5104.9 2172.57  5193.8 2173.55
    5257 2175.76  5313.9  2178.8    5424 2180.52  5454.1 2181.93  5524.1 2182.17
  5604.2 2183.47  5664.3 2183.39  5694.9 2184.32  5763.6 2184.17    5774 2184.15
#Mann= 8 ,-1 , 0
    4211      .1       0  4623.9     .16       0  4832.2      .1       0
  4965.7     .07       0  4971.7      .1       0    4978     .16       0
  5066.9      .1       0  5763.6     .16       0
Bank Sta=4832.2,5066.1
XS Rating Curve= 0 ,0
Exp/Cntr=0.3,0.1

Type RM Length L Ch R = 1 ,72248   ,524,524,524
BEGIN DESCRIPTION:
Mapping XS 4f5e578a
END DESCRIPTION:
XS GIS Cut Line= 4
      2621514.95     10056205.32      2621153.88     10055997.01
      2620709.43     10055983.12      2620071.97     10056156.35
#Sta/Elev= 30
  4380.7  2178.2  4561.6 2177.38  4607.5 2177.28  4694.1 2174.88    4723 2174.96
  4768.7 2173.88  4780.7  2172.9    4833 2172.46    4853 2171.14  4896.9 2170.51
    4933 2169.43  4973.1 2167.12  5000.1 2164.07  5002.8 2163.57  5006.1 2164.07
  5023.1 2165.68  5153.1 2165.26  5233.2 2166.71  5245.5  2166.9  5346.8 2171.32
  5359.3 2171.26  5502.3 2175.01    5637  2177.2  5683.4 2178.59    5718 2178.18
  5797.6 2180.16    5865  2180.1  5885.7 2181.17  5895.1 2180.92  5902.8 2180.66
#Mann= 8 ,-1 , 0
  4380.7      .1       0  4561.6     .16       0  4896.9      .1       0
  5000.1     .07       0  5006.1      .1       0  5245.5     .16       0
  5359.3      .1       0  5895.1     .16       0
Bank Sta=4973.1,5233.2
XS Rating Curve= 0 ,0
Exp/Cntr=0.3,0.1

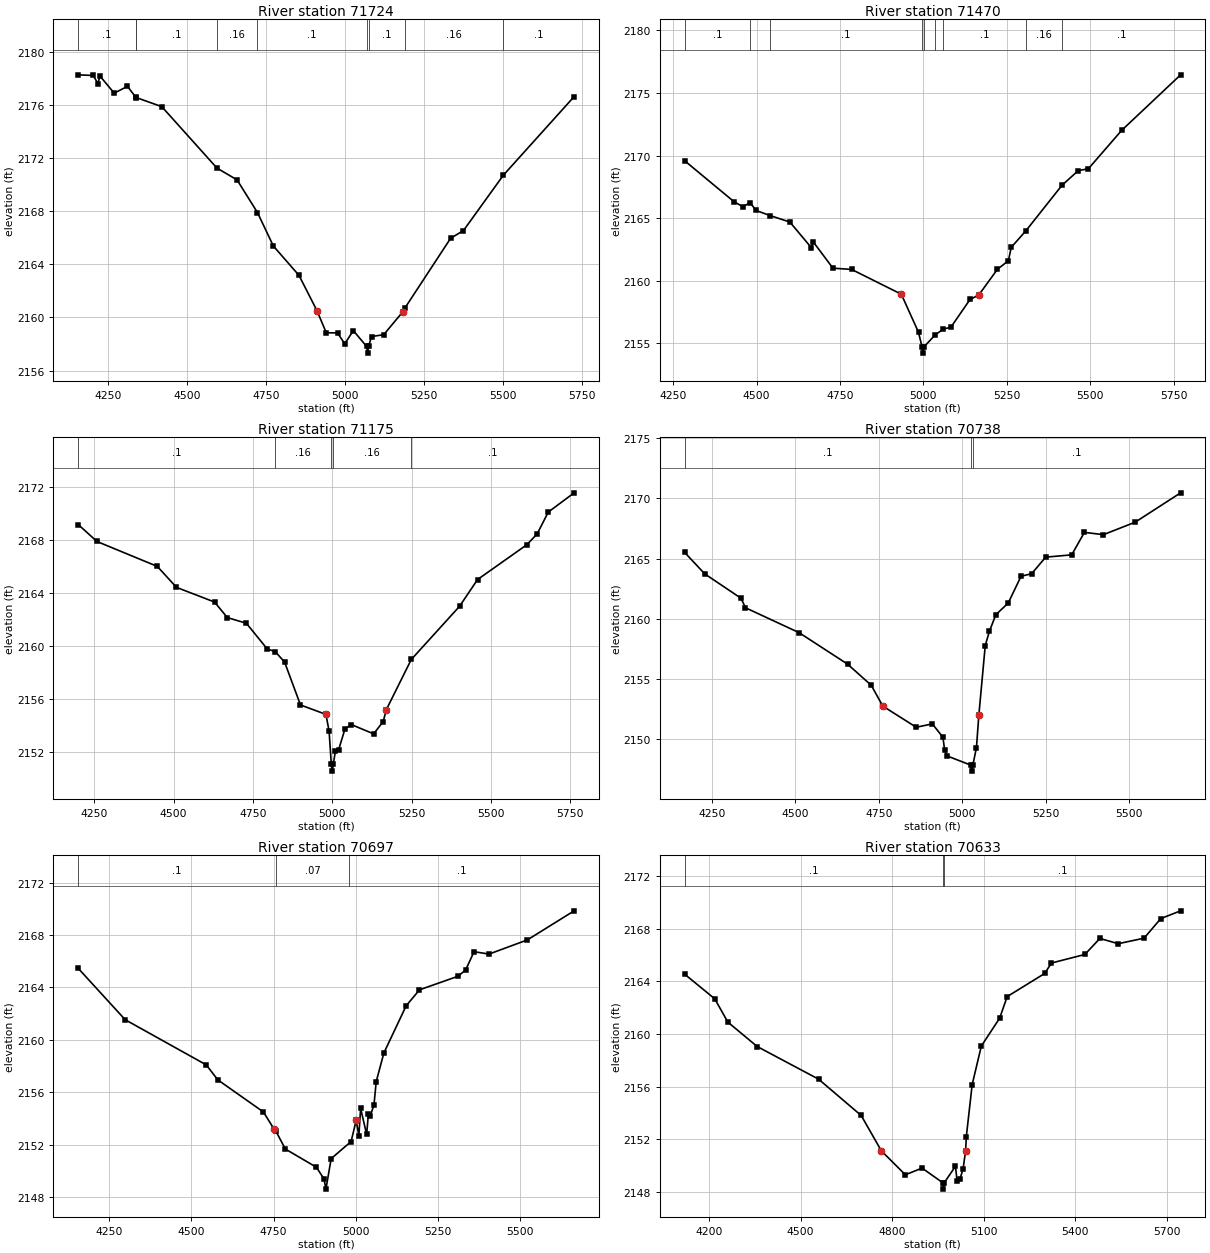
Type RM Length L Ch R = 1 ,71724   ,254,254,254
BEGIN DESCRIPTION:
Mapping XS e9a304ee
END DESCRIPTION:
XS GIS Cut Line= 3
      2621598.33     10056240.08      2621070.54     10055434.51
      2620473.43     10055330.36
#Sta/Elev= 30
  4155.5 2178.29  4202.9 2178.24    4218 2177.63    4224 2178.21  4269.3 2176.91
  4311.4 2177.42  4336.9 2176.62  4338.7 2176.58    4420 2175.89  4594.5 2171.26
  4658.1 2170.37  4722.7 2167.91  4772.8 2165.39  4854.1 2163.17  4911.4 2160.49
  4940.2 2158.85    4976 2158.83  4998.9 2158.01  5025.9 2159.01  5068.2 2157.81
    5071 2157.31  5074.2 2157.81  5083.6 2158.56  5122.2  2158.7  5181.6  2160.4
  5189.5 2160.72  5333.9 2165.97  5374.5 2166.55  5500.6 2170.72  5724.7 2176.65
#Mann= 9 ,-1 , 0
  4155.5      .1       0  4336.9     .16       0  4338.7      .1       0
  4594.5     .16       0  4722.7      .1       0  5068.2     .07       0
  5074.2      .1       0  5189.5     .16       0  5500.6      .1       0
Bank Sta=4911.4,5181.6
XS Rating Curve= 0 ,0
Exp/Cntr=0.3,0.1

Type RM Length L Ch R = 1 ,71470   ,295,295,295
BEGIN DESCRIPTION:
Mapping XS 11547c84
END DESCRIPTION:
XS GIS Cut Line= 4
       2621628.7     10055819.91      2621488.08     10055377.22
      2620951.62     10055247.01      2620481.91     10055239.22
#Sta/Elev= 30
  4284.6 2169.58  4432.7 2166.31    4459 2165.92  4481.3 2166.24  4497.9 2165.62
  4540.3 2165.21  4599.9 2164.69  4664.4 2162.64  4669.6 2163.12  4728.9 2161.01
  4784.9 2160.91  4933.9 2158.93  4985.4 2155.89  4995.9 2154.73  4998.7 2154.23
  5001.9 2154.73  5035.3 2155.69  5060.1 2156.15  5082.5  2156.3  5139.7 2158.51
    5166 2158.87  5222.1 2160.93  5254.7  2161.6  5263.2 2162.67  5307.7 2164.01
  5415.2 2167.62  5464.3  2168.8  5494.3 2168.94  5594.3 2172.01  5770.9 2176.44
#Mann= 9 ,-1 , 0
  4284.6      .1       0  4481.3     .16       0  4540.3      .1       0
  4995.9     .07       0  5001.9      .1       0  5035.3     .16       0
  5060.1      .1       0  5307.7     .16       0  5415.2      .1       0
Bank Sta=4933.9,5166
XS Rating Curve= 0 ,0
Exp/Cntr=0.3,0.1

Type RM Length L Ch R = 1 ,71175   ,437,437,437
BEGIN DESCRIPTION:
Mapping XS f9bac7c0
END DESCRIPTION:
XS GIS Cut Line= 3
      2622157.31     10055106.38       2621128.7     10055041.28
      2620613.78     10054908.65
#Sta/Elev= 30
  4199.6 2169.18  4258.6  2167.9  4448.9 2166.02  4509.1 2164.44  4629.3 2163.33
  4669.4 2162.16  4729.5 2161.73  4795.2 2159.79  4819.9  2159.6  4849.7 2158.81
  4899.8 2155.57    4980 2154.86    4990 2153.59    4997 2151.08  4999.8 2150.58
    5003 2151.08  5010.1 2152.11  5020.1  2152.2  5040.1 2153.77  5060.2 2154.09
  5130.3 2153.39  5160.4 2154.32  5170.4 2155.22  5248.9    2159  5400.9 2163.01
  5457.7 2165.03  5612.6 2167.65  5645.1 2168.46  5680.6 2170.12    5762 2171.57
#Mann= 5 ,-1 , 0
  4199.6      .1       0  4819.9     .16       0    4997     .07       0
    5003     .16       0  5248.9      .1       0
Bank Sta=4980,5170.4
XS Rating Curve= 0 ,0
Exp/Cntr=0.3,0.1

Type RM Length L Ch R = 1 ,70738   ,41,41,41
BEGIN DESCRIPTION:
Mapping XS d4de3ccf
END DESCRIPTION:
XS GIS Cut Line= 3
      2622013.72     10054998.78      2621338.82     10054712.33
      2620624.86     10054475.79
#Sta/Elev= 30
  4168.7 2165.51  4228.7 2163.73  4337.4  2161.7  4350.8 2160.91  4511.2 2158.84
  4656.5 2156.22  4727.5 2154.46    4762 2152.73  4862.1 2150.97  4910.4 2151.25
  4942.1 2150.14  4947.4 2149.04  4954.9 2148.58  5025.7 2147.82  5028.4 2147.32
  5031.7 2147.82  5042.5 2149.27  5049.7 2151.98  5068.9 2157.77  5081.3 2158.95
  5100.6 2160.33  5137.6  2161.3  5176.1 2163.53  5207.8 2163.74  5249.9 2165.12
  5327.8 2165.31  5365.8 2167.18  5422.9 2166.99    5518 2168.03    5654 2170.47
#Mann= 3 ,-1 , 0
  4168.7      .1       0  5025.7     .07       0  5031.7      .1       0
Bank Sta=4762,5049.7
XS Rating Curve= 0 ,0
Exp/Cntr=0.3,0.1

Type RM Length L Ch R = 1 ,70697   ,64,64,64
BEGIN DESCRIPTION:
Mapping XS 93974af5
END DESCRIPTION:
XS GIS Cut Line= 3
      2622037.52     10054973.56      2621178.18     10054608.99
       2620633.9     10054418.88
#Sta/Elev= 30
  4155.3 2165.45  4298.3 2161.53  4545.3 2158.08  4580.3 2156.94  4719.1 2154.49
  4751.4 2153.19  4756.9 2153.04    4786 2151.66  4880.6 2150.27  4903.8 2149.37
  4909.5  2148.6  4925.5 2150.93  4986.1 2152.23  5001.6 2153.84  5009.8 2152.68
  5015.2 2154.76  5033.5 2152.77  5038.9 2154.37    5045 2154.21  5055.9 2155.05
  5062.6  2156.8  5085.9 2158.99  5153.8 2162.59  5194.4 2163.81  5310.9 2164.84
  5334.8 2165.32  5360.5 2166.72  5406.2 2166.54  5522.8 2167.62  5665.3 2169.84
#Mann= 3 ,-1 , 0
  4155.3      .1       0  4756.9     .07       0  4979.8      .1       0
Bank Sta=4751.4,5001.6
XS Rating Curve= 0 ,0
Exp/Cntr=0.3,0.1

Type RM Length L Ch R = 1 ,70633   ,364,364,364
BEGIN DESCRIPTION:
Mapping XS f55b400f
END DESCRIPTION:
XS GIS Cut Line= 2
      2622100.51     10054896.78      2620582.47     10054315.59
#Sta/Elev= 30
  4120.3 2164.55  4218.9 2162.68  4261.7 2160.91  4358.1 2159.05  4559.2 2156.57
  4698.8 2153.81    4765 2151.12  4843.6  2149.3  4898.4 2149.81  4965.4 2148.71
  4968.2 2148.21  4971.4 2148.71  5007.9 2149.95  5013.2 2148.81  5021.9 2148.95
  5032.6 2149.71 5041.14 2151.13  5043.4  2152.2  5062.6 2156.16  5092.6 2159.09
  5152.7 2161.21  5177.4 2162.85  5300.4 2164.61  5322.3  2165.4  5431.8 2166.05
  5481.2 2167.27  5541.3 2166.87    5626 2167.29  5680.8 2168.78  5745.8 2169.37
#Mann= 3 ,-1 , 0
  4120.3      .1       0  4965.4     .07       0  4971.4      .1       0
Bank Sta=4765,5041.14
XS Rating Curve= 0 ,0
Exp/Cntr=0.3,0.1

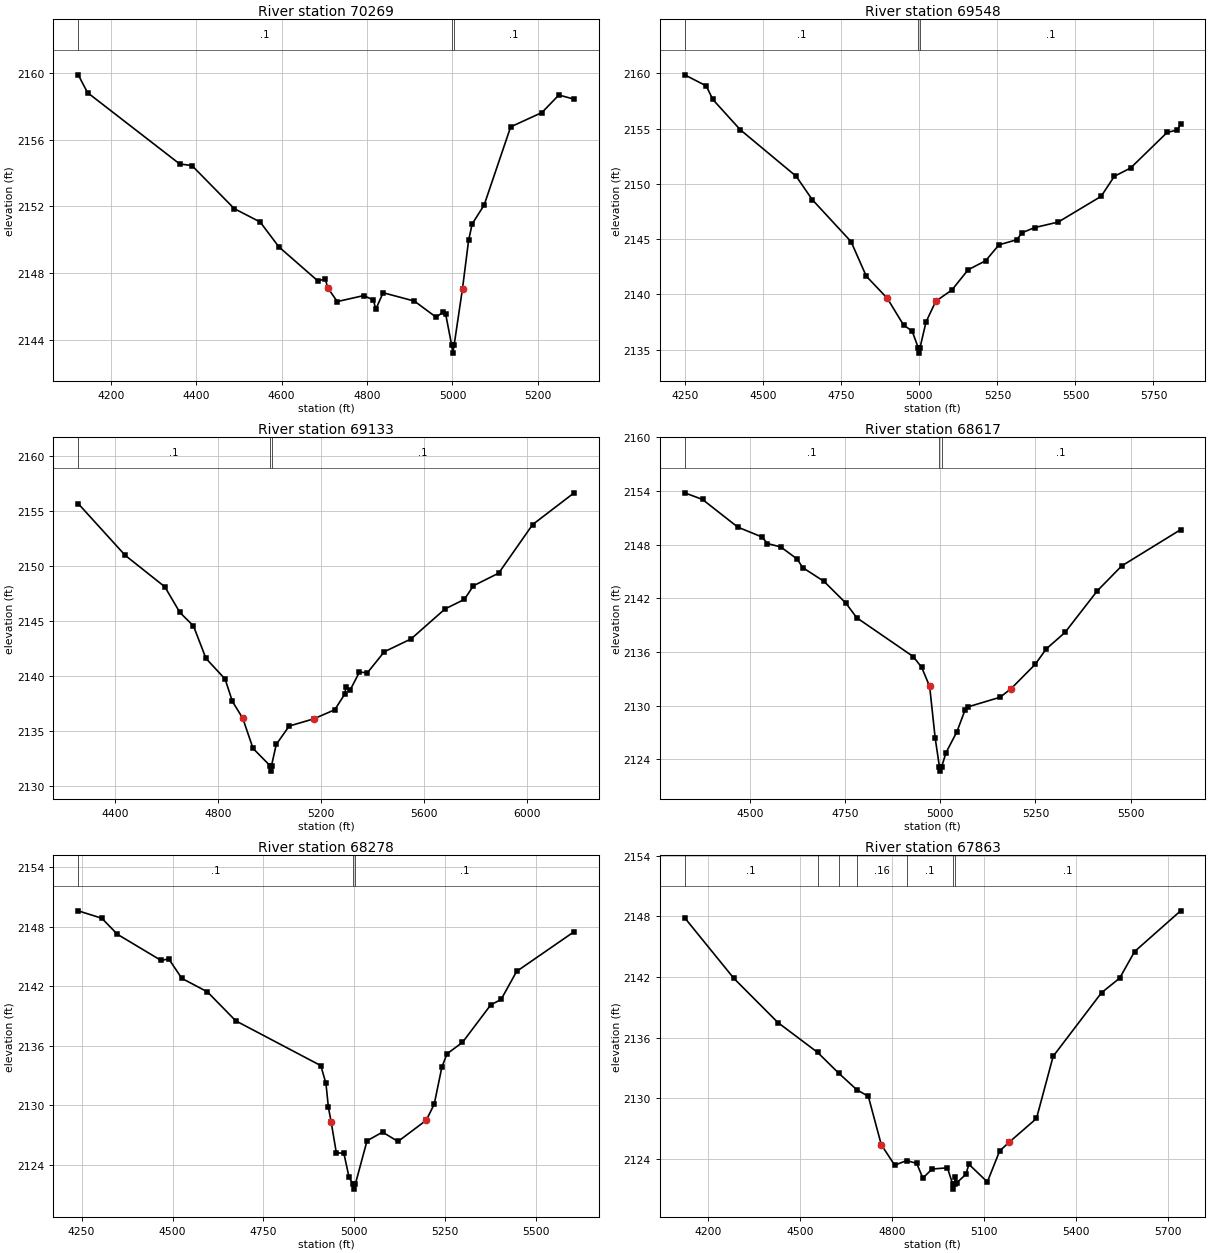
Type RM Length L Ch R = 1 ,70269   ,721,721,721
BEGIN DESCRIPTION:
Mapping XS 48adbbc2
END DESCRIPTION:
XS GIS Cut Line= 3
      2622248.51     10054635.04      2621784.95     10054431.91
      2621196.38     10054145.43
#Sta/Elev= 30
  4124.1 2159.89    4146 2158.82  4361.5 2154.55  4390.3 2154.45  4489.3 2151.87
  4549.9 2151.07  4593.7 2149.58  4685.3 2147.53  4702.3 2147.67  4707.9 2147.13
  4730.4  2146.3  4792.5 2146.66    4815 2146.39  4820.6 2145.84  4837.6 2146.83
  4910.8 2146.33  4961.4 2145.37  4978.4 2145.66    4984 2145.56    4998 2143.71
  5000.7 2143.21    5004 2143.71  5023.5 2147.08  5037.8 2149.97  5046.1 2150.95
  5074.2 2152.09  5136.2 2156.77  5209.4 2157.63    5249 2158.68  5284.8 2158.43
#Mann= 3 ,-1 , 0
  4124.1      .1       0    4998     .07       0    5004      .1       0
Bank Sta=4707.9,5023.5
XS Rating Curve= 0 ,0
Exp/Cntr=0.3,0.1

Type RM Length L Ch R = 1 ,69548   ,415,415,415
BEGIN DESCRIPTION:
Mapping XS 9a442932
END DESCRIPTION:
XS GIS Cut Line= 4
      2622639.13     10054317.33      2622087.04     10053968.36
      2621988.08     10053775.66      2621307.66     10054009.39
#Sta/Elev= 30
  4247.8 2159.86  4316.8 2158.86    4338 2157.63    4426 2154.89  4605.1 2150.68
  4656.8 2148.56  4780.9 2144.77  4829.8 2141.64  4896.8 2139.65    4949 2137.23
  4976.8 2136.67    4996 2135.18  4998.7 2134.68    5002 2135.18  5021.2  2137.5
  5052.3 2139.37  5104.3  2140.4    5156 2142.22  5212.3 2143.04    5255 2144.48
  5312.2 2144.94  5328.6 2145.57  5369.5 2146.04  5444.9 2146.54  5582.4 2148.87
  5624.7 2150.68  5676.7 2151.43  5793.9 2154.65  5825.6 2154.86    5837 2155.37
#Mann= 3 ,-1 , 0
  4247.8      .1       0    4996     .07       0    5002      .1       0
Bank Sta=4896.8,5052.3
XS Rating Curve= 0 ,0
Exp/Cntr=0.3,0.1

Type RM Length L Ch R = 1 ,69133   ,516,516,516
BEGIN DESCRIPTION:
Mapping XS 8c6280ef
END DESCRIPTION:
XS GIS Cut Line= 4
      2622904.74     10053858.99      2622394.33     10053556.91
      2622092.25     10053541.28      2621182.16     10054024.92
#Sta/Elev= 30
  4256.9 2155.67  4439.2 2150.98  4593.3 2148.12  4651.8 2145.79  4704.5 2144.57
  4753.1 2141.62  4827.3 2139.75  4855.9 2137.71  4895.9 2136.19    4936 2133.45
  5001.7 2131.89  5004.4 2131.39  5007.7 2131.89  5026.1 2133.81  5076.2 2135.48
  5171.1 2136.13  5253.3 2136.96  5291.6 2138.36  5297.3 2139.03  5313.6 2138.77
  5349.3 2140.39  5379.5  2140.3  5445.5 2142.22  5549.7 2143.39  5681.6 2146.11
    5757 2146.98  5791.5 2148.21    5890 2149.36  6021.9 2153.77  6183.1 2156.65
#Mann= 3 ,-1 , 0
  4256.9      .1       0  5001.7     .07       0  5007.7      .1       0
Bank Sta=4895.9,5171.1
XS Rating Curve= 0 ,0
Exp/Cntr=0.3,0.1

Type RM Length L Ch R = 1 ,68617   ,339,339,339
BEGIN DESCRIPTION:
Mapping XS f10307f3
END DESCRIPTION:
XS GIS Cut Line= 2
       2622993.3     10053754.83      2622159.97     10052754.84
#Sta/Elev= 30
  4329.2 2153.79    4376 2153.05  4468.4 2149.96  4532.2 2148.85  4546.5 2148.12
  4581.7 2147.73  4624.6 2146.38  4638.9 2145.43  4695.1 2143.88  4752.2 2141.46
  4780.8 2139.82  4929.4 2135.47  4951.4 2134.26  4972.2 2132.14  4986.5 2126.43
  4997.8 2123.17  5000.6 2122.67  5003.8 2123.17  5015.1 2124.73  5043.8 2127.08
  5064.6 2129.45  5072.4 2129.85    5157 2130.93  5185.7 2131.88  5249.4 2134.62
  5278.1 2136.33  5327.5 2138.18  5412.2 2142.83  5476.1 2145.61  5630.9 2149.67
#Mann= 3 ,-1 , 0
  4329.2      .1       0  4997.8     .07       0  5003.8      .1       0
Bank Sta=4972.2,5185.7
XS Rating Curve= 0 ,0
Exp/Cntr=0.3,0.1

Type RM Length L Ch R = 1 ,68278   ,415,415,415
BEGIN DESCRIPTION:
Mapping XS 1dd7054a
END DESCRIPTION:
XS GIS Cut Line= 2
      2623316.23     10053577.77      2622410.75      10052557.8
#Sta/Elev= 30
  4240.7 2149.59  4305.7 2148.84  4348.3 2147.23  4468.8 2144.59  4489.7 2144.75
  4525.6 2142.79  4595.9 2141.43    4674 2138.51  4907.8    2134    4922 2132.21
  4928.7 2129.81  4936.3 2128.33  4950.5 2125.23  4971.4 2125.16  4985.6 2122.74
  4996.8 2122.06  4999.6 2121.56  5002.8 2122.06    5035 2126.43  5077.6  2127.3
  5120.2 2126.36    5198  2128.5  5219.8 2130.12  5240.7 2133.83  5254.9 2135.19
  5297.5 2136.34  5375.3 2140.12  5403.7 2140.66  5446.4 2143.49  5604.6 2147.49
#Mann= 3 ,-1 , 0
  4240.7      .1       0  4996.8     .07       0  5002.8      .1       0
Bank Sta=4936.3,5198
XS Rating Curve= 0 ,0
Exp/Cntr=0.3,0.1

Type RM Length L Ch R = 1 ,67863   ,631,631,631
BEGIN DESCRIPTION:
Mapping XS ac517395
END DESCRIPTION:
XS GIS Cut Line= 4
      2623665.19     10053291.31      2623264.12     10052728.78
      2622764.12     10052702.74      2622415.74     10052458.35
#Sta/Elev= 30
  4124.7 2147.86  4285.1 2141.86  4428.8 2137.48  4557.9 2134.53  4626.5 2132.48
  4685.7 2130.83  4723.5 2130.17  4765.8 2125.38  4809.5 2123.35  4848.4 2123.81
  4881.3 2123.53  4901.3 2122.07  4931.4 2122.97  4981.4 2123.09  4998.5 2121.48
  5001.2 2120.98  5004.5 2121.48  5007.6 2122.18  5012.6 2121.63  5041.5 2122.44
  5051.5 2123.44  5111.6 2121.69  5151.7 2124.76  5181.7  2125.6  5271.8 2127.98
  5326.2 2134.14    5484 2140.44    5543 2141.88  5591.9 2144.52  5741.8 2148.55
#Mann= 7 ,-1 , 0
  4124.7      .1       0  4557.9     .16       0  4626.5      .1       0
  4685.7     .16       0  4848.4      .1       0  4998.5     .07       0
  5004.5      .1       0
Bank Sta=4765.8,5181.7
XS Rating Curve= 0 ,0
Exp/Cntr=0.3,0.1

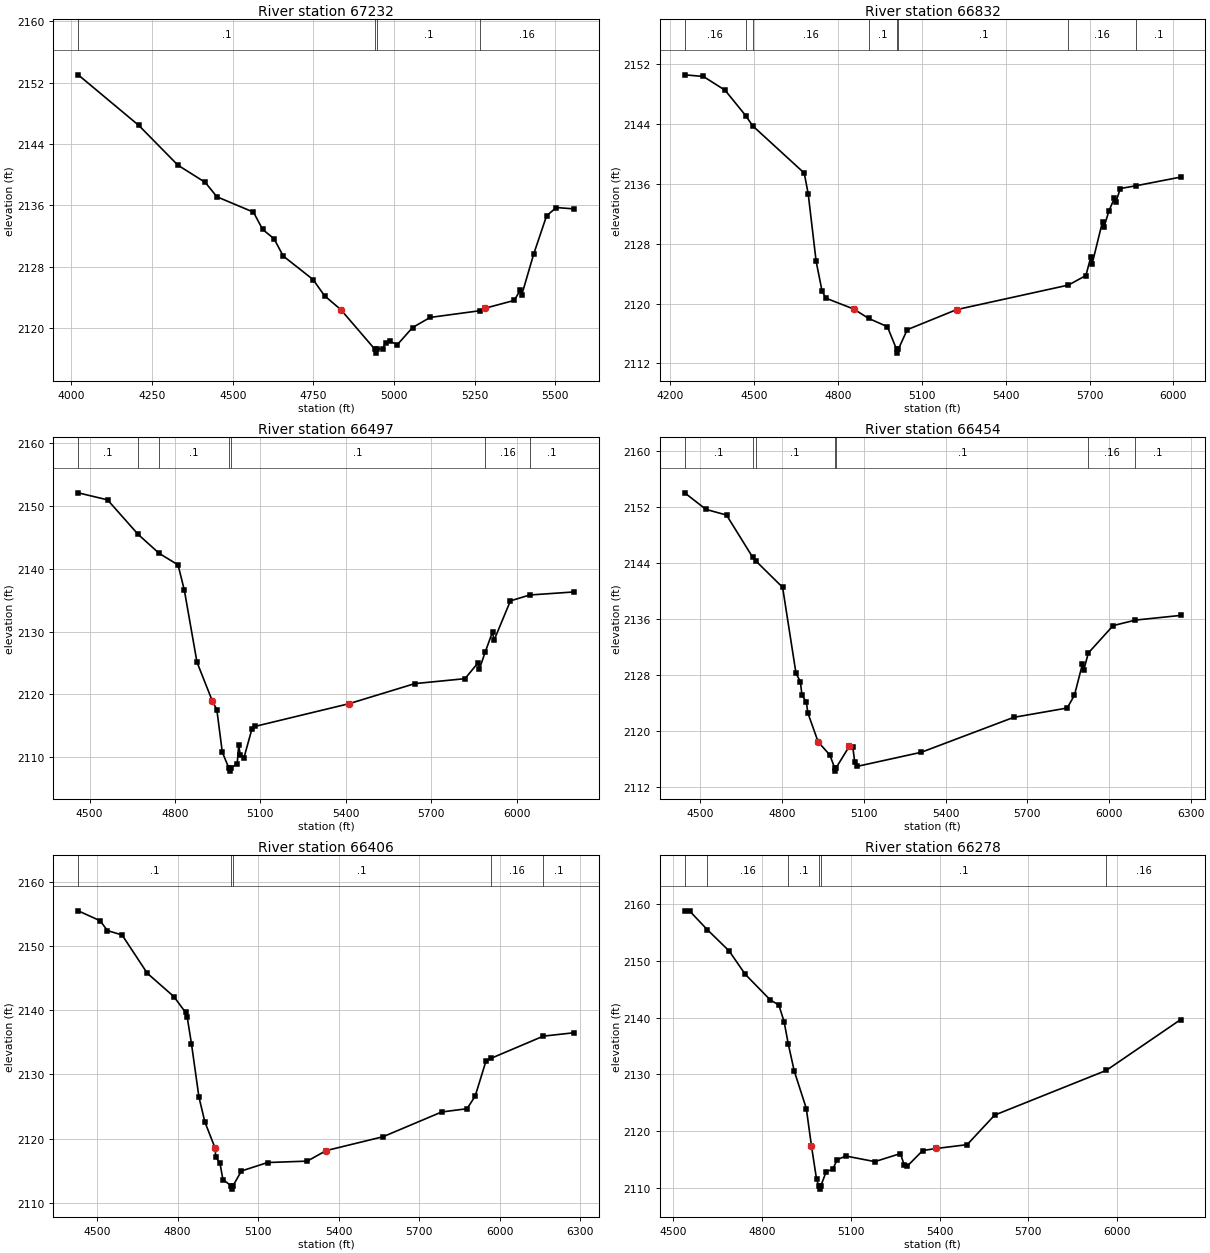
Type RM Length L Ch R = 1 ,67232   ,400,400,400
BEGIN DESCRIPTION:
Mapping XS 71dec805
END DESCRIPTION:
XS GIS Cut Line= 4
       2624123.5     10053103.78      2623670.37     10052562.11
      2623488.08     10052280.86       2622993.4     10052322.52
#Sta/Elev= 30
    4021 2153.02  4209.1 2146.42  4330.1 2141.25  4414.7 2139.01  4451.1 2137.13
  4564.3 2135.13    4593 2132.87  4628.1 2131.67  4656.7 2129.41  4749.1 2126.35
  4784.9 2124.23  4835.2 2122.43  4940.9 2117.26  4943.7 2116.76  4946.9 2117.26
  4965.1 2117.36  4974.2 2118.11  4987.4 2118.31  5010.5 2117.86  5057.7 2120.09
  5112.2 2121.41  5267.2 2122.29  5282.8 2122.61  5373.1 2123.63  5391.3 2124.94
  5396.3 2124.35  5433.3 2129.66  5473.4 2134.66  5503.5 2135.73  5558.8 2135.55
#Mann= 4 ,-1 , 0
    4021      .1       0  4940.9     .07       0  4946.9      .1       0
  5267.2     .16       0
Bank Sta=4835.2,5282.8
XS Rating Curve= 0 ,0
Exp/Cntr=0.3,0.1

Type RM Length L Ch R = 1 ,66832   ,335,335,335
BEGIN DESCRIPTION:
Mapping XS 1446a039
END DESCRIPTION:
XS GIS Cut Line= 4
      2624394.31      10052692.3      2623883.91     10052233.99
      2623779.75     10052108.99      2622878.69     10052322.53
#Sta/Elev= 30
    4251 2150.61  4317.8 2150.39  4395.5 2148.55  4469.3 2145.15  4494.4 2143.78
  4678.8 2137.46    4693 2134.69  4721.4 2125.65  4742.7 2121.65  4756.6 2120.71
    4856 2119.26  4909.1 2118.01  4976.4  2116.9  5009.3 2113.86  5012.1 2113.36
  5015.3 2113.86  5047.5  2116.5  5223.9 2119.18  5624.3 2122.47  5686.8 2123.75
  5703.9 2126.16  5709.1 2125.32  5746.2 2130.96  5751.3  2130.2    5769 2132.38
  5788.4 2134.07  5793.5 2133.55  5810.1 2135.39  5867.1 2135.77  6025.7 2136.92
#Mann= 8 ,-1 , 0
    4251     .16       0  4469.3      .1       0  4494.4     .16       0
  4909.1      .1       0  5009.3     .07       0  5015.3      .1       0
  5624.3     .16       0  5867.1      .1       0
Bank Sta=4856,5223.9
XS Rating Curve= 0 ,0
Exp/Cntr=0.3,0.1

Type RM Length L Ch R = 1 ,66497   ,43,43,43
BEGIN DESCRIPTION:
Mapping XS 45a479ad
END DESCRIPTION:
XS GIS Cut Line= 5
      2624398.48     10052530.29      2624190.13     10052094.05
      2624098.98     10052063.66      2623469.64     10052120.09
      2622948.84     10052224.25
#Sta/Elev= 30
  4459.8 2152.11  4562.8 2150.99  4670.2 2145.49  4744.2 2142.46  4810.6 2140.62
  4832.8 2136.56  4877.1 2125.11  4931.2  2118.9  4946.8 2117.54  4966.1 2110.75
    4989 2108.24  4991.8 2107.74    4995 2108.24  5018.4  2108.9  5023.7 2111.89
  5029.3 2110.28  5042.1 2109.86    5070 2114.44    5080 2114.86  5411.3 2118.49
  5642.2 2121.69  5818.7 2122.48  5864.6    2125  5869.7 2124.07  5890.2 2126.77
  5915.6 2129.95  5920.7 2128.58  5978.3 2134.88  6045.9 2135.82  6202.3 2136.31
#Mann= 7 ,-1 , 0
  4459.8      .1       0  4670.2     .16       0  4744.2      .1       0
    4989     .07       0    4995      .1       0  5890.2     .16       0
  6045.9      .1       0
Bank Sta=4931.2,5411.3
XS Rating Curve= 0 ,0
Exp/Cntr=0.3,0.1

Type RM Length L Ch R = 1 ,66454   ,48,48,48
BEGIN DESCRIPTION:
Mapping XS e6d885f4
END DESCRIPTION:
XS GIS Cut Line= 5
      2624450.55     10052508.56      2624194.47     10052048.47
      2624107.66     10052033.28      2623682.31     10052059.32
      2622914.13     10052187.35
#Sta/Elev= 30
  4442.9 2154.07    4521  2151.7  4596.4 2150.89  4692.5 2144.84  4703.7 2144.33
  4802.2 2140.55  4851.4 2128.23  4867.4 2127.06  4873.1 2125.13  4889.2 2124.14
  4894.9 2122.57  4932.6 2118.43  4975.5 2116.56  4992.8 2114.75  4995.6 2114.25
  4998.8 2114.75  5046.6 2117.78  5059.7 2117.71  5066.8 2115.55  5076.8 2114.94
  5311.3 2116.95  5649.8 2121.94  5846.3 2123.28  5872.9 2125.11  5902.1 2129.54
  5907.1  2128.7  5923.9 2131.15  6014.8 2135.07  6096.6 2135.86  6262.5 2136.53
#Mann= 7 ,-1 , 0
  4442.9      .1       0  4692.5     .16       0  4703.7      .1       0
  4992.8     .07       0  4998.8      .1       0  5923.9     .16       0
  6096.6      .1       0
Bank Sta=4932.6,5046.6
XS Rating Curve= 0 ,0
Exp/Cntr=0.3,0.1

Type RM Length L Ch R = 1 ,66406   ,128,128,128
BEGIN DESCRIPTION:
Mapping XS f4cfbc1f
END DESCRIPTION:
XS GIS Cut Line= 5
      2624493.07     10052477.93      2624252.19     10052024.38
        2624135.     10051991.83      2624039.52     10051987.49
      2622933.07     10052132.85
#Sta/Elev= 30
    4430 2155.46  4511.4 2153.92    4539 2152.38  4593.3  2151.7  4687.2 2145.74
  4785.8 2142.12  4829.8 2139.64  4835.5    2139  4851.8 2134.74  4879.4  2126.5
  4901.4 2122.61  4939.7 2118.52  4942.2 2117.14  4957.8 2116.16    4969  2113.6
  5000.3 2112.63    5003 2112.13  5006.3 2112.63  5037.5 2114.95  5135.1 2116.27
  5282.8 2116.49  5353.4 2118.13  5565.2 2120.29  5783.3 2124.14  5877.9 2124.65
  5908.2 2126.62  5948.5 2132.09  5967.5  2132.5    6162 2135.95  6276.7 2136.48
#Mann= 5 ,-1 , 0
    4430      .1       0  5000.3     .07       0  5006.3      .1       0
  5967.5     .16       0    6162      .1       0
Bank Sta=4939.7,5353.4
XS Rating Curve= 0 ,0
Exp/Cntr=0.3,0.1

Type RM Length L Ch R = 1 ,66278   ,479,479,479
BEGIN DESCRIPTION:
Mapping XS 63b29377
END DESCRIPTION:
XS GIS Cut Line= 2
      2624715.27      10052117.9      2623185.34     10051434.32
#Sta/Elev= 30
  4538.6 2158.84  4556.3 2158.75  4614.8 2155.53  4688.8 2151.77  4743.2 2147.65
    4828 2143.12  4856.7 2142.24  4874.5  2139.3    4889 2135.28  4908.6 2130.63
  4949.6 2123.98 4967.05 2117.35  4984.2 2111.51  4992.1 2110.27  4994.9 2109.77
  4998.1 2110.27    5017 2112.87  5038.9 2113.25  5053.3 2114.94  5082.7 2115.61
  5181.3 2114.62  5267.7 2116.04  5279.9 2114.08  5290.8 2113.83  5342.8 2116.57
  5389.2 2116.94    5493 2117.61  5585.9 2122.82  5963.3 2130.71  6214.3 2139.66
#Mann= 6 ,-1 , 0
  4538.6      .1       0  4614.8     .16       0    4889      .1       0
  4992.1     .07       0  4998.1      .1       0  5963.3     .16       0
Bank Sta=4967.05,5389.2
XS Rating Curve= 0 ,0
Exp/Cntr=0.3,0.1