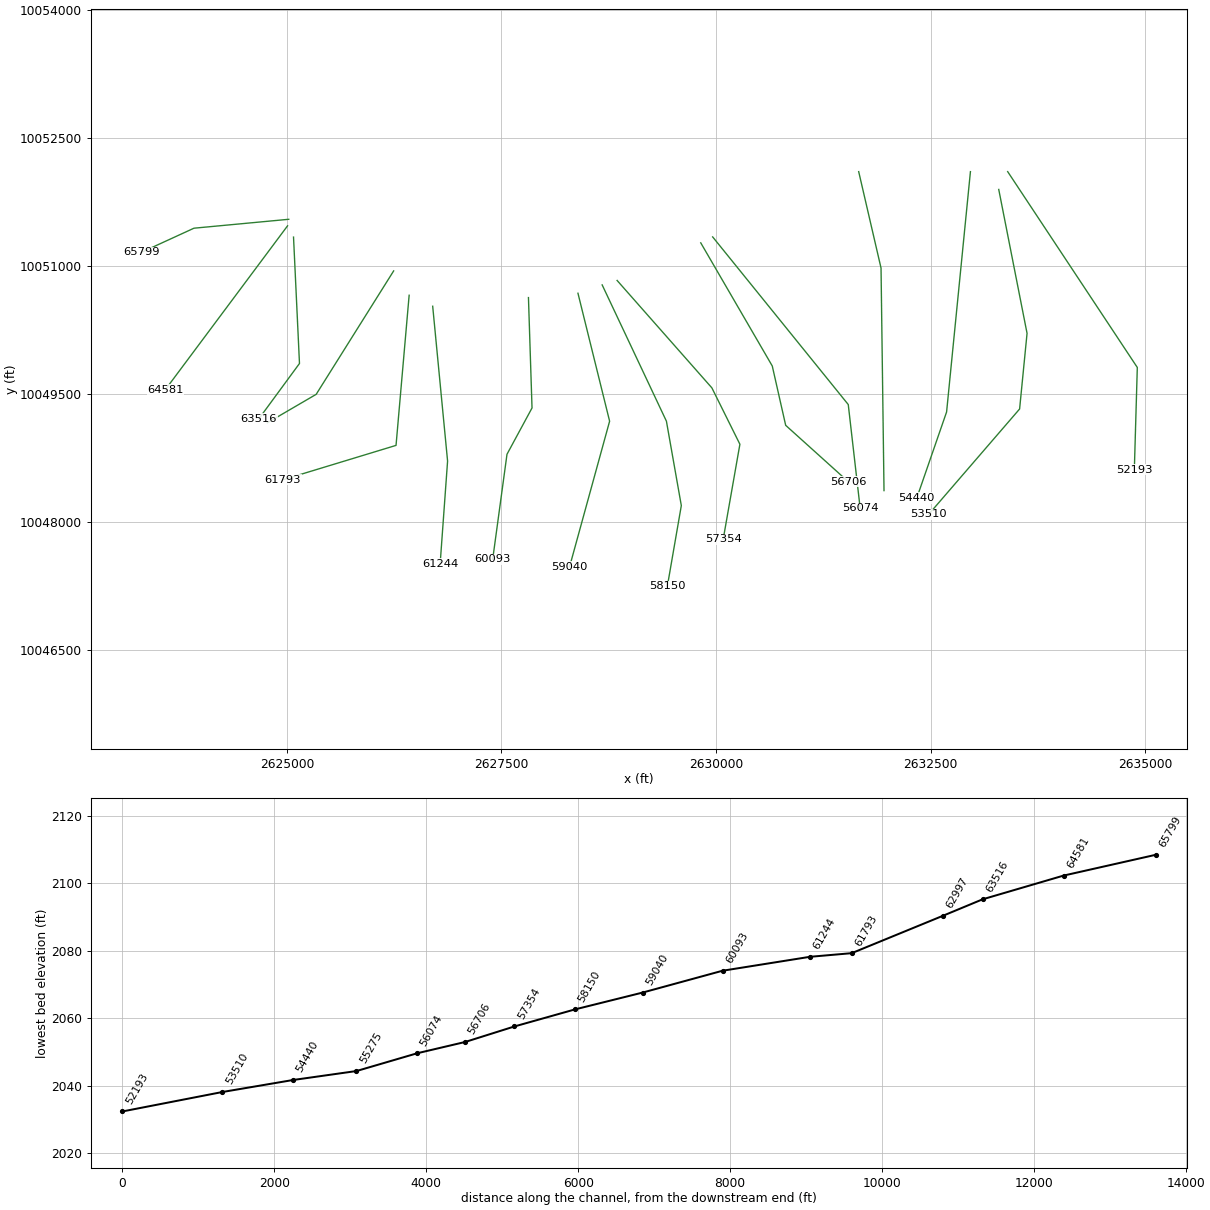
HEC-RAS study KLEIN BRANCH.prj: KLEIN BRANCH Base Level Engineering

--- KLEIN BRANCH.g01 (geometry) --- (continued)

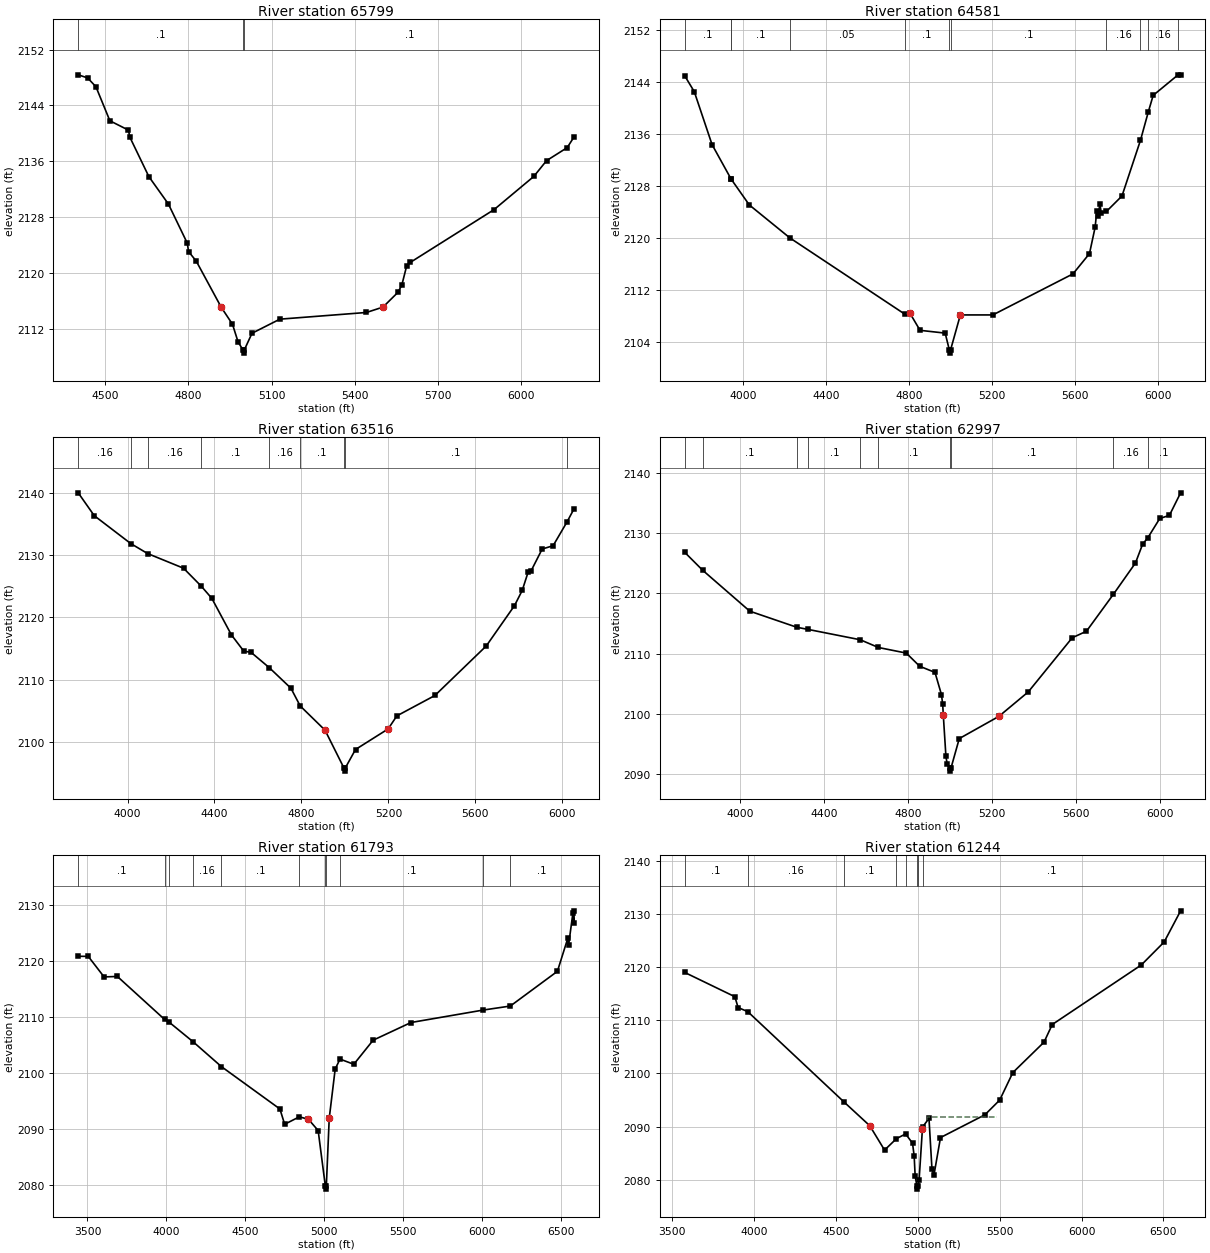
Type RM Length L Ch R = 1 ,65799   ,1218,1218,1218
BEGIN DESCRIPTION:
Mapping XS 552f1942
END DESCRIPTION:
XS GIS Cut Line= 3
      2625022.08     10051545.88      2623917.94     10051441.71
      2623301.63      10051157.8
#Sta/Elev= 30
  4403.3 2148.39  4437.1 2147.95  4467.2 2146.68  4517.4  2141.8  4584.3 2140.46
  4589.3 2139.46    4658 2133.79  4728.4 2129.86  4796.2 2124.27  4801.2 2123.04
  4828.8 2121.67  4919.2 2115.03  4959.4 2112.62  4979.5 2110.09  4996.5 2108.98
  4999.3 2108.48  5002.5 2108.98  5029.7 2111.33  5130.1 2113.35  5442.1 2114.31
  5501.8 2115.08  5555.8  2117.2  5569.8 2118.25  5587.3    2121  5599.8 2121.48
  5902.2 2129.06  6045.5 2133.82  6091.4 2136.08  6165.8 2137.95  6190.9 2139.51
#Mann= 3 ,-1 , 0
  4403.3      .1       0  4996.5     .07       0  5002.5      .1       0
Bank Sta=4919.2,5501.8
XS Rating Curve= 0 ,0
Exp/Cntr=0.3,0.1

Type RM Length L Ch R = 1 ,64581   ,1065,1065,1065
BEGIN DESCRIPTION:
Mapping XS fb759f03
END DESCRIPTION:
XS GIS Cut Line= 2
      2625008.25     10051469.53      2623584.59     10049552.81
#Sta/Elev= 30
  3720.7 2144.99  3766.9 2142.54  3852.5 2134.39  3944.3 2129.08  3944.6 2129.07
  4031.9  2125.1    4227 2120.03    4779 2108.32  4803.7 2108.51  4853.8  2105.8
  4974.8 2105.37  4994.8 2102.79  4997.5 2102.29  5000.8 2102.79  5047.9 2108.17
  5204.3 2108.17  5590.2 2114.49  5669.5 2117.61  5696.6 2121.65    5705 2124.24
  5711.2 2123.37  5719.6 2125.27  5725.8 2123.93  5751.2  2124.1    5826 2126.48
  5914.9 2135.04    5953 2139.45  5976.2 2141.97  6095.8 2145.12  6108.3 2145.13
#Mann= 11 ,-1 , 0
  3720.7      .1       0  3944.3     .16       0  3944.6      .1       0
    4227     .05       0    4779      .1       0  4994.8     .07       0
  5000.8      .1       0  5751.2     .16       0  5914.9      .1       0
    5953     .16       0  6095.8      .1       0
Bank Sta=4803.7,5047.9
XS Rating Curve= 0 ,0
Exp/Cntr=0.3,0.1

Type RM Length L Ch R = 1 ,63516   ,519,519,519
BEGIN DESCRIPTION:
Mapping XS 2a195eab
END DESCRIPTION:
XS GIS Cut Line= 3
      2625077.66     10051337.58      2625147.11     10049858.38
      2624674.88     10049212.54
#Sta/Elev= 30
  3773.2 2140.04  3847.1 2136.36  4014.7 2131.88  4092.3 2130.27  4257.6 2127.91
  4339.4 2125.01  4387.7 2123.06  4477.8 2117.18  4534.8 2114.56  4567.9 2114.38
  4652.8 2111.88  4751.5  2108.6  4794.1 2105.75  4908.3 2101.85  4995.4 2095.76
  4998.2 2095.26  5001.4 2095.76  5048.5 2098.74  5198.6 2102.05  5238.7 2104.15
  5413.7 2107.43  5649.9  2115.4  5779.7 2121.89  5815.2 2124.33  5842.2 2127.26
  5856.9 2127.54  5907.1    2131  5957.3 2131.53  6021.5 2135.37  6054.1 2137.51
#Mann= 9 ,-1 , 0
  3773.2     .16       0  4014.7      .1       0  4092.3     .16       0
  4339.4      .1       0  4652.8     .16       0  4794.1      .1       0
  4995.4     .07       0  5001.4      .1       0  6021.5     .16       0
Bank Sta=4908.3,5198.6
XS Rating Curve= 0 ,0
Exp/Cntr=0.3,0.1

Type RM Length L Ch R = 1 ,62997   ,1204,1204,1204
BEGIN DESCRIPTION:
Mapping XS 19b8fb9e
END DESCRIPTION:
XS GIS Cut Line= 3
      2626244.32     10050941.69      2625341.55     10049497.27
      2624772.77     10049164.32
#Sta/Elev= 30
  3735.7 2126.86  3820.9 2123.88  4045.8 2117.05  4269.8 2114.37  4325.1    2114
    4572 2112.29  4658.6    2111  4791.3 2110.07    4855 2107.88  4928.1 2106.85
  4958.8 2103.16  4964.7 2101.56 4967.61 2099.76    4980 2092.94  4985.9 2091.59
  4998.2 2090.91    5001 2090.41  5004.2 2090.91  5043.7 2095.83  5232.4 2099.53
  5372.5 2103.61  5581.7 2112.62  5649.6 2113.71  5777.5 2119.84  5882.9 2125.07
  5917.7 2128.26  5940.6  2129.2  5998.8 2132.49  6044.6    2133  6098.1 2136.76
#Mann= 10 ,-1 , 0
  3735.7     .16       0  3820.9      .1       0  4269.8     .16       0
  4325.1      .1       0    4572     .16       0  4658.6      .1       0
  4998.2     .07       0  5004.2      .1       0  5777.5     .16       0
  5940.6      .1       0
Bank Sta=4967.61,5232.4
XS Rating Curve= 0 ,0
Exp/Cntr=0.3,0.1

Type RM Length L Ch R = 1 ,61793   ,549,549,549
BEGIN DESCRIPTION:
Mapping XS 2c3060e8
END DESCRIPTION:
XS GIS Cut Line= 3
      2626424.89     10050657.01      2626272.11     10048900.05
      2624953.09      10048497.4
#Sta/Elev= 30
  3441.2 2120.86  3504.7 2120.85  3605.1 2117.18  3689.4 2117.26  3988.5 2109.59
  4017.8 2109.09  4169.2  2105.6  4348.4 2101.17  4719.3  2093.6  4749.4 2090.87
  4842.5  2092.2    4900 2091.76  4961.7 2089.75  5007.4 2079.79  5010.1 2079.29
  5013.4 2079.79 5031.82 2091.93  5069.6 2100.73  5100.1 2102.51  5187.6 2101.58
    5310 2105.88  5550.1 2109.04  6009.1 2111.27  6179.5 2111.98  6477.8 2118.18
  6543.4 2124.06  6548.6 2122.85  6576.2 2128.64  6581.4 2126.88  6583.9 2128.98
#Mann= 11 ,-1 , 0
  3441.2      .1       0  3988.5     .16       0  4017.8      .1       0
  4169.2     .16       0  4348.4      .1       0  4842.5     .16       0
  5007.4     .07       0  5013.4     .16       0  5100.1      .1       0
  6009.1     .16       0  6179.5      .1       0
Bank Sta=4900,5031.82
XS Rating Curve= 0 ,0
Exp/Cntr=0.3,0.1

Type RM Length L Ch R = 1 ,61244   ,1151,1151,1151
BEGIN DESCRIPTION:
Mapping XS 84689374
END DESCRIPTION:
XS GIS Cut Line= 3
      2626699.19     10050528.56       2626872.8     10048716.45
      2626785.99     10047511.98
#Sta/Elev= 30
  3576.9 2119.02  3883.1 2114.45  3903.2  2112.4  3961.9 2111.64  4546.7 2094.71
  4706.9 2090.15  4797.3 2085.56  4869.7 2087.71  4925.9 2088.61  4968.1 2086.85
  4978.1 2084.43    4984 2080.72  4995.2 2078.71    4998 2078.21  5001.2 2078.71
  5008.3 2080.01  5028.3 2089.49  5031.1 2089.98  5068.5 2091.53  5086.7 2081.99
  5098.7 2080.83  5138.8 2087.92  5410.1 2092.21  5500.3 2094.98  5580.5 2100.16
    5771 2105.89  5821.1 2109.21  6364.7 2120.42  6504.4 2124.75  6604.9 2130.62
#Mann= 8 ,-1 , 0
  3576.9      .1       0  3961.9     .16       0  4546.7      .1       0
  4869.7     .16       0  4925.9     .12       0  4995.2     .07       0
  5001.2     .12       0  5031.1      .1       0
#XS Ineff= 1 ,-1
 5059.09 5482.67 2091.81
Permanent Ineff=
       T
Bank Sta=4706.9,5028.3
XS Rating Curve= 0 ,0
Exp/Cntr=0.3,0.1

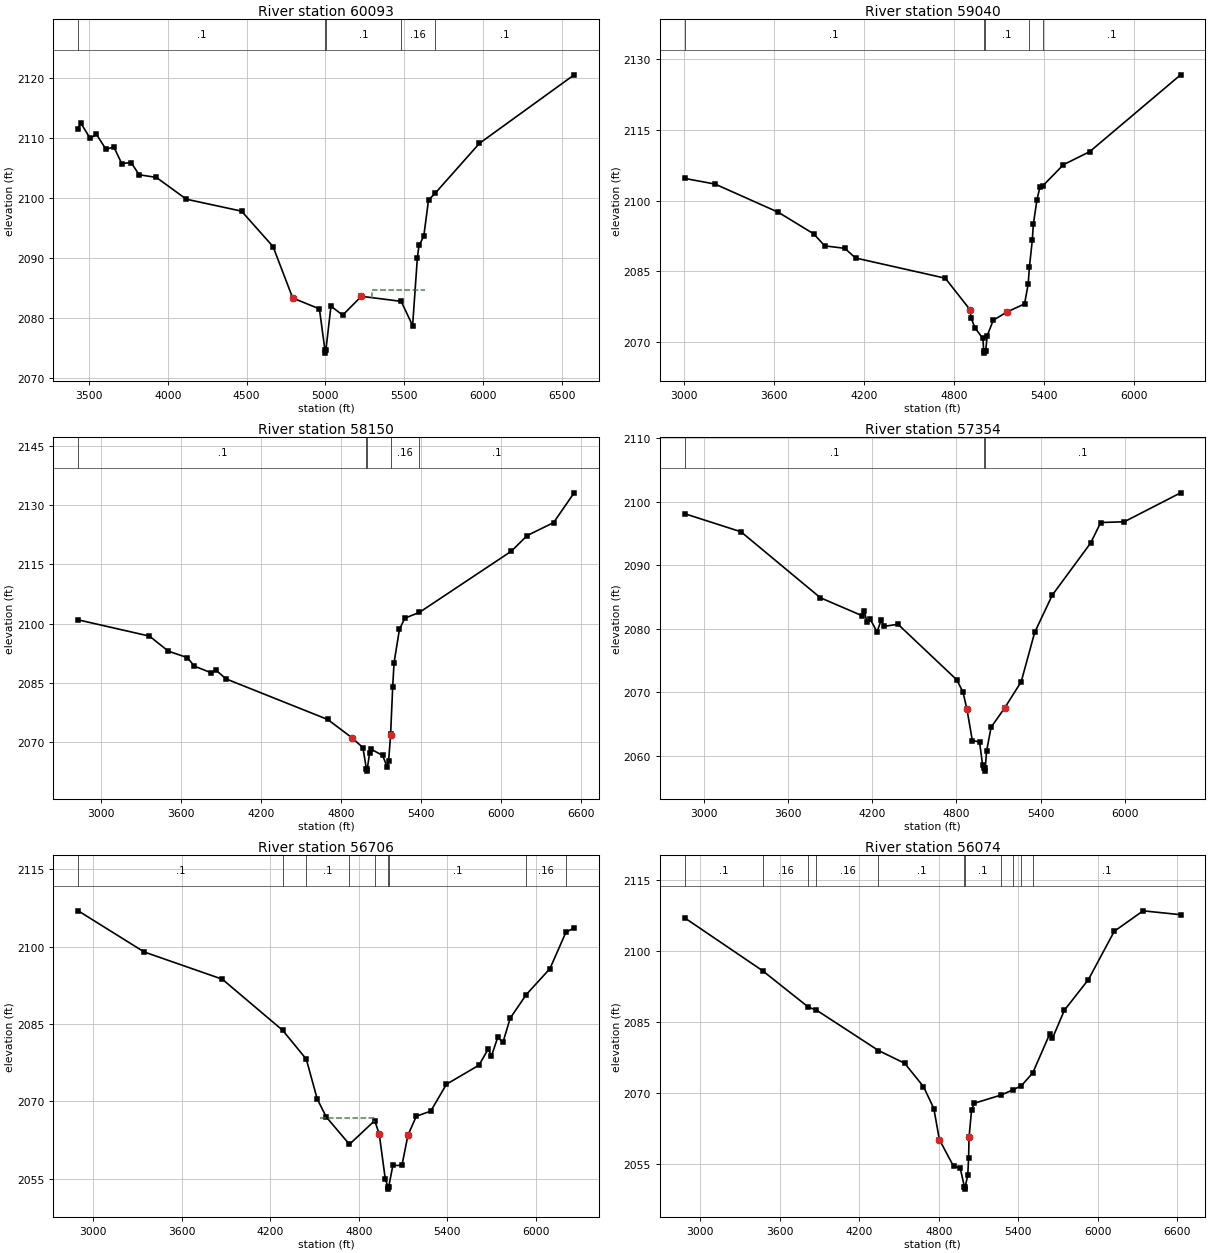
Type RM Length L Ch R = 1 ,60093   ,1053,1053,1053
BEGIN DESCRIPTION:
KLEIN BRANCH 32.0
END DESCRIPTION:
XS GIS Cut Line= 4
      2627815.08     10050629.63      2627856.74     10049337.98
      2627565.08     10048796.32      2627398.52     10047567.97
#Sta/Elev= 30
  3431.8 2111.59  3447.7 2112.54  3507.7 2109.95  3547.8 2110.62  3607.8 2108.13
  3657.8 2108.52  3707.8 2105.75  3767.9 2105.92  3817.9 2103.88    3928 2103.43
  4118.1 2099.79  4468.2  2097.8  4668.3 2091.87  4792.9 2083.29  4962.4 2081.47
  4997.5 2074.58  5000.3 2074.08  5003.5 2074.58  5035.6 2081.92  5110.1 2080.43
  5228.7 2083.57  5481.3 2082.73  5553.8 2078.67  5584.1 2090.05  5594.2 2092.06
  5624.5 2093.58  5654.8 2099.66    5697 2100.79  5977.7 2109.12  6578.9 2120.57
#Mann= 5 ,-1 , 0
  3431.8      .1       0  4997.5     .07       0  5003.5      .1       0
  5481.3     .16       0    5697      .1       0
#XS Ineff= 1 ,-1
 5295.45 5631.82 2084.57
Permanent Ineff=
       T
Bank Sta=4792.9,5228.7
XS Rating Curve= 0 ,0
Exp/Cntr=0.3,0.1

Type RM Length L Ch R = 1 ,59040   ,890,890,890
BEGIN DESCRIPTION:
Mapping XS 86c156ce
END DESCRIPTION:
XS GIS Cut Line= 3
      2628391.89     10050680.48      2628760.82     10049183.03
      2628294.25      10047479.5
#Sta/Elev= 30
  3003.2 2104.72  3205.8 2103.52  3628.1 2097.52    3865 2092.92  3937.1 2090.39
  4070.9 2089.87  4143.3 2087.81  4741.7 2083.52  4907.6 2076.79  4913.4 2075.16
  4938.7 2073.01  4992.7 2070.72  4997.9  2068.1  5000.7  2067.6  5003.9  2068.1
  5011.3 2068.15  5021.6 2071.31  5061.7 2074.59  5156.4 2076.39  5270.5 2078.06
  5294.5 2082.22  5303.4    2086  5322.3 2091.62    5329 2094.94  5353.4  2100.2
  5374.2    2103  5391.9 2103.13  5529.7 2107.63  5704.9  2110.4  6311.7 2126.73
#Mann= 5 ,-1 , 0
  3003.2      .1       0  4997.9     .07       0  5003.9      .1       0
  5303.4     .16       0  5391.9      .1       0
Bank Sta=4907.6,5156.4
XS Rating Curve= 0 ,0
Exp/Cntr=0.3,0.1

Type RM Length L Ch R = 1 ,58150   ,796,796,796
BEGIN DESCRIPTION:
Mapping XS 30770418
END DESCRIPTION:
XS GIS Cut Line= 4
        2628674.     10050778.12      2629422.71     10049183.03
      2629596.33     10048195.62      2629433.56     10047251.57
#Sta/Elev= 30
  2827.1 2100.96  3361.9 2096.84  3504.3 2093.01  3646.7 2091.39  3697.9 2089.24
  3826.2 2087.53  3863.1 2088.14  3937.1 2085.99  4700.1  2075.7  4885.1 2070.98
  4964.1 2068.56  4990.6 2063.11  4993.4 2062.61  4996.6 2063.11  5014.9 2067.32
    5025 2068.17  5112.3 2066.59  5146.9 2063.57    5157 2065.17  5171.6 2071.65
  5171.9 2071.91  5187.5 2083.83  5197.7 2090.05  5238.3 2098.56  5278.9 2101.39
  5387.7 2102.85  6077.5 2118.35  6197.3 2122.34  6395.3 2125.62  6549.7 2133.17
#Mann= 5 ,-1 , 0
  2827.1      .1       0  4990.6     .07       0  4996.6      .1       0
  5171.9     .16       0  5387.7      .1       0
Bank Sta=4885.1,5171.6
XS Rating Curve= 0 ,0
Exp/Cntr=0.3,0.1

Type RM Length L Ch R = 1 ,57354   ,648,648,648
BEGIN DESCRIPTION:
Mapping XS 3aae50c2
END DESCRIPTION:
XS GIS Cut Line= 4
      2628848.21     10050830.01      2629952.39     10049573.06
      2630278.78     10048913.33      2630084.33     10047802.22
#Sta/Elev= 30
  2861.8 2098.13  3263.3 2095.28  3829.8 2084.88  4127.7 2082.05  4141.9  2082.8
  4162.8 2081.03  4184.6 2081.52    4234 2079.51  4262.4 2081.34  4283.3 2080.37
  4382.9 2080.71  4801.9 2071.96  4846.5 2070.03    4875 2067.31  4913.4 2062.37
  4964.7 2062.17  4987.1 2058.45  4999.7 2058.06  5002.4 2057.56  5005.7 2058.06
  5015.1 2060.73  5047.3 2064.48  5144.2 2067.52  5261.9 2071.65  5358.3 2079.44
  5483.7  2085.3  5757.8 2093.53  5828.9 2096.74  5997.1 2096.86  6398.9 2101.42
#Mann= 3 ,-1 , 0
  2861.8      .1       0  4999.7     .07       0  5005.7      .1       0
Bank Sta=4875,5144.2
XS Rating Curve= 0 ,0
Exp/Cntr=0.3,0.1

Type RM Length L Ch R = 1 ,56706   ,632,632,632
BEGIN DESCRIPTION:
Mapping XS 8e26a408
END DESCRIPTION:
XS GIS Cut Line= 4
      2629822.72     10051270.27      2630656.05      10049829.3
       2630812.3     10049134.86      2631541.46     10048475.14
#Sta/Elev= 30
  2899.5 2106.96  3346.1 2098.98  3875.7 2093.69  4284.4 2083.78  4444.4 2078.19
  4518.8 2070.44    4580 2066.96  4736.8 2061.65  4908.1 2066.25  4938.8 2063.65
  4979.8 2054.91  4997.3 2053.46    5000 2052.96  5003.3 2053.46    5031 2057.55
  5092.5 2057.57  5133.5 2063.45    5190  2067.1    5288  2068.1  5394.1 2073.31
  5613.8    2077  5677.3 2080.14  5698.9 2078.78  5741.5 2082.41  5776.7 2081.43
    5826 2086.13  5934.3 2090.69    6095 2095.73  6203.6 2102.81  6259.2 2103.64
#Mann= 9 ,-1 , 0
  2899.5      .1       0  4284.4     .16       0  4444.4      .1       0
  4736.8     .16       0  4908.1      .1       0  4997.3     .07       0
  5003.3      .1       0  5934.3     .16       0  6203.6      .1       0
#XS Ineff= 1 ,-1
 4534.09    4900 2066.75
Permanent Ineff=
       T
Bank Sta=4938.8,5133.5
XS Rating Curve= 0 ,0
Exp/Cntr=0.3,0.1

Type RM Length L Ch R = 1 ,56074   ,799,799,799
BEGIN DESCRIPTION:
Mapping XS f965d954
END DESCRIPTION:
XS GIS Cut Line= 3
      2629961.63     10051339.68      2631541.46     10049377.91
      2631680.35     10048162.63
#Sta/Elev= 30
    2883 2107.05  3470.2 2095.87  3816.8 2088.14  3877.6 2087.51  4345.3 2078.96
  4542.3 2076.27  4684.6 2071.33    4763 2066.68  4804.6  2060.1  4911.8 2054.44
  4961.4 2054.13  4993.6 2050.11  4996.4 2049.61  4999.6 2050.11    5019 2052.61
  5025.4 2056.28 5028.69 2060.59  5047.7  2066.4  5068.6  2067.8  5270.1 2069.53
  5356.7  2070.6  5423.1 2071.49    5509  2074.2  5637.5 2082.48  5657.6 2081.53
  5748.2  2087.5  5929.4 2093.99  6124.8 2104.22  6342.1 2108.54    6625 2107.72
#Mann= 11 ,-1 , 0
    2883      .1       0  3470.2     .16       0  3816.8      .1       0
  3877.6     .16       0  4345.3      .1       0  4993.6     .07       0
  4999.6      .1       0  5270.1     .16       0  5356.7      .1       0
  5423.1     .16       0    5509      .1       0
Bank Sta=4804.6,5028.69
XS Rating Curve= 0 ,0
Exp/Cntr=0.3,0.1

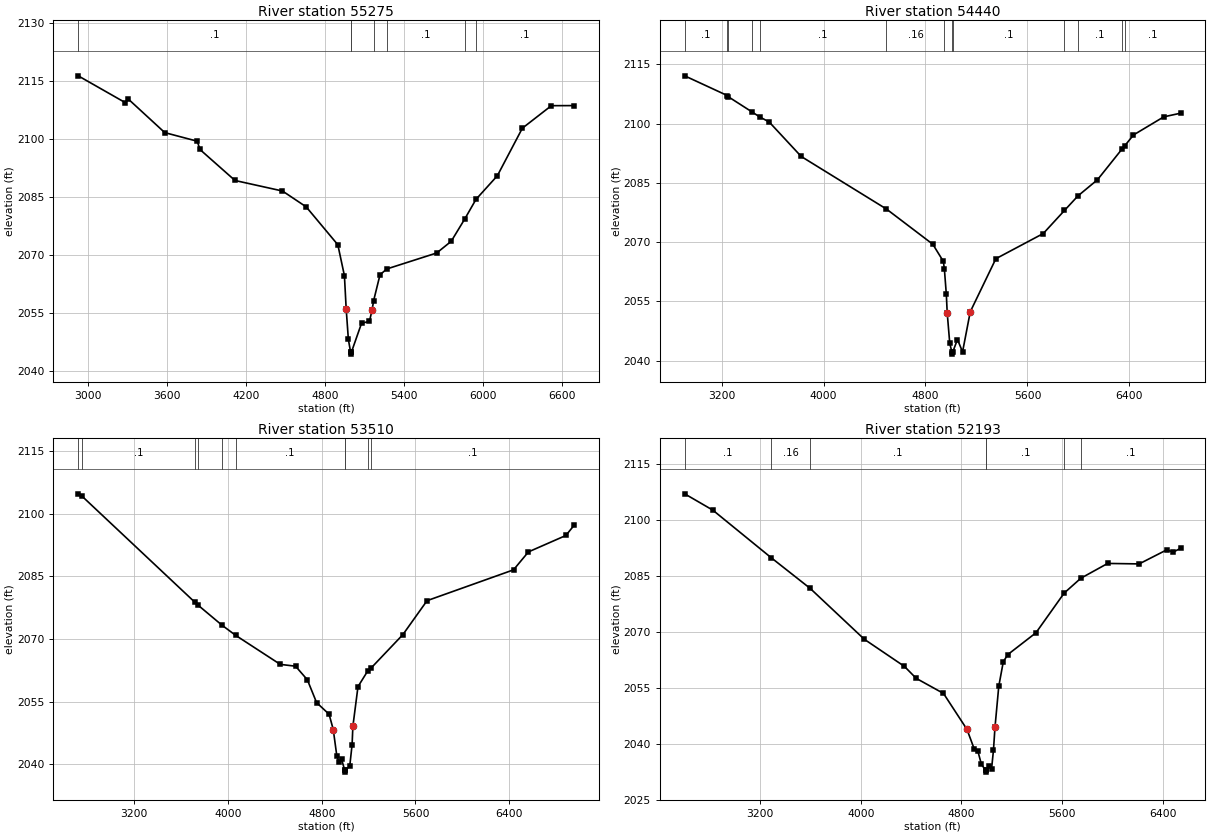
Type RM Length L Ch R = 1 ,55275   ,835,835,835
BEGIN DESCRIPTION:
Mapping XS 20926984
END DESCRIPTION:
XS GIS Cut Line= 3
        2631663.      10052103.6      2631923.41     10050975.14
      2631958.13     10048370.98
#Sta/Elev= 30
  2927.2 2116.32  3283.1 2109.41  3306.8 2110.32  3583.9 2101.63  3830.2 2099.41
  3850.7 2097.27  4116.7 2089.25  4476.8 2086.53  4656.8 2082.43  4896.8 2072.63
  4946.8 2064.63 4960.23 2056.02  4976.8 2048.14  4993.8 2044.84  4996.6 2044.34
  4999.8 2044.84  5076.8 2052.33  5136.8 2052.82  5156.8 2055.77    5168 2058.11
  5216.8 2064.87  5268.4 2066.37  5646.9  2070.5  5756.9 2073.52  5860.4 2079.33
  5945.2 2084.38  6106.9 2090.47  6296.9 2102.78  6516.9  2108.6  6689.7 2108.62
#Mann= 7 ,-1 , 0
  2927.2      .1       0  4993.8     .07       0  4999.8      .1       0
    5168     .16       0  5268.4      .1       0  5860.4     .16       0
  5945.2      .1       0
Bank Sta=4960.23,5156.8
XS Rating Curve= 0 ,0
Exp/Cntr=0.3,0.1

Type RM Length L Ch R = 1 ,54440   ,930,930,930
BEGIN DESCRIPTION:
Mapping XS c979785d
END DESCRIPTION:
XS GIS Cut Line= 3
      2632965.07     10052103.59       2632687.3     10049291.11
      2632340.07     10048284.16
#Sta/Elev= 30
  2910.5 2112.09  3246.4 2107.08  3254.2 2106.77  3439.6 2102.94  3498.2 2101.71
  3573.6 2100.41  3824.8 2091.69  4493.9 2078.38  4857.4 2069.48  4940.2 2065.14
  4948.4 2063.14  4963.5 2056.79  4970.3 2052.16  4990.4 2044.39  5007.5 2042.18
  5010.3 2041.68  5013.5 2042.18  5050.7 2045.38  5090.9 2042.26  5151.2 2052.39
  5352.2 2065.82    5724 2072.19  5890.6 2078.03  5996.2 2081.71  6149.5  2085.8
  6343.5 2093.63  6362.5 2094.35    6432 2097.13  6669.4 2101.71  6801.8 2102.64
#Mann= 13 ,-1 , 0
  2910.5      .1       0  3246.4     .16       0  3254.2      .1       0
  3439.6     .16       0  3498.2      .1       0  4493.9     .16       0
  4948.4      .1       0  5007.5     .07       0  5013.5      .1       0
  5890.6     .16       0  5996.2      .1       0  6343.5     .16       0
  6362.5      .1       0
Bank Sta=4970.3,5151.2
XS Rating Curve= 0 ,0
Exp/Cntr=0.3,0.1

Type RM Length L Ch R = 1 ,53510   ,1317,1317,1317
BEGIN DESCRIPTION:
Mapping XS dffd20be
END DESCRIPTION:
XS GIS Cut Line= 4
      2633294.94     10051895.27       2633624.8     10050211.25
      2633537.99     10049325.83      2632478.95     10048093.18
#Sta/Elev= 30
  2722.7 2104.78  2754.6 2104.23  3716.7 2078.84  3741.8 2078.19  3949.4 2073.31
  4065.4 2070.89  4446.3 2063.93  4576.9 2063.49  4677.4 2060.24  4756.3 2054.77
  4862.8 2051.99  4898.4 2048.32  4928.6 2042.05  4948.7 2040.44  4969.3 2041.17
  4995.9 2038.62  4998.7 2038.12  5001.9 2038.62  5039.1 2039.56  5059.2 2044.72
  5065.8 2049.07  5109.4  2058.6  5191.8 2062.32  5220.1 2063.02  5492.4 2071.06
  5698.7 2079.19  6436.1 2086.57  6563.4 2090.87  6882.7  2094.8  6953.5 2097.26
#Mann= 10 ,-1 , 0
  2722.7     .16       0  2754.6      .1       0  3716.7     .05       0
  3741.8      .1       0  3949.4     .05       0  4065.4      .1       0
  4995.9     .07       0  5001.9      .1       0  5191.8     .16       0
  5220.1      .1       0
Bank Sta=4898.4,5065.8
XS Rating Curve= 0 ,0
Exp/Cntr=0.3,0.1

Type RM Length L Ch R = 1 ,52193   ,1357,1357,1357
BEGIN DESCRIPTION:
Mapping XS c7e60a0c
END DESCRIPTION:
XS GIS Cut Line= 3
      2633399.11     10052103.59      2634909.52     10049811.94
       2634874.8     10048614.07
#Sta/Elev= 30
  2600.5 2106.92  2824.2 2102.55  3290.7 2089.74  3598.2 2081.58  4028.7 2067.95
  4347.9 2060.67  4441.2 2057.48  4658.1 2053.44  4844.7 2043.81  4901.9 2038.62
  4932.1  2037.9  4959.7 2034.44  4992.7 2032.85  4995.4 2032.35  4998.7 2032.85
  5019.4  2033.9  5040.5 2033.24  5055.5 2038.22  5067.5 2044.32  5097.7 2055.36
  5133.8 2061.95    5170 2063.86  5393.4 2069.69    5618 2080.34  5750.1  2084.3
  5963.6 2088.27  6213.7 2088.14  6433.8 2091.92  6483.8 2091.31  6543.5 2092.31
#Mann= 7 ,-1 , 0
  2600.5      .1       0  3290.7     .16       0  3598.2      .1       0
  4992.7     .07       0  4998.7      .1       0    5618     .16       0
  5750.1      .1       0
Bank Sta=4844.7,5067.5
XS Rating Curve= 0 ,0
Exp/Cntr=0.3,0.1