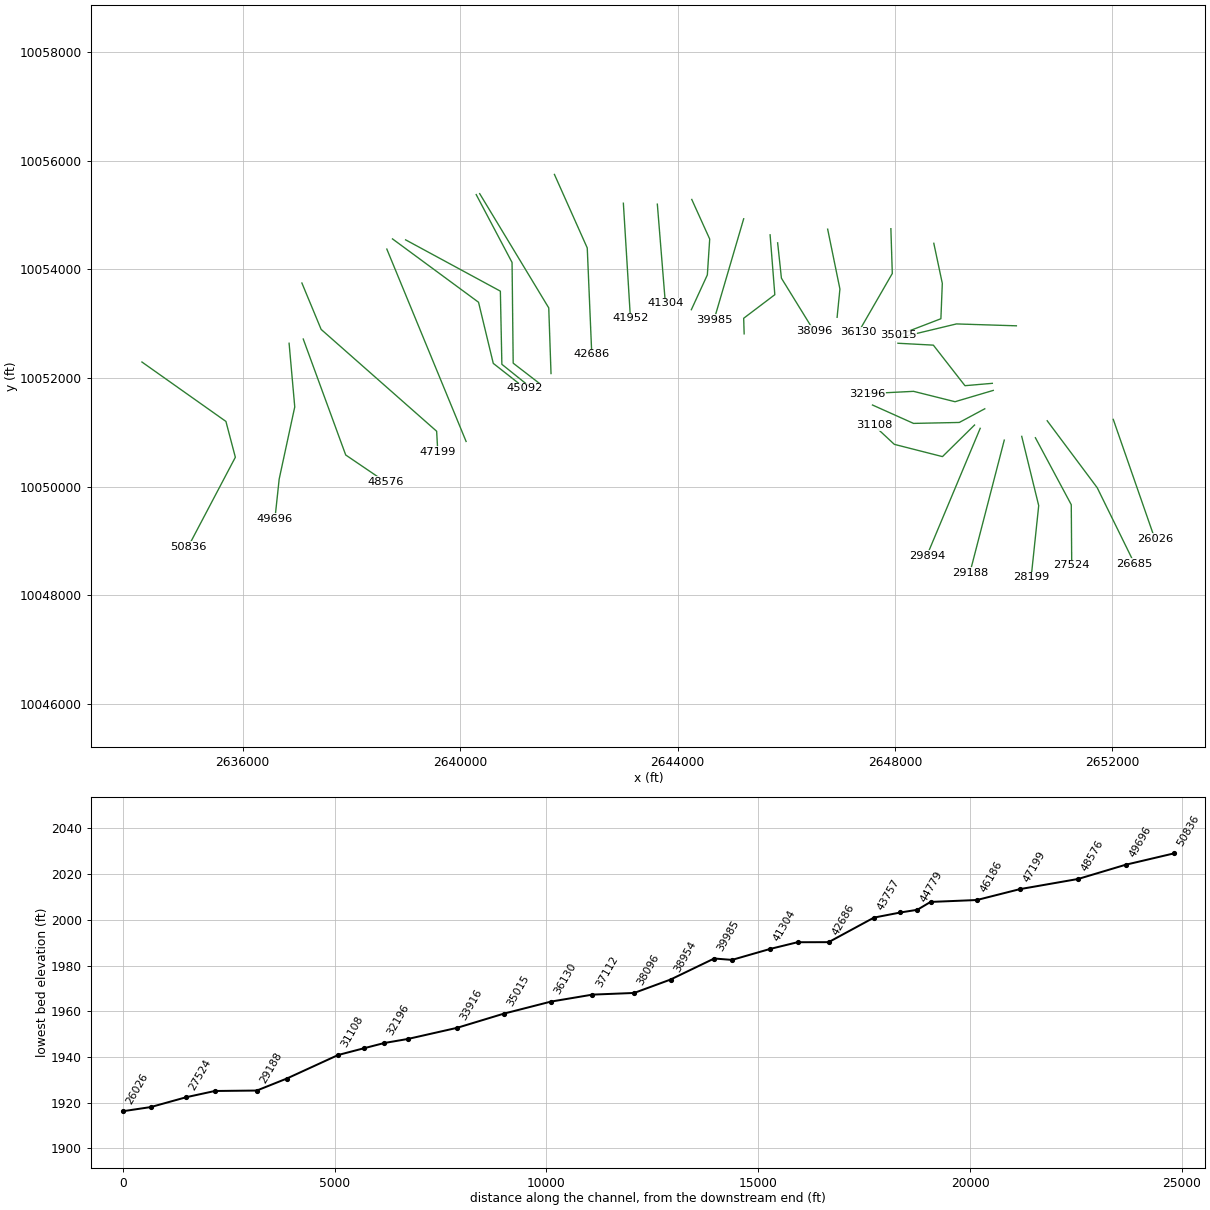
HEC-RAS study KLEIN BRANCH.prj: KLEIN BRANCH Base Level Engineering

--- KLEIN BRANCH.g01 (geometry) --- (continued)

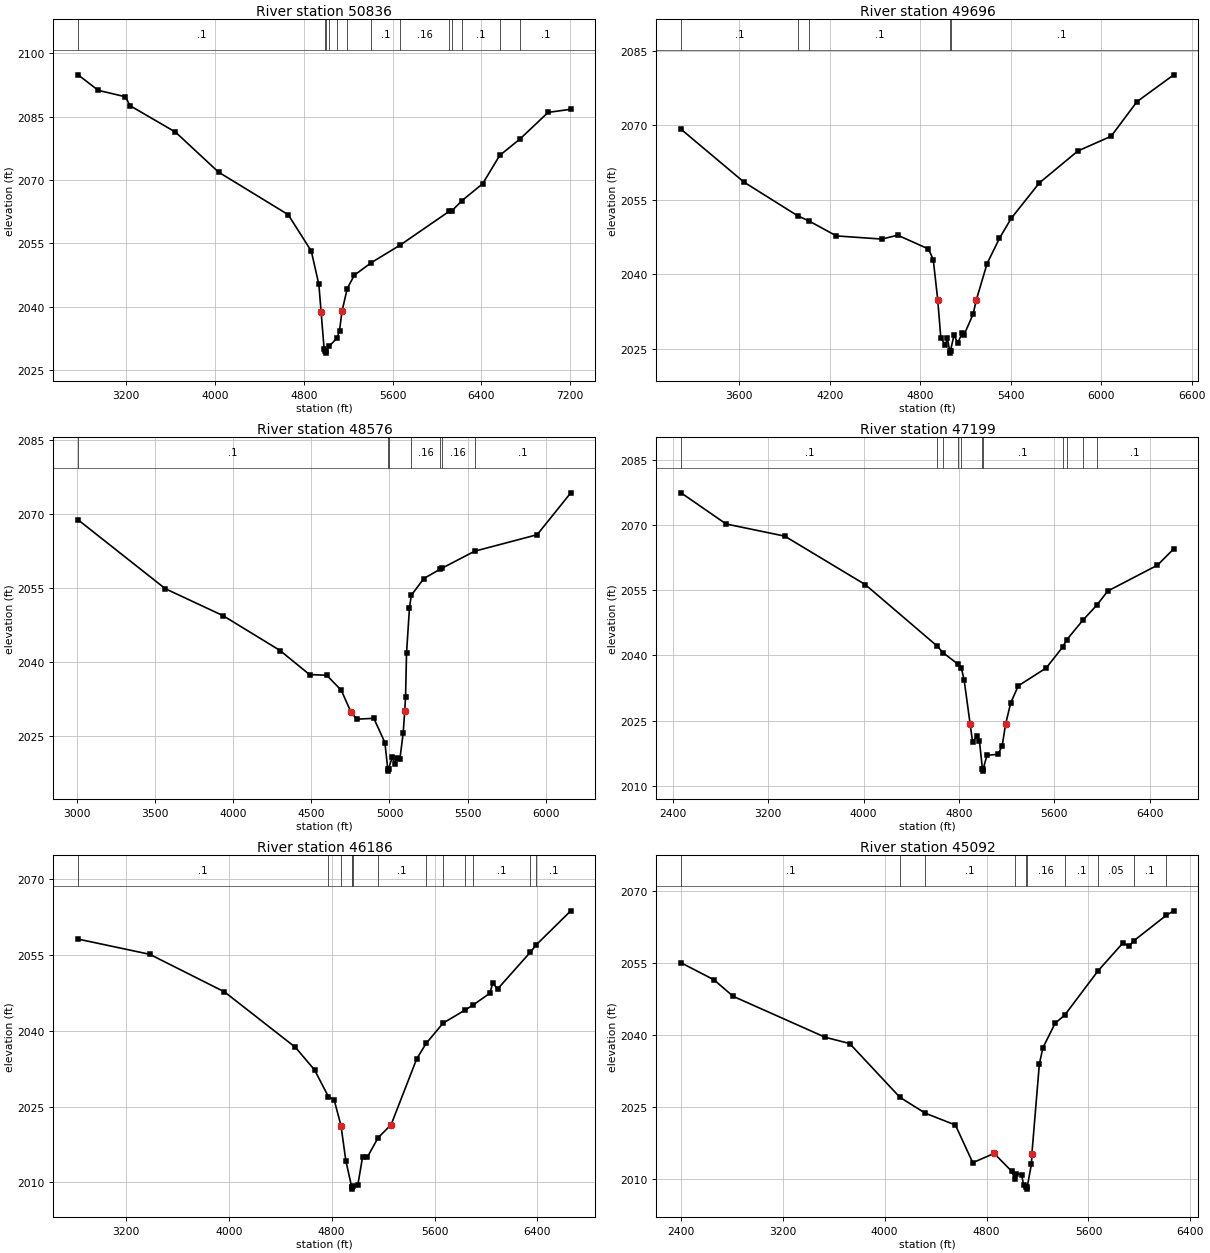
Type RM Length L Ch R = 1 ,50836   ,1140,1140,1140
BEGIN DESCRIPTION:
Mapping XS 1734c83e
END DESCRIPTION:
XS GIS Cut Line= 4
      2634145.63     10052294.58      2635690.77     10051200.83
      2635864.38     10050541.11      2634996.31     10048891.77
#Sta/Elev= 30
  2766.5 2094.87  2948.7  2091.2  3192.3 2089.69  3235.5 2087.56    3644 2081.33
  4031.9 2071.87  4659.6  2061.8  4867.6  2053.2  4935.8  2045.3  4956.5 2038.69
  4983.4 2029.99  4994.8 2029.56  4997.6 2029.06  5000.8 2029.56  5026.8 2030.63
  5100.5 2032.66  5121.9 2034.38  5144.7 2039.01  5191.7 2044.34  5255.4 2047.49
  5408.7 2050.46    5669 2054.62  6111.3 2062.61    6135 2062.74  6226.7 2065.15
    6412 2069.13  6564.6  2075.8  6745.5 2079.64  7001.3 2085.99  7205.6 2086.72
#Mann= 13 ,-1 , 0
  2766.5      .1       0  4994.8     .07       0  5000.8      .1       0
  5026.8     .16       0  5100.5      .1       0  5191.7     .16       0
  5408.7      .1       0    5669     .16       0  6111.3      .1       0
    6135     .16       0  6226.7      .1       0  6564.6     .16       0
  6745.5      .1       0
Bank Sta=4956.5,5144.7
XS Rating Curve= 0 ,0
Exp/Cntr=0.3,0.1

Type RM Length L Ch R = 1 ,49696   ,1120,1120,1120
BEGIN DESCRIPTION:
Mapping XS 0a3066ce
END DESCRIPTION:
XS GIS Cut Line= 4
      2636853.09     10052640.11      2636957.26     10051468.19
      2636670.81     10050140.07      2636592.69     10049410.95
#Sta/Elev= 30
  3212.8 2069.21  3630.8 2058.54  3986.9 2051.76  4063.2  2050.7  4243.2 2047.71
  4545.9 2047.07  4649.7 2047.86  4854.3 2045.08  4885.9 2042.94  4915.6 2034.86
  4936.1 2027.17  4966.8 2025.71  4979.3 2027.17  4994.5 2024.59  4997.2 2024.09
  5000.5 2024.59  5023.5  2027.7  5048.6 2026.16  5079.3 2028.23  5089.5 2027.71
  5150.9 2031.99  5171.4 2034.78    5243 2042.13  5324.8  2047.2  5402.5 2051.23
  5589.4 2058.38  5844.9 2064.82  6066.2  2067.8  6237.1 2074.76  6481.3 2080.17
#Mann= 5 ,-1 , 0
  3212.8      .1       0  3986.9     .05       0  4063.2      .1       0
  4994.5     .07       0  5000.5      .1       0
Bank Sta=4915.6,5171.4
XS Rating Curve= 0 ,0
Exp/Cntr=0.3,0.1

Type RM Length L Ch R = 1 ,48576   ,1377,1377,1377
BEGIN DESCRIPTION:
Mapping XS 6e63b437
END DESCRIPTION:
XS GIS Cut Line= 3
      2637113.51     10052718.21      2637894.76     10050582.77
      2638623.14     10050088.52
#Sta/Elev= 30
  3006.7 2068.81  3565.2 2054.85  3935.2 2049.38  4299.9 2042.32  4488.6 2037.44
  4598.1 2037.32  4691.6 2034.27  4752.7 2029.91  4789.7 2028.41    4900 2028.58
  4970.7 2023.67    4989 2018.38  4991.8 2017.88    4995 2018.38  5016.8 2020.65
  5034.6 2019.35  5047.3 2020.64  5066.6 2020.27  5087.9 2025.61  5097.7 2030.06
    5103 2032.83  5109.2 2041.75  5128.2 2051.02    5140 2053.52  5219.8 2056.91
  5324.2  2058.8  5336.1    2059  5545.3 2062.45  5945.2 2065.79  6160.8 2074.28
#Mann= 7 ,-1 , 0
  3006.7      .1       0    4989     .07       0    4995      .1       0
    5140     .16       0  5324.2      .1       0  5336.1     .16       0
  5545.3      .1       0
Bank Sta=4752.7,5097.7
XS Rating Curve= 0 ,0
Exp/Cntr=0.3,0.1

Type RM Length L Ch R = 1 ,47199   ,1013,1013,1013
BEGIN DESCRIPTION:
Mapping XS 2d1a1839
END DESCRIPTION:
XS GIS Cut Line= 4
      2637088.79     10053748.97      2637442.94     10052894.84
      2639567.94     10051019.84      2639588.66      10050646.8
#Sta/Elev= 30
  2469.2 2077.36  2847.6  2070.2  3339.2 2067.41  4014.7 2056.27    4620 2042.09
  4664.6 2040.67  4791.3    2038  4820.2 2037.09  4843.6 2034.36  4893.8 2024.24
  4914.7 2020.05  4949.8 2021.49  4971.6 2020.37    4997 2013.92  4999.8 2013.42
    5003 2013.92  5035.2 2017.06  5127.2 2017.28  5162.3 2019.17  5190.7 2024.14
  5233.4 2029.04    5297 2033.01  5531.3 2037.11  5669.3  2041.9  5702.6 2043.57
  5841.1 2048.15  5954.2  2051.5  6048.3  2054.8  6464.3 2060.73  6601.4 2064.49
#Mann= 11 ,-1 , 0
  2469.2      .1       0    4620     .16       0  4664.6      .1       0
  4791.3     .16       0  4820.2      .1       0    4997     .07       0
    5003      .1       0  5669.3     .16       0  5702.6      .1       0
  5841.1     .16       0  5954.2      .1       0
Bank Sta=4893.8,5190.7
XS Rating Curve= 0 ,0
Exp/Cntr=0.3,0.1

Type RM Length L Ch R = 1 ,46186   ,1094,1094,1094
BEGIN DESCRIPTION:
Mapping XS 828c4367
END DESCRIPTION:
XS GIS Cut Line= 2
      2638651.29     10054373.97       2640109.6     10050832.36
#Sta/Elev= 30
  2829.1 2058.12  3386.3 2055.11  3967.2 2047.68  4518.8 2036.71  4667.8 2032.23
  4775.3 2026.95  4819.2 2026.38  4873.3 2021.18  4874.7 2020.88  4910.4 2014.31
  4955.3 2009.17  4958.1 2008.67  4961.3 2009.17  4968.1 2009.26  5003.1 2009.39
    5041 2015.09  5078.8 2015.05  5161.2 2018.83  5262.6 2021.42    5462 2034.47
  5535.4 2037.51  5666.9 2041.51  5840.6 2044.14  5896.8 2045.03  6030.5 2047.42
  6052.1 2049.42  6090.7 2048.26  6345.4 2055.55  6392.4 2057.03  6659.2 2063.71
#Mann= 13 ,-1 , 0
  2829.1      .1       0  4775.3     .05       0  4874.7      .1       0
  4955.3     .07       0  4961.3      .1       0  4968.1     .16       0
  5161.2      .1       0  5535.4     .16       0  5666.9      .1       0
  5840.6     .16       0  5896.8      .1       0  6345.4     .16       0
  6392.4      .1       0
Bank Sta=4873.3,5262.6
XS Rating Curve= 0 ,0
Exp/Cntr=0.3,0.1

Type RM Length L Ch R = 1 ,45092   ,313,313,313
BEGIN DESCRIPTION:
Mapping XS 61826e65
END DESCRIPTION:
XS GIS Cut Line= 4
      2638755.42     10054561.52      2640338.77     10053394.84
      2640609.61     10052269.84      2641192.97     10051811.48
#Sta/Elev= 30
  2403.3    2055  2661.3 2051.47  2811.7 2048.02  3534.4 2039.48  3726.4 2038.17
  4120.6 2026.97  4319.8 2023.65  4556.1 2021.19  4692.2 2013.34  4859.9 2015.27
  4998.6 2011.53  5020.5 2010.03  5032.8 2011.06  5074.7 2010.83  5091.2 2008.77
  5113.7 2008.33  5116.4 2007.83  5119.7 2008.33  5152.9 2013.12 5156.25 2015.24
  5214.6  2033.9  5242.5 2037.29  5338.1 2042.38  5414.3 2044.12  5675.6 2053.34
  5872.2 2059.19  5915.5 2058.44    5955 2059.57  6210.4  2064.9  6269.1 2065.83
#Mann= 10 ,-1 , 0
  2403.3      .1       0  4120.6     .05       0  4319.8      .1       0
  5020.5     .16       0  5113.7     .07       0  5119.7     .16       0
  5414.3      .1       0  5675.6     .05       0    5955      .1       0
  6210.4     .16       0
Bank Sta=4859.9,5156.25
XS Rating Curve= 0 ,0
Exp/Cntr=0.3,0.1

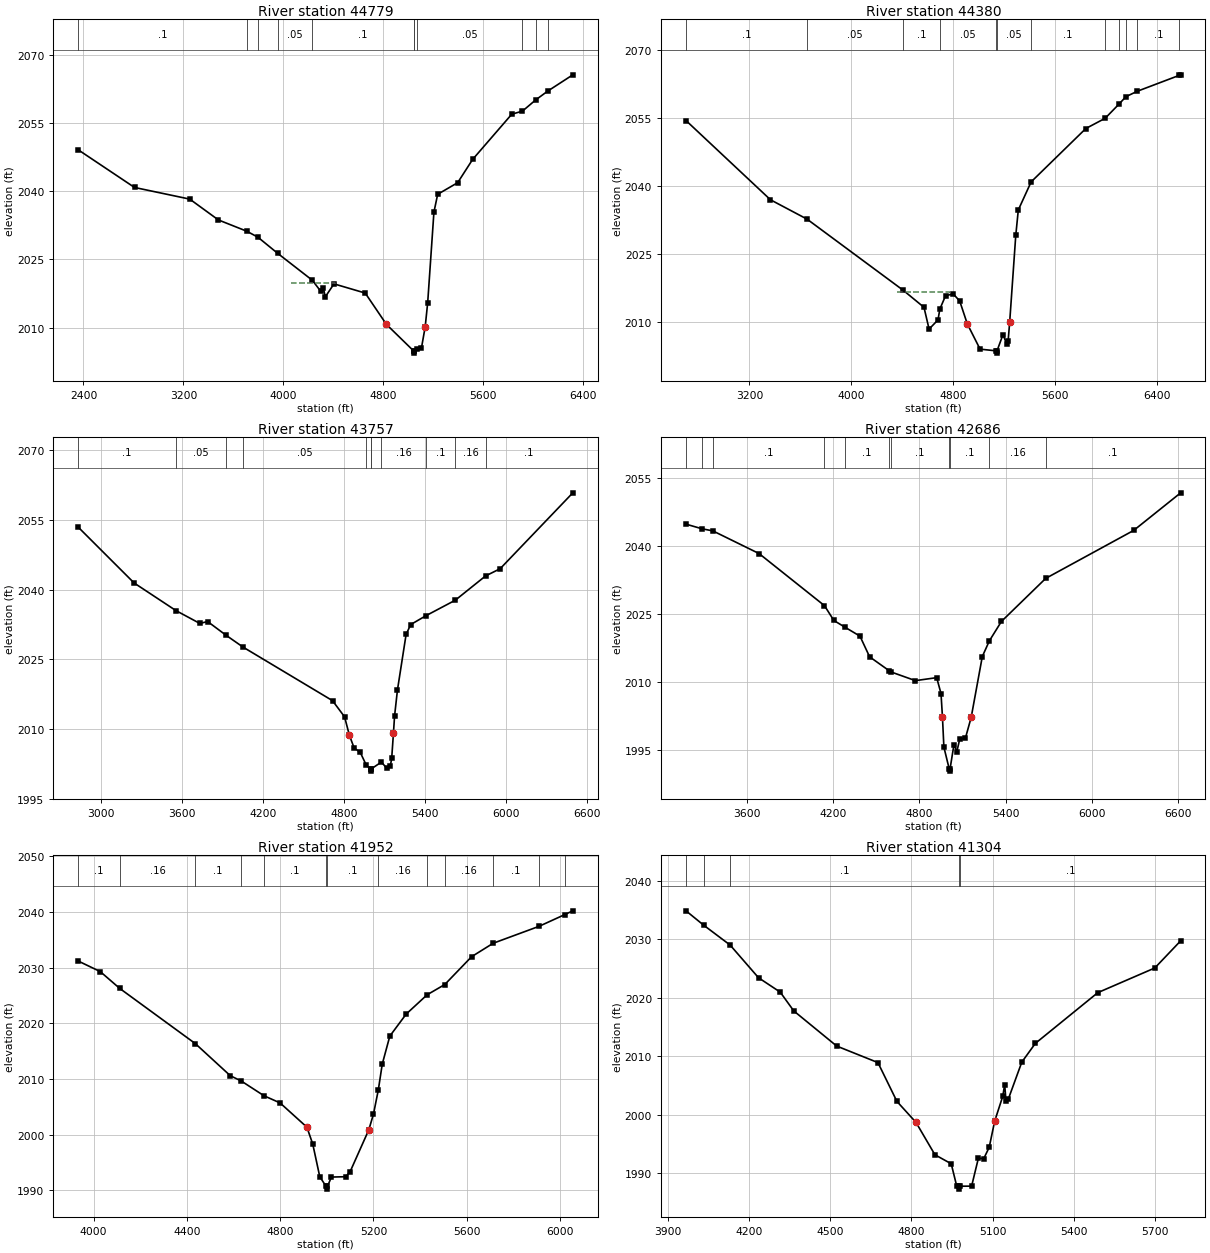
Type RM Length L Ch R = 1 ,44779   ,399,399,399
BEGIN DESCRIPTION:
Mapping XS ef9bfb69
END DESCRIPTION:
XS GIS Cut Line= 4
      2638997.09     10054544.01      2640740.12     10053599.58
       2640767.9     10052252.36       2641259.6     10051857.62
#Sta/Elev= 30
  2357.4 2049.11  2808.8 2040.82  3250.9 2038.26  3480.1 2033.68  3707.5  2031.2
  3796.8 2029.88  3956.5  2026.3    4232 2020.42  4298.9 2018.02  4320.8 2018.66
  4336.1 2016.76  4405.7 2019.62  4655.8  2017.6  4825.8  2010.7  5042.8 2004.89
  5045.6 2004.39  5048.8 2004.89    5073 2005.29  5105.9 2005.49  5135.9 2010.17
  5155.9 2015.47  5205.9  2035.4  5235.9 2039.32  5395.9 2041.87  5515.9 2046.99
  5829.1 2056.93  5914.6 2057.61    6021 2060.08    6118 2062.03  6317.9 2065.59
#Mann= 11 ,-1 , 0
  2357.4      .1       0  3707.5     .05       0  3796.8      .1       0
  3956.5     .05       0    4232      .1       0  5042.8     .07       0
  5048.8      .1       0    5073     .05       0  5914.6      .1       0
    6021     .16       0    6118      .1       0
#XS Ineff= 1 ,-1
  4062.5 4411.93  2019.8
Permanent Ineff=
       T
Bank Sta=4825.8,5135.9
XS Rating Curve= 0 ,0
Exp/Cntr=0.3,0.1

Type RM Length L Ch R = 1 ,44380   ,623,623,623
BEGIN DESCRIPTION:
Mapping XS 1b120163
END DESCRIPTION:
XS GIS Cut Line= 4
      2640295.66     10055377.39       2640955.4     10054127.36
      2640976.23     10052273.19      2641461.96     10051898.49
#Sta/Elev= 30
  2702.1 2054.42  3364.6 2036.98    3652 2032.71    4408 2017.01  4569.2  2013.3
  4609.2  2008.5  4679.2 2010.53  4693.7 2012.91  4739.2 2015.89  4799.2 2016.22
  4849.2 2014.71  4909.2 2009.64  5009.2 2004.09  5136.2 2003.71    5139 2003.21
  5142.2 2003.71  5189.2 2007.29  5219.2 2005.13  5229.2 2005.81 5241.48 2009.99
  5289.3 2029.12  5309.3 2034.74    5410 2040.92  5839.3 2052.67  5990.7 2054.92
  6101.6 2058.11  6153.6 2059.68  6244.4 2060.89  6573.5 2064.39  6583.3 2064.49
#Mann= 12 ,-1 , 0
  2702.1      .1       0    3652     .05       0    4408      .1       0
  4693.7     .05       0  5136.2     .04       0  5142.2     .05       0
    5410      .1       0  5990.7     .16       0  6101.6      .1       0
  6153.6     .16       0  6244.4      .1       0  6573.5     .16       0
#XS Ineff= 1 ,-1
 4357.95 4772.73 2016.73
Permanent Ineff=
       T
Bank Sta=4909.2,5241.48
XS Rating Curve= 0 ,0
Exp/Cntr=0.3,0.1

Type RM Length L Ch R = 1 ,43757   ,1071,1071,1071
BEGIN DESCRIPTION:
Mapping XS 475c4247
END DESCRIPTION:
XS GIS Cut Line= 3
      2640359.63     10055394.81      2641630.44     10053290.67
      2641672.11     10052082.31
#Sta/Elev= 30
  2830.8 2053.42  3245.6 2041.41  3556.1 2035.47  3732.7 2032.72  3790.9 2033.12
    3928 2030.16  4053.9 2027.62  4716.6 2016.12  4805.9 2012.65  4841.4  2008.7
  4876.5 2005.98  4922.3    2005  4967.6 2002.22  4998.9 2001.48  5001.6 2000.98
  5004.9 2001.48  5079.5 2002.94  5118.3 2001.58  5145.5 2002.15  5155.2 2003.71
  5168.5 2009.25  5176.5 2012.81  5197.9 2018.41    5262 2030.34  5295.9 2032.47
  5410.1 2034.39  5626.9 2037.71  5851.1 2042.92  5959.2 2044.47    6498 2060.78
#Mann= 11 ,-1 , 0
  2830.8      .1       0  3556.1     .05       0    3928      .1       0
  4053.9     .05       0  4967.6      .1       0  4998.9     .07       0
  5004.9      .1       0  5079.5     .16       0  5410.1      .1       0
  5626.9     .16       0  5851.1      .1       0
Bank Sta=4841.4,5168.5
XS Rating Curve= 0 ,0
Exp/Cntr=0.3,0.1

Type RM Length L Ch R = 1 ,42686   ,734,734,734
BEGIN DESCRIPTION:
KLEIN BRANCH 70.0
END DESCRIPTION:
XS GIS Cut Line= 3
      2641734.62     10055748.98      2642338.77     10054394.84
      2642422.06     10052437.61
#Sta/Elev= 30
    3176 2044.84  3289.6  2043.8  3362.3 2043.36  3684.3 2038.34  4139.4 2026.82
  4204.8 2023.54  4283.2 2022.03  4386.3 2020.08  4453.4 2015.51  4589.1 2012.44
  4603.4 2012.15  4772.1 2010.24  4920.1  2010.9  4950.2 2007.39  4960.2 2002.24
  4970.2 1995.55  5007.2 1990.73    5010 1990.23  5013.2 1990.73  5040.3 1996.11
  5060.3 1994.56  5080.3 1997.28  5120.3 1997.55  5160.4 2002.16  5237.5 2015.56
  5286.5 2019.03  5370.6 2023.33  5678.8 2032.85  6291.4 2043.47  6617.8 2051.77
#Mann= 11 ,-1 , 0
    3176      .1       0  3289.6     .16       0  3362.3      .1       0
  4139.4     .16       0  4283.2      .1       0  4589.1     .16       0
  4603.4      .1       0  5007.2     .07       0  5013.2      .1       0
  5286.5     .16       0  5678.8      .1       0
Bank Sta=4960.2,5160.4
XS Rating Curve= 0 ,0
Exp/Cntr=0.3,0.1

Type RM Length L Ch R = 1 ,41952   ,648,648,648
BEGIN DESCRIPTION:
KLEIN BRANCH 69.0
END DESCRIPTION:
XS GIS Cut Line= 2
      2643003.27     10055218.23      2643133.47     10053100.23
#Sta/Elev= 30
  3933.4 2031.21  4028.1 2029.31  4112.1 2026.27    4436 2016.36  4586.3 2010.58
  4632.6 2009.65  4730.9 2006.98  4799.5  2005.7  4914.6 2001.34  4939.8  1998.3
  4969.9 1992.43  4996.9  1990.7  4999.7  1990.2  5002.9  1990.7  5019.9 1992.37
  5081.3 1992.43  5100.1 1993.34  5180.3 2000.87  5200.3 2003.69    5221 2008.02
  5237.9 2012.67  5270.4 2017.71  5340.6 2021.67  5430.5 2025.14  5506.1 2026.98
  5621.1 2031.98  5713.7  2034.4  5910.3 2037.44  6020.2 2039.54  6055.4 2040.23
#Mann= 13 ,-1 , 0
  3933.4      .1       0  4112.1     .16       0    4436      .1       0
  4632.6     .16       0  4730.9      .1       0  4996.9     .07       0
  5002.9      .1       0    5221     .16       0  5430.5      .1       0
  5506.1     .16       0  5713.7      .1       0  5910.3     .16       0
  6020.2      .1       0
Bank Sta=4914.6,5180.3
XS Rating Curve= 0 ,0
Exp/Cntr=0.3,0.1

Type RM Length L Ch R = 1 ,41304   ,898,898,898
BEGIN DESCRIPTION:
KLEIN BRANCH 68.0
END DESCRIPTION:
XS GIS Cut Line= 2
      2643628.27     10055200.84      2643775.81      10053378.3
#Sta/Elev= 30
  3967.1 2034.88  4031.9 2032.44  4130.2 2029.02  4235.1 2023.43  4315.3 2020.97
  4365.5 2017.75  4524.1 2011.74  4676.5 2008.91  4746.7 2002.27    4817 1998.69
  4887.2 1993.14  4947.4  1991.6  4967.5 1987.82  4974.5 1987.76  4977.3 1987.26
  4980.5 1987.76  5022.8 1987.77  5047.7 1992.53  5067.8 1992.49  5087.9 1994.43
  5107.9 1998.87    5138 2003.16    5145 2005.15    5150 2002.27  5158.1 2002.62
  5208.3 2008.99  5258.4  2012.2  5489.2 2020.88  5699.9  2025.1  5795.6 2029.75
#Mann= 5 ,-1 , 0
  3967.1      .1       0  4031.9     .16       0  4130.2      .1       0
  4974.5     .07       0  4980.5      .1       0
Bank Sta=4817,5107.9
XS Rating Curve= 0 ,0
Exp/Cntr=0.3,0.1

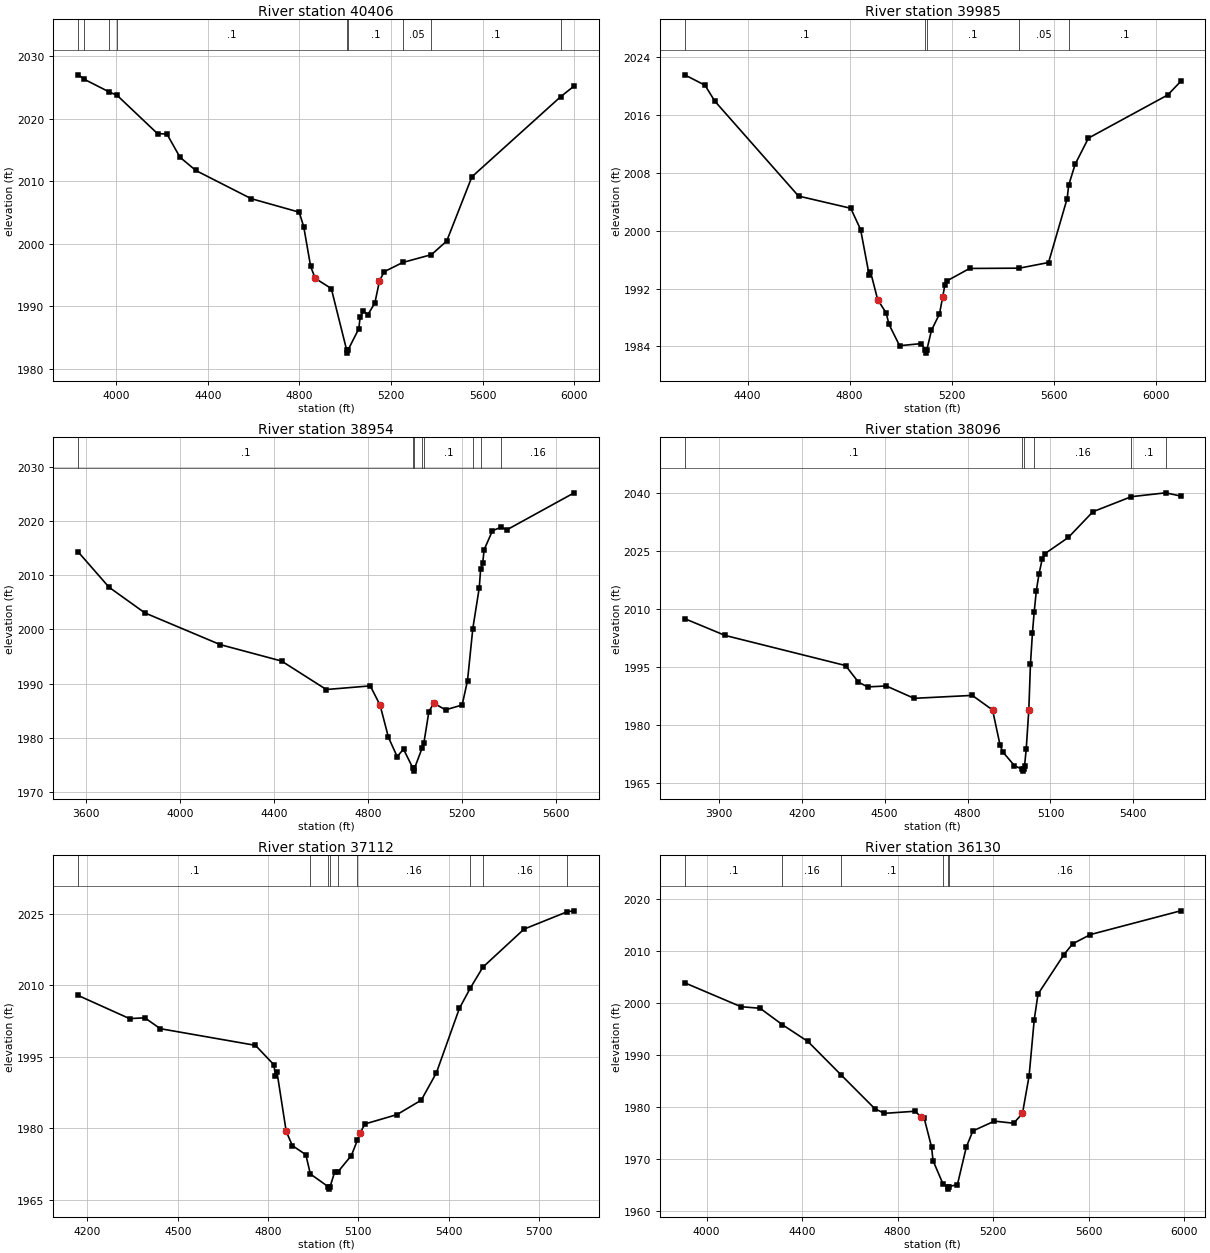
Type RM Length L Ch R = 1 ,40406   ,421,421,421
BEGIN DESCRIPTION:
KLEIN BRANCH 67.0
END DESCRIPTION:
XS GIS Cut Line= 4
      2644261.96     10055287.63      2644591.81     10054558.47
      2644548.41     10053898.75      2644253.92     10053257.81
#Sta/Elev= 30
  3833.4 2027.01  3860.8 2026.28  3966.7 2024.31  4003.8 2023.71  4180.1 2017.59
  4220.8 2017.55    4278 2013.82  4347.3  2011.7  4589.3 2007.19  4798.8 2005.03
  4818.8 2002.68  4848.9 1996.34  4868.9 1994.44  4939.1 1992.81  5006.2 1982.97
    5009 1982.47  5012.2 1982.97  5059.4 1986.38  5064.9 1988.18  5079.4 1989.18
  5099.4 1988.65  5129.5  1990.5  5149.5 1993.99  5169.6 1995.49  5251.4 1996.98
  5376.7 1998.23  5443.4 2000.41  5553.5 2010.69    5941  2023.5  6000.2 2025.22
#Mann= 9 ,-1 , 0
  3833.4     .16       0  3860.8      .1       0  3966.7     .16       0
  4003.8      .1       0  5006.2     .07       0  5012.2      .1       0
  5251.4     .05       0  5376.7      .1       0    5941     .16       0
Bank Sta=4868.9,5149.5
XS Rating Curve= 0 ,0
Exp/Cntr=0.3,0.1

Type RM Length L Ch R = 1 ,39985   ,1031,1031,1031
BEGIN DESCRIPTION:
KLEIN BRANCH 66.0
END DESCRIPTION:
XS GIS Cut Line= 2
      2645216.82     10054931.77      2644670.42     10053067.08
#Sta/Elev= 30
  4153.5  2021.6  4233.1 2020.16  4271.7 2017.95  4599.5 2004.82  4804.1 2003.13
  4842.8 2000.18  4876.2 1993.91  4881.4 1994.37  4909.6 1990.49    4943 1988.63
  4953.8 1987.08  4995.5 1984.11  5078.9 1984.39  5096.7 1983.58  5099.5 1983.08
  5102.7 1983.58  5120.5 1986.25  5151.8  1988.5  5164.3 1990.84  5172.7 1992.49
  5183.1 1993.12  5269.8  1994.8  5464.6 1994.84  5579.1 1995.62    5652 2004.47
  5658.2 2006.34  5683.3 2009.22  5735.4 2012.84  6046.5 2018.82  6096.6 2020.68
#Mann= 5 ,-1 , 0
  4153.5      .1       0  5096.7     .07       0  5102.7      .1       0
  5464.6     .05       0  5658.2      .1       0
Bank Sta=4909.6,5164.3
XS Rating Curve= 0 ,0
Exp/Cntr=0.3,0.1

Type RM Length L Ch R = 1 ,38954   ,858,858,858
BEGIN DESCRIPTION:
KLEIN BRANCH 65.0
END DESCRIPTION:
XS GIS Cut Line= 4
      2645702.92     10054636.62      2645789.73     10053534.16
      2645216.81     10053100.14      2645225.49     10052813.69
#Sta/Elev= 30
  3567.2 2014.26  3698.5 2007.76    3851 2003.03    4172 1997.18  4432.8 1994.16
  4623.3 1988.91  4810.5 1989.58  4852.1 1986.04  4887.9 1980.09  4924.9 1976.55
    4952 1977.91  4992.6 1974.37  4995.4 1973.87  4998.6 1974.37  5031.6 1978.17
  5038.8 1979.09  5060.1 1984.85  5080.9 1986.39  5130.9 1985.16  5201.6 1986.06
  5224.5 1990.56    5247 2000.15  5274.4 2007.65  5280.3 2011.08    5289 2012.17
  5295.2 2014.68  5330.6 2018.17  5367.5 2018.83  5391.8 2018.34  5678.4 2025.16
#Mann= 8 ,-1 , 0
  3567.2      .1       0  4992.6     .07       0  4998.6      .1       0
  5031.6     .05       0  5038.8      .1       0    5247     .16       0
  5280.3      .1       0  5367.5     .16       0
Bank Sta=4852.1,5080.9
XS Rating Curve= 0 ,0
Exp/Cntr=0.3,0.1

Type RM Length L Ch R = 1 ,38096   ,984,984,984
BEGIN DESCRIPTION:
KLEIN BRANCH 63.0
END DESCRIPTION:
XS GIS Cut Line= 3
      2645841.81     10054489.01      2645911.26     10053837.98
      2646509.31     10052867.23
#Sta/Elev= 30
  3776.2 2007.51  3922.3 2003.17  4358.6 1995.36    4405 1991.06  4438.5 1989.83
  4505.9 1990.07  4606.5 1986.87    4817 1987.63  4890.4 1983.86  4917.5  1974.8
  4927.1 1973.02  4969.6 1969.43  4996.7 1968.51  4999.4 1968.01  5002.7 1968.51
  5006.3 1969.35  5012.2 1973.63  5021.7 1983.86  5027.6 1995.69  5034.9 2003.91
  5041.1  2009.2  5048.9 2014.75  5058.4 2019.03  5070.2 2022.96  5079.7 2024.33
  5164.8 2028.55  5253.6 2035.21  5392.6 2039.11  5517.1 2040.11  5571.1 2039.28
#Mann= 6 ,-1 , 0
  3776.2      .1       0  4996.7     .07       0  5002.7      .1       0
  5041.1     .16       0  5392.6      .1       0  5517.1     .16       0
Bank Sta=4890.4,5021.7
XS Rating Curve= 0 ,0
Exp/Cntr=0.3,0.1

Type RM Length L Ch R = 1 ,37112   ,982,982,982
BEGIN DESCRIPTION:
KLEIN BRANCH 61.0
END DESCRIPTION:
XS GIS Cut Line= 3
      2646761.95     10054740.75      2646987.65     10053638.33
      2646935.62     10053118.11
#Sta/Elev= 30
  4169.4 2007.83  4339.9 2002.99  4390.9 2003.15    4442 2000.88  4758.4 1997.39
  4819.6 1993.33  4824.9 1990.94    4830 1991.79  4860.5  1979.4  4880.9  1976.4
  4925.8 1974.49  4940.9 1970.45  5000.4 1967.78  5003.1 1967.28  5006.4 1967.78
  5021.6 1970.85  5032.4  1970.9  5077.2 1974.32  5097.1 1977.52  5105.4 1978.97
  5122.5 1980.93  5228.5 1982.88  5309.4 1985.91  5359.6 1991.62  5436.1 2005.13
  5472.5 2009.39  5514.3 2013.77    5651 2021.73  5794.6 2025.37  5817.5 2025.56
#Mann= 9 ,-1 , 0
  4169.4      .1       0  4940.9     .16       0  5000.4     .07       0
  5006.4     .16       0  5032.4      .1       0  5097.1     .16       0
  5472.5      .1       0  5514.3     .16       0  5794.6      .1       0
Bank Sta=4860.5,5105.4
XS Rating Curve= 0 ,0
Exp/Cntr=0.3,0.1

Type RM Length L Ch R = 1 ,36130   ,1115,1115,1115
BEGIN DESCRIPTION:
KLEIN BRANCH 59.0
END DESCRIPTION:
XS GIS Cut Line= 3
      2647925.15     10054749.44      2647951.19     10053924.79
      2647326.17     10052839.69
#Sta/Elev= 30
    3908  2003.9  4143.8  1999.3  4223.9    1999  4317.6 1995.83    4424 1992.62
  4562.6 1986.21  4704.1  1979.7  4744.3 1978.79  4873.6  1979.2  4895.8 1978.18
    4911 1977.89    4942 1972.34  4948.3 1969.69  4990.1  1965.2    5010 1964.72
  5012.8 1964.22    5016 1964.72  5050.4 1965.09  5087.7 1972.32  5115.1 1975.41
  5205.5  1977.3    5286 1976.89  5322.8 1978.77  5350.6 1985.97  5372.2 1996.83
    5388 2001.73  5495.9 2009.28  5533.1  2011.4  5607.8 2013.18  5985.3 2017.74
#Mann= 6 ,-1 , 0
    3908      .1       0  4317.6     .16       0  4562.6      .1       0
  4990.1     .16       0    5010     .07       0    5016     .16       0
Bank Sta=4895.8,5322.8
XS Rating Curve= 0 ,0
Exp/Cntr=0.3,0.1

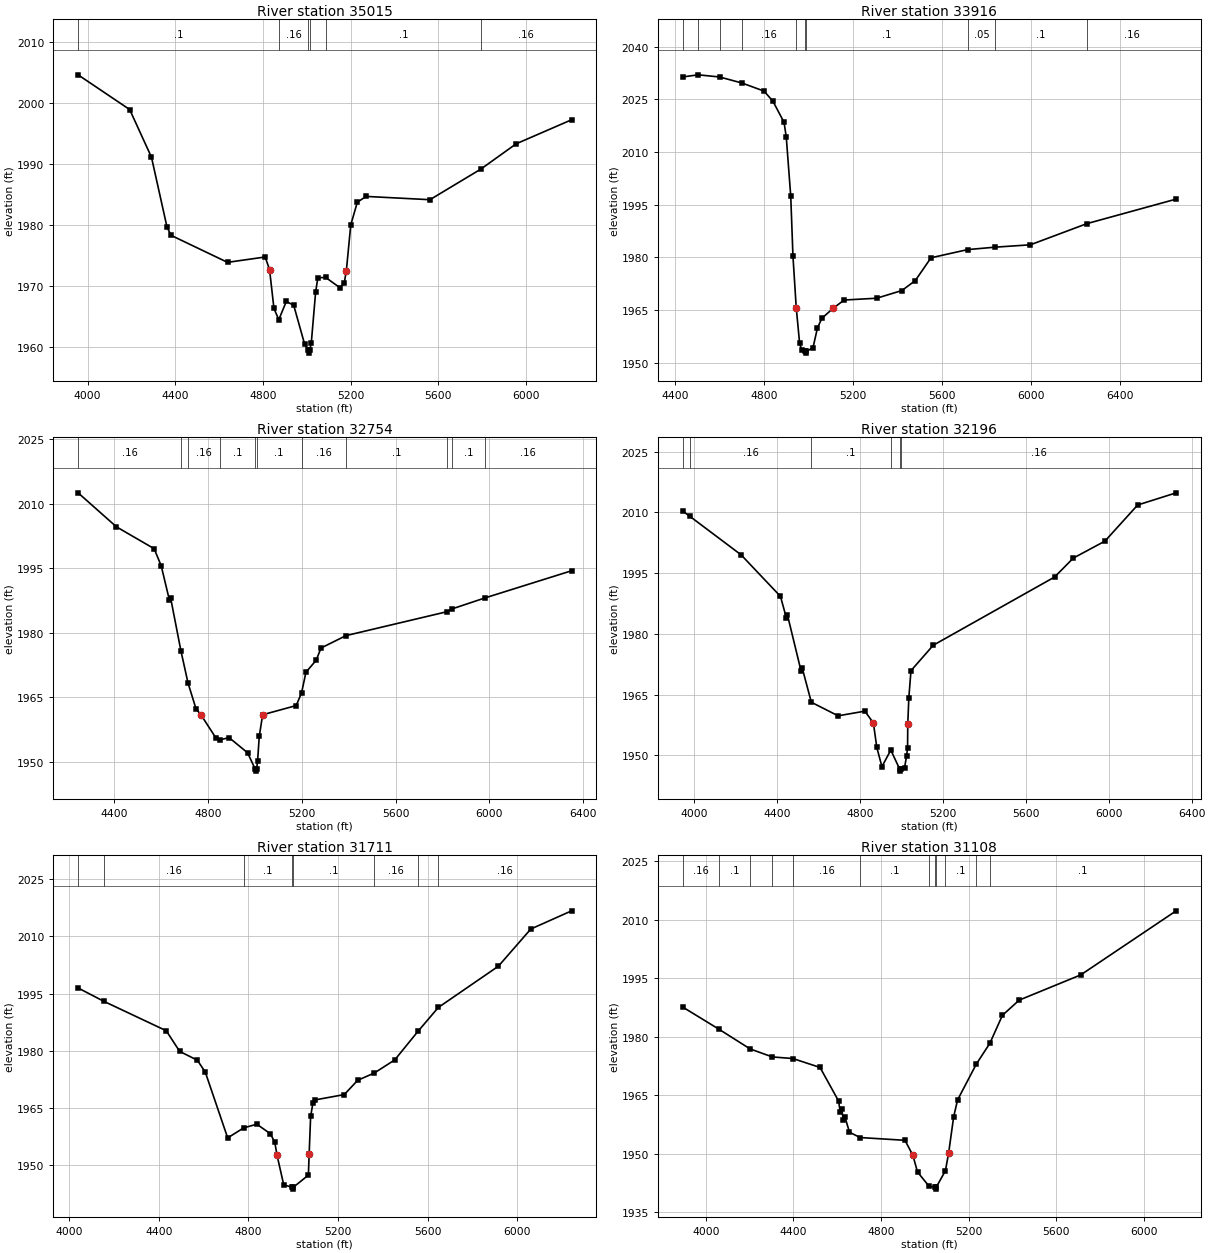
Type RM Length L Ch R = 1 ,35015   ,1099,1099,1099
BEGIN DESCRIPTION:
KLEIN BRANCH 58.0
END DESCRIPTION:
XS GIS Cut Line= 4
      2648715.07     10054480.37      2648871.33      10053742.5
      2648845.28     10053091.45       2648056.8     10052788.19
#Sta/Elev= 30
  3956.8 2004.64    4192 1998.94  4291.4 1991.11  4362.2 1979.65  4380.5 1978.28
  4638.2 1973.84  4809.9 1974.72  4829.9 1972.65  4849.9 1966.28    4872 1964.42
  4906.3 1967.41    4940  1966.8    4990 1960.38    5007 1959.43  5009.8 1958.93
    5013 1959.43  5020.1 1960.54  5040.1 1968.99  5050.1  1971.3  5085.5 1971.37
  5150.2 1969.69  5170.2 1970.39  5180.2 1972.48  5200.2 1979.98  5230.2 1983.72
  5270.3 1984.67  5561.3 1984.13  5794.1 1989.17  5954.5 1993.31  6207.4 1997.26
#Mann= 6 ,-1 , 0
  3956.8      .1       0    4872     .16       0    5007     .07       0
    5013     .16       0  5085.5      .1       0  5794.1     .16       0
Bank Sta=4829.9,5180.2
XS Rating Curve= 0 ,0
Exp/Cntr=0.3,0.1

Type RM Length L Ch R = 1 ,33916   ,1162,1162,1162
BEGIN DESCRIPTION:
KLEIN BRANCH 55.0
END DESCRIPTION:
XS GIS Cut Line= 3
      2650234.18     10052961.25      2649131.74     10052995.97
      2648046.64     10052735.54
#Sta/Elev= 30
  4432.8 2031.34  4502.9 2031.94  4598.8 2031.33  4700.5 2029.59  4798.7 2027.31
  4838.7 2024.43  4888.7 2018.43  4898.7 2014.26  4918.8 1997.44  4928.8 1980.31
  4943.5 1965.72  4958.8 1955.49  4968.8 1953.52    4983 1953.25  4985.8 1952.75
    4989 1953.25  5018.8 1954.27  5038.8 1959.89  5058.8 1962.67  5108.8 1965.47
  5158.9 1967.86  5304.9 1968.37    5419 1970.57    5479 1973.41  5549.4 1979.88
  5714.3 1982.21  5839.4 1982.91    5996 1983.57  6250.5  1989.6  6651.7 1996.58
#Mann= 10 ,-1 , 0
  4432.8      .1       0  4502.9     .16       0  4598.8      .1       0
  4700.5     .16       0  4943.5      .1       0    4983     .07       0
    4989      .1       0  5714.3     .05       0  5839.4      .1       0
  6250.5     .16       0
Bank Sta=4943.5,5108.8
XS Rating Curve= 0 ,0
Exp/Cntr=0.3,0.1

Type RM Length L Ch R = 1 ,32754   ,558,558,558
BEGIN DESCRIPTION:
KLEIN BRANCH 53.0
END DESCRIPTION:
XS GIS Cut Line= 4
      2649791.42     10051902.21      2649287.99     10051858.82
       2648706.4     10052605.34      2648055.35     10052640.07
#Sta/Elev= 30
  4246.9 2012.49  4410.5 2004.59  4571.1 1999.52  4601.2 1995.54  4636.5  1987.5
  4641.5 1988.04  4685.1 1975.83  4715.4 1968.35  4749.4 1962.37  4770.3 1960.98
  4834.5 1955.56  4853.4 1955.17  4890.6 1955.66  4969.3 1952.14  5001.6 1948.38
  5004.4 1947.88  5007.6 1948.38    5012 1950.18  5019.1 1955.97  5033.6 1960.97
  5176.5  1963.1  5199.3 1966.02  5218.1 1970.85  5261.6 1973.61  5282.4 1976.46
  5388.8 1979.34  5820.7 1984.91  5840.8 1985.54  5979.9 1988.07  6350.5  1994.4
#Mann= 11 ,-1 , 0
  4246.9     .16       0  4685.1      .1       0  4715.4     .16       0
  4853.4      .1       0  5001.6     .07       0  5007.6      .1       0
  5199.3     .16       0  5388.8      .1       0  5820.7     .16       0
  5840.8      .1       0  5979.9     .16       0
Bank Sta=4770.3,5033.6
XS Rating Curve= 0 ,0
Exp/Cntr=0.3,0.1

Type RM Length L Ch R = 1 ,32196   ,485,485,485
BEGIN DESCRIPTION:
KLEIN BRANCH 52.0
END DESCRIPTION:
XS GIS Cut Line= 4
      2649808.78       10051772.       2649105.7     10051563.68
      2648341.81     10051754.65       2647482.9     10051711.27
#Sta/Elev= 30
  3944.7 2010.34  3979.9 2009.01  4226.6 1999.52  4416.7 1989.25  4444.7    1984
  4449.9 1984.75  4516.4 1970.73  4521.6 1971.56  4565.5 1963.11  4694.7 1959.76
  4823.6 1960.91  4864.8    1958  4881.3 1951.97    4906  1947.2  4948.8  1951.3
  4991.7  1946.6  4994.4  1946.1  4997.7  1946.6  5015.3 1946.95  5024.6 1949.76
  5029.7 1951.72 5030.68 1957.72  5035.9 1964.28  5046.2 1970.91  5153.4 1977.18
  5739.1 1994.04  5829.2 1998.71  5981.8  2002.9  6139.6 2011.82  6325.4 2014.83
#Mann= 6 ,-1 , 0
  3944.7      .1       0  3979.9     .16       0  4565.5      .1       0
  4948.8     .16       0  4991.7     .07       0  4997.7     .16       0
Bank Sta=4864.8,5030.68
XS Rating Curve= 0 ,0
Exp/Cntr=0.3,0.1

Type RM Length L Ch R = 1 ,31711   ,603,603,603
BEGIN DESCRIPTION:
KLEIN BRANCH 51.0
END DESCRIPTION:
XS GIS Cut Line= 4
      2649652.56     10051433.46      2649183.83     10051181.73
      2648341.81     10051164.37      2647586.57     10051502.93
#Sta/Elev= 30
  4040.1 1996.49  4153.5 1993.03  4433.4 1985.28  4493.5 1979.86  4572.1 1977.56
  4607.5 1974.46  4707.5  1957.2  4778.9 1959.83  4837.6 1960.79  4897.6 1958.31
  4917.6 1956.09  4927.6 1952.67  4957.6  1944.9  4994.6 1944.28  4997.3 1943.78
  5000.6 1944.28  5067.6 1947.45 5071.02 1953.02  5077.6 1962.81  5087.6 1966.28
  5097.6 1967.16  5227.6 1968.55  5287.7  1972.3  5362.1 1974.22  5452.9 1977.64
  5556.1 1985.09  5647.1 1991.37  5915.3 2002.19  6059.9 2011.93    6242  2016.7
#Mann= 8 ,-1 , 0
  4040.1      .1       0  4153.5     .16       0  4778.9      .1       0
  4994.6     .07       0  5000.6      .1       0  5362.1     .16       0
  5556.1      .1       0  5647.1     .16       0
Bank Sta=4927.6,5071.02
XS Rating Curve= 0 ,0
Exp/Cntr=0.3,0.1

Type RM Length L Ch R = 1 ,31108   ,1214,1214,1214
BEGIN DESCRIPTION:
KLEIN BRANCH 50.0
END DESCRIPTION:
XS GIS Cut Line= 4
       2649464.4     10051134.48      2648874.15      10050552.9
      2647988.73     10050778.59      2647615.44     10051125.84
#Sta/Elev= 30
  3894.2  1987.6  4060.2 1981.89  4202.6 1976.83  4303.5 1974.79    4397 1974.38
  4521.2 1972.09    4606 1963.46  4613.1 1960.67  4620.2 1961.45  4627.3 1958.53
  4634.3 1959.47  4655.6 1955.46  4704.2  1954.1  4908.8 1953.39  4944.6 1949.57
  4966.1 1945.26  5019.3 1941.55  5045.6 1941.36  5048.4 1940.86  5051.6 1941.36
  5093.3 1945.57  5108.1 1950.14  5131.2 1959.49    5149 1963.77  5234.6 1972.97
  5296.2 1978.29  5353.4 1985.46    5430 1989.37  5711.1 1995.85  6146.4 2012.29
#Mann= 12 ,-1 , 0
  3894.2     .16       0  4060.2      .1       0  4202.6     .05       0
  4303.5      .1       0    4397     .16       0  4704.2      .1       0
  5019.3     .05       0  5045.6     .07       0  5051.6     .05       0
  5093.3      .1       0  5234.6     .16       0  5296.2      .1       0
Bank Sta=4944.6,5108.1
XS Rating Curve= 0 ,0
Exp/Cntr=0.3,0.1

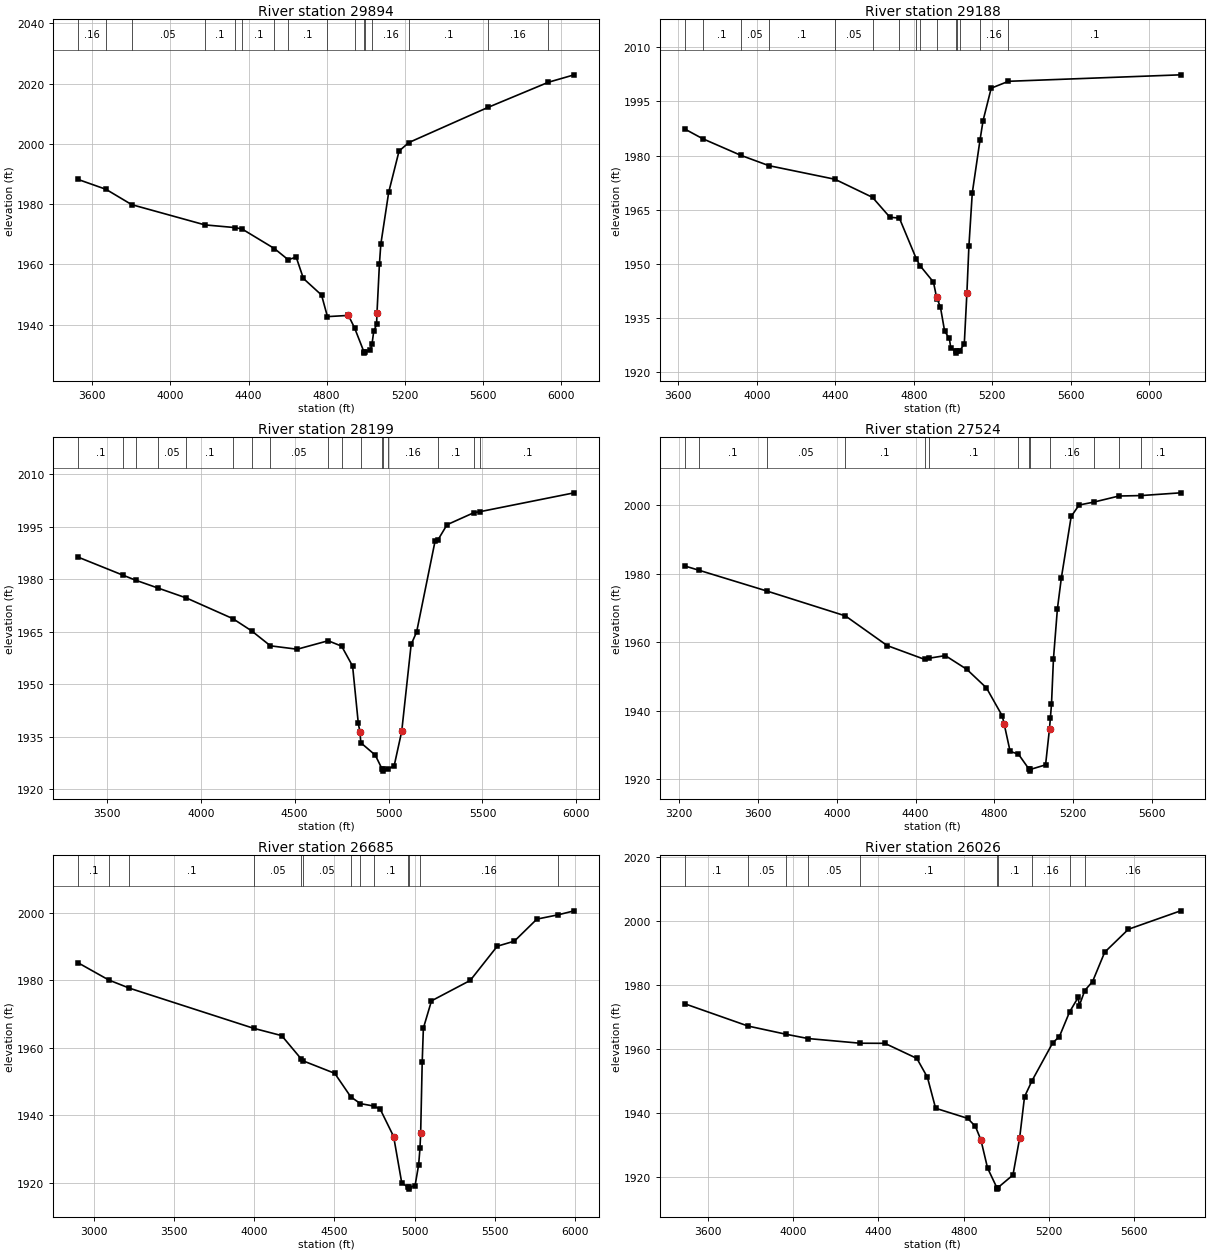
Type RM Length L Ch R = 1 ,29894   ,706,706,706
BEGIN DESCRIPTION:
KLEIN BRANCH 48.0
END DESCRIPTION:
XS GIS Cut Line= 2
      2649568.59     10051073.72       2648587.7     10048730.01
#Sta/Elev= 30
  3527.3 1988.19  3669.6 1984.93  3801.3 1979.84  4176.1 1973.12  4330.7 1972.22
    4367 1971.74  4532.3 1965.26  4603.2 1961.54  4643.9 1962.43    4681 1955.32
  4773.9 1949.82  4804.1 1942.66  4911.4 1943.06  4942.8 1938.97  4990.6 1931.04
  4993.4 1930.54  4996.6 1931.04  5023.3 1931.43  5032.8 1933.73  5041.2 1937.77
  5055.8 1940.05 5057.95 1943.88  5070.4 1960.14  5077.5 1966.68    5118 1983.98
    5171 1997.64  5221.3 2000.46  5625.9 2012.11  5936.5 2020.49    6068 2022.94
#Mann= 16 ,-1 , 0
  3527.3     .16       0  3669.6      .1       0  3801.3     .05       0
  4176.1      .1       0  4330.7     .05       0    4367      .1       0
  4532.3     .05       0  4603.2      .1       0  4804.1     .05       0
  4942.8      .1       0  4990.6     .07       0  4996.6      .1       0
  5032.8     .16       0  5221.3      .1       0  5625.9     .16       0
  5936.5      .1       0
Bank Sta=4911.4,5057.95
XS Rating Curve= 0 ,0
Exp/Cntr=0.3,0.1

Type RM Length L Ch R = 1 ,29188   ,989,989,989
BEGIN DESCRIPTION:
KLEIN BRANCH 46.0
END DESCRIPTION:
XS GIS Cut Line= 2
       2650011.3     10050856.72      2649377.62     10048408.81
#Sta/Elev= 30
    3632 1987.35  3723.1 1984.67  3917.5 1980.07  4061.5 1977.19  4398.1 1973.43
  4589.7 1968.42  4678.4 1962.91  4726.6 1962.68  4813.4 1951.36  4831.5 1949.55
  4900.4 1944.97    4916 1940.83  4919.5 1940.26  4935.8 1938.11  4957.3  1931.4
  4981.6 1929.37  4988.3 1926.84    5014 1925.81  5016.8 1925.31    5020 1925.81
  5034.9 1926.01  5057.6 1927.85  5070.9 1941.92  5081.2 1954.94  5098.3 1969.62
  5137.7 1984.26  5153.5 1989.69  5194.9 1998.64    5283 2000.54  6160.6 2002.33
#Mann= 15 ,-1 , 0
    3632     .16       0  3723.1      .1       0  3917.5     .05       0
  4061.5      .1       0  4398.1     .05       0  4589.7      .1       0
  4726.6     .16       0  4813.4      .1       0  4831.5     .16       0
  4919.5      .1       0    5014     .07       0    5020      .1       0
  5034.9     .05       0  5137.7     .16       0    5283      .1       0
Bank Sta=4916,5070.9
XS Rating Curve= 0 ,0
Exp/Cntr=0.3,0.1

Type RM Length L Ch R = 1 ,28199   ,675,675,675
BEGIN DESCRIPTION:
KLEIN BRANCH 45.0
END DESCRIPTION:
XS GIS Cut Line= 3
      2650332.49     10050926.14      2650644.98     10049650.12
      2650506.09     10048330.64
#Sta/Elev= 30
  3347.7  1986.3  3586.5 1981.14  3652.8 1979.73  3769.9 1977.52  3923.6 1974.63
  4170.7 1968.73  4270.9 1965.23  4371.1 1960.95  4513.6 1959.98  4678.5  1962.4
  4750.3 1960.85  4808.6 1955.15  4838.8 1938.86 4847.73 1936.27  4852.4 1933.23
  4929.3  1929.7  4966.5 1925.62  4969.3 1925.12  4972.5 1925.62  4994.8 1925.68
  5029.8 1926.62  5070.1 1936.49  5120.3 1961.34  5149.5 1964.91  5247.5 1990.85
  5264.2 1991.35  5311.4 1995.58  5454.6 1999.03  5488.8 1999.33  5988.2  2004.7
#Mann= 17 ,-1 , 0
  3347.7      .1       0  3586.5     .05       0  3652.8      .1       0
  3769.9     .05       0  3923.6      .1       0  4170.7     .05       0
  4270.9      .1       0  4371.1     .05       0  4678.5      .1       0
  4750.3     .05       0  4852.4      .1       0  4966.5     .07       0
  4972.5      .1       0  4994.8     .16       0  5264.2      .1       0
  5454.6     .16       0  5488.8      .1       0
Bank Sta=4847.73,5070.1
XS Rating Curve= 0 ,0
Exp/Cntr=0.3,0.1

Type RM Length L Ch R = 1 ,27524   ,839,839,839
BEGIN DESCRIPTION:
KLEIN BRANCH 43.0
END DESCRIPTION:
XS GIS Cut Line= 3
      2650584.21     10050900.13      2651243.94     10049667.48
      2651252.62     10048548.21
#Sta/Elev= 30
    3228 1982.27  3299.4 1981.04    3645 1974.96  4043.8  1967.7  4256.1 1959.03
  4446.4    1955  4466.7 1955.33    4551 1956.11  4659.8 1952.12  4759.8 1946.69
  4839.8 1938.54  4849.8 1936.12  4879.9 1928.17  4922.3 1927.34  4976.9  1922.9
  4979.6  1922.4  4982.9  1922.9  5059.9 1924.23  5079.9 1934.81  5084.4 1937.98
  5089.9 1941.85  5099.9 1955.14  5119.9 1969.74  5139.9 1978.74  5189.9 1996.71
  5229.9 2000.05  5303.7 2000.89  5432.3 2002.68  5544.4 2002.81  5745.4 2003.61
#Mann= 13 ,-1 , 0
    3228     .05       0  3299.4      .1       0    3645     .05       0
  4043.8      .1       0  4446.4     .05       0  4466.7      .1       0
  4922.3     .05       0  4976.9    .035       0  4982.9     .05       0
  5084.4     .16       0  5303.7      .1       0  5432.3     .16       0
  5544.4      .1       0
Bank Sta=4849.8,5079.9
XS Rating Curve= 0 ,0
Exp/Cntr=0.3,0.1

Type RM Length L Ch R = 1 ,26685   ,659,659,659
BEGIN DESCRIPTION:
KLEIN BRANCH 42.0
END DESCRIPTION:
XS GIS Cut Line= 3
      2650801.25     10051212.59      2651721.37     10049979.98
      2652407.13     10048582.43
#Sta/Elev= 30
  2901.4 1985.22  3092.6 1980.12    3221 1977.71  3996.2  1965.8  4171.1 1963.63
  4292.1 1956.76  4302.2 1956.19  4502.2 1952.44  4602.4 1945.46  4662.3 1943.45
  4744.9 1942.74  4785.6 1941.84  4869.8 1933.69  4920.5 1919.91  4962.5 1918.58
  4965.2 1918.08  4968.5 1918.58  5003.5 1919.12  5025.8 1925.28  5034.1 1930.14
  5038.5 1934.82    5048 1955.66  5055.4 1965.85    5106 1973.95  5347.8 1980.01
  5516.4 1990.16  5623.2 1991.66  5763.7  1998.2  5897.6 1999.49  5996.3 2000.66
#Mann= 13 ,-1 , 0
  2901.4      .1       0  3092.6     .05       0    3221      .1       0
  3996.2     .05       0  4292.1      .1       0  4302.2     .05       0
  4602.4      .1       0  4662.3     .05       0  4744.9      .1       0
  4962.5     .07       0  4968.5      .1       0  5034.1     .16       0
  5897.6      .1       0
Bank Sta=4869.8,5038.5
XS Rating Curve= 0 ,0
Exp/Cntr=0.3,0.1

Type RM Length L Ch R = 1 ,26026   ,527,527,527
BEGIN DESCRIPTION:
KLEIN BRANCH 41.0
END DESCRIPTION:
XS GIS Cut Line= 2
      2652016.51     10051238.66      2652780.38     10049042.52
#Sta/Elev= 30
  3491.8 1974.17  3789.1  1967.2  3967.9 1964.63  4070.5  1963.3  4314.4 1961.84
  4430.1 1961.81  4580.3  1957.1  4629.9 1951.19  4668.3 1941.52  4818.5 1938.37
  4854.9 1935.86  4880.7 1931.62  4911.8 1922.86  4955.1 1916.76  4957.9 1916.26
  4961.1 1916.76  5030.9 1920.67    5062 1932.09  5085.2 1945.12  5120.4 1950.14
  5217.6 1961.98  5248.7 1963.92  5296.2 1971.59  5336.7 1976.16    5342 1973.57
  5367.6 1978.31  5404.2 1981.11  5461.1 1990.28  5572.2 1997.44    5817  2003.2
#Mann= 10 ,-1 , 0
  3491.8      .1       0  3789.1     .05       0  3967.9      .1       0
  4070.5     .05       0  4314.4      .1       0  4955.1     .07       0
  4961.1      .1       0  5120.4     .16       0  5296.2      .1       0
  5367.6     .16       0
Bank Sta=4880.7,5062
XS Rating Curve= 0 ,0
Exp/Cntr=0.3,0.1