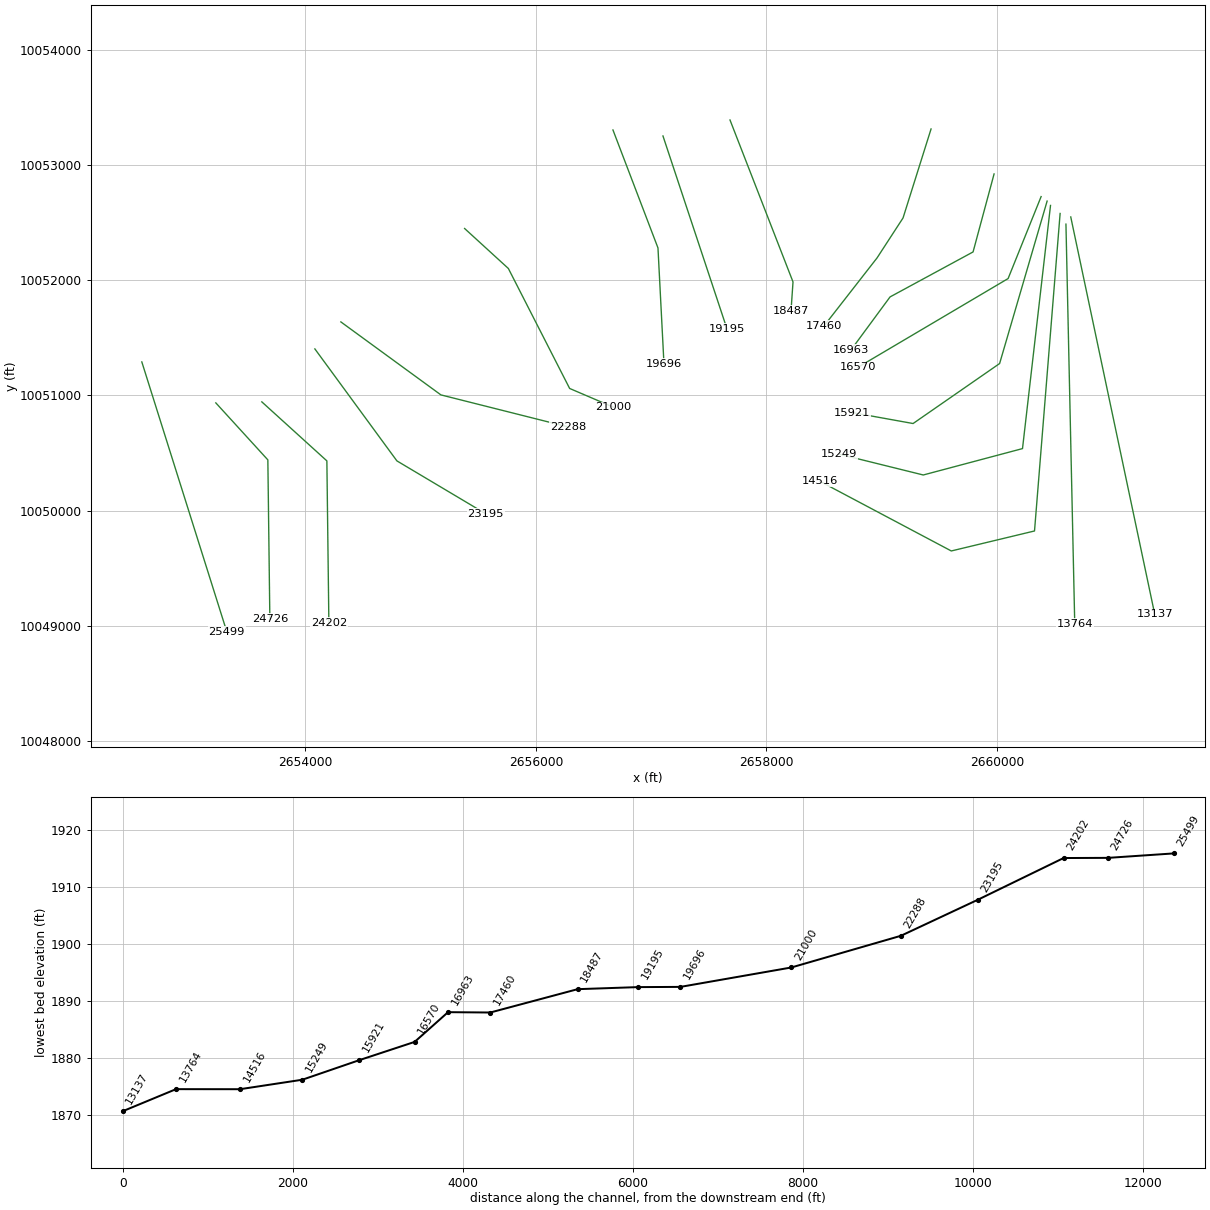
HEC-RAS study KLEIN BRANCH.prj: KLEIN BRANCH Base Level Engineering

--- KLEIN BRANCH.g01 (geometry) --- (continued)

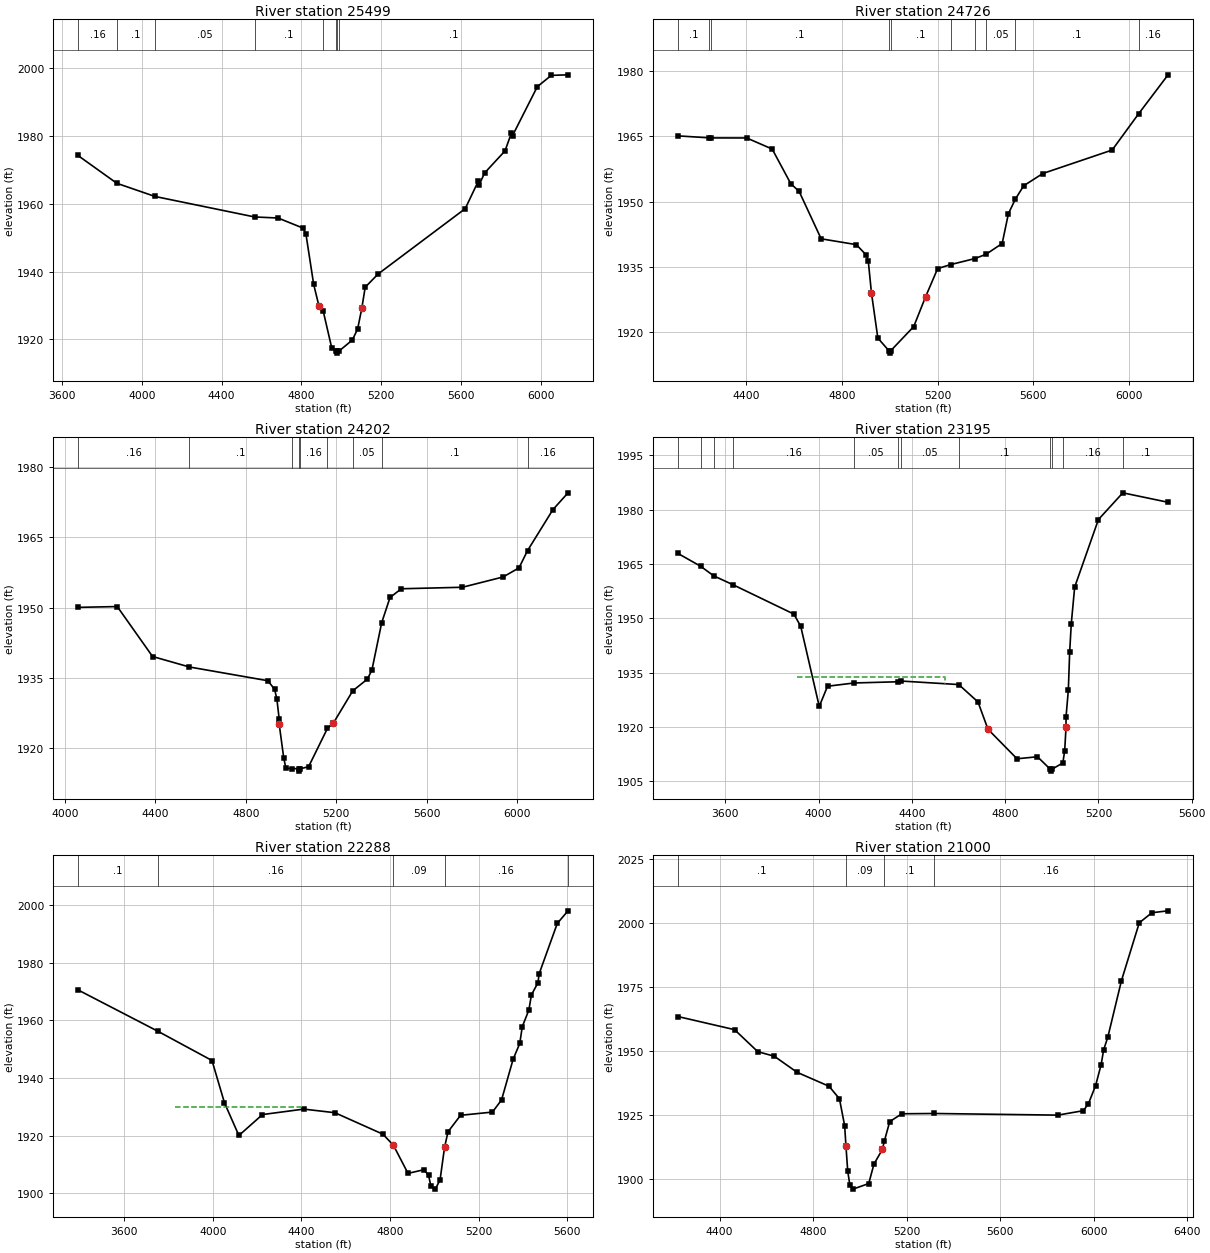
Type RM Length L Ch R = 1 ,25499   ,773,773,773
BEGIN DESCRIPTION:
KLEIN BRANCH 39.0
END DESCRIPTION:
XS GIS Cut Line= 2
      2652580.76      10051290.7      2653318.32     10048947.86
#Sta/Elev= 30
  3680.3 1974.25  3875.5 1966.03  4066.5 1962.15  4565.9  1956.1  4683.3 1955.79
  4809.4 1952.79  4823.3 1950.96  4861.8 1936.21  4888.1 1929.85    4910 1928.22
  4952.8 1917.33  4974.1 1916.42  4976.9 1915.92  4980.1 1916.42  4990.2  1916.6
  5055.2 1919.76    5082 1923.01  5102.9 1929.13    5120 1935.37  5184.7 1939.27
  5621.3 1958.55  5686.1 1966.57  5691.3 1965.61  5718.5 1969.09  5820.8  1975.6
  5853.2 1980.95  5858.5 1980.12  5982.7 1994.55  6052.7 1997.88  6136.5 1998.04
#Mann= 8 ,-1 , 0
  3680.3     .16       0  3875.5      .1       0  4066.5     .05       0
  4565.9      .1       0    4910     .05       0  4974.1     .07       0
  4980.1     .05       0  4990.2      .1       0
Bank Sta=4888.1,5102.9
XS Rating Curve= 0 ,0
Exp/Cntr=0.3,0.1

Type RM Length L Ch R = 1 ,24726   ,524,524,524
BEGIN DESCRIPTION:
KLEIN BRANCH 38.0
END DESCRIPTION:
XS GIS Cut Line= 3
      2653223.13     10050934.82      2653674.49     10050440.05
      2653691.86     10049059.88
#Sta/Elev= 30
    4114 1965.14  4243.9 1964.69  4252.9 1964.67  4401.5 1964.66    4508 1962.11
  4585.9 1954.14    4621 1952.34  4712.9 1941.45    4860 1940.11    4900 1937.81
    4910 1936.37  4923.3 1929.01    4950 1918.61  4997.1 1915.64  4999.8 1915.14
  5003.1 1915.64  5100.1 1921.25  5150.1 1928.16  5200.1 1934.59  5254.1 1935.51
  5356.3 1936.91  5402.2 1937.88  5470.1 1940.37  5496.1 1947.23  5525.7 1950.63
  5560.1 1953.66  5640.1 1956.48  5930.1 1961.88  6040.6 1970.21    6164 1979.19
#Mann= 10 ,-1 , 0
    4114      .1       0  4243.9     .16       0  4252.9      .1       0
  4997.1     .07       0  5003.1      .1       0  5254.1     .05       0
  5356.3      .1       0  5402.2     .05       0  5525.7      .1       0
  6040.6     .16       0
Bank Sta=4923.3,5150.1
XS Rating Curve= 0 ,0
Exp/Cntr=0.3,0.1

Type RM Length L Ch R = 1 ,24202   ,1007,1007,1007
BEGIN DESCRIPTION:
KLEIN BRANCH 37.0
END DESCRIPTION:
XS GIS Cut Line= 3
      2653622.39     10050943.54      2654186.65     10050431.37
      2654203.99     10049026.92
#Sta/Elev= 30
  4057.7 1950.07  4231.6 1950.24  4387.7 1939.58  4550.7 1937.34  4897.4 1934.41
  4927.4 1932.56  4937.4 1930.41  4947.4 1926.23 4947.44 1925.16  4967.4 1917.96
  4977.4 1915.69  5003.1 1915.65  5034.4 1915.61  5037.1 1915.11  5040.4 1915.61
  5077.4 1916.05  5160.7 1924.23  5187.4  1925.4  5272.8 1932.26  5337.4 1934.75
  5357.4  1936.7  5400.5 1946.78  5437.4 1952.18  5487.4 1954.04  5757.5 1954.36
  5937.5 1956.56  6007.5  1958.5  6045.5  1962.2  6157.5 1970.93  6224.3 1974.52
#Mann= 9 ,-1 , 0
  4057.7     .16       0  4550.7      .1       0  5003.1     .16       0
  5034.4     .07       0  5040.4     .16       0  5160.7      .1       0
  5272.8     .05       0  5400.5      .1       0  6045.5     .16       0
Bank Sta=4947.44,5187.4
XS Rating Curve= 0 ,0
Exp/Cntr=0.3,0.1

Type RM Length L Ch R = 1 ,23195   ,907,907,907
BEGIN DESCRIPTION:
KLEIN BRANCH 36.0
END DESCRIPTION:
XS GIS Cut Line= 3
       2654082.5     10051403.56      2654794.29     10050431.37
      2655565.15     10049972.32
#Sta/Elev= 30
  3396.7 1967.91  3493.8 1964.38  3550.5 1961.71  3633.8 1959.24  3893.8 1951.17
  3923.2  1947.8  4002.7 1925.67  4038.2 1931.25  4152.4 1932.15  4339.3 1932.48
  4352.3 1932.69  4601.1 1931.71  4683.5 1926.91  4726.4 1919.37  4850.9 1911.22
  4938.6 1911.78    4994 1908.31  4996.8 1907.81    5000 1908.31  5047.5 1910.07
  5055.4 1913.47 5061.08  1919.9  5061.2 1922.84    5071 1930.15  5076.8 1940.78
  5083.7 1948.57  5098.2 1958.62    5200 1977.27  5304.7 1984.65  5498.8 1982.04
#Mann= 12 ,-1 , 0
  3396.7      .1       0  3493.8     .16       0  3550.5      .1       0
  3633.8     .16       0  4152.4     .05       0  4339.3      .1       0
  4352.3     .05       0  4601.1      .1       0    4994     .07       0
    5000      .1       0  5047.5     .16       0  5304.7      .1       0
#XS Ineff= 1 ,-1
 3906.25 4544.03 1933.79
Permanent Ineff=
       T
Bank Sta=4726.4,5061.08
XS Rating Curve= 0 ,0
Exp/Cntr=0.3,0.1

Type RM Length L Ch R = 1 ,22288   ,1288,1288,1288
BEGIN DESCRIPTION:
KLEIN BRANCH 34.0
END DESCRIPTION:
XS GIS Cut Line= 3
      2654308.19     10051637.96      2655176.23     10051004.29
      2656278.65     10050726.51
#Sta/Elev= 30
  3391.8 1970.58  3751.8 1956.26  3996.8 1946.08  4053.2 1931.39  4118.1 1920.08
  4224.7 1927.34  4410.8 1929.23  4551.3 1927.98  4767.9 1920.54  4815.5 1916.69
  4881.3 1906.94  4953.5 1908.22  4974.1 1906.27    4985  1902.4  5004.8 1901.48
  5026.1 1904.73  5046.3 1916.03    5062 1921.38  5118.5 1927.08  5262.3  1928.2
  5303.4  1932.4  5355.7 1946.53  5385.6    1952    5397 1957.81  5426.7  1963.6
  5438.2 1968.84  5467.8 1973.06  5472.9 1976.11  5555.1 1993.65  5603.4 1997.99
#Mann= 5 ,-1 , 0
  3391.8      .1       0  3751.8     .16       0  4815.5     .09       0
  5046.3     .16       0  5603.4     .16       0
#XS Ineff= 1 ,-1
 3830.11 4404.55 1929.91
Permanent Ineff=
       T
Bank Sta=4815.5,5046.3
XS Rating Curve= 0 ,0
Exp/Cntr=0.3,0.1

Type RM Length L Ch R = 1 ,21000   ,1304,1304,1304
BEGIN DESCRIPTION:
KLEIN BRANCH 31.0
END DESCRIPTION:
XS GIS Cut Line= 4
      2655381.88     10052449.13      2655761.69     10052101.87
      2656293.37      10051060.2      2656671.66     10050898.08
#Sta/Elev= 30
  4222.2 1963.33  4464.1 1958.21  4563.4 1949.62  4634.3 1947.82  4731.7 1941.54
  4868.3  1936.1  4912.7 1931.21    4935 1920.67  4940.6 1912.62  4948.1 1902.95
  4957.2 1897.52  4970.3 1895.93  5037.9  1898.1  5060.3 1905.73  5096.2 1911.41
  5105.2 1914.88  5127.7 1922.29  5179.4 1925.36  5318.6 1925.47  5846.2 1924.83
  5955.4 1926.56  5977.2 1929.25    6008 1936.35  6031.6 1944.54  6042.4 1950.31
  6060.6 1955.41  6118.6 1977.37  6194.8 1999.96  6249.1 2003.89  6317.9 2004.62
#Mann= 4 ,-1 , 0
  4222.2      .1       0  4940.6     .09       0  5105.2      .1       0
  5318.6     .16       0
Bank Sta=4940.6,5096.2
XS Rating Curve= 0 ,0
Exp/Cntr=0.3,0.1

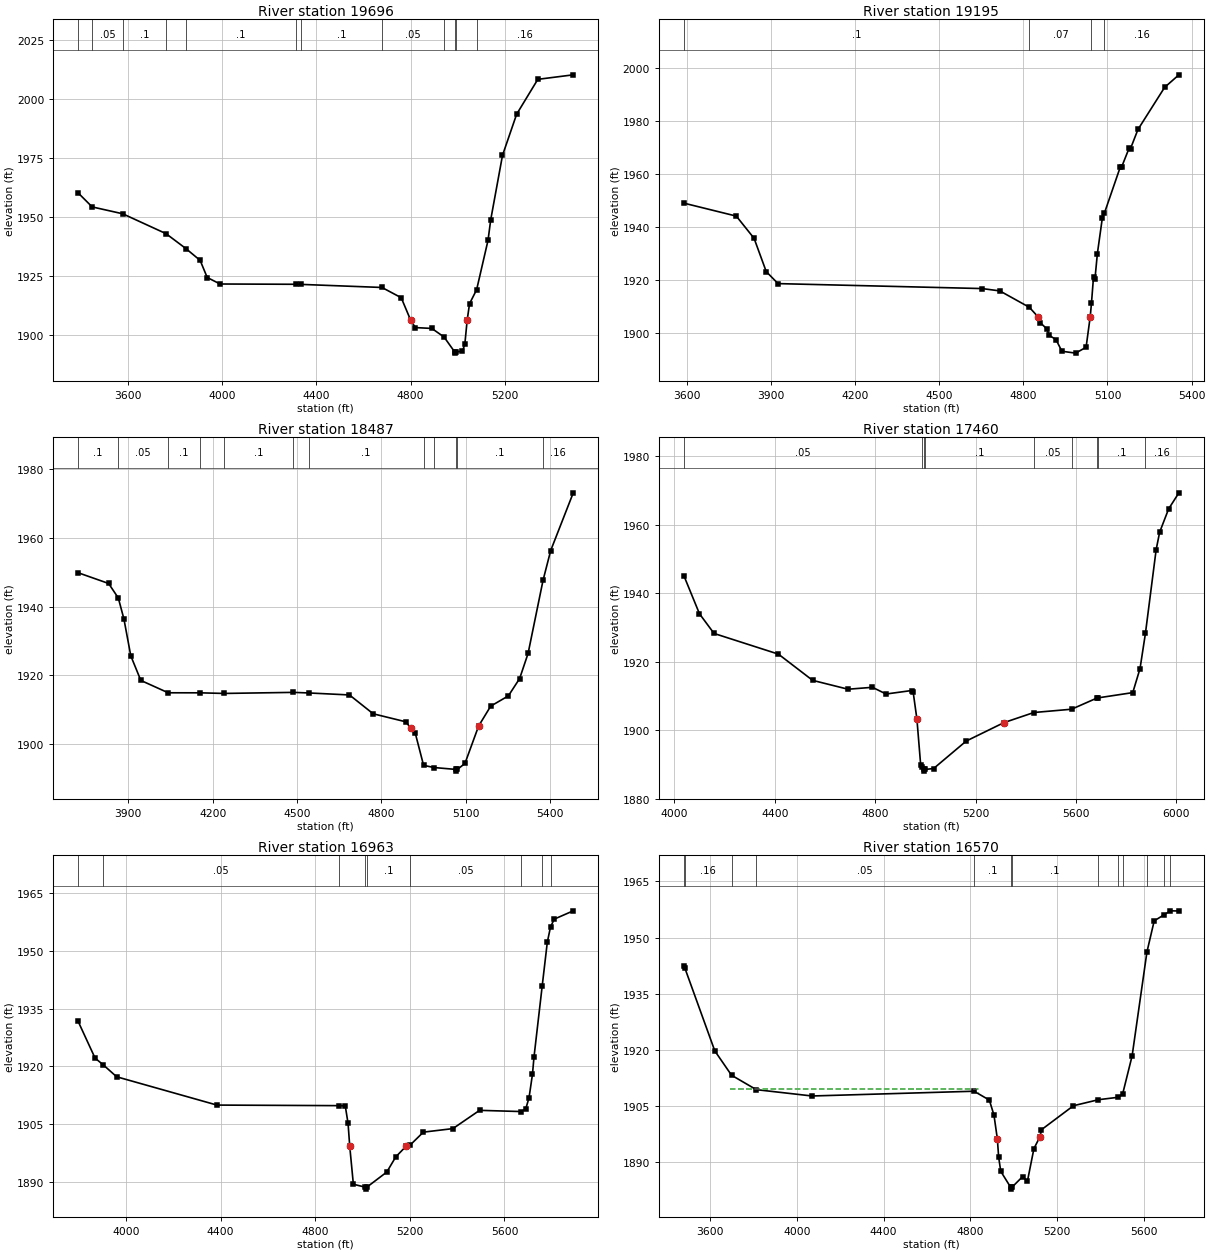
Type RM Length L Ch R = 1 ,19696   ,501,501,501
BEGIN DESCRIPTION:
KLEIN BRANCH 29.0
END DESCRIPTION:
XS GIS Cut Line= 3
      2656669.27     10053304.67      2657059.91     10052280.33
      2657111.99     10051273.38
#Sta/Elev= 30
  3387.2 1960.38  3446.7 1954.46  3576.3 1951.56  3760.6 1943.14  3845.1 1936.82
  3905.7 1931.81  3935.8 1924.56  3990.6 1921.81  4314.7 1921.69  4335.9 1921.64
  4678.7 1920.34  4760.5    1916  4800.5 1906.51  4820.5 1903.35  4890.6 1902.99
  4942.7 1899.35  4987.8 1893.03  4990.5 1892.53  4993.8 1893.03  5020.8 1893.37
  5030.8 1896.22  5040.8 1906.43  5050.9 1913.46  5081.1 1919.41  5129.5 1940.31
    5141 1949.04    5191 1976.29  5251.1 1993.72  5341.2  2008.5  5491.8 2010.41
#Mann= 12 ,-1 , 0
  3387.2      .1       0  3446.7     .05       0  3576.3      .1       0
  3760.6     .12       0  3845.1      .1       0  4314.7     .05       0
  4335.9      .1       0  4678.7     .05       0  4942.7      .1       0
  4987.8     .07       0  4993.8      .1       0  5081.1     .16       0
Bank Sta=4800.5,5040.8
XS Rating Curve= 0 ,0
Exp/Cntr=0.3,0.1

Type RM Length L Ch R = 1 ,19195   ,708,708,708
BEGIN DESCRIPTION:
KLEIN BRANCH 28.0
END DESCRIPTION:
XS GIS Cut Line= 2
      2657103.33     10053252.51      2657658.61     10051577.97
#Sta/Elev= 30
  3590.4 1949.11  3777.5 1944.21  3840.8 1935.82  3884.1 1923.26  3926.2 1918.73
  4653.2 1916.86  4716.4 1915.98  4821.8 1909.78  4853.4 1906.09  4860.2 1904.05
    4885 1901.51  4891.8 1899.25  4916.6 1897.61  4937.6  1893.2  4986.7 1892.49
  5023.9 1894.71 5038.64 1906.28    5043 1911.29  5050.3 1921.18  5055.6 1920.63
  5064.1 1930.06    5082 1943.68  5088.9 1945.25  5145.4 1962.64  5150.6 1962.76
    5177 1969.82  5182.3 1969.71  5208.7 1976.91  5303.8 1992.81  5354.6 1997.54
#Mann= 4 ,-1 , 0
  3590.4      .1       0  4821.8     .07       0    5043      .1       0
  5088.9     .16       0
Bank Sta=4853.4,5038.64
XS Rating Curve= 0 ,0
Exp/Cntr=0.3,0.1

Type RM Length L Ch R = 1 ,18487   ,1027,1027,1027
BEGIN DESCRIPTION:
KLEIN BRANCH 27.0
END DESCRIPTION:
XS GIS Cut Line= 3
      2657684.92     10053391.41      2658231.79     10051985.19
      2658214.43      10051733.5
#Sta/Elev= 30
  3721.6 1949.84  3829.9 1946.72  3864.3 1942.51  3884.3 1936.41  3908.8 1925.67
  3944.4 1918.52  4041.9 1914.92  4154.8 1914.91  4240.9 1914.73    4487 1915.04
  4542.4 1914.87  4686.7 1914.29    4771 1908.81  4888.6 1906.45  4904.3 1904.54
  4920.8 1903.16  4950.3 1893.81  4988.1 1893.17  5064.6 1892.63  5067.3 1892.13
  5070.6 1892.63  5097.5 1894.37  5146.1 1905.26  5189.1 1911.04  5251.9 1914.02
    5292 1919.07  5322.1 1926.39  5375.2 1947.62  5402.3 1956.26  5482.7 1973.09
#Mann= 12 ,-1 , 0
  3721.6      .1       0  3864.3     .05       0  4041.9      .1       0
  4154.8     .05       0  4240.9      .1       0    4487     .05       0
  4542.4      .1       0  4950.3     .05       0  4988.1      .1       0
  5064.6     .07       0  5070.6      .1       0  5375.2     .16       0
Bank Sta=4904.3,5146.1
XS Rating Curve= 0 ,0
Exp/Cntr=0.3,0.1

Type RM Length L Ch R = 1 ,17460   ,497,497,497
BEGIN DESCRIPTION:
KLEIN BRANCH 25.0
END DESCRIPTION:
XS GIS Cut Line= 4
       2659429.7      10053313.3      2659186.65     10052540.75
      2658960.95     10052193.52      2658500.89     10051603.25
#Sta/Elev= 30
  4037.5 1945.16  4099.9 1933.99  4157.9 1928.25  4414.4 1922.21  4550.7 1914.55
  4691.8 1911.96    4789 1912.52  4843.2 1910.56  4945.1 1911.58  4951.2 1911.13
  4966.2 1903.21  4981.3 1889.69  4985.1  1889.1  4993.5 1888.54  4996.2 1888.04
  4999.5 1888.54  5032.7  1888.8  5162.5 1896.82  5312.3 1902.19  5432.1 1905.16
  5582.3 1906.12  5682.1 1909.34  5688.3 1909.44  5826.1 1910.97  5855.1 1918.01
  5876.5 1928.24  5919.3 1952.73  5933.2 1957.82    5969 1964.63  6009.9 1969.32
#Mann= 9 ,-1 , 0
  4037.5     .05       0  4985.1      .1       0  4993.5     .07       0
  4999.5      .1       0  5432.1     .05       0  5582.3      .1       0
  5682.1     .05       0  5688.3      .1       0  5876.5     .16       0
Bank Sta=4966.2,5312.3
XS Rating Curve= 0 ,0
Exp/Cntr=0.3,0.1

Type RM Length L Ch R = 1 ,16963   ,393,393,393
BEGIN DESCRIPTION:
KLEIN BRANCH 24.0
END DESCRIPTION:
XS GIS Cut Line= 4
      2659976.57     10052922.64      2659794.29     10052245.61
       2659073.8     10051854.98      2658735.27     10051394.92
#Sta/Elev= 30
  3798.6 1931.71    3870 1922.18    3904 1920.45  3961.2 1917.32    4385 1909.96
  4902.2 1909.81  4927.2 1909.74    4939 1905.19 4946.02 1899.26  4961.4 1889.37
  5012.1  1888.6  5014.9  1888.1  5018.1  1888.6  5102.6 1892.54  5140.6 1896.49
  5184.4 1899.27  5202.1 1899.61  5257.1 1902.92    5382 1903.84  5494.7 1908.59
  5668.3 1908.28  5689.1 1908.83  5703.7 1911.88  5718.2 1917.99  5724.6 1922.44
  5759.5 1941.05  5780.9 1952.33  5794.5  1956.3  5810.2 1958.32  5890.5 1960.48
#Mann= 9 ,-1 , 0
  3798.6      .1       0    3904     .05       0  4902.2      .1       0
  5012.1     .07       0  5018.1      .1       0  5202.1     .05       0
  5668.3      .1       0  5759.5     .16       0  5794.5      .1       0
Bank Sta=4946.02,5184.4
XS Rating Curve= 0 ,0
Exp/Cntr=0.3,0.1

Type RM Length L Ch R = 1 ,16570   ,649,649,649
BEGIN DESCRIPTION:
KLEIN BRANCH 23.0
END DESCRIPTION:
XS GIS Cut Line= 3
      2660384.84     10052726.23      2660098.39     10052014.44
      2658792.68      10051242.3
#Sta/Elev= 30
  3478.7 1942.53    3483 1941.98  3621.6 1919.79  3698.9 1913.29  3813.1 1909.44
  4070.3 1907.75  4817.9 1909.02  4888.3 1906.66  4909.7 1902.65  4925.3 1896.29
  4931.3 1891.41    4941 1887.64  4986.6 1883.39  4989.4 1882.89  4992.6 1883.39
  5042.4 1886.26  5063.8 1884.94    5094  1893.7  5122.3 1896.93  5128.8 1898.75
  5276.4 1905.15  5391.9 1906.76  5483.7 1907.41  5503.7 1908.36  5547.1 1918.47
  5615.4 1946.18  5648.9 1954.49  5692.4 1956.04  5723.7 1957.17  5762.9 1957.13
#Mann= 13 ,-1 , 0
  3478.7      .1       0    3483     .16       0  3698.9      .1       0
  3813.1     .05       0  4817.9      .1       0  4986.6     .07       0
  4992.6      .1       0  5391.9     .16       0  5483.7      .1       0
  5503.7     .16       0  5615.4      .1       0  5692.4     .08       0
  5723.7     .05       0
#XS Ineff= 1 ,-1
 3690.34  4835.8 1909.74
Permanent Ineff=
       T
Bank Sta=4925.3,5122.3
XS Rating Curve= 0 ,0
Exp/Cntr=0.3,0.1

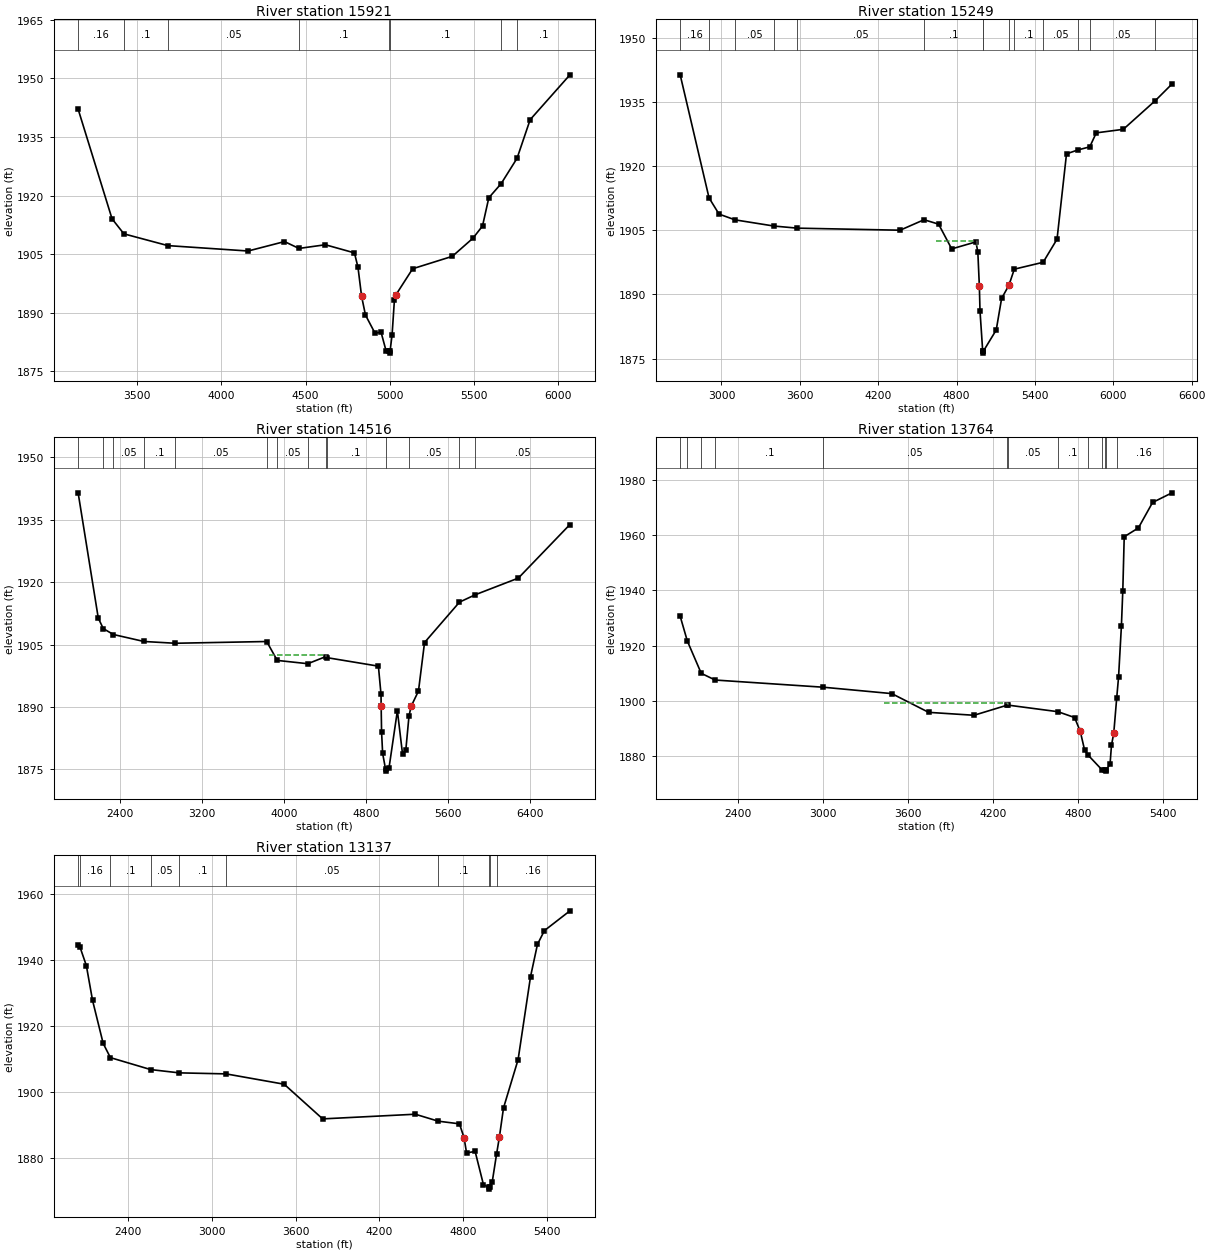
Type RM Length L Ch R = 1 ,15921   ,672,672,672
BEGIN DESCRIPTION:
KLEIN BRANCH 22.0
END DESCRIPTION:
XS GIS Cut Line= 4
      2660436.92     10052687.15       2660024.6     10051276.59
      2659273.74     10050755.76      2658744.18     10050851.26
#Sta/Elev= 30
  3148.8 1942.12  3350.3 1914.06  3420.7 1910.22  3681.9 1907.21  4158.4 1905.83
  4374.7 1908.24  4460.7 1906.49  4617.3 1907.43  4790.1 1905.35  4811.1 1901.69
  4832.7 1894.23  4855.6 1889.45  4912.4  1884.8  4948.2 1885.07  4977.9 1880.32
  4995.8  1880.2  4998.6  1879.7  5001.8  1880.2  5013.7 1884.33  5027.5 1893.21
  5034.6 1894.49    5136 1901.29  5371.7 1904.47    5494  1909.1  5550.9 1912.22
  5588.4 1919.45  5661.8 1923.07  5756.2 1929.56    5834 1939.44  6070.3 1950.91
#Mann= 8 ,-1 , 0
  3148.8     .16       0  3420.7      .1       0  3681.9     .05       0
  4460.7      .1       0  4995.8     .07       0  5001.8      .1       0
  5661.8     .05       0  5756.2      .1       0
Bank Sta=4832.7,5034.6
XS Rating Curve= 0 ,0
Exp/Cntr=0.3,0.1

Type RM Length L Ch R = 1 ,15249   ,733,733,733
BEGIN DESCRIPTION:
Mapping XS c8d24923
END DESCRIPTION:
XS GIS Cut Line= 4
      2660466.38     10052649.22      2660223.32     10050538.08
      2659362.21     10050308.91      2658634.75     10050489.04
#Sta/Elev= 30
  2683.7 1941.33  2904.7 1912.56  2981.1 1908.77  3103.7 1907.42  3402.3 1905.97
  3581.1 1905.48  4367.8    1905  4550.9 1907.45  4662.2 1906.42  4762.8 1900.63
  4948.3 1902.27  4962.8 1899.88 4974.43 1891.93  4979.4 1886.12    5000 1876.76
  5002.7 1876.26    5006 1876.76  5103.6 1881.67  5144.9 1889.06  5200.9 1892.13
    5242 1895.89  5462.9  1897.5  5569.2  1902.9  5641.7 1922.85  5727.9 1923.76
  5819.8 1924.49  5869.6 1927.76  6076.7 1928.59  6322.1 1935.31  6449.3 1939.18
#Mann= 14 ,-1 , 0
  2683.7     .16       0  2904.7      .1       0  3103.7     .05       0
  3402.3      .1       0  3581.1     .05       0  4550.9      .1       0
    5000     .07       0    5006      .1       0  5200.9     .05       0
    5242      .1       0  5462.9     .05       0  5727.9      .1       0
  5819.8     .05       0  6322.1      .1       0
#XS Ineff= 1 ,-1
 4644.89 4954.55 1902.44
Permanent Ineff=
       T
Bank Sta=4974.43,5200.9
XS Rating Curve= 0 ,0
Exp/Cntr=0.3,0.1

Type RM Length L Ch R = 1 ,14516   ,752,752,752
BEGIN DESCRIPTION:
KLEIN BRANCH 21.0
END DESCRIPTION:
XS GIS Cut Line= 4
      2660549.71     10052579.73      2660327.49      10049822.8
      2659605.26     10049649.19      2658466.36     10050253.36
#Sta/Elev= 30
  1988.1 1941.44  2184.7 1911.35  2233.4 1908.83  2332.5 1907.41  2629.6 1905.74
    2934 1905.31  3827.8 1905.73  3930.4 1901.19  4228.8  1900.4  4406.5 1902.13
  4414.1 1901.86  4917.5 1899.81  4942.9 1893.03 4944.32 1890.13  4948.4 1884.02
  4958.7 1878.86    4987  1875.1  4989.7  1874.6  5020.4 1875.27  5102.6  1889.1
  5152.7 1878.74  5184.9 1879.67  5215.8 1887.81  5236.4 1890.15  5308.3 1893.83
  5367.6 1905.49  5708.6 1915.19  5863.3 1916.97  6282.6 1920.96    6786 1933.83
#Mann= 14 ,-1 , 0
  1988.1     .16       0  2233.4      .1       0  2332.5     .05       0
  2629.6      .1       0    2934     .05       0  3827.8      .1       0
  3930.4     .05       0  4228.8      .1       0  4406.5     .05       0
  4414.1      .1       0    4987     .07       0  5215.8     .05       0
  5708.6      .1       0  5863.3     .05       0
#XS Ineff= 1 ,-1
 3846.59 4409.09 1902.44
Permanent Ineff=
       T
Bank Sta=4944.32,5236.4
XS Rating Curve= 0 ,0
Exp/Cntr=0.3,0.1

Type RM Length L Ch R = 1 ,13764   ,627,627,627
BEGIN DESCRIPTION:
KLEIN BRANCH 20.0
END DESCRIPTION:
XS GIS Cut Line= 2
      2660600.28       10052487.      2660676.62     10049016.74
#Sta/Elev= 30
  1994.3 1930.65  2044.6 1921.72  2142.9    1910  2241.2 1907.57  3005.2 1904.97
  3487.9 1902.66    3748 1895.88  4068.1 1894.82  4299.8 1898.44  4306.1 1898.51
  4660.8 1896.11  4778.2    1894  4818.2 1888.96  4848.3 1882.33    4870 1880.59
  4970.7 1875.12  4995.3 1875.11    4998 1874.61  5001.3 1875.11  5028.3 1877.11
  5038.3 1883.93 5054.55 1888.39    5075  1900.9  5088.3 1908.59  5108.3 1926.96
  5118.3 1939.93  5128.3 1959.42  5228.3 1962.61  5328.4 1971.82  5465.4 1975.31
#Mann= 13 ,-1 , 0
  1994.3     .16       0  2044.6      .1       0  2142.9     .16       0
  2241.2      .1       0  3005.2     .05       0  4299.8      .1       0
  4306.1     .05       0  4660.8      .1       0    4870     .05       0
  4970.7      .1       0  4995.3     .07       0  5001.3      .1       0
    5075     .16       0
#XS Ineff= 1 ,-1
 3431.82 4304.55  1899.2
Permanent Ineff=
       T
Bank Sta=4818.2,5054.55
XS Rating Curve= 0 ,0
Exp/Cntr=0.3,0.1

Type RM Length L Ch R = 1 ,13137   ,536,536,536
BEGIN DESCRIPTION:
KLEIN BRANCH 19.0
END DESCRIPTION:
XS GIS Cut Line= 2
      2660641.95     10052549.47      2661371.04     10049098.45
#Sta/Elev= 30
  2039.9  1944.6  2053.2 1943.84  2098.8 1938.25  2143.4 1927.71  2219.5 1914.74
  2271.3 1910.45  2560.3 1906.84  2764.7 1905.85    3101 1905.54  3517.6 1902.42
  3793.7 1891.95  4457.9 1893.36  4622.5 1891.26  4774.7 1890.46  4807.6 1886.29
  4825.8 1881.67  4887.1 1882.13  4946.6 1872.13  4986.3 1871.24  4989.1 1870.74
  4992.3 1871.24  5009.8 1872.93  5041.1 1881.37  5060.9 1886.39  5090.7 1895.27
  5195.3 1909.85  5284.6 1934.94  5334.3 1944.67  5384.1 1948.81  5567.1 1954.78
#Mann= 10 ,-1 , 0
  2039.9      .1       0  2053.2     .16       0  2271.3      .1       0
  2560.3     .05       0  2764.7      .1       0    3101     .05       0
  4622.5      .1       0  4986.3     .07       0  4992.3      .1       0
  5041.1     .16       0
Bank Sta=4807.6,5060.9
XS Rating Curve= 0 ,0
Exp/Cntr=0.3,0.1