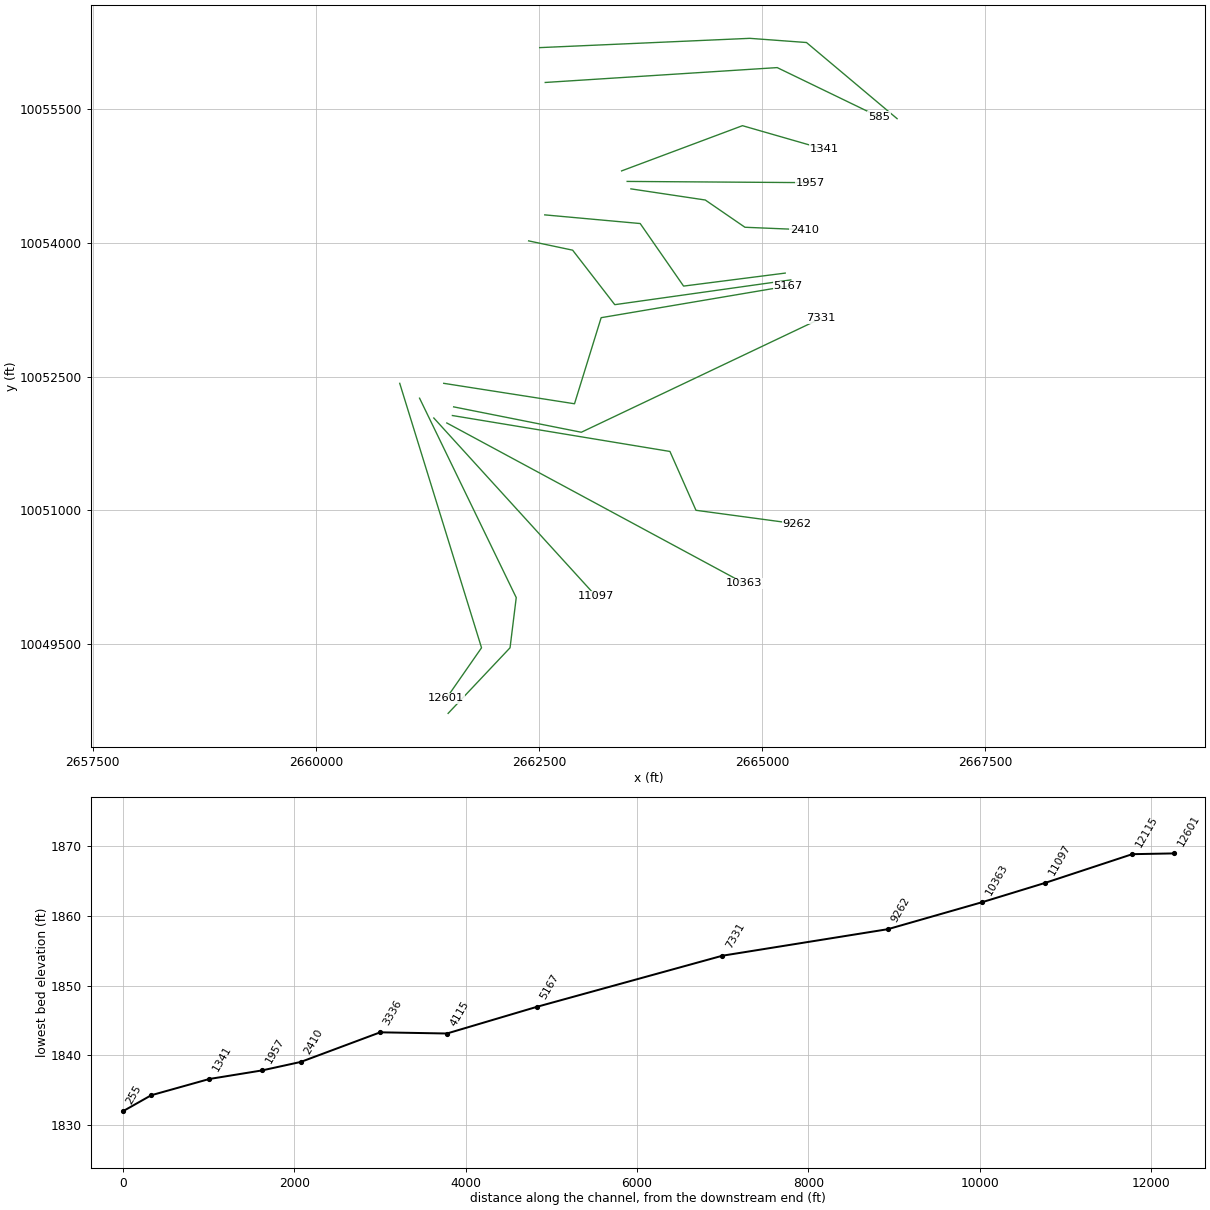
HEC-RAS study KLEIN BRANCH.prj: KLEIN BRANCH Base Level Engineering

--- KLEIN BRANCH.g01 (geometry) --- (continued)

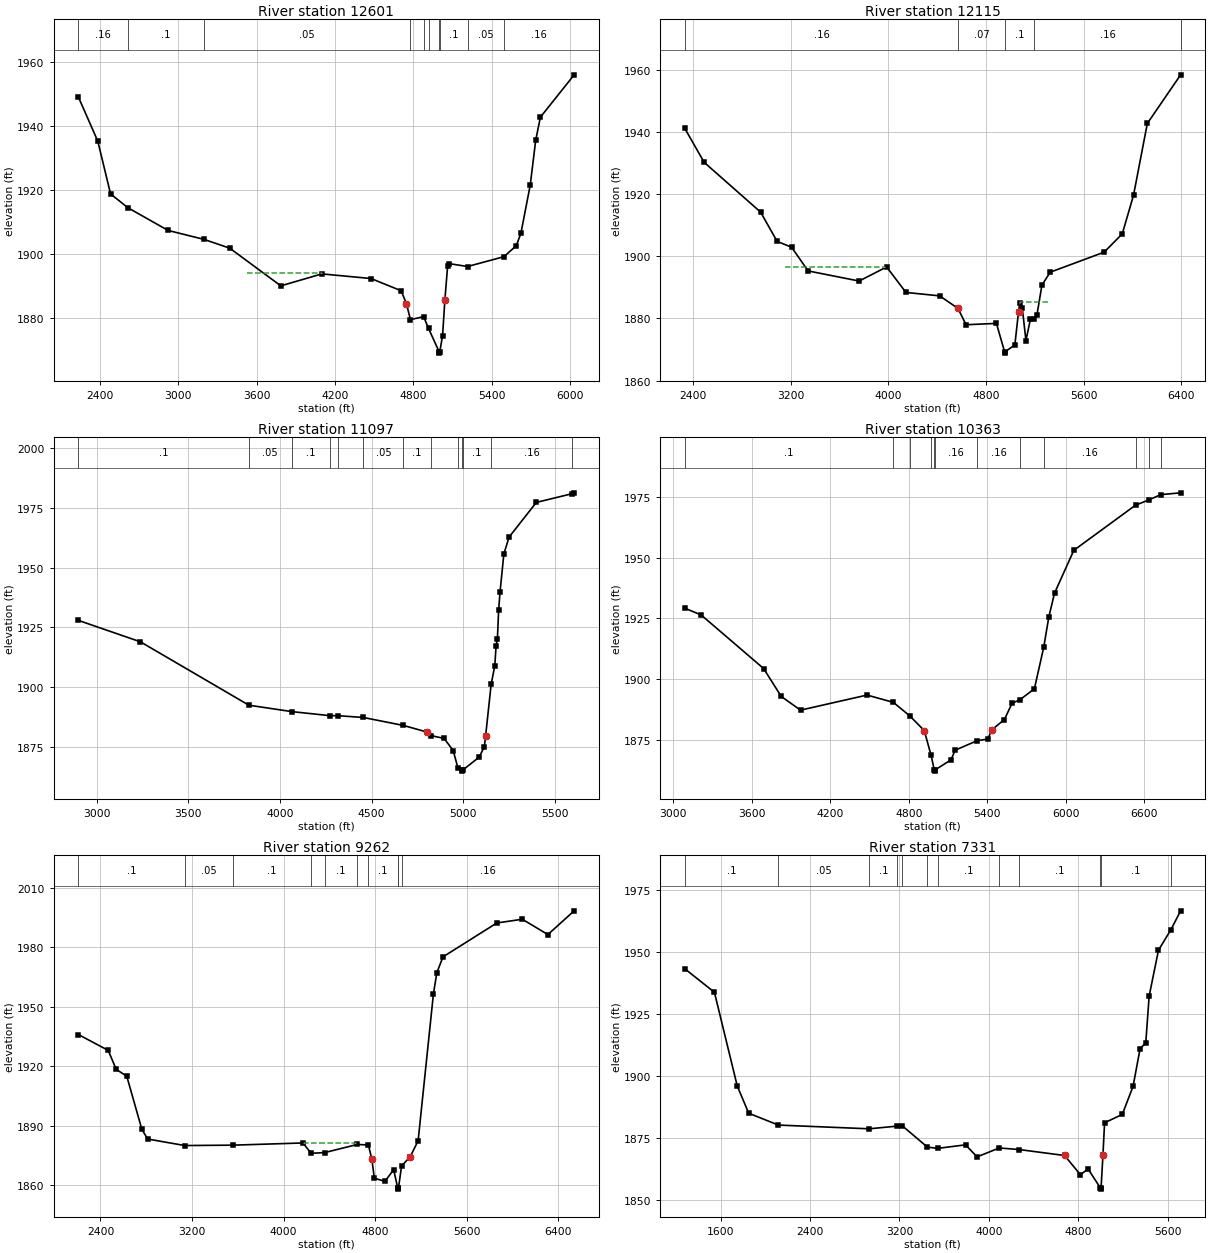
Type RM Length L Ch R = 1 ,12601   ,486,486,486
BEGIN DESCRIPTION:
KLEIN BRANCH 18.0
END DESCRIPTION:
XS GIS Cut Line= 3
      2660940.56     10052424.48      2661857.22     10049459.24
      2661462.42     10048891.27
#Sta/Elev= 30
  2234.7 1949.16  2383.6 1935.29  2481.5 1918.78  2613.1 1914.48  2921.4 1907.35
  3197.1 1904.54  3393.9 1901.79  3784.6    1890  4098.6 1893.74  4474.7  1892.3
  4705.7 1888.47  4746.2 1884.43  4776.8 1879.43  4878.1 1880.35  4915.5 1876.66
  4995.8 1869.44  4998.5 1868.94  5001.8 1869.44  5022.9 1874.44  5040.6 1885.69
  5061.6 1896.22    5072 1896.97  5213.7 1896.05  5491.8 1899.12  5586.4 1902.53
  5622.2  1906.4  5693.8 1921.53  5735.7 1935.56  5771.5 1942.79  6030.1 1956.06
#Mann= 10 ,-1 , 0
  2234.7     .16       0  2613.1      .1       0  3197.1     .05       0
  4776.8      .1       0  4878.1     .05       0  4915.5      .1       0
  4995.8     .07       0  5001.8      .1       0  5213.7     .05       0
  5491.8     .16       0
#XS Ineff= 1 ,-1
 3528.41 4102.27 1894.04
Permanent Ineff=
       T
Bank Sta=4746.2,5040.6
XS Rating Curve= 0 ,0
Exp/Cntr=0.3,0.1

Type RM Length L Ch R = 1 ,12115   ,1018,1018,1018
BEGIN DESCRIPTION:
KLEIN BRANCH 17.0
END DESCRIPTION:
XS GIS Cut Line= 4
      2661162.76     10052257.88      2662246.11     10050021.74
      2662176.66     10049459.24      2661482.84     10048723.78
#Sta/Elev= 30
  2332.6  1941.1    2491 1930.19  2953.7 1914.18  3089.2 1904.76  3207.6 1902.88
  3343.1 1895.26  3760.7 1892.01  3986.4 1896.54  4144.5 1888.35    4421 1887.24
  4570.7 1883.22  4637.3 1877.96  4885.9 1878.39  4956.1 1868.83  4959.4 1869.33
    5037 1871.48  5067.2  1882.2  5077.3 1884.94  5097.5 1883.44  5127.7 1872.89
  5164.2 1879.67  5197.3 1879.96  5218.4  1881.2  5258.7 1890.69  5326.4 1894.85
  5768.7  1901.3  5917.2 1907.19  6009.4 1919.62  6122.3 1942.68  6395.2 1958.32
#Mann= 5 ,-1 , 0
  2332.6     .16       0  4570.7     .07       0  4959.4      .1       0
  5197.3     .16       0  6395.2     .16       0
#XS Ineff= 2 ,-1
 3156.25 3974.43 1896.67  5076.7 5323.86 1885.28
Permanent Ineff=
       T       T
Bank Sta=4570.7,5067.2
XS Rating Curve= 0 ,0
Exp/Cntr=0.3,0.1

Type RM Length L Ch R = 1 ,11097   ,734,734,734
BEGIN DESCRIPTION:
KLEIN BRANCH 15.0
END DESCRIPTION:
XS GIS Cut Line= 2
      2661322.52      10052035.6      2663141.92     10050035.65
#Sta/Elev= 30
  2900.9 1927.89  3239.4 1918.91  3830.9 1892.34  4064.5 1889.66  4272.1 1887.96
  4317.5 1887.94  4455.4 1887.19  4673.3 1883.86  4803.6 1881.06    4824  1879.6
  4895.5 1878.41  4944.9 1873.35  4970.8 1866.04  4991.9 1865.21  4994.6 1864.71
  4997.9 1865.21  5086.7 1870.57  5115.1    1875  5121.9 1879.54  5151.9 1901.05
  5171.9 1908.92  5178.6 1916.95  5186.1  1920.2  5192.8 1932.25  5200.3 1939.71
  5221.2 1955.68  5249.6 1962.79  5398.3 1977.33  5593.2 1980.98  5604.6 1981.35
#Mann= 13 ,-1 , 0
  2900.9      .1       0  3830.9     .05       0  4064.5      .1       0
  4272.1     .05       0  4317.5      .1       0  4455.4     .05       0
  4673.3      .1       0    4824     .16       0  4970.8      .1       0
  4991.9     .07       0  4997.9      .1       0  5151.9     .16       0
  5593.2      .1       0
Bank Sta=4803.6,5121.9
XS Rating Curve= 0 ,0
Exp/Cntr=0.3,0.1

Type RM Length L Ch R = 1 ,10363   ,1101,1101,1101
BEGIN DESCRIPTION:
KLEIN BRANCH 14.0
END DESCRIPTION:
XS GIS Cut Line= 2
      2661468.29     10051980.09      2664801.69     10050181.44
#Sta/Elev= 30
  3089.5 1929.22  3213.9 1926.46  3691.9  1904.3    3826  1892.8  3973.6 1887.13
  4481.9 1893.36  4682.9 1890.34  4808.7 1884.73    4919 1878.69  4970.2 1868.58
  4995.7 1862.45  4998.4 1861.95  5001.7 1862.45  5123.7 1866.63  5154.1 1870.58
  5322.2  1874.5  5405.4 1875.23    5433 1878.91  5531.1 1883.26  5589.5 1889.98
  5649.6 1891.43    5760 1895.94  5831.3 1913.06    5870 1925.53  5913.8 1935.44
  6061.4 1953.13  6533.1 1971.79  6635.2 1973.94  6724.7 1976.12  6877.2 1976.87
#Mann= 12 ,-1 , 0
  3089.5      .1       0  4682.9     .05       0  4808.7      .1       0
  4970.2     .16       0  4995.7     .07       0  5001.7     .16       0
  5322.2     .16       0  5649.6      .1       0  5831.3     .16       0
  6533.1      .1       0  6635.2     .16       0  6724.7      .1       0
Bank Sta=4919,5433
XS Rating Curve= 0 ,0
Exp/Cntr=0.3,0.1

Type RM Length L Ch R = 1 ,9262    ,1931,1931,1931
BEGIN DESCRIPTION:
KLEIN BRANCH 12.0
END DESCRIPTION:
XS GIS Cut Line= 4
      2661530.84      10052063.4      2663968.33     10051660.62
        2664260.      10051000.9      2665391.97     10050848.12
#Sta/Elev= 30
  2206.3 1936.02  2467.4 1928.02  2537.5 1918.44  2629.6 1915.03  2761.4 1888.25
    2812 1883.34  3137.2 1880.05    3560 1880.25  4170.2 1881.35  4240.8 1876.15
  4359.1  1876.5  4644.6 1880.59  4741.5 1880.35  4771.9 1873.26  4793.8 1863.56
    4887 1862.02  4962.4 1867.91  4998.5 1858.58  5001.2 1858.08  5004.5 1858.58
    5032 1869.76  5107.7 1874.44  5176.4 1882.45  5310.4  1956.6  5340.4 1967.22
  5393.9 1975.16  5864.4 1992.25  6087.5 1994.12  6310.7  1986.4  6540.4 1998.37
#Mann= 10 ,-1 , 0
  2206.3      .1       0  3137.2     .05       0    3560      .1       0
  4240.8     .05       0  4359.1      .1       0  4644.6     .05       0
  4741.5      .1       0  4998.5     .07       0  5004.5      .1       0
    5032     .16       0
#XS Ineff= 1 ,-1
 4176.14 4633.52 1881.45
Permanent Ineff=
       T
Bank Sta=4771.9,5107.7
XS Rating Curve= 0 ,0
Exp/Cntr=0.3,0.1

Type RM Length L Ch R = 1 ,7331    ,2164,2164,2164
BEGIN DESCRIPTION:
KLEIN BRANCH 10.0
END DESCRIPTION:
XS GIS Cut Line= 3
      2661544.69     10052160.63      2662975.28      10051875.9
      2665662.73     10053153.66
#Sta/Elev= 30
  1280.4 1943.11  1545.3 1933.63  1749.7 1895.83  1851.9 1884.88  2117.2  1880.1
  2928.8  1878.6  3182.3 1879.69    3227 1879.75  3450.8 1871.19  3545.3 1870.73
  3791.3 1872.13  3894.1 1867.28  4092.7 1870.87  4268.1 1870.25  4676.7 1867.84
  4818.5  1860.1  4886.7 1862.42  4997.3 1854.78    5000 1854.28  5003.3 1854.78
 5019.89 1867.86  5034.6 1881.03  5193.1  1884.4  5289.5 1895.71  5352.1 1910.87
  5403.1 1913.23  5433.3 1932.11  5516.7  1950.6  5628.7 1958.92  5714.8 1966.47
#Mann= 12 ,-1 , 0
  1280.4      .1       0  2117.2     .05       0  2928.8      .1       0
  3182.3     .05       0    3227      .1       0  3450.8     .05       0
  3545.3      .1       0  4092.7     .05       0  4268.1      .1       0
  4997.3     .07       0  5003.3      .1       0  5628.7     .16       0
Bank Sta=4676.7,5019.89
XS Rating Curve= 0 ,0
Exp/Cntr=0.3,0.1

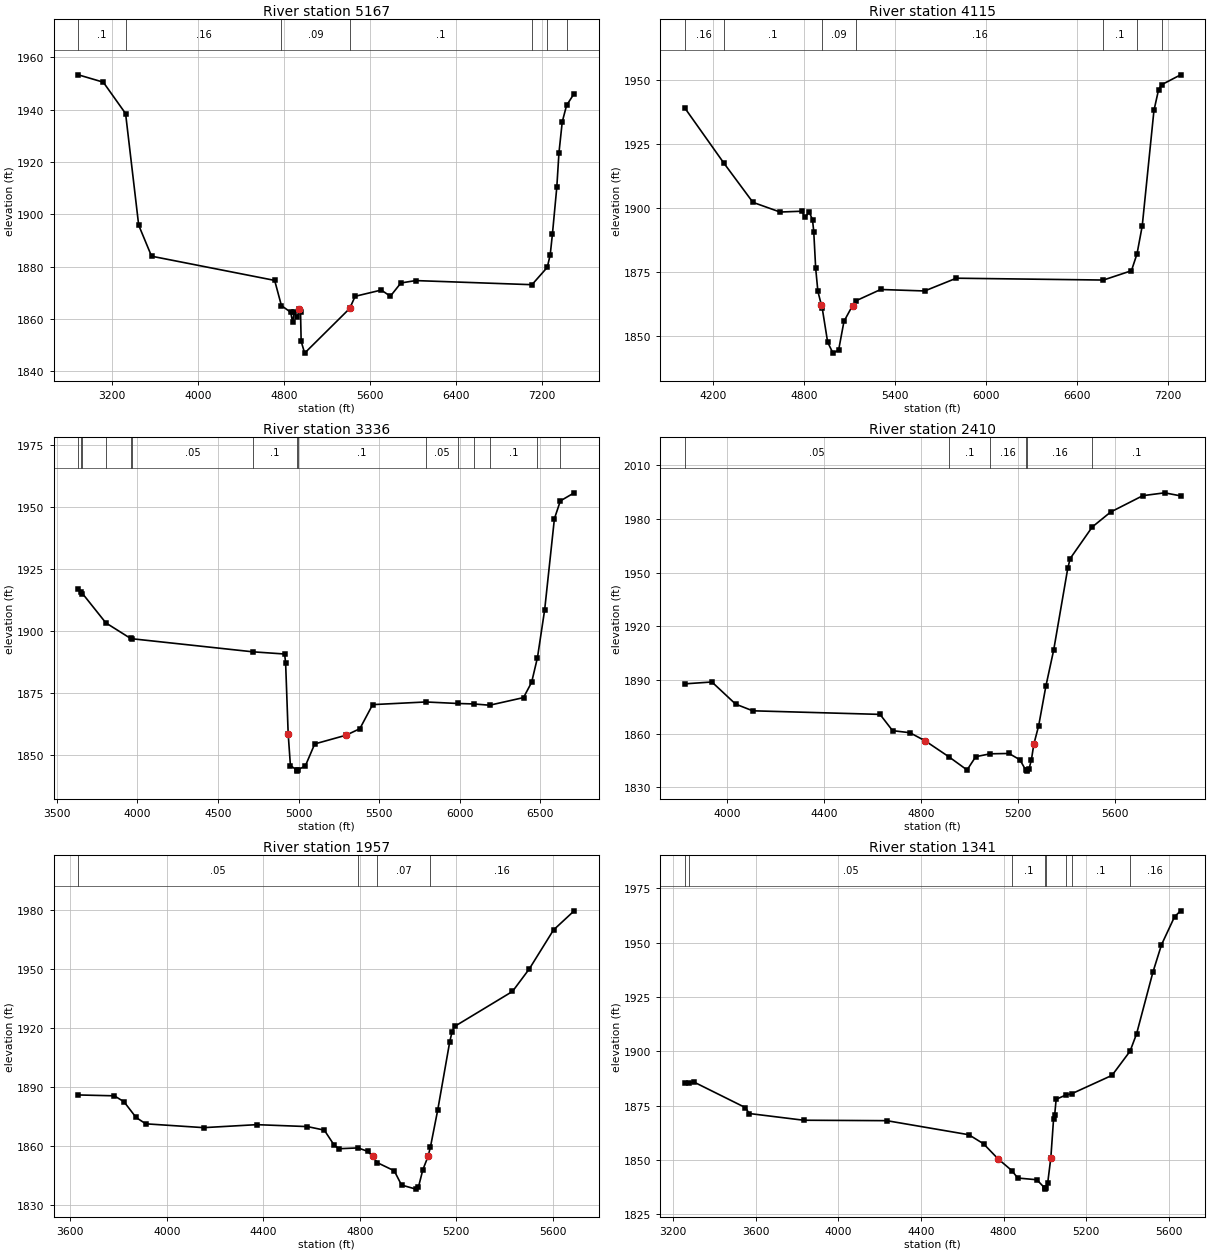
Type RM Length L Ch R = 1 ,5167    ,1052,1052,1052
BEGIN DESCRIPTION:
KLEIN BRANCH 9.0
END DESCRIPTION:
XS GIS Cut Line= 4
      2661433.61     10052424.51      2662898.89     10052195.35
       2663197.5     10053160.62      2665287.81      10053514.8
#Sta/Elev= 30
  2886.4 1953.34  3118.5 1950.53  3326.1 1938.53    3448 1895.87  3567.7 1884.01
  4713.2 1874.76    4776 1865.13  4861.9  1862.6  4880.7 1858.72  4894.5 1862.52
  4921.9 1860.63  4943.5 1863.69    4954 1862.52  4959.7  1851.5  4992.1 1846.96
  5411.3 1864.03    5462 1868.68  5705.4 1871.07  5789.6  1868.7    5888 1873.78
    6026 1874.69  7107.4 1873.12  7249.9 1879.75  7277.5 1884.66  7297.8  1892.5
  7338.4 1910.33  7358.7 1923.61  7389.1 1935.34  7429.3 1941.65    7500 1946.18
#Mann= 7 ,-1 , 0
  2886.4      .1       0  3326.1     .16       0    4776     .09       0
  5411.3      .1       0  7107.4      .1       0  7249.9     .16       0
  7429.3      .1       0
Bank Sta=4943.5,5411.3
XS Rating Curve= 0 ,0
Exp/Cntr=0.3,0.1

Type RM Length L Ch R = 1 ,4115    ,779,779,779
BEGIN DESCRIPTION:
KLEIN BRANCH 8.0
END DESCRIPTION:
XS GIS Cut Line= 4
      2662385.04     10054021.73      2662878.05     10053917.57
      2663350.28     10053306.46      2665322.51     10053584.24
#Sta/Elev= 30
  4015.4  1939.2  4271.6  1917.7  4464.4 1902.22  4643.4 1898.42  4786.5 1898.74
  4807.3 1896.43  4836.3 1898.29  4857.1 1895.41  4865.3 1890.75    4878 1876.38
  4892.5 1867.35  4915.1  1862.1  4921.4 1860.68  4956.8 1847.47  4991.8 1843.13
  5029.2 1844.31  5064.5 1855.58  5120.7 1861.74  5143.3 1863.63  5306.4 1868.07
  5596.2 1867.49  5804.8 1872.49  6774.3 1871.77  6959.1 1875.42    6996 1882.07
  7030.3 1892.99  7107.5 1938.23  7137.8 1946.33  7158.9 1948.34  7283.3 1952.19
#Mann= 7 ,-1 , 0
  4015.4     .16       0  4271.6      .1       0  4921.4     .09       0
  5143.3     .16       0  6774.3      .1       0    6996     .16       0
  7158.9      .1       0
Bank Sta=4915.1,5120.7
XS Rating Curve= 0 ,0
Exp/Cntr=0.3,0.1

Type RM Length L Ch R = 1 ,3336    ,926,926,926
BEGIN DESCRIPTION:
KLEIN BRANCH 6.0
END DESCRIPTION:
XS GIS Cut Line= 4
      2662565.57      10054313.4        2663635.     10054216.18
      2664121.11     10053514.79        2665260.     10053660.62
#Sta/Elev= 30
  3634.2 1916.71  3651.8 1915.55  3659.8 1914.97  3804.8 1903.13  3957.9 1896.87
  3968.6 1896.71  4716.5 1891.45  4913.9 1890.56    4920 1886.78  4935.8 1858.32
  4949.7 1845.51  4988.6  1843.8  4991.3  1843.3  4994.6  1843.8  5042.2 1845.39
  5100.4 1854.27    5295  1857.8  5380.2 1860.41  5459.7 1870.14  5789.5 1871.21
  5987.4  1870.6  6086.3 1870.41  6185.2  1869.9  6395.5 1872.97  6445.9 1879.17
    6482 1889.12  6526.6 1908.37  6587.1 1945.17  6623.9 1952.35  6709.6 1955.61
#Mann= 15 ,-1 , 0
  3634.2      .1       0  3651.8     .05       0  3659.8      .1       0
  3804.8     .05       0  3957.9      .1       0  3968.6     .05       0
  4716.5      .1       0  4988.6     .07       0  4994.6      .1       0
  5789.5     .05       0  5987.4      .1       0  6086.3     .05       0
  6185.2      .1       0    6482     .16       0  6623.9      .1       0
Bank Sta=4935.8,5295
XS Rating Curve= 0 ,0
Exp/Cntr=0.3,0.1

Type RM Length L Ch R = 1 ,2410    ,453,453,453
BEGIN DESCRIPTION:
KLEIN BRANCH 4.0
END DESCRIPTION:
XS GIS Cut Line= 4
      2663530.88     10054605.06      2664364.16     10054480.07
      2664808.61     10054174.51      2665474.37     10054146.77
#Sta/Elev= 30
  3824.7 1887.86  3936.7  1888.9  4034.6 1876.53  4105.4 1872.79  4631.2 1870.78
    4683 1861.69  4754.7 1860.53  4818.2 1855.95  4916.3 1847.01  4990.8 1839.71
  5026.6 1847.14  5086.4 1848.74    5164 1848.93  5209.1  1845.4  5233.5 1839.56
  5236.3 1839.06  5239.5 1839.56  5246.5 1840.12  5256.6 1845.43  5266.6 1854.12
  5286.6 1864.47  5316.6 1886.73  5348.6 1906.77  5406.7 1952.41  5416.7  1957.9
  5507.9 1975.56  5583.8 1983.91    5717 1993.08    5807 1994.66    5873 1992.96
#Mann= 6 ,-1 , 0
  3824.7     .05       0  4916.3      .1       0  5086.4     .16       0
  5233.5     .07       0  5239.5     .16       0  5507.9      .1       0
Bank Sta=4818.2,5266.6
XS Rating Curve= 0 ,0
Exp/Cntr=0.3,0.1

Type RM Length L Ch R = 1 ,1957    ,616,616,616
BEGIN DESCRIPTION:
KLEIN BRANCH 3.0
END DESCRIPTION:
XS GIS Cut Line= 2
      2663489.12      10054688.4      2665544.08     10054674.52
#Sta/Elev= 30
  3633.3  1885.8  3782.6 1885.36  3822.6 1882.32  3872.6 1874.34  3912.7  1871.1
  4152.7 1869.15  4372.7 1870.67  4582.7 1869.69  4652.7 1867.89  4692.7 1860.41
  4712.7 1858.41  4792.9 1858.83  4832.7 1857.07  4852.7 1854.56  4872.7 1851.31
  4942.7 1847.17  4972.7 1839.93  5032.4 1837.84  5042.7 1838.78  5061.1  1847.7
  5082.7 1854.46  5092.7 1859.34  5122.7 1878.05  5172.7 1912.96  5182.7 1918.11
  5192.7 1920.69  5432.7 1938.52  5502.7 1950.05  5602.7 1969.82  5688.3 1979.57
#Mann= 4 ,-1 , 0
  3633.3     .05       0  4792.9      .1       0  4872.7     .07       0
  5092.7     .16       0
Bank Sta=4852.7,5082.7
XS Rating Curve= 0 ,0
Exp/Cntr=0.3,0.1

Type RM Length L Ch R = 1 ,1341    ,678,678,678
BEGIN DESCRIPTION:
KLEIN BRANCH 2.0
END DESCRIPTION:
XS GIS Cut Line= 3
      2663426.66     10054806.46      2664780.83      10055313.4
      2665697.45     10055049.53
#Sta/Elev= 30
  3256.8 1885.61  3277.6 1885.43  3301.4 1885.83  3550.4 1874.08  3568.4 1871.38
  3831.9 1868.29  4234.4 1868.09  4631.6 1861.62  4702.7 1857.46  4773.1 1850.52
  4839.6 1845.14  4868.1 1841.71  4960.4 1840.93  4999.1 1837.11  5001.8 1836.61
  5005.1 1837.11  5013.2  1839.4 5028.41 1851.04  5041.7  1868.9  5046.9 1870.55
  5054.1 1877.92  5099.9 1879.83  5131.1 1880.54  5324.7 1888.94  5411.9 1900.04
  5443.5 1908.05  5522.4 1936.34    5564 1948.98  5627.5 1961.92  5656.6 1964.58
#Mann= 8 ,-1 , 0
  3256.8      .1       0  3277.6     .05       0  4839.6      .1       0
  4999.1     .07       0  5005.1      .1       0  5099.9     .16       0
  5131.1      .1       0  5411.9     .16       0
Bank Sta=4773.1,5028.41
XS Rating Curve= 0 ,0
Exp/Cntr=0.3,0.1

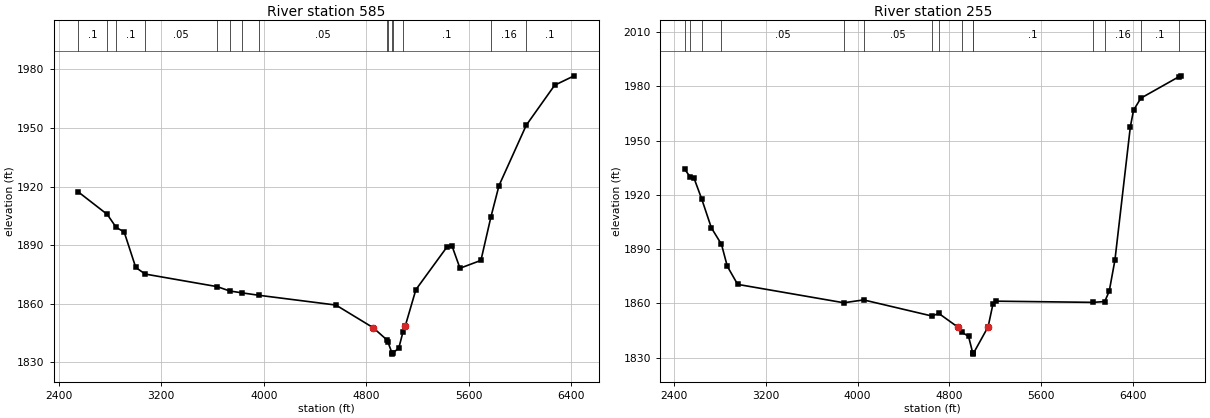
Type RM Length L Ch R = 1 ,585     ,330,330,330
BEGIN DESCRIPTION:
Mapping XS 7cfc821a
END DESCRIPTION:
XS GIS Cut Line= 3
      2662571.18     10055798.05      2665170.15     10055964.72
      2666310.76     10055412.64
#Sta/Elev= 30
  2552.5 1917.26  2778.4 1905.77    2848 1899.12  2910.5 1896.77  3000.7 1878.64
  3074.3 1875.25  3636.8 1868.81  3735.3 1866.58  3833.9  1865.6  3962.1 1864.39
  4563.9 1859.39  4854.5 1847.81  4964.8 1841.39  4970.8 1840.34  5001.8 1834.78
  5004.6 1834.28  5007.8 1834.78  5054.9 1837.41  5087.2  1845.6    5105 1848.64
  5188.1 1867.27  5432.7 1889.27  5470.3 1889.62  5532.5 1878.23  5696.1 1882.25
  5774.1  1904.5  5837.2 1920.52  6049.9 1951.39  6271.9 1971.89    6424 1976.68
#Mann= 15 ,-1 , 0
  2552.5      .1       0  2778.4     .05       0    2848      .1       0
  3074.3     .05       0  3636.8      .1       0  3735.3     .05       0
  3833.9      .1       0  3962.1     .05       0  4964.8      .1       0
  4970.8     .05       0  5001.8    .035       0  5007.8     .05       0
  5087.2      .1       0  5774.1     .16       0  6049.9      .1       0
Bank Sta=4854.5,5105
XS Rating Curve= 0 ,0
Exp/Cntr=0.3,0.1

Type RM Length L Ch R = 1 ,255     ,0,0,0
BEGIN DESCRIPTION:
KLEIN BRANCH 1.0
END DESCRIPTION:
XS GIS Cut Line= 4
      2662508.66     10056188.68      2664862.86     10056292.85
      2665498.27     10056245.97      2666513.67       10055392.
#Sta/Elev= 30
  2494.1 1934.06  2539.1  1930.1    2574 1929.31  2641.7 1917.69  2725.3 1901.82
  2813.7 1892.67  2864.3 1880.56  2954.4 1870.54  3879.8 1860.37  4052.4 1861.95
  4646.7 1853.06  4707.8 1854.46  4876.3 1846.79  4905.3 1844.24  4966.5 1841.79
  5003.6 1832.49  5006.4 1831.99  5009.6 1832.49    5137  1847.1  5180.2 1859.95
  5207.2 1861.25  6048.9  1860.6  6153.4 1861.04  6192.6 1866.84    6242 1883.92
  6376.5 1957.67  6404.6 1966.84  6468.1 1973.45  6800.5 1985.33  6814.5 1985.79
#Mann= 15 ,-1 , 0
  2494.1     .16       0  2539.1     .05       0  2641.7      .1       0
  2813.7     .05       0  3879.8      .1       0  4052.4     .05       0
  4646.7     .16       0  4707.8     .05       0  4905.3      .1       0
  5003.6     .07       0  5009.6      .1       0  6048.9     .05       0
  6153.4     .16       0  6468.1      .1       0  6800.5     .16       0
Bank Sta=4876.3,5137
XS Rating Curve= 0 ,0
Exp/Cntr=0.3,0.1

Chan Stop Cuts=-1
Use User Specified Reach Order=0
Composite Channel Slope=5