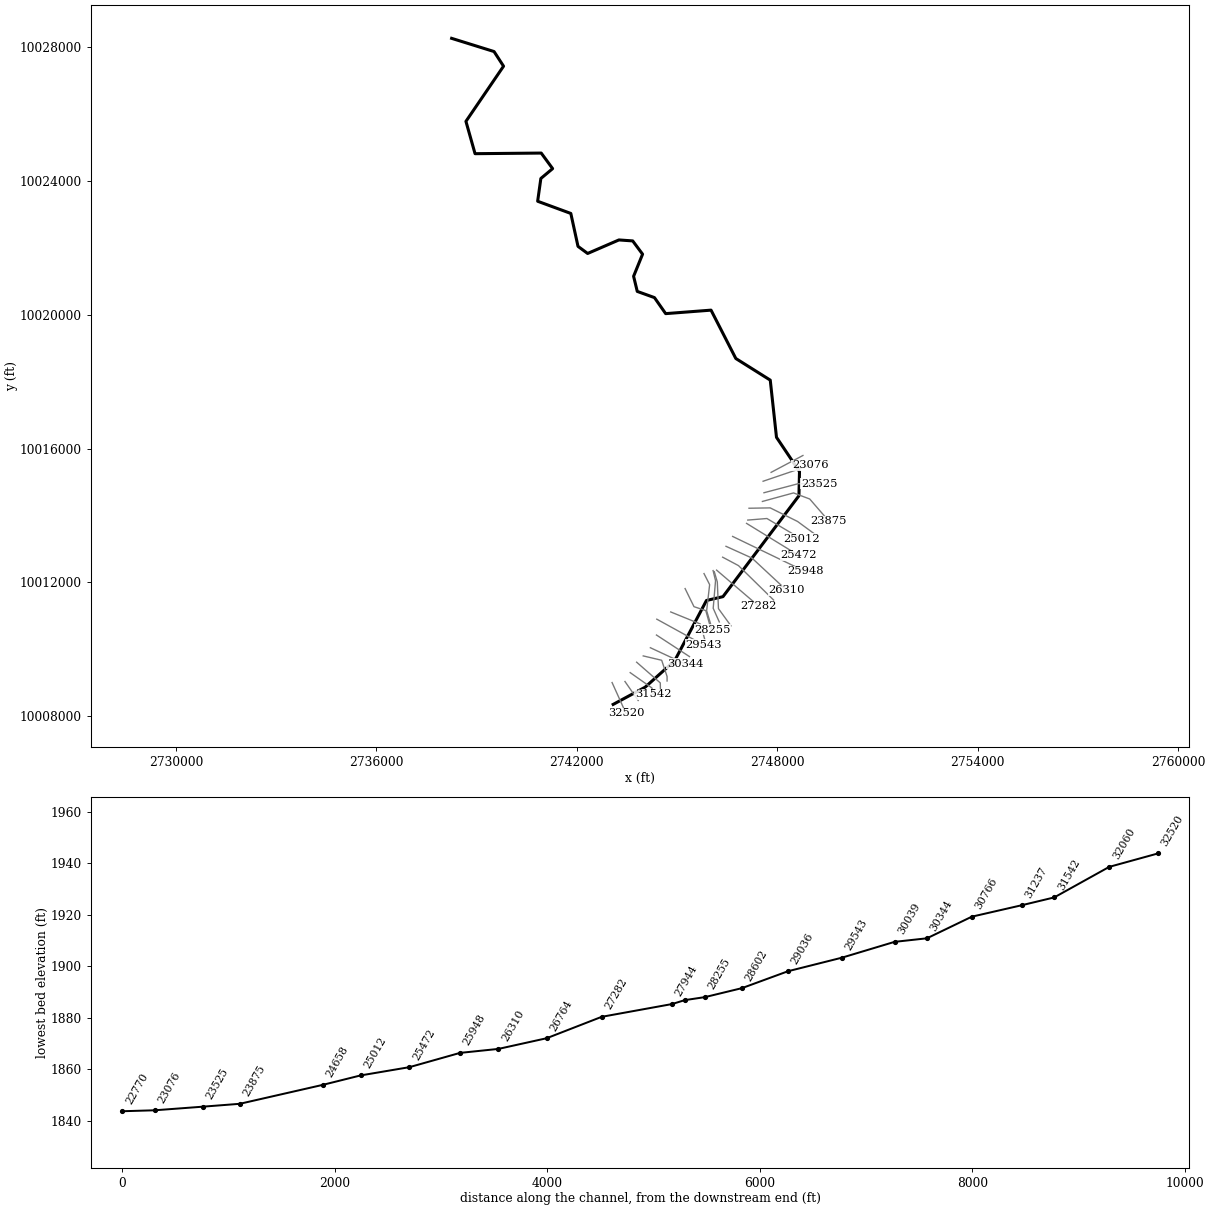
--- LEFT BEAR CREEK.prj (project) ---

Proj Title=LEFT BEAR CREEK Base Level Engineering
Current Plan=p01
Default Exp/Contr=0.3,0.1
English Units
Geom File=g01
Flow File=f01
Plan File=p01
Y Axis Title=Elevation
X Axis Title(PF)=Main Channel Distance
X Axis Title(XS)=Station
BEGIN DESCRIPTION:
LEFT BEAR CREEK
END DESCRIPTION:
DSS Export Rating Curves= 0
DSS Export Rating Curve Sorted= 0
DSS Export Volume Flow Curves= 0
DXF OffsetX= 0
DXF OffsetY= 0
DXF ScaleX= 1
DXF ScaleY= 10

--- LEFT BEAR CREEK.p01 (plan) ---

Plan Title=Multiple Run
Short Identifier=Multiple
Geom File=g01
Flow File=f01
Subcritical Flow
K Sum by GR= 0
Std Step Tol= 0.01
Critical Tol= 0.01
Num of Std Step Trials= 20
Max Error Tol= 0.3
Flow Tol Ratio= 0.001
Split Flow NTrial= 30
Split Flow Tol= 0.02
Split Flow Ratio= 0.02
Log Output Level= 0
Friction Slope Method= 1
Unsteady Friction Slope Method= 2
Unsteady Bridges Friction Slope Method= 1
Parabolic Critical Depth
Global Vel Dist=  1 , 1 , 1
Global Log Level= 0
CheckData=True
Encroach Param= -1, 0, 0, 0
BEGIN DESCRIPTION:
Multiple Run
END DESCRIPTION:

--- LEFT BEAR CREEK.f01 (steady flow) ---

Flow Title=Multiple
Program Version=4.10
Number of Profiles= 7
Profile Names=10-year,25-year,50-year,1pct_min,100-year,1pct_plu,500-year
River Rch & RM=LEFT BEAR CREEK,Reach-1         ,32520
     747    1065    1336    1227    1659    2244    2568
River Rch & RM=LEFT BEAR CREEK,Reach-1         ,30344
    1358    2001    2566    2405    3252    4398    5245
River Rch & RM=LEFT BEAR CREEK,Reach-1         ,28063
    1676    2487    3205    3014    4076    5513    6624
River Rch & RM=LEFT BEAR CREEK,Reach-1         ,21474
    2426    3661    4772    4533    6130    8291   10170
River Rch & RM=LEFT BEAR CREEK,Reach-1         ,20604
    2426    3661    4772    4533    6130    8291   10170
River Rch & RM=LEFT BEAR CREEK,Reach-1         ,20190
    2426    3661    4772    4533    6130    8291   10170
River Rch & RM=LEFT BEAR CREEK,Reach-1         ,16143
    2574    3886    5065    4811    6506    8799   10788
River Rch & RM=LEFT BEAR CREEK,Reach-1         ,11365
    3449    5266    6917    6615    8947   12099   15041
River Rch & RM=LEFT BEAR CREEK,Reach-1         ,10361
    3449    5266    6917    6615    8947   12099   15041
River Rch & RM=LEFT BEAR CREEK,Reach-1         ,8541
    3532    5391    7078    6765    9149   12372   15362
Boundary for River Rch & Prof#=LEFT BEAR CREEK,Reach-1         , 1
Up Type= 0
Dn Type= 3
Dn Slope=0.011
Boundary for River Rch & Prof#=LEFT BEAR CREEK,Reach-1         , 2
Up Type= 0
Dn Type= 3
Dn Slope=0.011
Boundary for River Rch & Prof#=LEFT BEAR CREEK,Reach-1         , 3
Up Type= 0
Dn Type= 3
Dn Slope=0.011
Boundary for River Rch & Prof#=LEFT BEAR CREEK,Reach-1         , 4
Up Type= 0
Dn Type= 3
Dn Slope=0.011
Boundary for River Rch & Prof#=LEFT BEAR CREEK,Reach-1         , 5
Up Type= 0
Dn Type= 3
Dn Slope=0.011
Boundary for River Rch & Prof#=LEFT BEAR CREEK,Reach-1         , 6
Up Type= 0
Dn Type= 3
Dn Slope=0.011
Boundary for River Rch & Prof#=LEFT BEAR CREEK,Reach-1         , 7
Up Type= 0
Dn Type= 3
Dn Slope=0.011
DSS Import GetInterval= 0
DSS Import GetPeak= 0
DSS Import FillOption= 0

--- LEFT BEAR CREEK.g01 (geometry) ---

Geom Title=Existing Conditions
Program Version=4.10

River Reach=LEFT BEAR CREEK ,Reach-1
Reach XY= 30
      2743087.66     10008347.22      2744044.42     10008861.85
      2744929.14      10009654.3      2745880.62     10011456.14
      2746374.71     10011570.35      2748648.23     10014588.76
      2748665.34     10015312.44      2747976.59     10016337.14
      2747790.08     10018047.43      2746759.35     10018694.11
      2746017.63     10020140.67      2744659.61     10020036.49
      2744324.23     10020515.64      2743809.26     10020701.07
      2743699.64     10021153.62      2743968.42     10021814.75
      2743672.73      10022211.8      2743259.75     10022240.63
      2742323.88     10021835.97      2742035.46     10022048.61
      2741820.51     10023033.21      2740827.62     10023398.07
      2740923.56      10024079.3      2741276.04     10024373.77
      2740934.61      10024839.4      2738953.89     10024820.92
      2738680.96      10025787.7      2739806.75     10027437.96
       2739522.8       10027876.      2738252.54     10028271.26

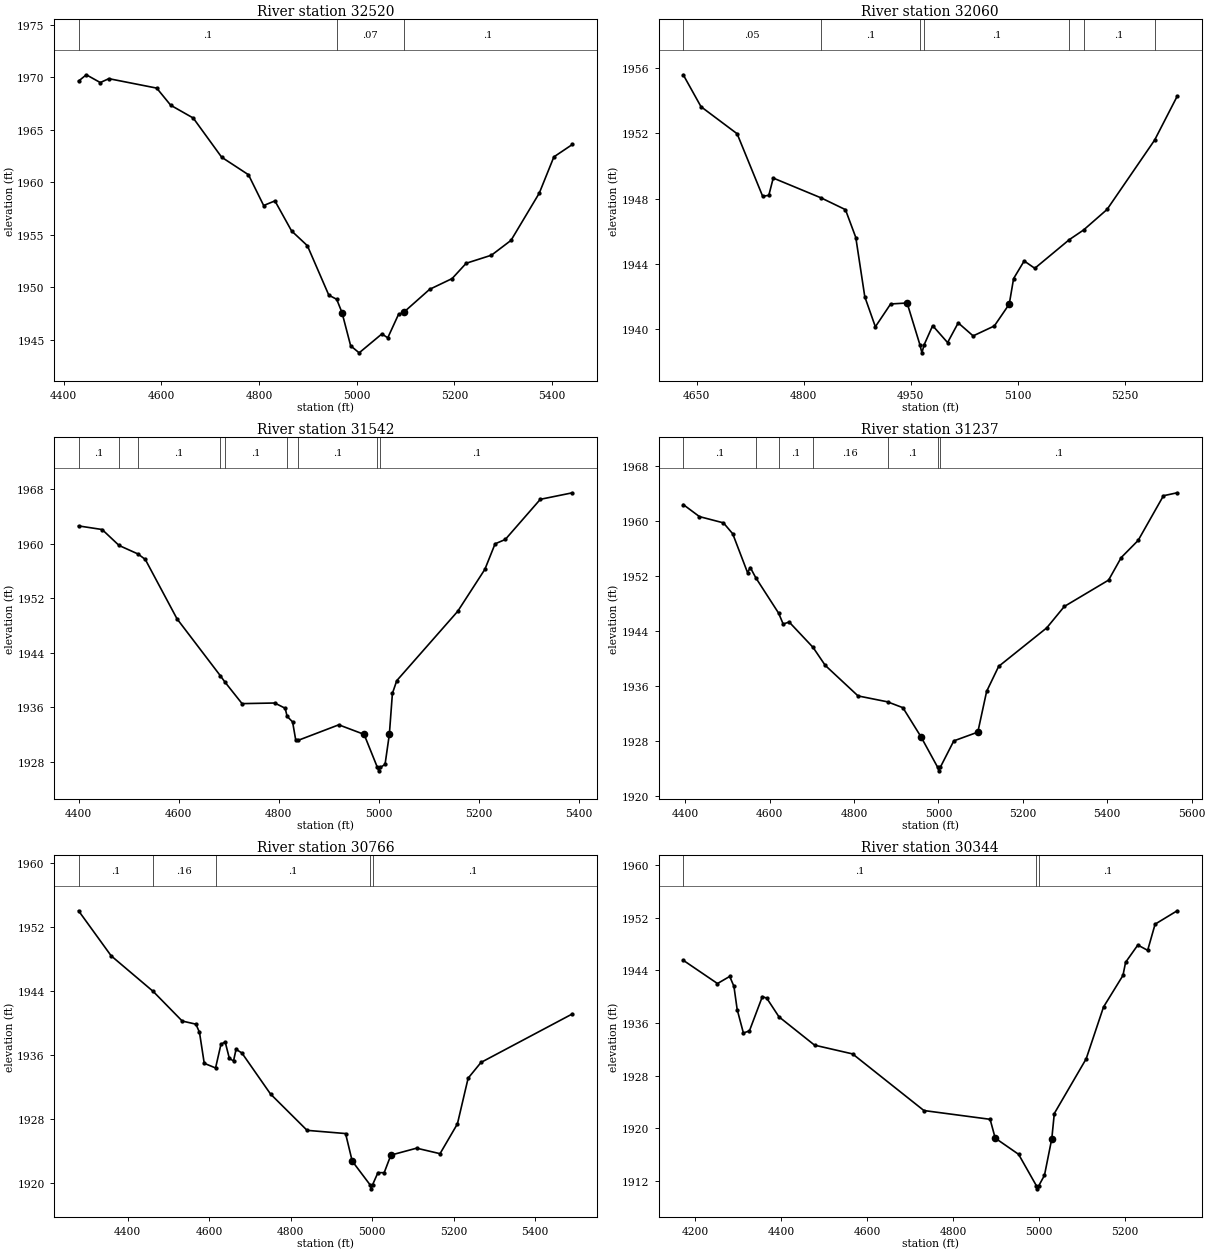
Type RM Length L Ch R = 1 ,32520   ,460,460,460
BEGIN DESCRIPTION:
LEFT BEAR CREEK 68.0
END DESCRIPTION:
XS GIS Cut Line= 2
      2743055.84     10009000.81      2743472.48     10008078.99
#Sta/Elev= 30
  4430.4 1969.63  4446.3 1970.23  4474.9 1969.49  4492.5 1969.86  4590.5 1968.96
  4619.1 1967.33  4665.3 1966.11  4723.5 1962.38  4778.4 1960.71  4809.5 1957.78
  4832.6 1958.22  4866.7 1955.36  4899.1 1953.95    4943 1949.24  4959.1 1948.85
    4970 1947.58  4987.7 1944.42  5005.1 1943.75  5051.6 1945.55  5063.7 1945.18
  5085.7 1947.41  5096.6 1947.62  5149.5  1949.8  5195.4 1950.82  5224.3 1952.28
  5276.1 1953.05  5316.1 1954.46    5374 1958.96  5403.9 1962.41    5442  1963.6
#Mann= 3 ,-1 , 0
  4430.4      .1       0  4959.1     .07       0  5096.6      .1       0
Bank Sta=4970,5096.6
XS Rating Curve= 0 ,0
Exp/Cntr=0.3,0.1

Type RM Length L Ch R = 1 ,32060   ,518,518,518
BEGIN DESCRIPTION:
LEFT BEAR CREEK 67.0
END DESCRIPTION:
XS GIS Cut Line= 2
      2743441.25     10009032.08       2743837.1     10008464.35
#Sta/Elev= 30
  4631.4  1955.6  4656.3 1953.64  4706.9 1951.98  4742.7 1948.14  4751.3  1948.2
  4757.5 1949.26  4824.7 1948.04  4858.7 1947.32  4873.2 1945.61  4885.8 1941.97
  4900.6 1940.13    4922 1941.53  4945.1 1941.59    4963 1939.03  4965.8 1938.53
    4969 1939.03  4980.9  1940.2  5001.8 1939.16  5016.7 1940.37  5037.6 1939.57
  5067.3 1940.18  5088.2 1941.52  5094.3 1943.09  5109.1 1944.17    5124 1943.72
  5172.4 1945.48  5192.3 1946.07  5225.2 1947.33  5291.9 1951.59  5323.5 1954.28
#Mann= 7 ,-1 , 0
  4631.4     .05       0  4824.7      .1       0    4963     .07       0
    4969      .1       0  5172.4     .16       0  5192.3      .1       0
  5291.9     .16       0
Bank Sta=4945.1,5088.2
XS Rating Curve= 0 ,0
Exp/Cntr=0.3,0.1

Type RM Length L Ch R = 1 ,31542   ,305,305,305
BEGIN DESCRIPTION:
LEFT BEAR CREEK 66.0
END DESCRIPTION:
XS GIS Cut Line= 3
      2743597.51      10009297.7      2744248.54     10008839.38
        2744285.     10008651.87
#Sta/Elev= 30
  4399.7 1962.61  4446.8 1962.08  4480.7 1959.74  4518.6 1958.49  4533.1 1957.69
  4596.5 1948.98  4682.9 1940.65  4692.1 1939.72  4726.5 1936.54  4791.8 1936.63
  4812.7 1935.86  4816.5 1934.68  4827.5 1933.86  4833.6 1931.27  4839.2 1931.17
  4919.8 1933.43  4970.4 1932.03    4997 1927.18  4999.7 1926.68    5003 1927.18
  5012.3 1927.63  5020.9 1932.04    5027 1938.04  5035.7 1939.91  5157.6 1950.09
  5211.8 1956.24  5232.2 1959.98  5252.6 1960.62  5322.6 1966.51  5386.9 1967.47
#Mann= 9 ,-1 , 0
  4399.7      .1       0  4480.7     .16       0  4518.6      .1       0
  4682.9     .16       0  4692.1      .1       0  4816.5     .16       0
  4839.2      .1       0    4997     .07       0    5003      .1       0
Bank Sta=4970.4,5020.9
XS Rating Curve= 0 ,0
Exp/Cntr=0.3,0.1

Type RM Length L Ch R = 1 ,31237   ,471,471,471
BEGIN DESCRIPTION:
LEFT BEAR CREEK 65.0
END DESCRIPTION:
XS GIS Cut Line= 3
      2743790.22      10009610.2      2744498.54     10008990.42
      2744503.75     10008761.27
#Sta/Elev= 30
  4395.3 1962.33  4433.7 1960.58  4490.6 1959.67  4512.5 1958.09  4547.6 1952.46
  4554.2 1953.18  4567.5 1951.67  4621.2 1946.57  4632.1 1944.98  4646.3 1945.27
    4703 1941.58  4731.7 1938.98  4809.5 1934.54  4879.4 1933.68  4915.8 1932.83
  4958.5 1928.62  4998.3 1924.16    5001 1923.66  5004.3 1924.16  5036.4 1928.01
  5093.3 1929.28  5114.2  1935.2  5142.7 1938.83  5256.6 1944.42  5298.3 1947.53
  5403.2 1951.36  5433.2 1954.64  5473.2 1957.12  5533.2 1963.61  5565.7 1964.04
#Mann= 7 ,-1 , 0
  4395.3      .1       0  4567.5     .16       0  4621.2      .1       0
    4703     .16       0  4879.4      .1       0  4998.3     .07       0
  5004.3      .1       0
Bank Sta=4958.5,5093.3
XS Rating Curve= 0 ,0
Exp/Cntr=0.3,0.1

Type RM Length L Ch R = 1 ,30766   ,422,422,422
BEGIN DESCRIPTION:
LEFT BEAR CREEK 64.0
END DESCRIPTION:
XS GIS Cut Line= 4
       2743988.1     10009797.72      2744540.21      10009667.5
      2744701.66     10009183.13      2744701.66     10009048.26
#Sta/Elev= 30
  4279.2 1954.01  4359.3 1948.37  4462.6 1943.91  4533.7 1940.21  4567.3 1939.82
  4576.1  1938.8  4587.8 1934.92  4615.6 1934.34  4628.9 1937.31  4639.2 1937.59
  4649.5 1935.53  4659.7 1935.22  4665.9 1936.67  4680.3 1936.21  4750.5 1931.08
  4840.3 1926.53  4934.8 1926.13  4951.1 1922.68    4995 1919.71  4997.8 1919.21
    5001 1919.71  5014.3 1921.24  5029.6 1921.23    5046 1923.43  5109.2  1924.3
  5166.7 1923.61  5209.4 1927.34  5235.7 1933.06  5267.3 1935.03  5491.9 1941.11
#Mann= 5 ,-1 , 0
  4279.2      .1       0  4462.6     .16       0  4615.6      .1       0
    4995     .07       0    5001      .1       0
Bank Sta=4951.1,5046
XS Rating Curve= 0 ,0
Exp/Cntr=0.3,0.1

Type RM Length L Ch R = 1 ,30344   ,305,305,305
BEGIN DESCRIPTION:
LEFT BEAR CREEK 63.0
END DESCRIPTION:
XS GIS Cut Line= 2
      2744201.67      10010042.5      2745242.73     10009558.41
#Sta/Elev= 30
    4173 1945.51  4252.6 1941.98    4281 1943.06  4290.8 1941.56  4298.4 1938.03
  4312.8 1934.48  4326.8 1934.79  4356.9    1940  4367.1 1939.76  4395.5 1936.93
  4478.3 1932.63  4566.7  1931.3  4732.4 1922.71  4886.3 1921.38  4898.1 1918.53
  4952.5 1916.07  4993.6 1911.33  4996.3 1910.83  4999.6 1911.33  5012.6 1912.87
  5029.7 1918.45  5035.5 1922.26  5109.6 1930.56  5149.9 1938.42  5195.1 1943.21
  5201.2  1945.2  5229.6 1947.82  5252.5 1947.02  5269.8 1950.99  5321.1 1953.02
#Mann= 3 ,-1 , 0
    4173      .1       0  4993.6     .07       0  4999.6      .1       0
Bank Sta=4898.1,5029.7
XS Rating Curve= 0 ,0
Exp/Cntr=0.3,0.1

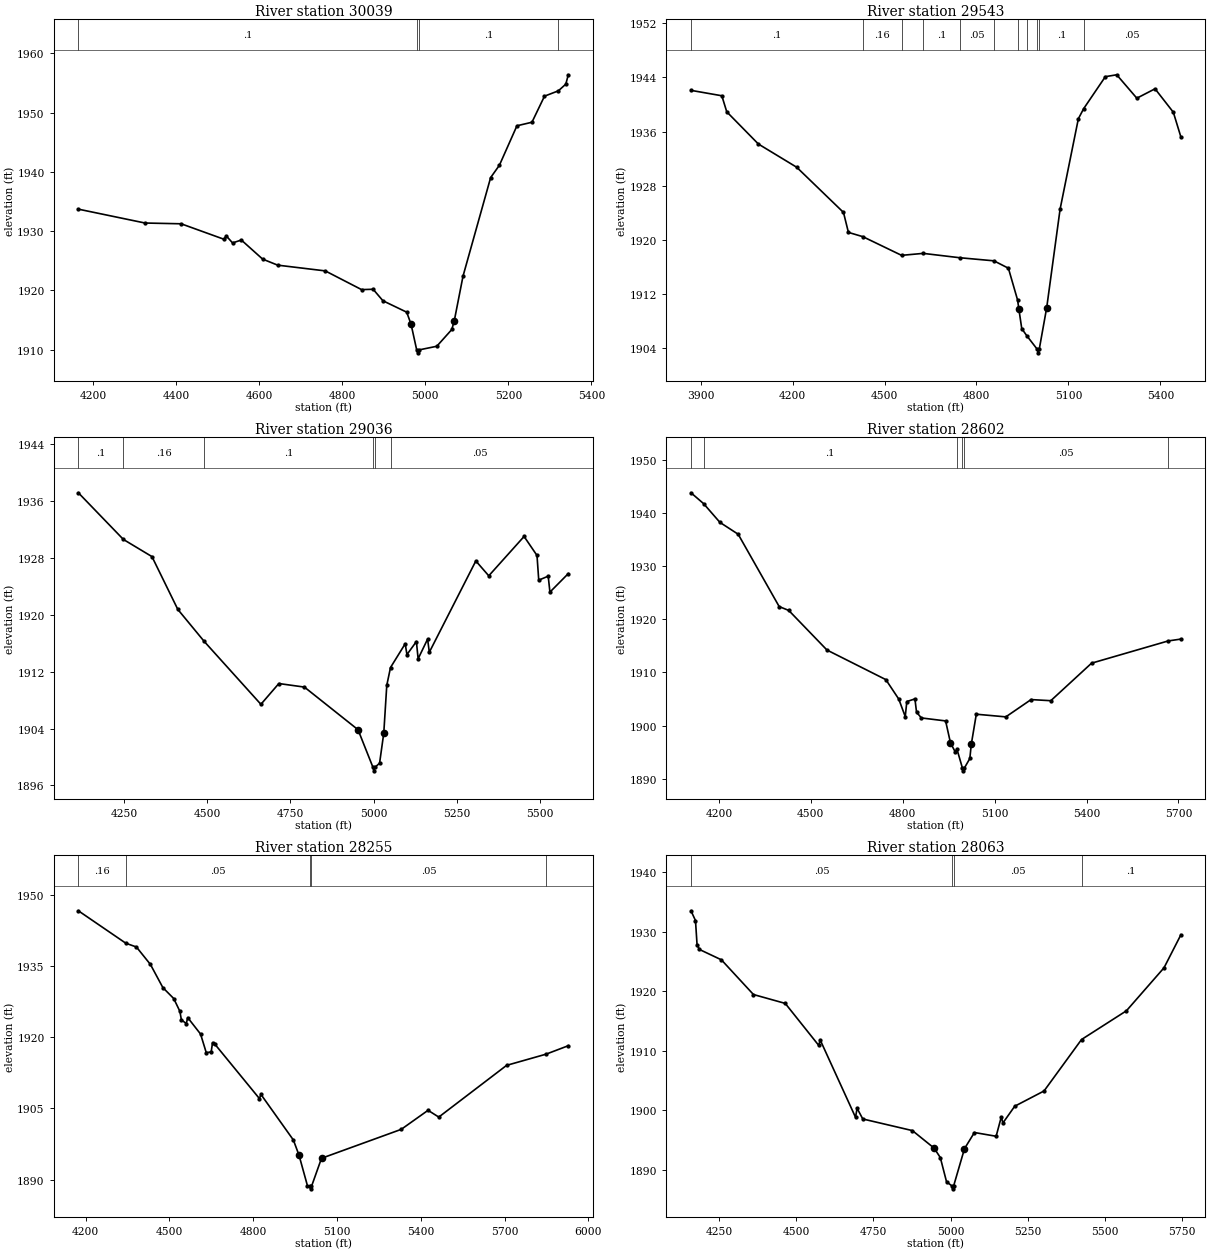
Type RM Length L Ch R = 1 ,30039   ,496,496,496
BEGIN DESCRIPTION:
LEFT BEAR CREEK 62.0
END DESCRIPTION:
XS GIS Cut Line= 2
      2744383.98     10010422.69      2745372.07     10009777.83
#Sta/Elev= 30
  4164.4  1933.7    4325 1931.36    4412 1931.23  4514.7 1928.63  4520.7 1929.18
  4535.8    1928  4556.9 1928.49  4608.2 1925.27  4644.4 1924.25    4759 1923.28
  4846.5 1920.12  4874.3 1920.18  4897.9 1918.24  4955.2 1916.31 4965.68 1914.27
  4979.2 1909.95    4982 1909.45  4985.2 1909.95  5027.6 1910.56  5063.8 1913.39
  5069.8 1914.89  5090.8  1922.4  5157.3 1939.03  5178.4 1941.11  5220.6 1947.77
  5256.8 1948.37    5287 1952.77  5320.4 1953.67  5338.3  1954.8  5344.3 1956.38
#Mann= 4 ,-1 , 0
  4164.4      .1       0  4979.2     .07       0  4985.2      .1       0
  5320.4     .05       0
Bank Sta=4965.68,5069.8
XS Rating Curve= 0 ,0
Exp/Cntr=0.3,0.1

Type RM Length L Ch R = 1 ,29543   ,507,507,507
BEGIN DESCRIPTION:
LEFT BEAR CREEK 61.0
END DESCRIPTION:
XS GIS Cut Line= 2
      2744394.36     10010896.68      2745794.44     10010126.37
#Sta/Elev= 30
  3868.8 1942.08  3969.4 1941.28  3985.5 1938.91  4088.7 1934.15  4213.7 1930.72
  4366.2 1924.05  4382.3  1921.1  4429.3 1920.47  4555.7 1917.71  4626.2    1918
  4744.9 1917.36  4856.9  1916.9  4904.1 1915.81  4934.1 1911.11  4938.3 1909.76
  4947.7 1906.88  4964.9 1905.79  4998.6 1903.81  5001.4 1903.31  5004.6 1903.81
  5029.1    1910  5072.7 1924.53  5132.3 1937.89  5149.8 1939.39  5220.3  1944.1
  5257.4 1944.38    5323 1940.92  5382.4 1942.31    5442 1938.85  5466.8 1935.18
#Mann= 11 ,-1 , 0
  3868.8      .1       0  4429.3     .16       0  4555.7     .05       0
  4626.2      .1       0  4744.9     .05       0  4856.9     .16       0
  4934.1     .05       0  4964.9      .1       0  4998.6     .07       0
  5004.6      .1       0  5149.8     .05       0
Bank Sta=4938.3,5029.1
XS Rating Curve= 0 ,0
Exp/Cntr=0.3,0.1

Type RM Length L Ch R = 1 ,29036   ,434,434,434
BEGIN DESCRIPTION:
Mapping XS b75c0ee2
END DESCRIPTION:
XS GIS Cut Line= 3
        2744811.     10011112.83      2745696.46     10010752.57
      2745839.53      10010258.3
#Sta/Elev= 30
  4113.4 1937.14  4248.6 1930.58  4334.3 1928.17  4411.9 1920.75  4491.3 1916.24
  4661.3 1907.41  4715.2 1910.33  4791.9 1909.83  4952.8 1903.84  4997.6 1898.56
  5000.4 1898.06  5003.6 1898.56  5017.5 1899.13  5030.1 1903.37  5039.1 1910.08
  5050.3 1912.58  5094.4 1915.92  5099.6  1914.4    5128 1916.23  5133.2 1913.81
  5161.6 1916.57  5166.8 1914.73  5306.4 1927.56  5345.2 1925.47  5451.2    1931
    5490 1928.33  5495.2 1924.86  5523.6 1925.42  5528.8 1923.18  5583.9 1925.78
#Mann= 6 ,-1 , 0
  4113.4      .1       0  4248.6     .16       0  4491.3      .1       0
  4997.6     .07       0  5003.6      .1       0  5050.3     .05       0
Bank Sta=4952.8,5030.1
XS Rating Curve= 0 ,0
Exp/Cntr=0.3,0.1

Type RM Length L Ch R = 1 ,28602   ,347,347,347
BEGIN DESCRIPTION:
LEFT BEAR CREEK 60.0
END DESCRIPTION:
XS GIS Cut Line= 4
      2745241.01     10011811.94      2745507.41     10011270.73
      2745860.72     10011152.96      2746028.95     10010552.94
#Sta/Elev= 30
  4109.1 1943.75  4150.3 1941.71  4203.5 1938.19  4263.1 1935.96  4396.9 1922.37
  4428.2 1921.64  4552.9  1914.2    4745 1908.64  4787.2 1904.98  4808.3 1901.69
  4813.5 1904.52  4839.9 1905.02  4845.2 1902.51    4861 1901.44    4940 1900.88
  4955.9 1896.76  4971.7 1895.02  4976.8 1895.62    4995    1892  4997.8  1891.5
    5001    1892  5019.1 1893.82 5023.75 1896.46  5040.2 1902.14  5136.5 1901.64
  5218.9 1904.89  5283.3 1904.68  5416.3 1911.73  5666.4 1915.91  5707.9 1916.26
#Mann= 6 ,-1 , 0
  4109.1     .16       0  4150.3      .1       0  4976.8     .05       0
    4995     .04       0    5001     .05       0  5666.4      .1       0
Bank Sta=4955.9,5023.75
XS Rating Curve= 0 ,0
Exp/Cntr=0.3,0.1

Type RM Length L Ch R = 1 ,28255   ,192,192,192
BEGIN DESCRIPTION:
LEFT BEAR CREEK 59.0
END DESCRIPTION:
XS GIS Cut Line= 4
      2745807.45     10012260.53      2745975.68     10011929.68
      2745885.95     10011150.16      2746056.49     10010577.02
#Sta/Elev= 30
  4174.4 1946.74  4344.3 1939.89  4382.3 1939.09  4432.4 1935.41  4476.9 1930.52
  4515.8 1928.21    4538 1925.49  4543.1 1923.72  4560.8 1922.92  4565.8 1924.19
  4611.9 1920.71  4632.1 1916.81  4649.8 1916.92  4654.8 1918.91  4662.3 1918.63
  4822.8 1907.07  4827.8 1907.98  4944.1 1898.34  4964.3 1895.13  4994.5 1888.68
  5002.9 1888.53  5005.6 1888.03  5008.9 1888.53  5044.8 1894.48  5330.2 1900.59
  5426.2 1904.61  5464.6 1903.18  5707.3  1914.1  5848.4 1916.46  5928.2 1918.25
#Mann= 5 ,-1 , 0
  4174.4     .16       0  4344.3     .05       0  5002.9     .04       0
  5008.9     .05       0  5848.4      .1       0
Bank Sta=4964.3,5044.8
XS Rating Curve= 0 ,0
Exp/Cntr=0.3,0.1

Type RM Length L Ch R = 1 ,28063   ,119,119,119
BEGIN DESCRIPTION:
LEFT BEAR CREEK 57.0
END DESCRIPTION:
XS GIS Cut Line= 4
      2746079.42     10012350.33      2746152.34     10012047.45
      2746082.24     10011223.06        2746264.     10010814.79
#Sta/Elev= 30
  4159.6 1933.49  4174.2 1931.85  4179.3 1927.78    4187    1927  4258.1 1925.26
  4361.8 1919.44  4464.7 1917.95    4573 1910.91    4578  1911.8  4692.2 1898.84
  4697.3 1900.35  4715.7 1898.56  4876.3 1896.61  4946.6 1893.67  4966.6 1892.09
  4986.7 1888.04  5003.8 1887.34  5006.5 1886.84  5009.8 1887.34  5044.9 1893.58
    5077 1896.29  5147.3 1895.66  5164.1 1898.92  5169.2 1897.89  5207.5  1900.7
  5302.4 1903.26  5423.7 1911.89    5569 1916.71  5690.6 1923.92  5745.4 1929.47
#Mann= 4 ,-1 , 0
  4159.6     .05       0  5003.8     .04       0  5009.8     .05       0
  5423.7      .1       0
Bank Sta=4946.6,5044.9
XS Rating Curve= 0 ,0
Exp/Cntr=0.3,0.1

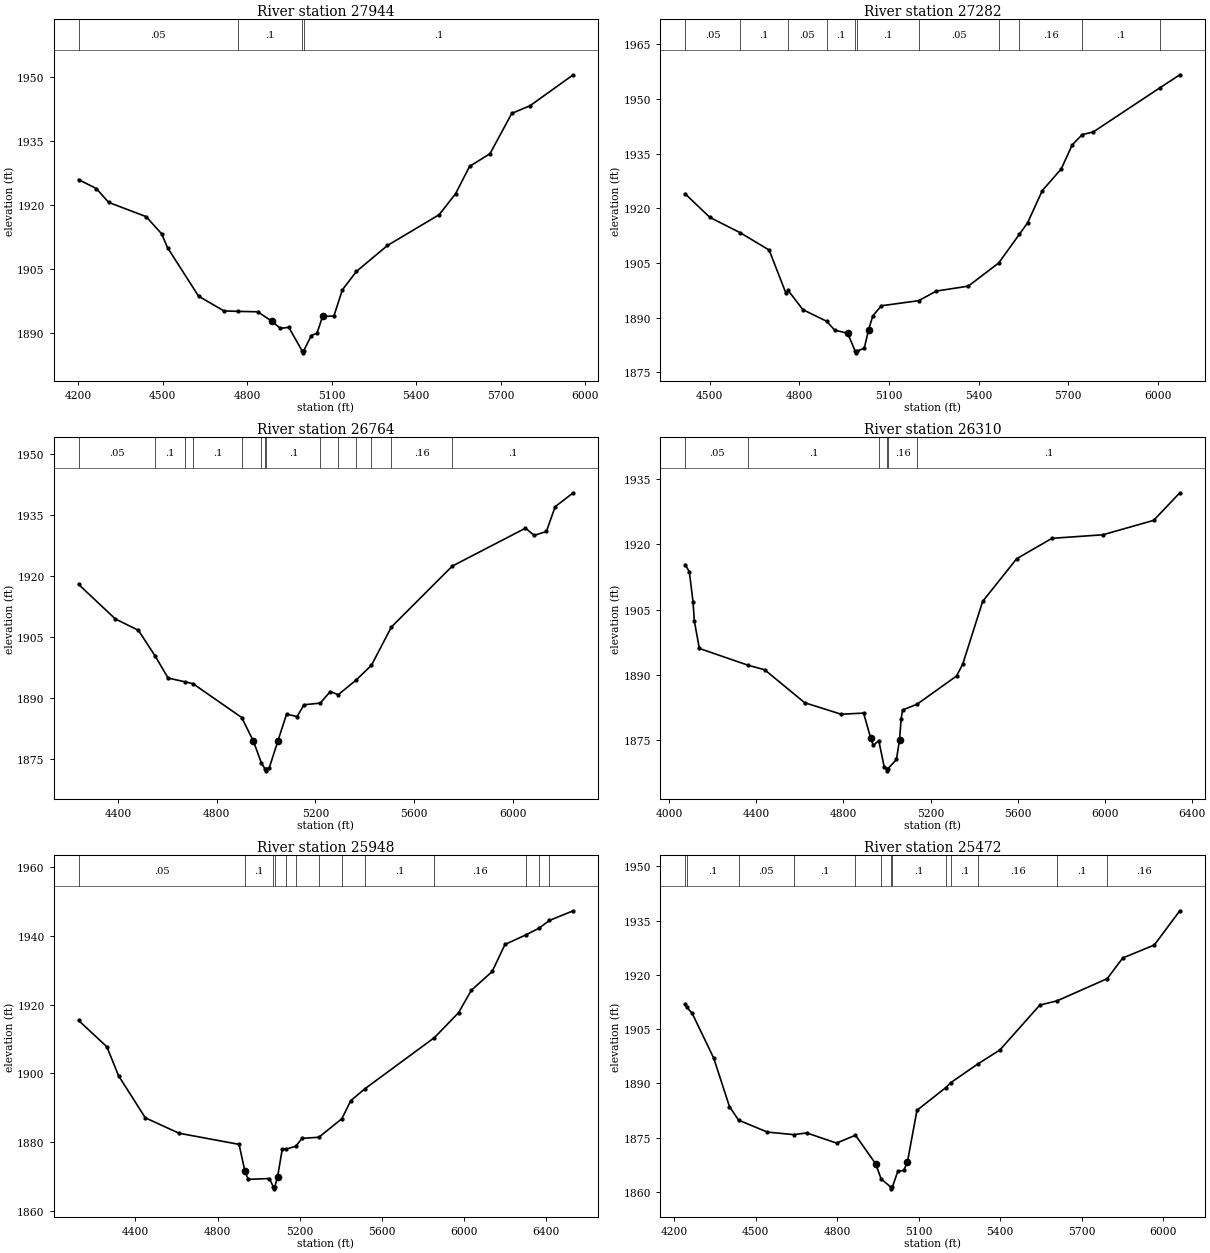
Type RM Length L Ch R = 1 ,27944   ,662,662,662
BEGIN DESCRIPTION:
LEFT BEAR CREEK 58.0
END DESCRIPTION:
XS GIS Cut Line= 4
      2746114.86     10012316.37      2746205.14     10012010.82
      2746239.86     10011212.21      2746614.19     10010695.77
#Sta/Elev= 30
  4201.6 1925.93  4264.5 1923.85  4308.6 1920.59  4441.3 1917.26  4496.3 1913.24
  4517.3 1909.99  4627.4 1898.62  4717.5 1895.16    4766 1895.05  4837.6 1894.95
  4887.6 1892.74  4917.7 1891.06  4947.7 1891.31  4994.7 1885.83  4997.5 1885.33
  5000.7 1885.83  5027.8 1889.39  5047.8 1889.93  5067.8 1893.88  5107.8 1893.95
  5137.9  1900.1  5187.9 1904.42    5298  1910.5  5481.7 1917.72    5540 1922.66
  5589.4 1929.03  5661.9 1932.01  5739.2 1941.46  5804.2 1943.26  5957.4 1950.51
#Mann= 4 ,-1 , 0
  4201.6     .05       0    4766      .1       0  4994.7     .07       0
  5000.7      .1       0
Bank Sta=4887.6,5067.8
XS Rating Curve= 0 ,0
Exp/Cntr=0.3,0.1

Type RM Length L Ch R = 1 ,27282   ,518,518,518
BEGIN DESCRIPTION:
LEFT BEAR CREEK 56.0
END DESCRIPTION:
XS GIS Cut Line= 2
      2746183.46     10012364.53      2747441.79     10011288.44
#Sta/Elev= 30
  4417.6 1923.97    4500 1917.53  4602.5 1913.28  4698.7 1908.56  4754.7 1896.76
  4762.1 1897.51  4811.8 1892.21  4891.2 1889.03  4918.2  1886.6  4961.1 1885.77
  4986.6 1880.88  4989.4 1880.38  4992.6 1880.88    5017 1881.63  5031.3 1886.61
  5045.6  1890.5  5074.1 1893.28  5199.2 1894.68  5258.5 1897.32    5365 1898.66
  5466.8 1904.99  5535.8 1912.83  5563.7 1916.02  5613.1 1924.87  5676.8 1930.85
    5713 1937.38  5746.7 1940.22  5783.3 1940.92  6006.4 1953.03  6073.3 1956.61
#Mann= 11 ,-1 , 0
  4417.6     .05       0  4602.5      .1       0  4762.1     .05       0
  4891.2      .1       0  4986.6     .07       0  4992.6      .1       0
  5199.2     .05       0  5466.8      .1       0  5535.8     .16       0
  5746.7      .1       0  6006.4     .05       0
Bank Sta=4961.1,5031.3
XS Rating Curve= 0 ,0
Exp/Cntr=0.3,0.1

Type RM Length L Ch R = 1 ,26764   ,454,454,454
BEGIN DESCRIPTION:
LEFT BEAR CREEK 55.0
END DESCRIPTION:
XS GIS Cut Line= 3
      2746365.73     10012750.84      2746838.82      10012499.1
      2747889.13     10011470.49
#Sta/Elev= 30
  4239.7  1917.9  4388.8 1909.41  4482.3 1906.62    4551 1900.22  4602.8 1894.88
  4670.3 1893.97  4703.9 1893.49  4901.3 1885.18  4948.8 1879.34  4980.7 1874.07
  4995.4 1872.58  4998.2 1872.08  5001.4 1872.58  5012.6 1872.75  5047.9  1879.4
  5083.1 1886.02  5125.6 1885.42  5153.9 1888.32  5219.7 1888.72    5260 1891.56
  5292.7  1890.8    5364 1894.32  5427.3 1898.02  5508.2 1907.43  5755.1  1922.4
    6052 1931.72  6087.4 1929.95  6136.8 1930.91  6172.3 1936.99  6245.7 1940.42
#Mann= 14 ,-1 , 0
  4239.7     .05       0    4551      .1       0  4670.3     .05       0
  4703.9      .1       0  4901.3     .05       0  4980.7      .1       0
  4995.4     .07       0  5001.4      .1       0  5219.7     .05       0
  5292.7      .1       0    5364     .05       0  5427.3      .1       0
  5508.2     .16       0  5755.1      .1       0
Bank Sta=4948.8,5047.9
XS Rating Curve= 0 ,0
Exp/Cntr=0.3,0.1

Type RM Length L Ch R = 1 ,26310   ,362,362,362
BEGIN DESCRIPTION:
LEFT BEAR CREEK 54.0
END DESCRIPTION:
XS GIS Cut Line= 3
      2746465.54     10013076.36      2747242.46      10012724.8
      2748282.82     10011758.13
#Sta/Elev= 30
  4072.7 1915.33  4091.8 1913.75  4108.8 1906.82  4114.9 1902.35    4138 1896.08
  4360.8 1892.24  4438.1 1891.18    4622  1883.6  4789.3 1880.96  4892.7 1881.22
  4925.5  1875.4  4937.4 1873.78  4962.3  1874.9  4987.3 1868.84  4998.5 1868.44
  5001.2 1867.94  5004.5 1868.44  5043.5 1870.55  5057.6 1875.08    5065 1879.85
  5071.8 1881.94  5138.4 1883.26  5319.5 1889.74  5347.9 1892.46  5439.7  1906.9
  5595.6  1916.7  5758.3 1921.41  5991.9 1922.22  6225.4 1925.54  6345.6 1931.88
#Mann= 6 ,-1 , 0
  4072.7     .05       0  4360.8      .1       0  4962.3     .16       0
  4998.5     .07       0  5004.5     .16       0  5138.4      .1       0
Bank Sta=4925.5,5057.6
XS Rating Curve= 0 ,0
Exp/Cntr=0.3,0.1

Type RM Length L Ch R = 1 ,25948   ,476,476,476
BEGIN DESCRIPTION:
LEFT BEAR CREEK 53.0
END DESCRIPTION:
XS GIS Cut Line= 2
      2746664.33      10013371.5      2748834.84     10012325.28
#Sta/Elev= 30
  4123.1 1915.39  4260.9 1907.73  4317.8  1899.3    4448 1887.07  4611.9 1882.58
  4904.8 1879.33  4933.1 1871.56  4949.2 1869.15  5052.7 1869.39  5072.3 1866.89
    5075 1866.39  5078.3 1866.89  5092.3 1869.83    5115 1877.89  5135.1 1877.96
  5181.7 1878.81    5211 1881.08  5293.5  1881.4  5405.4 1886.79  5448.7 1892.04
  5517.2 1895.49  5856.2 1910.39    5974 1917.65  6036.3 1924.17  6137.8 1929.64
  6200.1 1937.51  6300.2 1940.25    6365 1942.21  6416.7  1944.5  6532.6 1947.31
#Mann= 13 ,-1 , 0
  4123.1     .05       0  4933.1      .1       0  5072.3     .07       0
  5078.3      .1       0  5135.1     .16       0  5181.7     .05       0
  5293.5      .1       0  5405.4     .05       0  5517.2      .1       0
  5856.2     .16       0  6300.2     .05       0    6365      .1       0
  6416.7     .05       0
Bank Sta=4933.1,5092.3
XS Rating Curve= 0 ,0
Exp/Cntr=0.3,0.1

Type RM Length L Ch R = 1 ,25472   ,460,460,460
BEGIN DESCRIPTION:
LEFT BEAR CREEK 52.0
END DESCRIPTION:
XS GIS Cut Line= 2
      2747081.03      10013762.1      2748633.05     10012809.02
#Sta/Elev= 30
  4239.8 1911.84  4246.3 1910.97  4265.7 1909.34    4345 1896.96    4403 1883.57
  4436.3 1879.85  4541.9 1876.55  4640.3 1875.83  4687.2 1876.31  4797.3  1873.5
  4866.9 1875.68  4940.9 1867.81  4961.4  1863.6  4996.6 1861.36  4999.3 1860.86
  5002.6 1861.36    5023 1865.73  5044.7 1865.93  5058.2 1868.35  5093.4 1882.57
  5199.3 1888.82  5218.1 1890.22  5318.3 1895.41  5398.6 1899.23  5545.5 1911.63
  5609.4 1912.81    5794 1918.95  5850.9 1924.65  5966.9 1928.22  6061.1 1937.69
#Mann= 13 ,-1 , 0
  4239.8     .05       0  4246.3      .1       0  4436.3     .05       0
  4640.3      .1       0  4866.9     .05       0  4961.4      .1       0
  4996.6     .07       0  5002.6      .1       0  5199.3     .16       0
  5218.1      .1       0  5318.3     .16       0  5609.4      .1       0
    5794     .16       0
Bank Sta=4940.9,5058.2
XS Rating Curve= 0 ,0
Exp/Cntr=0.3,0.1

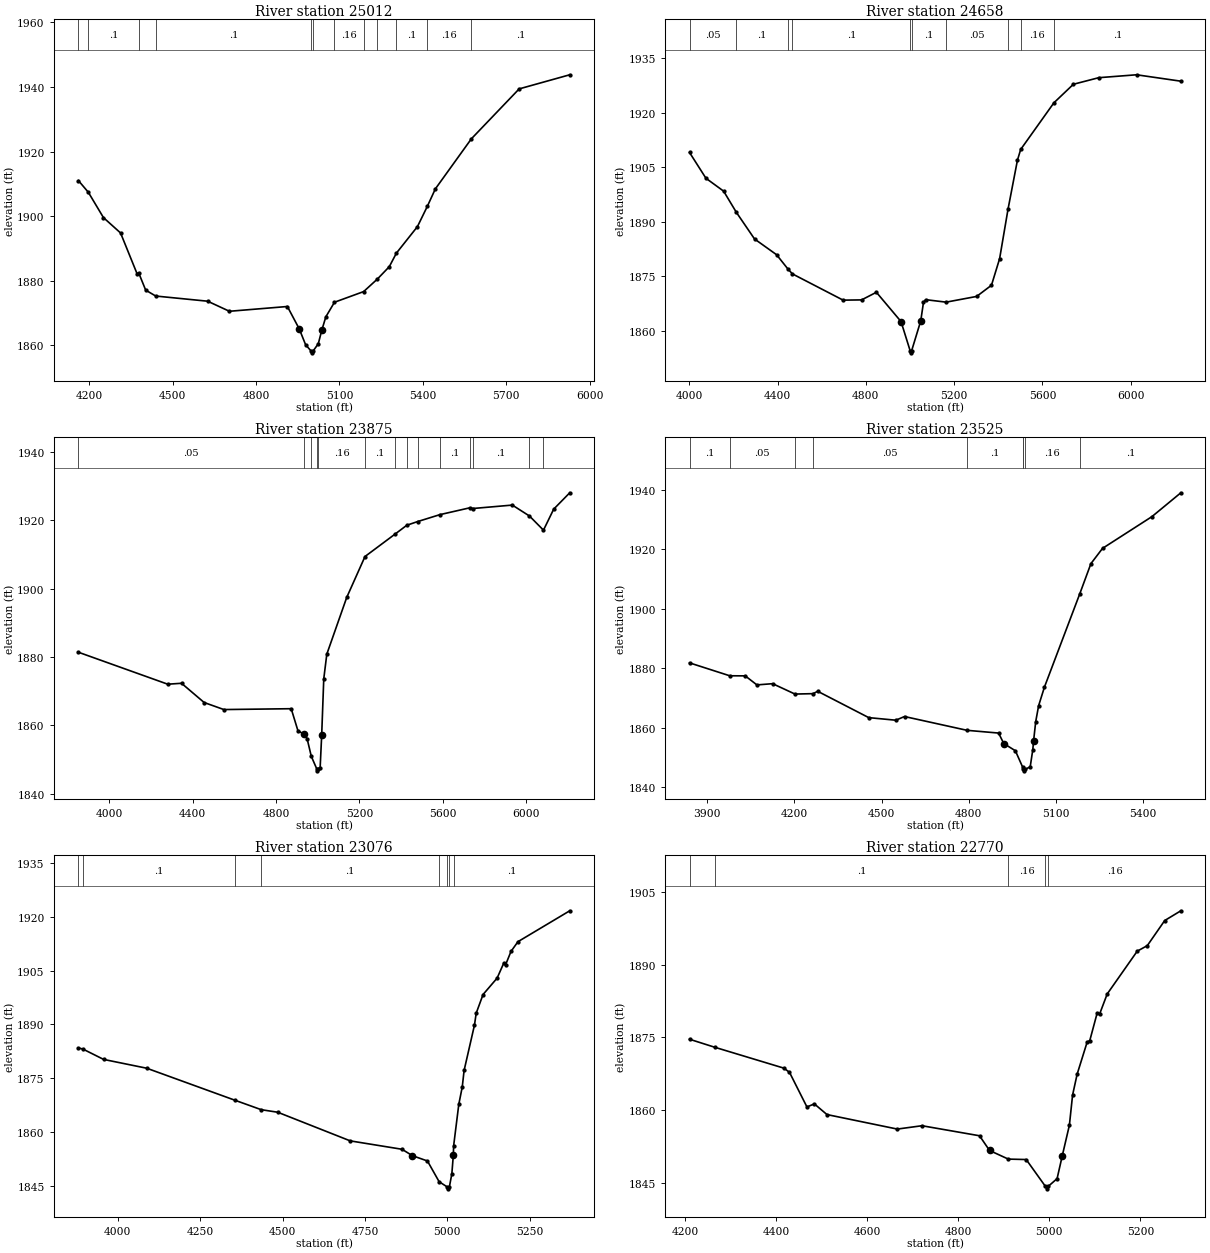
Type RM Length L Ch R = 1 ,25012   ,354,354,354
BEGIN DESCRIPTION:
LEFT BEAR CREEK 51.0
END DESCRIPTION:
XS GIS Cut Line= 3
       2747117.5     10013861.08      2747690.38     10013907.96
      2748714.83     10013299.52
#Sta/Elev= 30
  4161.6 1910.99  4197.1 1907.39  4251.6 1899.53  4313.1 1894.77  4373.1    1882
    4378 1882.46  4403.4 1877.07  4439.5 1875.24  4626.2 1873.64  4704.4 1870.52
  4912.8    1872  4955.6 1865.04  4978.4 1860.14  4998.7 1858.15  5001.4 1857.65
  5004.7 1858.15  5023.9 1860.46  5036.6 1864.69  5051.1 1868.81  5082.1 1873.32
    5187 1876.62  5236.4 1880.51  5279.1 1884.33  5304.8 1888.54  5380.4 1896.75
    5416 1903.04  5444.7 1908.42  5574.2 1923.93    5746 1939.39  5927.9 1943.76
#Mann= 12 ,-1 , 0
  4161.6     .05       0  4197.1      .1       0    4378     .05       0
  4439.5      .1       0  4998.7     .07       0  5004.7      .1       0
  5082.1     .16       0    5187      .1       0  5236.4     .05       0
  5304.8      .1       0    5416     .16       0  5574.2      .1       0
Bank Sta=4955.6,5036.6
XS Rating Curve= 0 ,0
Exp/Cntr=0.3,0.1

Type RM Length L Ch R = 1 ,24658   ,783,783,783
BEGIN DESCRIPTION:
LEFT BEAR CREEK 50.0
END DESCRIPTION:
XS GIS Cut Line= 4
      2747153.93     10014215.25      2747789.34     10014225.66
      2748607.05     10013819.41      2749153.42     10013418.74
#Sta/Elev= 30
  4001.2 1909.04  4075.7 1901.95  4155.8 1898.41  4213.4  1892.6  4295.8 1885.28
  4395.8 1880.95  4447.5    1877  4467.7 1875.68  4697.2 1868.48  4780.9 1868.55
  4847.9 1870.64  4959.5  1862.6  5001.2 1854.51    5004 1854.01  5007.2 1854.51
  5048.9  1862.8  5061.2 1867.86  5071.2 1868.61  5163.9 1867.93  5302.1  1869.5
  5369.3 1872.57  5406.2 1879.87  5444.2 1893.43  5486.9  1906.9  5501.6 1909.86
  5652.1 1922.67  5740.3 1927.76  5855.3 1929.57  6026.7 1930.37  6227.3 1928.61
#Mann= 10 ,-1 , 0
  4001.2     .05       0  4213.4      .1       0  4447.5     .05       0
  4467.7      .1       0  5001.2     .07       0  5007.2      .1       0
  5163.9     .05       0  5444.2      .1       0  5501.6     .16       0
  5652.1      .1       0
Bank Sta=4959.5,5048.9
XS Rating Curve= 0 ,0
Exp/Cntr=0.3,0.1

Type RM Length L Ch R = 1 ,23875   ,350,350,350
BEGIN DESCRIPTION:
LEFT BEAR CREEK 49.0
END DESCRIPTION:
XS GIS Cut Line= 4
        2747555.     10014418.38      2748487.25     10014673.58
      2748971.63     10014491.29      2749543.97     10013830.49
#Sta/Elev= 30
  3851.1 1881.35  4279.8    1872    4346 1872.27  4454.6 1866.64  4549.3 1864.58
  4872.4 1864.83  4904.4 1858.45  4933.6 1857.33  4948.7 1856.07  4968.8 1850.91
  4995.5 1847.15  4998.3 1846.65  5001.5 1847.15  5011.3 1847.56 5018.75 1857.15
  5028.7 1873.58  5043.3 1880.79  5138.9 1897.39  5226.6 1909.36  5371.3 1915.94
  5427.3 1918.51  5479.4 1919.59    5586 1921.61  5730.3 1923.62  5744.6 1923.41
  5933.8 1924.41    6016 1921.21  6083.2 1917.07  6132.3 1923.22  6209.4 1928.01
#Mann= 14 ,-1 , 0
  3851.1     .05       0  4933.6      .1       0  4968.8     .16       0
  4995.5     .07       0  5001.5     .16       0  5226.6      .1       0
  5371.3     .16       0  5427.3      .1       0  5479.4     .05       0
    5586      .1       0  5730.3     .16       0  5744.6      .1       0
    6016     .05       0  6083.2      .1       0
Bank Sta=4933.6,5018.75
XS Rating Curve= 0 ,0
Exp/Cntr=0.3,0.1

Type RM Length L Ch R = 1 ,23525   ,449,449,449
BEGIN DESCRIPTION:
LEFT BEAR CREEK 48.0
END DESCRIPTION:
XS GIS Cut Line= 3
      2747601.85     10014678.79      2748627.88     10014949.62
      2749258.09     10014944.41
#Sta/Elev= 30
  3838.8 1881.83  3977.2 1877.49  4030.6 1877.46  4070.8 1874.42  4124.9 1874.83
  4201.9 1871.34  4264.4 1871.48    4280 1872.28  4455.8 1863.42    4549 1862.55
  4578.9 1863.79  4794.2 1859.15  4902.8 1858.23  4920.6 1854.71  4960.6 1852.28
  4985.1 1846.88  4987.6 1846.03  4990.3 1845.53  4993.6 1846.03  5011.6 1846.87
  5020.6 1852.68 5023.18 1855.52  5030.6 1862.09  5040.6 1867.43  5060.6 1873.68
  5182.5 1905.11  5220.6 1915.19  5260.6 1920.32  5430.6 1930.99  5530.2 1939.01
#Mann= 9 ,-1 , 0
  3838.8      .1       0  3977.2     .05       0  4201.9      .1       0
  4264.4     .05       0  4794.2      .1       0  4985.1     .16       0
  4987.6     .07       0  4993.6     .16       0  5182.5      .1       0
Bank Sta=4920.6,5023.18
XS Rating Curve= 0 ,0
Exp/Cntr=0.3,0.1

Type RM Length L Ch R = 1 ,23076   ,306,306,306
BEGIN DESCRIPTION:
LEFT BEAR CREEK 47.0
END DESCRIPTION:
XS GIS Cut Line= 2
      2747575.83     10015022.55      2748987.21     10015501.69
#Sta/Elev= 30
  3880.8 1883.44  3894.4 1883.14  3957.2 1880.25  4088.1 1877.79  4356.2 1868.84
  4435.5 1866.22  4485.5 1865.51  4705.4 1857.52  4862.4 1855.18  4893.8  1853.4
  4939.6 1851.91    4975 1846.13    5000 1844.64  5002.8 1844.14    5006 1844.64
  5013.6 1848.33 5018.18 1853.64    5019 1856.12  5034.7 1867.73  5045.2 1872.58
  5050.8 1877.18  5082.2 1889.81  5087.5 1893.15  5108.3 1898.36  5150.9 1902.93
  5171.1 1907.12  5176.4  1906.6  5193.1 1910.39  5214.2  1913.1  5371.3 1921.72
#Mann= 8 ,-1 , 0
  3880.8     .05       0  3894.4      .1       0  4356.2     .05       0
  4435.5      .1       0    4975     .16       0    5000     .07       0
    5006     .16       0    5019      .1       0
Bank Sta=4893.8,5018.18
XS Rating Curve= 0 ,0
Exp/Cntr=0.3,0.1

Type RM Length L Ch R = 1 ,22770   ,428,428,428
BEGIN DESCRIPTION:
LEFT BEAR CREEK 46.0
END DESCRIPTION:
XS GIS Cut Line= 2
      2747815.38     10015288.16      2748768.47     10015793.35
#Sta/Elev= 30
  4210.2 1874.61  4265.5 1872.96  4417.4 1868.65  4429.7 1867.79    4468 1860.65
  4484.3 1861.28    4512 1859.08  4666.4 1856.09  4720.6 1856.78  4846.9 1854.71
  4868.9 1851.68  4910.1  1849.9  4949.4 1849.81  4991.6 1844.27  4994.4 1843.77
  4997.6 1844.27  5017.2 1845.87  5028.6  1850.6  5044.2 1856.88  5051.2  1863.1
  5061.2  1867.4  5083.2 1874.03  5088.9 1874.31  5105.2 1880.02  5110.8 1879.86
  5127.2 1883.94  5193.2 1892.77  5215.2  1893.9  5253.5 1899.08  5288.9 1901.09
#Mann= 5 ,-1 , 0
  4210.2     .05       0  4265.5      .1       0  4910.1     .16       0
  4991.6     .07       0  4997.6     .16       0
Bank Sta=4868.9,5028.6
XS Rating Curve= 0 ,0
Exp/Cntr=0.3,0.1