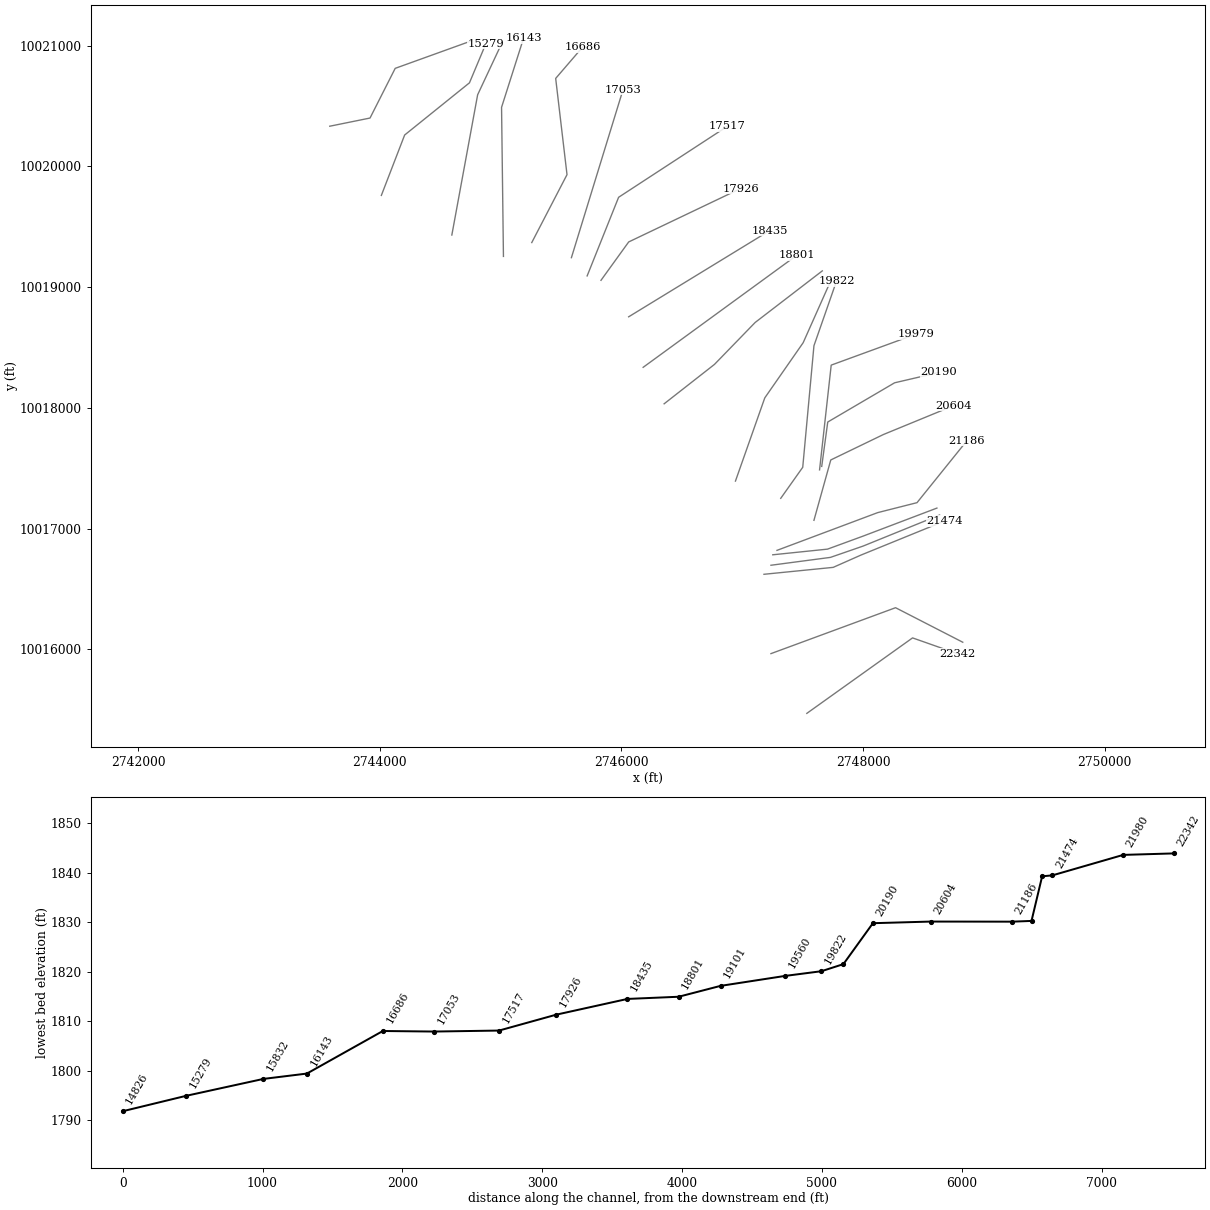
HEC-RAS study LEFT BEAR CREEK.prj: LEFT BEAR CREEK Base Level Engineering

--- LEFT BEAR CREEK.g01 (geometry) --- (continued)

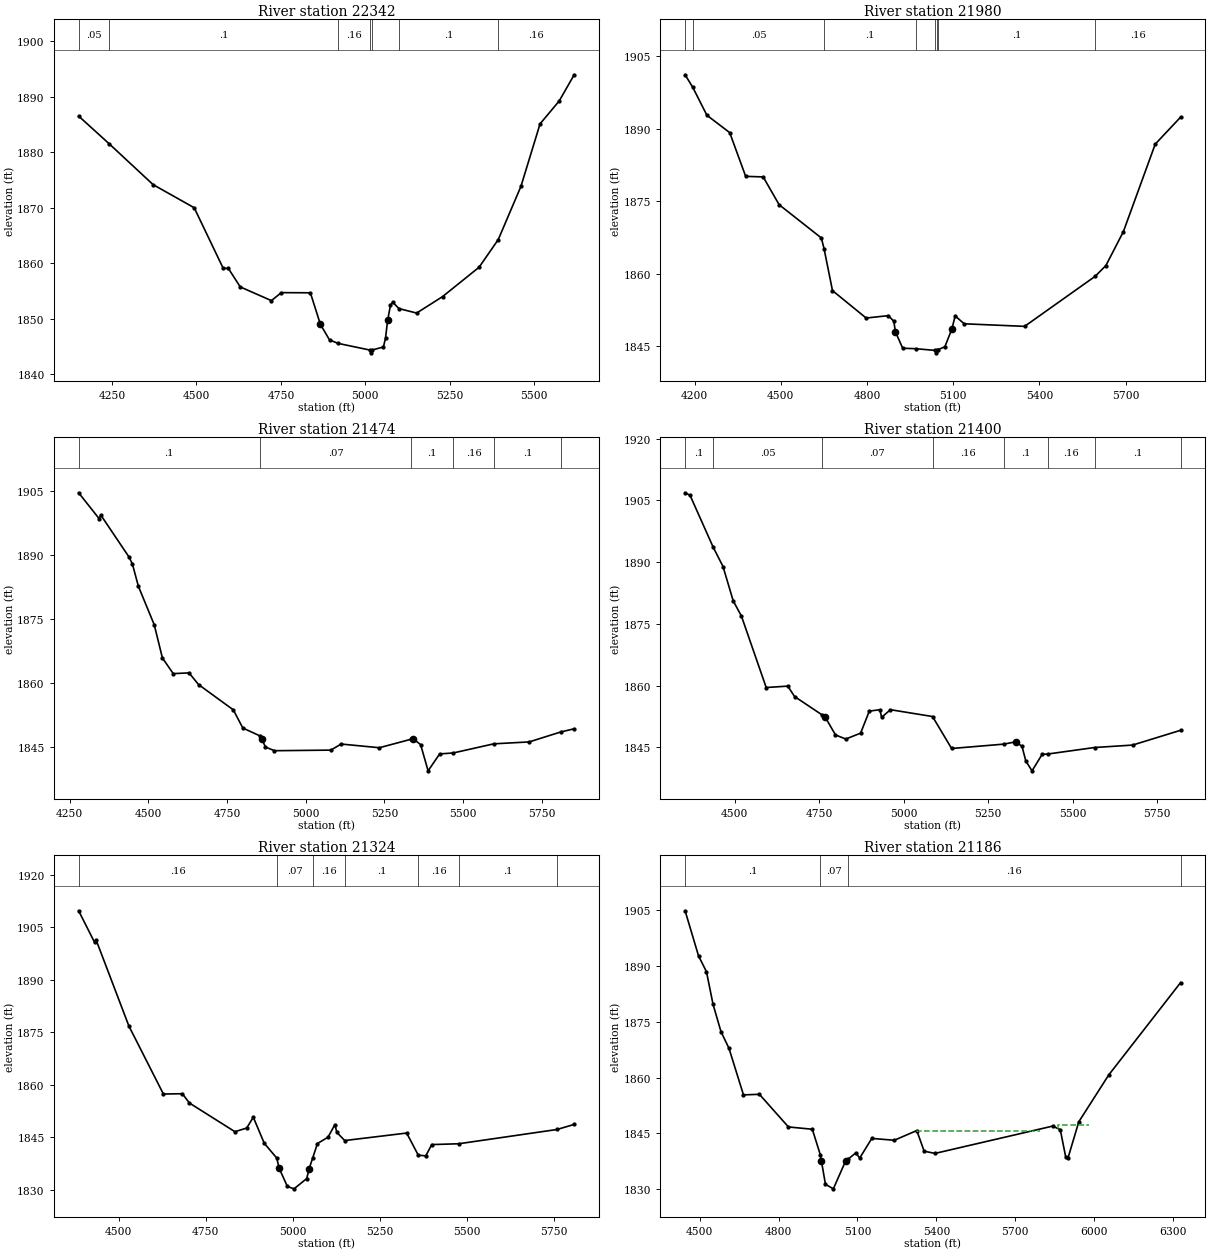
Type RM Length L Ch R = 1 ,22342   ,362,362,362
BEGIN DESCRIPTION:
LEFT BEAR CREEK 45.0
END DESCRIPTION:
XS GIS Cut Line= 3
       2747534.1     10015470.44      2748409.13     10016095.46
      2748778.95     10015965.24
#Sta/Elev= 30
    4151 1886.56  4241.7 1881.55  4371.6  1874.2  4493.2 1870.04  4579.3  1859.1
    4594 1859.14  4629.6 1855.77  4721.8  1853.3  4751.3 1854.74  4837.3 1854.71
  4866.8 1849.04  4893.9 1846.22  4919.6 1845.59  5013.6 1844.39  5016.3 1843.89
  5019.6 1844.39  5053.5 1844.95  5059.8 1846.55  5065.9 1849.73  5074.5 1852.49
  5080.7 1853.02  5099.8 1851.86  5151.9 1851.06  5228.6 1854.02  5336.9 1859.32
  5393.6  1864.3  5460.7 1873.88  5517.4 1885.16    5574 1889.27  5618.4    1894
#Mann= 7 ,-1 , 0
    4151     .05       0  4241.7      .1       0  4919.6     .16       0
  5013.6     .07       0  5019.6     .16       0  5099.8      .1       0
  5393.6     .16       0
Bank Sta=4866.8,5065.9
XS Rating Curve= 0 ,0
Exp/Cntr=0.3,0.1

Type RM Length L Ch R = 1 ,21980   ,506,506,506
BEGIN DESCRIPTION:
LEFT BEAR CREEK 44.0
END DESCRIPTION:
XS GIS Cut Line= 3
      2747237.24     10015965.24       2748268.5     10016345.46
      2748824.62      10016059.6
#Sta/Elev= 30
  4167.1 1901.14  4193.9 1898.53    4243 1892.76  4322.3 1889.17  4377.9 1880.12
  4438.8    1880  4494.3 1874.25  4641.2 1867.37  4650.6 1865.16    4680 1856.47
  4797.2 1850.79  4874.1 1851.29  4893.2 1850.15  4899.2 1847.92  4924.3 1844.54
  4969.3 1844.45  5037.7 1844.09  5040.5 1843.59  5043.7 1844.09  5047.9 1844.25
  5071.2 1844.86  5095.7 1848.58  5106.9 1851.23  5138.3  1849.6  5348.5 1849.07
  5594.1 1859.43  5631.3 1861.65  5692.2 1868.67  5803.1 1886.79  5891.5 1892.38
#Mann= 8 ,-1 , 0
  4167.1      .1       0  4193.9     .05       0  4650.6      .1       0
  4969.3     .05       0  5037.7    .033       0  5043.7     .05       0
  5047.9      .1       0  5594.1     .16       0
Bank Sta=4899.2,5095.7
XS Rating Curve= 0 ,0
Exp/Cntr=0.3,0.1

Type RM Length L Ch R = 1 ,21474   ,74,74,74
BEGIN DESCRIPTION:
Mapping XS f0c7f284
END DESCRIPTION:
XS GIS Cut Line= 4
      2747179.39     10016622.16      2747752.32     10016679.45
      2747981.49     10016781.01      2748674.25     10017063.25
#Sta/Elev= 30
  4278.7 1904.53  4343.9 1898.47    4349 1899.33  4438.6 1889.52  4449.5 1887.87
  4468.7 1882.62    4519 1873.63  4544.9 1865.87  4579.3 1862.21  4629.5 1862.38
  4659.7 1859.65  4770.2 1853.73  4800.4 1849.48  4854.5 1847.65  4861.2 1846.87
    4872 1845.05  4900.8 1844.17  5080.1 1844.31  5112.7 1845.73  5234.2 1844.87
  5335.8 1846.87  5341.2 1846.98  5365.3  1845.6  5389.1 1839.46  5425.8 1843.42
  5468.6 1843.64  5597.9 1845.78  5710.3 1846.23  5810.8 1848.56  5853.2  1849.3
#Mann= 6 ,-1 , 0
  4278.7      .1       0  4854.5     .07       0  5335.8      .1       0
  5468.6     .16       0  5597.9      .1       0  5810.8     .05       0
Bank Sta=4861.2,5341.2
XS Rating Curve= 0 ,0
Exp/Cntr=0.3,0.1

Type RM Length L Ch R = 1 ,21400   ,76,76,76
BEGIN DESCRIPTION:
Mapping XS 3c0bdf25
END DESCRIPTION:
XS GIS Cut Line= 4
      2747237.27     10016697.02      2747729.44     10016762.12
      2748000.27     10016855.87      2748633.28     10017113.01
#Sta/Elev= 30
    4353 1906.84  4367.7 1906.21  4435.9 1893.65  4465.2 1888.92  4495.4 1880.56
  4519.6 1876.89    4593 1859.51  4656.8 1859.85    4677 1857.32  4757.7 1852.89
  4767.8 1852.28    4798 1847.99  4828.5 1846.99  4872.3 1848.42  4898.1 1853.77
  4929.3 1854.12  4934.6 1852.26  4960.5 1854.12  5085.1 1852.46  5141.6 1844.69
    5296 1845.75  5331.7 1846.32    5350 1845.21  5361.2 1841.63  5379.6 1839.26
  5409.4 1843.26  5425.5 1843.34  5564.6 1844.93  5677.1 1845.52  5819.3 1849.12
#Mann= 8 ,-1 , 0
    4353      .1       0  4435.9     .05       0  4757.7     .07       0
  5085.1     .16       0    5296      .1       0  5425.5     .16       0
  5564.6      .1       0  5819.3     .05       0
Bank Sta=4767.8,5331.7
XS Rating Curve= 0 ,0
Exp/Cntr=0.3,0.1

Type RM Length L Ch R = 1 ,21324   ,138,138,138
BEGIN DESCRIPTION:
Mapping XS d612bedc
END DESCRIPTION:
XS GIS Cut Line= 4
      2747252.29     10016783.61      2747705.45     10016830.49
      2747997.11     10016937.26      2748610.68      10017170.3
#Sta/Elev= 30
  4385.2 1909.71  4430.8 1900.72  4435.8 1901.26  4529.6 1876.74  4628.5 1857.35
    4683 1857.43  4703.1 1854.78  4833.8 1846.58  4867.7 1847.63  4886.6 1850.72
  4918.1 1843.26  4953.9 1839.05  4961.1 1836.07  4984.4 1830.93  5003.5 1830.25
  5040.1  1833.2  5046.3 1835.82    5057 1839.04  5070.7 1843.18  5101.2 1845.03
  5120.9 1848.61  5126.4 1846.37  5149.1 1844.05  5326.9 1846.19  5360.2 1839.87
  5381.8 1839.68  5398.8  1842.9  5476.2 1843.13  5758.5 1847.21  5807.7 1848.66
#Mann= 7 ,-1 , 0
  4385.2     .16       0  4953.9     .07       0    5057     .16       0
  5149.1      .1       0  5360.2     .16       0  5476.2      .1       0
  5758.5     .05       0
Bank Sta=4961.1,5046.3
XS Rating Curve= 0 ,0
Exp/Cntr=0.3,0.1

Type RM Length L Ch R = 1 ,21186   ,582,582,582
BEGIN DESCRIPTION:
LEFT BEAR CREEK 43.0
END DESCRIPTION:
XS GIS Cut Line= 4
      2747287.18     10016820.29       2748120.5     10017132.78
      2748446.02     10017215.25      2748858.35     10017727.41
#Sta/Elev= 30
  4444.8 1904.81  4495.8 1892.71    4526 1888.44    4551 1879.68  4581.2 1872.33
  4611.5 1867.87  4666.7 1855.34  4727.2  1855.5  4837.5 1846.73  4928.3 1846.11
  4958.8 1839.23 4963.07 1837.51  4978.2 1831.32  5008.2  1830.1  5054.9  1837.6
  5063.6 1838.04  5093.9 1839.78  5108.3 1838.36  5154.4 1843.65  5239.8 1843.15
  5325.3 1845.76  5353.3 1840.22  5394.6 1839.62  5841.9 1846.96  5870.7    1846
  5891.5 1838.58  5899.5 1838.26  5941.1 1848.12  6054.7 1860.69  6328.1 1885.53
#Mann= 4 ,-1 , 0
  4444.8      .1       0  4958.8     .07       0  5063.6     .16       0
  6328.1      .1       0
#XS Ineff= 2 ,-1
  5326.7 5792.61 1845.62 5862.22 5978.69 1847.22
Permanent Ineff=
       F       F
Bank Sta=4963.07,5054.9
XS Rating Curve= 0 ,0
Exp/Cntr=0.3,0.1

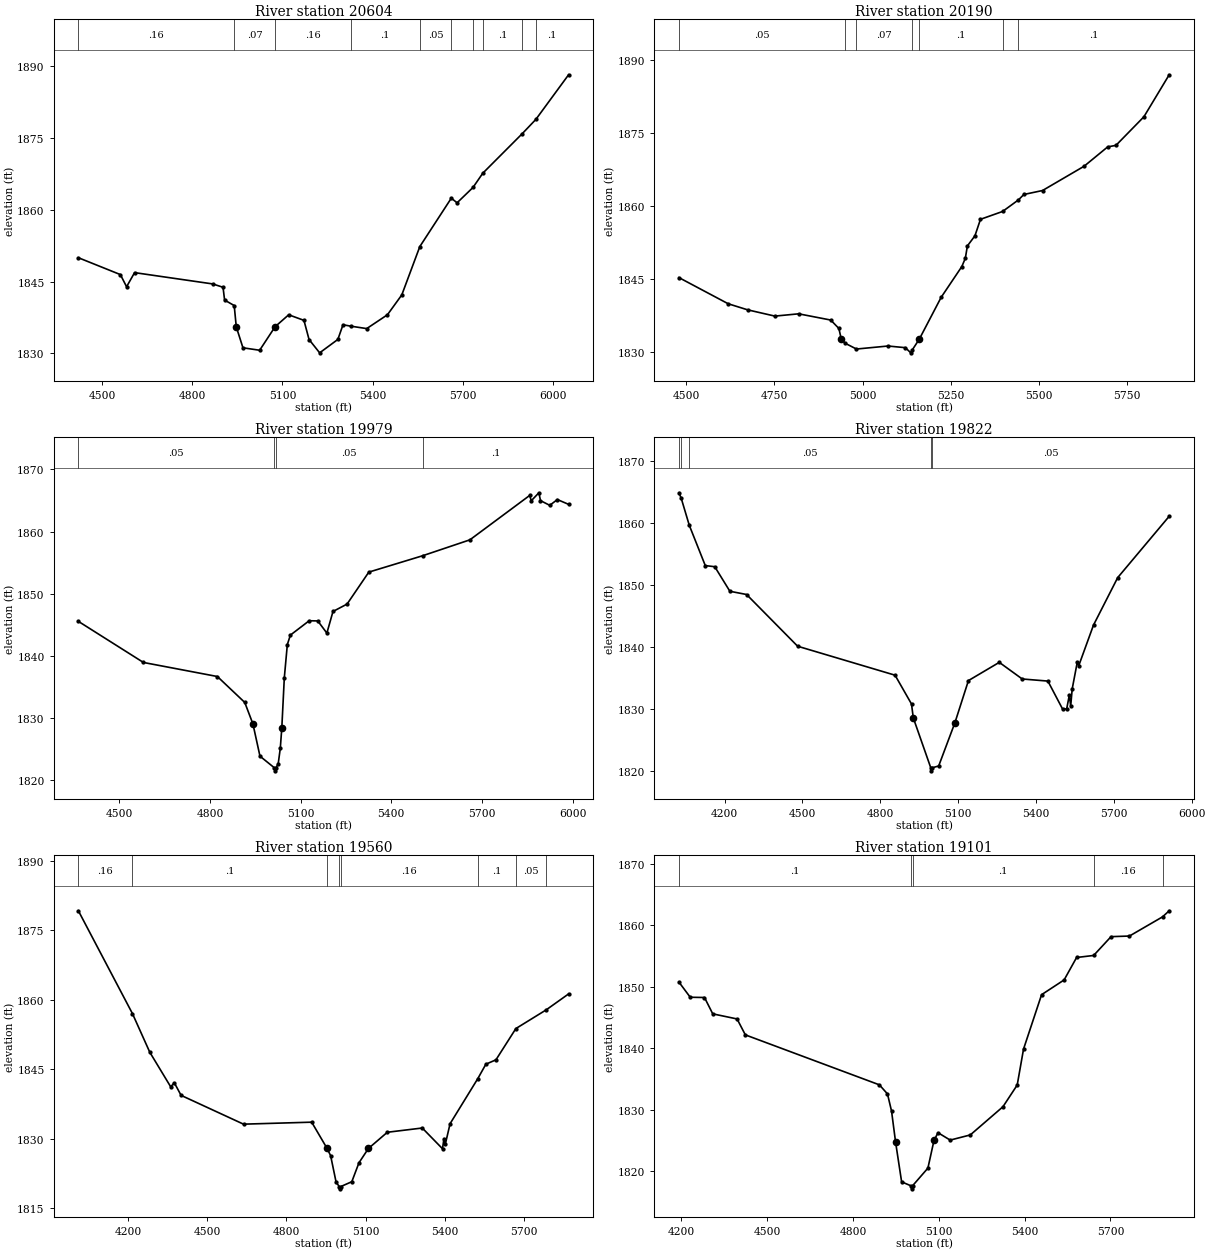
Type RM Length L Ch R = 1 ,20604   ,414,414,414
BEGIN DESCRIPTION:
LEFT BEAR CREEK 42.0
END DESCRIPTION:
XS GIS Cut Line= 4
      2747593.09      10017069.1      2747732.31     10017568.85
      2748167.81     10017779.46      2748749.64     10018018.62
#Sta/Elev= 30
  4420.8 1849.97  4560.6 1846.45  4581.3 1843.91  4607.9 1846.86  4868.1  1844.5
  4902.3  1843.8  4907.5 1841.13  4939.5 1839.99  4946.4 1835.54  4968.6 1831.17
  5024.2 1830.66  5075.6 1835.57  5120.8 1838.06  5171.6  1836.9  5188.6  1832.9
  5223.9 1830.12  5284.5 1832.92  5301.6 1835.98  5327.1 1835.69  5380.5 1835.18
  5449.4 1838.06  5497.3 1842.21  5557.3  1852.3  5662.1  1862.4  5681.3 1861.43
  5734.2 1864.63  5766.9 1867.61  5898.2 1875.86  5943.5 1878.84  6052.4 1888.15
#Mann= 10 ,-1 , 0
  4420.8     .16       0  4939.5     .07       0  5075.6     .16       0
  5327.1      .1       0  5557.3     .05       0  5662.1      .1       0
  5734.2     .05       0  5766.9      .1       0  5898.2     .05       0
  5943.5      .1       0
Bank Sta=4946.4,5075.6
XS Rating Curve= 0 ,0
Exp/Cntr=0.3,0.1

Type RM Length L Ch R = 1 ,20190   ,211,211,211
BEGIN DESCRIPTION:
Mapping XS 19d416eb
END DESCRIPTION:
XS GIS Cut Line= 4
      2747657.35     10017515.32      2747707.32     10017882.99
      2748260.62     10018207.82      2748628.31      10018293.5
#Sta/Elev= 30
  4479.2 1845.23  4618.9 1839.86  4673.8 1838.62  4751.2 1837.33  4818.6  1837.8
  4909.6 1836.52  4932.7 1834.79  4939.6 1832.56  4950.7 1831.75  4982.5 1830.57
  5071.9 1831.19  5121.2 1830.85  5136.6 1829.79  5139.9 1830.29  5160.9 1832.62
  5222.8  1841.2  5281.4 1847.51  5291.3 1849.21  5297.1 1851.74  5318.5 1853.81
  5334.2  1857.2  5396.9 1858.81  5441.8 1861.18  5457.3  1862.3  5510.2 1863.11
  5628.2  1868.1    5695 1872.07  5718.4 1872.38  5797.7 1878.25  5869.4 1886.87
#Mann= 7 ,-1 , 0
  4479.2     .05       0  4950.7     .16       0  4982.5     .07       0
  5139.9     .16       0  5160.9      .1       0  5396.9     .05       0
  5441.8      .1       0
Bank Sta=4939.6,5160.9
XS Rating Curve= 0 ,0
Exp/Cntr=0.3,0.1

Type RM Length L Ch R = 1 ,19979   ,157,157,157
BEGIN DESCRIPTION:
LEFT BEAR CREEK 41.0
END DESCRIPTION:
XS GIS Cut Line= 3
       2747639.5     10017486.72      2747735.88     10018354.18
      2748439.09     10018611.19
#Sta/Elev= 30
  4364.9 1845.56  4580.1 1838.95  4824.7 1836.69  4915.3 1832.52  4942.3 1829.06
  4965.6 1823.88  5012.9 1822.02  5015.6 1821.52  5018.9 1822.02    5026 1822.68
  5032.9 1825.18  5037.9 1828.49  5046.1 1836.47  5056.1 1841.83  5066.2 1843.35
  5128.4 1845.66  5156.8 1845.63  5186.9 1843.67  5207.1 1847.15  5253.7 1848.34
  5325.6 1853.48  5503.4 1856.11  5659.9 1858.67  5857.7 1865.81    5863 1864.96
  5888.2 1866.24  5893.5 1864.98  5924.1 1864.22  5949.3 1865.15  5986.4 1864.38
#Mann= 4 ,-1 , 0
  4364.9     .05       0  5012.9     .04       0  5018.9     .05       0
  5503.4      .1       0
Bank Sta=4942.3,5037.9
XS Rating Curve= 0 ,0
Exp/Cntr=0.3,0.1

Type RM Length L Ch R = 1 ,19822   ,262,262,262
BEGIN DESCRIPTION:
LEFT BEAR CREEK 40.0
END DESCRIPTION:
XS GIS Cut Line= 4
      2747318.24     10017251.16      2747500.28     10017508.17
      2747593.09     10018514.82      2747778.71     10019046.69
#Sta/Elev= 30
  4024.2 1864.92  4032.9 1864.03  4063.9 1859.68  4125.6 1853.18  4162.1    1853
  4220.4 1849.04  4284.7 1848.52  4481.5 1840.18  4856.9 1835.51  4920.3 1830.87
  4927.2 1828.63  4994.5 1820.59  4997.2 1820.09  5000.5 1820.59    5025 1820.87
  5087.9 1827.88  5139.7 1834.64  5258.6 1837.58    5347  1834.9  5445.9 1834.56
  5502.7 1830.04  5518.4 1830.08  5528.5 1832.29  5533.8 1830.53  5539.6  1833.3
  5559.5 1837.68  5564.8 1837.04  5621.7 1843.59  5714.9 1851.24  5913.4 1861.13
#Mann= 5 ,-1 , 0
  4024.2     .16       0  4032.9      .1       0  4063.9     .05       0
  4994.5     .04       0  5000.5     .05       0
Bank Sta=4927.2,5087.9
XS Rating Curve= 0 ,0
Exp/Cntr=0.3,0.1

Type RM Length L Ch R = 1 ,19560   ,459,459,459
BEGIN DESCRIPTION:
LEFT BEAR CREEK 39.0
END DESCRIPTION:
XS GIS Cut Line= 4
      2746943.43     10017393.98      2747186.15     10018082.89
      2747503.85      10018539.8      2747735.38     10019059.86
#Sta/Elev= 30
  4012.5 1879.19  4217.2 1856.99    4283 1848.63  4362.1 1841.17  4375.9 1842.03
  4401.5 1839.32  4637.8  1833.1    4896 1833.53  4952.8    1828  4955.7 1827.66
  4967.6 1826.32  4988.5 1820.55  5000.4 1819.63  5003.1 1819.13  5006.4 1819.63
  5047.9 1820.67    5075 1824.76  5110.8 1827.85  5182.4 1831.35  5314.7 1832.27
  5391.3 1827.79  5396.8 1829.97  5402.3 1828.86    5420  1833.2    5525 1842.94
  5555.5 1846.05  5593.7    1847  5669.1 1853.75    5784 1857.79  5868.7 1861.23
#Mann= 8 ,-1 , 0
  4012.5     .16       0  4217.2      .1       0  4955.7     .16       0
  5000.4     .07       0  5006.4     .16       0    5525      .1       0
  5669.1     .05       0    5784      .1       0
Bank Sta=4952.8,5110.8
XS Rating Curve= 0 ,0
Exp/Cntr=0.3,0.1

Type RM Length L Ch R = 1 ,19101   ,300,300,300
BEGIN DESCRIPTION:
LEFT BEAR CREEK 38.0
END DESCRIPTION:
XS GIS Cut Line= 4
      2746353.17     10018033.85      2746769.81     10018360.21
      2747106.61     10018707.43      2747662.14      10019134.5
#Sta/Elev= 30
  4191.9 1850.76  4231.3  1848.3  4281.1 1848.26    4310  1845.6    4395 1844.77
  4423.9 1842.18  4892.5 1834.05  4920.8 1832.57    4935 1829.78    4949 1824.77
  4970.2 1818.27  5002.5 1817.63  5005.2 1817.13  5008.5 1817.63  5062.1  1820.5
  5083.4 1825.01  5097.5 1826.26    5140 1825.06  5210.3  1825.9  5324.5 1830.49
  5374.3 1834.02  5396.4 1839.87  5459.5 1848.72  5538.3 1851.12  5581.9 1854.77
  5641.5  1855.1  5702.3 1858.16  5766.7 1858.26  5882.3 1861.38  5905.6 1862.37
#Mann= 5 ,-1 , 0
  4191.9      .1       0  5002.5     .07       0  5008.5      .1       0
  5641.5     .16       0  5882.3      .1       0
Bank Sta=4949,5083.4
XS Rating Curve= 0 ,0
Exp/Cntr=0.3,0.1

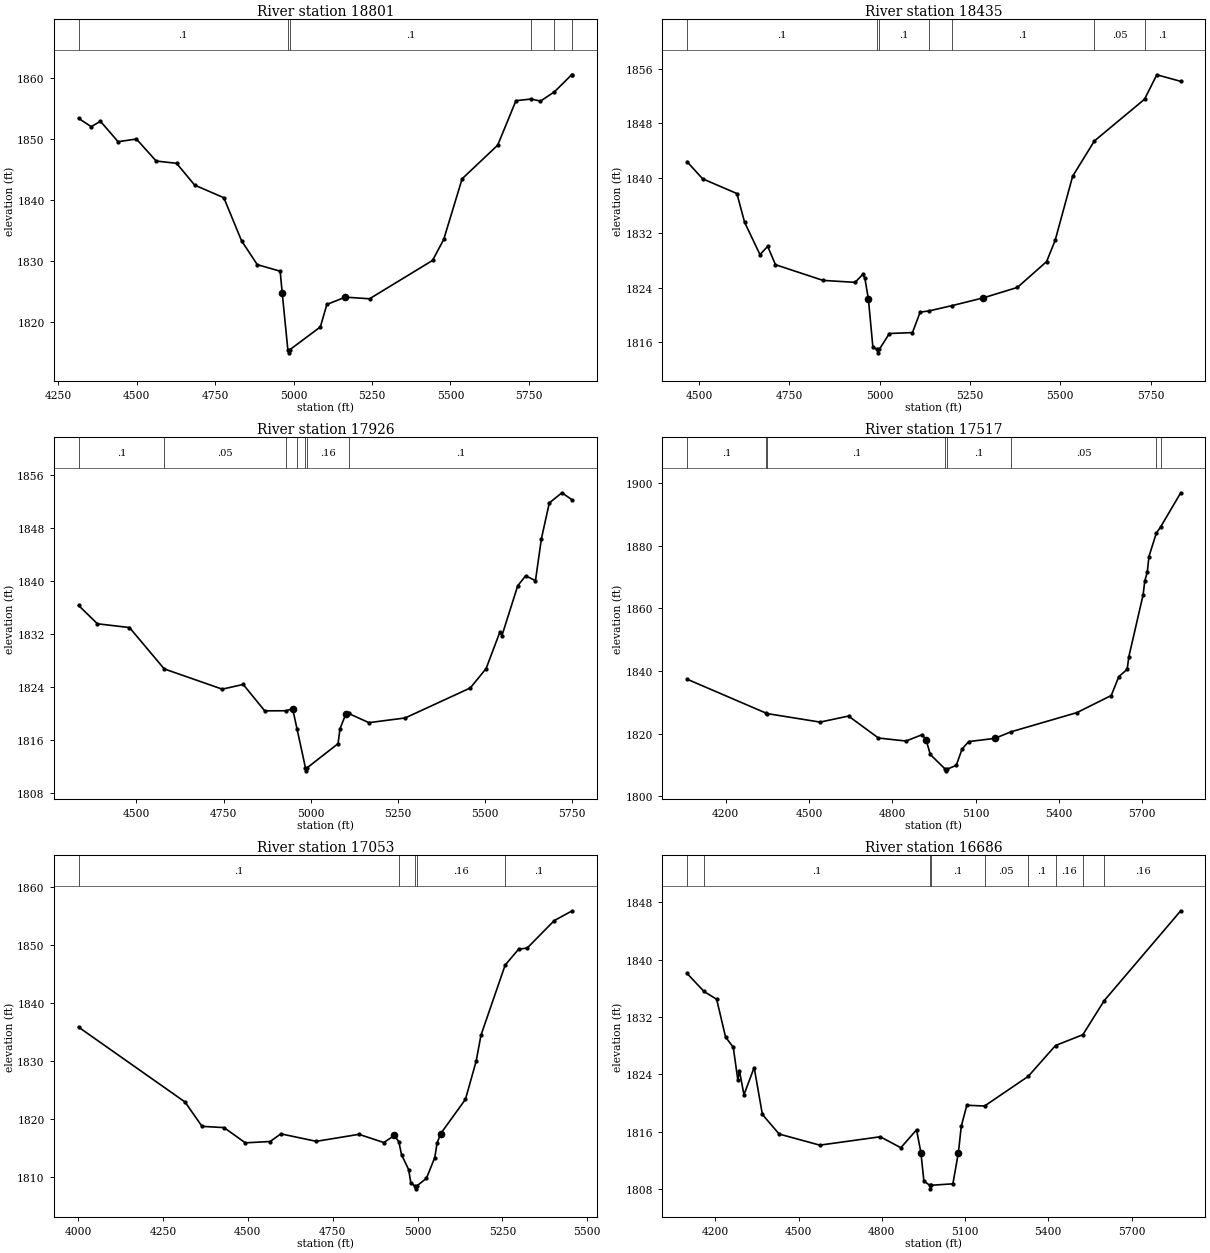
Type RM Length L Ch R = 1 ,18801   ,366,366,366
BEGIN DESCRIPTION:
LEFT BEAR CREEK 37.0
END DESCRIPTION:
XS GIS Cut Line= 2
      2746179.51     10018335.89      2747450.38       10019263.
#Sta/Elev= 30
  4314.9 1853.38  4355.3    1852  4384.6 1852.89    4441 1849.54  4499.3 1849.98
  4562.3 1846.37  4627.2    1846    4685 1842.42  4777.8 1840.36  4834.2 1833.31
  4884.4 1829.39  4957.3 1828.31    4964 1824.67  4981.8 1815.43  4984.6 1814.93
  4987.8 1815.43  5085.3 1819.17  5106.1 1822.86  5164.8 1824.06  5242.1 1823.79
  5442.9 1830.08  5478.4 1833.51  5537.1 1843.46  5650.4 1848.97  5708.6 1856.26
  5757.3 1856.54  5786.6 1856.19  5831.1 1857.71    5886 1860.51    5888 1860.51
#Mann= 6 ,-1 , 0
  4314.9      .1       0  4981.8     .07       0  4987.8      .1       0
  5757.3     .16       0  5831.1      .1       0    5886     .16       0
Bank Sta=4964,5164.8
XS Rating Curve= 0 ,0
Exp/Cntr=0.3,0.1

Type RM Length L Ch R = 1 ,18435   ,509,509,509
BEGIN DESCRIPTION:
LEFT BEAR CREEK 36.0
END DESCRIPTION:
XS GIS Cut Line= 2
      2746059.71     10018754.29      2747224.95     10019466.96
#Sta/Elev= 30
  4467.1 1842.41  4510.3  1839.9  4605.1 1837.75  4626.4 1833.55    4669 1828.83
  4690.3 1830.04  4711.8 1827.36  4843.2 1825.07  4932.1 1824.78  4953.4 1825.94
  4959.3 1825.35  4968.9 1822.34  4981.4  1815.3    4993 1814.99  4995.8 1814.49
    4999 1814.99  5026.9 1817.31  5090.8 1817.45  5112.1 1820.43  5136.4 1820.61
    5200 1821.38  5286.3 1822.51  5381.1 1824.04    5462 1827.82  5485.5  1830.9
    5534 1840.28  5594.2 1845.43  5732.9 1851.52  5766.8 1855.09    5833 1854.13
#Mann= 7 ,-1 , 0
  4467.1      .1       0    4993     .07       0    4999      .1       0
  5136.4     .05       0    5200      .1       0  5594.2     .05       0
  5732.9      .1       0
Bank Sta=4968.9,5286.3
XS Rating Curve= 0 ,0
Exp/Cntr=0.3,0.1

Type RM Length L Ch R = 1 ,17926   ,409,409,409
BEGIN DESCRIPTION:
LEFT BEAR CREEK 35.0
END DESCRIPTION:
XS GIS Cut Line= 3
      2745830.59     10019056.41      2746059.74      10019374.1
      2746985.13       10019816.
#Sta/Elev= 30
  4333.8 1836.34    4388 1833.56    4480 1832.99  4579.8 1826.73  4746.3 1823.67
  4806.5 1824.38  4868.2 1820.39  4930.4  1820.4  4948.2 1820.73  4960.8  1817.7
    4985 1811.81  4987.8 1811.31    4991 1811.81  5078.7 1815.42  5084.3 1817.68
  5100.9 1819.88  5108.9 1819.99  5167.4  1818.6  5271.3 1819.31  5458.3 1823.85
  5503.7 1826.78  5543.5 1832.34  5549.1 1831.76  5594.4  1839.3  5617.1 1840.82
  5645.4 1840.09  5662.5 1846.45  5685.2 1851.85  5721.4 1853.38    5751  1852.3
#Mann= 7 ,-1 , 0
  4333.8      .1       0  4579.8     .05       0  4930.4      .1       0
  4960.8     .16       0    4985     .07       0    4991     .16       0
  5108.9      .1       0
Bank Sta=4948.2,5100.9
XS Rating Curve= 0 ,0
Exp/Cntr=0.3,0.1

Type RM Length L Ch R = 1 ,17517   ,464,464,464
BEGIN DESCRIPTION:
LEFT BEAR CREEK 34.0
END DESCRIPTION:
XS GIS Cut Line= 3
      2745715.97     10019092.81       2745976.4     10019743.89
      2746877.48     10020332.46
#Sta/Elev= 30
  4061.1 1837.37  4344.3 1826.58  4350.1 1826.37  4540.2 1823.66  4642.5 1825.59
  4750.2 1818.58  4849.4 1817.61  4908.1 1819.66  4921.8 1818.03  4936.9 1813.33
  4991.2  1808.6  4993.9  1808.1  4997.2  1808.6  5030.4 1809.86  5051.5 1815.09
  5075.3 1817.44  5169.2 1818.46  5226.4 1820.53  5464.8 1826.69  5588.5 1832.15
  5615.6 1838.17  5645.8 1840.52  5651.8 1844.53  5703.1 1864.27  5709.1 1868.67
  5718.2 1871.58  5724.2 1876.52  5750.6 1883.96  5766.5 1886.01  5838.6 1896.87
#Mann= 8 ,-1 , 0
  4061.1      .1       0  4344.3     .05       0  4350.1      .1       0
  4991.2     .07       0  4997.2      .1       0  5226.4     .05       0
  5750.6      .1       0  5766.5     .16       0
Bank Sta=4921.8,5169.2
XS Rating Curve= 0 ,0
Exp/Cntr=0.3,0.1

Type RM Length L Ch R = 1 ,17053   ,367,367,367
BEGIN DESCRIPTION:
LEFT BEAR CREEK 33.0
END DESCRIPTION:
XS GIS Cut Line= 2
      2745585.77     10019243.86      2746012.87     10020634.55
#Sta/Elev= 30
  4001.2 1835.85  4314.9 1822.91    4365  1818.7    4430 1818.48  4492.7 1815.85
    4566 1816.08  4597.3  1817.4    4702 1816.11  4827.5 1817.32  4900.7  1815.9
  4932.1 1817.13  4945.1 1816.01    4953 1813.79  4973.9 1811.23  4980.2 1808.96
  4991.9  1808.4  4994.6  1807.9  4997.9  1808.4  5026.2 1809.71  5050.8 1813.29
  5057.6 1815.77  5068.1 1817.42  5141.3 1823.37  5172.7 1829.93    5187 1834.44
  5258.3 1846.57  5298.2 1849.33  5323.1  1849.5  5402.8 1854.25    5456 1855.95
#Mann= 5 ,-1 , 0
  4001.2      .1       0  4945.1     .16       0  4991.9     .07       0
  4997.9     .16       0  5258.3      .1       0
Bank Sta=4932.1,5068.1
XS Rating Curve= 0 ,0
Exp/Cntr=0.3,0.1

Type RM Length L Ch R = 1 ,16686   ,543,543,543
BEGIN DESCRIPTION:
LEFT BEAR CREEK 32.0
END DESCRIPTION:
XS GIS Cut Line= 4
      2745257.66     10019368.91      2745549.32     10019931.39
      2745455.57     10020728.27       2745679.5     10020988.65
#Sta/Elev= 30
    4098 1838.09  4159.1 1835.57  4204.8 1834.48    4237 1829.19  4264.7 1827.78
  4281.2 1823.21  4286.8 1824.51  4303.3 1821.15    4340 1824.95  4369.7 1818.39
  4430.1 1815.66  4576.5 1814.11  4794.4 1815.28  4868.6 1813.75  4925.3 1816.25
 4940.91 1813.08  4951.7  1809.1  4972.6 1808.51  4975.4 1808.01  4978.6 1808.51
  5056.2 1808.71 5076.14 1813.08  5086.4 1816.75  5106.5 1819.68  5170.3 1819.57
  5327.6 1823.71  5426.2 1828.02  5524.7 1829.53  5601.7 1834.29  5877.4 1846.83
#Mann= 9 ,-1 , 0
    4098     .05       0  4159.1      .1       0  4972.6     .07       0
  4978.6      .1       0  5170.3     .05       0  5327.6      .1       0
  5426.2     .16       0  5524.7      .1       0  5601.7     .16       0
Bank Sta=4940.91,5076.14
XS Rating Curve= 0 ,0
Exp/Cntr=0.3,0.1

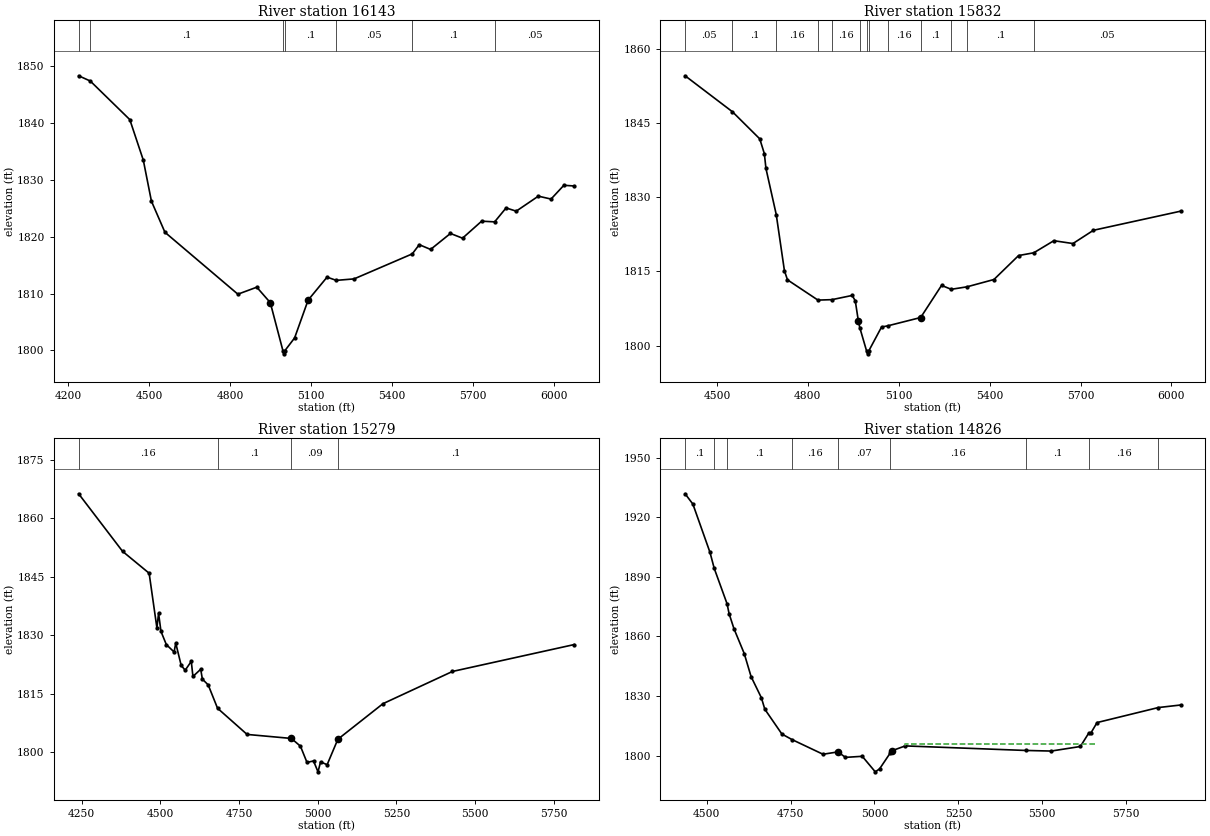
Type RM Length L Ch R = 1 ,16143   ,311,311,311
BEGIN DESCRIPTION:
LEFT BEAR CREEK 31.0
END DESCRIPTION:
XS GIS Cut Line= 3
      2745023.28     10019254.35      2745007.65     10020488.68
      2745189.47     10021060.12
#Sta/Elev= 30
  4239.4 1848.31  4282.4 1847.39  4428.8  1840.6  4478.8 1833.47  4508.8 1826.26
  4558.8 1820.79  4828.8  1809.9  4898.8 1811.13  4948.8 1808.41  4995.8 1799.91
  4998.6 1799.41  5001.8 1799.91  5038.8 1802.21  5088.8 1808.86  5158.9  1812.9
    5193 1812.33  5258.9 1812.59  5474.3 1816.99  5500.1 1818.61  5542.1 1817.77
  5615.5 1820.58  5660.3 1819.75    5731 1822.74  5779.1 1822.62  5821.5 1825.07
    5859  1824.5  5940.9 1827.14  5987.9 1826.63  6035.3 1829.05  6073.5 1828.93
#Mann= 7 ,-1 , 0
  4239.4     .05       0  4282.4      .1       0  4995.8     .07       0
  5001.8      .1       0    5193     .05       0  5474.3      .1       0
  5779.1     .05       0
Bank Sta=4948.8,5088.8
XS Rating Curve= 0 ,0
Exp/Cntr=0.3,0.1

Type RM Length L Ch R = 1 ,15832   ,553,553,553
BEGIN DESCRIPTION:
LEFT BEAR CREEK 30.0
END DESCRIPTION:
XS GIS Cut Line= 3
      2744596.19     10019431.38      2744809.74     10020592.85
      2745002.45     10021004.32
#Sta/Elev= 30
    4395 1854.52  4551.4 1847.24  4641.4 1841.77  4656.6 1838.77  4661.8 1835.79
  4695.8 1826.48  4722.8 1815.12  4732.9 1813.28  4833.4 1809.19  4879.7 1809.28
  4946.4 1810.13  4956.6 1809.04  4966.8 1804.96  4971.6  1803.6  4994.3 1798.83
    4997 1798.33  5000.3 1798.83  5043.3 1803.75  5063.2 1803.98  5172.4 1805.67
  5241.3 1812.16  5273.2 1811.37  5325.1 1811.87  5414.2 1813.35  5495.5 1818.19
  5545.6 1818.75  5611.9 1821.19  5674.9 1820.62  5742.6  1823.3  6030.3 1827.16
#Mann= 13 ,-1 , 0
    4395     .05       0  4551.4      .1       0  4695.8     .16       0
  4833.4      .1       0  4879.7     .16       0  4971.6      .1       0
  4994.3     .07       0  5000.3      .1       0  5063.2     .16       0
  5172.4      .1       0  5273.2     .05       0  5325.1      .1       0
  5545.6     .05       0
Bank Sta=4966.8,5172.4
XS Rating Curve= 0 ,0
Exp/Cntr=0.3,0.1

Type RM Length L Ch R = 1 ,15279   ,453,453,453
BEGIN DESCRIPTION:
LEFT BEAR CREEK 29.0
END DESCRIPTION:
XS GIS Cut Line= 4
      2744012.86     10019759.53      2744205.57     10020259.52
      2744742.03     10020691.81      2744877.46     10021014.76
#Sta/Elev= 30
  4240.3 1866.27  4379.9  1851.5  4464.4 1845.88  4489.1 1831.84  4494.4 1835.61
    4502 1830.95  4519.1 1827.56  4543.7 1825.67    4549 1827.94  4566.3 1822.21
    4579 1820.99  4598.3 1823.26  4603.6 1819.39  4628.3 1821.23  4633.6  1818.7
  4652.1 1817.22  4681.8 1811.23  4775.7 1804.51  4916.5 1803.48  4945.3 1801.49
  4966.1 1797.33  4986.9  1797.7  5001.1 1794.91  5009.3 1797.46  5030.1 1796.74
  5063.5 1803.13  5065.3 1803.34  5207.6  1812.4  5428.4 1820.67  5815.3 1827.57
#Mann= 4 ,-1 , 0
  4240.3     .16       0  4681.8      .1       0  4916.5     .09       0
  5063.5      .1       0
Bank Sta=4916.5,5065.3
XS Rating Curve= 0 ,0
Exp/Cntr=0.3,0.1

Type RM Length L Ch R = 1 ,14826   ,287,287,287
BEGIN DESCRIPTION:
LEFT BEAR CREEK 28.0
END DESCRIPTION:
XS GIS Cut Line= 4
      2743585.75     10020332.43      2743919.11     10020400.14
      2744127.44      10020811.6      2744762.82     10021040.75
#Sta/Elev= 30
  4435.6 1931.75  4458.8 1926.56  4509.8 1902.25  4522.4 1894.21  4560.6 1876.42
  4566.8 1871.36  4581.2 1863.85  4611.8 1851.35  4632.3 1839.71  4662.9  1829.1
  4673.2 1823.31  4724.1 1810.82  4754.7    1808  4846.6 1800.65  4891.2 1801.84
  4913.5 1799.08  4963.6 1799.62  5002.3  1791.8  5015.2 1793.29  5047.1 1801.31
  5052.7 1802.47  5091.7 1804.85  5450.7 1802.56  5526.8 1802.26  5613.6 1804.56
  5639.2 1811.47  5644.2 1811.14  5663.3  1816.6  5845.7 1824.15  5912.4 1825.44
#Mann= 9 ,-1 , 0
  4435.6      .1       0  4522.4     .16       0  4560.6      .1       0
  4754.7     .16       0  4891.2     .07       0  5047.1     .16       0
  5450.7      .1       0  5639.2     .16       0  5845.7     .05       0
#XS Ineff= 1 ,-1
    5090 5657.27 1805.63
Permanent Ineff=
       F
Bank Sta=4891.2,5052.7
XS Rating Curve= 0 ,0
Exp/Cntr=0.3,0.1