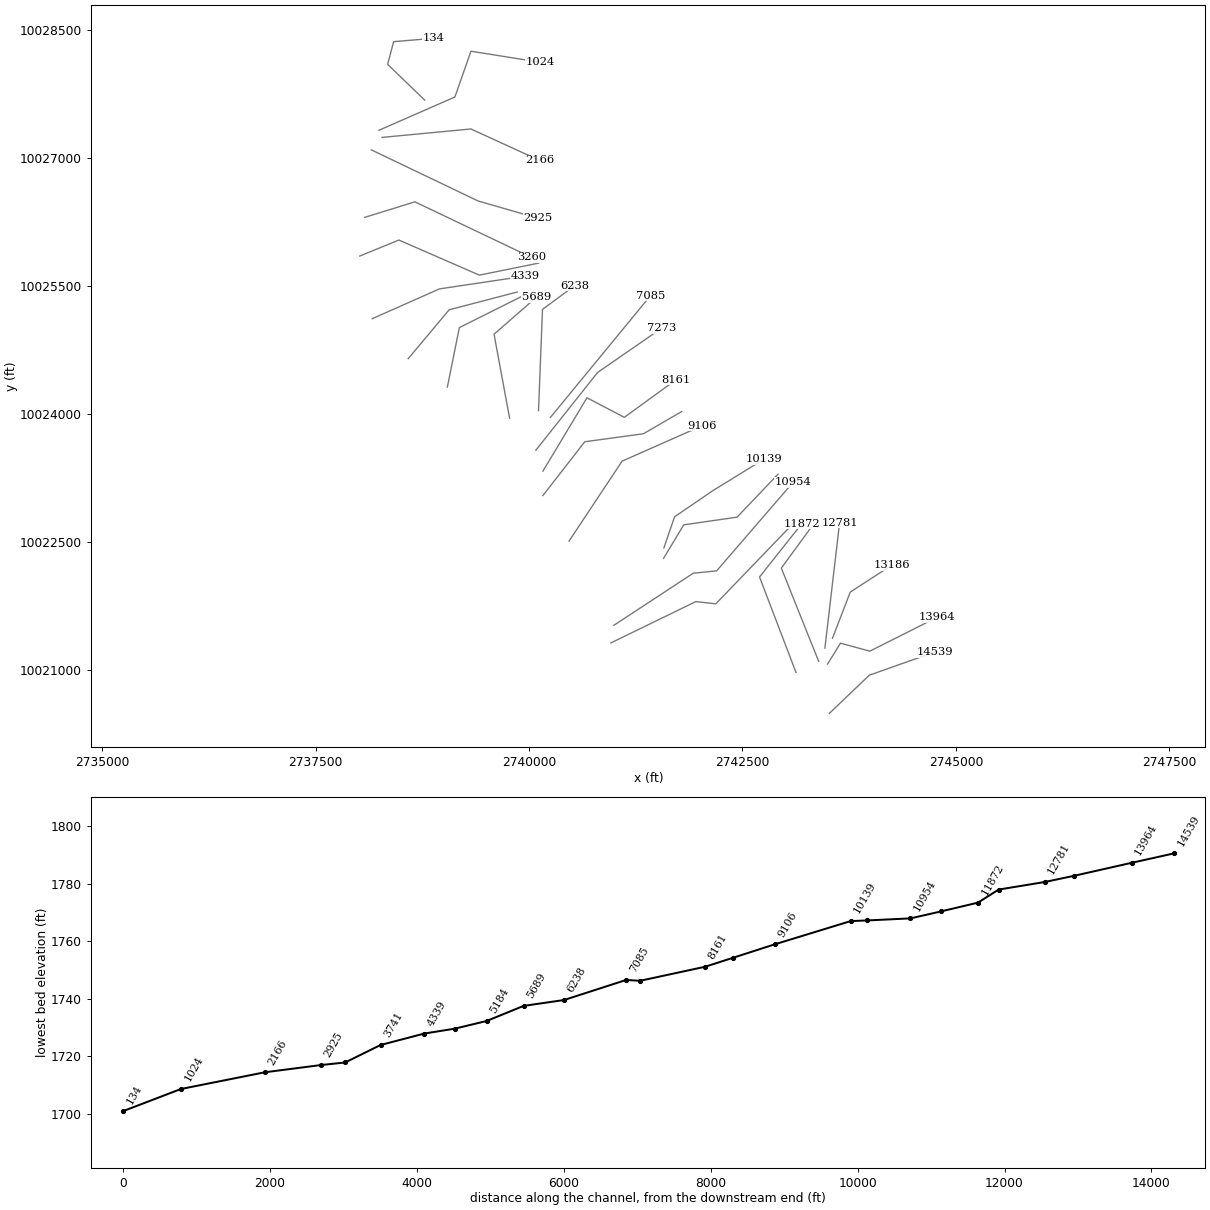
HEC-RAS study LEFT BEAR CREEK.prj: LEFT BEAR CREEK Base Level Engineering

--- LEFT BEAR CREEK.g01 (geometry) --- (continued)

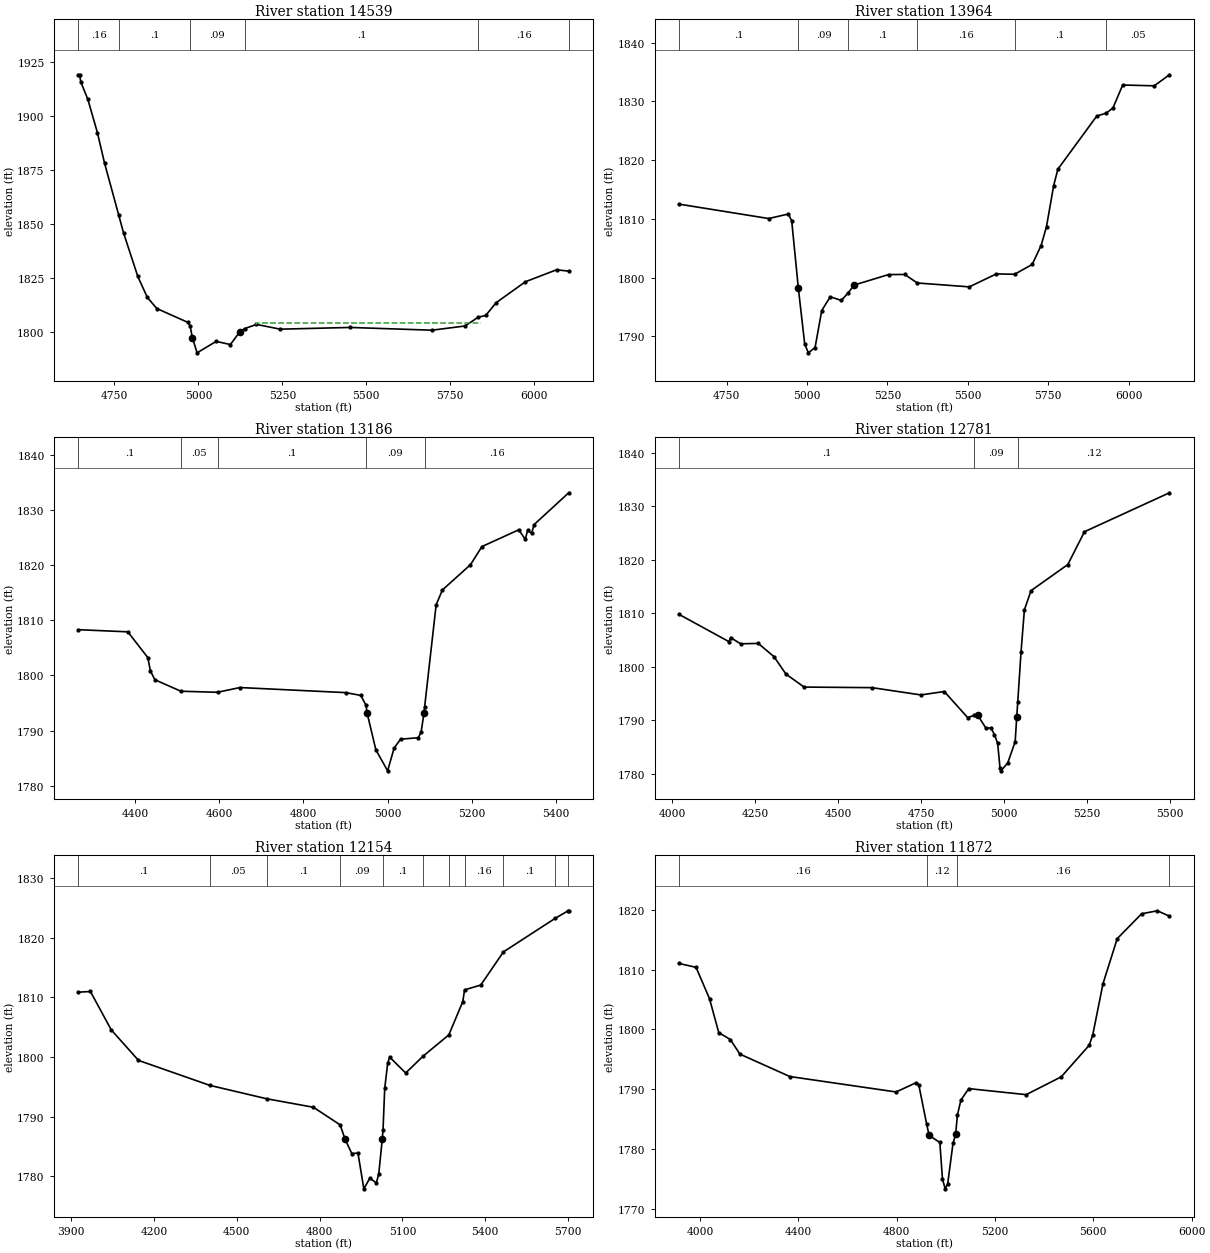
Type RM Length L Ch R = 1 ,14539   ,575,575,575
BEGIN DESCRIPTION:
LEFT BEAR CREEK 27.0
END DESCRIPTION:
XS GIS Cut Line= 3
       2743518.1     10020493.93      2743986.82     10020941.81
      2744752.43     10021212.64
#Sta/Elev= 30
  4642.5 1919.02    4646 1919.02  4649.7 1915.75  4670.8 1907.63  4699.1 1892.32
  4720.5 1878.16  4762.9 1854.02  4777.1 1845.89  4819.5 1825.78  4847.8 1816.12
  4876.1 1810.96    4968 1804.59    4975 1803.02  4982.1 1797.56    4996 1790.47
  5052.9 1795.76  5095.3 1794.31  5123.7  1800.3  5137.8 1801.68    5173 1803.61
  5243.8 1801.41  5451.7 1802.21  5695.6 1800.94  5793.9 1802.88  5833.3 1806.93
  5855.7 1807.76  5886.6 1813.63    5974 1823.34  6066.9 1828.88  6102.9 1828.22
#Mann= 6 ,-1 , 0
  4642.5     .16       0  4762.9      .1       0    4975     .09       0
  5137.8      .1       0  5833.3     .16       0  6102.9     .05       0
#XS Ineff= 1 ,-1
 5171.82 5840.91 1804.36
Permanent Ineff=
       F
Bank Sta=4982.1,5123.7
XS Rating Curve= 0 ,0
Exp/Cntr=0.3,0.1

Type RM Length L Ch R = 1 ,13964   ,778,778,778
BEGIN DESCRIPTION:
LEFT BEAR CREEK 26.0
END DESCRIPTION:
XS GIS Cut Line= 4
      2743497.25     10021072.04      2743648.28     10021316.81
      2743992.03     10021223.06      2744778.33     10021618.81
#Sta/Elev= 30
  4602.4 1812.51  4880.7 1810.06    4942 1810.83  4952.4 1809.65  4973.1 1798.16
  4992.7 1788.73    5004  1787.2    5025  1788.1  5045.7 1794.39  5072.2 1796.74
  5106.7 1796.12  5128.6 1797.46  5146.5 1798.74  5253.4 1800.52  5303.7 1800.54
  5342.7 1799.09  5504.5 1798.43  5588.2 1800.63  5645.4 1800.58  5699.8 1802.24
  5727.7 1805.47  5744.4  1808.7  5766.7 1815.68  5779.7 1818.46  5900.6  1827.5
    5929 1827.98  5950.8 1828.86  5981.2 1832.79  6079.2 1832.65  6126.6 1834.53
#Mann= 6 ,-1 , 0
  4602.4      .1       0  4973.1     .09       0  5128.6      .1       0
  5342.7     .16       0  5645.4      .1       0    5929     .05       0
Bank Sta=4973.1,5146.5
XS Rating Curve= 0 ,0
Exp/Cntr=0.3,0.1

Type RM Length L Ch R = 1 ,13186   ,405,405,405
BEGIN DESCRIPTION:
LEFT BEAR CREEK 25.0
END DESCRIPTION:
XS GIS Cut Line= 3
      2743554.53     10021374.11      2743762.86     10021915.77
      2744252.47     10022233.49
#Sta/Elev= 30
  4265.6 1808.29    4383  1807.9  4430.5 1803.23  4436.6 1800.81  4447.3 1799.22
    4509 1797.14    4596 1796.95  4649.1 1797.81  4900.3 1796.89  4936.1 1796.38
  4948.6 1794.57 4950.91 1793.22  4971.8 1786.53  4999.7 1782.72  5015.1 1786.84
  5030.3 1788.45  5072.5 1788.72  5079.1 1789.68 5086.14 1793.22  5087.6 1794.33
  5114.9  1812.8  5129.8 1815.49  5196.4 1820.06  5223.5 1823.34  5311.1 1826.39
  5326.3 1824.66  5332.2 1826.28  5341.4 1825.73  5347.4 1827.33  5429.6 1833.09
#Mann= 5 ,-1 , 0
  4265.6      .1       0    4509     .05       0    4596      .1       0
  4948.6     .09       0  5087.6     .16       0
Bank Sta=4950.91,5086.14
XS Rating Curve= 0 ,0
Exp/Cntr=0.3,0.1

Type RM Length L Ch R = 1 ,12781   ,627,627,627
BEGIN DESCRIPTION:
LEFT BEAR CREEK 24.0
END DESCRIPTION:
XS GIS Cut Line= 2
      2743465.98     10021259.49      2743637.86     10022728.27
#Sta/Elev= 30
    4020 1809.77  4170.3 1804.68  4175.4 1805.43  4205.5 1804.28  4258.7 1804.35
  4306.2 1801.87    4342 1798.63  4396.8 1796.19  4601.9 1796.08  4749.2 1794.72
  4819.7 1795.36  4890.1 1790.49  4910.3  1790.9  4920.3 1790.96  4945.1 1788.52
  4960.6 1788.55  4970.7 1787.31  4980.7 1785.68  4987.8 1781.03  4990.6 1780.53
    5011    1782  5033.5 1785.98 5038.18 1790.59  5041.2 1793.36  5051.2 1802.79
  5061.3 1810.64  5081.4 1814.22  5192.2 1819.09  5242.5 1825.23  5498.8 1832.51
#Mann= 3 ,-1 , 0
    4020      .1       0  4910.3     .09       0  5041.2     .12       0
Bank Sta=4920.3,5038.18
XS Rating Curve= 0 ,0
Exp/Cntr=0.3,0.1

Type RM Length L Ch R = 1 ,12154   ,282,282,282
BEGIN DESCRIPTION:
LEFT BEAR CREEK 23.0
END DESCRIPTION:
XS GIS Cut Line= 3
      2743393.07     10021103.27      2742955.57     10022197.02
      2743308.76     10022680.06
#Sta/Elev= 30
  3926.1 1810.86  3969.7 1810.98  4045.1 1804.55  4143.9 1799.43  4402.1 1795.25
  4608.7    1793  4777.5 1791.58  4874.4 1788.63  4892.5  1786.2  4916.7 1783.82
    4939 1783.91  4960.3 1777.91  4982.1 1779.71  5005.5  1778.9  5014.4 1780.42
 5026.99 1786.22  5029.8  1787.8  5035.9 1794.74  5046.7 1798.97    5054 1799.97
  5111.9 1797.32  5174.5 1800.12  5268.2 1803.71  5318.8 1809.28  5325.2 1811.25
  5383.7 1812.05    5466 1817.61  5653.7 1823.24  5698.2 1824.44  5702.5  1824.5
#Mann= 11 ,-1 , 0
  3926.1      .1       0  4402.1     .05       0  4608.7      .1       0
  4874.4     .09       0  5029.8      .1       0  5174.5     .16       0
  5268.2      .1       0  5325.2     .16       0    5466      .1       0
  5653.7     .05       0  5698.2      .1       0
Bank Sta=4892.5,5026.99
XS Rating Curve= 0 ,0
Exp/Cntr=0.3,0.1

Type RM Length L Ch R = 1 ,11872   ,507,507,507
BEGIN DESCRIPTION:
LEFT BEAR CREEK 22.0
END DESCRIPTION:
XS GIS Cut Line= 3
      2743127.44     10020973.08      2742700.36     10022092.85
      2743194.28     10022716.75
#Sta/Elev= 30
  3915.5 1811.02  3984.3 1810.38  4039.1 1805.14  4076.7 1799.47    4124 1798.31
  4162.4 1795.88  4365.7 1792.13  4797.9 1789.55  4877.4 1791.06  4890.1 1790.76
  4922.2 1784.19  4932.2 1782.29  4975.8 1781.11  4986.5 1775.02  4997.5 1773.36
  5007.9 1774.23  5029.3 1780.95    5040 1782.45  5047.2 1785.67  5061.4 1788.18
  5093.5 1790.11    5327  1789.1  5469.6 1792.08  5583.4 1797.36  5597.8  1799.1
  5639.4 1807.65  5697.2 1815.17  5796.5 1819.33  5860.6 1819.83  5909.7 1818.92
#Mann= 4 ,-1 , 0
  3915.5     .16       0  4922.2     .12       0  5047.2     .16       0
  5909.7      .1       0
Bank Sta=4932.2,5040
XS Rating Curve= 0 ,0
Exp/Cntr=0.3,0.1

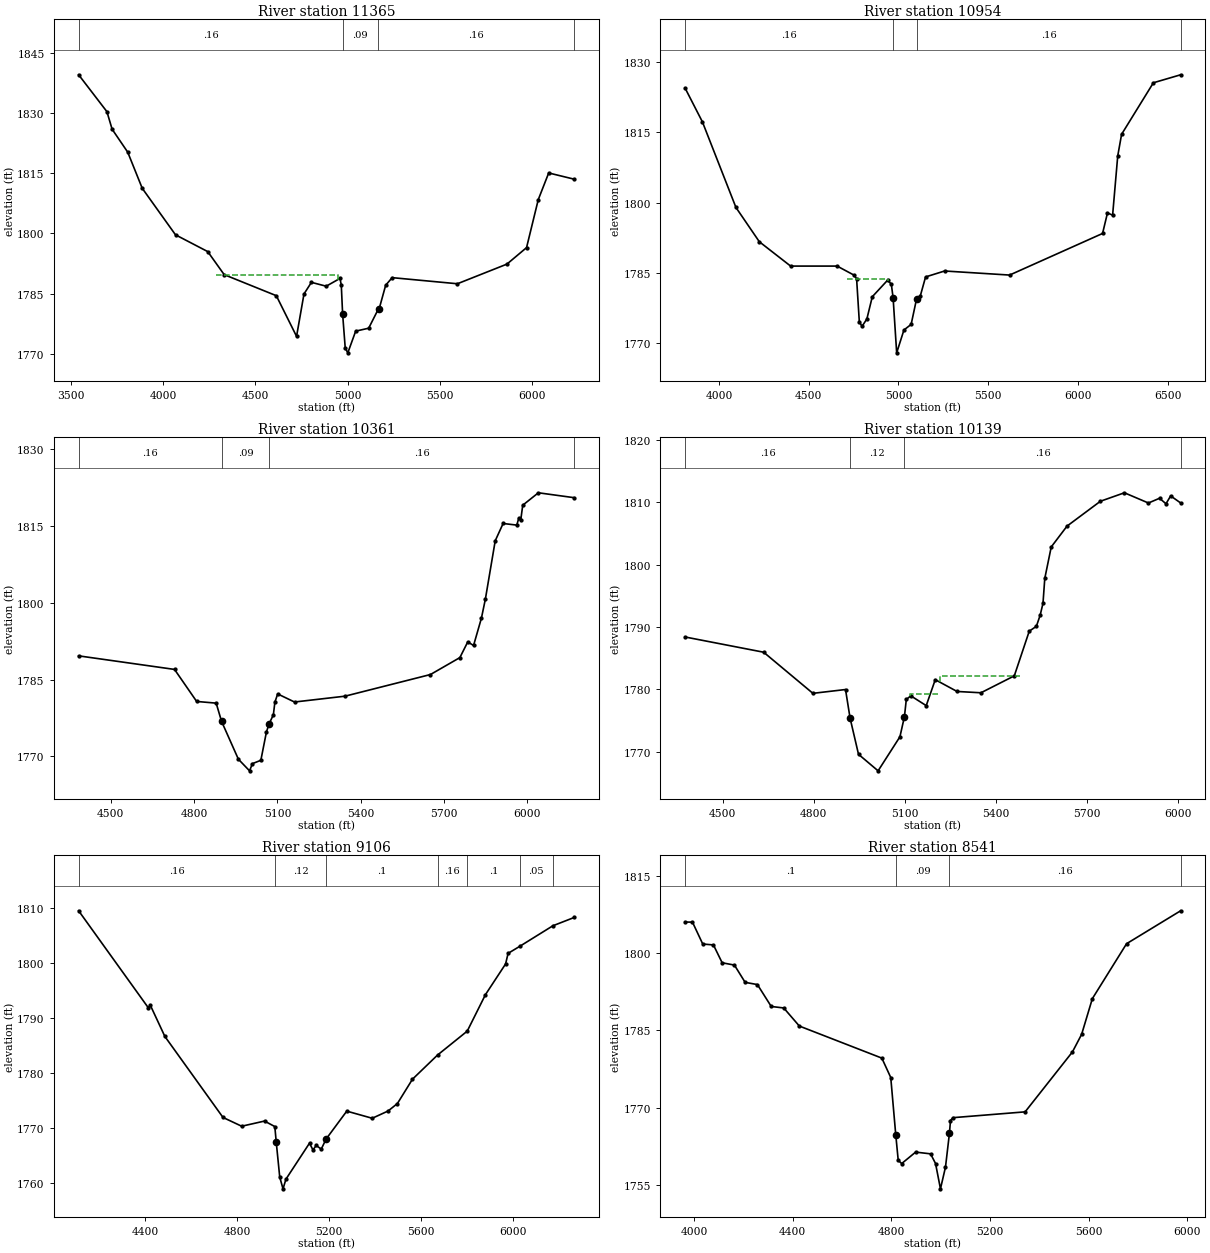
Type RM Length L Ch R = 1 ,11365   ,411,411,411
BEGIN DESCRIPTION:
LEFT BEAR CREEK 21.0
END DESCRIPTION:
XS GIS Cut Line= 4
      2740959.02      10021319.9      2741953.79     10021804.27
      2742188.17     10021778.22      2743120.44     10022746.95
#Sta/Elev= 30
  3541.9 1839.48  3695.3  1830.3  3723.4 1825.94    3808 1820.23  3886.8 1811.23
  4067.1 1799.66  4241.9 1795.48    4331 1789.75  4613.7 1784.51  4723.5 1774.39
  4763.7 1784.94    4804 1787.83  4884.1 1786.87  4959.1 1788.81    4966 1787.11
  4973.2 1779.94  4987.4 1771.45  5001.3 1770.29    5044 1775.69  5114.4 1776.42
  5164.1 1780.93    5171 1781.19  5206.6 1787.11  5241.8    1789  5595.5 1787.48
  5864.1 1792.37  5970.4 1796.47  6033.9 1808.41  6090.5 1815.05  6228.6  1813.5
#Mann= 4 ,-1 , 0
  3541.9     .16       0  4973.2     .09       0  5164.1     .16       0
  6228.6      .1       0
#XS Ineff= 1 ,-1
  4285.8 4947.16 1789.54
Permanent Ineff=
       F
Bank Sta=4973.2,5171
XS Rating Curve= 0 ,0
Exp/Cntr=0.3,0.1

Type RM Length L Ch R = 1 ,10954   ,593,593,593
BEGIN DESCRIPTION:
LEFT BEAR CREEK 20.0
END DESCRIPTION:
XS GIS Cut Line= 4
      2740992.82     10021525.74      2741923.41     10022136.88
      2742197.71     10022164.65      2743093.49     10023202.78
#Sta/Elev= 30
  3811.4 1824.47  3907.9 1817.25  4094.7 1798.96  4224.9 1791.64  4399.1 1786.44
  4658.2 1786.44  4751.6 1784.52  4766.7 1783.74  4781.8 1774.55  4796.9 1773.55
  4823.9 1775.14  4854.1 1779.89    4939 1783.41    4960  1782.6    4970 1779.68
  4989.9  1767.9  5030.3 1772.78  5070.5 1773.98  5100.7 1779.42  5120.8 1779.96
  5150.9 1784.12  5256.9 1785.39  5618.9 1784.52  6136.7 1793.41  6164.1  1797.8
  6192.7 1797.32  6221.2 1809.98  6242.7  1814.6  6419.7 1825.61  6571.6 1827.32
#Mann= 4 ,-1 , 0
  3811.4     .16       0    4970     .09       0  5100.7     .16       0
  6571.6     .16       0
#XS Ineff= 1 ,-1
 4711.08 4941.76 1783.74
Permanent Ineff=
       F
Bank Sta=4970,5100.7
XS Rating Curve= 0 ,0
Exp/Cntr=0.3,0.1

Type RM Length L Ch R = 1 ,10361   ,222,222,222
BEGIN DESCRIPTION:
LEFT BEAR CREEK 19.0
END DESCRIPTION:
XS GIS Cut Line= 4
      2741576.16     10022311.61       2741812.3     10022704.01
       2742437.3     10022794.28      2742916.46     10023297.76
#Sta/Elev= 30
  4384.1 1789.65  4729.4    1787  4809.1 1780.74  4879.4 1780.41  4898.8 1776.85
  4959.4 1769.45  4999.6 1767.18    5010 1768.59  5040.3 1769.24  5060.5 1774.81
  5070.6 1776.43  5085.4 1778.14  5090.8 1780.59  5100.9 1782.21  5161.5 1780.63
  5343.4 1781.77    5651    1786    5757 1789.31  5785.3 1792.37  5806.3 1791.68
  5834.6 1797.02  5848.8 1800.73  5884.3 1812.14  5912.7 1815.52    5962  1815.2
  5969.3  1816.6  5976.2 1816.19  5983.4 1819.09  6039.7 1821.52  6168.6 1820.56
#Mann= 4 ,-1 , 0
  4384.1     .16       0  4898.8     .09       0  5070.6     .16       0
  6168.6      .1       0
Bank Sta=4898.8,5070.6
XS Rating Curve= 0 ,0
Exp/Cntr=0.3,0.1

Type RM Length L Ch R = 1 ,10139   ,1033,1033,1033
BEGIN DESCRIPTION:
LEFT BEAR CREEK 18.0
END DESCRIPTION:
XS GIS Cut Line= 4
      2741579.66     10022433.19      2741704.66     10022797.76
      2742145.63     10023099.84      2742753.31     10023474.86
#Sta/Elev= 30
    4376  1788.4    4635 1785.96  4797.4 1779.37    4905 1779.98    4920  1775.4
  4947.8  1769.6  5012.4 1766.95  5084.4 1772.41  5099.3 1775.65  5105.4 1778.39
  5120.3 1778.97  5171.1  1777.4  5200.9 1781.56  5272.7 1779.67  5351.5 1779.46
  5461.5 1782.17  5510.8 1789.33  5534.3 1790.11  5546.6 1791.86  5556.1 1793.79
    5562 1797.78  5583.3 1802.83  5635.4 1806.17  5745.4 1810.15  5824.6 1811.51
  5903.8 1809.87  5940.4 1810.63  5961.7 1809.75  5977.1 1811.01    6010 1809.88
#Mann= 4 ,-1 , 0
    4376     .16       0    4920     .12       0  5099.3     .16       0
    6010      .1       0
#XS Ineff= 2 ,-1
 5118.18 5215.91 1779.22 5215.91 5481.82 1782.08
Permanent Ineff=
       F       F
Bank Sta=4920,5099.3
XS Rating Curve= 0 ,0
Exp/Cntr=0.3,0.1

Type RM Length L Ch R = 1 ,9106    ,565,565,565
BEGIN DESCRIPTION:
LEFT BEAR CREEK 16.0
END DESCRIPTION:
XS GIS Cut Line= 3
      2740468.56     10022513.05      2741090.07     10023450.53
      2742031.05      10023867.2
#Sta/Elev= 30
  4112.1 1809.55  4414.7 1791.89  4423.8 1792.33  4486.9 1786.65  4739.6 1771.89
  4820.8 1770.29    4920 1771.23  4964.8 1770.23  4971.2 1767.33  4986.2 1761.02
  5000.5 1758.88  5013.3 1760.65  5115.6  1767.2  5130.6 1765.97  5144.8 1766.78
  5166.7 1766.12  5187.7 1767.95  5277.6 1773.04  5388.2 1771.74    5457 1773.06
  5497.6 1774.42  5563.2 1778.86  5672.1 1783.26  5801.2 1787.62  5880.4 1794.27
  5967.9 1799.86  5978.8 1801.79  6029.8 1803.08  6173.6 1806.82    6266 1808.33
#Mann= 7 ,-1 , 0
  4112.1     .16       0  4964.8     .12       0  5187.7      .1       0
  5672.1     .16       0  5801.2      .1       0  6029.8     .05       0
  6173.6      .1       0
Bank Sta=4971.2,5187.7
XS Rating Curve= 0 ,0
Exp/Cntr=0.3,0.1

Type RM Length L Ch R = 1 ,8541    ,380,380,380
BEGIN DESCRIPTION:
LEFT BEAR CREEK 15.0
END DESCRIPTION:
XS GIS Cut Line= 4
      2740163.02     10023047.79      2740652.57     10023677.96
      2741340.07     10023771.71      2741788.02     10024032.15
#Sta/Elev= 30
  3963.1    1806    3993 1805.99  4034.7 1801.74  4078.1 1801.56  4113.4  1798.1
  4163.2 1797.65  4206.6  1794.3  4256.4 1793.87  4312.5 1789.62  4363.2 1789.33
  4426.5 1785.82  4761.1  1779.6  4797.3 1775.83  4817.5 1764.75  4827.6 1759.75
  4841.8 1759.14  4898.2 1761.36  4958.8 1761.02    4979 1759.14  4998.9 1754.23
  5019.3 1758.45 5035.51 1765.09  5039.5 1767.48  5049.6 1768.04  5342.3 1769.17
  5534.2  1780.8  5571.5 1784.21    5615 1791.14  5753.8  1801.8  5973.1 1808.19
#Mann= 4 ,-1 , 0
  3963.1      .1       0  4817.5     .09       0 5035.51     .16       0
  5973.1     .05       0
Bank Sta=4817.5,5035.51
XS Rating Curve= 0 ,0
Exp/Cntr=0.3,0.1

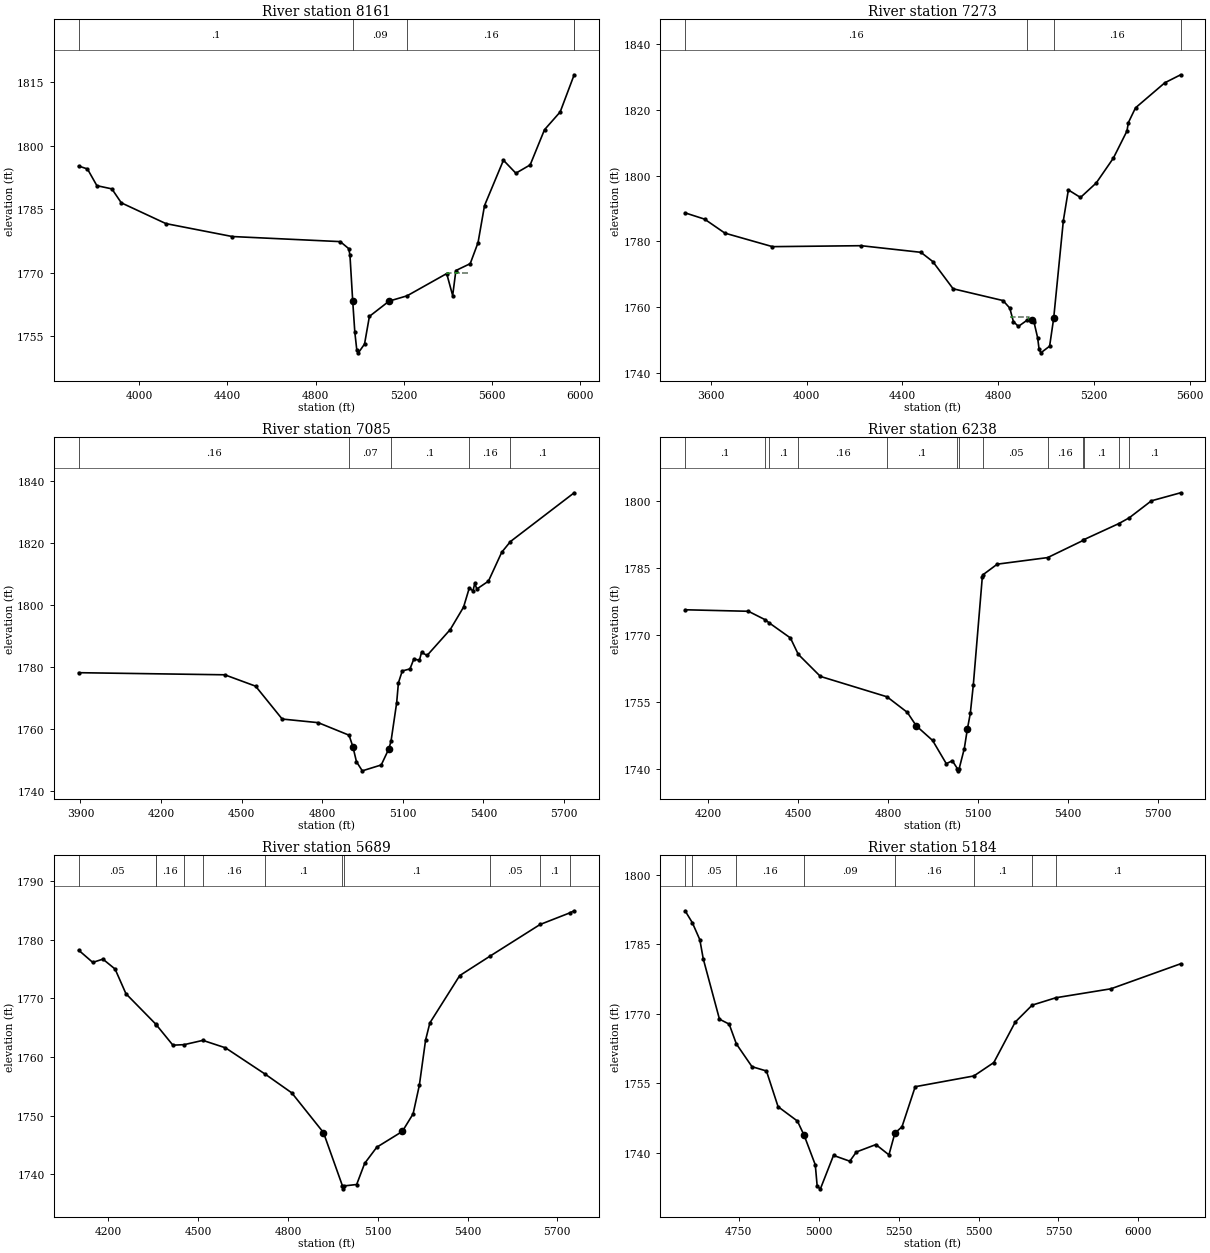
Type RM Length L Ch R = 1 ,8161    ,888,888,888
BEGIN DESCRIPTION:
LEFT BEAR CREEK 14.0
END DESCRIPTION:
XS GIS Cut Line= 4
      2740162.99     10023334.21      2740678.62     10024193.59
      2741116.12     10023964.42      2741724.45     10024406.37
#Sta/Elev= 30
  3725.4 1795.18  3765.4 1794.49  3808.2 1790.55  3876.2 1789.79    3919  1786.5
  4121.3  1781.6  4422.4 1778.55  4912.1 1777.35  4950.6  1775.7  4956.2 1774.17
 4968.75 1763.32  4978.3 1756.01  4987.1 1751.86  4994.4 1751.11  5022.4 1753.19
  5044.5 1759.71  5133.8 1763.31  5215.3 1764.56  5395.1 1769.81  5422.2 1764.62
  5436.8 1770.53  5501.8 1772.15  5537.3 1777.11  5566.7 1785.85  5652.5 1796.55
  5708.9 1793.49  5773.8 1795.45  5838.8 1803.75  5909.9 1807.94  5973.4 1816.71
#Mann= 5 ,-1 , 0
  3725.4      .1       0 4968.75     .09       0  5215.3     .16       0
  5973.4     .16       0  5973.4      .1       0
#XS Ineff= 1 ,-1
 5394.89 5490.06 1769.97
Permanent Ineff=
       F
Bank Sta=4968.75,5133.8
XS Rating Curve= 0 ,0
Exp/Cntr=0.3,0.1

Type RM Length L Ch R = 1 ,7273    ,188,188,188
BEGIN DESCRIPTION:
LEFT BEAR CREEK 13.0
END DESCRIPTION:
XS GIS Cut Line= 3
      2740079.63     10023578.97      2740803.62     10024490.46
      2741548.41     10025006.09
#Sta/Elev= 30
  3492.3 1788.68  3573.7 1786.78  3658.6 1782.53  3857.3 1778.43  4227.3 1778.72
  4477.3 1776.71  4526.9 1773.91  4611.8 1765.65  4820.3 1762.07  4848.6 1759.78
  4863.5 1755.71  4884.5 1754.23  4920.3 1756.09    4942  1756.3    4950 1755.44
  4964.9 1750.76  4970.9 1747.34  4978.2 1746.21  5014.9 1748.23 5031.82 1756.65
  5072.3 1786.33  5093.2 1795.64  5143.9 1793.35  5209.5 1797.74  5281.1 1805.28
  5337.9  1813.5  5343.9 1816.07  5373.7 1820.55    5496 1828.15  5562.2 1830.58
#Mann= 4 ,-1 , 0
  3492.3     .16       0  4920.3     .12       0 5031.82     .16       0
  5562.2      .1       0
#XS Ineff= 1 ,-1
 4847.73 4929.55 1757.15
Permanent Ineff=
       F
Bank Sta=4942,5031.82
XS Rating Curve= 0 ,0
Exp/Cntr=0.3,0.1

Type RM Length L Ch R = 1 ,7085    ,847,847,847
BEGIN DESCRIPTION:
LEFT BEAR CREEK 12.0
END DESCRIPTION:
XS GIS Cut Line= 2
       2740251.5     10023964.38      2741422.25     10025390.09
#Sta/Elev= 30
  3893.1 1778.21  4437.1 1777.53  4551.9 1773.86  4650.9 1763.24  4785.1 1762.07
  4899.9 1758.02  4914.2 1754.27  4927.4 1749.46  4949.1 1746.51  5019.7 1748.41
  5048.4 1753.71  5056.3  1756.2  5077.1 1768.51  5083.6 1774.94  5097.9 1778.76
  5126.6 1779.44    5141 1782.61  5161.8 1782.26  5169.7 1784.75  5190.5 1783.79
  5276.6 1792.15  5326.1 1799.39  5347.6 1805.61  5361.3 1804.59  5367.7 1807.06
  5375.6 1805.24  5418.7 1807.77  5468.2 1817.11  5500.8 1820.58  5737.9 1836.32
#Mann= 5 ,-1 , 0
  3893.1     .16       0  4899.9     .07       0  5056.3      .1       0
  5347.6     .16       0  5500.8      .1       0
Bank Sta=4914.2,5048.4
XS Rating Curve= 0 ,0
Exp/Cntr=0.3,0.1

Type RM Length L Ch R = 1 ,6238    ,549,549,549
BEGIN DESCRIPTION:
LEFT BEAR CREEK 11.0
END DESCRIPTION:
XS GIS Cut Line= 3
      2740110.91      10024042.5      2740157.78     10025230.05
      2740532.77     10025506.08
#Sta/Elev= 30
  4121.9 1775.59  4333.3 1775.25  4389.4 1773.35  4402.7 1772.65  4473.4 1769.28
  4499.6 1765.62  4573.5 1760.67  4795.8 1756.11  4863.7 1752.62  4893.7 1749.59
  4948.1 1746.33  4993.8 1741.13  5013.8 1741.79  5030.8 1740.03  5033.6 1739.53
  5036.8 1740.03  5053.9 1744.52  5063.9  1748.8  5073.9 1752.39  5083.9 1758.72
  5113.9 1782.85  5117.1 1783.47  5163.9  1785.8  5332.1 1787.27  5450.8 1791.12
  5453.4  1791.3  5569.5 1794.88  5604.1 1796.16  5678.4 1799.98    5776 1801.78
#Mann= 13 ,-1 , 0
  4121.9      .1       0  4389.4     .16       0  4402.7      .1       0
  4499.6     .16       0  4795.8      .1       0  5030.8     .07       0
  5036.8      .1       0  5117.1     .05       0  5332.1     .16       0
  5450.8     .05       0  5453.4      .1       0  5569.5     .05       0
  5604.1      .1       0
Bank Sta=4893.7,5063.9
XS Rating Curve= 0 ,0
Exp/Cntr=0.3,0.1

Type RM Length L Ch R = 1 ,5689    ,505,505,505
BEGIN DESCRIPTION:
LEFT BEAR CREEK 10.0
END DESCRIPTION:
XS GIS Cut Line= 3
      2739772.37     10023953.97      2739590.07     10024938.38
      2740083.07      10025369.1
#Sta/Elev= 30
  4100.5 1778.22  4147.7 1776.13  4181.6 1776.69  4222.3    1775  4258.6 1770.79
  4357.7 1765.63  4360.6 1765.45  4415.5 1762.01  4453.2  1762.1  4515.6 1762.83
  4591.1 1761.56  4724.4 1757.05  4812.8 1753.87  4918.6  1747.1  4982.1    1738
  4984.8  1737.5  4988.1    1738  5029.5 1738.24  5056.2 1741.84  5096.7  1744.6
    5182 1747.29  5218.1 1750.29    5239 1755.18  5259.8 1762.88  5274.1 1765.81
  5373.8 1773.88  5475.7 1777.22  5642.4  1782.6  5741.1 1784.57  5756.3 1784.94
#Mann= 11 ,-1 , 0
  4100.5     .05       0  4357.7      .1       0  4360.6     .16       0
  4453.2      .1       0  4515.6     .16       0  4724.4      .1       0
  4982.1     .07       0  4988.1      .1       0  5475.7     .05       0
  5642.4      .1       0  5741.1     .16       0
Bank Sta=4918.6,5182
XS Rating Curve= 0 ,0
Exp/Cntr=0.3,0.1

Type RM Length L Ch R = 1 ,5184    ,435,435,435
BEGIN DESCRIPTION:
LEFT BEAR CREEK 9.0
END DESCRIPTION:
XS GIS Cut Line= 3
      2739043.19     10024318.56      2739183.82     10025016.51
      2739933.65     10025391.42
#Sta/Elev= 30
    4582 1792.22  4604.7 1789.64  4628.1 1785.98  4638.7 1781.88  4689.5 1768.84
  4719.9 1767.77  4742.4  1763.5  4791.3 1758.59  4836.5 1757.66  4872.9 1749.96
  4933.4 1746.86  4954.5 1743.77  4989.3 1737.42  4995.3 1732.76  5005.3 1732.24
  5046.3 1739.45  5097.3  1738.2  5117.7 1740.19  5178.9 1741.79  5219.7 1739.57
  5238.3 1744.26  5260.5 1745.62  5301.9 1754.27  5485.4 1756.59  5547.8 1759.48
  5614.9 1768.22  5667.9 1771.87    5742 1773.46  5914.1 1775.39  6132.3 1780.79
#Mann= 8 ,-1 , 0
    4582      .1       0  4604.7     .05       0  4742.4     .16       0
  4954.5     .09       0  5238.3     .16       0  5485.4      .1       0
  5667.9     .16       0    5742      .1       0
Bank Sta=4954.5,5238.3
XS Rating Curve= 0 ,0
Exp/Cntr=0.3,0.1

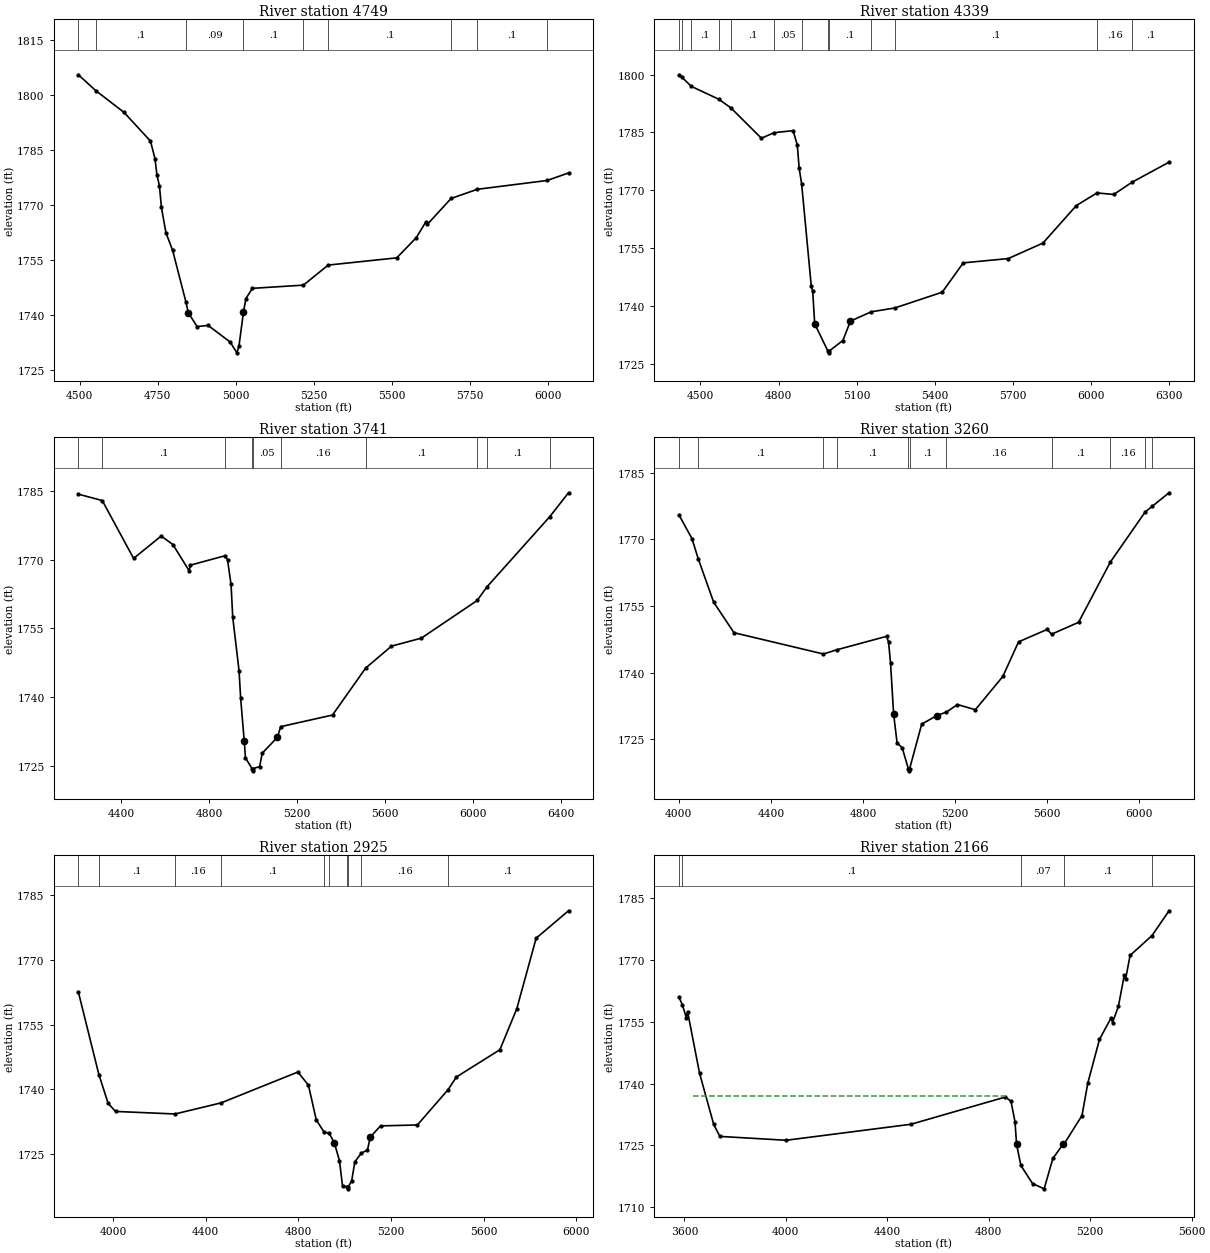
Type RM Length L Ch R = 1 ,4749    ,410,410,410
BEGIN DESCRIPTION:
LEFT BEAR CREEK 8.0
END DESCRIPTION:
XS GIS Cut Line= 3
      2738584.86     10024651.92      2739064.03     10025224.84
      2739860.86     10025433.16
#Sta/Elev= 30
  4495.7 1805.48  4551.6 1801.14  4641.5 1795.25  4726.8 1787.37  4741.1 1782.62
  4747.6 1778.06  4755.4 1775.21  4761.9 1769.25  4776.2 1762.38  4797.9 1757.51
    4840 1743.57  4847.8 1740.56  4876.1 1736.74  4911.5 1737.06  4981.8 1732.54
  5003.7 1729.57  5010.5 1731.54  5024.8 1740.75  5032.6  1744.4  5053.4 1747.18
  5216.7 1748.05  5296.2 1753.53  5515.9  1755.5  5578.7 1761.04  5608.8 1765.28
    5614 1764.65  5689.9 1771.71  5774.1 1774.22  5997.4 1776.62  6066.2 1778.67
#Mann= 9 ,-1 , 0
  4495.7     .05       0  4551.6      .1       0    4840     .09       0
  5024.8      .1       0  5216.7     .16       0  5296.2      .1       0
  5689.9     .16       0  5774.1      .1       0  5997.4     .16       0
Bank Sta=4847.8,5024.8
XS Rating Curve= 0 ,0
Exp/Cntr=0.3,0.1

Type RM Length L Ch R = 1 ,4339    ,598,598,598
BEGIN DESCRIPTION:
LEFT BEAR CREEK 7.0
END DESCRIPTION:
XS GIS Cut Line= 3
      2738163.02     10025120.69      2738949.45     10025469.63
      2739959.86     10025620.67
#Sta/Elev= 30
  4417.5 1799.94  4429.1 1799.31  4465.3 1796.93  4571.1 1793.59  4617.2 1791.36
  4734.2  1783.5  4782.9 1784.93    4856 1785.47    4872 1781.77  4879.3 1775.74
  4888.8 1771.67  4925.8 1745.19  4931.3 1743.81 4938.92 1735.42  4989.3  1728.4
  4992.1  1727.9  4995.3  1728.4    5047 1731.09  5076.4 1736.13    5156 1738.53
  5246.3 1739.52  5428.5 1743.61  5509.4 1751.21    5682 1752.32  5815.4 1756.34
  5943.7 1766.07  6022.9 1769.33  6087.1 1768.93  6156.9 1772.08  6299.5  1777.3
#Mann= 13 ,-1 , 0
  4417.5      .1       0  4429.1     .05       0  4465.3      .1       0
  4571.1     .05       0  4617.2      .1       0  4782.9     .05       0
  4888.8      .1       0  4989.3     .07       0  4995.3      .1       0
    5156     .16       0  5246.3      .1       0  6022.9     .16       0
  6156.9      .1       0
Bank Sta=4938.92,5076.4
XS Rating Curve= 0 ,0
Exp/Cntr=0.3,0.1

Type RM Length L Ch R = 1 ,3741    ,481,481,481
BEGIN DESCRIPTION:
LEFT BEAR CREEK 6.0
END DESCRIPTION:
XS GIS Cut Line= 4
      2738017.12     10025855.03      2738475.49     10026042.55
       2739418.2     10025631.09      2740110.94     10025771.72
#Sta/Elev= 30
    4205 1784.34  4313.8 1782.94  4456.4  1770.3  4581.9 1775.19  4635.3 1773.33
  4709.4 1767.59  4714.8 1768.83  4874.1 1770.91  4884.1  1769.9  4899.9 1764.63
  4907.6 1757.43  4936.4 1745.72  4943.5 1739.82  4959.8 1730.49  4965.4 1726.76
  4995.1  1724.4  4997.8  1723.9  5001.1  1724.4  5030.1 1724.83  5041.7 1727.76
  5111.2 1731.24  5125.6 1733.55  5361.7 1736.09  5512.5 1746.35  5630.1 1751.14
    5766 1752.89    6020 1761.11  6063.3 1764.02  6349.7 1779.38  6435.7 1784.64
#Mann= 10 ,-1 , 0
    4205     .05       0  4313.8      .1       0  4874.1     .05       0
  4995.1    .035       0  5001.1     .05       0  5125.6     .16       0
  5512.5      .1       0    6020     .16       0  6063.3      .1       0
  6349.7     .16       0
Bank Sta=4959.8,5111.2
XS Rating Curve= 0 ,0
Exp/Cntr=0.3,0.1

Type RM Length L Ch R = 1 ,3260    ,335,335,335
BEGIN DESCRIPTION:
LEFT BEAR CREEK 5.0
END DESCRIPTION:
XS GIS Cut Line= 3
      2738074.45     10026308.17      2738662.99     10026490.46
      2740027.61     10025839.41
#Sta/Elev= 30
  4000.2 1775.53  4056.8 1770.18  4084.2 1765.62    4151 1755.86  4239.3 1748.97
  4627.6 1744.17  4685.3 1745.11    4902 1748.15  4910.5 1746.86  4919.1 1742.13
  4932.6  1730.6  4947.4 1724.18  4970.1 1722.99  4996.1 1718.34  4998.9 1717.84
  5002.1 1718.34  5054.5 1728.38    5121 1730.31  5161.9 1731.09  5209.6 1732.78
  5287.2 1731.61  5406.7 1739.11  5474.8  1746.9  5599.3 1749.71  5618.4 1748.63
  5735.5 1751.31  5873.5 1764.89  6024.5 1776.16  6054.5 1777.42  6128.3  1780.5
#Mann= 11 ,-1 , 0
  4000.2     .05       0  4084.2      .1       0  4627.6     .16       0
  4685.3      .1       0  4996.1     .07       0  5002.1      .1       0
  5161.9     .16       0  5618.4      .1       0  5873.5     .16       0
  6024.5      .1       0  6054.5     .16       0
Bank Sta=4932.6,5121
XS Rating Curve= 0 ,0
Exp/Cntr=0.3,0.1

Type RM Length L Ch R = 1 ,2925    ,759,759,759
BEGIN DESCRIPTION:
LEFT BEAR CREEK 4.0
END DESCRIPTION:
XS GIS Cut Line= 3
      2738152.54     10027099.85      2739402.57     10026500.88
      2740102.91     10026298.56
#Sta/Elev= 30
  3850.7 1762.57  3939.2 1743.43  3979.2 1736.76  4011.1 1734.88  4267.8 1734.29
    4467 1736.87  4798.2 1744.02  4843.5 1740.97  4877.4  1732.9  4911.1 1730.08
  4932.6 1729.82  4955.1 1727.64  4977.2 1723.49  4990.6 1717.64  5010.2 1717.43
    5013 1716.93  5016.2 1717.43  5030.3 1718.84  5043.8  1723.2  5072.1 1725.23
  5098.3 1725.92  5110.3 1728.92  5154.7 1731.53  5313.6 1731.74  5445.5 1739.89
  5482.4 1742.88  5669.7 1749.19  5742.6 1758.69  5826.1 1775.05  5965.8 1781.41
#Mann= 10 ,-1 , 0
  3850.7     .16       0  3939.2      .1       0  4267.8     .16       0
    4467      .1       0  4911.1     .16       0  4932.6      .1       0
  5010.2     .07       0  5016.2      .1       0  5072.1     .16       0
  5445.5      .1       0
#XS Ineff= 1 ,-1
 3869.32 4801.14 1743.64
Permanent Ineff=
       F
Bank Sta=4955.1,5110.3
XS Rating Curve= 0 ,0
Exp/Cntr=0.3,0.1

Type RM Length L Ch R = 1 ,2166    ,1142,1142,1142
BEGIN DESCRIPTION:
LEFT BEAR CREEK 3.0
END DESCRIPTION:
XS GIS Cut Line= 3
      2738277.57     10027245.67      2739319.24     10027344.63
      2740124.97     10026975.55
#Sta/Elev= 30
  3578.2 1761.01  3591.5 1759.21  3607.4 1756.04  3612.4  1757.5  3659.5 1742.56
  3715.5 1730.07  3739.8 1727.17    4001 1726.23  4493.2 1730.12  4865.7 1736.74
  4887.7 1735.69  4903.5 1730.71  4909.7 1725.23  4926.5 1720.12  4972.5 1715.72
  5018.3 1714.43  5052.7 1721.81  5093.1 1725.28  5098.6 1725.49  5167.6 1732.24
  5190.6 1740.16  5236.6 1750.74  5282.6 1755.99  5288.1 1754.84  5311.1 1758.76
  5334.1 1766.28  5339.6 1765.42  5357.1 1771.13  5443.9 1775.98  5510.8 1781.99
#Mann= 5 ,-1 , 0
  3578.2     .16       0  3591.5      .1       0  4926.5     .07       0
  5098.6      .1       0  5443.9     .05       0
#XS Ineff= 1 ,-1
  3632.1  4867.9 1736.93
Permanent Ineff=
       F
Bank Sta=4909.7,5093.1
XS Rating Curve= 0 ,0
Exp/Cntr=0.3,0.1

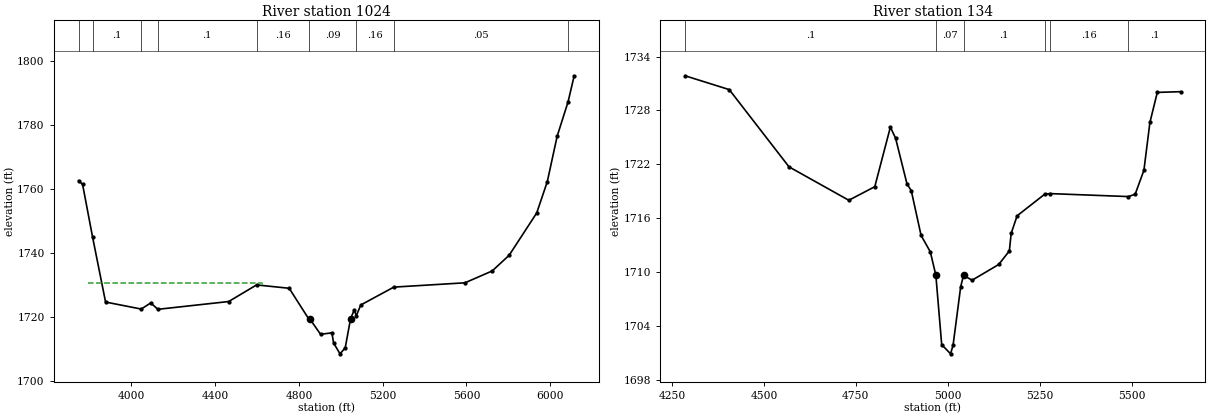
Type RM Length L Ch R = 1 ,1024    ,790,790,790
BEGIN DESCRIPTION:
LEFT BEAR CREEK 2.0
END DESCRIPTION:
XS GIS Cut Line= 4
      2738241.15     10027329.02      2739131.74     10027719.63
      2739319.24     10028256.09      2740135.19     10028126.16
#Sta/Elev= 30
  3747.5 1762.68  3766.3 1761.57  3813.9 1745.16  3876.2  1724.8  4046.4 1722.61
  4091.9 1724.52  4126.1 1722.53  4464.3 1724.96  4597.5 1730.15  4753.2  1729.1
  4846.3 1719.56  4851.6 1719.54  4903.1 1714.73  4957.4 1715.18  4965.2 1712.05
    4996 1708.62  5020.9  1710.5  5046.4 1719.59  5063.6 1722.27  5073.9 1720.53
  5095.1 1723.88    5253 1729.46  5592.9 1730.81  5722.9 1734.51  5803.9 1739.41
  5935.6 1752.63  5986.2 1762.42  6033.2  1776.6  6085.4 1787.34  6114.5 1795.48
#Mann= 9 ,-1 , 0
  3747.5     .16       0  3813.9      .1       0  4046.4     .05       0
  4126.1      .1       0  4597.5     .16       0  4846.3     .09       0
  5073.9     .16       0    5253     .05       0  6085.4      .1       0
#XS Ineff= 1 ,-1
 3791.48 4621.59 1730.79
Permanent Ineff=
       F
Bank Sta=4851.6,5046.4
XS Rating Curve= 0 ,0
Exp/Cntr=0.3,0.1

Type RM Length L Ch R = 1 ,134     ,0,0,0
BEGIN DESCRIPTION:
LEFT BEAR CREEK 1.0
END DESCRIPTION:
XS GIS Cut Line= 4
      2738777.61     10027683.14      2738343.45     10028102.48
      2738413.77     10028368.11      2738881.77     10028407.13
#Sta/Elev= 30
  4285.6 1731.86  4405.7 1730.32  4568.3 1721.72  4730.9    1718  4801.6 1719.51
    4844 1726.14  4858.2 1724.91  4889.2 1719.82  4900.8 1719.08  4927.5 1714.09
  4952.6 1712.26  4967.7 1709.66  4983.6 1701.93  5007.7  1700.9  5014.6 1701.87
  5035.3 1708.38    5043 1709.63  5066.4  1709.1  5138.8 1710.85  5167.7 1712.36
  5172.6 1714.31  5188.8 1716.27  5264.3 1718.69  5279.1 1718.74  5491.5 1718.41
  5509.9 1718.67  5533.7 1721.34    5550 1726.66  5570.1 1730.01  5633.6 1730.09
#Mann= 6 ,-1 , 0
  4285.6      .1       0  4967.7     .07       0    5043      .1       0
  5264.3      .1       0  5279.1     .16       0  5491.5      .1       0
Bank Sta=4967.7,5043
XS Rating Curve= 0 ,0
Exp/Cntr=0.3,0.1

Chan Stop Cuts=-1
Use User Specified Reach Order=0
Composite Channel Slope=5