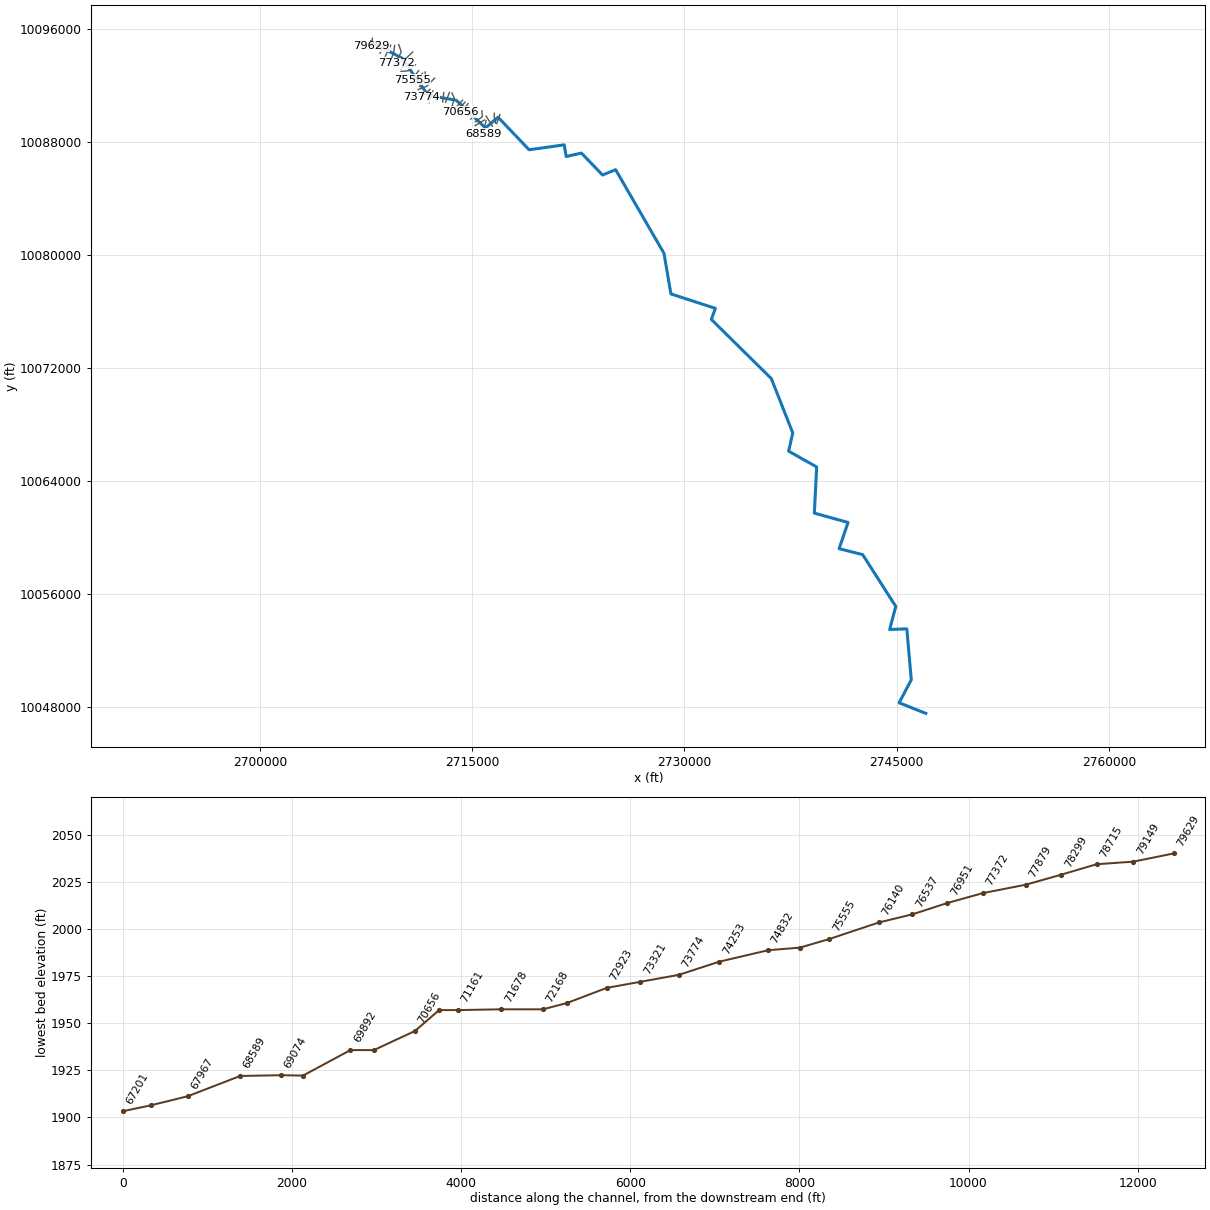
--- LIVE OAK CREEK.prj (project) ---

Proj Title=LIVE OAK CREEK Base Level Engineering
Current Plan=p01
Default Exp/Contr=0.3,0.1
English Units
Geom File=g01
Flow File=f01
Plan File=p01
Y Axis Title=Elevation
X Axis Title(PF)=Main Channel Distance
X Axis Title(XS)=Station
BEGIN DESCRIPTION:
LIVE OAK CREEK
END DESCRIPTION:
DSS Export Rating Curves= 0
DSS Export Rating Curve Sorted= 0
DSS Export Volume Flow Curves= 0
DXF OffsetX= 0
DXF OffsetY= 0
DXF ScaleX= 1
DXF ScaleY= 10

--- LIVE OAK CREEK.p01 (plan) ---

Plan Title=Multiple Run
Short Identifier=Multiple
Geom File=g01
Flow File=f01
Subcritical Flow
K Sum by GR= 0
Std Step Tol= 0.01
Critical Tol= 0.01
Num of Std Step Trials= 20
Max Error Tol= 0.3
Flow Tol Ratio= 0.001
Split Flow NTrial= 30
Split Flow Tol= 0.02
Split Flow Ratio= 0.02
Log Output Level= 0
Friction Slope Method= 1
Unsteady Friction Slope Method= 2
Unsteady Bridges Friction Slope Method= 1
Parabolic Critical Depth
Global Vel Dist=  1 , 1 , 1
Global Log Level= 0
CheckData=True
Encroach Param= -1, 0, 0, 0
BEGIN DESCRIPTION:
Multiple Run
END DESCRIPTION:

--- LIVE OAK CREEK.f01 (steady flow) ---

Flow Title=Multiple
Program Version=4.10
Number of Profiles= 7
Profile Names=10-year,25-year,50-year,1pct_min,100-year,1pct_plu,500-year
River Rch & RM=LIVE OAK CREEK,Reach-1         ,79629
    1927    2895    3758    3551    4803    6495    7845
River Rch & RM=LIVE OAK CREEK,Reach-1         ,75555
    2623    3998    5238    4991    6750    9128   11214
River Rch & RM=LIVE OAK CREEK,Reach-1         ,73321
    3148    4826    6349    6068    8206   11097   13720
River Rch & RM=LIVE OAK CREEK,Reach-1         ,66213
    4411    6867    9127    8808   11911   16109   20321
River Rch & RM=LIVE OAK CREEK,Reach-1         ,62599
    4520    7026    9330    8997   12168   16455   20737
River Rch & RM=LIVE OAK CREEK,Reach-1         ,56596
    4668    7252    9629    9284   12556   16981   21405
River Rch & RM=LIVE OAK CREEK,Reach-1         ,51677
    4663    7235    9598    9246   12504   16910   21280
River Rch & RM=LIVE OAK CREEK,Reach-1         ,47538
    6299    9864   13174   12779   17283   23373   29852
River Rch & RM=LIVE OAK CREEK,Reach-1         ,42343
    6519   10218   13655   13254   17924   24241   31001
River Rch & RM=LIVE OAK CREEK,Reach-1         ,41602
    6625   10371   13848   13429   18162   24561   31356
River Rch & RM=LIVE OAK CREEK,Reach-1         ,35875
    9124   14427   19397   18926   25595   34614   44709
River Rch & RM=LIVE OAK CREEK,Reach-1         ,34232
    9113   14392   19334   18848   25490   34472   44452
River Rch & RM=LIVE OAK CREEK,Reach-1         ,31209
    9231   14563   19549   19043   25753   34828   44843
River Rch & RM=LIVE OAK CREEK,Reach-1         ,30576
    9231   14563   19549   19043   25753   34828   44843
River Rch & RM=LIVE OAK CREEK,Reach-1         ,29695
    9231   14563   19549   19043   25753   34828   44843
River Rch & RM=LIVE OAK CREEK,Reach-1         ,25662
    9251   14585   19572   19057   25772   34854   44840
River Rch & RM=LIVE OAK CREEK,Reach-1         ,24082
    9169   14420   19317   18776   25393   34341   44028
River Rch & RM=LIVE OAK CREEK,Reach-1         ,17561
    9154   14379   19246   18692   25279   34186   43757
River Rch & RM=LIVE OAK CREEK,Reach-1         ,13688
    9346   14659   19601   19015   25715   34777   44416
River Rch & RM=LIVE OAK CREEK,Reach-1         ,12837
    9346   14659   19601   19015   25715   34777   44416
River Rch & RM=LIVE OAK CREEK,Reach-1         ,3986
    9289   14556   19450   18856   25501   34487   43987
Boundary for River Rch & Prof#=LIVE OAK CREEK,Reach-1         , 1
Up Type= 0
Dn Type= 3
Dn Slope=0.002
Boundary for River Rch & Prof#=LIVE OAK CREEK,Reach-1         , 2
Up Type= 0
Dn Type= 3
Dn Slope=0.002
Boundary for River Rch & Prof#=LIVE OAK CREEK,Reach-1         , 3
Up Type= 0
Dn Type= 3
Dn Slope=0.002
Boundary for River Rch & Prof#=LIVE OAK CREEK,Reach-1         , 4
Up Type= 0
Dn Type= 3
Dn Slope=0.002
Boundary for River Rch & Prof#=LIVE OAK CREEK,Reach-1         , 5
Up Type= 0
Dn Type= 3
Dn Slope=0.002
Boundary for River Rch & Prof#=LIVE OAK CREEK,Reach-1         , 6
Up Type= 0
Dn Type= 3
Dn Slope=0.002
Boundary for River Rch & Prof#=LIVE OAK CREEK,Reach-1         , 7
Up Type= 0
Dn Type= 3
Dn Slope=0.002
DSS Import GetInterval= 0
DSS Import GetPeak= 0
DSS Import FillOption= 0

--- LIVE OAK CREEK.g01 (geometry) ---

Geom Title=Existing Conditions
Program Version=4.10

River Reach=LIVE OAK CREEK  ,Reach-1
Reach XY= 30
      2707858.47     10095063.73      2710045.06     10093915.67
      2711893.72     10091289.84      2713888.47     10090933.73
      2715949.64     10088978.42      2716832.46     10089738.33
      2719029.59     10087436.45      2721512.91     10087782.26
      2721651.51     10086960.27      2722727.63     10087201.71
      2724220.09     10085651.46      2725144.23     10086025.74
      2728563.47     10080109.79      2729052.94     10077241.09
      2732192.21      10076220.5      2731912.72     10075435.15
       2736149.7     10071253.09      2737664.51     10067411.53
      2737372.73     10066119.72      2739353.23     10065004.17
      2739190.23     10061739.46      2741570.46     10061080.13
      2740941.99     10059224.22      2742607.81     10058801.41
      2744943.97     10055141.46      2744513.59     10053510.05
      2745725.65     10053556.21      2746041.87     10049949.13
      2745182.29     10048325.31      2747069.85     10047576.94

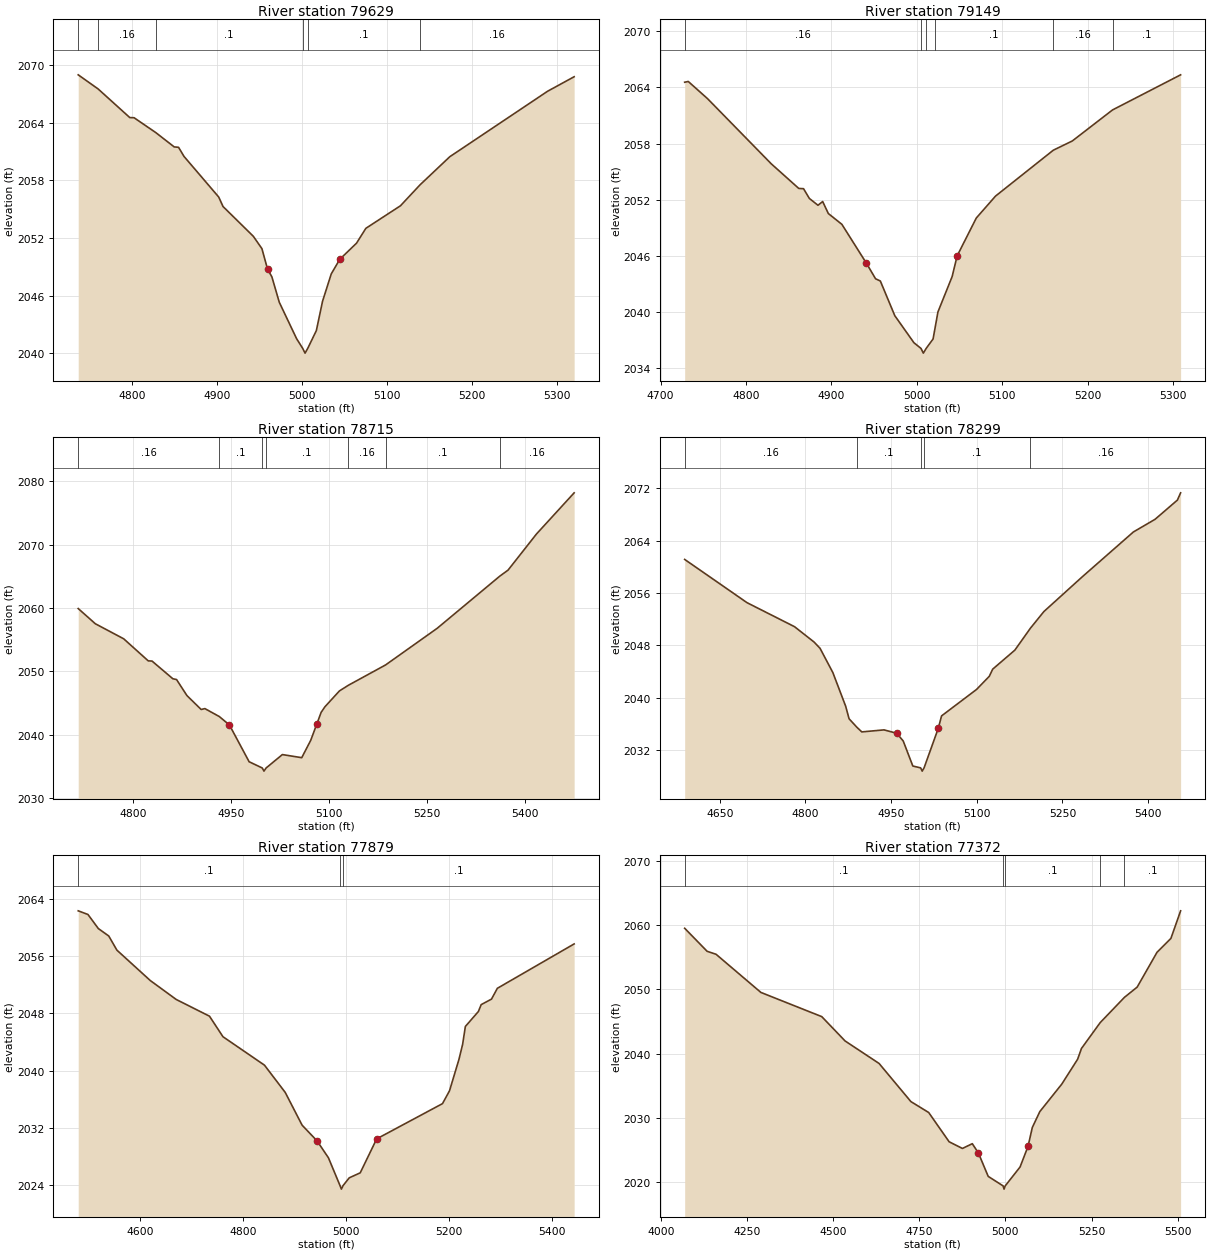
Type RM Length L Ch R = 1 ,79629   ,480,480,480
BEGIN DESCRIPTION:
LIVE OAK CREEK 156.0
END DESCRIPTION:
XS GIS Cut Line= 2
      2707955.16     10095316.01      2707846.65     10094743.09
#Sta/Elev= 30
  4736.8 2068.99  4760.2 2067.52  4797.4 2064.54  4802.5 2064.52  4827.9 2062.98
  4849.7 2061.48  4854.8 2061.44  4861.2 2060.49    4902 2056.26  4907.1 2055.27
  4942.7 2052.17  4952.8 2050.88  4959.4 2048.75  4964.5 2047.95  4973.2  2045.3
  4993.6  2041.5  5000.7  2040.5  5003.5    2040  5006.7  2040.5  5016.8 2042.35
  5024.1 2045.41  5034.3 2048.25  5044.4 2049.78    5064 2051.45    5075    2053
  5115.7 2055.35  5138.7 2057.53  5173.7 2060.46  5288.7 2067.28  5319.9 2068.79
#Mann= 6 ,-1 , 0
  4736.8      .1       0  4760.2     .16       0  4827.9      .1       0
  5000.7     .07       0  5006.7      .1       0  5138.7     .16       0
Bank Sta=4959.4,5044.4
XS Rating Curve= 0 ,0
Exp/Cntr=0.3,0.1

Type RM Length L Ch R = 1 ,79149   ,434,434,434
BEGIN DESCRIPTION:
LIVE OAK CREEK 155.0
END DESCRIPTION:
XS GIS Cut Line= 2
      2708454.28     10095094.62       2708198.2     10094573.77
#Sta/Elev= 30
  4728.2 2064.56  4732.4 2064.64  4754.9 2062.81  4829.5 2055.85  4861.7 2053.22
  4867.3 2053.19  4874.1 2052.15  4884.2 2051.42  4889.7 2051.82  4896.3 2050.54
  4912.2 2049.38  4940.9 2045.23  4951.6 2043.57  4957.2 2043.33  4974.1 2039.63
  4996.5 2036.74  5004.8 2036.13  5007.5 2035.63  5010.8 2036.13  5018.9 2037.14
  5020.7 2038.05  5024.6 2040.03  5041.2  2043.8  5047.1 2046.02  5069.5 2050.06
    5092  2052.4  5159.6  2057.3  5181.9 2058.29  5228.9  2061.6  5308.6 2065.35
#Mann= 6 ,-1 , 0
  4728.2     .16       0  5004.8     .07       0  5010.8     .16       0
  5020.7      .1       0  5159.6     .16       0  5228.9      .1       0
Bank Sta=4940.9,5047.1
XS Rating Curve= 0 ,0
Exp/Cntr=0.3,0.1

Type RM Length L Ch R = 1 ,78715   ,416,416,416
BEGIN DESCRIPTION:
LIVE OAK CREEK 154.0
END DESCRIPTION:
XS GIS Cut Line= 2
      2708866.64     10094921.06      2708493.42     10094261.42
#Sta/Elev= 30
  4716.6  2059.9  4742.8  2057.5  4786.1 2055.13  4823.6 2051.65  4829.4 2051.62
  4861.2 2048.83  4866.9  2048.7  4882.8 2046.17  4904.5 2043.98  4910.2 2044.12
  4932.2 2042.87  4947.7 2041.54  4977.8 2035.74  4997.8 2034.76  5000.5 2034.26
  5003.8 2034.76  5028.6 2036.87  5058.2 2036.38  5071.9 2039.11  5081.2 2041.68
  5087.8 2043.52  5093.5 2044.39  5115.7  2046.9  5129.3 2047.79  5186.4 2051.01
    5265 2056.77    5361 2065.02  5373.5 2065.96  5416.8 2071.64  5474.5 2078.15
#Mann= 7 ,-1 , 0
  4716.6     .16       0  4932.2      .1       0  4997.8     .07       0
  5003.8      .1       0  5129.3     .16       0  5186.4      .1       0
    5361     .16       0
Bank Sta=4947.7,5081.2
XS Rating Curve= 0 ,0
Exp/Cntr=0.3,0.1

Type RM Length L Ch R = 1 ,78299   ,420,420,420
BEGIN DESCRIPTION:
LIVE OAK CREEK 153.0
END DESCRIPTION:
XS GIS Cut Line= 2
      2709252.88      10094825.5      2708862.88     10094049.83
#Sta/Elev= 30
  4588.7 2061.14  4697.9 2054.52    4781 2050.85  4815.1 2048.51  4825.7 2047.54
  4848.1 2043.83  4870.5 2038.69  4876.5 2036.76  4890.3 2035.45  4898.8 2034.75
  4937.7 2035.06    4960 2034.54  4971.3 2033.36  4988.1 2029.53  5001.8 2029.25
  5004.5 2028.75  5007.8 2029.25  5032.7 2035.31  5038.4  2037.2  5099.7 2041.25
    5122 2043.26  5127.9 2044.35  5166.7 2047.26  5193.9 2050.61  5217.5 2053.16
  5284.6 2058.47  5374.2 2065.34  5412.2 2067.28  5451.3 2070.22  5456.9 2071.33
#Mann= 5 ,-1 , 0
  4588.7     .16       0  4890.3      .1       0  5001.8     .07       0
  5007.8      .1       0  5193.9     .16       0
Bank Sta=4960,5032.7
XS Rating Curve= 0 ,0
Exp/Cntr=0.3,0.1

Type RM Length L Ch R = 1 ,77879   ,507,507,507
BEGIN DESCRIPTION:
LIVE OAK CREEK 152.0
END DESCRIPTION:
XS GIS Cut Line= 3
      2709521.99     10094812.51      2709469.91     10094352.44
      2709300.64     10093883.68
#Sta/Elev= 30
  4480.7 2062.35  4499.6 2061.84  4519.7 2059.87  4539.9 2058.83  4555.7 2056.85
  4620.4  2052.6  4670.7 2049.95  4735.2 2047.61  4761.3 2044.74  4841.8 2040.76
    4882 2036.95  4914.7 2032.37  4943.7 2030.17  4965.8  2027.8  4988.2 2023.92
  4990.9 2023.42  4994.2 2023.92  5006.1    2025  5027.4  2025.7  5059.3 2030.45
  5186.9 2035.38  5200.5 2037.18  5218.8 2041.57  5225.9 2043.67  5231.2 2046.17
  5256.5 2048.27  5261.9 2049.23  5281.9    2050  5293.2 2051.51  5442.1 2057.72
#Mann= 3 ,-1 , 0
  4480.7      .1       0  4988.2     .07       0  4994.2      .1       0
Bank Sta=4943.7,5059.3
XS Rating Curve= 0 ,0
Exp/Cntr=0.3,0.1

Type RM Length L Ch R = 1 ,77372   ,421,421,421
BEGIN DESCRIPTION:
LIVE OAK CREEK 151.0
END DESCRIPTION:
XS GIS Cut Line= 3
      2709812.78     10094881.99      2709990.74     10094365.46
      2709622.65     10093551.33
#Sta/Elev= 30
  4068.9  2059.5  4134.1 2055.92    4160 2055.46  4290.2 2049.53  4466.9 2045.77
  4534.6 2041.99  4633.2  2038.5  4725.7 2032.57  4777.4 2030.87  4836.6 2026.33
  4875.3 2025.29  4903.9 2026.03  4921.5  2024.6  4950.1 2020.95  4993.4 2019.47
  4996.1 2018.97  4999.4 2019.47  5042.6 2022.41  5065.7 2025.61  5078.1 2028.54
    5100 2031.02  5163.6 2035.28  5209.7 2039.15  5220.8 2040.82  5275.2 2044.84
  5345.7 2048.77  5382.6 2050.36  5440.2 2055.77  5480.5 2057.92  5508.7 2062.21
#Mann= 5 ,-1 , 0
  4068.9      .1       0  4993.4     .07       0  4999.4      .1       0
  5275.2     .16       0  5345.7      .1       0
Bank Sta=4921.5,5065.7
XS Rating Curve= 0 ,0
Exp/Cntr=0.3,0.1

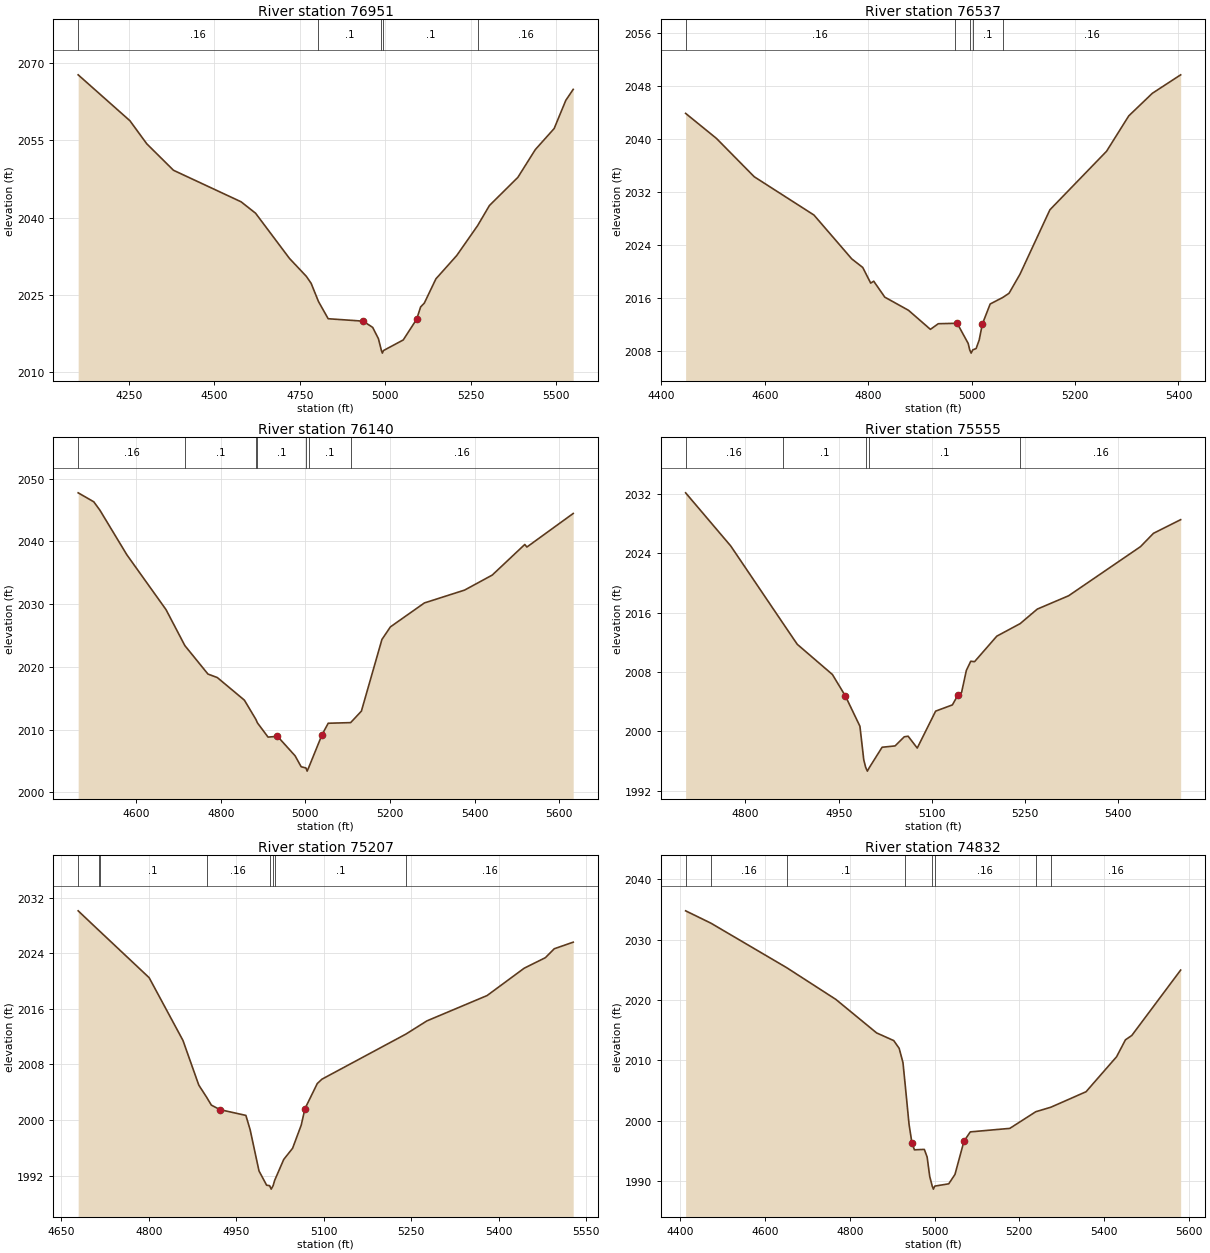
Type RM Length L Ch R = 1 ,76951   ,414,414,414
BEGIN DESCRIPTION:
LIVE OAK CREEK 150.0
END DESCRIPTION:
XS GIS Cut Line= 3
      2710802.38     10094343.76      2710220.78     10093796.88
      2709639.16     10093506.08
#Sta/Elev= 30
  4101.3 2067.69  4252.7 2058.79  4302.1 2054.31  4380.2 2049.18    4578 2043.07
  4620.5 2040.85  4719.6 2032.09    4769 2028.61  4783.1 2027.25  4804.5 2023.73
  4832.9 2020.39  4935.2 2019.92  4963.1 2018.71  4979.9 2016.52  4988.7 2014.22
  4991.4 2013.72  4994.7 2014.22  5052.6 2016.28  5091.7 2020.29  5103.5 2022.69
  5114.1 2023.41  5148.2 2028.13  5209.1 2032.65  5270.4 2038.47  5304.7 2042.34
    5388 2047.81  5438.9 2053.18  5494.2 2057.28  5528.3 2062.75  5549.9 2064.87
#Mann= 5 ,-1 , 0
  4101.3     .16       0  4804.5      .1       0  4988.7     .07       0
  4994.7      .1       0  5270.4     .16       0
Bank Sta=4935.2,5091.7
XS Rating Curve= 0 ,0
Exp/Cntr=0.3,0.1

Type RM Length L Ch R = 1 ,76537   ,397,397,397
BEGIN DESCRIPTION:
LIVE OAK CREEK 149.0
END DESCRIPTION:
XS GIS Cut Line= 2
      2710785.02      10093679.7      2709973.39     10093171.89
#Sta/Elev= 30
  4446.9  2043.9  4506.5 2040.12  4579.6 2034.33  4695.1 2028.55  4768.2 2021.93
  4789.5 2020.63  4804.8 2018.27  4810.7 2018.56  4832.1 2016.15  4877.9 2014.17
  4920.3 2011.29  4935.6 2012.14    4968  2012.2  4972.2 2012.19  4993.4 2009.16
  4996.3  2008.2  4999.1  2007.7  5002.3  2008.2  5008.7 2008.39  5014.6 2009.66
  5020.8 2012.09  5035.9 2015.12  5060.4 2016.11  5072.4 2016.74  5093.6 2019.62
  5151.4 2029.34    5261 2038.18  5303.9 2043.52  5349.5 2046.93  5404.3 2049.72
#Mann= 5 ,-1 , 0
  4446.9     .16       0    4968      .1       0  4996.3     .07       0
  5002.3      .1       0  5060.4     .16       0
Bank Sta=4972.2,5020.8
XS Rating Curve= 0 ,0
Exp/Cntr=0.3,0.1

Type RM Length L Ch R = 1 ,76140   ,585,585,585
BEGIN DESCRIPTION:
LIVE OAK CREEK 148.0
END DESCRIPTION:
XS GIS Cut Line= 3
      2710993.36     10093440.99      2710476.86     10093015.63
      2709977.68     10092980.91
#Sta/Elev= 30
  4463.3 2047.73  4500.2  2046.3  4514.5 2044.98  4578.4 2037.85  4670.9 2029.11
  4715.4 2023.38  4769.9 2018.85  4792.1 2018.29    4856 2014.69  4883.2 2011.62
  4886.7 2011.08  4911.9  2008.8  4934.2 2008.93  4975.8 2005.82  4990.1 2004.08
  5001.5 2003.88  5004.2 2003.38  5007.5 2003.88  5039.6 2009.21    5054 2011.01
    5107 2011.11  5132.4 2012.94  5180.9 2024.36    5201 2026.37  5281.2 2030.18
  5376.2 2032.23  5441.5 2034.62  5518.4  2039.5  5523.4 2039.09  5632.8 2044.44
#Mann= 7 ,-1 , 0
  4463.3     .16       0  4715.4      .1       0  4883.2     .16       0
  4886.7      .1       0  5001.5     .07       0  5007.5      .1       0
    5107     .16       0
Bank Sta=4934.2,5039.6
XS Rating Curve= 0 ,0
Exp/Cntr=0.3,0.1

Type RM Length L Ch R = 1 ,75555   ,348,348,348
BEGIN DESCRIPTION:
LIVE OAK CREEK 147.0
END DESCRIPTION:
XS GIS Cut Line= 2
      2711219.04     10093032.98      2710758.96     10092381.94
#Sta/Elev= 30
  4703.6 2032.15  4776.2 2024.99  4860.3 2014.57  4883.4 2011.72    4940 2007.65
  4960.9 2004.75  4984.3 2000.67  4990.5 1996.13  4993.6 1995.12  4996.3 1994.62
  4999.6 1995.12    5020 1997.84  5040.9 1998.02  5055.7 1999.25  5061.9 1999.33
  5076.6 1997.73  5106.2 2002.71  5133.2 2003.55  5141.9 2004.84    5148 2005.24
  5155.7 2008.21  5162.8 2009.44  5168.9 2009.38  5204.7 2012.82  5242.3 2014.51
  5269.9 2016.47  5320.4 2018.27  5436.1 2024.89    5457 2026.69  5500.8 2028.53
#Mann= 5 ,-1 , 0
  4703.6     .16       0  4860.3      .1       0  4993.6     .07       0
  4999.6      .1       0  5242.3     .16       0
Bank Sta=4960.9,5141.9
XS Rating Curve= 0 ,0
Exp/Cntr=0.3,0.1

Type RM Length L Ch R = 1 ,75207   ,375,375,375
BEGIN DESCRIPTION:
LIVE OAK CREEK 146.0
END DESCRIPTION:
XS GIS Cut Line= 2
       2711492.5     10092846.39      2711036.75     10092130.21
#Sta/Elev= 30
  4678.9  2030.1  4715.3 2027.21  4715.6 2027.19  4800.6 2020.48  4858.6 2011.45
  4885.7 2005.03  4899.2 2003.27  4907.3 2002.14  4922.1 2001.49  4966.5 2000.66
  4973.8  1998.6    4989 1992.67  5002.1 1990.61  5007.2 1990.55  5009.9 1990.05
  5013.2 1990.55  5015.9 1991.32  5031.4 1994.32  5046.6 1995.93  5061.4 1999.26
  5067.8 2001.63  5088.9 2005.24  5096.9 2005.87  5240.9 2012.36  5276.9 2014.26
  5380.2 2017.91  5443.7 2021.84  5480.1 2023.36  5495.3 2024.64  5527.8 2025.59
#Mann= 8 ,-1 , 0
  4678.9      .1       0  4715.3     .16       0  4715.6      .1       0
  4899.2     .16       0  5007.2     .07       0  5013.2     .16       0
  5015.9      .1       0  5240.9     .16       0
Bank Sta=4922.1,5067.8
XS Rating Curve= 0 ,0
Exp/Cntr=0.3,0.1

Type RM Length L Ch R = 1 ,74832   ,579,579,579
BEGIN DESCRIPTION:
LIVE OAK CREEK 145.0
END DESCRIPTION:
XS GIS Cut Line= 3
      2711683.45     10092937.53      2711709.49     10092486.12
      2711310.19     10091891.51
#Sta/Elev= 30
  4412.4 2034.77    4472 2032.73  4650.6 2025.37  4766.8 2020.11  4863.2 2014.55
  4903.6 2013.28  4916.4    2012  4925.4 2009.63    4931  2005.7  4939.7 1999.43
  4946.4 1996.39  4952.4 1995.19  4975.8 1995.26  4982.4    1994  4988.5 1990.79
  4994.4 1989.18  4997.2 1988.68  5000.4 1989.18  5033.4 1989.56  5048.1 1991.11
  5069.4 1996.62  5084.3 1998.16  5177.5 1998.74  5238.9  2001.5  5274.6 2002.25
  5357.5 2004.81  5429.5  2010.6  5450.5 2013.41  5465.5 2014.13  5580.8 2024.96
#Mann= 8 ,-1 , 0
  4412.4      .1       0    4472     .16       0  4650.6      .1       0
    4931     .16       0  4994.4     .07       0  5000.4     .16       0
  5238.9      .1       0  5274.6     .16       0
Bank Sta=4946.4,5069.4
XS Rating Curve= 0 ,0
Exp/Cntr=0.3,0.1

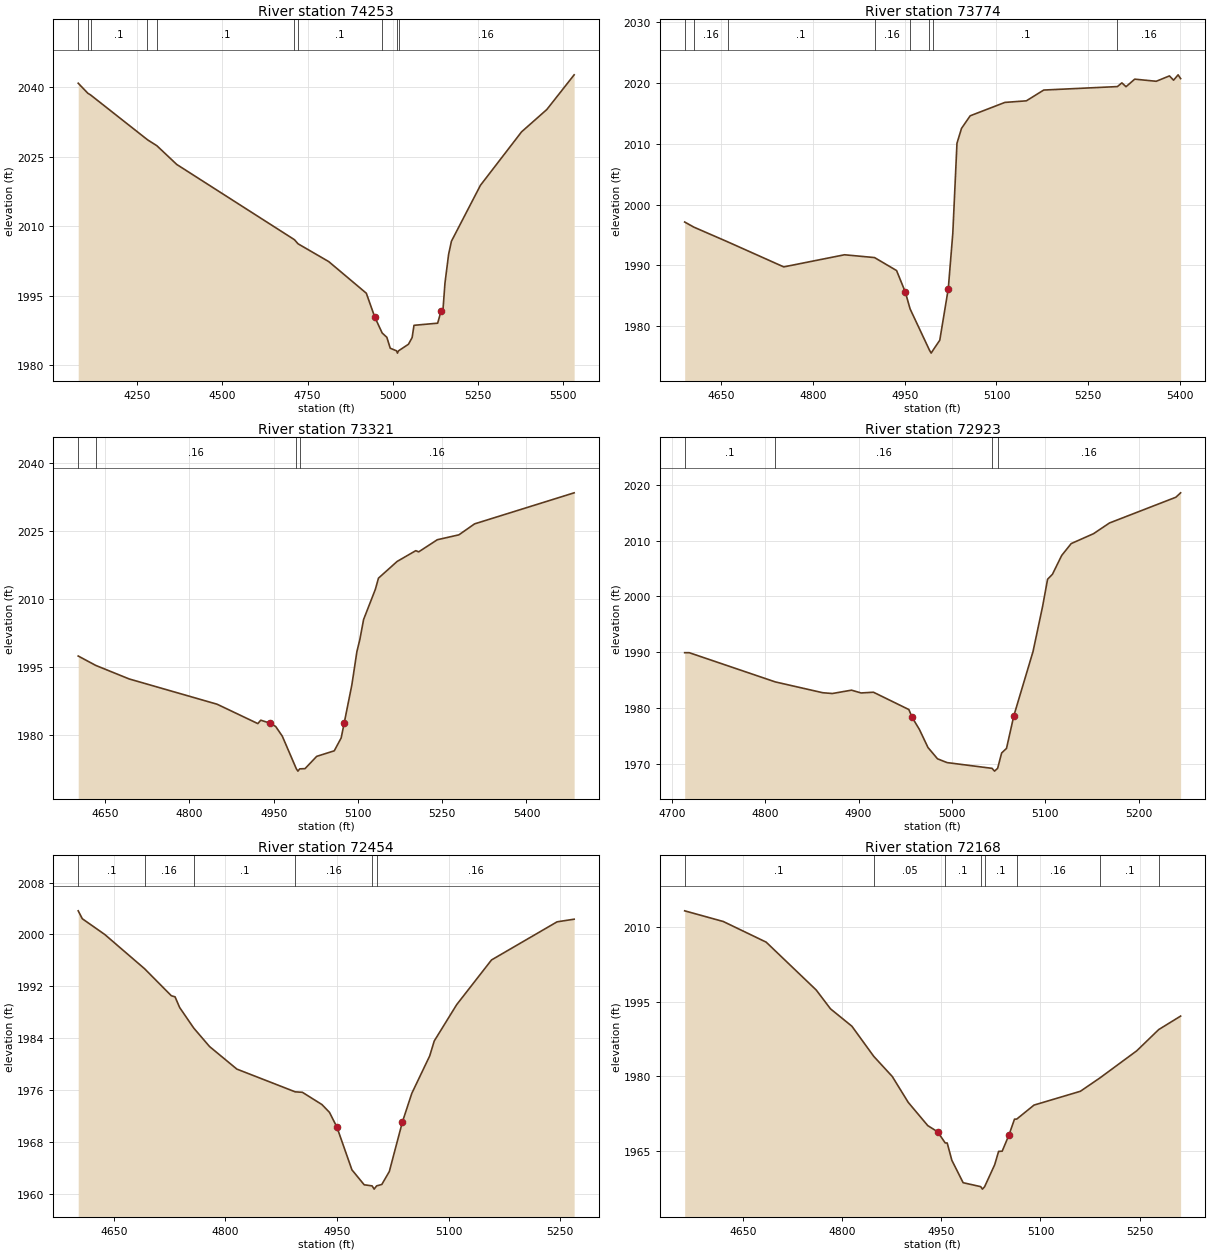
Type RM Length L Ch R = 1 ,74253   ,479,479,479
BEGIN DESCRIPTION:
LIVE OAK CREEK 144.0
END DESCRIPTION:
XS GIS Cut Line= 3
      2712347.48     10092503.45      2711800.64     10091926.22
      2711184.33     10091691.85
#Sta/Elev= 30
  4077.4 2040.83  4105.9 2038.65  4113.5 2038.31  4280.6 2028.63  4308.2 2027.34
  4366.3 2023.31  4711.6 2007.07  4722.1 2006.19  4812.1 2002.35  4922.4 1995.52
  4947.1 1990.39  4968.9 1986.94  4982.6 1986.01  4992.5 1983.66  5010.9  1983.1
  5013.7  1982.6  5016.9  1983.1    5046 1984.52  5056.7 1985.96  5062.2  1988.6
  5131.6 1989.06  5141.9 1991.76  5147.2 1991.93    5153 1997.68  5163.7 2003.91
    5172 2006.74    5257  2018.8  5377.7 2030.34  5451.8 2035.16  5531.9 2042.64
#Mann= 10 ,-1 , 0
  4077.4      .1       0  4105.9     .16       0  4113.5      .1       0
  4280.6     .16       0  4308.2      .1       0  4711.6     .16       0
  4722.1      .1       0  4968.9     .16       0  5010.9     .07       0
  5016.9     .16       0
Bank Sta=4947.1,5141.9
XS Rating Curve= 0 ,0
Exp/Cntr=0.3,0.1

Type RM Length L Ch R = 1 ,73774   ,453,453,453
BEGIN DESCRIPTION:
LIVE OAK CREEK 143.0
END DESCRIPTION:
XS GIS Cut Line= 2
      2712026.33     10091704.86      2711427.79     10091158.37
#Sta/Elev= 30
  4590.5 1997.13  4605.5 1996.29  4660.9 1993.87  4752.4 1989.76  4851.7 1991.75
  4900.8 1991.29  4936.8 1989.16    4951 1985.65  4958.9 1982.86  4990.5  1976.1
  4993.3  1975.6  4996.5  1976.1  5007.4 1977.72  5021.3 1986.18  5028.7 1995.28
  5035.5 2010.06  5042.9  2012.5  5057.1 2014.57  5113.8 2016.77  5148.9 2017.03
  5177.3  2018.8  5297.7 2019.37    5305 2019.98  5311.8 2019.35    5326 2020.59
  5361.1 2020.24  5382.7 2021.12  5389.5 2020.42  5396.9  2021.3    5401 2020.68
#Mann= 8 ,-1 , 0
  4590.5      .1       0  4605.5     .16       0  4660.9      .1       0
  4900.8     .16       0  4958.9      .1       0  4990.5     .07       0
  4996.5      .1       0  5297.7     .16       0
Bank Sta=4951,5021.3
XS Rating Curve= 0 ,0
Exp/Cntr=0.3,0.1

Type RM Length L Ch R = 1 ,73321   ,398,398,398
BEGIN DESCRIPTION:
LIVE OAK CREEK 142.0
END DESCRIPTION:
XS GIS Cut Line= 2
        2712226.     10091600.73      2711974.26     10090754.38
#Sta/Elev= 30
  4601.9 1997.37    4633  1995.3  4692.7  1992.3  4849.2 1986.72  4921.7 1982.44
  4926.9 1983.19  4943.1 1982.55  4953.5  1981.8  4965.3 1979.66  4990.3 1972.44
  4993.1 1971.94  4996.3 1972.44  5005.7 1972.49  5026.5  1975.2  5057.8 1976.43
  5070.1 1979.27 5075.57 1982.62  5089.1 1990.98  5098.1 1998.35  5103.3 2000.99
    5110 2005.43  5130.9 2012.08  5136.5 2014.57  5169.7 2018.26  5202.9 2020.64
  5208.1 2020.38  5241.3 2023.06  5279.7 2024.14  5307.6 2026.56  5484.9 2033.42
#Mann= 4 ,-1 , 0
  4601.9      .1       0    4633     .16       0  4990.3     .07       0
  4996.3     .16       0
Bank Sta=4943.1,5075.57
XS Rating Curve= 0 ,0
Exp/Cntr=0.3,0.1

Type RM Length L Ch R = 1 ,72923   ,469,469,469
BEGIN DESCRIPTION:
LIVE OAK CREEK 141.0
END DESCRIPTION:
XS GIS Cut Line= 2
      2712555.84     10091418.38      2712443.36     10090899.23
#Sta/Elev= 30
  4713.7 1989.92  4718.6 1989.92  4810.7 1984.69  4861.6 1982.75  4871.9 1982.61
  4892.4 1983.21  4902.6 1982.71  4915.9 1982.84  4953.8 1979.74 4957.39 1978.32
  4965.1 1976.18  4974.3 1972.94  4984.5 1970.92  4994.7 1970.24  5042.9 1969.21
  5045.6 1968.71  5048.9 1969.21  5053.2 1971.96  5058.4 1972.78  5066.3 1978.65
  5086.8 1990.12    5097 1998.15  5102.4 2003.07  5107.6 2003.96  5117.5 2007.33
  5127.7 2009.46  5151.6 2011.23  5168.7 2013.15  5239.8 2017.76  5244.9 2018.55
#Mann= 4 ,-1 , 0
  4713.7      .1       0  4810.7     .16       0  5042.9     .07       0
  5048.9     .16       0
Bank Sta=4957.39,5066.3
XS Rating Curve= 0 ,0
Exp/Cntr=0.3,0.1

Type RM Length L Ch R = 1 ,72454   ,286,286,286
BEGIN DESCRIPTION:
LIVE OAK CREEK 140.0
END DESCRIPTION:
XS GIS Cut Line= 2
      2712998.56     10091479.17      2712920.65     10090816.94
#Sta/Elev= 30
    4602 2003.65  4607.5 2002.43  4637.7    2000  4691.2 1994.72  4727.2 1990.55
  4732.2 1990.38  4738.4 1988.73  4757.4 1985.55  4778.6 1982.71  4815.3 1979.23
  4893.8 1975.72  4903.4 1975.65  4929.7 1973.76  4939.8 1972.56  4949.8 1970.29
    4970 1963.69  4986.5 1961.38  4997.2 1961.21  4999.9 1960.71  5003.2 1961.21
  5010.2 1961.43  5020.3 1963.43  5037.9 1971.08  5050.5 1975.48  5074.6 1981.27
  5080.7 1983.57  5110.9 1989.18  5157.7 1996.07  5245.8 2001.95  5268.8 2002.36
#Mann= 6 ,-1 , 0
    4602      .1       0  4691.2     .16       0  4757.4      .1       0
  4893.8     .16       0  4997.2     .07       0  5003.2     .16       0
Bank Sta=4949.8,5037.9
XS Rating Curve= 0 ,0
Exp/Cntr=0.3,0.1

Type RM Length L Ch R = 1 ,72168   ,490,490,490
BEGIN DESCRIPTION:
LIVE OAK CREEK 139.0
END DESCRIPTION:
XS GIS Cut Line= 2
      2713402.21     10091487.88      2713120.08      10090793.4
#Sta/Elev= 30
  4562.2 2013.31  4620.6 2011.16  4685.4 2007.01    4761 1997.39  4782.6  1993.6
  4814.9 1990.11    4848 1984.04    4876 1979.99  4900.1 1974.79  4929.6 1970.12
  4944.5 1968.87    4956 1966.63    4959 1966.62    4966 1963.15  4983.1 1958.63
  5009.6 1957.84  5012.3 1957.34  5015.6 1957.84  5030.8 1962.26  5036.7 1964.93
  5042.1 1964.97  5052.4 1968.25  5060.7 1971.41  5064.1 1971.43  5090.2 1974.24
  5160.3 1977.02  5189.8  1979.7  5245.5 1985.16  5278.7 1989.43  5311.8 1992.14
#Mann= 8 ,-1 , 0
  4562.2      .1       0    4848     .05       0    4956      .1       0
  5009.6     .07       0  5015.6      .1       0  5064.1     .16       0
  5189.8      .1       0  5278.7     .16       0
Bank Sta=4944.5,5052.4
XS Rating Curve= 0 ,0
Exp/Cntr=0.3,0.1

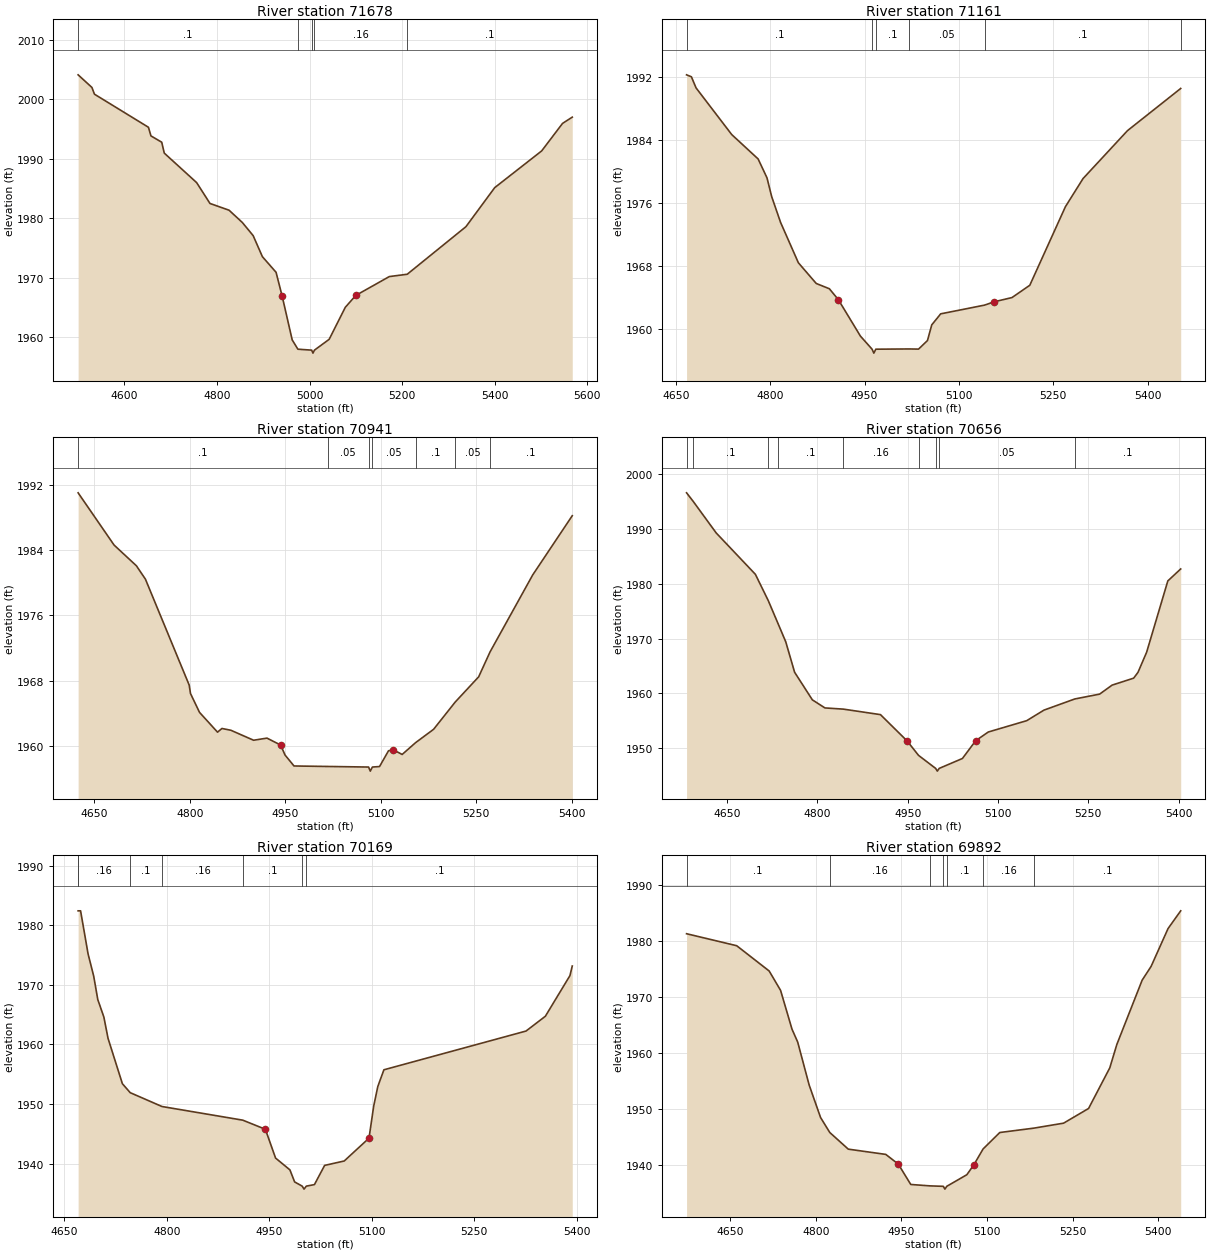
Type RM Length L Ch R = 1 ,71678   ,517,517,517
BEGIN DESCRIPTION:
LIVE OAK CREEK 138.0
END DESCRIPTION:
XS GIS Cut Line= 3
      2713580.16     10091453.12      2713740.74     10091088.55
      2713567.13     10090441.82
#Sta/Elev= 30
  4499.8 2004.11  4529.6 2001.99  4535.1 2000.86  4651.8  1995.3  4657.2 1993.85
  4680.5 1992.79    4686 1990.96    4756    1986  4784.8  1982.5    4826 1981.37
  4854.8  1979.3  4878.1  1977.1  4898.1 1973.56  4927.6 1970.94 4940.68 1966.97
  4962.5 1959.58  4974.8 1958.02  5004.6 1957.86  5007.4 1957.36  5010.6 1957.86
  5042.4 1959.68  5077.3 1965.06  5099.9 1967.05  5172.4 1970.22  5211.1 1970.61
    5338  1978.6  5400.2 1985.16  5501.7 1991.33  5546.8 1995.95  5567.8    1997
#Mann= 5 ,-1 , 0
  4499.8      .1       0  4974.8     .16       0  5004.6     .07       0
  5010.6     .16       0  5211.1      .1       0
Bank Sta=4940.68,5099.9
XS Rating Curve= 0 ,0
Exp/Cntr=0.3,0.1

Type RM Length L Ch R = 1 ,71161   ,220,220,220
BEGIN DESCRIPTION:
LIVE OAK CREEK 137.0
END DESCRIPTION:
XS GIS Cut Line= 2
      2714326.66     10090936.62      2713793.13     10090359.71
#Sta/Elev= 30
  4666.9  1992.3  4674.6 1992.05    4682 1990.64  4738.7 1984.71  4780.7 1981.61
  4794.8 1979.21  4802.2 1976.84  4816.4 1973.55  4844.7 1968.42  4873.1 1965.79
    4894 1965.12  4908.2 1963.74  4943.4  1959.1  4961.9 1957.44  4964.7 1956.94
  4967.9 1957.44  5021.2 1957.47  5035.8 1957.45    5050 1958.54  5056.8 1960.53
    5071 1961.93  5140.8 1963.04    5156 1963.46  5184.4    1964  5212.7 1965.56
  5269.4 1975.55  5297.4 1979.12  5368.1 1985.21  5452.6 1990.56  5452.7 1990.57
#Mann= 6 ,-1 , 0
  4666.9      .1       0  4961.9     .07       0  4967.9      .1       0
  5021.2     .05       0  5140.8      .1       0  5452.6     .16       0
Bank Sta=4908.2,5156
XS Rating Curve= 0 ,0
Exp/Cntr=0.3,0.1

Type RM Length L Ch R = 1 ,70941   ,285,285,285
BEGIN DESCRIPTION:
Mapping XS effddf7a
END DESCRIPTION:
XS GIS Cut Line= 2
      2714505.37     10090806.39      2713975.43      10090238.7
#Sta/Elev= 30
  4624.5    1991    4681 1984.61  4716.1 1982.07  4730.3 1980.43  4799.1 1967.46
  4801.1 1966.44  4815.3 1964.13  4843.6 1961.71  4850.5 1962.16  4864.6 1961.94
  4900.3 1960.72  4921.3 1960.98  4942.8 1960.13  4949.7 1958.91  4963.8 1957.57
  5016.7 1957.51    5081 1957.44  5083.7 1956.94    5087 1957.44  5098.2  1957.5
  5112.3 1959.43  5119.7 1959.55  5133.8 1958.98  5154.8 1960.42  5183.2 1962.06
  5217.2  1965.4    5254 1968.48  5271.9 1971.53    5339 1980.96  5401.1  1988.2
#Mann= 7 ,-1 , 0
  4624.5      .1       0  5016.7     .05       0    5081     .07       0
    5087     .05       0  5154.8      .1       0  5217.2     .05       0
  5271.9      .1       0
Bank Sta=4942.8,5119.7
XS Rating Curve= 0 ,0
Exp/Cntr=0.3,0.1

Type RM Length L Ch R = 1 ,70656   ,487,487,487
BEGIN DESCRIPTION:
LIVE OAK CREEK 136.0
END DESCRIPTION:
XS GIS Cut Line= 3
      2714718.47     10090703.74      2714468.47     10090353.73
       2714168.5     10090103.76
#Sta/Elev= 30
  4582.9 1996.51    4594 1994.94  4632.1 1989.21  4697.2 1981.68  4718.7 1976.87
  4735.3 1972.59  4747.6 1969.41  4762.3 1963.87  4791.8 1958.84  4812.7 1957.37
  4843.4 1957.15  4904.9 1956.15  4949.1 1951.37  4968.1 1948.74  4996.5 1946.37
  4999.3 1945.87  5002.5 1946.37    5041 1948.17  5063.1 1951.41    5084 1952.99
  5147.8 1955.05  5176.4 1956.97  5227.6    1959  5268.8 1959.88  5289.6 1961.52
  5325.4 1962.79  5332.6 1963.85  5346.9  1967.5  5382.1 1980.48  5403.5 1982.66
#Mann= 9 ,-1 , 0
  4582.9     .16       0    4594      .1       0  4718.7     .16       0
  4735.3      .1       0  4843.4     .16       0  4968.1     .05       0
  4996.5    .035       0  5002.5     .05       0  5227.6      .1       0
Bank Sta=4949.1,5063.1
XS Rating Curve= 0 ,0
Exp/Cntr=0.3,0.1

Type RM Length L Ch R = 1 ,70169   ,277,277,277
BEGIN DESCRIPTION:
LIVE OAK CREEK 135.0
END DESCRIPTION:
XS GIS Cut Line= 2
      2715077.52     10090415.77      2714670.22     10089817.81
#Sta/Elev= 30
    4670 1982.41  4670.2 1982.41  4673.6 1982.41  4684.6 1975.17  4692.8 1971.46
  4698.8 1967.52  4707.7 1964.59  4713.8 1961.02  4734.8 1953.41  4746.3  1951.9
  4792.8 1949.58  4911.1 1947.29  4944.2 1945.76  4959.1 1940.93  4980.1 1938.95
    4987 1936.93  4998.1 1936.22  5000.8 1935.72  5004.1 1936.22    5016 1936.48
  5030.9  1939.7  5059.6 1940.44  5095.9 1944.27  5102.8 1949.67  5108.8 1952.94
  5117.7 1955.74  5325.8 1962.24  5354.1 1964.72  5390.1 1971.54  5393.5 1973.15
#Mann= 7 ,-1 , 0
    4670      .1       0  4670.2     .16       0  4746.3      .1       0
  4792.8     .16       0  4911.1      .1       0  4998.1     .07       0
  5004.1      .1       0
Bank Sta=4944.2,5095.9
XS Rating Curve= 0 ,0
Exp/Cntr=0.3,0.1

Type RM Length L Ch R = 1 ,69892   ,560,560,560
BEGIN DESCRIPTION:
LIVE OAK CREEK 134.0
END DESCRIPTION:
XS GIS Cut Line= 3
      2715207.76     10090398.42      2715194.74     10090138.03
      2714908.27     10089604.15
#Sta/Elev= 30
  4573.1 1981.34    4661  1979.2    4718 1974.68    4738 1971.22    4758  1964.3
    4768 1961.99  4788.1 1954.32  4808.1 1948.52  4824.2 1945.85  4856.7 1942.87
  4922.5 1941.93  4944.4  1940.2  4966.3 1936.56  5000.1 1936.31  5023.4 1936.23
  5026.2 1935.73  5029.4 1936.23  5064.6  1938.3    5077 1940.08  5093.1  1942.9
  5122.4 1945.84  5182.1 1946.62  5234.3 1947.51  5278.1 1950.13  5315.3 1957.38
  5327.7 1961.57  5372.1 1973.05  5387.8 1975.51  5417.5 1982.26  5439.7 1985.43
#Mann= 7 ,-1 , 0
  4573.1      .1       0  4824.2     .16       0  5000.1      .1       0
  5023.4     .07       0  5029.4      .1       0  5093.1     .16       0
  5182.1      .1       0
Bank Sta=4944.4,5077
XS Rating Curve= 0 ,0
Exp/Cntr=0.3,0.1

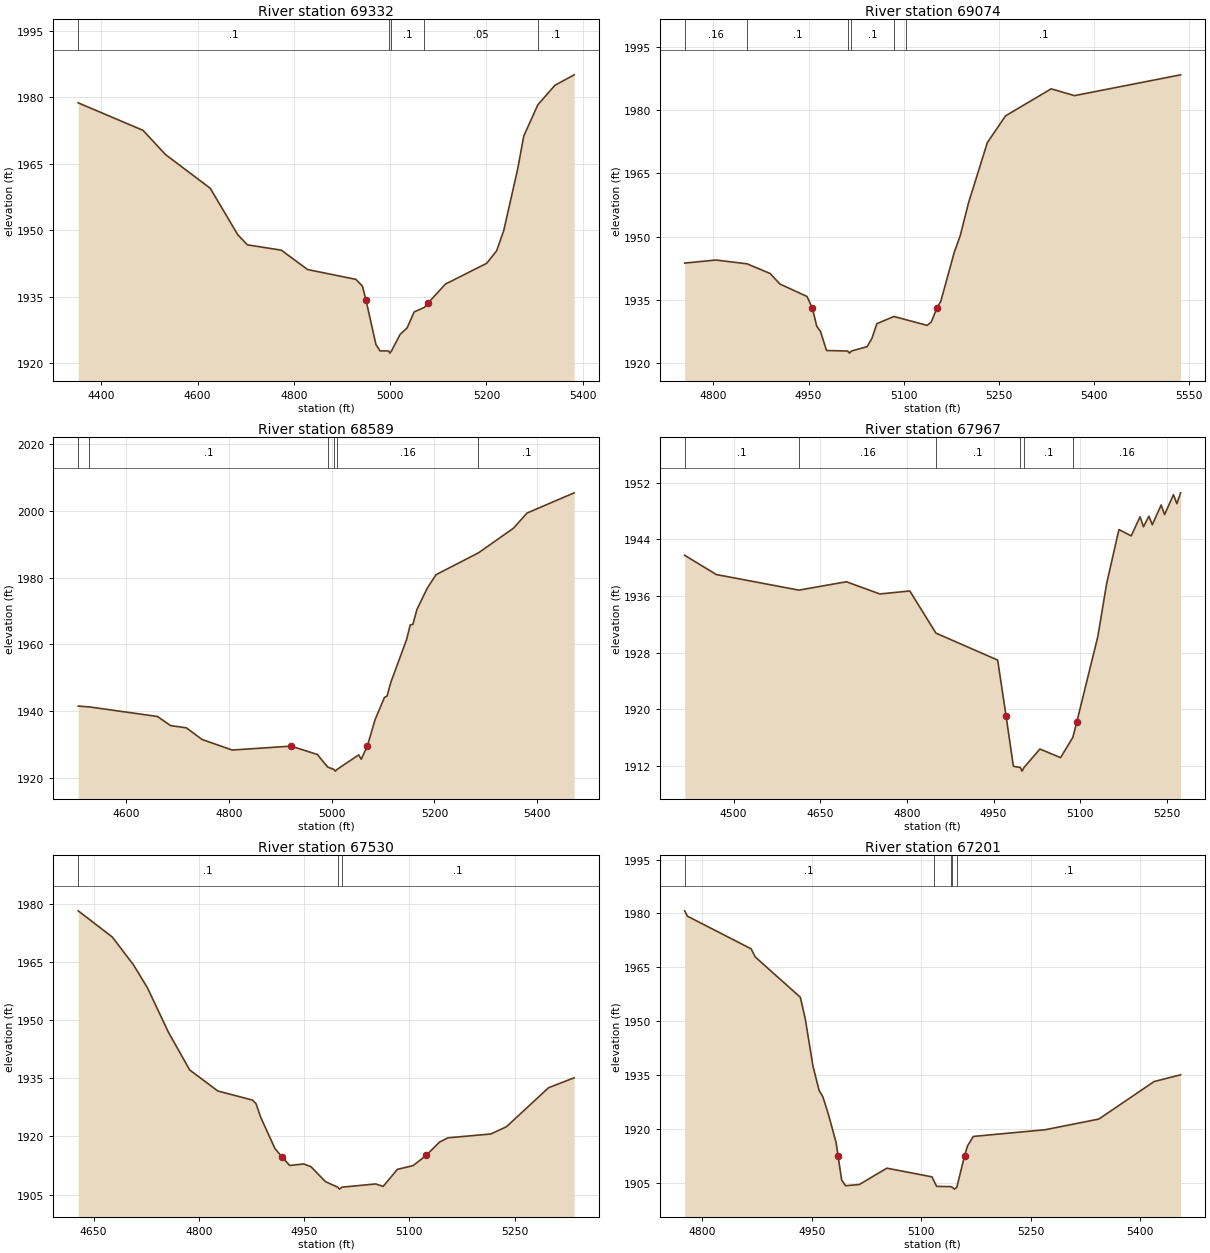
Type RM Length L Ch R = 1 ,69332   ,258,258,258
BEGIN DESCRIPTION:
LIVE OAK CREEK 133.0
END DESCRIPTION:
XS GIS Cut Line= 3
      2715693.87     10090194.45      2715724.25     10089773.45
      2715233.83     10089413.22
#Sta/Elev= 30
  4351.8 1978.75  4486.5 1972.54    4533 1967.09  4626.1 1959.46  4683.4 1948.96
  4703.4 1946.67  4773.9 1945.47  4828.5 1941.09  4928.8 1938.88  4942.4 1937.34
  4949.7 1934.26  4970.5 1924.16    4979 1922.71  4996.8 1922.71  4999.6 1922.21
  5002.8 1922.71  5020.7 1926.44  5035.3 1927.92    5050 1931.52    5071 1932.54
  5078.9 1933.53  5114.8  1937.8  5200.5  1942.5  5221.3 1945.32    5236 1949.87
    5265 1963.78  5277.7 1971.26    5307 1978.32  5342.5 1982.72  5382.4 1985.08
#Mann= 5 ,-1 , 0
  4351.8      .1       0  4996.8     .07       0  5002.8      .1       0
    5071     .05       0    5307      .1       0
Bank Sta=4949.7,5078.9
XS Rating Curve= 0 ,0
Exp/Cntr=0.3,0.1

Type RM Length L Ch R = 1 ,69074   ,485,485,485
BEGIN DESCRIPTION:
LIVE OAK CREEK 132.0
END DESCRIPTION:
XS GIS Cut Line= 2
      2715880.49     10089547.74      2715212.75     10089140.16
#Sta/Elev= 30
  4754.6 1943.75  4803.8 1944.48    4853 1943.58  4889.4 1941.29  4904.8 1938.79
  4947.5 1935.85  4956.1 1933.04  4962.9  1928.8  4968.8 1927.55  4978.4 1923.03
  5011.7 1922.91  5014.5 1922.41  5017.7 1922.91  5042.3 1923.94  5049.9 1925.89
  5057.8  1929.4  5084.8  1931.1  5104.4  1930.3  5137.2 1928.99  5143.6 1929.81
  5152.6 1933.15  5158.5 1934.66  5179.8 1946.28  5189.4 1950.33  5202.2 1957.97
    5232  1972.3  5260.7 1978.65  5332.7 1985.06  5369.5 1983.45  5536.9 1988.38
#Mann= 6 ,-1 , 0
  4754.6     .16       0    4853      .1       0  5011.7     .07       0
  5017.7      .1       0  5084.8     .05       0  5104.4      .1       0
Bank Sta=4956.1,5152.6
XS Rating Curve= 0 ,0
Exp/Cntr=0.3,0.1

Type RM Length L Ch R = 1 ,68589   ,622,622,622
BEGIN DESCRIPTION:
LIVE OAK CREEK 131.0
END DESCRIPTION:
XS GIS Cut Line= 2
      2715984.67     10089500.02      2715789.36     10088553.86
#Sta/Elev= 30
  4506.1  1941.5  4527.5 1941.27  4660.5 1938.39  4686.1 1935.66  4716.7    1935
  4747.4  1931.5  4806.2 1928.34    4921 1929.51    4972    1927  4991.9 1923.27
  5004.2 1922.52    5007 1922.02  5010.2 1922.52  5052.4 1926.88  5057.5 1925.58
 5069.55 1929.64  5084.3  1937.4  5102.6 1944.09  5107.7 1944.49    5115 1948.59
  5145.6 1961.36  5152.9 1965.84    5158 1965.99    5166 1970.48  5186.4 1976.94
  5203.2 1980.88  5285.8 1987.42  5353.9 1994.79  5380.4 1999.34  5472.2  2005.4
#Mann= 6 ,-1 , 0
  4506.1     .16       0  4527.5      .1       0  4991.9     .16       0
  5004.2     .07       0  5010.2     .16       0  5285.8      .1       0
Bank Sta=4921,5069.55
XS Rating Curve= 0 ,0
Exp/Cntr=0.3,0.1

Type RM Length L Ch R = 1 ,67967   ,437,437,437
BEGIN DESCRIPTION:
LIVE OAK CREEK 130.0
END DESCRIPTION:
XS GIS Cut Line= 2
      2715984.65     10089825.56      2716439.65     10089097.56
#Sta/Elev= 30
  4415.2 1941.73    4470 1939.01  4612.9 1936.81  4695.2 1937.99    4753 1936.27
  4804.9 1936.69  4850.1 1930.74    4957 1926.93  4971.6 1919.01  4984.2 1911.94
  4996.5 1911.75  4999.2 1911.25  5002.5 1911.75  5030.1 1914.37  5065.9 1913.16
  5087.1 1916.01  5093.8 1918.13  5130.4 1930.26  5145.7 1937.76  5166.9 1945.36
  5188.2 1944.47  5203.5 1947.17  5209.4 1945.76  5218.8 1947.25  5224.7 1946.05
    5240 1948.83  5245.9 1947.48  5261.3 1950.28  5267.2 1949.02  5273.7 1950.55
#Mann= 6 ,-1 , 0
  4415.2      .1       0  4612.9     .16       0  4850.1      .1       0
  4996.5     .07       0  5002.5      .1       0  5087.1     .16       0
Bank Sta=4971.6,5093.8
XS Rating Curve= 0 ,0
Exp/Cntr=0.3,0.1

Type RM Length L Ch R = 1 ,67530   ,329,329,329
BEGIN DESCRIPTION:
LIVE OAK CREEK 129.0
END DESCRIPTION:
XS GIS Cut Line= 3
      2716574.95     10090012.16      2716557.58     10089786.47
      2716665.98     10089318.21
#Sta/Elev= 30
    4628 1978.12  4676.6 1971.37  4706.7 1964.23  4726.7 1958.29  4756.8 1946.78
  4786.9 1937.13    4827 1931.71  4876.5 1929.37  4881.6  1928.4    4888    1925
  4908.5 1916.87  4918.8 1914.67  4929.5 1912.52  4949.5 1912.92  4959.8 1912.21
  4980.3 1908.38  4997.9 1906.93  5000.6 1906.43  5003.9 1906.93  5052.2 1907.77
  5062.7 1907.12    5083 1911.52  5105.4 1912.49    5124 1915.11    5143 1918.53
  5154.8 1919.64  5216.4 1920.64  5238.6 1922.52  5298.5 1932.55    5335 1935.11
#Mann= 3 ,-1 , 0
    4628      .1       0  4997.9     .07       0  5003.9      .1       0
Bank Sta=4918.8,5124
XS Rating Curve= 0 ,0
Exp/Cntr=0.3,0.1

Type RM Length L Ch R = 1 ,67201   ,433,433,433
BEGIN DESCRIPTION:
LIVE OAK CREEK 128.0
END DESCRIPTION:
XS GIS Cut Line= 2
      2716965.58     10089929.73      2716740.11     10089287.99
#Sta/Elev= 30
  4775.6 1980.73  4779.3 1979.25  4866.8 1970.15  4872.3 1967.91  4934.2  1956.7
  4940.9  1950.8  4951.5  1937.6  4959.9 1930.82  4965.2 1928.97  4972.7 1924.14
  4983.3 1916.28 4985.91 1912.64  4990.9 1905.87  4996.2 1904.27  5015.1  1904.6
  5052.9 1909.15  5114.8 1906.73  5116.9 1905.85  5121.1 1904.09  5140.9 1904.01
  5142.8 1903.82  5145.6 1903.32  5148.8 1903.82 5159.55 1912.64  5163.5 1915.33
  5171.5 1917.98  5269.7 1919.83  5343.7 1922.81  5419.4 1933.24  5455.8 1935.12
#Mann= 5 ,-1 , 0
  4775.6      .1       0  5116.9     .16       0  5140.9      .1       0
  5142.8     .07       0  5148.8      .1       0
Bank Sta=4985.91,5159.55
XS Rating Curve= 0 ,0
Exp/Cntr=0.3,0.1