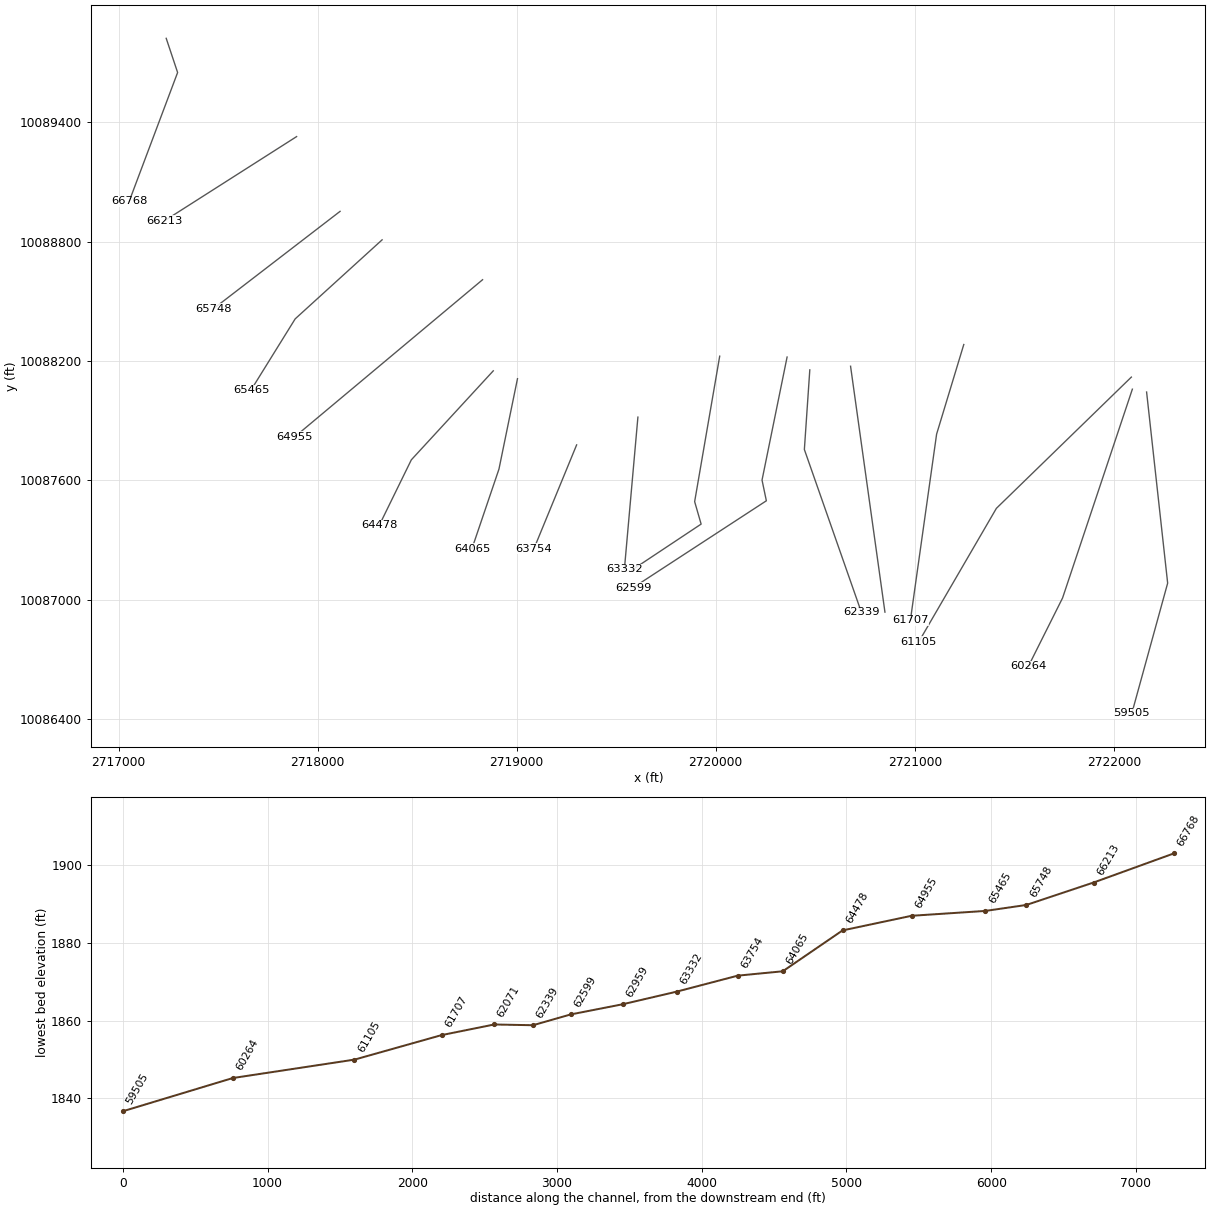
HEC-RAS study LIVE OAK CREEK.prj: LIVE OAK CREEK Base Level Engineering

--- LIVE OAK CREEK.g01 (geometry) --- (continued)

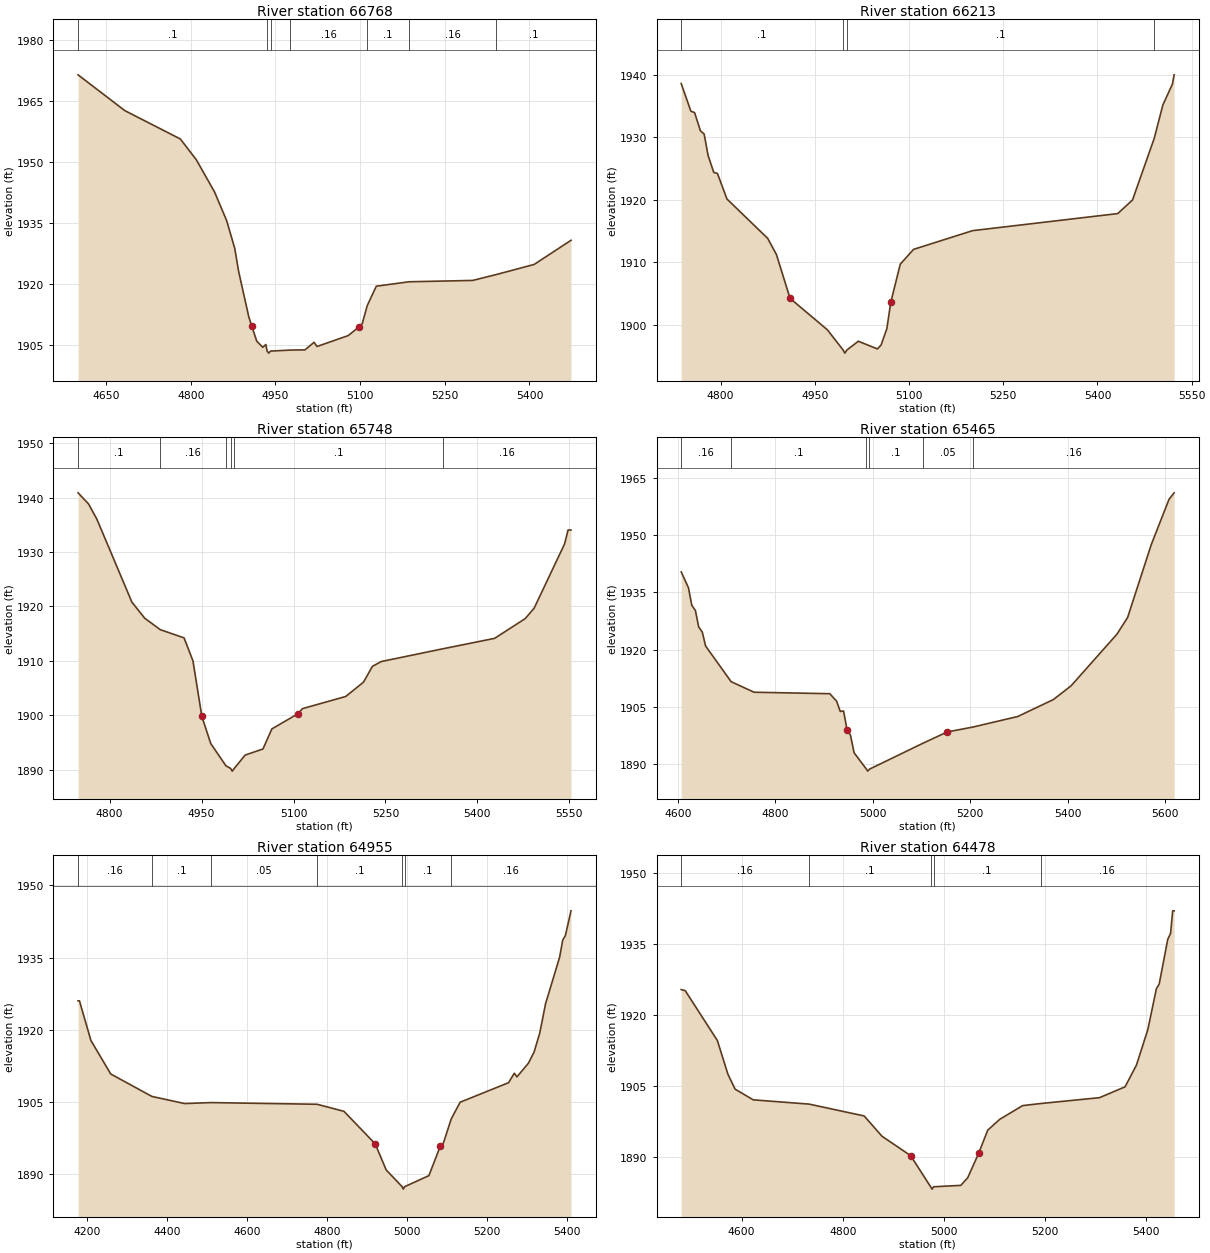
Type RM Length L Ch R = 1 ,66768   ,555,555,555
BEGIN DESCRIPTION:
LIVE OAK CREEK 127.0
END DESCRIPTION:
XS GIS Cut Line= 3
      2717239.47     10089822.26      2717296.76      10089650.4
      2717053.41     10089002.66
#Sta/Elev= 30
  4600.4 1971.49  4683.2 1962.68  4781.6 1955.69    4810 1950.55  4842.1 1942.66
  4863.5 1935.63  4877.9 1928.78  4884.8  1923.1  4902.8  1911.9  4908.1  1909.6
  4916.9 1905.91  4927.6  1904.4    4933 1905.08  4935.3 1903.46  4938.1 1902.96
  4941.3 1903.46  4976.4 1903.71  5002.3 1903.76  5018.4 1905.62  5023.7  1904.6
  5078.9 1907.28  5098.4 1909.46  5103.8 1910.22  5112.6 1914.66  5128.7 1919.44
  5186.7 1920.53  5299.4 1920.86  5340.9  1922.3  5408.3  1924.8  5473.5 1930.74
#Mann= 7 ,-1 , 0
  4600.4      .1       0  4935.3     .07       0  4941.3      .1       0
  4976.4     .16       0  5112.6      .1       0  5186.7     .16       0
  5340.9      .1       0
Bank Sta=4908.1,5098.4
XS Rating Curve= 0 ,0
Exp/Cntr=0.3,0.1

Type RM Length L Ch R = 1 ,66213   ,465,465,465
BEGIN DESCRIPTION:
LIVE OAK CREEK 126.0
END DESCRIPTION:
XS GIS Cut Line= 2
      2717894.53     10089328.22      2717232.87     10088906.19
#Sta/Elev= 30
  4737.3 1938.56  4752.7 1934.14  4758.6 1933.91  4767.9 1931.01  4773.8 1930.49
  4780.1 1927.07  4789.1 1924.36    4795 1924.19  4810.2  1920.1    4875 1913.82
  4888.9 1911.24  4910.6 1904.23  4969.9 1899.22  4995.1 1895.98  4997.8 1895.48
  5001.1 1895.98  5019.3 1897.38  5049.7 1896.15  5055.6 1896.79  5064.7 1899.39
  5070.9 1903.57  5086.1  1909.7  5107.3 1912.06  5201.2 1915.05  5432.4 1917.78
  5455.9 1919.96  5490.4  1929.8  5504.2 1935.14  5519.4 1938.48  5522.1 1939.95
#Mann= 4 ,-1 , 0
  4737.3      .1       0  4995.1     .07       0  5001.1      .1       0
  5490.4     .16       0
Bank Sta=4910.6,5070.9
XS Rating Curve= 0 ,0
Exp/Cntr=0.3,0.1

Type RM Length L Ch R = 1 ,65748   ,283,283,283
BEGIN DESCRIPTION:
LIVE OAK CREEK 125.0
END DESCRIPTION:
XS GIS Cut Line= 2
       2718112.9     10088952.36      2717475.76     10088461.98
#Sta/Elev= 30
  4748.6  1940.9  4765.7 1938.86  4779.4 1936.03  4836.4  1920.8  4857.2 1917.85
  4882.7 1915.73  4921.5 1914.22    4936    1910  4950.5 1899.78    4965 1894.79
  4989.8 1890.69  4997.4 1890.21  5000.1 1889.71  5003.4 1890.21  5021.2 1892.67
  5050.2 1893.78  5064.7 1897.47  5107.5 1900.28  5114.5  1901.2  5185.2 1903.44
  5214.2 1906.08  5228.7 1908.98  5243.2 1909.87    5344 1912.22    5428 1914.13
  5477.9 1917.76  5492.4 1919.66  5542.2 1931.51  5547.8 1934.06  5552.6 1934.06
#Mann= 6 ,-1 , 0
  4748.6      .1       0  4882.7     .16       0  4989.8      .1       0
  4997.4     .07       0  5003.4      .1       0    5344     .16       0
Bank Sta=4950.5,5107.5
XS Rating Curve= 0 ,0
Exp/Cntr=0.3,0.1

Type RM Length L Ch R = 1 ,65465   ,510,510,510
BEGIN DESCRIPTION:
LIVE OAK CREEK 124.0
END DESCRIPTION:
XS GIS Cut Line= 3
      2718324.08     10088809.17      2717887.39     10088411.85
      2717665.44     10088053.86
#Sta/Elev= 30
  4606.6 1940.37  4621.5 1936.21  4628.3 1931.64  4635.7 1930.26  4642.5 1925.95
  4649.9 1924.59  4656.7 1920.95    4709 1911.62    4756 1908.85  4911.6 1908.46
  4925.6 1906.49    4933 1903.82  4939.8 1903.93  4947.2 1898.84    4954  1897.6
  4961.4 1892.99  4986.8 1888.68  4989.5 1888.18  4992.8 1888.68  5102.1 1895.45
  5152.6 1898.44  5205.4 1899.73  5297.1 1902.48  5370.3 1906.92  5406.6 1910.51
  5500.7 1924.03  5522.7 1928.41  5571.3 1947.53  5607.7 1959.37  5618.2 1961.08
#Mann= 6 ,-1 , 0
  4606.6     .16       0    4709      .1       0  4986.8     .07       0
  4992.8      .1       0  5102.1     .05       0  5205.4     .16       0
Bank Sta=4947.2,5152.6
XS Rating Curve= 0 ,0
Exp/Cntr=0.3,0.1

Type RM Length L Ch R = 1 ,64955   ,477,477,477
BEGIN DESCRIPTION:
LIVE OAK CREEK 123.0
END DESCRIPTION:
XS GIS Cut Line= 2
      2718828.82     10088608.72      2717884.44     10087818.16
#Sta/Elev= 30
  4177.6 1926.01  4181.1 1926.01  4209.7 1917.78  4259.2 1910.83    4362 1906.17
  4443.9 1904.69  4509.7 1904.89    4775 1904.54  4842.1 1903.07  4920.1 1896.32
  4947.5 1890.91  4987.4 1887.43  4990.2 1886.93  4993.4 1887.43  5054.2 1889.73
  5082.8 1895.88  5090.6 1896.54  5110.1 1901.52  5132.3 1904.97  5253.3 1909.02
  5267.6 1910.99  5274.1 1910.22  5302.7 1913.05    5317 1915.37  5331.3 1919.37
  5345.6 1925.38  5380.8 1935.06  5388.6 1938.63  5395.1 1939.53  5409.2 1944.69
#Mann= 7 ,-1 , 0
  4177.6     .16       0    4362      .1       0  4509.7     .05       0
    4775      .1       0  4987.4     .07       0  4993.4      .1       0
  5110.1     .16       0
Bank Sta=4920.1,5082.8
XS Rating Curve= 0 ,0
Exp/Cntr=0.3,0.1

Type RM Length L Ch R = 1 ,64478   ,413,413,413
BEGIN DESCRIPTION:
LIVE OAK CREEK 122.0
END DESCRIPTION:
XS GIS Cut Line= 3
      2718882.55     10088150.57      2718470.87     10087703.09
      2718309.77     10087373.72
#Sta/Elev= 30
  4480.5  1925.3  4488.5 1925.07    4552 1914.55  4572.9 1907.42  4587.1 1904.28
  4622.9 1902.02  4733.5 1901.12  4842.3 1898.62  4877.5 1894.34  4934.2 1890.24
  4973.7 1883.67  4976.5 1883.17  4979.7 1883.67  5033.3 1883.96    5047 1885.57
  5068.6 1890.71  5086.6 1895.62  5110.5 1897.92  5155.5  1900.8  5191.1 1901.24
  5307.6 1902.48  5358.2 1904.77  5380.7 1909.36  5403.2 1916.86  5420.1 1925.47
  5425.7 1926.48  5442.6 1935.92  5448.2 1937.17  5452.4 1941.93  5455.2 1941.93
#Mann= 5 ,-1 , 0
  4480.5     .16       0  4733.5      .1       0  4973.7     .07       0
  4979.7      .1       0  5191.1     .16       0
Bank Sta=4934.2,5068.6
XS Rating Curve= 0 ,0
Exp/Cntr=0.3,0.1

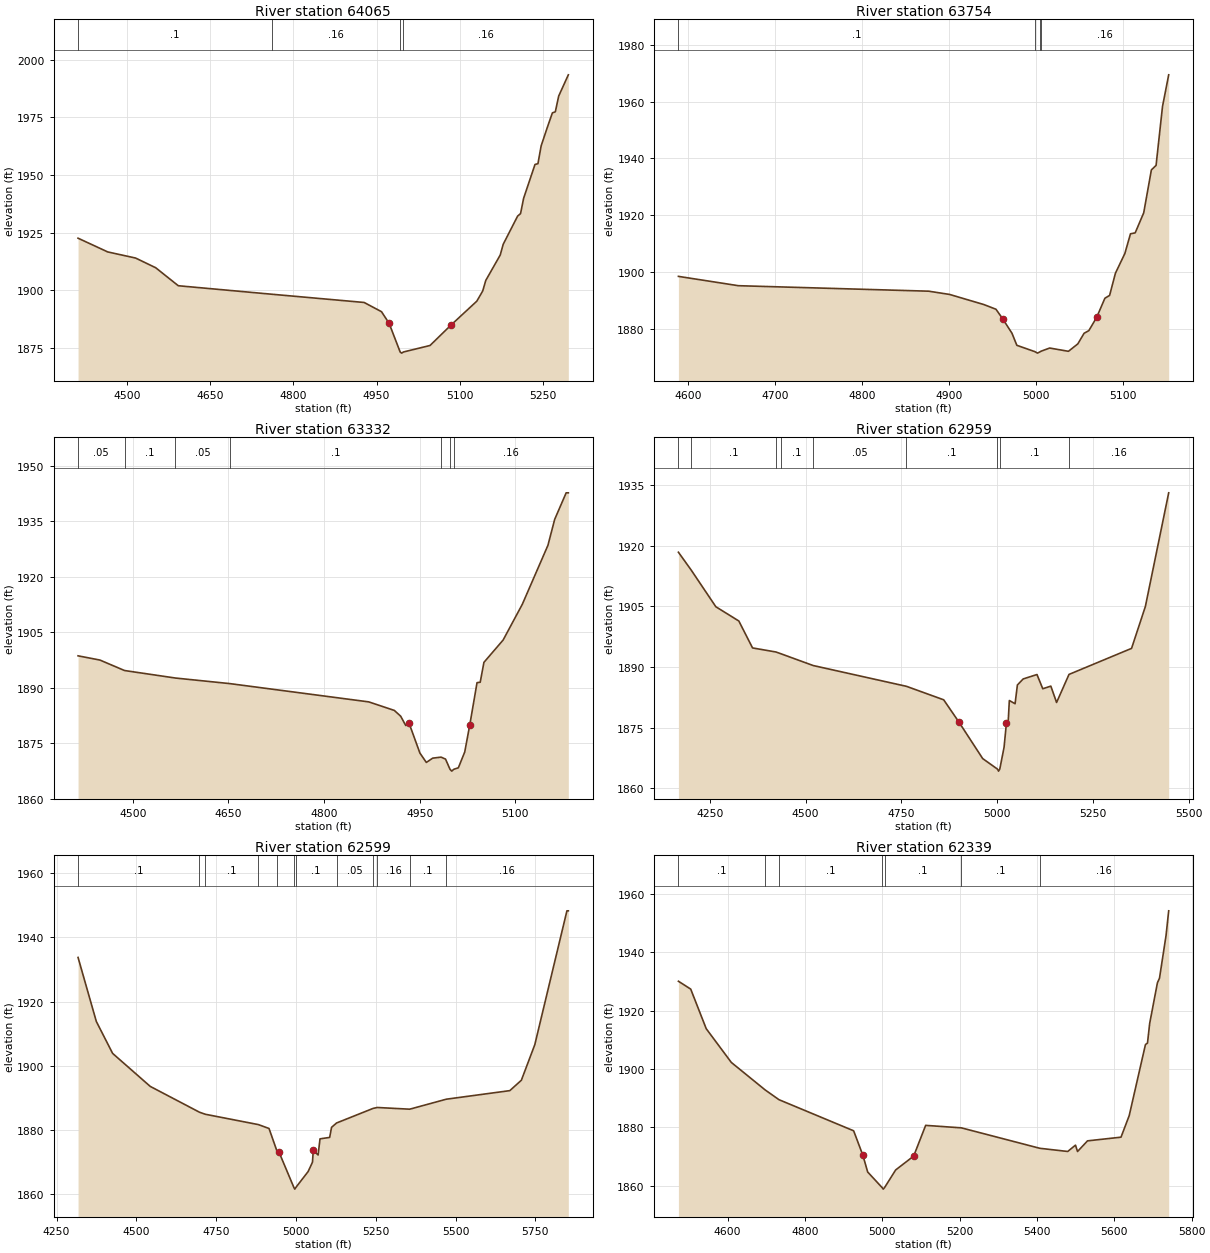
Type RM Length L Ch R = 1 ,64065   ,311,311,311
BEGIN DESCRIPTION:
LIVE OAK CREEK 121.0
END DESCRIPTION:
XS GIS Cut Line= 3
      2719004.22     10088111.13      2718911.16     10087656.55
      2718775.67     10087257.21
#Sta/Elev= 30
  4410.8 1922.54  4464.4 1916.58  4514.8 1913.92    4551 1909.73  4591.9 1901.91
  4760.5 1898.23  4927.6 1894.65    4959 1890.65  4972.8 1885.57  4992.7 1873.17
  4995.4 1872.67  4998.7 1873.17  5046.7 1875.99  5084.6 1884.86  5131.2 1895.22
  5141.8 1899.62  5147.4 1904.23  5173.5 1915.25  5178.8 1919.87  5204.9 1932.13
  5210.2 1933.21  5215.7 1939.83  5236.3 1954.53  5241.6 1954.87  5247.4  1962.6
  5257.9 1970.15  5267.7 1976.92    5273 1977.37  5279.1 1984.21  5296.5 1993.42
#Mann= 4 ,-1 , 0
  4410.8      .1       0  4760.5     .16       0  4992.7     .07       0
  4998.7     .16       0
Bank Sta=4972.8,5084.6
XS Rating Curve= 0 ,0
Exp/Cntr=0.3,0.1

Type RM Length L Ch R = 1 ,63754   ,422,422,422
BEGIN DESCRIPTION:
LIVE OAK CREEK 120.0
END DESCRIPTION:
XS GIS Cut Line= 2
      2719301.34     10087778.27      2719087.19     10087257.16
#Sta/Elev= 30
  4588.7 1898.54  4657.6 1895.26  4876.3 1893.33  4900.3 1892.19  4939.6 1888.64
  4953.6 1886.98  4961.2 1883.69    4972 1878.55  4977.6  1874.3  4998.5 1872.05
  5001.3 1871.55  5004.5 1872.05  5005.6 1872.24  5015.3 1873.34  5036.9 1872.19
  5047.7 1874.81  5054.9 1878.54  5060.3 1879.45  5069.3  1884.1  5078.8 1890.86
  5084.2 1891.84  5090.9 1899.66  5101.7 1906.56  5108.2 1913.51  5113.6 1913.84
  5123.4 1920.89  5132.2 1935.97  5137.6 1937.57    5145 1958.29  5152.1 1969.41
#Mann= 4 ,-1 , 0
  4588.7      .1       0  4998.5     .07       0  5004.5      .1       0
  5005.6     .16       0
Bank Sta=4961.2,5069.3
XS Rating Curve= 0 ,0
Exp/Cntr=0.3,0.1

Type RM Length L Ch R = 1 ,63332   ,373,373,373
BEGIN DESCRIPTION:
LIVE OAK CREEK 119.0
END DESCRIPTION:
XS GIS Cut Line= 2
      2719609.18     10087917.85      2719541.18     10087151.86
#Sta/Elev= 30
  4414.1 1898.59  4448.4 1897.45    4487 1894.62  4566.9 1892.59  4651.9 1891.09
    4870 1886.15  4910.2 1883.84  4920.2 1882.27  4928.1 1879.76  4933.2 1880.44
  4950.3 1872.32  4960.4 1869.79  4970.4 1870.95  4983.5 1871.22  4990.5 1870.69
  4997.5 1867.94  5000.3 1867.44  5003.5 1867.94  5010.6 1868.34  5020.6  1872.6
 5028.64 1880.03  5039.9 1891.34  5044.9 1891.46  5050.7 1896.82  5080.8 1902.85
  5110.9 1912.51  5151.1 1928.44  5161.7 1935.46  5179.7 1942.63  5183.1 1942.63
#Mann= 7 ,-1 , 0
  4414.1     .05       0    4487      .1       0  4566.9     .05       0
  4651.9      .1       0  4983.5     .16       0  4997.5     .07       0
  5003.5     .16       0
Bank Sta=4933.2,5028.64
XS Rating Curve= 0 ,0
Exp/Cntr=0.3,0.1

Type RM Length L Ch R = 1 ,62959   ,360,360,360
BEGIN DESCRIPTION:
Mapping XS 19b7efd8
END DESCRIPTION:
XS GIS Cut Line= 4
      2720020.12     10088224.28      2719894.24      10087492.9
       2719926.8     10087380.06      2719578.06     10087148.29
#Sta/Elev= 30
  4168.6 1918.41  4202.3 1913.94  4266.2 1904.91  4326.1 1901.38  4361.9 1894.71
  4423.1  1893.7    4436 1893.26    4520 1890.35  4763.2  1885.2  4860.3 1881.86
  4899.7 1876.39  4961.9 1867.31  5000.5  1864.7  5003.3  1864.2  5006.5  1864.7
  5017.7 1870.12  5023.7 1876.01  5028.2 1876.01  5031.4 1881.69  5046.4 1880.89
  5052.4 1885.53  5067.5 1887.03  5103.5 1888.12  5118.6  1884.6  5139.6 1885.25
  5154.6  1881.2    5187 1888.15  5350.1  1894.6  5386.1 1904.97  5446.9 1933.12
#Mann= 9 ,-1 , 0
  4168.6     .05       0  4202.3      .1       0  4423.1     .05       0
    4436      .1       0    4520     .05       0  4763.2      .1       0
  5000.5     .07       0  5006.5      .1       0    5187     .16       0
Bank Sta=4899.7,5023.7
XS Rating Curve= 0 ,0
Exp/Cntr=0.3,0.1

Type RM Length L Ch R = 1 ,62599   ,260,260,260
BEGIN DESCRIPTION:
LIVE OAK CREEK 118.0
END DESCRIPTION:
XS GIS Cut Line= 4
      2720358.65     10088219.89      2720232.79     10087601.41
      2720254.49     10087497.24      2719586.08     10087061.04
#Sta/Elev= 30
  4317.4 1933.75  4374.7 1913.79  4425.7 1903.86  4543.5 1893.58  4697.7 1885.54
    4716  1884.9  4882.3 1881.68  4915.6 1880.47  4940.3 1873.47  4946.8 1873.12
  4993.5 1862.08  4996.3 1861.58  4999.5 1862.08  5038.1 1867.06  5051.7 1869.98
  5054.2 1873.69  5069.3 1872.21  5075.3 1877.24  5105.5 1877.69  5111.5 1880.83
  5127.1 1882.18  5241.6 1886.73  5254.5 1887.01  5356.2 1886.48  5470.8 1889.59
  5669.8 1892.26    5706  1895.5  5748.1 1906.58  5848.7 1948.27  5853.1 1948.27
#Mann= 12 ,-1 , 0
  4317.4      .1       0  4697.7     .16       0    4716      .1       0
  4882.3     .05       0  4940.3      .1       0  4993.5     .07       0
  4999.5      .1       0  5127.1     .05       0  5241.6      .1       0
  5254.5     .16       0  5356.2      .1       0  5470.8     .16       0
Bank Sta=4946.8,5054.2
XS Rating Curve= 0 ,0
Exp/Cntr=0.3,0.1

Type RM Length L Ch R = 1 ,62339   ,268,268,268
BEGIN DESCRIPTION:
LIVE OAK CREEK 117.0
END DESCRIPTION:
XS GIS Cut Line= 3
      2720472.76     10088155.45      2720445.46     10087755.06
      2720731.67     10086937.32
#Sta/Elev= 30
  4472.9 1930.09  4504.7 1927.39  4544.8 1913.82  4609.7 1902.25  4697.4  1892.8
    4733 1889.47    4926 1878.81  4949.8 1870.43  4962.3 1864.68  4999.8 1859.31
  5002.5 1858.81  5005.8 1859.31  5034.6 1865.38  5081.2 1870.14  5112.2 1880.67
  5204.5 1879.82  5407.4 1872.81  5479.5 1871.72  5499.6 1873.89  5504.9 1871.71
  5530.7 1875.36  5617.3 1876.62  5638.5 1884.01  5680.5 1908.37  5685.8  1908.9
  5691.4 1915.59  5711.5 1929.59  5716.8  1931.1  5733.8 1945.82  5740.6 1954.23
#Mann= 7 ,-1 , 0
  4472.9      .1       0  4697.4     .05       0    4733      .1       0
  4999.8     .07       0  5005.8      .1       0  5204.5      .1       0
  5407.4     .16       0
Bank Sta=4949.8,5081.2
XS Rating Curve= 0 ,0
Exp/Cntr=0.3,0.1

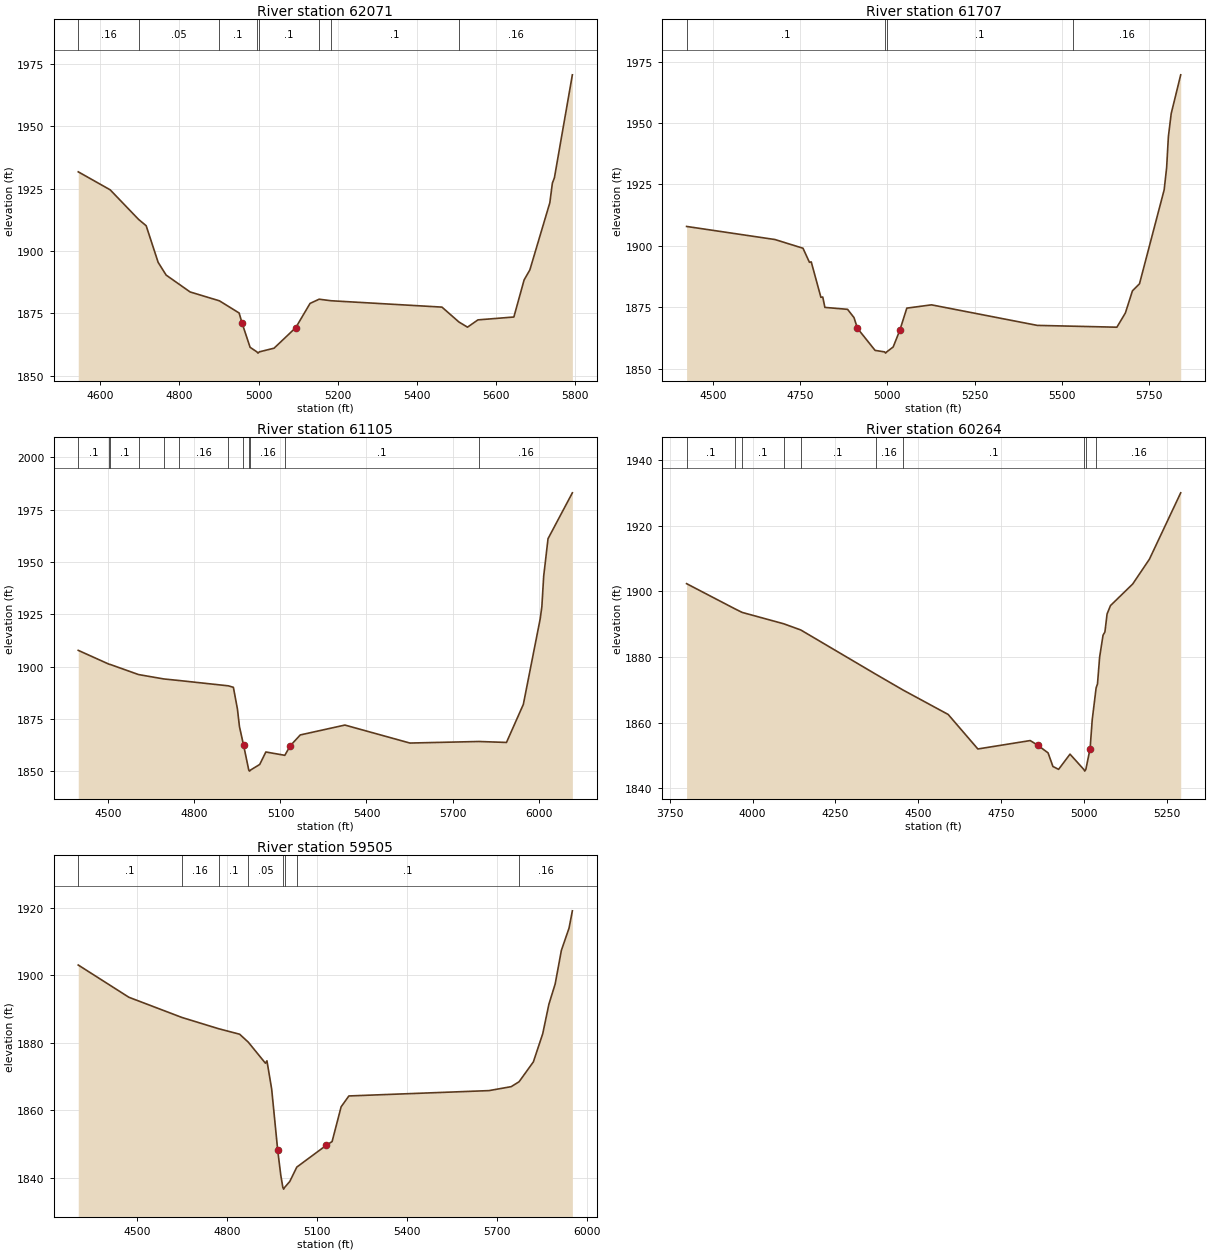
Type RM Length L Ch R = 1 ,62071   ,364,364,364
BEGIN DESCRIPTION:
LIVE OAK CREEK 116.0
END DESCRIPTION:
XS GIS Cut Line= 2
      2720677.54     10088173.68      2720850.26     10086937.38
#Sta/Elev= 30
  4544.6 1931.69  4625.3 1924.47  4696.9 1912.63  4716.2 1910.08  4746.5 1895.38
  4766.7 1890.28  4827.3 1883.52  4901.3 1879.97  4951.1 1875.08  4958.5 1871.02
  4978.7 1861.34  4995.9  1859.5  4998.7    1859  5001.9  1859.5  5039.3 1860.98
  5094.1 1869.22  5130.2 1878.93  5153.2 1880.62  5183.4    1880  5463.4 1877.45
  5506.5 1871.46    5528 1869.41  5554.3 1872.33  5645.1 1873.48    5671 1888.36
  5685.5 1892.37    5736 1919.32  5742.4 1927.18  5747.5 1929.27  5792.9 1970.58
#Mann= 8 ,-1 , 0
  4544.6     .16       0  4696.9     .05       0  4901.3      .1       0
  4995.9     .07       0  5001.9      .1       0  5153.2     .16       0
  5183.4      .1       0  5506.5     .16       0
Bank Sta=4958.5,5094.1
XS Rating Curve= 0 ,0
Exp/Cntr=0.3,0.1

Type RM Length L Ch R = 1 ,61707   ,602,602,602
BEGIN DESCRIPTION:
LIVE OAK CREEK 115.0
END DESCRIPTION:
XS GIS Cut Line= 3
      2721246.33     10088282.88      2721109.83     10087832.42
      2720978.12     10086896.83
#Sta/Elev= 30
  4424.9 1907.88  4678.1 1902.55  4758.4    1899  4776.8 1893.28    4782 1893.44
  4809.7 1879.01    4815 1879.13  4821.1  1874.9    4886 1874.11  4904.4 1870.77
  4914.5 1866.36  4964.9 1857.39  4992.2 1856.77    4995 1856.27  4998.2 1856.77
  5016.7 1858.77  5035.6 1865.53  5055.8  1874.6  5126.5 1875.94  5429.5 1867.57
    5532 1867.24  5657.6 1866.83    5682 1872.66  5702.1 1881.64  5722.3 1884.51
    5793 1922.79  5800.1 1931.87  5805.1  1944.5  5813.2 1953.88  5840.4 1969.65
#Mann= 4 ,-1 , 0
  4424.9      .1       0  4992.2     .07       0  4998.2      .1       0
    5532     .16       0
Bank Sta=4914.5,5035.6
XS Rating Curve= 0 ,0
Exp/Cntr=0.3,0.1

Type RM Length L Ch R = 1 ,61105   ,841,841,841
BEGIN DESCRIPTION:
LIVE OAK CREEK 114.0
END DESCRIPTION:
XS GIS Cut Line= 3
      2722088.17     10088119.09      2721410.16     10087459.28
      2721019.67     10086787.27
#Sta/Elev= 30
  4394.7 1907.73  4502.7 1901.07  4505.9    1901    4605 1896.15  4693.3 1894.05
  4747.8 1893.29  4918.4 1890.76  4935.8 1890.04  4949.9 1879.66  4956.9 1871.31
  4969.3 1863.58  4971.1 1862.55  4989.4 1850.47  4992.1 1849.97  4995.4 1850.47
  5027.6 1853.16    5049 1859.13  5115.2 1857.53  5133.8 1862.05  5169.1 1867.28
  5324.7    1872  5551.4  1863.4  5792.2 1864.14  5888.2 1863.69    5947 1881.89
  6005.8 1922.79  6011.6 1928.69    6018 1943.21  6033.1 1961.13    6118 1983.07
#Mann= 12 ,-1 , 0
  4394.7      .1       0  4502.7     .16       0  4505.9      .1       0
    4605     .16       0  4693.3      .1       0  4747.8     .16       0
  4918.4      .1       0  4969.3     .16       0  4989.4     .07       0
  4995.4     .16       0  5115.2      .1       0  5792.2     .16       0
Bank Sta=4971.1,5133.8
XS Rating Curve= 0 ,0
Exp/Cntr=0.3,0.1

Type RM Length L Ch R = 1 ,60264   ,759,759,759
BEGIN DESCRIPTION:
LIVE OAK CREEK 113.0
END DESCRIPTION:
XS GIS Cut Line= 3
      2722093.24     10088058.39      2721742.63     10087008.64
      2721570.79     10086664.96
#Sta/Elev= 30
    3801 1902.35  3945.9 1894.73  3968.7 1893.59    4094 1890.13  4145.6 1888.24
  4371.6 1874.78  4453.9 1869.96  4590.4  1862.5  4679.9 1851.99  4837.9 1854.55
  4860.2 1853.16  4891.8  1850.8  4906.4 1846.66  4923.5 1845.78    4958 1850.41
  4999.7 1845.74  5002.4 1845.24  5005.7 1845.74  5018.6  1852.1    5025 1860.88
  5036.8 1870.62  5040.9 1871.79  5047.4 1880.03  5057.7 1886.67  5063.3 1887.63
  5069.8 1893.11  5080.1 1895.67  5147.1 1902.24  5197.5 1909.79    5292 1930.02
#Mann= 10 ,-1 , 0
    3801      .1       0  3945.9     .16       0  3968.7      .1       0
    4094     .16       0  4145.6      .1       0  4371.6     .16       0
  4453.9      .1       0  4999.7     .07       0  5005.7      .1       0
  5036.8     .16       0
Bank Sta=4860.2,5018.6
XS Rating Curve= 0 ,0
Exp/Cntr=0.3,0.1

Type RM Length L Ch R = 1 ,59505   ,430,430,430
BEGIN DESCRIPTION:
LIVE OAK CREEK 112.0
END DESCRIPTION:
XS GIS Cut Line= 3
      2722164.74     10088044.11      2722270.56     10087083.16
      2722090.44     10086428.44
#Sta/Elev= 30
  4305.3    1903    4474 1893.46  4650.9 1887.48  4773.2 1884.15  4842.9 1882.53
  4871.7 1880.18  4928.8 1873.95  4933.8 1874.66  4949.5 1866.35  4969.7 1848.18
  4979.7 1840.96  4986.8 1837.21  4989.5 1836.71  4992.8 1837.21  5009.9 1838.98
  5033.3 1843.23  5130.6 1849.62  5150.8 1850.78  5180.9 1861.06  5206.7 1864.27
  5673.3 1865.85  5747.3 1867.02  5773.7 1868.48  5821.2 1874.35  5852.3 1882.65
    5873 1891.43  5893.8 1897.39  5914.5 1907.34  5940.1 1913.94  5951.1 1919.03
#Mann= 8 ,-1 , 0
  4305.3      .1       0  4650.9     .16       0  4773.2      .1       0
  4871.7     .05       0  4986.8    .035       0  4992.8     .05       0
  5033.3      .1       0  5773.7     .16       0
Bank Sta=4969.7,5130.6
XS Rating Curve= 0 ,0
Exp/Cntr=0.3,0.1