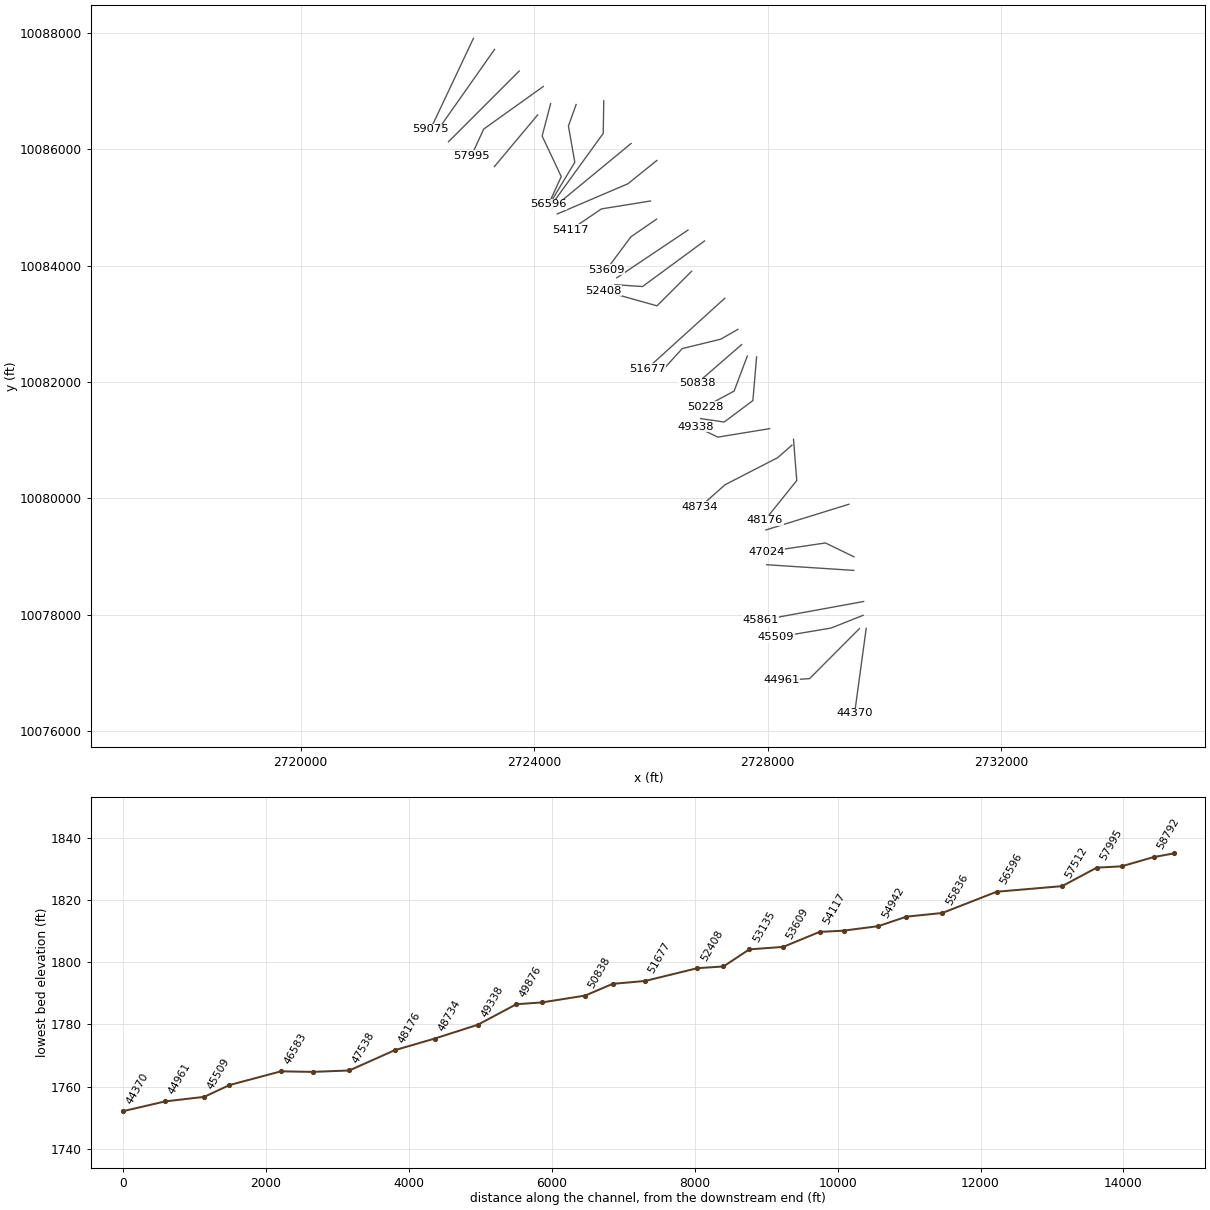
HEC-RAS study LIVE OAK CREEK.prj: LIVE OAK CREEK Base Level Engineering

--- LIVE OAK CREEK.g01 (geometry) --- (continued)

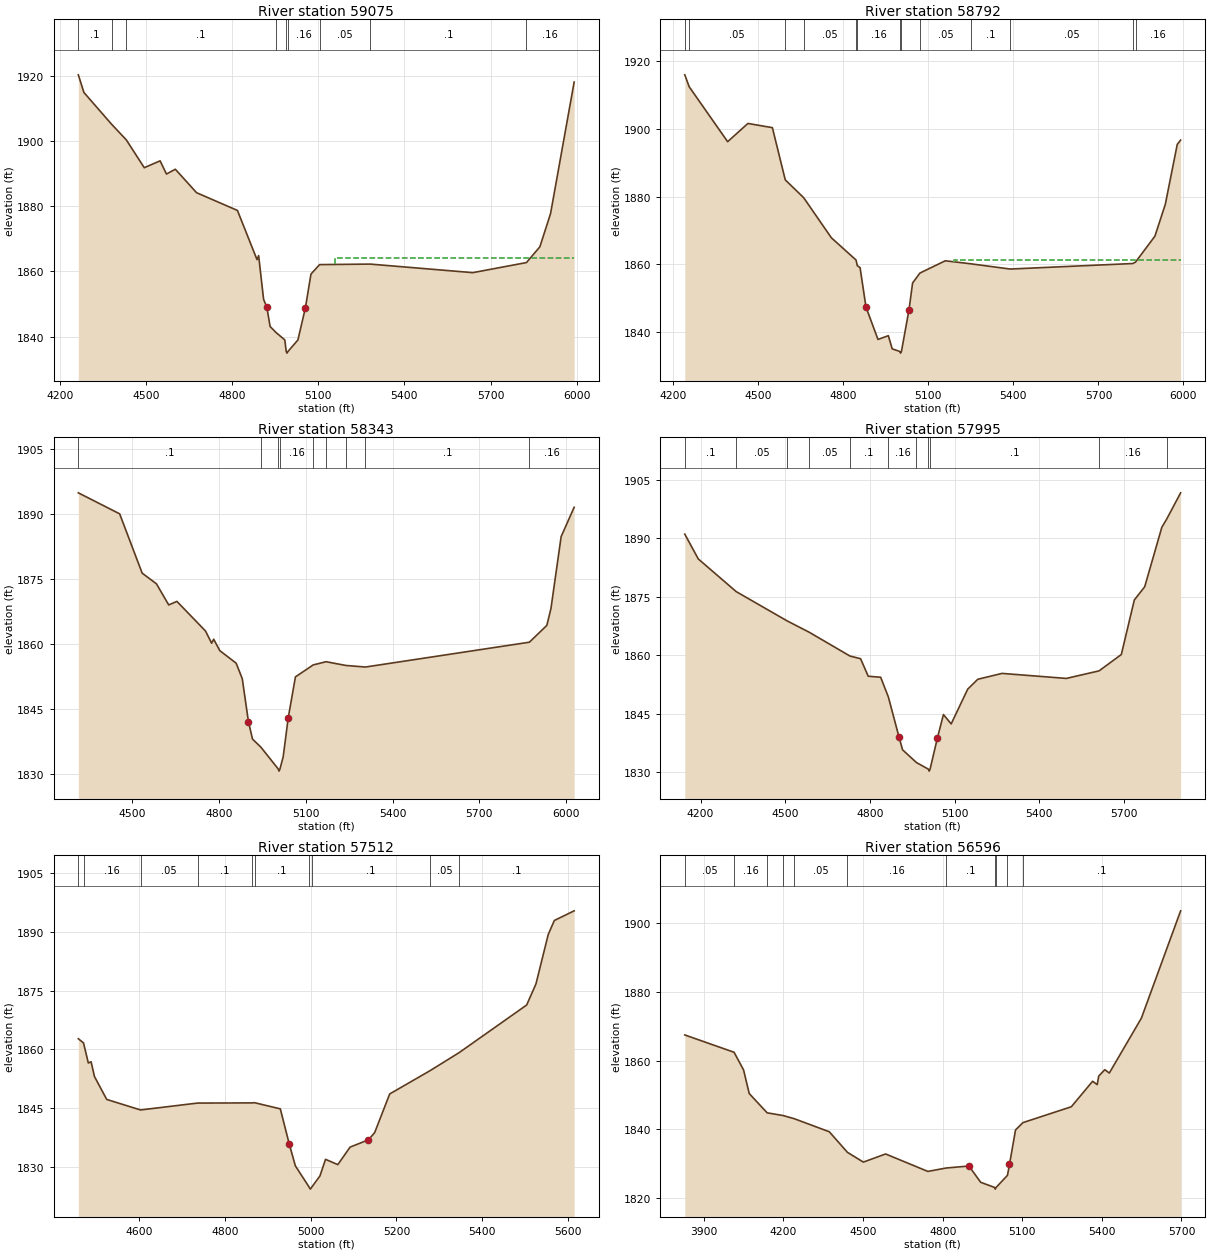
Type RM Length L Ch R = 1 ,59075   ,283,283,283
BEGIN DESCRIPTION:
LIVE OAK CREEK 111.0
END DESCRIPTION:
XS GIS Cut Line= 2
      2722958.76     10087901.41      2722223.18     10086339.34
#Sta/Elev= 30
  4264.6 1920.42  4284.1 1914.99  4380.2 1905.26  4431.6 1900.44  4494.2 1891.88
  4549.4 1893.99  4571.5 1889.93  4602.4 1891.41  4676.3  1884.2  4818.6 1878.75
  4886.9 1863.62  4892.5 1864.87  4909.7 1851.44 4921.02 1848.99  4932.5 1843.08
  4953.1 1841.23  4983.6 1838.96  4988.6  1835.4  4991.3  1834.9  4994.6  1835.4
  5029.2 1838.94    5055 1848.69  5074.8 1859.21  5104.7  1862.1  5280.8 1862.26
  5638.3 1859.63  5825.1 1862.73  5871.7 1867.55    5909 1877.76  5991.2 1918.19
#Mann= 9 ,-1 , 0
  4264.6      .1       0  4380.2     .05       0  4431.6      .1       0
  4953.1     .16       0  4988.6     .07       0  4994.6     .16       0
  5104.7     .05       0  5280.8      .1       0  5825.1     .16       0
#XS Ineff= 2 , 0
                         5157.27         1864.01
Permanent Ineff=
       T       T
Bank Sta=4921.02,5055
XS Rating Curve= 0 ,0
Exp/Cntr=0.3,0.1

Type RM Length L Ch R = 1 ,58792   ,449,449,449
BEGIN DESCRIPTION:
LIVE OAK CREEK 110.0
END DESCRIPTION:
XS GIS Cut Line= 2
      2723320.89     10087711.72      2722316.31     10086279.51
#Sta/Elev= 30
  4240.5 1916.04    4256 1912.51  4391.7 1896.26  4463.2 1901.66  4549.5 1900.41
    4595 1884.96  4659.9  1879.7  4757.8 1867.82  4844.7 1861.26  4849.1 1859.59
  4858.9 1859.01  4879.8 1847.34  4922.1 1837.77  4958.7 1838.88  4972.2 1834.99
  4998.9 1834.22  5001.6 1833.72  5004.9 1834.22  5031.5 1846.52  5044.2 1854.46
  5070.2 1857.41  5159.6 1861.03  5249.6 1860.14  5388.6 1858.59  5821.8 1860.23
  5830.8 1860.65  5899.2 1868.31  5935.9 1877.74    5978 1895.46  5989.9 1896.72
#Mann= 13 ,-1 , 0
  4240.5      .1       0    4256     .05       0    4595      .1       0
  4659.9     .05       0  4844.7      .1       0  4849.1     .16       0
  4998.9     .07       0  5004.9     .16       0  5070.2     .05       0
  5249.6      .1       0  5388.6     .05       0  5821.8      .1       0
  5830.8     .16       0
#XS Ineff= 2 , 0
                         5191.02          1861.3
Permanent Ineff=
       T       T
Bank Sta=4879.8,5031.5
XS Rating Curve= 0 ,0
Exp/Cntr=0.3,0.1

Type RM Length L Ch R = 1 ,58343   ,348,348,348
BEGIN DESCRIPTION:
LIVE OAK CREEK 109.0
END DESCRIPTION:
XS GIS Cut Line= 2
      2723743.41     10087340.99      2722532.16     10086126.44
#Sta/Elev= 30
  4312.7 1894.97  4455.7 1890.12  4533.5 1876.44    4583 1873.97  4625.4  1869.1
  4653.7 1869.92  4752.7 1863.08  4773.9 1860.26  4780.9 1861.19  4802.2 1858.55
  4858.7 1855.66  4879.9 1852.07  4901.2 1842.17  4915.3 1838.14  4944.3 1836.28
  5004.2 1831.25    5007 1830.75  5010.2 1831.25  5021.4 1834.06 5038.64 1842.97
  5063.8  1852.5  5125.3 1855.26  5169.9    1856  5238.4 1855.13  5305.9 1854.77
  5873.1  1860.5  5933.5 1864.38  5947.7 1868.26    5983 1884.87    6028 1891.64
#Mann= 9 ,-1 , 0
  4312.7      .1       0  4944.3     .16       0  5004.2     .07       0
  5010.2     .16       0  5125.3     .05       0  5169.9      .1       0
  5238.4     .05       0  5305.9      .1       0  5873.1     .16       0
Bank Sta=4901.2,5038.64
XS Rating Curve= 0 ,0
Exp/Cntr=0.3,0.1

Type RM Length L Ch R = 1 ,57995   ,483,483,483
BEGIN DESCRIPTION:
LIVE OAK CREEK 108.0
END DESCRIPTION:
XS GIS Cut Line= 3
      2724155.23     10087074.57      2723134.26     10086342.44
       2722925.7     10085888.18
#Sta/Elev= 30
    4144 1891.11  4191.9 1884.74  4326.1 1876.37  4505.7 1868.89  4585.1 1865.93
  4729.1 1859.84  4766.6 1859.16  4793.7 1854.66  4837.8  1854.4    4865 1849.35
  4902.9 1839.03  4915.3 1835.79  4964.6 1832.52  5006.8 1830.82  5009.5 1830.32
  5012.8 1830.82  5038.3  1838.7  5060.1 1844.83  5087.5 1842.43  5146.1 1851.35
  5181.7 1853.88  5267.7 1855.39  5495.3  1854.1  5611.4 1856.04  5690.2 1860.24
  5736.2 1874.22    5773 1877.62  5833.6 1892.86  5851.1    1895  5900.2 1901.71
#Mann= 11 ,-1 , 0
    4144      .1       0  4326.1     .05       0  4505.7      .1       0
  4585.1     .05       0  4729.1      .1       0    4865     .16       0
  4964.6      .1       0  5006.8     .07       0  5012.8      .1       0
  5611.4     .16       0  5851.1      .1       0
Bank Sta=4902.9,5038.3
XS Rating Curve= 0 ,0
Exp/Cntr=0.3,0.1

Type RM Length L Ch R = 1 ,57512   ,916,916,916
BEGIN DESCRIPTION:
LIVE OAK CREEK 107.0
END DESCRIPTION:
XS GIS Cut Line= 2
      2724058.66     10086586.27      2723317.77     10085698.64
#Sta/Elev= 30
  4458.1 1862.72  4470.2 1861.65  4481.4 1856.54  4487.9 1856.85  4495.7  1853.1
  4524.3 1847.25  4603.1 1844.57    4736 1846.32  4864.1 1846.37  4868.9 1846.42
  4929.1 1844.85  4949.9 1835.91  4964.2 1830.32  4996.4 1824.89  4999.1 1824.39
  5002.4 1824.89  5021.5 1827.75  5034.5 1831.98  5063.2 1830.64  5091.8  1835.1
  5134.7 1836.96  5149.1 1838.79  5184.2 1848.65  5278.9 1854.62  5346.1 1859.18
  5503.5 1871.31  5525.2 1876.68  5553.8 1889.27  5568.1 1892.86  5614.3 1895.32
#Mann= 10 ,-1 , 0
  4458.1      .1       0  4470.2     .16       0  4603.1     .05       0
    4736      .1       0  4864.1     .05       0  4868.9      .1       0
  4996.4     .07       0  5002.4      .1       0  5278.9     .05       0
  5346.1      .1       0
Bank Sta=4949.9,5134.7
XS Rating Curve= 0 ,0
Exp/Cntr=0.3,0.1

Type RM Length L Ch R = 1 ,56596   ,760,760,760
BEGIN DESCRIPTION:
LIVE OAK CREEK 106.0
END DESCRIPTION:
XS GIS Cut Line= 4
      2724280.84     10086778.56      2724135.22     10086223.39
      2724462.85     10085527.17      2724244.41     10085049.34
#Sta/Elev= 30
    3828 1867.49  4013.7 1862.45  4049.5 1857.31  4070.8 1850.43  4138.4 1844.81
  4198.4 1844.02  4240.6  1843.1  4372.6  1839.3  4441.1  1833.3    4501 1830.46
  4584.8 1832.83  4744.2 1827.75  4813.3 1828.74  4898.9 1829.32  4943.3 1824.58
  4995.4 1823.09  4998.1 1822.59  5001.4 1823.09  5044.2 1826.61  5051.8  1829.8
  5074.6 1839.83  5102.5 1841.96  5284.9 1846.58    5365    1854  5382.5 1853.03
    5388  1855.5    5411 1857.37  5428.1  1856.4    5549  1872.4  5696.8 1903.64
#Mann= 11 ,-1 , 0
    3828     .05       0  4013.7     .16       0  4138.4     .05       0
  4198.4      .1       0  4240.6     .05       0  4441.1     .16       0
  4813.3      .1       0  4995.4     .07       0  5001.4      .1       0
  5044.2     .16       0  5102.5      .1       0
Bank Sta=4898.9,5051.8
XS Rating Curve= 0 ,0
Exp/Cntr=0.3,0.1

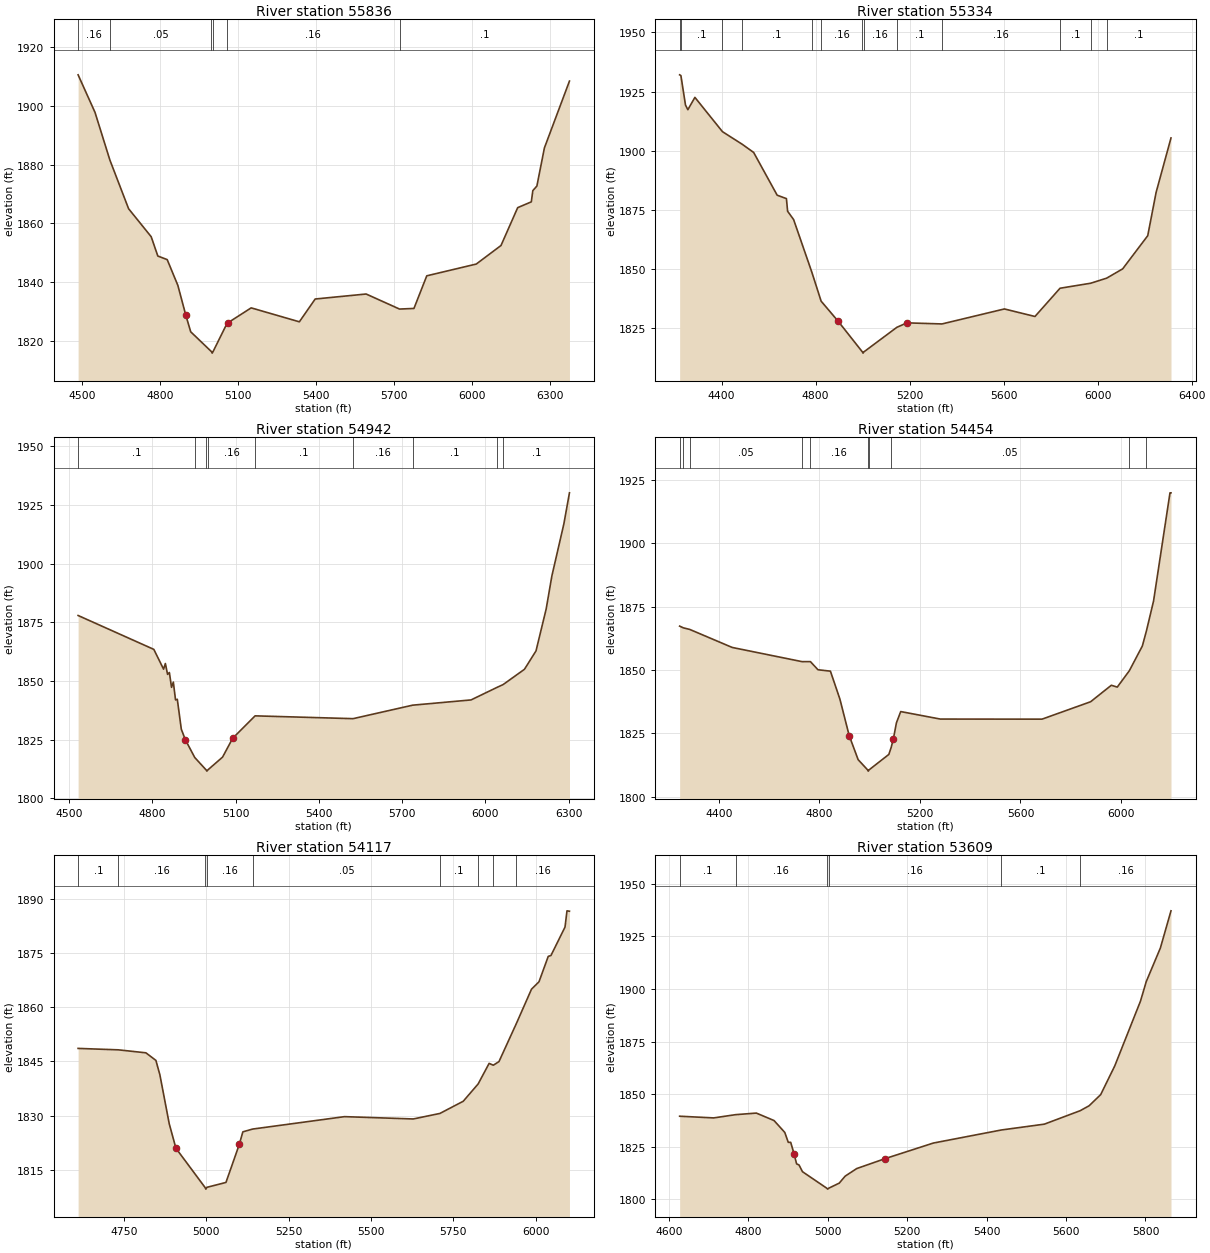
Type RM Length L Ch R = 1 ,55836   ,502,502,502
BEGIN DESCRIPTION:
LIVE OAK CREEK 105.0
END DESCRIPTION:
XS GIS Cut Line= 4
      2724717.69     10086764.94      2724585.71     10086396.31
      2724694.92      10085772.9      2724248.98     10085031.18
#Sta/Elev= 30
  4484.1 1910.59  4549.1  1897.8  4606.2 1881.59  4678.3 1864.97  4765.2 1855.43
  4790.7 1848.86  4826.8 1847.63  4867.8 1838.85  4898.6 1828.62  4917.2 1823.04
  4997.1 1816.27  4999.8 1815.77  5003.1 1816.27  5056.3 1825.79    5061 1826.15
  5149.8 1831.19  5335.1 1826.44    5396 1834.21    5592 1835.91  5720.5 1830.78
  5775.9    1831  5825.2 1842.11  6015.6 1846.12  6110.7 1852.44  6174.9 1865.34
  6227.3 1867.31  6233.1 1871.13  6248.7  1872.7  6277.7  1885.7    6374 1908.46
#Mann= 6 ,-1 , 0
  4484.1     .16       0  4606.2     .05       0  4997.1    .035       0
  5003.1     .05       0  5056.3     .16       0  5720.5      .1       0
Bank Sta=4898.6,5061
XS Rating Curve= 0 ,0
Exp/Cntr=0.3,0.1

Type RM Length L Ch R = 1 ,55334   ,392,392,392
BEGIN DESCRIPTION:
LIVE OAK CREEK 104.0
END DESCRIPTION:
XS GIS Cut Line= 3
      2725190.92     10086828.58      2725181.82      10086268.9
      2724286.14     10085027.68
#Sta/Elev= 30
  4221.7 1932.08  4227.1 1931.75  4246.5 1919.34  4256.6 1917.36  4286.6 1922.56
  4403.9 1908.08  4488.4 1902.73  4536.6  1899.3  4636.6 1881.26    4676 1879.82
    4681 1874.49  4706.6 1870.97  4783.9 1848.82  4823.6 1836.53  4895.5 1828.12
  4999.2 1815.09    5002 1814.59  5005.2 1815.09  5145.7 1825.48  5188.7 1827.37
  5337.8 1826.91  5603.4 1833.24  5733.4 1830.06    5840 1841.98  5970.5  1844.1
  6038.4 1846.24  6106.4 1850.16  6213.1 1864.16  6248.7 1882.43  6312.1 1905.43
#Mann= 13 ,-1 , 0
  4221.7     .16       0  4227.1      .1       0  4403.9     .05       0
  4488.4      .1       0  4783.9     .05       0  4823.6     .16       0
  4999.2     .07       0  5005.2     .16       0  5145.7      .1       0
  5337.8     .16       0    5840      .1       0  5970.5     .16       0
  6038.4      .1       0
Bank Sta=4895.5,5188.7
XS Rating Curve= 0 ,0
Exp/Cntr=0.3,0.1

Type RM Length L Ch R = 1 ,54942   ,488,488,488
BEGIN DESCRIPTION:
LIVE OAK CREEK 103.0
END DESCRIPTION:
XS GIS Cut Line= 2
      2725659.59     10086095.95      2724295.22     10084968.08
#Sta/Elev= 30
  4532.6 1877.91  4805.4 1863.46  4840.5 1855.03    4847 1857.44  4854.9 1852.81
  4861.4 1853.59  4869.2 1847.28  4875.7 1849.51  4883.6 1841.92    4890 1842.18
  4904.4 1829.44  4918.7 1825.01  4952.8 1817.36  4993.9 1812.05  4996.6 1811.55
  4999.9 1812.05    5053 1817.52  5089.4 1825.54  5170.3 1835.12  5523.2 1833.92
  5737.8 1839.67  5948.3 1841.91  6042.8 1847.31  6063.7 1848.45  6140.6 1854.96
  6182.3 1862.81  6218.8 1880.63  6239.6 1894.86  6282.6 1916.94  6302.8 1930.21
#Mann= 9 ,-1 , 0
  4532.6      .1       0  4952.8     .16       0  4993.9     .07       0
  4999.9     .16       0  5170.3      .1       0  5523.2     .16       0
  5737.8      .1       0  6042.8     .16       0  6063.7      .1       0
Bank Sta=4918.7,5089.4
XS Rating Curve= 0 ,0
Exp/Cntr=0.3,0.1

Type RM Length L Ch R = 1 ,54454   ,337,337,337
BEGIN DESCRIPTION:
LIVE OAK CREEK 102.0
END DESCRIPTION:
XS GIS Cut Line= 3
        2726101.     10085804.74      2725605.01     10085404.31
      2724394.64     10084885.58
#Sta/Elev= 30
  4244.4 1867.33  4259.6 1866.64  4284.4 1866.04  4453.3 1858.92  4731.5 1853.31
  4764.6 1853.32  4794.5 1850.12  4844.1 1849.55  4881.8 1838.52  4918.8  1824.1
  4954.3 1814.63  4991.9 1810.59  4994.7 1810.09  4997.9 1810.59  5076.5 1816.69
  5085.9  1819.5  5094.7 1822.94  5106.6 1829.17  5123.7  1833.6  5281.4 1830.64
  5685.8 1830.61    5879 1837.48  5961.4 1843.99    5985 1843.26  6032.9 1849.71
  6084.7 1859.48  6101.1  1865.5  6129.3 1877.24  6194.7 1919.96  6198.7 1919.96
#Mann= 10 ,-1 , 0
  4244.4     .05       0  4259.6      .1       0  4284.4     .05       0
  4731.5      .1       0  4764.6     .16       0  4991.9     .07       0
  4997.9     .16       0  5085.9     .05       0  6032.9      .1       0
  6101.1     .16       0
Bank Sta=4918.8,5094.7
XS Rating Curve= 0 ,0
Exp/Cntr=0.3,0.1

Type RM Length L Ch R = 1 ,54117   ,508,508,508
BEGIN DESCRIPTION:
LIVE OAK CREEK 101.0
END DESCRIPTION:
XS GIS Cut Line= 3
      2725991.62     10085107.87      2725150.42     10084971.85
      2724622.05     10084611.27
#Sta/Elev= 30
  4610.7 1848.61  4733.3 1848.21  4816.5 1847.39  4846.9 1845.29    4859  1841.3
  4887.4 1827.75  4907.7 1820.99  4995.8 1810.18  4998.6 1809.68  5001.8 1810.18
  5059.6 1811.53  5100.1 1822.05  5110.9 1825.53  5140.8  1826.3  5419.4 1829.73
  5628.3 1829.09  5709.2 1830.62    5780 1833.99  5825.2 1838.77  5858.6 1844.47
  5871.3 1843.96  5888.5 1844.96  5941.2 1855.47  5987.3    1865    6010 1867.04
  6038.1 1874.07  6046.3 1874.31    6089 1882.17    6095 1886.67  6102.5 1886.56
#Mann= 9 ,-1 , 0
  4610.7      .1       0  4733.3     .16       0  4995.8     .07       0
  5001.8     .16       0  5140.8     .05       0  5709.2      .1       0
  5825.2     .16       0  5871.3      .1       0  5941.2     .16       0
Bank Sta=4907.7,5100.1
XS Rating Curve= 0 ,0
Exp/Cntr=0.3,0.1

Type RM Length L Ch R = 1 ,53609   ,474,474,474
BEGIN DESCRIPTION:
LIVE OAK CREEK 100.0
END DESCRIPTION:
XS GIS Cut Line= 3
      2726095.44     10084796.45      2725655.15     10084492.18
      2725237.14      10083927.7
#Sta/Elev= 30
  4626.7 1839.51  4712.4 1838.71  4767.7 1840.25  4819.9    1841  4864.5 1837.45
  4891.5 1831.81  4900.3  1827.1  4906.4  1827.1  4914.8 1821.68  4921.3 1816.86
  4927.3 1816.37  4936.1 1813.15  4996.8 1805.37  4999.6 1804.87  5002.8 1805.37
  5028.7 1807.72  5043.6 1811.04  5072.8 1814.65    5145 1819.41  5265.6 1826.76
  5436.7 1832.96  5545.3 1835.74  5635.6 1842.14    5658 1844.47  5687.2 1849.78
  5722.7 1863.44  5787.4 1894.18    5802 1903.49  5837.5 1919.42  5864.3  1937.1
#Mann= 6 ,-1 , 0
  4626.7      .1       0  4767.7     .16       0  4996.8     .07       0
  5002.8     .16       0  5436.7      .1       0  5635.6     .16       0
Bank Sta=4914.8,5145
XS Rating Curve= 0 ,0
Exp/Cntr=0.3,0.1

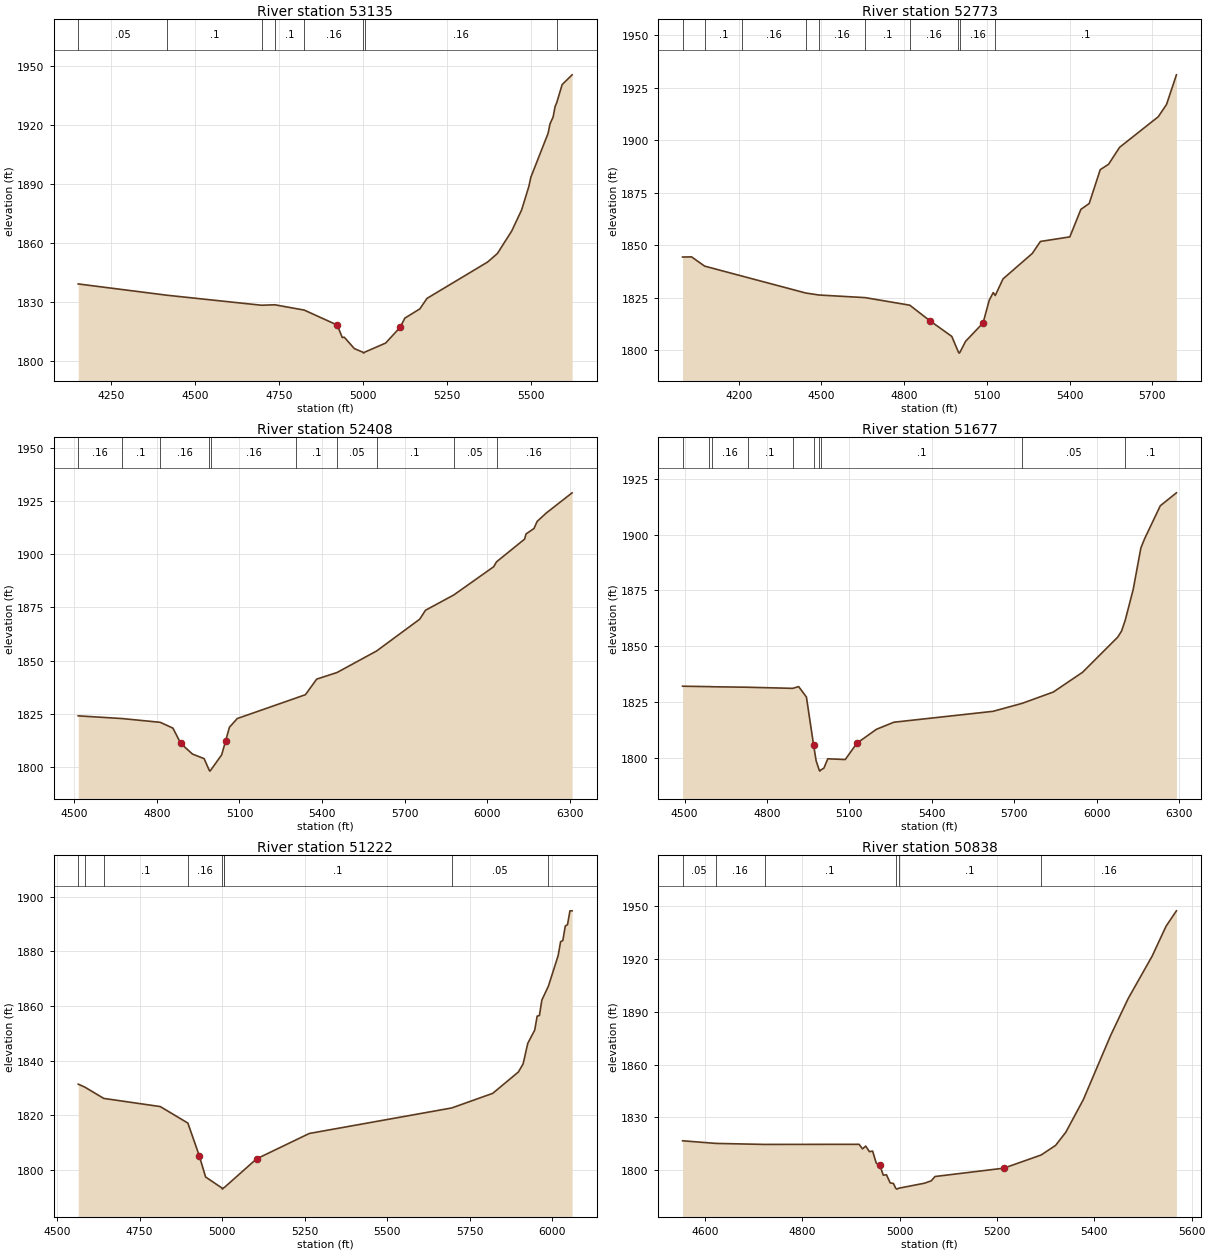
Type RM Length L Ch R = 1 ,53135   ,362,362,362
BEGIN DESCRIPTION:
LIVE OAK CREEK 99.0
END DESCRIPTION:
XS GIS Cut Line= 2
      2726633.45       10084608.      2725413.89      10083788.9
#Sta/Elev= 30
  4152.1 1839.25  4416.6  1833.5  4697.4 1828.42    4737 1828.65  4824.6 1825.95
  4922.5 1818.35  4937.5 1812.02  4943.5 1812.18  4973.5 1806.38  4998.3 1804.58
  5001.1 1804.08  5004.3 1804.58  5066.5 1809.19  5109.8 1817.22  5123.6 1821.86
  5168.5  1826.6  5189.5  1831.9  5369.6 1850.36  5398.9 1854.69  5441.6 1866.16
  5471.1  1876.9  5492.6 1888.85  5498.6 1893.55  5549.6 1915.73  5555.6 1920.68
  5564.6 1924.03  5570.6 1929.45  5575.4 1931.36  5591.6 1940.58  5621.2 1945.55
#Mann= 8 ,-1 , 0
  4152.1     .05       0  4416.6      .1       0  4697.4     .16       0
    4737      .1       0  4824.6     .16       0  4998.3     .07       0
  5004.3     .16       0  5575.4      .1       0
Bank Sta=4922.5,5109.8
XS Rating Curve= 0 ,0
Exp/Cntr=0.3,0.1

Type RM Length L Ch R = 1 ,52773   ,365,365,365
BEGIN DESCRIPTION:
LIVE OAK CREEK 98.0
END DESCRIPTION:
XS GIS Cut Line= 3
      2726915.53      10084421.4      2725855.29     10083638.74
      2725382.79     10083670.54
#Sta/Elev= 30
  3996.3 1844.37  4029.1 1844.45  4076.3 1840.05  4213.5 1835.25  4443.8 1827.21
  4491.6 1826.28  4658.9 1825.03  4820.5 1821.43  4893.5 1814.02  4972.9 1806.56
  4996.9 1799.09  4999.7 1798.59  5002.9 1799.09    5023 1804.22  5086.4 1812.97
  5108.6 1823.75  5123.2 1827.45  5130.6 1826.05  5158.7 1833.95  5265.1 1846.11
  5294.4  1851.8  5401.1 1853.98  5441.2  1867.1  5471.3 1869.87  5511.4 1886.01
  5541.5 1888.56  5581.6 1896.65  5721.9 1911.23  5751.9 1917.09  5787.7 1931.19
#Mann= 10 ,-1 , 0
  3996.3     .16       0  4076.3      .1       0  4213.5     .16       0
  4443.8      .1       0  4491.6     .16       0  4658.9      .1       0
  4820.5     .16       0  4996.9     .07       0  5002.9     .16       0
  5130.6      .1       0
Bank Sta=4893.5,5086.4
XS Rating Curve= 0 ,0
Exp/Cntr=0.3,0.1

Type RM Length L Ch R = 1 ,52408   ,731,731,731
BEGIN DESCRIPTION:
LIVE OAK CREEK 97.0
END DESCRIPTION:
XS GIS Cut Line= 3
      2726696.78     10083901.51       2726102.6     10083307.33
      2725186.25     10083565.05
#Sta/Elev= 30
    4515 1824.01  4673.8 1822.74  4812.4 1820.98  4858.7 1818.24    4887 1811.07
  4929.4 1806.07  4971.9 1803.91  4990.1 1798.54  4992.8 1798.04  4996.1 1798.54
  5035.5 1805.69  5049.6 1812.14  5063.8 1818.68  5092.1 1822.75  5305.7 1832.41
  5339.5 1833.96  5380.4 1841.27  5454.3 1844.38  5597.8 1854.49  5754.3 1869.43
  5775.1 1873.62  5877.9 1880.81  6022.3 1894.04  6033.1 1896.39  6134.8 1907.04
    6140 1909.47  6168.9 1912.02  6180.2 1915.33  6213.3 1919.29  6307.2 1928.79
#Mann= 10 ,-1 , 0
    4515     .16       0  4673.8      .1       0  4812.4     .16       0
  4990.1     .07       0  4996.1     .16       0  5305.7      .1       0
  5454.3     .05       0  5597.8      .1       0  5877.9     .05       0
  6033.1     .16       0
Bank Sta=4887,5049.6
XS Rating Curve= 0 ,0
Exp/Cntr=0.3,0.1

Type RM Length L Ch R = 1 ,51677   ,455,455,455
BEGIN DESCRIPTION:
LIVE OAK CREEK 96.0
END DESCRIPTION:
XS GIS Cut Line= 2
      2727262.41     10083436.21      2725932.12      10082227.5
#Sta/Elev= 30
  4492.8 1832.04    4588 1831.86  4601.2  1831.8  4729.5 1831.58  4893.8 1831.08
  4915.3 1831.87  4943.6 1827.21  4969.9 1805.53  4978.8 1798.68    4990 1794.43
  4992.7 1793.93    4996 1794.43  5007.2 1795.27  5021.4 1799.47  5084.9 1799.13
  5127.4 1806.47  5198.4  1812.7  5261.9 1815.88  5622.8 1820.77  5729.1 1824.36
  5842.4 1829.44  5948.5 1838.28  6076.2 1854.01  6090.4 1856.74  6103.9 1861.67
    6133  1875.5  6160.7 1894.01  6174.8 1898.34  6231.6 1913.03  6290.2 1918.83
#Mann= 10 ,-1 , 0
  4492.8     .16       0    4588      .1       0  4601.2     .16       0
  4729.5      .1       0  4893.8     .16       0  4969.9      .1       0
    4990     .07       0    4996      .1       0  5729.1     .05       0
  6103.9      .1       0
Bank Sta=4969.9,5127.4
XS Rating Curve= 0 ,0
Exp/Cntr=0.3,0.1

Type RM Length L Ch R = 1 ,51222   ,384,384,384
BEGIN DESCRIPTION:
LIVE OAK CREEK 95.0
END DESCRIPTION:
XS GIS Cut Line= 4
      2727487.94     10082902.85      2727194.38     10082734.59
      2726535.73     10082573.51      2726213.53     10082219.09
#Sta/Elev= 30
  4564.4 1831.41  4584.7 1830.31  4641.6  1826.2  4812.8 1823.21  4896.4 1817.17
    4931 1805.19    4950 1797.45  4998.5  1793.5  5001.2    1793  5004.5  1793.5
  5007.2 1793.64  5104.4 1804.08  5264.1 1813.37  5695.5 1822.71  5819.5 1828.05
  5897.2 1835.87  5911.4 1838.81  5925.6 1846.36  5946.6 1851.19    5954 1856.31
  5960.8 1856.52  5968.2 1862.18  5988.1  1867.3  6017.5 1878.44    6025 1883.55
  6031.7 1883.95  6039.1 1889.27  6045.9 1889.77  6053.3 1894.84  6059.8 1894.84
#Mann= 9 ,-1 , 0
  4564.4      .1       0  4584.7     .05       0  4641.6      .1       0
  4896.4     .16       0  4998.5     .07       0  5004.5     .16       0
  5007.2      .1       0  5695.5     .05       0  5988.1     .16       0
Bank Sta=4931,5104.4
XS Rating Curve= 0 ,0
Exp/Cntr=0.3,0.1

Type RM Length L Ch R = 1 ,50838   ,610,610,610
BEGIN DESCRIPTION:
LIVE OAK CREEK 94.0
END DESCRIPTION:
XS GIS Cut Line= 2
      2727552.31     10082641.49       2726786.3     10081975.71
#Sta/Elev= 30
  4553.8 1816.71  4622.5 1815.22  4722.5 1814.64  4916.6 1814.71  4923.6 1812.12
  4930.2  1813.7  4937.8 1810.54  4944.4 1810.86    4952  1803.9  4958.7 1803.22
  4966.3 1797.18  4972.9 1797.37  4980.5 1792.77  4987.2 1792.47  4991.8 1789.73
  4994.5 1789.23  4997.8 1789.73  5050.8 1792.58    5065 1793.96  5072.6  1796.4
  5214.1 1801.15  5290.8 1808.64  5320.5 1814.11  5341.3 1821.53  5377.4 1840.11
  5433.4 1876.53  5469.5 1897.53  5518.9 1921.72  5547.4 1938.66  5568.7 1947.43
#Mann= 6 ,-1 , 0
  4553.8     .05       0  4622.5     .16       0  4722.5      .1       0
  4991.8     .07       0  4997.8      .1       0  5290.8     .16       0
Bank Sta=4958.7,5214.1
XS Rating Curve= 0 ,0
Exp/Cntr=0.3,0.1

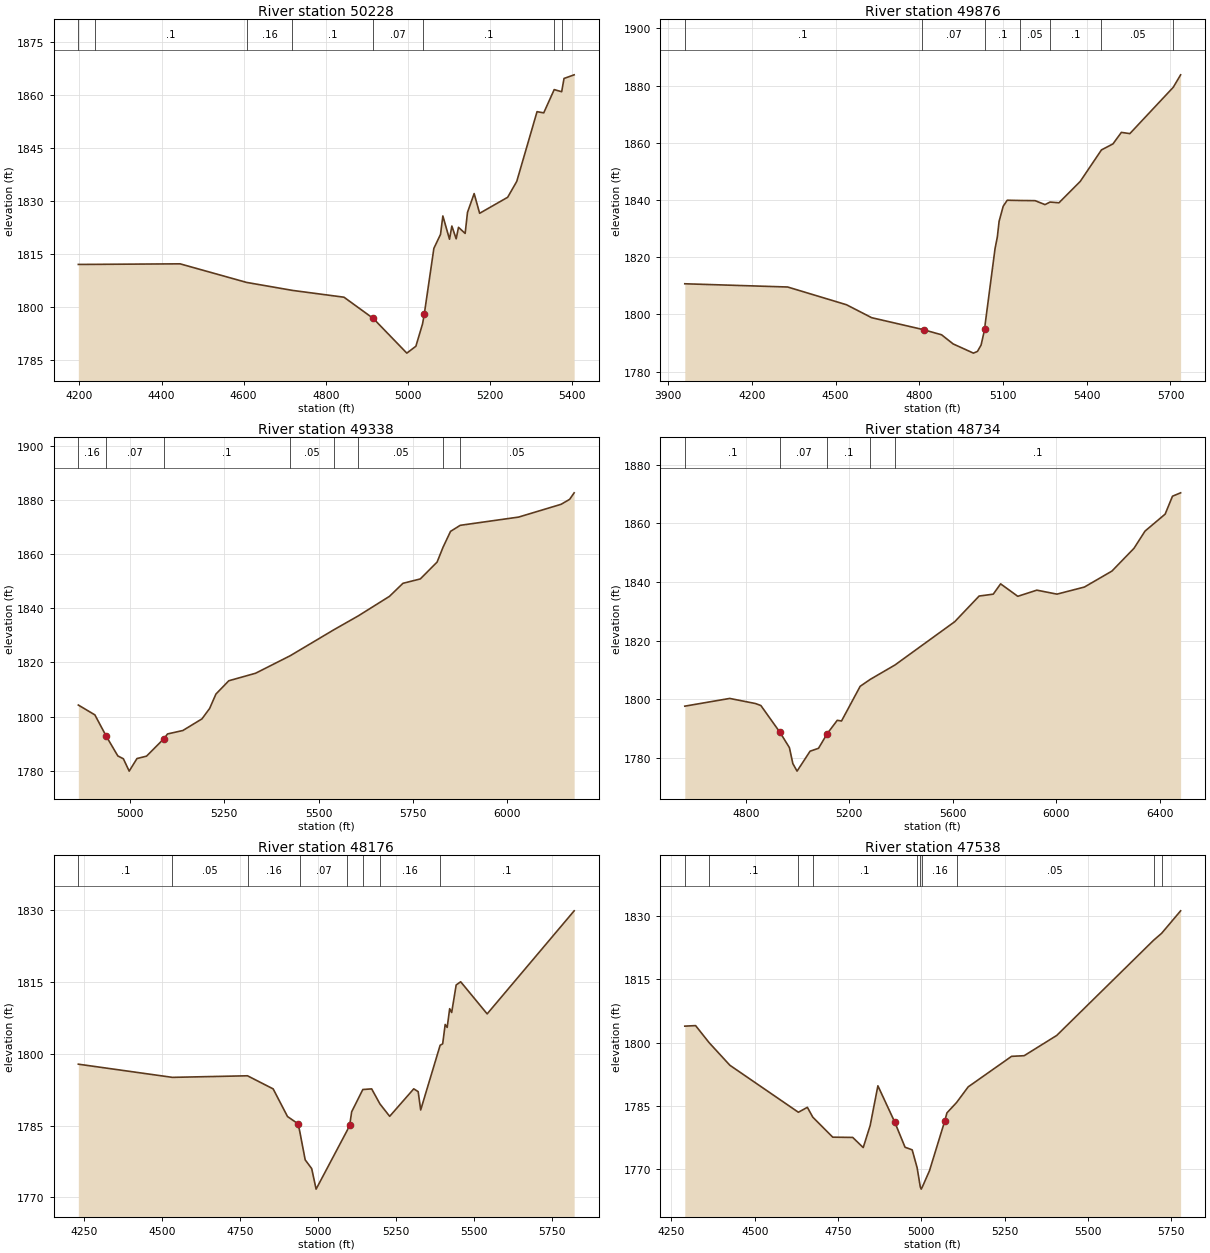
Type RM Length L Ch R = 1 ,50228   ,352,352,352
BEGIN DESCRIPTION:
LIVE OAK CREEK 93.0
END DESCRIPTION:
XS GIS Cut Line= 3
        2727649.     10082444.67      2727423.47     10081843.27
      2726925.88     10081574.78
#Sta/Elev= 30
  4197.4 1812.13  4237.1 1812.15  4445.2  1812.3  4607.2 1807.04    4719 1804.78
  4844.5 1802.85  4915.8 1796.84  4997.5 1787.02  5019.6 1788.97  5035.8  1795.3
    5040 1798.02  5063.4 1816.68  5079.6 1820.64  5085.3 1825.86  5101.5 1819.26
  5107.2    1823  5117.7 1819.38  5123.4 1822.63  5139.6 1820.91  5145.3 1826.87
  5161.5 1832.19  5174.9 1826.61  5243.1 1831.14  5265.3 1835.64  5314.7 1855.38
    5331 1855.04  5356.5 1861.63  5374.7 1861.02  5380.4 1864.78  5405.1 1865.81
#Mann= 8 ,-1 , 0
  4197.4     .16       0  4237.1      .1       0  4607.2     .16       0
    4719      .1       0  4915.8     .07       0  5035.8      .1       0
  5356.5     .16       0  5374.7     .05       0
Bank Sta=4915.8,5040
XS Rating Curve= 0 ,0
Exp/Cntr=0.3,0.1

Type RM Length L Ch R = 1 ,49876   ,538,538,538
BEGIN DESCRIPTION:
LIVE OAK CREEK 92.0
END DESCRIPTION:
XS GIS Cut Line= 4
       2727808.5     10082431.11      2727744.79     10081680.28
      2727253.34     10081311.69      2726848.38     10081370.84
#Sta/Elev= 30
  3959.4 1810.72  4328.1 1809.59  4538.9 1803.39  4629.2 1798.86  4808.3 1794.82
    4815 1794.65  4879.6 1792.89  4921.3 1789.68    4994 1786.47  5008.3 1787.07
  5021.3 1789.28 5034.56 1794.97  5035.9 1796.59  5071.3 1822.97  5079.6  1827.1
  5085.9 1832.54  5100.5 1837.81    5115 1839.93  5161.1 1839.84    5215 1839.78
  5250.5  1838.4  5268.4 1839.29  5300.5 1839.04  5376.8 1846.52  5452.8 1857.53
  5493.9 1859.62  5524.2 1863.66  5554.5 1863.22    5710 1879.41  5736.5 1883.78
#Mann= 7 ,-1 , 0
  3959.4      .1       0  4808.3     .07       0  5035.9      .1       0
  5161.1     .05       0  5268.4      .1       0  5452.8     .05       0
    5710      .1       0
Bank Sta=4815,5034.56
XS Rating Curve= 0 ,0
Exp/Cntr=0.3,0.1

Type RM Length L Ch R = 1 ,49338   ,604,604,604
BEGIN DESCRIPTION:
LIVE OAK CREEK 91.0
END DESCRIPTION:
XS GIS Cut Line= 3
      2728031.47     10081197.93      2727144.13     10081052.32
      2726772.23     10081233.73
#Sta/Elev= 30
  4863.5 1804.26  4907.3 1800.64  4937.7  1792.7  4968.1 1785.49  4982.8 1784.44
  4998.2 1779.88  5018.8 1784.52  5044.1  1785.4  5089.7 1791.79  5099.8  1793.6
  5140.4 1794.87    5191 1799.17  5211.3 1803.01  5227.9 1808.31    5262 1813.22
  5332.9 1815.99  5424.6 1822.45  5540.2 1832.03  5605.1 1837.17  5687.6 1844.37
  5723.2 1849.17  5769.2 1850.79  5813.7 1857.01  5829.4 1862.47  5849.3 1868.34
  5874.9 1870.57  6029.6 1873.61  6142.2 1878.33  6164.7 1880.15  6176.7 1882.56
#Mann= 8 ,-1 , 0
  4863.5     .16       0  4937.7     .07       0  5089.7      .1       0
  5424.6     .05       0  5540.2      .1       0  5605.1     .05       0
  5829.4      .1       0  5874.9     .05       0
Bank Sta=4937.7,5089.7
XS Rating Curve= 0 ,0
Exp/Cntr=0.3,0.1

Type RM Length L Ch R = 1 ,48734   ,558,558,558
BEGIN DESCRIPTION:
LIVE OAK CREEK 90.0
END DESCRIPTION:
XS GIS Cut Line= 4
      2728412.86      10080914.2      2728171.33     10080700.79
      2727268.37     10080234.74      2726836.28      10079851.2
#Sta/Elev= 30
  4564.2 1797.61  4737.7 1800.25  4836.9 1798.52  4858.2 1797.83  4931.9 1788.69
  4968.5 1783.45  4981.8    1778  4998.1 1775.43  5048.3 1782.23    5081 1783.23
  5114.8 1788.25  5153.4 1792.78  5169.9 1792.55    5242  1804.4  5281.2 1806.77
  5376.3 1811.66  5607.4 1826.45  5701.7 1835.21  5756.2 1835.85  5784.7 1839.37
  5851.1 1835.12  5924.7 1837.22  6002.4 1835.86  6108.6 1838.28  6214.9 1843.73
  6300.2 1851.51  6342.8 1857.38  6420.6 1863.18    6449  1869.3  6480.4 1870.45
#Mann= 5 ,-1 , 0
  4564.2      .1       0  4931.9     .07       0  5114.8      .1       0
  5281.2     .16       0  5376.3      .1       0
Bank Sta=4931.9,5114.8
XS Rating Curve= 0 ,0
Exp/Cntr=0.3,0.1

Type RM Length L Ch R = 1 ,48176   ,638,638,638
BEGIN DESCRIPTION:
LIVE OAK CREEK 89.0
END DESCRIPTION:
XS GIS Cut Line= 3
      2728440.71     10081015.46      2728496.59     10080307.56
      2727948.02     10079623.06
#Sta/Elev= 30
  4232.6 1797.85  4533.8 1795.09  4774.2 1795.42  4856.3 1792.68  4902.2  1786.9
  4936.5 1785.35  4942.1 1783.56  4958.9 1777.83  4979.7    1776  4993.8 1771.71
  5093.3 1783.99  5101.3  1785.1  5107.7  1787.9  5143.4 1792.55  5171.7 1792.68
    5198 1789.55  5229.3 1786.94  5306.4 1792.69  5320.6  1792.1  5328.6 1788.27
  5390.9 1801.81    5399  1802.1    5407 1806.16  5413.4 1805.54  5421.4 1809.46
  5427.8 1808.66  5442.2 1814.42  5456.6 1815.09  5541.4 1808.37  5819.9 1829.93
#Mann= 8 ,-1 , 0
  4232.6      .1       0  4533.8     .05       0  4774.2     .16       0
  4942.1     .07       0  5093.3     .16       0  5143.4      .1       0
    5198     .16       0  5390.9      .1       0
Bank Sta=4936.5,5101.3
XS Rating Curve= 0 ,0
Exp/Cntr=0.3,0.1

Type RM Length L Ch R = 1 ,47538   ,514,514,514
BEGIN DESCRIPTION:
LIVE OAK CREEK 88.0
END DESCRIPTION:
XS GIS Cut Line= 2
      2729389.82     10079899.77      2727968.59     10079458.36
#Sta/Elev= 30
  4290.1 1803.89  4322.5 1804.02  4363.2 1799.96  4425.4  1794.6    4631 1783.44
    4658 1784.61  4674.3 1782.27  4734.2 1777.52  4794.1 1777.46  4825.6 1775.05
  4846.5 1780.29  4869.7 1789.72  4919.8 1781.18  4951.2 1775.13  4972.6 1774.51
  4987.4 1770.27    4997 1765.68  4999.7 1765.18    5003 1765.68  5024.5 1769.55
  5070.3 1781.35  5076.9 1783.29  5105.8 1785.75  5140.7 1789.47  5270.9 1796.72
  5308.7 1796.87  5406.4 1801.68  5697.3  1824.3  5721.2 1825.93  5778.3 1831.28
#Mann= 10 ,-1 , 0
  4290.1     .05       0  4363.2      .1       0    4631     .05       0
  4674.3      .1       0  4987.4     .16       0    4997     .07       0
    5003     .16       0  5105.8     .05       0  5697.3      .1       0
  5721.2     .05       0
Bank Sta=4919.8,5070.3
XS Rating Curve= 0 ,0
Exp/Cntr=0.3,0.1

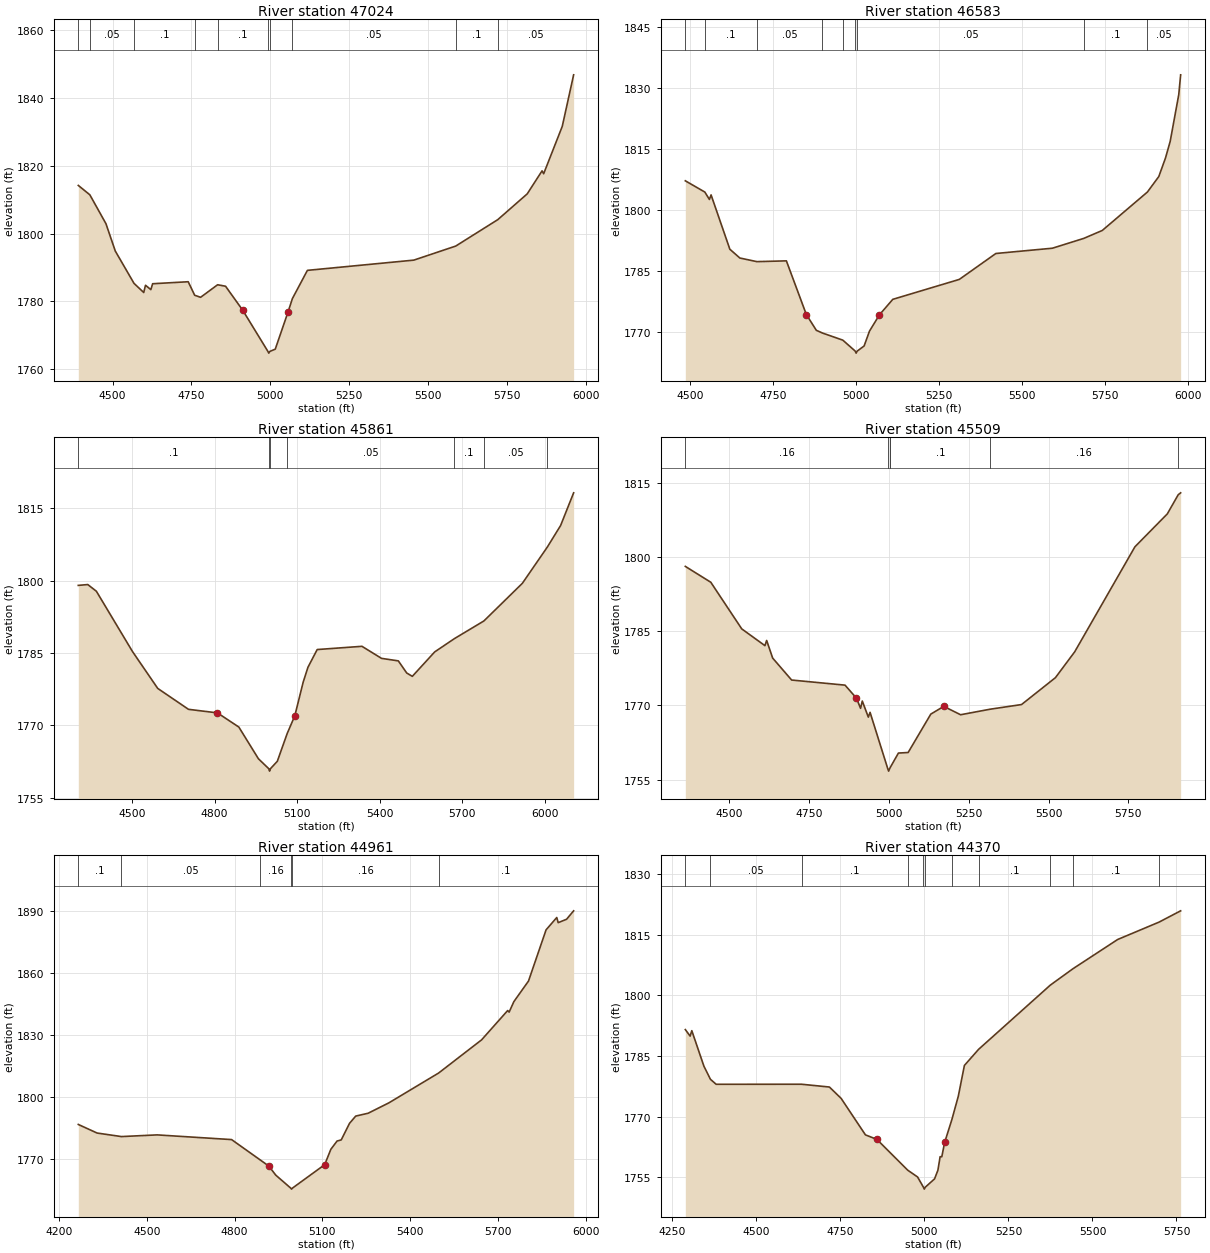
Type RM Length L Ch R = 1 ,47024   ,441,441,441
BEGIN DESCRIPTION:
LIVE OAK CREEK 87.0
END DESCRIPTION:
XS GIS Cut Line= 3
      2729477.24     10078996.81      2728986.91     10079234.69
      2727972.89     10079084.28
#Sta/Elev= 30
  4391.6 1814.25  4428.1 1811.49  4479.2 1802.96  4508.8 1794.88  4568.2 1785.33
    4599 1782.63  4604.6 1784.77  4621.6 1783.48  4627.2 1785.22    4740 1785.81
  4760.4 1781.83  4779.2 1781.21  4833.2 1784.92  4858.4 1784.48  4912.6 1777.42
  4992.7 1765.23  4995.4 1764.73  4998.7 1765.23  5015.9  1765.9  5056.3 1776.84
  5070.2 1780.83  5117.8 1789.17    5455 1792.19  5587.9 1796.34  5721.2 1804.14
  5814.5 1811.75  5861.6 1818.55  5866.7  1817.7  5925.7  1831.7  5961.7 1846.91
#Mann= 10 ,-1 , 0
  4391.6      .1       0  4428.1     .05       0  4568.2      .1       0
  4760.4     .05       0  4833.2      .1       0  4992.7     .07       0
  4998.7      .1       0  5070.2     .05       0  5587.9      .1       0
  5721.2     .05       0
Bank Sta=4912.6,5056.3
XS Rating Curve= 0 ,0
Exp/Cntr=0.3,0.1

Type RM Length L Ch R = 1 ,46583   ,722,722,722
BEGIN DESCRIPTION:
LIVE OAK CREEK 86.0
END DESCRIPTION:
XS GIS Cut Line= 2
      2729472.38     10078763.79      2727982.74     10078860.83
#Sta/Elev= 30
  4485.1 1807.27  4543.9  1804.5  4557.7 1802.69  4562.7 1803.81  4619.3 1790.45
  4649.4 1788.29  4700.7  1787.4  4789.7 1787.59  4849.8  1774.4  4879.9 1770.52
  4898.4 1769.85  4959.8  1768.1  4997.1 1765.41  4999.9 1764.91  5003.1 1765.41
  5023.9 1766.66  5040.2 1770.33  5070.3 1774.34  5110.3 1778.13  5310.8 1783.03
    5421  1789.4  5591.4  1790.7  5685.8 1793.11  5741.7 1795.06  5877.7 1804.51
    5912 1808.31  5932.1 1812.84  5946.4 1816.96  5972.2 1828.45  5977.9 1833.32
#Mann= 9 ,-1 , 0
  4485.1     .05       0  4543.9      .1       0  4700.7     .05       0
  4898.4      .1       0  4959.8     .05       0  4997.1    .035       0
  5003.1     .05       0  5685.8      .1       0  5877.7     .05       0
Bank Sta=4849.8,5070.3
XS Rating Curve= 0 ,0
Exp/Cntr=0.3,0.1

Type RM Length L Ch R = 1 ,45861   ,352,352,352
BEGIN DESCRIPTION:
LIVE OAK CREEK 85.0
END DESCRIPTION:
XS GIS Cut Line= 2
      2729642.28     10078229.78      2727871.86     10077904.79
#Sta/Elev= 30
  4304.6 1799.02    4339 1799.19  4370.2 1797.81  4501.7 1785.28  4593.2 1777.65
    4705 1773.31  4810.3 1772.57    4888 1769.63  4959.2 1763.05  4996.8 1760.99
  4999.6 1760.49  5002.8 1760.99  5027.8 1762.53  5063.6 1768.28  5091.3 1771.96
  5121.8 1778.95  5139.1 1782.03  5172.7 1785.71  5335.4 1786.38  5406.5 1783.88
  5467.5 1783.36    5498 1780.85  5518.4 1780.15  5599.7 1785.22  5671.5 1787.98
  5778.5 1791.64  5918.3 1799.45  6009.5 1807.01  6057.2 1811.43  6104.6 1818.22
#Mann= 7 ,-1 , 0
  4304.6      .1       0  4996.8     .07       0  5002.8      .1       0
  5063.6     .05       0  5671.5      .1       0  5778.5     .05       0
  6009.5     .16       0
Bank Sta=4810.3,5091.3
XS Rating Curve= 0 ,0
Exp/Cntr=0.3,0.1

Type RM Length L Ch R = 1 ,45509   ,548,548,548
BEGIN DESCRIPTION:
LIVE OAK CREEK 84.0
END DESCRIPTION:
XS GIS Cut Line= 3
      2729632.61     10077991.91        2729084.     10077773.44
      2728137.37     10077613.24
#Sta/Elev= 30
  4362.9 1798.07  4442.7 1794.86  4539.6 1785.44  4612.1 1782.06  4617.5 1783.11
  4636.4 1779.54  4695.7 1775.11  4862.9 1774.08 4898.52 1771.46  4911.5  1769.4
  4916.9 1770.87  4935.8 1767.62  4941.2 1768.59  4996.6 1757.21  4999.3 1756.71
  5002.6 1757.21    5005 1757.52    5030 1760.36  5060.4 1760.47  5131.4 1768.23
    5172 1769.79  5224.6  1768.1  5317.3 1769.22  5415.4 1770.16  5521.5 1775.59
  5581.8 1780.81  5770.4 1802.03  5871.8 1808.68  5905.9 1812.54  5913.5 1812.93
#Mann= 6 ,-1 , 0
  4362.9     .16       0  4996.6     .07       0  5002.6     .16       0
    5005      .1       0  5317.3     .16       0  5905.9      .1       0
Bank Sta=4898.52,5172
XS Rating Curve= 0 ,0
Exp/Cntr=0.3,0.1

Type RM Length L Ch R = 1 ,44961   ,591,591,591
BEGIN DESCRIPTION:
LIVE OAK CREEK 83.0
END DESCRIPTION:
XS GIS Cut Line= 3
      2729569.49     10077763.75      2728715.05     10076904.46
      2728234.42     10076875.33
#Sta/Elev= 30
  4265.7 1786.62  4330.1 1782.45  4413.2 1780.74  4535.1 1781.56  4789.7 1779.28
    4887 1769.46    4917 1766.42  4940.8 1762.02  4991.8 1755.74  4994.5 1755.24
  4997.8 1755.74  5107.9  1767.1  5129.1 1774.58  5150.3 1778.58  5164.5 1779.12
  5192.8 1787.14    5214 1790.68  5256.4 1792.06  5327.1 1797.08  5497.4 1811.57
  5644.4 1827.68  5733.5  1841.9  5738.5 1841.14  5754.6  1846.2  5804.7 1856.21
  5864.8 1881.06  5901.3 1887.04  5906.3 1884.55  5934.9  1886.2    5959 1890.29
#Mann= 6 ,-1 , 0
  4265.7      .1       0  4413.2     .05       0    4887     .16       0
  4991.8     .07       0  4997.8     .16       0  5497.4      .1       0
Bank Sta=4917,5107.9
XS Rating Curve= 0 ,0
Exp/Cntr=0.3,0.1

Type RM Length L Ch R = 1 ,44370   ,456,456,456
BEGIN DESCRIPTION:
LIVE OAK CREEK 82.0
END DESCRIPTION:
XS GIS Cut Line= 2
      2729685.98      10077768.6      2729487.04     10076308.08
#Sta/Elev= 30
  4288.5 1791.55  4302.8 1789.94  4307.8 1791.28  4343.9 1782.48  4363.2 1779.26
  4380.2 1778.02  4634.3 1778.03  4717.3 1777.34  4752.1 1774.54  4824.5 1765.51
  4858.6 1764.39  4950.4 1756.77  4979.7 1755.09  4996.9 1752.59  4999.6 1752.09
  5002.9 1752.59  5030.2 1754.63  5040.2 1756.78  5046.7 1760.11  5051.7 1760.09
  5060.4 1763.69  5081.7 1769.29  5100.8 1775.05    5119 1782.68  5161.2 1786.66
  5374.6 1802.54  5442.1  1806.6  5575.1 1813.83  5698.3 1818.13  5762.5 1820.92
#Mann= 11 ,-1 , 0
  4288.5     .16       0  4363.2     .05       0  4634.3      .1       0
  4950.4     .05       0  4996.9    .035       0  5002.9     .05       0
  5081.7     .16       0  5161.2      .1       0  5374.6     .16       0
  5442.1      .1       0  5698.3     .05       0
Bank Sta=4858.6,5060.4
XS Rating Curve= 0 ,0
Exp/Cntr=0.3,0.1