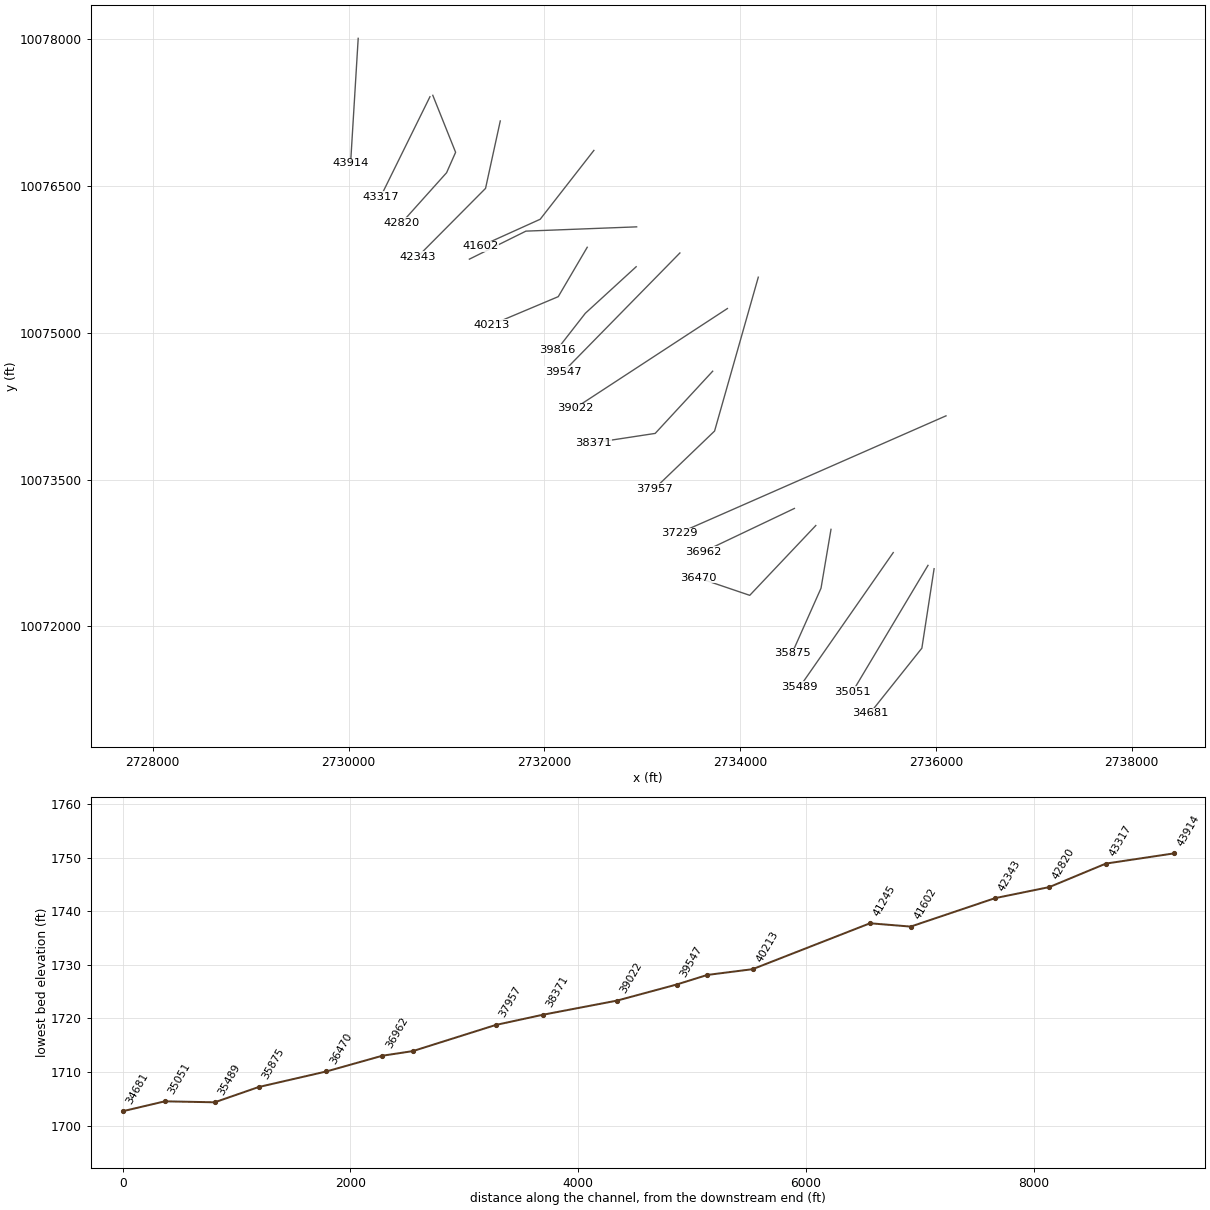
HEC-RAS study LIVE OAK CREEK.prj: LIVE OAK CREEK Base Level Engineering

--- LIVE OAK CREEK.g01 (geometry) --- (continued)

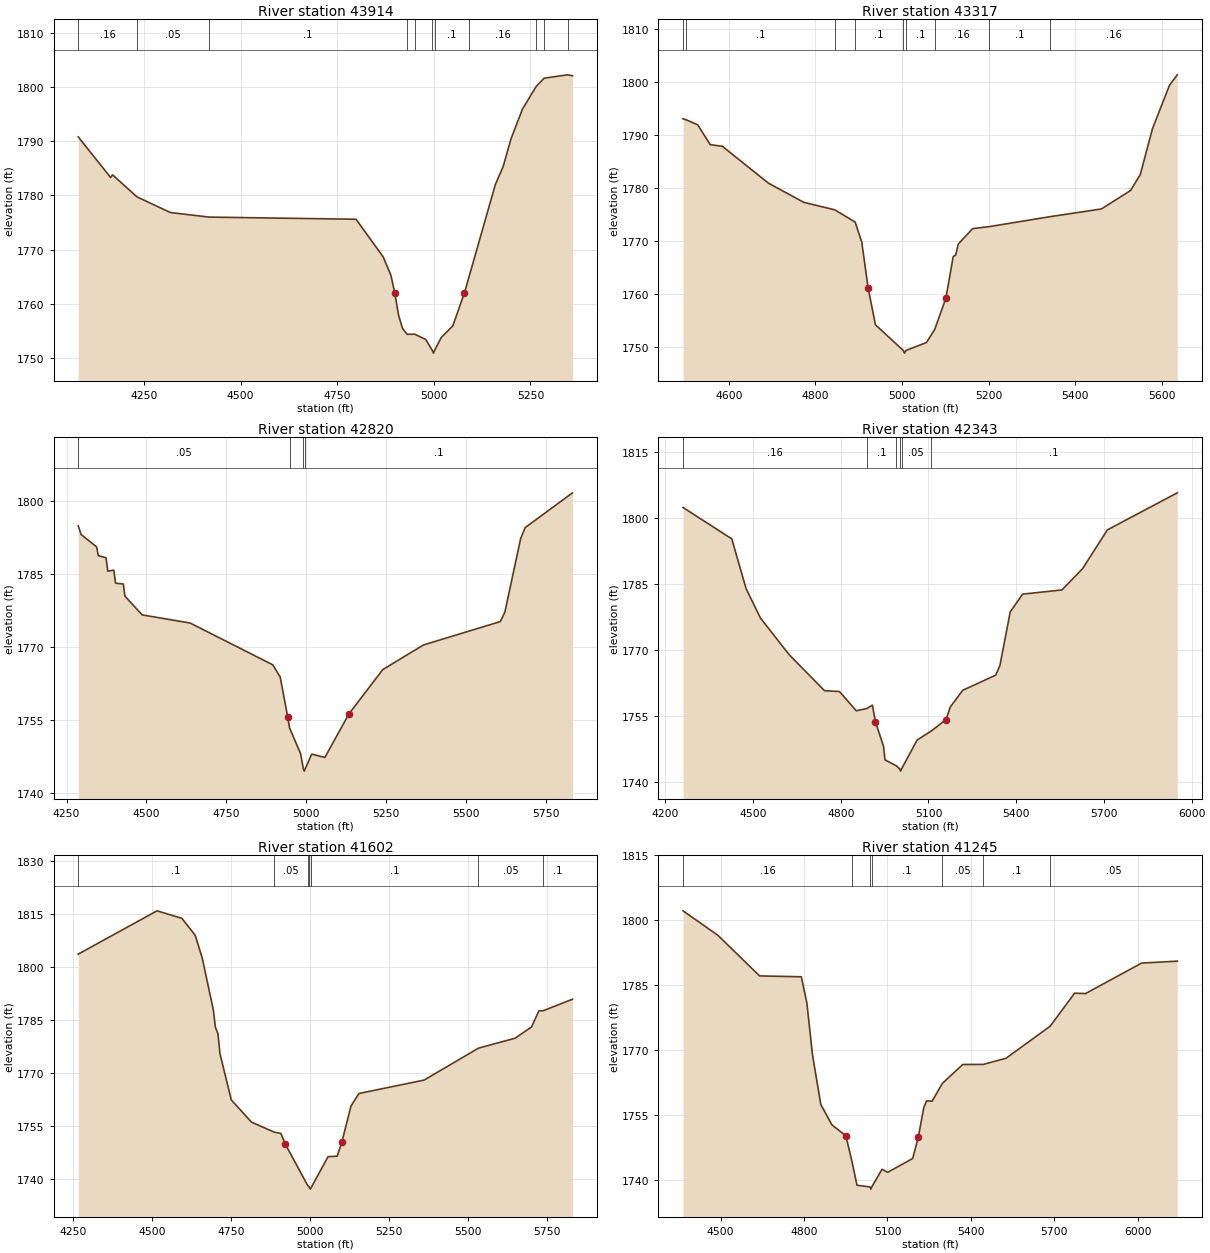
Type RM Length L Ch R = 1 ,43914   ,597,597,597
BEGIN DESCRIPTION:
LIVE OAK CREEK 81.0
END DESCRIPTION:
XS GIS Cut Line= 2
      2730098.62     10078011.35      2730020.94     10076734.51
#Sta/Elev= 30
  4079.7 1790.84  4163.5 1783.32  4168.6 1783.81  4231.7 1779.74  4317.8 1776.85
  4417.3    1776  4798.6  1775.6  4868.8 1768.65  4888.8 1765.26  4898.8 1761.97
  4908.8 1757.83  4918.9 1755.39    4931  1754.3  4950.3 1754.34    4979 1753.36
    4996 1751.33  4998.8 1750.83    5002 1751.33  5019.1 1753.72  5049.1 1755.88
  5079.2 1761.97  5090.3 1764.76  5159.3 1782.05  5179.3 1785.33  5199.4 1790.42
  5229.4 1795.99    5265 1800.18  5285.5  1801.7  5345.9 1802.32  5358.9 1802.15
#Mann= 11 ,-1 , 0
  4079.7     .16       0  4231.7     .05       0  4417.3      .1       0
    4931     .05       0  4950.3      .1       0    4996     .07       0
    5002      .1       0  5090.3     .16       0    5265      .1       0
  5285.5     .16       0  5345.9      .1       0
Bank Sta=4898.8,5079.2
XS Rating Curve= 0 ,0
Exp/Cntr=0.3,0.1

Type RM Length L Ch R = 1 ,43317   ,497,497,497
BEGIN DESCRIPTION:
LIVE OAK CREEK 80.0
END DESCRIPTION:
XS GIS Cut Line= 2
      2730831.68     10077414.21      2730326.79     10076389.88
#Sta/Elev= 30
  4493.9 1793.14  4501.7 1792.93  4527.9    1792  4556.7 1788.26  4584.8 1787.95
  4691.5 1780.98  4773.1 1777.37  4844.3 1775.97  4891.6 1773.66  4906.9 1769.88
  4921.6 1761.22  4938.5 1754.27  5002.9 1749.43  5005.6 1748.93  5008.9 1749.43
  5056.4 1750.93  5075.5 1753.41  5101.3  1759.3  5118.2 1767.16  5123.8 1767.41
  5129.9 1769.51  5163.1 1772.42  5201.2 1772.79  5341.9 1774.67  5460.6 1776.13
    5528 1779.61  5550.5 1782.64  5578.5 1791.25  5617.8 1799.44  5635.9 1801.43
#Mann= 9 ,-1 , 0
  4493.9     .05       0  4501.7      .1       0  4844.3     .05       0
  4891.6      .1       0  5002.9     .07       0  5008.9      .1       0
  5075.5     .16       0  5201.2      .1       0  5341.9     .16       0
Bank Sta=4921.6,5101.3
XS Rating Curve= 0 ,0
Exp/Cntr=0.3,0.1

Type RM Length L Ch R = 1 ,42820   ,477,477,477
BEGIN DESCRIPTION:
LIVE OAK CREEK 79.0
END DESCRIPTION:
XS GIS Cut Line= 4
      2730860.81     10077428.73      2731093.82      10076846.2
      2731001.58     10076637.46      2730540.42     10076122.89
#Sta/Elev= 30
  4286.6 1794.85  4295.6 1793.07    4344 1790.54  4349.4 1788.74  4373.6 1788.29
    4379 1785.56  4397.9 1785.75  4403.3 1783.09  4427.5 1782.92  4432.9 1780.41
  4486.7 1776.58  4636.6 1774.92  4895.1 1766.35  4918.5 1763.85  4941.8 1755.74
  4947.7 1753.42  4982.3 1748.12  4990.9 1745.04  4993.7 1744.54  4996.9 1745.04
  5017.2 1748.03  5058.3 1747.35  5133.7 1756.29  5239.4 1765.36  5366.5 1770.41
  5607.2 1775.21  5621.4 1777.13  5670.9 1792.25  5684.9 1794.48  5833.2 1801.62
#Mann= 4 ,-1 , 0
  4286.6     .05       0  4947.7      .1       0  4990.9     .07       0
  4996.9      .1       0
Bank Sta=4941.8,5133.7
XS Rating Curve= 0 ,0
Exp/Cntr=0.3,0.1

Type RM Length L Ch R = 1 ,42343   ,741,741,741
BEGIN DESCRIPTION:
LIVE OAK CREEK 78.0
END DESCRIPTION:
XS GIS Cut Line= 3
      2731550.16     10077166.61      2731399.66     10076477.25
      2730705.73     10075778.46
#Sta/Elev= 30
  4260.5 1802.47  4427.2 1795.33  4476.3 1783.98  4525.4  1777.3  4623.4 1768.98
  4744.5 1760.77  4795.7 1760.58  4853.2  1756.2  4888.6 1756.71  4908.3 1757.48
  4918.5 1753.72  4946.2 1748.13  4951.3 1745.04  4990.2 1743.68  5001.8 1742.97
  5004.5 1742.47  5007.8 1742.97  5061.3 1749.55  5108.6 1751.56  5160.3 1754.21
  5174.5 1757.06  5216.9 1760.85  5330.1 1764.32  5344.2 1766.48  5379.6 1778.71
    5422 1782.75  5556.3  1783.7    5627 1788.54  5711.9 1797.37  5950.9  1805.8
#Mann= 6 ,-1 , 0
  4260.5     .16       0  4888.6      .1       0  4990.2     .05       0
  5001.8     .04       0  5007.8     .05       0  5108.6      .1       0
Bank Sta=4918.5,5160.3
XS Rating Curve= 0 ,0
Exp/Cntr=0.3,0.1

Type RM Length L Ch R = 1 ,41602   ,357,357,357
BEGIN DESCRIPTION:
LIVE OAK CREEK 77.0
END DESCRIPTION:
XS GIS Cut Line= 3
      2732506.53     10076865.63      2731957.95      10076161.7
      2731346.28     10075884.99
#Sta/Elev= 30
  4267.2 1803.72  4516.5 1815.98  4595.2 1813.85  4637.3 1809.04  4659.5  1802.6
  4694.7 1787.84  4701.1 1782.99  4709.2 1781.19  4715.6  1775.5  4751.4 1762.42
  4815.1 1756.15  4886.7 1753.31  4908.3 1752.94  4922.7 1749.85  4992.6 1738.26
  4998.4 1737.66  5001.2 1737.16  5004.4 1737.66  5057.5 1746.35  5086.5  1746.5
  5100.9 1750.37  5129.9 1760.66  5155.2 1764.24  5361.5 1768.05  5533.5 1777.09
  5649.8 1779.91  5701.5 1783.11  5724.6 1787.68  5737.7 1787.66    5831 1790.95
#Mann= 7 ,-1 , 0
  4267.2      .1       0  4886.7     .05       0  4992.6      .1       0
  4998.4     .07       0  5004.4      .1       0  5533.5     .05       0
  5737.7      .1       0
Bank Sta=4922.7,5100.9
XS Rating Curve= 0 ,0
Exp/Cntr=0.3,0.1

Type RM Length L Ch R = 1 ,41245   ,1032,1032,1032
BEGIN DESCRIPTION:
LIVE OAK CREEK 76.0
END DESCRIPTION:
XS GIS Cut Line= 3
      2732943.43     10076084.03      2731812.31     10076040.33
      2731234.58      10075753.9
#Sta/Elev= 30
  4365.1 1802.14  4490.2  1796.5  4640.3 1787.09  4790.4 1786.89  4810.4 1780.83
  4830.4  1768.9  4860.4 1757.37  4900.5 1752.63  4950.5 1750.12  4972.8 1744.07
  4990.5 1738.68  5037.6 1738.28  5040.3 1737.78  5043.6 1738.28  5080.6 1742.38
  5100.6 1741.66  5190.7 1744.86  5210.7 1749.74  5230.7 1756.64  5240.7 1758.19
  5260.7 1758.12  5297.5 1762.24  5370.8 1766.61  5444.2 1766.62  5526.2 1768.04
  5685.2 1775.47  5772.8 1783.09  5812.1 1783.01  6013.8 1790.06  6141.9  1790.5
#Mann= 7 ,-1 , 0
  4365.1     .16       0  4972.8      .1       0  5037.6     .07       0
  5043.6      .1       0  5297.5     .05       0  5444.2      .1       0
  5685.2     .05       0
Bank Sta=4950.5,5210.7
XS Rating Curve= 0 ,0
Exp/Cntr=0.3,0.1

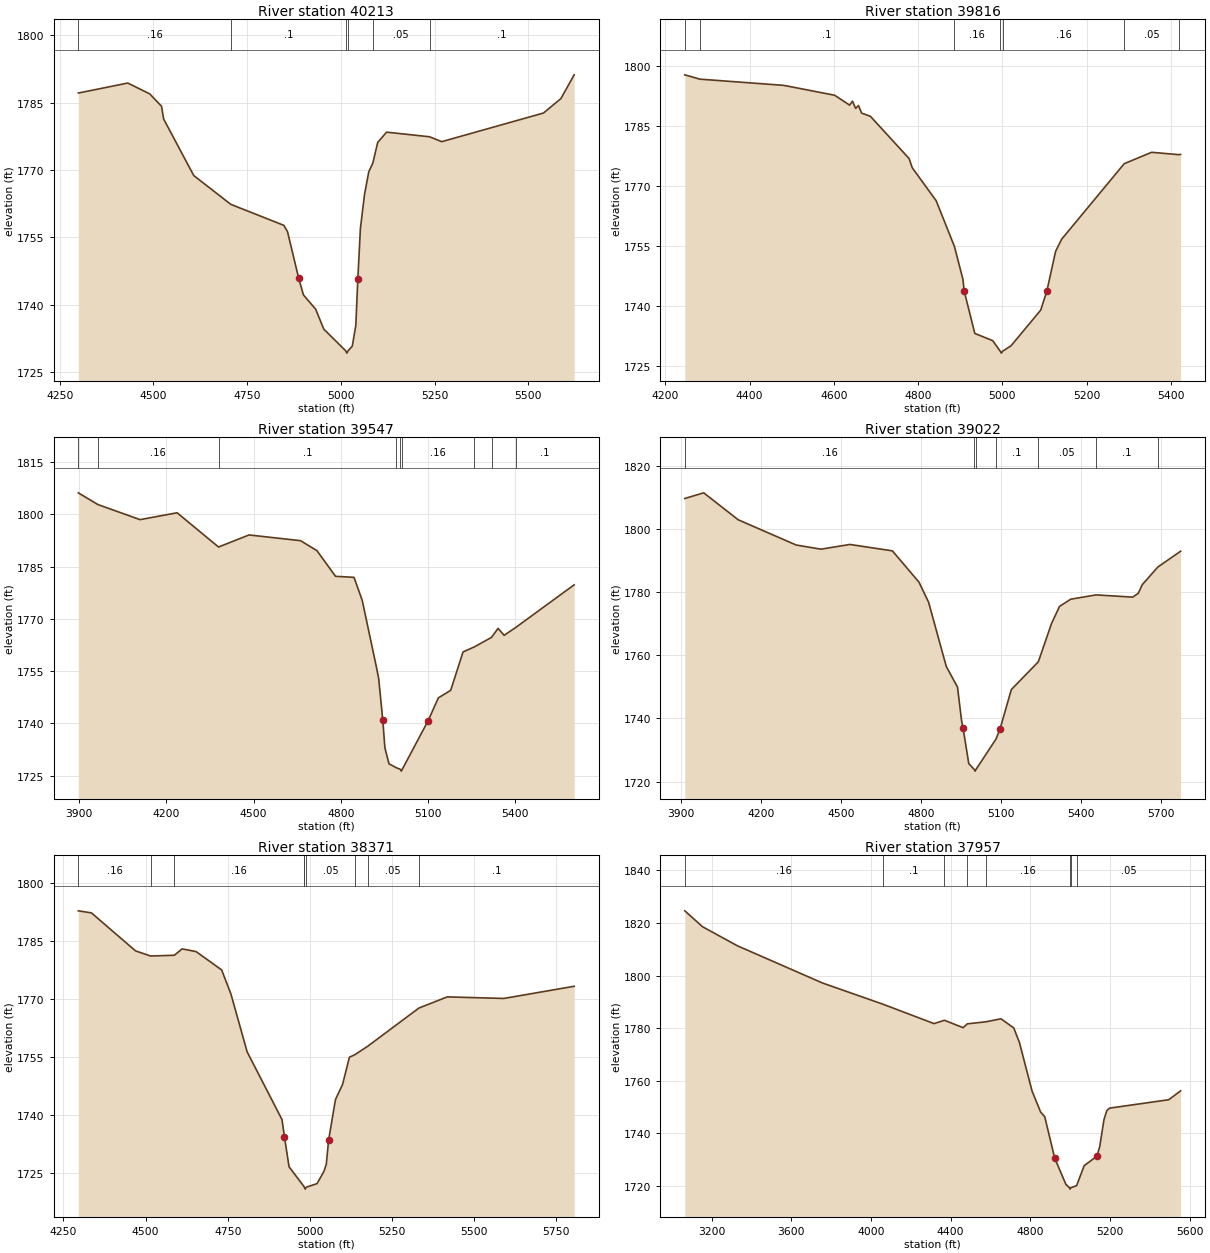
Type RM Length L Ch R = 1 ,40213   ,397,397,397
BEGIN DESCRIPTION:
LIVE OAK CREEK 75.0
END DESCRIPTION:
XS GIS Cut Line= 3
      2732438.55     10075875.26      2732142.42     10075370.39
      2731463.09      10075084.1
#Sta/Elev= 30
  4299.9 1787.14  4431.8 1789.37  4490.4 1786.95  4521.8  1784.2  4527.5 1781.35
  4607.7 1768.77  4706.7 1762.34    4848 1757.67  4857.9 1756.26  4887.3    1746
  4900.3 1742.17  4932.9 1738.99  4954.6 1734.55  5013.3  1729.7    5016  1729.2
  5019.3  1729.7  5030.6 1730.76    5040 1735.34  5045.4  1745.7  5052.3 1756.99
  5063.1 1764.47  5074.6 1769.61  5085.4 1771.52  5098.3 1776.12    5122 1778.43
  5236.6  1777.4  5269.3 1776.31  5540.6 1782.69  5587.1 1785.91  5622.4  1791.2
#Mann= 6 ,-1 , 0
  4299.9     .16       0  4706.7      .1       0  5013.3     .07       0
  5019.3      .1       0  5085.4     .05       0  5236.6      .1       0
Bank Sta=4887.3,5045.4
XS Rating Curve= 0 ,0
Exp/Cntr=0.3,0.1

Type RM Length L Ch R = 1 ,39816   ,269,269,269
BEGIN DESCRIPTION:
LIVE OAK CREEK 74.0
END DESCRIPTION:
XS GIS Cut Line= 3
      2732938.56     10075676.22      2732419.14     10075200.48
      2732128.63     10074827.66
#Sta/Elev= 30
  4246.3 1797.72  4281.9 1796.64  4481.6 1795.08  4601.8 1792.62  4637.6 1790.15
  4644.4 1791.14  4651.8 1789.32  4658.6 1790.04    4666 1788.15  4686.9 1787.35
  4778.8 1776.78  4786.2 1774.49    4843 1766.24  4886.4 1754.79  4906.5  1746.6
 4909.55 1743.63  4934.8 1733.05  4977.2 1731.25    4995 1728.63  4997.8 1728.13
    5001 1728.63  5020.6 1729.95  5091.2 1738.89  5105.7 1743.64  5126.5 1753.57
  5140.9 1756.62  5289.4  1775.5  5354.5 1778.35  5418.4 1777.76  5423.3 1777.83
#Mann= 7 ,-1 , 0
  4246.3     .16       0  4281.9      .1       0  4886.4     .16       0
    4995     .07       0    5001     .16       0  5289.4     .05       0
  5418.4      .1       0
Bank Sta=4909.55,5105.7
XS Rating Curve= 0 ,0
Exp/Cntr=0.3,0.1

Type RM Length L Ch R = 1 ,39547   ,525,525,525
BEGIN DESCRIPTION:
LIVE OAK CREEK 73.0
END DESCRIPTION:
XS GIS Cut Line= 2
      2733385.18     10075816.99      2732192.32     10074599.88
#Sta/Elev= 30
  3897.7 1806.15  3964.9 1802.79  4109.9 1798.46  4237.2 1800.43  4379.6 1790.61
  4484.6 1794.07  4661.4 1792.43  4717.9 1789.56  4781.7 1782.21  4845.2 1781.91
  4873.5  1775.3  4923.1 1755.85  4930.1 1752.85  4944.2 1740.93  4951.4 1733.02
  4965.5 1728.44  4990.6 1727.32    5005 1726.84  5007.7 1726.34    5011 1726.84
  5099.8 1740.77  5135.1 1747.35  5177.6 1749.52    5220 1760.53  5259.3 1761.98
  5317.9  1764.7  5340.3 1767.27  5361.4 1765.28  5403.1 1767.66  5601.9 1779.77
#Mann= 9 ,-1 , 0
  3897.7      .1       0  3964.9     .16       0  4379.6      .1       0
  4990.6     .16       0    5005     .07       0    5011     .16       0
  5259.3      .1       0  5317.9     .05       0  5403.1      .1       0
Bank Sta=4944.2,5099.8
XS Rating Curve= 0 ,0
Exp/Cntr=0.3,0.1

Type RM Length L Ch R = 1 ,39022   ,651,651,651
BEGIN DESCRIPTION:
LIVE OAK CREEK 72.0
END DESCRIPTION:
XS GIS Cut Line= 2
      2733870.65     10075249.01      2732312.89     10074229.92
#Sta/Elev= 30
    3914 1809.69    3985 1811.48  4114.6 1802.94  4331.8 1794.96  4425.2 1793.63
  4533.8 1795.13  4693.4  1793.1  4793.1  1783.2  4829.3 1776.83  4895.7 1756.49
  4937.9 1749.93    4953 1739.38    4959 1736.84  4980.1 1725.73    5001 1723.83
  5003.8 1723.33    5007 1723.83  5082.4 1733.49  5097.7 1736.76  5139.9 1749.15
  5241.3 1757.97  5290.8 1770.08  5320.9 1775.51    5363 1777.79  5458.1 1779.15
  5595.3 1778.44  5616.4 1779.64  5631.5 1782.39  5689.9 1787.97  5775.5 1792.99
#Mann= 7 ,-1 , 0
    3914     .16       0    5001     .07       0    5007     .16       0
  5082.4      .1       0  5241.3     .05       0  5458.1      .1       0
  5689.9     .05       0
Bank Sta=4959,5097.7
XS Rating Curve= 0 ,0
Exp/Cntr=0.3,0.1

Type RM Length L Ch R = 1 ,38371   ,414,414,414
BEGIN DESCRIPTION:
LIVE OAK CREEK 71.0
END DESCRIPTION:
XS GIS Cut Line= 3
      2733720.21     10074608.25      2733132.77     10073972.26
      2732496.82     10073875.17
#Sta/Elev= 30
  4295.3 1792.88  4335.1 1792.35  4469.5 1782.49    4515 1781.16  4587.5 1781.35
  4611.2 1783.01  4653.8  1782.3  4731.5 1777.55  4759.8 1771.29  4809.1  1756.3
  4915.2 1738.73  4922.5 1734.33  4936.7 1726.48  4981.8  1721.4  4983.1 1721.19
  4985.8 1720.69  4989.1 1721.19  5021.8 1722.12  5042.8 1725.29  5050.1 1727.18
  5056.9 1733.32  5077.9 1743.91  5099.5 1747.84  5120.4 1754.91  5136.2 1755.52
  5175.9 1757.74  5331.9 1767.66  5418.3 1770.56  5590.3 1770.15  5804.4 1773.31
#Mann= 9 ,-1 , 0
  4295.3     .16       0    4515      .1       0  4587.5     .16       0
  4981.8     .05       0  4983.1     .04       0  4989.1     .05       0
  5136.2      .1       0  5175.9     .05       0  5331.9      .1       0
Bank Sta=4922.5,5056.9
XS Rating Curve= 0 ,0
Exp/Cntr=0.3,0.1

Type RM Length L Ch R = 1 ,37957   ,728,728,728
BEGIN DESCRIPTION:
LIVE OAK CREEK 70.0
END DESCRIPTION:
XS GIS Cut Line= 3
      2734186.22      10075569.4       2733739.6     10073996.53
      2733123.26     10073404.45
#Sta/Elev= 30
  3065.1  1824.6  3154.1 1818.56  3328.6 1811.33  3757.1 1797.14  4058.4 1789.14
  4316.6 1781.72  4368.9 1782.99  4462.5 1780.16  4483.8 1781.63    4576 1782.39
  4652.8 1783.55    4717 1780.06  4745.3 1774.55  4809.1 1756.01  4851.5 1748.14
  4872.6 1746.29  4922.3 1730.63  4978.9 1720.56    4997 1719.28  4999.7 1718.78
    5003 1719.28  5032.4 1720.11  5070.7 1727.71  5134.3 1731.31  5148.4 1734.84
  5169.8 1745.17  5183.9 1748.59  5198.1 1749.58    5495 1752.77  5554.8 1756.16
#Mann= 8 ,-1 , 0
  3065.1     .16       0  4058.4      .1       0  4368.9     .16       0
  4483.8      .1       0    4576     .16       0    4997     .07       0
    5003     .16       0  5032.4     .05       0
Bank Sta=4922.3,5134.3
XS Rating Curve= 0 ,0
Exp/Cntr=0.3,0.1

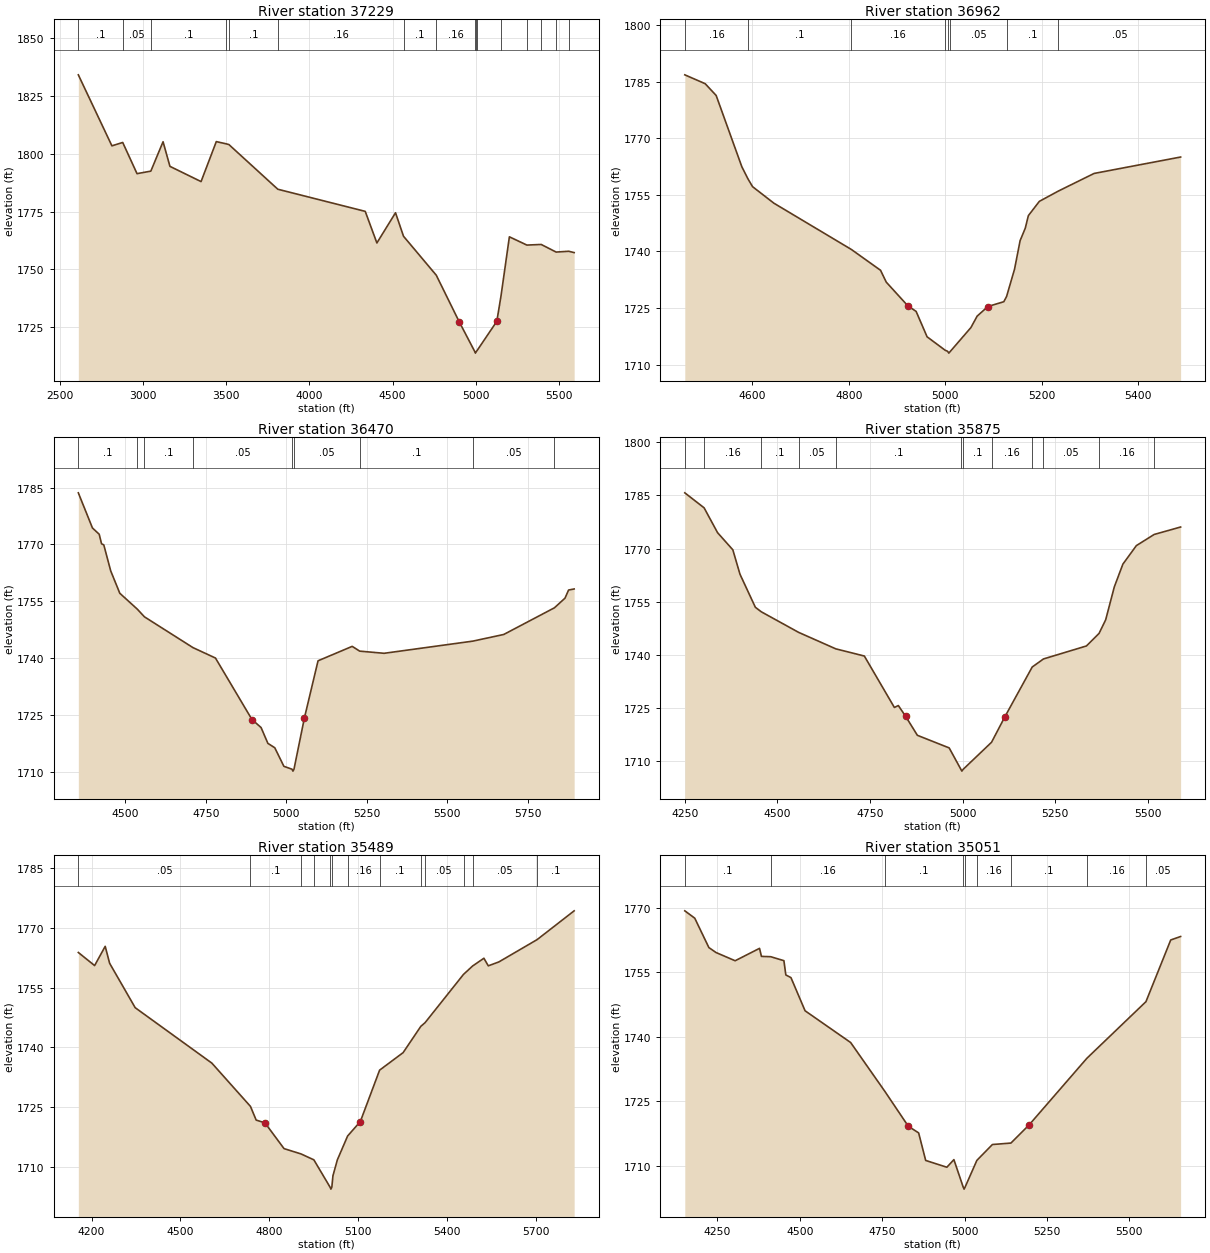
Type RM Length L Ch R = 1 ,37229   ,267,267,267
BEGIN DESCRIPTION:
LIVE OAK CREEK 69.0
END DESCRIPTION:
XS GIS Cut Line= 2
       2736103.8     10074151.88      2733375.48     10072952.77
#Sta/Elev= 30
  2611.2 1833.97    2813 1803.33    2878 1804.79    2964 1791.33    3047 1792.42
  3120.5  1805.1  3161.8 1794.48  3348.9 1787.91  3440.5 1805.16  3498.3 1804.22
  3516.1 1803.89  3810.2 1784.61  4335.7 1775.06  4405.7 1761.43  4517.7 1774.46
  4565.7 1764.33  4762.8  1747.5    4900  1727.5  4995.3  1714.4    4998  1713.9
  5001.3  1714.4    5008 1715.01  5126.6 1727.62  5151.5 1738.46  5202.1 1764.08
  5307.2 1760.52  5393.4 1760.78  5483.1  1757.5  5558.2 1757.85  5591.4 1757.27
#Mann= 16 ,-1 , 0
  2611.2      .1       0    2878     .05       0    3047      .1       0
  3498.3     .16       0  3516.1      .1       0  3810.2     .16       0
  4565.7      .1       0  4762.8     .16       0  4995.3     .07       0
  5001.3     .16       0    5008     .05       0  5151.5      .1       0
  5307.2     .05       0  5393.4      .1       0  5483.1     .05       0
  5558.2      .1       0
Bank Sta=4900,5126.6
XS Rating Curve= 0 ,0
Exp/Cntr=0.3,0.1

Type RM Length L Ch R = 1 ,36962   ,492,492,492
BEGIN DESCRIPTION:
LIVE OAK CREEK 68.0
END DESCRIPTION:
XS GIS Cut Line= 2
      2734555.19     10073205.23      2733627.95     10072763.46
#Sta/Elev= 30
  4460.3 1786.84  4502.6 1784.48  4525.3 1781.36  4578.5 1762.45  4591.4 1759.19
  4600.7 1757.18    4645 1752.79  4805.6 1740.51  4865.8 1735.01  4877.6 1731.87
  4922.3 1725.59  4939.5  1724.1  4962.2 1717.37  4999.6 1713.81  5004.6 1713.54
  5007.3 1713.04  5010.6 1713.54    5053 1719.82  5065.9 1722.85  5088.1  1725.4
  5121.1 1726.67  5126.9 1728.07  5143.4 1735.32  5154.9 1742.87  5165.6 1746.17
    5172  1749.5  5194.7 1753.28  5233.9    1756  5308.2 1760.69  5487.4 1765.04
#Mann= 8 ,-1 , 0
  4460.3     .16       0  4591.4      .1       0  4805.6     .16       0
  4999.6     .05       0  5004.6     .04       0  5010.6     .05       0
  5126.9      .1       0  5233.9     .05       0
Bank Sta=4922.3,5088.1
XS Rating Curve= 0 ,0
Exp/Cntr=0.3,0.1

Type RM Length L Ch R = 1 ,36470   ,595,595,595
BEGIN DESCRIPTION:
LIVE OAK CREEK 67.0
END DESCRIPTION:
XS GIS Cut Line= 3
      2734773.61     10073030.43      2734098.84     10072316.83
       2733571.6      10072495.8
#Sta/Elev= 30
  4354.5  1783.6  4398.3 1774.32  4419.3 1772.66  4426.6 1770.13  4433.5 1769.86
  4454.9 1763.01  4483.2 1757.08  4537.5 1752.88  4559.7 1750.85  4710.3 1742.72
  4780.1 1739.97  4893.4 1723.73  4921.7 1721.61  4942.8 1717.43  4964.2 1716.28
  4992.5 1711.37  5017.8  1710.6  5020.6  1710.1  5023.8  1710.6    5056 1724.07
  5098.5 1739.24  5204.5 1743.05  5227.8 1741.79  5303.6 1741.22  5578.8 1744.43
  5674.9 1746.19  5832.1 1753.23    5865 1755.78  5876.1 1757.93  5893.4 1758.21
#Mann= 9 ,-1 , 0
  4354.5      .1       0  4537.5     .16       0  4559.7      .1       0
  4710.3     .05       0  5017.8     .04       0  5023.8     .05       0
  5227.8      .1       0  5578.8     .05       0  5832.1      .1       0
Bank Sta=4893.4,5056
XS Rating Curve= 0 ,0
Exp/Cntr=0.3,0.1

Type RM Length L Ch R = 1 ,35875   ,386,386,386
BEGIN DESCRIPTION:
LIVE OAK CREEK 66.0
END DESCRIPTION:
XS GIS Cut Line= 3
      2734928.98      10072991.6      2734827.04     10072389.65
      2734530.89     10071724.52
#Sta/Elev= 30
    4250 1785.74  4302.1 1781.51  4338.5 1774.49  4379.7 1769.65  4398.9 1762.79
  4440.5 1753.43  4456.7 1752.15  4557.2 1746.36  4657.7  1741.7  4734.7 1739.68
  4815.8 1725.16  4826.5  1725.7  4846.2 1722.66  4877.9  1717.3  4963.8 1713.74
  4995.4 1707.69  4998.1 1707.19  5001.4 1707.69  5078.1 1715.33  5114.2 1722.54
  5187.9 1736.57  5218.3 1738.85  5334.3 1742.52  5368.4 1746.06  5386.3 1749.91
  5409.5 1759.16  5432.7 1765.61  5469.1 1770.84  5517.2 1773.99  5588.6 1776.09
#Mann= 12 ,-1 , 0
    4250      .1       0  4302.1     .16       0  4456.7      .1       0
  4557.2     .05       0  4657.7      .1       0  4995.4     .07       0
  5001.4      .1       0  5078.1     .16       0  5187.9      .1       0
  5218.3     .05       0  5368.4     .16       0  5517.2      .1       0
Bank Sta=4846.2,5114.2
XS Rating Curve= 0 ,0
Exp/Cntr=0.3,0.1

Type RM Length L Ch R = 1 ,35489   ,438,438,438
BEGIN DESCRIPTION:
LIVE OAK CREEK 65.0
END DESCRIPTION:
XS GIS Cut Line= 2
      2735564.94     10072753.74      2734608.55     10071379.84
#Sta/Elev= 30
  4155.2 1763.87  4210.2 1760.58  4245.9 1765.42  4260.8 1761.17  4347.2 1749.98
    4606 1736.04  4736.4 1725.15  4755.6 1721.71  4785.3 1721.01  4849.7 1714.53
  4906.9  1713.2  4950.4 1711.71  5005.1 1704.84  5007.9 1704.34  5011.1 1704.84
  5014.8  1707.7  5029.7  1711.7  5064.4 1717.71  5107.3 1721.34  5172.4 1734.27
  5251.8 1738.68  5311.6  1745.3  5325.6 1746.19  5455.6 1758.36  5486.3 1760.47
  5524.5 1762.42  5539.3 1760.51  5575.1  1761.5    5704  1767.1  5829.2 1774.35
#Mann= 13 ,-1 , 0
  4155.2     .05       0  4736.4      .1       0  4906.9     .05       0
  4950.4      .1       0  5005.1     .07       0  5011.1      .1       0
  5064.4     .16       0  5172.4      .1       0  5311.6     .16       0
  5325.6     .05       0  5455.6      .1       0  5486.3     .05       0
    5704      .1       0
Bank Sta=4785.3,5107.3
XS Rating Curve= 0 ,0
Exp/Cntr=0.3,0.1

Type RM Length L Ch R = 1 ,35051   ,370,370,370
BEGIN DESCRIPTION:
Mapping XS 0735aeb2
END DESCRIPTION:
XS GIS Cut Line= 2
      2735919.87     10072623.05      2735149.04     10071331.38
#Sta/Elev= 30
  4151.3 1769.34  4181.5 1767.63  4224.3 1760.79  4245.7 1759.64  4304.1 1757.71
    4378  1760.6  4383.8 1758.73  4412.1 1758.65    4452 1757.73  4457.8 1754.41
  4473.4 1753.78  4516.2 1746.06  4654.4 1738.67  4758.5 1727.26  4829.5 1719.15
  4860.7 1717.62  4882.1  1711.2  4946.3 1709.62  4967.7 1711.39  4995.8 1705.02
  4998.6 1704.52  5001.8 1705.02  5037.4 1711.22  5084.5 1714.91  5140.7 1715.25
  5195.4 1719.44  5370.9 1734.98  5550.3 1748.18  5625.5 1762.55  5655.5 1763.36
#Mann= 9 ,-1 , 0
  4151.3      .1       0  4412.1     .16       0  4758.5      .1       0
  4995.8     .07       0  5001.8      .1       0  5037.4     .16       0
  5140.7      .1       0  5370.9     .16       0  5550.3     .05       0
Bank Sta=4829.5,5195.4
XS Rating Curve= 0 ,0
Exp/Cntr=0.3,0.1

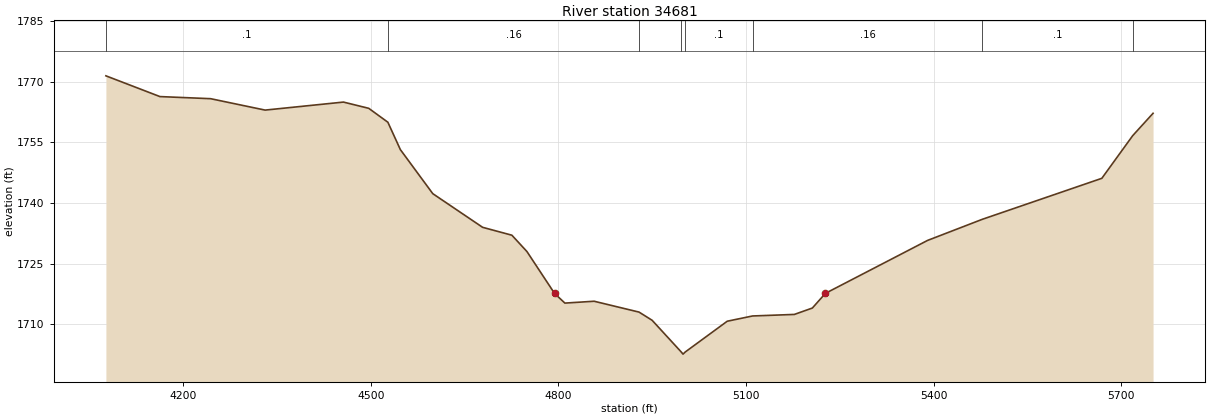
Type RM Length L Ch R = 1 ,34681   ,449,449,449
BEGIN DESCRIPTION:
LIVE OAK CREEK 64.0
END DESCRIPTION:
XS GIS Cut Line= 3
      2735982.36     10072589.17      2735857.36     10071776.68
      2735326.11     10071110.01
#Sta/Elev= 30
  4076.3 1771.45  4162.7 1766.32  4243.7  1765.8  4330.9 1762.98  4456.2 1764.96
  4496.6 1763.42  4527.2 1759.98  4547.2 1753.21    4599 1742.33  4678.7 1734.01
  4725.5 1732.06  4749.6 1728.02  4793.8 1717.66  4810.3 1715.28    4857 1715.74
  4928.8 1713.06  4949.8 1711.03  4996.5 1703.17  4999.2 1702.67  5002.5 1703.17
  5069.9  1710.8  5110.4  1712.1  5177.2 1712.48    5206 1714.06  5226.9 1717.69
  5390.2 1730.77  5477.8 1735.99  5668.9 1746.12  5718.3 1756.67  5750.8 1762.19
#Mann= 8 ,-1 , 0
  4076.3      .1       0  4527.2     .16       0  4928.8      .1       0
  4996.5     .07       0  5002.5      .1       0  5110.4     .16       0
  5477.8      .1       0  5718.3     .05       0
Bank Sta=4793.8,5226.9
XS Rating Curve= 0 ,0
Exp/Cntr=0.3,0.1