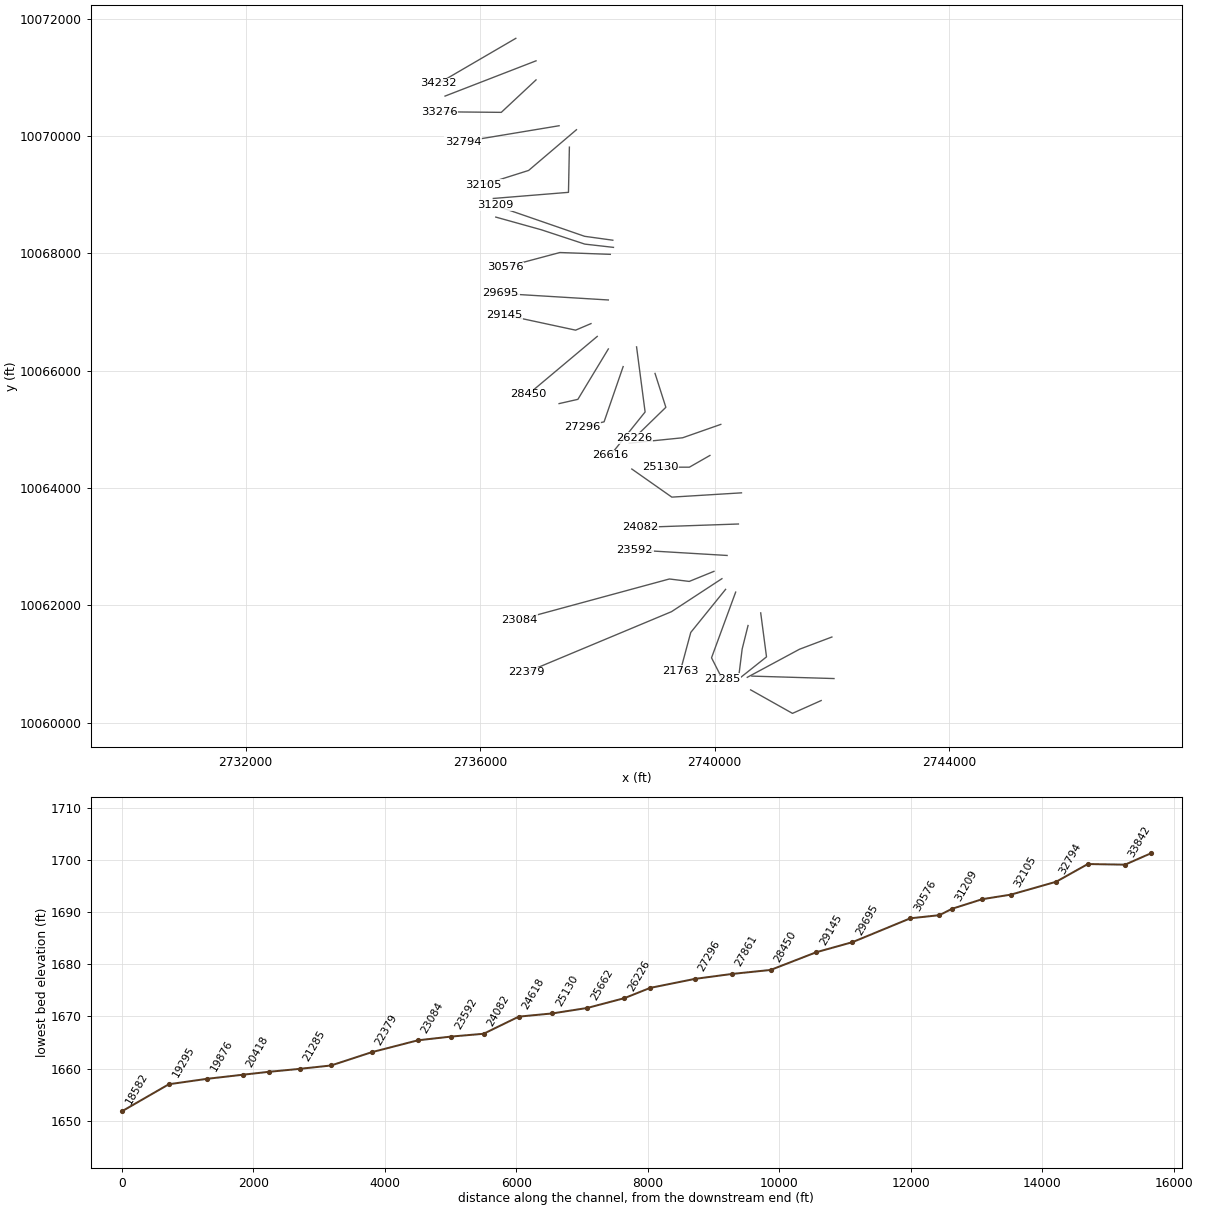
HEC-RAS study LIVE OAK CREEK.prj: LIVE OAK CREEK Base Level Engineering

--- LIVE OAK CREEK.g01 (geometry) --- (continued)

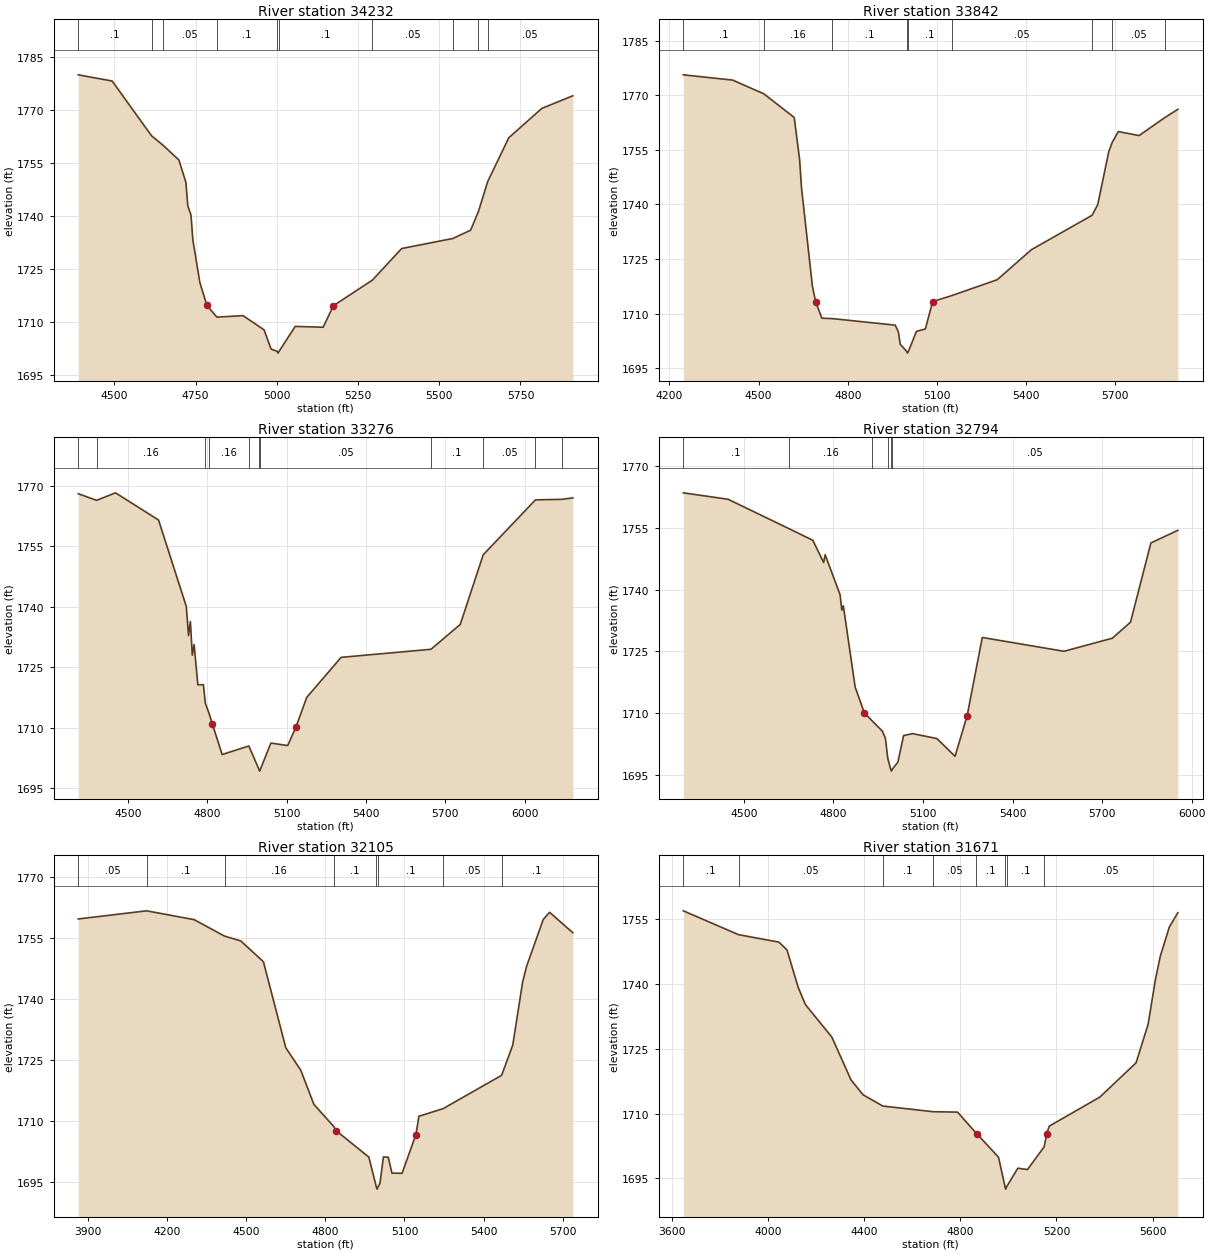
Type RM Length L Ch R = 1 ,34232   ,390,390,390
BEGIN DESCRIPTION:
LIVE OAK CREEK 63.0
END DESCRIPTION:
XS GIS Cut Line= 2
      2736608.68      10071666.3      2735293.31     10070899.41
#Sta/Elev= 30
  4388.6 1779.83    4493 1778.08  4614.1 1762.64  4650.9 1759.86  4698.5 1755.79
    4720 1749.47  4725.8 1742.91  4735.7 1740.22  4741.5 1733.15    4763 1721.21
  4784.5 1714.76  4815.4 1711.45  4896.2 1711.85  4960.7 1707.85  4982.2 1702.44
  5000.7 1701.78  5003.4 1701.28  5006.7 1701.78  5056.6 1708.82  5142.6 1708.59
  5174.1 1714.66  5294.1 1721.88  5384.3  1730.8    5542 1733.64  5596.7 1735.99
  5620.8  1741.3  5649.3 1749.73  5714.1 1762.07  5815.8 1770.35  5911.2 1773.92
#Mann= 10 ,-1 , 0
  4388.6      .1       0  4614.1     .16       0  4650.9     .05       0
  4815.4      .1       0  5000.7     .07       0  5006.7      .1       0
  5294.1     .05       0    5542      .1       0  5620.8     .16       0
  5649.3     .05       0
Bank Sta=4784.5,5174.1
XS Rating Curve= 0 ,0
Exp/Cntr=0.3,0.1

Type RM Length L Ch R = 1 ,33842   ,566,566,566
BEGIN DESCRIPTION:
LIVE OAK CREEK 62.0
END DESCRIPTION:
XS GIS Cut Line= 2
      2736953.39      10071282.8      2735401.71     10070681.52
#Sta/Elev= 30
  4246.5 1775.62  4412.6 1774.17  4517.6  1770.4  4619.7 1763.89  4637.9 1752.29
  4644.2 1744.58  4680.8 1717.56  4691.5 1713.28  4712.9 1708.72  4746.3 1708.62
  4959.6 1706.81  4970.3 1704.93  4976.5 1701.55  4998.1 1699.62  5000.8 1699.12
  5004.1 1699.62    5031 1705.11  5060.9 1705.75  5085.5 1713.29  5149.7 1714.93
  5302.8  1719.3  5417.8 1727.55    5622 1737.01  5641.1 1739.95  5678.1 1754.49
  5689.5 1757.01  5710.3 1760.02    5780 1758.92  5867.7 1763.92  5910.6 1766.14
#Mann= 9 ,-1 , 0
  4246.5      .1       0  4517.6     .16       0  4746.3      .1       0
  4998.1     .07       0  5004.1      .1       0  5149.7     .05       0
    5622     .16       0  5689.5     .05       0  5867.7      .1       0
Bank Sta=4691.5,5085.5
XS Rating Curve= 0 ,0
Exp/Cntr=0.3,0.1

Type RM Length L Ch R = 1 ,33276   ,482,482,482
BEGIN DESCRIPTION:
LIVE OAK CREEK 61.0
END DESCRIPTION:
XS GIS Cut Line= 3
      2736953.37     10070957.53       2736361.1      10070404.1
      2735303.15     10070413.81
#Sta/Elev= 30
    4313 1768.07  4382.4 1766.43  4453.7 1768.29  4616.4 1761.54  4721.3 1740.07
  4729.7 1732.88  4736.6 1736.36  4743.9 1728.02  4750.7 1730.63  4764.9 1720.67
  4785.9 1720.68  4793.1 1716.09  4806.8 1713.66  4819.6 1710.93  4856.7 1703.36
  4957.5 1705.48  4995.4 1699.74  4998.2 1699.24  5001.4 1699.74  5040.9  1706.2
  5104.4 1705.59  5136.2 1710.28  5176.2 1717.53  5306.2 1727.47  5645.6 1729.47
  5756.3 1735.63  5843.1 1752.92  6040.5 1766.55  6139.3 1766.67  6181.6 1767.04
#Mann= 11 ,-1 , 0
    4313     .05       0  4382.4     .16       0  4793.1      .1       0
  4806.8     .16       0  4957.5     .05       0  4995.4    .035       0
  5001.4     .05       0  5645.6      .1       0  5843.1     .05       0
  6040.5     .16       0  6139.3     .05       0
Bank Sta=4819.6,5136.2
XS Rating Curve= 0 ,0
Exp/Cntr=0.3,0.1

Type RM Length L Ch R = 1 ,32794   ,689,689,689
BEGIN DESCRIPTION:
LIVE OAK CREEK 60.0
END DESCRIPTION:
XS GIS Cut Line= 2
      2737346.61     10070175.93      2735712.03     10069904.31
#Sta/Elev= 30
  4296.8 1763.53    4447 1761.96  4650.4 1754.83  4730.8 1751.98    4767 1746.58
  4772.1 1748.47  4822.1 1738.74  4827.9 1735.01    4833 1736.05  4872.7 1716.25
  4903.1 1710.07  4929.6 1708.05    4964 1705.55  4974.1  1703.8  4981.7 1699.03
  4991.4 1696.34  4994.1 1695.84  4997.4 1696.34  5015.8 1698.04  5034.9  1704.5
  5065.3 1704.96  5146.4 1703.76  5207.3 1699.45  5247.8 1709.34  5298.5 1728.35
  5572.2 1724.99  5734.4 1728.17  5795.2 1732.08  5863.5 1751.34  5953.8 1754.42
#Mann= 6 ,-1 , 0
  4296.8      .1       0  4650.4     .16       0  4929.6      .1       0
  4981.7     .05       0  4991.4    .035       0  4997.4     .05       0
Bank Sta=4903.1,5247.8
XS Rating Curve= 0 ,0
Exp/Cntr=0.3,0.1

Type RM Length L Ch R = 1 ,32105   ,434,434,434
BEGIN DESCRIPTION:
LIVE OAK CREEK 59.0
END DESCRIPTION:
XS GIS Cut Line= 3
       2737642.7     10070107.94      2736827.15     10069413.75
      2736061.74     10069171.54
#Sta/Elev= 30
    3864 1759.69  4122.7 1761.69  4302.9 1759.53  4418.1 1755.49    4480 1754.29
  4565.6 1749.19  4650.3 1728.08  4707.4 1722.52  4756.8 1714.17  4832.2 1708.75
  4841.3  1707.7  4965.1 1701.23  4993.5 1693.87  4996.3 1693.37  4999.5 1693.87
    5007 1694.76  5020.3 1701.28  5038.5 1701.21  5052.6  1697.3  5090.9 1697.25
  5143.4 1706.77  5154.8 1711.26  5246.5 1713.13  5468.1 1721.31  5510.2  1728.7
  5547.7 1744.21  5562.9 1748.11  5625.9 1759.58  5649.9 1761.33  5737.8 1756.32
#Mann= 8 ,-1 , 0
    3864     .05       0  4122.7      .1       0  4418.1     .16       0
  4832.2      .1       0  4993.5     .07       0  4999.5      .1       0
  5246.5     .05       0  5468.1      .1       0
Bank Sta=4841.3,5143.4
XS Rating Curve= 0 ,0
Exp/Cntr=0.3,0.1

Type RM Length L Ch R = 1 ,31671   ,462,462,462
BEGIN DESCRIPTION:
LIVE OAK CREEK 58.0
END DESCRIPTION:
XS GIS Cut Line= 3
      2737522.17     10069811.09      2737506.55     10069040.22
       2736225.3     10068936.05
#Sta/Elev= 30
  3648.6 1756.98  3878.7 1751.45    4046 1749.73  4079.7 1747.94  4126.1 1739.28
  4156.1 1735.28  4266.1 1727.74  4346.1  1717.8  4396.1 1714.36  4478.1 1711.75
    4687 1710.44  4788.9 1710.34  4864.1 1705.63  4869.2 1705.34  4959.5 1699.88
  4986.6    1693  4989.3  1692.5  4992.6    1693  5039.7 1697.35  5079.9 1697.04
    5149 1702.29  5160.1 1705.38  5170.2 1707.09  5380.9 1713.83  5531.4 1721.77
  5581.5  1730.7  5611.6 1740.99  5631.7 1746.36  5669.4 1753.19  5705.1 1756.55
#Mann= 8 ,-1 , 0
  3648.6      .1       0  3878.7     .05       0  4478.1      .1       0
    4687     .05       0  4864.1      .1       0  4986.6     .07       0
  4992.6      .1       0    5149     .05       0
Bank Sta=4869.2,5160.1
XS Rating Curve= 0 ,0
Exp/Cntr=0.3,0.1

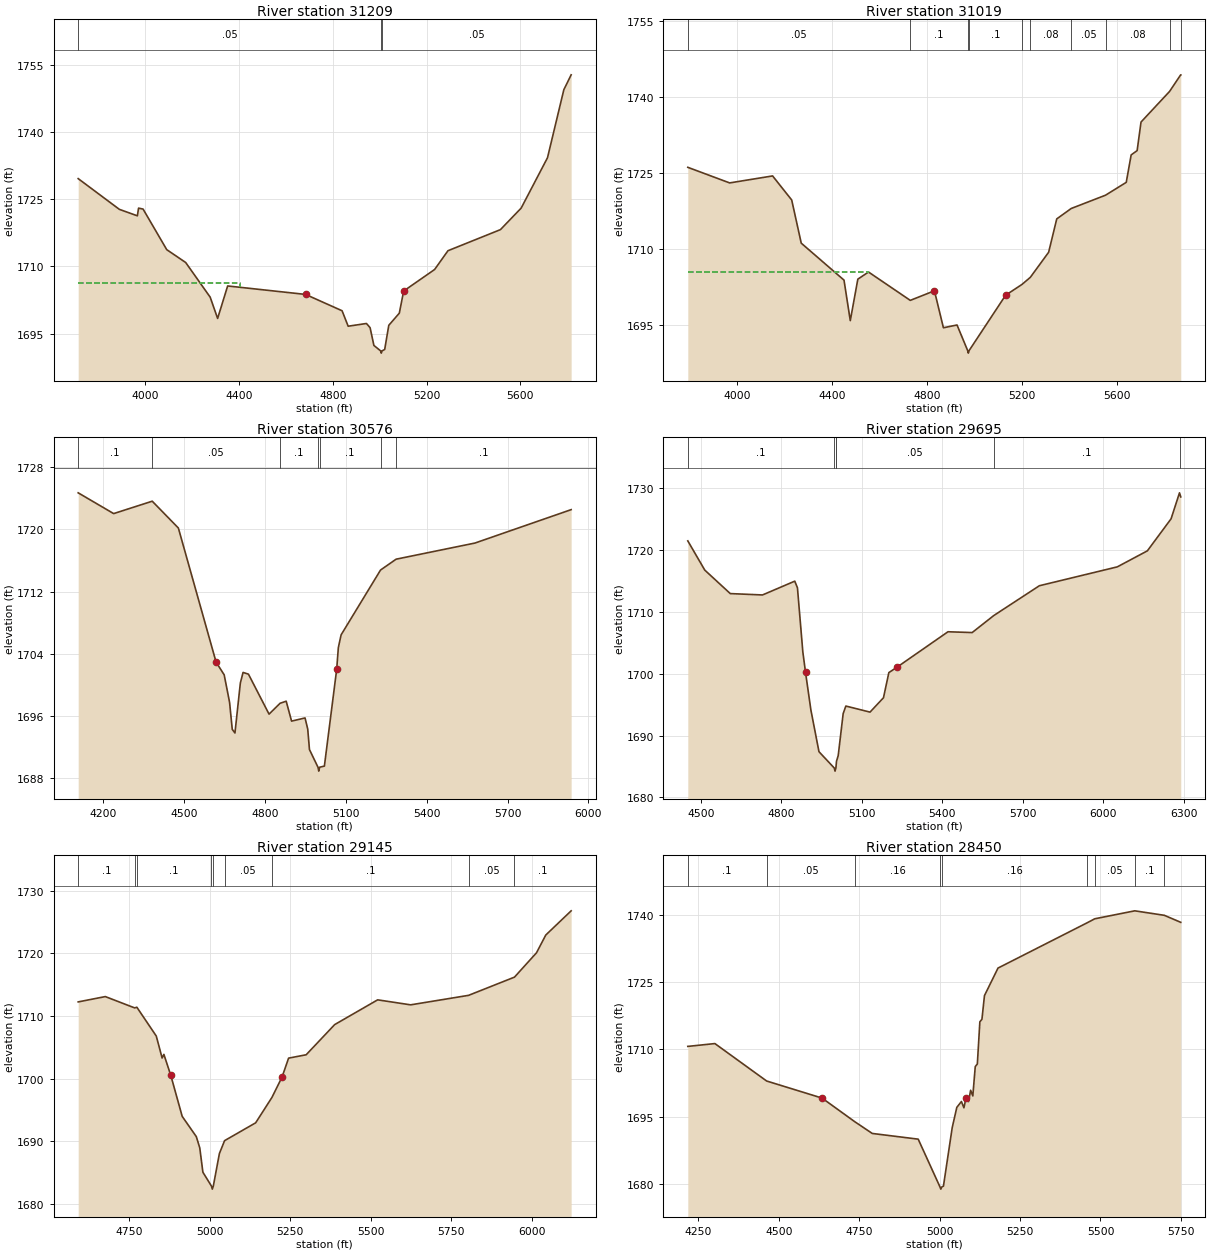
Type RM Length L Ch R = 1 ,31209   ,190,190,190
BEGIN DESCRIPTION:
LIVE OAK CREEK 57.0
END DESCRIPTION:
XS GIS Cut Line= 4
      2738262.64     10068223.98      2737781.82     10068290.56
       2736797.9     10068630.86      2736253.05     10068818.61
#Sta/Elev= 30
  3713.9 1729.62  3889.5 1722.76  3966.4 1721.31  3971.4 1723.03  3990.7 1722.82
  4091.6 1713.76  4172.4 1710.89  4276.9 1703.15  4308.7  1698.4  4351.5 1705.65
  4683.8 1703.76  4839.6 1700.11  4865.5 1696.66  4943.5 1697.27    4959 1696.34
  4975.3 1692.37    5004 1691.15  5006.8 1690.65    5010 1691.15  5021.3 1691.46
  5038.8 1696.86  5083.7 1699.57  5102.3 1704.52  5234.2 1709.32  5291.3 1713.52
  5515.1 1718.23  5603.5 1723.04  5715.8 1734.28  5785.5 1749.47  5816.7  1752.8
#Mann= 3 ,-1 , 0
  3713.9     .05       0    5004     .04       0    5010     .05       0
#XS Ineff= 2 , 0
         4406.25 1706.21
Permanent Ineff=
       T       T
Bank Sta=4683.8,5102.3
XS Rating Curve= 0 ,0
Exp/Cntr=0.3,0.1

Type RM Length L Ch R = 1 ,31019   ,443,443,443
BEGIN DESCRIPTION:
LIVE OAK CREEK 56.0
END DESCRIPTION:
XS GIS Cut Line= 4
      2738273.78     10068101.91      2737785.52     10068157.39
      2737042.16     10068402.35      2736266.97     10068618.34
#Sta/Elev= 30
  3792.1 1726.13  3968.5 1723.05  4149.7 1724.43  4230.2 1719.68  4270.5 1711.15
  4450.8 1703.85  4477.3 1695.85  4509.1 1704.04  4554.2 1705.45  4730.3 1699.85
  4832.1 1701.74    4870 1694.44  4927.4 1694.99  4972.3 1689.93  4975.1 1689.43
  4978.3 1689.93  5132.3 1700.86  5201.6 1703.01  5236.5  1704.4  5313.7 1709.35
  5347.9 1715.94    5409    1718  5553.5 1720.62    5641 1723.16  5661.7 1728.58
  5686.9 1729.43  5703.3 1735.07  5823.7 1741.12  5870.6  1744.4  5870.9  1744.4
#Mann= 10 ,-1 , 0
  3792.1     .05       0  4730.3      .1       0  4972.3     .07       0
  4978.3      .1       0  5201.6     .05       0  5236.5     .08       0
    5409     .05       0  5553.5     .08       0  5823.7     .05       0
  5870.6     .08       0
#XS Ineff= 2 , 0
          4555.4 1705.49
Permanent Ineff=
       T       T
Bank Sta=4832.1,5132.3
XS Rating Curve= 0 ,0
Exp/Cntr=0.3,0.1

Type RM Length L Ch R = 1 ,30576   ,881,881,881
BEGIN DESCRIPTION:
LIVE OAK CREEK 55.0
END DESCRIPTION:
XS GIS Cut Line= 3
      2738220.12     10067982.93      2737360.71     10068014.18
      2736423.34     10067764.21
#Sta/Elev= 30
  4106.1 1724.73  4237.8 1722.05    4381 1723.65    4478 1720.19  4618.1 1702.89
  4648.1 1701.25  4668.1 1697.71  4678.1 1694.22  4688.1 1693.75  4708.1 1700.19
  4718.2 1701.56  4738.2 1701.34  4814.7 1696.18  4855.5 1697.58  4878.3 1697.85
  4898.3 1695.28  4948.3 1695.69  4958.3 1694.25  4964.7 1691.61  4996.4 1689.33
  4999.2 1688.83  5002.4 1689.33  5020.1 1689.48  5065.8 1701.97  5071.9 1704.76
  5082.2 1706.41  5228.6 1714.77  5286.4 1716.17    5579 1718.25  5936.2 1722.56
#Mann= 7 ,-1 , 0
  4106.1      .1       0    4381     .05       0  4855.5      .1       0
  4996.4     .07       0  5002.4      .1       0  5228.6     .05       0
  5286.4      .1       0
Bank Sta=4618.1,5065.8
XS Rating Curve= 0 ,0
Exp/Cntr=0.3,0.1

Type RM Length L Ch R = 1 ,29695   ,550,550,550
BEGIN DESCRIPTION:
LIVE OAK CREEK 54.0
END DESCRIPTION:
XS GIS Cut Line= 2
      2738186.46     10067204.89      2736352.45     10067316.49
#Sta/Elev= 30
  4451.9 1721.47  4515.1 1716.75  4610.2 1712.95  4730.4 1712.73  4850.6 1714.96
  4860.6 1713.88  4880.7  1703.5  4890.7 1700.21  4910.7 1694.13  4940.8 1687.39
  4997.9 1684.75  5000.7 1684.25  5003.9 1684.75  5006.1 1685.84  5012.5 1686.76
    5031 1693.55    5041 1694.77  5131.1 1693.79  5181.2 1696.11  5201.3 1700.18
  5231.3 1701.04  5421.7 1706.78  5511.8 1706.65  5592.3  1709.4  5762.3 1714.22
  6052.8 1717.27  6164.8 1719.86  6253.2 1725.04  6284.6 1729.24  6289.3 1728.58
#Mann= 6 ,-1 , 0
  4451.9      .1       0  4997.9     .07       0  5003.9      .1       0
  5006.1     .05       0  5592.3      .1       0  6284.6     .16       0
Bank Sta=4890.7,5231.3
XS Rating Curve= 0 ,0
Exp/Cntr=0.3,0.1

Type RM Length L Ch R = 1 ,29145   ,695,695,695
BEGIN DESCRIPTION:
LIVE OAK CREEK 53.0
END DESCRIPTION:
XS GIS Cut Line= 3
      2737890.33     10066801.96      2737628.17      10066690.3
      2736411.56     10066952.04
#Sta/Elev= 30
  4592.4 1712.25  4676.6  1713.1  4767.7 1711.29  4774.4  1711.4  4834.7 1706.79
  4852.8 1703.28  4858.3 1703.86  4879.8 1700.49  4915.1 1693.95  4958.9 1690.71
  4969.6 1688.91  4979.3 1685.02  5005.7 1682.82  5008.5 1682.32  5011.7 1682.82
  5030.5 1688.01  5046.6 1690.07    5143 1692.92  5193.4 1696.97  5224.8 1700.23
  5245.2 1703.26  5299.7  1703.8  5388.1 1708.62  5521.5 1712.58  5623.8 1711.78
  5803.7  1713.3    5946 1716.21  6014.3  1720.1  6043.1 1722.94  6121.8 1726.81
#Mann= 9 ,-1 , 0
  4592.4      .1       0  4767.7     .05       0  4774.4      .1       0
  5005.7     .07       0  5011.7      .1       0  5046.6     .05       0
  5193.4      .1       0  5803.7     .05       0    5946      .1       0
Bank Sta=4879.8,5224.8
XS Rating Curve= 0 ,0
Exp/Cntr=0.3,0.1

Type RM Length L Ch R = 1 ,28450   ,589,589,589
BEGIN DESCRIPTION:
LIVE OAK CREEK 52.0
END DESCRIPTION:
XS GIS Cut Line= 2
      2737997.13     10066583.51      2736823.33     10065598.87
#Sta/Elev= 30
  4217.5 1710.68  4301.7 1711.31  4462.5 1702.98  4634.7 1699.18  4736.9  1693.9
  4790.8 1691.31  4933.6 1690.04  5001.2 1679.42  5003.9 1678.92  5007.2 1679.42
    5012 1679.58  5039.3 1692.62  5053.6 1697.12  5067.9 1698.41  5075.7 1697.02
  5082.2 1699.26    5090  1698.4  5096.5 1700.92  5103.3 1699.66  5110.9 1706.19
  5117.4 1706.78  5125.2 1716.15  5131.7 1716.73  5139.5 1721.98  5181.6 1728.11
  5458.2 1738.17  5482.4 1739.08  5606.7 1740.85  5698.6 1739.85  5749.6 1738.29
#Mann= 9 ,-1 , 0
  4217.5      .1       0  4462.5     .05       0  4736.9     .16       0
  5001.2     .07       0  5007.2     .16       0  5458.2      .1       0
  5482.4     .05       0  5606.7      .1       0  5698.6     .05       0
Bank Sta=4634.7,5082.2
XS Rating Curve= 0 ,0
Exp/Cntr=0.3,0.1

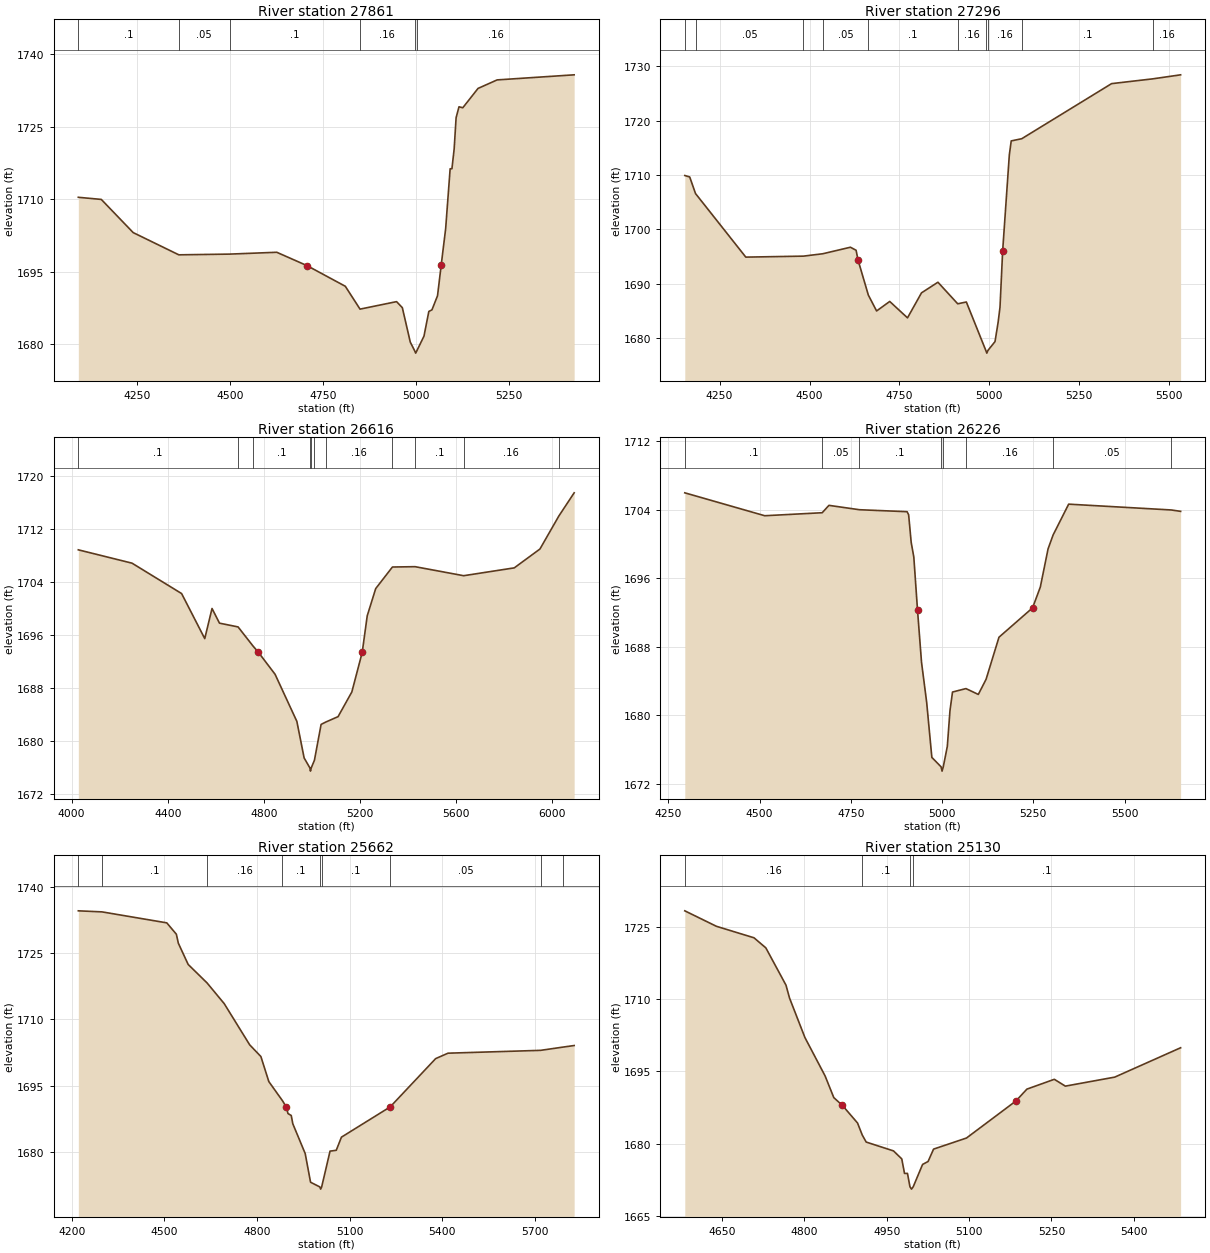
Type RM Length L Ch R = 1 ,27861   ,565,565,565
BEGIN DESCRIPTION:
LIVE OAK CREEK 51.0
END DESCRIPTION:
XS GIS Cut Line= 3
      2738186.44     10066369.88        2737667.     10065510.62
      2737346.63     10065437.81
#Sta/Elev= 30
    4092 1710.38  4153.7 1709.94  4239.4 1703.08  4362.1 1698.48  4498.8 1698.63
  4625.3 1699.01  4706.8 1696.24  4809.5 1691.98  4849.1 1687.25  4947.3  1688.8
  4962.8 1687.55  4984.2 1680.42  4995.9 1678.65  4998.7 1678.15  5001.9 1678.65
    5021 1681.67    5034 1686.77  5042.4  1687.1  5057.4 1690.02 5067.27 1696.37
  5079.2 1703.86  5091.3 1716.28  5096.1 1716.28  5102.1 1720.38  5107.3 1726.84
  5115.1  1729.1  5125.3  1728.9  5166.3  1732.9  5217.6 1734.66  5424.6 1735.71
#Mann= 6 ,-1 , 0
    4092      .1       0  4362.1     .05       0  4498.8      .1       0
  4849.1     .16       0  4995.9     .07       0  5001.9     .16       0
Bank Sta=4706.8,5067.27
XS Rating Curve= 0 ,0
Exp/Cntr=0.3,0.1

Type RM Length L Ch R = 1 ,27296   ,680,680,680
BEGIN DESCRIPTION:
LIVE OAK CREEK 50.0
END DESCRIPTION:
XS GIS Cut Line= 3
      2738438.88     10066068.88      2738113.63     10065127.11
      2737741.61     10065040.14
#Sta/Elev= 30
  4153.3 1709.89    4167 1709.62  4183.1 1706.57  4322.9 1694.87    4483 1695.05
    4537 1695.49  4613.7 1696.69  4629.5 1696.13  4634.8 1694.36  4663.6 1687.88
  4686.5 1684.96    4723 1686.71  4772.4 1683.69  4811.3 1688.29    4857 1690.25
    4912 1686.28    4936 1686.61  4990.1  1677.7  4992.9  1677.2  4996.1  1677.7
  5015.7 1679.32  5024.3 1682.85  5029.6 1685.66  5036.9 1695.96  5055.5 1713.69
  5060.8 1716.26    5090 1716.66  5339.8  1726.8  5454.4 1727.68  5531.7 1728.42
#Mann= 10 ,-1 , 0
  4153.3      .1       0  4183.1     .05       0    4483      .1       0
    4537     .05       0  4663.6      .1       0    4912     .16       0
  4990.1     .07       0  4996.1     .16       0    5090      .1       0
  5454.4     .16       0
Bank Sta=4634.8,5036.9
XS Rating Curve= 0 ,0
Exp/Cntr=0.3,0.1

Type RM Length L Ch R = 1 ,26616   ,390,390,390
BEGIN DESCRIPTION:
LIVE OAK CREEK 49.0
END DESCRIPTION:
XS GIS Cut Line= 3
      2738667.64     10066405.27      2738813.26     10065294.97
      2738222.94     10064559.35
#Sta/Elev= 30
  4027.8 1708.82  4251.2 1706.81  4457.5 1702.23  4553.8 1695.44  4584.1 1699.98
  4615.1 1697.77  4692.5  1697.2  4754.5 1694.33  4775.7 1693.44  4846.5 1690.06
  4937.1 1682.96  4967.3 1677.46    4991 1675.97  4993.7 1675.47    4997 1675.97
  5010.1  1677.1  5037.9 1682.51  5057.6 1682.87  5108.5 1683.68  5165.8  1687.4
    5209 1693.37  5229.8 1698.87  5265.1 1702.98  5334.7 1706.23    5429 1706.28
    5631 1704.92  5841.6  1706.1  5948.4 1708.94  6027.2 1713.92  6090.8 1717.41
#Mann= 11 ,-1 , 0
  4027.8      .1       0  4692.5     .05       0  4754.5      .1       0
    4991     .07       0    4997      .1       0  5010.1     .05       0
  5057.6     .16       0  5334.7     .05       0    5429      .1       0
    5631     .16       0  6027.2     .05       0
Bank Sta=4775.7,5209
XS Rating Curve= 0 ,0
Exp/Cntr=0.3,0.1

Type RM Length L Ch R = 1 ,26226   ,564,564,564
BEGIN DESCRIPTION:
LIVE OAK CREEK 48.0
END DESCRIPTION:
XS GIS Cut Line= 3
      2738982.61     10065952.38      2739167.09     10065374.69
       2738628.2     10064850.37
#Sta/Elev= 30
  4295.2 1705.95  4514.2 1703.28  4671.7 1703.63    4690 1704.49  4773.5 1703.98
  4904.2 1703.75  4908.4 1703.39  4915.4 1700.18  4922.6 1698.46 4932.73 1692.28
  4943.7  1686.2  4957.8 1681.53    4972 1675.11  4997.3 1674.01    5000 1673.51
  5003.3 1674.01  5014.4  1676.4  5021.6 1680.54  5028.6 1682.73  5065.4 1683.13
  5099.3 1682.45  5120.6 1684.22  5155.9 1689.12  5247.9 1692.54  5269.1 1694.96
  5290.4 1699.42  5304.1 1701.03  5346.8 1704.63  5628.4 1703.95  5653.5 1703.79
#Mann= 8 ,-1 , 0
  4295.2      .1       0  4671.7     .05       0  4773.5      .1       0
  4997.3     .07       0  5003.3      .1       0  5065.4     .16       0
  5304.1     .05       0  5628.4      .1       0
Bank Sta=4932.73,5247.9
XS Rating Curve= 0 ,0
Exp/Cntr=0.3,0.1

Type RM Length L Ch R = 1 ,25662   ,532,532,532
BEGIN DESCRIPTION:
LIVE OAK CREEK 47.0
END DESCRIPTION:
XS GIS Cut Line= 3
      2740104.01     10065083.41      2739453.51     10064855.25
       2738542.1     10064763.14
#Sta/Elev= 30
  4221.3 1734.56  4298.1 1734.32  4507.7 1731.84  4538.7 1729.27  4545.1 1727.24
  4576.9 1722.44  4638.2 1718.25  4693.7 1713.57  4776.1 1704.26  4812.4 1701.61
  4838.1 1695.95  4882.2 1691.63  4894.8 1690.19  4900.1 1688.72  4910.7 1688.28
  4915.7 1686.42  4955.9 1679.67  4973.2 1673.19  5003.2 1672.13  5005.9 1671.63
  5009.2 1672.13  5036.3 1680.22  5056.4 1680.41  5073.2 1683.38    5231 1690.22
  5378.2 1701.14  5418.3 1702.37    5718 1703.01  5789.1 1703.73  5826.7  1704.1
#Mann= 9 ,-1 , 0
  4221.3     .05       0  4298.1      .1       0  4638.2     .16       0
  4882.2      .1       0  5003.2     .07       0  5009.2      .1       0
    5231     .05       0    5718      .1       0  5789.1     .16       0
Bank Sta=4894.8,5231
XS Rating Curve= 0 ,0
Exp/Cntr=0.3,0.1

Type RM Length L Ch R = 1 ,25130   ,512,512,512
BEGIN DESCRIPTION:
LIVE OAK CREEK 46.0
END DESCRIPTION:
XS GIS Cut Line= 3
      2739918.46     10064553.73      2739568.47     10064353.73
      2739068.48     10064353.73
#Sta/Elev= 30
  4582.2  1728.3  4639.8 1725.09  4708.2 1722.71  4729.8 1720.62  4766.5 1712.89
    4773  1710.2    4801 1702.02  4837.7 1694.07  4853.6 1689.56  4869.4 1687.93
  4896.8  1684.3  4905.4 1681.81  4912.6 1680.34  4962.3 1678.51  4977.4 1676.85
  4982.4 1673.84  4987.8 1673.84  4992.3 1671.08  4995.1 1670.58  4998.3 1671.08
  5015.3  1675.7  5025.3 1676.31  5035.3 1678.88  5095.3 1681.18  5185.3 1688.86
  5205.3 1691.32  5255.3 1693.36  5275.3 1691.94  5365.3 1693.81  5485.3  1699.9
#Mann= 4 ,-1 , 0
  4582.2     .16       0  4905.4      .1       0  4992.3     .07       0
  4998.3      .1       0
Bank Sta=4869.4,5185.3
XS Rating Curve= 0 ,0
Exp/Cntr=0.3,0.1

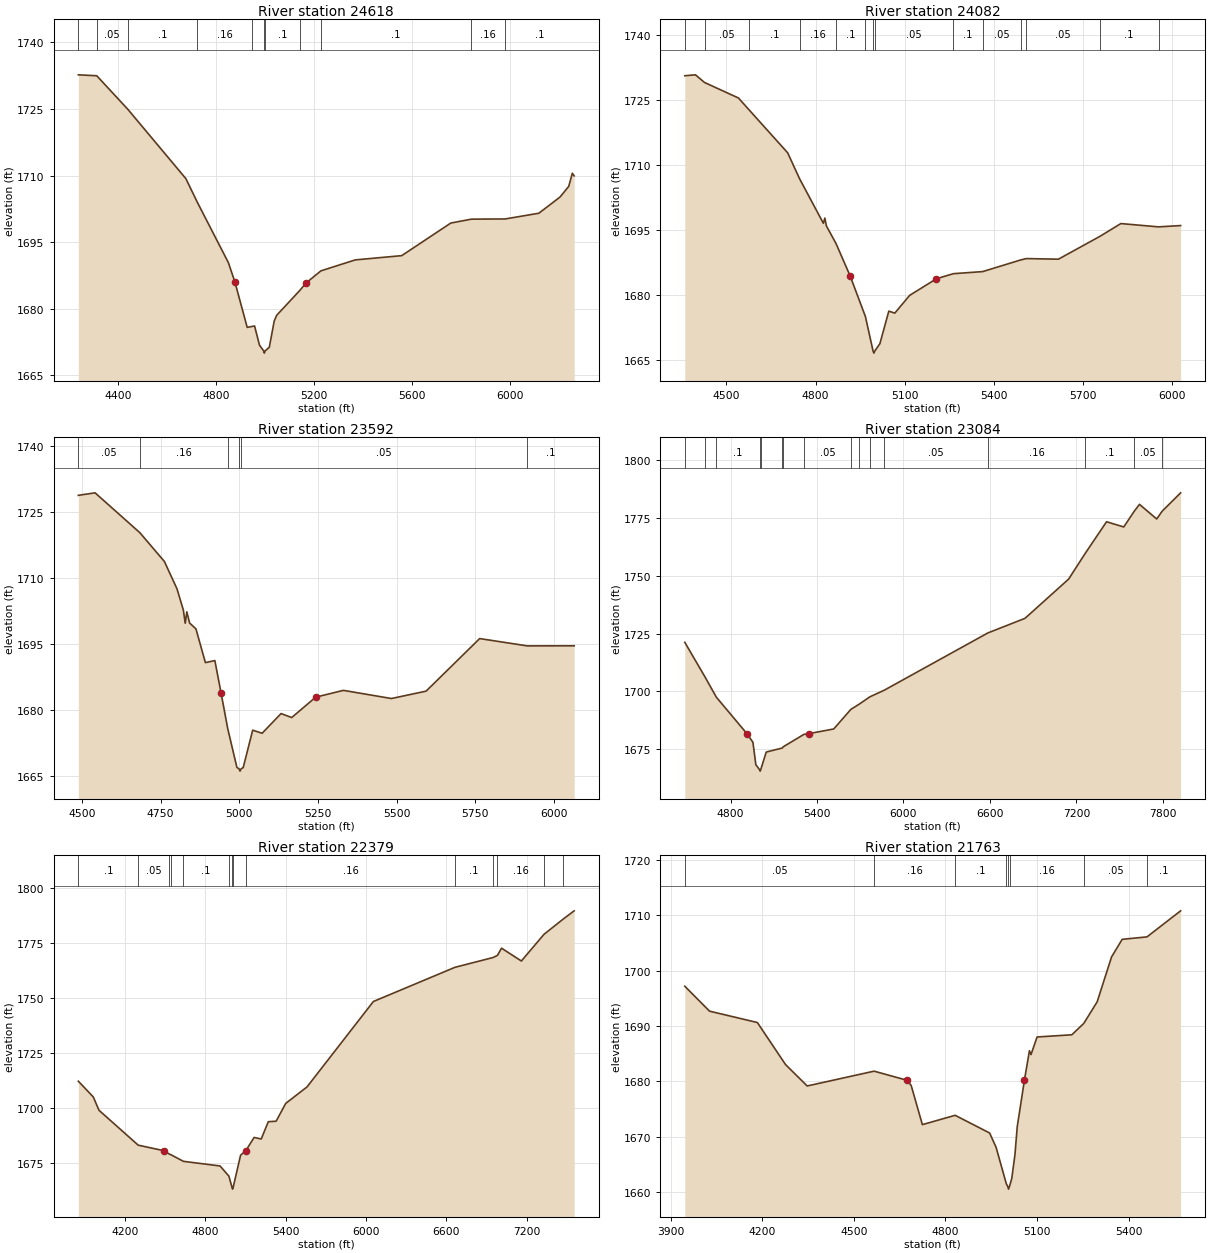
Type RM Length L Ch R = 1 ,24618   ,536,536,536
BEGIN DESCRIPTION:
LIVE OAK CREEK 45.0
END DESCRIPTION:
XS GIS Cut Line= 3
      2740456.41     10063916.17      2739268.87     10063843.25
      2738586.59     10064322.41
#Sta/Elev= 30
  4239.2 1732.71  4314.4  1732.5  4440.6 1724.98    4678 1709.31  4725.3 1703.93
  4851.6 1690.36  4878.3 1685.98  4928.4 1675.76  4949.3 1675.99  4958.5 1676.08
  4978.5 1671.76  4995.6 1670.46  4998.3 1669.96  5001.6 1670.46  5018.6 1671.29
  5038.6 1677.19  5048.7 1678.49    5143 1684.09  5168.9 1685.79  5229.3 1688.51
  5369.3 1690.98    5559 1691.94  5759.4 1699.29  5843.7 1700.17  5980.6 1700.21
  6118.5  1701.5  6204.8 1705.14  6240.5 1707.55  6255.3 1710.52  6262.7 1709.93
#Mann= 11 ,-1 , 0
  4239.2      .1       0  4314.4     .05       0  4440.6      .1       0
  4725.3     .16       0  4949.3      .1       0  4995.6     .07       0
  5001.6      .1       0    5143     .05       0  5229.3      .1       0
  5843.7     .16       0  5980.6      .1       0
Bank Sta=4878.3,5168.9
XS Rating Curve= 0 ,0
Exp/Cntr=0.3,0.1

Type RM Length L Ch R = 1 ,24082   ,490,490,490
BEGIN DESCRIPTION:
LIVE OAK CREEK 44.0
END DESCRIPTION:
XS GIS Cut Line= 2
       2740404.3     10063384.91      2738737.59     10063327.62
#Sta/Elev= 30
  4360.3  1730.6  4396.2 1730.81  4426.8 1729.04  4540.8 1725.47  4577.4 1722.67
  4706.3 1712.84  4746.4 1706.86  4826.4 1696.59  4831.4  1697.8  4836.4 1696.02
  4869.2 1691.89  4916.5 1684.45  4967.8  1675.1  4993.5 1667.17  4996.3 1666.67
  4999.5 1667.17  5016.5 1668.85  5046.5 1676.35  5066.6 1675.89  5116.6 1679.98
  5206.6 1683.81  5263.6 1684.98  5362.2 1685.46  5490.3 1688.15  5509.1 1688.46
  5616.9 1688.32  5756.5 1693.58    5827 1696.53  5953.7 1695.77    6028 1696.07
#Mann= 14 ,-1 , 0
  4360.3      .1       0  4426.8     .05       0  4577.4      .1       0
  4746.4     .16       0  4869.2      .1       0  4967.8     .05       0
  4993.5    .035       0  4999.5     .05       0  5263.6      .1       0
  5362.2     .05       0  5490.3     .16       0  5509.1     .05       0
  5756.5      .1       0  5953.7     .05       0
Bank Sta=4916.5,5206.6
XS Rating Curve= 0 ,0
Exp/Cntr=0.3,0.1

Type RM Length L Ch R = 1 ,23592   ,508,508,508
BEGIN DESCRIPTION:
LIVE OAK CREEK 43.0
END DESCRIPTION:
XS GIS Cut Line= 2
      2740211.57     10062848.46      2738638.66     10062942.21
#Sta/Elev= 30
  4488.4 1728.77  4541.6 1729.34  4683.9 1720.29    4762 1713.74  4802.1 1707.51
  4822.1 1702.74  4828.1 1699.73  4833.2 1702.31  4842.1 1699.77  4862.2 1698.44
  4892.2 1690.78  4922.3 1691.25  4942.3 1683.78  4963.1 1675.82  4992.3 1666.99
  4999.4 1666.64  5002.2 1666.14  5005.4 1666.64  5012.4 1666.96  5042.5 1675.44
  5072.5 1674.74  5132.6 1679.21  5166.5 1678.31  5242.8 1682.94  5330.7 1684.48
  5483.3 1682.63  5593.5  1684.3  5763.8 1696.24  5915.3 1694.58  6064.1  1694.6
#Mann= 6 ,-1 , 0
  4488.4     .05       0  4683.9     .16       0  4963.1     .05       0
  4999.4    .035       0  5005.4     .05       0  5915.3      .1       0
Bank Sta=4942.3,5242.8
XS Rating Curve= 0 ,0
Exp/Cntr=0.3,0.1

Type RM Length L Ch R = 1 ,23084   ,705,705,705
BEGIN DESCRIPTION:
LIVE OAK CREEK 42.0
END DESCRIPTION:
XS GIS Cut Line= 4
      2739987.62     10062577.62      2739565.75     10062405.75
       2739227.2     10062447.41      2736675.08     10061754.69
#Sta/Elev= 30
  4482.4 1721.19  4622.2 1706.25  4701.5 1697.43  4913.4 1681.66  4955.3  1677.9
  4975.5 1668.19  5002.7 1665.92  5005.5 1665.42  5008.7 1665.92  5047.6 1673.68
  5159.5 1675.43  5165.6 1675.96  5308.7 1681.32  5347.7 1681.71    5516 1683.67
  5635.1 1692.17  5694.7 1694.49    5766 1697.56  5867.1 1700.47  6586.3 1725.27
  6843.4 1731.57  7146.3 1748.57  7262.1 1759.75  7409.4  1773.4  7528.9 1771.14
  7600.6 1777.85    7638 1780.93  7757.4  1774.6    7795 1777.93  7923.5 1785.92
#Mann= 16 ,-1 , 0
  4482.4      .1       0  4622.2     .16       0  4701.5      .1       0
  5002.7     .07       0  5008.7      .1       0  5159.5     .16       0
  5165.6      .1       0  5308.7     .05       0  5635.1      .1       0
  5694.7     .05       0    5766      .1       0  5867.1     .05       0
  6586.3     .16       0  7262.1      .1       0  7600.6     .05       0
    7795     .16       0
Bank Sta=4913.4,5347.7
XS Rating Curve= 0 ,0
Exp/Cntr=0.3,0.1

Type RM Length L Ch R = 1 ,22379   ,616,616,616
BEGIN DESCRIPTION:
LIVE OAK CREEK 41.0
END DESCRIPTION:
XS GIS Cut Line= 3
      2740123.06     10062452.64      2739263.66     10061890.12
      2736794.92     10060858.88
#Sta/Elev= 30
  3851.9  1712.2  3963.8 1705.02  4005.9    1699  4299.1 1683.11  4490.8  1680.6
  4531.9 1679.06  4546.4 1678.68  4636.4 1675.77  4910.2 1673.66  4976.1 1669.06
  5000.9 1663.63  5003.6 1663.13  5006.9 1663.63  5063.5 1678.55  5102.7 1680.63
  5164.5 1686.62  5217.6 1685.92  5270.6 1693.77    5329 1694.01  5400.5 1702.09
  5559.6 1709.59  6055.3 1748.43  6664.6 1763.97  6949.3 1768.42  6981.8  1769.4
  7012.1 1772.67  7160.4 1766.84  7329.3 1778.97    7473 1785.91  7554.5 1789.65
#Mann= 14 ,-1 , 0
  3851.9      .1       0  4299.1     .05       0  4531.9      .1       0
  4546.4     .16       0  4636.4      .1       0  4976.1     .05       0
  5000.9     .04       0  5006.9     .05       0  5102.7     .16       0
  6664.6      .1       0  6949.3     .05       0  6981.8     .16       0
  7329.3     .05       0    7473      .1       0
Bank Sta=4490.8,5102.7
XS Rating Curve= 0 ,0
Exp/Cntr=0.3,0.1

Type RM Length L Ch R = 1 ,21763   ,478,478,478
BEGIN DESCRIPTION:
LIVE OAK CREEK 40.0
END DESCRIPTION:
XS GIS Cut Line= 3
      2740185.56     10062270.36      2739591.79     10061535.96
      2739414.71     10060879.74
#Sta/Elev= 30
  3946.3 1697.17  4027.4 1692.68    4184 1690.63  4276.3 1683.05  4347.2 1679.19
  4566.3 1681.86  4674.9 1680.21  4687.8 1679.28  4724.5 1672.22  4831.8  1673.9
  4944.8 1670.71  4965.9 1668.14  4999.5 1661.55  5003.9 1661.09  5006.7 1660.59
  5009.9 1661.09  5017.3  1662.5  5027.7 1666.79  5035.3 1671.87  5058.7 1680.21
  5075.2 1685.55  5080.4 1684.85  5100.2 1688.02  5214.1 1688.42  5253.2 1690.47
    5297 1694.36  5344.2 1702.46    5379 1705.63  5460.2 1706.07  5570.4 1710.77
#Mann= 8 ,-1 , 0
  3946.3     .05       0  4566.3     .16       0  4831.8      .1       0
  4999.5     .16       0  5003.9     .07       0  5009.9     .16       0
  5253.2     .05       0  5460.2      .1       0
Bank Sta=4674.9,5058.7
XS Rating Curve= 0 ,0
Exp/Cntr=0.3,0.1

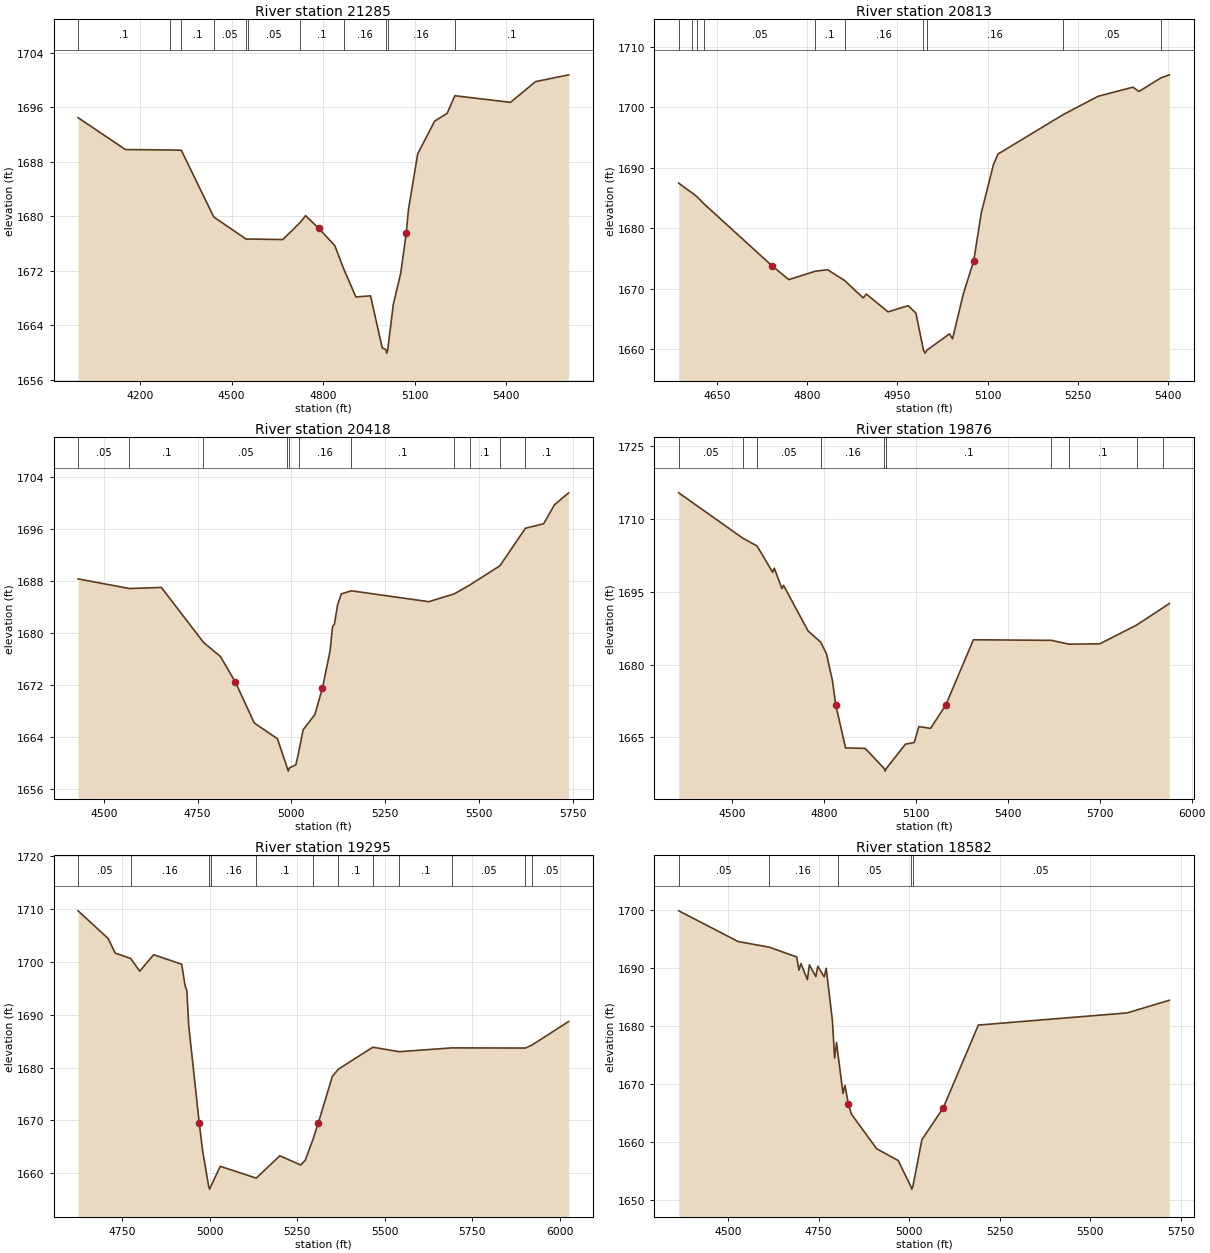
Type RM Length L Ch R = 1 ,21285   ,472,472,472
BEGIN DESCRIPTION:
LIVE OAK CREEK 39.0
END DESCRIPTION:
XS GIS Cut Line= 3
      2740357.41     10062223.45      2739945.95     10061103.66
      2740133.46     10060733.87
#Sta/Elev= 30
  3996.8  1694.5  4152.1 1689.82  4297.2 1689.76  4335.1 1689.72  4441.6 1679.92
  4548.1 1676.66  4552.9 1676.69  4667.7 1676.61  4725.2 1679.14  4742.3 1680.12
  4784.9 1678.29  4838.1 1675.72  4867.5 1672.29  4907.2 1668.19  4955.3 1668.35
  4993.3 1660.74  5005.6 1660.44  5008.3 1659.94  5011.6 1660.44  5029.9  1667.1
  5054.3  1671.7  5072.5 1677.61  5079.4 1680.98  5109.9  1689.2  5165.5    1694
  5206.5 1695.15  5231.6 1697.72  5413.9 1696.75  5495.9 1699.79  5604.4 1700.79
#Mann= 11 ,-1 , 0
  3996.8      .1       0  4297.2     .05       0  4335.1      .1       0
  4441.6     .05       0  4548.1      .1       0  4552.9     .05       0
  4725.2      .1       0  4867.5     .16       0  5005.6     .07       0
  5011.6     .16       0  5231.6      .1       0
Bank Sta=4784.9,5072.5
XS Rating Curve= 0 ,0
Exp/Cntr=0.3,0.1

Type RM Length L Ch R = 1 ,20813   ,395,395,395
BEGIN DESCRIPTION:
LIVE OAK CREEK 38.0
END DESCRIPTION:
XS GIS Cut Line= 3
      2740568.48     10061653.78      2740468.47     10061253.73
      2740418.46      10060853.7
#Sta/Elev= 30
  4586.7 1687.46  4608.1 1685.92  4616.7 1685.26    4629 1684.02  4741.4 1673.84
  4769.7 1671.52  4813.2  1672.9  4834.1 1673.16  4862.5 1671.37  4893.4 1668.49
  4898.6 1669.14  4934.6 1666.19  4968.1 1667.22    4981 1665.98  4993.5 1659.87
  4996.2 1659.37  4999.5 1659.87  5036.8 1662.55  5041.9 1661.73  5059.5 1669.06
 5077.05 1674.63  5089.8 1682.62  5109.9 1690.56  5117.5 1692.29  5225.2 1698.77
  5283.8 1701.83  5341.7 1703.34  5351.8 1702.63  5388.5 1704.89  5402.2 1705.38
#Mann= 10 ,-1 , 0
  4586.7      .1       0  4608.1     .05       0  4616.7      .1       0
    4629     .05       0  4813.2      .1       0  4862.5     .16       0
  4993.5     .07       0  4999.5     .16       0  5225.2     .05       0
  5388.5      .1       0
Bank Sta=4741.4,5077.05
XS Rating Curve= 0 ,0
Exp/Cntr=0.3,0.1

Type RM Length L Ch R = 1 ,20418   ,542,542,542
BEGIN DESCRIPTION:
LIVE OAK CREEK 37.0
END DESCRIPTION:
XS GIS Cut Line= 3
       2740784.5     10061869.27      2740883.45     10061119.29
      2740452.33     10060776.47
#Sta/Elev= 30
  4431.6 1688.35  4568.5 1686.87  4653.6 1687.04  4765.8  1678.6  4810.7 1676.44
  4850.7 1672.51  4901.2 1666.21  4962.8 1663.79    4989 1659.31  4991.7 1658.81
    4995 1659.31  5012.1 1659.79  5019.2 1661.62  5031.3 1665.16  5062.6 1667.49
  5082.7 1671.54  5102.9  1677.2  5109.8 1680.97  5114.9 1681.44  5123.1 1684.34
  5133.2 1686.05    5160 1686.52  5366.3 1684.85    5434 1686.05  5475.4 1687.41
  5555.8 1690.37  5623.8 1696.14  5672.3 1696.82  5701.1 1699.74  5738.9 1701.58
#Mann= 11 ,-1 , 0
  4431.6     .05       0  4568.5      .1       0  4765.8     .05       0
    4989    .035       0    4995     .05       0  5019.2     .16       0
    5160      .1       0    5434     .05       0  5475.4      .1       0
  5555.8     .05       0  5623.8      .1       0
Bank Sta=4850.7,5082.7
XS Rating Curve= 0 ,0
Exp/Cntr=0.3,0.1

Type RM Length L Ch R = 1 ,19876   ,581,581,581
BEGIN DESCRIPTION:
LIVE OAK CREEK 36.0
END DESCRIPTION:
XS GIS Cut Line= 3
      2741998.06     10061457.84      2741445.95      10061249.5
      2740555.29     10060770.31
#Sta/Elev= 30
  4325.5 1715.44  4536.3 1706.02  4581.1 1704.48  4632.1 1699.05  4637.5 1699.88
  4662.3 1695.68  4667.6 1696.35  4747.5 1686.97  4788.6 1684.66  4807.9 1682.22
  4827.4 1676.65  4838.1 1671.66  4870.2 1662.82  4934.1 1662.72  4996.8 1658.53
  4999.5 1658.03  5002.8 1658.53    5003 1658.56  5065.5 1663.59  5094.4 1663.94
  5109.3 1667.22  5147.5 1666.85    5197 1671.63  5287.5 1685.13  5541.8 1685.01
  5599.6 1684.22  5700.1 1684.29  5820.7 1688.18  5906.8 1691.75    5927  1692.6
#Mann= 11 ,-1 , 0
  4325.5     .05       0  4536.3      .1       0  4581.1     .05       0
  4788.6     .16       0  4996.8     .07       0  5002.8     .16       0
    5003      .1       0  5541.8     .05       0  5599.6      .1       0
  5820.7     .05       0  5906.8      .1       0
Bank Sta=4838.1,5197
XS Rating Curve= 0 ,0
Exp/Cntr=0.3,0.1

Type RM Length L Ch R = 1 ,19295   ,713,713,713
BEGIN DESCRIPTION:
LIVE OAK CREEK 35.0
END DESCRIPTION:
XS GIS Cut Line= 2
      2742034.48      10060749.5       2740633.5     10060791.16
#Sta/Elev= 30
    4624 1709.68  4710.1 1704.43  4730.1 1701.67  4774.2 1700.67  4800.1 1698.27
  4840.1 1701.37  4920.1 1699.56  4929.9 1695.43  4934.9 1694.62  4940.2 1687.94
  4970.2  1669.5  4980.2 1664.12  4997.2 1657.49  4999.9 1656.99  5003.2 1657.49
  5030.2 1661.31  5133.1 1659.07  5200.3  1663.3  5260.3 1661.56  5273.2 1662.48
  5295.4 1666.46  5310.3  1669.5  5350.3 1678.29  5367.3 1679.68  5466.1 1683.86
  5541.5 1683.01  5691.4 1683.73  5902.3  1683.7  5921.8 1684.31  6025.6 1688.73
#Mann= 12 ,-1 , 0
    4624     .05       0  4774.2     .16       0  4997.2    .035       0
  5003.2     .16       0  5133.1      .1       0  5295.4     .05       0
  5367.3      .1       0  5466.1     .05       0  5541.5      .1       0
  5691.4     .05       0  5902.3      .1       0  5921.8     .05       0
Bank Sta=4970.2,5310.3
XS Rating Curve= 0 ,0
Exp/Cntr=0.3,0.1

Type RM Length L Ch R = 1 ,18582   ,523,523,523
BEGIN DESCRIPTION:
LIVE OAK CREEK 34.0
END DESCRIPTION:
XS GIS Cut Line= 3
      2741815.75      10060374.5      2741326.16     10060155.75
      2740613.02     10060556.57
#Sta/Elev= 30
    4364 1699.92    4528 1694.61  4613.5 1693.64  4689.6 1691.95  4695.9 1689.67
  4701.4 1690.81  4719.2 1688.02  4724.6  1690.6  4742.4 1688.55  4747.8 1690.34
  4765.6 1688.51  4771.1 1689.99  4788.2 1680.95  4794.3 1674.47  4799.7 1677.17
  4802.6 1675.64  4817.5 1668.36  4822.9 1669.75    4832  1666.6  4840.7 1664.78
  4910.6 1658.78  4969.9 1656.75  5004.5 1652.31  5007.2 1651.81  5010.5 1652.31
  5035.2 1660.35  5094.2 1665.85  5191.1 1680.17  5601.7 1682.27  5718.3 1684.46
#Mann= 5 ,-1 , 0
    4364     .05       0  4613.5     .16       0  4802.6     .05       0
  5004.5     .04       0  5010.5     .05       0
Bank Sta=4832,5094.2
XS Rating Curve= 0 ,0
Exp/Cntr=0.3,0.1