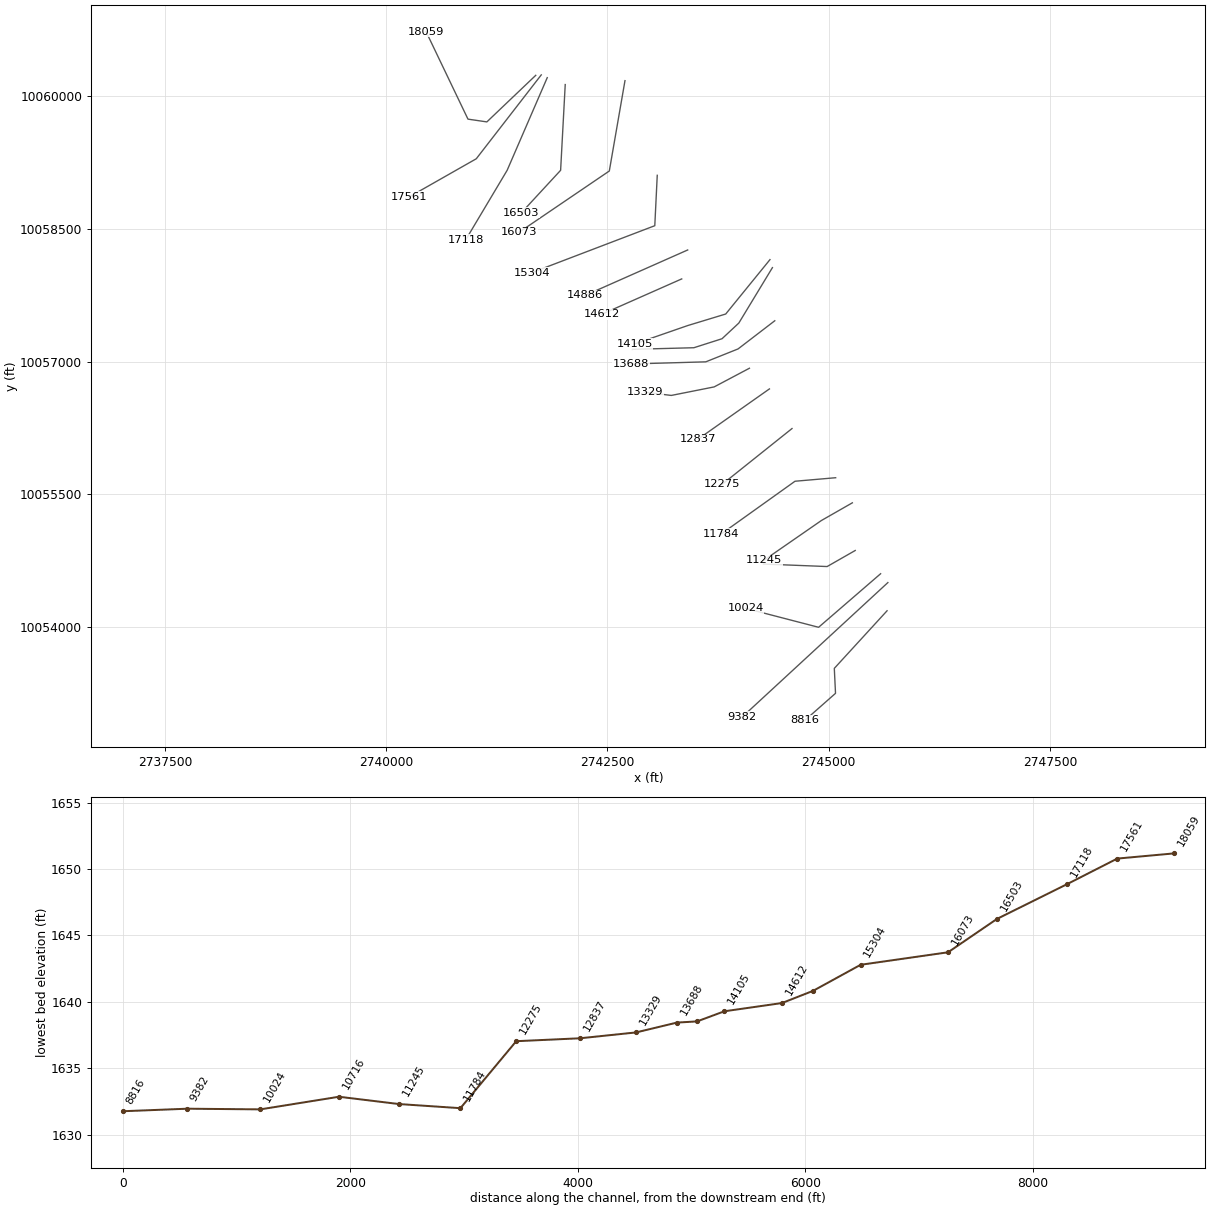
HEC-RAS study LIVE OAK CREEK.prj: LIVE OAK CREEK Base Level Engineering

--- LIVE OAK CREEK.g01 (geometry) --- (continued)

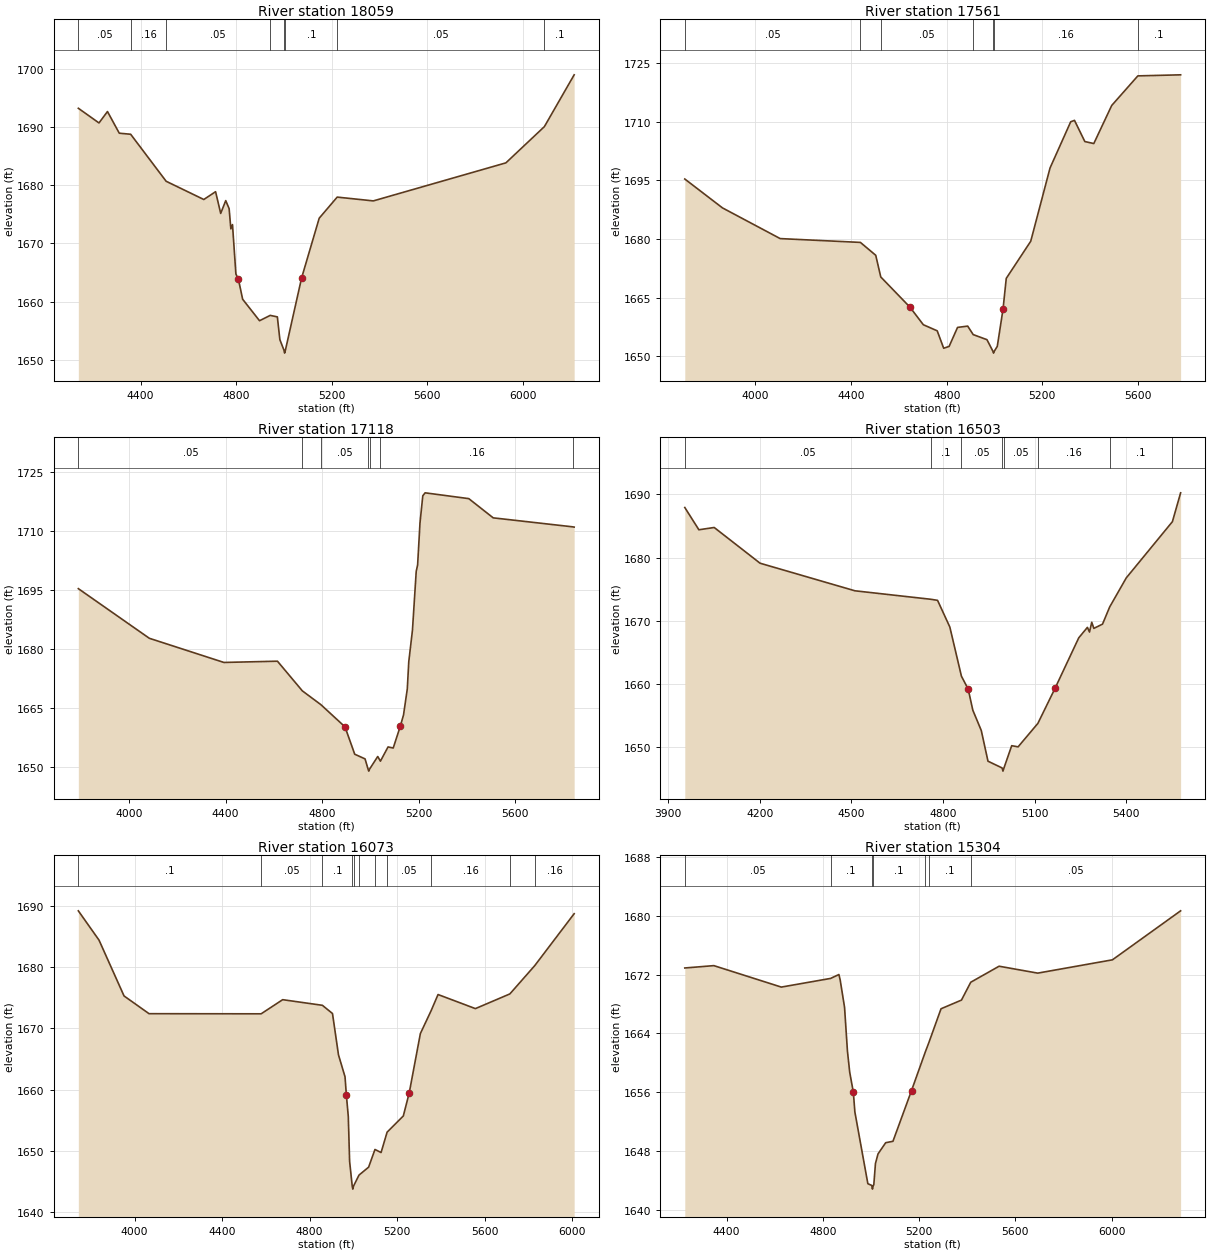
Type RM Length L Ch R = 1 ,18059   ,498,498,498
BEGIN DESCRIPTION:
LIVE OAK CREEK 33.0
END DESCRIPTION:
XS GIS Cut Line= 4
      2741690.78      10060233.9      2741138.66     10059707.83
      2740925.12     10059739.08      2740451.15      10060728.7
#Sta/Elev= 30
  4139.4  1693.2  4225.9 1690.68  4261.4 1692.64  4310.8 1688.92  4358.5 1688.74
    4507 1680.67  4664.7 1677.54    4714 1678.88  4735.4 1675.15  4756.5 1677.35
  4770.7 1675.97  4777.9  1672.5  4784.8 1673.23    4799 1664.76 4809.66 1663.83
  4827.3 1660.42    4898 1656.73  4942.8 1657.65  4972.6 1657.39  4983.1 1653.49
  5000.3 1651.67    5003 1651.17  5006.3 1651.67    5074 1664.06  5147.8 1674.33
  5223.1 1677.95  5374.4  1677.3  5929.4 1683.83  6090.5 1690.05  6215.1 1698.94
#Mann= 8 ,-1 , 0
  4139.4     .05       0  4358.5     .16       0    4507     .05       0
  4942.8      .1       0  5000.3     .07       0  5006.3      .1       0
  5223.1     .05       0  6090.5      .1       0
Bank Sta=4809.66,5074
XS Rating Curve= 0 ,0
Exp/Cntr=0.3,0.1

Type RM Length L Ch R = 1 ,17561   ,443,443,443
BEGIN DESCRIPTION:
LIVE OAK CREEK 32.0
END DESCRIPTION:
XS GIS Cut Line= 3
      2741753.25     10060239.08      2741018.87     10059291.16
      2740258.46     10058858.88
#Sta/Elev= 30
  3704.5 1695.32  3862.1 1687.93  4103.4 1680.08    4439  1679.1  4503.1 1675.81
  4524.2 1670.26  4646.1 1662.55  4702.2 1658.04  4760.2 1656.49  4787.3 1652.03
    4810  1652.5  4845.3 1657.36  4887.7 1657.69  4910.8 1655.52  4968.3 1654.22
  4993.1 1651.28  4995.8 1650.78  4999.1 1651.28  5011.5 1652.51 5035.51 1662.02
    5049  1669.9  5151.4  1679.4  5232.1 1698.13  5318.6 1709.96  5334.4 1710.32
  5377.7  1704.9  5415.2 1704.39  5490.1 1714.13  5599.4  1721.7  5778.3 1721.97
#Mann= 7 ,-1 , 0
  3704.5     .05       0    4439      .1       0  4524.2     .05       0
  4910.8     .16       0  4993.1     .07       0  4999.1     .16       0
  5599.4      .1       0
Bank Sta=4646.1,5035.51
XS Rating Curve= 0 ,0
Exp/Cntr=0.3,0.1

Type RM Length L Ch R = 1 ,17118   ,615,615,615
BEGIN DESCRIPTION:
LIVE OAK CREEK 31.0
END DESCRIPTION:
XS GIS Cut Line= 3
      2741820.96     10060207.85      2741367.83     10059160.96
      2740899.09     10058374.51
#Sta/Elev= 30
  3789.1 1695.38  4083.6 1682.72  4392.9 1676.56  4614.9 1676.88  4718.2 1669.31
  4794.8 1665.81    4895 1660.14  4935.4 1653.16  4978.2 1651.97  4990.8 1649.35
  4993.6 1648.85  4996.8 1649.35  5030.8 1652.58    5042 1651.39  5073.6 1655.02
    5095 1654.74  5124.5 1660.31  5137.8 1663.19  5153.4 1669.82  5159.5 1676.73
  5174.8 1684.78  5190.4 1699.78  5196.2 1701.42    5206  1712.1  5217.7 1719.06
  5227.4 1719.81  5408.4 1718.33  5509.7 1713.43    5839 1711.14  5845.4 1711.07
#Mann= 7 ,-1 , 0
  3789.1     .05       0  4718.2      .1       0  4794.8     .05       0
  4990.8    .035       0  4996.8     .05       0    5042     .16       0
    5839      .1       0
Bank Sta=4895,5124.5
XS Rating Curve= 0 ,0
Exp/Cntr=0.3,0.1

Type RM Length L Ch R = 1 ,16503   ,430,430,430
BEGIN DESCRIPTION:
LIVE OAK CREEK 30.0
END DESCRIPTION:
XS GIS Cut Line= 3
      2742024.08     10060129.75        2741972.     10059160.96
      2741529.26     10058681.76
#Sta/Elev= 30
  3954.9 1687.92    4001  1684.4  4051.1 1684.76  4201.3 1679.11  4511.7 1674.75
  4760.1 1673.41  4782.1 1673.24  4822.2 1669.03  4860.2 1661.25  4882.3  1659.2
  4897.5 1655.87  4925.1 1652.67  4947.1 1647.81  4993.4 1646.74  4996.1 1646.24
  4999.4 1646.74  5024.7 1650.26  5045.7 1650.08  5110.4 1653.79  5166.4 1659.32
  5244.2 1667.32  5272.5 1668.97  5279.3 1668.23  5286.7 1669.78  5293.5 1668.81
  5321.9 1669.48  5345.4  1672.2  5399.6 1676.79  5550.6 1685.68  5577.5 1690.24
#Mann= 8 ,-1 , 0
  3954.9     .05       0  4760.1      .1       0  4860.2     .05       0
  4993.4    .035       0  4999.4     .05       0  5110.4     .16       0
  5345.4      .1       0  5550.6     .16       0
Bank Sta=4882.3,5166.4
XS Rating Curve= 0 ,0
Exp/Cntr=0.3,0.1

Type RM Length L Ch R = 1 ,16073   ,769,769,769
BEGIN DESCRIPTION:
LIVE OAK CREEK 29.0
END DESCRIPTION:
XS GIS Cut Line= 3
      2742699.29     10060173.83      2742522.21     10059153.01
      2741504.84     10058462.03
#Sta/Elev= 30
  3743.2 1689.21  3837.8 1684.42  3952.1  1675.3  4066.4  1672.4  4578.6 1672.38
    4677 1674.69  4858.5 1673.77  4904.7 1672.43  4932.1 1665.67    4962 1662.09
    4968 1659.14  4976.9 1655.61    4983 1648.24  4994.9 1644.23  4997.6 1643.73
  5000.9 1644.23  5025.8 1646.02  5069.8 1647.32  5098.8 1650.21  5126.7 1649.71
  5154.3 1653.04  5228.4 1655.69  5255.5 1659.48  5306.3 1669.15  5355.7 1672.91
  5387.1 1675.53  5557.8 1673.23  5715.3 1675.63  5828.9 1680.25  6009.1 1688.74
#Mann= 11 ,-1 , 0
  3743.2      .1       0  4578.6     .05       0  4858.5      .1       0
  4994.9     .07       0  5000.9      .1       0  5025.8     .05       0
  5098.8      .1       0  5154.3     .05       0  5355.7     .16       0
  5715.3      .1       0  5828.9     .16       0
Bank Sta=4968,5255.5
XS Rating Curve= 0 ,0
Exp/Cntr=0.3,0.1

Type RM Length L Ch R = 1 ,15304   ,418,418,418
BEGIN DESCRIPTION:
LIVE OAK CREEK 28.0
END DESCRIPTION:
XS GIS Cut Line= 3
      2743063.88     10059104.37       2743036.1     10058534.95
       2741643.7     10058003.69
#Sta/Elev= 30
  4226.6 1672.89  4347.4 1673.21  4627.7 1670.29  4832.6 1671.47    4867    1672
  4872.3 1671.26  4890.5 1667.53  4902.4 1661.61  4911.9  1658.7  4927.1 1655.96
  4933.3  1653.3  4987.3 1643.53  5003.7 1643.29  5006.4 1642.79  5009.7 1643.29
    5012 1643.36  5018.9 1646.28  5029.6 1647.59  5061.5 1649.11  5091.6  1649.3
  5168.8 1656.21  5225.6 1661.42  5240.9 1662.74  5291.4 1667.34  5376.3 1668.52
  5414.9 1670.95  5532.7 1673.13  5693.2 1672.19  6003.6    1674    6287 1680.67
#Mann= 7 ,-1 , 0
  4226.6     .05       0  4832.6      .1       0  5003.7     .07       0
  5009.7      .1       0  5225.6     .05       0  5240.9      .1       0
  5414.9     .05       0
Bank Sta=4927.1,5168.8
XS Rating Curve= 0 ,0
Exp/Cntr=0.3,0.1

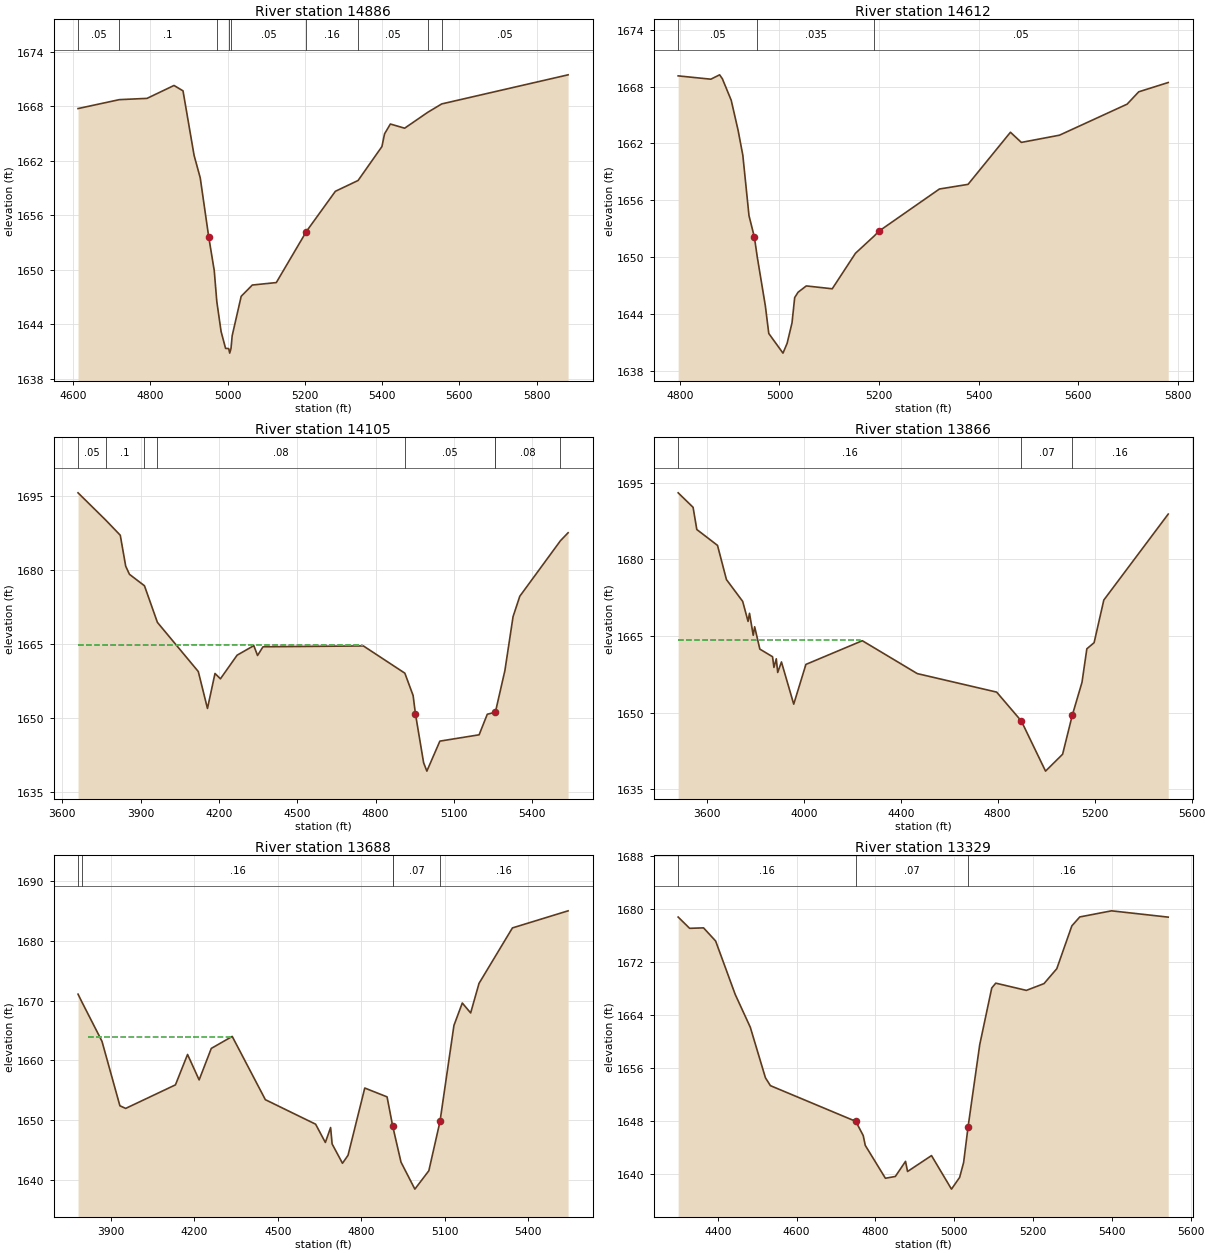
Type RM Length L Ch R = 1 ,14886   ,274,274,274
BEGIN DESCRIPTION:
LIVE OAK CREEK 27.0
END DESCRIPTION:
XS GIS Cut Line= 2
      2743407.67     10058260.67      2742247.92     10057746.77
#Sta/Elev= 30
    4613 1667.73  4719.8 1668.71  4791.6 1668.85  4861.4 1670.27  4884.7 1669.68
  4913.4 1662.58  4929.3 1660.11  4951.2 1653.63  4965.5 1649.93  4972.2  1646.5
  4983.3  1643.2  4994.9 1641.35  5002.9 1641.33  5005.6 1640.83  5008.9 1641.33
    5012 1642.75  5035.3 1647.08  5064.1 1648.32  5126.2 1648.59  5202.8 1654.12
    5204 1654.21  5279.1 1658.63  5337.9 1659.82  5399.6 1663.55  5406.4 1664.95
  5421.5 1666.03  5458.4 1665.57  5518.3 1667.32  5554.4 1668.24  5881.5 1671.44
#Mann= 9 ,-1 , 0
    4613     .05       0  4719.8      .1       0  4972.2     .05       0
  5002.9    .035       0  5008.9     .05       0    5204     .16       0
  5337.9     .05       0  5518.3     .16       0  5554.4     .05       0
Bank Sta=4951.2,5202.8
XS Rating Curve= 0 ,0
Exp/Cntr=0.3,0.1

Type RM Length L Ch R = 1 ,14612   ,507,507,507
BEGIN DESCRIPTION:
LIVE OAK CREEK 26.0
END DESCRIPTION:
XS GIS Cut Line= 2
     2743340.379     10057933.75      2742438.87     10057534.95
#Sta/Elev= 30
  4796.7 1669.12  4862.3 1668.77  4879.9 1669.23  4885.4 1668.82  4903.2 1666.55
    4917 1663.39  4926.5 1660.76  4938.9 1654.39  4949.8 1652.11  4955.3  1650.1
  4971.7  1644.9  4978.6 1641.98  5007.1 1639.91  5015.4 1640.94  5025.2 1643.09
  5030.6 1645.76  5037.3 1646.32  5053.9 1646.99    5106 1646.69  5152.6 1650.43
  5190.4 1652.26  5199.2 1652.74  5321.1  1657.2  5378.6 1657.69  5463.7 1663.18
  5485.6 1662.11  5562.1 1662.87  5697.9 1666.14  5721.2 1667.44  5780.4 1668.42
#Mann= 3 ,-1 , 0
  4796.7     .05       0  4955.3    .035       0  5190.4     .05       0
Bank Sta=4949.8,5199.2
XS Rating Curve= 0 ,0
Exp/Cntr=0.3,0.1

Type RM Length L Ch R = 1 ,14105   ,239,239,239
BEGIN DESCRIPTION:
LIVE OAK CREEK 25.0
END DESCRIPTION:
XS GIS Cut Line= 4
      2744337.54     10058151.65      2743837.53     10057537.05
      2743407.63     10057406.48      2742807.77     10057198.44
#Sta/Elev= 30
  3660.8  1695.6  3766.7 1690.09  3822.5 1687.02  3843.3 1680.76  3857.7 1679.11
  3915.1  1676.8  3964.7 1669.39  4121.3 1659.44  4156.4 1651.97  4185.2 1659.05
    4206 1657.97  4269.9 1662.75  4333.8 1664.68  4348.2 1662.69    4369 1664.45
  4753.5 1664.62  4912.2 1659.11  4943.8  1654.6  4952.8 1650.87    4984    1641
  4996.5 1639.29  5046.3 1645.36  5196.6 1646.64  5227.8  1650.8  5258.9 1651.22
  5295.3 1659.64  5326.5 1670.54  5352.3 1674.67    5508 1685.91  5537.3 1687.52
#Mann= 8 ,-1 , 0
  3660.8     .05       0  3766.7      .1       0  3915.1     .16       0
  3964.7     .08       0  4912.2     .05       0  5258.9     .07       0
  5258.9     .08       0    5508     .05       0
#XS Ineff= 2 , 0
         4748.96  1664.8
Permanent Ineff=
       T       T
Bank Sta=4952.8,5258.9
XS Rating Curve= 0 ,0
Exp/Cntr=0.3,0.1

Type RM Length L Ch R = 1 ,13866   ,178,178,178
XS GIS Cut Line= 5
      2744365.29     10058061.33      2743985.59      10057434.8
      2743795.49     10057257.72      2743477.78     10057156.16
      2742782.97     10057137.94
#Sta/Elev= 30
  3482.3 1693.01  3543.8 1690.18  3559.2 1685.83  3644.6 1682.72  3681.4 1676.03
  3748.4 1671.76  3770.6 1667.84  3776.5 1669.43  3791.9 1665.12  3797.8 1666.79
  3819.1 1662.42  3871.5 1660.93  3877.3 1658.83    3887 1660.52  3892.8 1657.84
  3908.3  1659.9  3958.9 1651.64  4009.1 1659.42  4241.8 1664.06  4468.5 1657.62
  4795.8    1654  4897.6 1648.34  4997.4 1638.53  5067.7 1641.83  5107.7 1649.47
  5147.7 1655.91  5167.7 1662.47  5197.7 1663.68  5237.7 1672.02  5503.3 1688.85
#Mann= 3 , 0 , 0
  3482.3     .16       0  4897.6     .07       0  5107.7     .16       0
#XS Ineff= 2 , 0
         4232.37 1664.26
Permanent Ineff=
       T       T
Bank Sta=4897.6,5107.7
XS Rating Curve= 0 ,0
Exp/Cntr=0.3,0.1

Type RM Length L Ch R = 1 ,13688   ,359,359,359
BEGIN DESCRIPTION:
LIVE OAK CREEK 24.0
END DESCRIPTION:
XS GIS Cut Line= 4
      2744391.83     10057460.84      2743977.07     10057142.59
      2743612.49     10056996.76       2742768.7     10056972.45
#Sta/Elev= 30
  3783.1 1671.07  3798.3 1669.64    3869 1663.19  3933.4 1652.39  3954.2 1651.95
  4132.8 1655.89  4176.3 1660.98  4217.9 1656.72  4261.5 1661.99  4336.7    1664
  4455.7 1653.41  4636.1 1649.31  4671.1 1646.25    4690 1648.75  4695.4    1646
  4732.6 1642.77  4752.6 1644.11  4812.6 1655.36  4892.7 1653.88  4912.7 1649.03
  4942.7 1642.96  4992.5 1638.44  5042.7 1641.52  5082.7 1649.76  5132.8 1665.84
  5162.8 1669.59  5192.8 1667.93  5222.8 1672.87  5342.8 1682.16  5542.7 1685.02
#Mann= 5 ,-1 , 0
  3783.1     .05       0  3798.3     .16       0  4912.7     .05       0
  4912.7     .07       0  5082.7     .16       0
#XS Ineff= 2 ,-1
  3819.5 4331.95 1663.97 4404.56 4815.35 1655.22
Permanent Ineff=
       T       T
Bank Sta=4912.7,5082.7
XS Rating Curve= 0 ,0
Exp/Cntr=0.3,0.1

Type RM Length L Ch R = 1 ,13329   ,492,492,492
XS GIS Cut Line= 4
      2744105.39     10056924.39      2743706.95     10056713.45
      2743222.57      10056617.1       2742925.7     10056653.55
#Sta/Elev= 30
  4299.6 1678.74  4328.7 1677.04    4364 1677.11  4394.7 1675.13  4444.4 1667.07
  4482.7 1662.12  4521.1  1654.5  4533.7 1653.31  4750.4 1647.92  4769.3 1645.78
  4774.5  1644.3  4825.6 1639.34  4850.8 1639.61  4876.7 1641.89  4881.8 1640.36
  4942.6 1642.76  4993.3  1637.7    5014 1639.47  5024.2 1641.74  5035.2    1647
    5065 1659.49  5095.5 1668.04  5105.7 1668.77  5183.4 1667.68  5228.1  1668.7
  5260.6 1670.95  5298.8 1677.41    5319 1678.76  5399.6 1679.68  5543.4 1678.73
#Mann= 3 , 0 , 0
  4299.6     .16       0  4750.4     .07       0  5035.2     .16       0
Bank Sta=4750.4,5035.2
XS Rating Curve= 0 ,0
Exp/Cntr=0.3,0.1

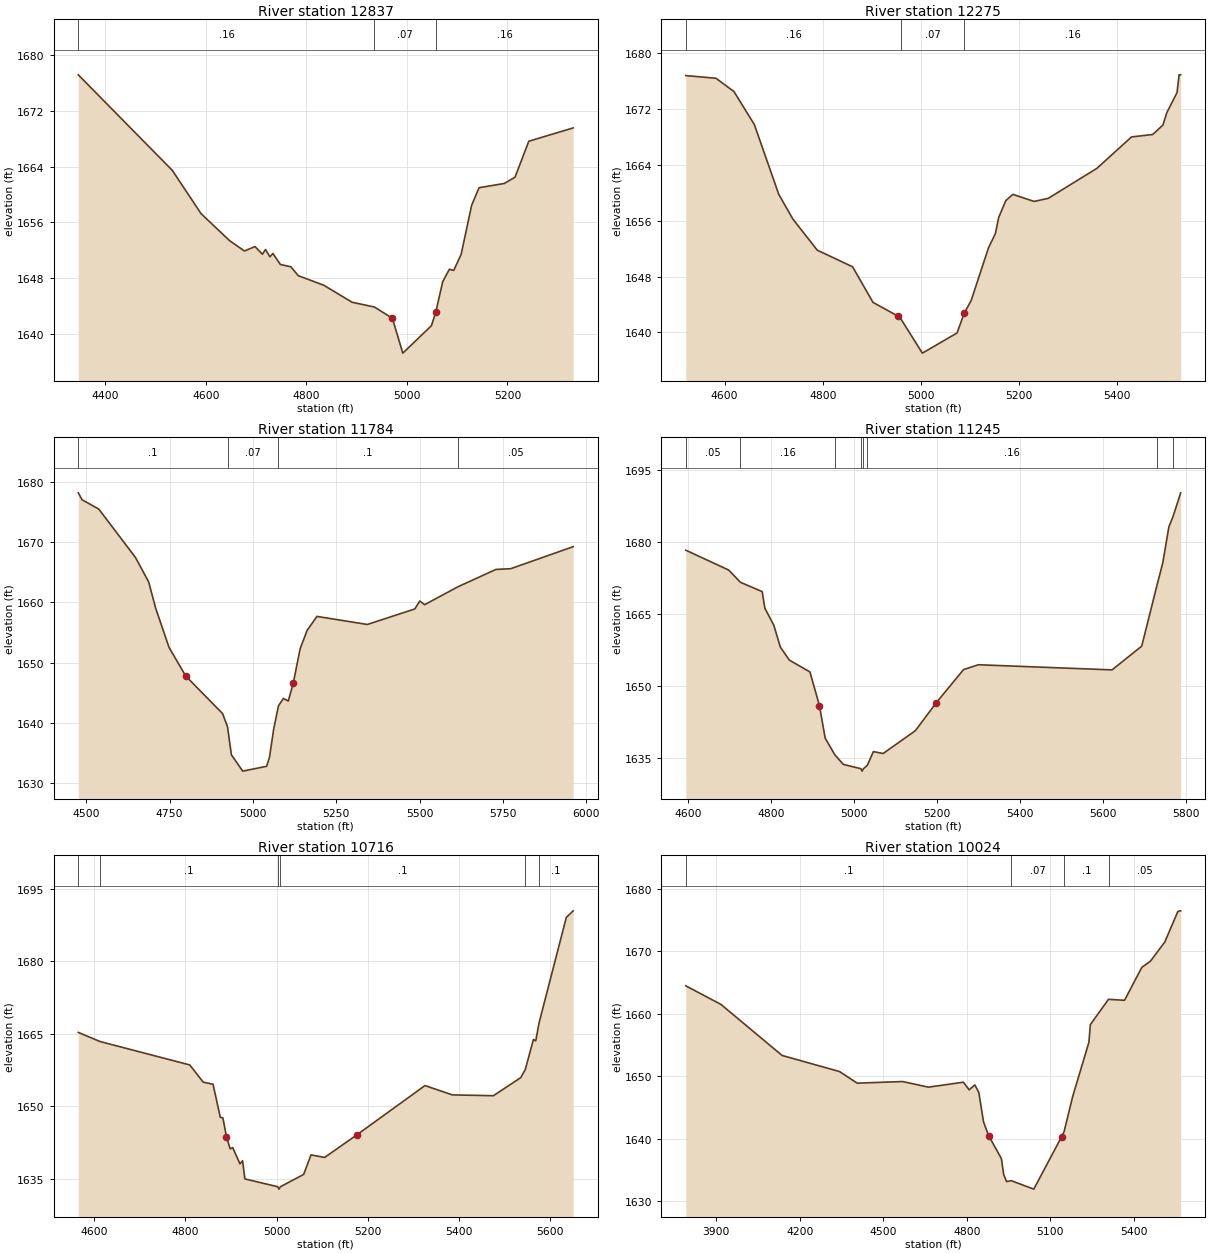
Type RM Length L Ch R = 1 ,12837   ,562,562,562
BEGIN DESCRIPTION:
LIVE OAK CREEK 23.0
END DESCRIPTION:
XS GIS Cut Line= 2
      2744331.34     10056690.84      2743526.25     10056123.87
#Sta/Elev= 30
  4346.1 1677.16  4533.1 1663.47  4590.5 1657.25  4647.1 1653.39  4676.7  1651.9
  4697.7 1652.54  4712.5 1651.44  4718.6 1652.12  4727.3 1651.07  4733.4 1651.54
  4748.2 1649.97  4769.1 1649.64  4783.9 1648.36  4834.4    1647    4891 1644.55
  4935.4 1643.87  4971.1 1642.25  4991.8 1637.26  5048.7 1641.19  5057.4 1643.14
  5071.2  1647.5  5084.4 1649.28  5093.1 1649.12  5107.9 1651.43  5128.8 1658.47
  5143.6 1660.98  5193.5 1661.58    5215 1662.48  5242.5 1667.64  5330.8 1669.55
#Mann= 3 ,-1 , 0
  4346.1     .16       0  4935.4     .07       0  5057.4     .16       0
Bank Sta=4971.1,5057.4
XS Rating Curve= 0 ,0
Exp/Cntr=0.3,0.1

Type RM Length L Ch R = 1 ,12275   ,491,491,491
BEGIN DESCRIPTION:
LIVE OAK CREEK 22.0
END DESCRIPTION:
XS GIS Cut Line= 2
      2744586.54     10056242.95      2743798.41     10055613.57
#Sta/Elev= 30
  4520.9 1676.81  4582.4 1676.43  4619.1 1674.53  4660.7 1669.79  4710.4  1659.8
  4739.2 1656.25  4788.8  1651.8  4860.9 1649.41  4902.5 1644.31  4953.5 1642.34
  4960.1 1641.85  5003.1 1637.04  5073.8 1639.93  5088.2 1642.74  5102.6 1644.59
  5137.9 1652.14  5151.9 1654.17  5158.7 1656.49  5173.1 1658.89  5187.5 1659.79
  5230.7 1658.78  5259.6 1659.22  5358.8 1663.52  5429.3 1668.02  5472.5 1668.37
  5493.3 1669.72  5501.3  1671.5  5522.1 1674.38  5526.3 1676.92  5529.5 1676.92
#Mann= 3 ,-1 , 0
  4520.9     .16       0  4960.1     .07       0  5088.2     .16       0
Bank Sta=4953.5,5088.2
XS Rating Curve= 0 ,0
Exp/Cntr=0.3,0.1

Type RM Length L Ch R = 1 ,11784   ,539,539,539
BEGIN DESCRIPTION:
LIVE OAK CREEK 21.0
END DESCRIPTION:
XS GIS Cut Line= 3
      2745079.85     10055687.28      2744620.54     10055647.59
      2743787.05     10055052.24
#Sta/Elev= 30
  4475.7 1678.21  4487.1 1677.06  4537.3 1675.51  4647.7 1667.45    4687 1663.41
  4707.9 1659.06  4748.1 1652.54  4798.3 1647.78  4908.7 1641.56  4923.6 1639.36
  4935.2 1634.71  4969.3    1632  5040.9  1632.8  5049.5 1634.29  5062.2 1639.01
  5076.5 1642.84  5091.2 1644.07    5106 1643.64  5120.7 1646.56  5141.6 1652.33
  5162.5 1655.37    5192 1657.69  5343.2 1656.35  5485.7 1658.93  5500.5 1660.25
  5515.2 1659.64  5615.2 1662.61    5729 1665.49  5773.3 1665.61    5961 1669.27
#Mann= 4 ,-1 , 0
  4475.7      .1       0  4923.6     .07       0  5076.5      .1       0
  5615.2     .05       0
Bank Sta=4798.3,5120.7
XS Rating Curve= 0 ,0
Exp/Cntr=0.3,0.1

Type RM Length L Ch R = 1 ,11245   ,529,529,529
BEGIN DESCRIPTION:
LIVE OAK CREEK 20.0
END DESCRIPTION:
XS GIS Cut Line= 3
      2745268.51     10055403.75      2744918.47     10055203.73
      2744268.49     10054753.75
#Sta/Elev= 30
    4594 1678.36  4697.7 1674.21  4725.8 1671.67  4778.3 1669.72  4784.8 1666.26
  4806.4 1662.71  4822.2 1658.15  4843.8 1655.45  4893.5 1652.98  4916.5 1645.96
  4930.2  1639.2  4953.6  1635.7  4974.1 1633.71  5016.5 1632.81  5019.2 1632.31
  5022.5 1632.81  5032.1 1633.54  5046.5 1636.38  5070.1 1635.98  5147.8 1640.74
  5198.5  1646.6  5264.1 1653.48  5299.9 1654.48  5622.2 1653.41  5693.8 1658.36
  5729.6 1670.72  5744.5  1675.7  5759.3 1683.24  5769.3 1685.36  5787.7 1690.31
#Mann= 8 ,-1 , 0
    4594     .05       0  4725.8     .16       0  4953.6      .1       0
  5016.5     .07       0  5022.5      .1       0  5032.1     .16       0
  5729.6     .05       0  5769.3      .1       0
Bank Sta=4916.5,5198.5
XS Rating Curve= 0 ,0
Exp/Cntr=0.3,0.1

Type RM Length L Ch R = 1 ,10716   ,692,692,692
BEGIN DESCRIPTION:
LIVE OAK CREEK 19.0
END DESCRIPTION:
XS GIS Cut Line= 3
      2745300.94     10054865.14      2744983.42      10054683.7
      2744263.38     10054712.05
#Sta/Elev= 30
  4564.8 1665.28    4613 1663.38  4809.5 1658.55    4839 1654.99  4860.6 1654.56
  4876.5 1647.73  4882.2 1647.59  4890.1 1643.72  4898.1  1641.2  4903.8 1641.45
  4919.7 1638.08  4925.4 1638.72  4930.5 1634.97  5002.5 1633.36  5005.3 1632.86
  5008.5 1633.36  5059.5  1635.9  5075.6 1639.94  5105.6 1639.42  5175.7 1644.05
  5325.8 1654.28  5385.8 1652.36  5475.9 1652.18  5535.9 1655.92  5545.9 1657.59
  5563.9 1663.83  5568.9 1663.52  5576.3 1667.29    5636 1689.06  5651.1 1690.43
#Mann= 6 ,-1 , 0
  4564.8     .05       0    4613      .1       0  5002.5     .07       0
  5008.5      .1       0  5545.9     .05       0  5576.3      .1       0
Bank Sta=4890.1,5175.7
XS Rating Curve= 0 ,0
Exp/Cntr=0.3,0.1

Type RM Length L Ch R = 1 ,10024   ,642,642,642
BEGIN DESCRIPTION:
LIVE OAK CREEK 18.0
END DESCRIPTION:
XS GIS Cut Line= 3
      2745587.76     10054602.54      2744887.01     10053997.35
      2744063.43     10054211.21
#Sta/Elev= 30
    3791 1664.47  3917.4 1661.49  4136.8 1653.32    4343 1650.74  4406.6 1648.88
  4569.6 1649.14  4662.1 1648.24  4787.7 1649.04  4808.4 1647.81    4829  1648.6
  4843.2 1647.38    4860 1642.69  4878.5 1640.46  4924.3 1636.79  4932.4 1634.25
  4942.7 1633.12  4959.7 1633.26  5040.5 1631.91  5140.6 1640.32  5149.3 1641.12
  5180.3 1646.78  5238.4 1655.43  5243.6 1658.26  5308.7 1662.31  5366.3 1662.15
  5428.3 1667.42  5459.3 1668.42  5510.9 1671.49  5557.7 1676.38  5567.8 1676.48
#Mann= 4 ,-1 , 0
    3791      .1       0  4959.7     .07       0  5149.3      .1       0
  5308.7     .05       0
Bank Sta=4878.5,5140.6
XS Rating Curve= 0 ,0
Exp/Cntr=0.3,0.1

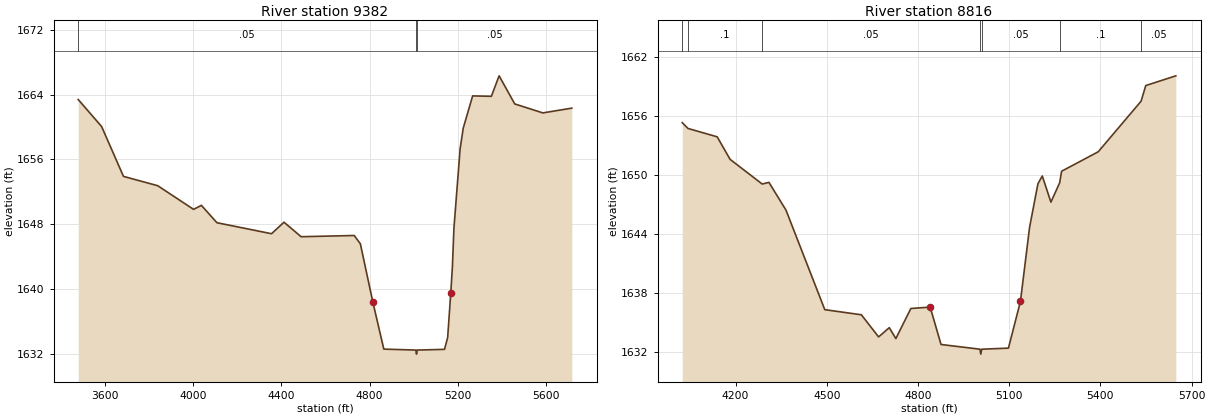
Type RM Length L Ch R = 1 ,9382    ,566,566,566
BEGIN DESCRIPTION:
LIVE OAK CREEK 17.0
END DESCRIPTION:
XS GIS Cut Line= 2
      2745669.65     10054502.42      2744022.98     10052983.11
#Sta/Elev= 30
  3477.8  1663.4    3584 1660.07  3683.2 1653.91  3838.6 1652.76  4001.3 1649.84
    4037 1650.33  4107.4 1648.19  4355.2 1646.83  4411.9 1648.25  4489.5 1646.46
  4730.5 1646.61  4758.4 1645.59    4815 1638.41  4864.9 1632.58  5010.5 1632.46
  5013.3 1631.96  5016.5 1632.46  5140.5 1632.55  5154.7 1634.01  5168.9 1639.53
  5176.3 1642.75  5183.1 1647.47  5211.4 1657.35  5225.6 1659.88  5268.1 1663.85
  5353.2  1663.8  5388.3 1666.33  5459.2 1662.86  5586.8 1661.75  5718.3 1662.34
#Mann= 3 ,-1 , 0
  3477.8     .05       0  5010.5    .033       0  5016.5     .05       0
Bank Sta=4815,5168.9
XS Rating Curve= 0 ,0
Exp/Cntr=0.3,0.1

Type RM Length L Ch R = 1 ,8816    ,835,835,835
BEGIN DESCRIPTION:
LIVE OAK CREEK 16.0
END DESCRIPTION:
XS GIS Cut Line= 4
       2745660.6     10054183.93      2745064.48      10053533.2
      2745078.13     10053251.07      2744734.31     10052947.97
#Sta/Elev= 30
  4024.7  1655.3  4043.6 1654.71  4139.6 1653.86  4182.1 1651.57  4287.7 1649.06
  4309.8 1649.23  4365.9 1646.41  4493.5 1636.29  4613.8 1635.77  4670.5 1633.52
  4705.6 1634.46  4727.2 1633.35  4776.6 1636.41  4840.1 1636.55  4875.8 1632.75
  5003.8 1632.27  5006.5 1631.77  5009.8 1632.27  5097.5 1632.38  5136.9 1637.12
    5167 1644.66  5194.5 1649.09  5208.8 1649.88  5237.2 1647.22    5266 1649.19
  5272.3 1650.36  5392.8 1652.34  5533.7 1657.48  5549.1 1659.07    5648 1660.06
#Mann= 7 ,-1 , 0
  4024.7     .05       0  4043.6      .1       0  4287.7     .05       0
  5003.8    .033       0  5009.8     .05       0    5266      .1       0
  5533.7     .05       0
Bank Sta=4840.1,5136.9
XS Rating Curve= 0 ,0
Exp/Cntr=0.3,0.1