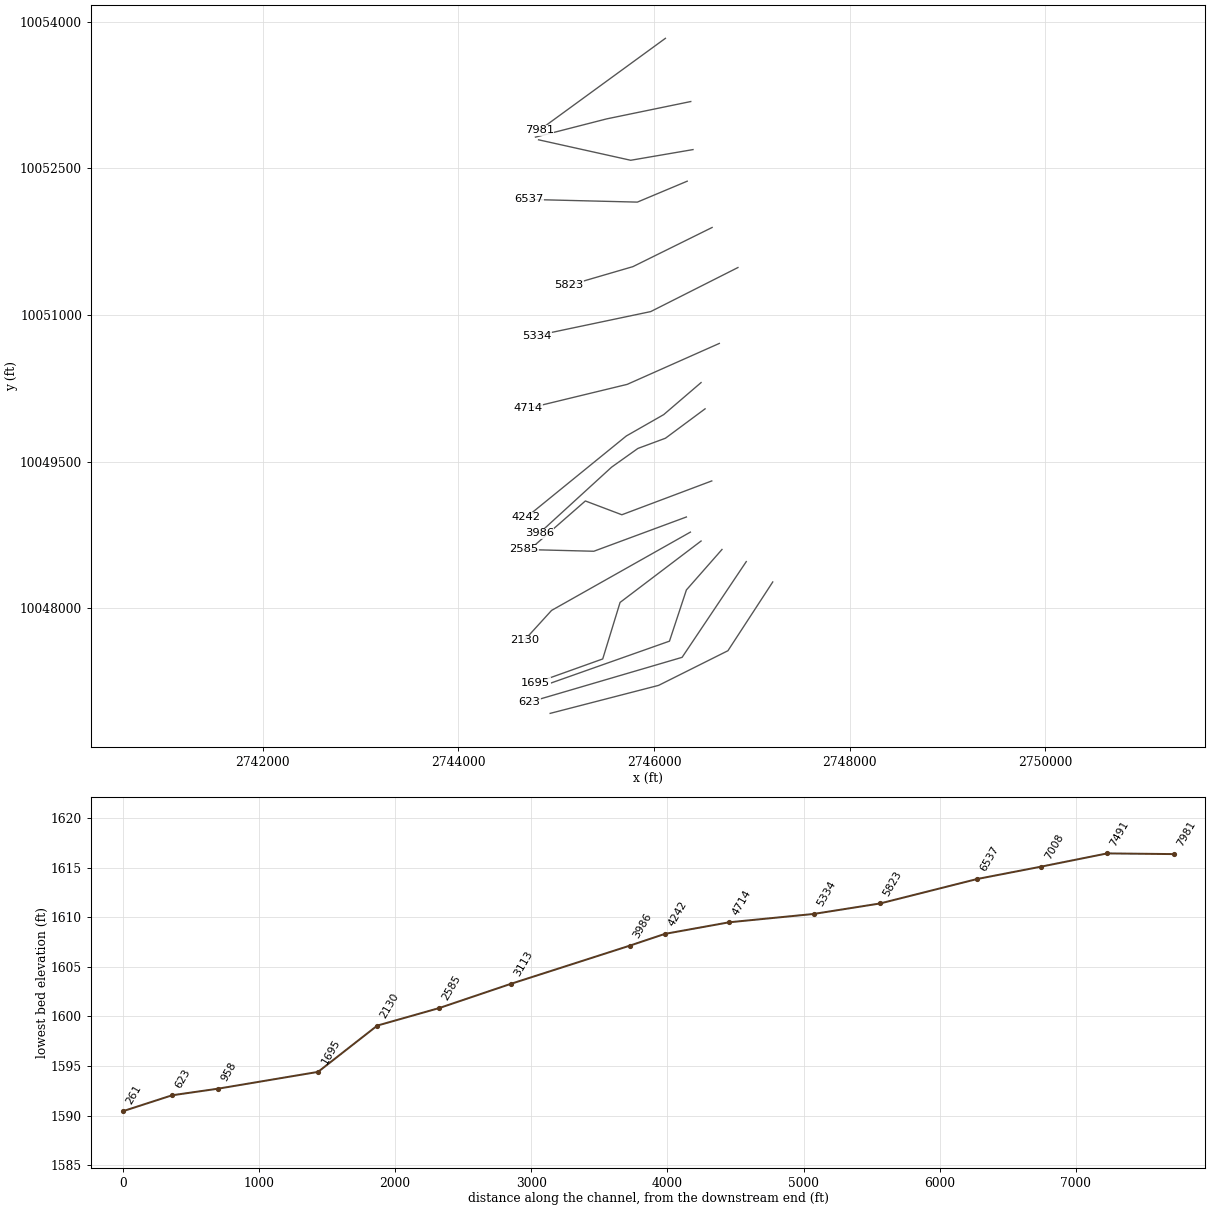
HEC-RAS study LIVE OAK CREEK.prj: LIVE OAK CREEK Base Level Engineering

--- LIVE OAK CREEK.g01 (geometry) --- (continued)

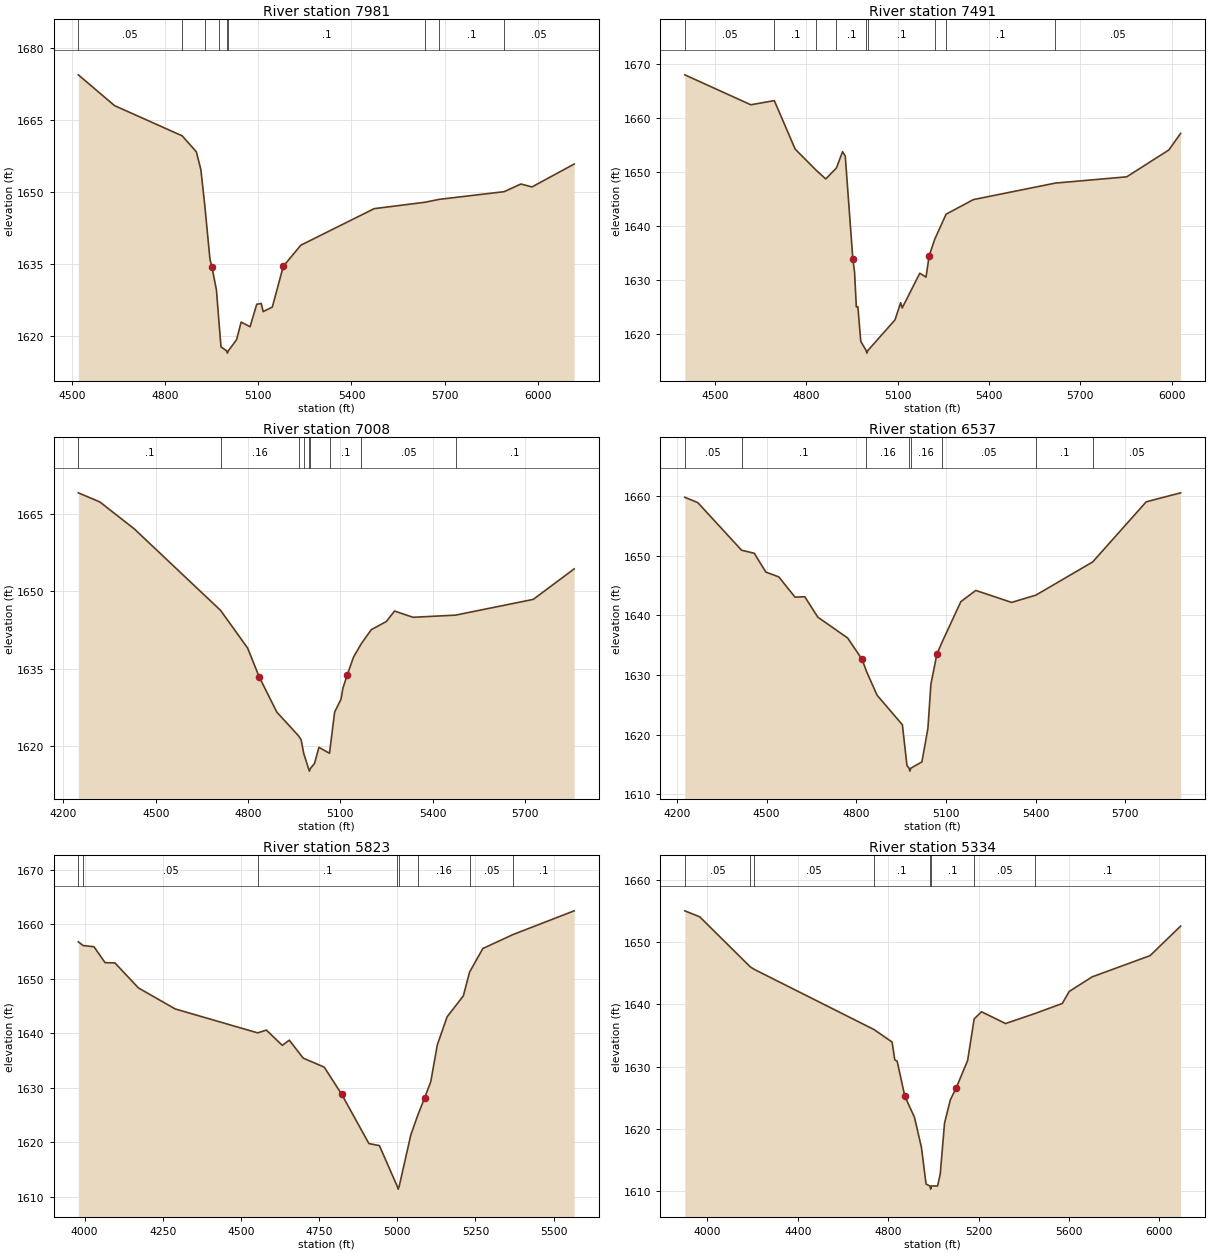
Type RM Length L Ch R = 1 ,7981    ,490,490,490
BEGIN DESCRIPTION:
LIVE OAK CREEK 15.0
END DESCRIPTION:
XS GIS Cut Line= 2
      2746115.62     10053828.98      2744824.57     10052887.96
#Sta/Elev= 30
    4520 1674.42  4636.6    1668  4854.5  1661.7  4900.1 1658.38  4914.8 1654.66
  4927.1 1647.42  4944.1 1635.98  4950.3 1634.38    4965 1629.57  4972.8 1623.14
  4979.7 1617.68  4997.5 1616.88  5000.3 1616.38  5003.5 1616.88  5029.9 1619.18
  5044.6 1622.86  5073.3 1621.88  5094.8 1626.57  5109.4 1626.73  5115.6 1625.04
    5145 1625.98  5180.5  1634.5  5236.9 1638.89  5473.3 1646.51  5637.3 1647.85
  5682.9 1648.45  5891.8 1650.05  5946.1 1651.65  5981.7 1651.04  6117.6 1655.81
#Mann= 9 ,-1 , 0
    4520     .05       0  4854.5      .1       0  4927.1     .16       0
  4972.8      .1       0  4997.5     .07       0  5003.5      .1       0
  5637.3     .05       0  5682.9      .1       0  5891.8     .05       0
Bank Sta=4950.3,5180.5
XS Rating Curve= 0 ,0
Exp/Cntr=0.3,0.1

Type RM Length L Ch R = 1 ,7491    ,483,483,483
BEGIN DESCRIPTION:
LIVE OAK CREEK 14.0
END DESCRIPTION:
XS GIS Cut Line= 3
      2746374.97     10053182.81      2745514.97     10053005.35
      2744786.91     10052818.78
#Sta/Elev= 30
    4400 1668.02    4617 1662.47  4694.2 1663.24  4762.7 1654.26  4832.7 1650.29
  4863.3 1648.73  4898.3 1650.76  4918.6 1653.78  4927.4 1652.97 4952.44 1633.82
    4958 1631.46  4963.8    1625  4968.9 1625.05  4978.4 1618.63  4995.9 1616.95
  4998.6 1616.45  5001.9 1616.95  5090.8  1622.6  5109.5 1625.79  5114.6 1624.82
  5172.4 1631.26  5192.9 1630.54  5203.1 1634.47  5221.8  1637.6  5258.8 1642.19
  5348.5  1644.9  5618.1 1647.96  5852.6 1649.12  5990.8 1654.09  6029.7 1657.17
#Mann= 9 ,-1 , 0
    4400     .05       0  4694.2      .1       0  4832.7     .16       0
  4898.3      .1       0  4995.9     .07       0  5001.9      .1       0
  5221.8     .05       0  5258.8      .1       0  5618.1     .05       0
Bank Sta=4952.44,5203.1
XS Rating Curve= 0 ,0
Exp/Cntr=0.3,0.1

Type RM Length L Ch R = 1 ,7008    ,471,471,471
BEGIN DESCRIPTION:
LIVE OAK CREEK 13.0
END DESCRIPTION:
XS GIS Cut Line= 3
      2746397.77     10052691.37       2745760.7     10052582.16
      2744818.74     10052791.48
#Sta/Elev= 30
  4248.6 1669.05  4318.6 1667.28  4430.5 1662.06  4710.9 1646.27  4798.9 1638.96
  4836.4 1633.38  4893.6 1626.56  4964.3 1621.96  4972.7 1621.19    4981 1618.57
  4996.7 1615.62  4999.4 1615.12  5002.7 1615.62  5016.3 1616.63  5030.4 1619.73
  5064.9 1618.58  5066.3 1619.28  5081.6 1626.58  5102.1 1629.04  5108.5 1631.22
  5122.6 1633.78  5143.1 1637.24  5168.4 1639.83  5200.7 1642.54  5249.3  1644.1
  5276.3 1646.14  5336.4 1644.93  5474.6 1645.35    5727  1648.4  5859.9 1654.31
#Mann= 9 ,-1 , 0
  4248.6      .1       0  4710.9     .16       0  4964.3      .1       0
    4981     .05       0  4996.7    .035       0  5002.7     .05       0
  5066.3      .1       0  5168.4     .05       0  5474.6      .1       0
Bank Sta=4836.4,5122.6
XS Rating Curve= 0 ,0
Exp/Cntr=0.3,0.1

Type RM Length L Ch R = 1 ,6537    ,714,714,714
BEGIN DESCRIPTION:
LIVE OAK CREEK 12.0
END DESCRIPTION:
XS GIS Cut Line= 3
      2746338.58     10052368.28      2745828.95     10052154.42
      2744723.37     10052181.71
#Sta/Elev= 30
  4226.1 1659.82  4269.6 1658.93  4416.1 1650.94  4458.4 1650.43  4497.3 1647.27
  4540.7 1646.46  4594.9 1643.06  4627.5 1643.14  4670.9 1639.72  4770.8 1636.21
  4819.3 1632.62  4833.6 1630.64  4869.3 1626.61    4954 1621.65  4969.3  1614.8
  4976.3 1614.37  4979.1 1613.87  4982.3 1614.37  5019.3 1615.42  5039.3 1621.02
  5049.3 1628.44  5069.4 1633.51  5085.6 1635.39  5149.4  1642.3  5199.4 1644.19
  5319.4 1642.18  5400.4  1643.4  5590.5 1648.97  5769.6 1659.06  5884.7 1660.57
#Mann= 8 ,-1 , 0
  4226.1     .05       0  4416.1      .1       0  4833.6     .16       0
  4976.3     .07       0  4982.3     .16       0  5085.6     .05       0
  5400.4      .1       0  5590.5     .05       0
Bank Sta=4819.3,5069.4
XS Rating Curve= 0 ,0
Exp/Cntr=0.3,0.1

Type RM Length L Ch R = 1 ,5823    ,489,489,489
BEGIN DESCRIPTION:
LIVE OAK CREEK 11.0
END DESCRIPTION:
XS GIS Cut Line= 3
      2746593.41     10051895.03      2745783.45      10051494.6
      2745128.19     10051303.48
#Sta/Elev= 30
  3979.8 1656.79  3994.9 1656.11  4029.9 1655.89  4065.3 1652.97  4096.9 1652.92
    4172 1648.33  4289.7 1644.47  4553.5 1640.08  4581.4 1640.59  4632.3 1637.79
  4654.6 1638.74  4699.3 1635.44  4766.5 1633.79    4822 1628.83  4909.4 1619.76
  4942.9 1619.39  5000.1  1611.9  5002.9  1611.4  5006.1  1611.9  5043.4 1621.35
  5065.9    1625  5087.3 1628.12  5107.3 1631.14  5128.1 1637.86  5159.4 1643.02
  5211.4 1646.87  5231.4 1651.24  5273.9 1655.57  5370.9 1658.14  5565.9 1662.48
#Mann= 8 ,-1 , 0
  3979.8      .1       0  3994.9     .05       0  4553.5      .1       0
  5000.1     .07       0  5006.1      .1       0  5065.9     .16       0
  5231.4     .05       0  5370.9      .1       0
Bank Sta=4822,5087.3
XS Rating Curve= 0 ,0
Exp/Cntr=0.3,0.1

Type RM Length L Ch R = 1 ,5334    ,620,620,620
BEGIN DESCRIPTION:
LIVE OAK CREEK 10.0
END DESCRIPTION:
XS GIS Cut Line= 3
      2746857.37      10051485.5      2745965.47     10051035.01
      2744796.02     10050789.28
#Sta/Elev= 30
  3900.2 1655.04  3966.2 1654.08    4190 1646.04  4208.5 1645.62  4737.6 1635.97
  4817.6 1633.96  4829.5  1631.1    4840 1630.88  4874.1 1625.24  4916.8 1621.86
  4947.4 1617.04  4967.9 1611.15  4985.3 1610.84  4988.1 1610.34  4991.3 1610.84
    5019 1610.85  5030.7 1612.78  5049.6 1620.93  5075.5  1624.7  5100.7 1626.55
  5151.8    1631  5180.8 1637.68  5213.1 1638.83  5319.7 1636.94  5447.8 1638.52
  5570.8 1640.16  5601.4 1642.09  5703.3 1644.44  5959.1 1647.84  6094.4 1652.59
#Mann= 8 ,-1 , 0
  3900.2     .05       0    4190      .1       0  4208.5     .05       0
  4737.6      .1       0  4985.3     .07       0  4991.3      .1       0
  5180.8     .05       0  5447.8      .1       0
Bank Sta=4874.1,5100.7
XS Rating Curve= 0 ,0
Exp/Cntr=0.3,0.1

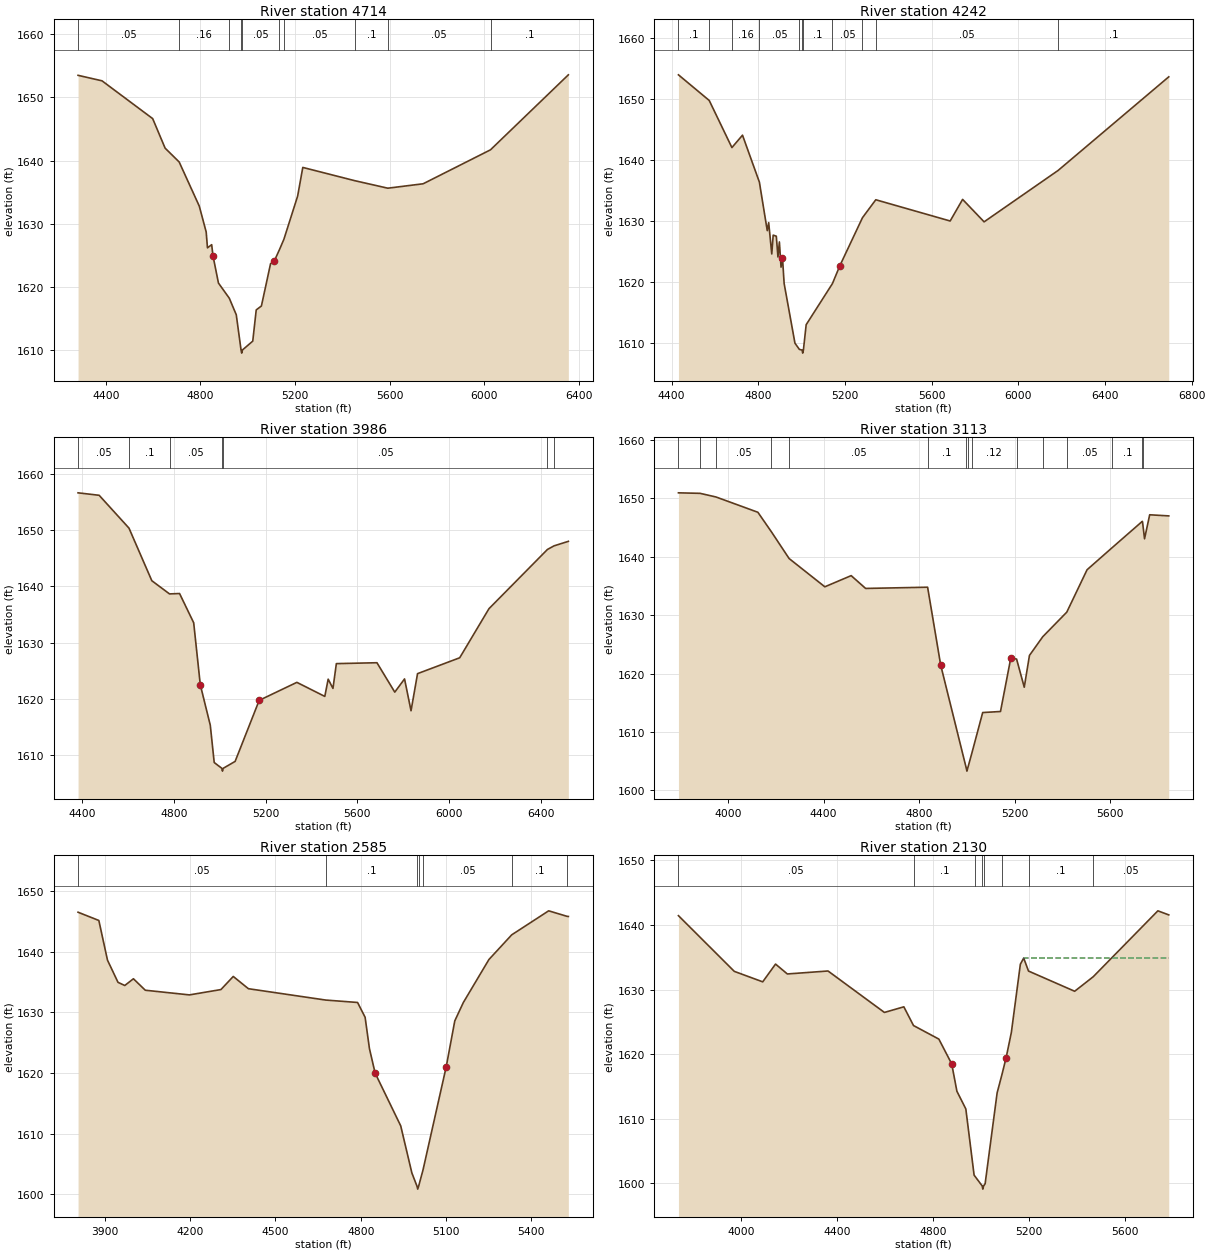
Type RM Length L Ch R = 1 ,4714    ,472,472,472
BEGIN DESCRIPTION:
LIVE OAK CREEK 9.0
END DESCRIPTION:
XS GIS Cut Line= 3
       2746666.9     10050709.49      2745724.99     10050290.86
      2744711.83     10050045.52
#Sta/Elev= 30
  4282.5 1653.51  4383.8 1652.64  4598.1 1646.65  4650.5 1641.98  4710.1 1639.78
  4795.1 1632.79  4824.3 1628.69  4829.7 1626.18  4847.5 1626.68    4853 1624.92
  4876.2  1620.6    4922  1618.2  4951.5 1615.58  4971.7    1610  4974.5  1609.5
  4977.7    1610  5021.2  1611.4  5035.9 1616.35  5057.8 1616.97  5096.5 1623.67
  5112.5 1624.11  5133.8 1625.87    5153 1627.55    5211 1634.38  5232.8 1638.92
  5452.5 1636.82  5592.2 1635.63  5741.8 1636.33  6026.5 1641.71  6355.7 1653.59
#Mann= 10 ,-1 , 0
  4282.5     .05       0  4710.1     .16       0    4922     .05       0
  4971.7    .035       0  4977.7     .05       0  5133.8      .1       0
    5153     .05       0  5452.5      .1       0  5592.2     .05       0
  6026.5      .1       0
Bank Sta=4853,5112.5
XS Rating Curve= 0 ,0
Exp/Cntr=0.3,0.1

Type RM Length L Ch R = 1 ,4242    ,256,256,256
BEGIN DESCRIPTION:
LIVE OAK CREEK 8.0
END DESCRIPTION:
XS GIS Cut Line= 4
      2746480.35     10050309.05      2746098.12     10049981.43
      2745715.89     10049763.01      2744692.73     10048930.84
#Sta/Elev= 30
  4431.8 1653.93  4573.8 1649.73  4678.5 1642.01  4727.4 1644.04  4805.3 1636.35
  4841.6  1628.4  4848.2 1629.71  4862.4 1624.58    4869 1627.66  4883.3 1627.49
    4891 1624.08  4897.6 1626.55  4905.2 1622.42  4911.8 1623.99  4919.5 1619.74
  4969.4 1609.96  4989.9 1608.94  5002.4 1608.83  5005.2 1608.33  5008.4 1608.83
  5021.2 1612.99  5142.3 1619.72  5176.7 1622.66    5281 1630.52  5342.4 1633.46
  5685.6 1629.98  5743.1 1633.52  5842.2 1629.84  6183.7 1638.26  6694.3  1653.6
#Mann= 11 ,-1 , 0
  4431.8      .1       0  4573.8     .05       0  4678.5     .16       0
  4805.3     .05       0  4989.9      .1       0  5002.4     .07       0
  5008.4      .1       0  5142.3     .05       0    5281      .1       0
  5342.4     .05       0  6183.7      .1       0
Bank Sta=4911.8,5176.7
XS Rating Curve= 0 ,0
Exp/Cntr=0.3,0.1

Type RM Length L Ch R = 1 ,3986    ,873,873,873
BEGIN DESCRIPTION:
LIVE OAK CREEK 7.0
END DESCRIPTION:
XS GIS Cut Line= 5
      2746521.35     10050040.61      2746116.33     10049740.26
       2745834.2      10049635.6      2745565.72     10049444.48
      2744825.27     10048767.62
#Sta/Elev= 30
  4382.4 1656.65  4474.4 1656.21  4604.5 1650.37    4704 1641.02  4781.2 1638.67
    4825 1638.74  4886.6 1633.54  4915.4 1622.51    4959 1615.31  4976.1 1608.68
  5009.3 1607.65  5012.1 1607.15  5015.3 1607.65  5067.3 1608.88  5172.3 1619.74
  5336.5 1622.94  5458.3 1620.44    5473 1623.51  5493.9 1621.86  5508.7 1626.27
  5685.7 1626.43  5763.4  1621.2    5806 1623.55  5834.3 1617.89  5862.7 1624.49
  6046.5 1627.31  6174.1 1636.04  6429.2 1646.58    6458 1647.22  6520.3 1648.02
#Mann= 7 ,-1 , 0
  4382.4     .05       0  4604.5      .1       0  4781.2     .05       0
  5009.3     .04       0  5015.3     .05       0  6429.2      .1       0
    6458     .05       0
Bank Sta=4915.4,5172.3
XS Rating Curve= 0 ,0
Exp/Cntr=0.3,0.1

Type RM Length L Ch R = 1 ,3113    ,528,528,528
BEGIN DESCRIPTION:
LIVE OAK CREEK 6.0
END DESCRIPTION:
XS GIS Cut Line= 4
       2746589.6     10049303.42      2745670.38     10048957.58
      2745297.25     10049098.64      2744792.16     10048657.26
#Sta/Elev= 30
  3792.6 1650.95  3883.3 1650.86  3949.7 1650.24    4125 1647.62  4181.2  1644.3
  4255.7  1639.7  4405.2 1634.86  4515.4 1636.77  4575.9 1634.58  4835.3 1634.79
  4890.1 1621.44  4997.1  1603.8  4999.8  1603.3  5003.1  1603.8  5019.8 1606.28
  5065.8 1613.33  5140.3 1613.51  5183.7 1622.73  5207.7 1622.48  5239.7 1617.67
  5261.5 1623.11  5317.1 1626.31  5417.7 1630.52  5502.6 1637.78  5608.4 1641.59
  5733.9 1646.07  5734.7 1645.97  5743.1 1643.08  5764.6 1647.19  5844.4    1647
#Mann= 15 ,-1 , 0
  3792.6     .05       0  3883.3      .1       0  3949.7     .05       0
  4181.2      .1       0  4255.7     .05       0  4835.3      .1       0
  4997.1     .07       0  5003.1      .1       0  5019.8     .12       0
  5207.7     .05       0  5317.1      .1       0  5417.7     .05       0
  5608.4      .1       0  5733.9     .05       0  5734.7      .1       0
Bank Sta=4890.1,5183.7
XS Rating Curve= 0 ,0
Exp/Cntr=0.3,0.1

Type RM Length L Ch R = 1 ,2585    ,455,455,455
BEGIN DESCRIPTION:
LIVE OAK CREEK 5.0
END DESCRIPTION:
XS GIS Cut Line= 3
      2746330.19     10048934.82       2745383.7     10048584.44
      2744669.29     10048602.64
#Sta/Elev= 30
  3806.2  1646.5  3879.3 1645.14  3909.7  1638.6  3946.7 1634.94  3970.5 1634.42
  4000.9 1635.53  4042.6 1633.64  4197.7 1632.87  4308.6 1633.75  4351.9 1635.91
  4405.2 1633.89  4676.9 1632.02    4789 1631.62  4815.5 1629.18  4830.7 1624.02
  4850.7 1619.98  4940.7 1611.28  4979.8 1603.53  4997.8 1601.35  5000.5 1600.85
  5003.8 1601.35  5019.2 1604.04  5100.8 1621.05  5130.8 1628.59  5160.8 1631.61
  5250.8  1638.7  5330.9 1642.77  5460.9 1646.73  5525.6 1645.82  5530.1  1645.8
#Mann= 7 ,-1 , 0
  3806.2     .05       0  4676.9      .1       0  4997.8     .07       0
  5003.8      .1       0  5019.2     .05       0  5330.9      .1       0
  5525.6     .05       0
Bank Sta=4850.7,5100.8
XS Rating Curve= 0 ,0
Exp/Cntr=0.3,0.1

Type RM Length L Ch R = 1 ,2130    ,435,435,435
BEGIN DESCRIPTION:
LIVE OAK CREEK 4.0
END DESCRIPTION:
XS GIS Cut Line= 3
      2746371.14     10048780.11      2744951.41     10047979.23
       2744673.8     10047674.32
#Sta/Elev= 30
  3739.2 1641.44  3971.9 1632.81  4090.2 1631.19  4143.7 1633.94  4192.8 1632.41
  4362.3 1632.87  4597.2 1626.45  4678.1 1627.32  4718.4 1624.42    4824 1622.32
  4877.5 1618.48  4899.1 1614.25  4936.3  1611.5  4970.8 1601.24  4976.2 1600.98
  5004.4 1599.58  5007.2 1599.08  5010.4 1599.58  5016.7 1599.91  5066.7 1613.99
  5086.8 1616.83  5104.2 1619.44  5125.9 1623.34  5163.5 1633.92  5177.4 1634.87
  5197.4 1632.86  5389.7 1629.73    5467 1631.98  5736.3 1642.19  5781.6 1641.56
#Mann= 8 ,-1 , 0
  3739.2     .05       0  4718.4      .1       0  4976.2     .16       0
  5004.4     .07       0  5010.4     .16       0  5086.8     .05       0
  5197.4      .1       0    5467     .05       0
#XS Ineff= 2 , 0
                         5178.76         1634.88
Permanent Ineff=
       T       T
Bank Sta=4877.5,5104.2
XS Rating Curve= 0 ,0
Exp/Cntr=0.3,0.1

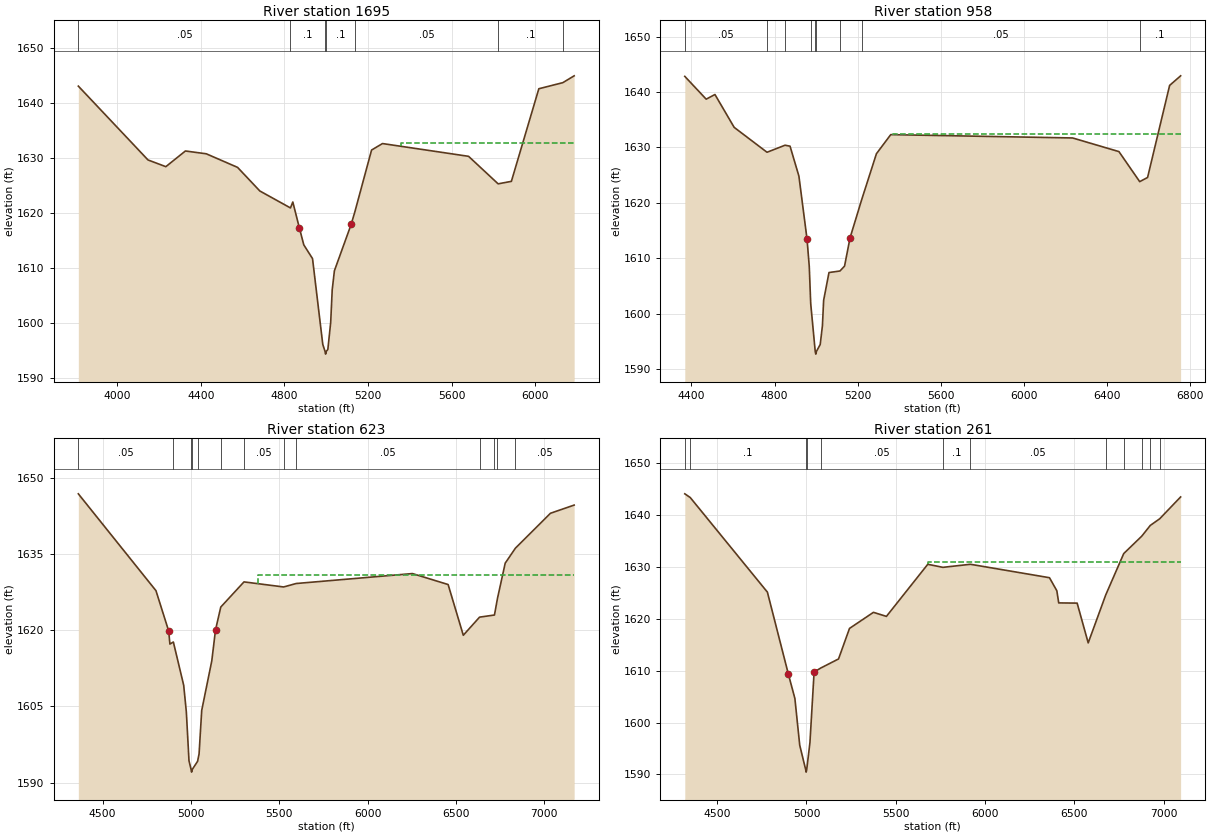
Type RM Length L Ch R = 1 ,1695    ,737,737,737
BEGIN DESCRIPTION:
LIVE OAK CREEK 3.0
END DESCRIPTION:
XS GIS Cut Line= 4
      2746480.35     10048689.09      2745652.18     10048061.14
      2745474.71     10047483.23      2744789.29     10047238.12
#Sta/Elev= 30
  3813.9 1643.12  4147.2  1629.7  4232.5 1628.48  4326.1 1631.33  4425.9 1630.82
  4575.7 1628.35  4682.2 1624.06  4828.7 1620.98  4839.9 1622.06  4871.4 1617.33
  4892.4 1614.27  4934.2 1611.77  4983.2 1596.18    4994 1594.91  4996.7 1594.41
    5000 1594.91  5007.4 1595.25  5021.1 1600.19  5028.3 1606.08  5038.8 1609.56
  5119.3 1618.02  5137.2 1620.34  5216.6  1631.5  5268.9 1632.68  5680.6 1630.36
    5822 1625.36  5885.4 1625.81  6016.7 1642.64  6131.6 1643.75  6185.7 1644.99
#Mann= 7 ,-1 , 0
  3813.9     .05       0  4828.7      .1       0    4994     .07       0
    5000      .1       0  5137.2     .05       0    5822      .1       0
  6131.6     .05       0
#XS Ineff= 2 , 0
                         5355.96         1632.77
Permanent Ineff=
       T       T
Bank Sta=4871.4,5119.3
XS Rating Curve= 0 ,0
Exp/Cntr=0.3,0.1

Type RM Length L Ch R = 1 ,958     ,335,335,335
BEGIN DESCRIPTION:
LIVE OAK CREEK 2.0
END DESCRIPTION:
XS GIS Cut Line= 4
      2746694.25     10048602.66       2746330.2     10048188.55
      2746157.28     10047665.25      2744948.63     10047238.14
#Sta/Elev= 30
  4368.6 1642.82  4471.4 1638.71  4513.6 1639.55  4606.1 1633.62    4764 1629.13
  4850.5  1630.4  4874.7 1630.23  4917.4 1624.82  4956.6 1613.41  4967.2 1608.49
  4974.1 1601.84  4995.8 1593.21  4998.5 1592.71  5001.8 1593.21  5019.8 1594.45
  5030.4 1597.82  5036.3 1602.42    5062 1607.43  5114.9 1607.71  5136.8 1608.59
  5163.3 1613.69    5220 1620.67  5290.2 1628.87  5358.9 1632.31  6233.5 1631.71
  6456.3 1629.25  6556.2 1623.83  6594.1 1624.58  6700.1 1641.19    6753 1642.92
#Mann= 9 ,-1 , 0
  4368.6     .05       0    4764     .16       0  4850.5      .1       0
  4974.1     .16       0  4995.8     .07       0  5001.8     .16       0
  5114.9      .1       0    5220     .05       0  6556.2      .1       0
#XS Ineff= 2 , 0
                         5367.88          1632.4
Permanent Ineff=
       T       T
Bank Sta=4956.6,5163.3
XS Rating Curve= 0 ,0
Exp/Cntr=0.3,0.1

Type RM Length L Ch R = 1 ,623     ,362,362,362
BEGIN DESCRIPTION:
Mapping XS 95a149a7
END DESCRIPTION:
XS GIS Cut Line= 3
      2746942.51     10048478.78      2746286.29     10047499.66
      2744723.81     10047041.33
#Sta/Elev= 30
  4362.2 1646.91  4801.7 1627.82  4873.9 1619.85  4880.6 1617.29  4900.2  1617.7
  4958.7 1609.17  4973.7 1603.89  4988.7 1594.29  5000.7 1592.55  5003.4 1592.05
  5006.7 1592.55  5037.3 1594.18  5045.7 1595.62  5060.7 1604.22  5117.8    1614
  5138.8 1620.07  5168.6 1624.59    5300 1629.55  5524.4 1628.55  5595.4 1629.23
  6253.6 1631.19  6455.7 1629.03  6541.6 1619.03  6633.6  1622.6    6718 1623.02
  6735.2 1626.31  6778.8 1633.24  6836.7  1636.2  7035.2 1643.08  7169.2 1644.69
#Mann= 13 ,-1 , 0
  4362.2     .05       0  4900.2      .1       0  5000.7     .07       0
  5006.7      .1       0  5037.3     .16       0  5168.6      .1       0
    5300     .05       0  5524.4      .1       0  5595.4     .05       0
  6633.6      .1       0    6718     .05       0  6735.2      .1       0
  6836.7     .05       0
#XS Ineff= 2 , 0
                         5378.24         1630.91
Permanent Ineff=
       T       T
Bank Sta=4873.9,5138.8
XS Rating Curve= 0 ,0
Exp/Cntr=0.3,0.1

Type RM Length L Ch R = 1 ,261     ,0,0,0
BEGIN DESCRIPTION:
LIVE OAK CREEK 1.0
END DESCRIPTION:
XS GIS Cut Line= 4
      2747213.35     10048270.46      2746755.04     10047567.37
       2746046.7      10047213.2      2744937.31     10046926.74
#Sta/Elev= 30
  4318.5 1644.12  4348.9 1643.41  4781.1 1625.16  4898.9  1609.3  4935.1 1604.65
  4962.2 1595.64  4995.4 1590.94  4998.2 1590.44  5001.4 1590.94  5019.5 1596.18
  5042.7 1609.74  5079.5 1610.51  5179.5 1612.27    5241 1618.16  5375.1 1621.26
  5447.8 1620.48  5679.4 1630.53  5763.9 1629.94  5918.2 1630.53    6361 1627.94
  6402.3 1625.42  6412.7 1623.08  6515.9 1623.04  6577.9 1615.37  6676.1 1624.62
  6776.9  1632.6  6877.7 1635.95  6925.5 1638.02  6978.4 1639.31  7095.5 1643.52
#Mann= 12 ,-1 , 0
  4318.5     .05       0  4348.9      .1       0  4995.4     .07       0
  5001.4      .1       0  5079.5     .05       0  5763.9      .1       0
  5918.2     .05       0  6676.1      .1       0  6776.9     .05       0
  6877.7      .1       0  6925.5     .05       0  6978.4      .1       0
#XS Ineff= 2 , 0
                         5679.27         1630.91
Permanent Ineff=
       T       T
Bank Sta=4898.9,5042.7
XS Rating Curve= 0 ,0
Exp/Cntr=0.3,0.1

Chan Stop Cuts=-1
Use User Specified Reach Order=0
Composite Channel Slope=5