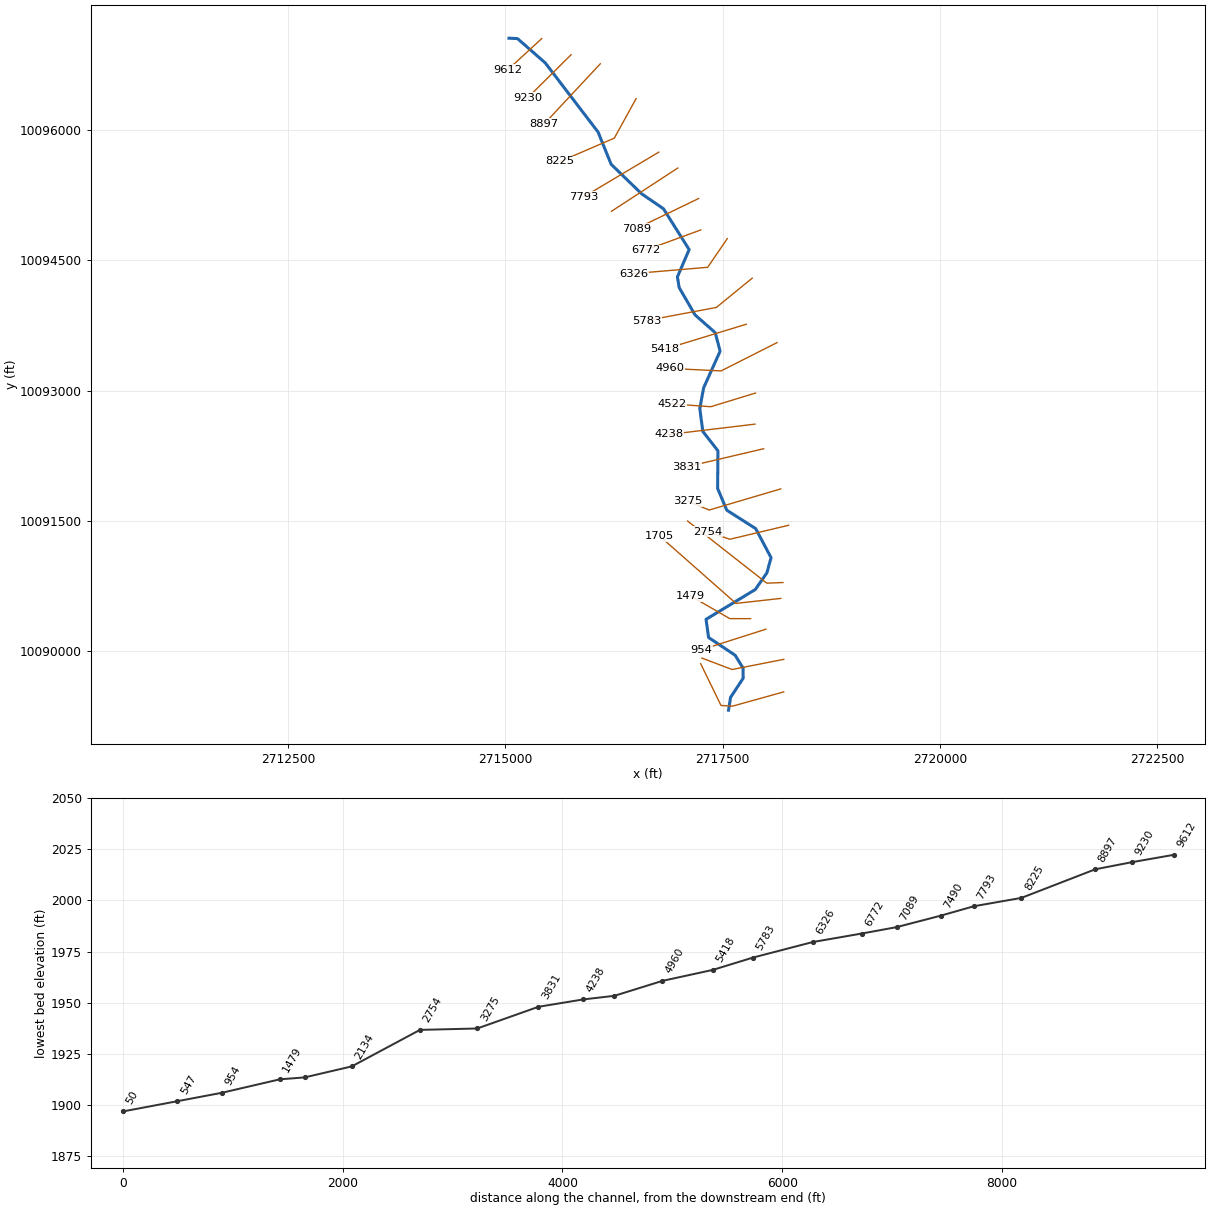
--- MIDDLE CREEK 2.prj (project) ---

Proj Title=MIDDLE CREEK Base Level Engineering
Current Plan=p01
Default Exp/Contr=0.3,0.1
English Units
Geom File=g01
Flow File=f01
Plan File=p01
BEGIN DESCRIPTION:
MIDDLE CREEK
END DESCRIPTION:

--- MIDDLE CREEK 2.p01 (plan) ---

Plan Title=Multiple Run
Short Identifier=Multiple
Geom File=g01
Flow File=f01
Subcritical Flow
K Sum by GR= 0
Std Step Tol= 0.01
Critical Tol= 0.01
Num of Std Step Trials= 20
Max Error Tol= 0.3
Flow Tol Ratio= 0.001
Split Flow NTrial= 30
Split Flow Tol= 0.02
Split Flow Ratio= 0.02
Log Output Level= 0
Friction Slope Method= 1
Unsteady Friction Slope Method= 2
Unsteady Bridges Friction Slope Method= 1
Parabolic Critical Depth
Global Vel Dist=  1 , 1 , 1
Global Log Level= 0
CheckData=True
Encroach Param= -1, 0, 0, 0
BEGIN DESCRIPTION:
Multiple Run
END DESCRIPTION:

--- MIDDLE CREEK 2.f01 (steady flow) ---

Flow Title=Multiple
Number of Profiles=7
Profile Names=10-year,25-year,50-year,1pct_min,100-year,1pct_plu,500-year
River Rch & RM= MIDDLE CREEK,Reach-1,9612
    1175    1721    2197    2045    2765    3740    4380
River Rch & RM= MIDDLE CREEK,Reach-1,8225
    1661    2483    3212    3028    4095    5538    6660
River Rch & RM= MIDDLE CREEK,Reach-1,5783
    1925    2899    3769    3569    4827    6528    7932
Boundary for River Rch & Prof#=MIDDLE CREEK,Reach-1,1
Up Type=0
Dn Type=3
Dn Slope=0.005
Boundary for River Rch & Prof#=MIDDLE CREEK,Reach-1,2
Up Type=0
Dn Type=3
Dn Slope=0.005
Boundary for River Rch & Prof#=MIDDLE CREEK,Reach-1,3
Up Type=0
Dn Type=3
Dn Slope=0.005
Boundary for River Rch & Prof#=MIDDLE CREEK,Reach-1,4
Up Type=0
Dn Type=3
Dn Slope=0.005
Boundary for River Rch & Prof#=MIDDLE CREEK,Reach-1,5
Up Type=0
Dn Type=3
Dn Slope=0.005
Boundary for River Rch & Prof#=MIDDLE CREEK,Reach-1,6
Up Type=0
Dn Type=3
Dn Slope=0.005
Boundary for River Rch & Prof#=MIDDLE CREEK,Reach-1,7
Up Type=0
Dn Type=3
Dn Slope=0.005

--- MIDDLE CREEK 2.g01 (geometry) ---

Geom Title=Existing Conditions

River Reach=MIDDLE CREEK,Reach-1
Reach XY= 30
      2715043.44     10097053.73      2715141.22     10097049.15
      2715460.57     10096769.57      2716068.47     10095973.73
      2716218.25     10095603.58      2716567.99     10095264.75
      2716820.70     10095091.33      2717115.78     10094622.37
      2716980.88     10094308.03      2717001.18     10094184.87
      2717183.32     10093871.06      2717416.26     10093666.24
      2717471.93     10093453.10      2717282.30     10093032.10
      2717238.34     10092793.76      2717272.91     10092530.85
      2717446.64     10092307.99      2717443.48     10091873.08
      2717549.63     10091623.65      2717881.05     10091412.82
      2718057.94     10091078.50      2718010.05     10090903.57
      2717875.76     10090711.15      2717310.10     10090368.82
      2717339.28     10090160.41      2717644.52     10089956.15
      2717736.58     10089807.91      2717736.99     10089690.68
      2717592.36     10089472.10      2717568.47     10089323.73

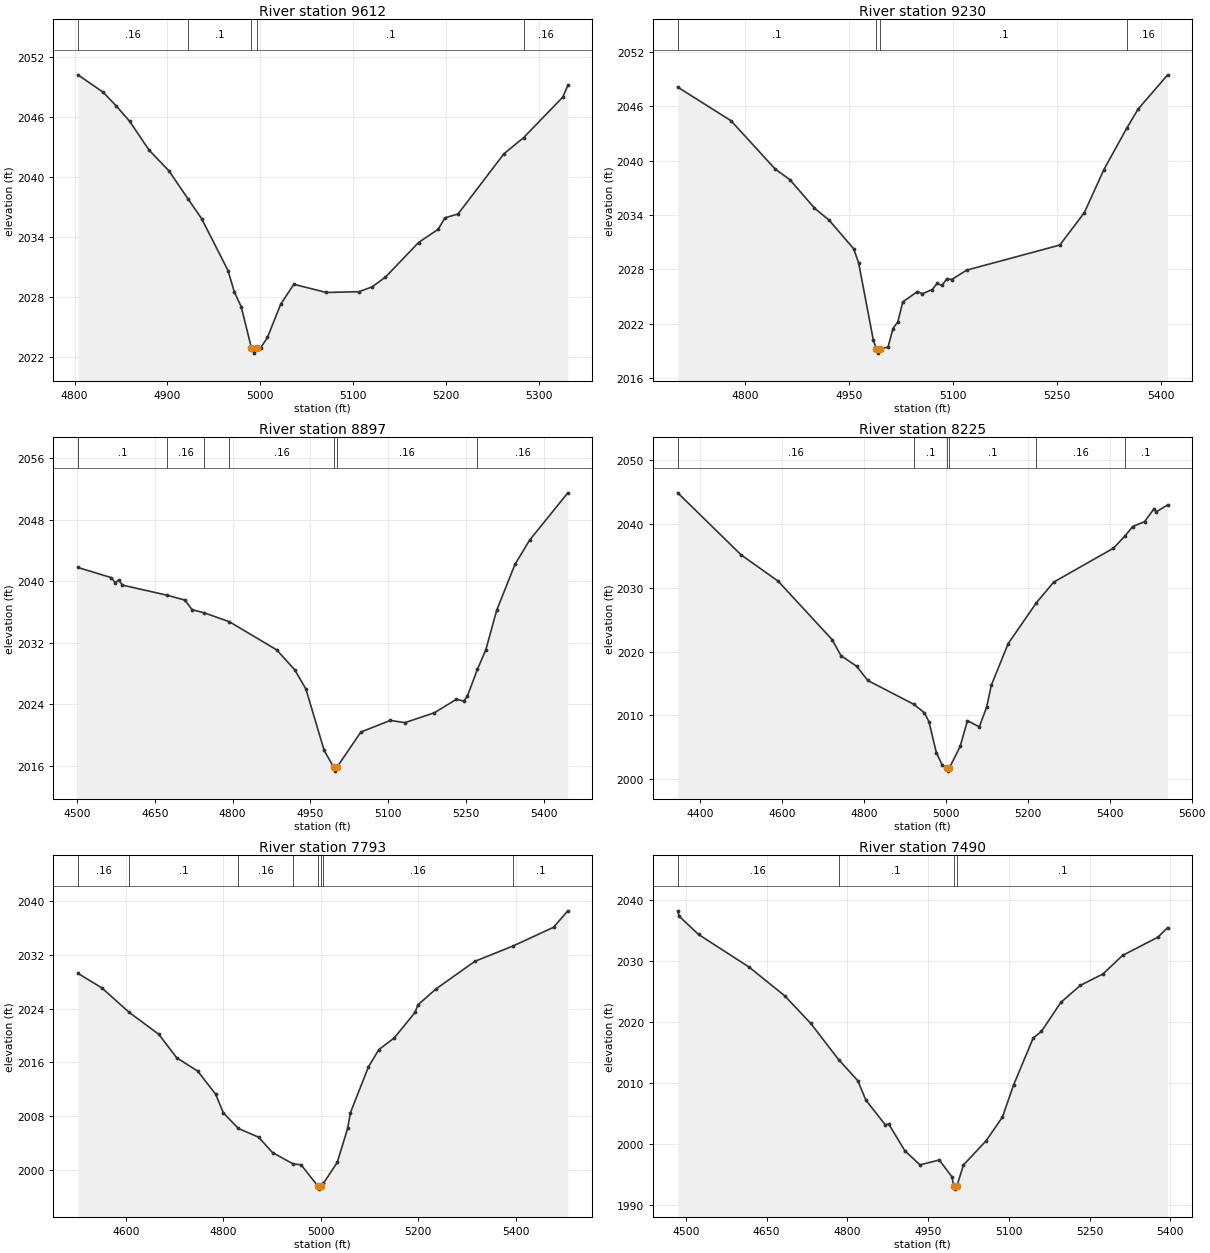
Type RM Length L Ch R = 1,9612,382,382,382
BEGIN DESCRIPTION:
MIDDLE CREEK 22.0
END DESCRIPTION:
XS GIS Cut Line= 2
      2715421.05     10097049.46      2715032.13     10096692.65
#Sta/Elev= 30
  4803.6 2050.26  4830.9 2048.51  4845.0 2047.13  4859.2 2045.62  4880.2 2042.72
  4901.8 2040.62  4922.1 2037.84  4936.9 2035.84  4965.3 2030.64  4972.1 2028.50
  4979.5 2027.02  4990.6 2022.86  4993.4 2022.36  4996.6 2022.86  5000.4 2022.88
  5007.8 2023.93  5022.0 2027.25  5036.2 2029.26  5071.3 2028.44  5106.5 2028.52
  5120.7 2029.01  5134.9 2029.98  5170.6 2033.45  5191.6 2034.77  5199.0 2035.92
  5213.2 2036.32  5262.5 2042.34  5283.7 2043.96  5326.0 2048.03  5331.4 2049.21
#Mann=5,-1,0
  4803.6    0.16       0  4922.1     0.1       0  4990.6    0.07       0
  4996.6     0.1       0  5283.7    0.16       0
Bank Sta=4990.6,4996.6
Exp/Cntr=0.3,0.1

Type RM Length L Ch R = 1,9230,333,333,333
BEGIN DESCRIPTION:
MIDDLE CREEK 21.0
END DESCRIPTION:
XS GIS Cut Line= 2
      2715757.53     10096863.32      2715256.39     10096365.75
#Sta/Elev= 30
  4702.9 2048.12  4779.7 2044.41  4843.3 2039.08  4864.6 2037.90  4899.9 2034.77
  4921.2 2033.42  4956.5 2030.27  4963.6 2028.72  4984.8 2020.20  4988.9 2019.25
  4991.6 2018.75  4994.9 2019.25  5006.0 2019.41  5013.1 2021.46  5020.2 2022.21
  5027.2 2024.40  5048.4 2025.55  5055.5 2025.31  5069.6 2025.76  5076.7 2026.44
  5083.8 2026.23  5090.9 2026.97  5097.9 2026.88  5119.2 2027.91  5253.5 2030.68
  5288.9 2034.25  5317.1 2039.01  5349.9 2043.56  5366.6 2045.71  5409.1 2049.48
#Mann=4,-1,0
  4702.9     0.1       0  4988.9    0.07       0  4994.9     0.1       0
  5349.9    0.16       0
Bank Sta=4988.9,4994.9
Exp/Cntr=0.3,0.1

Type RM Length L Ch R = 1,8897,672,672,672
BEGIN DESCRIPTION:
MIDDLE CREEK 20.0
END DESCRIPTION:
XS GIS Cut Line= 2
      2716094.00     10096759.49      2715449.74     10096068.70
#Sta/Elev= 30
  4501.7 2041.78  4566.1 2040.46  4573.5 2039.80  4580.3 2040.15  4587.6 2039.49
  4673.6 2038.17  4707.8 2037.54  4722.0 2036.28  4745.2 2035.88  4793.7 2034.72
  4884.7 2031.07  4919.8 2028.46  4941.3 2025.96  4976.5 2017.96  4995.0 2015.77
  4997.7 2015.27  5001.0 2015.77  5047.3 2020.36  5104.0 2021.87  5132.3 2021.58
  5189.0 2022.87  5231.5 2024.62  5245.7 2024.39  5252.5 2025.02  5271.9 2028.51
  5288.2 2031.07  5309.2 2036.23  5344.4 2042.19  5372.7 2045.35  5446.3 2051.50
#Mann=7,-1,0
  4501.7     0.1       0  4673.6    0.16       0  4745.2     0.1       0
  4793.7    0.16       0  4995.0    0.07       0  5001.0    0.16       0
  5271.9    0.16       0
Bank Sta=4995,5001
Exp/Cntr=0.3,0.1

Type RM Length L Ch R = 1,8225,432,432,432
BEGIN DESCRIPTION:
MIDDLE CREEK 19.0
END DESCRIPTION:
XS GIS Cut Line= 3
      2716505.66     10096358.59      2716255.09     10095903.98
      2715632.83     10095635.76
#Sta/Elev= 30
  4344.7 2044.91  4499.3 2035.19  4590.0 2031.05  4721.7 2021.89  4743.5 2019.36
  4781.4 2017.73  4808.9 2015.48  4921.6 2011.73  4947.2 2010.41  4958.2 2009.04
  4976.3 2004.18  4990.8 2002.20  5002.2 2001.76  5005.0 2001.26  5008.2 2001.76
  5034.4 2005.13  5052.3 2009.17  5081.3 2008.21  5099.3 2011.33  5110.6 2014.73
  5151.8 2021.26  5220.5 2027.65  5263.0 2030.91  5408.8 2036.22  5436.6 2038.10
  5455.8 2039.62  5484.8 2040.38  5508.3 2042.44  5513.8 2041.93  5541.4 2043.03
#Mann=6,-1,0
  4344.7    0.16       0  4921.6     0.1       0  5002.2    0.07       0
  5008.2     0.1       0  5220.5    0.16       0  5436.6     0.1       0
Bank Sta=5002.2,5008.2
Exp/Cntr=0.3,0.1

Type RM Length L Ch R = 1,7793,303,303,303
BEGIN DESCRIPTION:
MIDDLE CREEK 18.0
END DESCRIPTION:
XS GIS Cut Line= 2
      2716767.00     10095742.91      2715903.16     10095228.89
#Sta/Elev= 30
  4501.7 2029.25  4550.7 2027.09  4607.1 2023.44  4667.5 2020.20  4704.5 2016.69
  4747.4 2014.73  4784.4 2011.28  4800.0 2008.52  4830.9 2006.20  4872.4 2004.90
  4901.2 2002.60  4942.9 2000.95  4959.6 2000.79  4993.6 1997.68  4996.4 1997.18
  4999.6 1997.68  5005.2 1998.02  5033.7 2001.14  5055.1 2006.20  5060.9 2008.56
  5097.9 2015.36  5119.3 2017.93  5150.5 2019.63  5193.3 2023.43  5199.2 2024.56
  5236.2 2026.92  5316.0 2031.03  5394.6 2033.32  5477.5 2036.09  5506.9 2038.54
#Mann=8,-1,0
  4501.7    0.16       0  4607.1     0.1       0  4830.9    0.16       0
  4942.9     0.1       0  4993.6    0.07       0  4999.6     0.1       0
  5005.2    0.16       0  5394.6     0.1       0
Bank Sta=4993.6,4999.6
Exp/Cntr=0.3,0.1

Type RM Length L Ch R = 1,7490,401,401,401
BEGIN DESCRIPTION:
MIDDLE CREEK 17.0
END DESCRIPTION:
XS GIS Cut Line= 2
      2716985.29     10095560.31      2716223.21     10095062.99
#Sta/Elev= 30
  4484.9 2038.30  4487.4 2037.42  4523.6 2034.41  4617.2 2029.06  4683.6 2024.33
  4731.9 2019.79  4783.6 2013.85  4819.3 2010.37  4834.4 2007.17  4870.6 2003.09
  4876.6 2003.26  4906.8 1998.84  4934.9 1996.53  4970.7 1997.33  4994.4 1994.53
  4997.3 1993.04  5000.1 1992.54  5003.3 1993.04  5015.5 1996.50  5057.6 2000.49
  5087.9 2004.37  5109.0 2009.74  5145.2 2017.40  5160.3 2018.46  5196.5 2023.25
  5232.7 2026.04  5274.9 2027.93  5311.1 2030.97  5376.7 2033.96  5394.9 2035.55
#Mann=4,-1,0
  4484.9    0.16       0  4783.6     0.1       0  4997.3    0.07       0
  5003.3     0.1       0
Bank Sta=4997.3,5003.3
Exp/Cntr=0.3,0.1

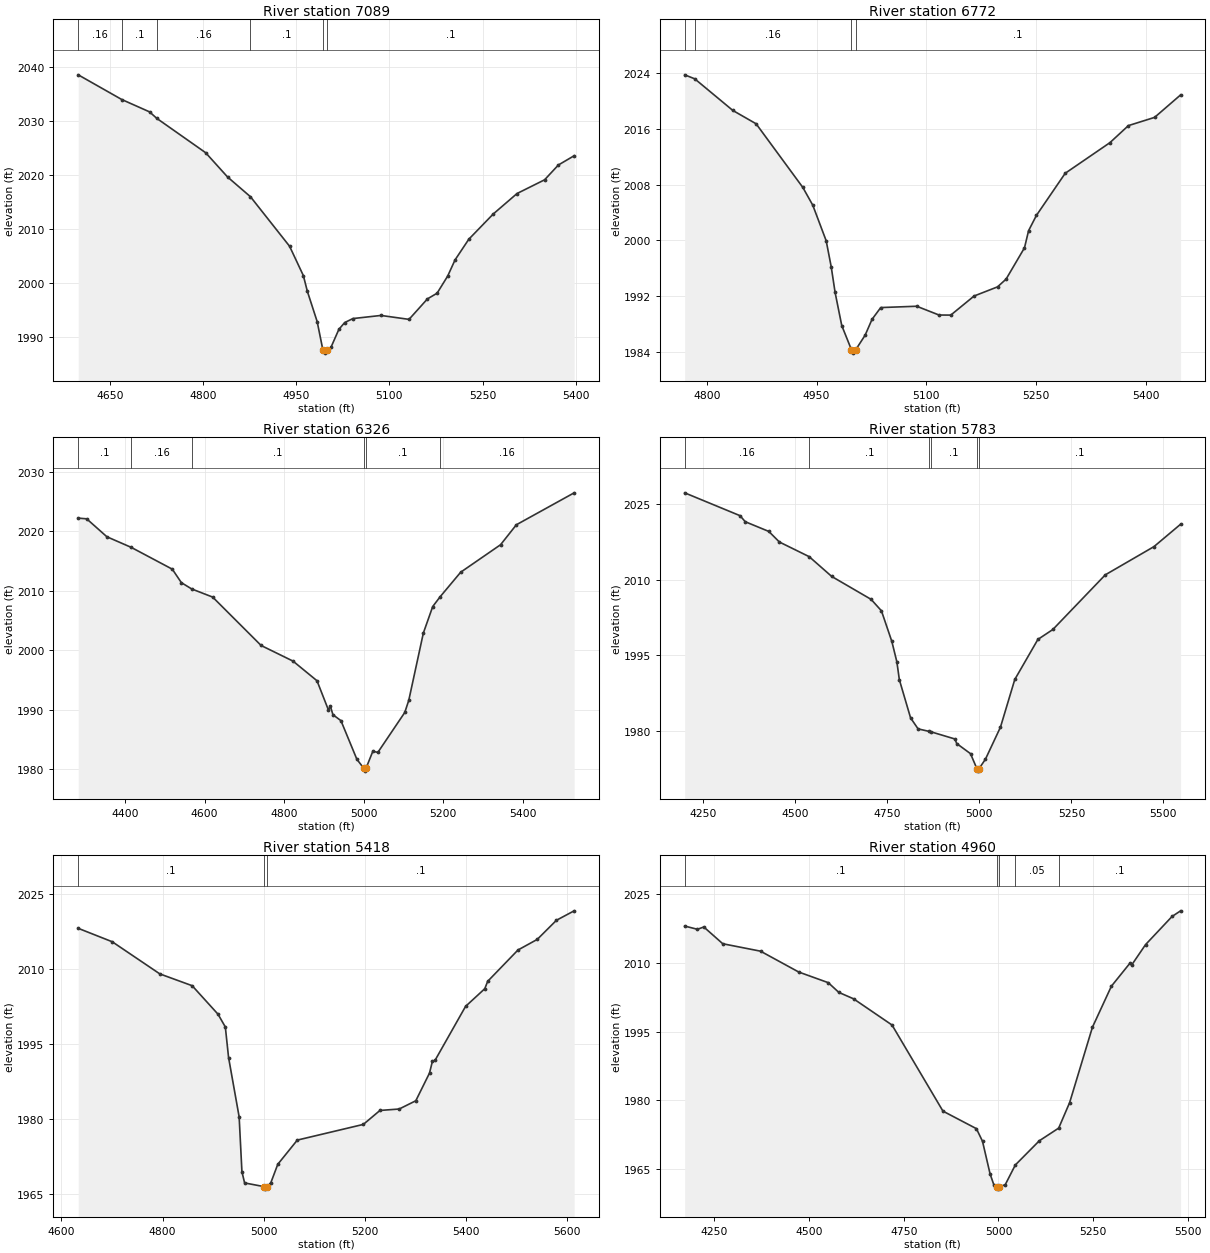
Type RM Length L Ch R = 1,7089,317,317,317
BEGIN DESCRIPTION:
MIDDLE CREEK 16.0
END DESCRIPTION:
XS GIS Cut Line= 2
      2717225.12     10095209.51      2716505.62     10094862.29
#Sta/Elev= 30
  4598.7 2038.63  4668.9 2034.04  4713.6 2031.75  4725.4 2030.53  4804.0 2024.16
  4839.3 2019.65  4876.2 2015.98  4939.2 2006.78  4961.4 2001.33  4967.8 1998.42
  4983.6 1992.80  4993.0 1987.43  4995.7 1986.93  4999.0 1987.43  5005.8 1987.99
  5018.6 1991.35  5028.0 1992.61  5041.2 1993.35  5086.4 1993.93  5131.6 1993.20
  5161.3 1997.01  5176.8 1998.06  5193.9 2001.25  5205.7 2004.24  5227.9 2008.09
  5267.2 2012.77  5305.6 2016.58  5350.0 2019.13  5372.2 2021.88  5397.6 2023.60
#Mann=6,-1,0
  4598.7    0.16       0  4668.9     0.1       0  4725.4    0.16       0
  4876.2     0.1       0  4993.0    0.07       0  4999.0     0.1       0
Bank Sta=4993,4999
Exp/Cntr=0.3,0.1

Type RM Length L Ch R = 1,6772,446,446,446
BEGIN DESCRIPTION:
MIDDLE CREEK 15.0
END DESCRIPTION:
XS GIS Cut Line= 2
      2717250.27     10094848.01      2716613.21     10094615.38
#Sta/Elev= 30
  4769.6 2023.75  4783.3 2023.18  4835.4 2018.64  4867.3 2016.72  4931.2 2007.58
  4944.8 2005.03  4963.1 1999.93  4970.0 1996.19  4975.3 1992.51  4984.4 1987.76
  4997.6 1984.30  5000.3 1983.80  5003.6 1984.30  5016.4 1986.38  5025.8 1988.65
  5037.7 1990.34  5086.9 1990.53  5117.4 1989.27  5133.5 1989.26  5165.4 1992.00
  5197.4 1993.31  5209.1 1994.42  5234.3 1998.92  5239.9 2001.38  5250.6 2003.57
  5290.0 2009.62  5351.1 2014.01  5376.4 2016.46  5412.2 2017.64  5447.8 2020.87
#Mann=4,-1,0
  4769.6     0.1       0  4783.3    0.16       0  4997.6    0.07       0
  5003.6     0.1       0
Bank Sta=4997.6,5003.6
Exp/Cntr=0.3,0.1

Type RM Length L Ch R = 1,6326,543,543,543
BEGIN DESCRIPTION:
MIDDLE CREEK 14.0
END DESCRIPTION:
XS GIS Cut Line= 3
      2717554.49     10094747.76      2717328.97     10094418.44
      2716484.14     10094346.84
#Sta/Elev= 30
  4282.1 2022.24  4303.4 2022.12  4354.2 2019.10  4415.2 2017.32  4518.7 2013.64
  4541.5 2011.37  4567.5 2010.31  4620.2 2008.94  4742.0 2000.79  4822.2 1998.16
  4882.5 1994.85  4911.1 1989.95  4916.1 1990.57  4922.6 1989.13  4942.7 1988.13
  4982.8 1981.62  4999.9 1980.13  5002.6 1979.63  5005.9 1980.13  5023.0 1982.99
  5035.5 1982.78  5103.2 1989.51  5113.3 1991.56  5149.9 2002.88  5173.5 2007.35
  5192.3 2009.01  5243.8 2013.13  5344.1 2017.76  5383.8 2021.12  5529.1 2026.50
#Mann=6,-1,0
  4282.1     0.1       0  4415.2    0.16       0  4567.5     0.1       0
  4999.9    0.07       0  5005.9     0.1       0  5192.3    0.16       0
Bank Sta=4999.9,5005.9
Exp/Cntr=0.3,0.1

Type RM Length L Ch R = 1,5783,365,365,365
BEGIN DESCRIPTION:
MIDDLE CREEK 13.0
END DESCRIPTION:
XS GIS Cut Line= 3
      2717840.84     10094293.14      2717429.20     10093956.67
      2716627.34     10093806.32
#Sta/Elev= 30
  4199.3 2027.18  4349.7 2022.65  4364.0 2021.45  4427.9 2019.53  4456.7 2017.43
  4537.6 2014.53  4598.8 2010.61  4705.8 2006.07  4733.9 2003.80  4762.2 1997.72
  4775.8 1993.69  4782.6 1990.14  4813.1 1982.58  4833.5 1980.40  4864.3 1979.89
  4868.5 1979.82  4933.5 1978.40  4938.5 1977.49  4975.9 1975.49  4993.2 1972.53
  4996.0 1972.03  4999.2 1972.53  5016.6 1974.41  5057.3 1980.74  5096.2 1990.19
  5159.0 1998.13  5199.7 2000.10  5342.2 2010.93  5474.4 2016.52  5546.8 2020.96
#Mann=6,-1,0
  4199.3    0.16       0  4537.6     0.1       0  4864.3    0.16       0
  4868.5     0.1       0  4993.2    0.07       0  4999.2     0.1       0
Bank Sta=4993.2,4999.2
Exp/Cntr=0.3,0.1

Type RM Length L Ch R = 1,5418,458,458,458
BEGIN DESCRIPTION:
MIDDLE CREEK 12.0
END DESCRIPTION:
XS GIS Cut Line= 2
      2717772.81     10093763.36      2716834.95     10093476.99
#Sta/Elev= 30
  4633.1 2018.18  4700.4 2015.49  4794.5 2009.06  4858.4 2006.70  4909.5 2001.00
  4924.0 1998.44  4930.4 1992.33  4951.3 1980.46  4956.8 1969.48  4962.1 1967.24
  5000.6 1966.50  5003.3 1966.00  5006.6 1966.50  5014.0 1967.29  5027.7 1970.97
  5066.3 1975.81  5196.9 1978.95  5229.7 1981.74  5267.8 1982.03  5300.6 1983.68
  5327.7 1989.22  5333.4 1991.56  5338.6 1991.76  5399.0 2002.56  5437.0 2006.10
  5442.7 2007.57  5502.6 2013.84  5540.7 2015.96  5578.7 2019.79  5613.7 2021.68
#Mann=3,-1,0
  4633.1     0.1       0  5000.6    0.07       0  5006.6     0.1       0
Bank Sta=5000.6,5006.6
Exp/Cntr=0.3,0.1

Type RM Length L Ch R = 1,4960,438,438,438
BEGIN DESCRIPTION:
MIDDLE CREEK 11.0
END DESCRIPTION:
XS GIS Cut Line= 3
      2718127.20     10093552.16      2717482.90     10093226.43
      2716895.85     10093255.06
#Sta/Elev= 30
  4171.3 2018.01  4205.1 2017.30  4221.8 2017.81  4271.9 2014.15  4371.6 2012.53
  4472.5 2007.98  4550.5 2005.66  4578.4 2003.54  4617.3 2002.14  4718.9 1996.42
  4853.4 1977.64  4941.7 1973.82  4957.8 1971.07  4977.8 1963.96  4987.8 1961.55
  4994.8 1961.13  4997.6 1960.63  5000.8 1961.13  5017.8 1961.59  5044.5 1965.90
  5107.9 1971.18  5159.0 1973.94  5188.0 1979.52  5248.1 1995.94  5298.2 2004.89
  5347.1 2009.90  5352.1 2009.56  5388.3 2013.95  5458.4 2020.10  5481.0 2021.33
#Mann=5,-1,0
  4171.3     0.1       0  4994.8    0.07       0  5000.8     0.1       0
  5044.5    0.05       0  5159.0     0.1       0
Bank Sta=4994.8,5000.8
Exp/Cntr=0.3,0.1

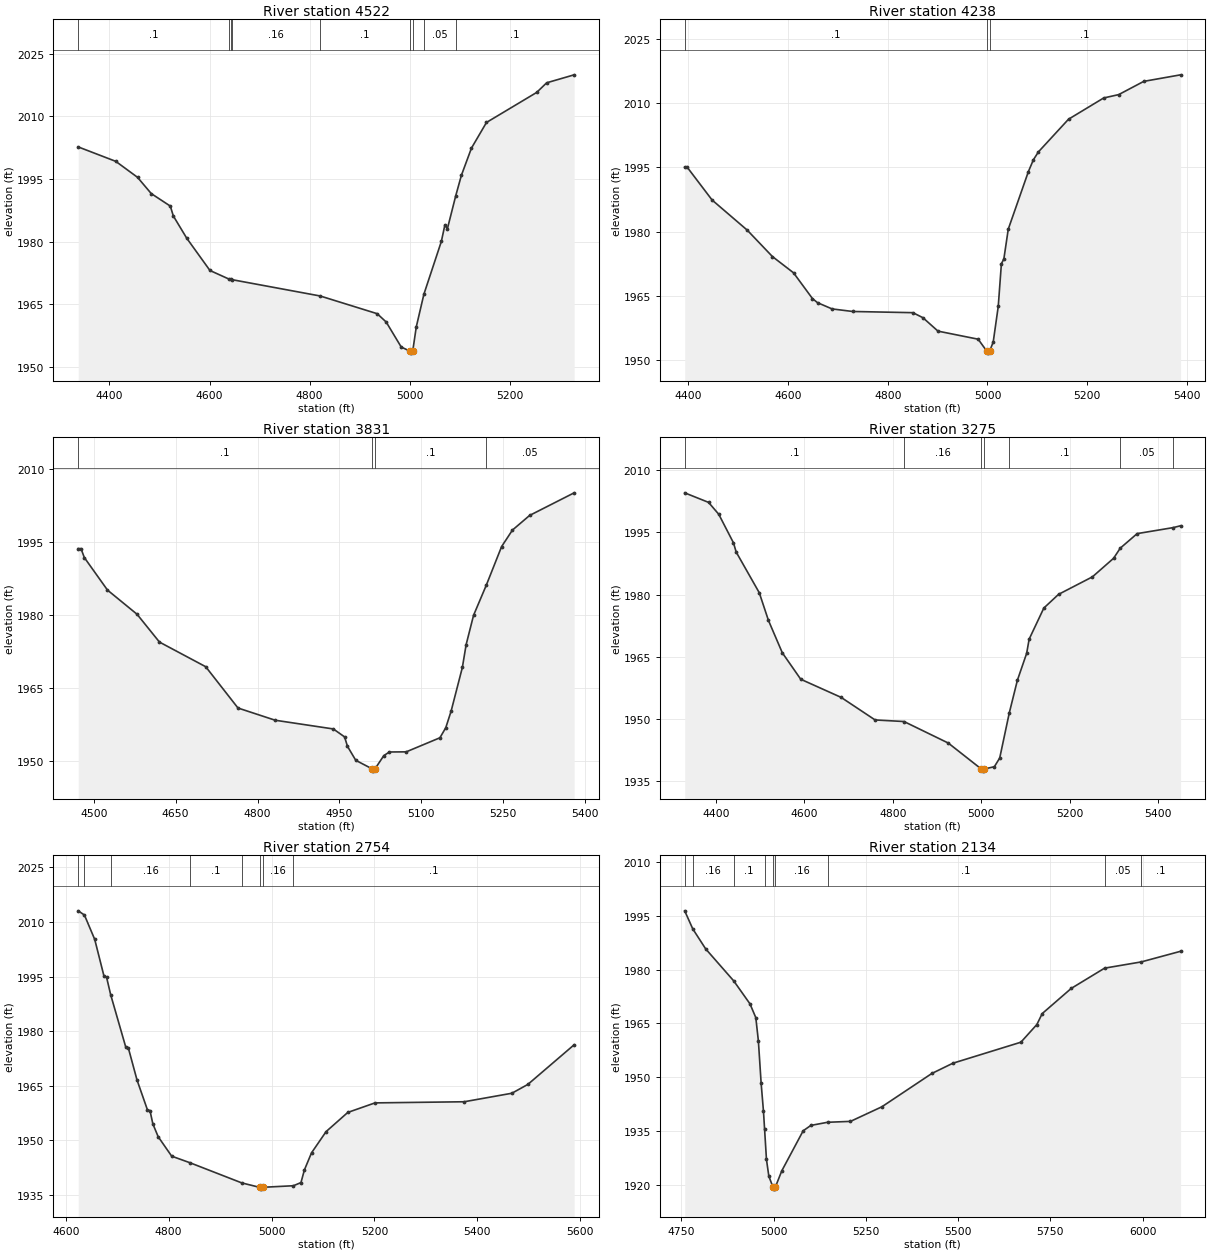
Type RM Length L Ch R = 1,4522,284,284,284
BEGIN DESCRIPTION:
MIDDLE CREEK 10.0
END DESCRIPTION:
XS GIS Cut Line= 3
      2717880.26     10092972.28      2717364.77     10092814.77
      2716913.74     10092846.99
#Sta/Elev= 30
  4337.6 2002.70  4412.7 1999.24  4456.1 1995.42  4483.6 1991.52  4521.7 1988.52
  4527.7 1986.16  4554.5 1980.83  4600.9 1973.10  4639.3 1971.02  4642.1 1970.99
  4645.4 1970.89  4821.2 1966.99  4935.1 1962.75  4953.1 1960.76  4983.2 1954.76
  5000.2 1953.80  5003.0 1953.30  5006.2 1953.80  5013.3 1959.59  5028.5 1967.41
  5063.4 1980.06  5070.5 1984.03  5075.5 1983.10  5092.2 1991.02  5103.5 1995.91
  5123.6 2002.42  5153.6 2008.56  5253.9 2015.75  5273.9 2018.06  5328.8 2019.97
#Mann=9,-1,0
  4337.6     0.1       0  4639.3    0.16       0  4642.1     0.1       0
  4645.4    0.16       0  4821.2     0.1       0  5000.2    0.07       0
  5006.2     0.1       0  5028.5    0.05       0  5092.2     0.1       0
Bank Sta=5000.2,5006.2
Exp/Cntr=0.3,0.1

Type RM Length L Ch R = 1,4238,407,407,407
BEGIN DESCRIPTION:
MIDDLE CREEK 9.0
END DESCRIPTION:
XS GIS Cut Line= 2
      2717873.10     10092614.32      2716885.14     10092496.19
#Sta/Elev= 30
  4392.5 1995.07  4397.4 1995.07  4447.5 1987.37  4518.0 1980.32  4568.4 1974.15
  4610.9 1970.33  4648.9 1964.29  4659.0 1963.34  4688.2 1961.88  4729.5 1961.28
  4850.4 1961.00  4870.5 1959.82  4900.7 1956.68  4981.3 1954.79  4998.4 1952.03
  5001.2 1951.53  5004.4 1952.03  5011.5 1954.12  5021.6 1962.46  5027.9 1972.44
  5032.9 1973.60  5041.7 1980.55  5082.0 1994.00  5092.1 1996.79  5102.2 1998.64
  5162.6 2006.29  5233.1 2011.26  5263.3 2012.05  5313.6 2015.15  5387.5 2016.68
#Mann=3,-1,0
  4392.5     0.1       0  4998.4    0.07       0  5004.4     0.1       0
Bank Sta=4998.4,5004.4
Exp/Cntr=0.3,0.1

Type RM Length L Ch R = 1,3831,556,556,556
BEGIN DESCRIPTION:
MIDDLE CREEK 8.0
END DESCRIPTION:
XS GIS Cut Line= 2
      2717973.30     10092331.53      2717089.15     10092123.91
#Sta/Elev= 30
  4471.6 1993.61  4476.7 1993.61  4482.8 1991.78  4525.2 1985.10  4579.3 1980.14
  4620.4 1974.42  4705.1 1969.36  4764.2 1960.88  4832.4 1958.37  4938.8 1956.58
  4959.4 1954.95  4964.7 1953.01  4979.9 1950.14  5009.3 1948.42  5012.1 1947.92
  5015.3 1948.42  5031.3 1951.11  5041.5 1951.85  5072.3 1951.88  5134.0 1954.77
  5144.7 1956.83  5154.5 1960.24  5175.1 1969.21  5182.0 1973.89  5195.6 1979.92
  5218.7 1986.04  5247.0 1994.04  5266.8 1997.42  5298.3 2000.43  5379.8 2005.07
#Mann=4,-1,0
  4471.6     0.1       0  5009.3    0.07       0  5015.3     0.1       0
  5218.7    0.05       0
Bank Sta=5009.3,5015.3
Exp/Cntr=0.3,0.1

Type RM Length L Ch R = 1,3275,521,521,521
BEGIN DESCRIPTION:
MIDDLE CREEK 7.0
END DESCRIPTION:
XS GIS Cut Line= 3
      2718170.23     10091869.77      2717346.87     10091626.34
      2717103.48     10091726.56
#Sta/Elev= 30
  4329.5 2004.58  4383.5 2002.27  4406.6 1999.39  4439.9 1992.48  4446.0 1990.26
  4498.2 1980.43  4519.0 1973.73  4550.3 1965.92  4592.0 1959.52  4683.3 1955.14
  4760.2 1949.68  4825.6 1949.30  4925.7 1944.10  5000.6 1937.81  5003.4 1937.31
  5006.6 1937.81  5030.0 1938.38  5042.1 1940.48  5063.8 1951.41  5082.1 1959.29
  5103.0 1965.77  5108.7 1969.22  5141.9 1976.73  5175.2 1980.04  5251.8 1984.27
  5299.7 1988.76  5314.8 1991.21  5353.0 1994.72  5434.3 1996.17  5451.3 1996.62
#Mann=7,-1,0
  4329.5     0.1       0  4825.6    0.16       0  5000.6    0.07       0
  5006.6    0.16       0  5063.8     0.1       0  5314.8    0.05       0
  5434.3     0.1       0
Bank Sta=5000.6,5006.6
Exp/Cntr=0.3,0.1

Type RM Length L Ch R = 1,2754,620,620,620
BEGIN DESCRIPTION:
MIDDLE CREEK 6.0
END DESCRIPTION:
XS GIS Cut Line= 3
      2718259.65     10091450.94      2717583.13     10091289.86
      2717329.81     10091379.05
#Sta/Elev= 30
  4624.2 2013.04  4636.3 2011.88  4656.3 2005.19  4674.3 1995.11  4679.4 1994.75
  4687.3 1990.00  4716.4 1975.73  4721.6 1975.40  4738.5 1966.59  4758.6 1958.45
  4763.7 1958.18  4769.3 1954.54  4779.6 1951.02  4805.9 1945.67  4841.7 1943.85
  4942.1 1938.33  4976.6 1937.12  4979.3 1936.62  4982.6 1937.12  5042.5 1937.55
  5057.2 1938.42  5063.9 1941.90  5077.7 1946.58  5106.0 1952.41  5148.2 1957.68
  5201.1 1960.30  5374.4 1960.61  5467.2 1962.95  5498.2 1965.37  5588.2 1976.26
#Mann=8,-1,0
  4624.2    0.16       0  4636.3     0.1       0  4687.3    0.16       0
  4841.7     0.1       0  4942.1    0.16       0  4976.6    0.07       0
  4982.6    0.16       0  5042.5     0.1       0
Bank Sta=4976.6,4982.6
Exp/Cntr=0.3,0.1

Type RM Length L Ch R = 1,2134,429,429,429
BEGIN DESCRIPTION:
MIDDLE CREEK 5.0
END DESCRIPTION:
XS GIS Cut Line= 3
      2718195.26     10090792.29      2718009.10     10090785.13
      2717097.77     10091499.90
#Sta/Elev= 30
  4758.8 1996.43  4780.7 1991.39  4815.6 1985.82  4892.0 1976.84  4935.7 1970.48
  4951.6 1966.62  4958.6 1960.11  4966.1 1948.24  4972.4 1940.47  4975.3 1935.65
  4980.5 1927.02  4986.9 1922.38  4998.3 1919.25  5001.1 1918.75  5004.3 1919.25
  5022.2 1923.89  5080.0 1935.03  5100.8 1936.53  5146.2 1937.41  5208.3 1937.66
  5293.3 1941.73  5428.8 1951.03  5485.8 1953.89  5670.3 1959.76  5713.6 1964.70
  5728.1 1967.75  5806.7 1974.77  5897.2 1980.43  5996.6 1982.17  6103.3 1985.14
#Mann=9,-1,0
  4758.8     0.1       0  4780.7    0.16       0  4892.0     0.1       0
  4975.3    0.16       0  4998.3    0.07       0  5004.3    0.16       0
  5146.2     0.1       0  5897.2    0.05       0  5996.6     0.1       0
Bank Sta=4998.3,5004.3
Exp/Cntr=0.3,0.1

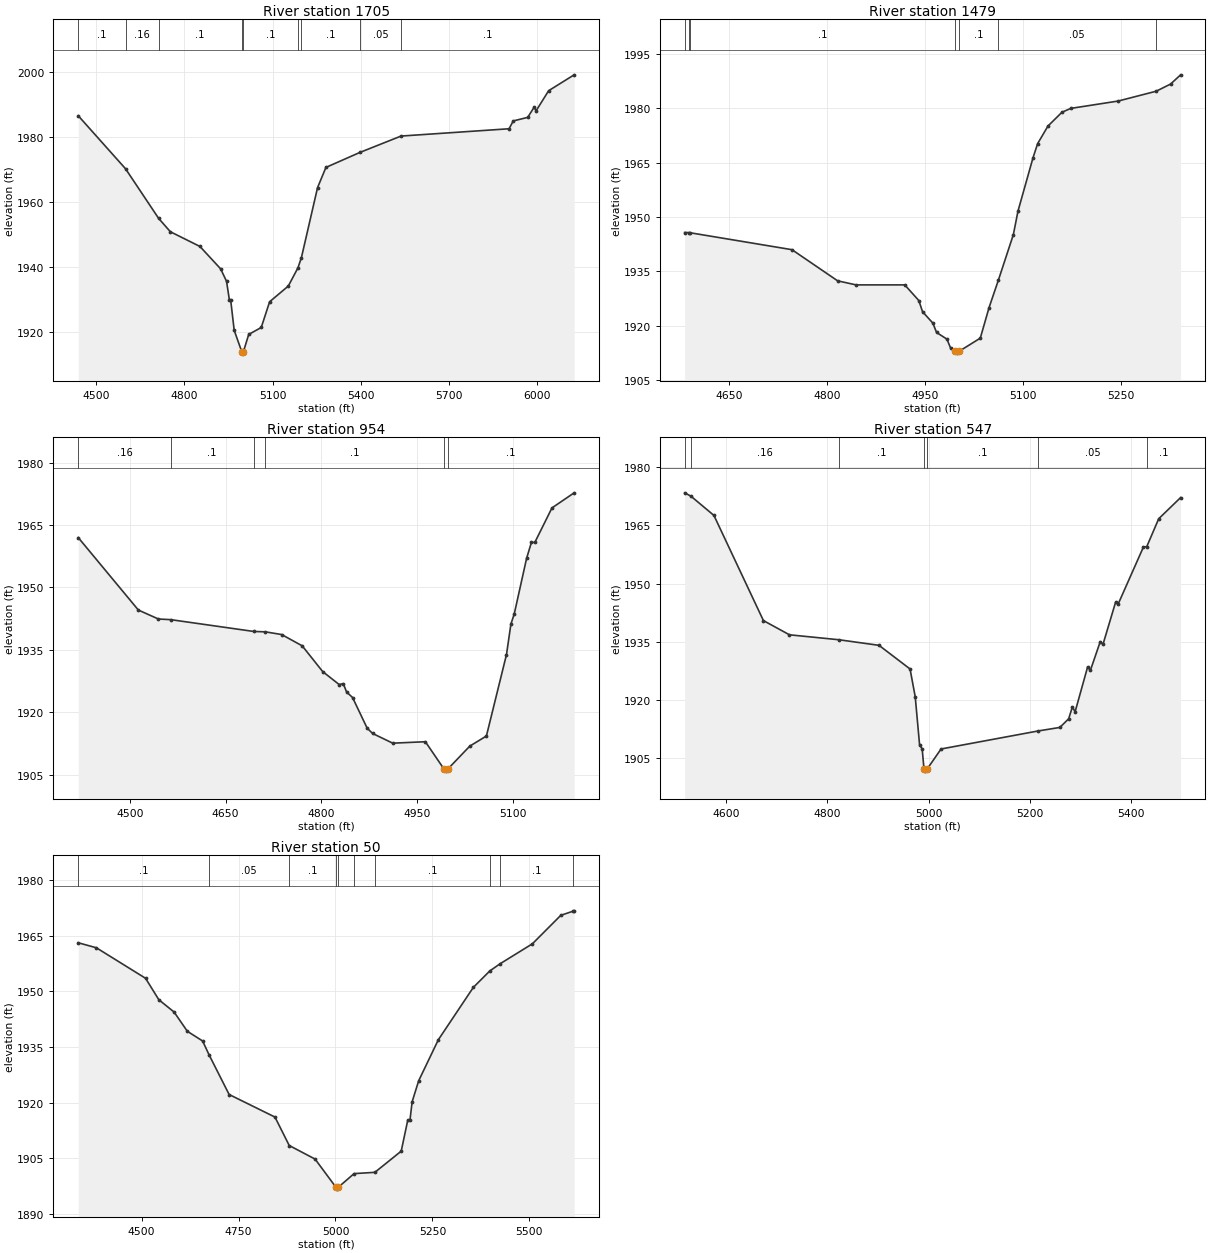
Type RM Length L Ch R = 1,1705,226,226,226
BEGIN DESCRIPTION:
MIDDLE CREEK 4.0
END DESCRIPTION:
XS GIS Cut Line= 3
      2718170.22     10090609.74      2717654.72     10090552.46
      2716777.75     10091325.62
#Sta/Elev= 30
  4438.7 1986.51  4599.7 1970.17  4712.4 1954.87  4752.4 1950.75  4853.0 1946.22
  4923.4 1939.32  4943.5 1935.48  4953.0 1929.85  4957.4 1929.85  4969.6 1920.36
  4995.1 1913.85  4997.8 1913.35  5001.1 1913.85  5019.0 1919.12  5061.6 1921.25
  5090.1 1929.18  5153.7 1934.02  5186.6 1939.65  5198.4 1942.81  5253.2 1964.34
  5281.7 1970.58  5397.7 1975.21  5537.4 1980.24  5905.0 1982.49  5919.2 1984.90
  5968.5 1986.00  5990.3 1989.13  5997.0 1988.02  6039.7 1994.22  6126.5 1999.11
#Mann=9,-1,0
  4438.7     0.1       0  4599.7    0.16       0  4712.4     0.1       0
  4995.1    0.07       0  5001.1     0.1       0  5186.6    0.05       0
  5198.4     0.1       0  5397.7    0.05       0  5537.4     0.1       0
Bank Sta=4995.1,5001.1
Exp/Cntr=0.3,0.1

Type RM Length L Ch R = 1,1479,525,525,525
BEGIN DESCRIPTION:
MIDDLE CREEK 3.0
END DESCRIPTION:
XS GIS Cut Line= 3
      2717822.93     10090377.06      2717583.13     10090377.06
      2717132.76     10090637.98
#Sta/Elev= 30
  4581.6 1945.71  4587.6 1945.69  4589.4 1945.66  4746.1 1940.97  4816.1 1932.37
  4844.4 1931.25  4919.0 1931.25  4940.5 1926.94  4946.3 1923.84  4962.0 1920.71
  4967.8 1918.11  4983.6 1916.28  4989.4 1913.76  4996.3 1912.91  4999.1 1912.41
  5002.3 1912.91  5034.8 1916.55  5048.2 1924.97  5062.4 1932.49  5085.5 1945.14
  5092.6 1951.64  5115.7 1966.40  5122.7 1970.25  5138.5 1975.10  5160.0 1978.92
  5173.5 1979.98  5246.1 1982.01  5304.4 1984.72  5326.5 1986.70  5341.9 1989.25
#Mann=7,-1,0
  4581.6     0.1       0  4587.6    0.16       0  4589.4     0.1       0
  4996.3    0.07       0  5002.3     0.1       0  5062.4    0.05       0
  5304.4     0.1       0
Bank Sta=4996.3,5002.3
Exp/Cntr=0.3,0.1

Type RM Length L Ch R = 1,954,407,407,407
BEGIN DESCRIPTION:
MIDDLE CREEK 2.0
END DESCRIPTION:
XS GIS Cut Line= 2
      2717998.34     10090255.34      2717257.39     10090019.10
#Sta/Elev= 30
  4418.8 1962.00  4513.1 1944.57  4544.6 1942.41  4563.8 1942.26  4694.1 1939.42
  4712.2 1939.33  4737.8 1938.68  4770.0 1935.97  4802.2 1929.77  4828.0 1926.66
  4834.4 1926.88  4839.7 1924.85  4849.0 1923.54  4871.9 1916.17  4880.5 1914.89
  4912.0 1912.56  4963.2 1912.91  4992.4 1906.34  4995.2 1905.84  4998.4 1906.34
  5032.9 1911.86  5058.9 1914.28  5090.4 1933.87  5097.3 1941.17  5102.6 1943.65
  5121.9 1956.98  5129.5 1960.84  5134.8 1960.82  5161.7 1969.12  5196.5 1972.75
#Mann=6,-1,0
  4418.8    0.16       0  4563.8     0.1       0  4694.1    0.16       0
  4712.2     0.1       0  4992.4    0.07       0  4998.4     0.1       0
Bank Sta=4992.4,4998.4
Exp/Cntr=0.3,0.1

Type RM Length L Ch R = 1,547,497,497,497
BEGIN DESCRIPTION:
Mapping XS 494e253d
END DESCRIPTION:
XS GIS Cut Line= 3
      2718204.54     10089909.02      2717609.89     10089791.83
      2717262.01     10089923.64
#Sta/Elev= 30
  4518.9 1973.36  4531.3 1972.49  4576.6 1967.54  4674.2 1940.46  4725.6 1936.80
  4823.0 1935.53  4902.2 1934.09  4963.4 1928.00  4973.6 1920.85  4982.2 1908.44
  4987.3 1907.44  4990.9 1902.20  4993.7 1901.70  4996.9 1902.20  5024.5 1907.40
  5215.9 1912.04  5258.8 1912.95  5276.2 1915.18  5283.6 1918.25  5288.9 1916.97
  5313.7 1928.58  5319.1 1927.65  5338.5 1935.05  5343.9 1934.34  5368.7 1945.17
  5374.0 1944.77  5423.6 1959.39  5430.3 1959.52  5453.8 1966.69  5497.0 1972.14
#Mann=7,-1,0
  4518.9     0.1       0  4531.3    0.16       0  4823.0     0.1       0
  4990.9    0.07       0  4996.9     0.1       0  5215.9    0.05       0
  5430.3     0.1       0
Bank Sta=4990.9,4996.9
Exp/Cntr=0.3,0.1

Type RM Length L Ch R = 1,50,0,0,0
BEGIN DESCRIPTION:
MIDDLE CREEK 1.0
END DESCRIPTION:
XS GIS Cut Line= 4
      2718203.59     10089534.58      2717615.09     10089370.53
      2717482.27     10089378.34      2717248.22     10089859.44
#Sta/Elev= 30
  4336.6 1963.08  4383.4 1961.73  4510.3 1953.50  4544.5 1947.72  4583.9 1944.40
  4618.0 1939.22  4657.4 1936.60  4674.1 1932.86  4725.8 1922.17  4844.0 1916.09
  4880.8 1908.42  4947.5 1904.76  5001.3 1897.16  5004.0 1896.66  5007.3 1897.16
  5048.0 1900.84  5101.7 1901.19  5169.6 1906.90  5186.6 1915.31  5192.2 1915.27
  5197.8 1920.22  5214.7 1925.89  5265.4 1936.94  5355.6 1951.05  5398.3 1955.50
  5424.8 1957.43  5507.9 1962.80  5581.1 1970.47  5613.2 1971.61  5615.6 1971.69
#Mann=10,-1,0
  4336.6     0.1       0  4674.1    0.05       0  4880.8     0.1       0
  5001.3    0.07       0  5007.3     0.1       0  5048.0    0.05       0
  5101.7     0.1       0  5398.3    0.05       0  5424.8     0.1       0
  5613.2    0.05       0
Bank Sta=5001.3,5007.3
Exp/Cntr=0.3,0.1

Chan Stop Cuts=-1