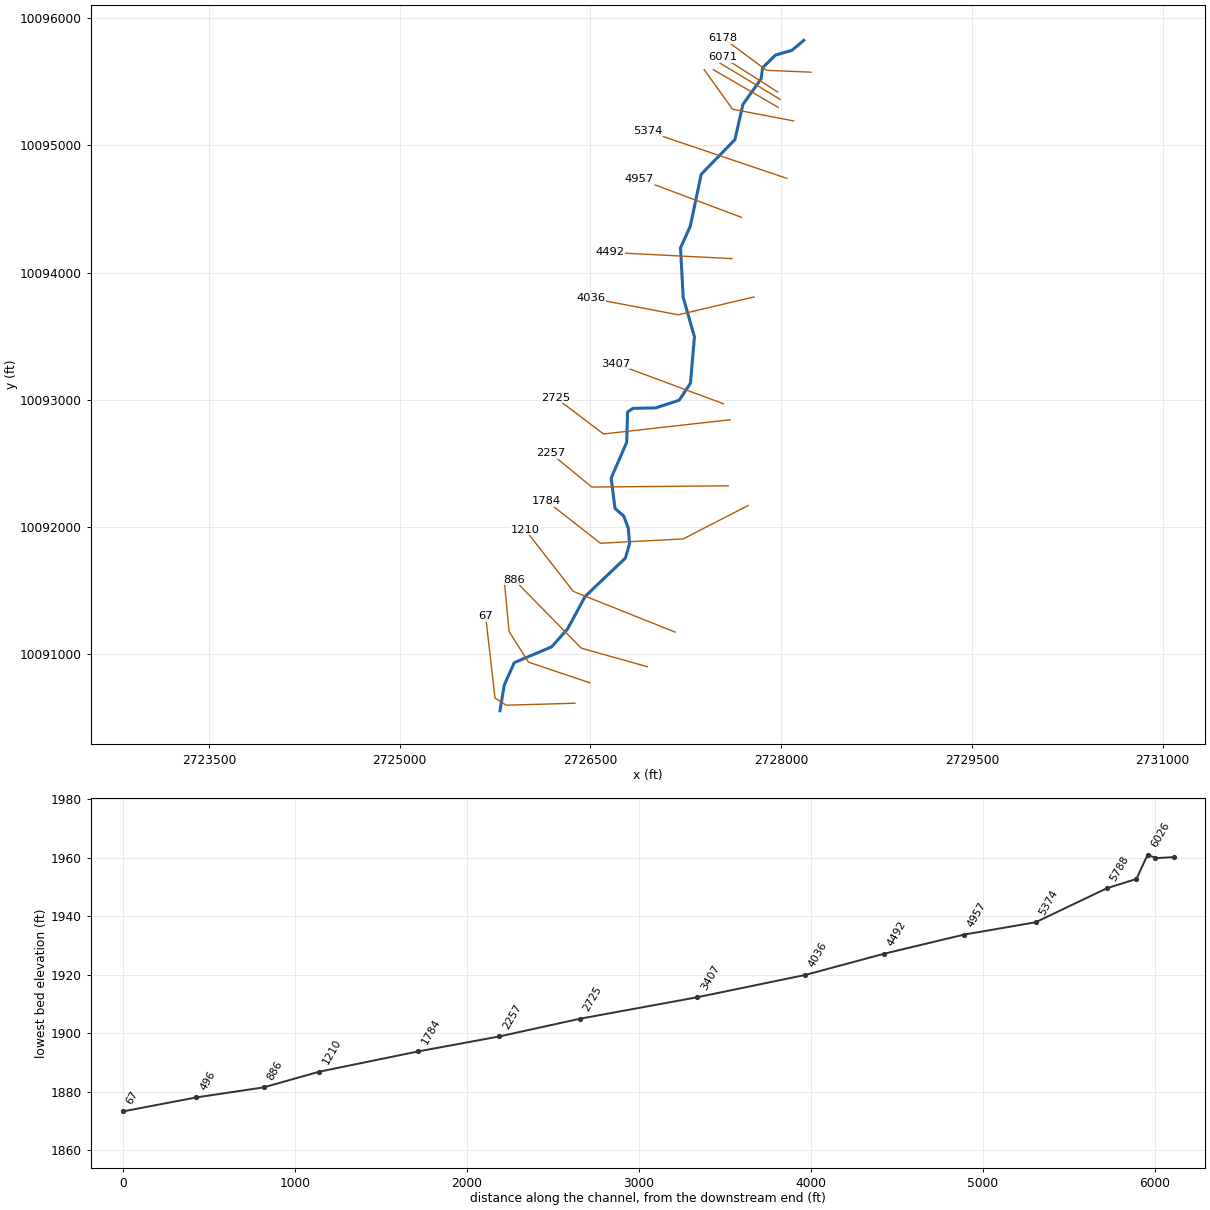
--- MOCCASIN CREEK.prj (project) ---

Proj Title=MOCCASIN CREEK Base Level Engineering
Current Plan=p01
Default Exp/Contr=0.3,0.1
English Units
Geom File=g01
Flow File=f01
Plan File=p01
BEGIN DESCRIPTION:
MOCCASIN CREEK
END DESCRIPTION:

--- MOCCASIN CREEK.p01 (plan) ---

Plan Title=Multiple Run
Short Identifier=Multiple
Geom File=g01
Flow File=f01
Subcritical Flow
K Sum by GR= 0
Std Step Tol= 0.01
Critical Tol= 0.01
Num of Std Step Trials= 20
Max Error Tol= 0.3
Flow Tol Ratio= 0.001
Split Flow NTrial= 30
Split Flow Tol= 0.02
Split Flow Ratio= 0.02
Log Output Level= 0
Friction Slope Method= 1
Unsteady Friction Slope Method= 2
Unsteady Bridges Friction Slope Method= 1
Parabolic Critical Depth
Global Vel Dist=  1 , 1 , 1
Global Log Level= 0
CheckData=True
Encroach Param= -1, 0, 0, 0
BEGIN DESCRIPTION:
Multiple Run
END DESCRIPTION:

--- MOCCASIN CREEK.f01 (steady flow) ---

Flow Title=Multiple
Number of Profiles=7
Profile Names=10-year,25-year,50-year,1pct_min,100-year,1pct_plu,500-year
River Rch & RM= MOCCASIN CREEK,Reach-1,6178
     805    1168    1484    1381    1868    2526    2969
River Rch & RM= MOCCASIN CREEK,Reach-1,5374
    1282    1903    2453    2312    3127    4229    5105
Boundary for River Rch & Prof#=MOCCASIN CREEK,Reach-1,1
Up Type=0
Dn Type=3
Dn Slope=0.005
Boundary for River Rch & Prof#=MOCCASIN CREEK,Reach-1,2
Up Type=0
Dn Type=3
Dn Slope=0.005
Boundary for River Rch & Prof#=MOCCASIN CREEK,Reach-1,3
Up Type=0
Dn Type=3
Dn Slope=0.005
Boundary for River Rch & Prof#=MOCCASIN CREEK,Reach-1,4
Up Type=0
Dn Type=3
Dn Slope=0.005
Boundary for River Rch & Prof#=MOCCASIN CREEK,Reach-1,5
Up Type=0
Dn Type=3
Dn Slope=0.005
Boundary for River Rch & Prof#=MOCCASIN CREEK,Reach-1,6
Up Type=0
Dn Type=3
Dn Slope=0.005
Boundary for River Rch & Prof#=MOCCASIN CREEK,Reach-1,7
Up Type=0
Dn Type=3
Dn Slope=0.005

--- MOCCASIN CREEK.g01 (geometry) ---

Geom Title=Existing Conditions

River Reach=MOCCASIN CREEK,Reach-1
Reach XY= 30
      2728178.44     10095825.90      2728084.51     10095747.13
      2727955.18     10095709.45      2727855.06     10095611.90
      2727842.07     10095522.35      2727699.68     10095322.03
      2727636.07     10095044.67      2727371.24     10094772.64
      2727285.67     10094364.89      2727208.61     10094193.67
      2727229.67     10093803.64      2727318.17     10093495.01
      2727286.48     10093129.10      2727197.86     10092995.41
      2727012.69     10092935.60      2726833.72     10092931.96
      2726791.88     10092902.54      2726785.23     10092665.03
      2726663.22     10092383.37      2726693.48     10092144.60
      2726762.21     10092084.89      2726797.11     10091992.27
      2726807.94     10091869.04      2726775.32     10091755.03
      2726458.91     10091453.65      2726320.42     10091197.60
      2726195.18     10091056.89      2725900.90     10090932.24
      2725822.62     10090756.69      2725788.47     10090553.73

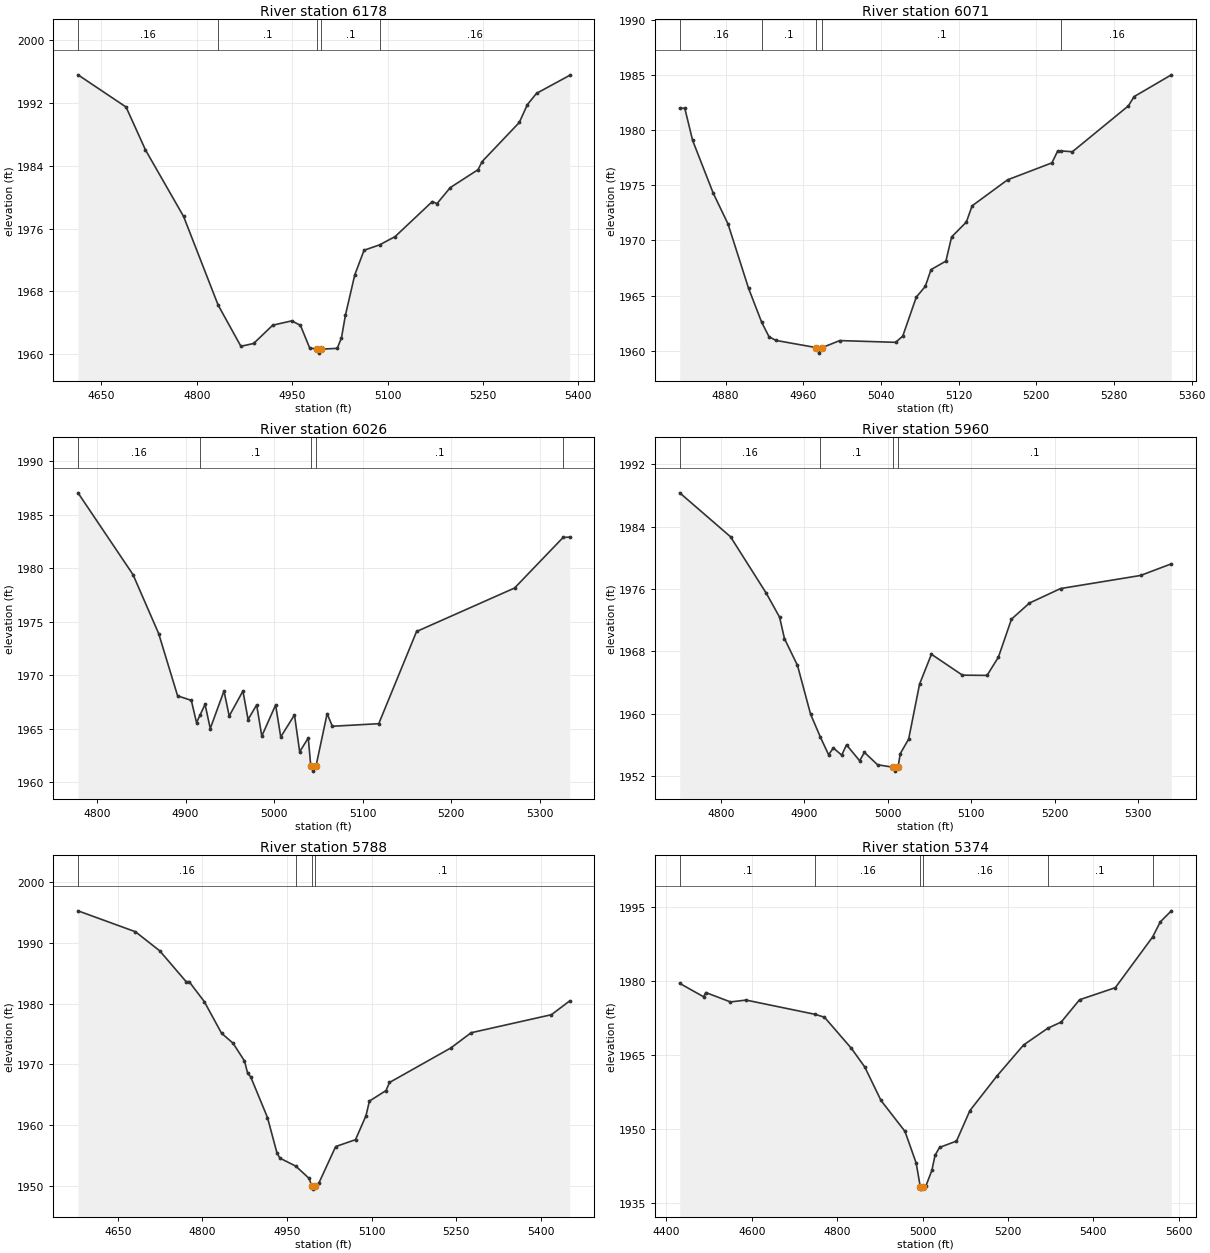
Type RM Length L Ch R = 1,6178,107,107,107
BEGIN DESCRIPTION:
MOCCASIN CREEK 14.0
END DESCRIPTION:
XS GIS Cut Line= 3
      2728234.47     10095575.40      2727884.91     10095589.96
      2727545.08     10095842.41
#Sta/Elev= 30
  4613.1 1995.57  4688.7 1991.47  4719.2 1986.01  4779.2 1977.53  4833.5 1966.25
  4869.3 1961.00  4889.3 1961.36  4919.4 1963.69  4949.4 1964.24  4963.0 1963.66
  4977.4 1960.80  4989.1 1960.63  4991.8 1960.13  4995.1 1960.63  5020.8 1960.74
  5027.5 1962.09  5033.7 1964.97  5048.4 1970.10  5063.0 1973.23  5087.5 1973.92
  5111.8 1974.97  5170.3 1979.43  5177.7 1979.17  5198.6 1981.21  5242.4 1983.50
  5248.6 1984.52  5307.1 1989.50  5319.8 1991.77  5334.2 1993.21  5386.3 1995.50
#Mann=5,-1,0
  4613.1    0.16       0  4833.5     0.1       0  4989.1    0.07       0
  4995.1     0.1       0  5087.5    0.16       0
Bank Sta=4989.1,4995.1
Exp/Cntr=0.3,0.1

Type RM Length L Ch R = 1,6071,45,45,45
BEGIN DESCRIPTION:
Mapping XS 3537c940
END DESCRIPTION:
XS GIS Cut Line= 2
      2727972.27     10095420.07      2727545.12     10095691.89
#Sta/Elev= 30
  4832.8 1982.00  4838.0 1982.00  4846.1 1979.07  4867.3 1974.29  4882.5 1971.50
  4903.7 1965.65  4917.3 1962.55  4924.8 1961.25  4932.1 1960.92  4973.5 1960.27
  4976.2 1959.77  4979.5 1960.27  4997.6 1960.91  5055.2 1960.75  5062.5 1961.32
  5076.4 1964.85  5085.7 1965.83  5091.6 1967.35  5106.9 1968.12  5112.8 1970.32
  5128.0 1971.67  5133.9 1973.14  5170.4 1975.50  5216.1 1977.04  5222.0 1978.11
  5225.9 1978.12  5237.2 1978.05  5294.8 1982.21  5300.7 1983.05  5339.1 1985.03
#Mann=5,-1,0
  4832.8    0.16       0  4917.3     0.1       0  4973.5    0.07       0
  4979.5     0.1       0  5225.9    0.16       0
Bank Sta=4973.5,4979.5
Exp/Cntr=0.3,0.1

Type RM Length L Ch R = 1,6026,66,66,66
BEGIN DESCRIPTION:
Mapping XS e7236b91
END DESCRIPTION:
XS GIS Cut Line= 2
      2727991.67     10095361.82      2727515.93     10095648.23
#Sta/Elev= 30
  4778.5 1987.06  4840.6 1979.41  4869.6 1973.89  4891.0 1968.06  4906.5 1967.63
  4912.4 1965.55  4916.5 1966.28  4922.0 1967.26  4927.9 1965.00  4943.4 1968.51
  4949.3 1966.17  4964.8 1968.51  4970.6 1965.84  4980.3 1967.21  4986.1 1964.29
  5001.7 1967.20  5007.5 1964.21  5023.0 1966.27  5028.9 1962.82  5038.6 1964.12
  5041.4 1961.51  5044.2 1961.01  5047.4 1961.51  5059.9 1966.39  5065.8 1965.21
  5118.2 1965.45  5160.9 1974.08  5271.6 1978.15  5326.4 1982.88  5333.8 1982.92
#Mann=5,-1,0
  4778.5    0.16       0  4916.5     0.1       0  5041.4    0.07       0
  5047.4     0.1       0  5326.4    0.16       0
Bank Sta=5041.4,5047.4
Exp/Cntr=0.3,0.1

Type RM Length L Ch R = 1,5960,172,172,172
BEGIN DESCRIPTION:
Mapping XS f02197f6
END DESCRIPTION:
XS GIS Cut Line= 2
      2727977.11     10095298.70      2727467.39     10095594.83
#Sta/Elev= 30
  4750.6 1988.33  4811.5 1982.70  4854.5 1975.44  4870.3 1972.40  4876.2 1969.64
  4891.8 1966.21  4907.5 1959.96  4919.3 1957.01  4929.1 1954.76  4934.8 1955.63
  4944.8 1954.71  4950.6 1956.03  4966.3 1953.99  4972.1 1955.06  4987.8 1953.48
  5006.3 1953.16  5009.1 1952.66  5012.3 1953.16  5015.1 1954.91  5025.1 1956.77
  5038.2 1963.82  5052.4 1967.64  5089.6 1964.96  5119.1 1964.93  5132.7 1967.27
  5148.4 1972.14  5169.9 1974.20  5207.2 1976.06  5303.2 1977.74  5340.1 1979.23
#Mann=4,-1,0
  4750.6    0.16       0  4919.3     0.1       0  5006.3    0.07       0
  5012.3     0.1       0
Bank Sta=5006.3,5012.3
Exp/Cntr=0.3,0.1

Type RM Length L Ch R = 1,5788,414,414,414
BEGIN DESCRIPTION:
MOCCASIN CREEK 13.0
END DESCRIPTION:
XS GIS Cut Line= 3
      2728098.49     10095191.89      2727617.90     10095284.12
      2727394.58     10095594.83
#Sta/Elev= 30
  4579.4 1995.25  4681.3 1991.81  4724.5 1988.66  4771.3 1983.59  4776.4 1983.62
  4803.4 1980.32  4834.0 1975.12  4854.4 1973.48  4874.7 1970.56  4880.4 1968.50
  4885.5 1967.99  4915.5 1961.25  4932.4 1955.40  4937.5 1954.58  4965.7 1953.26
  4989.5 1951.23  4993.9 1949.98  4996.7 1949.48  4999.9 1949.98  5007.1 1950.57
  5036.4 1956.48  5071.6 1957.61  5090.1 1961.53  5096.3 1963.96  5125.7 1965.69
  5131.9 1967.02  5240.7 1972.70  5276.7 1975.20  5419.2 1978.17  5451.4 1980.43
#Mann=4,-1,0
  4579.4    0.16       0  4965.7     0.1       0  4993.9    0.07       0
  4999.9     0.1       0
Bank Sta=4993.9,4999.9
Exp/Cntr=0.3,0.1

Type RM Length L Ch R = 1,5374,417,417,417
BEGIN DESCRIPTION:
MOCCASIN CREEK 12.0
END DESCRIPTION:
XS GIS Cut Line= 2
      2728045.07     10094740.41      2726954.03     10095108.94
#Sta/Elev= 30
  4431.1 1979.47  4487.0 1976.76  4492.2 1977.61  4549.9 1975.72  4586.6 1976.09
  4747.6 1973.22  4770.1 1972.63  4833.0 1966.35  4864.4 1962.58  4902.5 1955.80
  4958.8 1949.53  4985.0 1943.11  4994.5 1938.36  4997.2 1937.86  5000.5 1938.36
  5008.0 1938.57  5021.7 1941.64  5029.2 1944.71  5039.7 1946.29  5079.4 1947.58
  5110.8 1953.74  5173.7 1960.69  5236.6 1967.02  5293.3 1970.40  5324.7 1971.65
  5367.7 1976.16  5451.4 1978.60  5538.7 1988.84  5556.9 1991.92  5582.7 1994.14
#Mann=6,-1,0
  4431.1     0.1       0  4747.6    0.16       0  4994.5    0.07       0
  5000.5    0.16       0  5293.3     0.1       0  5538.7    0.16       0
Bank Sta=4994.5,5000.5
Exp/Cntr=0.3,0.1

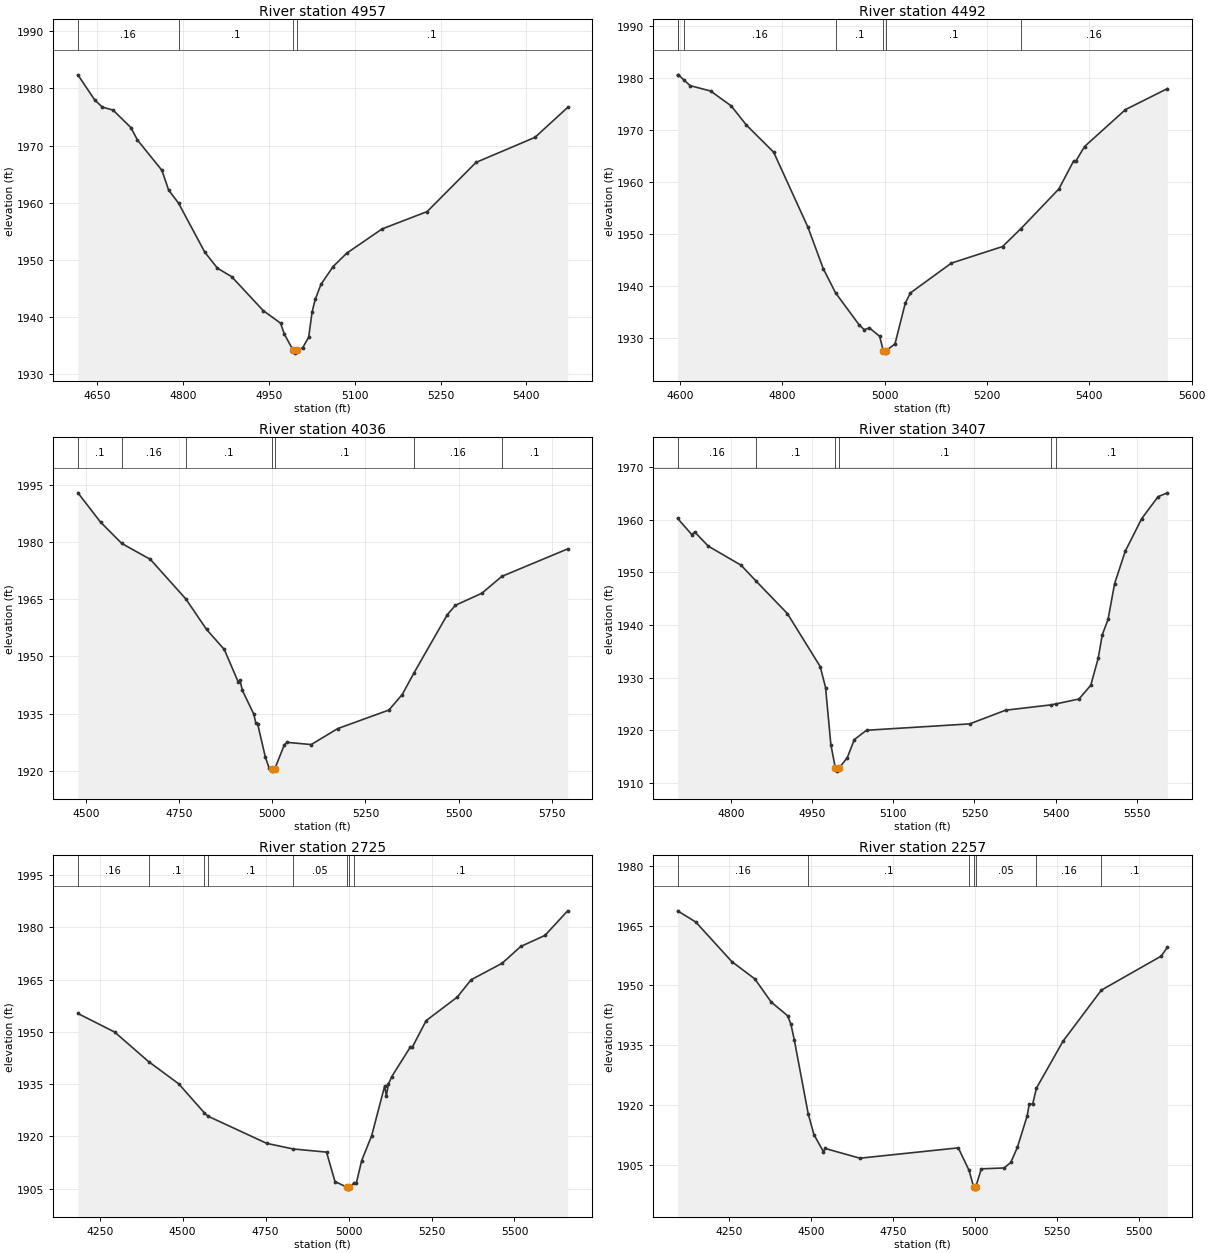
Type RM Length L Ch R = 1,4957,465,465,465
BEGIN DESCRIPTION:
MOCCASIN CREEK 11.0
END DESCRIPTION:
XS GIS Cut Line= 2
      2727685.90     10094434.55      2726884.89     10094735.53
#Sta/Elev= 30
  4616.4 1982.39  4645.7 1977.99  4659.2 1976.73  4677.8 1976.22  4709.0 1973.14
  4720.5 1970.96  4763.2 1965.65  4774.8 1962.22  4792.3 1959.89  4838.0 1951.33
  4860.2 1948.51  4885.1 1947.02  4940.3 1941.07  4970.5 1938.88  4976.9 1937.00
  4992.4 1934.13  4995.1 1933.63  4998.4 1934.13  5008.9 1934.54  5019.6 1936.43
  5025.6 1940.85  5031.0 1943.03  5041.0 1945.67  5062.3 1948.80  5086.1 1951.14
  5147.8 1955.39  5226.6 1958.43  5312.0 1967.05  5414.9 1971.43  5472.1 1976.68
#Mann=4,-1,0
  4616.4    0.16       0  4792.3     0.1       0  4992.4    0.07       0
  4998.4     0.1       0
Bank Sta=4992.4,4998.4
Exp/Cntr=0.3,0.1

Type RM Length L Ch R = 1,4492,456,456,456
BEGIN DESCRIPTION:
MOCCASIN CREEK 10.0
END DESCRIPTION:
XS GIS Cut Line= 2
      2727613.02     10094109.30      2726656.65     10094157.85
#Sta/Elev= 30
  4594.9 1980.56  4596.4 1980.56  4606.6 1979.63  4619.5 1978.48  4659.5 1977.45
  4699.6 1974.60  4729.6 1970.89  4782.8 1965.69  4849.8 1951.27  4879.8 1943.30
  4903.7 1938.68  4949.9 1932.52  4959.9 1931.59  4969.9 1931.94  4990.0 1930.32
  4997.0 1927.59  4999.7 1927.09  5003.0 1927.59  5020.0 1928.87  5040.0 1936.68
  5050.0 1938.65  5130.1 1944.38  5230.3 1947.57  5266.4 1951.03  5340.4 1958.64
  5369.1 1963.99  5374.1 1964.07  5390.5 1966.78  5470.6 1973.88  5552.5 1977.91
#Mann=7,-1,0
  4594.9    0.16       0  4596.4     0.1       0  4606.6    0.16       0
  4903.7     0.1       0  4997.0    0.07       0  5003.0     0.1       0
  5266.4    0.16       0
Bank Sta=4997,5003
Exp/Cntr=0.3,0.1

Type RM Length L Ch R = 1,4036,629,629,629
BEGIN DESCRIPTION:
MOCCASIN CREEK 9.0
END DESCRIPTION:
XS GIS Cut Line= 3
      2727787.82     10093808.31      2727190.69     10093667.53
      2726502.43     10093798.39
#Sta/Elev= 30
  4478.4 1992.99  4539.4 1985.26  4596.2 1979.68  4672.9 1975.50  4768.5 1965.05
  4823.6 1957.09  4871.0 1951.86  4908.2 1943.38  4913.4 1943.71  4919.5 1941.12
  4950.4 1934.82  4955.7 1932.53  4960.8 1932.22  4981.2 1923.60  4991.4 1920.68
  5000.2 1920.37  5002.9 1919.87  5006.2 1920.37  5032.5 1926.84  5040.4 1927.43
  5104.3 1926.85  5175.6 1931.05  5312.8 1935.92  5348.6 1940.00  5380.2 1945.69
  5469.4 1960.95  5491.2 1963.44  5562.4 1966.62  5615.9 1971.04  5792.5 1978.26
#Mann=7,-1,0
  4478.4     0.1       0  4596.2    0.16       0  4768.5     0.1       0
  5000.2    0.07       0  5006.2     0.1       0  5380.2    0.16       0
  5615.9     0.1       0
Bank Sta=5000.2,5006.2
Exp/Cntr=0.3,0.1

Type RM Length L Ch R = 1,3407,682,682,682
BEGIN DESCRIPTION:
MOCCASIN CREEK 7.0
END DESCRIPTION:
XS GIS Cut Line= 2
      2727545.11     10092968.45      2726695.52     10093284.01
#Sta/Elev= 30
  4700.6 1960.22  4726.9 1957.15  4732.2 1957.66  4757.3 1954.96  4818.0 1951.34
  4846.0 1948.30  4903.7 1942.16  4964.5 1932.09  4974.4 1928.10  4984.2 1917.28
  4992.7 1912.73  4995.5 1912.23  4998.7 1912.73  5014.5 1914.76  5027.7 1918.23
  5050.2 1919.99  5241.1 1921.20  5307.5 1923.80  5392.4 1924.82  5399.9 1924.98
  5443.3 1925.92  5465.1 1928.53  5479.0 1933.70  5486.4 1938.11  5497.1 1941.03
  5509.3 1947.85  5529.0 1954.00  5559.4 1960.18  5589.7 1964.35  5606.9 1965.08
#Mann=6,-1,0
  4700.6    0.16       0  4846.0     0.1       0  4992.7    0.07       0
  4998.7     0.1       0  5392.4    0.05       0  5399.9     0.1       0
Bank Sta=4992.7,4998.7
Exp/Cntr=0.3,0.1

Type RM Length L Ch R = 1,2725,468,468,468
BEGIN DESCRIPTION:
MOCCASIN CREEK 6.0
END DESCRIPTION:
XS GIS Cut Line= 3
      2727598.49     10092842.24      2726603.28     10092730.58
      2726224.65     10093016.98
#Sta/Elev= 30
  4184.2 1955.27  4294.9 1949.95  4397.3 1941.47  4487.9 1935.11  4564.4 1926.87
  4576.5 1925.80  4753.3 1918.02  4833.0 1916.41  4933.5 1915.51  4959.1 1907.06
  4996.3 1905.39  4999.1 1904.89  5002.3 1905.39  5015.4 1906.56  5023.7 1906.75
  5039.6 1913.10  5069.7 1920.25  5108.8 1934.49  5113.8 1931.67  5120.1 1934.97
  5130.1 1937.17  5185.6 1945.56  5191.8 1945.56  5233.9 1953.24  5327.6 1959.97
  5369.2 1964.94  5462.8 1969.68  5519.0 1974.50  5591.8 1977.66  5660.4 1984.72
#Mann=8,-1,0
  4184.2    0.16       0  4397.3     0.1       0  4564.4    0.05       0
  4576.5     0.1       0  4833.0    0.05       0  4996.3   0.035       0
  5002.3    0.05       0  5015.4     0.1       0
Bank Sta=4996.3,5002.3
Exp/Cntr=0.3,0.1

Type RM Length L Ch R = 1,2257,473,473,473
BEGIN DESCRIPTION:
MOCCASIN CREEK 5.0
END DESCRIPTION:
XS GIS Cut Line= 3
      2727583.90     10092322.79      2726511.04     10092313.08
      2726186.57     10092579.44
#Sta/Elev= 30
  4093.5 1968.75  4148.9 1965.94  4258.9 1955.98  4328.9 1951.65  4378.9 1945.83
  4428.9 1942.40  4438.9 1940.24  4449.0 1936.42  4491.4 1917.83  4509.0 1912.54
  4538.0 1908.24  4543.0 1909.06  4649.0 1906.61  4949.0 1909.21  4981.7 1903.57
  4996.0 1899.34  4998.7 1898.84  5002.0 1899.34  5019.0 1903.94  5089.0 1904.16
  5109.0 1905.54  5129.0 1909.32  5159.0 1917.26  5165.2 1920.13  5175.8 1920.27
  5187.3 1924.23  5268.3 1936.02  5385.0 1948.83  5566.8 1957.35  5586.2 1959.57
#Mann=7,-1,0
  4093.5    0.16       0  4491.4     0.1       0  4981.7    0.05       0
  4996.0   0.035       0  5002.0    0.05       0  5187.3    0.16       0
  5385.0     0.1       0
Bank Sta=4996,5002
Exp/Cntr=0.3,0.1

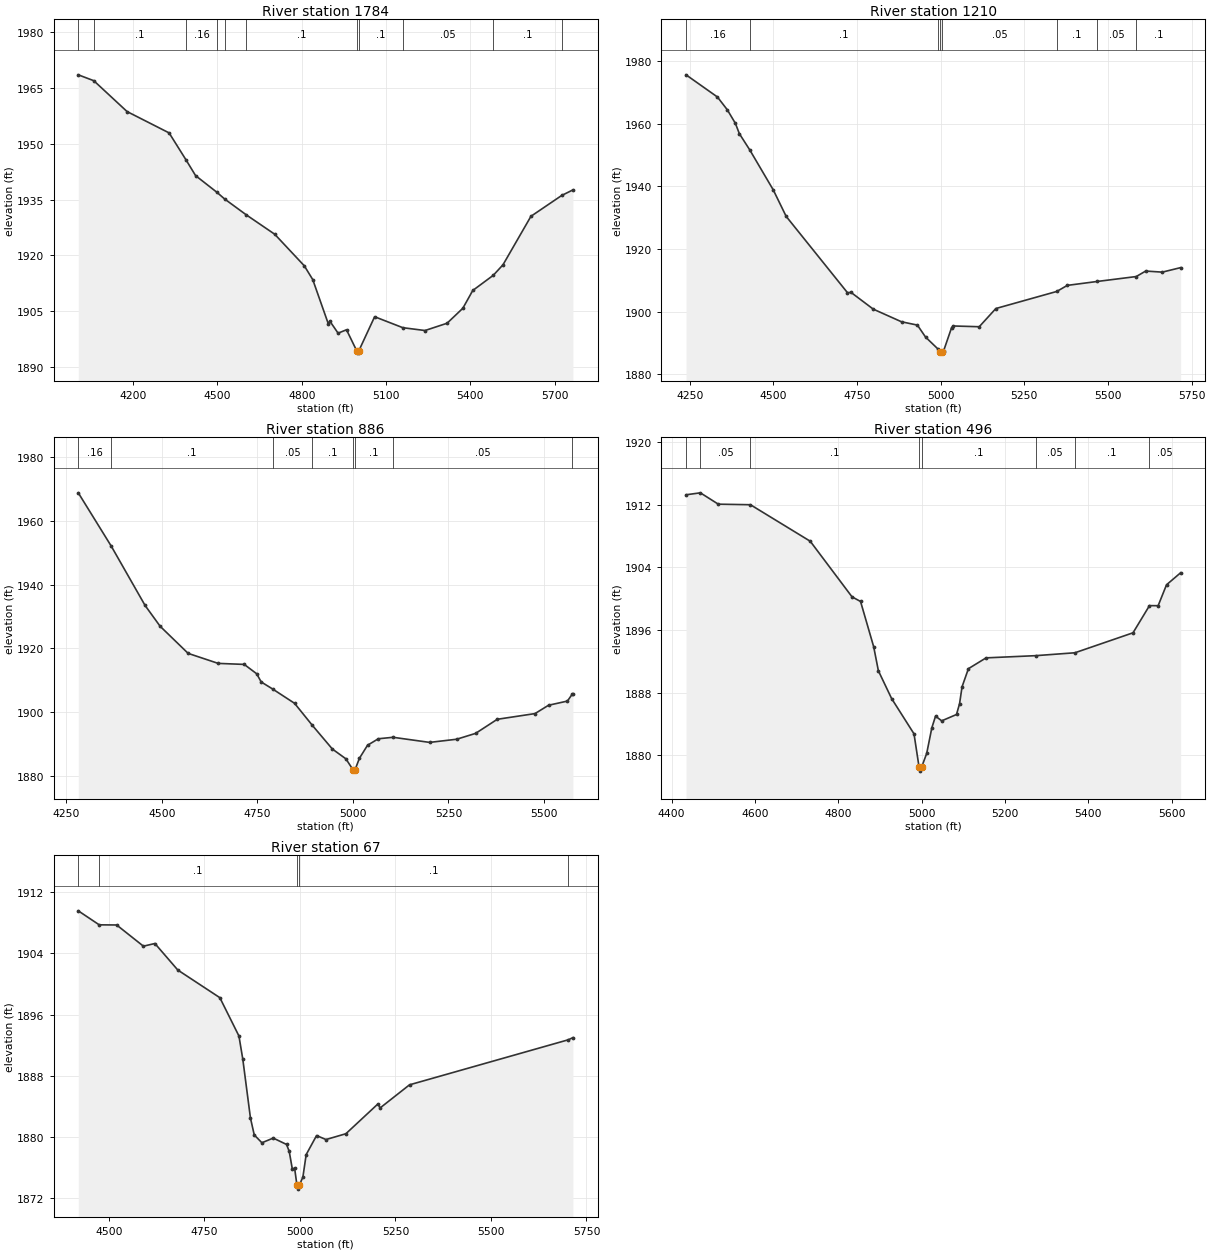
Type RM Length L Ch R = 1,1784,574,574,574
BEGIN DESCRIPTION:
MOCCASIN CREEK 4.0
END DESCRIPTION:
XS GIS Cut Line= 4
      2727739.29     10092167.45      2727229.53     10091905.29
      2726579.01     10091871.31      2726156.65     10092201.43
#Sta/Elev= 30
  4004.6 1968.56  4059.8 1966.98  4178.3 1958.68  4327.9 1952.94  4388.7 1945.61
  4422.2 1941.45  4497.2 1937.02  4526.0 1935.14  4603.2 1930.87  4703.8 1925.69
  4809.2 1917.19  4839.2 1913.49  4894.8 1901.55  4899.8 1902.34  4929.4 1899.08
  4959.4 1899.99  4996.5 1894.21  4999.2 1893.71  5002.5 1894.21  5059.5 1903.50
  5159.9 1900.55  5238.8 1899.79  5317.4 1901.75  5373.5 1905.78  5408.8 1910.56
  5481.8 1914.64  5516.4 1917.47  5615.9 1930.51  5725.3 1936.11  5765.3 1937.61
#Mann=11,-1,0
  4004.6    0.16       0  4059.8     0.1       0  4388.7    0.16       0
  4497.2     0.1       0  4526.0    0.16       0  4603.2     0.1       0
  4996.5    0.07       0  5002.5     0.1       0  5159.9    0.05       0
  5481.8     0.1       0  5725.3    0.16       0
Bank Sta=4996.5,5002.5
Exp/Cntr=0.3,0.1

Type RM Length L Ch R = 1,1210,324,324,324
BEGIN DESCRIPTION:
MOCCASIN CREEK 3.0
END DESCRIPTION:
XS GIS Cut Line= 3
      2727166.40     10091172.25      2726365.40     10091492.65
      2725986.73     10091978.13
#Sta/Elev= 30
  4239.1 1975.57  4332.9 1968.50  4362.5 1964.41  4386.7 1960.07  4398.4 1956.81
  4429.5 1951.63  4499.8 1938.86  4538.4 1930.41  4721.5 1906.08  4732.3 1906.16
  4798.7 1900.82  4883.1 1896.79  4930.6 1895.73  4954.9 1891.92  4993.3 1887.98
  4998.6 1887.29  5001.3 1886.79  5004.6 1887.29  5008.7 1887.44  5032.9 1894.95
  5038.3 1895.45  5115.4 1895.21  5165.1 1901.02  5347.3 1906.47  5378.6 1908.40
  5468.0 1909.65  5584.7 1911.22  5612.9 1912.97  5662.6 1912.63  5717.5 1914.07
#Mann=8,-1,0
  4239.1    0.16       0  4429.5     0.1       0  4993.3    0.05       0
  4998.6   0.035       0  5004.6    0.05       0  5347.3     0.1       0
  5468.0    0.05       0  5584.7     0.1       0
Bank Sta=4998.6,5004.6
Exp/Cntr=0.3,0.1

Type RM Length L Ch R = 1,886,390,390,390
BEGIN DESCRIPTION:
MOCCASIN CREEK 2.0
END DESCRIPTION:
XS GIS Cut Line= 3
      2726947.93     10090900.39      2726428.51     10091046.02
      2725899.35     10091584.90
#Sta/Elev= 30
  4281.1 1968.78  4367.2 1952.09  4456.0 1933.42  4495.3 1926.90  4568.7 1918.38
  4647.3 1915.24  4715.5 1914.92  4747.9 1912.00  4760.0 1909.40  4789.7 1907.21
  4847.2 1902.71  4893.5 1895.83  4946.2 1888.35  4981.6 1885.28  4999.8 1881.92
  5002.5 1881.42  5005.8 1881.92  5016.9 1885.44  5038.2 1889.54  5066.5 1891.58
  5105.0 1892.04  5200.8 1890.44  5271.5 1891.43  5321.1 1893.27  5377.7 1897.69
  5476.5 1899.48  5512.0 1902.10  5561.4 1903.41  5573.5 1905.49  5575.8 1905.49
#Mann=8,-1,0
  4281.1    0.16       0  4367.2     0.1       0  4789.7    0.05       0
  4893.5     0.1       0  4999.8    0.07       0  5005.8     0.1       0
  5105.0    0.05       0  5573.5    0.16       0
Bank Sta=4999.8,5005.8
Exp/Cntr=0.3,0.1

Type RM Length L Ch R = 1,496,429,429,429
BEGIN DESCRIPTION:
Mapping XS f23c216f
END DESCRIPTION:
XS GIS Cut Line= 4
      2726496.11     10090773.75      2726012.19     10090936.50
      2725860.28     10091177.39      2725823.42     10091567.60
#Sta/Elev= 30
  4434.5 1913.28  4468.9 1913.53  4512.0 1912.08  4589.1 1912.01  4732.6 1907.35
  4832.9 1900.25  4853.4 1899.66  4884.9 1893.88  4896.2 1890.81  4927.9 1887.27
  4981.7 1882.76  4993.9 1878.50  4996.7 1878.00  4999.9 1878.50  5012.2 1880.27
  5024.5 1883.53  5033.4 1885.02  5048.2 1884.42  5083.7 1885.23  5091.1 1886.62
  5097.0 1888.76  5112.3 1891.08  5154.7 1892.46  5273.6 1892.74  5367.9 1893.11
  5507.4 1895.66  5546.9 1899.13  5567.7 1899.12  5587.8 1901.79  5621.8 1903.33
#Mann=8,-1,0
  4434.5     0.1       0  4468.9    0.05       0  4589.1     0.1       0
  4993.9    0.07       0  4999.9     0.1       0  5273.6    0.05       0
  5367.9     0.1       0  5546.9    0.05       0
Bank Sta=4993.9,4999.9
Exp/Cntr=0.3,0.1

Type RM Length L Ch R = 1,67,0,0,0
BEGIN DESCRIPTION:
MOCCASIN CREEK 1.0
END DESCRIPTION:
XS GIS Cut Line= 4
      2726378.95     10090613.15      2725836.40     10090597.96
      2725749.60     10090654.39      2725675.83     10091298.79
#Sta/Elev= 30
  4419.7 1909.57  4474.5 1907.74  4520.2 1907.72  4590.2 1904.95  4620.3 1905.30
  4680.3 1901.83  4790.3 1898.22  4840.3 1893.21  4850.4 1890.18  4870.4 1882.50
  4880.4 1880.28  4900.4 1879.26  4930.1 1879.87  4964.9 1879.04  4971.9 1878.14
  4980.1 1875.81  4986.0 1875.96  4992.2 1873.70  4994.9 1873.20  4998.2 1873.70
  5007.7 1874.77  5016.3 1877.71  5043.5 1880.20  5068.2 1879.68  5120.3 1880.44
  5204.5 1884.35  5209.6 1883.80  5286.8 1886.83  5702.7 1892.72  5714.6 1893.00
#Mann=5,-1,0
  4419.7    0.05       0  4474.5     0.1       0  4992.2    0.07       0
  4998.2     0.1       0  5702.7    0.05       0
Bank Sta=4992.2,4998.2
Exp/Cntr=0.3,0.1

Chan Stop Cuts=-1