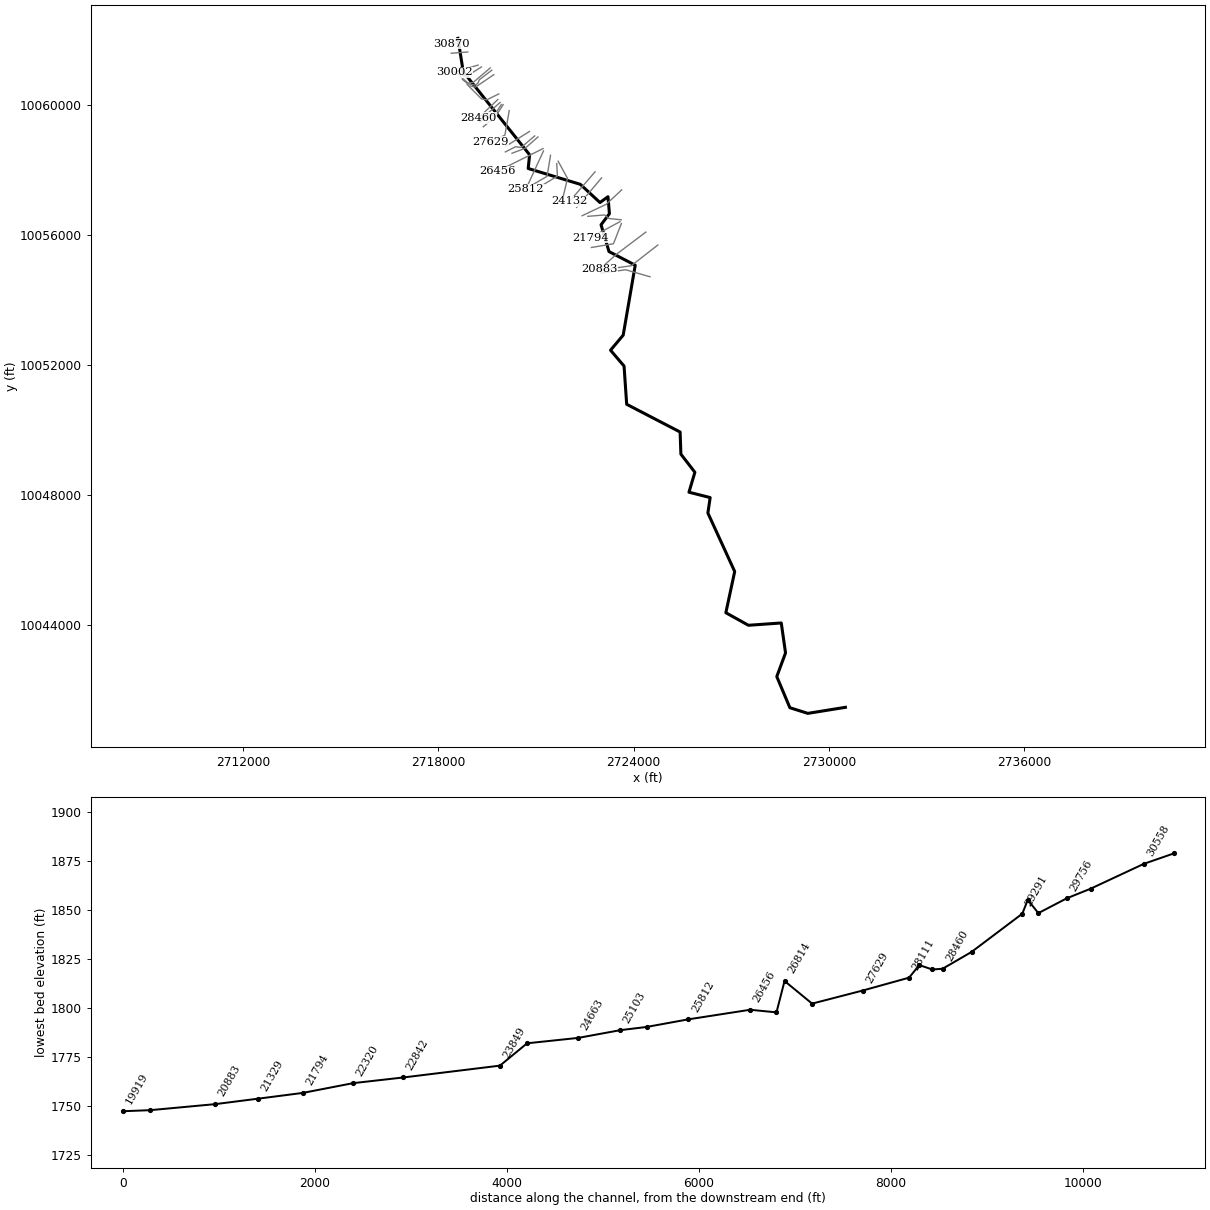
--- MUD CREEK.prj (project) ---

Proj Title=MUD CREEK Base Level Engineering
Current Plan=p01
Default Exp/Contr=0.3,0.1
English Units
Geom File=g01
Flow File=f01
Plan File=p01
Y Axis Title=Elevation
X Axis Title(PF)=Main Channel Distance
X Axis Title(XS)=Station
BEGIN DESCRIPTION:
MUD CREEK
END DESCRIPTION:
DSS Export Rating Curves= 0
DSS Export Rating Curve Sorted= 0
DSS Export Volume Flow Curves= 0
DXF OffsetX= 0
DXF OffsetY= 0
DXF ScaleX= 1
DXF ScaleY= 10

--- MUD CREEK.p01 (plan) ---

Plan Title=Multiple Run
Short Identifier=Multiple
Geom File=g01
Flow File=f01
Subcritical Flow
K Sum by GR= 0
Std Step Tol= 0.01
Critical Tol= 0.01
Num of Std Step Trials= 20
Max Error Tol= 0.3
Flow Tol Ratio= 0.001
Split Flow NTrial= 30
Split Flow Tol= 0.02
Split Flow Ratio= 0.02
Log Output Level= 0
Friction Slope Method= 1
Unsteady Friction Slope Method= 2
Unsteady Bridges Friction Slope Method= 1
Parabolic Critical Depth
Global Vel Dist=  1 , 1 , 1
Global Log Level= 0
CheckData=True
Encroach Param= -1, 0, 0, 0
BEGIN DESCRIPTION:
Multiple Run
END DESCRIPTION:

--- MUD CREEK.f01 (steady flow) ---

Flow Title=Multiple
Program Version=4.10
Number of Profiles= 7
Profile Names=10-year,25-year,50-year,1pct_min,100-year,1pct_plu,500-year
River Rch & RM=MUD CREEK,Reach-1         ,30870
     382     530     653     590     798    1079    1196
River Rch & RM=MUD CREEK,Reach-1         ,28460
    1323    1969    2542    2397    3241    4383    5277
River Rch & RM=MUD CREEK,Reach-1         ,27101
    1711    2584    3369    3205    4334    5862    7201
River Rch & RM=MUD CREEK,Reach-1         ,24132
    1881    2841    3704    3521    4762    6440    7905
River Rch & RM=MUD CREEK,Reach-1         ,17830
    2111    3204    4191    3997    5406    7311    9035
River Rch & RM=MUD CREEK,Reach-1         ,15705
    2179    3298    4304    4093    5536    7486    9203
River Rch & RM=MUD CREEK,Reach-1         ,6498
    2905    4444    5842    5593    7564   10229   12743
Boundary for River Rch & Prof#=MUD CREEK,Reach-1         , 1
Up Type= 0
Dn Type= 3
Dn Slope=0.0098
Boundary for River Rch & Prof#=MUD CREEK,Reach-1         , 2
Up Type= 0
Dn Type= 3
Dn Slope=0.0098
Boundary for River Rch & Prof#=MUD CREEK,Reach-1         , 3
Up Type= 0
Dn Type= 3
Dn Slope=0.0098
Boundary for River Rch & Prof#=MUD CREEK,Reach-1         , 4
Up Type= 0
Dn Type= 3
Dn Slope=0.0098
Boundary for River Rch & Prof#=MUD CREEK,Reach-1         , 5
Up Type= 0
Dn Type= 3
Dn Slope=0.0098
Boundary for River Rch & Prof#=MUD CREEK,Reach-1         , 6
Up Type= 0
Dn Type= 3
Dn Slope=0.0098
Boundary for River Rch & Prof#=MUD CREEK,Reach-1         , 7
Up Type= 0
Dn Type= 3
Dn Slope=0.0098
DSS Import GetInterval= 0
DSS Import GetPeak= 0
DSS Import FillOption= 0

--- MUD CREEK.g01 (geometry) ---

Geom Title=Existing Conditions
Program Version=4.10

River Reach=MUD CREEK       ,Reach-1
Reach XY= 30
      2718599.39     10062044.19      2718763.17     10061017.59
      2720803.27     10058465.42      2720759.31     10058043.88
      2722361.18      10057557.4       2722965.4     10056998.02
      2723212.62     10057176.63      2723255.74     10056654.83
      2722998.71     10056313.87      2723243.16     10055490.96
      2724048.92     10055071.52      2723679.13     10052921.13
      2723289.88     10052459.07      2723705.57     10051972.53
      2723786.42     10050797.23      2725428.54     10049944.64
      2725452.39     10049265.17      2725882.53     10048707.58
      2725700.85     10048094.73      2726352.06      10047930.1
      2726282.12     10047455.21      2727106.06     10045657.91
      2726834.47      10044390.9      2727528.39     10044005.11
      2728537.46     10044075.99      2728668.85     10043156.18
      2728399.44     10042428.41       2728802.2     10041471.49
       2729353.4     10041297.65      2730508.97     10041483.99

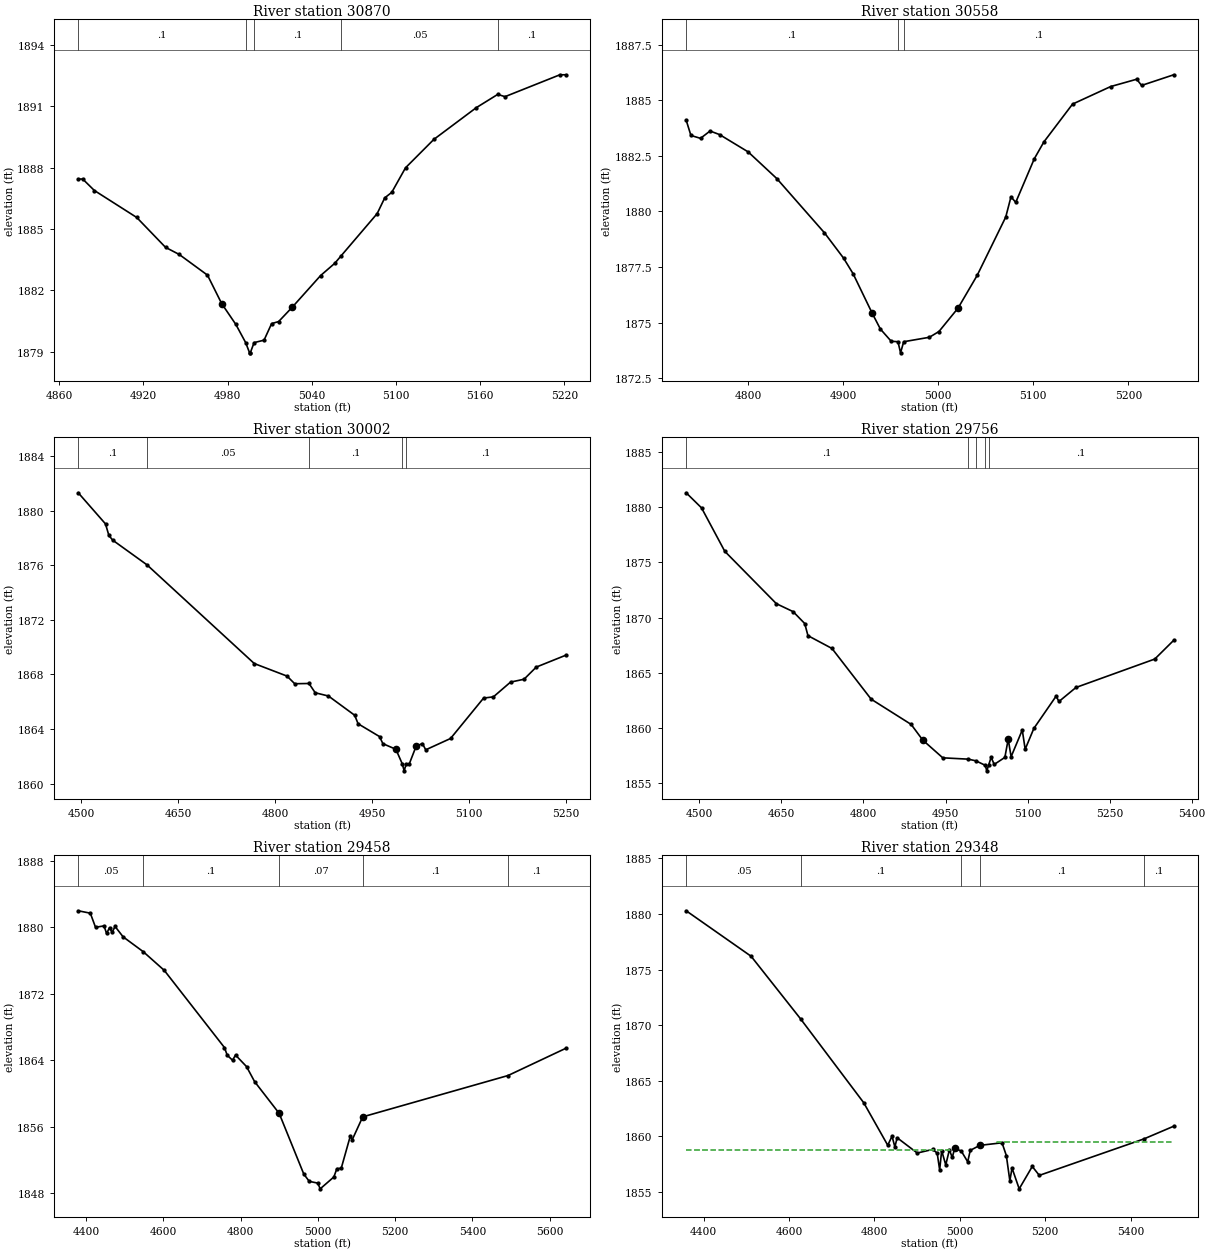
Type RM Length L Ch R = 1 ,30870   ,312,312,312
BEGIN DESCRIPTION:
MUD CREEK 64.0
END DESCRIPTION:
XS GIS Cut Line= 2
      2718759.87     10061925.86      2718415.15     10061882.77
#Sta/Elev= 30
  4873.6 1887.44  4876.8 1887.44  4885.1 1886.88  4915.3 1885.56  4935.8  1884.1
  4945.6 1883.75  4965.7 1882.74  4975.8 1881.35  4985.9 1880.33  4992.9 1879.44
  4995.7 1878.94  4996.2 1878.94  4998.9 1879.44    5006 1879.56  5011.4 1880.37
  5016.4 1880.47  5026.2 1881.18  5046.3 1882.72  5056.4 1883.32  5061.1  1883.7
  5086.6 1885.75    5092 1886.52    5097 1886.79  5106.8 1887.99    5127 1889.38
  5157.2 1890.93  5172.5 1891.58  5177.7 1891.47  5216.8 1892.54    5221 1892.54
#Mann= 5 ,-1 , 0
  4873.6      .1       0  4992.9     .07       0  4998.9      .1       0
  5061.1     .05       0  5172.5      .1       0
Bank Sta=4975.8,5026.2
XS Rating Curve= 0 ,0
Exp/Cntr=0.3,0.1

Type RM Length L Ch R = 1 ,30558   ,556,556,556
BEGIN DESCRIPTION:
MUD CREEK 63.0
END DESCRIPTION:
XS GIS Cut Line= 2
      2718903.49     10061624.23      2718392.32     10061586.02
#Sta/Elev= 30
  4735.1 1884.11  4740.1 1883.42  4750.2 1883.29  4760.2 1883.62  4770.2 1883.46
  4800.3 1882.68  4830.4 1881.48  4880.5 1879.04  4900.6  1877.9  4910.6  1877.2
  4930.7 1875.42  4939.3 1874.71  4950.7 1874.16  4957.8 1874.14  4960.5 1873.64
  4963.8 1874.14  4990.8 1874.34  5000.9  1874.6  5020.9 1875.65    5041 1877.12
  5071.1 1879.75  5076.6 1880.66  5081.6 1880.41  5101.1 1882.37  5111.2 1883.13
  5141.3 1884.83  5181.4 1885.62  5208.8 1885.95  5213.9 1885.67  5247.7 1886.15
#Mann= 3 ,-1 , 0
  4735.1      .1       0  4957.8     .07       0  4963.8      .1       0
Bank Sta=4930.7,5020.9
XS Rating Curve= 0 ,0
Exp/Cntr=0.3,0.1

Type RM Length L Ch R = 1 ,30002   ,246,246,246
BEGIN DESCRIPTION:
MUD CREEK 62.0
END DESCRIPTION:
XS GIS Cut Line= 2
      2719219.53     10061222.08      2718496.55     10061006.62
#Sta/Elev= 30
    4495 1881.31  4537.2 1879.03  4542.4 1878.19  4548.3 1877.84  4601.4 1876.03
  4767.4  1868.8  4818.1 1867.88    4830 1867.32    4852 1867.34  4861.7 1866.66
  4882.2 1866.42  4922.8 1865.01    4928 1864.39  4961.2 1863.45  4966.4 1862.93
  4986.5 1862.52  4996.5 1861.44  4999.3 1860.94  5002.5 1861.44  5007.4 1861.47
  5017.8 1862.74  5027.5 1862.94  5032.7 1862.48  5071.1 1863.31  5122.2 1866.27
  5137.4 1866.36  5163.9 1867.44  5184.8 1867.65  5203.7 1868.54  5249.4 1869.41
#Mann= 5 ,-1 , 0
    4495      .1       0  4601.4     .05       0    4852      .1       0
  4996.5     .07       0  5002.5      .1       0
Bank Sta=4986.5,5017.8
XS Rating Curve= 0 ,0
Exp/Cntr=0.3,0.1

Type RM Length L Ch R = 1 ,29756   ,298,298,298
BEGIN DESCRIPTION:
Mapping XS 7487fe46
END DESCRIPTION:
XS GIS Cut Line= 3
      2719324.31     10061165.54      2718850.37     10060868.68
      2718537.41     10060979.06
#Sta/Elev= 30
    4476 1881.32  4504.1 1879.95  4546.6 1876.01  4640.9 1871.26  4671.5 1870.54
  4692.7 1869.46  4698.6 1868.36  4742.5  1867.2  4814.1  1862.6  4887.2 1860.31
  4908.4 1858.89    4945 1857.28  4991.5 1857.16  5005.4 1857.01  5022.7  1856.6
  5025.4  1856.1  5028.7  1856.6  5033.4 1857.33    5039 1856.68  5058.5 1857.32
  5064.6 1858.97  5069.9 1857.38  5090.3  1859.8  5095.6 1858.06  5111.5 1859.95
  5152.1 1862.87  5157.4 1862.39  5188.4 1863.66  5332.5 1866.24  5367.1 1867.94
#Mann= 5 ,-1 , 0
    4476      .1       0  4991.5     .05       0  5005.4      .1       0
  5022.7    .035       0  5028.7      .1       0
Bank Sta=4908.4,5064.6
XS Rating Curve= 0 ,0
Exp/Cntr=0.3,0.1

Type RM Length L Ch R = 1 ,29458   ,110,110,110
BEGIN DESCRIPTION:
MUD CREEK 61.0
END DESCRIPTION:
XS GIS Cut Line= 4
      2719592.29     10061133.82      2719073.54     10060692.42
      2718909.72     10060669.67      2718595.74      10060942.7
#Sta/Elev= 30
  4379.3    1882  4410.6 1881.71  4424.1 1880.01  4446.1 1880.18  4452.7 1879.27
  4460.4 1879.97    4467 1879.39  4474.7 1880.11  4495.5 1878.86  4547.7 1877.07
  4602.1 1874.82    4758 1865.52  4765.1  1864.6  4778.9 1863.99  4786.6 1864.62
  4815.1 1863.23    4836 1861.42  4899.7 1857.59  4963.4 1850.28  4977.6  1849.4
  4999.6 1849.19  5005.9  1848.5  5041.3 1849.93    5049 1850.92  5060.4 1850.98
    5084 1854.88    5089 1854.43    5116 1857.17  5492.3 1862.15  5641.9 1865.43
#Mann= 5 ,-1 , 0
  4379.3     .05       0  4547.7      .1       0  4899.7     .07       0
    5116      .1       0  5492.3      .1       0
Bank Sta=4899.7,5116
XS Rating Curve= 0 ,0
Exp/Cntr=0.3,0.1

Type RM Length L Ch R = 1 ,29348   ,57,57,57
BEGIN DESCRIPTION:
Mapping XS 331c84d3
END DESCRIPTION:
XS GIS Cut Line= 6
       2719640.8     10061063.77      2719257.81     10060770.83
      2719210.06     10060660.15      2719130.85     10060609.16
      2718907.33     10060642.79      2718738.07     10060781.67
#Sta/Elev= 30
  4359.2 1880.28  4511.3 1876.19  4627.6 1870.54  4775.1 1863.02  4831.3  1859.2
  4841.4 1860.01    4848 1859.05  4853.4 1859.87  4900.5  1858.5  4936.2 1858.82
  4947.1  1858.5  4952.9 1856.98  4957.6 1858.71  4967.2 1857.43  4975.7 1858.79
  4982.3  1858.1  4988.3 1858.92  5003.5 1858.68  5018.6 1857.71  5024.6 1858.74
  5047.1 1859.19    5099 1859.42  5109.1 1858.27  5117.3    1856  5122.4 1857.15
  5139.2 1855.28  5169.8 1857.29  5186.3 1856.49  5431.4 1859.77  5501.1 1860.91
#Mann= 5 ,-1 , 0
  4359.2     .05       0  4627.6      .1       0  5003.5     .07       0
  5047.1      .1       0  5431.4      .1       0
#XS Ineff= 2 , 0
       0 4976.31 1858.76 5086.19       0 1859.53
Permanent Ineff=
       T       T
Bank Sta=4988.3,5047.1
XS Rating Curve= 0 ,0
Exp/Cntr=0.3,0.1

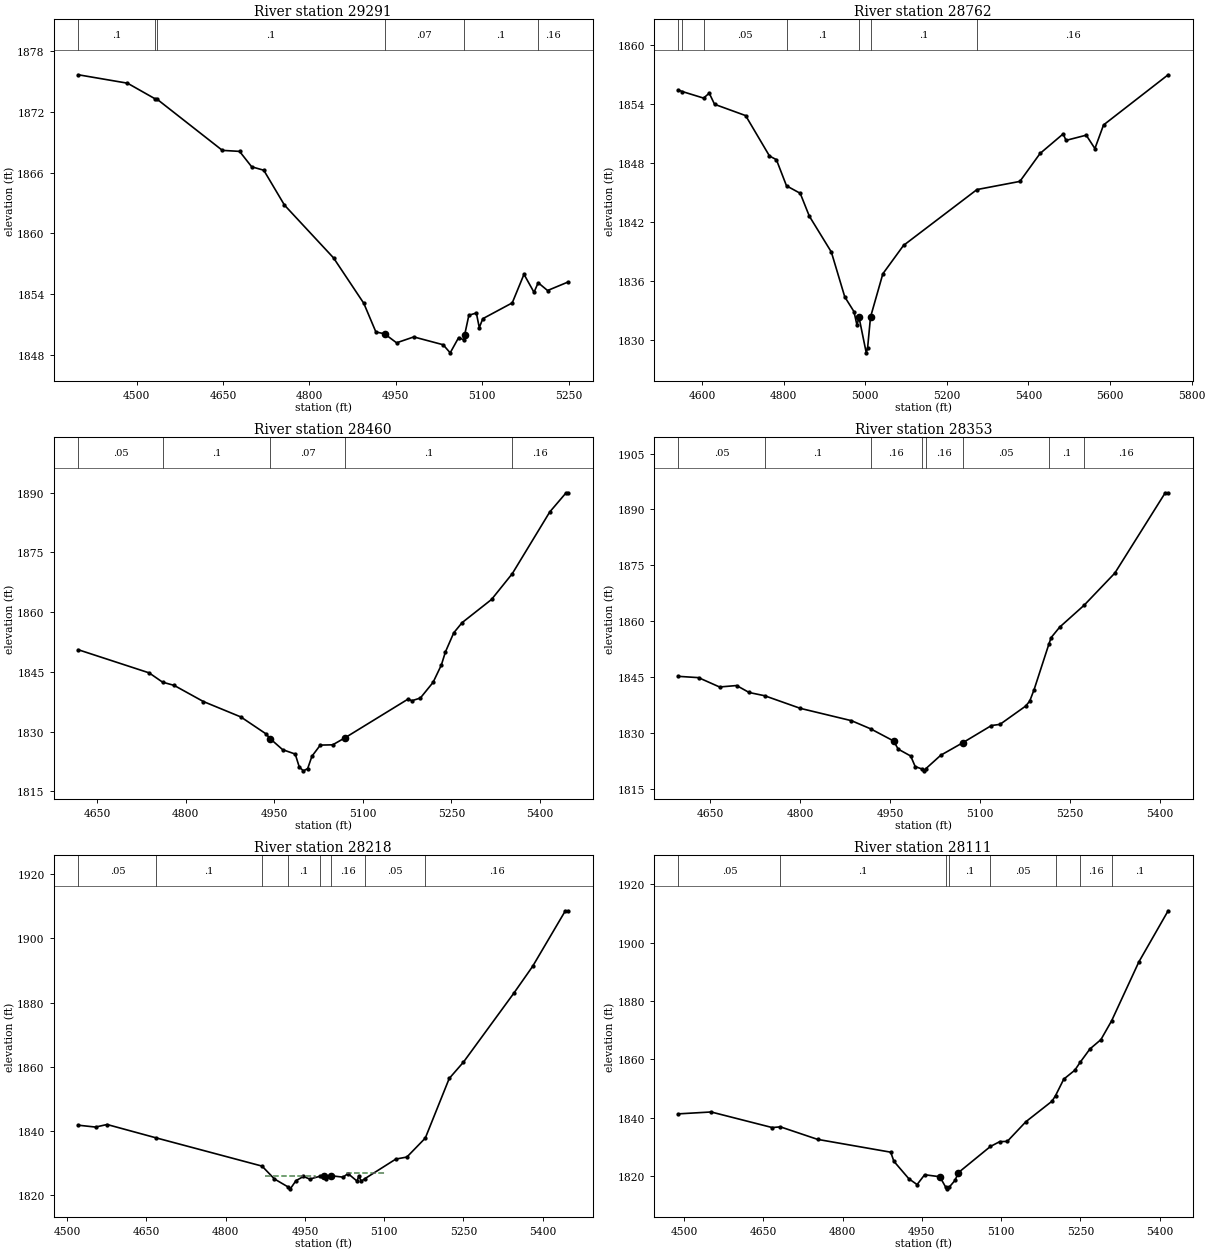
Type RM Length L Ch R = 1 ,29291   ,529,529,529
BEGIN DESCRIPTION:
Mapping XS b31b2d89
END DESCRIPTION:
XS GIS Cut Line= 3
      2719702.69     10060927.58      2719140.22     10060545.65
      2718973.59     10060580.37
#Sta/Elev= 30
  4398.8 1875.65  4484.1 1874.82  4532.6 1873.26    4535 1873.26  4648.8 1868.19
  4678.7 1868.09  4699.7 1866.57  4720.7 1866.23  4756.6 1862.79  4841.8 1857.58
  4894.3  1853.1  4915.3 1850.27  4930.3 1850.09  4951.2  1849.2  4981.1 1849.78
    5032 1849.01  5044.3 1848.21    5059 1849.72  5067.9 1849.49 5069.31 1849.96
  5076.7 1851.92  5089.7 1852.14  5094.8  1850.7  5100.9 1851.58    5152 1853.14
  5172.4 1855.96  5189.8 1854.18    5197 1855.13  5213.3 1854.36  5248.9  1855.2
#Mann= 6 ,-1 , 0
  4398.8      .1       0  4532.6     .05       0    4535      .1       0
  4930.3     .07       0  5067.9      .1       0    5197     .16       0
Bank Sta=4930.3,5069.31
XS Rating Curve= 0 ,0
Exp/Cntr=0.3,0.1

Type RM Length L Ch R = 1 ,28762   ,302,302,302
BEGIN DESCRIPTION:
MUD CREEK 60.0
END DESCRIPTION:
XS GIS Cut Line= 4
      2719856.22     10060336.31      2719487.61      10060154.4
      2719329.61     10060178.34      2718884.39     10060623.57
#Sta/Elev= 30
  4541.8 1855.43  4551.8 1855.27  4603.5 1854.61  4617.4 1855.11  4630.4 1853.98
  4706.6 1852.83  4765.1 1848.72    4782 1848.35  4806.8 1845.69  4840.4 1844.93
  4862.7 1842.61  4916.7 1838.96  4949.6  1834.4  4972.2  1832.9  4979.5 1831.53
  4984.6 1832.31  5002.3 1828.71  5005.6 1829.21  5012.7 1832.34    5043 1836.75
  5093.6 1839.63  5273.7 1845.31  5378.9 1846.14  5428.4 1848.98    5485 1850.97
    5492 1850.31  5541.5 1850.84  5562.8 1849.48    5584 1851.88  5742.3 1856.98
#Mann= 7 ,-1 , 0
  4541.8     .05       0  4551.8      .1       0  4603.5     .05       0
  4806.8      .1       0  4984.6     .07       0  5012.7      .1       0
  5273.7     .16       0
Bank Sta=4984.6,5012.7
XS Rating Curve= 0 ,0
Exp/Cntr=0.3,0.1

Type RM Length L Ch R = 1 ,28460   ,107,107,107
BEGIN DESCRIPTION:
MUD CREEK 59.0
END DESCRIPTION:
XS GIS Cut Line= 2
      2719827.57       10060164.      2719224.29     10059594.24
#Sta/Elev= 30
    4618 1850.53  4737.9 1844.73  4760.7  1842.4  4780.4 1841.58  4829.8 1837.54
  4893.3 1833.67  4935.8 1829.44    4943 1828.22  4964.1 1825.46  4985.5 1824.35
  4992.4 1821.08  4999.4 1820.14  5006.6 1820.71  5013.8 1823.81    5028  1826.6
    5049 1826.67  5070.5 1828.49  5176.5 1838.13  5183.4 1837.75  5197.5 1838.41
    5219 1842.33  5233.1  1846.7    5240 1849.99  5254.1 1854.78  5268.3 1857.34
  5318.1 1863.15  5353.3 1869.63  5416.8 1885.12  5444.5 1889.93  5447.8 1889.93
#Mann= 5 ,-1 , 0
    4618     .05       0  4760.7      .1       0    4943     .07       0
  5070.5      .1       0  5353.3     .16       0
Bank Sta=4943,5070.5
XS Rating Curve= 0 ,0
Exp/Cntr=0.3,0.1

Type RM Length L Ch R = 1 ,28353   ,135,135,135
BEGIN DESCRIPTION:
Mapping XS aef3c22e
END DESCRIPTION:
XS GIS Cut Line= 2
      2719895.07       10060074.      2719286.37      10059530.4
#Sta/Elev= 30
    4597 1845.16  4630.5 1844.81  4665.6  1842.3    4694 1842.69  4714.9 1840.82
  4740.7 1839.95  4800.2 1836.56  4885.4 1833.25  4917.5 1831.05  4955.7 1827.79
  4963.2 1825.62  4984.1 1823.76  4991.6 1820.93  5002.8 1820.28  5005.6 1819.78
  5008.8 1820.28  5034.2 1823.97  5070.7 1827.31  5118.7 1831.95  5132.9 1832.26
  5175.5 1837.15  5182.4 1838.49  5189.7 1841.57  5214.5 1853.88  5218.2 1855.58
  5232.4 1858.38  5273.2 1864.27  5324.3 1872.89  5408.3 1894.46  5413.1 1894.46
#Mann= 8 ,-1 , 0
    4597     .05       0  4740.7      .1       0  4917.5     .16       0
  5002.8     .07       0  5008.8     .16       0  5070.7     .05       0
  5214.5      .1       0  5273.2     .16       0
Bank Sta=4955.7,5070.7
XS Rating Curve= 0 ,0
Exp/Cntr=0.3,0.1

Type RM Length L Ch R = 1 ,28218   ,107,107,107
BEGIN DESCRIPTION:
Mapping XS c439532c
END DESCRIPTION:
XS GIS Cut Line= 4
      2719935.24     10060011.08      2719708.47     10059662.79
      2719597.79     10059699.68      2719274.46     10059472.91
#Sta/Elev= 30
    4521 1841.84  4553.6 1841.26  4575.4 1842.06  4668.9 1837.87  4868.8  1829.1
  4892.3 1825.09  4917.9 1822.63  4922.3 1822.02  4933.1 1824.57  4947.2 1825.87
  4959.2 1825.05  4978.8 1825.96  4985.5 1826.06  4990.8 1824.98  4999.9 1826.09
  5022.4 1825.66  5031.5 1826.78  5048.8 1824.41  5051.8    1826  5056.7 1824.41
  5063.6  1825.2  5122.1 1831.29    5143 1831.92  5177.9 1837.83  5223.2  1856.4
  5250.2  1861.5  5345.2 1882.89    5381 1891.29  5443.1 1908.63  5448.2 1908.63
#Mann= 8 ,-1 , 0
    4521     .05       0  4668.9      .1       0  4868.8     .16       0
  4917.9      .1       0  4978.8     .07       0  4999.9     .16       0
  5063.6     .05       0  5177.9     .16       0
#XS Ineff= 2 ,-1
 4875.29 4969.48    1826 5030.52 5102.03 1826.86
Permanent Ineff=
       T       T
Bank Sta=4985.5,4999.9
XS Rating Curve= 0 ,0
Exp/Cntr=0.3,0.1

Type RM Length L Ch R = 1 ,28111   ,482,482,482
BEGIN DESCRIPTION:
MUD CREEK 58.0
END DESCRIPTION:
XS GIS Cut Line= 3
      2719990.32     10060005.99      2719755.72     10059637.33
      2719377.47     10059326.11
#Sta/Elev= 30
  4489.3 1841.29  4551.2 1841.94  4666.8  1836.6  4682.3 1836.84  4752.7 1832.55
  4891.1 1828.16  4897.1 1825.04  4925.4 1819.06    4941 1817.06  4955.3 1820.43
    4984 1819.75  4995.4  1816.1  4998.1  1815.6  5001.4  1816.1  5012.7 1818.48
  5019.2 1821.16  5079.8 1830.12  5097.4 1831.77  5111.7 1831.86  5146.9  1838.6
  5196.4 1845.64  5203.1 1847.57  5218.6 1853.19  5239.4 1856.23  5249.7 1858.98
  5268.1 1863.53  5288.9 1866.73    5309 1873.12  5360.6 1893.32  5416.1 1910.88
#Mann= 8 ,-1 , 0
  4489.3     .05       0  4682.3      .1       0  4995.4     .07       0
  5001.4      .1       0  5079.8     .05       0  5203.1      .1       0
  5249.7     .16       0    5309      .1       0
Bank Sta=4984,5019.2
XS Rating Curve= 0 ,0
Exp/Cntr=0.3,0.1

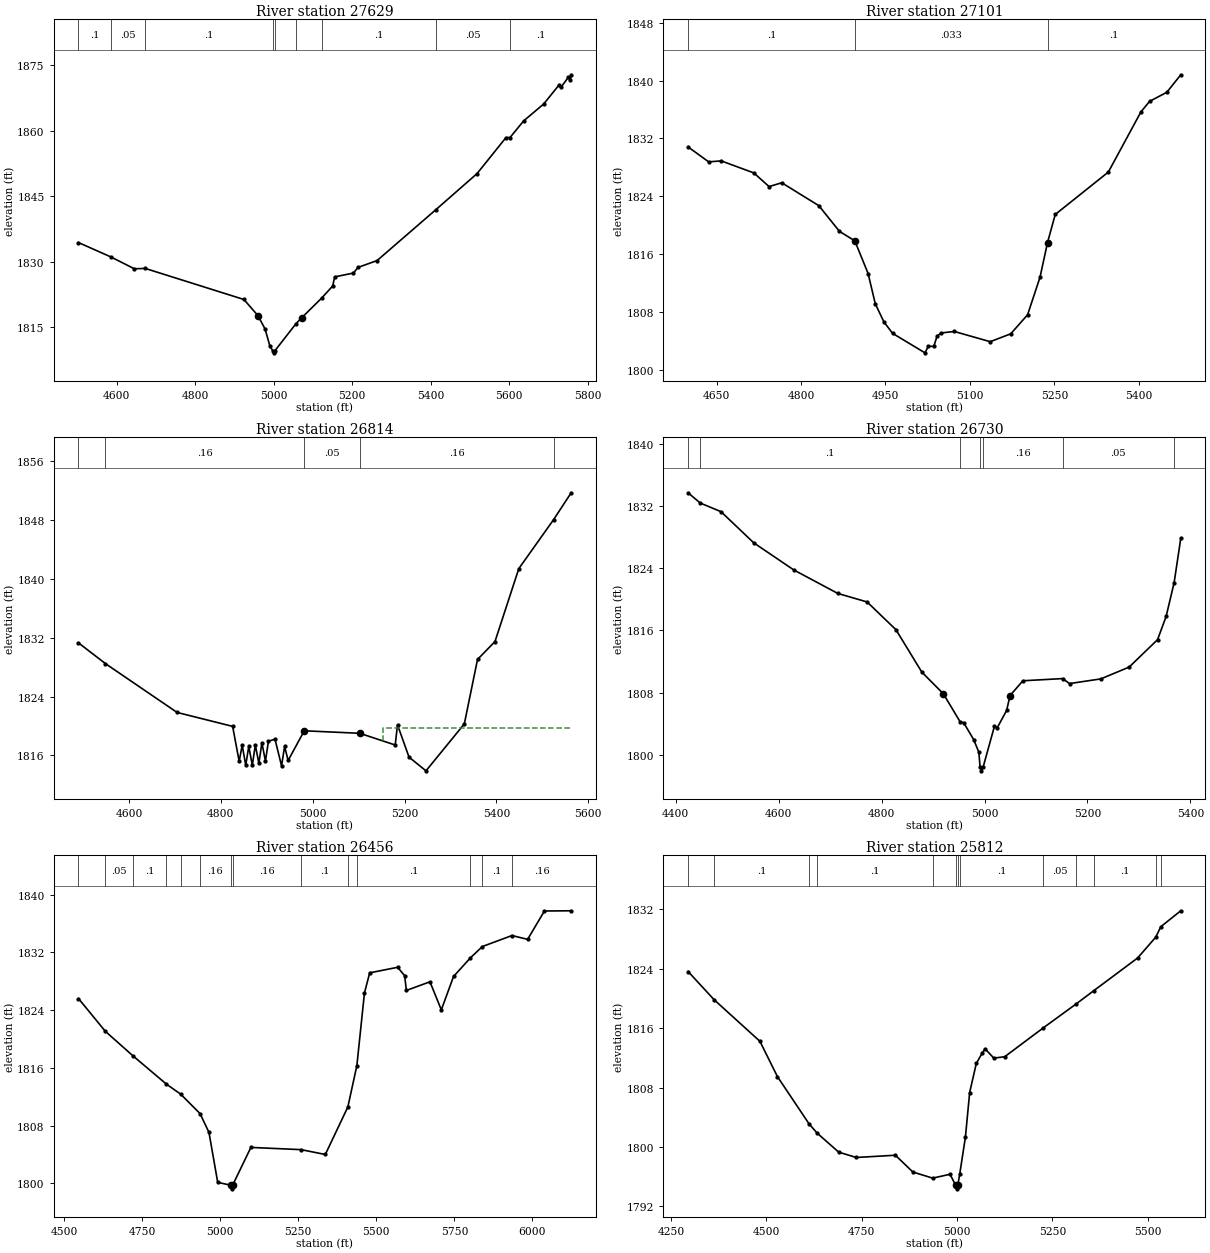
Type RM Length L Ch R = 1 ,27629   ,528,528,528
BEGIN DESCRIPTION:
MUD CREEK 57.0
END DESCRIPTION:
XS GIS Cut Line= 3
      2720177.04     10059824.02      2720042.98     10059067.59
      2719603.03     10058857.17
#Sta/Elev= 30
  4502.4 1834.34  4584.4 1831.07  4644.9 1828.33  4672.6 1828.41  4924.1 1821.29
  4959.7 1817.61  4978.1 1814.51  4990.2 1810.65  4997.3 1809.56  5000.1 1809.06
  5003.3 1809.56  5056.4  1815.7  5071.4  1817.1    5122 1821.59  5150.4 1824.39
  5155.5 1826.48  5203.4 1827.35  5214.6 1828.63  5263.6 1830.22  5413.1 1841.86
  5518.4 1850.16    5592  1858.4  5602.4 1858.43  5637.3 1862.25  5688.2 1866.11
    5728 1870.54  5733.6 1870.11  5750.7 1872.19  5756.3  1871.6  5758.3 1872.81
#Mann= 9 ,-1 , 0
  4502.4      .1       0  4584.4     .05       0  4672.6      .1       0
  4997.3     .07       0  5003.3      .1       0  5056.4     .16       0
    5122      .1       0  5413.1     .05       0  5602.4      .1       0
Bank Sta=4959.7,5071.4
XS Rating Curve= 0 ,0
Exp/Cntr=0.3,0.1

Type RM Length L Ch R = 1 ,27101   ,287,287,287
BEGIN DESCRIPTION:
MUD CREEK 56.0
END DESCRIPTION:
XS GIS Cut Line= 2
      2720799.42     10059182.48      2720057.86     10058718.41
#Sta/Elev= 30
  4599.5 1830.83    4636 1828.77  4658.4  1828.9  4716.2 1827.24  4743.3 1825.35
  4765.8 1825.88  4831.7 1822.71  4868.3 1819.16  4895.5 1817.86  4919.1 1813.34
  4931.9 1809.15  4947.3 1806.64  4962.6 1805.07  5020.1 1802.38  5026.2 1803.31
  5035.7 1803.26  5041.6 1804.69  5048.9 1805.13  5072.2 1805.33  5135.9 1803.92
  5172.4 1805.01  5202.3 1807.64  5224.3 1812.81  5237.7 1817.62  5251.4  1821.5
  5345.7 1827.36  5403.5 1835.67  5418.8 1837.12  5449.5 1838.38  5474.3  1840.8
#Mann= 3 , 0 , 0
  4599.5      .1       0  4895.5    .033       0  5237.7      .1       0
Bank Sta=4895.5,5237.7
XS Rating Curve= 0 ,0
Exp/Cntr=0.3,0.1

Type RM Length L Ch R = 1 ,26814   ,84,84,84
BEGIN DESCRIPTION:
Mapping XS 507fcca2
END DESCRIPTION:
XS GIS Cut Line= 4
      2720959.64     10059045.64      2720542.99     10058691.48
      2720369.38     10058712.32      2720056.91     10058552.61
#Sta/Elev= 30
  4490.1 1831.29  4548.9 1828.47  4704.8 1821.84  4825.7 1819.95  4839.9  1815.2
  4846.5 1817.38  4854.2 1814.67  4860.8 1817.23  4868.5 1814.68  4875.1  1817.4
  4882.8 1814.94  4889.4 1817.72  4897.1 1815.23  4903.6 1817.93  4917.9 1818.21
  4932.2 1814.58  4938.8 1817.23  4946.5 1815.32  4981.6 1819.35  5102.4 1819.01
  5179.6 1817.42  5184.6 1820.16  5209.7 1815.77  5246.6 1813.91  5330.1 1820.29
  5358.8 1829.04  5396.8 1831.47  5448.7 1841.38  5524.5 1848.04  5562.7 1851.68
#Mann= 5 ,-1 , 0
  4490.1      .1       0  4548.9     .16       0  4981.6     .05       0
  5102.4     .16       0  5524.5      .1       0
#XS Ineff= 2 ,-1
 4814.24 4980.81 1819.09 5152.62  5562.7 1819.78
Permanent Ineff=
       T       T
Bank Sta=4981.6,5102.4
XS Rating Curve= 0 ,0
Exp/Cntr=0.3,0.1

Type RM Length L Ch R = 1 ,26730   ,274,274,274
BEGIN DESCRIPTION:
MUD CREEK 55.0
END DESCRIPTION:
XS GIS Cut Line= 3
      2721060.12     10059012.06      2720660.13     10058662.07
      2720261.81      10058512.7
#Sta/Elev= 30
  4424.3  1833.7  4447.9 1832.38  4488.2 1831.27  4551.8 1827.26  4629.6 1823.77
    4715 1820.75    4772 1819.65    4828 1816.08  4878.3 1810.62    4920 1807.84
  4953.1 1804.18  4959.4 1804.13  4978.9 1801.95    4989 1800.32  4991.4 1798.42
  4994.1 1797.92  4997.4 1798.42  5019.3 1803.66  5024.6 1803.45    5043 1805.69
  5049.5  1807.6  5074.5 1809.51  5151.6 1809.79  5165.2 1809.15  5225.8 1809.75
  5280.9 1811.27  5336.1  1814.8  5352.7 1817.78  5368.3 1822.14  5381.2 1827.85
#Mann= 7 ,-1 , 0
  4424.3     .05       0  4447.9      .1       0  4953.1     .16       0
  4991.4     .07       0  4997.4     .16       0  5151.6     .05       0
  5368.3      .1       0
Bank Sta=4920,5049.5
XS Rating Curve= 0 ,0
Exp/Cntr=0.3,0.1

Type RM Length L Ch R = 1 ,26456   ,644,644,644
BEGIN DESCRIPTION:
MUD CREEK 54.0
END DESCRIPTION:
XS GIS Cut Line= 2
      2721215.99     10058655.85      2719803.63     10057952.06
#Sta/Elev= 30
  4546.1 1825.62  4631.8 1821.09  4719.7 1817.71  4827.6 1813.76  4873.4 1812.37
  4935.5 1809.67    4964 1807.07    4992 1800.15  5033.7 1799.75  5036.5 1799.25
  5039.7 1799.75  5098.3 1804.99  5259.2 1804.68  5336.6 1804.01  5408.8 1810.59
  5437.7 1816.33    5462 1826.39  5478.8 1829.18  5568.3 1829.95  5590.7 1828.79
  5596.3 1826.74  5671.8 1827.94  5708.2 1824.05  5747.4 1828.68  5801.4 1831.26
  5839.8 1832.83  5934.5 1834.35  5984.6 1833.82  6038.4 1837.75  6124.1 1837.78
#Mann= 14 ,-1 , 0
  4546.1      .1       0  4631.8     .05       0  4719.7      .1       0
  4827.6     .16       0  4873.4      .1       0  4935.5     .16       0
  5033.7     .07       0  5039.7     .16       0  5259.2      .1       0
  5408.8     .16       0  5437.7      .1       0  5801.4     .16       0
  5839.8      .1       0  5934.5     .16       0
Bank Sta=5033.7,5039.7
XS Rating Curve= 0 ,0
Exp/Cntr=0.3,0.1

Type RM Length L Ch R = 1 ,25812   ,436,436,436
BEGIN DESCRIPTION:
MUD CREEK 53.0
END DESCRIPTION:
XS GIS Cut Line= 2
      2721230.33     10058584.01      2720689.34     10057411.06
#Sta/Elev= 30
  4295.1 1823.61  4363.4 1819.81  4483.4 1814.22  4529.3 1809.47    4612 1803.13
  4633.4 1801.87  4689.9 1799.31  4735.8 1798.59  4838.6 1798.89  4884.5 1796.63
  4936.3 1795.81  4981.9 1796.33  4996.3 1794.87  4999.1 1794.37  5002.3 1794.87
  5007.4 1796.41  5022.2 1801.34  5033.3 1807.33  5050.7 1811.24  5066.3 1812.65
  5073.7 1813.21  5096.6 1811.96  5125.1 1812.14  5225.6    1816  5311.5 1819.21
  5358.2 1821.01  5473.7 1825.43  5521.5 1828.25  5534.3 1829.63  5586.8 1831.78
#Mann= 13 ,-1 , 0
  4295.1     .05       0  4363.4      .1       0    4612     .16       0
  4633.4      .1       0  4936.3     .16       0  4996.3     .07       0
  5002.3     .16       0  5007.4      .1       0  5225.6     .05       0
  5311.5     .16       0  5358.2      .1       0  5521.5     .16       0
  5534.3      .1       0
Bank Sta=4996.3,5002.3
XS Rating Curve= 0 ,0
Exp/Cntr=0.3,0.1

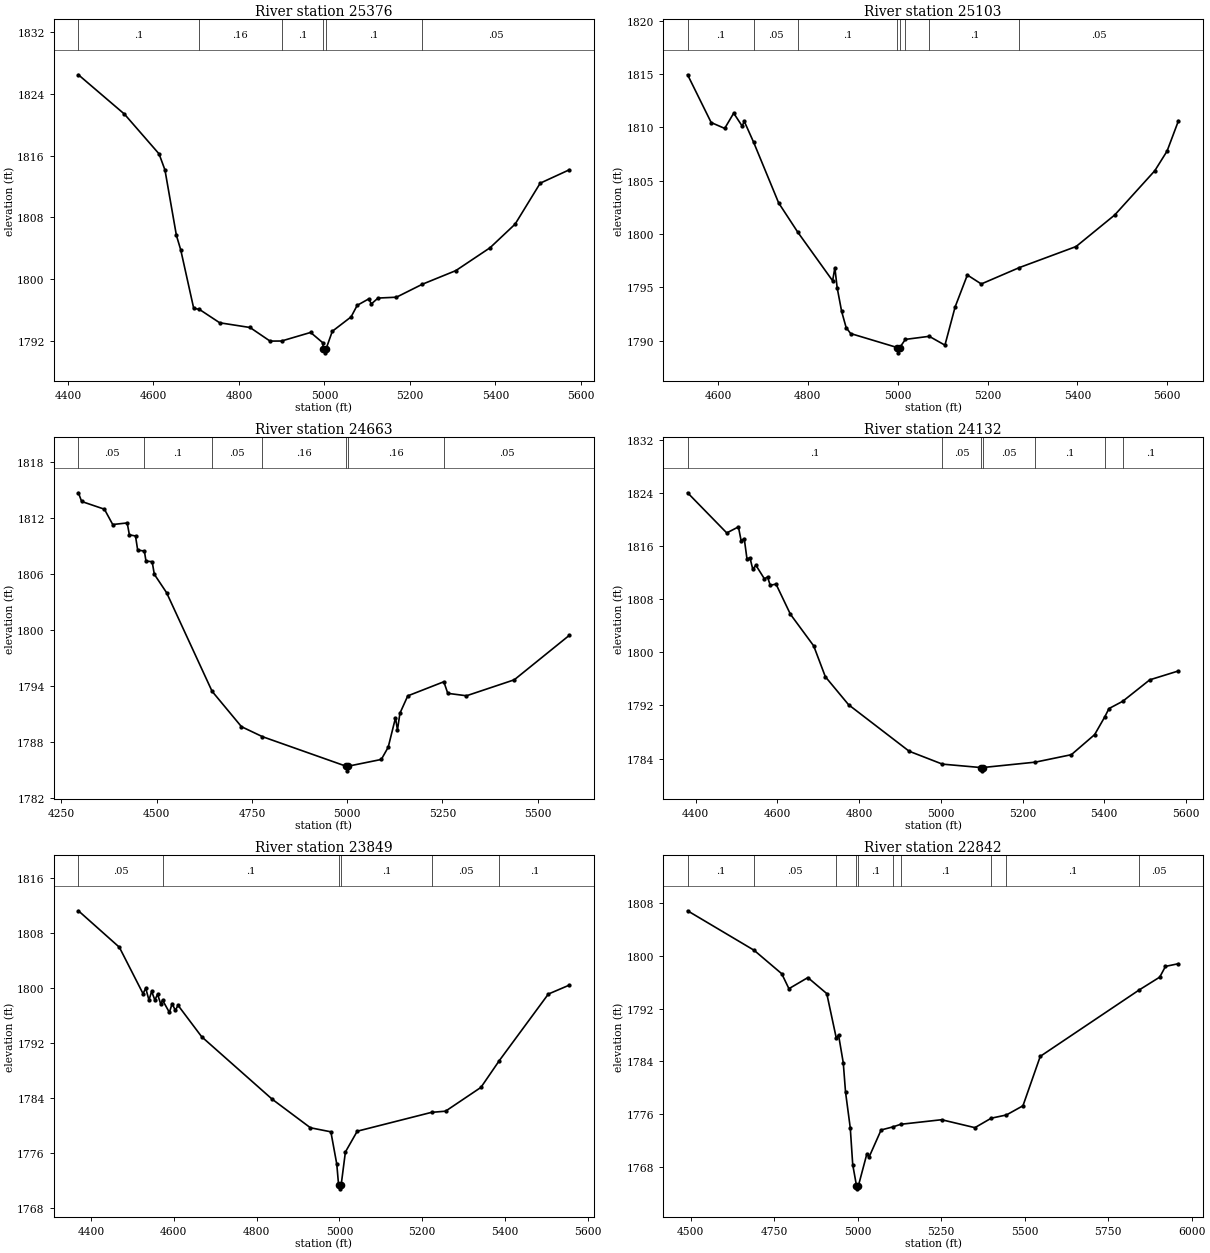
Type RM Length L Ch R = 1 ,25376   ,273,273,273
BEGIN DESCRIPTION:
MUD CREEK 52.0
END DESCRIPTION:
XS GIS Cut Line= 3
       2721445.8     10058450.01      2721340.46     10057803.63
      2720914.36     10057554.67
#Sta/Elev= 30
  4424.4 1826.47  4532.1 1821.38  4613.1 1816.23  4626.9 1814.15  4653.7 1805.68
  4663.8 1803.81  4694.2 1796.23    4707 1796.12    4755 1794.37  4825.9 1793.76
  4872.8    1792  4899.6 1792.01  4967.7 1793.12  4995.8  1791.8  4997.8 1790.98
  5000.6 1790.48  5003.8 1790.98  5018.4 1793.27  5062.3 1795.13  5076.7 1796.63
  5103.9 1797.47  5109.7 1796.81  5125.4 1797.57  5168.4 1797.68  5229.1 1799.36
  5307.3 1801.12  5387.4 1804.08  5446.1 1807.14  5504.8 1812.44  5572.8 1814.17
#Mann= 6 ,-1 , 0
  4424.4      .1       0    4707     .16       0  4899.6      .1       0
  4997.8     .07       0  5003.8      .1       0  5229.1     .05       0
Bank Sta=4997.8,5003.8
XS Rating Curve= 0 ,0
Exp/Cntr=0.3,0.1

Type RM Length L Ch R = 1 ,25103   ,440,440,440
BEGIN DESCRIPTION:
MUD CREEK 51.0
END DESCRIPTION:
XS GIS Cut Line= 3
       2721637.3     10058196.22      2721656.45     10057808.41
      2721053.34     10057444.64
#Sta/Elev= 30
  4532.3 1814.93  4584.8 1810.45  4614.9  1809.9  4634.9 1811.33  4653.6 1810.13
  4658.6 1810.55  4679.3  1808.6    4735 1802.91  4777.5 1800.17  4855.1 1795.61
  4860.1 1796.83  4865.2 1794.96  4875.2 1792.73  4885.2 1791.22  4895.2 1790.66
  4998.6 1789.35  5001.4 1788.85  5004.6 1789.35    5017 1790.11  5070.1  1790.4
  5105.1 1789.57  5127.8 1793.16    5155 1796.15    5186 1795.31    5271 1796.85
    5397 1798.82    5483 1801.78  5572.2 1805.93  5599.5 1807.77  5624.9 1810.62
#Mann= 8 ,-1 , 0
  4532.3      .1       0  4679.3     .05       0  4777.5      .1       0
  4998.6     .07       0  5004.6      .1       0    5017     .16       0
  5070.1      .1       0    5271     .05       0
Bank Sta=4998.6,5004.6
XS Rating Curve= 0 ,0
Exp/Cntr=0.3,0.1

Type RM Length L Ch R = 1 ,24663   ,531,531,531
BEGIN DESCRIPTION:
MUD CREEK 50.0
END DESCRIPTION:
XS GIS Cut Line= 3
      2721680.41       10058268.      2721967.65     10057741.39
      2721809.66     10057071.11
#Sta/Elev= 30
  4294.5 1814.68    4303 1813.75  4362.8 1812.92  4384.6 1811.28  4422.6 1811.45
  4428.3 1810.18  4444.4 1810.05  4450.1 1808.54  4467.7 1808.44  4471.9 1807.36
  4488.1  1807.3  4493.8 1805.95    4526 1803.98  4645.4 1793.42  4722.5 1789.63
  4777.6 1788.56  4996.8  1785.4  4999.6  1784.9  5002.8  1785.4  5089.6 1786.12
  5107.7 1787.43  5126.8 1790.57    5132 1789.28  5138.5 1791.07  5159.1 1792.93
  5253.7 1794.44  5264.1  1793.2  5313.2 1792.94  5438.6 1794.65    5583 1799.41
#Mann= 7 ,-1 , 0
  4294.5     .05       0  4467.7      .1       0  4645.4     .05       0
  4777.6     .16       0  4996.8     .07       0  5002.8     .16       0
  5253.7     .05       0
Bank Sta=4996.8,5002.8
XS Rating Curve= 0 ,0
Exp/Cntr=0.3,0.1

Type RM Length L Ch R = 1 ,24132   ,283,283,283
BEGIN DESCRIPTION:
MUD CREEK 49.0
END DESCRIPTION:
XS GIS Cut Line= 2
       2722815.1      10057942.5       2722029.9     10057032.81
#Sta/Elev= 30
    4380 1823.99  4475.9 1817.95  4504.4 1818.86    4511 1816.81  4518.7 1817.09
  4525.3 1814.08  4532.9 1814.16  4539.5  1812.5  4547.2 1813.09    4568 1811.05
  4575.7 1811.32  4582.3 1810.08  4596.5 1810.25  4631.7 1805.72  4688.7 1800.96
  4717.2 1796.32  4774.2  1792.1  4922.4 1785.11  5003.7 1783.17  5097.1 1782.66
  5099.8 1782.16  5103.1 1782.66  5231.6 1783.47  5319.5 1784.59  5376.5 1787.61
  5401.2 1790.27  5411.6 1791.53  5445.4 1792.63  5511.4 1795.85  5581.7 1797.19
#Mann= 7 ,-1 , 0
    4380      .1       0  5003.7     .05       0  5097.1     .07       0
  5103.1     .05       0  5231.6      .1       0  5401.2     .16       0
  5445.4      .1       0
Bank Sta=5097.1,5103.1
XS Rating Curve= 0 ,0
Exp/Cntr=0.3,0.1

Type RM Length L Ch R = 1 ,23849   ,1007,1007,1007
BEGIN DESCRIPTION:
MUD CREEK 48.0
END DESCRIPTION:
XS GIS Cut Line= 2
      2723016.14     10057755.72       2722250.1     10056850.83
#Sta/Elev= 30
  4369.4  1811.2  4468.3  1805.9  4525.5 1799.15    4532 1799.94  4539.8 1798.22
  4546.3 1799.47  4554.1 1798.23  4560.6 1799.06  4568.4 1797.62  4572.6 1798.21
  4589.2 1796.42  4595.8  1797.7  4603.5 1796.71    4610 1797.46  4667.2 1792.88
  4837.5  1783.8  4929.8 1779.65  4979.2 1779.06  4993.5 1774.35  4997.9 1771.27
  5000.7 1770.77  5003.9 1771.27  5014.3 1776.13  5042.9 1779.15  5222.3 1781.89
  5256.1 1782.06  5341.6 1785.52  5386.2 1789.43  5504.4 1799.09    5555 1800.39
#Mann= 6 ,-1 , 0
  4369.4     .05       0  4572.6      .1       0  4997.9     .07       0
  5003.9      .1       0  5222.3     .05       0  5386.2      .1       0
Bank Sta=4997.9,5003.9
XS Rating Curve= 0 ,0
Exp/Cntr=0.3,0.1

Type RM Length L Ch R = 1 ,22842   ,522,522,522
BEGIN DESCRIPTION:
MUD CREEK 47.0
END DESCRIPTION:
XS GIS Cut Line= 3
      2723633.75     10057387.07      2723155.01     10056941.84
      2722417.73     10056592.35
#Sta/Elev= 30
  4490.9 1806.78    4690 1800.81  4772.8 1797.26  4794.3    1795    4851 1796.68
  4907.6 1794.26  4936.1 1787.53  4942.8 1788.01    4957  1783.8  4963.8 1779.36
    4978 1773.94  4985.3  1768.4  4996.5 1765.24  4999.2 1764.74  5002.5 1765.24
  5027.8 1770.05  5034.7 1769.59  5070.3 1773.64  5105.2  1774.1  5129.2  1774.5
  5251.5 1775.19  5351.1 1773.99    5400 1775.42  5445.5 1775.91    5495  1777.3
  5546.8 1784.77    5843 1794.81  5904.5 1796.75  5921.7 1798.37  5960.6 1798.78
#Mann= 10 ,-1 , 0
  4490.9      .1       0    4690     .05       0  4936.1      .1       0
  4996.5     .07       0  5002.5      .1       0  5105.2     .16       0
  5129.2      .1       0    5400     .16       0  5445.5      .1       0
    5843     .05       0
Bank Sta=4996.5,5002.5
XS Rating Curve= 0 ,0
Exp/Cntr=0.3,0.1

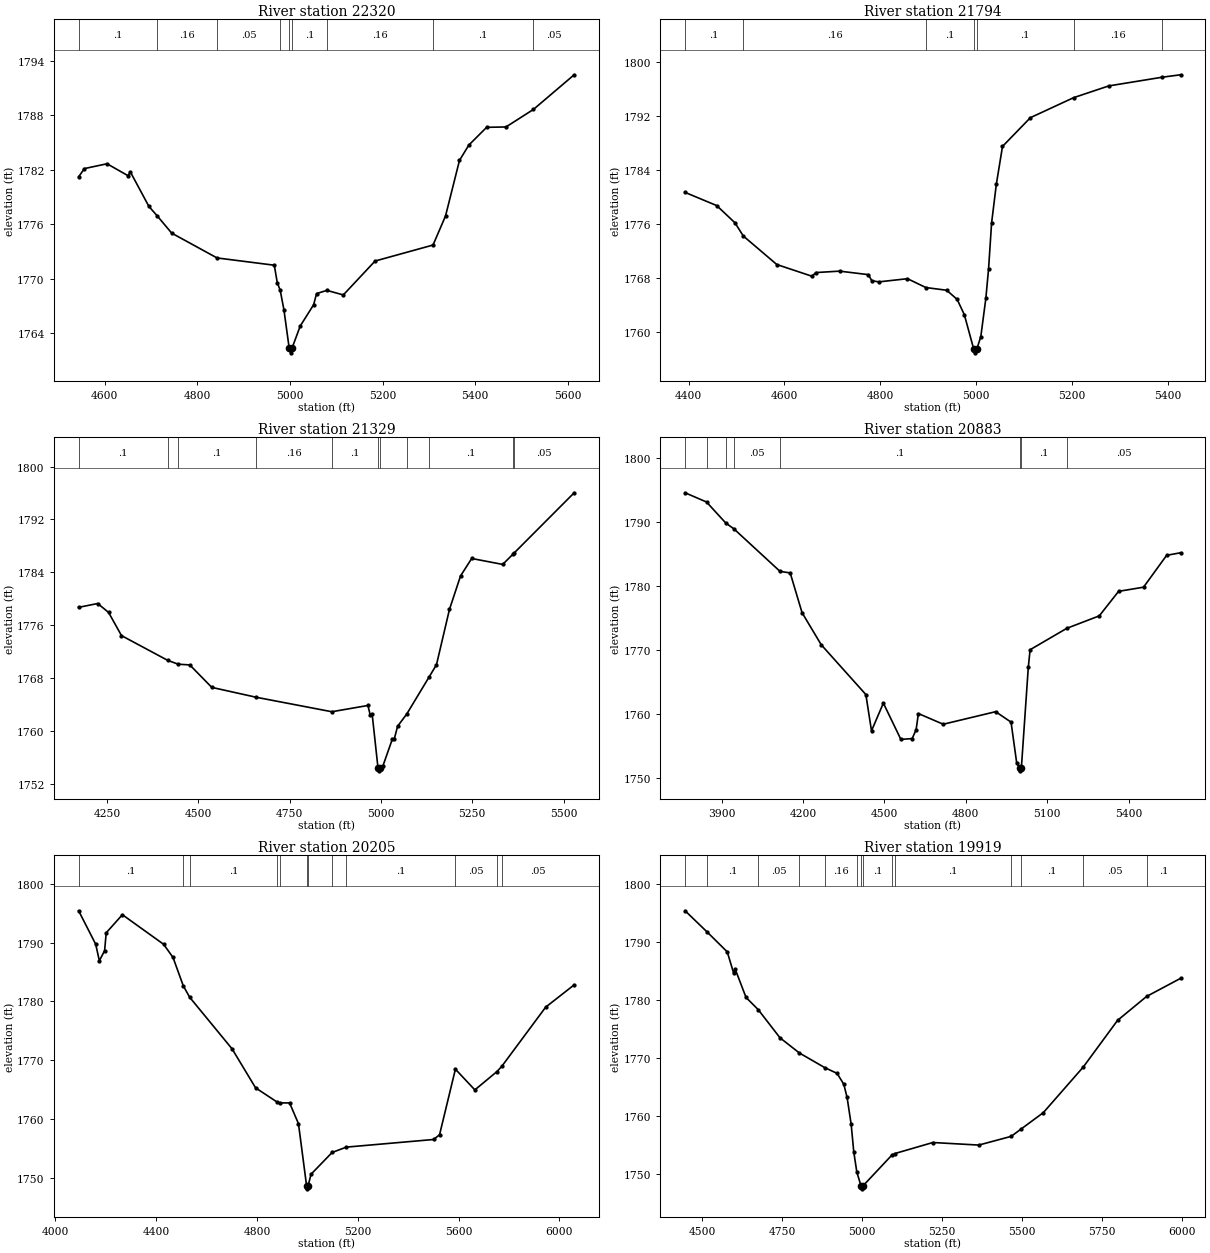
Type RM Length L Ch R = 1 ,22320   ,526,526,526
BEGIN DESCRIPTION:
MUD CREEK 46.0
END DESCRIPTION:
XS GIS Cut Line= 4
      2723619.45     10056467.85      2723245.98     10056506.15
      2723107.13     10056616.27      2722591.77     10056573.32
#Sta/Elev= 30
  4543.9 1781.21  4556.3 1782.12  4605.2 1782.65  4650.5 1781.34  4655.5 1781.76
  4695.7 1777.95  4713.7 1776.91  4744.8 1775.02  4842.7 1772.29  4966.3 1771.49
  4972.7 1769.58  4979.1 1768.72  4987.1 1766.59  4998.5 1762.35  5001.3 1761.85
  5004.5 1762.35  5022.3  1764.8  5051.2 1767.14  5057.6 1768.37  5079.9 1768.72
  5115.3 1768.22  5183.9 1771.95    5309 1773.71    5336 1776.91  5366.1 1783.02
  5386.2  1784.7  5424.7 1786.66  5466.5  1786.7  5525.8 1788.63  5613.7 1792.44
#Mann= 9 ,-1 , 0
  4543.9      .1       0  4713.7     .16       0  4842.7     .05       0
  4979.1      .1       0  4998.5     .07       0  5004.5      .1       0
  5079.9     .16       0    5309      .1       0  5525.8     .05       0
Bank Sta=4998.5,5004.5
XS Rating Curve= 0 ,0
Exp/Cntr=0.3,0.1

Type RM Length L Ch R = 1 ,21794   ,465,465,465
BEGIN DESCRIPTION:
MUD CREEK 45.0
END DESCRIPTION:
XS GIS Cut Line= 2
      2723581.14     10056410.41      2722671.42     10055917.25
#Sta/Elev= 30
  4392.6 1780.62  4458.6 1778.67  4496.7 1776.12  4514.2 1774.16  4584.1 1769.94
  4657.3 1768.21  4665.9 1768.75  4715.3 1768.96  4775.3 1768.44  4782.4 1767.54
  4797.1 1767.37    4857 1767.84  4895.4 1766.53  4938.8 1766.13  4960.7 1764.78
  4975.8 1762.49  4995.5 1757.36  4998.3 1756.86  5001.5 1757.36  5010.1 1759.25
  5020.6 1764.91  5026.3 1769.28  5032.6 1776.07  5042.5 1781.81  5055.4 1787.43
  5113.7 1791.69  5203.9 1794.65  5277.3 1796.39  5388.9 1797.68  5427.4 1798.04
#Mann= 7 ,-1 , 0
  4392.6      .1       0  4514.2     .16       0  4895.4      .1       0
  4995.5     .07       0  5001.5      .1       0  5203.9     .16       0
  5388.9      .1       0
Bank Sta=4995.5,5001.5
XS Rating Curve= 0 ,0
Exp/Cntr=0.3,0.1

Type RM Length L Ch R = 1 ,21329   ,446,446,446
BEGIN DESCRIPTION:
MUD CREEK 44.0
END DESCRIPTION:
XS GIS Cut Line= 3
      2723624.21     10056352.96      2723380.03     10055730.54
      2722701.85     10055615.92
#Sta/Elev= 30
  4172.8 1778.69    4225 1779.27  4254.8 1777.92  4290.1 1774.41  4416.3 1770.67
  4445.3 1770.08  4477.1 1769.97  4537.2 1766.57  4658.2 1765.08  4865.9 1762.88
  4964.7 1763.83    4971 1762.36  4976.1 1762.59  4992.1 1754.43  4994.9 1753.93
  4998.1 1754.43  5005.3 1754.61  5031.4 1758.72  5036.5 1758.69  5045.8 1760.67
    5071 1762.54  5132.2 1768.15  5152.3    1770  5187.8 1778.37  5218.2 1783.45
  5248.7 1786.09  5333.6 1785.19  5362.5 1786.79  5363.6 1786.85  5529.2 1796.04
#Mann= 11 ,-1 , 0
  4172.8      .1       0  4416.3     .16       0  4445.3      .1       0
  4658.2     .16       0  4865.9      .1       0  4992.1     .07       0
  4998.1      .1       0    5071     .16       0  5132.2      .1       0
  5362.5     .16       0  5363.6     .05       0
Bank Sta=4992.1,4998.1
XS Rating Curve= 0 ,0
Exp/Cntr=0.3,0.1

Type RM Length L Ch R = 1 ,20883   ,678,678,678
BEGIN DESCRIPTION:
MUD CREEK 43.0
END DESCRIPTION:
XS GIS Cut Line= 3
      2724375.86      10056089.6      2723480.57     10055414.55
      2722953.93     10054945.35
#Sta/Elev= 30
  3765.5 1794.59  3844.4 1793.15    3916 1789.84  3944.7 1788.98  4115.4 1782.31
  4152.9 1782.07  4196.6 1775.86  4267.4 1770.84  4431.8 1763.07  4452.6  1757.4
  4496.3 1761.73  4560.9 1756.06  4602.5 1756.19  4617.1 1757.58  4625.4  1760.1
    4717 1758.43  4910.1 1760.39    4967 1758.76  4987.9 1752.35  4999.1 1751.65
  5001.8 1751.15  5005.1 1751.65  5030.5  1767.3  5037.2 1770.07  5172.7 1773.42
  5292.2 1775.36  5363.3 1779.19  5455.3 1779.84  5540.5 1784.82  5592.1 1785.22
#Mann= 8 ,-1 , 0
  3765.5      .1       0  3844.4     .05       0    3916      .1       0
  3944.7     .05       0  4115.4      .1       0  4999.1     .07       0
  5005.1      .1       0  5172.7     .05       0
Bank Sta=4999.1,5005.1
XS Rating Curve= 0 ,0
Exp/Cntr=0.3,0.1

Type RM Length L Ch R = 1 ,20205   ,286,286,286
BEGIN DESCRIPTION:
MUD CREEK 42.0
END DESCRIPTION:
XS GIS Cut Line= 3
      2724744.52     10055692.23      2723925.83     10055055.47
      2723006.62     10054921.42
#Sta/Elev= 30
  4092.4  1795.4  4160.2  1789.7  4174.6 1786.89  4195.5 1788.61  4201.8 1791.65
    4266 1794.73  4429.8 1789.69  4466.9 1787.45  4507.6 1782.63  4533.1 1780.67
  4701.3 1771.89  4794.5 1765.26  4879.6 1762.85  4892.4 1762.69  4929.3  1762.7
  4964.6 1759.17  4996.9 1748.57  4999.7 1748.07  5002.9 1748.57  5014.4 1750.55
  5098.1 1754.26  5154.4 1755.17  5500.8 1756.47  5524.4 1757.28  5587.3 1768.44
  5664.4 1764.91  5752.1 1768.03  5771.6 1768.94  5945.5    1779  6058.5 1782.79
#Mann= 12 ,-1 , 0
  4092.4      .1       0  4507.6     .05       0  4533.1      .1       0
  4879.6     .16       0  4892.4      .1       0  4996.9     .07       0
  5002.9      .1       0  5098.1     .16       0  5154.4      .1       0
  5587.3     .05       0  5752.1      .1       0  5771.6     .05       0
Bank Sta=4996.9,5002.9
XS Rating Curve= 0 ,0
Exp/Cntr=0.3,0.1

Type RM Length L Ch R = 1 ,19919   ,419,419,419
BEGIN DESCRIPTION:
MUD CREEK 41.0
END DESCRIPTION:
XS GIS Cut Line= 3
      2724505.11     10054715.55      2723758.26     10054930.99
      2722992.82     10054830.53
#Sta/Elev= 30
  4446.1 1795.37  4515.2 1791.71  4577.9  1788.3  4597.7 1784.68  4602.9 1785.31
  4636.6 1780.46  4674.9 1778.35  4742.7 1773.52  4803.5  1770.9  4882.9 1768.38
  4921.4 1767.39  4942.2 1765.53  4952.6 1763.25  4965.4  1758.6  4973.4 1753.91
    4983 1750.42  4996.1 1748.03  4998.8 1747.53  5002.1 1748.03  5092.7 1753.34
  5102.4 1753.61  5220.7  1755.5  5364.4 1755.06  5465.6 1756.56  5496.6 1757.82
  5566.1 1760.64    5691 1768.49  5798.1 1776.51  5888.9 1780.63  5995.4 1783.75
#Mann= 14 ,-1 , 0
  4446.1     .05       0  4515.2      .1       0  4674.9     .05       0
  4803.5      .1       0  4882.9     .16       0    4983      .1       0
  4996.1     .07       0  5002.1      .1       0  5092.7     .16       0
  5102.4      .1       0  5465.6     .05       0  5496.6      .1       0
    5691     .05       0  5888.9      .1       0
Bank Sta=4996.1,5002.1
XS Rating Curve= 0 ,0
Exp/Cntr=0.3,0.1