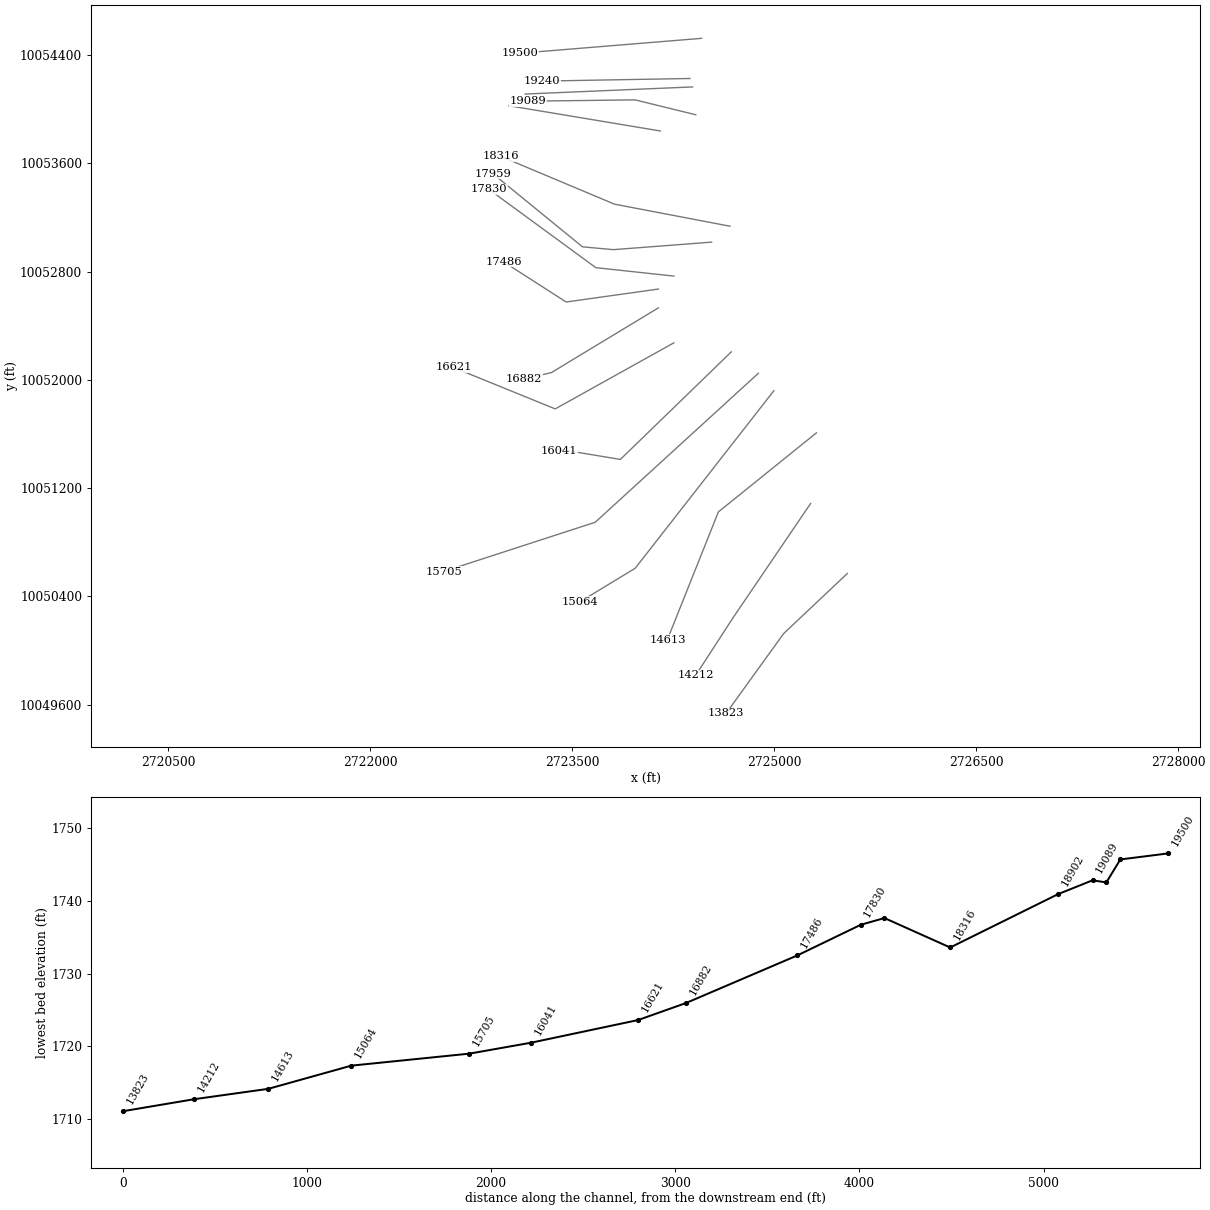
HEC-RAS study MUD CREEK.prj: MUD CREEK Base Level Engineering

--- MUD CREEK.g01 (geometry) --- (continued)

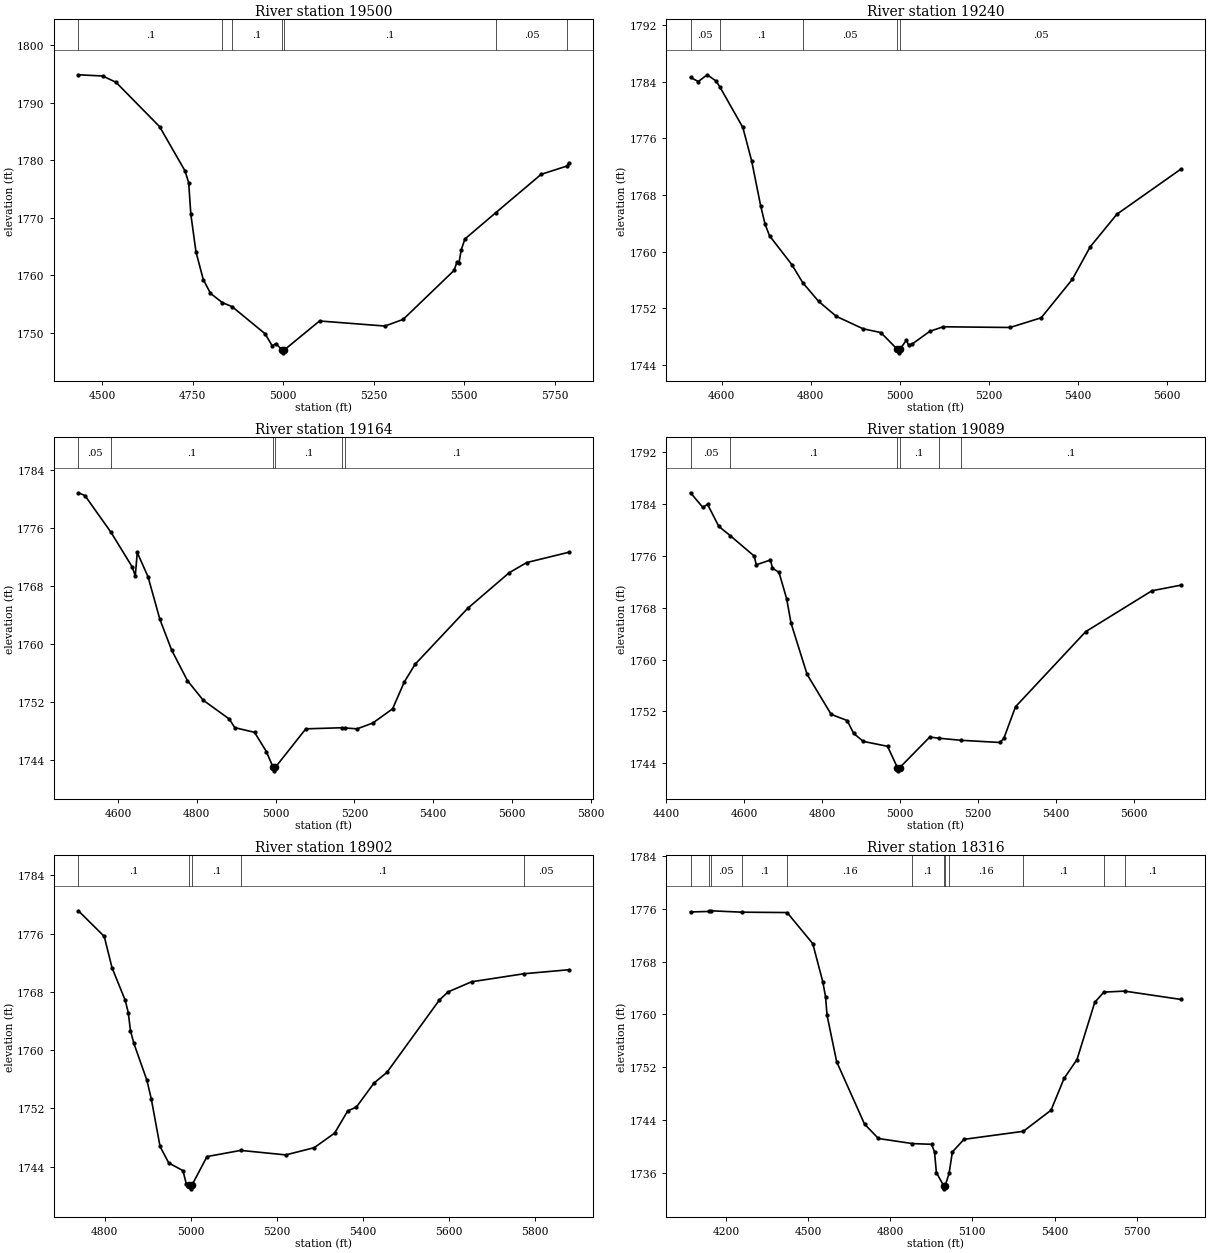
Type RM Length L Ch R = 1 ,19500   ,260,260,260
BEGIN DESCRIPTION:
MUD CREEK 40.0
END DESCRIPTION:
XS GIS Cut Line= 2
      2724462.08     10054524.03      2723112.67     10054413.98
#Sta/Elev= 30
  4434.5 1794.89  4501.5 1794.68  4538.5 1793.58  4658.9 1785.86  4729.1 1778.16
  4739.1  1776.1    4745 1770.63  4759.2  1764.1  4779.3 1759.29  4799.3 1756.88
  4832.3 1755.26  4858.8 1754.58  4949.8 1749.87  4969.9 1747.75  4979.9 1748.15
    4997 1747.04  4999.7 1746.54    5003 1747.04  5100.3 1752.08  5280.9  1751.2
  5331.1 1752.35  5471.6 1760.86  5480.2 1762.36  5485.2 1762.12  5491.6 1764.45
  5501.7 1766.34  5586.6 1770.89  5712.3 1777.58  5783.9 1779.03  5788.4 1779.57
#Mann= 7 ,-1 , 0
  4434.5      .1       0  4832.3     .16       0  4858.8      .1       0
    4997     .07       0    5003      .1       0  5586.6     .05       0
  5783.9      .1       0
Bank Sta=4997,5003
XS Rating Curve= 0 ,0
Exp/Cntr=0.3,0.1

Type RM Length L Ch R = 1 ,19240   ,76,76,76
BEGIN DESCRIPTION:
Mapping XS 1b0fdd06
END DESCRIPTION:
XS GIS Cut Line= 2
      2724375.93     10054227.19      2723274.69     10054208.04
#Sta/Elev= 30
  4530.1 1784.59  4547.6 1784.02  4567.6 1784.97  4587.6 1784.08  4596.6 1783.19
  4647.6 1777.53  4667.6 1772.76  4687.6 1766.47  4697.6 1763.86  4707.6 1762.23
  4757.6 1758.17  4782.3  1755.6  4817.6 1752.99  4857.6 1750.86  4917.6 1749.11
  4957.6 1748.57  4994.6 1746.21  4997.4 1745.71  5000.6 1746.21  5014.7 1747.49
  5019.7 1746.85  5027.6 1746.94  5067.6 1748.75  5097.6 1749.39  5247.7 1749.29
  5317.7 1750.66  5387.7 1756.09  5427.7 1760.67  5487.7 1765.28  5631.5 1771.65
#Mann= 5 ,-1 , 0
  4530.1     .05       0  4596.6      .1       0  4782.3     .05       0
  4994.6     .04       0  5000.6     .05       0
Bank Sta=4994.6,5000.6
XS Rating Curve= 0 ,0
Exp/Cntr=0.3,0.1

Type RM Length L Ch R = 1 ,19164   ,75,75,75
BEGIN DESCRIPTION:
Mapping XS 46361d9a
END DESCRIPTION:
XS GIS Cut Line= 2
      2724395.04     10054164.95      2723151.85     10054112.36
#Sta/Elev= 30
  4499.5 1780.88  4516.1  1780.5  4582.4 1775.42  4636.2 1770.65  4643.9  1769.4
  4648.9 1772.65  4676.2 1769.31  4706.3 1763.44  4736.3 1759.18  4776.3 1754.98
  4816.4 1752.28  4882.3  1749.7  4896.4  1748.5  4946.5 1747.86  4976.5 1745.21
  4993.5 1743.05  4996.3 1742.55  4999.5 1743.05  5076.6 1748.34  5168.2 1748.49
  5175.4 1748.46  5206.7 1748.34  5246.7 1749.14  5296.8  1751.1  5326.8 1754.83
  5354.1 1757.25    5487 1764.93  5592.5 1769.85  5637.1 1771.26  5743.8 1772.68
#Mann= 6 ,-1 , 0
  4499.5     .05       0  4582.4      .1       0  4993.5     .07       0
  4999.5      .1       0  5168.2     .16       0  5175.4      .1       0
Bank Sta=4993.5,4999.5
XS Rating Curve= 0 ,0
Exp/Cntr=0.3,0.1

Type RM Length L Ch R = 1 ,19089   ,187,187,187
BEGIN DESCRIPTION:
MUD CREEK 39.0
END DESCRIPTION:
XS GIS Cut Line= 3
      2724418.97     10053959.08      2723968.92      10054069.2
      2723174.21     10054059.62
#Sta/Elev= 30
  4462.3  1785.7  4493.7 1783.46    4506 1783.91  4534.9 1780.52  4564.2 1779.09
  4625.8 1775.94  4630.9  1774.6  4667.4 1775.34  4672.5 1774.08  4689.3 1773.43
    4709 1769.34  4720.2  1765.6  4761.4  1757.7  4823.1 1751.55  4864.3 1750.59
  4880.7 1748.62  4905.5 1747.38  4967.7 1746.62  4993.1 1743.34  4995.8 1742.84
  4999.1 1743.34  5076.1 1748.05  5099.2 1747.87  5155.8 1747.55  5256.1 1747.21
  5266.1 1747.84  5296.1 1752.72  5476.1 1764.29  5646.1  1770.6  5720.4 1771.46
#Mann= 6 ,-1 , 0
  4462.3     .05       0  4564.2      .1       0  4993.1     .07       0
  4999.1      .1       0  5099.2     .16       0  5155.8      .1       0
Bank Sta=4993.1,4999.1
XS Rating Curve= 0 ,0
Exp/Cntr=0.3,0.1

Type RM Length L Ch R = 1 ,18902   ,586,586,586
BEGIN DESCRIPTION:
MUD CREEK 38.0
END DESCRIPTION:
XS GIS Cut Line= 2
      2724155.65     10053839.39      2723032.02     10054025.86
#Sta/Elev= 30
  4738.6 1779.13  4798.7 1775.61  4816.8  1771.3  4847.3 1766.85  4854.5 1765.15
  4859.6 1762.67  4867.5 1760.92  4897.9 1755.83  4908.1 1753.25  4928.3 1746.76
  4948.6 1744.49  4981.5 1743.44  4989.2 1741.64  4996.3 1741.44  4999.1 1740.94
  5002.3 1741.44  5037.4 1745.37  5115.8 1746.22  5220.2  1745.6  5286.3 1746.59
  5333.8 1748.59  5364.2 1751.64  5384.5 1752.18    5425 1755.45  5455.5 1756.95
  5577.1 1766.87  5597.4 1767.99    5652 1769.38  5773.4 1770.48  5877.6 1771.03
#Mann= 5 ,-1 , 0
  4738.6      .1       0  4996.3     .07       0  5002.3      .1       0
  5115.8      .1       0  5773.4     .05       0
Bank Sta=4996.3,5002.3
XS Rating Curve= 0 ,0
Exp/Cntr=0.3,0.1

Type RM Length L Ch R = 1 ,18316   ,357,357,357
BEGIN DESCRIPTION:
MUD CREEK 37.0
END DESCRIPTION:
XS GIS Cut Line= 3
      2724672.76     10053135.58      2723815.72     10053298.37
      2722968.27     10053652.68
#Sta/Elev= 30
  4070.7 1775.51  4138.9 1775.59  4143.7 1775.69  4257.9 1775.48  4423.5 1775.42
  4517.1 1770.72  4553.5 1764.98  4563.7 1762.71  4569.3 1759.87  4604.4 1752.84
  4706.2  1743.4    4757 1741.22  4881.3 1740.45  4950.9 1740.34  4961.8 1739.19
  4968.6 1736.06  4994.8  1734.1  4997.5  1733.6  5000.8  1734.1  5014.9 1735.93
    5027 1739.18  5069.2 1741.09  5286.2 1742.31  5387.3  1745.5  5434.9 1750.31
    5482 1753.16  5547.1 1761.84  5580.4 1763.38    5656 1763.53  5861.6 1762.27
#Mann= 12 ,-1 , 0
  4070.7     .05       0  4138.9      .1       0  4143.7     .05       0
  4257.9      .1       0  4423.5     .16       0  4881.3      .1       0
  4994.8     .07       0  5000.8      .1       0  5014.9     .16       0
  5286.2      .1       0  5580.4     .05       0    5656      .1       0
Bank Sta=4994.8,5000.8
XS Rating Curve= 0 ,0
Exp/Cntr=0.3,0.1

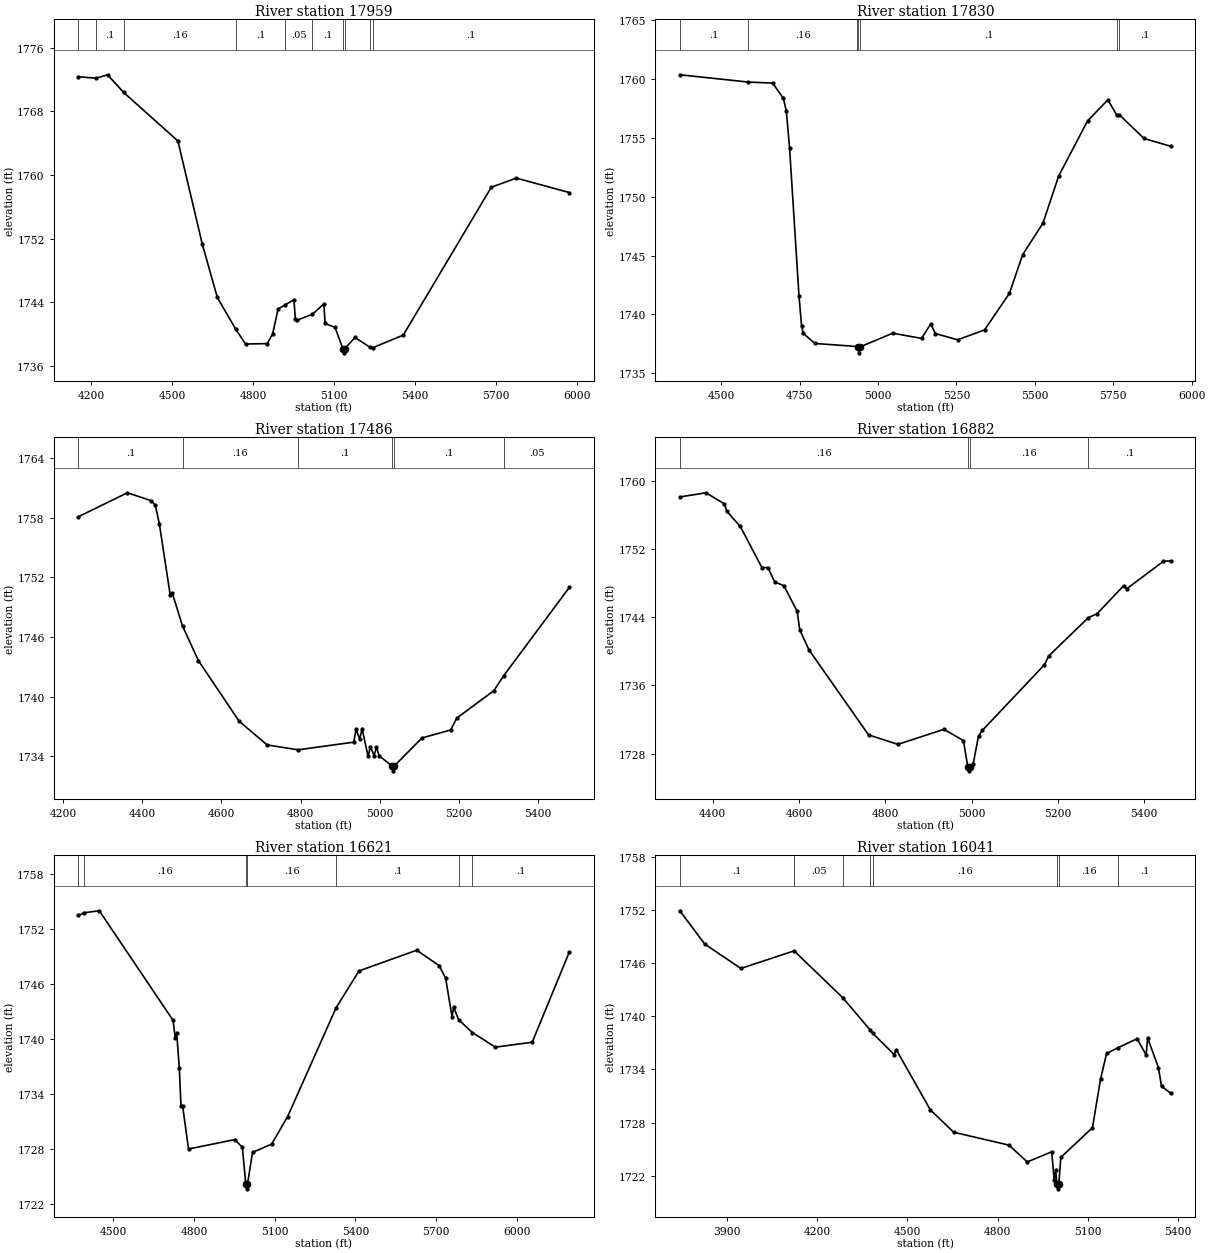
Type RM Length L Ch R = 1 ,17959   ,129,129,129
BEGIN DESCRIPTION:
Mapping XS 9b13189e
END DESCRIPTION:
XS GIS Cut Line= 4
      2724536.03     10053017.87      2723806.88     10052962.32
      2723577.72     10052983.15      2722912.25     10053523.84
#Sta/Elev= 30
  4153.2 1772.36  4219.5 1772.18  4261.1 1772.61  4320.5  1770.4  4521.8 1764.29
  4612.1 1751.32  4667.8 1744.61  4735.9 1740.63  4772.5 1738.76  4852.8 1738.81
  4872.8 1740.06  4892.9 1743.16  4919.1 1743.68  4951.7 1744.34  4956.7 1741.93
  4963.2 1741.75  5020.2  1742.5  5062.2  1743.8  5067.2 1741.34  5103.8 1740.85
  5133.1 1738.15  5135.9 1737.65  5139.1 1738.15    5178 1739.58  5232.4 1738.37
  5244.8 1738.31  5356.6 1739.88  5682.7 1758.47  5775.4 1759.62    5972  1757.8
#Mann= 10 ,-1 , 0
  4153.2     .05       0  4219.5      .1       0  4320.5     .16       0
  4735.9      .1       0  4919.1     .05       0  5020.2      .1       0
  5133.1    .035       0  5139.1      .1       0  5232.4     .05       0
  5244.8      .1       0
Bank Sta=5133.1,5139.1
XS Rating Curve= 0 ,0
Exp/Cntr=0.3,0.1

Type RM Length L Ch R = 1 ,17830   ,344,344,344
BEGIN DESCRIPTION:
MUD CREEK 36.0
END DESCRIPTION:
XS GIS Cut Line= 3
      2724256.16     10052766.94      2723676.87     10052829.18
      2722882.77     10053408.01
#Sta/Elev= 30
  4368.3 1760.38  4586.9 1759.76  4664.3 1759.67  4697.9 1758.39  4707.9 1757.29
    4718 1754.19  4748.2 1741.54  4756.4 1739.01  4761.4 1738.39  4798.5 1737.52
    4932 1737.26  4936.3 1737.22    4939 1736.72  4942.3 1737.22  5046.9 1738.39
  5138.8 1737.95  5168.2 1739.18  5182.9 1738.36  5253.9 1737.83  5339.7 1738.67
  5419.2 1741.79    5461 1745.06  5525.9 1747.76  5576.1 1751.77    5668 1756.45
  5732.9 1758.25  5761.8 1756.92  5769.8 1756.97    5848 1754.96  5933.6 1754.29
#Mann= 7 ,-1 , 0
  4368.3      .1       0  4586.9     .16       0    4932      .1       0
  4936.3     .07       0  4942.3      .1       0  5761.8     .16       0
  5769.8      .1       0
Bank Sta=4936.3,4942.3
XS Rating Curve= 0 ,0
Exp/Cntr=0.3,0.1

Type RM Length L Ch R = 1 ,17486   ,604,604,604
BEGIN DESCRIPTION:
MUD CREEK 35.0
END DESCRIPTION:
XS GIS Cut Line= 3
      2724141.27     10052671.18      2723456.64     10052575.43
      2722992.88     10052871.85
#Sta/Elev= 30
  4238.3 1758.12  4362.3 1760.53  4422.9 1759.73    4433 1759.25  4443.1 1757.38
  4470.4 1750.25  4475.5 1750.45  4501.9 1747.07  4541.9 1743.61    4645  1737.5
  4715.7 1735.12  4793.7 1734.63  4934.6  1735.4  4940.5 1736.68  4949.8 1735.71
  4955.7 1736.76  4970.9 1733.98  4976.9 1734.95  4986.1 1734.03  4992.1 1734.92
  4998.6 1734.03  5031.4 1733.01  5034.1 1732.51  5037.4 1733.01  5107.1 1735.82
  5179.9 1736.63  5195.1 1737.82    5289 1740.59  5313.4 1742.07    5480    1751
#Mann= 6 ,-1 , 0
  4238.3      .1       0  4501.9     .16       0  4793.7      .1       0
  5031.4     .07       0  5037.4      .1       0  5313.4     .05       0
Bank Sta=5031.4,5037.4
XS Rating Curve= 0 ,0
Exp/Cntr=0.3,0.1

Type RM Length L Ch R = 1 ,16882   ,261,261,261
BEGIN DESCRIPTION:
MUD CREEK 34.0
END DESCRIPTION:
XS GIS Cut Line= 3
      2724141.29     10052532.34      2723346.52     10052053.56
      2723142.02     10052006.01
#Sta/Elev= 30
    4324 1758.16  4384.5 1758.65  4427.2 1757.35  4433.1 1756.46  4464.1 1754.69
  4514.1 1749.86  4528.2 1749.86  4543.7 1748.17  4565.1 1747.73  4595.8 1744.72
    4602 1742.53  4623.3 1740.18  4761.2  1730.2  4829.2 1729.08    4936 1730.85
  4981.1 1729.53  4991.2 1726.47    4994 1725.97  4997.2 1726.47  5003.9 1726.82
  5016.1 1730.07  5025.3 1730.74    5169 1738.44  5178.7 1739.46  5270.5 1743.97
  5290.9 1744.44  5352.5 1747.73  5359.6 1747.37  5444.8  1750.6  5461.8 1750.66
#Mann= 4 ,-1 , 0
    4324     .16       0  4991.2     .07       0  4997.2     .16       0
  5270.5      .1       0
Bank Sta=4991.2,4997.2
XS Rating Curve= 0 ,0
Exp/Cntr=0.3,0.1

Type RM Length L Ch R = 1 ,16621   ,580,580,580
BEGIN DESCRIPTION:
MUD CREEK 33.0
END DESCRIPTION:
XS GIS Cut Line= 3
      2724256.17     10052273.79      2723375.24     10051785.45
      2722618.77     10052091.87
#Sta/Elev= 30
  4371.1 1753.49  4392.7 1753.79  4448.8    1754  4722.9 1742.02  4730.4 1740.14
  4736.1 1740.69  4745.8 1736.81  4752.1  1732.7  4757.9 1732.72  4780.1 1727.97
  4951.6    1729  4979.9 1728.17    4993 1724.12  4995.7 1723.62    4999 1724.12
  5017.7  1727.6  5088.8 1728.51  5148.2 1731.52  5328.1  1743.4  5413.2 1747.43
  5627.6 1749.69  5710.7 1748.01  5734.8 1746.65  5758.9 1742.39  5764.3 1743.47
  5783.4 1742.09  5834.5 1740.69  5919.7  1739.1  6056.5 1739.64  6194.5 1749.51
#Mann= 7 ,-1 , 0
  4371.1      .1       0  4392.7     .16       0    4993     .07       0
    4999     .16       0  5328.1      .1       0  5783.4     .16       0
  5834.5      .1       0
Bank Sta=4993,4999
XS Rating Curve= 0 ,0
Exp/Cntr=0.3,0.1

Type RM Length L Ch R = 1 ,16041   ,336,336,336
BEGIN DESCRIPTION:
MUD CREEK 32.0
END DESCRIPTION:
XS GIS Cut Line= 4
      2724682.29     10052206.77       2723858.8     10051412.01
       2723394.4     10051488.61      2723403.69     10051474.66
#Sta/Elev= 30
  3743.4 1751.94  3826.1 1748.18  3946.2 1745.42  4123.1 1747.41  4285.6 1742.09
  4374.8 1738.51  4384.2 1738.11  4455.6 1735.69  4462.5 1736.25  4575.7 1729.45
  4653.4 1726.91  4837.3 1725.45  4898.3 1723.55  4979.4  1724.7  4987.5 1721.54
  4992.6 1722.61  4996.7 1721.01  4999.4 1720.51  5002.7 1721.01  5009.8 1724.07
  5114.9 1727.42  5141.6 1732.91  5161.8 1735.81  5200.2 1736.47  5263.2 1737.48
  5293.2 1735.64  5298.2 1737.57  5334.1 1734.21  5344.3  1732.1  5375.3 1731.31
#Mann= 8 ,-1 , 0
  3743.4      .1       0  4123.1     .05       0  4285.6      .1       0
  4374.8     .05       0  4384.2     .16       0  4996.7     .07       0
  5002.7     .16       0  5200.2      .1       0
Bank Sta=4996.7,5002.7
XS Rating Curve= 0 ,0
Exp/Cntr=0.3,0.1

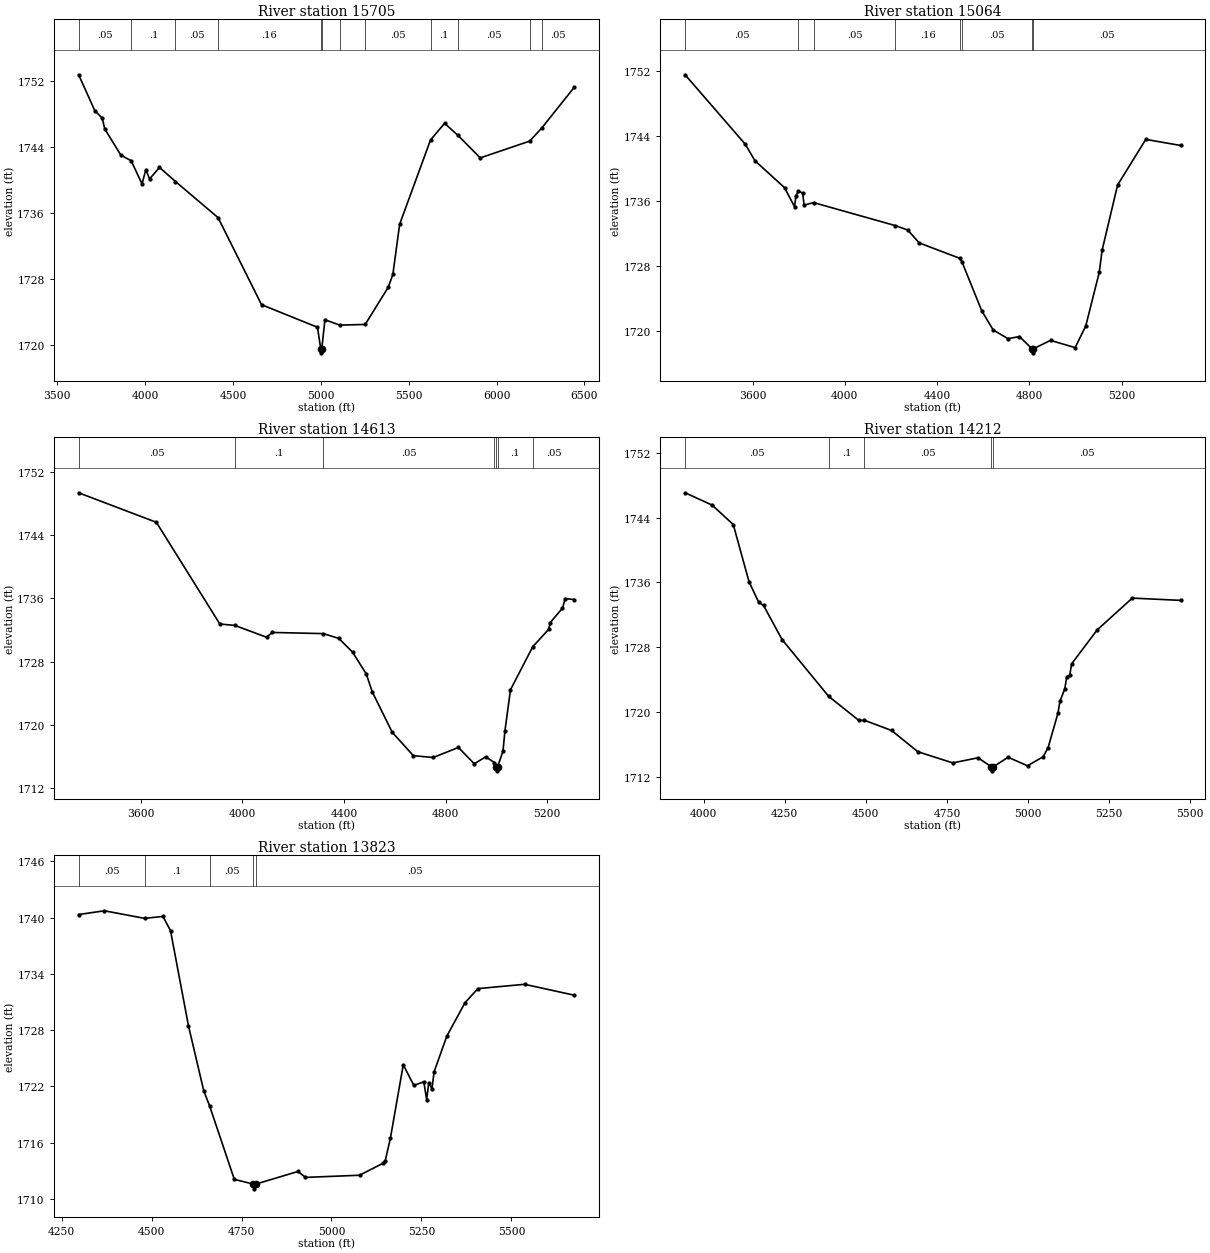
Type RM Length L Ch R = 1 ,15705   ,641,641,641
BEGIN DESCRIPTION:
MUD CREEK 31.0
END DESCRIPTION:
XS GIS Cut Line= 3
      2724883.38     10052048.78      2723672.08      10050947.6
      2722546.98     10050583.73
#Sta/Elev= 30
  3621.8 1752.79  3713.7 1748.44  3756.2 1747.52  3770.4 1746.21  3862.3 1743.02
  3920.8 1742.34  3982.6 1739.52  4004.2 1741.27  4025.2 1740.13  4081.9 1741.53
  4172.8 1739.82  4415.2 1735.43  4662.4 1724.85  4980.7 1722.11  4999.3  1719.5
    5002    1719  5005.3  1719.5  5023.2 1723.02  5107.3 1722.37  5252.3 1722.45
  5384.3    1727  5409.8 1728.55  5448.3 1734.62    5624 1744.87    5704 1746.89
  5779.4 1745.44    5907 1742.69  6188.4 1744.73  6258.3 1746.36  6441.3 1751.26
#Mann= 12 ,-1 , 0
  3621.8     .05       0  3920.8      .1       0  4172.8     .05       0
  4415.2     .16       0  4999.3     .07       0  5005.3     .16       0
  5107.3      .1       0  5252.3     .05       0    5624      .1       0
  5779.4     .05       0  6188.4      .1       0  6258.3     .05       0
Bank Sta=4999.3,5005.3
XS Rating Curve= 0 ,0
Exp/Cntr=0.3,0.1

Type RM Length L Ch R = 1 ,15064   ,451,451,451
BEGIN DESCRIPTION:
MUD CREEK 30.0
END DESCRIPTION:
XS GIS Cut Line= 3
      2724998.31     10051919.54      2723968.92     10050607.67
      2723557.16      10050358.7
#Sta/Elev= 30
  3307.5 1751.52  3568.6 1742.98  3610.3 1740.96  3738.6 1737.65    3782 1735.31
  3788.3 1736.66  3799.1 1737.24  3817.2 1736.97  3823.6 1735.51    3865 1735.81
  4219.7 1732.98  4272.8 1732.44  4322.5 1730.86    4498 1728.97  4508.3 1728.51
  4593.7 1722.52  4643.4 1720.16  4707.6 1719.09  4757.3 1719.35  4811.8 1717.85
  4814.5 1717.35  4817.8 1717.85    4892 1718.88  4998.9 1717.99    5045 1720.67
  5103.3 1727.24  5115.8 1729.97  5182.8 1737.97  5305.1 1743.58  5456.2 1742.83
#Mann= 8 ,-1 , 0
  3307.5     .05       0  3799.1      .1       0    3865     .05       0
  4219.7     .16       0    4498      .1       0  4508.3     .05       0
  4811.8     .03       0  4817.8     .05       0
Bank Sta=4811.8,4817.8
XS Rating Curve= 0 ,0
Exp/Cntr=0.3,0.1

Type RM Length L Ch R = 1 ,14613   ,401,401,401
BEGIN DESCRIPTION:
MUD CREEK 29.0
END DESCRIPTION:
XS GIS Cut Line= 3
      2725314.25     10051608.29      2724586.54      10051024.2
      2724208.32     10050081.04
#Sta/Elev= 30
  3356.6 1749.38  3662.4 1745.64    3912 1732.76    3971 1732.58  4096.1 1731.08
  4118.4 1731.69  4319.6 1731.54  4380.2 1730.93    4434  1729.2  4487.8 1726.45
    4512 1724.14    4590 1719.05  4673.4 1716.08  4751.4 1715.85  4850.5 1717.12
  4912.8 1715.06  4958.2 1715.93    4992 1715.21  4998.6 1714.66  5001.4 1714.16
  5004.6 1714.66  5025.8 1716.64  5033.6 1719.24  5055.4 1724.43  5143.2 1729.89
    5206  1732.1  5211.4 1732.93  5259.9 1734.76  5270.7 1735.97  5305.9 1735.86
#Mann= 7 ,-1 , 0
  3356.6     .05       0    3971      .1       0  4319.6     .05       0
    4992      .1       0  4998.6     .07       0  5004.6      .1       0
  5143.2     .05       0
Bank Sta=4998.6,5004.6
XS Rating Curve= 0 ,0
Exp/Cntr=0.3,0.1

Type RM Length L Ch R = 1 ,14212   ,389,389,389
BEGIN DESCRIPTION:
MUD CREEK 28.0
END DESCRIPTION:
XS GIS Cut Line= 3
      2725271.18     10051086.43      2724696.66      10050243.8
      2724419.33     10049818.25
#Sta/Elev= 30
  3942.9 1747.06  4026.2 1745.54  4091.4 1743.14    4140 1736.08  4169.8 1733.55
  4184.8 1733.15  4241.7 1728.95  4385.4 1721.94  4478.7 1718.96  4495.8 1718.98
  4579.7 1717.72  4660.3  1715.1  4768.1 1713.72    4846 1714.35  4887.2 1713.24
    4890 1712.74  4893.2 1713.24  4938.8 1714.42  4998.6 1713.36  5047.1 1714.49
  5062.2 1715.62  5092.5 1719.86  5098.5 1721.31  5113.6 1722.87  5119.6 1724.35
  5128.7 1724.55  5134.7 1725.95  5213.5 1730.14  5321.7 1734.06  5470.7 1733.78
#Mann= 5 ,-1 , 0
  3942.9     .05       0  4385.4      .1       0  4495.8     .05       0
  4887.2     .03       0  4893.2     .05       0
Bank Sta=4887.2,4893.2
XS Rating Curve= 0 ,0
Exp/Cntr=0.3,0.1

Type RM Length L Ch R = 1 ,13823   ,566,566,566
BEGIN DESCRIPTION:
MUD CREEK 27.0
END DESCRIPTION:
XS GIS Cut Line= 3
      2725544.12      10050569.4       2725070.1     10050124.11
      2724644.02     10049535.26
#Sta/Elev= 30
  4297.3 1740.33    4369 1740.73  4480.5 1739.92  4531.7 1740.13  4552.7  1738.6
  4602.5 1728.47    4645 1721.54  4661.4 1719.91    4730 1712.09  4783.2 1711.58
  4785.9 1711.08  4789.2 1711.58  4906.8 1712.93  4927.8  1712.3  5078.1 1712.53
    5143  1713.8  5149.2 1714.04  5163.9 1716.51  5199.5 1724.31  5228.9 1722.11
  5256.7 1722.49  5264.5  1720.6  5270.6 1722.41  5279.2 1721.74  5285.3 1723.57
  5320.9 1727.39  5371.2 1730.93  5406.8 1732.43  5536.7 1732.89  5674.5 1731.73
#Mann= 5 ,-1 , 0
  4297.3     .05       0  4480.5      .1       0  4661.4     .05       0
  4783.2     .03       0  4789.2     .05       0
Bank Sta=4783.2,4789.2
XS Rating Curve= 0 ,0
Exp/Cntr=0.3,0.1