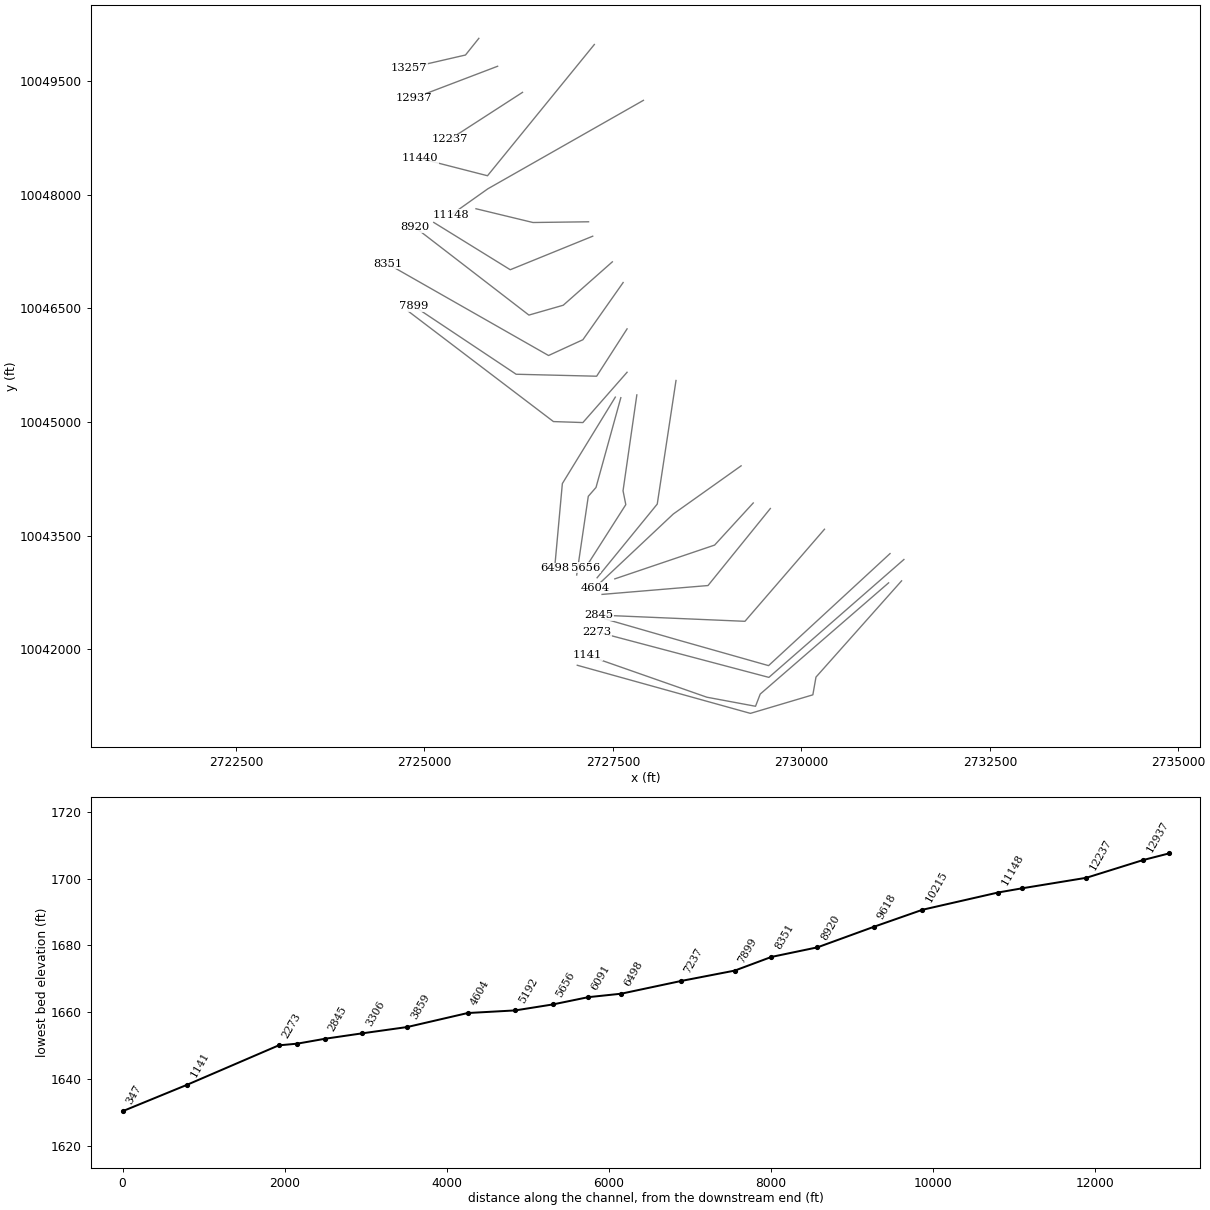
HEC-RAS study MUD CREEK.prj: MUD CREEK Base Level Engineering

--- MUD CREEK.g01 (geometry) --- (continued)

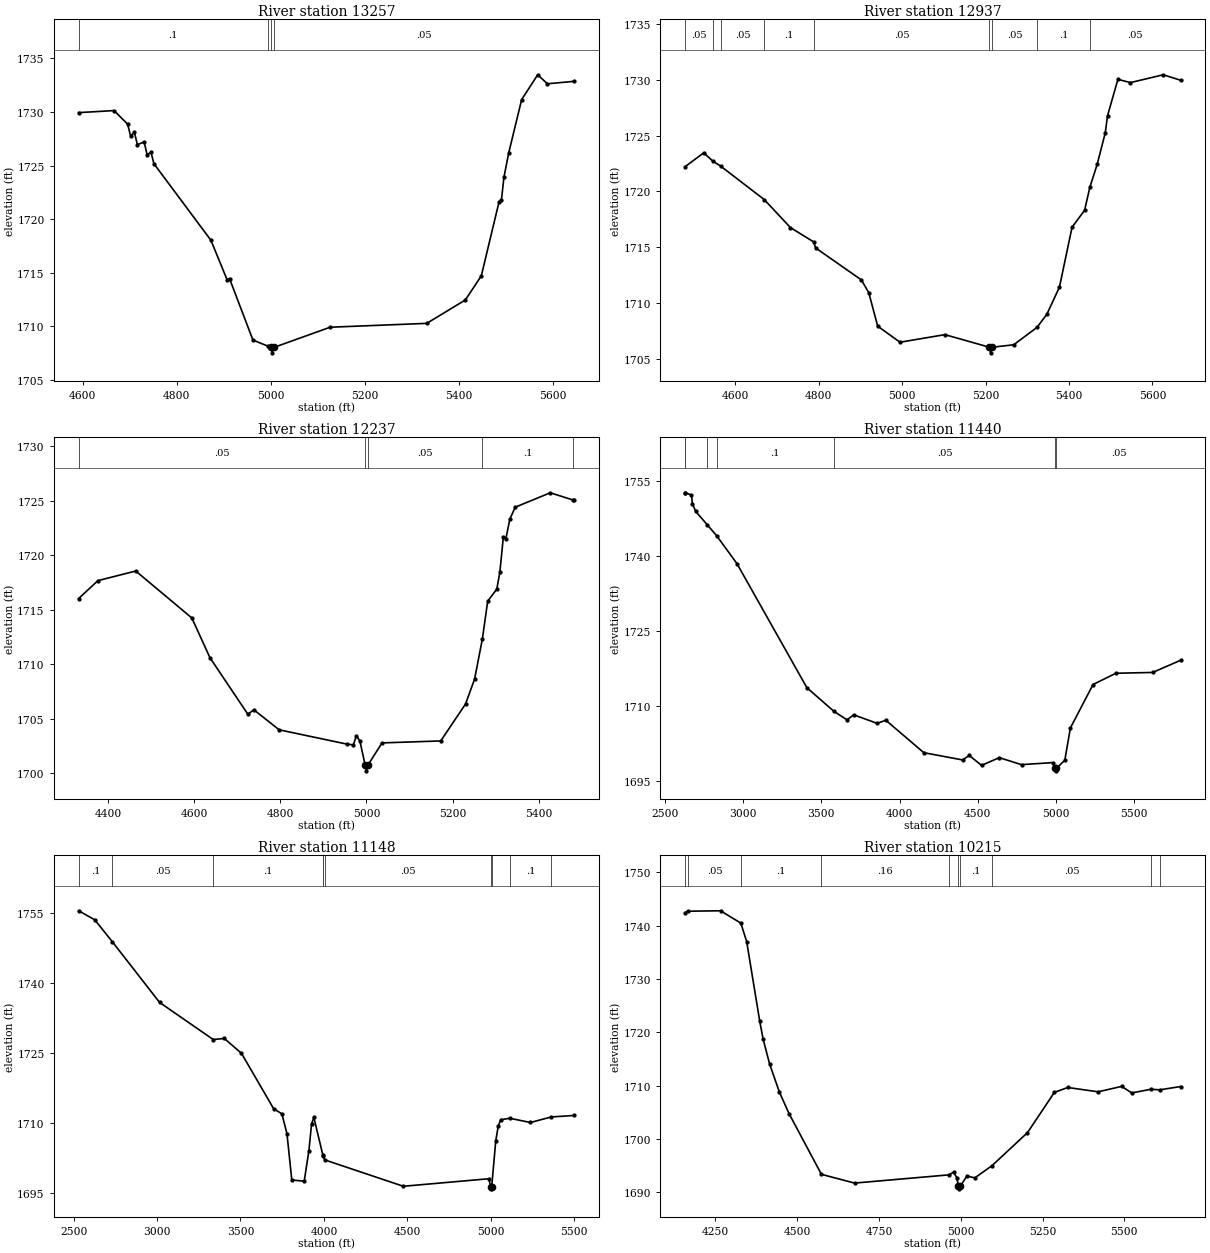
Type RM Length L Ch R = 1 ,13257   ,320,320,320
BEGIN DESCRIPTION:
MUD CREEK 26.0
END DESCRIPTION:
XS GIS Cut Line= 3
      2725721.26      10050066.7      2725544.09     10049846.42
      2724792.97     10049674.19
#Sta/Elev= 30
  4591.5 1729.94  4666.8 1730.13  4695.6 1728.87    4702 1727.75    4710 1728.11
  4716.4 1726.95  4730.8  1727.2  4737.2 1725.99  4745.2 1726.25  4751.6 1725.17
  4872.7 1718.03  4907.1 1714.34  4912.2 1714.46    4962 1708.72  4993.5 1708.16
  5000.1 1708.03  5002.9 1707.53  5006.1 1708.03  5126.2 1709.92  5331.4 1710.28
  5413.4 1712.46  5447.4 1714.71  5485.2 1721.63  5490.3 1721.82  5495.5 1723.91
  5505.8 1726.21  5533.2 1731.16  5567.3 1733.47  5587.9 1732.63  5644.8 1732.86
#Mann= 4 ,-1 , 0
  4591.5      .1       0  4993.5     .05       0  5000.1     .03       0
  5006.1     .05       0
Bank Sta=5000.1,5006.1
XS Rating Curve= 0 ,0
Exp/Cntr=0.3,0.1

Type RM Length L Ch R = 1 ,12937   ,700,700,700
BEGIN DESCRIPTION:
MUD CREEK 25.0
END DESCRIPTION:
XS GIS Cut Line= 2
      2725970.18       10049698.       2724859.4     10049276.67
#Sta/Elev= 30
  4479.5 1722.21  4524.1 1723.45  4545.7 1722.72  4565.5 1722.24  4669.4 1719.26
  4731.9 1716.76  4787.9 1715.47  4792.2 1714.94  4902.1 1712.07  4919.8 1710.93
  4941.2 1707.93  4994.7 1706.49  5102.4 1707.17  5209.2 1706.04    5212 1705.54
  5215.2 1706.04  5267.2 1706.26  5322.9 1707.81  5346.9    1709    5377 1711.43
  5407.2 1716.79  5437.3 1718.31  5449.8 1720.36  5467.5 1722.43  5486.7 1725.23
  5492.3 1726.78  5517.1 1730.03  5547.2 1729.74  5625.7 1730.44  5667.5 1729.95
#Mann= 9 ,-1 , 0
  4479.5     .05       0  4545.7      .1       0  4565.5     .05       0
  4669.4      .1       0  4787.9     .05       0  5209.2     .03       0
  5215.2     .05       0  5322.9      .1       0  5449.8     .05       0
Bank Sta=5209.2,5215.2
XS Rating Curve= 0 ,0
Exp/Cntr=0.3,0.1

Type RM Length L Ch R = 1 ,12237   ,797,797,797
BEGIN DESCRIPTION:
MUD CREEK 23.0
END DESCRIPTION:
XS GIS Cut Line= 2
      2726300.57      10049353.3      2725333.45     10048730.89
#Sta/Elev= 30
  4332.1 1716.02  4376.9 1717.66  4464.7 1718.54  4594.8 1714.24    4637 1710.59
  4724.8 1705.42  4738.9 1705.82  4797.5 1703.99  4954.6 1702.68  4969.8 1702.61
  4976.8 1703.45    4985 1702.95  4997.2 1700.73  4999.9 1700.23  5003.2 1700.73
  5036.2 1702.79  5172.5 1702.97    5230 1706.35  5251.1 1708.64  5269.2 1712.33
  5281.5 1715.78  5302.6 1716.88  5309.7 1718.42  5317.8 1721.66  5323.7  1721.5
    5333 1723.31  5345.4 1724.39  5426.7 1725.71  5479.5 1725.05  5482.2 1725.01
#Mann= 5 ,-1 , 0
  4332.1     .05       0  4997.2     .03       0  5003.2     .05       0
  5269.2      .1       0  5479.5     .05       0
Bank Sta=4997.2,5003.2
XS Rating Curve= 0 ,0
Exp/Cntr=0.3,0.1

Type RM Length L Ch R = 1 ,11440   ,292,292,292
BEGIN DESCRIPTION:
MUD CREEK 22.0
END DESCRIPTION:
XS GIS Cut Line= 3
      2727253.32     10049985.29      2725836.14     10048252.11
      2724936.03     10048481.92
#Sta/Elev= 30
    2629 1752.68  2630.5 1752.68  2669.7 1752.23  2676.2 1750.46    2697 1748.94
  2771.1 1746.26  2831.4 1744.06  2960.5 1738.51  3407.7 1713.68    3579    1709
  3664.4 1707.25  3706.3 1708.27  3856.3 1706.56  3912.3 1707.18    4155 1700.69
  4402.6 1699.24  4445.7 1700.13    4524 1698.15  4637.4  1699.7  4779.5  1698.3
  4979.8 1698.71  4996.6 1697.56  4999.3 1697.06  5002.6 1697.56  5056.3 1699.18
    5092 1705.64    5237 1714.33  5383.1 1716.58  5617.9 1716.74  5796.8 1719.18
#Mann= 7 ,-1 , 0
    2629     .05       0  2630.5      .1       0  2771.1     .05       0
  2831.4      .1       0    3579     .05       0  4996.6     .03       0
  5002.6     .05       0
Bank Sta=4996.6,5002.6
XS Rating Curve= 0 ,0
Exp/Cntr=0.3,0.1

Type RM Length L Ch R = 1 ,11148   ,933,933,933
BEGIN DESCRIPTION:
MUD CREEK 21.0
END DESCRIPTION:
XS GIS Cut Line= 3
      2727904.43     10049247.95      2725840.92     10048079.75
      2725353.06     10047735.37
#Sta/Elev= 30
  2530.5 1755.37    2627 1753.44    2732 1748.76  3015.2 1735.75  3336.6  1727.8
  3403.3 1728.02  3505.8 1724.85    3698 1713.02  3748.2 1711.86  3778.4 1707.64
  3807.4 1697.72  3881.8 1697.45  3909.9 1704.02  3925.8  1709.7  3939.3 1711.13
  3993.2 1703.09  3994.8 1702.86  4004.5 1702.02  4475.6 1696.37  4987.3 1697.98
    4999 1696.32  5001.8 1695.82    5005 1696.32  5029.1 1706.09  5043.9 1709.23
  5058.7 1710.62    5113 1710.93  5237.2 1710.03  5362.4 1711.22  5498.9 1711.53
#Mann= 10 ,-1 , 0
  2530.5      .1       0    2732     .05       0  3336.6      .1       0
  3993.2     .05       0  3994.8      .1       0  4004.5     .05       0
    4999     .04       0    5005     .05       0    5113      .1       0
  5362.4     .05       0
Bank Sta=4999,5005
XS Rating Curve= 0 ,0
Exp/Cntr=0.3,0.1

Type RM Length L Ch R = 1 ,10215   ,597,597,597
BEGIN DESCRIPTION:
MUD CREEK 19.0
END DESCRIPTION:
XS GIS Cut Line= 3
      2727176.75     10047644.07      2726439.39     10047634.49
      2725683.17     10047816.37
#Sta/Elev= 30
  4157.1 1742.46  4166.6 1742.73  4265.4 1742.81  4327.4  1740.5  4345.4 1737.03
  4385.4 1722.06  4395.4 1718.82  4415.4 1714.09  4445.4  1708.8  4475.4  1704.7
    4574 1693.37  4675.4 1691.73  4963.4 1693.27  4977.8 1693.76    4988 1692.76
  4992.7 1691.15  4995.4 1690.65  4998.7 1691.15  5018.9 1693.07  5042.8  1692.7
    5095 1694.97    5204 1701.19  5286.3 1708.75  5327.4 1709.66    5420 1708.85
    5492 1709.87  5522.9 1708.64  5581.7 1709.33  5608.1 1709.22  5672.3 1709.84
#Mann= 10 ,-1 , 0
  4157.1      .1       0  4166.6     .05       0  4327.4      .1       0
    4574     .16       0  4963.4      .1       0  4992.7     .07       0
  4998.7      .1       0    5095     .05       0  5581.7      .1       0
  5608.1     .05       0
Bank Sta=4992.7,4998.7
XS Rating Curve= 0 ,0
Exp/Cntr=0.3,0.1

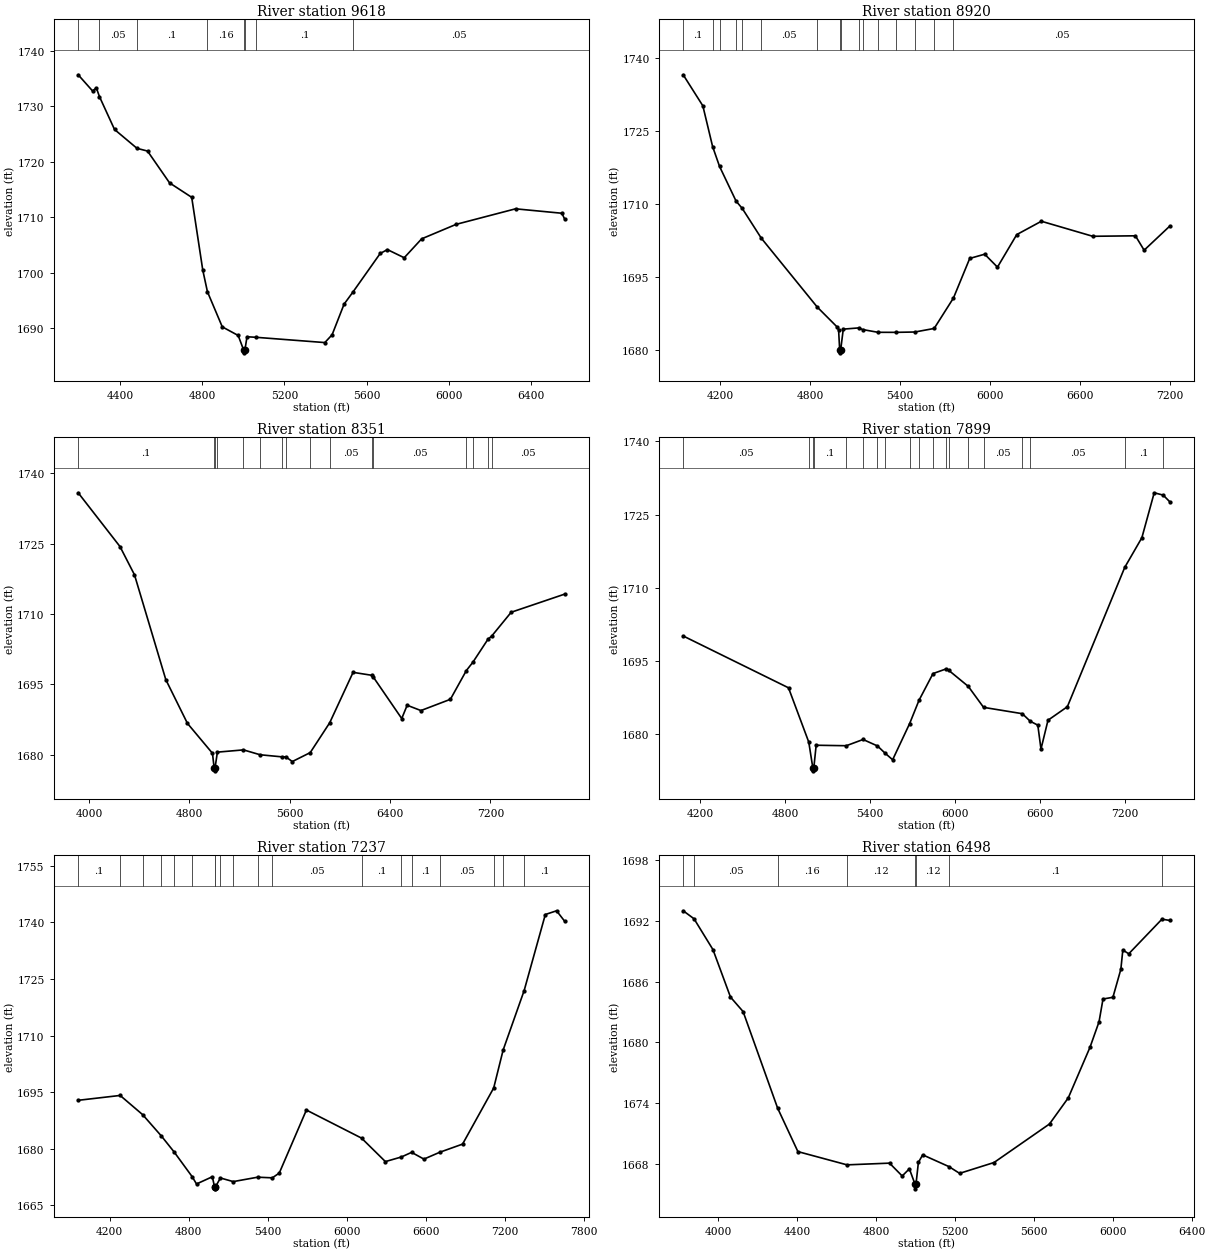
Type RM Length L Ch R = 1 ,9618    ,698,698,698
BEGIN DESCRIPTION:
MUD CREEK 18.0
END DESCRIPTION:
XS GIS Cut Line= 3
      2727231.72     10047453.69      2726137.94     10047010.97
      2725122.92      10047635.6
#Sta/Elev= 30
  4193.9 1735.69    4264 1732.78  4282.7 1733.32  4297.6 1731.76  4371.2 1725.83
  4480.8 1722.43  4532.1 1721.94  4639.7  1716.2  4747.6  1713.6  4801.5 1700.49
  4824.3 1696.58  4896.7 1690.25  4974.2  1688.7  5000.9 1686.07  5003.7 1685.57
  5006.9 1686.07  5017.3 1688.47  5061.4 1688.37  5396.7 1687.42  5432.3 1688.83
  5490.7 1694.35  5533.5 1696.51  5666.8 1703.48    5702 1704.18  5783.9 1702.71
    5869 1706.12  6037.1 1708.73  6326.9 1711.53    6553 1710.73  6565.7 1709.72
#Mann= 8 ,-1 , 0
  4193.9      .1       0  4297.6     .05       0  4480.8      .1       0
  4824.3     .16       0  5000.9     .07       0  5006.9     .16       0
  5061.4      .1       0  5533.5     .05       0
Bank Sta=5000.9,5006.9
XS Rating Curve= 0 ,0
Exp/Cntr=0.3,0.1

Type RM Length L Ch R = 1 ,8920    ,569,569,569
BEGIN DESCRIPTION:
MUD CREEK 16.0
END DESCRIPTION:
XS GIS Cut Line= 4
      2727492.11     10047115.13      2726841.07     10046542.22
      2726385.34     10046412.01      2724876.31     10047569.79
#Sta/Elev= 30
    3953 1736.54  4084.1 1730.16  4149.2 1721.79  4195.2 1717.73  4305.8 1710.57
  4346.8 1709.08  4473.4 1702.98  4846.6 1688.82  4981.3 1684.66  4989.3 1684.14
  4996.7  1679.9  4999.5  1679.4  5002.7  1679.9  5020.5 1684.27  5122.3 1684.52
  5150.6 1684.18    5252 1683.62  5369.3 1683.61  5497.9 1683.68  5626.6 1684.41
  5755.3 1690.67  5863.8  1698.8  5963.5 1699.67  6048.7 1697.01  6177.4  1703.7
  6341.5 1706.44  6684.1 1703.35  6968.7 1703.45  7026.8 1700.49  7196.2  1705.4
#Mann= 16 ,-1 , 0
    3953      .1       0  4149.2     .05       0  4195.2      .1       0
  4305.8     .05       0  4346.8      .1       0  4473.4     .05       0
  4846.6      .1       0  4996.7     .07       0  5002.7      .1       0
  5122.3     .05       0  5150.6      .1       0    5252     .12       0
  5369.3      .1       0  5497.9     .12       0  5626.6      .1       0
  5755.3     .05       0
Bank Sta=4996.7,5002.7
XS Rating Curve= 0 ,0
Exp/Cntr=0.3,0.1

Type RM Length L Ch R = 1 ,8351    ,452,452,452
BEGIN DESCRIPTION:
MUD CREEK 15.0
END DESCRIPTION:
XS GIS Cut Line= 4
      2727635.36     10046841.73      2727101.48     10046086.49
      2726645.76     10045878.15      2724512.21     10047088.03
#Sta/Elev= 30
  3912.4 1735.84  4245.8 1724.37  4361.5 1718.34  4611.4 1695.97  4783.7 1686.65
  4983.5 1680.26  4997.2 1677.02  4999.9 1676.52  5003.2 1677.02  5022.7 1680.51
  5230.6 1680.99  5363.5 1679.95  5538.6  1679.5  5569.4 1679.49  5620.1  1678.5
  5763.1 1680.41  5918.3 1686.77  6104.8 1697.53  6255.1  1696.9  6267.3 1696.48
  6492.8 1687.68  6536.1 1690.51  6645.8 1689.38  6880.9 1691.78  7008.3 1697.92
    7060 1699.68  7181.2 1704.62  7210.3 1705.27  7365.6 1710.35  7791.1 1714.21
#Mann= 16 ,-1 , 0
  3912.4      .1       0  4997.2     .07       0  5003.2      .1       0
  5022.7     .05       0  5230.6      .1       0  5363.5     .16       0
  5538.6      .1       0  5569.4     .12       0  5763.1      .1       0
  5918.3     .05       0  6255.1      .1       0  6267.3     .05       0
  7008.3      .1       0    7060     .05       0  7181.2      .1       0
  7210.3     .05       0
Bank Sta=4997.2,5003.2
XS Rating Curve= 0 ,0
Exp/Cntr=0.3,0.1

Type RM Length L Ch R = 1 ,7899    ,662,662,662
BEGIN DESCRIPTION:
MUD CREEK 14.0
END DESCRIPTION:
XS GIS Cut Line= 4
      2727687.44     10046229.74      2727283.78     10045604.72
      2726216.07     10045630.76      2724863.04     10046528.44
#Sta/Elev= 30
  4080.7 1700.09  4824.7 1689.46  4967.9 1678.32  4997.1 1672.93  4999.9 1672.43
  5003.1 1672.93  5020.1 1677.68  5232.8 1677.58  5351.6 1678.86  5453.4 1677.53
  5507.1 1676.05  5560.3  1674.7  5680.4 1682.12  5746.8 1686.91  5845.6 1692.38
  5938.6 1693.34  5956.4 1693.05  6094.8 1689.75  6202.7 1685.45  6476.5 1684.15
  6532.3  1682.6  6585.9  1681.8  6608.3  1676.9  6657.9 1682.81  6794.7 1685.58
    7200 1714.16    7321 1720.24  7408.2 1729.46  7471.6 1728.98  7516.5 1727.66
#Mann= 19 ,-1 , 0
  4080.7     .05       0  4967.9      .1       0  4997.1     .07       0
  5003.1      .1       0  5232.8     .05       0  5351.6      .1       0
  5453.4     .16       0  5507.1      .1       0  5680.4     .05       0
  5746.8      .1       0  5845.6     .05       0  5938.6      .1       0
  5956.4     .05       0  6094.8      .1       0  6202.7     .05       0
  6476.5      .1       0  6532.3     .05       0    7200      .1       0
  7471.6     .05       0
Bank Sta=4997.1,5003.1
XS Rating Curve= 0 ,0
Exp/Cntr=0.3,0.1

Type RM Length L Ch R = 1 ,7237    ,739,739,739
BEGIN DESCRIPTION:
MUD CREEK 13.0
END DESCRIPTION:
XS GIS Cut Line= 4
      2727687.43     10045656.81      2727101.48     10044992.74
      2726710.86     10045005.76      2724783.74     10046464.12
#Sta/Elev= 30
  3960.9 1692.81  4279.6  1694.1  4450.6    1689  4592.7 1683.34  4689.4 1679.11
  4825.8 1672.58  4859.6 1670.61  4979.6 1672.53  4996.6 1669.82  4999.4 1669.32
  5002.6 1669.82  5041.2  1672.2  5138.6 1671.24  5323.7 1672.41  5435.2 1672.24
  5487.9  1673.5  5693.9 1690.23  6112.7 1682.78  6293.8 1676.55  6414.9 1677.77
  6492.8    1679  6586.5 1677.21  6706.9 1679.03  6879.9 1681.19  7116.3 1696.09
    7188 1706.16  7347.5 1721.93  7508.3 1742.11  7593.6  1743.1  7654.1 1740.37
#Mann= 19 ,-1 , 0
  3960.9      .1       0  4279.6     .05       0  4450.6      .1       0
  4592.7     .05       0  4689.4      .1       0  4825.8     .16       0
  4996.6     .07       0  5002.6     .16       0  5041.2      .1       0
  5138.6     .05       0  5323.7      .1       0  5435.2     .05       0
  6112.7      .1       0  6414.9     .05       0  6492.8      .1       0
  6706.9     .05       0  7116.3      .1       0    7188     .05       0
  7347.5      .1       0
Bank Sta=4996.6,5002.6
XS Rating Curve= 0 ,0
Exp/Cntr=0.3,0.1

Type RM Length L Ch R = 1 ,6498    ,407,407,407
BEGIN DESCRIPTION:
MUD CREEK 12.0
END DESCRIPTION:
XS GIS Cut Line= 3
      2727531.64      10045328.7      2726829.09     10044187.06
       2726726.7     10043068.02
#Sta/Elev= 30
  3823.4 1692.99  3878.3  1692.2  3974.3 1689.15  4063.1 1684.46  4126.9 1683.03
    4302 1673.48  4404.6 1669.19  4653.5 1667.88  4868.9 1668.05    4933 1666.78
  4969.4 1667.49  4997.2 1666.01    5000 1665.51  5003.2 1666.01  5015.1 1668.12
  5036.9 1668.87  5169.6 1667.71    5224 1667.04  5398.2 1668.11  5679.4 1671.92
  5774.5  1674.5  5884.6  1679.5  5930.4 1682.02  5950.5 1684.27  6000.7 1684.44
  6040.9 1687.21  6050.9 1689.11    6081 1688.74  6249.1 1692.16  6287.6 1692.04
#Mann= 8 ,-1 , 0
  3823.4      .1       0  3878.3     .05       0    4302     .16       0
  4653.5     .12       0  4997.2     .07       0  5003.2     .12       0
  5169.6      .1       0  6249.1     .05       0
Bank Sta=4997.2,5003.2
XS Rating Curve= 0 ,0
Exp/Cntr=0.3,0.1

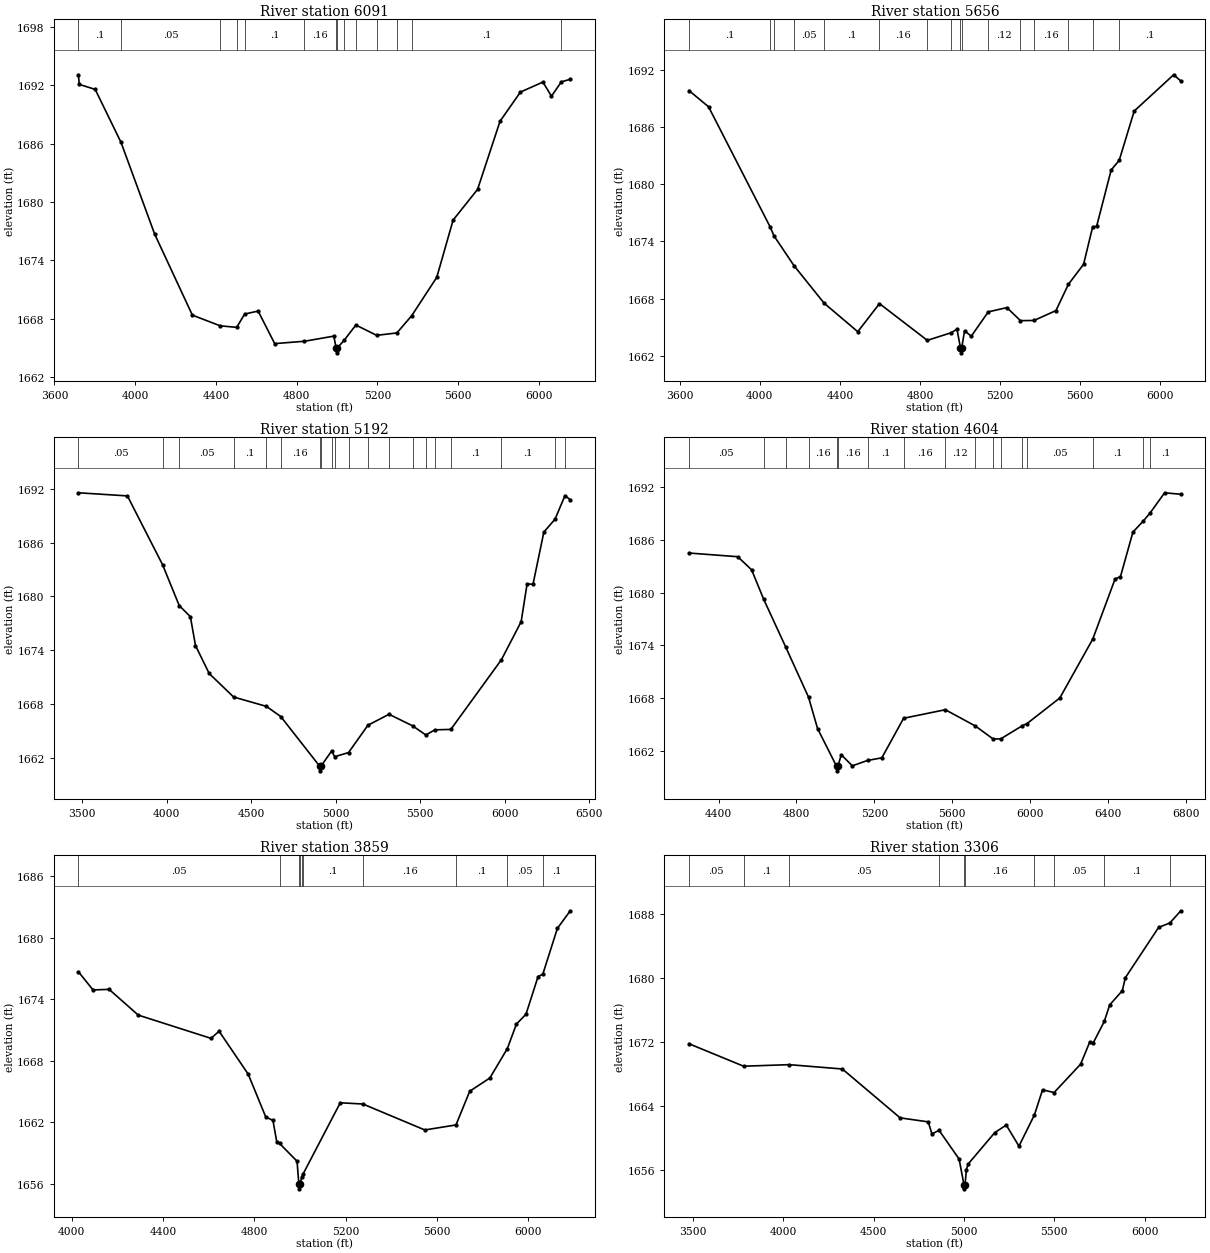
Type RM Length L Ch R = 1 ,6091    ,435,435,435
BEGIN DESCRIPTION:
MUD CREEK 11.0
END DESCRIPTION:
XS GIS Cut Line= 4
      2727604.83     10045321.38      2727275.51     10044135.83
      2727173.05     10044018.74      2727019.37     10042979.57
#Sta/Elev= 30
  3718.9 1693.08  3722.8 1692.09  3801.7 1691.58  3929.7 1686.13  4096.4 1676.69
  4283.3 1668.35  4421.2 1667.25  4502.9 1667.09  4542.2 1668.46    4609 1668.77
  4691.1 1665.42  4838.3 1665.66  4984.1 1666.19  4995.3 1664.97  4998.1 1664.47
  5001.3 1664.97  5034.8 1665.75  5093.3 1667.33  5196.5 1666.27  5296.6 1666.52
  5369.8 1668.29  5494.1 1672.24    5575 1678.13  5696.3 1681.29  5807.5  1688.3
  5908.6  1691.3  6019.8 1692.33  6062.2 1690.88  6111.2 1692.35  6155.4 1692.62
#Mann= 14 ,-1 , 0
  3718.9      .1       0  3929.7     .05       0  4421.2      .1       0
  4502.9     .16       0  4542.2      .1       0  4838.3     .16       0
  4995.3     .07       0  5001.3     .16       0  5034.8     .12       0
  5093.3     .16       0  5196.5     .12       0  5296.6     .16       0
  5369.8      .1       0  6111.2     .05       0
Bank Sta=4995.3,5001.3
XS Rating Curve= 0 ,0
Exp/Cntr=0.3,0.1

Type RM Length L Ch R = 1 ,5656    ,464,464,464
BEGIN DESCRIPTION:
MUD CREEK 10.0
END DESCRIPTION:
XS GIS Cut Line= 4
      2727817.06     10045357.95      2727634.11     10044091.92
       2727670.7     10043908.96      2727136.49     10043074.71
#Sta/Elev= 30
  3646.3 1689.84  3743.9 1688.14  4052.8 1675.47  4070.9 1674.58  4170.9 1671.45
  4321.3 1667.51  4489.2 1664.52  4597.6 1667.47  4836.5 1663.61  4955.4 1664.41
  4984.8 1664.78  5002.2  1662.8    5005  1662.3  5008.2  1662.8  5022.4  1664.6
  5056.2 1664.05  5140.9  1666.6  5233.9 1667.05  5301.8 1665.68  5369.7  1665.7
  5479.1 1666.74    5541 1669.49    5617  1671.6  5662.2 1675.52  5682.1 1675.58
  5754.8  1681.5  5794.9 1682.51  5869.8 1687.69  6066.8  1691.5  6102.7 1690.85
#Mann= 16 ,-1 , 0
  3646.3      .1       0  4052.8     .05       0  4070.9      .1       0
  4170.9     .05       0  4321.3      .1       0  4597.6     .16       0
  4836.5      .1       0  4955.4     .16       0  5002.2     .07       0
  5008.2     .16       0  5140.9     .12       0  5301.8      .1       0
  5369.7     .16       0    5541      .1       0  5662.2     .05       0
  5794.9      .1       0
Bank Sta=5002.2,5008.2
XS Rating Curve= 0 ,0
Exp/Cntr=0.3,0.1

Type RM Length L Ch R = 1 ,5192    ,588,588,588
BEGIN DESCRIPTION:
MUD CREEK 9.0
END DESCRIPTION:
XS GIS Cut Line= 3
      2728336.66     10045548.22      2728087.84     10043916.28
      2727290.12     10042942.91
#Sta/Elev= 30
  3478.1 1691.58  3767.8 1691.23  3976.1 1683.53  4074.1 1678.98  4140.2 1677.74
  4170.5 1674.51  4251.4 1671.39  4395.8 1668.76  4590.5 1667.71  4675.1 1666.57
  4905.9 1661.01  4908.7 1660.51  4911.9 1661.01  4975.6 1662.72    4994 1662.09
  5075.7 1662.55  5190.8 1665.61  5315.5 1666.83  5454.5 1665.54  5533.1 1664.52
  5586.4 1665.09  5680.9 1665.14  5980.3 1672.93  6096.8 1677.17    6132 1681.39
  6167.1 1681.36  6231.2 1687.19  6297.7 1688.64  6356.2 1691.27  6387.4  1690.8
#Mann= 20 ,-1 , 0
  3478.1     .05       0  3976.1      .1       0  4074.1     .05       0
  4395.8      .1       0  4590.5     .05       0  4675.1     .16       0
  4905.9     .07       0  4911.9     .16       0  4975.6     .12       0
    4994     .16       0  5075.7     .12       0  5190.8     .16       0
  5315.5     .12       0  5454.5     .16       0  5533.1      .1       0
  5586.4     .05       0  5680.9      .1       0  5980.3      .1       0
  6297.7     .05       0  6356.2      .1       0
Bank Sta=4905.9,4911.9
XS Rating Curve= 0 ,0
Exp/Cntr=0.3,0.1

Type RM Length L Ch R = 1 ,4604    ,745,745,745
BEGIN DESCRIPTION:
MUD CREEK 8.0
END DESCRIPTION:
XS GIS Cut Line= 3
      2729200.25     10044421.26      2728300.07     10043784.55
      2727262.14     10042812.41
#Sta/Elev= 30
  4248.4 1684.49  4498.5 1684.07  4569.8 1682.58  4631.7 1679.23  4744.6 1673.81
  4861.9  1668.1  4908.4 1664.52  5006.3 1660.22  5009.1 1659.72  5012.3 1660.22
  5030.2 1661.55  5086.8 1660.29  5164.7  1660.9  5238.2  1661.2  5350.2  1665.7
  5564.1 1666.67  5718.3 1664.82  5809.2 1663.35  5848.1 1663.35  5960.1 1664.86
  5982.8 1665.08  6152.1 1668.01  6321.2 1674.71  6435.4 1681.53  6463.3 1681.81
  6527.2 1686.87  6579.3  1688.1    6615 1689.03  6689.9 1691.34  6773.1 1691.17
#Mann= 17 ,-1 , 0
  4248.4     .05       0  4631.7      .1       0  4744.6     .05       0
  4861.9     .16       0  5006.3     .07       0  5012.3     .16       0
  5164.7      .1       0  5350.2     .16       0  5564.1     .12       0
  5718.3     .16       0  5809.2     .12       0  5848.1     .16       0
  5960.1      .1       0  5982.8     .05       0  6321.2      .1       0
  6579.3     .05       0    6615      .1       0
Bank Sta=5006.3,5012.3
XS Rating Curve= 0 ,0
Exp/Cntr=0.3,0.1

Type RM Length L Ch R = 1 ,3859    ,553,553,553
BEGIN DESCRIPTION:
MUD CREEK 7.0
END DESCRIPTION:
XS GIS Cut Line= 3
      2729361.23     10043930.92      2728848.95     10043374.72
      2727524.98     10042928.53
#Sta/Elev= 30
  4029.6 1676.69  4093.5 1674.92  4163.8 1674.98  4291.4 1672.47  4610.2  1670.2
  4645.3  1670.9  4772.9 1666.71  4849.6 1662.54  4881.2  1662.2  4897.8 1660.12
  4909.9 1659.96  4986.8 1658.22  4994.5 1656.03  4997.3 1655.53  5000.5 1656.03
  5007.7 1656.72  5012.5 1656.95  5175.9 1663.92  5275.1  1663.8  5546.1 1661.27
  5682.6 1661.76  5742.6 1665.04    5831 1666.34  5907.3  1669.2  5947.1 1671.59
  5989.2 1672.56    6042 1676.23  6062.6 1676.45  6126.5 1680.92  6182.9 1682.64
#Mann= 10 ,-1 , 0
  4029.6     .05       0  4909.9      .1       0  4994.5     .07       0
  5000.5      .1       0  5007.7     .16       0  5012.5      .1       0
  5275.1     .16       0  5682.6      .1       0  5907.3     .05       0
  6062.6      .1       0
Bank Sta=4994.5,5000.5
XS Rating Curve= 0 ,0
Exp/Cntr=0.3,0.1

Type RM Length L Ch R = 1 ,3306    ,461,461,461
BEGIN DESCRIPTION:
MUD CREEK 6.0
END DESCRIPTION:
XS GIS Cut Line= 3
      2729588.07      10043857.7      2728761.13     10042840.49
      2727356.03      10042723.4
#Sta/Elev= 30
  3478.8 1671.76  3780.6 1668.96  4033.6 1669.15  4327.2 1668.61  4646.8 1662.51
  4802.4 1662.01  4822.5 1660.51  4862.3 1660.95    4973 1657.37  5000.1 1654.15
  5002.9 1653.65  5006.1 1654.15  5013.2 1656.04  5023.2 1656.75  5170.4 1660.67
  5233.9 1661.61  5304.2 1658.98  5389.8 1662.88  5434.6 1666.01  5498.6 1665.67
  5645.3 1669.21  5695.5 1671.96  5715.6 1671.89  5776.3 1674.55  5805.9  1676.6
  5876.1 1678.39  5892.9 1680.01  6076.8 1686.28    6139 1686.84  6199.7 1688.36
#Mann= 10 ,-1 , 0
  3478.8     .05       0  3780.6      .1       0  4033.6     .05       0
  4862.3     .16       0  5000.1     .07       0  5006.1     .16       0
  5389.8      .1       0  5498.6     .05       0  5776.3      .1       0
    6139     .05       0
Bank Sta=5000.1,5006.1
XS Rating Curve= 0 ,0
Exp/Cntr=0.3,0.1

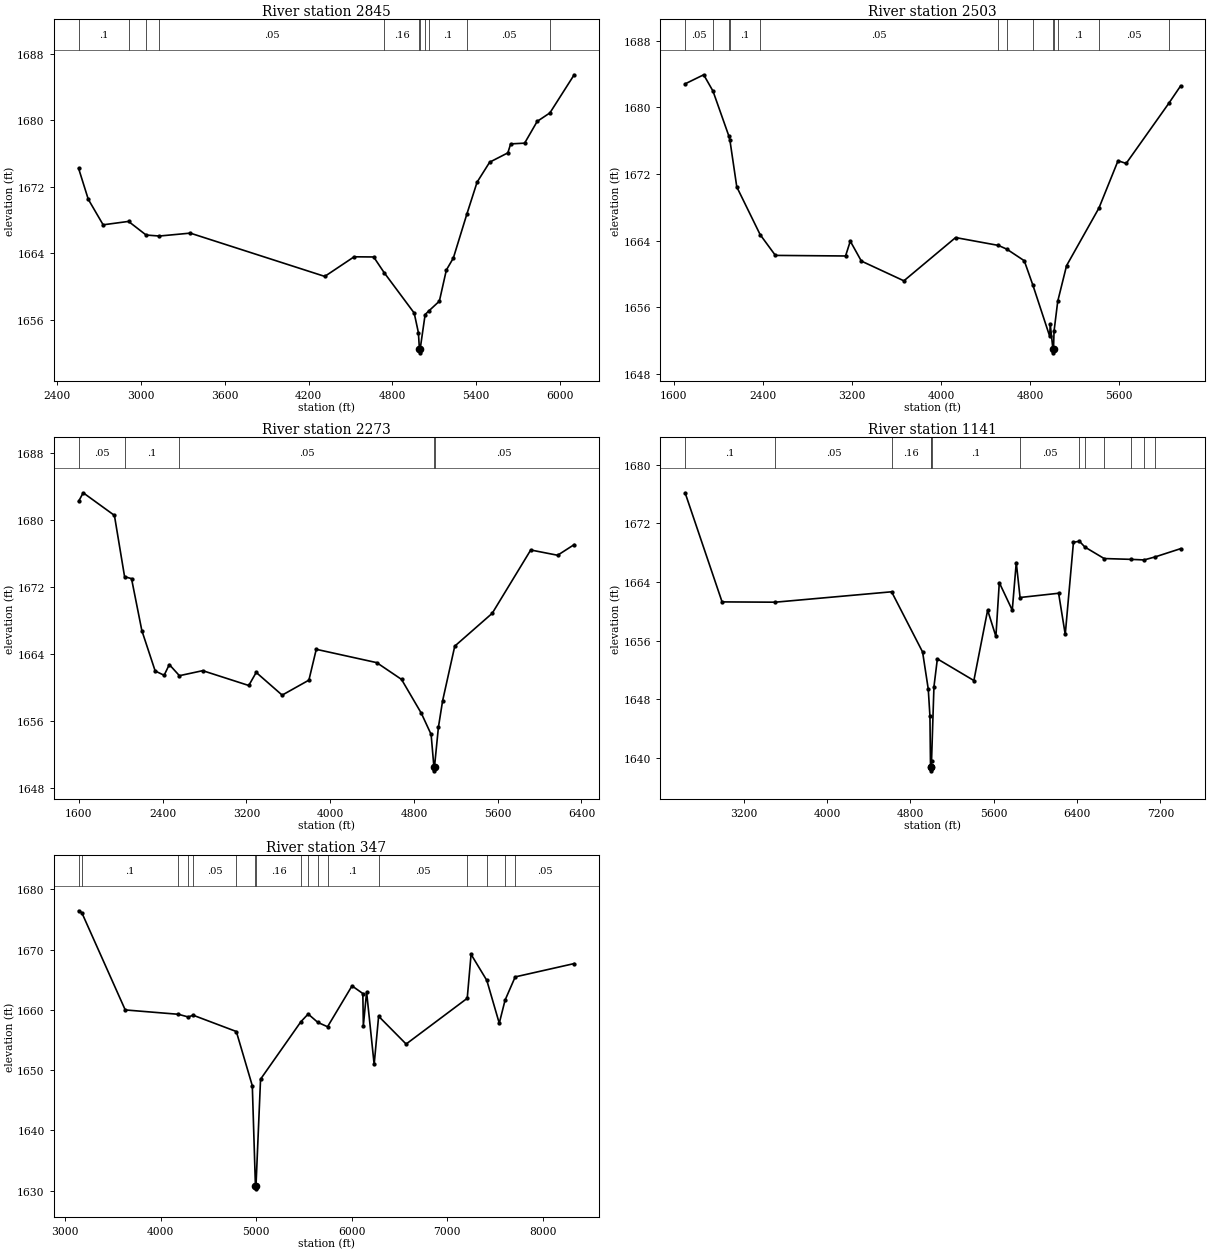
Type RM Length L Ch R = 1 ,2845    ,342,342,342
BEGIN DESCRIPTION:
MUD CREEK 5.0
END DESCRIPTION:
XS GIS Cut Line= 3
      2730306.17     10043583.92      2729251.06     10042368.06
      2727313.95      10042450.5
#Sta/Elev= 30
  2553.3 1674.21  2622.4  1670.5  2728.8 1667.43  2910.6 1667.84  3036.6  1666.2
  3131.3 1666.08  3352.7 1666.43  4315.9 1661.22  4526.1 1663.58  4666.2 1663.56
  4740.9 1661.68  4956.4 1656.81  4986.5 1654.45  4993.5 1652.52  4996.2 1652.02
  4999.5 1652.52  5034.7 1656.63  5060.3 1657.05  5136.6 1658.24  5186.7 1661.99
  5236.7 1663.43  5334.6 1668.78  5406.9 1672.57  5496.9 1674.97    5627 1676.09
  5647.1 1677.17  5747.2 1677.26  5837.2 1679.88  5928.2  1680.9    6102 1685.49
#Mann= 11 ,-1 , 0
  2553.3      .1       0  2910.6     .05       0  3036.6      .1       0
  3131.3     .05       0  4740.9     .16       0  4993.5     .07       0
  4999.5     .16       0  5034.7     .05       0  5060.3      .1       0
  5334.6     .05       0  5928.2      .1       0
Bank Sta=4993.5,4999.5
XS Rating Curve= 0 ,0
Exp/Cntr=0.3,0.1

Type RM Length L Ch R = 1 ,2503    ,230,230,230
BEGIN DESCRIPTION:
MUD CREEK 4.0
END DESCRIPTION:
XS GIS Cut Line= 4
      2731175.74     10043262.39      2729564.29     10041782.82
      2728364.95     10042120.78      2727388.18     10042401.03
#Sta/Elev= 30
    1703 1682.82    1870 1683.91  1953.5 1681.95  2096.8 1676.53  2105.6 1676.05
  2167.2 1670.45    2377 1664.73  2513.8 1662.24  3143.9 1662.17  3186.4 1663.95
  3285.7 1661.56  3667.8 1659.19  4132.1 1664.38  4515.9 1663.44  4591.8 1662.99
  4748.7  1661.6  4826.9 1658.64  4976.9 1652.54  4982.1    1654  5005.4 1651.05
  5008.1 1650.55  5011.4 1651.05  5016.1 1653.15  5049.3 1656.74  5128.5 1661.01
  5419.6 1667.93  5590.8  1673.6  5663.6 1673.27  6046.2 1680.48  6152.9 1682.58
#Mann= 13 ,-1 , 0
    1703     .05       0  1953.5      .1       0  2096.8     .05       0
  2105.6      .1       0    2377     .05       0  4515.9      .1       0
  4591.8     .05       0  4826.9     .16       0  5005.4     .07       0
  5011.4     .16       0  5049.3      .1       0  5419.6     .05       0
  6046.2      .1       0
Bank Sta=5005.4,5011.4
XS Rating Curve= 0 ,0
Exp/Cntr=0.3,0.1

Type RM Length L Ch R = 1 ,2273    ,1132,1132,1132
BEGIN DESCRIPTION:
MUD CREEK 3.0
END DESCRIPTION:
XS GIS Cut Line= 3
      2731359.73     10043184.34      2729568.53     10041627.51
       2727287.3      10042228.2
#Sta/Elev= 30
  1598.2 1682.22  1641.7 1683.24  1939.9 1680.54    2037 1673.22  2103.3 1672.99
    2202 1666.78  2329.2 1661.96  2414.7 1661.45  2464.1 1662.73  2560.6  1661.4
  2783.1    1662  3222.8 1660.23    3294 1661.79  3541.8 1659.08  3797.2 1660.87
  3867.5 1664.55  4444.7 1662.96  4681.5 1660.96  4871.1 1656.91  4964.2 1654.39
  4990.7 1650.54  4993.4 1650.04  4996.7 1650.54    5034 1655.25  5074.3 1658.42
  5190.1 1664.93  5547.8 1668.85  5915.6 1676.41  6172.2 1675.78  6330.4 1677.05
#Mann= 5 ,-1 , 0
  1598.2     .05       0    2037      .1       0  2560.6     .05       0
  4990.7     .04       0  4996.7     .05       0
Bank Sta=4990.7,4996.7
XS Rating Curve= 0 ,0
Exp/Cntr=0.3,0.1

Type RM Length L Ch R = 1 ,1141    ,794,794,794
BEGIN DESCRIPTION:
Mapping XS ffd7405f
END DESCRIPTION:
XS GIS Cut Line= 5
      2731157.05     10042876.22      2729453.91     10041407.46
      2729391.41       10041246.      2728745.57      10041365.8
      2727162.89     10041917.65
#Sta/Elev= 30
  2639.5 1676.18  2994.3 1661.28  3505.2 1661.24    4621 1662.66  4918.4 1654.44
  4972.9 1649.37    4989 1645.65  4994.4 1638.71  4997.2 1638.21  5000.4 1638.71
  5004.3 1639.55  5027.4 1649.69  5060.2  1653.5  5410.5 1650.54  5542.6 1660.15
  5621.9 1656.56  5654.5 1663.91  5778.9 1660.15  5817.3 1666.65  5853.8 1661.88
  6223.7 1662.46  6287.3 1656.83    6366 1669.42  6423.6 1669.56  6475.8 1668.77
  6660.5  1667.2  6914.6 1667.09  7043.4 1667.01  7146.9 1667.41  7394.6 1668.55
#Mann= 13 ,-1 , 0
  2639.5      .1       0  3505.2     .05       0    4621     .16       0
  4994.4     .07       0  5000.4     .16       0  5004.3      .1       0
  5853.8     .05       0  6423.6      .1       0  6475.8     .05       0
  6660.5      .1       0  6914.6     .05       0  7043.4      .1       0
  7146.9     .05       0
Bank Sta=4994.4,5000.4
XS Rating Curve= 0 ,0
Exp/Cntr=0.3,0.1

Type RM Length L Ch R = 1 ,347     ,0,0,0
BEGIN DESCRIPTION:
MUD CREEK 1.0
END DESCRIPTION:
XS GIS Cut Line= 5
       2731328.9     10042902.25      2730193.49     10041631.42
      2730151.82     10041397.05       2729323.7     10041152.25
      2727026.82     10041787.67
#Sta/Elev= 30
    3141 1676.44  3174.4 1676.12    3629 1659.99  4184.4 1659.27  4289.7 1658.82
    4339 1659.12  4792.2 1656.41  4959.6 1647.41  4992.2 1630.81  4994.9 1630.31
  4998.2 1630.81  5045.9  1648.5  5468.6 1658.04  5544.4 1659.31    5646 1657.92
  5747.5  1657.2  6003.7 1663.98    6117 1662.71  6122.2 1657.37  6156.5 1662.96
  6235.5 1650.95  6282.2 1658.94  6570.3 1654.33  7210.1 1661.92  7250.3 1669.21
  7415.2 1664.89  7545.6 1657.78  7606.4 1661.62  7712.3 1665.47  8329.9 1667.68
#Mann= 17 ,-1 , 0
    3141     .05       0  3174.4      .1       0  4184.4     .05       0
  4289.7      .1       0    4339     .05       0  4792.2     .16       0
  4992.2     .07       0  4998.2     .16       0  5468.6     .05       0
  5544.4     .16       0    5646     .05       0  5747.5      .1       0
  6282.2     .05       0  7210.1      .1       0  7415.2     .05       0
  7606.4      .1       0  7712.3     .05       0
Bank Sta=4992.2,4998.2
XS Rating Curve= 0 ,0
Exp/Cntr=0.3,0.1

Chan Stop Cuts=-1
Use User Specified Reach Order=0
Composite Channel Slope=5