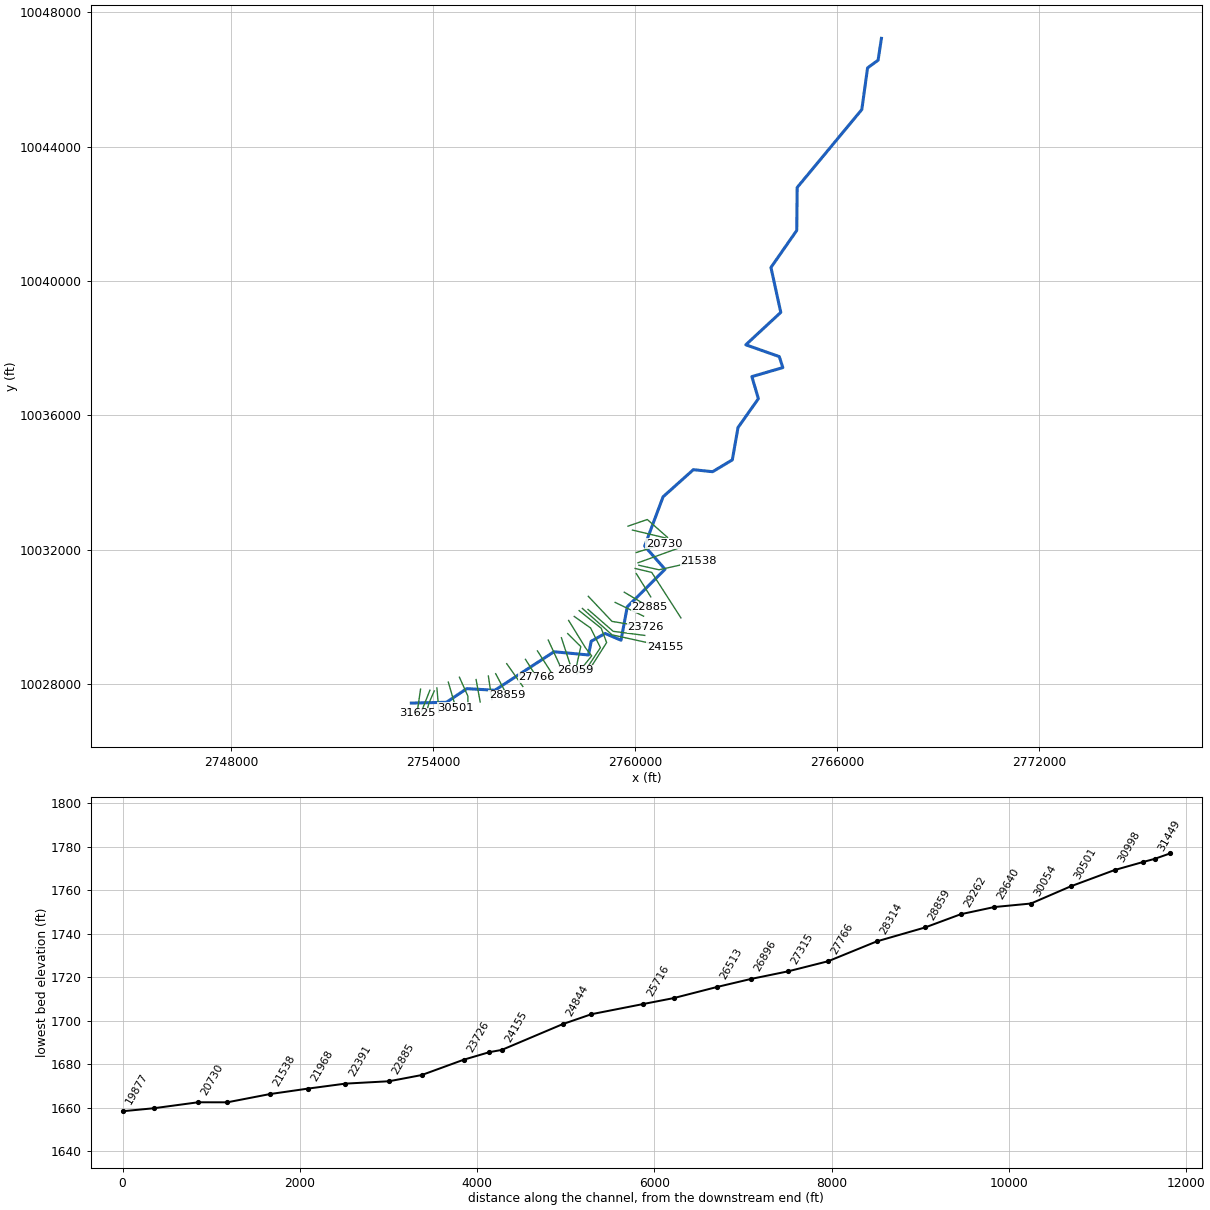
--- MUESEBACH CREEK.prj (project) ---

Proj Title=MUESEBACH CREEK Base Level Engineering
Current Plan=p01
Default Exp/Contr=0.3,0.1
English Units
Geom File=g01
Flow File=f01
Plan File=p01
Y Axis Title=Elevation
X Axis Title(PF)=Main Channel Distance
X Axis Title(XS)=Station
BEGIN DESCRIPTION:
MUESEBACH CREEK
END DESCRIPTION:
DSS Export Rating Curves= 0
DSS Export Rating Curve Sorted= 0
DSS Export Volume Flow Curves= 0
DXF OffsetX= 0
DXF OffsetY= 0
DXF ScaleX= 1
DXF ScaleY= 10

--- MUESEBACH CREEK.p01 (plan) ---

Plan Title=Multiple Run
Short Identifier=Multiple
Geom File=g01
Flow File=f01
Subcritical Flow
K Sum by GR= 0
Std Step Tol= 0.01
Critical Tol= 0.01
Num of Std Step Trials= 20
Max Error Tol= 0.3
Flow Tol Ratio= 0.001
Split Flow NTrial= 30
Split Flow Tol= 0.02
Split Flow Ratio= 0.02
Log Output Level= 0
Friction Slope Method= 1
Unsteady Friction Slope Method= 2
Unsteady Bridges Friction Slope Method= 1
Parabolic Critical Depth
Global Vel Dist=  1 , 1 , 1
Global Log Level= 0
CheckData=True
Encroach Param= -1, 0, 0, 0
BEGIN DESCRIPTION:
Multiple Run
END DESCRIPTION:

--- MUESEBACH CREEK.f01 (steady flow) ---

Flow Title=Multiple
Program Version=4.10
Number of Profiles= 7
Profile Names=10-year,25-year,50-year,1pct_min,100-year,1pct_plu,500-year
River Rch & RM=MUESEBACH CREEK,Reach-1         ,31625
    1054    1550    1986    1862    2519    3406    4068
River Rch & RM=MUESEBACH CREEK,Reach-1         ,31323
    1272    1882    2420    2276    3078    4162    5000
River Rch & RM=MUESEBACH CREEK,Reach-1         ,24014
    3402    5280    7014    6793    9186   12423   15839
River Rch & RM=MUESEBACH CREEK,Reach-1         ,19450
    4059    6326    8429    8180   11063   14962   19160
River Rch & RM=MUESEBACH CREEK,Reach-1         ,14997
    4060    6307    8382    8114   10973   14839   18901
River Rch & RM=MUESEBACH CREEK,Reach-1         ,9443
    4365    6769    8986    8683   11743   15882   20161
Boundary for River Rch & Prof#=MUESEBACH CREEK,Reach-1         , 1
Up Type= 0
Dn Type= 3
Dn Slope=0.0031
Boundary for River Rch & Prof#=MUESEBACH CREEK,Reach-1         , 2
Up Type= 0
Dn Type= 3
Dn Slope=0.0031
Boundary for River Rch & Prof#=MUESEBACH CREEK,Reach-1         , 3
Up Type= 0
Dn Type= 3
Dn Slope=0.0031
Boundary for River Rch & Prof#=MUESEBACH CREEK,Reach-1         , 4
Up Type= 0
Dn Type= 3
Dn Slope=0.0031
Boundary for River Rch & Prof#=MUESEBACH CREEK,Reach-1         , 5
Up Type= 0
Dn Type= 3
Dn Slope=0.0031
Boundary for River Rch & Prof#=MUESEBACH CREEK,Reach-1         , 6
Up Type= 0
Dn Type= 3
Dn Slope=0.0031
Boundary for River Rch & Prof#=MUESEBACH CREEK,Reach-1         , 7
Up Type= 0
Dn Type= 3
Dn Slope=0.0031
DSS Import GetInterval= 0
DSS Import GetPeak= 0
DSS Import FillOption= 0

--- MUESEBACH CREEK.g01 (geometry) ---

Geom Title=Existing Conditions
Program Version=4.10

River Reach=MUESEBACH CREEK ,Reach-1
Reach XY= 30
      2753352.53     10027443.75      2754394.73      10027468.3
      2754998.92     10027872.99      2755832.57     10027825.89
      2757589.56     10028971.12      2758612.82     10028875.38
      2758693.61     10029283.82      2759106.83     10029515.55
      2759578.47     10029313.73      2759763.32     10030306.43
      2760885.99     10031424.95      2760279.39     10032113.61
       2760826.5     10033580.25      2761725.96     10034387.96
      2762297.01     10034327.24      2762882.48     10034679.68
       2763052.1     10035642.23      2763656.06     10036499.73
      2763463.67     10037156.54      2764381.91     10037423.84
      2764277.88     10037751.56      2763283.32     10038103.01
      2764321.33     10039067.47      2764029.59     10040403.18
      2764795.43     10041504.99      2764808.13      10042781.9
      2766727.36     10045102.12      2766897.95     10046340.03
      2767210.47     10046569.71      2767309.55     10047219.82

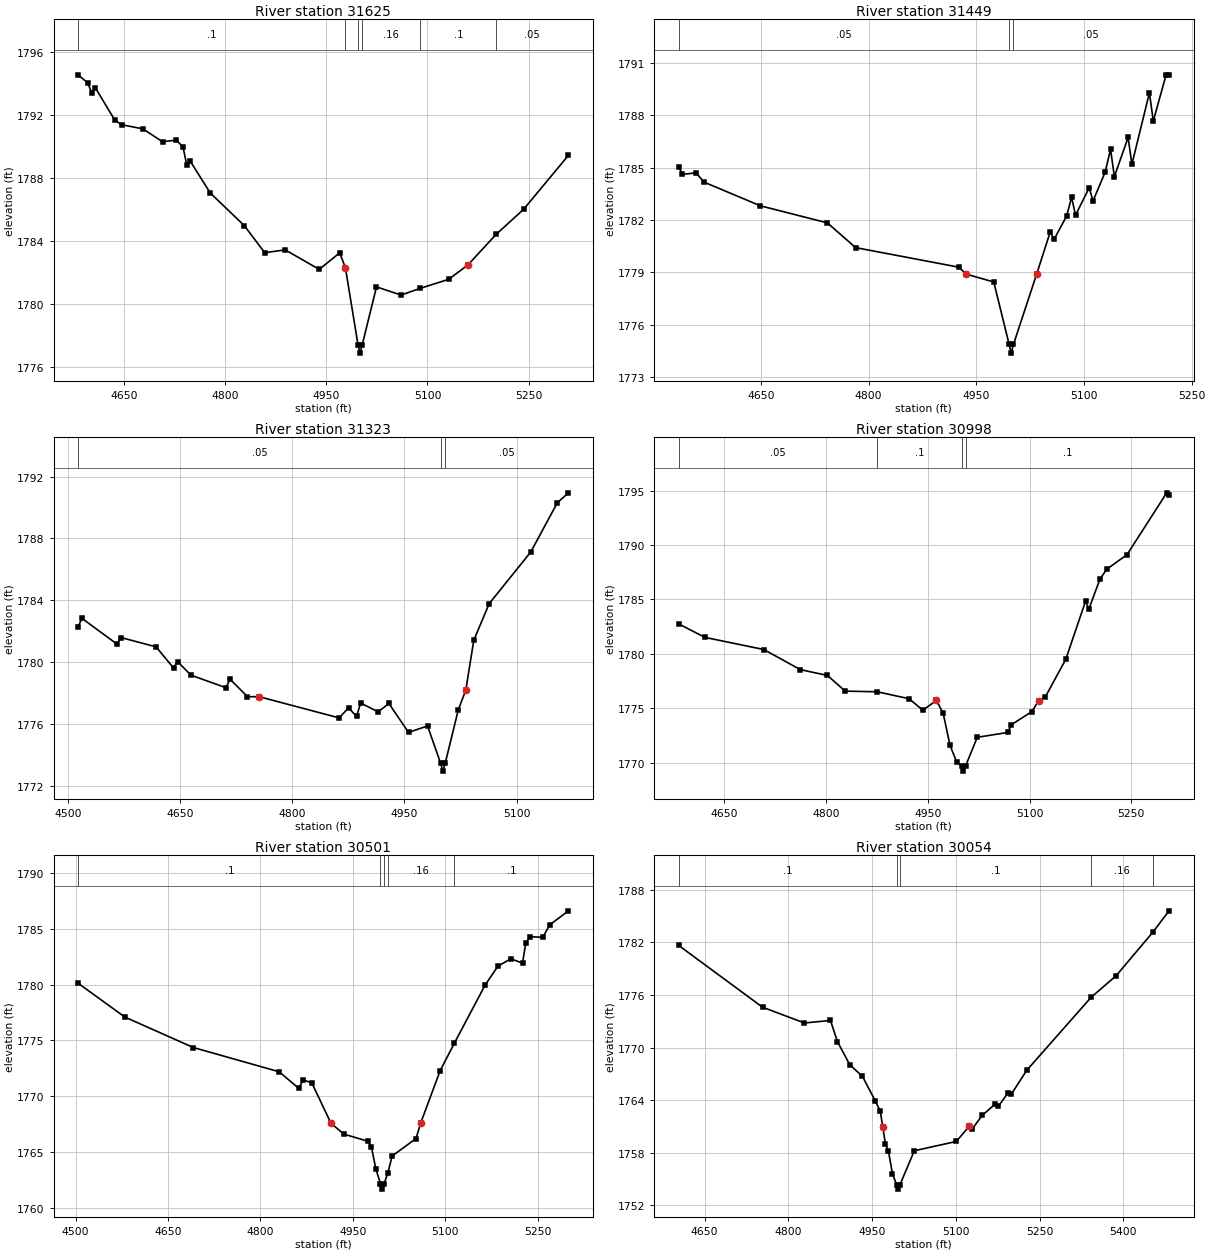
Type RM Length L Ch R = 1 ,31625   ,176,176,176
BEGIN DESCRIPTION:
MUESEBACH CREEK 61.0
END DESCRIPTION:
XS GIS Cut Line= 2
      2753626.63     10027857.66      2753522.57     10027137.95
#Sta/Elev= 30
  4581.9 1794.56    4596 1794.06  4602.5 1793.39  4607.6 1793.73  4636.4 1791.68
  4646.5 1791.39  4677.9 1791.13  4707.1 1790.31  4727.3 1790.41  4737.4 1789.99
  4743.1 1788.84  4748.2 1789.08  4777.8 1787.06  4828.4 1784.98  4858.7 1783.26
    4889 1783.44  4939.5  1782.2  4969.8 1783.25  4978.3 1782.31  4997.1 1777.38
  4999.9 1776.88  5003.1 1777.38  5024.4 1781.09  5060.8 1780.57  5089.6    1781
  5131.5 1781.57  5159.9 1782.48  5201.7 1784.42  5242.6 1786.02  5309.1 1789.45
#Mann= 6 ,-1 , 0
  4581.9      .1       0  4978.3     .16       0  4997.1     .07       0
  5003.1     .16       0  5089.6      .1       0  5201.7     .05       0
Bank Sta=4978.3,5159.9
XS Rating Curve= 0 ,0
Exp/Cntr=0.3,0.1

Type RM Length L Ch R = 1 ,31449   ,126,126,126
BEGIN DESCRIPTION:
Mapping XS 68c3eac4
END DESCRIPTION:
XS GIS Cut Line= 2
       2753904.4     10027826.41      2753654.41     10027191.02
#Sta/Elev= 30
  4535.6 1785.06    4541 1784.61    4560  1784.7  4570.8 1784.17  4649.4 1782.81
  4742.7 1781.83  4782.1 1780.41  4925.6 1779.29  4936.1 1778.89  4974.4 1778.44
  4995.8 1774.86  4998.6 1774.36  5001.8 1774.86    5034 1778.88    5053 1781.31
  5058.4 1780.89  5075.8 1782.22  5082.8  1783.3  5088.2 1782.27  5107.2 1783.84
  5112.6 1783.09  5129.5 1784.74    5137 1786.05  5142.3 1784.48  5161.4 1786.73
  5166.7 1785.19  5191.1 1789.29  5196.5 1787.67  5214.3 1790.32  5218.4 1790.32
#Mann= 3 ,-1 , 0
  4535.6     .05       0  4995.8     .04       0  5001.8     .05       0
Bank Sta=4936.1,5034
XS Rating Curve= 0 ,0
Exp/Cntr=0.3,0.1

Type RM Length L Ch R = 1 ,31323   ,325,325,325
BEGIN DESCRIPTION:
Mapping XS 9d4c31d9
END DESCRIPTION:
XS GIS Cut Line= 3
      2754034.62     10027805.58      2753873.15     10027435.78
      2753810.64     10027190.95
#Sta/Elev= 30
  4513.3 1782.29  4518.5 1782.84  4565.3 1781.18  4570.7  1781.6  4617.6    1781
    4641 1779.64  4646.4 1780.05  4664.4 1779.17  4711.2 1778.36  4716.6 1778.91
    4740 1777.78  4755.4 1777.78  4862.5 1776.41  4875.4 1777.06  4885.9  1776.5
  4891.4 1777.37  4914.8  1776.8  4929.2 1777.34  4955.5 1775.47  4980.9 1775.89
  4998.5 1773.47  5001.3 1772.97  5004.5 1773.47  5022.1 1776.94  5032.1 1778.21
  5042.8 1781.43  5063.4 1783.79  5118.9 1787.12  5154.6 1790.31  5169.5 1790.95
#Mann= 3 ,-1 , 0
  4513.3     .05       0  4998.5     .04       0  5004.5     .05       0
Bank Sta=4755.4,5032.1
XS Rating Curve= 0 ,0
Exp/Cntr=0.3,0.1

Type RM Length L Ch R = 1 ,30998   ,497,497,497
BEGIN DESCRIPTION:
MUESEBACH CREEK 60.0
END DESCRIPTION:
XS GIS Cut Line= 2
      2754112.74     10027892.34      2754173.48      10027172.1
#Sta/Elev= 30
  4582.7 1782.76  4621.4 1781.52  4708.5  1780.4  4761.9 1778.56  4802.1 1778.02
  4828.2 1776.58  4875.5 1776.52  4922.5 1775.88  4942.6 1774.83  4962.7 1775.72
  4972.7 1774.53  4982.7  1771.6  4992.8 1770.03  4999.8 1769.73  5002.5 1769.23
  5005.8 1769.73  5022.9 1772.34  5067.7 1772.78    5073 1773.49  5103.2 1774.69
  5113.2 1775.69  5123.2 1776.05  5153.3  1779.5  5182.4 1784.83  5187.4 1784.13
  5203.5 1786.84  5213.5 1787.77  5243.6 1789.12  5302.1  1794.8  5305.5 1794.59
#Mann= 4 ,-1 , 0
  4582.7     .05       0  4875.5      .1       0  4999.8     .07       0
  5005.8      .1       0
Bank Sta=4962.7,5113.2
XS Rating Curve= 0 ,0
Exp/Cntr=0.3,0.1

Type RM Length L Ch R = 1 ,30501   ,447,447,447
BEGIN DESCRIPTION:
MUESEBACH CREEK 59.0
END DESCRIPTION:
XS GIS Cut Line= 2
      2754451.08     10028067.71      2754673.32     10027303.78
#Sta/Elev= 30
  4504.1 1780.12  4580.1 1777.09  4691.1 1774.37  4830.4  1772.2  4862.3 1770.71
  4869.1 1771.47  4883.2 1771.22  4914.4  1767.6  4935.2 1766.63  4974.9 1765.98
  4980.1 1765.44  4987.3 1763.49  4994.7 1762.21  4997.5 1761.71  5000.7 1762.21
  5006.7 1763.17  5013.6 1764.67  5052.3 1766.23  5060.2 1767.66  5091.5  1772.3
  5114.3 1774.73  5164.4 1779.95  5185.2 1781.64    5206  1782.3  5225.1 1781.92
  5230.3 1783.69  5237.3 1784.28  5258.1 1784.22  5269.1 1785.33  5299.7 1786.59
#Mann= 5 ,-1 , 0
  4504.1      .1       0  4994.7     .07       0  5000.7      .1       0
  5006.7     .16       0  5114.3      .1       0
Bank Sta=4914.4,5060.2
XS Rating Curve= 0 ,0
Exp/Cntr=0.3,0.1

Type RM Length L Ch R = 1 ,30054   ,414,414,414
BEGIN DESCRIPTION:
MUESEBACH CREEK 58.0
END DESCRIPTION:
XS GIS Cut Line= 3
      2754781.15     10028213.54      2755032.88     10027649.33
      2755032.88     10027388.95
#Sta/Elev= 30
  4603.6 1781.66  4753.9  1774.6    4829  1772.8  4875.5 1773.09  4888.1 1770.67
    4910 1768.05  4932.9  1766.7  4956.1 1763.87  4964.7 1762.74 4969.32 1760.91
  4973.8 1759.04  4979.3 1758.19  4986.6 1755.59    4994 1754.34  4996.8 1753.84
    5000 1754.34  5025.7 1758.22  5100.9 1759.28  5124.1 1761.03  5129.6 1760.72
  5147.3 1762.26  5170.6 1763.55    5176 1763.27  5193.8 1764.85  5199.2 1764.66
    5227  1767.4    5342 1775.71    5387 1778.19  5453.1 1783.18  5481.8  1785.6
#Mann= 5 ,-1 , 0
  4603.6      .1       0    4994     .07       0    5000      .1       0
    5342     .16       0  5453.1      .1       0
Bank Sta=4969.32,5124.1
XS Rating Curve= 0 ,0
Exp/Cntr=0.3,0.1

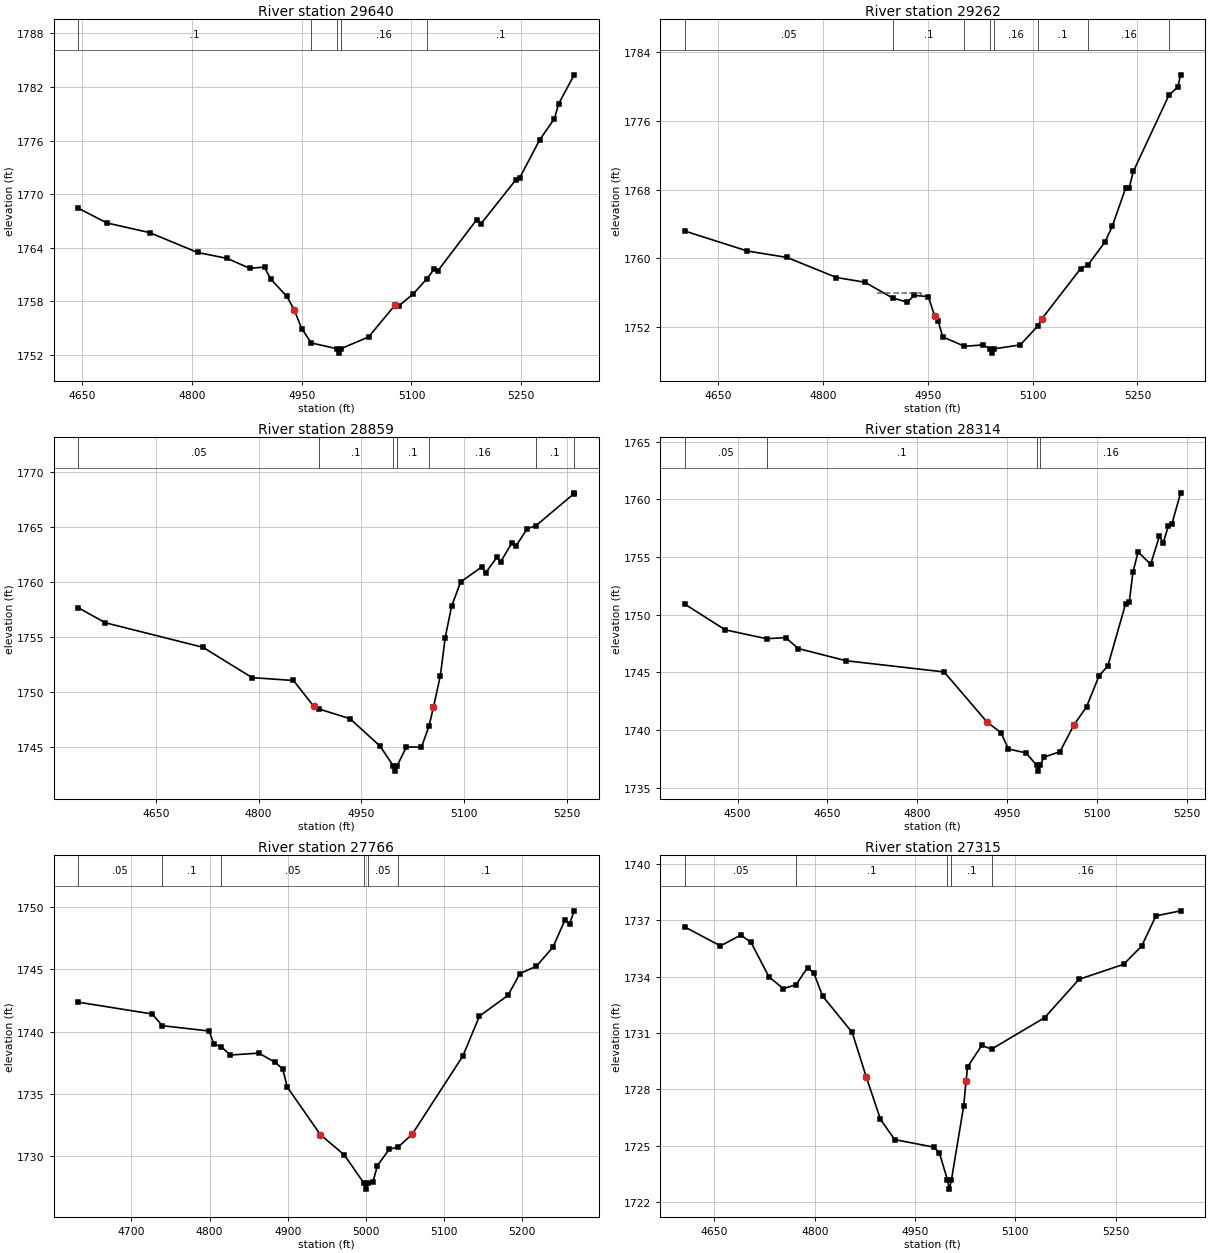
Type RM Length L Ch R = 1 ,29640   ,378,378,378
BEGIN DESCRIPTION:
MUESEBACH CREEK 57.0
END DESCRIPTION:
XS GIS Cut Line= 2
      2755275.93     10028144.13      2755397.18     10027477.27
#Sta/Elev= 30
  4644.6 1768.43  4683.7 1766.78  4742.1  1765.7  4807.6 1763.48  4848.3 1762.81
  4878.8 1761.71  4899.1 1761.84  4907.3 1760.52  4929.6 1758.57  4939.8 1757.06
  4949.9 1754.97    4963 1753.36  4997.7 1752.72  5000.5 1752.22  5003.7 1752.72
  5041.4 1754.03  5077.5 1757.59  5082.6  1757.5  5102.4 1758.84  5121.3 1760.56
  5130.9  1761.6    5136 1761.42  5189.3 1767.16  5194.4 1766.62  5242.7 1771.61
  5247.8  1771.8  5275.2 1776.07  5295.5 1778.46  5301.1  1780.1  5322.4 1783.35
#Mann= 5 ,-1 , 0
  4644.6      .1       0    4963     .16       0  4997.7     .07       0
  5003.7     .16       0  5121.3      .1       0
Bank Sta=4939.8,5077.5
XS Rating Curve= 0 ,0
Exp/Cntr=0.3,0.1

Type RM Length L Ch R = 1 ,29262   ,403,403,403
BEGIN DESCRIPTION:
MUESEBACH CREEK 56.0
END DESCRIPTION:
XS GIS Cut Line= 2
      2755640.51     10028248.32      2755744.41     10027546.97
#Sta/Elev= 30
  4602.7 1763.16  4692.2 1760.83  4748.9 1760.08  4819.6 1757.74  4860.1 1757.19
  4900.2 1755.34  4920.7 1754.87  4930.8 1755.65    4951 1755.52  4960.1 1753.21
  4965.1  1752.7  4971.3 1750.82  5002.6 1749.72  5029.6 1749.88    5039 1749.42
  5041.8 1748.92    5045 1749.42  5082.5 1749.88  5107.7 1752.11  5112.8 1752.87
  5168.6 1758.77  5179.4 1759.22  5203.8 1761.92  5213.9  1763.7    5233 1768.16
  5238.1  1768.2  5244.2 1770.14    5295    1779  5307.6 1779.96  5311.7 1781.38
#Mann= 8 ,-1 , 0
  4602.7     .05       0  4900.2      .1       0  5002.6     .16       0
    5039     .07       0    5045     .16       0  5107.7      .1       0
  5179.4     .16       0    5295      .1       0
#XS Ineff= 1 ,-1
 4878.18 4940.45 1755.91
Permanent Ineff=
       T
Bank Sta=4960.1,5112.8
XS Rating Curve= 0 ,0
Exp/Cntr=0.3,0.1

Type RM Length L Ch R = 1 ,28859   ,545,545,545
BEGIN DESCRIPTION:
MUESEBACH CREEK 55.0
END DESCRIPTION:
XS GIS Cut Line= 2
      2755857.52     10028317.75      2756195.17     10027677.08
#Sta/Elev= 30
  4536.7 1757.65  4575.9 1756.29  4718.7 1754.06  4790.5 1751.31  4850.9 1751.05
  4880.4 1748.72  4888.3 1748.46  4933.4 1747.59  4977.4  1745.1  4996.5 1743.33
  4999.2 1742.83  5002.5 1743.33  5015.8 1745.02  5037.9 1745.01  5048.8 1746.89
 5055.45 1748.64  5065.5  1751.5  5072.5 1754.92  5081.9 1757.79  5095.1 1759.99
    5126 1761.35  5131.6 1760.82    5148 1762.21  5153.7 1761.83    5170 1763.53
  5175.7 1763.22  5192.1  1764.8  5205.3  1765.1  5260.5 1767.99  5260.9 1768.07
#Mann= 7 ,-1 , 0
  4536.7     .05       0  4888.3      .1       0  4996.5     .07       0
  5002.5      .1       0  5048.8     .16       0  5205.3      .1       0
  5260.5     .05       0
Bank Sta=4880.4,5055.45
XS Rating Curve= 0 ,0
Exp/Cntr=0.3,0.1

Type RM Length L Ch R = 1 ,28314   ,548,548,548
BEGIN DESCRIPTION:
MUESEBACH CREEK 54.0
END DESCRIPTION:
XS GIS Cut Line= 2
      2756185.67     10028615.45      2756662.94      10027938.6
#Sta/Elev= 30
  4411.8 1750.91  4479.3 1748.68  4548.4 1747.91  4580.3 1748.01  4601.2 1747.06
  4681.3    1746    4845 1745.03  4916.5 1740.69  4939.9 1739.77  4952.3 1738.35
  4981.8 1738.01  4999.7 1736.93  5002.4 1736.43  5005.7 1736.93  5011.3 1737.64
  5038.4 1738.11  5061.8 1740.44  5082.8    1742  5103.7 1744.69  5118.5 1745.56
  5148.1 1750.94  5154.2 1751.06  5160.3 1753.67    5169 1755.44  5189.9 1754.36
  5204.7 1756.82  5210.8  1756.2  5219.5 1757.69  5225.6 1757.89    5240 1760.56
#Mann= 4 ,-1 , 0
  4411.8     .05       0  4548.4      .1       0  4999.7     .07       0
  5005.7     .16       0
Bank Sta=4916.5,5061.8
XS Rating Curve= 0 ,0
Exp/Cntr=0.3,0.1

Type RM Length L Ch R = 1 ,27766   ,451,451,451
BEGIN DESCRIPTION:
MUESEBACH CREEK 53.0
END DESCRIPTION:
XS GIS Cut Line= 2
      2756741.19     10028745.71      2757079.35     10028208.13
#Sta/Elev= 30
  4631.9 1742.36  4726.5 1741.41  4739.4 1740.47  4799.5 1740.04  4805.4 1739.01
    4815 1738.77  4826.6 1738.11  4863.1 1738.26  4884.3 1737.51  4893.7 1736.98
  4899.6 1735.52    4942  1731.7  4972.6 1730.07  4997.5 1727.82  5000.2 1727.32
  5003.5 1727.82  5009.1 1727.87    5015 1729.21  5030.3 1730.54  5041.3 1730.69
  5059.5 1731.73  5124.5 1738.04  5145.7 1741.24  5182.2 1742.91  5197.5 1744.66
  5218.7 1745.26  5239.9 1746.79  5255.2 1748.97  5261.1 1748.65    5267 1749.71
#Mann= 6 ,-1 , 0
  4631.9     .05       0  4739.4      .1       0    4815     .05       0
  4997.5    .035       0  5003.5     .05       0  5041.3      .1       0
Bank Sta=4942,5059.5
XS Rating Curve= 0 ,0
Exp/Cntr=0.3,0.1

Type RM Length L Ch R = 1 ,27315   ,419,419,419
BEGIN DESCRIPTION:
MUESEBACH CREEK 52.0
END DESCRIPTION:
XS GIS Cut Line= 2
      2757097.12     10028997.41      2757496.44     10028372.38
#Sta/Elev= 30
  4605.6 1736.65    4659 1735.64  4689.4 1736.22  4704.6 1735.83  4731.7 1733.98
  4752.9 1733.37  4772.1 1733.57  4789.2 1734.49  4798.5 1734.21  4811.7 1732.97
    4856 1731.03  4877.2 1728.64  4898.3  1726.4  4919.5 1725.32  4977.8 1724.92
  4986.3 1724.62  4998.5 1723.18  5001.3 1722.68  5004.5 1723.18  5022.7 1727.09
 5026.36 1728.45  5028.6 1729.19  5049.8 1730.34  5064.5 1730.14    5144 1731.82
  5195.3 1733.86  5262.1 1734.66  5289.2 1735.64  5310.3 1737.24  5347.3 1737.51
#Mann= 5 ,-1 , 0
  4605.6     .05       0  4772.1      .1       0  4998.5     .07       0
  5004.5      .1       0  5064.5     .16       0
Bank Sta=4877.2,5026.36
XS Rating Curve= 0 ,0
Exp/Cntr=0.3,0.1

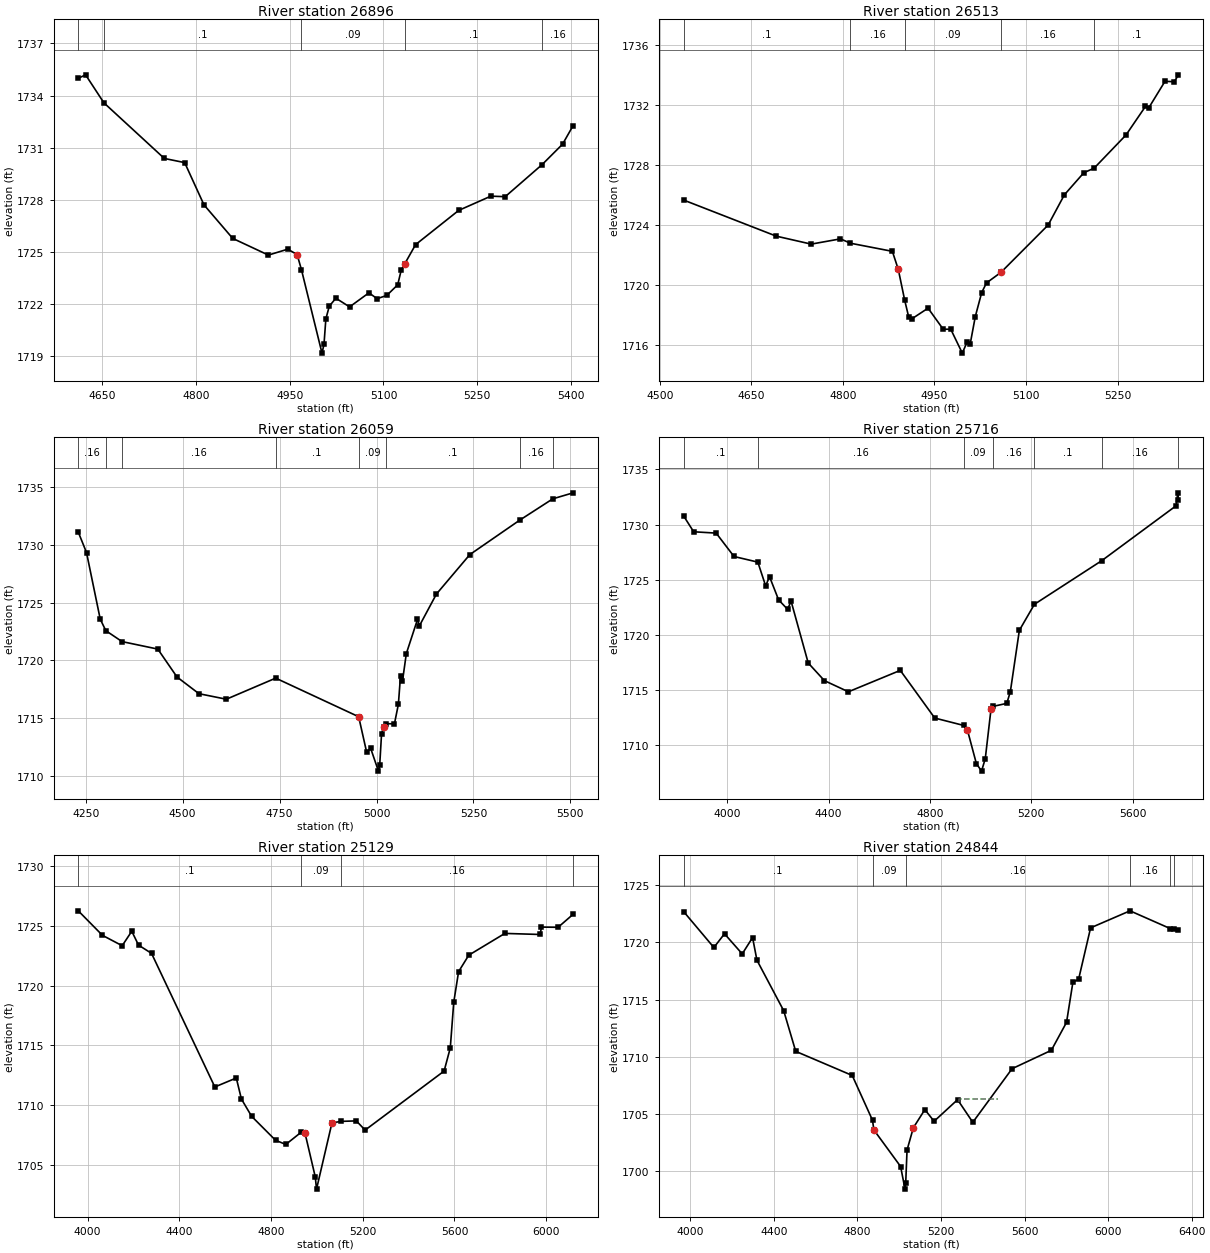
Type RM Length L Ch R = 1 ,26896   ,383,383,383
BEGIN DESCRIPTION:
MUESEBACH CREEK 51.0
END DESCRIPTION:
XS GIS Cut Line= 2
      2757418.29     10029318.61      2757748.02     10028598.41
#Sta/Elev= 30
  4611.5 1734.99  4623.2 1735.19  4652.5 1733.58  4749.2 1730.38  4781.8 1730.14
  4812.7 1727.71  4858.7 1725.78  4915.8 1724.82  4946.8 1725.16  4961.8 1724.85
  4968.8 1723.97  5001.6 1719.18  5004.8 1719.68  5007.8 1721.15  5013.3 1721.88
  5023.8 1722.34  5045.8 1721.84  5076.8 1722.65  5089.8 1722.31  5105.3  1722.5
  5122.8 1723.11  5128.4 1723.95  5133.8  1724.3  5151.4 1725.42  5220.4 1727.39
  5271.9 1728.21  5294.9 1728.18  5354.1 1730.03  5386.7  1731.2  5403.6 1732.27
#Mann= 5 ,-1 , 0
  4611.5     .05       0  4652.5      .1       0  4968.8     .09       0
  5133.8      .1       0  5354.1     .16       0
Bank Sta=4961.8,5133.8
XS Rating Curve= 0 ,0
Exp/Cntr=0.3,0.1

Type RM Length L Ch R = 1 ,26513   ,489,489,489
BEGIN DESCRIPTION:
MUESEBACH CREEK 50.0
END DESCRIPTION:
XS GIS Cut Line= 2
       2757808.9     10029388.09      2758060.13     10028617.08
#Sta/Elev= 30
    4539 1725.67  4690.8 1723.27    4748 1722.74    4796 1723.09  4812.3  1722.8
    4881 1722.26  4890.7 1721.06  4901.2 1719.01  4907.6 1717.92  4912.9 1717.77
  4939.5 1718.48  4964.3 1717.08  4976.7 1717.08  4995.6 1715.49  5003.4 1716.22
  5008.6 1716.11  5016.9 1717.92  5027.4 1719.52  5035.3 1720.16  5058.9 1720.86
  5136.3 1724.01  5162.9 1726.02  5194.8 1727.49  5211.6 1727.79  5263.9    1730
  5295.8  1731.9  5301.1  1731.8  5327.8 1733.57  5342.9 1733.54  5349.9    1734
#Mann= 5 ,-1 , 0
    4539      .1       0  4812.3     .16       0  4901.2     .09       0
  5058.9     .16       0  5211.6      .1       0
Bank Sta=4890.7,5058.9
XS Rating Curve= 0 ,0
Exp/Cntr=0.3,0.1

Type RM Length L Ch R = 1 ,26059   ,343,343,343
BEGIN DESCRIPTION:
MUESEBACH CREEK 49.0
END DESCRIPTION:
XS GIS Cut Line= 3
      2757995.44     10029510.75      2758384.35     10029125.32
       2758228.1     10028413.51
#Sta/Elev= 30
  4230.8 1731.12    4252 1729.35  4287.4 1723.57  4301.8 1722.57  4343.7 1721.62
  4435.9 1720.97  4485.4 1718.55    4542  1717.1  4612.7 1716.62    4740 1718.45
    4954  1715.1  4974.5 1712.03  4984.7 1712.38    5005 1710.38  5008.2 1710.88
    5013 1713.61  5018.1 1714.24  5025.7  1714.5  5046.2 1714.48  5056.4 1716.18
  5061.9 1718.64    5067  1718.2  5076.9 1720.58  5105.7 1723.54  5110.8    1723
  5154.6 1725.75  5240.7 1729.17    5369 1732.15  5454.7 1734.01  5507.1 1734.53
#Mann= 8 ,-1 , 0
  4230.8     .16       0  4301.8      .1       0  4343.7     .16       0
    4740      .1       0    4954     .09       0  5025.7      .1       0
    5369     .16       0  5454.7      .1       0
Bank Sta=4954,5018.1
XS Rating Curve= 0 ,0
Exp/Cntr=0.3,0.1

Type RM Length L Ch R = 1 ,25716   ,587,587,587
BEGIN DESCRIPTION:
MUESEBACH CREEK 48.0
END DESCRIPTION:
XS GIS Cut Line= 4
      2758023.24      10029903.1      2758526.71     10029083.65
      2758707.27     10028847.54      2758270.94     10028307.33
#Sta/Elev= 30
  3827.8 1730.78  3867.3 1729.35  3956.1 1729.23  4026.6 1727.11  4120.6  1726.6
  4151.4 1724.45  4166.8 1725.28  4202.6 1723.18  4237.8 1722.33    4252 1723.05
  4319.5 1717.46  4383.4 1715.86  4478.1 1714.85  4682.9 1716.79    4819 1712.47
  4933.3  1711.8  4947.8  1711.4  4983.2 1708.35  5003.7 1707.66  5018.5  1708.8
  5041.2  1713.3  5047.6 1713.52  5103.4  1713.8  5117.4 1714.86    5153 1720.42
  5212.5 1722.78  5478.1 1726.73  5771.9 1731.71  5778.3 1732.88  5781.2 1732.26
#Mann= 7 ,-1 , 0
  3827.8      .1       0  4120.6     .16       0  4933.3     .09       0
  5047.6     .16       0  5212.5      .1       0  5478.1     .16       0
  5781.2     .16       0
Bank Sta=4947.8,5041.2
XS Rating Curve= 0 ,0
Exp/Cntr=0.3,0.1

Type RM Length L Ch R = 1 ,25129   ,323,323,323
BEGIN DESCRIPTION:
MUESEBACH CREEK 47.0
END DESCRIPTION:
XS GIS Cut Line= 4
      2758189.88     10030021.17      2758676.02      10029677.4
      2758967.68     10029094.07      2758467.66     10028333.62
#Sta/Elev= 30
  3959.7 1726.25    4065  1724.2  4151.1 1723.33  4192.9 1724.54  4222.5 1723.38
  4279.1 1722.69  4555.1 1711.51  4648.7 1712.26    4671  1710.5  4715.7 1709.05
  4819.8 1707.05  4864.6  1706.7  4931.6 1707.72  4948.4 1707.64  4993.1 1703.98
  4998.5 1702.96  5065.8  1708.5  5104.9 1708.63    5172 1708.67  5210.5  1707.9
  5554.8 1712.84  5581.8 1714.78  5596.9  1718.6    5618 1721.16  5662.5 1722.54
  5819.8 1724.36  5973.5 1724.27  5979.5 1724.89  6051.8 1724.87  6117.4 1725.96
#Mann= 4 ,-1 , 0
  3959.7      .1       0  4931.6     .09       0  5104.9     .16       0
  6117.4     .16       0
Bank Sta=4948.4,5065.8
XS Rating Curve= 0 ,0
Exp/Cntr=0.3,0.1

Type RM Length L Ch R = 1 ,24844   ,689,689,689
BEGIN DESCRIPTION:
MUESEBACH CREEK 46.0
END DESCRIPTION:
XS GIS Cut Line= 4
      2758335.59      10030194.7      2758991.01      10029669.5
       2759151.6     10029244.15      2758574.91     10028337.92
#Sta/Elev= 30
  3968.4  1722.7    4113 1719.56  4163.9 1720.76  4248.7    1719  4298.3 1720.43
  4319.1 1718.45  4447.2 1714.03  4504.8 1710.47  4775.3 1708.36  4872.6 1704.43
  4878.6  1703.6  5006.9 1700.39    5028 1698.41  5031.2 1698.91  5037.7 1701.83
  5067.8 1703.78  5122.9 1705.37  5167.2 1704.35  5279.6 1706.24  5352.5 1704.26
  5540.4 1708.95  5728.4 1710.56  5801.2 1713.01  5831.7 1716.53  5858.8 1716.77
  5916.3 1721.28    6105 1722.77  6297.1 1721.22  6314.3 1721.16  6337.1 1721.13
#Mann= 6 ,-1 , 0
  3968.4      .1       0  4872.6     .09       0  5031.2     .16       0
    6105     .16       0  6297.1      .1       0  6314.3     .16       0
#XS Ineff= 1 ,-1
 5288.17 5472.39 1706.34
Permanent Ineff=
       F
Bank Sta=4878.6,5067.8
XS Rating Curve= 0 ,0
Exp/Cntr=0.3,0.1

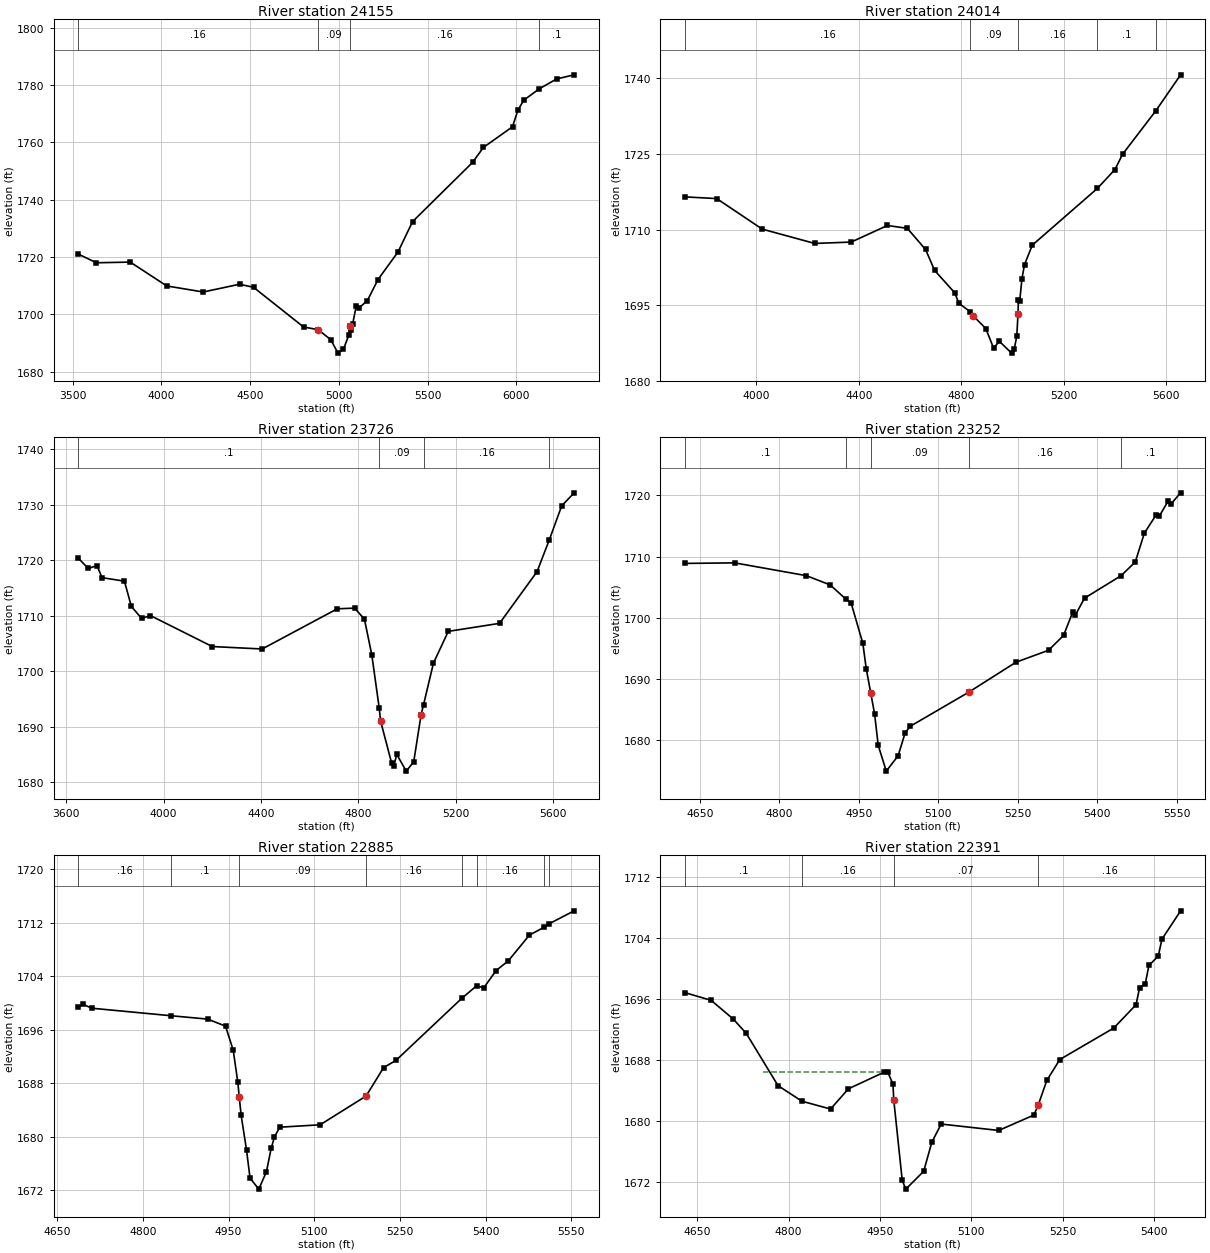
Type RM Length L Ch R = 1 ,24155   ,141,141,141
BEGIN DESCRIPTION:
Mapping XS 454c83f0
END DESCRIPTION:
XS GIS Cut Line= 3
      2758431.13     10030259.76      2759312.19     10029474.18
      2760887.76     10029126.95
#Sta/Elev= 30
    3532 1721.05  3633.8 1718.02  3824.5 1718.26  4030.1 1709.95  4235.8 1707.84
  4440.6 1710.55  4519.2 1709.48  4800.8 1695.66  4882.7 1694.72  4954.4 1691.24
  4995.1 1686.54  5026.1 1687.92  5056.8 1692.96  5062.4 1695.94  5067.6 1694.72
  5077.3 1696.57  5097.7 1702.91  5111.3  1702.2  5160.1 1704.78  5220.6 1712.19
  5333.2 1721.78  5415.2 1732.36  5753.1 1752.97  5814.5 1758.22  5978.4 1765.41
  6009.1 1771.24  6041.8 1774.67  6129.3 1778.64  6226.9 1782.07  6325.8 1783.51
#Mann= 4 ,-1 , 0
    3532     .16       0  4882.7     .09       0  5062.4     .16       0
  6129.3      .1       0
Bank Sta=4882.7,5062.4
XS Rating Curve= 0 ,0
Exp/Cntr=0.3,0.1

Type RM Length L Ch R = 1 ,24014   ,288,288,288
BEGIN DESCRIPTION:
MUESEBACH CREEK 45.0
END DESCRIPTION:
XS GIS Cut Line= 3
      2758598.83     10030230.07      2759345.38     10029579.01
      2760282.88     10029457.49
#Sta/Elev= 30
  3720.3 1716.47    3845 1716.13  4022.5 1710.08  4227.5 1707.24    4370 1707.51
  4511.4  1710.8  4589.2 1710.23  4660.4 1706.04  4695.6  1701.9  4774.5 1697.44
  4790.2 1695.39    4835 1693.69  4845.1 1692.94  4895.5 1690.38  4925.7 1686.52
  4948.7 1687.83  4996.1  1685.5  5006.4  1686.3  5016.5 1688.84 5021.31 1693.32
  5022.9 1696.02  5027.9 1695.78  5036.6 1700.23  5046.7 1703.05    5077  1706.9
  5331.2 1718.15  5399.7 1721.89  5429.9 1724.94  5559.3 1733.53  5656.2 1740.66
#Mann= 5 ,-1 , 0
  3720.3     .16       0    4835     .09       0 5021.31     .16       0
  5331.2      .1       0  5559.3     .16       0
Bank Sta=4845.1,5021.31
XS Rating Curve= 0 ,0
Exp/Cntr=0.3,0.1

Type RM Length L Ch R = 1 ,23726   ,474,474,474
BEGIN DESCRIPTION:
MUESEBACH CREEK 44.0
END DESCRIPTION:
XS GIS Cut Line= 3
      2758607.51      10030620.7      2759310.65     10029874.15
      2760308.88     10029709.23
#Sta/Elev= 30
  3649.8 1720.34  3690.7 1718.49  3726.3 1719.01  3747.3 1716.84  3839.2 1716.21
  3867.5 1711.68    3910  1709.5  3945.6 1710.03  4200.1 1704.45  4405.2 1704.01
  4713.7 1711.24  4784.6 1711.36  4825.2 1709.41  4855.6 1702.96    4886 1693.42
  4891.8 1691.04  4936.7 1683.56  4946.8 1683.02    4958 1685.06  4997.2 1682.04
  5027.9 1683.72  5058.3 1692.22  5068.4 1694.02    5109 1701.47  5169.8 1707.18
  5380.5 1708.62  5534.6 1717.92    5585 1723.65    5636 1729.77  5687.1  1732.1
#Mann= 4 ,-1 , 0
  3649.8      .1       0    4886     .09       0  5068.4     .16       0
    5585      .1       0
Bank Sta=4891.8,5058.3
XS Rating Curve= 0 ,0
Exp/Cntr=0.3,0.1

Type RM Length L Ch R = 1 ,23252   ,367,367,367
BEGIN DESCRIPTION:
MUESEBACH CREEK 43.0
END DESCRIPTION:
XS GIS Cut Line= 2
      2759406.12      10030438.4      2760248.18     10030030.39
#Sta/Elev= 30
  4621.4 1708.89  4715.4 1708.98  4850.9 1706.89    4896 1705.37  4925.7 1703.03
  4935.1 1702.47  4957.4 1695.84  4963.8 1691.71 4972.16  1687.8  4979.6 1684.31
  4986.4  1679.2  5001.6 1674.99    5024  1677.5  5037.1 1681.21  5046.3 1682.28
  5157.4 1687.88  5246.3 1692.76    5308 1694.72  5336.2 1697.14  5353.2 1700.88
  5358.7 1700.51  5375.8 1703.22  5444.8 1706.89  5471.6 1709.13  5488.6 1713.82
  5511.2 1716.85  5516.8 1716.59  5533.8  1719.1  5539.4 1718.65  5557.1 1720.41
#Mann= 5 ,-1 , 0
  4621.4      .1       0  4925.7     .16       0 4972.16     .09       0
  5157.4     .16       0  5444.8      .1       0
Bank Sta=4972.16,5157.4
XS Rating Curve= 0 ,0
Exp/Cntr=0.3,0.1

Type RM Length L Ch R = 1 ,22885   ,494,494,494
BEGIN DESCRIPTION:
MUESEBACH CREEK 42.0
END DESCRIPTION:
XS GIS Cut Line= 2
      2759675.21     10030742.22      2760421.81     10030299.47
#Sta/Elev= 30
    4687 1699.39  4695.2 1699.81  4710.8 1699.23  4848.7 1698.11  4913.5  1697.6
  4944.7 1696.55  4958.2 1692.92  4966.2 1688.13 4968.75 1685.89    4972 1683.21
  4981.4 1678.03  4987.6  1673.8  5002.9 1672.15  5016.3 1674.76  5024.6 1678.25
  5030.4 1679.98  5039.6 1681.42  5110.3 1681.78  5190.7 1686.08  5221.5 1690.35
  5242.9 1691.41    5358 1700.69  5384.1 1702.58  5396.9 1702.29  5418.3 1704.87
  5439.7 1706.32  5476.8 1710.19  5501.8 1711.32  5510.2 1711.83    5555 1713.81
#Mann= 8 ,-1 , 0
    4687     .16       0  4848.7      .1       0 4968.75     .09       0
  5190.7     .16       0    5358      .1       0  5384.1     .16       0
  5501.8      .1       0  5510.2     .16       0
Bank Sta=4968.75,5190.7
XS Rating Curve= 0 ,0
Exp/Cntr=0.3,0.1

Type RM Length L Ch R = 1 ,22391   ,423,423,423
BEGIN DESCRIPTION:
MUESEBACH CREEK 41.0
END DESCRIPTION:
XS GIS Cut Line= 2
      2760031.81     10031297.25      2760461.28     10030605.06
#Sta/Elev= 30
  4629.4 1696.81  4672.6  1695.8  4709.2 1693.33  4730.5 1691.45  4782.5 1684.62
  4821.9 1682.57  4868.9 1681.55  4898.2  1684.2  4956.1 1686.35  4963.1 1686.35
  4971.4  1684.8 4972.73 1682.72  4986.6 1672.21  4992.5 1671.05  5021.9 1673.39
  5035.2 1677.19  5050.6 1679.58  5145.1 1678.74  5202.9 1680.76  5210.2 1682.11
  5224.2  1685.3  5245.5 1688.04  5334.1 1692.16  5370.7 1695.22  5376.6 1697.44
    5386    1698  5391.9 1700.38  5407.3 1701.59  5413.2  1703.8    5444 1707.53
#Mann= 4 ,-1 , 0
  4629.4      .1       0  4821.9     .16       0 4972.73     .07       0
  5210.2     .16       0
#XS Ineff= 1 ,-1
 4758.52 4956.25 1686.42
Permanent Ineff=
       T
Bank Sta=4972.73,5210.2
XS Rating Curve= 0 ,0
Exp/Cntr=0.3,0.1

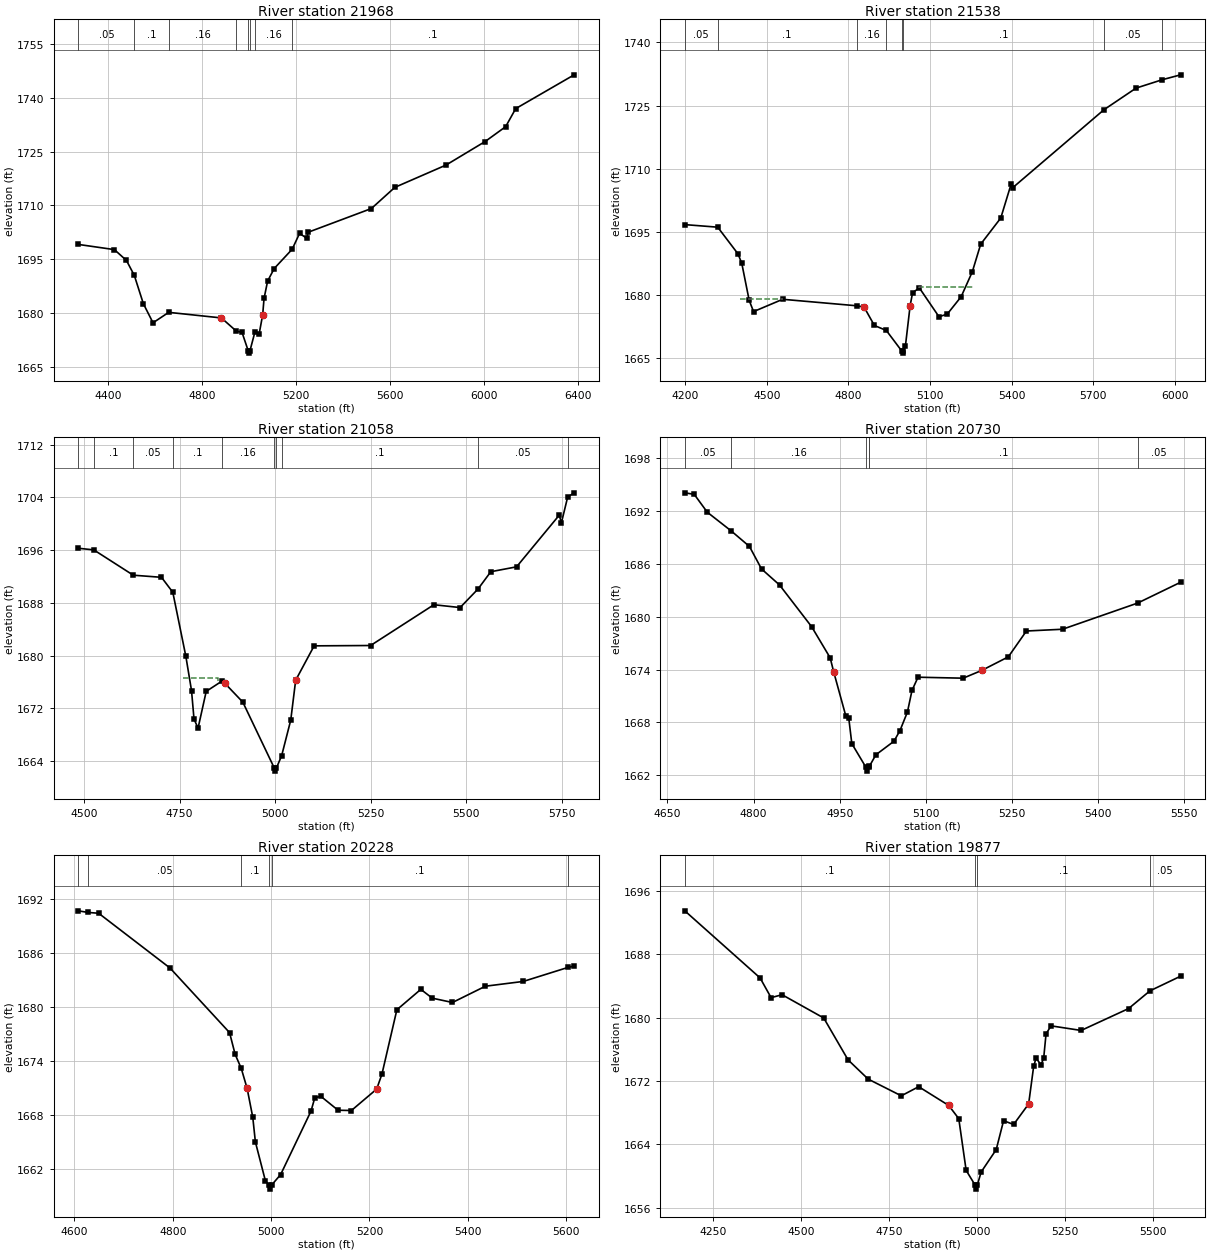
Type RM Length L Ch R = 1 ,21968   ,430,430,430
BEGIN DESCRIPTION:
MUESEBACH CREEK 40.0
END DESCRIPTION:
XS GIS Cut Line= 3
       2759999.1     10031448.79      2760489.58      10031331.6
      2761357.21      10029978.1
#Sta/Elev= 30
  4271.6 1699.12  4425.2 1697.67  4476.6 1694.64  4510.1 1690.46  4548.5 1682.58
  4589.7 1677.23  4656.6 1680.15    4881 1678.59  4944.7  1674.9  4968.9 1674.55
    4996 1669.26  4998.8 1668.76    5002 1669.26  5023.6 1674.62  5041.6 1674.05
  5056.8 1679.45  5062.7 1684.06  5077.9 1688.88  5105.9 1692.39  5182.5 1697.78
    5214 1702.21  5244.4 1700.84  5250.4 1702.52    5520 1709.15  5619.8 1715.06
  5837.9 1721.29  6004.4 1727.86  6091.8 1732.01  6134.6 1737.05  6383.6 1746.49
#Mann= 8 ,-1 , 0
  4271.6     .05       0  4510.1      .1       0  4656.6     .16       0
  4944.7      .1       0    4996     .07       0    5002      .1       0
  5023.6     .16       0  5182.5      .1       0
Bank Sta=4881,5056.8
XS Rating Curve= 0 ,0
Exp/Cntr=0.3,0.1

Type RM Length L Ch R = 1 ,21538   ,480,480,480
BEGIN DESCRIPTION:
MUESEBACH CREEK 39.0
END DESCRIPTION:
XS GIS Cut Line= 3
       2760107.6     10031544.28       2760706.6     10031409.72
      2761885.29     10031674.06
#Sta/Elev= 30
    4199 1696.75    4320 1696.14  4394.6 1689.79  4408.4 1687.55  4435.6 1678.75
  4451.7  1676.1  4558.6 1679.02  4830.9 1677.48  4857.5  1677.2  4895.7  1672.8
  4939.5 1671.62  4996.3 1666.74  4999.1 1666.24  5002.3 1666.74  5009.6  1667.9
 5026.99 1677.52    5036 1680.58  5060.8 1681.73    5133 1674.88  5163.3  1675.5
  5214.5 1679.64  5255.5 1685.56  5286.3 1692.11    5360 1698.31  5398.2  1706.4
  5403.3 1705.48  5739.1 1724.02  5857.2 1729.16    5953 1731.14  6020.9 1732.31
#Mann= 8 ,-1 , 0
    4199     .05       0    4320      .1       0  4830.9     .16       0
  4939.5      .1       0  4996.3     .07       0  5002.3      .1       0
  5739.1     .05       0    5953      .1       0
#XS Ineff= 2 ,-1
 4403.41 4558.24 1679.12 5059.66 5261.36 1681.83
Permanent Ineff=
       T       T
Bank Sta=4857.5,5026.99
XS Rating Curve= 0 ,0
Exp/Cntr=0.3,0.1

Type RM Length L Ch R = 1 ,21058   ,328,328,328
BEGIN DESCRIPTION:
MUESEBACH CREEK 38.0
END DESCRIPTION:
XS GIS Cut Line= 2
      2760083.93     10031618.05      2761303.47     10032060.73
#Sta/Elev= 30
  4485.2 1696.28  4525.7 1696.03    4629 1692.19  4702.8 1691.87  4732.4  1689.6
  4766.6 1679.86  4781.4 1674.67  4787.9 1670.35  4798.5 1668.99  4819.8 1674.56
  4861.5 1676.14  4867.9 1675.83  4915.6 1672.93  4997.7 1662.96  5000.4 1662.46
  5003.7 1662.96  5017.2  1664.8    5041  1670.2  5053.9 1676.25  5102.2 1681.47
  5249.9 1681.52  5415.6 1687.71  5484.2 1687.28  5531.1  1690.1  5564.5 1692.72
  5631.9 1693.46  5743.7 1701.31  5749.1 1700.11  5765.6 1704.05  5782.6 1704.69
#Mann= 10 ,-1 , 0
  4485.2     .05       0  4525.7      .1       0    4629     .05       0
  4732.4      .1       0  4861.5     .16       0  4997.7     .07       0
  5003.7     .16       0  5017.2      .1       0  5531.1     .05       0
  5765.6      .1       0
#XS Ineff= 1 ,-1
 4758.75 4851.82 1676.58
Permanent Ineff=
       T
Bank Sta=4867.9,5053.9
XS Rating Curve= 0 ,0
Exp/Cntr=0.3,0.1

Type RM Length L Ch R = 1 ,20730   ,502,502,502
BEGIN DESCRIPTION:
MUESEBACH CREEK 37.0
END DESCRIPTION:
XS GIS Cut Line= 2
       2760031.1     10031922.75      2760854.62     10032182.81
#Sta/Elev= 30
  4680.3 1694.04  4696.7 1693.87  4719.5 1691.84  4761.3 1689.71  4792.9 1687.96
  4813.9 1685.41  4845.3 1683.59  4901.2 1678.86  4933.5 1675.33  4939.7 1673.72
  4960.6 1668.77  4965.9 1668.48  4971.2  1665.6  4995.2 1662.98    4998 1662.48
  5001.2 1662.98    5002 1663.05  5013.1 1664.33  5044.6 1665.87  5055.1 1667.08
  5068.1 1669.19    5076 1671.63  5086.5 1673.13  5165.1 1673.02  5197.5  1673.9
  5243.8 1675.44  5275.3 1678.37  5338.2 1678.57  5469.1 1681.54  5543.9  1683.9
#Mann= 6 ,-1 , 0
  4680.3     .05       0  4761.3     .16       0  4995.2     .07       0
  5001.2     .16       0    5002      .1       0  5469.1     .05       0
Bank Sta=4939.7,5197.5
XS Rating Curve= 0 ,0
Exp/Cntr=0.3,0.1

Type RM Length L Ch R = 1 ,20228   ,351,351,351
BEGIN DESCRIPTION:
MUESEBACH CREEK 36.0
END DESCRIPTION:
XS GIS Cut Line= 2
      2759918.27     10032591.17      2760899.16      10032356.8
#Sta/Elev= 30
  4607.8 1690.67  4627.6 1690.49  4649.1  1690.4  4794.3 1684.31  4915.4 1677.13
  4926.7 1674.72  4939.2 1673.15 4951.14 1670.92  4962.6 1667.72  4967.9 1664.98
  4988.4 1660.63  4995.7 1660.23  4998.4 1659.73  5001.7 1660.23  5019.3 1661.35
    5081  1668.4  5088.9 1669.91  5101.5 1670.03  5136.1  1668.5  5163.2 1668.47
  5214.6 1670.85  5225.4 1672.53  5255.7 1679.67  5304.4 1681.94  5327.7 1680.96
  5368.8 1680.48  5435.8 1682.29  5512.8 1682.82  5603.2 1684.37  5616.3 1684.53
#Mann= 6 ,-1 , 0
  4607.8      .1       0  4627.6     .05       0  4939.2      .1       0
  4995.7     .07       0  5001.7      .1       0  5603.2     .05       0
Bank Sta=4951.14,5214.6
XS Rating Curve= 0 ,0
Exp/Cntr=0.3,0.1

Type RM Length L Ch R = 1 ,19877   ,427,427,427
BEGIN DESCRIPTION:
MUESEBACH CREEK 35.0
END DESCRIPTION:
XS GIS Cut Line= 3
      2759785.91     10032707.48       2760358.8     10032905.38
      2760957.74     10032374.14
#Sta/Elev= 30
  4170.9 1693.49  4384.5 1685.02  4415.7 1682.53  4446.9  1682.9  4565.1 1679.96
    4634 1674.68  4691.1 1672.25  4785.1 1670.14  4834.5 1671.29  4919.8 1668.92
  4948.2 1667.25  4969.1 1660.73  4994.6 1658.86  4997.3 1658.36  5000.6 1658.86
  5011.8 1660.53  5054.4 1663.35  5075.3    1667  5103.8 1666.52  5146.4 1669.11
  5160.6 1673.84  5167.3 1674.89  5181.6 1674.06  5189.1  1674.9  5195.8 1677.96
    5210 1678.97  5295.3 1678.39  5429.9 1681.15  5490.6 1683.39  5577.6 1685.24
#Mann= 4 ,-1 , 0
  4170.9      .1       0  4994.6     .07       0  5000.6      .1       0
  5490.6     .05       0
Bank Sta=4919.8,5146.4
XS Rating Curve= 0 ,0
Exp/Cntr=0.3,0.1