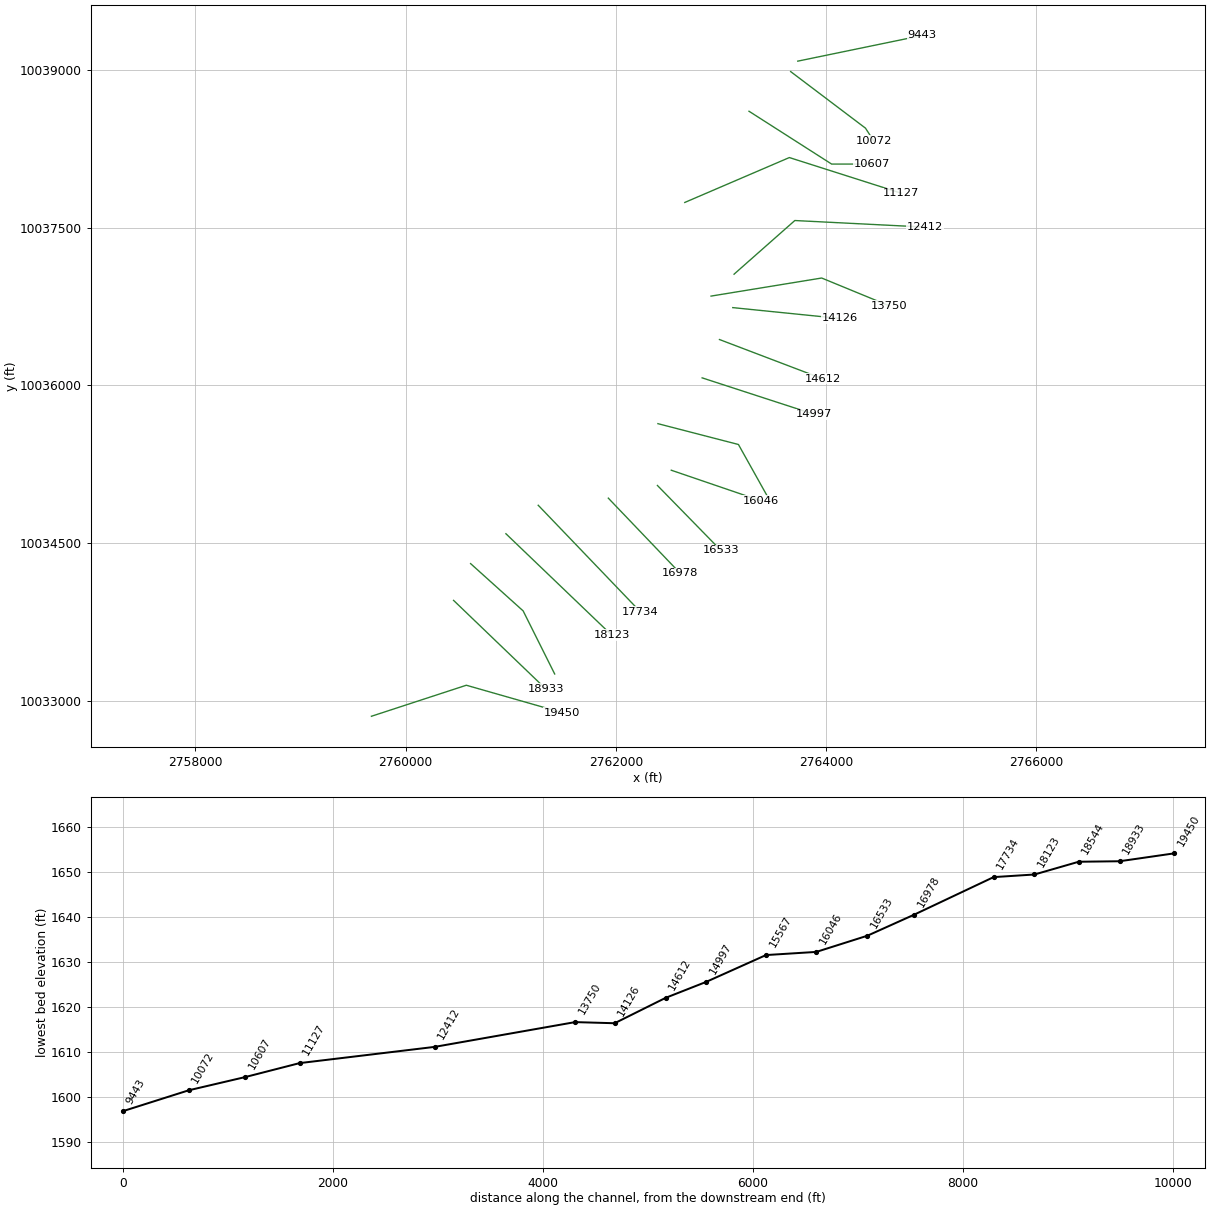
HEC-RAS study MUESEBACH CREEK.prj: MUESEBACH CREEK Base Level Engineering

--- MUESEBACH CREEK.g01 (geometry) --- (continued)

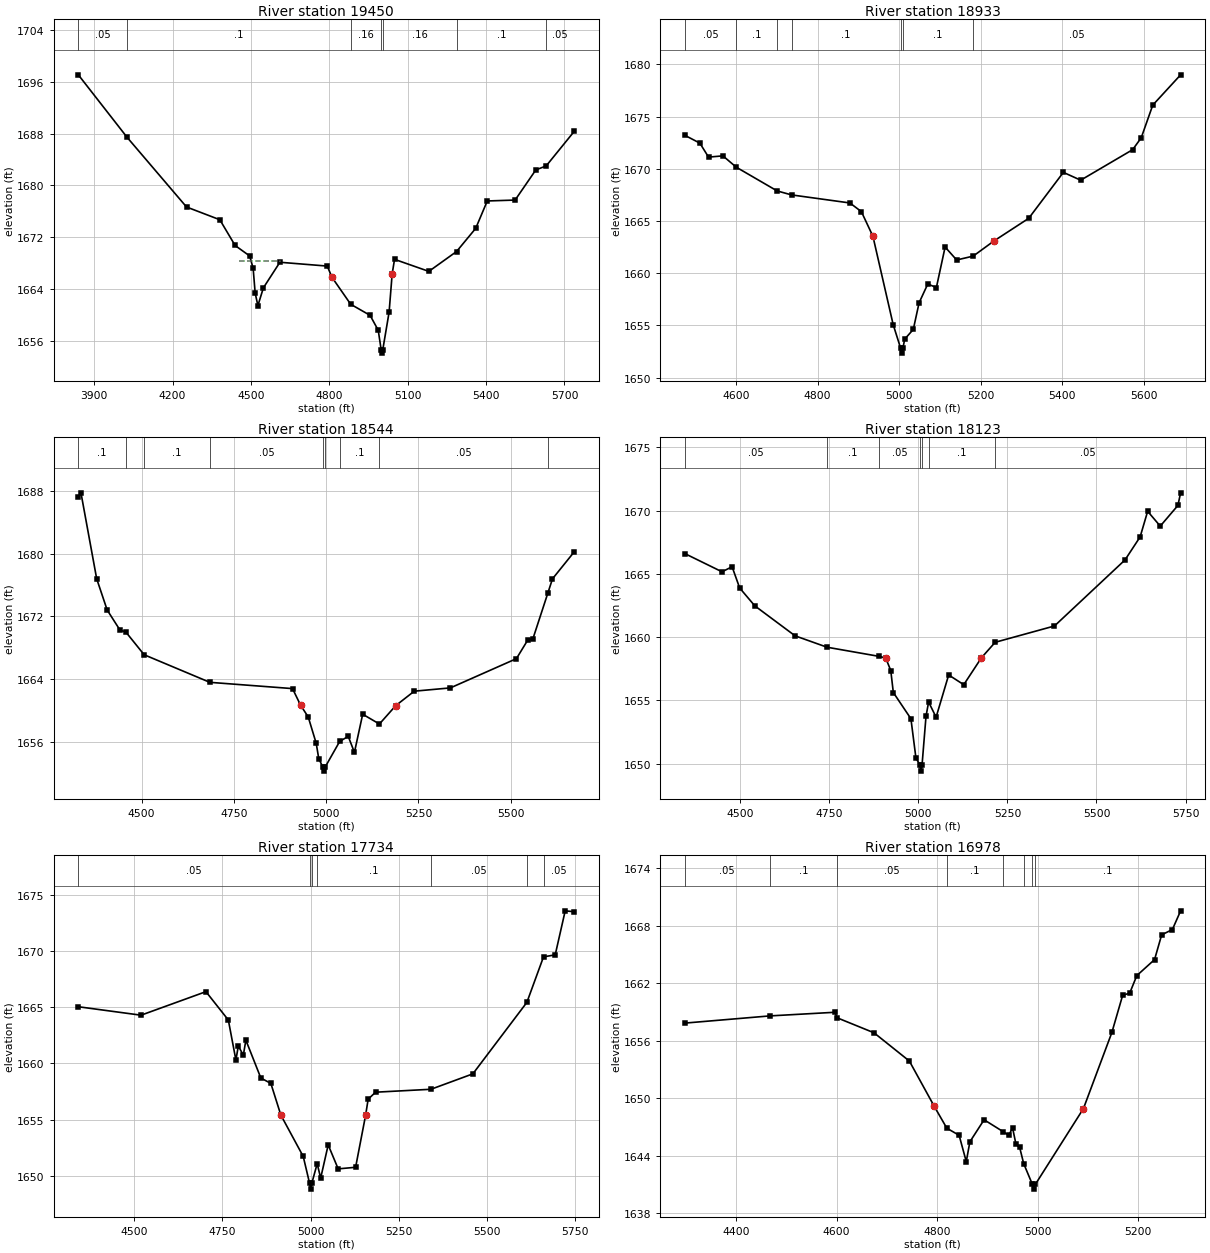
Type RM Length L Ch R = 1 ,19450   ,517,517,517
BEGIN DESCRIPTION:
MUESEBACH CREEK 34.0
END DESCRIPTION:
XS GIS Cut Line= 3
      2759675.21     10032851.57      2760578.02     10033146.72
      2761489.51     10032886.29
#Sta/Elev= 30
  3839.2 1697.09  4026.3 1687.41  4253.3 1676.67  4380.8  1674.7  4439.3 1670.72
  4494.9 1669.11  4508.3  1667.2    4516 1663.38  4526.5 1661.43  4547.5 1664.18
  4610.7 1668.13  4791.9 1667.54  4810.3 1665.79  4881.7 1661.64  4955.9 1659.93
  4987.1 1657.62  4998.4 1654.59  5001.2 1654.09  5004.4 1654.59  5028.7 1660.42
  5040.4 1666.33  5049.5 1668.58  5180.8 1666.72  5286.9 1669.79  5360.2 1673.37
  5404.4  1677.6    5511 1677.74  5590.3  1682.4  5629.8 1683.01    5737 1688.34
#Mann= 7 ,-1 , 0
  3839.2     .05       0  4026.3      .1       0  4881.7     .16       0
  4998.4     .07       0  5004.4     .16       0  5286.9      .1       0
  5629.8     .05       0
#XS Ineff= 1 ,-1
 4455.97  4610.8 1668.34
Permanent Ineff=
       T
Bank Sta=4810.3,5040.4
XS Rating Curve= 0 ,0
Exp/Cntr=0.3,0.1

Type RM Length L Ch R = 1 ,18933   ,389,389,389
BEGIN DESCRIPTION:
MUESEBACH CREEK 33.0
END DESCRIPTION:
XS GIS Cut Line= 2
      2760456.51     10033953.99      2761333.25     10033111.97
#Sta/Elev= 30
  4474.6 1673.21  4511.5 1672.46  4532.8 1671.12  4568.1 1671.24  4600.6 1670.16
  4701.1 1667.88  4736.5  1667.5  4879.4 1666.73  4907.5  1665.9  4935.8 1663.54
  4985.4 1655.09  5003.5 1652.85  5006.3 1652.35  5009.5 1652.85  5013.7 1653.69
  5034.8 1654.62    5049 1657.17  5070.3 1658.97  5091.4 1658.63  5112.8 1662.51
  5141.1 1661.27  5181.6 1661.64  5232.9  1663.1  5317.8 1665.26  5402.7 1669.66
  5445.2 1668.91  5572.5 1671.83  5593.6 1672.97  5621.9  1676.1  5690.2    1679
#Mann= 7 ,-1 , 0
  4474.6     .05       0  4600.6      .1       0  4701.1     .05       0
  4736.5      .1       0  5003.5     .07       0  5009.5      .1       0
  5181.6     .05       0
Bank Sta=4935.8,5232.9
XS Rating Curve= 0 ,0
Exp/Cntr=0.3,0.1

Type RM Length L Ch R = 1 ,18544   ,421,421,421
BEGIN DESCRIPTION:
MUESEBACH CREEK 32.0
END DESCRIPTION:
XS GIS Cut Line= 3
      2760618.48     10034303.72      2761118.47     10033853.73
      2761418.47     10033253.72
#Sta/Elev= 30
  4328.4 1687.16  4335.5 1687.75  4378.1 1676.79  4406.5  1672.8  4441.6 1670.21
  4456.8 1670.01  4506.7 1667.09  4684.8 1663.57  4908.8 1662.77  4930.4 1660.67
  4951.4 1659.14    4973 1655.78  4979.8 1653.85    4991 1652.74  4993.7 1652.24
    4997 1652.74  5036.7 1656.04  5059.8 1656.67  5076.5 1654.63  5098.9  1659.5
  5144.2 1658.25  5188.3 1660.59  5238.6 1662.44  5336.5 1662.86  5515.4 1666.59
  5546.1 1668.96  5560.1 1669.12  5600.7 1674.97  5613.2 1676.78  5671.9 1680.21
#Mann= 9 ,-1 , 0
  4328.4      .1       0  4456.8     .05       0  4506.7      .1       0
  4684.8     .05       0    4991     .04       0    4997     .05       0
  5036.7      .1       0  5144.2     .05       0  5600.7      .1       0
Bank Sta=4930.4,5188.3
XS Rating Curve= 0 ,0
Exp/Cntr=0.3,0.1

Type RM Length L Ch R = 1 ,18123   ,389,389,389
BEGIN DESCRIPTION:
MUESEBACH CREEK 31.0
END DESCRIPTION:
XS GIS Cut Line= 2
      2760954.56     10034587.66      2761959.75     10033624.14
#Sta/Elev= 30
  4343.9  1666.6  4448.4 1665.16  4476.7 1665.56    4498 1663.88  4540.5 1662.47
  4653.7  1660.1  4743.5  1659.2  4889.2 1658.48  4908.1 1658.35  4922.3 1657.36
  4929.5 1655.62  4978.9 1653.55    4993 1650.44  5004.2 1649.91  5006.9 1649.41
  5010.2 1649.91  5021.3 1653.75  5028.6 1654.87  5049.6 1653.67  5084.9 1657.01
  5127.3 1656.24    5177 1658.37  5215.5 1659.59  5382.1 1660.88  5580.2  1666.1
  5622.6 1667.92  5643.7 1669.94  5679.1 1668.77  5728.6  1670.4  5736.3  1671.4
#Mann= 7 ,-1 , 0
  4343.9     .05       0  4743.5      .1       0  4889.2     .05       0
  5004.2     .04       0  5010.2     .05       0  5028.6      .1       0
  5215.5     .05       0
Bank Sta=4908.1,5177
XS Rating Curve= 0 ,0
Exp/Cntr=0.3,0.1

Type RM Length L Ch R = 1 ,17734   ,756,756,756
BEGIN DESCRIPTION:
MUESEBACH CREEK 30.0
END DESCRIPTION:
XS GIS Cut Line= 2
      2761261.88     10034858.47      2762234.62     10033844.11
#Sta/Elev= 30
  4341.5 1665.03  4519.2 1664.28  4703.2 1666.37  4766.7 1663.85  4788.1  1660.3
    4795 1661.54  4809.2 1660.73  4816.4 1662.06  4858.8  1658.7  4887.2 1658.22
  4915.5 1655.41    4979 1651.73  4997.1 1649.33  4999.8 1648.83  5003.1 1649.33
  5018.5 1651.09  5028.4 1649.81  5049.7 1652.76    5078 1650.63  5127.4 1650.77
  5155.7 1655.38    5163 1656.82    5184 1657.44    5341  1657.7  5459.8 1659.07
  5612.9 1665.42    5660 1669.46  5693.2 1669.64  5721.5 1673.55  5746.9 1673.47
#Mann= 7 ,-1 , 0
  4341.5     .05       0  4997.1     .04       0  5003.1     .05       0
  5018.5      .1       0    5341     .05       0  5612.9      .1       0
    5660     .05       0
Bank Sta=4915.5,5155.7
XS Rating Curve= 0 ,0
Exp/Cntr=0.3,0.1

Type RM Length L Ch R = 1 ,16978   ,445,445,445
BEGIN DESCRIPTION:
MUESEBACH CREEK 29.0
END DESCRIPTION:
XS GIS Cut Line= 2
      2761928.53     10034926.19      2762610.79     10034212.69
#Sta/Elev= 30
  4297.6 1657.83  4466.5 1658.58  4596.3 1658.96  4601.1 1658.38  4674.3 1656.82
  4744.7 1653.87  4794.4 1649.13  4819.3 1646.86  4843.8 1646.12    4858 1643.37
  4865.2 1645.44  4893.5 1647.74  4931.4  1646.5  4942.9 1646.11  4950.1 1646.92
    4957 1645.18  4964.3 1644.86  4972.3 1643.17  4989.6    1641  4992.3  1640.5
  4995.6    1641  5091.3 1648.91  5147.9 1656.85  5169.3 1660.72  5183.5 1660.97
  5197.6 1662.79  5232.9 1664.46    5247 1667.04  5268.4  1667.6  5284.8 1669.55
#Mann= 8 ,-1 , 0
  4297.6     .05       0  4466.5      .1       0  4601.1     .05       0
  4819.3      .1       0  4931.4     .05       0  4972.3      .1       0
  4989.6     .07       0  4995.6      .1       0
Bank Sta=4794.4,5091.3
XS Rating Curve= 0 ,0
Exp/Cntr=0.3,0.1

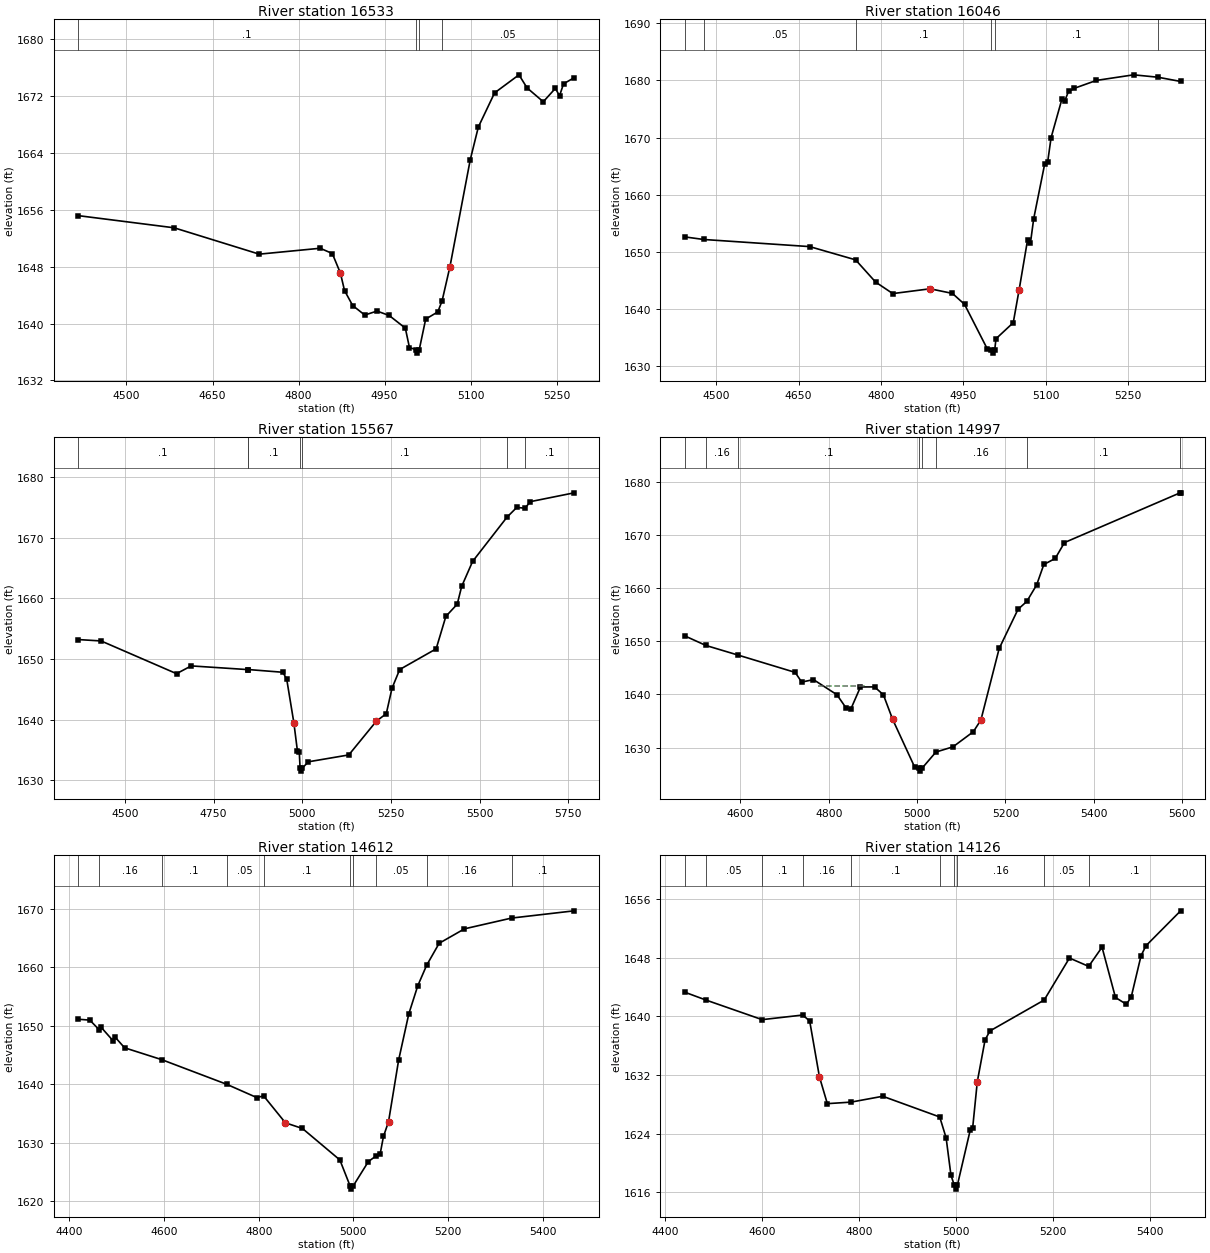
Type RM Length L Ch R = 1 ,16533   ,487,487,487
BEGIN DESCRIPTION:
MUESEBACH CREEK 28.0
END DESCRIPTION:
XS GIS Cut Line= 2
      2762395.51     10035046.89      2762999.68     10034428.83
#Sta/Elev= 30
  4416.1 1655.18  4583.1 1653.47  4731.5 1649.76  4837.7 1650.59  4858.8 1649.85
    4873 1647.08  4880.1 1644.64  4894.3 1642.53  4915.4 1641.19  4936.7 1641.75
  4957.9 1641.13  4986.1 1639.35  4993.3 1636.61  5004.4 1636.33  5007.2 1635.83
  5010.4 1636.33  5021.6 1640.62  5042.7 1641.63  5050.2 1643.19  5063.9 1648.01
  5099.3 1663.06  5113.4 1667.66  5141.7 1672.46  5184.2    1675  5198.3 1673.16
  5226.6 1671.21  5247.7  1673.1  5254.9 1672.04  5261.9 1673.74  5280.4 1674.59
#Mann= 4 ,-1 , 0
  4416.1      .1       0  5004.4     .07       0  5010.4      .1       0
  5050.2     .05       0
Bank Sta=4873,5063.9
XS Rating Curve= 0 ,0
Exp/Cntr=0.3,0.1

Type RM Length L Ch R = 1 ,16046   ,479,479,479
BEGIN DESCRIPTION:
MUESEBACH CREEK 27.0
END DESCRIPTION:
XS GIS Cut Line= 2
      2762527.43     10035191.84      2763381.61     10034900.18
#Sta/Elev= 30
    4443 1652.59  4477.1 1652.14  4670.3 1650.89  4753.9 1648.57  4790.3 1644.68
  4821.6 1642.66  4889.5  1643.5  4930.2 1642.69  4952.2 1640.78  4993.6 1632.98
  5001.1 1632.73  5003.9 1632.23  5007.1 1632.73  5009.5 1634.75  5040.9 1637.56
  5051.7 1643.37  5066.9 1652.02  5072.2 1651.51  5078.1 1655.76  5098.2 1665.39
  5103.5 1665.68  5109.8 1669.98  5129.6 1676.76  5134.8 1676.46  5141.5 1678.06
  5152.1 1678.62  5192.2    1680  5260.1 1680.98  5304.3 1680.56  5345.6 1679.82
#Mann= 6 ,-1 , 0
    4443      .1       0  4477.1     .05       0  4753.9      .1       0
  5001.1     .07       0  5007.1      .1       0  5304.3     .05       0
Bank Sta=4889.5,5051.7
XS Rating Curve= 0 ,0
Exp/Cntr=0.3,0.1

Type RM Length L Ch R = 1 ,15567   ,570,570,570
BEGIN DESCRIPTION:
MUESEBACH CREEK 26.0
END DESCRIPTION:
XS GIS Cut Line= 3
      2762400.44     10035634.56      2763166.09     10035436.63
      2763462.04     10034907.03
#Sta/Elev= 30
    4369 1653.21  4433.2 1652.98  4645.8 1647.59  4687.2 1648.87  4846.8 1648.26
    4848 1648.27  4945.4 1647.82  4956.3 1646.69  4976.4 1639.53  4986.6 1634.82
  4991.7 1634.74    4994 1632.03  4996.8 1631.53    5000 1632.03  5017.7 1633.07
  5131.3  1634.2    5209 1639.76    5237    1641    5253 1645.17  5274.7 1648.27
  5377.5 1651.68  5404.9 1657.03  5436.9 1659.04  5449.5 1661.98  5480.3 1666.09
  5577.1 1673.37  5604.8 1674.99  5628.3 1674.85  5642.5 1675.93  5766.5 1677.39
#Mann= 7 ,-1 , 0
    4369      .1       0  4846.8     .16       0    4848      .1       0
    4994     .07       0    5000      .1       0  5577.1     .05       0
  5628.3      .1       0
Bank Sta=4976.4,5209
XS Rating Curve= 0 ,0
Exp/Cntr=0.3,0.1

Type RM Length L Ch R = 1 ,14997   ,385,385,385
BEGIN DESCRIPTION:
MUESEBACH CREEK 25.0
END DESCRIPTION:
XS GIS Cut Line= 2
      2762820.83     10036070.32      2763888.59     10035723.08
#Sta/Elev= 30
  4473.9 1650.99  4521.7 1649.19  4594.6 1647.38  4723.8 1644.13  4738.6 1642.31
  4765.3 1642.77  4818.4 1639.93  4839.7 1637.37    4850 1637.26  4871.7 1641.39
  4903.6  1641.4  4923.6 1639.92  4944.6 1635.29  4994.2 1626.37  5004.7 1626.07
  5007.5 1625.57  5010.7 1626.07  5042.6 1629.16  5081.3 1630.14  5127.2 1632.97
  5144.4 1635.17  5185.8 1648.62  5228.5 1655.99  5248.3 1657.46  5270.6 1660.56
  5286.9 1664.41  5312.7 1665.54  5333.7 1668.53  5595.5 1677.88  5596.7 1677.88
#Mann= 8 ,-1 , 0
  4473.9      .1       0  4521.7     .16       0  4594.6      .1       0
  5004.7     .07       0  5010.7      .1       0  5042.6     .16       0
  5248.3      .1       0  5595.5     .05       0
#XS Ineff= 1 ,-1
 4775.68 4879.32 1641.63
Permanent Ineff=
       T
Bank Sta=4944.6,5144.4
XS Rating Curve= 0 ,0
Exp/Cntr=0.3,0.1

Type RM Length L Ch R = 1 ,14612   ,486,486,486
BEGIN DESCRIPTION:
MUESEBACH CREEK 24.0
END DESCRIPTION:
XS GIS Cut Line= 2
       2762985.8     10036434.89      2763965.09     10036062.24
#Sta/Elev= 30
  4418.8 1651.09  4443.1 1650.94  4462.4 1649.33    4467 1649.71  4491.8 1647.45
  4497.1 1647.98  4516.5 1646.21  4595.1 1644.18  4732.3 1639.97  4796.1 1637.69
  4810.3 1637.99  4856.4 1633.38  4892.4 1632.41  4971.5 1627.03  4993.3 1622.54
    4996 1622.04  4999.3 1622.54  5031.7 1626.75  5047.5 1627.69  5056.5    1628
  5063.6 1631.05  5074.3 1633.56  5095.7 1644.12  5117.1 1651.99  5136.1 1656.81
  5154.8 1660.31  5181.3 1664.08  5234.8 1666.55  5334.2 1668.39  5466.6 1669.63
#Mann= 10 ,-1 , 0
  4418.8      .1       0  4462.4     .16       0  4595.1      .1       0
  4732.3     .05       0  4810.3      .1       0  4993.3     .07       0
  4999.3      .1       0  5047.5     .05       0  5154.8     .16       0
  5334.2      .1       0
Bank Sta=4856.4,5074.3
XS Rating Curve= 0 ,0
Exp/Cntr=0.3,0.1

Type RM Length L Ch R = 1 ,14126   ,376,376,376
BEGIN DESCRIPTION:
MUESEBACH CREEK 23.0
END DESCRIPTION:
XS GIS Cut Line= 2
      2763112.22     10036738.48      2764129.71     10036635.44
#Sta/Elev= 30
  4440.3 1643.31  4484.3 1642.23  4599.9 1639.56  4683.6 1640.19  4697.9 1639.37
    4718 1631.74  4734.3 1628.08  4783.2 1628.29  4848.6 1629.09  4966.1 1626.26
  4979.3 1623.41  4989.3 1618.29  4996.4  1616.9  4999.1  1616.4  5002.4  1616.9
  5028.9 1624.43    5034 1624.73 5043.64 1631.09  5059.7 1636.81  5069.8 1638.02
  5181.6 1642.24  5233.7 1647.98  5273.3 1646.84  5300.9 1649.46  5328.6 1642.59
  5351.2 1641.65  5361.2 1642.68  5381.3 1648.28  5391.4 1649.65    5463 1654.43
#Mann= 10 ,-1 , 0
  4440.3     .05       0  4484.3     .05       0  4599.9      .1       0
  4683.6     .16       0  4783.2      .1       0  4966.1     .16       0
  4996.4     .07       0  5002.4     .16       0  5181.6     .05       0
  5273.3      .1       0
Bank Sta=4718,5043.64
XS Rating Curve= 0 ,0
Exp/Cntr=0.3,0.1

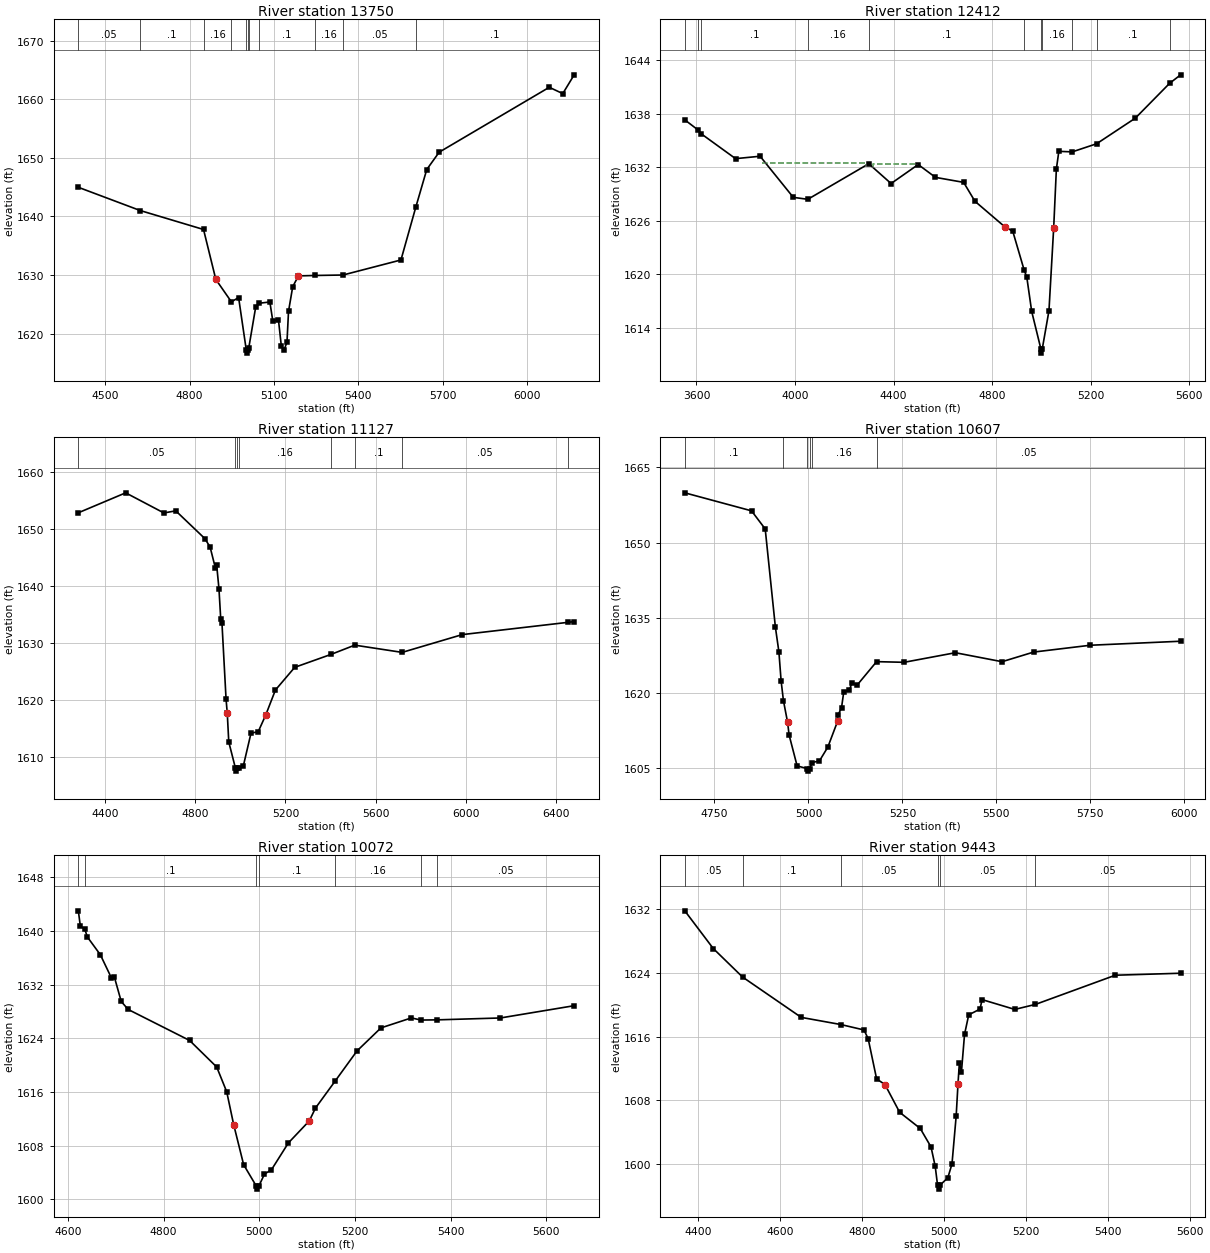
Type RM Length L Ch R = 1 ,13750   ,1338,1338,1338
BEGIN DESCRIPTION:
MUESEBACH CREEK 22.0
END DESCRIPTION:
XS GIS Cut Line= 3
      2762905.65     10036848.09      2763957.75     10037019.97
      2764603.52     10036754.37
#Sta/Elev= 30
    4404 1644.99  4624.1 1641.02  4849.5 1637.78  4893.2 1629.25  4948.7 1625.41
  4974.3 1626.15  5001.7 1617.15  5004.4 1616.65  5007.7 1617.15  5010.3 1617.49
  5035.1 1624.52  5046.3 1625.17  5085.5 1625.39  5095.9 1622.18  5116.1 1622.33
  5126.3 1617.88  5136.4 1617.19  5146.5 1618.59  5151.9 1623.79  5166.8 1627.99
  5187.1 1629.85  5246.5 1629.92  5345.8    1630    5552 1632.57  5604.9 1641.61
  5643.8 1648.03    5688 1650.99  6079.8 1662.08  6127.8    1661  6168.3 1664.21
#Mann= 11 ,-1 , 0
    4404     .05       0  4624.1      .1       0  4849.5     .16       0
  4948.7      .1       0  5001.7     .07       0  5007.7      .1       0
  5010.3     .16       0  5046.3      .1       0  5246.5     .16       0
  5345.8     .05       0  5604.9      .1       0
Bank Sta=4893.2,5187.1
XS Rating Curve= 0 ,0
Exp/Cntr=0.3,0.1

Type RM Length L Ch R = 1 ,12412   ,1285,1285,1285
BEGIN DESCRIPTION:
Mapping XS 15148a96
END DESCRIPTION:
XS GIS Cut Line= 3
      2763124.43     10037056.43      2763702.55     10037566.84
      2764942.17     10037504.34
#Sta/Elev= 30
  3552.6 1637.31  3604.3 1636.22  3620.1 1635.73  3758.6 1632.96  3858.2 1633.23
  3992.9 1628.62  4051.8  1628.4  4299.3 1632.39  4389.8 1630.17  4499.9  1632.3
    4570 1630.86  4684.3  1630.3  4730.2 1628.18  4850.4 1625.34  4883.7 1624.82
  4930.4 1620.42  4940.5  1619.7  4960.5 1615.83  4997.6 1611.65  5000.3 1611.15
  5003.6 1611.65  5030.6  1615.9 5049.72 1625.16  5060.7  1631.8  5070.7 1633.78
  5125.1 1633.72  5224.1 1634.63  5381.1  1637.5  5520.4 1641.41    5565 1642.36
#Mann= 11 ,-1 , 0
  3552.6      .1       0  3604.3     .05       0  3620.1      .1       0
  4051.8     .16       0  4299.3      .1       0  4930.4     .16       0
  4997.6     .07       0  5003.6     .16       0  5125.1     .05       0
  5224.1      .1       0  5520.4     .05       0
#XS Ineff= 2 ,-1
 3865.06 4286.93 1632.47 4316.76 4494.32 1632.34
Permanent Ineff=
       T       T
Bank Sta=4850.4,5049.72
XS Rating Curve= 0 ,0
Exp/Cntr=0.3,0.1

Type RM Length L Ch R = 1 ,11127   ,520,520,520
BEGIN DESCRIPTION:
MUESEBACH CREEK 21.0
END DESCRIPTION:
XS GIS Cut Line= 3
      2762655.71     10037738.73      2763650.46      10038165.8
      2764712.98     10037827.25
#Sta/Elev= 30
  4282.3 1652.87  4492.1 1656.37  4661.6 1652.84  4714.2 1653.21  4842.9 1648.35
  4866.4 1646.86    4890 1643.13  4895.4 1643.71  4905.6 1639.56  4913.5 1634.21
    4919 1633.46  4937.1 1620.17  4942.5 1617.67  4949.1 1612.67  4978.8 1608.05
  4981.5 1607.55  4984.8 1608.05    4994 1608.17  5013.2 1608.39  5047.6  1614.2
  5079.7 1614.48  5112.4 1617.34  5155.9 1621.78  5241.5 1625.76  5402.5 1628.03
  5507.5 1629.65  5717.5 1628.38  5984.1  1631.5  6452.5 1633.65    6480 1633.78
#Mann= 8 ,-1 , 0
  4282.3     .05       0  4978.8     .07       0  4984.8     .05       0
    4994     .16       0  5402.5     .05       0  5507.5      .1       0
  5717.5     .05       0  6452.5      .1       0
Bank Sta=4942.5,5112.4
XS Rating Curve= 0 ,0
Exp/Cntr=0.3,0.1

Type RM Length L Ch R = 1 ,10607   ,535,535,535
BEGIN DESCRIPTION:
MUESEBACH CREEK 20.0
END DESCRIPTION:
XS GIS Cut Line= 3
      2763266.72     10038606.18      2764052.45     10038103.83
      2764438.85     10038103.83
#Sta/Elev= 30
    4671 1659.91  4848.5 1656.32  4884.9 1652.71    4912 1633.13  4921.3 1628.23
  4927.2 1622.43  4933.4 1618.48 4944.43 1614.19  4948.4 1611.66  4969.8 1605.48
    4997 1604.94  4999.7 1604.44    5003 1604.94  5009.7 1606.15  5029.2 1606.48
  5051.5 1609.23 5077.27 1614.34  5078.6 1615.61  5087.9 1617.07  5093.8 1620.21
  5109.1 1620.63    5115 1621.92  5130.2 1621.66  5181.2 1626.26  5254.5 1626.13
  5390.7 1628.04    5515 1626.25    5599 1628.17  5749.6 1629.53    5990 1630.33
#Mann= 6 ,-1 , 0
    4671      .1       0  4933.4     .05       0    4997    .035       0
    5003     .05       0  5009.7     .16       0  5181.2     .05       0
Bank Sta=4944.43,5077.27
XS Rating Curve= 0 ,0
Exp/Cntr=0.3,0.1

Type RM Length L Ch R = 1 ,10072   ,629,629,629
BEGIN DESCRIPTION:
MUESEBACH CREEK 19.0
END DESCRIPTION:
XS GIS Cut Line= 3
      2763662.87     10038983.51       2764374.7      10038445.3
      2764452.84     10038323.75
#Sta/Elev= 30
  4621.6    1643  4625.9 1640.67  4634.8 1640.32  4640.5  1639.1  4667.6 1636.46
  4690.4 1633.06  4696.7  1633.2  4711.3 1629.49  4725.8  1628.3  4854.3 1623.68
    4911 1619.72  4931.9 1616.03  4946.4 1611.15  4967.3 1605.16  4993.4 1602.02
  4996.1 1601.52  4999.4 1602.02  5010.9 1603.77  5025.5 1604.41  5060.9 1608.41
  5104.6 1611.69  5117.5  1613.6  5158.4  1617.6  5204.4 1622.12  5254.4 1625.55
  5318.1 1627.04  5338.1 1626.72  5372.6 1626.75  5504.1 1627.03  5658.5 1628.86
#Mann= 7 ,-1 , 0
  4621.6     .05       0  4634.8      .1       0  4993.4     .07       0
  4999.4      .1       0  5158.4     .16       0  5338.1      .1       0
  5372.6     .05       0
Bank Sta=4946.4,5104.6
XS Rating Curve= 0 ,0
Exp/Cntr=0.3,0.1

Type RM Length L Ch R = 1 ,9443    ,221,221,221
BEGIN DESCRIPTION:
MUESEBACH CREEK 18.0
END DESCRIPTION:
XS GIS Cut Line= 2
      2763730.46     10039082.76      2764914.48     10039327.28
#Sta/Elev= 30
  4367.5 1631.79  4436.9 1627.06  4508.4 1623.48  4651.4 1618.42  4748.2 1617.52
  4804.5 1616.84  4814.7 1615.73  4835.2  1610.7  4855.6 1609.99  4891.4 1606.51
  4941.6 1604.48  4967.9 1602.16  4978.1 1599.73  4983.8 1597.37  4986.5 1596.87
  4989.8 1597.37  5008.8 1598.29    5019 1600.03  5029.2 1606.04 5033.64 1610.07
    5037 1612.69  5042.1  1611.6  5049.6 1616.29  5059.8 1618.74  5087.3 1619.46
  5092.4 1620.65  5172.1 1619.42  5222.6 1620.05  5417.2 1623.71  5576.5 1623.96
#Mann= 6 ,-1 , 0
  4367.5     .05       0  4508.4      .1       0  4748.2     .05       0
  4983.8     .07       0  4989.8     .05       0  5222.6     .05       0
Bank Sta=4855.6,5033.64
XS Rating Curve= 0 ,0
Exp/Cntr=0.3,0.1