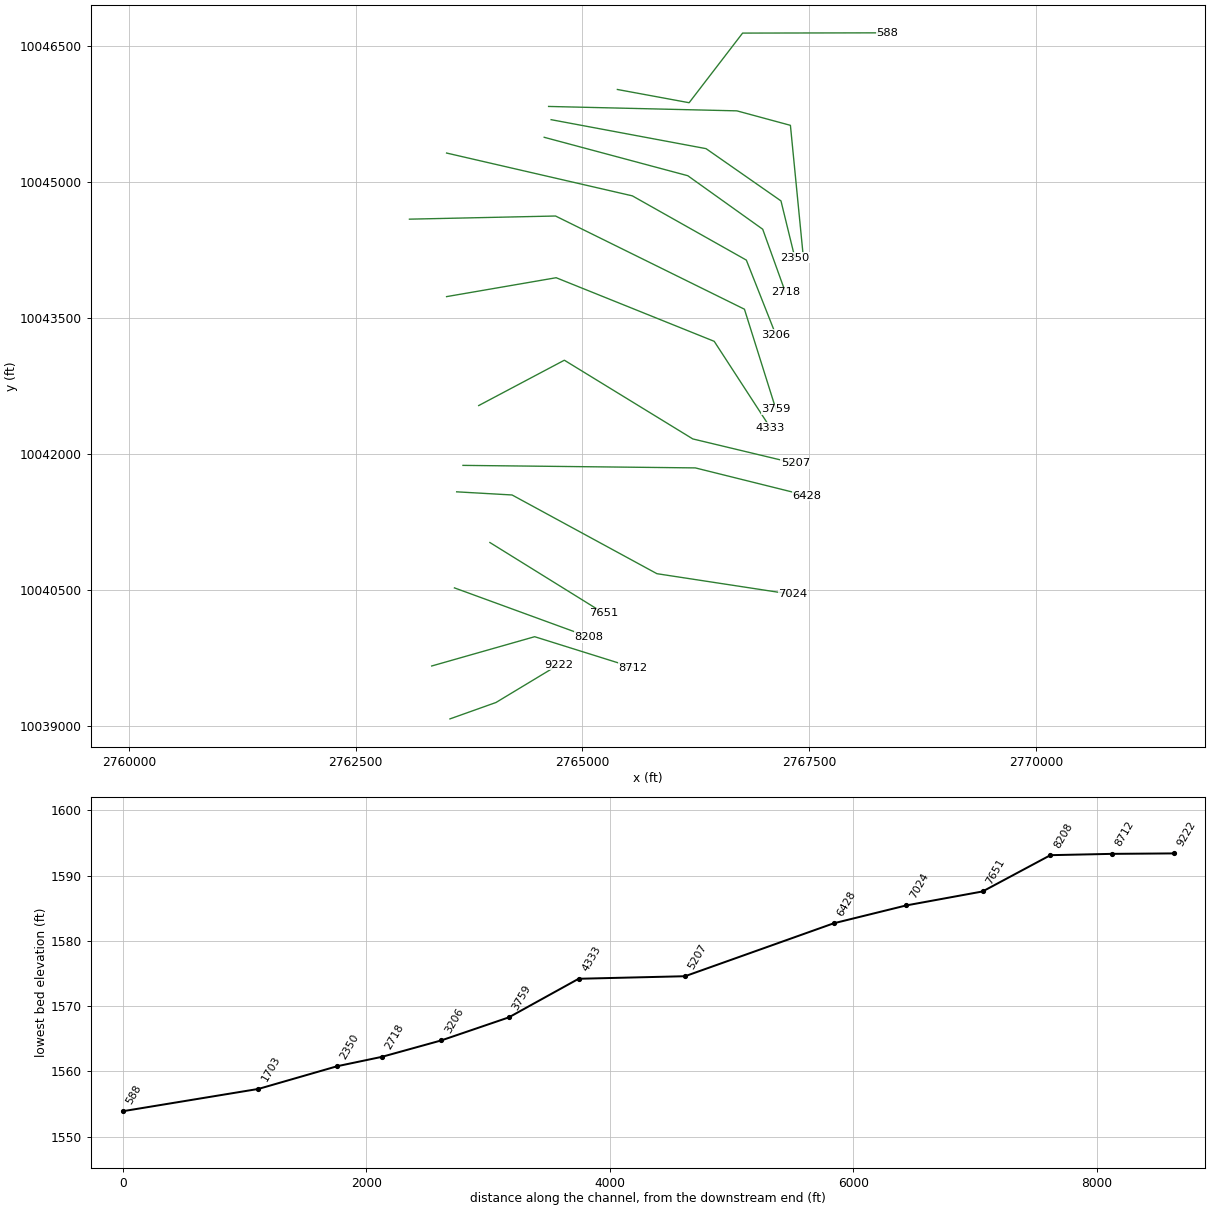
HEC-RAS study MUESEBACH CREEK.prj: MUESEBACH CREEK Base Level Engineering

--- MUESEBACH CREEK.g01 (geometry) --- (continued)

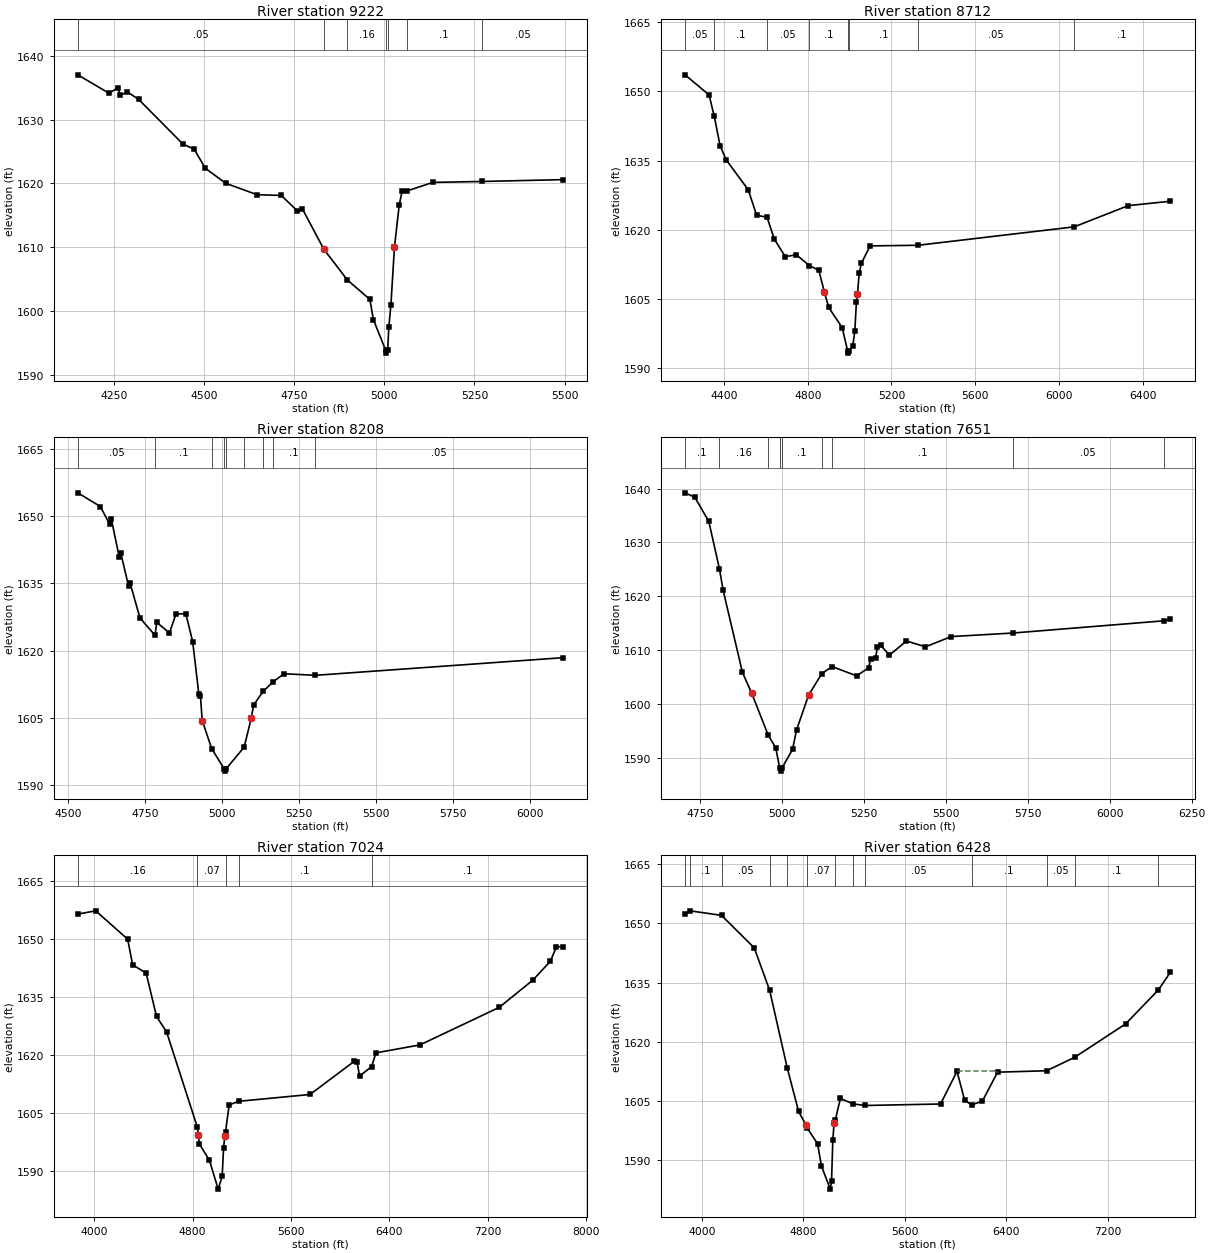
Type RM Length L Ch R = 1 ,9222    ,510,510,510
BEGIN DESCRIPTION:
MUESEBACH CREEK 17.0
END DESCRIPTION:
XS GIS Cut Line= 3
      2763539.32     10039080.72       2764046.3     10039261.29
      2764737.23     10039677.93
#Sta/Elev= 30
  4150.5 1637.02  4236.9 1634.14  4262.4    1635  4267.7 1633.78  4287.6 1634.34
  4318.8 1633.19  4442.1 1626.15  4472.9 1625.38  4503.7 1622.39  4560.1 1620.03
  4647.2 1618.23  4714.6 1618.11  4758.3 1615.73  4772.9 1616.02  4832.4 1609.69
  4897.9 1604.85  4960.2 1601.81  4969.9 1598.64  5003.5 1593.89  5006.2 1593.39
  5009.5 1593.89  5012.6 1597.44  5018.5 1600.99  5028.2 1609.98  5041.5 1616.62
  5049.5  1618.8  5062.1  1618.8    5135 1620.16  5270.4  1620.3  5495.5 1620.59
#Mann= 7 ,-1 , 0
  4150.5     .05       0  4832.4      .1       0  4897.9     .16       0
  5003.5     .07       0  5009.5     .16       0  5062.1      .1       0
  5270.4     .05       0
Bank Sta=4832.4,5028.2
XS Rating Curve= 0 ,0
Exp/Cntr=0.3,0.1

Type RM Length L Ch R = 1 ,8712    ,504,504,504
BEGIN DESCRIPTION:
MUESEBACH CREEK 16.0
END DESCRIPTION:
XS GIS Cut Line= 3
      2763337.96     10039664.06      2764473.38     10039986.98
      2765560.21      10039646.7
#Sta/Elev= 30
  4213.3 1653.55  4328.2 1649.19  4352.9 1644.54    4381 1638.16  4409.7 1635.16
  4515.3 1628.67  4555.5 1623.14    4605 1622.74  4640.1 1617.97  4692.1 1614.21
  4745.7 1614.59  4807.6 1612.27  4852.5 1611.27  4879.2 1606.55    4900  1603.2
  4964.5 1598.82  4990.2 1593.82    4993 1593.32  4996.2 1593.82  5014.4 1594.76
  5024.8 1598.12  5032.3 1604.37  5037.5 1606.08  5045.6 1610.62  5055.9 1612.74
  5097.5 1616.53  5326.6 1616.66  6073.4 1620.65  6331.7 1625.24  6532.6 1626.19
#Mann= 8 ,-1 , 0
  4213.3     .05       0  4352.9      .1       0    4605     .05       0
  4807.6      .1       0  4990.2     .07       0  4996.2      .1       0
  5326.6     .05       0  6073.4      .1       0
Bank Sta=4879.2,5037.5
XS Rating Curve= 0 ,0
Exp/Cntr=0.3,0.1

Type RM Length L Ch R = 1 ,8208    ,557,557,557
BEGIN DESCRIPTION:
MUESEBACH CREEK 15.0
END DESCRIPTION:
XS GIS Cut Line= 2
      2763588.74     10040525.38      2765070.04     10039984.39
#Sta/Elev= 30
  4531.3 1655.16  4604.6 1652.11  4635.1 1648.12  4640.5 1649.26  4665.7 1640.91
    4671 1641.76  4696.2 1634.39  4701.6 1634.95  4733.3 1627.27  4782.3 1623.39
  4787.9 1626.27  4829.1 1623.94  4850.4 1628.13  4882.3 1628.23  4904.7 1621.98
  4924.6 1610.33  4929.9 1609.88  4935.6  1604.4  4966.4 1598.16  5007.1 1593.62
  5009.8 1593.12  5013.1 1593.62  5071.9 1598.46  5095.3 1604.98  5102.6 1607.86
  5134.1 1610.92  5165.8 1613.01  5201.7 1614.83  5303.7 1614.48  6108.3 1618.41
#Mann= 9 ,-1 , 0
  4531.3     .05       0  4782.3      .1       0  4966.4     .16       0
  5007.1     .07       0  5013.1     .16       0  5071.9      .1       0
  5134.1     .16       0  5165.8      .1       0  5303.7     .05       0
Bank Sta=4935.6,5095.3
XS Rating Curve= 0 ,0
Exp/Cntr=0.3,0.1

Type RM Length L Ch R = 1 ,7651    ,627,627,627
BEGIN DESCRIPTION:
MUESEBACH CREEK 14.0
END DESCRIPTION:
XS GIS Cut Line= 2
       2763979.7     10041025.62      2765238.44     10040244.33
#Sta/Elev= 30
    4703  1639.2    4733 1638.37  4775.5 1633.88  4807.9  1625.1  4819.2 1621.13
  4878.1 1605.89  4906.6    1602  4956.8 1594.24  4979.8 1591.89  4992.2 1588.06
  4994.9 1587.56  4998.2 1588.06  5031.1 1591.58  5043.6 1595.24  5080.2 1601.66
  5120.7 1605.66  5151.9 1606.96  5226.7 1605.24  5263.3 1606.72  5269.2 1608.29
  5284.5 1608.58  5290.4 1610.53  5299.9 1610.94    5327 1609.08    5379 1611.71
  5436.9 1610.63    5516 1612.53  5702.9 1613.18  6164.6 1615.45  6184.5  1615.7
#Mann= 9 ,-1 , 0
    4703      .1       0  4807.9     .16       0  4956.8      .1       0
  4992.2     .07       0  4998.2      .1       0  5120.7     .16       0
  5151.9      .1       0  5702.9     .05       0  6164.6      .1       0
Bank Sta=4906.6,5080.2
XS Rating Curve= 0 ,0
Exp/Cntr=0.3,0.1

Type RM Length L Ch R = 1 ,7024    ,596,596,596
BEGIN DESCRIPTION:
MUESEBACH CREEK 13.0
END DESCRIPTION:
XS GIS Cut Line= 4
      2763613.27     10041584.68      2764224.34     10041549.96
      2765821.56      10040681.9      2767321.54     10040452.74
#Sta/Elev= 30
  3865.7 1656.36  4011.1  1657.2  4271.5 1649.88  4311.6 1643.29  4421.8 1641.12
  4506.1 1629.96  4587.8 1625.97  4838.6 1601.36  4846.7 1599.42  4854.8 1597.06
  4936.5 1592.86  5007.5 1585.42  5040.1 1588.68  5051.5 1595.96  5061.9 1599.24
  5067.6 1600.22    5097 1607.14  5173.7 1608.07  5754.6 1609.83  6114.7 1618.38
  6136.6 1618.29  6158.4 1614.58  6256.3 1617.04    6291 1620.56  6649.6 1622.62
    7294  1632.3  7567.1 1639.31  7710.4  1644.2  7759.3 1647.94    7813 1647.94
#Mann= 5 ,-1 , 0
  3865.7     .16       0  4838.6     .07       0  5067.6     .16       0
  5173.7      .1       0  6256.3      .1       0
Bank Sta=4846.7,5061.9
XS Rating Curve= 0 ,0
Exp/Cntr=0.3,0.1

Type RM Length L Ch R = 1 ,6428    ,1221,1221,1221
BEGIN DESCRIPTION:
MUESEBACH CREEK 12.0
END DESCRIPTION:
XS GIS Cut Line= 3
       2763682.7     10041876.34      2766245.17     10041848.57
      2767473.85     10041543.13
#Sta/Elev= 30
  3865.8 1652.48    3905 1653.19  4153.4 1652.04  4411.6 1643.81    4533 1633.07
  4671.6 1613.46  4761.6 1602.35  4821.6 1598.83  4831.6 1598.07  4911.6 1594.15
  4941.6 1588.58  5011.4 1582.68  5021.6 1584.67  5031.6 1595.01  5041.6 1599.44
  5051.6 1600.26  5091.6 1605.65  5190.3 1604.29    5287 1603.87  5881.7 1604.25
  6011.7 1612.52  6071.7 1605.22  6126.4    1604  6211.7 1604.97  6331.7 1612.31
  6718.2 1612.67  6938.8 1616.05  7341.7 1624.53  7600.2 1633.13  7694.5  1637.6
#Mann= 13 ,-1 , 0
  3865.8     .05       0    3905      .1       0  4153.4     .05       0
    4533      .1       0  4671.6     .16       0  4831.6     .07       0
  5051.6     .16       0  5190.3      .1       0    5287     .05       0
  6126.4      .1       0  6718.2     .05       0  6938.8      .1       0
  7600.2     .05       0
#XS Ineff= 1 ,-1
 6011.36  6326.7 1612.54
Permanent Ineff=
       T
Bank Sta=4821.6,5041.6
XS Rating Curve= 0 ,0
Exp/Cntr=0.3,0.1

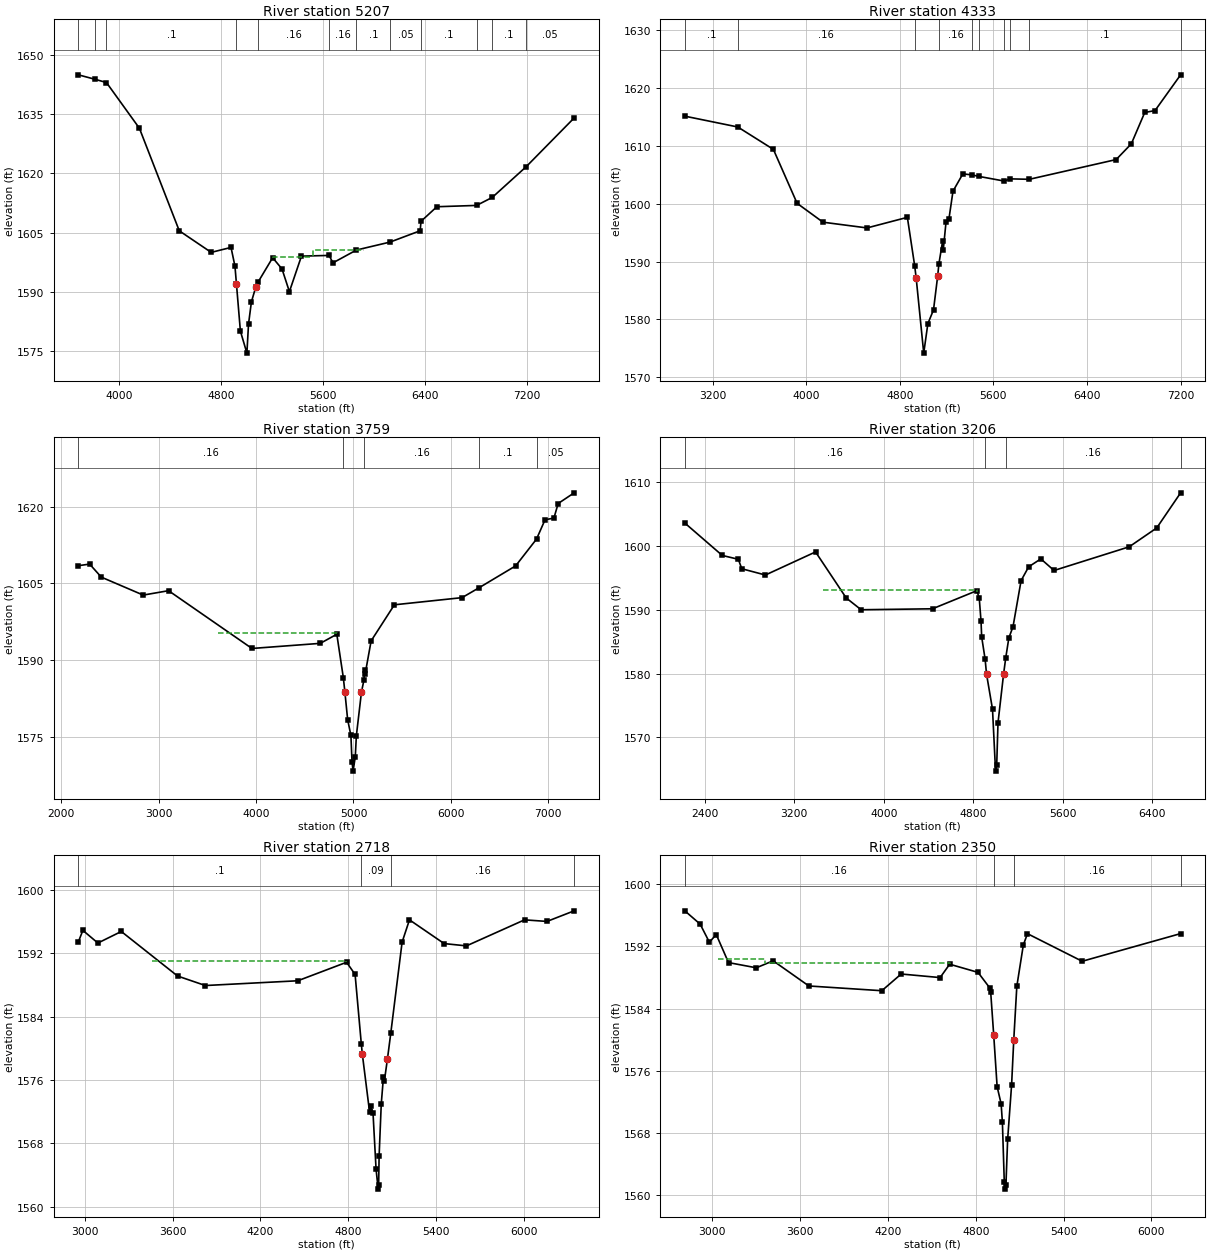
Type RM Length L Ch R = 1 ,5207    ,874,874,874
BEGIN DESCRIPTION:
MUESEBACH CREEK 10.0
END DESCRIPTION:
XS GIS Cut Line= 4
      2763856.26     10042536.05      2764800.72     10043036.07
      2766217.39     10042168.01      2767349.32     10041897.18
#Sta/Elev= 30
  3679.8 1644.87  3806.8 1643.78  3900.7 1642.92  4159.5 1631.37  4472.5 1605.47
  4723.3 1600.02    4879 1601.27  4909.9 1596.53  4921.7    1592  4952.5 1580.14
  5003.6 1574.57  5016.4 1581.91    5039  1587.5  5074.4 1591.39  5089.8 1592.43
  5205.9 1598.67  5279.4 1595.83  5337.4  1590.1  5432.1 1599.07  5648.9 1599.25
  5679.7 1597.38  5863.7 1600.61  6128.8 1602.63  6364.3 1605.48  6371.2 1607.87
  6495.6 1611.55  6807.3 1611.88  6930.5  1613.9  7196.7 1621.65  7573.8 1633.98
#Mann= 12 ,-1 , 0
  3679.8      .1       0  3806.8     .16       0  3900.7      .1       0
  4921.7     .07       0  5089.8     .16       0  5648.9     .16       0
  5863.7      .1       0  6128.8     .05       0  6371.2      .1       0
  6807.3     .05       0  6930.5      .1       0  7196.7     .05       0
#XS Ineff= 2 ,-1
 5210.23    5500 1598.94 5519.89  5923.3 1600.74
Permanent Ineff=
       T       T
Bank Sta=4921.7,5074.4
XS Rating Curve= 0 ,0
Exp/Cntr=0.3,0.1

Type RM Length L Ch R = 1 ,4333    ,574,574,574
BEGIN DESCRIPTION:
MUESEBACH CREEK 8.0
END DESCRIPTION:
XS GIS Cut Line= 4
      2763502.09     10043737.45      2764710.45     10043945.79
       2766453.5      10043244.4      2767071.57       10042293.
#Sta/Elev= 30
  2961.2 1615.12  3414.2 1613.25  3718.6 1609.38  3921.5 1600.06  4142.8  1596.8
  4519.4 1595.81  4864.3 1597.64  4926.7 1589.28  4939.8 1587.12  5004.2 1574.18
  5039.5 1579.27  5087.8 1581.65    5123 1587.42  5133.8 1589.59  5165.7 1593.54
  5171.1 1591.99  5195.3 1596.92  5219.5 1597.33  5254.4 1602.16  5338.6 1605.15
  5417.5 1604.97    5476 1604.71  5694.4  1603.9  5738.7 1604.29    5907 1604.21
  6649.5 1607.62  6779.3 1610.34    6894 1615.76  6981.7 1616.08  7200.8 1622.26
#Mann= 10 ,-1 , 0
  2961.2      .1       0  3414.2     .16       0  4926.7     .09       0
  5133.8     .16       0  5417.5      .1       0    5476     .16       0
  5694.4      .1       0  5738.7     .16       0    5907      .1       0
  7200.8     .05       0
Bank Sta=4939.8,5123
XS Rating Curve= 0 ,0
Exp/Cntr=0.3,0.1

Type RM Length L Ch R = 1 ,3759    ,553,553,553
BEGIN DESCRIPTION:
MUESEBACH CREEK 7.0
END DESCRIPTION:
XS GIS Cut Line= 4
       2763092.4     10044591.62       2764703.5     10044626.34
      2766786.84     10043598.57      2767133.76     10042495.36
#Sta/Elev= 30
  2174.7 1608.44  2290.8 1608.75  2410.8  1606.2  2840.9 1602.69    3101 1603.55
  3957.5 1592.25  4659.1 1593.25  4828.7 1595.03  4895.6 1586.55  4911.6 1583.73
  4940.2 1578.29  4973.4 1575.25  4984.8 1570.11  4995.6 1568.26  5018.3 1571.06
  5029.5 1575.19 5081.82 1583.74  5107.5  1586.1  5113.7 1588.03  5119.3 1587.23
  5181.1 1593.74  5419.7 1600.79  6114.4 1602.19  6292.5 1604.16  6664.7  1608.4
  6879.2 1613.64  6966.7 1617.42  7057.8 1617.75  7101.5  1620.6  7265.7 1622.69
#Mann= 5 ,-1 , 0
  2174.7     .16       0  4895.6     .09       0  5107.5     .16       0
  6292.5      .1       0  6879.2     .05       0
#XS Ineff= 1 ,-1
  3612.5 4829.55 1595.31
Permanent Ineff=
       T
Bank Sta=4911.6,5081.82
XS Rating Curve= 0 ,0
Exp/Cntr=0.3,0.1

Type RM Length L Ch R = 1 ,3206    ,488,488,488
BEGIN DESCRIPTION:
MUESEBACH CREEK 6.0
END DESCRIPTION:
XS GIS Cut Line= 4
      2763502.07      10045320.8      2765550.72     10044848.57
      2766807.67     10044140.23      2767133.77     10043314.57
#Sta/Elev= 30
    2221 1603.53    2556 1598.46  2699.6 1597.86  2730.4 1596.38  2941.7  1595.4
    3390 1599.01  3664.3 1591.81  3797.7 1589.97  4435.6 1590.12  4831.9 1592.95
  4853.6 1591.78  4869.5 1588.14  4875.2 1585.73  4906.2 1582.21  4918.6 1579.91
  4972.1 1574.41  4999.2 1564.74  5009.5 1565.63  5021.2  1572.3 5071.02  1579.9
  5089.9  1582.4    5118 1585.55  5155.6 1587.34  5227.6 1594.53  5295.7 1596.69
  5404.1 1597.92  5522.5 1596.11  6194.1 1599.81  6440.2 1602.76  6653.9 1608.25
#Mann= 4 ,-1 , 0
    2221     .16       0  4906.2     .09       0  5089.9     .16       0
  6653.9     .05       0
#XS Ineff= 1 ,-1
 3454.55 4835.23  1593.1
Permanent Ineff=
       T
Bank Sta=4918.6,5071.02
XS Rating Curve= 0 ,0
Exp/Cntr=0.3,0.1

Type RM Length L Ch R = 1 ,2718    ,368,368,368
BEGIN DESCRIPTION:
MUESEBACH CREEK 5.0
END DESCRIPTION:
XS GIS Cut Line= 4
      2764578.51      10045494.4      2766161.84     10045070.79
      2766988.22     10044480.51      2767237.74     10043787.42
#Sta/Elev= 30
  2954.6 1593.46  2985.6 1594.92  3088.3 1593.32  3248.5 1594.78  3633.4 1589.15
  3823.3 1587.95  4455.5 1588.55  4789.3 1590.89  4847.5 1589.35  4890.1 1580.56
  4896.7 1579.32  4946.6 1571.96  4955.2 1572.67    4970 1571.87  4990.9 1564.75
  5005.4 1562.22  5008.6 1562.72  5011.7 1566.37  5026.5    1573  5041.2 1576.33
  5047.4 1575.85  5068.7 1578.66  5091.6 1581.93    5169 1593.43  5219.4 1596.25
  5456.6 1593.25  5609.2 1592.96  6006.4 1596.25  6159.9 1596.05  6345.8 1597.39
#Mann= 4 ,-1 , 0
  2954.6      .1       0  4890.1     .09       0  5091.6     .16       0
  6345.8     .05       0
#XS Ineff= 1 ,-1
 3461.36 4788.64 1590.99
Permanent Ineff=
       T
Bank Sta=4896.7,5068.7
XS Rating Curve= 0 ,0
Exp/Cntr=0.3,0.1

Type RM Length L Ch R = 1 ,2350    ,647,647,647
BEGIN DESCRIPTION:
MUESEBACH CREEK 4.0
END DESCRIPTION:
XS GIS Cut Line= 4
      2764654.88     10045688.85      2766363.22      10045369.4
      2767189.61     10044793.01       2767342.3      10044168.4
#Sta/Elev= 30
  2811.7 1596.59  2916.6 1594.88  2979.4 1592.56  3026.9 1593.53  3110.4 1589.93
  3300.3 1589.26  3415.7 1590.16  3659.7 1586.92  4158.2 1586.31  4290.5 1588.46
  4556.5    1588  4621.9 1589.72  4815.6 1588.67  4895.9 1586.67    4902 1586.18
  4922.9 1580.59  4946.2 1573.96  4973.5 1571.76  4982.2 1569.37    4995 1561.74
  5002.9 1560.78  5006.2 1561.28    5018 1567.17    5045 1574.17  5059.9    1580
  5080.8 1586.88  5125.3  1592.2  5153.5 1593.65  5527.5  1590.1  6200.2 1593.66
#Mann= 4 ,-1 , 0
  2811.7     .16       0  4922.9     .09       0  5059.9     .16       0
  6200.2     .05       0
#XS Ineff= 2 ,-1
 3038.64 3361.36 1590.39 3388.64 4627.27 1589.89
Permanent Ineff=
       T       T
Bank Sta=4922.9,5059.9
XS Rating Curve= 0 ,0
Exp/Cntr=0.3,0.1

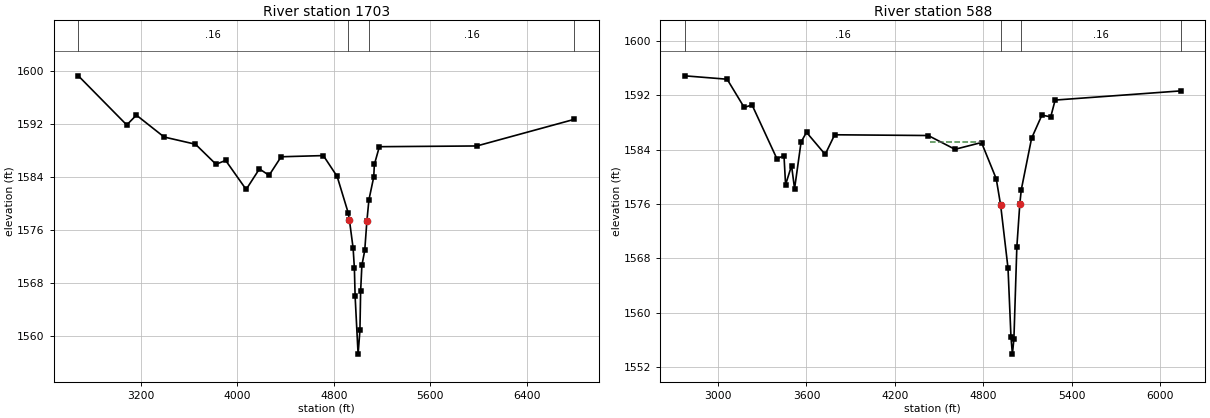
Type RM Length L Ch R = 1 ,1703    ,1115,1115,1115
BEGIN DESCRIPTION:
MUESEBACH CREEK 3.0
END DESCRIPTION:
XS GIS Cut Line= 4
      2764627.13     10045834.68       2766703.5     10045786.07
      2767293.78     10045626.34      2767432.67     10044209.68
#Sta/Elev= 30
  2681.4 1599.28  3082.8 1591.87  3162.9 1593.35  3392.9 1590.05    3653 1588.96
    3823 1585.94  3903.1 1586.52  4073.1 1582.14  4183.1 1585.24  4263.2 1584.27
  4363.2 1587.07  4713.3 1587.25  4827.8  1584.1  4918.9 1578.64  4929.2 1577.57
  4960.3 1573.27  4970.7 1570.27  4976.8 1566.02  5001.5  1557.3  5016.7 1560.88
  5022.5 1566.77  5032.8 1570.67  5056.6 1572.94  5074.3 1577.36  5091.3 1580.58
  5131.1 1584.01  5136.4 1585.91  5177.9 1588.59    5986  1588.7  6793.3 1592.71
#Mann= 4 ,-1 , 0
  2681.4     .16       0  4918.9     .09       0  5091.3     .16       0
  6793.3     .05       0
Bank Sta=4929.2,5074.3
XS Rating Curve= 0 ,0
Exp/Cntr=0.3,0.1

Type RM Length L Ch R = 1 ,588     ,0,0,0
BEGIN DESCRIPTION:
MUESEBACH CREEK 1.0
END DESCRIPTION:
XS GIS Cut Line= 4
      2765385.57     10046021.74      2766176.72     10045875.77
      2766766.46      10046643.6      2768360.48     10046646.52
#Sta/Elev= 30
  2773.7 1594.86  3061.1 1594.36  3177.2  1590.2  3230.2 1590.58  3399.3 1582.64
  3447.2 1583.11    3458 1578.83  3498.6 1581.64    3519 1578.23  3563.3 1585.12
  3600.1 1586.54  3726.9 1583.29  3791.3 1586.18  4426.6 1586.07  4608.4 1584.04
  4788.4 1585.04  4888.4  1579.7  4918.4  1575.8  4968.4 1566.53  4988.4 1556.42
  4998.1 1553.88  5008.4 1556.12  5028.4  1569.7  5048.4 1575.98  5058.4 1578.08
  5128.4 1585.66  5198.4 1589.07  5258.4 1588.82  5288.4 1591.29  6140.4 1592.64
#Mann= 4 ,-1 , 0
  2773.7     .16       0  4918.4     .09       0  5058.4     .16       0
  6140.4     .05       0
#XS Ineff= 1 ,-1
 4440.53 4778.69 1585.16
Permanent Ineff=
       T
Bank Sta=4918.4,5048.4
XS Rating Curve= 0 ,0
Exp/Cntr=0.3,0.1

Chan Stop Cuts=-1
Use User Specified Reach Order=0
Composite Channel Slope=5