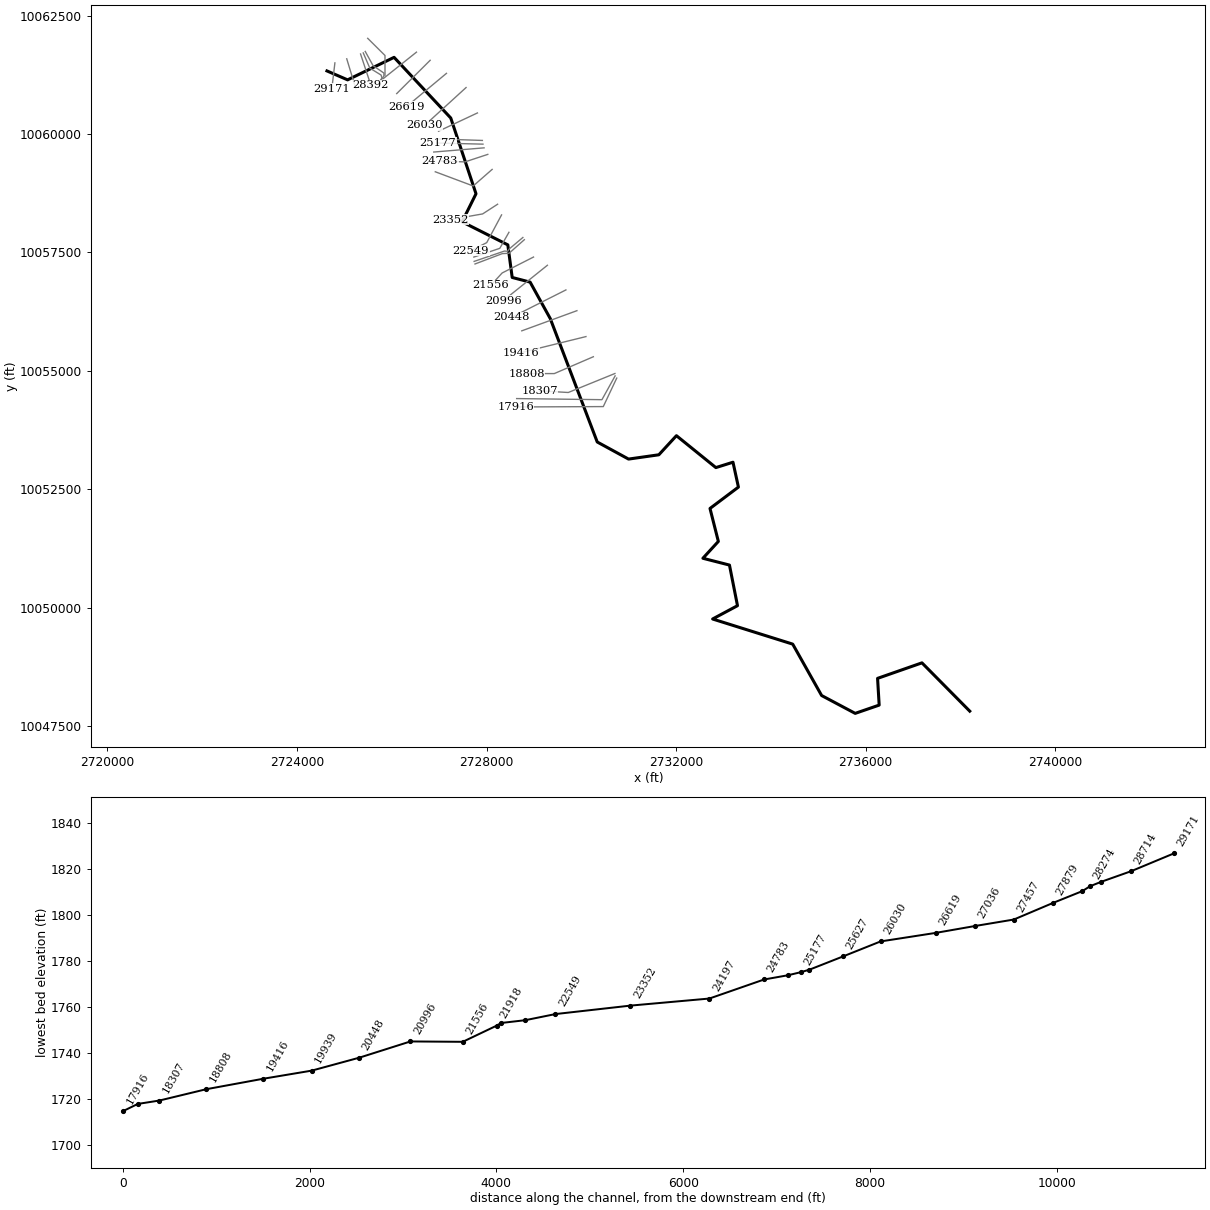
--- NASSE CREEK.prj (project) ---

Proj Title=NASSE CREEK Base Level Engineering
Current Plan=p01
Default Exp/Contr=0.3,0.1
English Units
Geom File=g01
Flow File=f01
Plan File=p01
Y Axis Title=Elevation
X Axis Title(PF)=Main Channel Distance
X Axis Title(XS)=Station
BEGIN DESCRIPTION:
NASSE CREEK
END DESCRIPTION:
DSS Export Rating Curves= 0
DSS Export Rating Curve Sorted= 0
DSS Export Volume Flow Curves= 0
DXF OffsetX= 0
DXF OffsetY= 0
DXF ScaleX= 1
DXF ScaleY= 10

--- NASSE CREEK.p01 (plan) ---

Plan Title=Multiple Run
Short Identifier=Multiple
Geom File=g01
Flow File=f01
Subcritical Flow
K Sum by GR= 0
Std Step Tol= 0.01
Critical Tol= 0.01
Num of Std Step Trials= 20
Max Error Tol= 0.3
Flow Tol Ratio= 0.001
Split Flow NTrial= 30
Split Flow Tol= 0.02
Split Flow Ratio= 0.02
Log Output Level= 0
Friction Slope Method= 1
Unsteady Friction Slope Method= 2
Unsteady Bridges Friction Slope Method= 1
Parabolic Critical Depth
Global Vel Dist=  1 , 1 , 1
Global Log Level= 0
CheckData=True
Encroach Param= -1, 0, 0, 0
BEGIN DESCRIPTION:
Multiple Run
END DESCRIPTION:

--- NASSE CREEK.f01 (steady flow) ---

Flow Title=Multiple
Program Version=4.10
Number of Profiles= 7
Profile Names=10-year,25-year,50-year,1pct_min,100-year,1pct_plu,500-year
River Rch & RM=NASSE CREEK,Reach-1         ,29171
     390     544     673     611     827    1118    1253
River Rch & RM=NASSE CREEK,Reach-1         ,27457
    1088    1599    2048    1917    2593    3506    4177
River Rch & RM=NASSE CREEK,Reach-1         ,13799
    1855    2802    3654    3477    4702    6359    7831
River Rch & RM=NASSE CREEK,Reach-1         ,12330
    2203    3340    4366    4161    5627    7610    9402
River Rch & RM=NASSE CREEK,Reach-1         ,5050
    2413    3667    4800    4579    6192    8374   10366
River Rch & RM=NASSE CREEK,Reach-1         ,1642
    2703    4127    5420    5186    7014    9485   11813
Boundary for River Rch & Prof#=NASSE CREEK,Reach-1         , 1
Up Type= 0
Dn Type= 3
Dn Slope=0.002
Boundary for River Rch & Prof#=NASSE CREEK,Reach-1         , 2
Up Type= 0
Dn Type= 3
Dn Slope=0.002
Boundary for River Rch & Prof#=NASSE CREEK,Reach-1         , 3
Up Type= 0
Dn Type= 3
Dn Slope=0.002
Boundary for River Rch & Prof#=NASSE CREEK,Reach-1         , 4
Up Type= 0
Dn Type= 3
Dn Slope=0.002
Boundary for River Rch & Prof#=NASSE CREEK,Reach-1         , 5
Up Type= 0
Dn Type= 3
Dn Slope=0.002
Boundary for River Rch & Prof#=NASSE CREEK,Reach-1         , 6
Up Type= 0
Dn Type= 3
Dn Slope=0.002
Boundary for River Rch & Prof#=NASSE CREEK,Reach-1         , 7
Up Type= 0
Dn Type= 3
Dn Slope=0.002
DSS Import GetInterval= 0
DSS Import GetPeak= 0
DSS Import FillOption= 0

--- NASSE CREEK.g01 (geometry) ---

Geom Title=Existing Conditions
Program Version=4.10

River Reach=NASSE CREEK     ,Reach-1
Reach XY= 30
       2724632.6     10061333.51      2725068.57     10061144.71
      2726049.09     10061620.32      2727245.32       10060339.
      2727778.02      10058739.4      2727484.63     10058146.71
      2728449.31     10057660.53      2728541.75     10056971.79
      2728920.33     10056873.23       2729345.3     10056102.76
      2730336.46     10053497.33      2730997.08     10053136.81
      2731636.53     10053227.47      2732007.41     10053630.95
      2732839.75     10052956.99      2733200.98     10053070.35
      2733315.51     10052545.08      2732715.98     10052094.07
      2732892.11      10051397.9      2732565.99     10051042.06
      2733126.57     10050898.76      2733296.03     10050040.81
      2732770.66      10049759.7      2734461.31     10049229.21
      2735071.35     10048143.81      2735779.73     10047766.78
      2736285.72     10047941.41        2736252.     10048505.99
      2737188.47     10048833.73      2738197.38     10047813.66

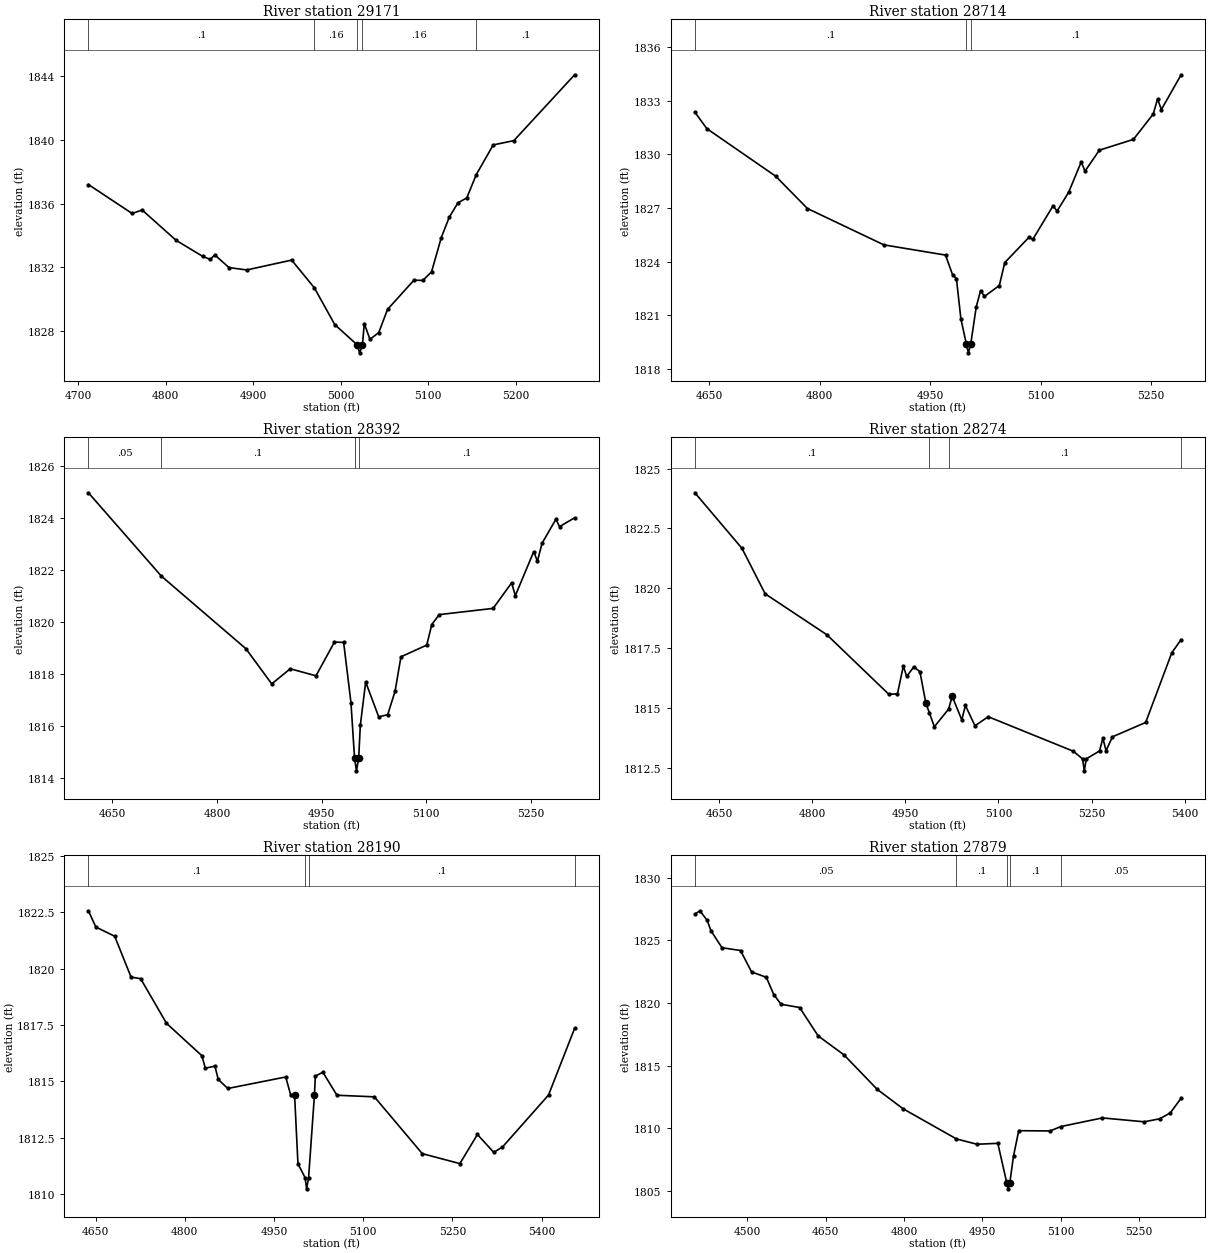
Type RM Length L Ch R = 1 ,29171   ,457,457,457
BEGIN DESCRIPTION:
NASSE CREEK 52.0
END DESCRIPTION:
XS GIS Cut Line= 2
      2724800.23     10061503.37      2724735.13     10060951.29
#Sta/Elev= 30
  4711.6  1837.2  4761.6 1835.38    4773  1835.6  4811.9 1833.69  4842.1 1832.69
    4851 1832.49    4856 1832.78  4872.3 1831.98  4892.5 1831.83    4944 1832.45
    4970  1830.7  4993.2  1828.4  5018.9 1827.12  5021.7 1826.62  5024.9 1827.12
    5027 1828.46  5033.5 1827.47  5043.5 1827.89  5053.6 1829.35  5083.8 1831.19
  5093.9 1831.17  5103.9 1831.71    5115 1833.86  5124.1 1835.14  5134.1 1836.05
  5144.2 1836.36    5155 1837.82  5174.4 1839.69    5198 1839.96  5267.5  1844.1
#Mann= 5 ,-1 , 0
  4711.6      .1       0    4970     .16       0  5018.9     .07       0
  5024.9     .16       0    5155      .1       0
Bank Sta=5018.9,5024.9
XS Rating Curve= 0 ,0
Exp/Cntr=0.3,0.1

Type RM Length L Ch R = 1 ,28714   ,322,322,322
BEGIN DESCRIPTION:
NASSE CREEK 51.0
END DESCRIPTION:
XS GIS Cut Line= 2
      2725050.23     10061589.34      2725242.61     10060957.58
#Sta/Elev= 30
  4630.3 1832.35  4646.6 1831.43  4739.9 1828.78  4783.2 1826.97    4887 1824.94
  4970.7 1824.37  4980.3 1823.27  4985.5 1823.06  4991.6 1820.81    4999 1819.41
  5001.8 1818.91    5005 1819.41  5012.5 1821.49  5018.4 1822.39  5023.6 1822.06
  5043.8 1822.67  5051.2 1823.95    5084 1825.36  5089.3 1825.25  5116.9 1827.13
  5122.1 1826.82  5137.9 1827.87    5155 1829.57  5160.2 1829.06  5179.7 1830.23
  5225.9 1830.83  5252.9 1832.25  5258.7 1833.09  5263.9  1832.5  5290.7 1834.44
#Mann= 3 ,-1 , 0
  4630.3      .1       0    4999     .07       0    5005      .1       0
Bank Sta=4999,5005
XS Rating Curve= 0 ,0
Exp/Cntr=0.3,0.1

Type RM Length L Ch R = 1 ,28392   ,118,118,118
BEGIN DESCRIPTION:
NASSE CREEK 50.0
END DESCRIPTION:
XS GIS Cut Line= 2
      2725341.89      10061690.9      2725560.65     10061029.43
#Sta/Elev= 30
  4615.9 1824.96  4720.4 1821.76  4841.6 1818.97  4878.6 1817.62  4905.1  1818.2
    4942 1817.93  4968.5 1819.23  4981.6 1819.21  4992.1  1816.9  4997.2 1814.78
    5000 1814.28  5003.2 1814.78  5005.5 1816.03  5013.2 1817.69  5031.9 1816.35
  5044.8 1816.44  5055.3 1817.34  5063.7 1818.66  5100.7 1819.11  5107.9  1819.9
  5118.5 1820.28  5195.8 1820.52  5222.3  1821.5  5227.6 1821.01    5254  1822.7
  5259.3 1822.33  5265.9 1823.02  5285.7 1823.94    5291 1823.66  5312.6    1824
#Mann= 4 ,-1 , 0
  4615.9     .05       0  4720.4      .1       0  4997.2     .07       0
  5003.2      .1       0
Bank Sta=4997.2,5003.2
XS Rating Curve= 0 ,0
Exp/Cntr=0.3,0.1

Type RM Length L Ch R = 1 ,28274   ,84,84,84
BEGIN DESCRIPTION:
Mapping XS 67d11879
END DESCRIPTION:
XS GIS Cut Line= 5
      2725398.92     10061713.46      2725536.95     10061393.11
      2725775.24     10061245.97      2725793.46     10061184.77
      2725743.35     10061108.97
#Sta/Elev= 30
  4610.8 1823.99  4686.7 1821.67  4724.1 1819.77  4823.6 1818.06  4923.2 1815.58
  4937.2 1815.59  4946.7 1816.75  4952.2 1816.32  4963.5 1816.72  4973.5 1816.52
    4983 1815.21  4988.9 1814.79  4996.7 1814.22  5019.7 1814.96  5025.5 1815.49
  5040.9 1814.51  5046.8 1815.11  5062.2 1814.26  5083.5 1814.64  5220.6  1813.2
  5235.6 1812.88  5238.4 1812.38  5241.6 1812.88  5262.9 1813.21  5268.3 1813.74
  5273.5 1813.22  5283.7  1813.8  5337.3  1814.4  5379.4 1817.31  5394.4 1817.86
#Mann= 4 ,-1 , 0
  4610.8      .1       0  4988.9     .07       0  5019.7      .1       0
  5394.4     .05       0
Bank Sta=4983,5025.5
XS Rating Curve= 0 ,0
Exp/Cntr=0.3,0.1

Type RM Length L Ch R = 1 ,28190   ,311,311,311
BEGIN DESCRIPTION:
Mapping XS d53456a6
END DESCRIPTION:
XS GIS Cut Line= 5
      2725440.58     10061744.71      2725605.96     10061445.19
      2725835.13     10061287.64      2725833.83     10061223.84
      2725757.02     10061114.48
#Sta/Elev= 30
  4637.9 1822.57  4650.4 1821.85  4682.1 1821.44  4709.6 1819.63  4725.7 1819.56
  4769.2 1817.58  4828.8 1816.14  4834.5 1815.59  4850.6 1815.68  4856.3 1815.09
  4872.3 1814.69  4969.7  1815.2    4978 1814.41  4984.6 1814.41  4990.3 1811.35
  5002.2 1810.74  5004.9 1810.24  5008.2 1810.74 5018.03  1814.4  5019.5 1815.24
  5032.2 1815.41  5055.9 1814.39  5118.8 1814.32  5199.4  1811.8  5262.6 1811.36
  5292.1 1812.65  5319.5 1811.86  5334.1 1812.09  5411.7  1814.4  5455.6 1817.36
#Mann= 4 ,-1 , 0
  4637.9      .1       0  5002.2     .07       0  5008.2      .1       0
  5455.6     .05       0
Bank Sta=4984.6,5018.03
XS Rating Curve= 0 ,0
Exp/Cntr=0.3,0.1

Type RM Length L Ch R = 1 ,27879   ,422,422,422
BEGIN DESCRIPTION:
NASSE CREEK 49.0
END DESCRIPTION:
XS GIS Cut Line= 3
      2725492.93     10062021.62      2725857.52     10061659.63
      2725857.52       10061243.
#Sta/Elev= 30
  4399.7 1827.08  4409.2 1827.35  4423.3 1826.58  4430.4 1825.76  4451.6  1824.4
    4487 1824.18  4508.2 1822.47  4536.5 1822.04  4550.6 1820.66  4564.7 1819.89
  4600.1 1819.63  4635.5 1817.37    4685 1815.85  4748.6  1813.1  4798.1 1811.55
  4900.3 1809.14  4939.4 1808.72  4979.4 1808.79  4996.4 1805.66  4999.1 1805.16
  5002.4 1805.66  5009.4 1807.78  5019.4  1809.8  5079.4 1809.78    5100 1810.13
  5179.4 1810.82  5259.4 1810.51  5289.4 1810.75  5309.4 1811.22  5330.1 1812.39
#Mann= 5 ,-1 , 0
  4399.7     .05       0  4900.3      .1       0  4996.4     .07       0
  5002.4      .1       0    5100     .05       0
Bank Sta=4996.4,5002.4
XS Rating Curve= 0 ,0
Exp/Cntr=0.3,0.1

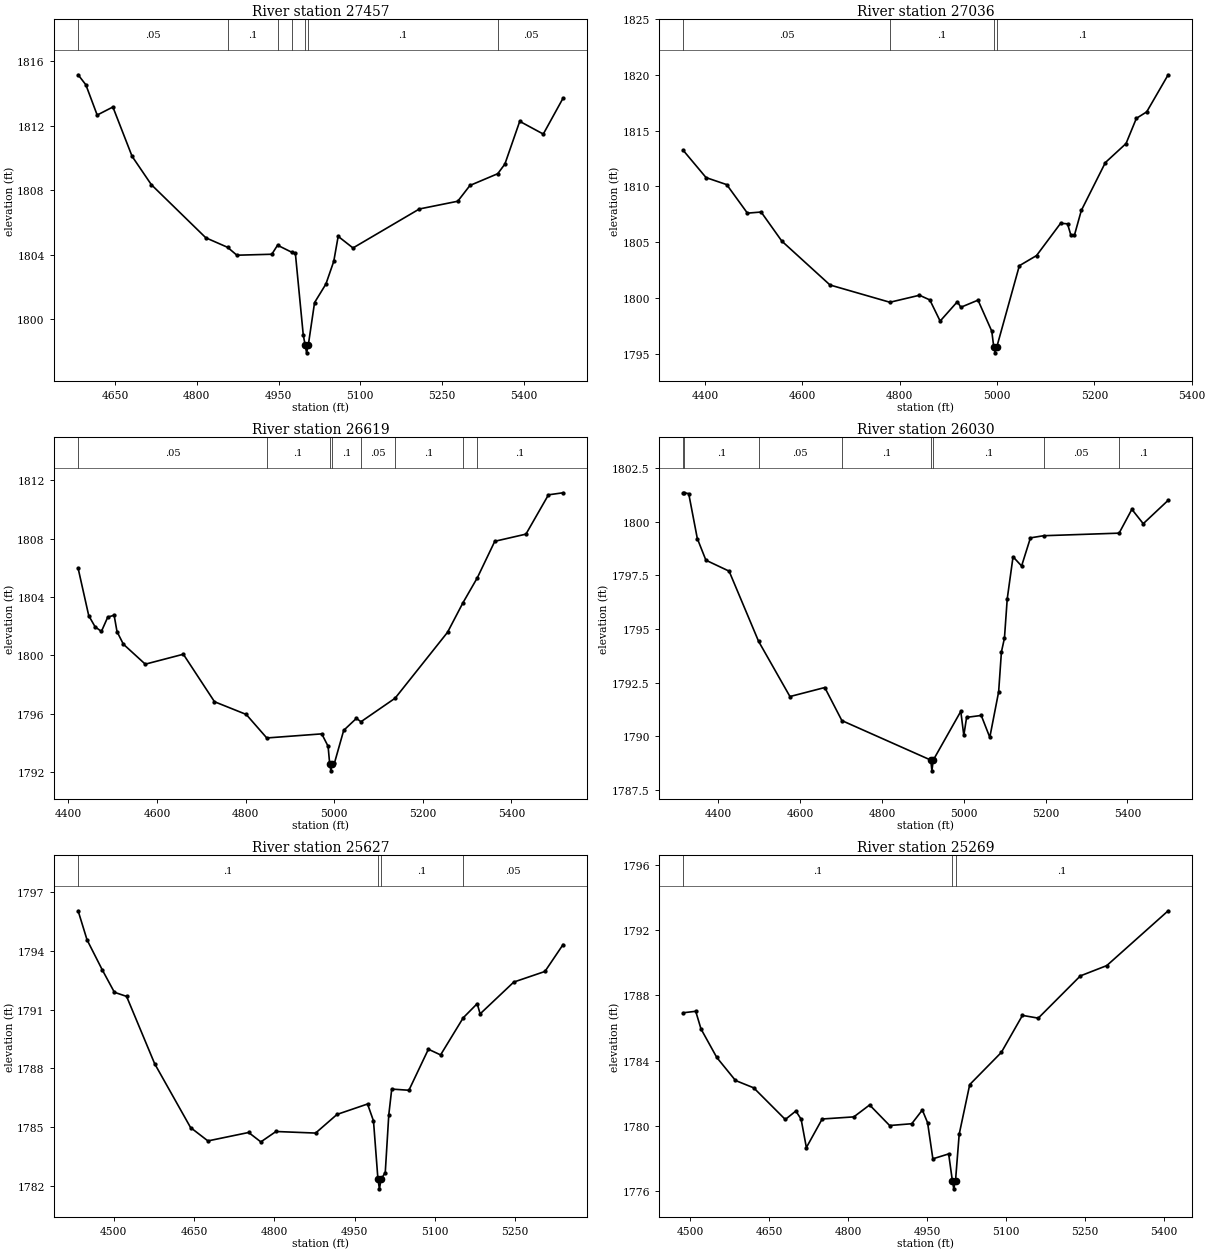
Type RM Length L Ch R = 1 ,27457   ,421,421,421
BEGIN DESCRIPTION:
NASSE CREEK 48.0
END DESCRIPTION:
XS GIS Cut Line= 2
      2726521.59     10061729.94      2725826.25     10061175.23
#Sta/Elev= 30
  4582.4 1815.17  4596.6 1814.55  4617.4 1812.67  4646.2 1813.17  4681.4 1810.11
  4716.7 1808.35  4816.7 1805.05  4856.6 1804.46  4873.6 1803.97  4937.7 1804.03
  4948.2 1804.59  4974.5 1804.15  4980.9 1804.08  4995.3 1799.04  4998.7 1798.41
  5001.5 1797.91  5004.7 1798.41  5016.1 1801.03  5036.9 1802.18  5051.3 1803.59
  5059.4 1805.14  5086.6 1804.42  5208.3 1806.84  5278.7 1807.32  5301.1  1808.3
  5352.1 1809.03  5365.2 1809.63  5392.4 1812.28  5435.6 1811.49  5471.9 1813.72
#Mann= 7 ,-1 , 0
  4582.4     .05       0  4856.6      .1       0  4948.2     .05       0
  4974.5      .1       0  4998.7     .07       0  5004.7      .1       0
  5352.1     .05       0
Bank Sta=4998.7,5004.7
XS Rating Curve= 0 ,0
Exp/Cntr=0.3,0.1

Type RM Length L Ch R = 1 ,27036   ,417,417,417
BEGIN DESCRIPTION:
NASSE CREEK 47.0
END DESCRIPTION:
XS GIS Cut Line= 2
      2726810.63     10061558.05      2726104.91     10060854.93
#Sta/Elev= 30
  4355.4 1813.24  4402.4 1810.79  4444.8 1810.16  4487.3  1807.6  4515.5  1807.7
    4558 1805.09    4657 1801.15    4780  1799.6  4840.8 1800.23    4862 1799.81
  4883.2 1797.91  4918.6 1799.65  4925.7 1799.15    4961 1799.79  4989.3    1797
  4993.4 1795.56  4996.1 1795.06  4999.4 1795.56  5045.9 1802.88  5081.2 1803.79
  5130.7 1806.69  5144.9 1806.64  5151.9  1805.6    5159 1805.61  5173.2 1807.84
  5222.6 1812.14  5265.1 1813.85  5286.3 1816.11  5307.5 1816.69  5351.6 1820.02
#Mann= 4 ,-1 , 0
  4355.4     .05       0    4780      .1       0  4993.4     .07       0
  4999.4      .1       0
Bank Sta=4993.4,4999.4
XS Rating Curve= 0 ,0
Exp/Cntr=0.3,0.1

Type RM Length L Ch R = 1 ,26619   ,589,589,589
BEGIN DESCRIPTION:
NASSE CREEK 46.0
END DESCRIPTION:
XS GIS Cut Line= 2
      2727154.38     10061282.01      2726313.35     10060581.58
#Sta/Elev= 30
  4422.1 1805.97  4446.1 1802.72  4460.4 1801.96  4474.7 1801.64    4489 1802.62
  4503.4 1802.75  4509.9 1801.63  4524.2 1800.77  4573.7  1799.4  4659.6 1800.08
  4729.9 1796.83  4801.5 1795.96  4847.9 1794.35    4972 1794.63  4986.3 1793.78
  4989.8  1792.6  4992.6  1792.1  4995.8  1792.6  5000.6 1792.63  5021.5 1794.87
  5050.1 1795.69  5060.5 1795.46  5137.5 1797.07  5255.8 1801.58  5290.8 1803.61
  5323.2 1805.32  5362.5 1807.81  5432.8  1808.3  5483.6 1810.99  5516.6 1811.13
#Mann= 8 ,-1 , 0
  4422.1     .05       0  4847.9      .1       0  4989.8     .07       0
  4995.8      .1       0  5060.5     .05       0  5137.5      .1       0
  5290.8     .05       0  5323.2      .1       0
Bank Sta=4989.8,4995.8
XS Rating Curve= 0 ,0
Exp/Cntr=0.3,0.1

Type RM Length L Ch R = 1 ,26030   ,403,403,403
BEGIN DESCRIPTION:
NASSE CREEK 45.0
END DESCRIPTION:
XS GIS Cut Line= 2
      2727568.44     10060982.52      2726693.47     10060183.07
#Sta/Elev= 30
  4314.3 1801.35  4316.5 1801.35  4327.8 1801.31  4348.8 1799.22  4369.8 1798.21
  4426.5  1797.7  4498.6 1794.43  4575.2 1791.86  4660.3 1792.28  4702.1 1790.74
  4919.4  1788.9  4922.1  1788.4  4925.4  1788.9  4992.7 1791.17  5000.1 1790.05
  5006.9 1790.89  5042.7 1790.98  5063.6 1789.96  5085.2 1792.08    5092 1793.94
  5099.4 1794.58  5106.2 1796.41  5120.4 1798.37  5141.3 1797.94  5162.9 1799.25
  5195.1 1799.35  5379.6 1799.47  5410.8 1800.58  5438.6 1799.91  5499.5    1801
#Mann= 8 ,-1 , 0
  4314.3     .05       0  4316.5      .1       0  4498.6     .05       0
  4702.1      .1       0  4919.4     .07       0  4925.4      .1       0
  5195.1     .05       0  5379.6      .1       0
Bank Sta=4919.4,4925.4
XS Rating Curve= 0 ,0
Exp/Cntr=0.3,0.1

Type RM Length L Ch R = 1 ,25627   ,358,358,358
BEGIN DESCRIPTION:
NASSE CREEK 44.0
END DESCRIPTION:
XS GIS Cut Line= 2
      2727808.03     10060446.07      2726987.75     10060060.68
#Sta/Elev= 30
  4433.4 1796.03  4450.1 1794.55  4478.4 1793.03  4501.2 1791.88    4524 1791.67
  4576.5 1788.24  4643.6 1784.99    4676 1784.31  4752.1 1784.74  4774.9 1784.26
  4803.2 1784.79  4877.2 1784.71  4917.3 1785.66  4974.3 1786.19  4985.4 1785.33
  4993.7 1782.37  4996.5 1781.87  4999.7 1782.37  5007.4  1782.7    5014 1785.64
  5019.5 1786.95  5051.6 1786.89    5088 1788.98  5110.8 1788.69  5153.1 1790.58
  5179.2  1791.3  5184.7 1790.78  5247.6  1792.4  5305.8 1792.94  5339.7 1794.31
#Mann= 4 ,-1 , 0
  4433.4      .1       0  4993.7     .07       0  4999.7      .1       0
  5153.1     .05       0
Bank Sta=4993.7,4999.7
XS Rating Curve= 0 ,0
Exp/Cntr=0.3,0.1

Type RM Length L Ch R = 1 ,25269   ,92,92,92
BEGIN DESCRIPTION:
Mapping XS f9c3db54
END DESCRIPTION:
XS GIS Cut Line= 2
      2727912.26     10059865.35      2726991.89     10059896.55
#Sta/Elev= 30
  4486.7 1786.94  4510.5 1787.03  4520.5 1785.95  4550.5  1784.2    4586 1782.79
  4620.6 1782.34  4680.6  1780.4  4700.6 1780.92  4710.6 1780.42  4720.6 1778.68
  4750.6 1780.43  4810.7 1780.56  4840.7 1781.29  4878.7 1780.03  4920.7 1780.14
  4940.8 1780.98  4950.8  1780.2  4960.8 1777.99  4990.8 1778.29  4997.8 1776.65
  5000.5 1776.15  5003.8 1776.65  5010.8  1779.5  5030.8 1782.54  5090.8 1784.51
  5130.9 1786.78  5160.9 1786.61  5240.9  1789.2    5291 1789.83  5407.6 1793.19
#Mann= 3 ,-1 , 0
  4486.7      .1       0  4997.8     .07       0  5003.8      .1       0
Bank Sta=4997.8,5003.8
XS Rating Curve= 0 ,0
Exp/Cntr=0.3,0.1

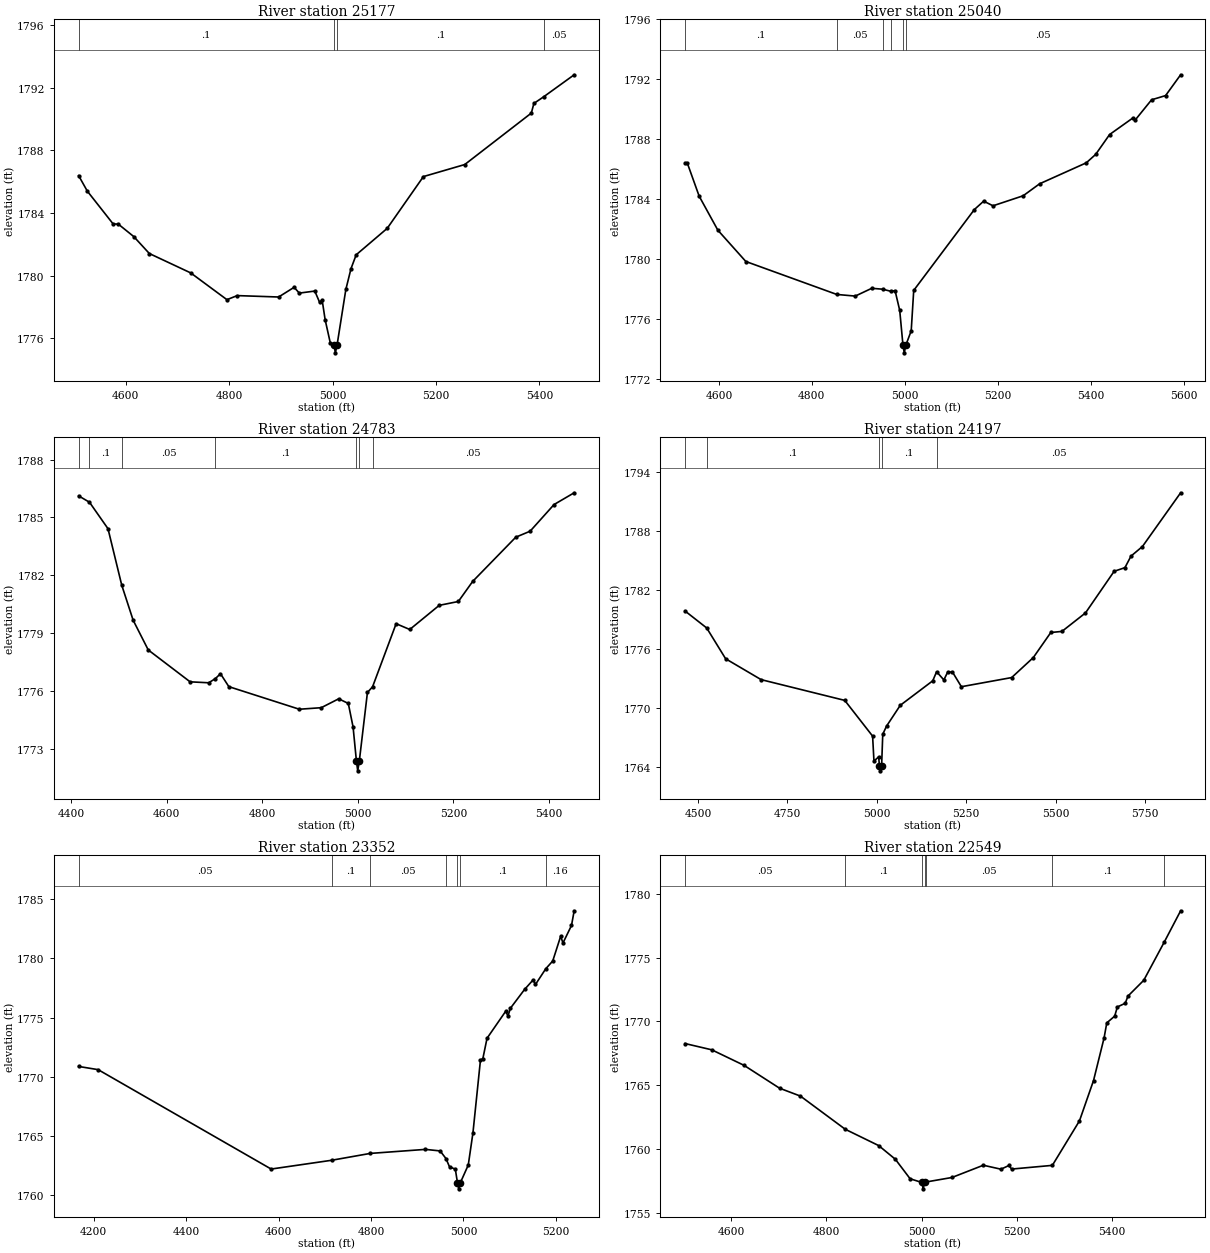
Type RM Length L Ch R = 1 ,25177   ,137,137,137
BEGIN DESCRIPTION:
Mapping XS b861dd0f
END DESCRIPTION:
XS GIS Cut Line= 2
      2727925.27     10059787.23      2726966.85     10059810.67
#Sta/Elev= 30
  4508.7 1786.39  4525.5  1785.4  4575.5  1783.3  4585.5 1783.29  4615.5 1782.49
  4645.5 1781.41  4725.6 1780.17  4795.6 1778.46  4815.6 1778.72  4895.6 1778.63
  4925.6 1779.25  4935.6 1778.88  4965.6 1779.01  4974.9 1778.29  4979.9 1778.42
  4985.6 1777.18  4995.6 1775.69  5002.7 1775.56  5005.4 1775.06  5008.7 1775.56
  5025.7 1779.12  5035.7 1780.45  5045.7 1781.33  5105.7 1783.02  5175.7 1786.33
  5255.7  1787.1  5384.5 1790.39  5389.5 1791.01  5408.3 1791.43  5467.4 1792.84
#Mann= 4 ,-1 , 0
  4508.7      .1       0  5002.7     .07       0  5008.7      .1       0
  5408.3     .05       0
Bank Sta=5002.7,5008.7
XS Rating Curve= 0 ,0
Exp/Cntr=0.3,0.1

Type RM Length L Ch R = 1 ,25040   ,257,257,257
BEGIN DESCRIPTION:
NASSE CREEK 43.0
END DESCRIPTION:
XS GIS Cut Line= 2
      2727948.67      10059709.1      2726886.16     10059620.56
#Sta/Elev= 30
  4527.3 1786.42  4532.2 1786.39  4557.6 1784.19  4597.8 1781.92    4658 1779.83
  4853.6 1777.63  4893.4 1777.52  4928.9 1778.04  4952.3 1777.98    4970 1777.84
  4979.1 1777.88  4989.1 1776.56  4996.1 1774.23  4998.9 1773.73  5002.1 1774.23
  5013.8  1775.2  5019.2  1777.9  5149.7  1783.3  5169.7 1783.86  5189.8 1783.55
  5254.7 1784.22  5290.1 1785.02  5390.5 1786.42  5410.6 1786.98  5440.7 1788.31
  5490.5 1789.41  5495.5 1789.27    5531 1790.63  5561.1 1790.91  5593.5  1792.3
#Mann= 6 ,-1 , 0
  4527.3      .1       0  4853.6     .05       0  4952.3      .1       0
    4970     .05       0  4996.1    .035       0  5002.1     .05       0
Bank Sta=4996.1,5002.1
XS Rating Curve= 0 ,0
Exp/Cntr=0.3,0.1

Type RM Length L Ch R = 1 ,24783   ,586,586,586
BEGIN DESCRIPTION:
NASSE CREEK 42.0
END DESCRIPTION:
XS GIS Cut Line= 3
      2728026.77     10059571.08      2727545.02     10059412.23
       2727016.4     10059430.46
#Sta/Elev= 30
  4416.2 1786.12  4438.9 1785.79  4477.6 1784.42  4506.4 1781.49  4530.2 1779.68
  4561.8 1778.14  4649.3 1776.49  4688.2 1776.44  4702.3 1776.66  4712.8 1776.91
  4730.3 1776.24  4877.7 1775.07  4923.5 1775.15    4960 1775.61  4980.1 1775.37
  4990.1 1774.15  4997.1 1772.38  4999.8 1771.88  5003.1 1772.38  5020.1 1775.94
  5030.8 1776.23  5080.1  1779.5  5108.6  1779.2  5170.2 1780.45  5210.2 1780.65
  5240.2 1781.69  5330.3 1783.98  5360.3 1784.29  5410.3 1785.67  5452.4 1786.28
#Mann= 7 ,-1 , 0
  4416.2     .05       0  4438.9      .1       0  4506.4     .05       0
  4702.3      .1       0  4997.1     .07       0  5003.1      .1       0
  5030.8     .05       0
Bank Sta=4997.1,5003.1
XS Rating Curve= 0 ,0
Exp/Cntr=0.3,0.1

Type RM Length L Ch R = 1 ,24197   ,845,845,845
BEGIN DESCRIPTION:
NASSE CREEK 41.0
END DESCRIPTION:
XS GIS Cut Line= 3
      2728118.45     10059253.72      2727718.47     10058903.73
      2726918.45     10059203.74
#Sta/Elev= 30
    4464 1779.85  4524.4 1778.13  4577.4    1775  4676.6 1772.88  4910.5 1770.77
  4988.4 1767.14  4992.2  1764.6  5005.3 1765.03  5007.6 1764.11  5010.4 1763.61
  5013.6 1764.11  5016.8 1767.33  5027.5 1768.16  5065.8 1770.27  5156.6 1772.76
  5167.4 1773.68  5187.7 1772.85  5198.4 1773.65  5211.8 1773.65  5236.7 1772.16
  5377.3 1773.09  5437.8 1775.12  5486.8 1777.67  5517.9 1777.78  5583.8 1779.66
  5663.9 1783.89  5694.1 1784.26    5711 1785.43  5743.1 1786.41  5849.9 1791.87
#Mann= 5 ,-1 , 0
    4464     .05       0  4524.4      .1       0  5007.6     .07       0
  5013.6      .1       0  5167.4     .05       0
Bank Sta=5007.6,5013.6
XS Rating Curve= 0 ,0
Exp/Cntr=0.3,0.1

Type RM Length L Ch R = 1 ,23352   ,803,803,803
BEGIN DESCRIPTION:
NASSE CREEK 40.0
END DESCRIPTION:
XS GIS Cut Line= 3
       2728233.8     10058518.55      2727917.85     10058313.71
      2727232.77     10058194.03
#Sta/Elev= 30
  4167.6 1770.87  4209.8  1770.6  4584.1 1762.21  4714.7 1762.95  4798.4 1763.53
  4917.9 1763.87  4949.6 1763.74  4962.2  1763.1  4969.9  1762.4  4982.5  1762.2
  4987.2 1761.04  4989.9 1760.54  4993.2 1761.04  5010.5 1762.55  5020.6 1765.26
  5036.9 1771.42    5042 1771.52  5051.1 1773.25  5091.3 1775.52  5096.4 1775.14
  5101.8 1775.79  5132.3 1777.37  5150.9 1778.18  5155.9 1777.79  5178.2 1779.12
  5193.2 1779.77  5210.4 1781.86  5215.4 1781.29  5233.8 1782.77  5239.6 1784.01
#Mann= 7 ,-1 , 0
  4167.6     .05       0  4714.7      .1       0  4798.4     .05       0
  4962.2      .1       0  4987.2     .07       0  4993.2      .1       0
  5178.2     .16       0
Bank Sta=4987.2,4993.2
XS Rating Curve= 0 ,0
Exp/Cntr=0.3,0.1

Type RM Length L Ch R = 1 ,22549   ,323,323,323
BEGIN DESCRIPTION:
NASSE CREEK 39.0
END DESCRIPTION:
XS GIS Cut Line= 3
      2728317.18      10058292.9      2728004.66      10057707.8
       2727669.6     10057535.93
#Sta/Elev= 30
  4503.8 1768.26  4559.7 1767.77  4627.6 1766.55    4702 1764.76  4745.9 1764.14
  4839.9 1761.54  4910.1 1760.26    4945 1759.19    4976 1757.66  5000.6 1757.37
  5003.4 1756.87  5006.6 1757.37  5008.4  1757.4  5063.8 1757.76  5129.6 1758.72
  5166.6 1758.41  5183.4  1758.7    5189 1758.42  5274.5 1758.71  5331.4  1762.2
  5360.9 1765.36  5383.1 1768.71  5388.7 1769.88  5405.3 1770.41  5410.9 1771.13
  5427.5 1771.42  5433.1 1771.98  5466.3 1773.22  5509.1  1776.2  5543.7 1778.67
#Mann= 7 ,-1 , 0
  4503.8     .05       0  4839.9      .1       0  5000.6     .07       0
  5006.6      .1       0  5008.4     .05       0  5274.5      .1       0
  5509.1     .05       0
Bank Sta=5000.6,5006.6
XS Rating Curve= 0 ,0
Exp/Cntr=0.3,0.1

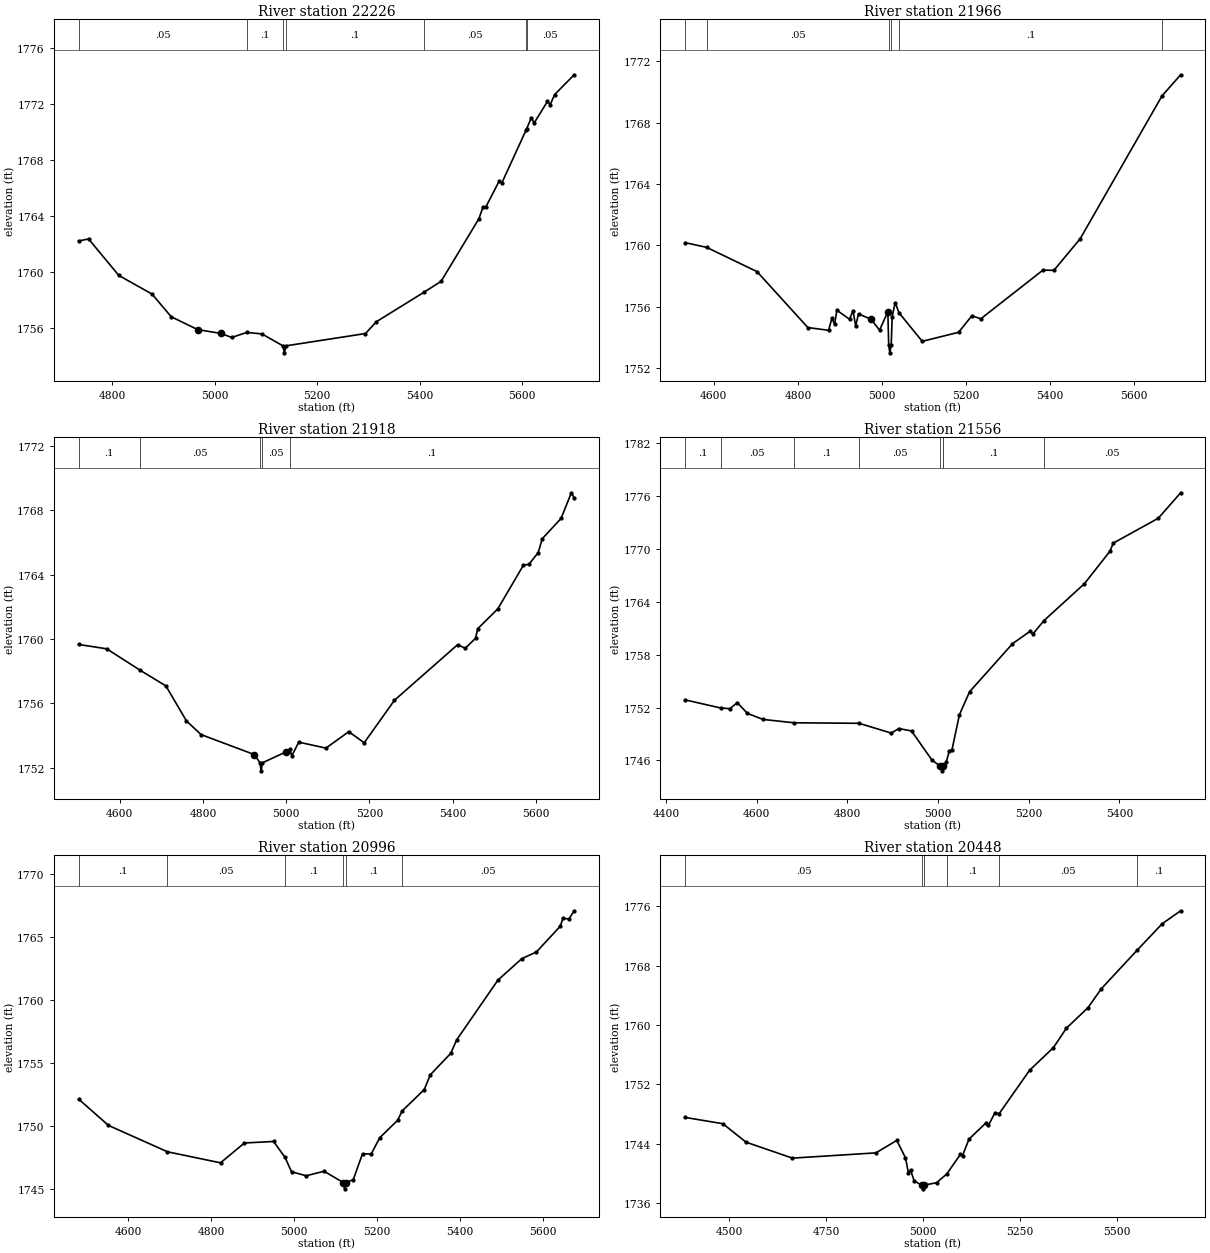
Type RM Length L Ch R = 1 ,22226   ,260,260,260
BEGIN DESCRIPTION:
Mapping XS 620e773b
END DESCRIPTION:
XS GIS Cut Line= 3
      2728472.99     10057925.79      2728280.26     10057587.21
      2727732.15     10057402.77
#Sta/Elev= 30
    4734  1762.2  4753.4 1762.35  4812.5 1759.74  4877.4 1758.41  4914.8 1756.79
  4966.5 1755.87  5011.4  1755.6    5033 1755.31  5062.7 1755.67  5092.1 1755.56
    5133 1754.71  5135.8 1754.21    5139 1754.71  5294.3 1755.59  5315.4 1756.43
  5408.1 1758.53    5442 1759.32  5515.9  1763.8  5523.8 1764.63  5529.1 1764.62
  5555.3 1766.47  5560.6 1766.35    5608 1770.13  5608.9  1770.2  5618.3 1771.02
  5623.6 1770.63  5649.8 1772.18  5655.1 1771.94  5663.6 1772.66  5701.9 1774.08
#Mann= 7 ,-1 , 0
    4734     .05       0  5062.7      .1       0    5133    .035       0
    5139      .1       0  5408.1     .05       0    5608      .1       0
  5608.9     .05       0
Bank Sta=4966.5,5011.4
XS Rating Curve= 0 ,0
Exp/Cntr=0.3,0.1

Type RM Length L Ch R = 1 ,21966   ,48,48,48
BEGIN DESCRIPTION:
NASSE CREEK 38.0
END DESCRIPTION:
XS GIS Cut Line= 5
      2728767.26     10057816.39      2728488.59       10057582.
      2728444.32     10057524.71      2728379.22     10057529.92
      2727738.59     10057311.16
#Sta/Elev= 30
  4531.6 1760.18  4582.9 1759.87  4702.6 1758.29  4823.6 1754.64    4873 1754.46
  4880.8 1755.25  4887.3 1754.85  4892.6 1755.77  4922.8 1755.18    4931 1755.75
  4937.3 1754.74  4944.1 1755.53    4974 1755.18  4994.1 1754.47  5013.9 1755.67
  5015.9 1753.49  5018.6 1752.99  5021.9 1753.49  5024.2 1755.34  5031.3 1756.27
  5040.3 1755.61  5095.7 1753.74  5182.2 1754.33  5213.9 1755.41    5235 1755.21
    5383 1758.39  5408.9 1758.37  5471.6 1760.44    5666 1769.75  5710.4 1771.13
#Mann= 6 ,-1 , 0
  4531.6      .1       0  4582.9     .05       0  5015.9    .035       0
  5021.9     .05       0  5040.3      .1       0    5666     .05       0
Bank Sta=4974,5013.9
XS Rating Curve= 0 ,0
Exp/Cntr=0.3,0.1

Type RM Length L Ch R = 1 ,21918   ,362,362,362
BEGIN DESCRIPTION:
Mapping XS 057a5a5a
END DESCRIPTION:
XS GIS Cut Line= 4
      2728798.47     10057769.48      2728475.57     10057483.04
      2728332.34     10057475.23       2727756.8     10057256.47
#Sta/Elev= 30
  4501.1 1759.66  4568.6 1759.39  4647.6 1758.08  4710.8 1757.09  4760.1 1754.92
  4795.2 1754.07  4923.2 1752.83  4936.9 1752.32  4939.6 1751.82  4942.9 1752.32
  4999.9    1753  5008.7 1753.15  5013.4 1752.75    5030  1753.6  5095.4 1753.23
  5150.3 1754.25  5187.3 1753.56  5260.1  1756.2    5412 1759.65  5430.1 1759.42
  5454.8 1760.04  5460.2 1760.64  5508.2 1761.86    5570 1764.58  5583.1 1764.63
  5605.5 1765.36  5615.2 1766.22  5660.4 1767.48  5685.1 1769.07  5691.9 1768.76
#Mann= 5 ,-1 , 0
  4501.1      .1       0  4647.6     .05       0  4936.9    .035       0
  4942.9     .05       0  5008.7      .1       0
Bank Sta=4923.2,4999.9
XS Rating Curve= 0 ,0
Exp/Cntr=0.3,0.1

Type RM Length L Ch R = 1 ,21556   ,560,560,560
BEGIN DESCRIPTION:
NASSE CREEK 37.0
END DESCRIPTION:
XS GIS Cut Line= 3
      2728991.61     10057403.18      2728329.68     10057066.79
      2728093.32     10056808.94
#Sta/Elev= 30
  4442.5 1752.87  4520.6 1751.95    4541 1751.87  4557.6 1752.55  4579.9 1751.33
  4614.3 1750.65  4682.3 1750.27  4825.9 1750.21  4897.1  1749.1  4913.7 1749.62
  4941.6 1749.34  4986.1 1746.08  5005.3 1745.32  5008.1 1744.82  5011.3 1745.32
  5011.4 1745.33  5018.1 1745.81    5025 1747.11  5030.6 1747.17  5047.2 1751.18
  5069.5 1753.78  5164.1 1759.23  5202.5 1760.63  5209.3 1760.35  5233.4 1761.85
  5322.7 1766.04  5379.1 1769.73  5386.2 1770.64  5485.5 1773.46  5534.8 1776.35
#Mann= 8 ,-1 , 0
  4442.5      .1       0  4520.6     .05       0  4682.3      .1       0
  4825.9     .05       0  5005.3    .035       0  5011.3     .05       0
  5011.4      .1       0  5233.4     .05       0
Bank Sta=5005.3,5011.3
XS Rating Curve= 0 ,0
Exp/Cntr=0.3,0.1

Type RM Length L Ch R = 1 ,20996   ,548,548,548
BEGIN DESCRIPTION:
NASSE CREEK 36.0
END DESCRIPTION:
XS GIS Cut Line= 2
      2729284.52     10057229.53      2728352.44      10056481.7
#Sta/Elev= 30
  4480.7 1752.12  4552.6 1750.03  4694.8 1747.93  4822.9 1747.05  4880.5 1748.63
  4950.9 1748.75  4978.5 1747.48  4994.1 1746.34  5029.3 1746.02  5072.5 1746.38
  5119.1 1745.48  5121.9 1744.98  5125.1 1745.48  5142.9 1745.71  5165.3 1747.77
  5186.1 1747.75  5206.9 1749.05  5250.1 1750.44  5260.8 1751.18  5314.2 1752.88
  5328.6 1754.05  5378.2 1755.77  5392.6 1756.85  5491.8 1761.59  5549.4  1763.3
  5584.6 1763.83  5642.2 1765.88  5648.6  1766.5    5663 1766.46  5675.7 1767.11
#Mann= 6 ,-1 , 0
  4480.7      .1       0  4694.8     .05       0  4978.5      .1       0
  5119.1     .07       0  5125.1      .1       0  5260.8     .05       0
Bank Sta=5119.1,5125.1
XS Rating Curve= 0 ,0
Exp/Cntr=0.3,0.1

Type RM Length L Ch R = 1 ,20448   ,509,509,509
BEGIN DESCRIPTION:
NASSE CREEK 35.0
END DESCRIPTION:
XS GIS Cut Line= 2
       2729675.2     10056708.74      2728535.82     10056133.62
#Sta/Elev= 30
  4387.2 1747.56  4484.4 1746.71  4544.3 1744.22  4663.6 1742.07  4878.7 1742.78
  4932.4 1744.46  4954.8 1742.12  4962.3  1740.1  4967.9 1740.47  4977.2 1738.99
  4996.6 1738.43  4999.4 1737.93  5002.6 1738.43  5034.8 1738.75  5061.2 1739.94
  5096.1 1742.56  5101.7  1742.4  5118.4 1744.64    5163 1746.86  5168.6  1746.5
  5185.3  1748.2    5196 1748.06  5274.5 1753.92  5335.7 1756.96  5369.3 1759.59
    5425 1762.36  5458.9 1764.89  5551.4  1770.1  5615.7 1773.66  5663.5 1775.42
#Mann= 6 ,-1 , 0
  4387.2     .05       0  4996.6    .035       0  5002.6     .05       0
  5061.2      .1       0    5196     .05       0  5551.4      .1       0
Bank Sta=4996.6,5002.6
XS Rating Curve= 0 ,0
Exp/Cntr=0.3,0.1

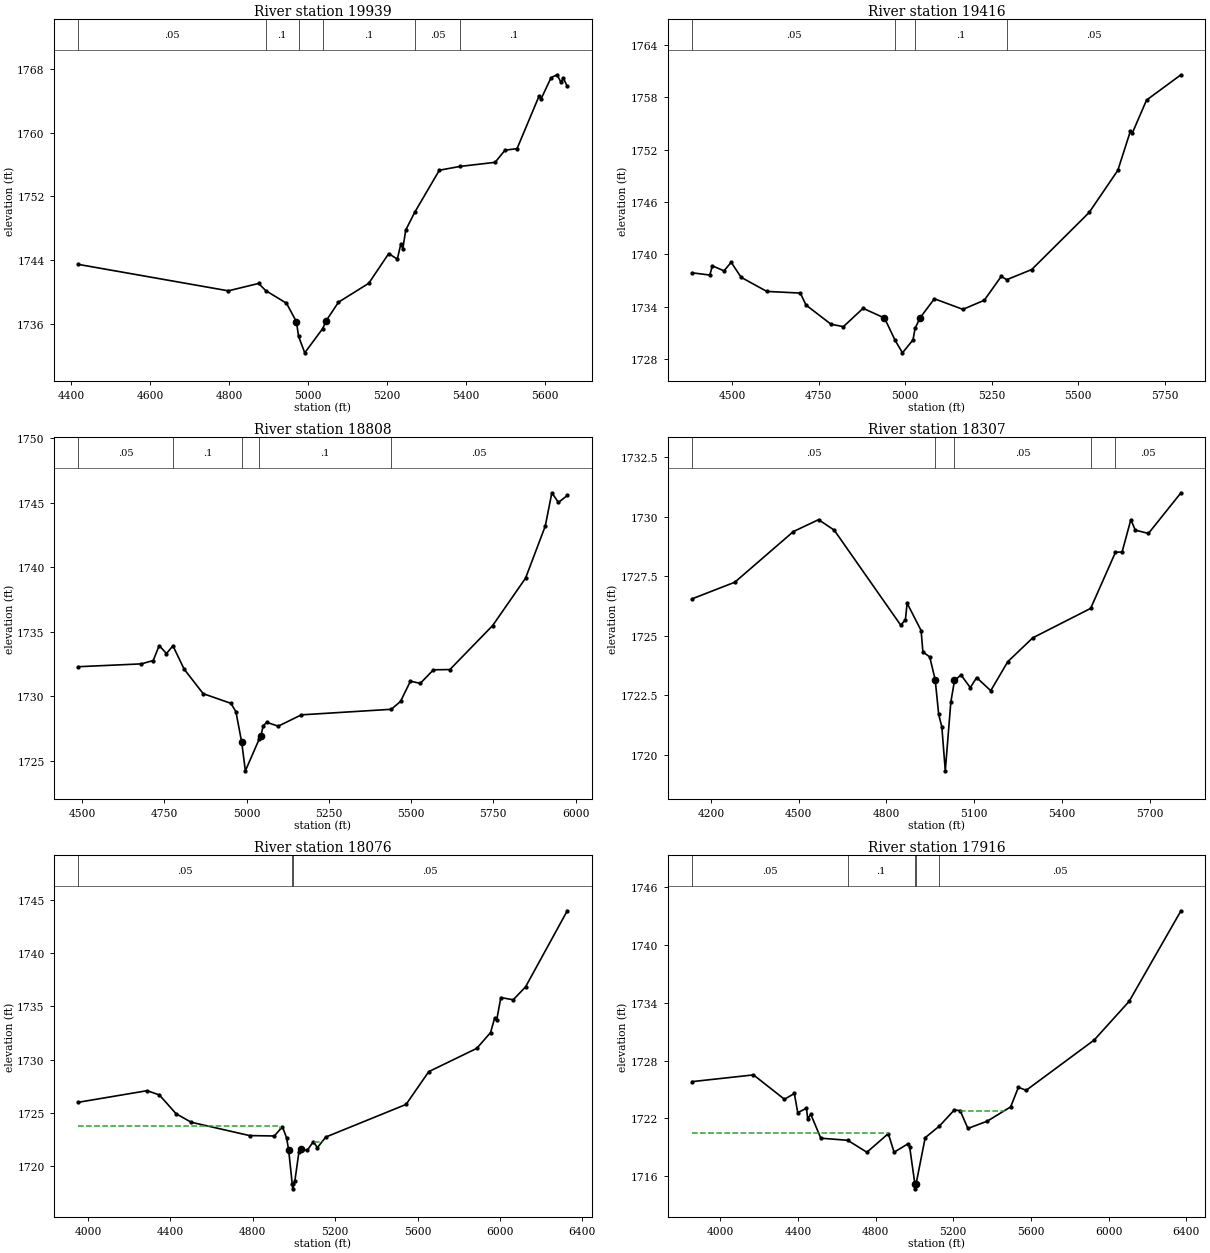
Type RM Length L Ch R = 1 ,19939   ,523,523,523
BEGIN DESCRIPTION:
NASSE CREEK 34.0
END DESCRIPTION:
XS GIS Cut Line= 2
      2729907.36     10056270.35      2728744.19     10055845.01
#Sta/Elev= 30
  4417.8 1743.45  4797.8 1740.12  4874.5 1741.05  4892.6 1740.14  4945.1 1738.56
  4970.3 1736.22  4975.7 1734.39  4991.3 1732.31  5036.7 1735.36  5044.8 1736.29
  5076.8 1738.69  5153.5 1741.07    5204 1744.81  5225.8 1744.11  5234.5 1745.98
  5239.8 1745.42  5247.1 1747.77  5270.1 1750.03  5332.3 1755.31  5384.8 1755.79
  5473.4  1756.3  5498.6 1757.83  5529.1 1758.03  5584.9 1764.66  5590.2 1764.32
  5615.4 1766.98  5630.4 1767.33  5640.6 1766.36  5645.9 1766.95  5656.3 1765.86
#Mann= 6 ,-1 , 0
  4417.8     .05       0  4892.6      .1       0  4975.7     .07       0
  5036.7      .1       0  5270.1     .05       0  5384.8      .1       0
Bank Sta=4970.3,5044.8
XS Rating Curve= 0 ,0
Exp/Cntr=0.3,0.1

Type RM Length L Ch R = 1 ,19416   ,608,608,608
BEGIN DESCRIPTION:
NASSE CREEK 33.0
END DESCRIPTION:
XS GIS Cut Line= 2
      2730098.34     10055723.47      2728726.81     10055384.93
#Sta/Elev= 30
  4383.9 1737.91  4435.3 1737.65  4442.9  1738.7  4476.5 1738.13  4497.1 1739.11
  4525.9 1737.39  4600.1 1735.78  4696.9 1735.59  4713.4 1734.22  4785.5 1732.03
  4821.3 1731.75  4878.2 1733.85    4940 1732.74  4970.9 1730.18    4992 1728.76
  5022.4 1730.24  5028.6 1731.57    5043 1732.77  5084.2 1734.94  5166.6 1733.73
  5228.4 1734.77  5277.4  1737.5  5293.3 1737.12  5365.4 1738.28  5531.3  1744.8
  5614.2 1749.62  5650.5  1754.1  5655.7 1753.85  5697.2 1757.65  5796.6 1760.54
#Mann= 4 ,-1 , 0
  4383.9     .05       0  4970.9     .07       0  5028.6      .1       0
  5293.3     .05       0
Bank Sta=4940,5043
XS Rating Curve= 0 ,0
Exp/Cntr=0.3,0.1

Type RM Length L Ch R = 1 ,18808   ,501,501,501
BEGIN DESCRIPTION:
NASSE CREEK 32.0
END DESCRIPTION:
XS GIS Cut Line= 3
       2730254.6     10055298.13      2729429.94     10054942.22
      2728841.53     10054942.22
#Sta/Elev= 30
  4488.1  1732.3  4679.9 1732.52  4715.9 1732.78    4734 1733.94  4756.2 1733.32
  4775.8 1733.92  4809.9 1732.11  4867.8 1730.21  4952.2 1729.46  4967.3 1728.81
  4984.9 1726.44    4996 1724.23  5037.9 1726.68  5043.3 1726.95  5050.3 1727.72
  5061.1 1727.99  5095.8 1727.69  5166.3 1728.57  5439.7    1729  5467.8 1729.61
  5497.8 1731.18  5527.8 1731.01  5567.8 1732.06  5617.8 1732.08  5747.8 1735.49
  5847.8 1739.16  5907.8  1743.2  5927.8 1745.78  5947.8 1745.03  5974.7 1745.57
#Mann= 5 ,-1 , 0
  4488.1     .05       0  4775.8      .1       0  4984.9     .07       0
  5037.9      .1       0  5439.7     .05       0
Bank Sta=4984.9,5043.3
XS Rating Curve= 0 ,0
Exp/Cntr=0.3,0.1

Type RM Length L Ch R = 1 ,18307   ,231,231,231
BEGIN DESCRIPTION:
NASSE CREEK 31.0
END DESCRIPTION:
XS GIS Cut Line= 3
      2730709.62     10054943.72      2729725.08     10054542.92
      2729117.47     10054577.64
#Sta/Elev= 30
  4135.3 1726.55  4281.7 1727.25    4482 1729.38    4568 1729.88  4621.5 1729.44
  4849.1 1725.44    4865 1725.68  4870.7 1726.37  4918.5 1725.22  4924.7 1724.32
  4947.9 1724.11  4966.6 1723.16  4978.7 1721.69  4989.5 1721.16  5001.2 1719.32
  5020.1  1722.2  5032.7 1723.12    5055 1723.35  5086.7 1722.82  5108.5 1723.24
  5156.6 1722.69  5214.9 1723.91  5300.1 1724.91  5498.2 1726.15    5583 1728.51
  5605.6 1728.52  5635.6 1729.88  5650.7 1729.44  5695.7  1729.3  5806.9 1731.01
#Mann= 5 ,-1 , 0
  4135.3     .05       0  4966.6    .035       0  5032.7     .05       0
  5498.2      .1       0    5583     .05       0
Bank Sta=4966.6,5032.7
XS Rating Curve= 0 ,0
Exp/Cntr=0.3,0.1

Type RM Length L Ch R = 1 ,18076   ,160,160,160
BEGIN DESCRIPTION:
Mapping XS 4dcad412
END DESCRIPTION:
XS GIS Cut Line= 3
      2730713.95     10054893.62      2730435.32     10054391.05
      2728635.82     10054414.48
#Sta/Elev= 30
  3952.6 1725.99  4286.7 1727.08  4346.2 1726.68  4427.5 1724.91  4501.3 1724.11
  4784.1 1722.86  4904.1 1722.82  4944.1 1723.69  4964.1 1722.63  4974.1 1721.48
  4991.1 1718.35  4993.9 1717.85  4997.1 1718.35  5004.1 1718.59  5024.1 1721.35
  5034.1  1721.6  5064.1 1721.47  5094.1 1722.29  5113.3 1721.72  5154.2 1722.72
  5544.2 1725.79  5654.2 1728.87  5887.3 1731.06  5954.2 1732.54  5974.2 1733.91
  5984.2 1733.72  6004.2 1735.84  6064.2 1735.63  6124.2 1736.84  6326.9    1744
#Mann= 3 ,-1 , 0
  3952.6     .05       0  4991.1     .04       0  4997.1     .05       0
#XS Ineff= 2 ,-1
  3952.6 4933.59 1723.74  5094.7 5139.89  1722.3
Permanent Ineff=
       T       T
Bank Sta=4974.1,5034.1
XS Rating Curve= 0 ,0
Exp/Cntr=0.3,0.1

Type RM Length L Ch R = 1 ,17916   ,229,229,229
BEGIN DESCRIPTION:
Mapping XS 1e32ef33
END DESCRIPTION:
XS GIS Cut Line= 3
      2730747.81     10054846.74      2730463.97     10054245.21
      2728611.62     10054237.41
#Sta/Elev= 30
  3854.6 1725.81  4171.2 1726.51  4330.7 1723.98  4381.7 1724.58    4399 1722.59
    4444 1723.05  4450.1 1721.96  4466.1 1722.42  4517.8 1719.94  4656.2 1719.72
  4755.2 1718.48  4865.2 1720.41  4895.2 1718.48  4965.2 1719.34  4975.2 1719.05
  5002.2 1715.18    5005 1714.68  5008.2 1715.18  5055.2 1719.99  5128.4  1721.2
  5205.2 1722.87  5235.2  1722.8  5275.2 1720.95  5375.2 1721.71  5495.2 1723.19
  5535.2 1725.22  5575.2 1724.91  5925.3 1730.13  6105.3 1734.15  6372.1 1743.55
#Mann= 5 ,-1 , 0
  3854.6     .05       0  4656.2      .1       0  5002.2     .07       0
  5008.2      .1       0  5128.4     .05       0
#XS Ineff= 2 ,-1
  3854.6 4864.34 1720.44    5235 5464.46 1722.81
Permanent Ineff=
       T       T
Bank Sta=5002.2,5008.2
XS Rating Curve= 0 ,0
Exp/Cntr=0.3,0.1