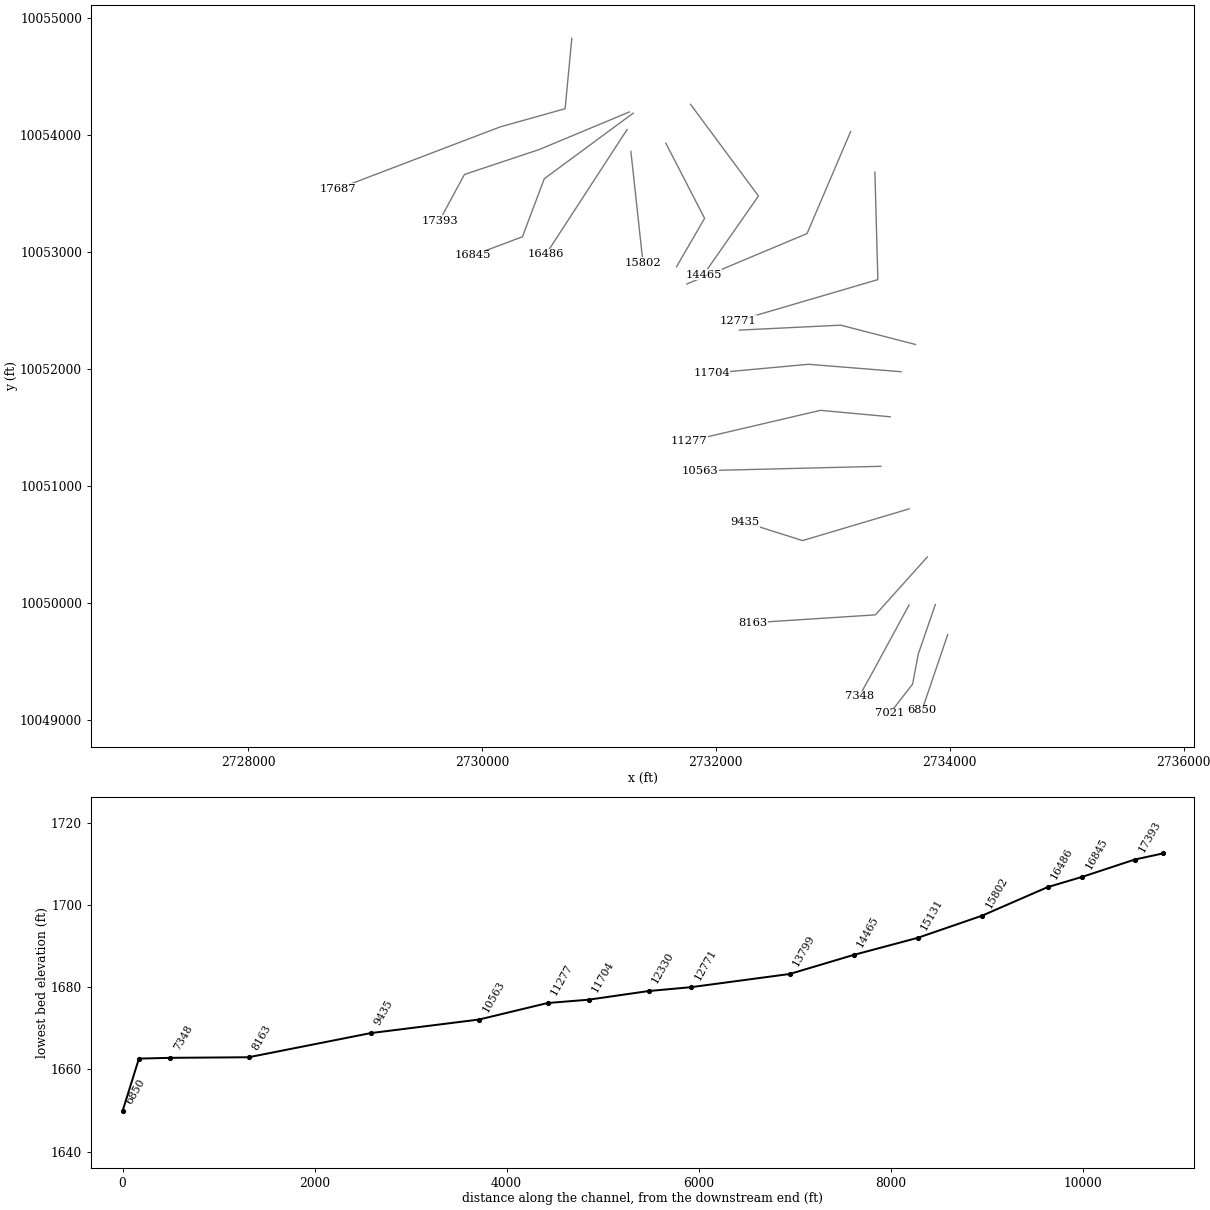
HEC-RAS study NASSE CREEK.prj: NASSE CREEK Base Level Engineering

--- NASSE CREEK.g01 (geometry) --- (continued)

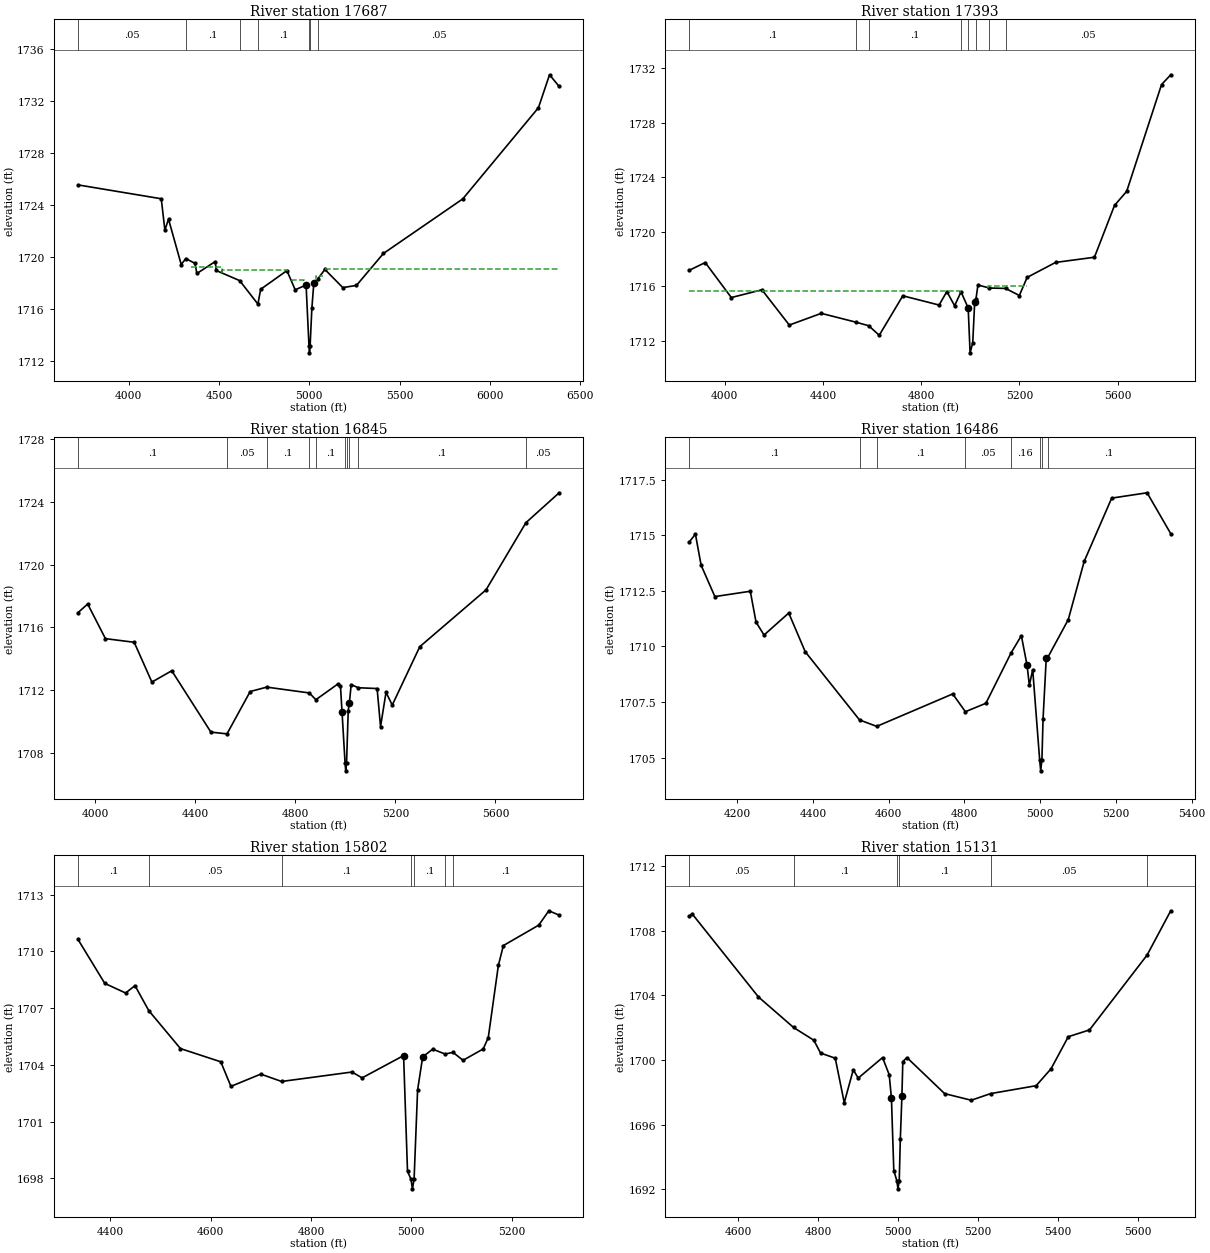
Type RM Length L Ch R = 1 ,17687   ,294,294,294
BEGIN DESCRIPTION:
NASSE CREEK 30.0
END DESCRIPTION:
XS GIS Cut Line= 4
      2730768.66     10054823.37      2730711.36     10054221.77
      2730154.07     10054065.52      2728768.61     10053536.86
#Sta/Elev= 30
  3718.2 1725.55  4179.9 1724.48    4200 1722.06  4220.1 1722.91  4290.4 1719.41
    4316 1719.87  4366.4  1719.5  4377.5 1718.72    4479 1719.64  4484.2 1718.95
  4614.1 1718.17  4715.4 1716.36  4730.6  1717.5    4876 1718.94  4921.9 1717.46
  4982.2 1717.83  4998.4  1713.1  5001.1  1712.6  5004.4  1713.1  5014.3 1716.06
    5025 1717.97  5046.2 1718.28  5086.3 1719.03  5185.6 1717.63  5261.4  1717.8
  5410.4 1720.26  5850.3 1724.47  6269.4  1731.5  6330.8 1734.04  6384.2 1733.14
#Mann= 7 ,-1 , 0
  3718.2     .05       0    4316      .1       0  4614.1     .05       0
  4715.4      .1       0  4998.4     .07       0  5004.4      .1       0
  5046.2     .05       0
#XS Ineff= 5 ,-1
 4345.53 4517.92 1719.24  4518.7 4875.49 1718.95 4901.83 4971.18 1718.23
  5036.9 5074.64 1718.49 5086.25  6384.2 1719.04
Permanent Ineff=
       T       T       T       T       T
Bank Sta=4982.2,5025
XS Rating Curve= 0 ,0
Exp/Cntr=0.3,0.1

Type RM Length L Ch R = 1 ,17393   ,548,548,548
BEGIN DESCRIPTION:
NASSE CREEK 29.0
END DESCRIPTION:
XS GIS Cut Line= 4
      2731260.77     10054194.14      2730487.61     10053871.77
      2729850.69     10053659.45      2729636.83     10053263.58
#Sta/Elev= 30
  3857.1 1717.18  3921.2 1717.74  4027.3 1715.17  4151.9 1715.74  4263.4 1713.15
  4393.4 1714.01  4532.9 1713.37  4586.6  1713.1  4629.5  1712.4  4725.5  1715.3
  4873.1 1714.62  4904.7 1715.61  4936.3 1714.57  4962.5 1715.59  4991.6  1714.4
  4999.3 1711.11  5010.1 1711.85    5018 1714.82  5023.3 1715.07  5031.2 1716.09
  5078.2 1715.87  5143.7 1715.84  5199.8 1715.32  5231.5 1716.65  5347.4 1717.75
  5505.5 1718.13  5587.3 1721.94  5636.8 1722.97  5778.6 1730.81  5816.1 1731.53
#Mann= 8 ,-1 , 0
  3857.1      .1       0  4532.9     .05       0  4586.6      .1       0
  4962.5     .16       0  4991.6     .07       0  5023.3     .16       0
  5078.2      .1       0  5143.7     .05       0
#XS Ineff= 2 ,-1
  3857.1 4959.53 1715.65  5073.5 5229.15 1716.03
Permanent Ineff=
       T       T
Bank Sta=4991.6,5018
XS Rating Curve= 0 ,0
Exp/Cntr=0.3,0.1

Type RM Length L Ch R = 1 ,16845   ,359,359,359
BEGIN DESCRIPTION:
NASSE CREEK 28.0
END DESCRIPTION:
XS GIS Cut Line= 4
      2731292.97     10054183.41      2730533.26     10053623.05
      2730346.69     10053127.05      2729924.72     10052968.24
#Sta/Elev= 30
  3930.2 1716.94  3969.3 1717.49  4040.3 1715.29  4155.2 1715.06  4226.1 1712.53
  4305.5 1713.25  4462.1 1709.35  4526.5 1709.24  4619.2 1711.93  4685.5 1712.21
  4855.6 1711.84  4881.9 1711.41 4969.12  1712.4  4980.3 1712.29  4986.5 1710.65
  4998.7 1707.39  5001.4 1706.89  5004.7 1707.39  5011.3  1710.7  5016.2 1711.23
  5023.1 1712.37    5052 1712.17  5126.9 1712.12  5140.6  1709.7  5162.5 1711.88
  5187.4 1711.07  5297.6 1714.78  5562.5 1718.39  5722.1 1722.66    5855 1724.56
#Mann= 10 ,-1 , 0
  3930.2      .1       0  4526.5     .05       0  4685.5      .1       0
  4855.6     .05       0  4881.9      .1       0  4998.7     .07       0
  5004.7      .1       0  5016.2     .16       0    5052      .1       0
  5722.1     .05       0
Bank Sta=4986.5,5016.2
XS Rating Curve= 0 ,0
Exp/Cntr=0.3,0.1

Type RM Length L Ch R = 1 ,16486   ,684,684,684
BEGIN DESCRIPTION:
NASSE CREEK 27.0
END DESCRIPTION:
XS GIS Cut Line= 2
      2731240.99     10054043.33      2730548.28     10052978.28
#Sta/Elev= 30
  4074.1 1714.71  4089.7 1715.05  4104.8 1713.65  4141.1 1712.24  4234.6 1712.48
  4249.8 1711.09  4270.9 1710.51  4336.1  1711.5  4379.6 1709.76    4523 1706.69
  4568.4  1706.4    4769 1707.86  4802.5 1707.06  4856.6 1707.44  4923.2 1709.71
  4950.2 1710.48  4965.3 1709.15  4971.3 1708.25  4980.2 1708.95  4998.5  1704.9
  5001.3  1704.4  5004.5  1704.9  5007.5 1706.73    5016 1709.49  5019.3 1709.48
    5074  1711.2  5116.2 1713.83  5188.7 1716.67  5282.2 1716.91  5344.6 1715.07
#Mann= 8 ,-1 , 0
  4074.1      .1       0    4523     .05       0  4568.4      .1       0
  4802.5     .05       0  4923.2     .16       0  4998.5     .07       0
  5004.5     .16       0  5019.3      .1       0
Bank Sta=4965.3,5016
XS Rating Curve= 0 ,0
Exp/Cntr=0.3,0.1

Type RM Length L Ch R = 1 ,15802   ,671,671,671
BEGIN DESCRIPTION:
NASSE CREEK 26.0
END DESCRIPTION:
XS GIS Cut Line= 2
      2731273.62     10053856.91      2731377.28     10052903.22
#Sta/Elev= 30
  4335.4 1710.64  4388.9 1708.31  4430.4  1707.8  4449.2 1708.19  4476.6 1706.87
  4539.8 1704.86  4620.2 1704.16  4640.4 1702.86  4699.9 1703.51  4741.4 1703.12
  4881.8 1703.62  4901.9 1703.31  4984.6 1704.49  4992.4 1698.37  4999.5 1697.94
  5002.2 1697.44  5005.5 1697.94  5012.5 1702.66  5022.6 1704.42  5042.7 1704.83
  5067.3 1704.57    5083 1704.66  5103.1 1704.24  5143.3 1704.84  5153.4 1705.44
  5173.5 1709.26  5183.5 1710.31    5254 1711.39  5274.1 1712.15  5294.7 1711.92
#Mann= 7 ,-1 , 0
  4335.4      .1       0  4476.6     .05       0  4741.4      .1       0
  4999.5     .07       0  5005.5      .1       0  5067.3     .16       0
    5083      .1       0
Bank Sta=4984.6,5022.6
XS Rating Curve= 0 ,0
Exp/Cntr=0.3,0.1

Type RM Length L Ch R = 1 ,15131   ,666,666,666
BEGIN DESCRIPTION:
Mapping XS 9071423e
END DESCRIPTION:
XS GIS Cut Line= 3
      2731572.16     10053927.37      2731903.87     10053284.69
      2731663.41     10052870.11
#Sta/Elev= 30
  4478.5 1708.91  4484.8 1709.06  4650.8 1703.91  4738.6 1702.02  4789.3 1701.23
  4805.9 1700.44  4842.7 1700.12  4865.2 1697.37  4887.7  1699.4  4900.1 1698.89
  4960.9 1700.16  4977.5  1699.1  4983.1 1697.64    4989 1693.17  4996.6 1692.54
  4999.4 1692.04  5002.6 1692.54  5005.3 1695.12 5009.32 1697.81  5011.5 1699.91
  5021.8 1700.16    5116 1697.93  5182.5 1697.52  5230.7 1697.93  5344.7 1698.42
    5382 1699.47    5425 1701.45    5478 1701.87  5621.9  1706.5    5681 1709.24
#Mann= 6 ,-1 , 0
  4478.5     .05       0  4738.6      .1       0  4996.6     .07       0
  5002.6      .1       0  5230.7     .05       0  5621.9      .1       0
Bank Sta=4983.1,5009.32
XS Rating Curve= 0 ,0
Exp/Cntr=0.3,0.1

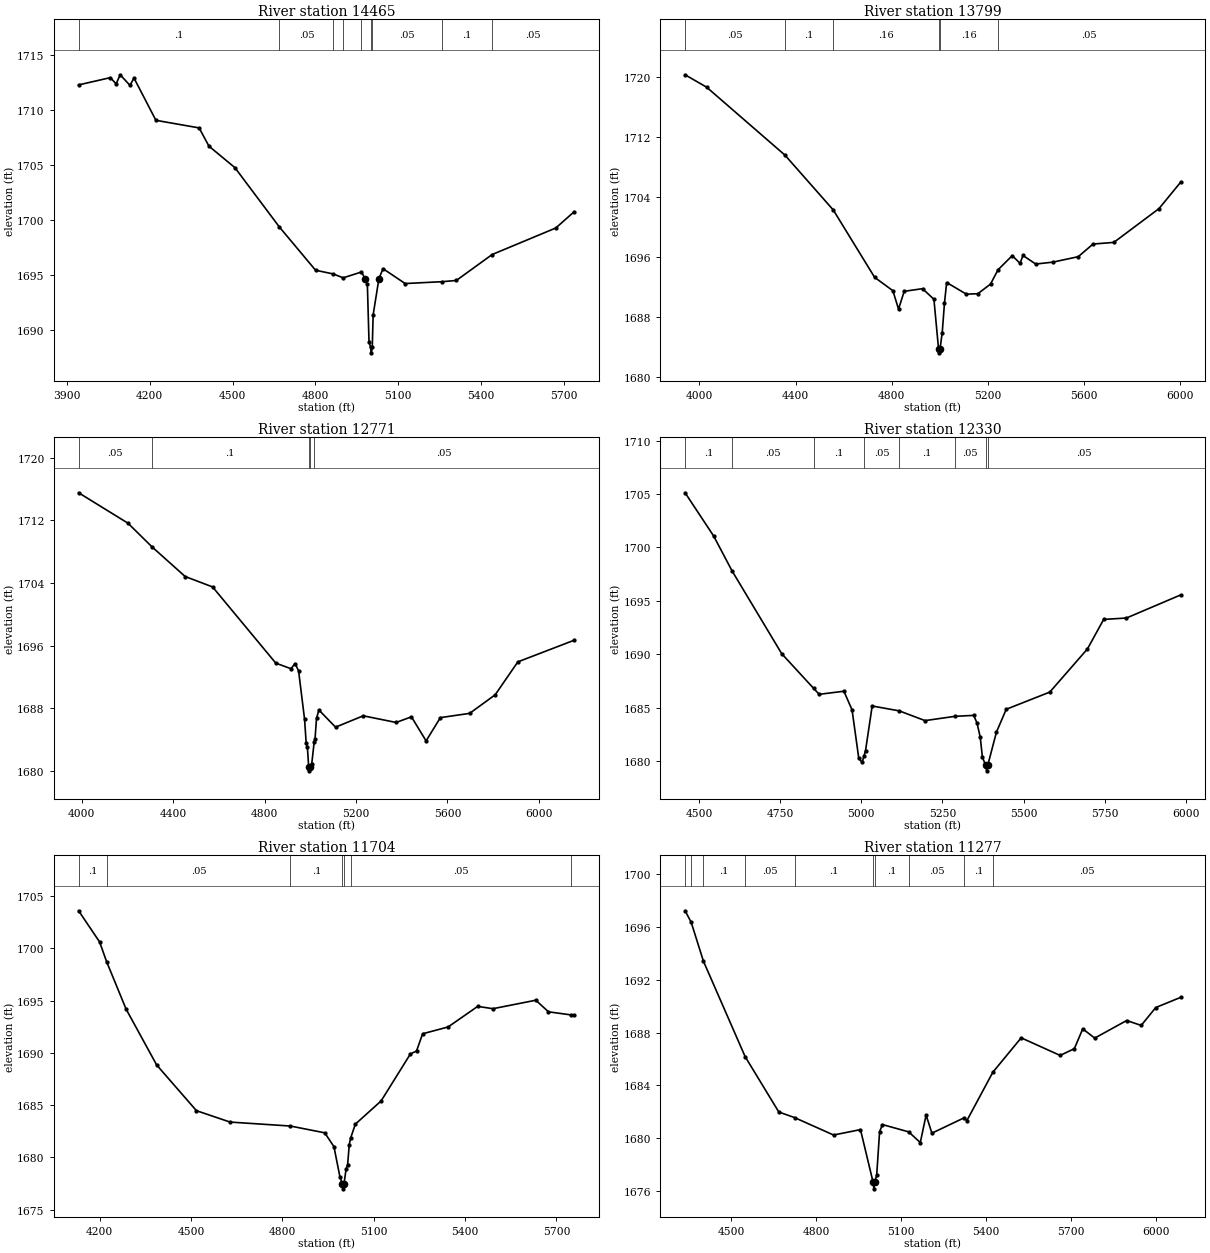
Type RM Length L Ch R = 1 ,14465   ,666,666,666
BEGIN DESCRIPTION:
NASSE CREEK 25.0
END DESCRIPTION:
XS GIS Cut Line= 3
      2731783.61      10054259.1      2732364.12     10053475.42
       2731895.6     10052803.74
#Sta/Elev= 30
  3942.4 1712.25  4057.3 1712.91  4078.2 1712.34  4092.8 1713.17  4128.2 1712.21
  4142.9 1712.87  4222.2 1709.03  4378.7 1708.34  4414.2 1706.68  4508.1 1704.73
  4669.6 1699.32  4800.3  1695.4  4864.7 1695.06  4900.3 1694.71  4966.5 1695.24
  4980.7 1694.58  4987.8 1694.13  4993.8 1688.87  4999.6 1688.39  5002.3 1687.89
  5005.6 1688.39  5008.7 1691.33  5029.6 1694.63  5044.5 1695.54  5124.7 1694.19
  5259.4 1694.36  5309.9 1694.47  5439.8 1696.83    5670 1699.24  5736.6 1700.72
#Mann= 9 ,-1 , 0
  3942.4      .1       0  4669.6     .05       0  4864.7     .16       0
  4900.3      .1       0  4966.5     .05       0  4999.6     .04       0
  5005.6     .05       0  5259.4      .1       0  5439.8     .05       0
Bank Sta=4980.7,5029.6
XS Rating Curve= 0 ,0
Exp/Cntr=0.3,0.1

Type RM Length L Ch R = 1 ,13799   ,1028,1028,1028
BEGIN DESCRIPTION:
NASSE CREEK 24.0
END DESCRIPTION:
XS GIS Cut Line= 3
      2733152.15     10054026.51      2732779.62     10053154.46
      2731752.15     10052723.18
#Sta/Elev= 30
  3940.1 1720.26  4030.1  1718.6  4355.9 1709.56    4557 1702.26  4728.7 1693.31
  4804.9 1691.52  4828.5 1689.07  4852.1 1691.44  4928.3 1691.79  4975.8 1690.38
  4995.1 1683.75  4997.8 1683.25  5001.1 1683.75  5010.4 1685.95  5019.8 1689.91
  5028.8 1692.61  5110.9 1691.06  5158.5 1691.12  5211.4  1692.4  5242.5  1694.3
  5301.8 1696.19  5334.3 1695.16  5346.5 1696.21  5399.4 1695.07  5470.7 1695.32
  5576.6 1696.05    5638 1697.73  5724.6 1697.95  5912.7 1702.45  6002.7 1705.96
#Mann= 6 ,-1 , 0
  3940.1     .05       0  4355.9      .1       0    4557     .16       0
  4995.1     .07       0  5001.1     .16       0  5242.5     .05       0
Bank Sta=4995.1,5001.1
XS Rating Curve= 0 ,0
Exp/Cntr=0.3,0.1

Type RM Length L Ch R = 1 ,12771   ,441,441,441
BEGIN DESCRIPTION:
NASSE CREEK 23.0
END DESCRIPTION:
XS GIS Cut Line= 3
      2733359.59     10053679.43      2733384.99     10052760.76
      2732186.98      10052409.4
#Sta/Elev= 30
  3986.8 1715.51  4202.6 1711.63  4306.4 1708.65  4452.7 1704.83  4572.7  1703.5
  4849.2 1693.78  4915.4 1693.07  4933.5 1693.72  4948.8 1692.81  4975.1 1686.61
  4982.2 1683.53  4987.4 1683.08    4993 1680.54  4995.7 1680.04    4999 1680.54
  5006.4 1680.93  5017.2 1683.74  5020.8  1684.1  5027.3 1686.73  5037.7  1687.8
  5110.6 1685.61  5231.6 1687.06  5375.7 1686.21  5442.5 1686.93  5506.6 1683.86
  5569.2 1686.83  5697.1 1687.37  5808.8 1689.74  5907.9 1693.94  6154.3  1696.7
#Mann= 5 ,-1 , 0
  3986.8     .05       0  4306.4      .1       0    4993     .07       0
    4999      .1       0  5017.2     .05       0
Bank Sta=4993,4999
XS Rating Curve= 0 ,0
Exp/Cntr=0.3,0.1

Type RM Length L Ch R = 1 ,12330   ,626,626,626
BEGIN DESCRIPTION:
NASSE CREEK 22.0
END DESCRIPTION:
XS GIS Cut Line= 3
      2733706.76     10052206.18      2733067.49     10052371.29
      2732201.57     10052329.05
#Sta/Elev= 30
    4457 1705.12  4545.1 1701.07  4601.9  1697.8  4754.8 1690.06  4853.3 1686.81
  4870.3 1686.26  4946.4 1686.55  4971.6  1684.8  4992.3 1680.26  5002.6 1679.89
  5008.2 1680.48    5013 1680.98  5033.6 1685.17  5117.2 1684.71  5196.4  1683.8
  5288.4  1684.2  5346.5 1684.29  5356.6 1683.58  5366.6 1682.25  5373.3 1680.37
  5383.6  1679.6  5386.3  1679.1  5389.6  1679.6  5416.6 1682.73  5446.7 1684.86
    5581 1686.47    5697 1690.51    5747 1693.27  5817.1  1693.4  5984.2 1695.56
#Mann= 8 ,-1 , 0
    4457      .1       0  4601.9     .05       0  4853.3      .1       0
  5008.2     .05       0  5117.2      .1       0  5288.4     .05       0
  5383.6     .07       0  5389.6     .05       0
Bank Sta=5383.6,5389.6
XS Rating Curve= 0 ,0
Exp/Cntr=0.3,0.1

Type RM Length L Ch R = 1 ,11704   ,427,427,427
BEGIN DESCRIPTION:
NASSE CREEK 21.0
END DESCRIPTION:
XS GIS Cut Line= 3
      2733583.99     10051973.35      2732792.32     10052036.86
      2731963.02      10051960.7
#Sta/Elev= 30
  4131.2  1703.6  4200.2 1700.61  4222.9 1698.74  4287.2 1694.18  4387.5 1688.84
    4518 1684.47  4628.3 1683.38  4826.6    1683  4939.3 1682.35  4969.4 1681.03
  4989.5 1678.08  4996.6 1677.49  4999.3 1676.99  5002.6 1677.49  5009.4 1678.89
  5014.4 1679.29  5019.7 1681.22  5024.6 1681.88  5039.7 1683.18  5124.3  1685.4
  5220.5  1689.9  5240.6 1690.18  5260.7 1691.83  5344.2 1692.48  5441.4 1694.45
  5491.6 1694.23  5632.2 1695.04  5673.9 1693.93  5749.2 1693.63  5758.2 1693.62
#Mann= 7 ,-1 , 0
  4131.2      .1       0  4222.9     .05       0  4826.6      .1       0
  4996.6     .07       0  5002.6      .1       0  5024.6     .05       0
  5749.2      .1       0
Bank Sta=4996.6,5002.6
XS Rating Curve= 0 ,0
Exp/Cntr=0.3,0.1

Type RM Length L Ch R = 1 ,11277   ,714,714,714
BEGIN DESCRIPTION:
NASSE CREEK 20.0
END DESCRIPTION:
XS GIS Cut Line= 3
       2733490.8     10051588.12      2732893.92     10051643.15
      2731772.81     10051380.86
#Sta/Elev= 30
  4336.1 1697.21  4357.6 1696.34    4401 1693.39  4548.2 1686.18  4667.2 1681.99
  4722.7 1681.57  4860.7 1680.25  4955.7 1680.66  5000.3 1676.68  5003.1 1676.18
  5006.3 1676.68    5013 1677.21  5023.3 1680.51  5033.5 1681.04  5125.9 1680.49
  5167.1 1679.68  5187.6 1681.76  5208.1 1680.39  5322.8 1681.56  5331.4 1681.33
  5423.4    1685  5523.5  1687.6  5661.2 1686.27  5711.4 1686.78    5741 1688.28
  5783.3 1687.58  5896.2 1688.91  5947.6 1688.54  5998.9 1689.89  6086.9 1690.66
#Mann= 10 ,-1 , 0
  4336.1      .1       0  4357.6     .05       0    4401      .1       0
  4548.2     .05       0  4722.7      .1       0  5000.3     .07       0
  5006.3      .1       0  5125.9     .05       0  5322.8      .1       0
  5423.4     .05       0
Bank Sta=5000.3,5006.3
XS Rating Curve= 0 ,0
Exp/Cntr=0.3,0.1

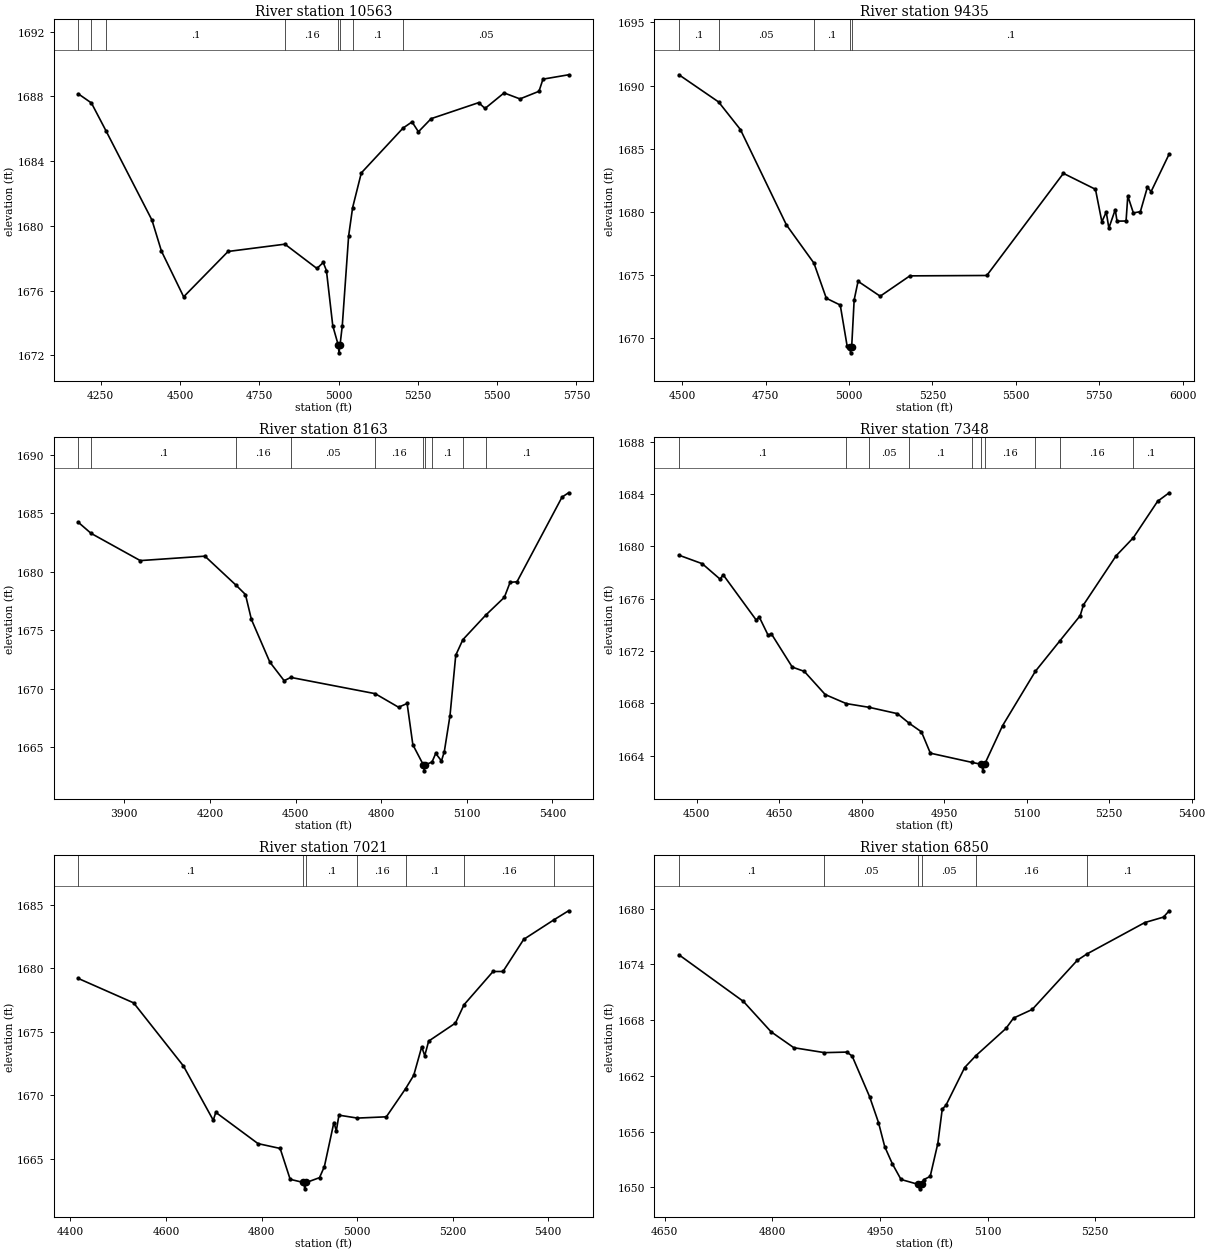
Type RM Length L Ch R = 1 ,10563   ,1128,1128,1128
BEGIN DESCRIPTION:
NASSE CREEK 19.0
END DESCRIPTION:
XS GIS Cut Line= 2
       2733410.4     10051164.78      2731865.17     10051126.68
#Sta/Elev= 30
  4179.3 1688.15  4220.4 1687.59  4266.4 1685.87  4411.3 1680.36  4441.3 1678.44
  4511.3 1675.62  4651.4 1678.42  4830.6 1678.87  4931.5 1677.37  4951.5 1677.74
  4961.5 1677.24  4981.5 1673.83  4998.5 1672.66  5001.2 1672.16  5004.5 1672.66
  5011.5 1673.84  5031.5 1679.38  5044.1 1681.13  5071.5 1683.27  5203.1 1686.04
  5231.4 1686.42  5251.6 1685.81  5291.6 1686.62  5441.6 1687.61  5461.6 1687.25
  5521.6 1688.21  5571.7 1687.84  5631.7 1688.31  5644.3 1689.06    5725 1689.33
#Mann= 8 ,-1 , 0
  4179.3      .1       0  4220.4     .05       0  4266.4      .1       0
  4830.6     .16       0  4998.5     .07       0  5004.5     .16       0
  5044.1      .1       0  5203.1     .05       0
Bank Sta=4998.5,5004.5
XS Rating Curve= 0 ,0
Exp/Cntr=0.3,0.1

Type RM Length L Ch R = 1 ,9435    ,1272,1272,1272
BEGIN DESCRIPTION:
NASSE CREEK 18.0
END DESCRIPTION:
XS GIS Cut Line= 3
      2733651.74     10050800.73      2732741.52     10050529.78
      2732246.19     10050686.42
#Sta/Elev= 30
  4490.6 1690.86  4609.4 1688.71  4674.7 1686.53  4812.7 1678.98  4895.1 1675.96
  4932.2 1673.18    4974 1672.64  4994.8 1669.37  5002.3 1669.36    5005 1668.86
  5008.3 1669.36  5015.7 1673.05  5027.4 1674.52  5093.7 1673.34  5182.6 1674.95
  5413.2 1674.98  5642.8 1683.06  5738.9  1681.8  5758.1 1679.23  5771.2    1680
  5779.1 1678.73  5798.2 1680.19  5803.5 1679.28  5830.6 1679.29  5835.8 1681.27
  5852.5 1679.93  5873.5 1680.03  5894.5 1681.96  5905.7 1681.62  5959.8 1684.59
#Mann= 5 ,-1 , 0
  4490.6      .1       0  4609.4     .05       0  4895.1      .1       0
  5002.3     .07       0  5008.3      .1       0
Bank Sta=5002.3,5008.3
XS Rating Curve= 0 ,0
Exp/Cntr=0.3,0.1

Type RM Length L Ch R = 1 ,8163    ,815,815,815
BEGIN DESCRIPTION:
NASSE CREEK 17.0
END DESCRIPTION:
XS GIS Cut Line= 3
      2733808.35     10050390.11      2733363.83     10049894.78
      2732313.96     10049827.04
#Sta/Elev= 30
    3739 1684.23  3783.5 1683.29  3955.9 1680.96  4182.4 1681.34  4291.3 1678.86
  4324.4 1678.06  4345.3 1675.93  4409.9 1672.28    4460 1670.69  4483.5 1670.97
    4779 1669.58  4860.9 1668.42  4890.9 1668.74    4911 1665.21    4948 1663.48
  4950.8 1662.98    4954 1663.48  4978.2 1663.74  4991.1 1664.47  5011.2 1663.83
  5021.2 1664.62  5041.2 1667.71  5061.3 1672.87  5086.3  1674.2  5165.7 1676.28
  5231.6 1677.82  5251.7  1679.1  5275.9 1679.15  5433.7 1686.39  5456.6 1686.76
#Mann= 10 ,-1 , 0
    3739     .05       0  3783.5      .1       0  4291.3     .16       0
  4483.5     .05       0    4779     .16       0    4948     .07       0
    4954     .16       0  4978.2      .1       0  5086.3     .05       0
  5165.7      .1       0
Bank Sta=4948,4954
XS Rating Curve= 0 ,0
Exp/Cntr=0.3,0.1

Type RM Length L Ch R = 1 ,7348    ,327,327,327
BEGIN DESCRIPTION:
NASSE CREEK 16.0
END DESCRIPTION:
XS GIS Cut Line= 3
      2733651.72     10049979.48      2733351.13     10049424.87
      2733224.83     10049197.53
#Sta/Elev= 30
  4468.1 1679.32  4510.4 1678.67  4542.8 1677.49  4548.5 1677.82  4608.4 1674.37
  4614.1 1674.59  4630.3 1673.19  4635.9 1673.32    4674 1670.77  4695.9 1670.44
  4733.9 1668.67  4772.1 1667.98  4814.2 1667.69  4865.1 1667.21  4886.7 1666.47
  4908.8 1665.82    4925 1664.19  5001.2 1663.48  5017.6 1663.34  5020.4 1662.84
  5023.6 1663.34  5056.2 1666.29  5115.9 1670.45  5159.9 1672.75  5197.3  1674.7
  5203.2 1675.52  5262.5 1679.27  5293.8 1680.65    5338 1683.44    5359 1684.09
#Mann= 10 ,-1 , 0
  4468.1      .1       0  4772.1     .16       0  4814.2     .05       0
  4886.7      .1       0  5001.2     .16       0  5017.6     .07       0
  5023.6     .16       0  5115.9      .1       0  5159.9     .16       0
  5293.8      .1       0
Bank Sta=5017.6,5023.6
XS Rating Curve= 0 ,0
Exp/Cntr=0.3,0.1

Type RM Length L Ch R = 1 ,7021    ,171,171,171
BEGIN DESCRIPTION:
Mapping XS 849748d1
END DESCRIPTION:
XS GIS Cut Line= 4
      2733876.32     10049983.12      2733730.49     10049559.54
      2733681.88      10049302.6      2733487.44     10049052.59
#Sta/Elev= 30
  4416.6 1679.21  4532.3 1677.29  4636.6 1672.32    4699 1668.05  4704.3 1668.67
  4792.7 1666.21    4839 1665.83    4860  1663.4  4887.8 1663.15  4890.6 1662.65
  4893.8 1663.15  4921.4 1663.53  4931.6  1664.4  4951.5 1667.87  4956.6 1667.22
  4962.1 1668.45  5000.7 1668.22  5061.3 1668.32  5101.7 1670.54  5118.7 1671.59
  5135.4 1673.83  5141.7 1673.13  5149.9 1674.28    5206  1675.7  5223.9 1677.14
  5284.7 1679.76  5305.5 1679.76  5348.9 1682.29  5412.2 1683.83  5442.8 1684.54
#Mann= 7 ,-1 , 0
  4416.6      .1       0  4887.8     .07       0  4893.8      .1       0
  5000.7     .16       0  5101.7      .1       0  5223.9     .16       0
  5412.2      .1       0
Bank Sta=4887.8,4893.8
XS Rating Curve= 0 ,0
Exp/Cntr=0.3,0.1

Type RM Length L Ch R = 1 ,6850    ,466,466,466
BEGIN DESCRIPTION:
NASSE CREEK 15.0
END DESCRIPTION:
XS GIS Cut Line= 2
      2733981.88      10049725.4      2733761.94     10049078.25
#Sta/Elev= 30
  4669.7 1675.03  4759.6 1670.01  4798.2 1666.74  4829.9 1665.03  4872.6  1664.5
  4903.8 1664.56  4911.2 1664.13  4935.5 1659.76  4947.9 1656.98  4956.6 1654.38
  4967.2 1652.54  4979.3 1650.85  5002.4 1650.34  5005.1 1649.84  5008.4 1650.34
  5010.7 1650.82    5020 1651.18  5030.6 1654.71  5036.8 1658.42    5042 1658.84
  5068.1  1662.9  5083.5 1664.16  5125.6  1667.1  5136.2 1668.22  5162.3 1669.15
  5225.1 1674.44  5238.5 1675.12  5319.2  1678.5  5345.3 1679.09  5353.2 1679.77
#Mann= 6 ,-1 , 0
  4669.7      .1       0  4872.6     .05       0  5002.4    .035       0
  5008.4     .05       0  5083.5     .16       0  5238.5      .1       0
Bank Sta=5002.4,5008.4
XS Rating Curve= 0 ,0
Exp/Cntr=0.3,0.1