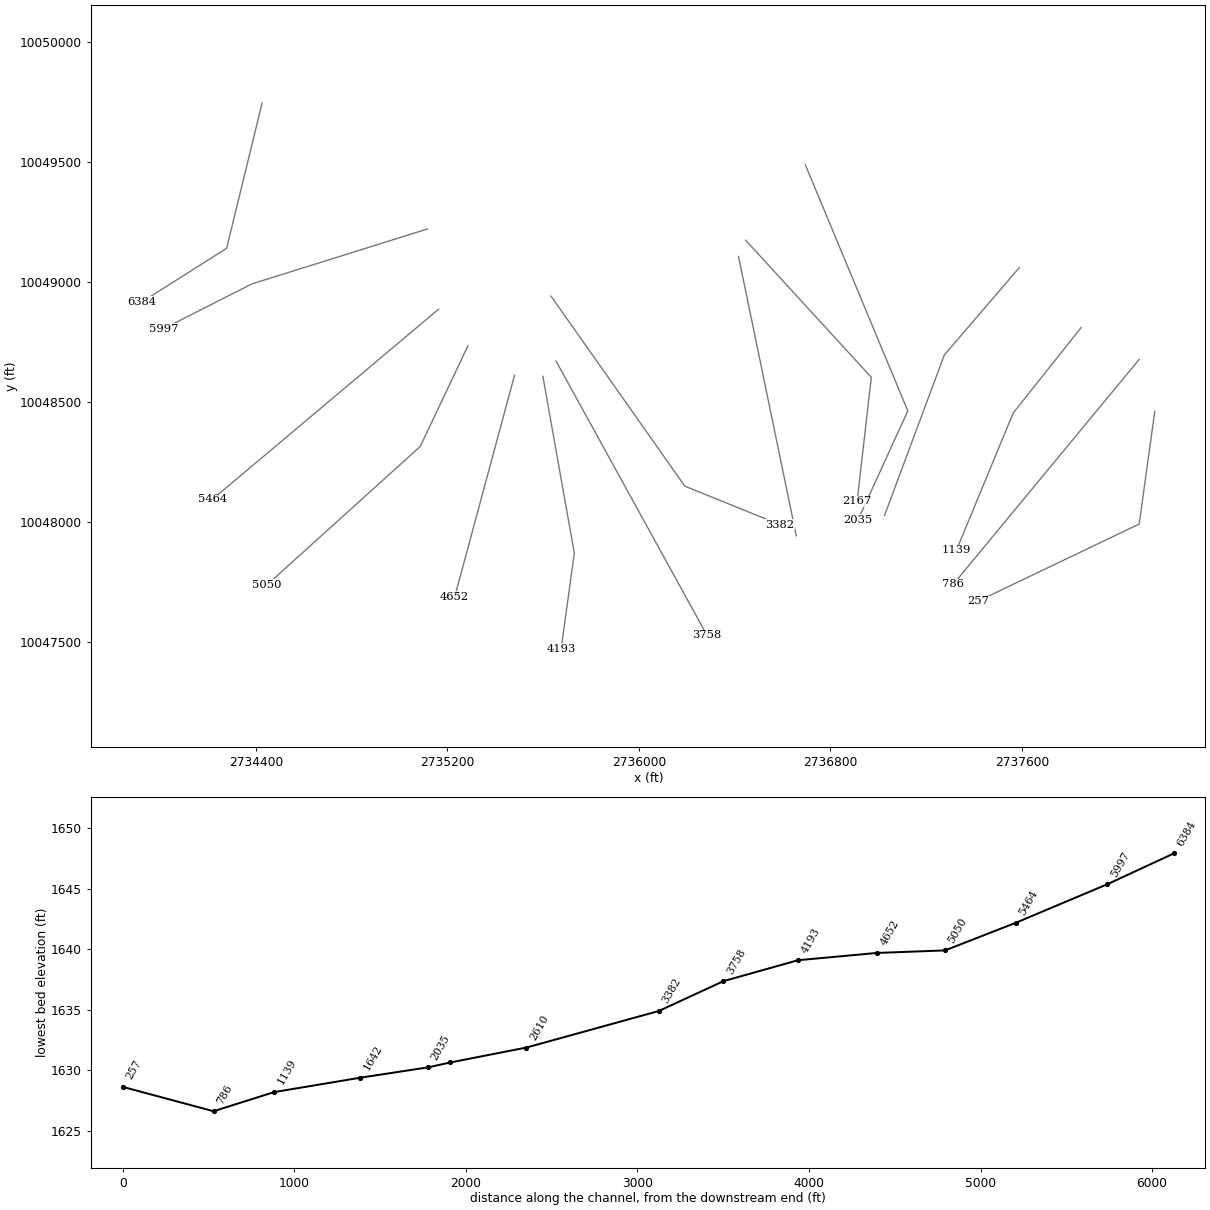
HEC-RAS study NASSE CREEK.prj: NASSE CREEK Base Level Engineering

--- NASSE CREEK.g01 (geometry) --- (continued)

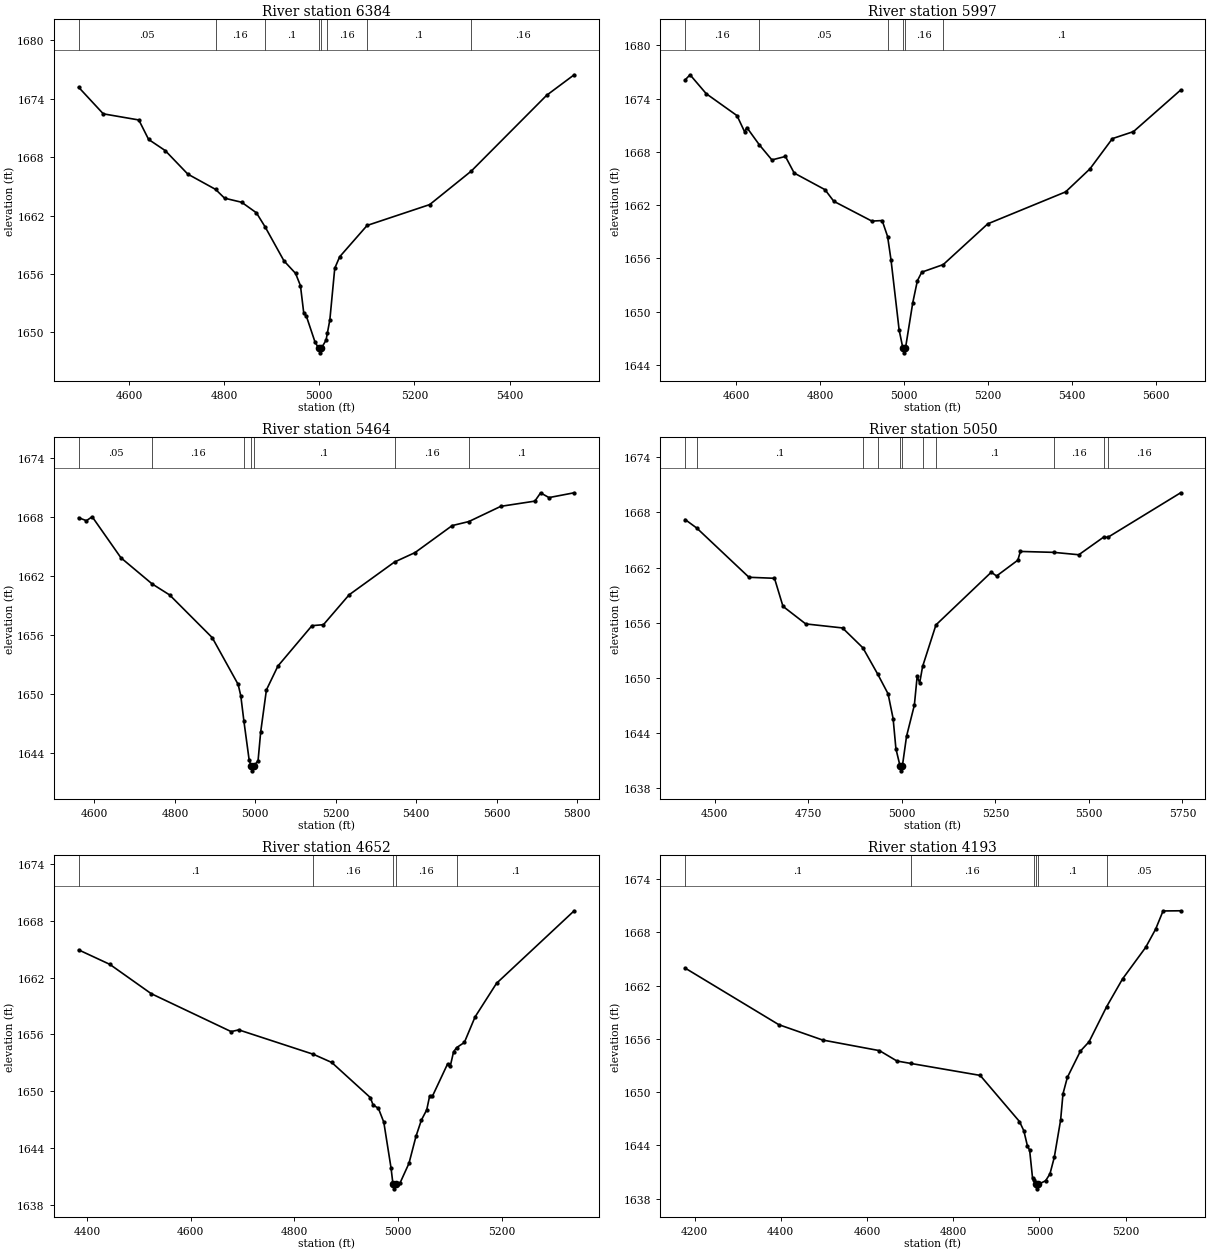
Type RM Length L Ch R = 1 ,6384    ,387,387,387
BEGIN DESCRIPTION:
NASSE CREEK 14.0
END DESCRIPTION:
XS GIS Cut Line= 3
       2734426.4     10049746.61      2734278.23     10049141.24
       2733924.5     10048918.05
#Sta/Elev= 30
  4494.3 1675.18  4546.1 1672.45  4620.8 1671.82  4641.4 1669.82  4676.2 1668.68
  4723.8 1666.26  4782.2 1664.69    4801 1663.79    4837 1663.37  4867.9 1662.29
  4886.4 1660.83  4925.9 1657.35  4950.2 1656.07  4960.5 1654.81  4967.5 1651.97
  4972.7 1651.71  4991.4 1648.98  4998.7 1648.41  5001.5 1647.91  5004.7 1648.41
  5014.3 1649.21  5017.1 1649.94  5022.3  1651.3  5032.6 1656.59  5042.9 1657.77
  5100.6 1660.99  5232.1 1663.13  5319.5 1666.57  5478.1 1674.36  5535.8 1676.46
#Mann= 8 ,-1 , 0
  4494.3     .05       0  4782.2     .16       0  4886.4      .1       0
  4998.7     .07       0  5004.7      .1       0  5017.1     .16       0
  5100.6      .1       0  5319.5     .16       0
Bank Sta=4998.7,5004.7
XS Rating Curve= 0 ,0
Exp/Cntr=0.3,0.1

Type RM Length L Ch R = 1 ,5997    ,533,533,533
BEGIN DESCRIPTION:
NASSE CREEK 13.0
END DESCRIPTION:
XS GIS Cut Line= 3
      2735116.47     10049221.68      2734384.07     10048993.07
      2734015.74     10048806.79
#Sta/Elev= 30
    4479 1676.11  4490.8 1676.69  4529.3 1674.56  4602.6 1672.09  4620.7 1670.27
    4626 1670.75  4656.1 1668.78  4685.7  1667.1  4717.9 1667.49  4738.8 1665.62
  4812.1 1663.75  4833.1 1662.44  4923.7 1660.21  4948.3 1660.27  4961.2 1658.47
  4969.3 1655.85  4988.7 1647.94  4997.7 1645.87  5000.4 1645.37  5003.7 1645.87
  5021.1 1651.01  5032.1 1653.49  5042.6 1654.46  5093.7 1655.31  5199.7  1659.9
  5385.1  1663.5    5443 1666.09  5496.5  1669.5  5546.7 1670.29    5659 1674.97
#Mann= 6 ,-1 , 0
    4479     .16       0  4656.1     .05       0  4961.2     .16       0
  4997.7     .07       0  5003.7     .16       0  5093.7      .1       0
Bank Sta=4997.7,5003.7
XS Rating Curve= 0 ,0
Exp/Cntr=0.3,0.1

Type RM Length L Ch R = 1 ,5464    ,414,414,414
BEGIN DESCRIPTION:
NASSE CREEK 12.0
END DESCRIPTION:
XS GIS Cut Line= 2
      2735163.03     10048887.26      2734218.94     10048095.57
#Sta/Elev= 30
  4560.6 1667.96    4580 1667.66  4594.3 1668.06  4665.8 1663.88  4743.4 1661.22
  4786.8  1660.1  4892.8 1655.75  4957.2 1650.99  4963.8 1649.83  4971.6 1647.23
  4984.6 1643.29  4989.4 1642.69  4992.1 1642.19  4995.4 1642.69  5006.7  1643.2
  5013.2 1646.13  5027.5 1650.43  5056.1 1652.86  5140.8 1656.97  5169.3 1657.07
  5233.1 1660.11    5346 1663.45    5397 1664.41  5489.4 1667.16  5530.8 1667.57
  5610.3 1669.12  5694.9 1669.65  5709.2 1670.49  5730.1 1670.01  5792.7  1670.5
#Mann= 7 ,-1 , 0
  4560.6     .05       0  4743.4     .16       0  4971.6      .1       0
  4989.4     .07       0  4995.4      .1       0    5346     .16       0
  5530.8      .1       0
Bank Sta=4989.4,4995.4
XS Rating Curve= 0 ,0
Exp/Cntr=0.3,0.1

Type RM Length L Ch R = 1 ,5050    ,398,398,398
BEGIN DESCRIPTION:
NASSE CREEK 11.0
END DESCRIPTION:
XS GIS Cut Line= 3
      2735285.79     10048734.87      2735086.81     10048315.73
      2734447.54     10047739.97
#Sta/Elev= 30
  4420.8 1667.23  4451.8 1666.31  4591.5 1660.95  4659.7 1660.84  4682.4 1657.79
  4743.1 1655.88  4841.5 1655.44  4895.9 1653.28  4935.5 1650.42  4963.2 1648.28
  4976.7 1645.59  4984.2  1642.3  4995.4  1640.4  4998.1  1639.9  5001.4  1640.4
  5012.6 1643.66  5033.5 1647.05    5041 1650.18  5047.7 1649.46  5055.5 1651.25
  5091.2 1655.77    5239  1661.5  5253.2 1661.09    5310 1662.81  5316.8 1663.76
  5406.1 1663.66    5473  1663.4    5539 1665.31  5550.8  1665.3  5745.1 1670.14
#Mann= 11 ,-1 , 0
  4420.8     .05       0  4451.8      .1       0  4895.9     .16       0
  4935.5      .1       0  4995.4     .07       0  5001.4      .1       0
  5055.5     .16       0  5091.2      .1       0  5406.1     .16       0
    5539     .05       0  5550.8     .16       0
Bank Sta=4995.4,5001.4
XS Rating Curve= 0 ,0
Exp/Cntr=0.3,0.1

Type RM Length L Ch R = 1 ,4652    ,459,459,459
BEGIN DESCRIPTION:
NASSE CREEK 10.0
END DESCRIPTION:
XS GIS Cut Line= 2
       2735480.5     10048612.05      2735230.73     10047689.15
#Sta/Elev= 30
  4384.1 1664.93  4444.3  1663.4    4524 1660.31  4678.3  1656.3  4693.1 1656.48
  4837.1  1653.9  4872.4 1653.04  4946.9 1649.33  4952.1 1648.56  4962.5 1648.19
  4972.9 1646.73  4986.8 1641.92  4990.6 1640.19  4993.3 1639.69  4996.6 1640.19
  5003.9 1640.27  5021.5 1642.39    5035 1645.24  5045.4 1646.95  5055.7 1648.03
  5061.3 1649.48  5066.5 1649.45    5096 1652.89  5101.2 1652.67  5107.5 1654.16
  5113.2  1654.6  5128.3 1655.15    5149 1657.85  5190.4  1661.4  5340.2 1669.06
#Mann= 5 ,-1 , 0
  4384.1      .1       0  4837.1     .16       0  4990.6     .07       0
  4996.6     .16       0  5113.2      .1       0
Bank Sta=4990.6,4996.6
XS Rating Curve= 0 ,0
Exp/Cntr=0.3,0.1

Type RM Length L Ch R = 1 ,4193    ,435,435,435
BEGIN DESCRIPTION:
NASSE CREEK 9.0
END DESCRIPTION:
XS GIS Cut Line= 3
      2735599.05      10048607.8      2735730.28     10047871.23
      2735675.24     10047473.28
#Sta/Elev= 30
  4177.9 1663.98  4395.3  1657.6  4496.9 1655.87    4629 1654.67  4669.6  1653.5
  4701.4 1653.23  4862.6 1651.88  4953.8 1646.68  4963.9 1645.64  4972.4  1643.9
  4977.4 1643.45  4984.1 1640.33  4986.8 1640.05  4991.2 1639.59    4994 1639.09
  4997.2 1639.59  5014.4    1640  5024.5 1640.77  5034.6 1642.64  5049.3 1646.85
  5054.8 1649.81  5064.9 1651.65  5095.2 1654.62  5115.3 1655.67  5156.1 1659.63
  5192.9 1662.75  5246.6 1666.31  5269.8 1668.37    5287 1670.42  5327.8 1670.44
#Mann= 6 ,-1 , 0
  4177.9      .1       0  4701.4     .16       0  4986.8      .1       0
  4991.2     .07       0  4997.2      .1       0  5156.1     .05       0
Bank Sta=4991.2,4997.2
XS Rating Curve= 0 ,0
Exp/Cntr=0.3,0.1

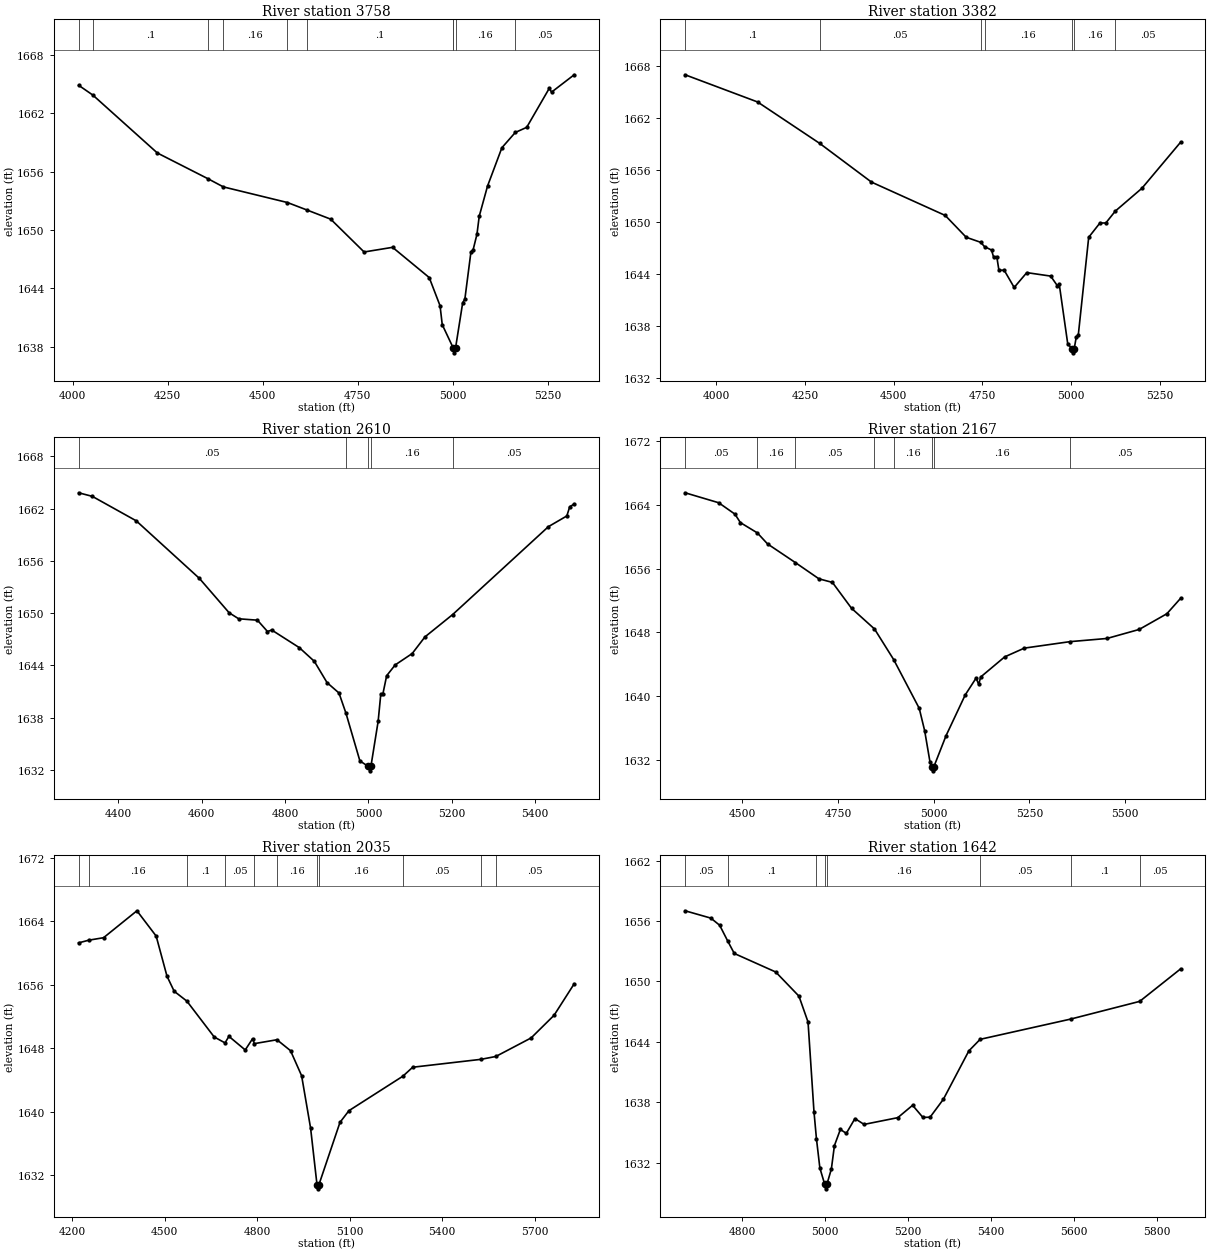
Type RM Length L Ch R = 1 ,3758    ,376,376,376
BEGIN DESCRIPTION:
NASSE CREEK 8.0
END DESCRIPTION:
XS GIS Cut Line= 2
      2735654.08     10048671.32      2736284.03      10047529.8
#Sta/Elev= 30
  4015.6  1664.9    4053 1663.89  4222.7 1657.93  4356.9 1655.26  4396.4 1654.44
  4565.1 1652.83  4615.8 1652.07  4678.8 1651.12  4766.7 1647.74  4841.6 1648.22
    4938 1645.11  4966.5 1642.21  4972.3 1640.26  5001.2 1637.86  5001.3 1637.86
    5004 1637.36  5007.3 1637.86  5026.1 1642.52  5031.8 1642.89  5047.8 1647.75
  5053.5 1647.96  5063.6 1649.56  5069.6 1651.42  5091.4 1654.52  5129.2 1658.47
  5164.4 1660.04  5194.5 1660.57  5254.1  1664.6  5259.8 1664.19  5319.4 1665.98
#Mann= 10 ,-1 , 0
  4015.6     .05       0    4053      .1       0  4356.9     .05       0
  4396.4     .16       0  4565.1     .05       0  4615.8      .1       0
  5001.2     .16       0  5001.3     .07       0  5007.3     .16       0
  5164.4     .05       0
Bank Sta=5001.3,5007.3
XS Rating Curve= 0 ,0
Exp/Cntr=0.3,0.1

Type RM Length L Ch R = 1 ,3382    ,772,772,772
BEGIN DESCRIPTION:
NASSE CREEK 7.0
END DESCRIPTION:
XS GIS Cut Line= 3
      2735632.89     10048942.29      2736191.71     10048150.63
      2736589.61     10047989.78
#Sta/Elev= 30
  3911.4    1667    4116 1663.86  4290.8 1659.09  4437.3 1654.61  4645.4 1650.76
  4704.6 1648.24  4745.4 1647.66  4756.5 1647.15    4776 1646.77  4782.1 1645.91
  4790.8 1646.01  4796.9 1644.43  4811.7 1644.44  4839.9 1642.45  4875.5 1644.16
  4942.9 1643.76  4961.7 1642.65  4967.1 1642.82  4991.2 1635.89  5003.4  1635.4
  5006.1  1634.9  5009.4  1635.4  5015.3 1636.77  5020.7 1636.91  5050.2 1648.24
  5081.9 1649.89  5098.5 1649.89  5125.2 1651.26  5200.4  1653.9  5309.6 1659.22
#Mann= 7 ,-1 , 0
  3911.4      .1       0  4290.8     .05       0  4745.4      .1       0
  4756.5     .16       0  5003.4     .07       0  5009.4     .16       0
  5125.2     .05       0
Bank Sta=5003.4,5009.4
XS Rating Curve= 0 ,0
Exp/Cntr=0.3,0.1

Type RM Length L Ch R = 1 ,2610    ,443,443,443
BEGIN DESCRIPTION:
NASSE CREEK 6.0
END DESCRIPTION:
XS GIS Cut Line= 2
      2736416.08     10049107.36      2736657.38      10047943.2
#Sta/Elev= 30
  4304.7 1663.81  4337.5  1663.4  4442.9 1660.59  4594.4 1653.98  4665.8 1650.03
  4688.7 1649.34  4733.7 1649.18  4757.8 1647.88    4768 1648.05  4834.1 1646.03
  4870.1 1644.46  4900.7 1642.01  4929.3 1640.82  4946.2 1638.48  4979.5 1633.02
  4999.9 1632.38  5002.6 1631.88  5005.9 1632.38  5023.3 1637.57  5029.6 1640.67
  5034.7 1640.72  5043.7  1642.8  5064.1 1644.04    5105 1645.35  5135.6 1647.26
  5201.9 1649.82  5431.8 1659.92    5476 1661.15  5482.8 1662.19  5493.6 1662.53
#Mann= 5 ,-1 , 0
  4304.7     .05       0  4946.2     .16       0  4999.9     .07       0
  5005.9     .16       0  5201.9     .05       0
Bank Sta=4999.9,5005.9
XS Rating Curve= 0 ,0
Exp/Cntr=0.3,0.1

Type RM Length L Ch R = 1 ,2167    ,132,132,132
BEGIN DESCRIPTION:
NASSE CREEK 5.0
END DESCRIPTION:
XS GIS Cut Line= 3
      2736445.68     10049175.14      2736970.65      10048603.6
      2736911.48     10048087.93
#Sta/Elev= 30
  4350.1 1665.52  4437.9 1664.27  4480.4 1662.84  4494.6 1661.78  4538.9 1660.49
  4565.5 1659.11  4638.2 1656.77  4699.9 1654.73  4735.1 1654.28    4785 1651.04
  4845.1 1648.44  4895.1 1644.61    4962 1638.49  4976.2 1635.68  4990.2 1631.74
  4994.1 1631.15  4996.9 1630.65  5000.1 1631.15  5032.3 1635.08  5082.2 1640.17
  5110.6 1642.28  5117.4  1641.5  5122.7 1642.42  5185.3 1644.94  5236.7 1646.04
  5355.8 1646.85  5452.7 1647.25  5536.8 1648.38  5609.2 1650.35  5645.2 1652.29
#Mann= 8 ,-1 , 0
  4350.1     .05       0  4538.9     .16       0  4638.2     .05       0
  4845.1      .1       0  4895.1     .16       0  4994.1     .07       0
  5000.1     .16       0  5355.8     .05       0
Bank Sta=4994.1,5000.1
XS Rating Curve= 0 ,0
Exp/Cntr=0.3,0.1

Type RM Length L Ch R = 1 ,2035    ,393,393,393
BEGIN DESCRIPTION:
NASSE CREEK 4.0
END DESCRIPTION:
XS GIS Cut Line= 3
      2736695.48     10049488.38      2737123.05      10048463.9
      2736915.63     10048010.96
#Sta/Elev= 30
  4220.3 1661.29  4253.5 1661.63  4301.2 1661.94  4409.5 1665.34  4471.9 1662.15
  4507.1 1657.08  4530.4 1655.18  4571.5 1653.94  4660.3 1649.41  4695.5 1648.66
    4708 1649.49    4761 1647.77  4784.8 1649.19  4790.8 1648.57    4864 1649.06
    4908 1647.68    4944 1644.52  4973.2 1637.89    4994 1630.74  4996.8 1630.24
    5000 1630.74  5068.5 1638.63  5097.7 1640.11  5272.7 1644.46  5304.5 1645.59
  5526.7 1646.59  5574.4 1646.95  5688.9 1649.29  5763.4 1652.15  5828.6 1656.12
#Mann= 11 ,-1 , 0
  4220.3      .1       0  4253.5     .16       0  4571.5      .1       0
  4695.5     .05       0  4790.8      .1       0    4864     .16       0
    4994     .07       0    5000     .16       0  5272.7     .05       0
  5526.7      .1       0  5574.4     .05       0
Bank Sta=4994,5000
XS Rating Curve= 0 ,0
Exp/Cntr=0.3,0.1

Type RM Length L Ch R = 1 ,1642    ,503,503,503
BEGIN DESCRIPTION:
NASSE CREEK 3.0
END DESCRIPTION:
XS GIS Cut Line= 3
      2737588.75     10049060.83      2737275.45     10048696.74
      2737025.83     10048028.25
#Sta/Elev= 30
  4662.5 1657.01  4724.6 1656.28  4745.8 1655.57    4765 1654.02    4781 1652.77
  4880.8 1650.93  4936.8 1648.53  4958.7 1645.96    4973 1637.06  4978.9 1634.39
  4987.2 1631.46  4998.5 1629.89  5001.2 1629.39  5004.5 1629.89  5014.9 1631.36
  5022.3 1633.69  5036.6 1635.29  5050.9  1634.9  5071.7 1636.37  5093.7 1635.79
  5174.9 1636.46  5210.6 1637.69  5235.5 1636.48  5252.8 1636.51  5284.8 1638.29
  5346.1 1643.09  5373.3 1644.24  5591.2 1646.25  5757.7 1648.01  5856.4 1651.24
#Mann= 8 ,-1 , 0
  4662.5     .05       0    4765      .1       0  4978.9     .16       0
  4998.5     .07       0  5004.5     .16       0  5373.3     .05       0
  5591.2      .1       0  5757.7     .05       0
Bank Sta=4998.5,5004.5
XS Rating Curve= 0 ,0
Exp/Cntr=0.3,0.1

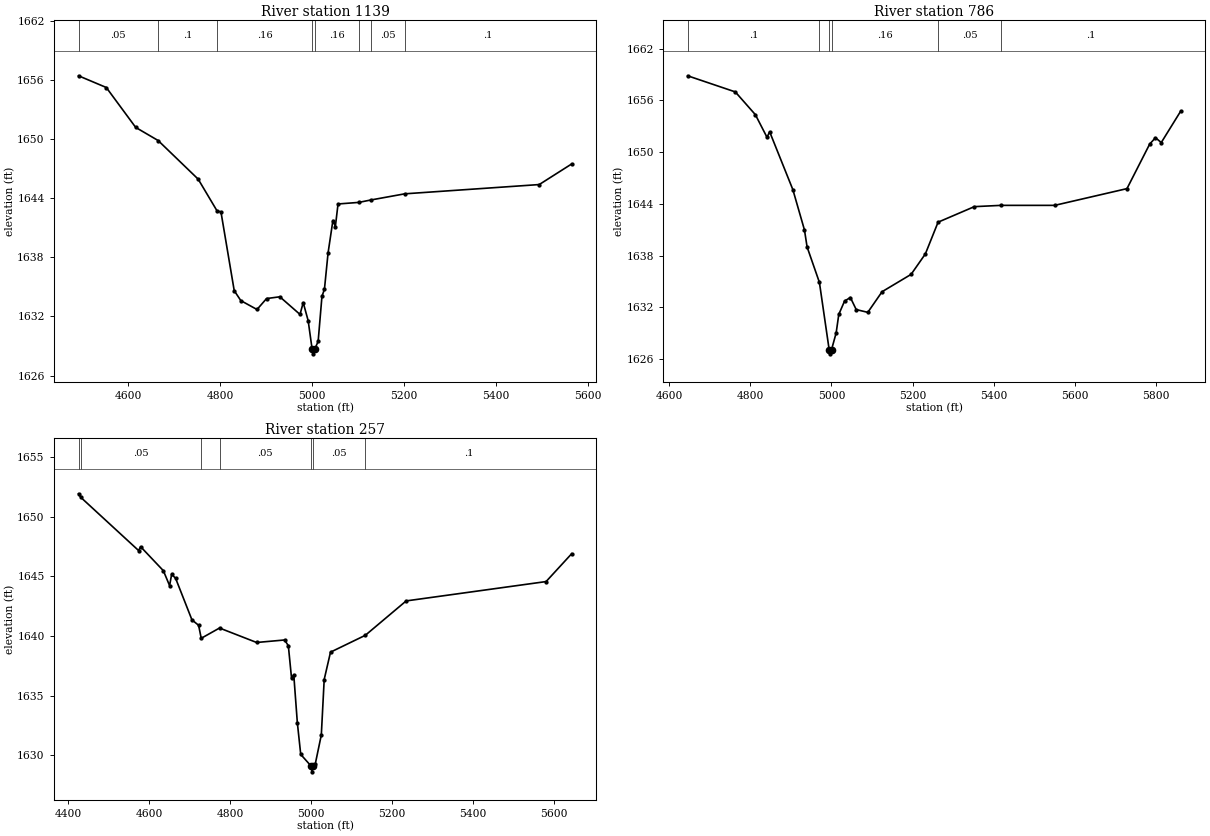
Type RM Length L Ch R = 1 ,1139    ,353,353,353
BEGIN DESCRIPTION:
NASSE CREEK 2.0
END DESCRIPTION:
XS GIS Cut Line= 3
      2737846.97     10048811.06      2737563.32     10048455.43
      2737326.26     10047883.95
#Sta/Elev= 30
  4491.2 1656.42  4551.7 1655.23  4615.7 1651.18  4664.5 1649.85  4751.7 1645.93
  4792.9  1642.7  4801.3 1642.61  4830.2 1634.61  4844.6  1633.6  4879.8  1632.7
  4900.6 1633.81  4929.5 1633.99  4973.4  1632.2  4980.4  1633.4  4991.2 1631.56
  4999.7  1628.7  5002.4  1628.2  5005.7  1628.7  5012.9 1629.46  5021.2 1634.04
  5026.6 1634.75  5034.5 1638.44    5045 1641.73  5050.4 1641.12  5056.2 1643.41
  5101.5 1643.57  5127.1 1643.81  5201.5 1644.44  5494.2 1645.38  5564.8 1647.47
#Mann= 8 ,-1 , 0
  4491.2     .05       0  4664.5      .1       0  4792.9     .16       0
  4999.7     .07       0  5005.7     .16       0  5101.5      .1       0
  5127.1     .05       0  5201.5      .1       0
Bank Sta=4999.7,5005.7
XS Rating Curve= 0 ,0
Exp/Cntr=0.3,0.1

Type RM Length L Ch R = 1 ,786     ,529,529,529
BEGIN DESCRIPTION:
Mapping XS 7bee903f
END DESCRIPTION:
XS GIS Cut Line= 2
      2738089.37     10048678.44      2737312.96     10047741.53
#Sta/Elev= 30
  4645.1 1658.85  4762.8 1656.98  4812.3 1654.34    4841 1651.72  4847.5 1652.36
  4904.8 1645.65  4933.4 1640.98  4939.9 1639.01  4970.3  1634.9  4994.3 1627.12
    4997 1626.62  5000.3 1627.12  5011.6 1629.04  5018.1 1631.19  5032.4 1632.74
  5046.7 1633.15  5061.1 1631.75  5089.7 1631.43  5124.9 1633.82  5196.5 1635.83
  5231.7  1638.2  5263.1 1641.88  5352.5 1643.68  5418.3 1643.83  5550.8 1643.83
  5729.2 1645.77  5785.2 1650.93  5799.5 1651.67  5813.8 1651.11  5861.9 1654.76
#Mann= 6 ,-1 , 0
  4645.1      .1       0  4970.3     .16       0  4994.3     .07       0
  5000.3     .16       0  5263.1     .05       0  5418.3      .1       0
Bank Sta=4994.3,5000.3
XS Rating Curve= 0 ,0
Exp/Cntr=0.3,0.1

Type RM Length L Ch R = 1 ,257     ,0,0,0
BEGIN DESCRIPTION:
NASSE CREEK 1.0
END DESCRIPTION:
XS GIS Cut Line= 3
      2738154.48     10048461.44      2738089.37     10047992.67
      2737416.58     10047671.47
#Sta/Elev= 30
    4425 1651.91    4431  1651.6  4573.4 1647.16  4578.5 1647.48  4634.7 1645.47
  4650.1 1644.22  4655.2 1645.17    4665 1644.83  4705.4 1641.35  4721.8  1640.9
  4728.3 1639.81  4773.5 1640.67  4865.2 1639.46  4934.3 1639.67  4943.6 1639.19
  4951.5 1636.47    4957 1636.76  4965.8 1632.76  4974.2 1630.09  4999.4 1629.13
  5002.1 1628.63  5005.4 1629.13  5010.1 1629.28  5025.1 1631.72  5032.2 1636.36
  5047.8 1638.65  5133.8 1640.06  5234.8 1642.94  5580.6 1644.56  5643.8 1646.89
#Mann= 7 ,-1 , 0
    4425      .1       0    4431     .05       0  4728.3     .16       0
  4773.5     .05       0  4999.4     .04       0  5005.4     .05       0
  5133.8      .1       0
Bank Sta=4999.4,5005.4
XS Rating Curve= 0 ,0
Exp/Cntr=0.3,0.1

Chan Stop Cuts=-1
Use User Specified Reach Order=0
Composite Channel Slope=5