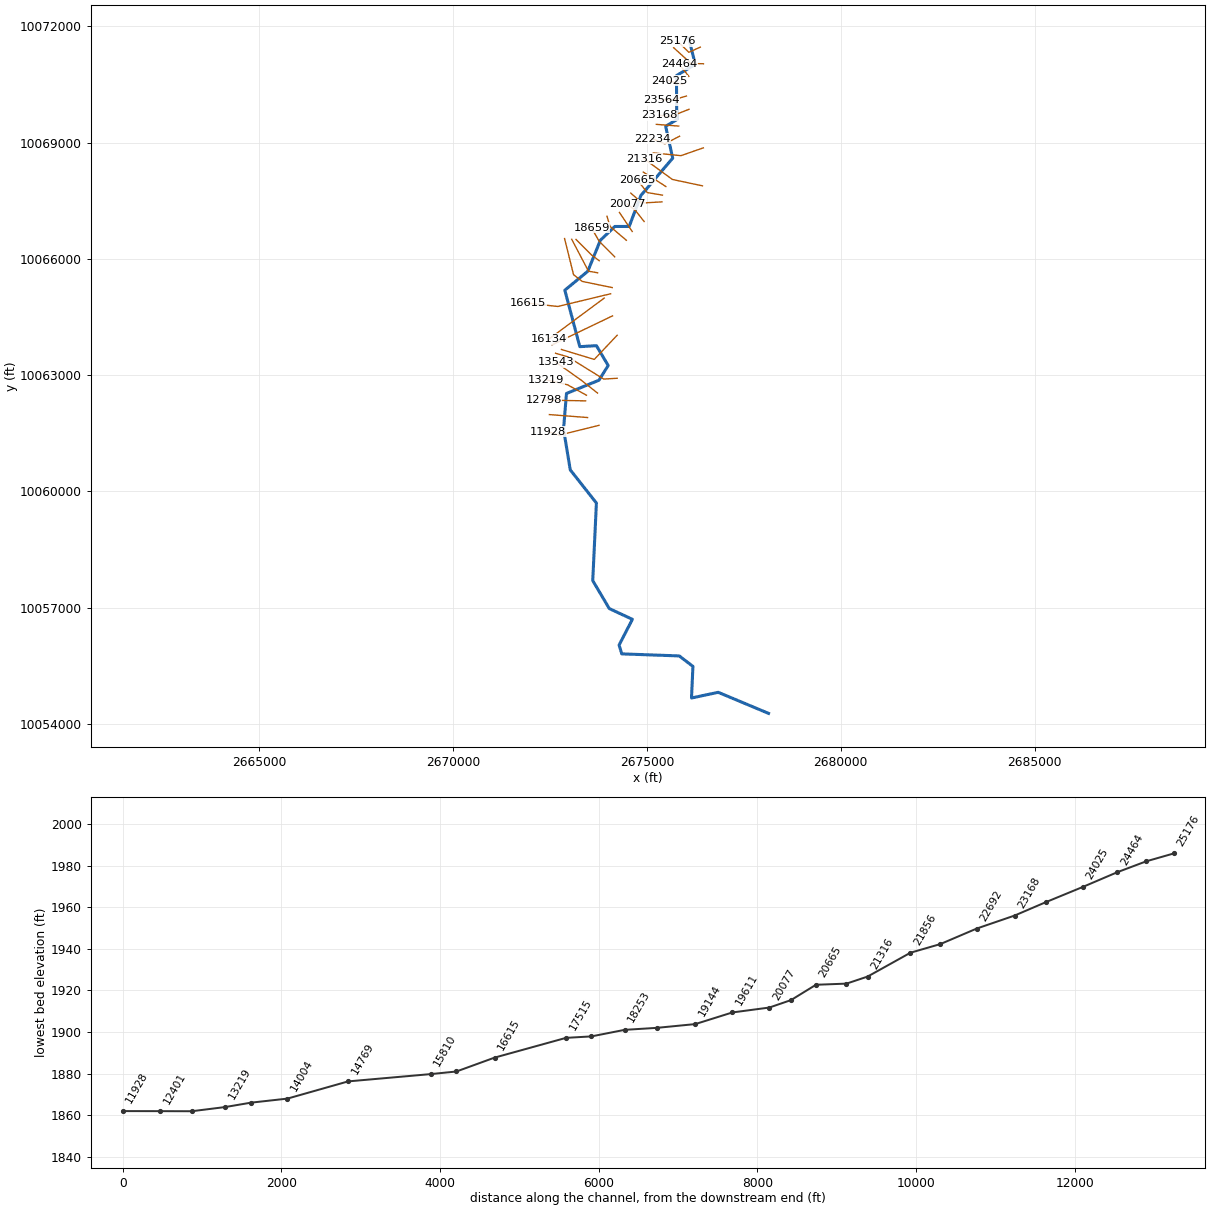
--- NORTH CREEK.prj (project) ---

Proj Title=NORTH CREEK Base Level Engineering
Current Plan=p01
Default Exp/Contr=0.3,0.1
English Units
Geom File=g01
Flow File=f01
Plan File=p01
Y Axis Title=Elevation
X Axis Title(PF)=Main Channel Distance
X Axis Title(XS)=Station
BEGIN DESCRIPTION:
NORTH CREEK
END DESCRIPTION:
DSS Export Rating Curves= 0
DSS Export Rating Curve Sorted= 0
DSS Export Volume Flow Curves= 0
DXF OffsetX= 0
DXF OffsetY= 0
DXF ScaleX= 1
DXF ScaleY= 10

--- NORTH CREEK.p01 (plan) ---

Plan Title=Multiple Run
Short Identifier=Multiple
Geom File=g01
Flow File=f01
Subcritical Flow
K Sum by GR= 0
Std Step Tol= 0.01
Critical Tol= 0.01
Num of Std Step Trials= 20
Max Error Tol= 0.3
Flow Tol Ratio= 0.001
Split Flow NTrial= 30
Split Flow Tol= 0.02
Split Flow Ratio= 0.02
Log Output Level= 0
Friction Slope Method= 1
Unsteady Friction Slope Method= 2
Unsteady Bridges Friction Slope Method= 1
Parabolic Critical Depth
Global Vel Dist=  1 , 1 , 1
Global Log Level= 0
CheckData=True
Encroach Param= -1, 0, 0, 0
BEGIN DESCRIPTION:
Multiple Run
END DESCRIPTION:

--- NORTH CREEK.f01 (steady flow) ---

Flow Title=Multiple
Program Version=4.10
Number of Profiles= 7
Profile Names=10-year,25-year,50-year,1pct_min,100-year,1pct_plu,500-year
River Rch & RM=NORTH CREEK,Reach-1         ,25176
    1434    2124    2732    2560    3462    4683    5562
River Rch & RM=NORTH CREEK,Reach-1         ,23168
    2204    3330    4338    4112    5561    7520    9139
River Rch & RM=NORTH CREEK,Reach-1         ,16615
    3937    6070    8013    7676   10381   14039   17442
River Rch & RM=NORTH CREEK,Reach-1         ,8709
    4137    6373    8408    8047   10882   14717   18249
Boundary for River Rch & Prof#=NORTH CREEK,Reach-1         , 1
Up Type= 0
Dn Type= 3
Dn Slope=0.002
Boundary for River Rch & Prof#=NORTH CREEK,Reach-1         , 2
Up Type= 0
Dn Type= 3
Dn Slope=0.002
Boundary for River Rch & Prof#=NORTH CREEK,Reach-1         , 3
Up Type= 0
Dn Type= 3
Dn Slope=0.002
Boundary for River Rch & Prof#=NORTH CREEK,Reach-1         , 4
Up Type= 0
Dn Type= 3
Dn Slope=0.002
Boundary for River Rch & Prof#=NORTH CREEK,Reach-1         , 5
Up Type= 0
Dn Type= 3
Dn Slope=0.002
Boundary for River Rch & Prof#=NORTH CREEK,Reach-1         , 6
Up Type= 0
Dn Type= 3
Dn Slope=0.002
Boundary for River Rch & Prof#=NORTH CREEK,Reach-1         , 7
Up Type= 0
Dn Type= 3
Dn Slope=0.002
DSS Import GetInterval= 0
DSS Import GetPeak= 0
DSS Import FillOption= 0

--- NORTH CREEK.g01 (geometry) ---

Geom Title=Existing Conditions
Program Version=4.10

River Reach=NORTH CREEK     ,Reach-1
Reach XY= 30
      2676078.47     10071693.73      2676246.84      10071019.5
      2675761.53     10070732.65      2675767.68     10069594.04
      2675481.62     10069424.03       2675664.2     10068600.81
      2674843.05     10067636.65      2674540.98     10066837.12
      2674171.58     10066837.81       2673799.3     10066482.78
      2673473.63     10065681.05      2672882.01     10065192.34
       2673267.8     10063735.01      2673696.32     10063760.96
      2674000.15     10063248.21       2673761.4     10062868.52
        2672924.     10062526.42      2672848.35     10061602.71
      2673021.75     10060555.06      2673696.03     10059698.46
      2673601.98     10057695.35       2674028.6      10056974.3
      2674624.39     10056696.87      2674281.15     10056032.51
      2674350.81     10055804.92       2675832.8     10055752.14
      2676185.91     10055482.32       2676149.5     10054665.96
      2676838.62     10054812.74      2678136.38     10054269.13

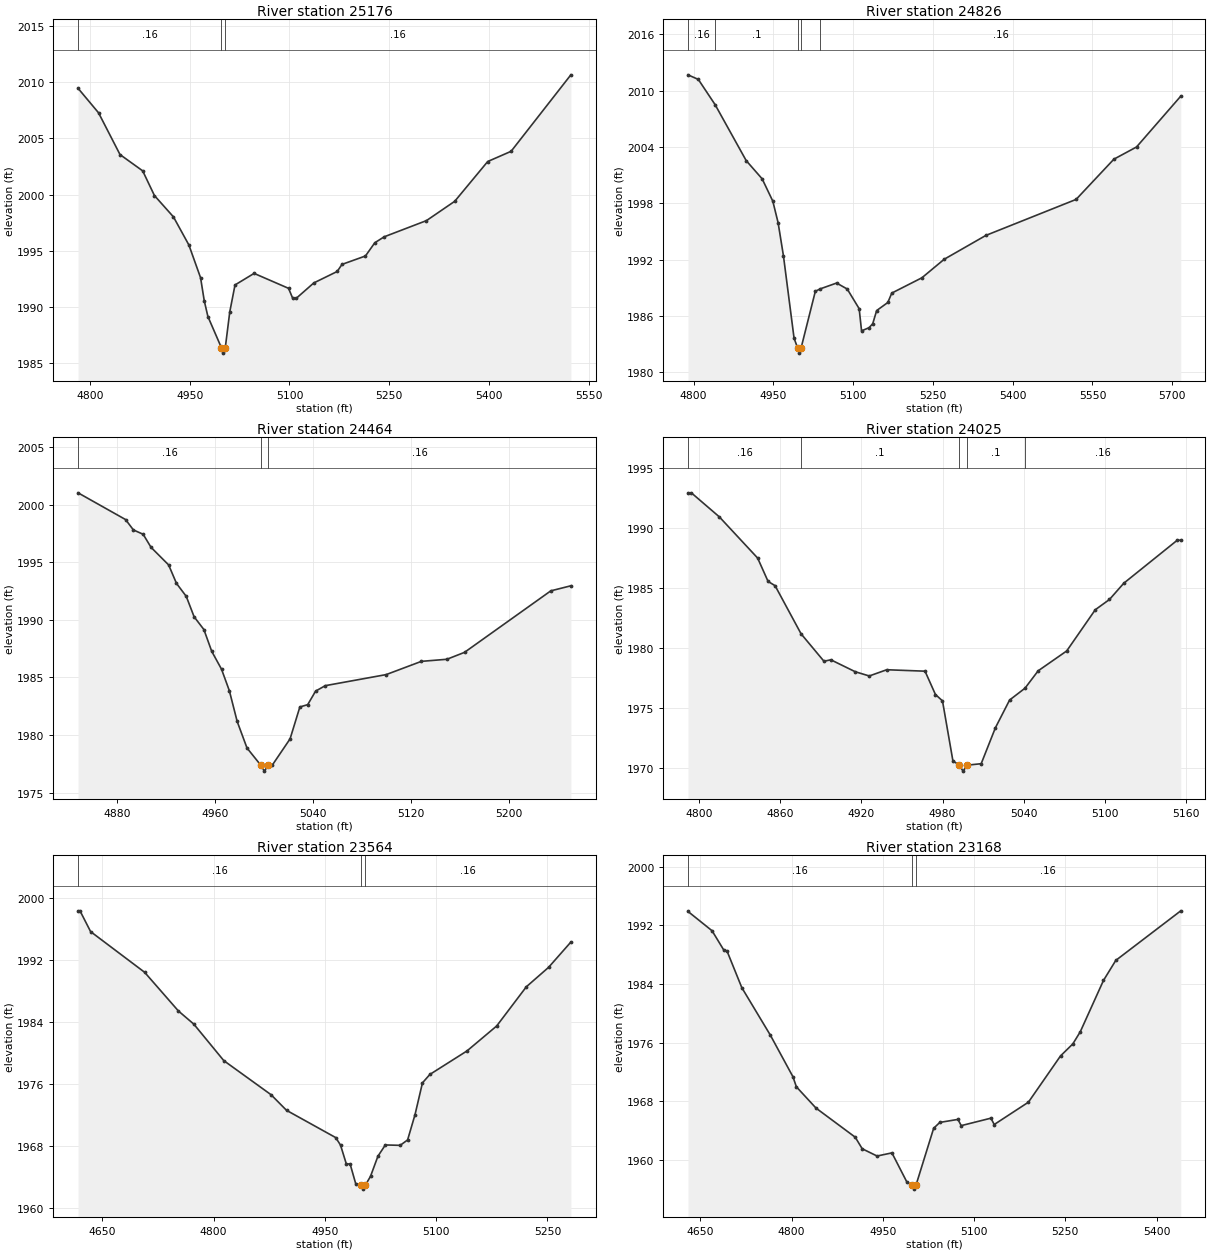
Type RM Length L Ch R = 1 ,25176   ,350,350,350
BEGIN DESCRIPTION:
NORTH CREEK 50.0
END DESCRIPTION:
XS GIS Cut Line= 3
      2676376.55     10071466.65      2676080.66      10071333.5
      2675782.25     10071624.53
#Sta/Elev= 30
    4782 2009.46  4812.8 2007.28  4845.1 2003.56  4879.2 2002.11  4896.9 1999.91
  4925.5 1998.01  4948.7 1995.51  4966.3 1992.59  4971.8 1990.55  4977.3 1989.14
  4997.5 1986.38  5000.2 1985.88  5003.5 1986.38  5010.2 1989.55  5018.1 1991.95
  5046.8 1992.98  5098.6 1991.65  5104.9 1990.76  5110.2 1990.76  5136.6 1992.13
  5171.8 1993.15    5179 1993.78  5214.3 1994.53  5228.4 1995.71  5242.6 1996.24
  5306.1 1997.68  5348.6  1999.4  5398.2 2002.94  5433.4 2003.85  5523.3 2010.66
#Mann= 3 ,-1 , 0
    4782     .16       0  4997.5     .07       0  5003.5     .16       0
Bank Sta=4997.5,5003.5
XS Rating Curve= 0 ,0
Exp/Cntr=0.3,0.1

Type RM Length L Ch R = 1 ,24826   ,362,362,362
BEGIN DESCRIPTION:
NORTH CREEK 49.0
END DESCRIPTION:
XS GIS Cut Line= 3
      2676457.92     10071037.64      2676136.13     10071045.04
      2675688.67     10071451.82
#Sta/Elev= 30
  4789.4 2011.68  4808.9 2011.19  4840.5  2008.5  4898.9 2002.55  4928.9 2000.61
  4948.9 1998.24  4958.9 1995.94  4968.9 1992.43  4988.9 1983.65  4995.9 1982.56
  4998.7 1982.06  5001.9 1982.56  5028.9 1988.64  5038.1  1988.9  5068.9 1989.52
  5088.9 1988.88  5111.3 1986.79  5115.8 1984.43    5130 1984.77  5136.8 1985.19
  5144.2 1986.59  5165.2 1987.45  5172.6 1988.45  5229.3 1990.08  5271.2 1992.05
  5349.6 1994.59  5519.2 1998.42  5590.2  2002.7  5632.8    2004    5716 2009.41
#Mann= 5 ,-1 , 0
  4789.4     .16       0  4840.5      .1       0  4995.9     .07       0
  5001.9      .1       0  5038.1     .16       0
Bank Sta=4995.9,5001.9
XS Rating Curve= 0 ,0
Exp/Cntr=0.3,0.1

Type RM Length L Ch R = 1 ,24464   ,439,439,439
BEGIN DESCRIPTION:
NORTH CREEK 48.0
END DESCRIPTION:
XS GIS Cut Line= 2
      2676080.66      10070712.2      2675829.16     10071026.57
#Sta/Elev= 30
  4848.1 2001.02  4886.9  1998.7  4893.3  1997.8  4901.3 1997.42  4907.7 1996.29
  4922.1 1994.76  4928.5 1993.16  4936.5 1992.03  4942.9 1990.26  4950.9 1989.15
  4957.3 1987.26  4965.3 1985.71  4971.7 1983.84  4978.1 1981.17  4986.1 1978.87
  4997.5 1977.36  5000.3 1976.86  5003.5 1977.36  5006.9  1977.4  5021.3 1979.66
  5029.3 1982.43  5035.7 1982.63  5042.2 1983.81  5050.1 1984.28  5099.8 1985.24
  5128.6 1986.39  5149.4 1986.57  5163.8 1987.17  5234.3 1992.51  5250.7 1992.95
#Mann= 3 ,-1 , 0
  4848.1     .16       0  4997.5     .07       0  5003.5     .16       0
Bank Sta=4997.5,5003.5
XS Rating Curve= 0 ,0
Exp/Cntr=0.3,0.1

Type RM Length L Ch R = 1 ,24025   ,461,461,461
BEGIN DESCRIPTION:
NORTH CREEK 47.0
END DESCRIPTION:
XS GIS Cut Line= 3
      2675918.44     10070503.74      2675718.47     10070553.73
       2675568.5     10070603.72
#Sta/Elev= 30
  4791.8 1992.96  4794.3 1992.96    4815 1990.95  4843.3 1987.51    4851 1985.56
  4856.2  1985.2  4875.4 1981.18  4892.3 1978.89  4897.4 1979.01  4915.5 1978.01
  4925.8 1977.66  4938.7 1978.18    4967 1978.06  4974.7 1976.11  4979.9 1975.58
  4987.6 1970.57  4992.3 1970.21  4995.1 1969.71  4998.3 1970.21  5008.5 1970.33
    5019 1973.33  5029.5 1975.65  5040.9 1976.64  5050.6 1978.09  5071.7 1979.75
  5092.8 1983.19  5103.3 1984.05  5113.9 1985.41  5153.4    1989    5156    1989
#Mann= 5 ,-1 , 0
  4791.8     .16       0  4875.4      .1       0  4992.3     .07       0
  4998.3      .1       0  5040.9     .16       0
Bank Sta=4992.3,4998.3
XS Rating Curve= 0 ,0
Exp/Cntr=0.3,0.1

Type RM Length L Ch R = 1 ,23564   ,396,396,396
BEGIN DESCRIPTION:
NORTH CREEK 46.0
END DESCRIPTION:
XS GIS Cut Line= 3
      2676018.51     10070203.75      2675668.47     10070103.73
      2675368.42     10070103.73
#Sta/Elev= 30
  4617.4 1998.39    4620 1998.39  4634.3 1995.71  4707.1 1990.46  4752.6 1985.47
  4773.4 1983.77  4813.8 1979.06  4877.5 1974.66  4898.3 1972.65  4964.6 1969.13
  4971.1 1968.16  4978.9 1965.73    4984 1965.73  4991.5  1963.2  4998.5 1962.98
  5001.2 1962.48  5004.5 1962.98  5011.5 1964.13  5021.5 1966.73  5031.5 1968.18
  5051.5 1968.13  5061.5 1968.83  5071.5  1972.1  5081.5 1976.19  5091.5 1977.28
  5141.5 1980.31  5181.5 1983.53  5221.5 1988.59  5251.5  1991.1  5281.5 1994.36
#Mann= 3 ,-1 , 0
  4617.4     .16       0  4998.5     .07       0  5004.5     .16       0
Bank Sta=4998.5,5004.5
XS Rating Curve= 0 ,0
Exp/Cntr=0.3,0.1

Type RM Length L Ch R = 1 ,23168   ,476,476,476
BEGIN DESCRIPTION:
NORTH CREEK 45.0
END DESCRIPTION:
XS GIS Cut Line= 3
      2676084.38     10069861.62      2675603.59       10069673.
      2675312.48     10069709.85
#Sta/Elev= 30
  4629.8 1993.92  4669.4 1991.28  4688.5 1988.67  4693.9 1988.53  4718.3 1983.51
  4765.1 1977.04  4802.3 1971.35    4808 1969.97  4840.3 1967.06  4904.7 1963.09
  4916.2 1961.51  4940.6 1960.52    4965 1960.95  4989.5 1956.98  4998.4  1956.5
  5001.1    1956  5004.4  1956.5  5033.6 1964.31  5043.7 1965.11  5073.5 1965.52
  5078.9 1964.67  5127.7 1965.69  5133.1 1964.82  5189.3 1967.87  5242.1 1974.19
  5262.3 1975.83  5274.5 1977.48  5312.7  1984.5  5332.9 1987.23  5439.7    1994
#Mann= 3 ,-1 , 0
  4629.8     .16       0  4998.4     .07       0  5004.4     .16       0
Bank Sta=4998.4,5004.4
XS Rating Curve= 0 ,0
Exp/Cntr=0.3,0.1

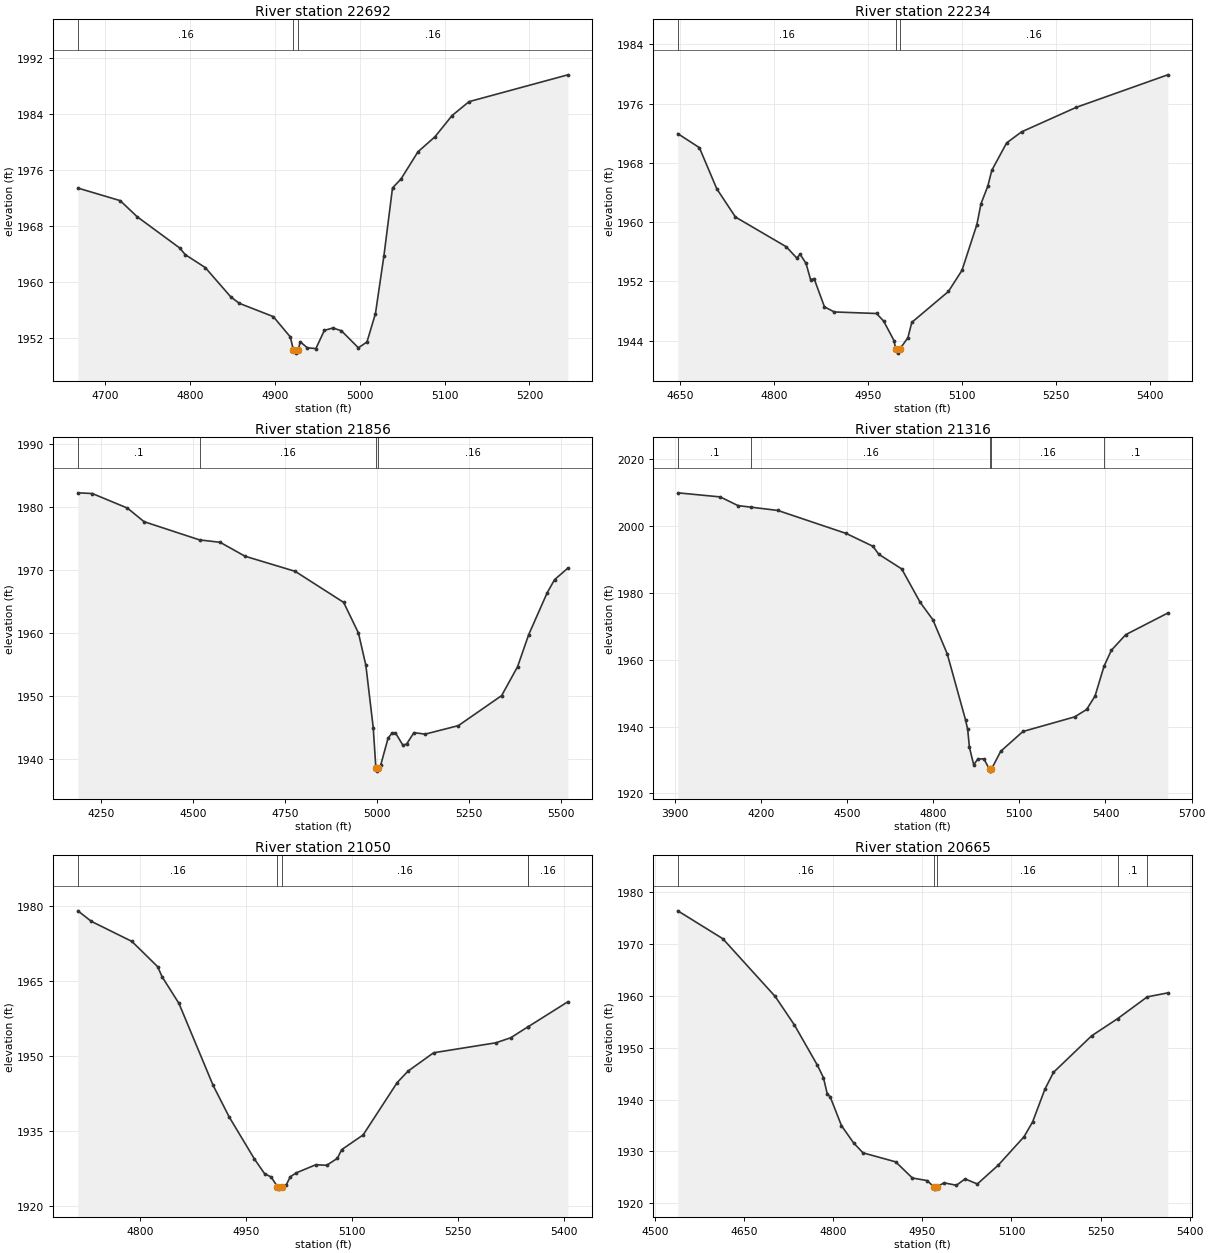
Type RM Length L Ch R = 1 ,22692   ,458,458,458
BEGIN DESCRIPTION:
NORTH CREEK 44.0
END DESCRIPTION:
XS GIS Cut Line= 2
      2675818.13     10069428.92      2675242.33     10069473.21
#Sta/Elev= 30
  4667.8 1973.41  4717.6 1971.61  4737.7  1969.3  4787.8 1964.83  4794.3 1963.88
  4817.9 1962.03    4848 1957.83    4858 1956.91  4898.1 1955.01  4918.2 1952.09
  4921.7 1950.28  4924.4 1949.78  4927.7 1950.28  4929.7 1951.41  4938.3 1950.54
  4948.3 1950.43  4958.3 1953.04  4968.4 1953.38  4978.4 1952.98  4998.4 1950.54
  5008.5 1951.38  5018.5 1955.44  5028.5 1963.73  5038.6 1973.43  5048.6 1974.71
  5068.6  1978.6  5088.7 1980.76  5108.8 1983.79  5128.8 1985.78  5245.3 1989.62
#Mann= 3 ,-1 , 0
  4667.8     .16       0  4921.7     .07       0  4927.7     .16       0
Bank Sta=4921.7,4927.7
XS Rating Curve= 0 ,0
Exp/Cntr=0.3,0.1

Type RM Length L Ch R = 1 ,22234   ,378,378,378
BEGIN DESCRIPTION:
NORTH CREEK 43.0
END DESCRIPTION:
XS GIS Cut Line= 3
      2675840.31     10069166.37      2675459.36     10068970.35
      2675133.89     10069107.19
#Sta/Elev= 30
  4646.7 1971.95  4681.1 1970.06  4708.9  1964.5  4738.7 1960.69  4819.7 1956.68
  4836.3 1955.17  4841.9 1955.65  4851.2 1954.44  4858.5 1952.24  4864.1 1952.38
  4880.6 1948.57  4896.2 1947.88  4963.7 1947.67    4975 1946.65  4991.5 1944.02
  4994.4 1942.82  4997.2 1942.32  5000.4 1942.82  5013.7  1944.4  5019.9 1946.47
  5078.3 1950.64    5100  1953.5  5123.7 1959.67  5130.3 1962.49  5141.2 1964.87
  5147.5 1966.99  5171.2  1970.7    5195 1972.19  5282.5 1975.51  5428.2 1979.89
#Mann= 3 ,-1 , 0
  4646.7     .16       0  4994.4     .07       0  5000.4     .16       0
Bank Sta=4994.4,5000.4
XS Rating Curve= 0 ,0
Exp/Cntr=0.3,0.1

Type RM Length L Ch R = 1 ,21856   ,540,540,540
BEGIN DESCRIPTION:
NORTH CREEK 42.0
END DESCRIPTION:
XS GIS Cut Line= 3
      2676455.47     10068867.19       2675878.2     10068665.29
      2675162.47      10068736.3
#Sta/Elev= 30
    4187 1982.25  4226.2 1982.14  4321.5 1979.83  4366.6 1977.68  4517.4 1974.79
  4573.3 1974.41  4640.7 1972.21  4777.1 1969.81  4908.8 1964.89    4949 1960.03
  4969.1 1954.92  4989.2 1944.99  4996.3 1938.65    4999 1938.15  5002.3 1938.65
  5009.3 1939.08  5029.4 1943.37  5040.3 1944.19  5049.5 1944.22  5069.6 1942.26
  5079.7 1942.44  5099.8 1944.25  5129.9 1944.01  5220.4 1945.36  5337.9 1950.12
  5381.1 1954.69  5411.3 1959.77  5461.5  1966.4  5481.6 1968.49  5517.8 1970.32
#Mann= 4 ,-1 , 0
    4187      .1       0  4517.4     .16       0  4996.3     .07       0
  5002.3     .16       0
Bank Sta=4996.3,5002.3
XS Rating Curve= 0 ,0
Exp/Cntr=0.3,0.1

Type RM Length L Ch R = 1 ,21316   ,266,266,266
BEGIN DESCRIPTION:
NORTH CREEK 41.0
END DESCRIPTION:
XS GIS Cut Line= 3
      2676432.74     10067886.09      2675656.39     10068051.03
      2674919.83     10068588.52
#Sta/Elev= 30
  3911.3 2009.93  4058.8 2008.71  4120.9 2006.11  4167.1 2005.63  4259.5 2004.66
  4497.4 1997.78  4590.4 1993.95  4610.8 1991.56  4690.7 1987.17    4755 1977.17
  4799.1 1971.99  4849.3 1961.73  4912.9 1942.01  4920.3 1939.16  4926.5 1933.78
  4941.2  1928.6  4955.9 1930.32  4976.7 1930.37  4996.5 1927.19  4999.3 1926.69
  5002.5 1927.19  5035.4 1932.64  5112.7 1938.55  5292.6 1942.91  5334.4 1945.13
  5363.7 1949.16  5394.8 1958.04  5420.4 1962.83  5470.3  1967.5  5616.8 1973.97
#Mann= 5 ,-1 , 0
  3911.3      .1       0  4167.1     .16       0  4996.5     .07       0
  5002.5     .16       0  5394.8      .1       0
Bank Sta=4996.5,5002.5
XS Rating Curve= 0 ,0
Exp/Cntr=0.3,0.1

Type RM Length L Ch R = 1 ,21050   ,385,385,385
BEGIN DESCRIPTION:
Mapping XS cf119310
END DESCRIPTION:
XS GIS Cut Line= 2
      2675488.93     10067868.29      2674904.61     10068241.81
#Sta/Elev= 30
  4711.8 1979.01  4730.7 1976.91  4788.2 1972.89  4824.6 1967.84    4831  1965.8
  4854.8 1960.48  4903.2 1944.06    4926 1937.73  4961.6 1929.34    4976  1926.4
  4985.3 1925.73  4994.2  1923.8  4996.9  1923.3  5000.2  1923.8  5006.4 1924.06
  5012.3 1925.76  5020.9 1926.56  5048.7 1928.19  5063.9 1928.07  5079.1 1929.47
  5085.1  1931.2  5115.5 1934.15  5163.7 1944.63    5179 1946.92  5215.3  1950.6
  5303.3 1952.59  5324.4  1953.6  5348.3 1955.75    5349  1955.8  5405.3 1960.81
#Mann= 5 ,-1 , 0
  4711.8     .16       0  4994.2     .07       0  5000.2     .16       0
  5348.3      .1       0    5349     .16       0
Bank Sta=4994.2,5000.2
XS Rating Curve= 0 ,0
Exp/Cntr=0.3,0.1

Type RM Length L Ch R = 1 ,20665   ,314,314,314
BEGIN DESCRIPTION:
NORTH CREEK 40.0
END DESCRIPTION:
XS GIS Cut Line= 3
      2675400.16      10067646.4      2675008.18     10067712.96
      2674742.98     10068048.14
#Sta/Elev= 30
  4538.2 1976.34  4613.9 1970.98  4702.2 1959.85  4734.5 1954.37  4773.2 1946.62
  4783.4 1944.23  4789.8 1941.11  4794.8 1940.52  4813.8 1934.97  4834.1 1931.67
    4850 1929.74  4905.1    1928  4933.1  1924.9  4957.7  1924.4  4969.1 1923.25
  4971.9 1922.75  4975.1 1923.25  4986.6 1923.96  5007.4 1923.49  5021.8 1924.72
  5042.6 1923.74  5077.9 1927.38  5121.2 1932.84  5135.6 1935.69  5156.4 1942.01
  5170.8 1945.24    5235 1952.27  5278.8 1955.58  5328.6 1959.77  5363.2 1960.54
#Mann= 5 ,-1 , 0
  4538.2     .16       0  4969.1     .07       0  4975.1     .16       0
  5278.8      .1       0  5328.6     .16       0
Bank Sta=4969.1,4975.1
XS Rating Curve= 0 ,0
Exp/Cntr=0.3,0.1

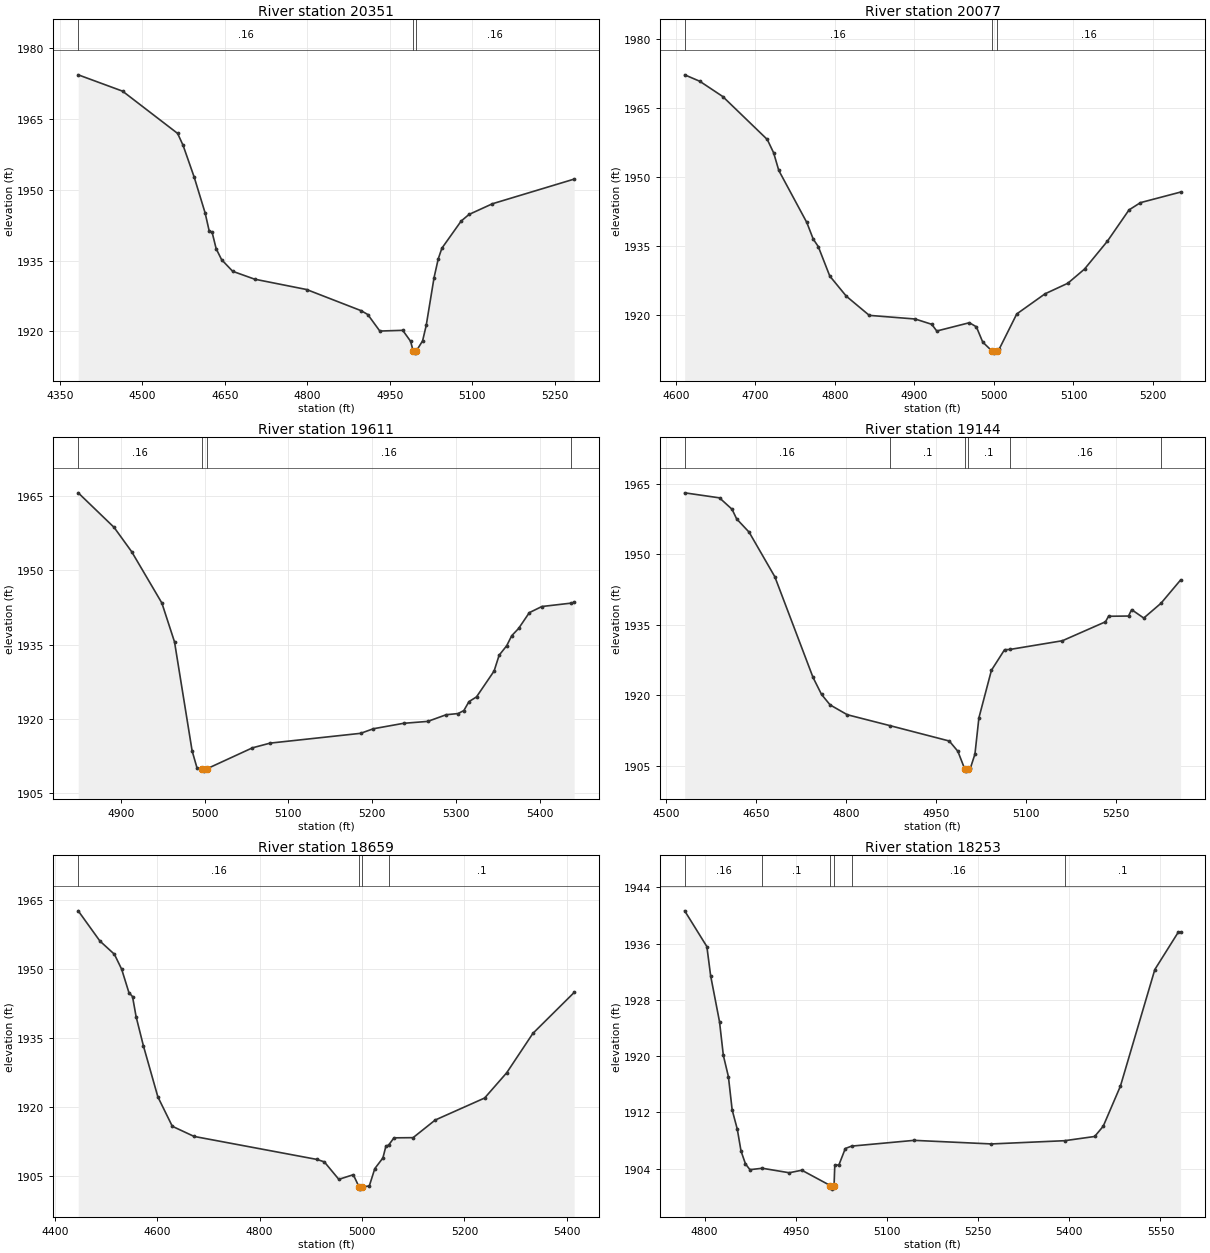
Type RM Length L Ch R = 1 ,20351   ,274,274,274
BEGIN DESCRIPTION:
NORTH CREEK 39.0
END DESCRIPTION:
XS GIS Cut Line= 3
      2675389.07     10067472.57      2674875.04     10067442.99
      2674583.17     10067697.91
#Sta/Elev= 30
  4383.2 1974.37  4463.9 1970.91  4564.1 1961.95  4574.1  1959.4  4594.2  1952.7
  4614.2 1945.07  4621.6 1941.24  4626.7 1941.07  4634.2 1937.52  4644.2 1935.18
  4664.3 1932.73  4704.3 1931.06  4798.8 1928.87  4898.1 1924.38  4910.1 1923.57
    4932 1920.07  4973.7 1920.22    4988  1917.9  4992.6 1915.89  4995.3 1915.39
  4998.6 1915.89  5009.8 1917.98  5016.4 1921.25  5030.7  1931.4  5038.3 1935.36
  5044.9 1937.62    5080 1943.38  5094.3 1944.78    5137 1947.05  5285.6 1952.27
#Mann= 3 ,-1 , 0
  4383.2     .16       0  4992.6     .07       0  4998.6     .16       0
Bank Sta=4992.6,4998.6
XS Rating Curve= 0 ,0
Exp/Cntr=0.3,0.1

Type RM Length L Ch R = 1 ,20077   ,466,466,466
BEGIN DESCRIPTION:
NORTH CREEK 38.0
END DESCRIPTION:
XS GIS Cut Line= 3
      2674926.84     10066965.89      2674704.93     10067246.98
      2674497.84     10067413.39
#Sta/Elev= 30
    4611 1972.31    4630 1970.91  4658.9 1967.59  4714.9 1958.25  4722.9 1955.35
  4729.4 1951.51  4764.6 1940.21  4772.7 1936.59    4779 1934.98  4793.5 1928.56
  4814.3 1924.18  4843.2 1920.01  4900.9 1919.22  4921.7 1918.07  4928.1 1916.61
  4969.1 1918.41  4977.9 1917.52  4985.9  1914.2  4997.3  1912.3    5000  1911.8
  5003.3  1912.3  5006.7 1912.71  5028.7 1920.32  5064.3  1924.7  5092.9 1926.99
  5113.9 1930.07  5142.7 1936.14  5169.9 1942.94  5184.3 1944.52  5234.8 1946.82
#Mann= 3 ,-1 , 0
    4611     .16       0  4997.3     .07       0  5003.3     .16       0
Bank Sta=4997.3,5003.3
XS Rating Curve= 0 ,0
Exp/Cntr=0.3,0.1

Type RM Length L Ch R = 1 ,19611   ,467,467,467
BEGIN DESCRIPTION:
NORTH CREEK 37.0
END DESCRIPTION:
XS GIS Cut Line= 2
      2674619.87     10066707.05       2674290.8      10067198.8
#Sta/Elev= 30
  4849.2 1965.67    4892 1958.69    4913 1953.77    4949 1943.41  4964.1 1935.55
  4985.1 1913.53  4991.1 1909.99  4997.1 1909.94  4999.8 1909.44  5003.1 1909.94
  5057.1 1914.15  5078.2  1915.1  5186.2 1917.08  5201.3    1918  5237.3  1919.1
  5266.3 1919.49  5288.3 1920.84  5302.4 1921.07  5309.3 1921.68  5315.4 1923.48
  5324.4 1924.44  5345.4 1929.67  5351.4 1932.86  5360.4 1934.77  5366.4  1936.8
  5374.6 1938.26  5387.4 1941.46  5402.4  1942.7  5436.6 1943.37  5440.9 1943.55
#Mann= 4 ,-1 , 0
  4849.2     .16       0  4997.1     .07       0  5003.1     .16       0
  5436.6      .1       0
Bank Sta=4997.1,5003.1
XS Rating Curve= 0 ,0
Exp/Cntr=0.3,0.1

Type RM Length L Ch R = 1 ,19144   ,485,485,485
BEGIN DESCRIPTION:
NORTH CREEK 36.0
END DESCRIPTION:
XS GIS Cut Line= 3
      2674468.22     10066481.48      2674046.65     10066840.18
        2673969.     10067102.72
#Sta/Elev= 30
  4530.7  1963.1  4588.8 1962.03  4609.7  1959.6  4617.4 1957.55  4638.2 1954.72
  4681.1 1945.23  4744.8  1923.8    4759 1920.18  4773.3 1917.95  4801.9 1915.86
    4873 1913.54  4972.1 1910.26  4986.4 1908.08  4997.7 1904.35  5000.4 1903.85
  5003.7 1904.35  5007.2 1904.43  5014.9 1907.48  5021.5 1915.18  5042.4 1925.32
  5064.3  1929.7    5073 1929.75  5160.8 1931.61  5232.6 1935.64  5237.8 1936.82
  5271.1 1936.87  5276.3 1938.23  5296.5 1936.44  5325.2 1939.58    5358 1944.55
#Mann= 6 ,-1 , 0
  4530.7     .16       0    4873      .1       0  4997.7     .07       0
  5003.7      .1       0    5073     .16       0  5325.2      .1       0
Bank Sta=4997.7,5003.7
XS Rating Curve= 0 ,0
Exp/Cntr=0.3,0.1

Type RM Length L Ch R = 1 ,18659   ,406,406,406
BEGIN DESCRIPTION:
NORTH CREEK 35.0
END DESCRIPTION:
XS GIS Cut Line= 3
      2674168.47     10066053.73      2673768.47     10066453.73
      2673568.47     10066803.73
#Sta/Elev= 30
  4445.6 1962.65    4488 1956.07  4516.3 1953.19  4530.5 1949.93  4544.6 1944.86
  4551.7 1943.97  4558.7 1939.59  4572.9 1933.27  4601.2 1922.13  4629.4 1915.73
  4671.9 1913.52  4912.3  1908.5  4926.4 1907.97  4954.7 1904.17    4983 1905.18
  4994.1 1902.54  4996.9 1902.04  5000.1 1902.54  5014.2 1902.72    5025 1906.51
  5040.8 1908.83  5046.6 1911.37  5052.2 1911.66  5062.4 1913.21  5099.8 1913.25
    5143 1917.09  5239.5 1921.88  5282.7 1927.39  5333.8 1935.96  5414.4 1944.87
#Mann= 4 ,-1 , 0
  4445.6     .16       0  4994.1     .07       0  5000.1     .16       0
  5052.2      .1       0
Bank Sta=4994.1,5000.1
XS Rating Curve= 0 ,0
Exp/Cntr=0.3,0.1

Type RM Length L Ch R = 1 ,18253   ,417,417,417
BEGIN DESCRIPTION:
NORTH CREEK 34.0
END DESCRIPTION:
XS GIS Cut Line= 3
      2673768.48     10065953.72      2673568.47     10066103.73
      2673168.47     10066503.73
#Sta/Elev= 30
  4767.4 1940.68  4803.9 1935.59  4810.1 1931.44  4824.7  1924.9    4831 1920.11
  4839.3  1917.1  4845.5 1912.35  4853.9 1909.62  4860.1 1906.49  4867.4 1904.67
  4874.7 1903.85  4895.1 1904.05  4939.3 1903.41  4960.1 1903.77  5007.1 1901.58
  5009.9 1901.08  5013.1 1901.58  5014.3 1904.51    5021 1904.51  5031.6 1906.86
  5041.9  1907.2  5144.7 1908.02    5272 1907.51  5392.2 1907.97  5441.7 1908.57
  5455.8 1910.03  5484.1 1915.74  5540.7 1932.33  5579.6 1937.69  5583.1 1937.69
#Mann= 6 ,-1 , 0
  4767.4     .16       0  4895.1      .1       0  5007.1     .07       0
  5013.1      .1       0  5041.9     .16       0  5392.2      .1       0
Bank Sta=5007.1,5013.1
XS Rating Curve= 0 ,0
Exp/Cntr=0.3,0.1

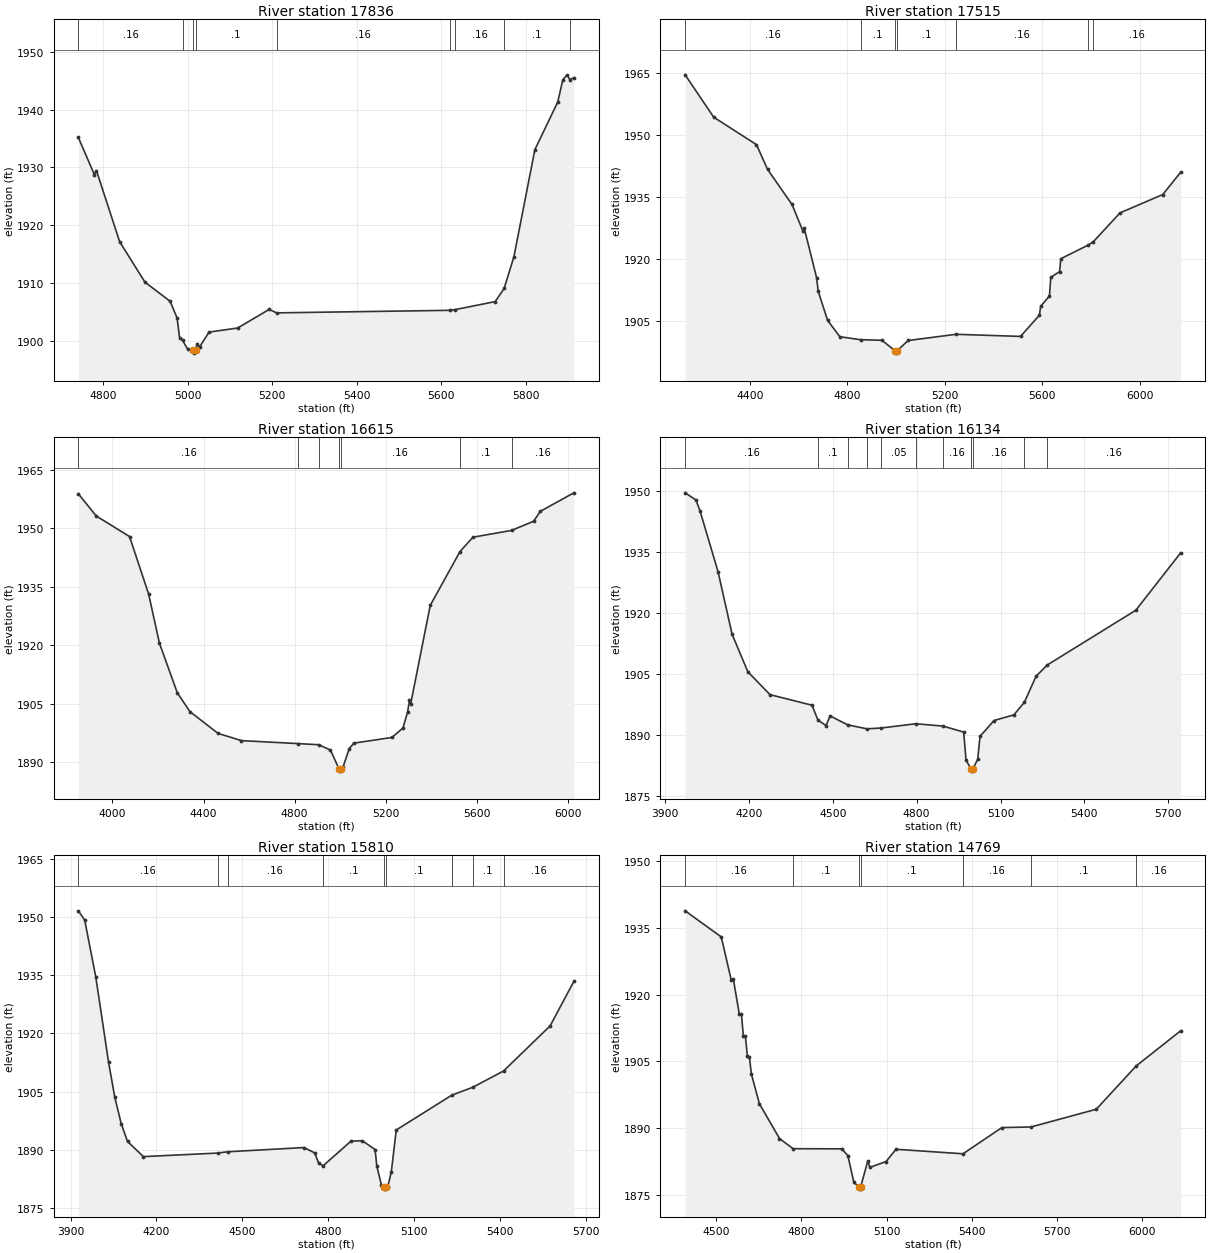
Type RM Length L Ch R = 1 ,17836   ,321,321,321
BEGIN DESCRIPTION:
NORTH CREEK 33.0
END DESCRIPTION:
XS GIS Cut Line= 3
       2673728.6     10065641.97      2673491.92     10065682.65
      2673059.21     10066507.37
#Sta/Elev= 30
  4741.5 1935.18  4779.3 1928.78  4784.4 1929.45  4839.3 1917.16  4899.2 1910.18
  4958.5  1906.9    4975 1904.02  4980.9  1900.6  4988.1 1900.14  4999.8 1898.63
  5013.2 1898.44    5016 1897.94  5019.2 1898.44  5021.9 1899.46  5028.1 1898.99
  5050.6 1901.57  5118.4 1902.28  5192.7 1905.49  5210.3 1904.89  5619.8 1905.33
  5632.3 1905.45  5727.1 1906.84  5748.2  1909.1  5771.2 1914.53    5821 1933.09
    5875 1941.29  5887.1 1945.17  5897.6 1945.99  5903.4 1945.16    5913 1945.49
#Mann= 9 ,-1 , 0
  4741.5     .16       0  4988.1      .1       0  5013.2     .07       0
  5019.2      .1       0  5210.3     .16       0  5619.8      .1       0
  5632.3     .16       0  5748.2      .1       0  5903.4     .16       0
Bank Sta=5013.2,5019.2
XS Rating Curve= 0 ,0
Exp/Cntr=0.3,0.1

Type RM Length L Ch R = 1 ,17515   ,900,900,900
BEGIN DESCRIPTION:
NORTH CREEK 32.0
END DESCRIPTION:
XS GIS Cut Line= 4
      2674103.23     10065260.32      2673329.66     10065419.58
      2673106.69      10065592.5      2672874.62     10066525.31
#Sta/Elev= 30
  4134.6 1964.65  4251.8 1954.39  4427.4 1947.73  4472.6 1941.76  4573.2 1933.24
  4618.4 1926.72  4623.5 1927.43  4673.9 1915.54  4680.6 1912.21  4719.1 1905.17
  4769.4  1901.2  4854.9 1900.48  4942.1 1900.35  4997.1 1897.73  4999.8 1897.23
  5003.1 1897.73  5049.8 1900.29  5246.1 1901.79  5510.8 1901.28  5588.3 1906.43
  5593.5 1908.57  5629.6 1911.08  5634.8 1915.59    5671 1916.97  5676.1  1920.1
  5788.6 1923.41  5809.3  1924.2  5918.9  1931.2  6094.5 1935.65  6167.8 1941.04
#Mann= 7 ,-1 , 0
  4134.6     .16       0  4854.9      .1       0  4997.1     .07       0
  5003.1      .1       0  5246.1     .16       0  5788.6      .1       0
  5809.3     .16       0
Bank Sta=4997.1,5003.1
XS Rating Curve= 0 ,0
Exp/Cntr=0.3,0.1

Type RM Length L Ch R = 1 ,16615   ,481,481,481
BEGIN DESCRIPTION:
NORTH CREEK 31.0
END DESCRIPTION:
XS GIS Cut Line= 3
      2674064.77     10065100.72      2672702.55     10064772.59
      2671932.75     10064857.02
#Sta/Elev= 30
    3850 1958.85  3928.5 1953.15  4074.8 1947.88  4158.7 1933.14  4206.2 1920.53
  4284.4 1907.86  4339.9    1903  4463.4 1897.42  4566.2 1895.56  4816.6 1894.79
  4905.2 1894.51  4957.1 1893.14  4995.2 1888.24    4998 1887.74  5001.2 1888.24
  5012.6 1888.85  5039.4 1893.49  5059.9 1894.92  5227.3 1896.37  5275.4  1898.8
  5295.5 1902.84    5304 1905.86  5309.1 1904.92  5395.2 1930.23  5525.8 1944.02
  5582.5  1947.7    5753 1949.46  5848.8 1951.79    5879 1954.35  6025.6 1959.08
#Mann= 7 ,-1 , 0
    3850     .16       0  4816.6     .05       0  4905.2     .16       0
  4995.2     .07       0  5001.2     .16       0  5525.8      .1       0
    5753     .16       0
Bank Sta=4995.2,5001.2
XS Rating Curve= 0 ,0
Exp/Cntr=0.3,0.1

Type RM Length L Ch R = 1 ,16134   ,324,324,324
BEGIN DESCRIPTION:
NORTH CREEK 30.0
END DESCRIPTION:
XS GIS Cut Line= 2
      2673898.31     10064988.81      2672474.66     10063933.22
#Sta/Elev= 30
    3972 1949.63  4010.5 1947.87  4025.2 1945.19  4089.9 1930.15  4139.9  1914.8
  4196.3 1905.54  4275.6 1899.91  4425.8 1897.31  4446.8 1893.67  4475.9 1892.29
  4490.5 1894.67  4553.4 1892.47  4622.3 1891.49  4672.4 1891.69  4797.7 1892.74
  4894.8 1892.16  4968.3 1890.69  4976.7 1883.82  4994.6 1881.57  4997.3 1881.07
  5000.6 1881.57  5018.4 1883.97  5026.8 1889.63  5076.9 1893.54  5147.8 1894.93
  5185.1 1897.99  5227.1 1904.43  5267.3 1907.22  5583.9  1920.7  5744.3 1934.84
#Mann= 11 ,-1 , 0
    3972     .16       0  4446.8      .1       0  4553.4     .16       0
  4622.3      .1       0  4672.4     .05       0  4797.7      .1       0
  4894.8     .16       0  4994.6     .07       0  5000.6     .16       0
  5185.1      .1       0  5267.3     .16       0
Bank Sta=4994.6,5000.6
XS Rating Curve= 0 ,0
Exp/Cntr=0.3,0.1

Type RM Length L Ch R = 1 ,15810   ,1041,1041,1041
BEGIN DESCRIPTION:
NORTH CREEK 29.0
END DESCRIPTION:
XS GIS Cut Line= 2
      2674113.54     10064530.44      2672552.28     10063781.03
#Sta/Elev= 30
  3927.3 1951.66  3949.6 1949.27  3988.4 1934.57  4032.8 1912.68  4054.9 1903.49
  4077.1 1896.75  4099.3 1892.12  4154.8 1888.21  4414.8 1889.13  4448.8 1889.46
  4715.9 1890.55  4753.8 1889.16  4766.8  1886.6  4782.6 1885.83    4880 1892.19
  4919.8 1892.32  4964.5 1890.04  4970.6 1885.74  4986.7 1880.89  4995.8 1880.32
  4998.5 1879.82  5001.8 1880.32  5008.9 1880.46  5021.4 1884.35  5038.5 1895.09
  5232.3 1904.06  5306.3 1906.12  5413.5 1910.32  5576.1 1921.94  5659.1 1933.42
#Mann= 9 ,-1 , 0
  3927.3     .16       0  4414.8     .05       0  4448.8     .16       0
  4782.6      .1       0  4995.8     .07       0  5001.8      .1       0
  5232.3     .16       0  5306.3      .1       0  5413.5     .16       0
Bank Sta=4995.8,5001.8
XS Rating Curve= 0 ,0
Exp/Cntr=0.3,0.1

Type RM Length L Ch R = 1 ,14769   ,765,765,765
BEGIN DESCRIPTION:
NORTH CREEK 28.0
END DESCRIPTION:
XS GIS Cut Line= 3
      2674231.59     10064030.42      2673641.34     10063405.45
      2672794.09      10063662.4
#Sta/Elev= 30
  4390.7 1938.82  4517.9 1932.96  4553.1 1923.29  4560.4 1923.53  4581.4 1915.64
  4588.7 1915.73  4595.6 1910.81  4602.9 1910.66  4609.8 1906.27    4617 1906.07
  4623.9 1902.19  4652.2 1895.49    4723 1887.68  4770.9 1885.39  4942.3 1885.36
  4963.8 1883.84  4984.8 1877.85  5002.8 1876.81  5005.6 1876.31  5008.8 1876.81
  5034.1 1882.67  5041.4  1881.2  5098.1  1882.5  5133.3 1885.26  5369.3 1884.25
  5506.1 1890.13  5608.5 1890.27  5838.5 1894.25  5979.2 1903.98  6135.7 1911.87
#Mann= 7 ,-1 , 0
  4390.7     .16       0  4770.9      .1       0  5002.8     .07       0
  5008.8      .1       0  5369.3     .16       0  5608.5      .1       0
  5979.2     .16       0
Bank Sta=5002.8,5008.8
XS Rating Curve= 0 ,0
Exp/Cntr=0.3,0.1

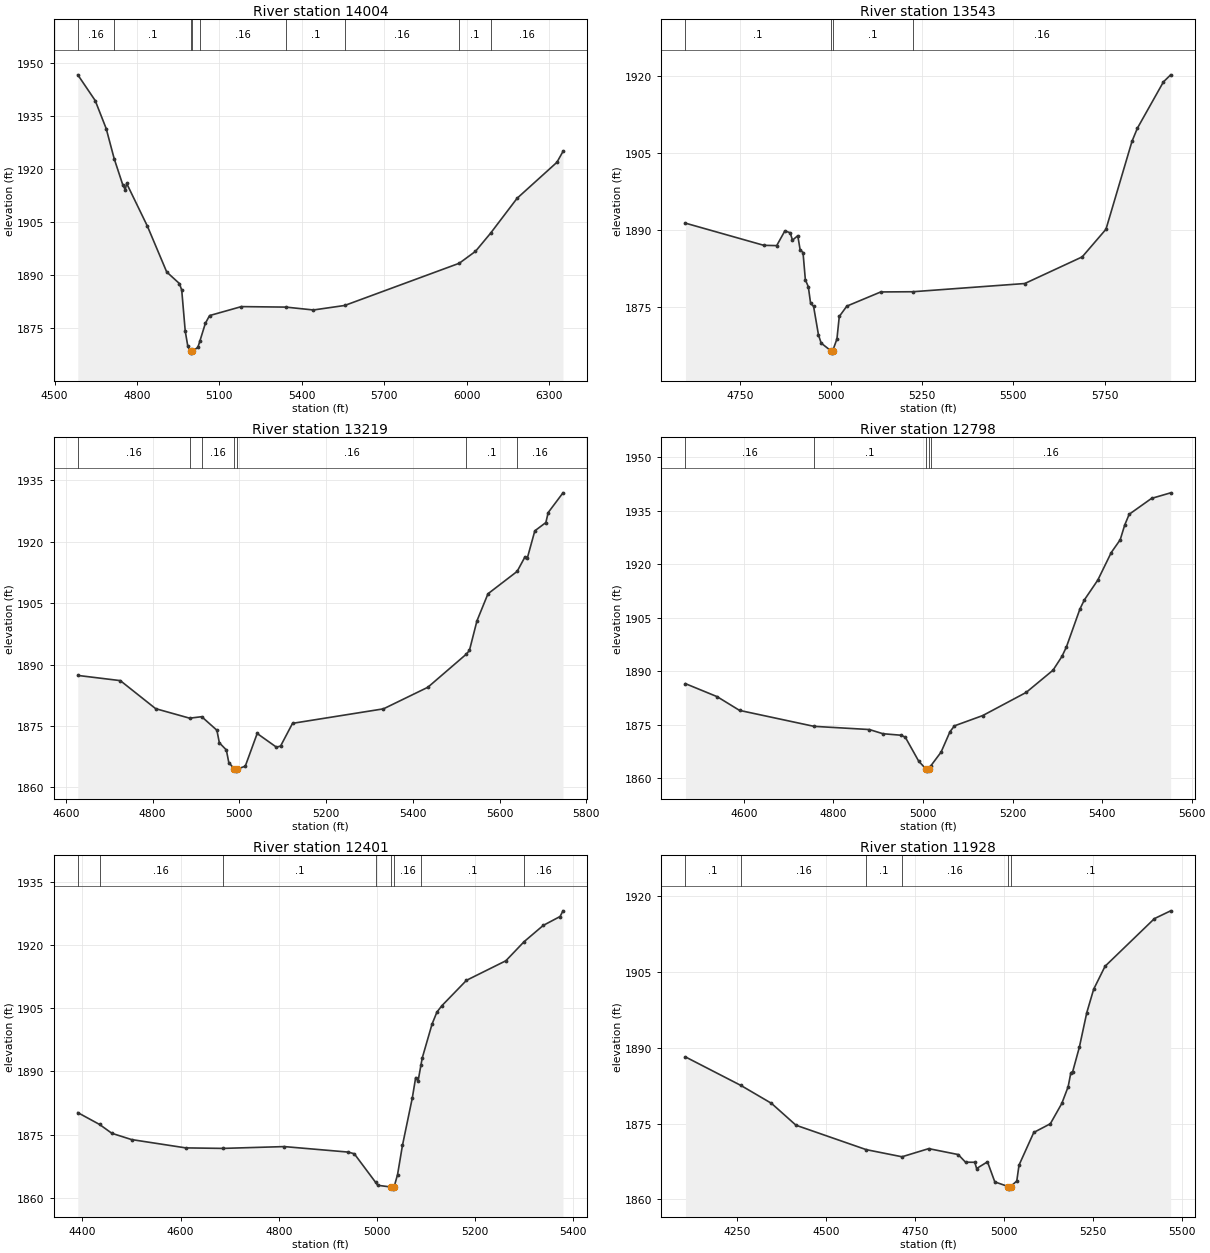
Type RM Length L Ch R = 1 ,14004   ,461,461,461
BEGIN DESCRIPTION:
NORTH CREEK 27.0
END DESCRIPTION:
XS GIS Cut Line= 4
      2674231.65     10062919.34      2673884.39      10062898.5
      2672953.84     10063474.89      2672642.36     10063564.88
#Sta/Elev= 30
  4584.4 1946.53  4647.7 1939.28  4687.8 1931.36    4717 1922.85  4747.9 1915.57
  4757.2 1914.11  4762.2 1915.91    4838 1903.82  4908.2 1890.92  4954.3 1887.67
  4962.8 1885.84  4975.6 1874.24  4985.1 1869.94  4995.1 1868.54  4997.8 1868.04
  5001.1 1868.54  5021.6 1869.67  5028.9 1871.43  5048.8 1876.43  5064.2 1878.63
    5180 1881.16  5342.2 1881.02  5442.3 1880.21  5556.2 1881.48  5973.5 1893.39
  6032.5 1896.75  6087.4 1901.86  6184.1 1911.72    6329 1921.86  6351.1 1924.92
#Mann= 9 ,-1 , 0
  4584.4     .16       0    4717      .1       0  4995.1     .07       0
  5001.1      .1       0  5028.9     .16       0  5342.2      .1       0
  5556.2     .16       0  5973.5      .1       0  6087.4     .16       0
Bank Sta=4995.1,5001.1
XS Rating Curve= 0 ,0
Exp/Cntr=0.3,0.1

Type RM Length L Ch R = 1 ,13543   ,324,324,324
BEGIN DESCRIPTION:
NORTH CREEK 26.0
END DESCRIPTION:
XS GIS Cut Line= 3
      2673724.65     10062537.41      2673294.12     10062877.67
      2672655.49     10063328.88
#Sta/Elev= 30
  4600.6  1891.4  4815.6 1887.08  4850.8 1887.03  4873.3 1889.91  4887.8 1889.52
  4894.1 1888.09  4908.6 1888.96    4915 1886.24    4923 1885.66  4929.4 1880.36
  4937.5 1879.02  4943.8 1875.77  4951.9 1875.21  4965.4 1869.62  4972.7 1868.04
  4998.6 1866.58  5001.3 1866.08  5004.6 1866.58    5016 1868.84  5022.4 1873.22
  5043.2 1875.24  5136.2    1878    5224 1878.04  5531.1 1879.64  5688.7 1884.83
  5753.9 1890.22  5825.3 1907.36  5840.1 1909.91  5911.5 1918.93  5931.3  1920.3
#Mann= 4 ,-1 , 0
  4600.6      .1       0  4998.6     .07       0  5004.6      .1       0
    5224     .16       0
Bank Sta=4998.6,5004.6
XS Rating Curve= 0 ,0
Exp/Cntr=0.3,0.1

Type RM Length L Ch R = 1 ,13219   ,421,421,421
BEGIN DESCRIPTION:
NORTH CREEK 25.0
END DESCRIPTION:
XS GIS Cut Line= 3
      2673439.91     10062481.86      2672946.89     10062752.67
      2672405.23     10062877.67
#Sta/Elev= 30
  4627.6 1887.35  4725.6 1886.08  4807.1 1879.23  4885.4 1876.91  4913.2 1877.27
  4948.2 1873.97  4953.9  1870.9    4970 1869.15  4975.7 1866.06  4988.8 1864.48
  4991.6 1863.98  4994.8 1864.48  5013.6 1865.18  5041.1 1873.17  5085.6 1869.82
  5095.1 1870.12  5122.6 1875.65  5332.2 1879.19  5434.5 1884.46  5522.7  1892.5
  5530.3 1893.44  5547.7 1900.68  5573.1 1907.29  5640.3 1912.75  5658.6 1916.34
  5663.7 1915.97  5681.1 1922.66  5706.5 1924.68  5711.9 1927.12    5746 1931.94
#Mann= 7 ,-1 , 0
  4627.6     .16       0  4885.4      .1       0  4913.2     .16       0
  4988.8     .07       0  4994.8     .16       0  5522.7      .1       0
  5640.3     .16       0
Bank Sta=4988.8,4994.8
XS Rating Curve= 0 ,0
Exp/Cntr=0.3,0.1

Type RM Length L Ch R = 1 ,12798   ,397,397,397
BEGIN DESCRIPTION:
NORTH CREEK 24.0
END DESCRIPTION:
XS GIS Cut Line= 2
      2673419.16       10062336.      2672335.76     10062356.84
#Sta/Elev= 30
  4469.5 1886.49  4540.2 1882.85  4590.2    1879  4756.3 1874.53  4880.3 1873.63
  4910.3 1872.46  4950.3 1872.04  4960.3 1871.51  4990.3 1864.78  5007.3 1862.47
    5010 1861.97  5013.3 1862.47  5017.7  1863.5  5040.3 1867.29  5060.3 1873.04
  5070.3 1874.67  5133.4 1877.55  5230.3 1884.03  5290.3 1890.26  5310.3 1894.13
  5320.3  1896.8  5350.4 1907.41  5360.4 1909.99  5390.4 1915.54  5420.4 1923.26
  5440.4 1926.84  5450.4 1930.94  5460.4 1933.98  5510.4 1938.44  5553.1    1940
#Mann= 5 ,-1 , 0
  4469.5     .16       0  4756.3      .1       0  5007.3     .07       0
  5013.3      .1       0  5017.7     .16       0
Bank Sta=5007.3,5013.3
XS Rating Curve= 0 ,0
Exp/Cntr=0.3,0.1

Type RM Length L Ch R = 1 ,12401   ,473,473,473
BEGIN DESCRIPTION:
NORTH CREEK 23.0
END DESCRIPTION:
XS GIS Cut Line= 2
      2673467.68     10061905.45      2672482.53     10061981.77
#Sta/Elev= 30
  4390.7 1880.21  4435.1 1877.39  4460.1 1875.29  4500.2  1873.8  4610.6 1871.82
  4686.1  1871.7  4811.2 1872.13  4941.6 1870.82  4953.8 1870.42  4997.3 1863.61
  5001.7 1862.92  5028.8 1862.51  5031.6 1862.01  5034.8 1862.51  5041.9 1865.47
  5051.9 1872.43    5072 1883.74  5078.8 1888.56  5083.8 1887.77  5089.6 1891.57
    5092 1893.14  5112.1 1901.26  5122.1 1904.14  5132.1 1905.64  5182.3 1911.69
  5262.5 1916.34  5299.5 1920.87  5338.6 1924.75  5372.9 1926.87  5378.8 1928.22
#Mann= 8 ,-1 , 0
  4390.7      .1       0  4435.1     .16       0  4686.1      .1       0
  4997.3     .16       0  5028.8     .07       0  5034.8     .16       0
  5089.6      .1       0  5299.5     .16       0
Bank Sta=5028.8,5034.8
XS Rating Curve= 0 ,0
Exp/Cntr=0.3,0.1

Type RM Length L Ch R = 1 ,11928   ,259,259,259
BEGIN DESCRIPTION:
NORTH CREEK 22.0
END DESCRIPTION:
XS GIS Cut Line= 3
      2673763.31     10061703.69      2672735.53     10061450.22
       2672443.9     10061543.96
#Sta/Elev= 30
  4104.6 1888.19  4260.5 1882.55  4346.5 1879.01  4415.5 1874.68  4613.1 1869.85
  4713.7 1868.44  4788.9 1870.05  4871.8 1868.88  4892.4 1867.37  4918.5 1867.35
  4923.6 1866.12  4954.2 1867.44  4974.8 1863.47    5013 1862.54  5015.7 1862.04
    5019 1862.54  5036.6 1863.65  5042.9 1866.79  5084.4 1873.25    5131 1874.97
  5163.2 1878.98  5181.1 1882.29  5188.7 1885.06  5193.9 1885.29  5212.6  1890.1
  5233.6 1896.97  5252.9 1901.58  5284.9 1906.12  5423.8 1915.55  5469.5 1917.09
#Mann= 6 ,-1 , 0
  4104.6      .1       0  4260.5     .16       0  4613.1      .1       0
  4713.7     .16       0    5013     .07       0    5019      .1       0
Bank Sta=5013,5019
XS Rating Curve= 0 ,0
Exp/Cntr=0.3,0.1