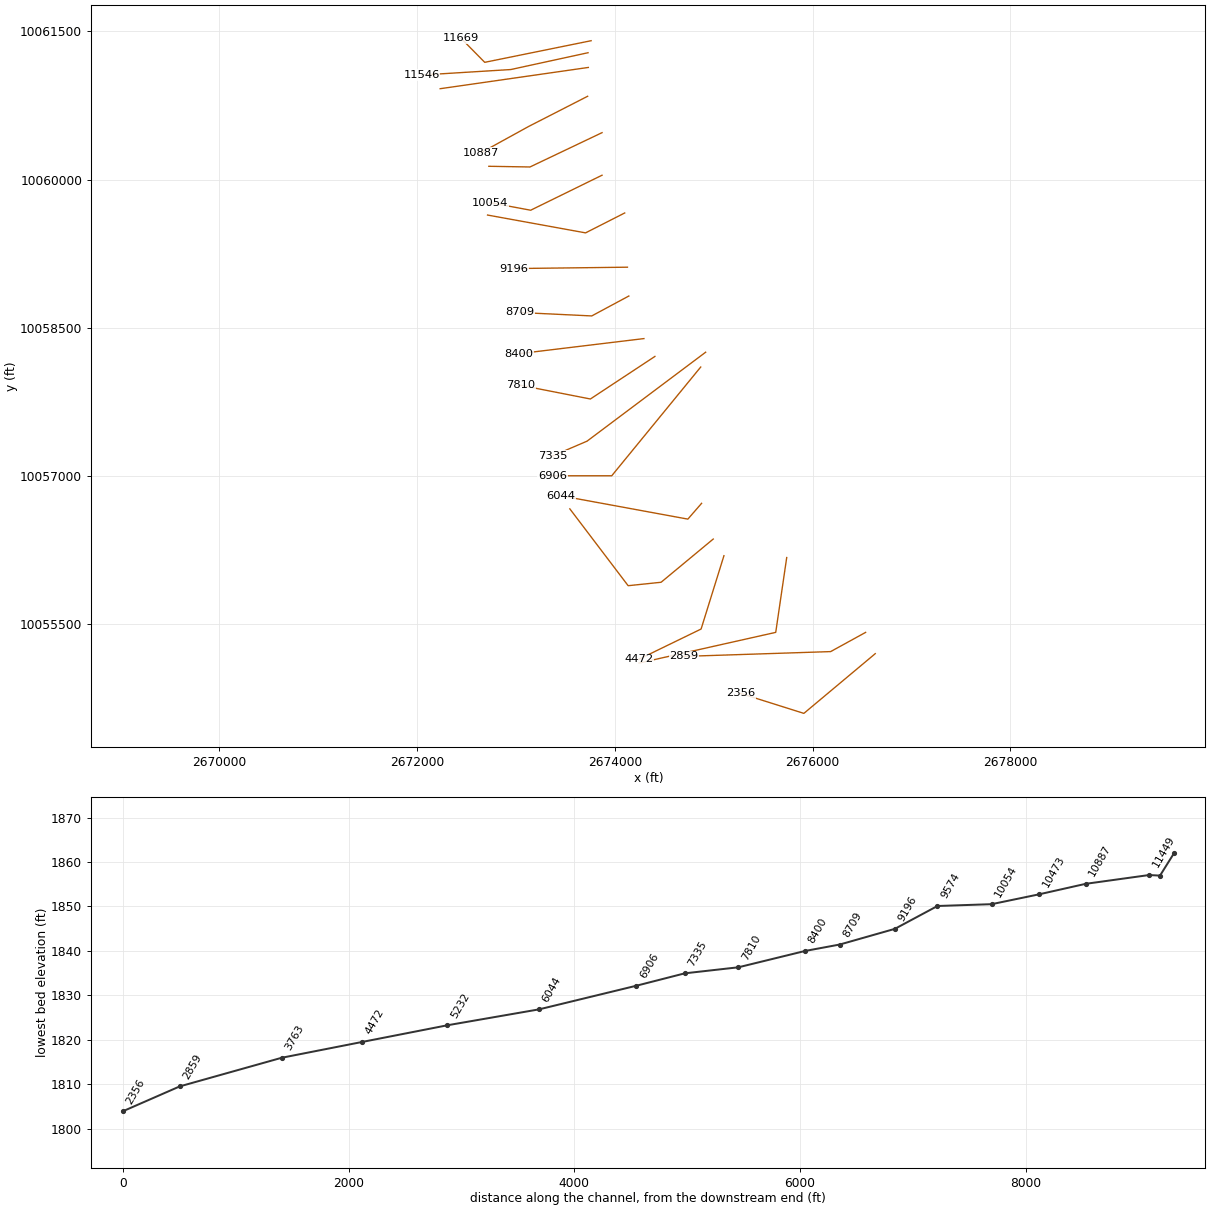
HEC-RAS study NORTH CREEK.prj: NORTH CREEK Base Level Engineering

--- NORTH CREEK.g01 (geometry) --- (continued)

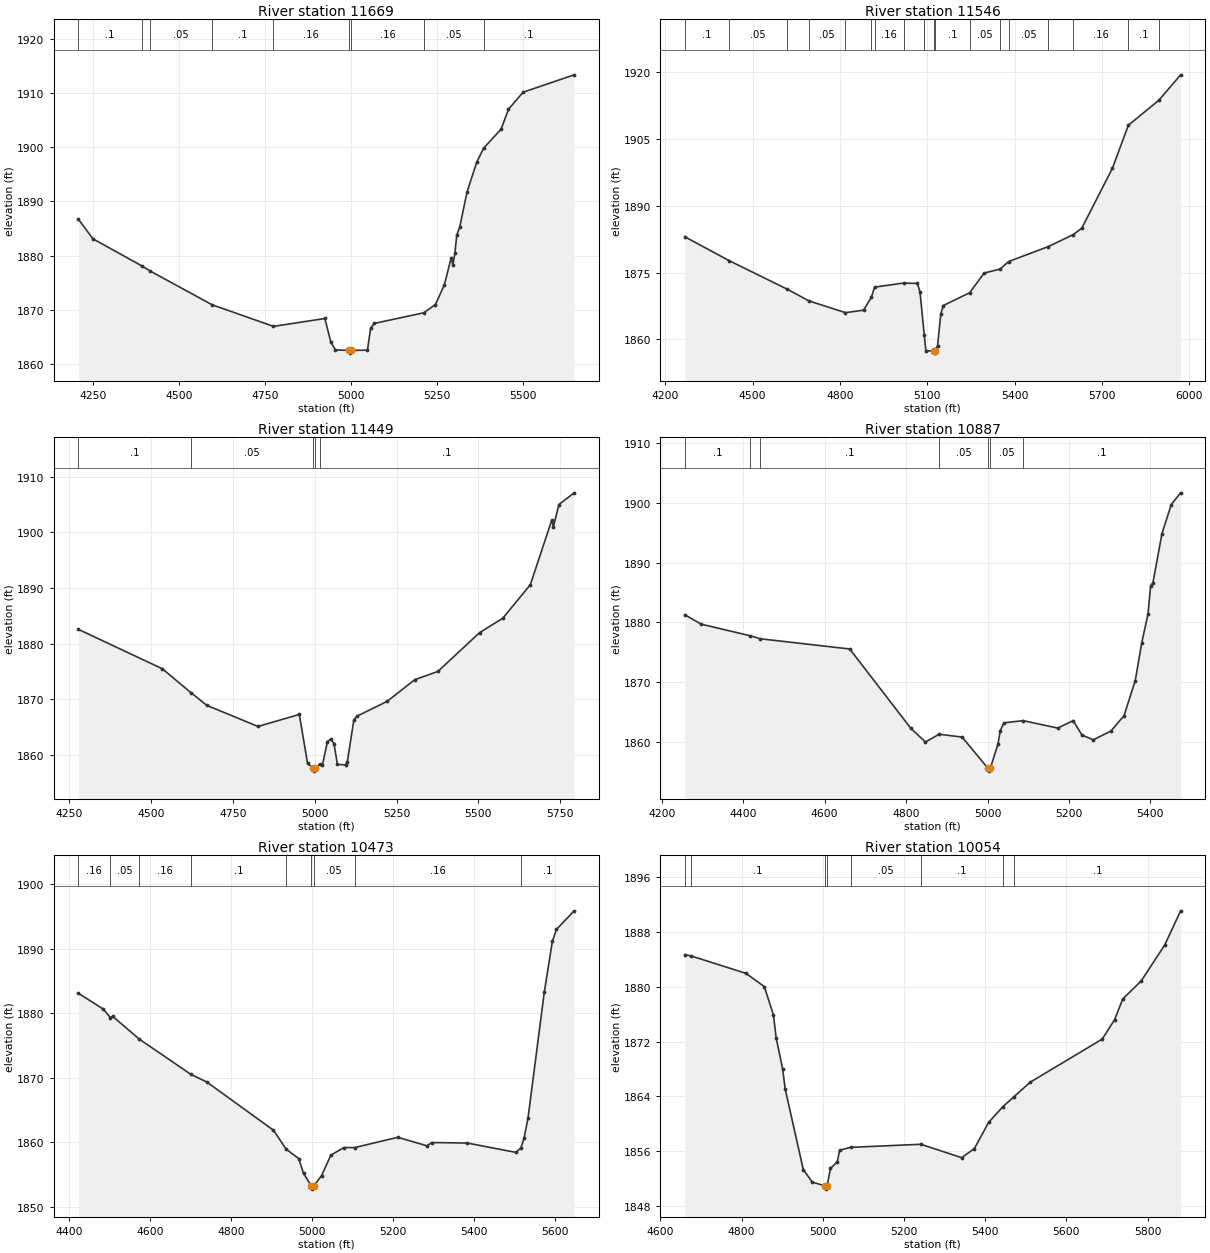
Type RM Length L Ch R = 1 ,11669   ,123,123,123
BEGIN DESCRIPTION:
Mapping XS 04e15808
END DESCRIPTION:
XS GIS Cut Line= 3
      2673759.87     10061405.09      2672683.45     10061186.33
      2672444.15     10061429.09
#Sta/Elev= 30
    4208 1886.74  4250.3  1883.1  4391.8  1878.1  4416.2 1877.15  4596.2 1870.89
  4774.5 1866.89  4923.7 1868.35    4941 1863.97  4954.4 1862.53  4993.7 1862.44
  4996.4 1861.94  4999.7 1862.44  5047.3 1862.49  5056.4 1866.51  5066.6 1867.43
  5210.9 1869.41  5244.7 1870.93  5270.7 1874.61  5290.2 1879.53  5295.3 1878.26
  5301.3 1880.51  5306.4 1883.77  5315.2 1885.28  5336.4 1891.78  5364.7  1897.3
  5384.5 1899.87  5435.4  1903.4  5456.7 1907.07  5499.1 1910.22  5647.3 1913.44
#Mann= 9 ,-1 , 0
    4208      .1       0  4391.8     .16       0  4416.2     .05       0
  4596.2      .1       0  4774.5     .16       0  4993.7     .07       0
  4999.7     .16       0  5210.9     .05       0  5384.5      .1       0
Bank Sta=4993.7,4999.7
XS Rating Curve= 0 ,0
Exp/Cntr=0.3,0.1

Type RM Length L Ch R = 1 ,11546   ,97,97,97
BEGIN DESCRIPTION:
Mapping XS a2a888a5
END DESCRIPTION:
XS GIS Cut Line= 3
      2673728.63     10061283.57      2672947.33     10061113.42
      2672044.55     10061057.86
#Sta/Elev= 30
  4266.7 1883.06  4418.7 1877.71  4618.7 1871.29  4693.1 1868.67  4818.8 1866.03
  4880.9 1866.58  4908.1 1869.46  4918.8 1871.75  5018.9 1872.67  5066.3 1872.58
  5075.2 1870.59  5089.7 1861.06  5095.2 1857.46  5122.3 1857.44    5125 1856.94
  5128.3 1857.44  5135.3 1858.55  5146.5 1865.71  5155.3 1867.63  5245.4 1870.48
  5295.6 1874.91  5350.6 1875.82  5379.7  1877.5  5516.6 1880.87  5601.1 1883.52
  5631.1 1884.98  5736.4 1898.44  5791.2  1908.1  5895.9  1913.7  5970.8 1919.41
#Mann= 18 ,-1 , 0
  4266.7      .1       0  4418.7     .05       0  4618.7      .1       0
  4693.1     .05       0  4818.8     .16       0  4908.1     .05       0
  4918.8     .16       0  5018.9     .05       0  5089.7      .1       0
  5122.3     .07       0  5128.3      .1       0  5245.4     .05       0
  5350.6      .1       0  5379.7     .05       0  5516.6      .1       0
  5601.1     .16       0  5791.2      .1       0  5895.9     .16       0
Bank Sta=5122.3,5128.3
XS Rating Curve= 0 ,0
Exp/Cntr=0.3,0.1

Type RM Length L Ch R = 1 ,11449   ,562,562,562
BEGIN DESCRIPTION:
NORTH CREEK 21.0
END DESCRIPTION:
XS GIS Cut Line= 2
      2673731.59     10061134.61      2672232.55     10060919.47
#Sta/Elev= 30
  4278.2 1882.55  4534.9 1875.46  4623.2 1871.12  4670.9 1868.88  4826.9  1865.1
  4953.1 1867.25  4978.4 1858.46  4995.6 1857.57  4998.4 1857.07  5001.6 1857.57
  5017.3 1858.37  5023.7 1858.15    5039 1862.39  5049.1 1862.81  5059.2 1862.01
  5069.4 1858.28  5094.3 1858.19  5099.7 1858.72  5119.9 1866.31    5130 1866.96
  5220.9 1869.59  5305.9  1873.5  5376.5 1874.99  5503.8 1881.96  5574.5 1884.54
  5658.7 1890.56  5724.2 1902.18  5729.2    1901  5746.2 1904.98  5792.6 1907.08
#Mann= 5 ,-1 , 0
  4278.2      .1       0  4623.2     .05       0  4995.6    .035       0
  5001.6     .05       0  5017.3      .1       0
Bank Sta=4995.6,5001.6
XS Rating Curve= 0 ,0
Exp/Cntr=0.3,0.1

Type RM Length L Ch R = 1 ,10887   ,414,414,414
BEGIN DESCRIPTION:
NORTH CREEK 20.0
END DESCRIPTION:
XS GIS Cut Line= 3
      2673724.64     10060842.93      2673127.45     10060537.39
      2672648.32     10060273.53
#Sta/Elev= 30
  4256.5 1881.28  4297.1 1879.69  4416.5 1877.77  4442.3 1877.25  4661.6 1875.54
  4811.4 1862.28  4847.5 1859.97  4881.2 1861.27  4937.6 1860.79  5000.9 1855.59
  5003.7 1855.09  5006.9 1855.59  5025.7 1859.62  5031.4 1861.88  5040.3 1863.18
  5087.8 1863.54  5172.4  1862.3  5210.3 1863.54  5232.1 1861.13  5259.6 1860.33
  5303.1  1861.8  5335.3 1864.38  5362.8 1870.22  5378.8 1876.57  5394.2  1881.4
  5400.6 1886.11  5406.3 1886.64  5428.5 1894.87  5451.3 1899.72  5474.3 1901.69
#Mann= 7 ,-1 , 0
  4256.5      .1       0  4416.5     .05       0  4442.3      .1       0
  4881.2     .05       0  5000.9    .035       0  5006.9     .05       0
  5087.8      .1       0
Bank Sta=5000.9,5006.9
XS Rating Curve= 0 ,0
Exp/Cntr=0.3,0.1

Type RM Length L Ch R = 1 ,10473   ,419,419,419
BEGIN DESCRIPTION:
NORTH CREEK 19.0
END DESCRIPTION:
XS GIS Cut Line= 3
      2673870.48     10060474.88      2673141.34     10060127.67
      2672724.68     10060134.62
#Sta/Elev= 30
  4423.5 1883.12  4485.5 1880.64  4502.7 1879.32  4508.2 1879.54    4574    1876
  4701.5 1870.53  4740.8 1869.34  4905.3 1861.86    4937 1858.89  4967.8 1857.47
  4979.5 1855.16  4998.7 1853.22  5001.4 1852.72  5004.7 1853.22  5024.3 1854.83
    5047 1857.99  5079.2 1859.17    5106 1859.17  5212.1 1860.76    5284 1859.45
  5296.8 1859.95    5384 1859.87    5504 1858.42  5516.1 1859.09    5524 1860.59
    5534  1863.8    5574 1883.26    5594 1891.18    5604 1893.02  5647.8 1895.91
#Mann= 9 ,-1 , 0
  4423.5     .16       0  4502.7     .05       0    4574     .16       0
  4701.5      .1       0    4937     .05       0  4998.7    .035       0
  5004.7     .05       0    5106     .16       0  5516.1      .1       0
Bank Sta=4998.7,5004.7
XS Rating Curve= 0 ,0
Exp/Cntr=0.3,0.1

Type RM Length L Ch R = 1 ,10054   ,480,480,480
BEGIN DESCRIPTION:
NORTH CREEK 18.0
END DESCRIPTION:
XS GIS Cut Line= 3
       2673870.5     10060044.34      2673148.28     10059690.17
      2672738.52     10059766.57
#Sta/Elev= 30
  4660.2 1884.66    4676 1884.46    4811 1881.92    4856    1880  4878.5 1875.87
  4885.2 1872.54    4901 1868.07  4907.5 1865.08    4952 1853.36  4974.3 1851.52
  5004.7 1851.01  5007.5 1850.51  5010.7 1851.01    5019 1853.52  5035.9  1854.5
  5041.5 1856.17  5068.4 1856.59  5241.8 1857.04  5341.9 1855.09  5373.4 1856.41
  5408.7 1860.24  5443.5 1862.51  5471.3 1863.98  5510.7 1866.07  5688.2 1872.35
  5718.7 1875.18    5739 1878.21  5784.5 1880.84  5842.3 1886.06  5881.4 1891.03
#Mann= 8 ,-1 , 0
  4660.2     .05       0    4676      .1       0  5004.7     .07       0
  5010.7      .1       0  5068.4     .05       0  5241.8      .1       0
  5443.5     .05       0  5471.3      .1       0
Bank Sta=5004.7,5010.7
XS Rating Curve= 0 ,0
Exp/Cntr=0.3,0.1

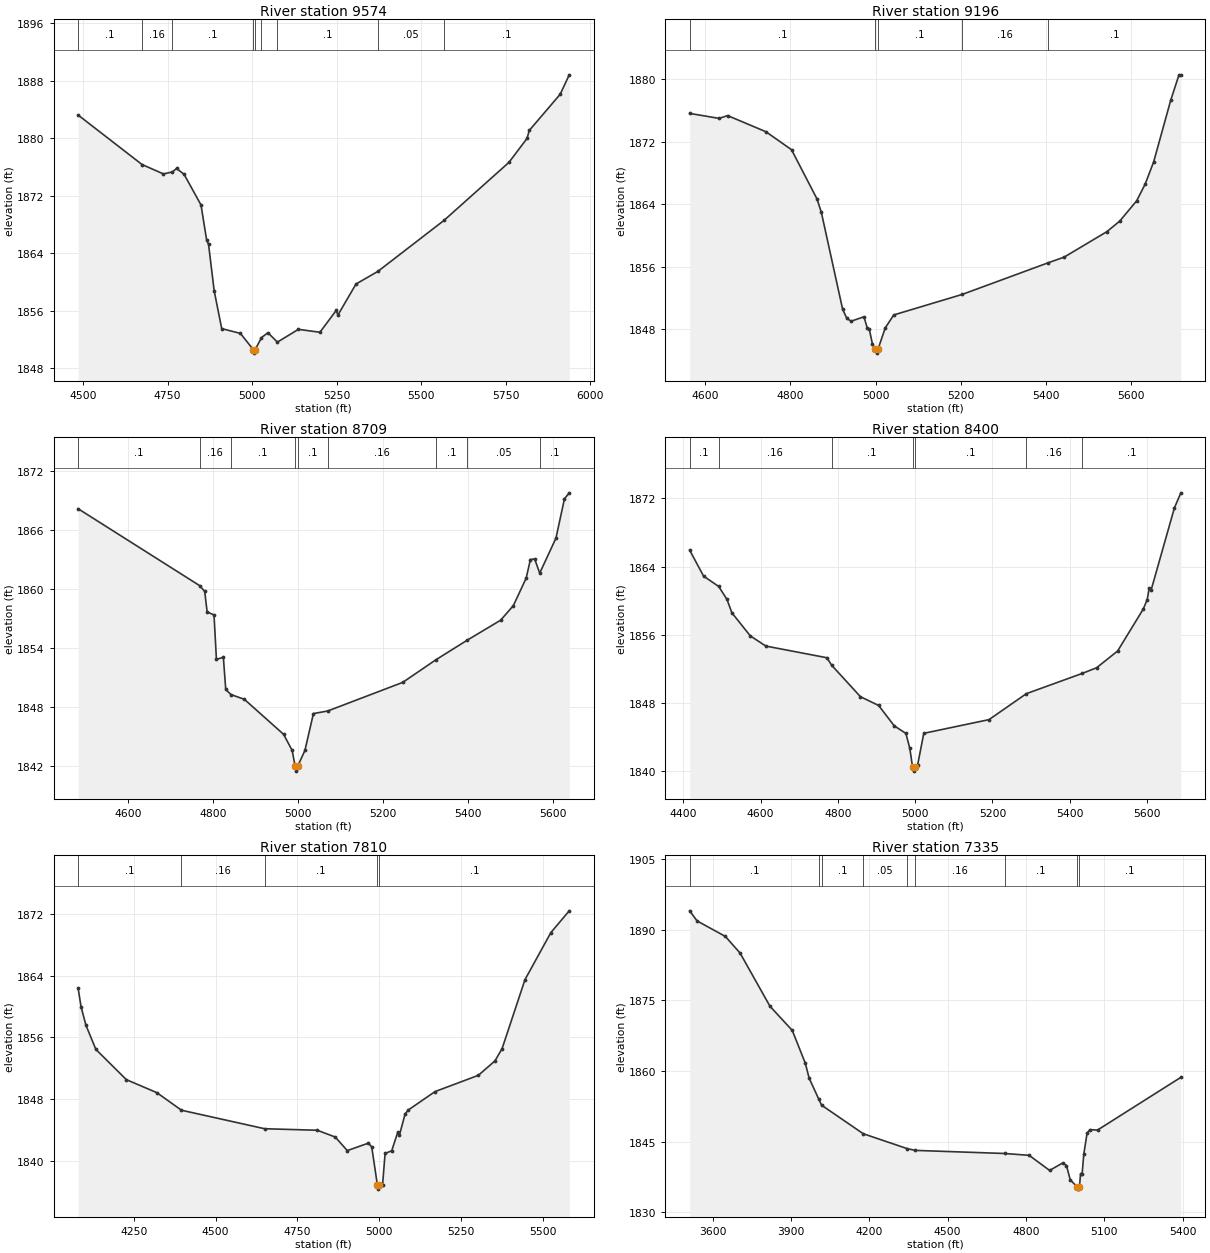
Type RM Length L Ch R = 1 ,9574    ,378,378,378
BEGIN DESCRIPTION:
NORTH CREEK 17.0
END DESCRIPTION:
XS GIS Cut Line= 3
      2674099.64     10059662.38      2673703.84       10059461.
      2672712.08     10059641.32
#Sta/Elev= 30
  4485.6 1883.21  4674.5 1876.33  4737.8 1875.02  4764.6  1875.3  4776.7 1875.78
  4798.9 1874.97    4849  1870.7  4865.7  1865.8  4871.3 1865.22  4887.9 1858.77
  4910.2 1853.51  4965.6 1852.84  5003.3  1850.6    5006  1850.1  5009.3  1850.6
  5027.8 1852.26  5046.9 1852.94  5074.8 1851.63    5137 1853.41  5200.5    1853
  5248.8 1856.04  5253.8  1855.4  5307.2 1859.71  5371.7 1861.46  5567.5 1868.56
  5759.5 1876.63  5812.9 1879.96  5819.4 1881.06  5910.9  1886.1  5937.7  1888.8
#Mann= 9 ,-1 , 0
  4485.6      .1       0  4674.5     .16       0  4764.6      .1       0
  5003.3     .07       0  5009.3      .1       0  5027.8     .16       0
  5074.8      .1       0  5371.7     .05       0  5567.5      .1       0
Bank Sta=5003.3,5009.3
XS Rating Curve= 0 ,0
Exp/Cntr=0.3,0.1

Type RM Length L Ch R = 1 ,9196    ,487,487,487
BEGIN DESCRIPTION:
NORTH CREEK 16.0
END DESCRIPTION:
XS GIS Cut Line= 2
      2674127.45     10059113.78      2672974.64     10059099.89
#Sta/Elev= 30
  4563.4 1875.65  4632.4 1875.01  4652.4 1875.37  4742.4  1873.3  4802.4    1871
  4862.4 1864.68  4872.4 1862.98  4922.4 1850.56  4932.4 1849.39  4942.4 1849.04
  4972.4  1849.6    4980 1848.21    4985 1848.01  4992.4  1846.1  4999.4 1845.45
  5002.2 1844.95  5005.4 1845.45  5022.4 1848.18  5042.4 1849.84  5203.2 1852.47
  5404.4 1856.51  5442.5 1857.25  5542.5  1860.5  5572.5 1861.84  5612.5 1864.45
  5632.5 1866.59  5652.5 1869.45  5692.5 1877.33  5711.9 1880.59  5716.3 1880.59
#Mann= 5 ,-1 , 0
  4563.4      .1       0  4999.4     .07       0  5005.4      .1       0
  5203.2     .16       0  5404.4      .1       0
Bank Sta=4999.4,5005.4
XS Rating Curve= 0 ,0
Exp/Cntr=0.3,0.1

Type RM Length L Ch R = 1 ,8709    ,309,309,309
BEGIN DESCRIPTION:
NORTH CREEK 15.0
END DESCRIPTION:
XS GIS Cut Line= 3
      2674141.37     10058822.13      2673766.34     10058620.73
      2673037.16     10058655.45
#Sta/Elev= 30
  4481.7 1868.19  4767.9 1860.34  4779.6 1859.76  4785.3 1857.68  4801.5 1857.35
  4807.2 1852.83  4823.5 1853.04  4829.1 1849.76  4841.4 1849.24    4873 1848.75
  4965.3 1845.18  4985.4 1843.54  4992.4 1841.93  4995.1 1841.43  4998.4 1841.93
  5015.4 1843.54  5035.4  1847.3  5068.9 1847.56  5245.6 1850.48  5324.1  1852.8
  5397.6 1854.79  5475.9 1856.82  5505.9 1858.31    5536 1861.11    5546 1863.01
    5556 1863.07  5567.9 1861.62  5606.1 1865.19  5626.1  1869.2  5637.4 1869.81
#Mann= 9 ,-1 , 0
  4481.7      .1       0  4767.9     .16       0  4841.4      .1       0
  4992.4     .07       0  4998.4      .1       0  5068.9     .16       0
  5324.1      .1       0  5397.6     .05       0  5567.9      .1       0
Bank Sta=4992.4,4998.4
XS Rating Curve= 0 ,0
Exp/Cntr=0.3,0.1

Type RM Length L Ch R = 1 ,8400    ,590,590,590
BEGIN DESCRIPTION:
NORTH CREEK 14.0
END DESCRIPTION:
XS GIS Cut Line= 2
      2674294.15     10058391.56      2673031.84     10058238.98
#Sta/Elev= 30
  4416.3 1865.92  4452.2 1862.88  4491.4 1861.66  4512.7 1860.15  4525.5 1858.57
  4573.1 1855.86  4613.4 1854.66  4771.4 1853.29    4784  1852.4  4858.4 1848.71
  4905.5 1847.68  4945.8 1845.29    4976  1844.4  4986.1 1842.64  4993.2 1840.47
  4995.9 1839.97  4999.2 1840.47  5006.2 1840.66  5022.3 1844.41  5191.2 1846.02
  5287.9 1849.07  5432.1 1851.44  5469.6 1852.11  5524.1 1854.08  5590.5 1859.01
  5600.5  1860.1    5606 1861.45  5611.1 1861.28  5671.1 1870.89  5687.8 1872.66
#Mann= 7 ,-1 , 0
  4416.3      .1       0  4491.4     .16       0    4784      .1       0
  4993.2     .07       0  4999.2      .1       0  5287.9     .16       0
  5432.1      .1       0
Bank Sta=4993.2,4999.2
XS Rating Curve= 0 ,0
Exp/Cntr=0.3,0.1

Type RM Length L Ch R = 1 ,7810    ,475,475,475
BEGIN DESCRIPTION:
NORTH CREEK 13.0
END DESCRIPTION:
XS GIS Cut Line= 3
      2674405.19     10058210.98      2673752.45     10057780.45
      2673045.65     10057919.04
#Sta/Elev= 30
  4079.5  1862.4  4088.6 1859.96  4103.6 1857.56  4133.8 1854.44  4227.1 1850.51
  4320.4 1848.82  4395.7 1846.54  4649.9 1844.14  4811.2 1843.94    4866 1843.06
  4902.8  1841.3  4967.4 1842.27  4977.6 1841.78    4995  1836.8  4997.7  1836.3
    5001  1836.8  5010.8 1836.88  5018.4 1840.93  5038.7 1841.28  5057.2 1843.69
  5062.3  1843.3  5079.5 1846.05  5089.7 1846.58  5171.2 1848.96  5303.7 1851.07
  5354.6 1852.95  5376.2 1854.53  5446.4  1863.5  5525.5  1869.6  5581.7 1872.42
#Mann= 5 ,-1 , 0
  4079.5      .1       0  4395.7     .16       0  4649.9      .1       0
    4995     .07       0    5001      .1       0
Bank Sta=4995,5001
XS Rating Curve= 0 ,0
Exp/Cntr=0.3,0.1

Type RM Length L Ch R = 1 ,7335    ,429,429,429
BEGIN DESCRIPTION:
NORTH CREEK 12.0
END DESCRIPTION:
XS GIS Cut Line= 3
       2674918.5     10058253.76      2673718.47     10057353.73
       2673368.5     10057203.75
#Sta/Elev= 30
  3512.2 1893.99  3540.4 1891.85  3648.7 1888.56    3705 1885.04  3819.5 1873.75
    3905 1868.61    3955 1861.64  3969.5  1858.5  4006.7    1854  4017.3 1852.75
  4176.9 1846.69  4343.7 1843.56  4375.5 1843.16  4718.9  1842.5  4812.2 1842.11
  4890.4 1838.91  4940.4 1840.49    4955 1839.95  4969.5  1836.9  4995.7 1835.44
  4998.5 1834.94  5001.7 1835.44    5005 1835.66  5009.1 1838.24    5015 1838.24
  5021.3 1842.35    5034 1846.84  5044.9 1847.56  5073.9 1847.47    5393 1858.66
#Mann= 9 ,-1 , 0
  3512.2      .1       0  4006.7     .05       0  4017.3      .1       0
  4176.9     .05       0  4343.7      .1       0  4375.5     .16       0
  4718.9      .1       0  4995.7     .07       0  5001.7      .1       0
Bank Sta=4995.7,5001.7
XS Rating Curve= 0 ,0
Exp/Cntr=0.3,0.1

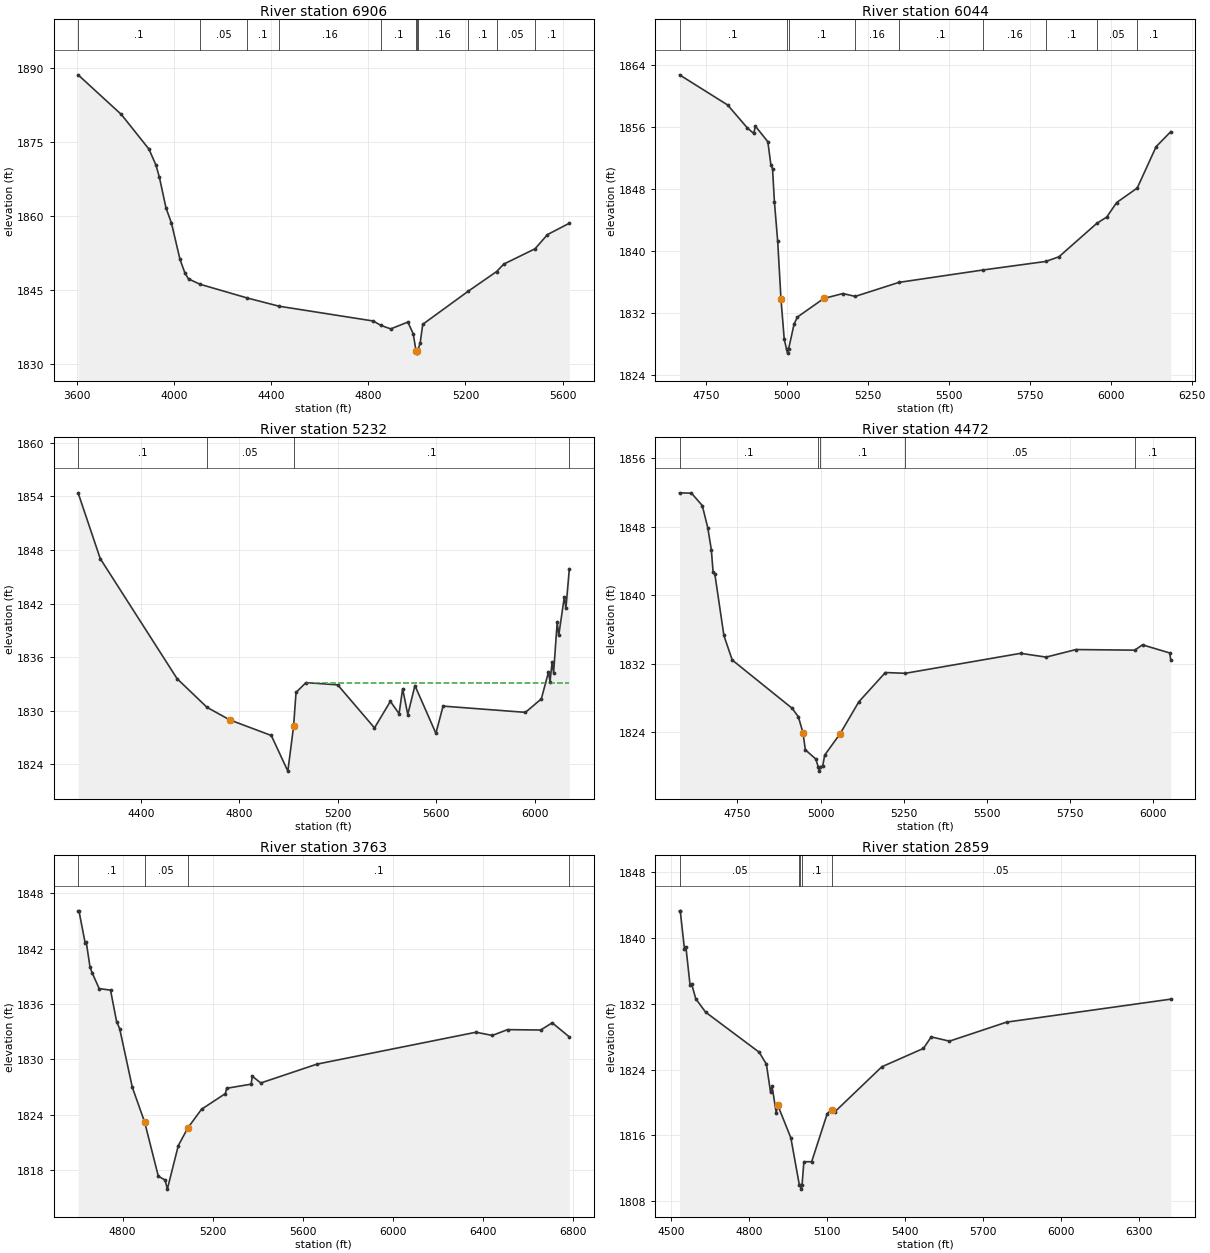
Type RM Length L Ch R = 1 ,6906    ,862,862,862
BEGIN DESCRIPTION:
NORTH CREEK 11.0
END DESCRIPTION:
XS GIS Cut Line= 3
      2674868.44      10058103.7      2673968.47     10057003.73
       2673368.5     10057003.73
#Sta/Elev= 30
  3606.2 1888.56  3784.2 1880.52  3897.6 1873.51  3926.3  1870.3  3940.7 1867.79
  3967.9 1861.57  3990.2 1858.53  4025.4 1851.15  4046.2 1848.33  4060.5 1847.19
  4107.8 1846.11  4301.2 1843.34    4433 1841.66  4820.7 1838.66  4851.3 1837.79
  4892.5 1837.06  4962.8 1838.45  4985.1 1836.07  4996.4 1832.65  4999.2 1832.15
  5002.4 1832.65  5005.7 1832.97  5013.8 1834.26  5024.2 1837.99  5211.9 1844.72
    5328 1848.68  5357.4 1850.19  5486.5 1853.31  5537.4 1856.18  5627.4 1858.48
#Mann= 11 ,-1 , 0
  3606.2      .1       0  4107.8     .05       0  4301.2      .1       0
    4433     .16       0  4851.3      .1       0  4996.4     .07       0
  5002.4      .1       0  5005.7     .16       0  5211.9      .1       0
    5328     .05       0  5486.5      .1       0
Bank Sta=4996.4,5002.4
XS Rating Curve= 0 ,0
Exp/Cntr=0.3,0.1

Type RM Length L Ch R = 1 ,6044    ,812,812,812
BEGIN DESCRIPTION:
NORTH CREEK 10.0
END DESCRIPTION:
XS GIS Cut Line= 3
      2674877.47     10056724.92      2674738.56     10056565.17
      2673453.88     10056801.28
#Sta/Elev= 30
  4667.4 1862.74    4816 1858.85  4876.7  1855.9  4896.6 1855.17  4901.7 1856.12
  4940.2 1854.11  4949.7 1851.13  4954.8 1850.62  4960.5 1846.39  4970.7 1841.25
  4980.9 1833.77    4991 1828.59  4998.2 1827.33    5001 1826.83  5004.2 1827.33
  5021.5 1830.61  5031.7 1831.49  5113.1 1833.88  5172.2 1834.52  5210.3 1834.15
  5345.5 1835.96  5605.3 1837.56    5799 1838.66  5839.7 1839.26  5956.8 1843.58
  5987.5 1844.39    6018 1846.26  6081.6 1848.13    6140 1853.47  6185.3 1855.41
#Mann= 9 ,-1 , 0
  4667.4      .1       0  4998.2     .07       0  5004.2      .1       0
  5210.3     .16       0  5345.5      .1       0  5605.3     .16       0
    5799      .1       0  5956.8     .05       0  6081.6      .1       0
Bank Sta=4980.9,5113.1
XS Rating Curve= 0 ,0
Exp/Cntr=0.3,0.1

Type RM Length L Ch R = 1 ,5232    ,760,760,760
BEGIN DESCRIPTION:
NORTH CREEK 9.0
END DESCRIPTION:
XS GIS Cut Line= 4
      2674995.47     10056363.75      2674467.73     10055926.28
      2674134.39     10055891.56      2673544.32     10056669.08
#Sta/Elev= 30
  4144.2 1854.41  4234.1 1847.05  4546.6  1833.6  4667.8  1830.4  4760.2 1828.99
  4929.5 1827.24  4996.7 1823.25    5020 1828.26    5030 1832.06  5070.2 1833.16
  5199.2 1832.91  5348.9 1828.09  5413.4 1831.06  5448.8 1829.68  5463.3 1832.47
  5484.2 1829.59  5513.3 1832.83  5598.5 1827.48  5627.6 1830.53  5962.5 1829.83
    6027 1831.34  6056.1 1834.34  6062.4 1833.27  6070.6 1835.42  6076.9 1834.26
  6091.5 1839.94  6097.7 1838.44  6120.6 1842.78  6126.8 1841.47  6140.9 1845.91
#Mann= 4 ,-1 , 0
  4144.2      .1       0  4667.8     .05       0    5020      .1       0
  6140.9      .1       0
#XS Ineff= 2 , 0
                         5070.12         1833.16
Permanent Ineff=
       T       T
Bank Sta=4760.2,5020
XS Rating Curve= 0 ,0
Exp/Cntr=0.3,0.1

Type RM Length L Ch R = 1 ,4472    ,709,709,709
BEGIN DESCRIPTION:
NORTH CREEK 8.0
END DESCRIPTION:
XS GIS Cut Line= 3
      2675103.52     10056195.02      2674872.46     10055453.18
      2674241.95     10055146.79
#Sta/Elev= 30
  4575.8 1851.93  4611.7 1851.89  4644.2 1850.45  4660.9 1847.83  4671.4 1845.31
  4676.8  1842.7    4682 1842.46  4709.3 1835.29  4734.3 1832.43  4914.9 1826.79
  4933.3 1825.81  4947.4 1823.92  4954.2 1821.96  4985.6 1820.89  4993.1 1819.97
  4995.9 1819.47  4999.1 1819.97  5006.6 1820.07  5012.5 1821.34  5058.9 1823.83
  5115.3 1827.56  5195.1 1830.97  5255.1 1830.88  5601.8 1833.21  5678.7 1832.77
  5768.6 1833.65  5945.5 1833.58  5968.7  1834.2  6050.7 1833.25  6053.8  1832.4
#Mann= 5 ,-1 , 0
  4575.8      .1       0  4993.1     .07       0  4999.1      .1       0
  5255.1     .05       0  5945.5      .1       0
Bank Sta=4947.4,5058.9
XS Rating Curve= 0 ,0
Exp/Cntr=0.3,0.1

Type RM Length L Ch R = 1 ,3763    ,904,904,904
BEGIN DESCRIPTION:
NORTH CREEK 7.0
END DESCRIPTION:
XS GIS Cut Line= 3
      2675738.56     10056176.29      2675627.45     10055419.34
      2674244.21     10055108.93
#Sta/Elev= 30
  4602.1  1846.1  4605.9  1846.1  4633.6  1842.6  4638.6 1842.67  4655.2 1839.98
  4665.3 1839.34  4695.7 1837.67  4746.2  1837.5  4773.2 1834.09  4786.6 1833.34
    4843 1826.97  4897.8 1823.19  4958.4 1817.34  4988.8 1816.91  4998.6 1815.93
  5047.3 1820.65  5089.8 1822.57  5150.5 1824.59  5256.7 1826.29  5261.8 1826.86
  5370.6 1827.31  5376.4 1828.16  5413.9 1827.44  5663.3 1829.48    6370 1832.94
  6442.2 1832.59  6510.3 1833.22  6657.5 1833.18  6708.7 1833.96  6784.8 1832.43
#Mann= 4 ,-1 , 0
  4602.1      .1       0  4897.8     .05       0  5089.8      .1       0
  6784.8      .1       0
Bank Sta=4897.8,5089.8
XS Rating Curve= 0 ,0
Exp/Cntr=0.3,0.1

Type RM Length L Ch R = 1 ,2859    ,503,503,503
BEGIN DESCRIPTION:
NORTH CREEK 6.0
END DESCRIPTION:
XS GIS Cut Line= 3
      2676537.13     10055419.32        2676183.     10055224.89
      2674696.89     10055176.28
#Sta/Elev= 30
  4531.1 1843.21  4533.8 1843.26  4549.9 1838.68  4555.6  1838.9  4571.7  1834.2
  4577.4 1834.42  4593.5 1832.59  4631.4 1830.96  4837.6  1826.1  4865.4 1824.65
  4881.5 1821.23  4887.2 1821.98  4903.3 1818.76    4909 1819.69  4959.6  1815.7
  4992.1 1810.01  4996.7 1809.98  4999.4 1809.48  5002.7 1809.98  5009.7  1812.8
  5039.7 1812.81  5099.7 1818.65  5116.2 1819.11  5129.7 1818.89  5309.8 1824.33
  5469.9 1826.56  5499.9 1827.96    5570 1827.44  5790.1 1829.75    6422 1832.54
#Mann= 5 ,-1 , 0
  4531.1     .05       0  4992.1      .1       0  4996.7     .07       0
  5002.7      .1       0  5116.2     .05       0
Bank Sta=4909,5116.2
XS Rating Curve= 0 ,0
Exp/Cntr=0.3,0.1

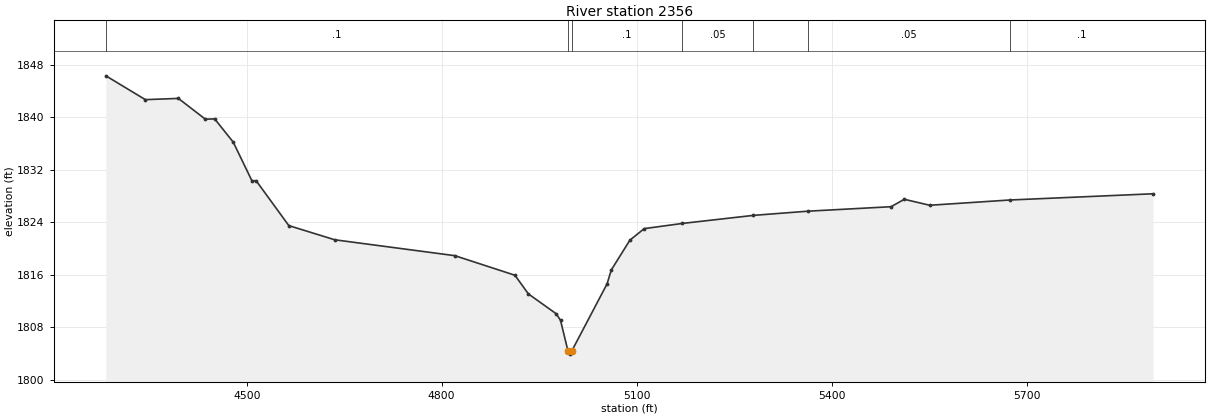
Type RM Length L Ch R = 1 ,2356    ,404,404,404
BEGIN DESCRIPTION:
NORTH CREEK 5.0
END DESCRIPTION:
XS GIS Cut Line= 3
      2676634.39     10055204.06      2675912.17     10054599.89
      2675273.36     10054801.26
#Sta/Elev= 30
  4283.3 1846.29    4344 1842.66  4394.8 1842.85  4436.4 1839.68  4450.7 1839.73
  4479.3 1836.18    4508  1830.3  4514.5 1830.31  4564.8 1823.47  4635.5 1821.31
  4820.3 1818.89  4912.7 1815.91  4933.5 1813.06  4976.4 1810.03  4982.9 1809.03
  4994.3 1804.39    4997 1803.89  5000.3 1804.39  5054.5 1814.59    5061 1816.71
  5089.6 1821.25  5111.7 1823.01  5170.3  1823.8  5279.8 1825.03  5363.9 1825.67
  5491.6 1826.35  5511.9 1827.48  5551.1 1826.57  5673.9 1827.37  5894.7 1828.32
#Mann= 7 ,-1 , 0
  4283.3      .1       0  4994.3     .07       0  5000.3      .1       0
  5170.3     .05       0  5279.8      .1       0  5363.9     .05       0
  5673.9      .1       0
Bank Sta=4994.3,5000.3
XS Rating Curve= 0 ,0
Exp/Cntr=0.3,0.1