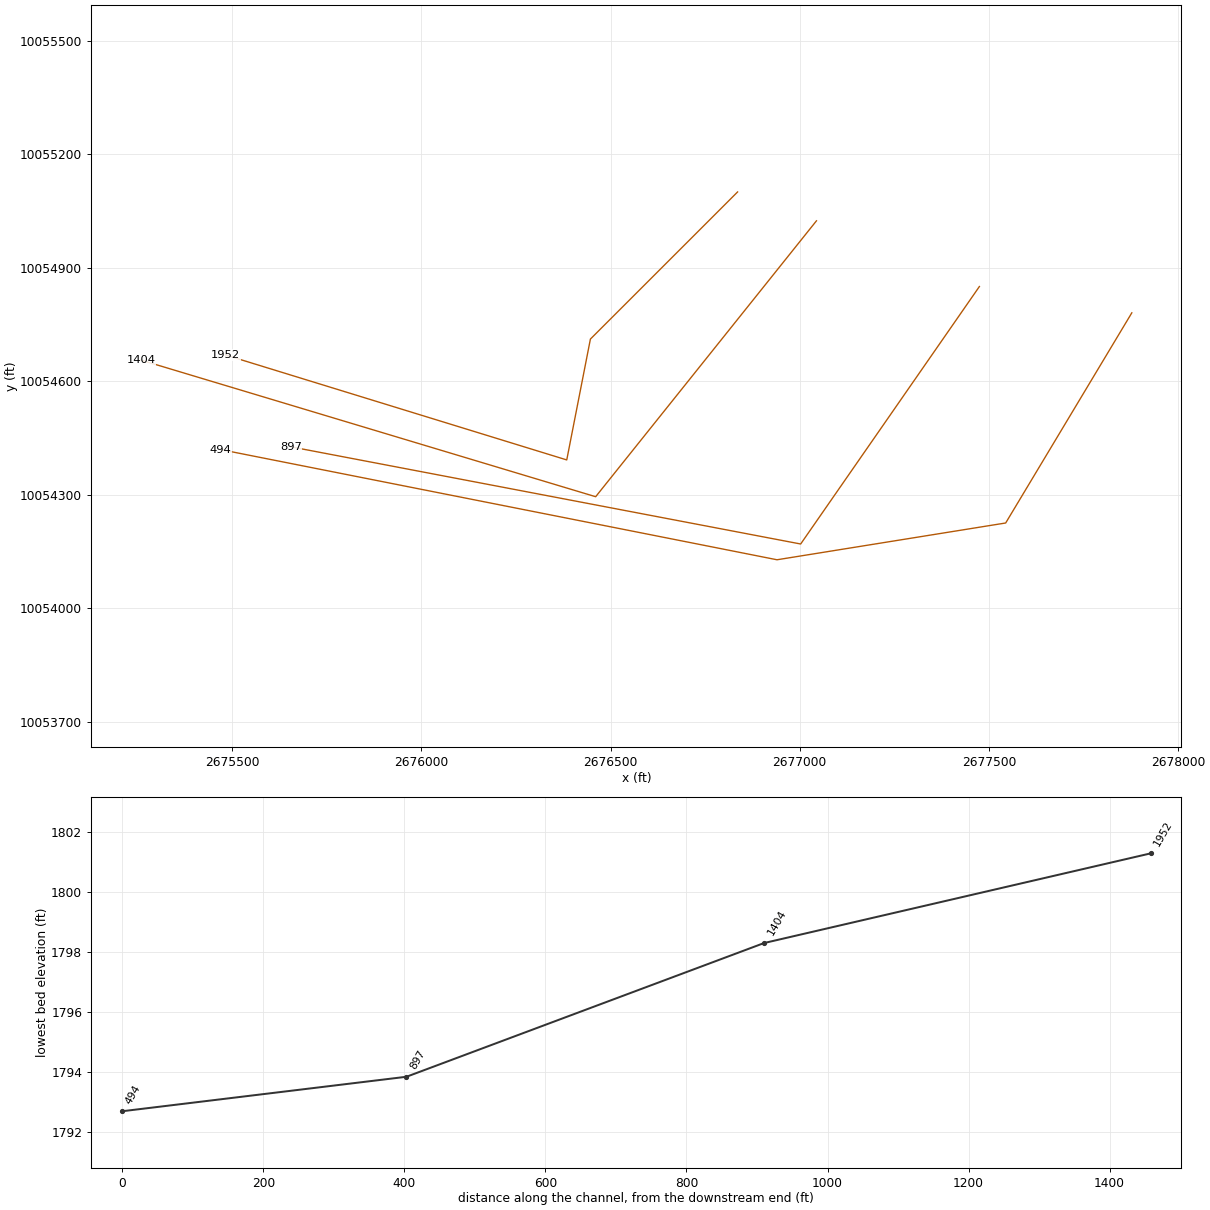
HEC-RAS study NORTH CREEK.prj: NORTH CREEK Base Level Engineering

--- NORTH CREEK.g01 (geometry) --- (continued)

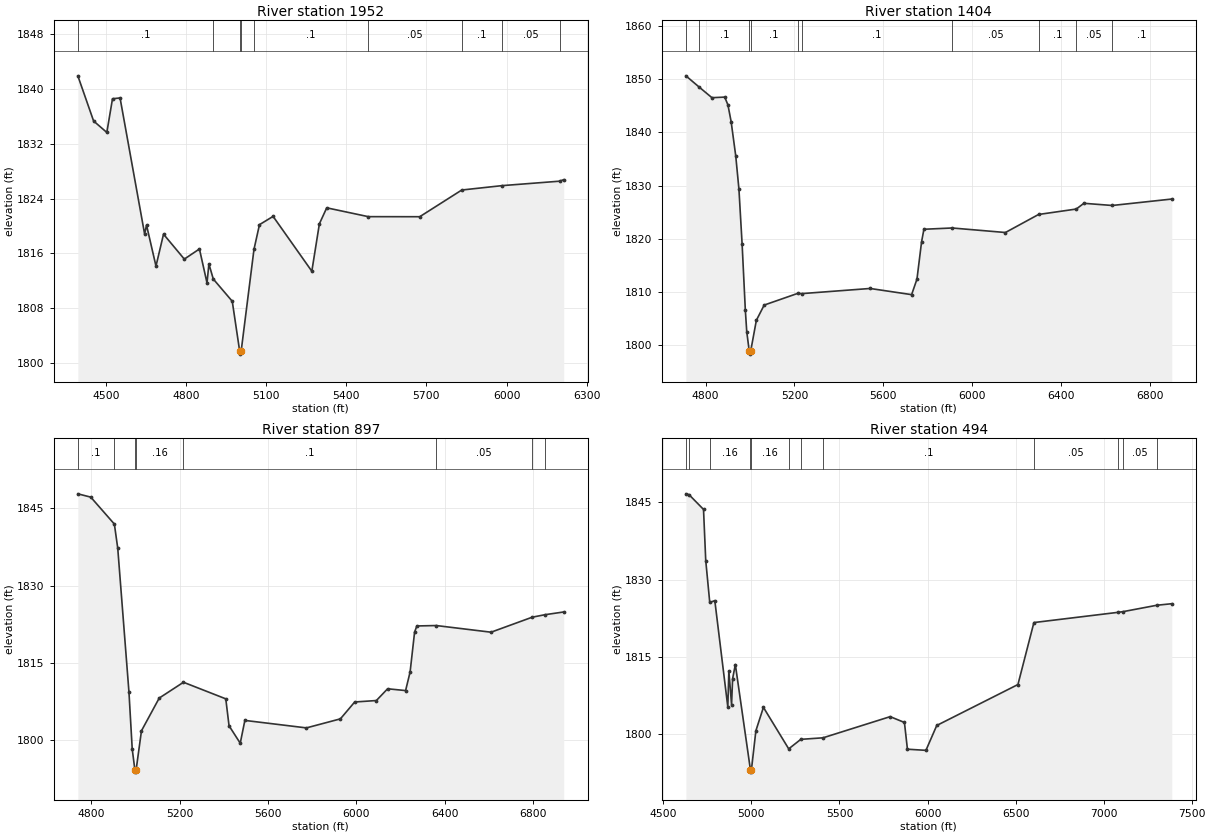
Type RM Length L Ch R = 1 ,1952    ,548,548,548
BEGIN DESCRIPTION:
NORTH CREEK 4.0
END DESCRIPTION:
XS GIS Cut Line= 4
      2676835.78     10055099.89      2676446.89       10054711.
      2676384.39     10054391.56      2675483.54     10054668.75
#Sta/Elev= 30
  4395.7 1841.95  4454.7 1835.35  4504.2 1833.68  4525.4  1838.6  4553.7 1838.72
  4645.6 1818.84  4652.7 1820.14  4688.1 1814.16  4716.3 1818.82  4794.1 1815.18
  4850.7 1816.66    4879  1811.7  4886.1 1814.47  4902.5 1812.27  4973.5 1809.02
    5001  1801.8  5003.8  1801.3    5007  1801.8  5054.8 1816.61  5075.3 1820.21
  5126.3 1821.42  5271.2 1813.41  5299.5 1820.34    5327 1822.67  5482.5 1821.38
  5674.9 1821.37  5832.2 1825.27  5982.7 1825.91  6197.9 1826.56  6213.7 1826.78
#Mann= 9 ,-1 , 0
  4395.7      .1       0  4902.5     .16       0    5001     .07       0
    5007     .16       0  5054.8      .1       0  5482.5     .05       0
  5832.2      .1       0  5982.7     .05       0  6197.9      .1       0
Bank Sta=5001,5007
XS Rating Curve= 0 ,0
Exp/Cntr=0.3,0.1

Type RM Length L Ch R = 1 ,1404    ,507,507,507
BEGIN DESCRIPTION:
NORTH CREEK 3.0
END DESCRIPTION:
XS GIS Cut Line= 3
      2677044.14     10055023.53      2676460.78     10054294.34
       2675259.4     10054655.45
#Sta/Elev= 30
    4711 1850.62  4771.8 1848.47  4828.3 1846.51  4885.9 1846.62  4900.3 1845.16
  4914.7 1842.03  4935.5 1835.57  4949.9 1829.31  4964.3 1818.92  4978.7 1806.59
  4985.1 1802.52  4996.5 1798.81  4999.3 1798.31  5002.5 1798.81  5028.4 1804.67
  5063.6 1807.53  5214.2 1809.72    5232 1809.68  5540.6 1810.65  5727.6 1809.49
  5751.7 1812.41  5772.5 1819.44    5783 1821.78  5910.1 1822.02  6150.1 1821.17
  6299.4 1824.56  6469.1 1825.58  6503.5 1826.66  6630.9 1826.25  6899.3 1827.46
#Mann= 10 ,-1 , 0
    4711     .05       0  4771.8      .1       0  4996.5     .07       0
  5002.5      .1       0  5214.2     .05       0    5232      .1       0
  5910.1     .05       0  6299.4      .1       0  6469.1     .05       0
  6630.9      .1       0
Bank Sta=4996.5,5002.5
XS Rating Curve= 0 ,0
Exp/Cntr=0.3,0.1

Type RM Length L Ch R = 1 ,897     ,403,403,403
BEGIN DESCRIPTION:
NORTH CREEK 2.0
END DESCRIPTION:
XS GIS Cut Line= 3
      2677474.67     10054849.89      2677002.45     10054169.34
      2675655.26     10054426.28
#Sta/Elev= 30
  4739.2 1847.77  4797.7 1847.13  4904.6 1841.91  4919.9 1837.22  4970.6 1809.39
  4985.5 1798.29  4997.3 1794.35  5000.1 1793.85  5003.3 1794.35  5027.3 1801.86
  5107.7  1808.2  5217.5 1811.26    5409 1808.05  5423.8 1802.83  5474.5 1799.45
  5495.4 1803.87    5774 1802.42  5927.9 1804.17  5992.7 1807.44  6090.8 1807.72
  6141.7    1810  6223.1 1809.65  6243.5 1813.25  6263.8 1820.97    6274 1822.17
  6361.9 1822.25    6610 1820.96  6796.5 1823.87  6854.1 1824.35    6939 1824.88
#Mann= 8 ,-1 , 0
  4739.2      .1       0  4904.6     .16       0  4997.3     .07       0
  5003.3     .16       0  5217.5      .1       0  6361.9     .05       0
  6796.5      .1       0  6854.1     .05       0
Bank Sta=4997.3,5003.3
XS Rating Curve= 0 ,0
Exp/Cntr=0.3,0.1

Type RM Length L Ch R = 1 ,494     ,0,0,0
BEGIN DESCRIPTION:
NORTH CREEK 1.0
END DESCRIPTION:
XS GIS Cut Line= 4
      2677877.42     10054780.41      2677544.12     10054224.89
      2676939.95     10054127.67      2675469.21     10054419.04
#Sta/Elev= 30
    4628 1846.62  4645.7 1846.46  4728.1  1843.6  4740.7 1833.69  4763.5 1825.57
  4792.2 1825.93  4866.1 1805.32  4871.9 1812.34  4887.4 1805.76  4893.3 1810.81
  4908.8 1813.55  4994.3  1793.2  4997.1  1792.7  5000.3  1793.2  5025.4 1800.71
  5068.2 1805.25  5211.9 1797.21  5280.5 1799.05  5406.7 1799.35    5788 1803.45
    5869 1802.32    5886 1797.14  5991.1 1796.92  6052.5 1801.74  6513.5 1809.67
  6604.2 1821.68  7079.7 1823.65  7111.4  1823.8  7301.9 1825.03  7387.1 1825.33
#Mann= 12 ,-1 , 0
    4628     .05       0  4645.7      .1       0  4763.5     .16       0
  4994.3     .07       0  5000.3     .16       0  5211.9      .1       0
  5280.5     .16       0  5406.7      .1       0  6604.2     .05       0
  7079.7      .1       0  7111.4     .05       0  7301.9      .1       0
Bank Sta=4994.3,5000.3
XS Rating Curve= 0 ,0
Exp/Cntr=0.3,0.1

Chan Stop Cuts=-1
Use User Specified Reach Order=0
Composite Channel Slope=5