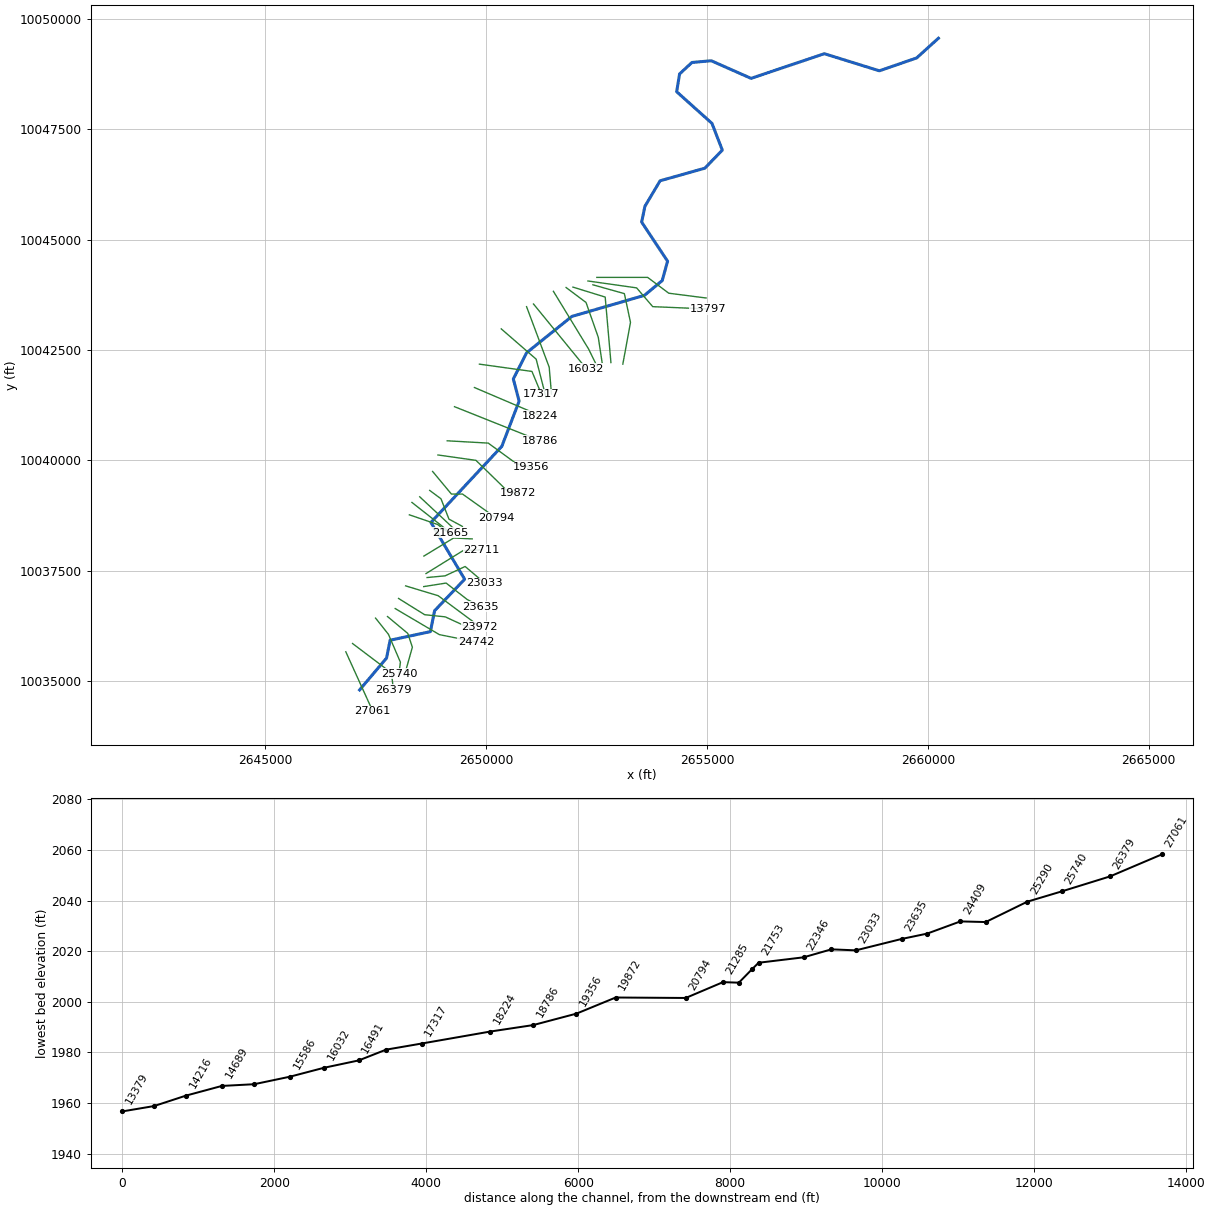
--- NOTT BRANCH.prj (project) ---

Proj Title=NOTT BRANCH Base Level Engineering
Current Plan=p01
Default Exp/Contr=0.3,0.1
English Units
Geom File=g01
Flow File=f01
Plan File=p01
Y Axis Title=Elevation
X Axis Title(PF)=Main Channel Distance
X Axis Title(XS)=Station
BEGIN DESCRIPTION:
NOTT BRANCH
END DESCRIPTION:
DSS Export Rating Curves= 0
DSS Export Rating Curve Sorted= 0
DSS Export Volume Flow Curves= 0
DXF OffsetX= 0
DXF OffsetY= 0
DXF ScaleX= 1
DXF ScaleY= 10

--- NOTT BRANCH.p01 (plan) ---

Plan Title=Multiple Run
Short Identifier=Multiple
Geom File=g01
Flow File=f01
Subcritical Flow
K Sum by GR= 0
Std Step Tol= 0.01
Critical Tol= 0.01
Num of Std Step Trials= 20
Max Error Tol= 0.3
Flow Tol Ratio= 0.001
Split Flow NTrial= 30
Split Flow Tol= 0.02
Split Flow Ratio= 0.02
Log Output Level= 0
Friction Slope Method= 1
Unsteady Friction Slope Method= 2
Unsteady Bridges Friction Slope Method= 1
Parabolic Critical Depth
Global Vel Dist=  1 , 1 , 1
Global Log Level= 0
CheckData=True
Encroach Param= -1, 0, 0, 0
BEGIN DESCRIPTION:
Multiple Run
END DESCRIPTION:

--- NOTT BRANCH.f01 (steady flow) ---

Flow Title=Multiple
Program Version=4.10
Number of Profiles= 7
Profile Names=10-year,25-year,50-year,1pct_min,100-year,1pct_plu,500-year
River Rch & RM=NOTT BRANCH,Reach-1         ,27061
    1042    1502    1895    1742    2356    3186    3642
River Rch & RM=NOTT BRANCH,Reach-1         ,24742
    2540    3828    4976    4699    6355    8595   10375
River Rch & RM=NOTT BRANCH,Reach-1         ,18786
    2941    4452    5805    5495    7431   10049   12188
River Rch & RM=NOTT BRANCH,Reach-1         ,13797
    4092    6261    8219    7825   10583   14312   17560
River Rch & RM=NOTT BRANCH,Reach-1         ,13379
    4092    6261    8219    7825   10583   14312   17560
River Rch & RM=NOTT BRANCH,Reach-1         ,1096
    4845    7465    9849    9419   12738   17227   21328
Boundary for River Rch & Prof#=NOTT BRANCH,Reach-1         , 1
Up Type= 0
Dn Type= 3
Dn Slope=0.013
Boundary for River Rch & Prof#=NOTT BRANCH,Reach-1         , 2
Up Type= 0
Dn Type= 3
Dn Slope=0.013
Boundary for River Rch & Prof#=NOTT BRANCH,Reach-1         , 3
Up Type= 0
Dn Type= 3
Dn Slope=0.013
Boundary for River Rch & Prof#=NOTT BRANCH,Reach-1         , 4
Up Type= 0
Dn Type= 3
Dn Slope=0.013
Boundary for River Rch & Prof#=NOTT BRANCH,Reach-1         , 5
Up Type= 0
Dn Type= 3
Dn Slope=0.013
Boundary for River Rch & Prof#=NOTT BRANCH,Reach-1         , 6
Up Type= 0
Dn Type= 3
Dn Slope=0.013
Boundary for River Rch & Prof#=NOTT BRANCH,Reach-1         , 7
Up Type= 0
Dn Type= 3
Dn Slope=0.013
DSS Import GetInterval= 0
DSS Import GetPeak= 0
DSS Import FillOption= 0

--- NOTT BRANCH.g01 (geometry) ---

Geom Title=Existing Conditions
Program Version=4.10

River Reach=NOTT BRANCH     ,Reach-1
Reach XY= 30
      2647136.18     10034802.73      2647746.06     10035524.69
       2647826.5     10035928.77      2648738.47     10036123.73
      2648833.38     10036596.44      2649514.26     10037310.78
      2648750.25     10038596.26      2650355.71     10040320.73
      2650747.41     10041344.37      2650615.73     10041846.82
       2650916.9     10042439.91      2651939.19     10043261.95
      2653585.15     10043740.36      2653986.02     10044074.67
      2654107.56     10044513.25      2653520.97     10045399.36
      2653594.16     10045756.33      2653938.12     10046334.84
      2654951.29     10046620.36      2655346.67     10047029.25
      2655112.22     10047635.06      2654313.63     10048352.45
      2654379.05      10048754.9      2654659.07     10049014.58
      2655096.15     10049053.78      2655997.63     10048654.62
      2657655.74     10049213.29      2658901.81      10048825.9
      2659746.21     10049117.77      2660238.47     10049563.73

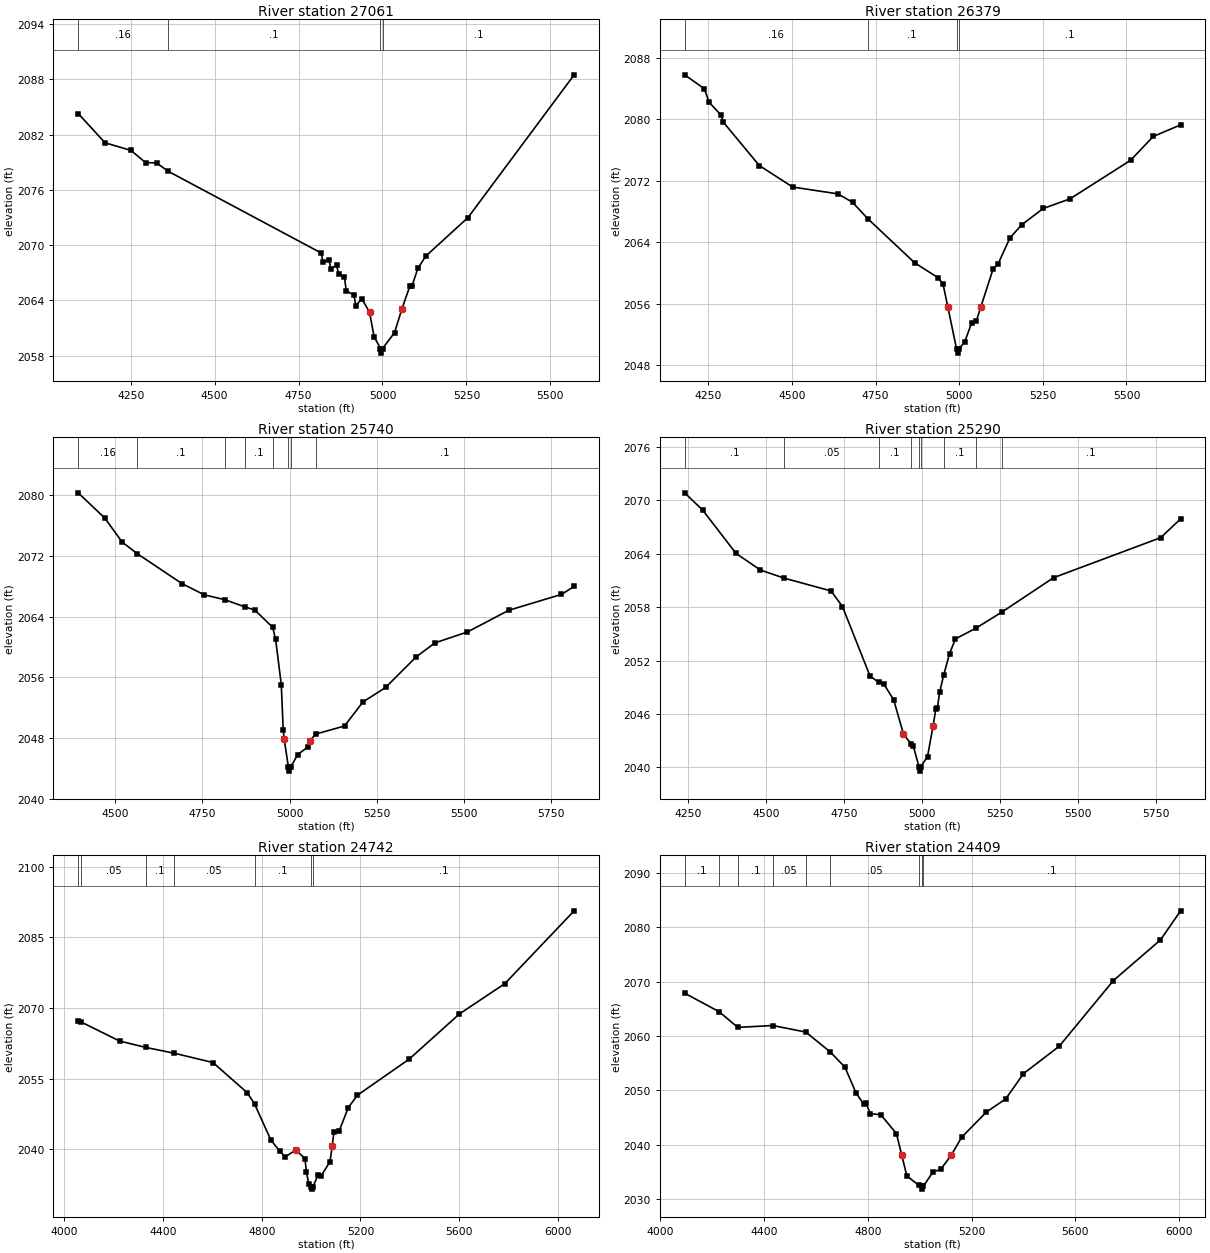
Type RM Length L Ch R = 1 ,27061   ,682,682,682
BEGIN DESCRIPTION:
NOTT BRANCH 60.0
END DESCRIPTION:
XS GIS Cut Line= 2
       2646823.8      10035666.6      2647434.19     10034320.97
#Sta/Elev= 30
  4093.5 2084.29  4173.5 2081.11  4250.4 2080.29  4294.3 2078.96  4327.2 2078.93
    4360 2078.05  4817.4 2069.15  4822.9 2068.14  4840.5 2068.44    4846 2067.43
  4863.6 2067.82  4869.1 2066.87  4886.6 2066.55  4892.1 2065.05  4915.2 2064.56
  4920.7 2063.42  4938.3 2064.19  4961.4 2062.72  4975.1 2060.06  4994.1 2058.78
  4996.8 2058.28  5000.1 2058.78  5036.1 2060.51 5057.27 2063.02  5082.3 2065.62
  5087.8 2065.56  5105.4 2067.47  5128.5 2068.79  5254.9    2073  5571.1 2088.49
#Mann= 4 ,-1 , 0
  4093.5     .16       0    4360      .1       0  4994.1     .07       0
  5000.1      .1       0
Bank Sta=4961.4,5057.27
XS Rating Curve= 0 ,0
Exp/Cntr=0.3,0.1

Type RM Length L Ch R = 1 ,26379   ,639,639,639
BEGIN DESCRIPTION:
NOTT BRANCH 59.0
END DESCRIPTION:
XS GIS Cut Line= 3
      2646976.56     10035854.13      2647858.52     10035187.45
      2647900.19     10034812.44
#Sta/Elev= 30
  4179.1 2085.78  4237.8 2083.97  4252.4 2082.19  4287.8 2080.55  4294.3 2079.64
  4402.2 2073.98  4502.1 2071.18  4637.4 2070.29  4681.1 2069.19  4726.8 2067.05
  4866.3 2061.34  4937.1 2059.37  4951.7 2058.54  4966.2 2055.51  4992.3 2050.07
  4995.1 2049.57  4998.3 2050.07  5016.2 2051.01    5037 2053.47  5051.5 2053.79
 5064.66 2055.59  5101.5 2060.55  5116.1 2061.17  5151.4 2064.54  5186.8 2066.27
  5251.3 2068.39  5331.6 2069.65  5512.7 2074.67  5580.2 2077.76    5662 2079.27
#Mann= 4 ,-1 , 0
  4179.1     .16       0  4726.8      .1       0  4992.3     .07       0
  4998.3      .1       0
Bank Sta=4966.2,5064.66
XS Rating Curve= 0 ,0
Exp/Cntr=0.3,0.1

Type RM Length L Ch R = 1 ,25740   ,450,450,450
BEGIN DESCRIPTION:
NOTT BRANCH 57.0
END DESCRIPTION:
XS GIS Cut Line= 4
      2647497.43     10036430.47      2647789.08     10036062.45
      2648059.91      10035430.5      2648025.33     10035167.68
#Sta/Elev= 30
  4393.9 2080.31  4470.3 2076.97    4520 2073.81  4563.2 2072.29  4691.5 2068.34
  4755.6 2066.86  4813.7 2066.23  4871.9 2065.27  4900.1 2064.86  4951.6 2062.58
    4960    2061  4976.2 2055.04  4981.8 2049.08 4984.43 2047.88  4996.8 2044.12
  4999.6 2043.62  5002.8 2044.12  5023.4 2045.81  5052.4  2046.8  5057.9 2047.62
  5075.4 2048.51  5157.6 2049.57  5210.2 2052.73  5275.4 2054.65  5362.5 2058.66
  5416.9 2060.53  5509.3 2061.95  5628.4 2064.82  5779.7 2066.92  5816.1 2067.97
#Mann= 8 ,-1 , 0
  4393.9     .16       0  4563.2      .1       0  4813.7     .05       0
  4871.9      .1       0  4951.6     .05       0  4996.8    .035       0
  5002.8     .05       0  5075.4      .1       0
Bank Sta=4984.43,5057.9
XS Rating Curve= 0 ,0
Exp/Cntr=0.3,0.1

Type RM Length L Ch R = 1 ,25290   ,548,548,548
BEGIN DESCRIPTION:
NOTT BRANCH 56.0
END DESCRIPTION:
XS GIS Cut Line= 4
      2647768.26     10036465.21      2648226.58     10036083.28
      2648330.74     10035770.78      2648150.19     10035131.91
#Sta/Elev= 30
  4239.6 2070.84  4297.5 2068.89  4404.3 2064.03  4482.4 2062.17  4558.1 2061.26
  4708.9 2059.82  4745.3 2058.07  4834.2 2050.23  4862.8 2049.54  4877.9 2049.36
  4909.5  2047.6  4941.1 2043.74    4965 2042.65  4972.8 2042.35  4990.8 2040.08
  4993.6 2039.58  4996.8 2040.08  5018.1 2041.22    5036 2044.66  5044.5 2046.51
  5049.8  2046.7  5057.1 2048.47  5069.8 2050.35  5088.7 2052.78  5107.7 2054.43
  5173.9 2055.65  5255.4 2057.42  5422.3 2061.31  5765.3  2065.8  5829.5 2067.91
#Mann= 9 ,-1 , 0
  4239.6      .1       0  4558.1     .05       0  4862.8      .1       0
    4965     .05       0  4990.8    .035       0  4996.8     .05       0
  5069.8      .1       0  5173.9     .05       0  5255.4      .1       0
Bank Sta=4941.1,5036
XS Rating Curve= 0 ,0
Exp/Cntr=0.3,0.1

Type RM Length L Ch R = 1 ,24742   ,333,333,333
BEGIN DESCRIPTION:
NOTT BRANCH 55.0
END DESCRIPTION:
XS GIS Cut Line= 3
      2647941.89     10036645.76      2648941.86      10036055.5
      2649774.29     10035889.01
#Sta/Elev= 30
  4056.3 2067.33  4067.4 2067.05  4224.1 2062.99  4331.2 2061.62  4444.7 2060.41
  4602.6 2058.42  4741.1 2052.02  4771.1 2049.63  4836.7 2042.01  4873.8 2039.56
  4895.3  2038.4  4938.2 2039.82  4975.3 2038.03  4981.3 2035.17  4990.9 2032.59
  5001.5 2032.03  5004.3 2031.53  5007.5 2032.03  5027.7 2034.45  5039.6 2034.23
  5076.7 2037.35  5085.8 2040.67  5092.4 2043.59  5113.8 2043.85  5150.9 2048.85
    5188 2051.48  5397.6 2059.14  5601.5 2068.75  5785.1 2075.17  6066.4 2090.65
#Mann= 7 ,-1 , 0
  4056.3      .1       0  4067.4     .05       0  4331.2      .1       0
  4444.7     .05       0  4771.1      .1       0  5001.5     .07       0
  5007.5      .1       0
Bank Sta=4938.2,5085.8
XS Rating Curve= 0 ,0
Exp/Cntr=0.3,0.1

Type RM Length L Ch R = 1 ,24409   ,437,437,437
BEGIN DESCRIPTION:
NOTT BRANCH 54.0
END DESCRIPTION:
XS GIS Cut Line= 4
      2648018.23     10036874.96      2648608.52     10036506.89
       2649073.8     10036458.28      2649753.87       10036146.
#Sta/Elev= 30
  4093.7 2067.88    4226 2064.48  4298.7 2061.58  4432.9 2061.93  4560.6 2060.72
  4654.9 2057.06  4711.5 2054.25  4753.9 2049.54  4784.6 2047.38  4791.8 2047.73
  4809.4 2045.68  4849.6 2045.49  4909.9 2042.02  4930.1 2038.11  4950.2  2034.2
  4995.4 2032.53  5007.5 2032.28  5010.2 2031.78  5013.5 2032.28  5050.7 2034.94
  5080.9 2035.43  5121.1 2038.02  5161.4 2041.33    5257    2046  5330.9 2048.38
  5399.8 2053.06  5537.4  2058.1  5746.5 2070.22  5927.5 2077.68  6005.5 2083.06
#Mann= 9 ,-1 , 0
  4093.7      .1       0    4226     .05       0  4298.7      .1       0
  4432.9     .05       0  4560.6      .1       0  4654.9     .05       0
  4995.4      .1       0  5007.5     .07       0  5013.5      .1       0
Bank Sta=4930.1,5121.1
XS Rating Curve= 0 ,0
Exp/Cntr=0.3,0.1

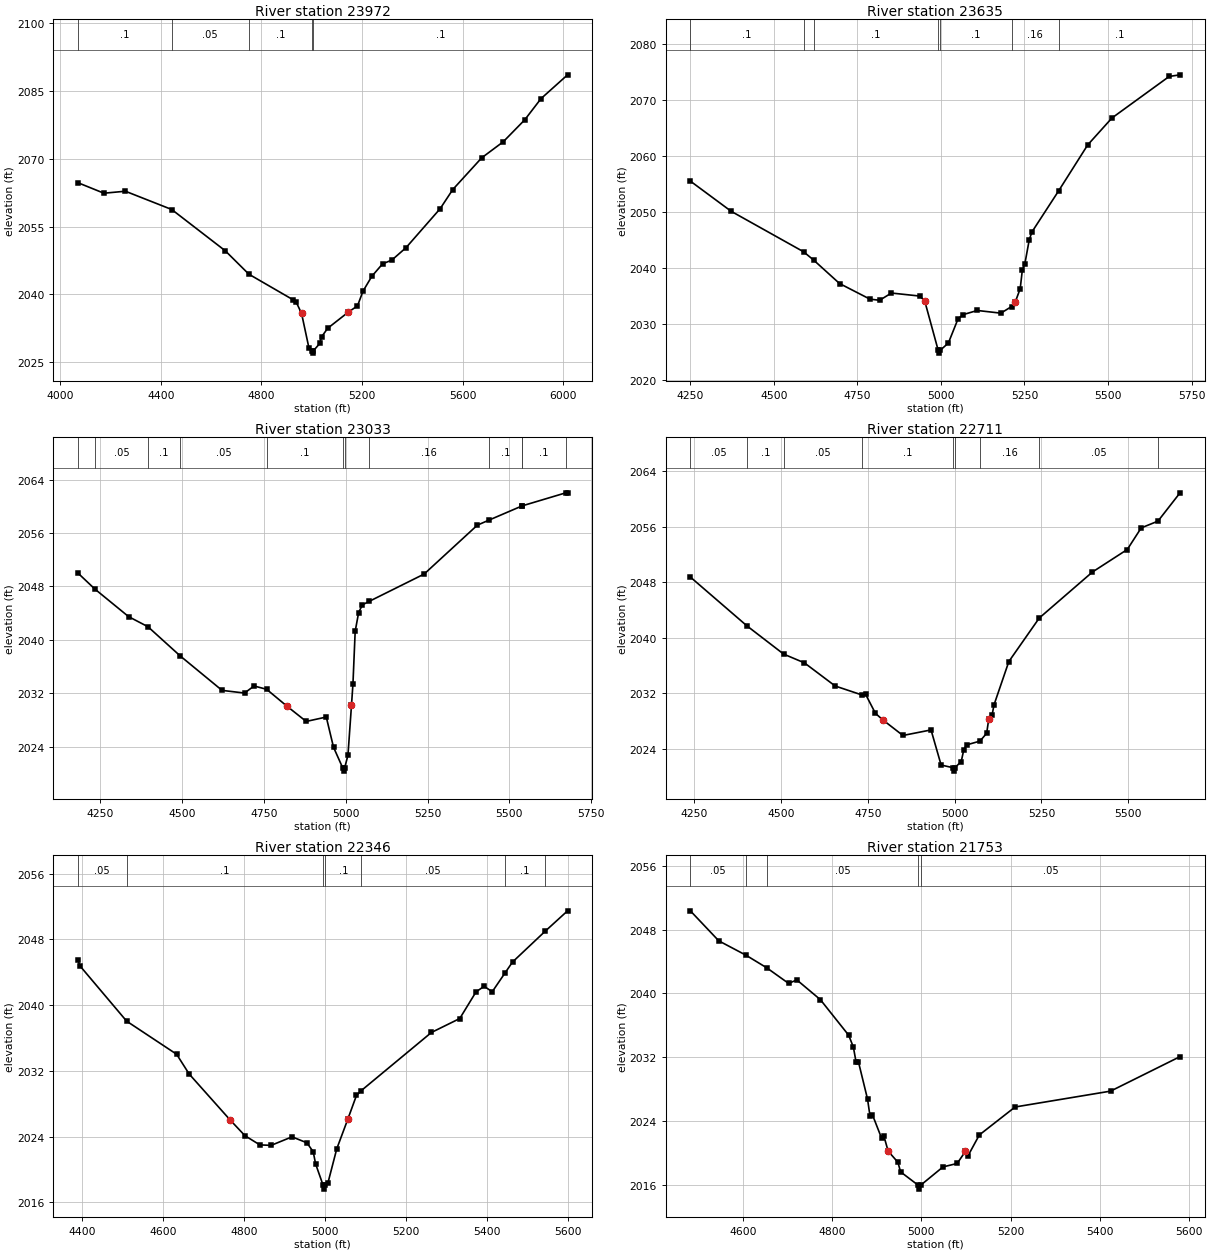
Type RM Length L Ch R = 1 ,23972   ,337,337,337
BEGIN DESCRIPTION:
NOTT BRANCH 53.0
END DESCRIPTION:
XS GIS Cut Line= 3
      2648177.95     10037159.67      2648914.08     10036937.45
      2649858.49     10036236.08
#Sta/Elev= 30
    4071 2064.72  4174.4 2062.39  4259.6 2062.83  4443.8 2058.78  4656.5 2049.63
  4750.2 2044.45    4924 2038.84  4938.6 2038.21  4959.5 2035.76  4988.7 2028.14
  5000.3 2027.46  5003.1 2026.96  5006.3 2027.46  5032.2 2029.13  5038.8 2030.55
  5063.4 2032.47  5145.1 2036.04  5181.7 2037.43  5203.6 2040.69    5239 2044.01
  5281.4 2046.74  5318.3 2047.58  5374.6 2050.33  5510.2 2058.97  5560.3 2063.21
  5675.1 2070.23  5760.6 2073.78  5846.1 2078.65  5910.8 2083.35  6016.3 2088.62
#Mann= 5 ,-1 , 0
    4071      .1       0  4443.8     .05       0  4750.2      .1       0
  5000.3     .07       0  5006.3      .1       0
Bank Sta=4959.5,5145.1
XS Rating Curve= 0 ,0
Exp/Cntr=0.3,0.1

Type RM Length L Ch R = 1 ,23635   ,602,602,602
BEGIN DESCRIPTION:
NOTT BRANCH 52.0
END DESCRIPTION:
XS GIS Cut Line= 4
      2648587.72      10037143.7      2649094.63     10037223.56
      2649570.33     10036852.03      2649879.34     10036692.31
#Sta/Elev= 30
  4250.7 2055.53  4372.9 2050.14  4589.4 2042.92  4619.1 2041.46  4696.9 2037.26
  4787.9 2034.47  4816.8 2034.27  4852.1 2035.56  4937.1 2035.02  4951.6 2034.16
    4992 2025.34  4994.7 2024.84    4998 2025.34  5022.5 2026.65  5051.1 2030.92
  5065.5 2031.69  5108.9 2032.45  5179.5 2031.97  5211.4 2033.15  5222.9 2034.02
  5237.3 2036.35  5243.7  2039.7  5250.9 2040.69  5264.5 2045.11  5272.6 2046.48
    5352 2053.77  5439.2 2061.99  5511.7 2066.79  5682.9  2074.2  5715.3 2074.49
#Mann= 7 ,-1 , 0
  4250.7      .1       0  4589.4     .05       0  4619.1      .1       0
    4992     .07       0    4998      .1       0  5211.4     .16       0
    5352      .1       0
Bank Sta=4951.6,5222.9
XS Rating Curve= 0 ,0
Exp/Cntr=0.3,0.1

Type RM Length L Ch R = 1 ,23033   ,322,322,322
BEGIN DESCRIPTION:
NOTT BRANCH 51.0
END DESCRIPTION:
XS GIS Cut Line= 4
      2648664.11     10037348.56      2649070.33     10037386.75
      2649525.19     10037598.56      2649973.13     10037220.07
#Sta/Elev= 30
  4181.7    2050  4233.6  2047.6  4336.7 2043.47  4395.8 2041.96  4494.5 2037.58
  4622.2 2032.43  4690.8 2032.03    4720 2033.09  4758.4 2032.59  4819.3 2030.11
  4879.3 2027.78  4940.6 2028.44  4962.7 2023.92  4990.7 2020.84  4993.5 2020.34
  4996.7 2020.84  5006.8  2022.7 5017.61  2030.2  5022.1 2033.39  5028.9 2041.27
  5039.5 2044.09    5051 2045.24  5072.2 2045.77  5239.7 2049.85  5402.2 2057.17
  5436.6  2057.9  5538.3 2060.04  5538.6 2060.05  5672.4 2062.01  5677.9 2062.01
#Mann= 12 ,-1 , 0
  4181.7      .1       0  4233.6     .05       0  4395.8      .1       0
  4494.5     .05       0  4758.4      .1       0  4990.7     .07       0
  4996.7      .1       0  5072.2     .16       0  5436.6      .1       0
  5538.3     .16       0  5538.6      .1       0  5672.4     .16       0
Bank Sta=4819.3,5017.61
XS Rating Curve= 0 ,0
Exp/Cntr=0.3,0.1

Type RM Length L Ch R = 1 ,22711   ,365,365,365
BEGIN DESCRIPTION:
NOTT BRANCH 50.0
END DESCRIPTION:
XS GIS Cut Line= 3
      2648639.74     10037438.82      2649480.05     10037959.67
      2649900.16     10037977.03
#Sta/Elev= 30
  4239.6 2048.72  4402.7 2041.67  4508.1 2037.61  4567.8 2036.35  4656.4 2033.01
  4733.5 2031.72    4744  2031.8  4772.2 2029.07  4793.4 2028.13  4851.3 2025.88
  4932.2 2026.68  4961.2 2021.62  4994.8 2021.24  4997.6 2020.74  5000.8 2021.24
  5019.1 2022.12  5026.4 2023.82  5034.4 2024.52  5073.1 2025.07  5092.3  2026.2
  5098.2 2028.23  5107.7  2028.8  5113.6 2030.32  5156.1 2036.54  5243.6 2042.81
  5396.8 2049.45  5496.9 2052.69  5536.9  2055.8  5585.2 2056.78  5648.7 2060.86
#Mann= 9 ,-1 , 0
  4239.6     .05       0  4402.7      .1       0  4508.1     .05       0
  4733.5      .1       0  4994.8     .07       0  5000.8      .1       0
  5073.1     .16       0  5243.6     .05       0  5585.2      .1       0
Bank Sta=4793.4,5098.2
XS Rating Curve= 0 ,0
Exp/Cntr=0.3,0.1

Type RM Length L Ch R = 1 ,22346   ,593,593,593
BEGIN DESCRIPTION:
NOTT BRANCH 49.0
END DESCRIPTION:
XS GIS Cut Line= 3
      2648591.13     10037834.65      2649264.77     10038244.39
      2649684.19     10038223.59
#Sta/Elev= 30
    4390 2045.46  4395.3 2044.77  4510.3 2038.05  4633.6 2034.02  4664.6 2031.61
  4765.4 2026.03  4802.2  2024.1    4839 2022.98  4866.8 2022.92  4918.4 2023.96
  4955.2 2023.23  4970.7 2022.14  4976.6 2020.66  4994.9 2018.09  4997.6 2017.59
  5000.9 2018.09  5007.2 2018.38  5028.8  2022.5    5056  2026.1  5077.4    2029
  5088.8 2029.57  5262.3 2036.67  5332.3 2038.37  5372.4 2041.61  5392.4  2042.3
  5412.4 2041.63    5444 2043.92  5462.5 2045.25    5543    2049  5598.4 2051.49
#Mann= 7 ,-1 , 0
    4390     .05       0  4510.3      .1       0  4994.9     .07       0
  5000.9      .1       0  5088.8     .05       0    5444      .1       0
    5543     .16       0
Bank Sta=4765.4,5056
XS Rating Curve= 0 ,0
Exp/Cntr=0.3,0.1

Type RM Length L Ch R = 1 ,21753   ,88,88,88
BEGIN DESCRIPTION:
NOTT BRANCH 48.0
END DESCRIPTION:
XS GIS Cut Line= 3
      2648262.64     10038769.26      2648902.81     10038550.08
      2649237.03     10038293.99
#Sta/Elev= 30
  4482.3 2050.37  4546.1  2046.6  4606.7 2044.81  4653.5 2043.22  4702.6 2041.26
    4721  2041.7  4773.8 2039.22  4837.3 2034.75  4847.8 2033.25  4853.8 2031.38
    4859 2031.44  4879.5 2026.74    4885 2024.62  4890.3  2024.8    4911 2021.83
  4916.3 2022.07 4925.68 2020.21  4947.6 2018.81  4953.5 2017.61  4992.8 2015.94
  4995.6 2015.44  4998.8 2015.94  5048.7 2018.23  5080.4 2018.66  5098.8 2020.17
  5104.1 2019.56  5130.1 2022.24  5210.3 2025.75  5424.3 2027.74    5580 2032.07
#Mann= 5 ,-1 , 0
  4482.3     .05       0  4606.7      .1       0  4653.5     .05       0
  4992.8     .04       0  4998.8     .05       0
Bank Sta=4925.68,5098.8
XS Rating Curve= 0 ,0
Exp/Cntr=0.3,0.1

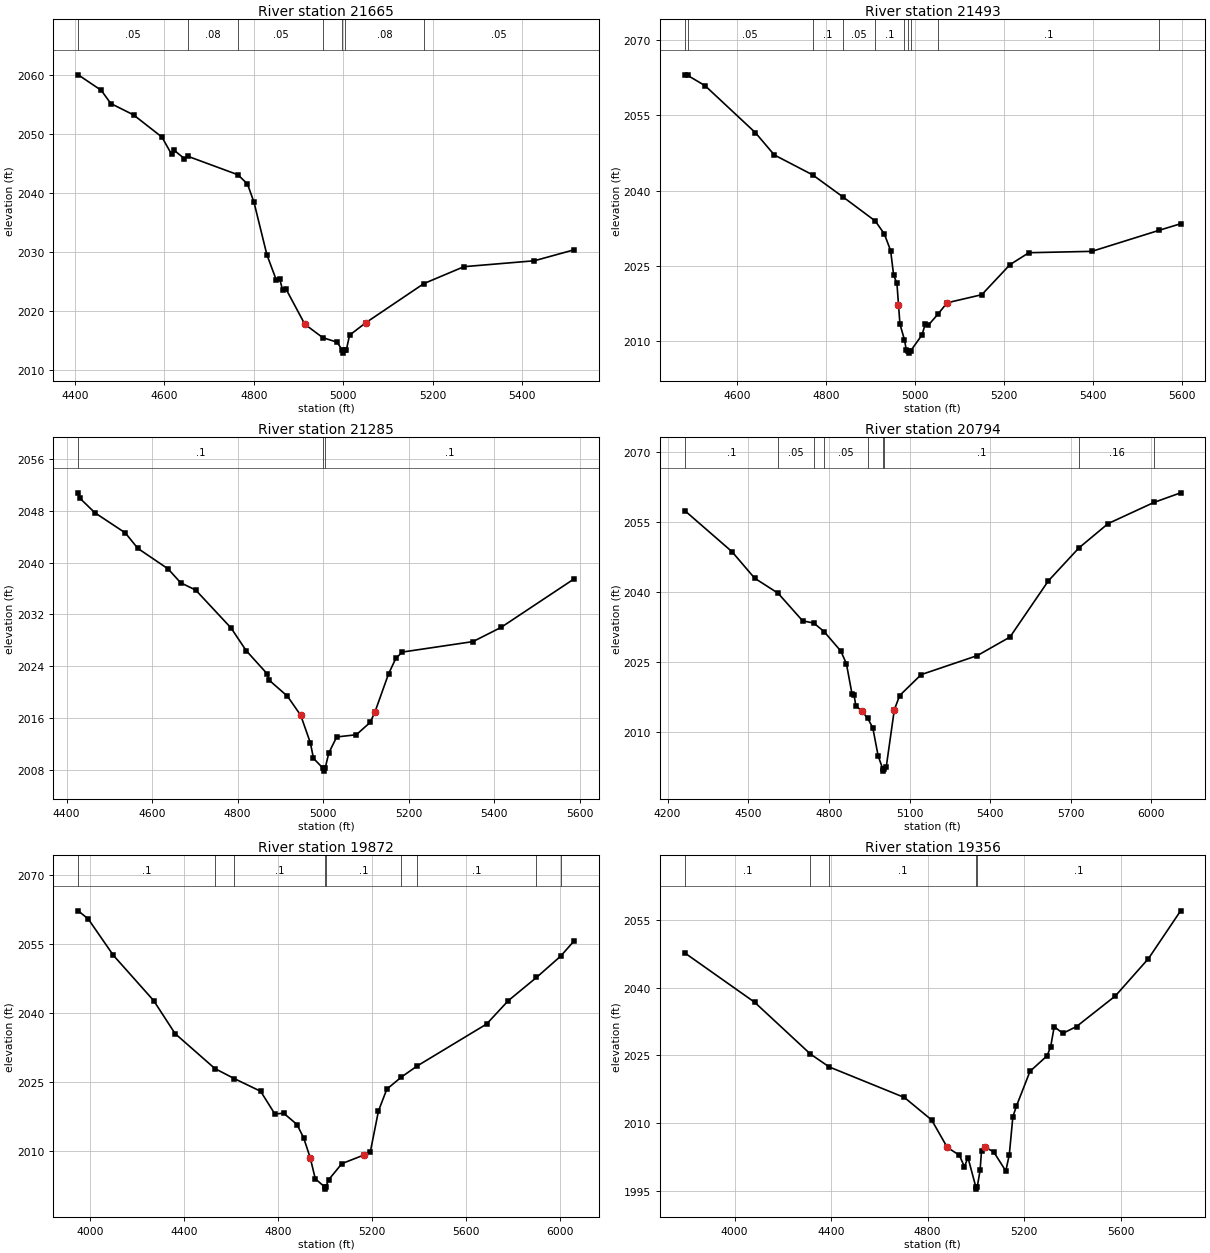
Type RM Length L Ch R = 1 ,21665   ,172,172,172
BEGIN DESCRIPTION:
Mapping XS 0fdf3757
END DESCRIPTION:
XS GIS Cut Line= 2
      2648321.19     10039049.23      2649193.54      10038363.5
#Sta/Elev= 30
    4407 2059.96  4458.6 2057.33  4479.9  2055.1  4530.7 2053.18  4594.3 2049.42
  4615.8 2046.52  4622.1 2047.15  4644.7 2045.76  4652.2 2046.17  4764.2 2043.04
  4785.7 2041.47  4800.2  2038.4  4829.1  2029.5  4849.9 2025.27    4858 2025.32
  4864.3 2023.53  4872.4 2023.61  4914.1 2017.71  4954.2 2015.45  4986.3 2014.68
  4997.8 2013.33  5000.5 2012.83  5003.8 2013.33  5007.1 2013.44  5014.1 2015.87
  5050.5 2017.98  5180.2  2024.6  5270.1 2027.47  5427.4 2028.47  5516.6 2030.33
#Mann= 7 ,-1 , 0
    4407     .05       0  4652.2     .08       0  4764.2     .05       0
  4954.2     .08       0  4997.8     .07       0  5003.8     .08       0
  5180.2     .05       0
Bank Sta=4914.1,5050.5
XS Rating Curve= 0 ,0
Exp/Cntr=0.3,0.1

Type RM Length L Ch R = 1 ,21493   ,208,208,208
BEGIN DESCRIPTION:
Mapping XS a8da2961
END DESCRIPTION:
XS GIS Cut Line= 2
      2648497.01     10039177.23      2649312.95     10038415.55
#Sta/Elev= 30
  4481.3  2063.1  4487.9 2062.99  4527.1 2060.94  4640.5 2051.55    4683 2047.11
  4769.4 2043.13  4838.2 2038.69  4910.2 2033.93  4930.6 2031.36  4944.8 2028.02
  4951.6 2023.11    4959  2021.5  4962.5 2017.26  4965.8 2013.35  4975.9 2010.24
    4980 2008.24  4984.3 2008.06  4987.1 2007.56  4990.3 2008.06  5015.6 2011.21
  5022.5 2013.33  5029.8 2013.15  5050.9 2015.29  5071.8  2017.6    5150 2019.22
  5213.5 2025.22    5256  2027.6  5397.7 2027.87  5549.1 2032.07  5597.5 2033.38
#Mann= 10 ,-1 , 0
  4481.3     .08       0  4487.9     .05       0  4769.4      .1       0
  4838.2     .05       0  4910.2      .1       0  4975.9     .05       0
  4984.3    .035       0  4990.3     .05       0  5050.9      .1       0
  5549.1     .05       0
Bank Sta=4962.5,5071.8
XS Rating Curve= 0 ,0
Exp/Cntr=0.3,0.1

Type RM Length L Ch R = 1 ,21285   ,491,491,491
BEGIN DESCRIPTION:
NOTT BRANCH 47.0
END DESCRIPTION:
XS GIS Cut Line= 4
      2648722.69     10039322.64      2648978.76     10039131.68
      2649158.88     10038671.61       2649462.7     10038506.68
#Sta/Elev= 30
  4427.3 2050.77  4431.1 2049.94  4466.5 2047.68  4537.4 2044.58  4566.6 2042.19
  4637.4 2039.02  4666.7 2036.88  4702.1 2035.74  4784.6 2029.89  4819.8  2026.4
  4868.7 2022.83  4874.1  2021.8  4916.4 2019.35  4947.4  2016.4    4970 2012.13
  4977.2 2009.76  4998.7 2008.28  5001.5 2007.78  5004.7 2008.28    5013 2010.58
  5031.5 2013.06  5077.4  2013.4  5109.7 2015.31    5121 2016.94  5152.6 2022.79
  5169.9 2025.23  5184.8 2026.17    5350 2027.79  5415.6 2029.98  5586.5 2037.48
#Mann= 3 ,-1 , 0
  4427.3      .1       0  4998.7     .07       0  5004.7      .1       0
Bank Sta=4947.4,5121
XS Rating Curve= 0 ,0
Exp/Cntr=0.3,0.1

Type RM Length L Ch R = 1 ,20794   ,922,922,922
BEGIN DESCRIPTION:
NOTT BRANCH 46.0
END DESCRIPTION:
XS GIS Cut Line= 4
      2648789.06     10039751.36      2649214.42     10039239.18
      2649466.16     10039239.18      2650221.39     10038700.98
#Sta/Elev= 30
  4263.6 2057.51  4439.3 2048.69    4524 2042.97  4610.8 2039.76  4702.4 2033.81
  4743.8 2033.34  4781.9 2031.52  4844.3 2027.33  4865.1 2024.63  4885.9 2018.16
  4893.8 2017.83  4900.3 2015.57  4922.4 2014.44  4944.7 2012.84  4963.4 2010.83
  4983.4 2004.76  5000.4 2002.02  5003.2 2001.52  5006.4 2002.02  5013.4  2002.4
  5043.4 2014.69  5063.4 2017.77  5143.4 2022.26    5352 2026.34  5473.7 2030.33
  5616.3 2042.39  5730.1 2049.48  5838.8 2054.71  6009.4 2059.26  6108.5 2061.32
#Mann= 9 ,-1 , 0
  4263.6      .1       0  4610.8     .05       0  4743.8      .1       0
  4781.9     .05       0  4944.7      .1       0  5000.4     .07       0
  5006.4      .1       0  5730.1     .16       0  6009.4      .1       0
Bank Sta=4922.4,5043.4
XS Rating Curve= 0 ,0
Exp/Cntr=0.3,0.1

Type RM Length L Ch R = 1 ,19872   ,516,516,516
BEGIN DESCRIPTION:
NOTT BRANCH 44.0
END DESCRIPTION:
XS GIS Cut Line= 4
       2648910.6      10040124.6      2649769.98     10040003.07
      2650473.11     10039317.31       2650724.2      10039256.7
#Sta/Elev= 30
  3950.6 2062.17  3993.2  2060.4  4099.9 2052.51  4271.6 2042.65  4362.5 2035.49
  4531.6  2027.9  4613.6 2025.73  4726.1 2022.96  4786.7 2018.02  4824.1  2018.2
  4880.7 2015.74  4908.9 2012.85  4937.2 2008.47  4958.4 2003.95  4997.8  2002.2
  5000.6  2001.7  5003.8  2002.2  5014.9 2003.71  5071.5 2007.24  5163.6 2009.08
  5191.9 2009.66  5227.1 2018.69  5262.6 2023.42  5324.7 2026.06  5392.6 2028.49
  5686.8 2037.57  5778.8 2042.64  5898.8 2047.69  6001.4 2052.31    6059 2055.64
#Mann= 9 ,-1 , 0
  3950.6      .1       0  4531.6     .16       0  4613.6      .1       0
  4997.8     .07       0  5003.8      .1       0  5324.7     .16       0
  5392.6      .1       0  5898.8     .16       0  6001.4      .1       0
Bank Sta=4937.2,5163.6
XS Rating Curve= 0 ,0
Exp/Cntr=0.3,0.1

Type RM Length L Ch R = 1 ,19356   ,570,570,570
BEGIN DESCRIPTION:
NOTT BRANCH 43.0
END DESCRIPTION:
XS GIS Cut Line= 4
      2649118.96     10040445.78      2650047.76      10040393.7
      2650690.12     10039924.95      2651011.29     10039846.82
#Sta/Elev= 30
  3792.8 2047.72  4082.8 2036.77  4314.2 2025.28  4392.2 2022.42  4703.7 2015.65
  4816.5 2010.67  4881.4 2004.59  4931.6 2002.85  4952.5 2000.28  4967.2 2002.34
  4999.7 1995.83  5002.4 1995.33  5005.7 1995.83  5017.4 1999.48  5023.5 2003.89
  5038.2 2004.62  5073.8  2003.6    5124 1999.35  5138.6 2002.97  5153.3 2011.36
    5168 2013.73  5224.4 2021.45  5295.4  2024.9  5310.1 2026.91  5324.8 2031.36
  5360.3 2029.87  5417.2 2031.38  5578.3 2038.17  5715.5 2046.45  5848.8 2057.04
#Mann= 5 ,-1 , 0
  3792.8      .1       0  4314.2     .16       0  4392.2      .1       0
  4999.7     .07       0  5005.7      .1       0
Bank Sta=4881.4,5038.2
XS Rating Curve= 0 ,0
Exp/Cntr=0.3,0.1

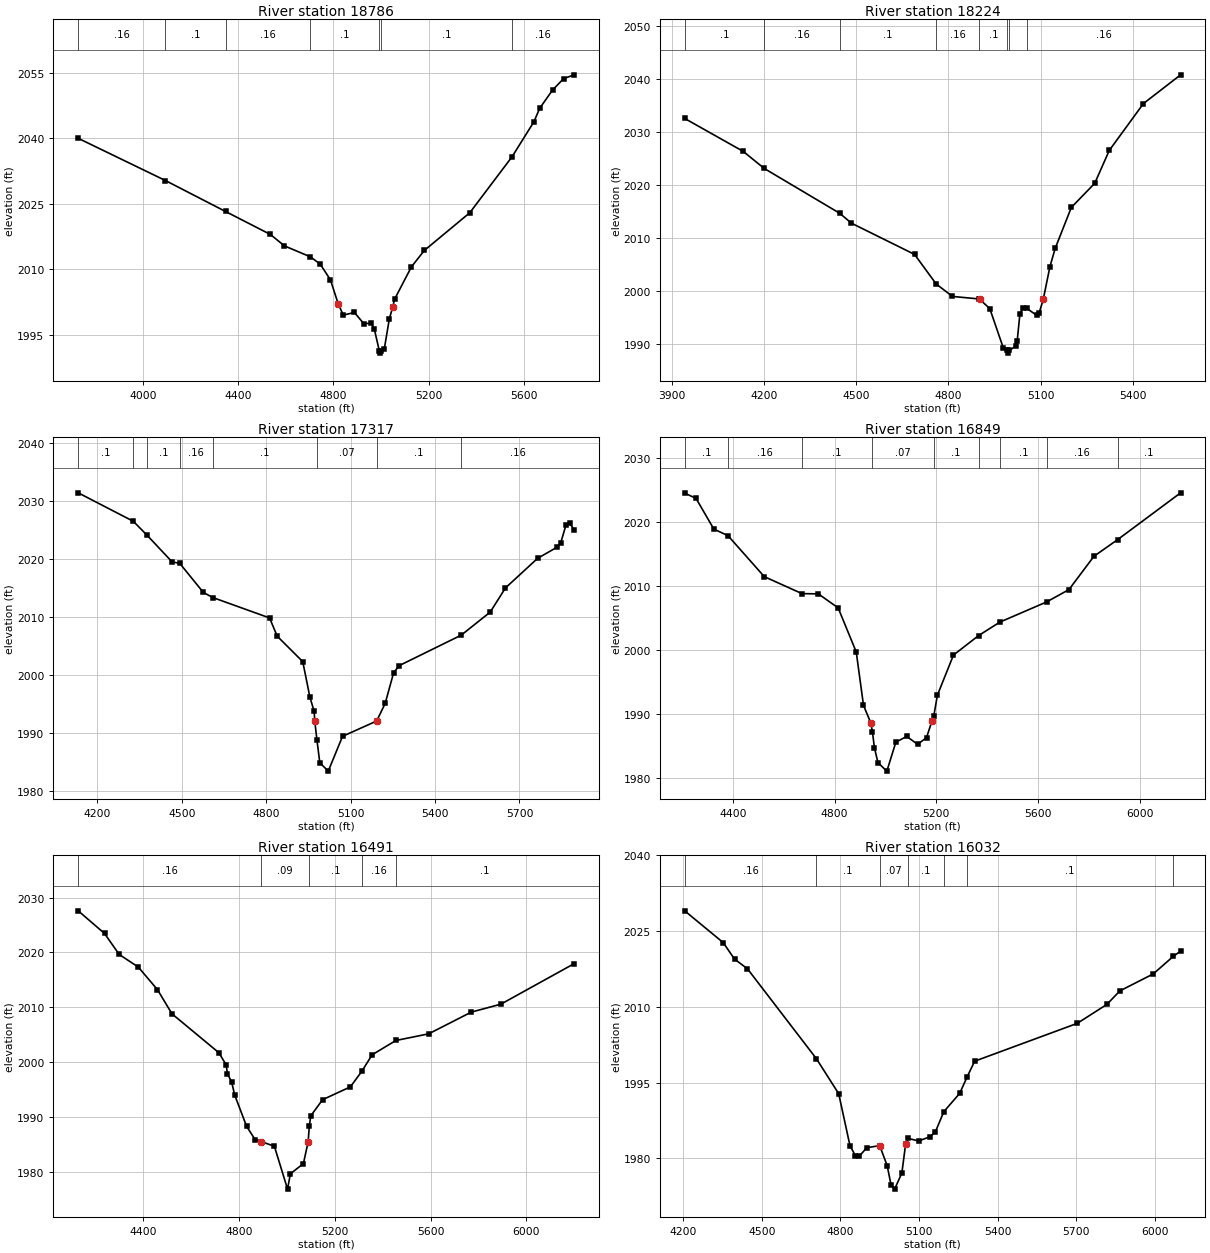
Type RM Length L Ch R = 1 ,18786   ,562,562,562
BEGIN DESCRIPTION:
NOTT BRANCH 42.0
END DESCRIPTION:
XS GIS Cut Line= 2
      2649283.91     10041218.33      2651219.64     10040445.78
#Sta/Elev= 30
  3727.8 2040.01  4094.2 2030.34  4346.8 2023.25  4535.5 2017.98  4594.7 2015.36
  4703.4 2012.86  4744.8 2011.19  4787.9 2007.58  4820.2 2002.12  4841.7 1999.51
  4888.5 2000.11  4927.8 1997.56  4960.1 1997.64    4972 1996.35  4993.3  1991.3
    4996  1990.8  4999.3  1991.3    5014 1991.72  5035.5 1998.72  5050.2 2001.45
  5057.1 2003.12  5128.3 2010.58  5182.2 2014.31  5373.5 2022.96  5551.4 2035.81
    5643 2043.81  5667.3 2046.89  5721.2 2051.06  5767.7 2053.68    5812 2054.55
#Mann= 7 ,-1 , 0
  3727.8     .16       0  4094.2      .1       0  4346.8     .16       0
  4703.4      .1       0  4993.3     .07       0  4999.3      .1       0
  5551.4     .16       0
Bank Sta=4820.2,5050.2
XS Rating Curve= 0 ,0
Exp/Cntr=0.3,0.1

Type RM Length L Ch R = 1 ,18224   ,907,907,907
BEGIN DESCRIPTION:
NOTT BRANCH 40.0
END DESCRIPTION:
XS GIS Cut Line= 2
      2649735.24     10041652.38      2651219.64      10041018.7
#Sta/Elev= 30
  3941.9 2032.59  4132.6 2026.36  4200.6 2023.15  4446.1 2014.69  4484.8  2012.8
    4690 2006.91  4760.5 2001.31  4813.5 1998.97  4900.4 1998.49  4902.2 1998.41
  4934.9 1996.67  4978.4 1989.31  4992.1 1988.76  4994.8 1988.26  4998.1 1988.76
  5018.7 1989.56  5024.1 1990.57  5032.7 1995.57  5042.3 1996.79    5055 1996.72
  5087.1 1995.42  5094.9 1995.75  5108.8  1998.4  5130.6  2004.6  5147.6 2008.03
  5200.2 2015.78  5276.5 2020.35  5323.7 2026.55    5435 2035.41  5555.9 2040.83
#Mann= 8 ,-1 , 0
  3941.9      .1       0  4200.6     .16       0  4446.1      .1       0
  4760.5     .16       0  4900.4      .1       0  4992.1     .07       0
  4998.1      .1       0    5055     .16       0
Bank Sta=4902.2,5108.8
XS Rating Curve= 0 ,0
Exp/Cntr=0.3,0.1

Type RM Length L Ch R = 1 ,17317   ,468,468,468
BEGIN DESCRIPTION:
NOTT BRANCH 38.0
END DESCRIPTION:
XS GIS Cut Line= 3
      2649848.11     10042181.89      2651037.34     10042016.96
      2651253.38     10041498.48
#Sta/Elev= 30
  4132.1 2031.39  4327.9 2026.49  4376.2 2024.12  4465.6 2019.51    4493 2019.25
  4576.7 2014.25  4610.5 2013.37  4812.1 2009.86  4839.2 2006.72    4930 2002.34
  4955.5 1996.21  4970.4 1993.81 4972.73 1992.09  4980.5 1988.82  4990.6 1984.94
  5020.6  1983.5  5071.4 1989.49  5192.5 1992.12  5222.8 1995.14  5253.1 2000.46
  5273.3 2001.67  5493.2  2006.9  5596.2 2010.87  5650.4 2015.03  5764.4 2020.11
  5834.5 2022.06  5846.7 2022.79  5865.1 2025.81  5877.9 2026.23  5894.4 2025.01
#Mann= 8 ,-1 , 0
  4132.1      .1       0  4327.9     .16       0  4376.2      .1       0
    4493     .16       0  4610.5      .1       0  4980.5     .07       0
  5192.5      .1       0  5493.2     .16       0
Bank Sta=4972.73,5192.5
XS Rating Curve= 0 ,0
Exp/Cntr=0.3,0.1

Type RM Length L Ch R = 1 ,16849   ,358,358,358
BEGIN DESCRIPTION:
NOTT BRANCH 37.0
END DESCRIPTION:
XS GIS Cut Line= 3
      2650342.87     10042980.53      2651132.83     10042294.74
      2651358.44     10041418.32
#Sta/Elev= 30
  4210.5 2024.49    4255 2023.68  4325.2 2018.88  4380.9 2017.85  4523.7 2011.45
  4671.9  2008.8  4736.4 2008.76  4814.3 2006.57  4885.5 1999.68    4914 1991.35
  4942.5 1988.63  4949.2 1987.24  4956.8 1984.75    4971 1982.39  5005.9 1981.08
  5041.3  1985.6    5084  1986.5  5126.8 1985.27  5161.9  1986.3  5183.8 1988.97
  5190.4 1989.65  5204.6 1992.93    5268 1999.21  5366.9 2002.25  5450.4 2004.35
  5634.9 2007.51  5722.3 2009.43  5820.6 2014.63  5914.1 2017.24  6161.6 2024.54
#Mann= 9 ,-1 , 0
  4210.5      .1       0  4380.9     .16       0  4671.9      .1       0
  4949.2     .07       0  5190.4      .1       0  5366.9     .16       0
  5450.4      .1       0  5634.9     .16       0  5914.1      .1       0
Bank Sta=4942.5,5183.8
XS Rating Curve= 0 ,0
Exp/Cntr=0.3,0.1

Type RM Length L Ch R = 1 ,16491   ,459,459,459
BEGIN DESCRIPTION:
NOTT BRANCH 36.0
END DESCRIPTION:
XS GIS Cut Line= 3
       2650915.8     10043484.02      2651427.97     10042112.45
      2651479.88     10041506.75
#Sta/Elev= 30
  4127.6 2027.58  4237.6 2023.45  4298.7 2019.63  4378.5 2017.33  4458.7 2013.21
  4519.3  2008.8    4715 2001.72  4745.8 1999.49  4751.1 1997.84  4768.4 1996.42
  4781.4 1993.99  4831.3 1988.27    4867 1985.85  4891.9 1985.52  4947.2 1984.65
  5002.2 1976.84  5013.9 1979.63  5068.4 1981.49  5088.1 1985.43  5093.4 1988.43
  5099.3 1990.21  5148.7 1993.15  5264.6 1995.48  5312.3 1998.31  5355.5 2001.33
  5454.7 2003.94  5591.7 2005.15  5769.6 2009.11  5893.4 2010.56  6199.6 2017.95
#Mann= 5 ,-1 , 0
  4127.6     .16       0  4891.9     .09       0  5093.4      .1       0
  5312.3     .16       0  5454.7      .1       0
Bank Sta=4891.9,5088.1
XS Rating Curve= 0 ,0
Exp/Cntr=0.3,0.1

Type RM Length L Ch R = 1 ,16032   ,446,446,446
BEGIN DESCRIPTION:
NOTT BRANCH 35.0
END DESCRIPTION:
XS GIS Cut Line= 2
      2651072.07     10043544.74      2652269.56     10042078.24
#Sta/Elev= 30
  4205.5    2029  4352.6 2022.71  4395.7 2019.45  4445.3 2017.52  4708.7 1999.71
  4793.5  1992.8  4836.5 1982.53  4857.4 1980.52  4871.7 1980.41  4900.4 1982.11
    4950 1982.53  4978.7 1978.54  4993.1  1974.8    5007 1973.92  5034.7 1977.13
    5049 1982.85    5057 1983.98  5098.6 1983.45  5141.7 1984.28  5162.5 1985.24
  5194.8 1989.25  5255.1 1992.85  5283.8 1996.13  5312.5 1999.24  5703.8 2006.72
  5817.3 2010.48  5866.8 2013.15  5994.6 2016.52    6071    2020  6098.8 2021.03
#Mann= 7 ,-1 , 0
  4205.5     .16       0  4708.7      .1       0    4950     .07       0
    5057      .1       0  5194.8     .16       0  5283.8      .1       0
    6071     .16       0
Bank Sta=4950,5049
XS Rating Curve= 0 ,0
Exp/Cntr=0.3,0.1

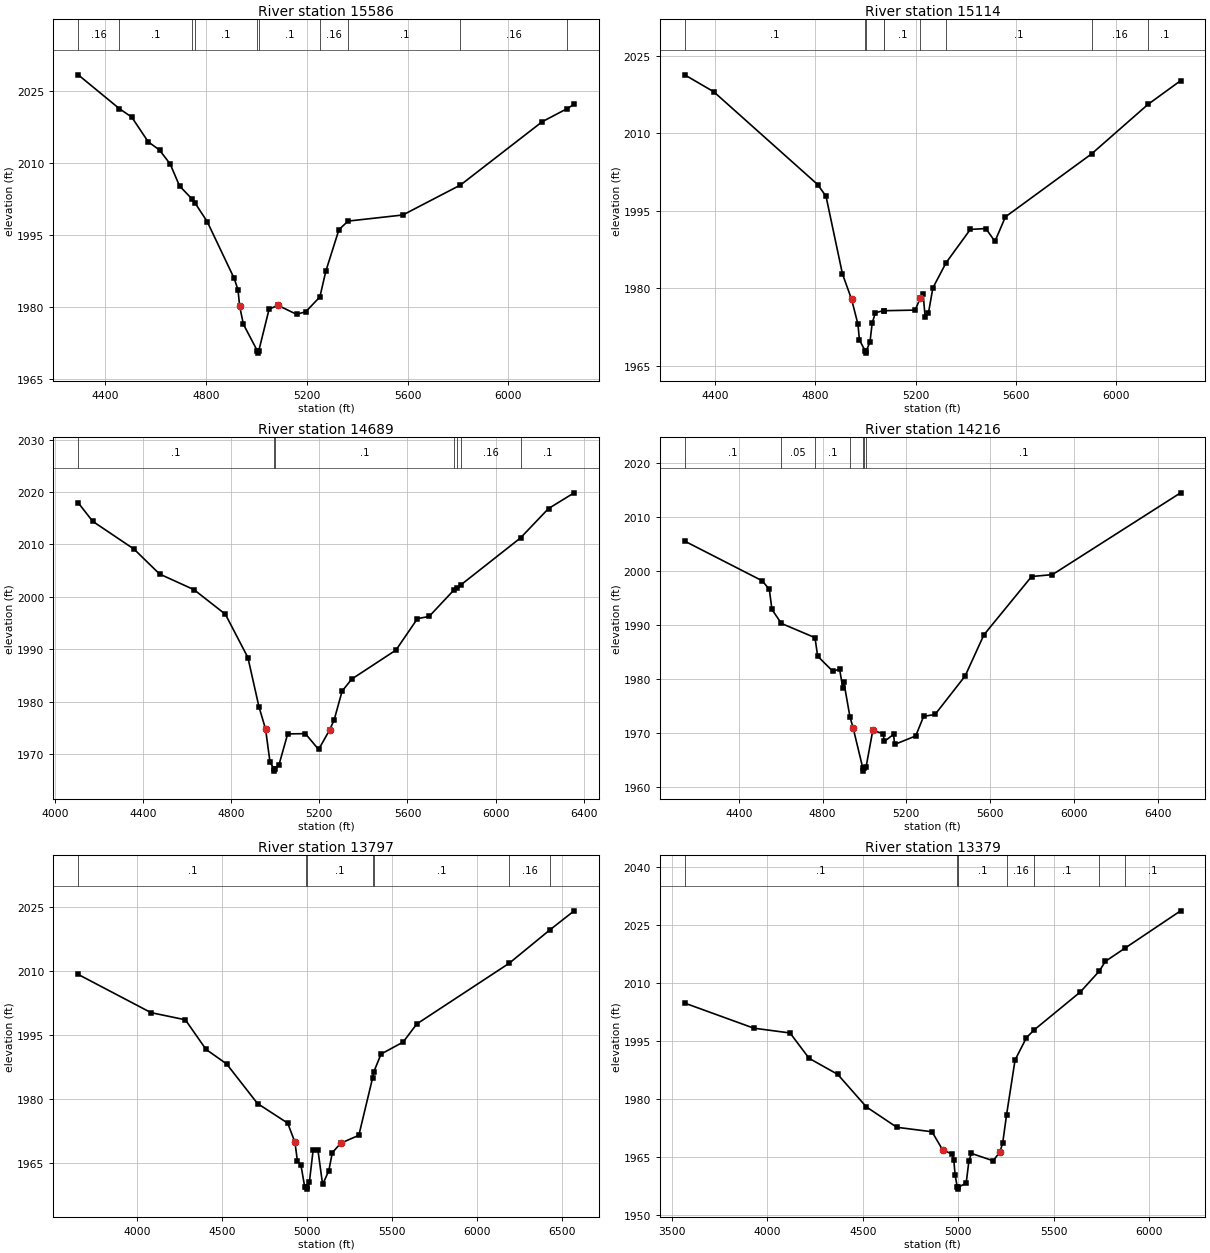
Type RM Length L Ch R = 1 ,15586   ,472,472,472
BEGIN DESCRIPTION:
NOTT BRANCH 34.0
END DESCRIPTION:
XS GIS Cut Line= 3
      2651523.46     10043831.19      2652322.06     10042520.43
      2652513.04      10042129.8
#Sta/Elev= 30
    4292 2028.35  4455.6  2021.3  4504.5 2019.55  4570.1  2014.4  4614.9 2012.69
  4657.5 2009.76  4694.3 2005.22  4742.8 2002.57  4755.4 2001.71  4804.3 1997.79
  4911.3 1985.99  4926.7 1983.57  4933.1 1980.18  4948.1 1976.42  5003.2 1970.91
  5005.9 1970.41  5009.2 1970.91  5050.2 1979.58  5085.6 1980.35  5159.2 1978.49
  5195.9 1979.03  5251.8 1982.11  5275.4 1987.47  5327.6 1996.13    5364  1997.9
  5581.3 1999.17  5810.2 2005.41  6134.9 2018.59  6234.5 2021.33  6261.7 2022.21
#Mann= 10 ,-1 , 0
    4292     .16       0  4455.6      .1       0  4742.8     .16       0
  4755.4      .1       0  5003.2     .07       0  5009.2      .1       0
  5251.8     .16       0    5364      .1       0  5810.2     .16       0
  6234.5      .1       0
Bank Sta=4933.1,5085.6
XS Rating Curve= 0 ,0
Exp/Cntr=0.3,0.1

Type RM Length L Ch R = 1 ,15114   ,425,425,425
BEGIN DESCRIPTION:
NOTT BRANCH 33.0
END DESCRIPTION:
XS GIS Cut Line= 4
      2651809.95     10043917.97       2652261.3     10043579.46
      2652539.08     10042789.53      2652625.72     10042217.69
#Sta/Elev= 30
  4278.4  2021.3  4394.5 2018.02  4809.1 2000.07  4842.6  1997.8  4908.2 1982.78
  4944.5 1977.87  4970.1 1973.04  4975.9    1970  4998.1 1967.93  5000.9 1967.43
  5004.1 1967.93  5018.3 1969.62  5026.8 1973.21  5039.5 1975.23  5072.6 1975.67
  5075.9 1975.64  5198.5 1975.76  5219.2 1978.11  5230.3 1978.86  5238.3 1974.47
  5251.5 1975.18  5269.3 1980.06  5321.9 1984.92  5418.8 1991.38  5480.8 1991.54
    5517 1989.06  5558.9 1993.81  5902.7 2005.99  6128.1 2015.58  6258.3 2020.17
#Mann= 9 ,-1 , 0
  4278.4      .1       0  4998.1     .07       0  5004.1      .1       0
  5072.6     .16       0  5075.9      .1       0  5219.2     .16       0
  5321.9      .1       0  5902.7     .16       0  6128.1      .1       0
Bank Sta=4944.5,5219.2
XS Rating Curve= 0 ,0
Exp/Cntr=0.3,0.1

Type RM Length L Ch R = 1 ,14689   ,473,473,473
BEGIN DESCRIPTION:
NOTT BRANCH 41.0
END DESCRIPTION:
XS GIS Cut Line= 3
      2651966.16     10043926.68      2652695.33     10043700.99
      2652825.44     10042217.68
#Sta/Elev= 30
  4104.8 2017.93  4170.4  2014.4  4358.4 2009.09  4474.4 2004.34  4630.6 2001.36
  4773.1 1996.67  4875.4 1988.42  4925.6 1979.03  4955.7 1974.76  4975.8 1968.47
  4992.8 1967.25  4995.6 1966.75  4998.8 1967.25  5015.9 1967.85  5056.1 1973.85
  5136.4  1973.9  5196.6 1970.88  5246.8 1974.62  5266.9 1976.49  5303.3 1982.01
  5347.2 1984.31    5548 1989.84  5645.6 1995.84  5698.5 1996.25  5809.4 2001.22
  5825.5 2001.65  5843.2 2002.29  6113.5 2011.23  6240.6 2016.83  6357.1 2019.83
#Mann= 7 ,-1 , 0
  4104.8      .1       0  4992.8     .07       0  4998.8      .1       0
  5809.4     .16       0  5825.5      .1       0  5843.2     .16       0
  6113.5      .1       0
Bank Sta=4955.7,5246.8
XS Rating Curve= 0 ,0
Exp/Cntr=0.3,0.1

Type RM Length L Ch R = 1 ,14216   ,419,419,419
BEGIN DESCRIPTION:
NOTT BRANCH 31.0
END DESCRIPTION:
XS GIS Cut Line= 4
      2652417.58     10043978.76      2653129.36     10043779.11
      2653268.24     10043128.07      2653094.64     10042181.91
#Sta/Elev= 30
  4142.2 2005.49  4512.2 1998.15  4546.3 1996.55  4558.6 1992.84  4603.7 1990.26
  4764.1 1987.62  4776.8  1984.2  4850.2 1981.36  4881.4 1981.84  4896.6 1978.36
  4901.7 1979.42  4930.6 1973.03  4946.1 1970.92  4992.7 1963.42  4995.4 1962.92
  4998.7 1963.42  5008.3 1963.75  5040.1 1970.49  5089.6 1969.83  5094.7 1968.41
  5139.1 1969.72  5144.2 1967.86  5244.8 1969.43  5282.6 1973.05  5337.2 1973.41
  5480.7 1980.53  5570.2 1988.14  5797.9 1998.94  5897.2 1999.29  6509.1 2014.43
#Mann= 7 ,-1 , 0
  4142.2      .1       0  4603.7     .05       0  4764.1      .1       0
  4930.6     .05       0  4992.7    .035       0  4998.7     .05       0
  5008.3      .1       0
Bank Sta=4946.1,5040.1
XS Rating Curve= 0 ,0
Exp/Cntr=0.3,0.1

Type RM Length L Ch R = 1 ,13797   ,418,418,418
BEGIN DESCRIPTION:
NOTT BRANCH 30.0
END DESCRIPTION:
XS GIS Cut Line= 4
      2652304.67     10044065.58      2653407.13     10043909.32
      2653771.72     10043483.97      2655013.03     10043431.89
#Sta/Elev= 30
  3655.3 2009.22  4083.3 2000.25  4285.3 1998.57  4406.5 1991.63  4527.7 1988.21
  4709.5 1978.91  4887.1  1974.3  4929.9 1969.78  4944.2 1965.37    4965 1964.43
  4986.9 1959.35  4997.1  1959.3  4999.9  1958.8  5003.1  1959.3  5014.4 1960.39
  5036.4  1967.9  5064.9 1967.97  5092.3  1959.9  5128.6 1963.08  5149.4 1967.36
  5198.8 1969.58  5305.3 1971.44  5385.9 1984.85    5394 1986.39  5435.8 1990.52
    5566 1993.34    5646 1997.59  6188.9 2011.83  6431.1 2019.76  6571.4 2024.16
#Mann= 7 ,-1 , 0
  3655.3      .1       0  4997.1     .07       0  5003.1      .1       0
  5385.9     .16       0    5394      .1       0  6188.9     .16       0
  6431.1      .1       0
Bank Sta=4929.9,5198.8
XS Rating Curve= 0 ,0
Exp/Cntr=0.3,0.1

Type RM Length L Ch R = 1 ,13379   ,451,451,451
BEGIN DESCRIPTION:
NOTT BRANCH 29.0
END DESCRIPTION:
XS GIS Cut Line= 4
      2652506.07     10044146.74      2653656.27     10044146.74
       2654133.7     10043788.66      2654980.08     10043680.15
#Sta/Elev= 30
  3566.1 2004.81  3928.5 1998.32  4118.5 1997.08  4218.5 1990.52  4368.5 1986.37
  4518.5 1977.96  4678.5 1972.68  4862.9 1971.52  4919.1 1966.79  4969.1 1965.75
  4977.5 1964.09  4983.7 1960.44  4995.3 1957.18  4998.1 1956.68  5001.3 1957.18
  5042.1 1958.24  5056.5 1964.01  5069.1 1965.93  5183.7 1964.01  5219.1 1966.32
  5233.7 1968.68  5253.8 1975.91  5298.3 1990.08  5358.2 1995.88  5399.2  1997.9
  5640.5 2007.68  5740.3  2013.1  5771.6  2015.6  5873.2 2018.97  6166.4 2028.68
#Mann= 7 ,-1 , 0
  3566.1      .1       0  4995.3     .07       0  5001.3      .1       0
  5253.8     .16       0  5399.2      .1       0  5740.3     .16       0
  5873.2      .1       0
Bank Sta=4919.1,5219.1
XS Rating Curve= 0 ,0
Exp/Cntr=0.3,0.1