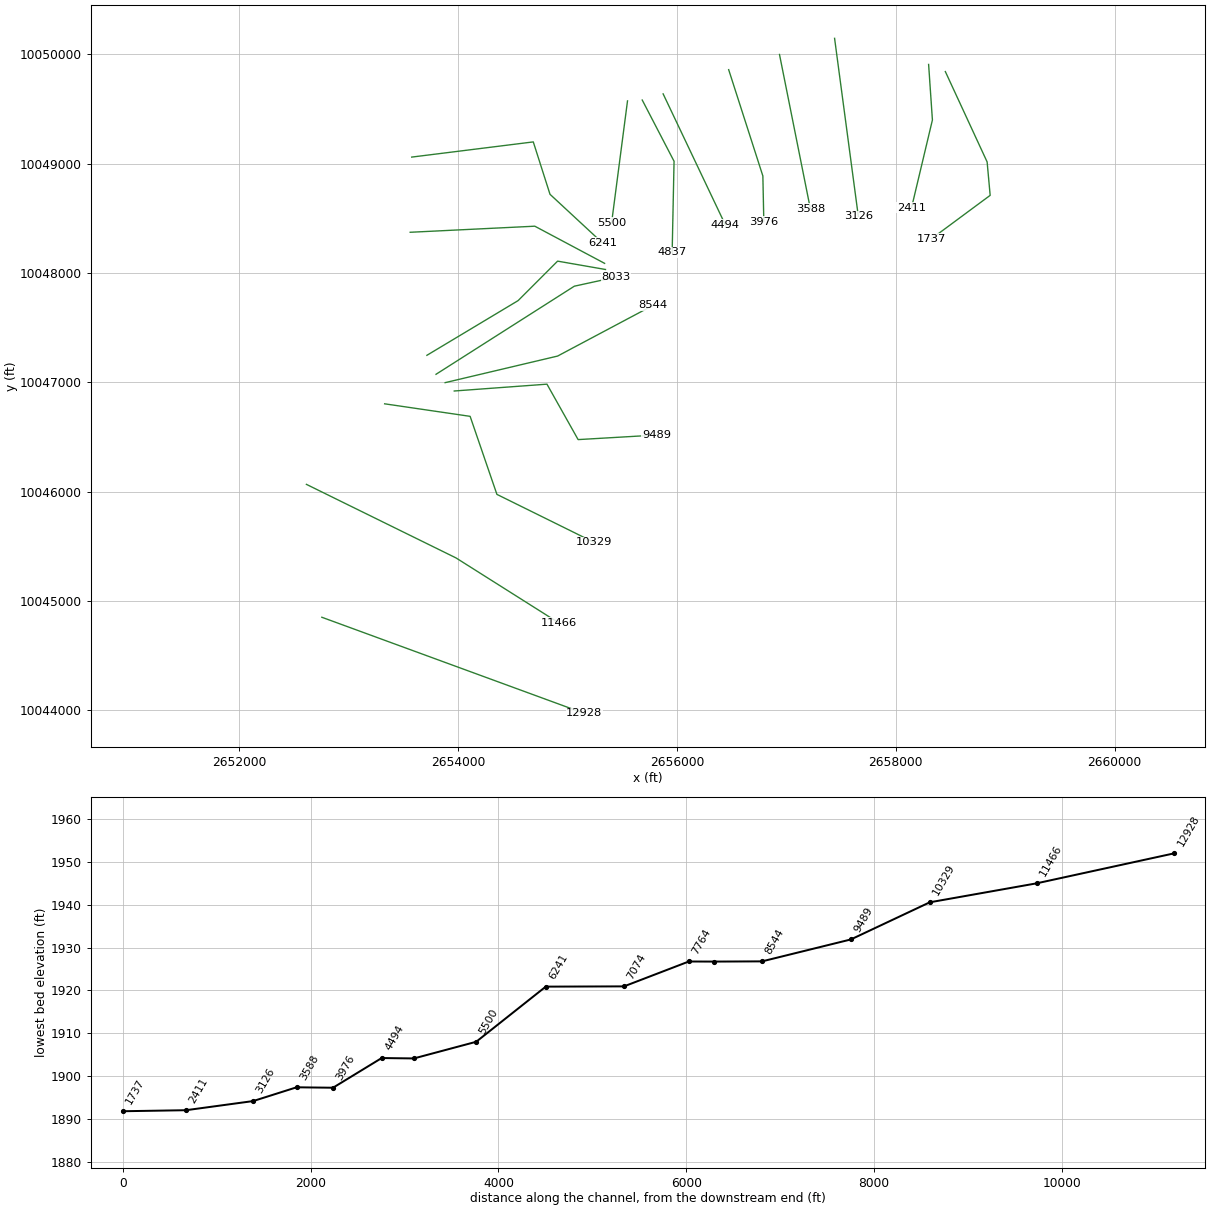
HEC-RAS study NOTT BRANCH.prj: NOTT BRANCH Base Level Engineering

--- NOTT BRANCH.g01 (geometry) --- (continued)

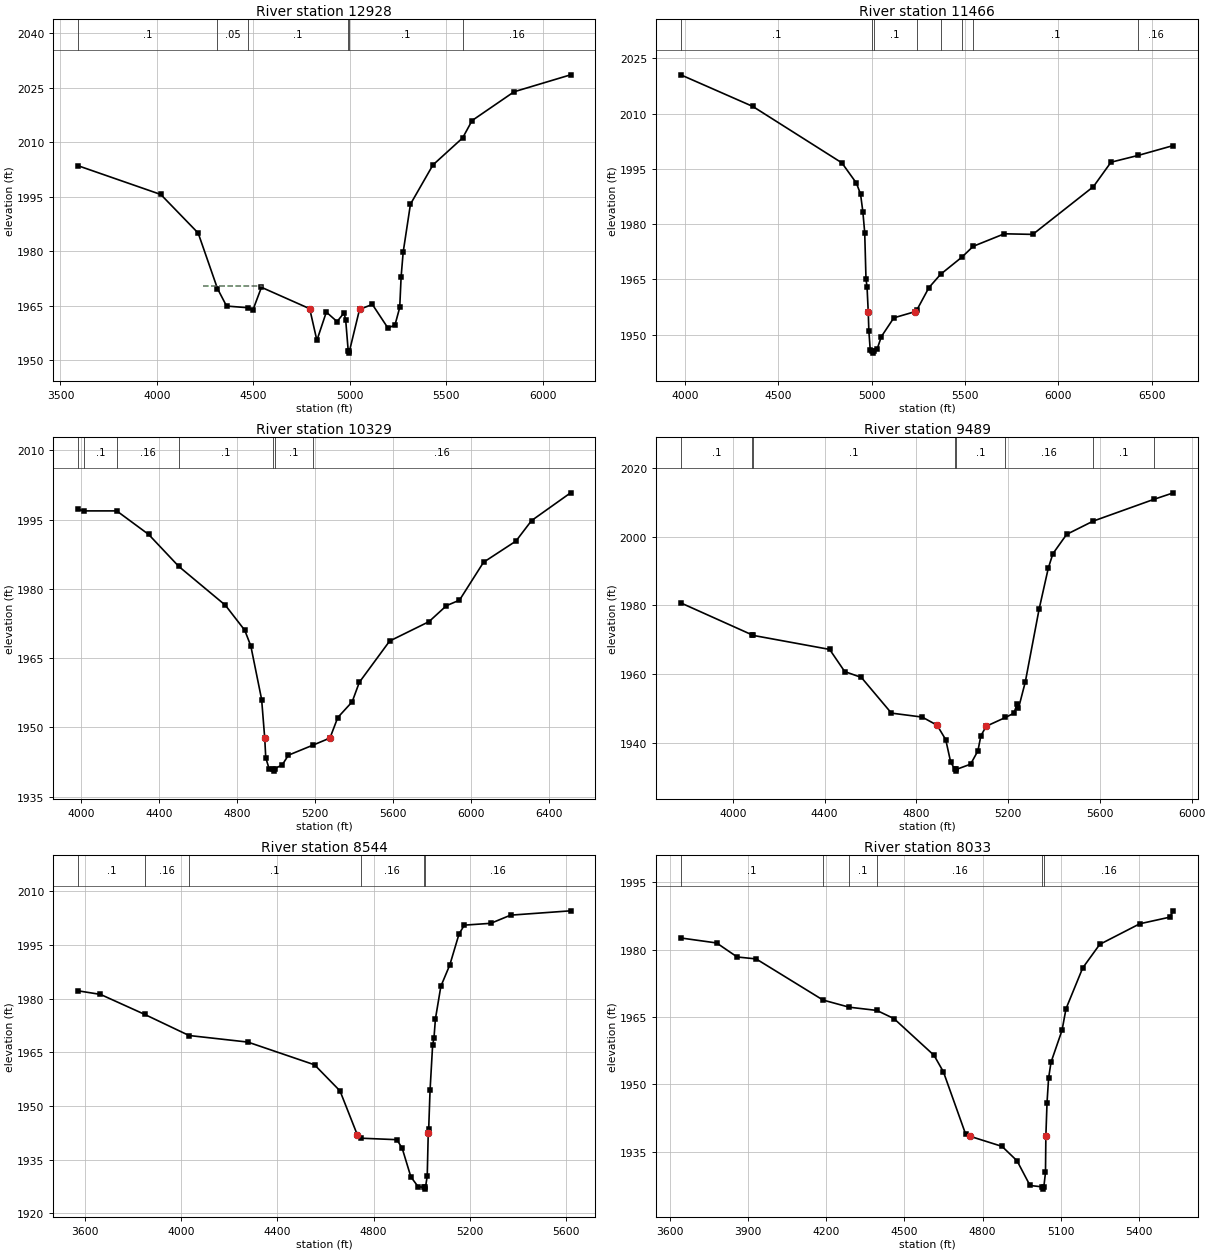
Type RM Length L Ch R = 1 ,12928   ,1462,1462,1462
BEGIN DESCRIPTION:
NOTT BRANCH 28.0
END DESCRIPTION:
XS GIS Cut Line= 2
      2652755.67     10044852.03      2655153.58     10043973.15
#Sta/Elev= 30
  3591.2  2003.5  4020.2 1995.59  4214.1 1984.97  4314.1  1969.7  4361.3 1964.89
  4472.9 1964.43  4497.9 1963.81  4542.1 1970.05  4792.3 1964.16  4829.6 1955.45
  4878.5 1963.23  4934.2 1960.62    4970 1962.99  4978.7 1961.19  4992.2 1952.44
  4994.9 1951.94  4998.2 1952.44  5050.8 1963.98  5117.2 1965.34    5198 1958.84
  5234.4 1959.67  5259.1  1964.5  5266.3 1972.92    5277 1979.73  5314.7 1992.92
  5431.4 2003.72  5585.3 2011.15  5634.3 2015.93  5852.1 2023.85  6145.1 2028.51
#Mann= 6 ,-1 , 0
  3591.2      .1       0  4314.1     .05       0  4472.9      .1       0
  4992.2     .07       0  4998.2      .1       0  5585.3     .16       0
#XS Ineff= 1 ,-1
 4241.48 4543.18 1970.29
Permanent Ineff=
       F
Bank Sta=4792.3,5050.8
XS Rating Curve= 0 ,0
Exp/Cntr=0.3,0.1

Type RM Length L Ch R = 1 ,11466   ,1137,1137,1137
BEGIN DESCRIPTION:
NOTT BRANCH 24.0
END DESCRIPTION:
XS GIS Cut Line= 3
      2652614.61      10046067.3      2653981.79     10045394.57
      2654923.89     10044798.98
#Sta/Elev= 30
  3977.5  2020.5  4362.8 2011.93  4840.2 1996.61    4918 1991.12  4940.3 1988.13
  4952.6 1983.38  4962.6 1977.68  4969.5 1965.08  4975.1  1962.9 4981.53 1956.15
  4984.9  1950.9    4992 1945.94  5004.1 1945.46  5006.9 1944.96  5010.1 1945.46
  5029.4  1946.1  5051.7 1949.44  5118.6 1954.54    5230 1956.18    5241 1956.58
  5306.5 1962.74    5369 1966.35  5483.5 1971.03  5543.7 1973.95  5710.3 1977.35
  5862.9 1977.19  6187.6 1990.15  6281.7 1996.78    6427 1998.62  6615.8 2001.31
#Mann= 8 ,-1 , 0
  3977.5      .1       0  5004.1     .07       0  5010.1      .1       0
    5241     .16       0    5369      .1       0  5483.5     .16       0
  5543.7      .1       0    6427     .16       0
Bank Sta=4981.53,5230
XS Rating Curve= 0 ,0
Exp/Cntr=0.3,0.1

Type RM Length L Ch R = 1 ,10329   ,840,840,840
BEGIN DESCRIPTION:
NOTT BRANCH 22.0
END DESCRIPTION:
XS GIS Cut Line= 4
      2653329.48     10046803.85      2654110.69     10046689.27
      2654355.48     10045975.73      2655240.42     10045538.47
#Sta/Elev= 30
  3982.4 1997.18  4012.3 1996.87    4181 1996.87  4345.2 1991.77  4500.1 1984.85
  4739.4 1976.45  4839.1 1971.03  4870.3 1967.61  4925.8 1956.04 4941.76 1947.62
    4947  1943.4  4964.1  1941.1  4986.3 1941.04    4989 1940.54  4992.3 1941.04
  5031.9 1941.91  5063.3 1943.99  5190.2 1946.18  5276.8  1947.7    5317 1952.14
    5391 1955.55  5427.8 1959.77  5583.6  1968.7  5785.5 1972.89  5875.3 1976.35
  5942.4 1977.55    6066 1985.75  6232.4 1990.33  6312.8 1994.77  6513.4 2000.78
#Mann= 7 ,-1 , 0
  3982.4     .16       0  4012.3      .1       0    4181     .16       0
  4500.1      .1       0  4986.3     .07       0  4992.3      .1       0
  5190.2     .16       0
Bank Sta=4941.76,5276.8
XS Rating Curve= 0 ,0
Exp/Cntr=0.3,0.1

Type RM Length L Ch R = 1 ,9489    ,945,945,945
BEGIN DESCRIPTION:
NOTT BRANCH 20.0
END DESCRIPTION:
XS GIS Cut Line= 4
      2653965.68     10046921.04      2654812.95     10046983.54
      2655097.67      10046476.6      2655812.96     10046518.26
#Sta/Elev= 30
  3772.7 1980.74    4084 1971.44  4088.3  1971.3  4421.6 1967.23  4487.4 1960.79
  4559.8  1959.1  4690.9 1948.73  4825.1 1947.58  4890.2 1945.21  4927.8 1941.01
  4949.5 1934.45  4968.2 1932.38  4970.9 1931.88  4974.2 1932.38  5036.2  1933.9
  5068.1 1937.77  5080.8 1942.08  5103.8  1944.9    5188 1947.46  5224.5 1948.69
    5240 1951.51    5245 1950.12  5274.6 1957.76  5334.7 1978.86  5374.8 1990.79
  5394.8 1995.01  5454.9 2000.64  5570.1 2004.48  5836.7 2010.85  5920.2 2012.71
#Mann= 8 ,-1 , 0
  3772.7      .1       0    4084     .16       0  4088.3      .1       0
  4968.2     .07       0  4974.2      .1       0    5188     .16       0
  5570.1      .1       0  5836.7     .16       0
Bank Sta=4890.2,5103.8
XS Rating Curve= 0 ,0
Exp/Cntr=0.3,0.1

Type RM Length L Ch R = 1 ,8544    ,511,511,511
BEGIN DESCRIPTION:
NOTT BRANCH 19.0
END DESCRIPTION:
XS GIS Cut Line= 3
      2653882.41     10046997.43      2654910.17     10047240.49
      2655784.36     10047705.33
#Sta/Elev= 30
  3572.2  1982.2  3665.3  1981.2  3848.7 1975.62  4033.3 1969.71  4277.7 1967.87
  4554.6 1961.52  4660.4 1954.23  4732.5 1941.92  4745.9 1941.01    4897 1940.59
    4919 1938.14  4954.8  1930.2  4984.9 1927.45  5009.5 1927.27  5012.3 1926.77
  5015.5 1927.27  5022.8 1930.44 5026.99  1942.4  5028.9 1943.69  5034.5 1954.37
  5045.2 1967.03  5050.8 1969.02  5056.8 1974.34  5079.4 1983.46  5116.8 1989.48
    5155 1998.11    5177 2000.56  5286.9 2001.07  5369.1 2003.35  5618.4 2004.56
#Mann= 6 ,-1 , 0
  3572.2      .1       0  3848.7     .16       0  4033.3      .1       0
  4745.9     .16       0  5009.5     .07       0  5015.5     .16       0
Bank Sta=4732.5,5026.99
XS Rating Curve= 0 ,0
Exp/Cntr=0.3,0.1

Type RM Length L Ch R = 1 ,8033    ,269,269,269
BEGIN DESCRIPTION:
NOTT BRANCH 17.0
END DESCRIPTION:
XS GIS Cut Line= 3
      2653799.07     10047073.83      2655062.95     10047879.37
      2655444.22     10047962.56
#Sta/Elev= 30
  3642.5  1982.6    3780 1981.49  3858.7 1978.37  3931.5 1977.94  4187.9 1968.79
  4288.3  1967.2  4394.3 1966.48    4460 1964.66  4613.7 1956.49  4649.7 1952.81
  4734.7 1938.98  4749.9 1938.51  4874.4 1936.23  4931.9 1933.03  4981.8 1927.53
  5028.8 1927.22  5031.5 1926.72  5034.8 1927.22  5041.1 1930.43 5042.61 1938.57
    5047 1945.92    5053 1951.39  5062.3 1954.94  5104.6 1962.06  5119.8 1966.85
  5183.9 1975.94  5249.3 1981.18  5402.8 1985.76    5517 1987.22  5531.5 1988.64
#Mann= 6 ,-1 , 0
  3642.5      .1       0  4187.9     .16       0  4288.3      .1       0
  4394.3     .16       0  5028.8     .07       0  5034.8     .16       0
Bank Sta=4749.9,5042.61
XS Rating Curve= 0 ,0
Exp/Cntr=0.3,0.1

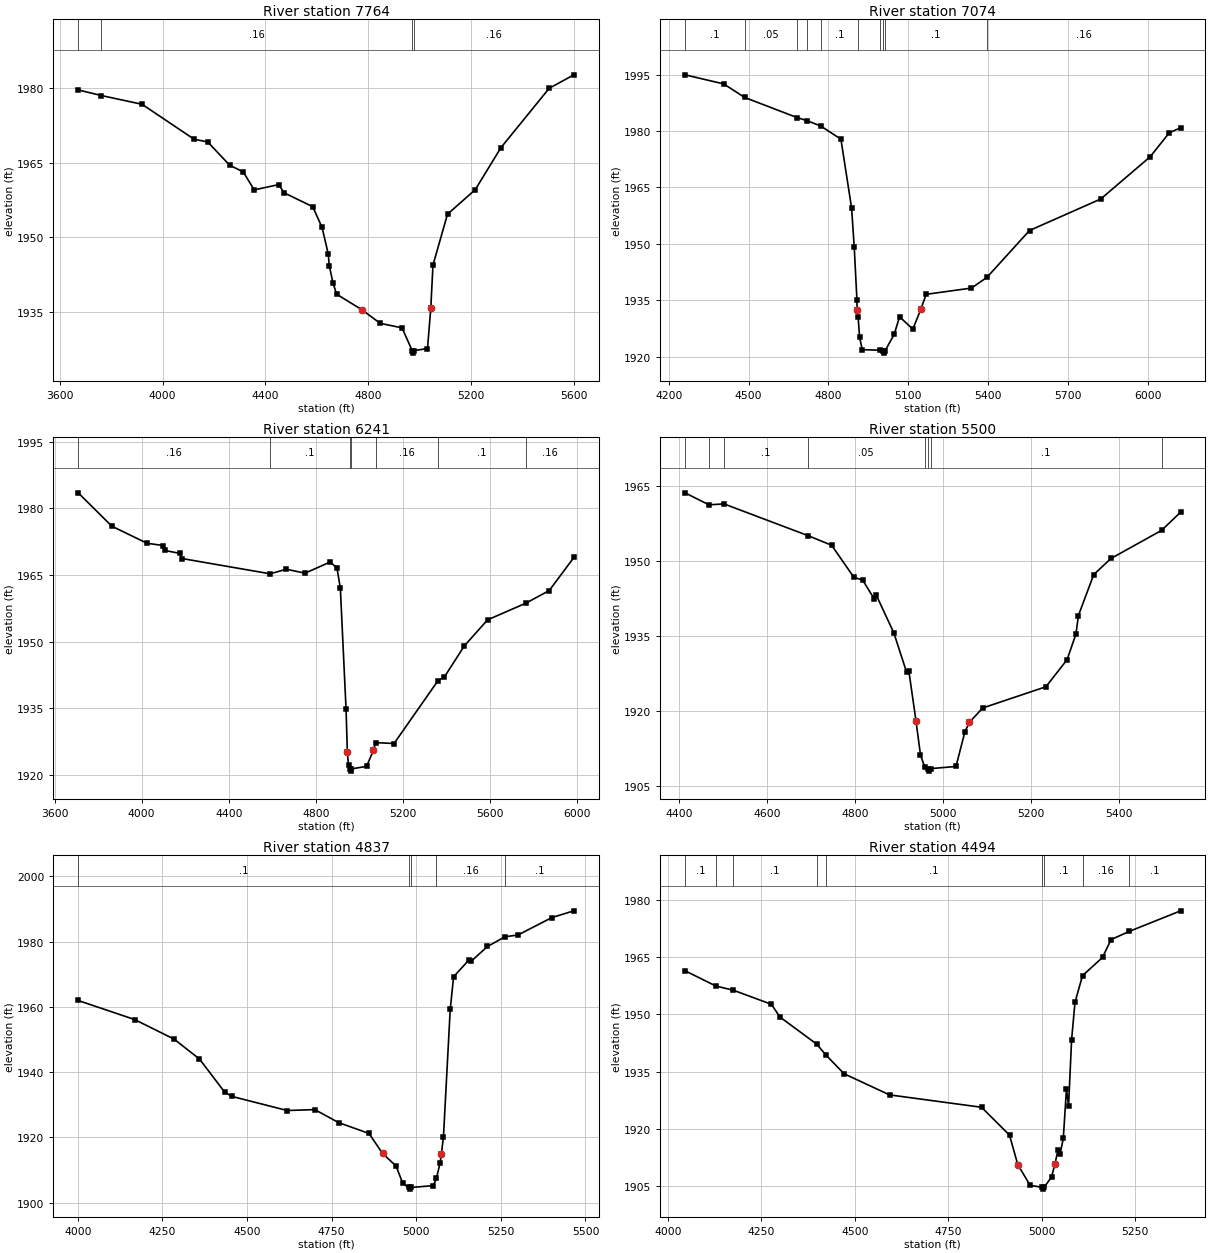
Type RM Length L Ch R = 1 ,7764    ,690,690,690
BEGIN DESCRIPTION:
NOTT BRANCH 16.0
END DESCRIPTION:
XS GIS Cut Line= 4
      2653715.69     10047247.41      2654549.06     10047747.43
      2654910.17     10048108.54      2655347.69     10048032.15
#Sta/Elev= 30
  3672.1 1979.66  3762.6 1978.52  3920.2 1976.77    4123 1969.73  4175.5  1969.2
    4261 1964.51  4313.5 1963.18  4356.3 1959.56  4451.5 1960.62  4472.9 1958.96
  4583.7 1956.18    4620 1952.01    4644 1946.69    4648 1944.34  4662.1 1940.93
  4676.3  1938.6  4775.3 1935.44    4846 1932.73  4930.9 1931.82  4970.3 1927.24
    4973 1926.74  4976.3 1927.24  5029.8 1927.66 5042.61 1935.77  5051.1 1944.43
  5107.6 1954.68  5215.3 1959.59  5315.3 1968.05  5502.8 1979.98  5598.8 1982.69
#Mann= 4 ,-1 , 0
  3672.1      .1       0  3762.6     .16       0  4970.3     .07       0
  4976.3     .16       0
Bank Sta=4775.3,5042.61
XS Rating Curve= 0 ,0
Exp/Cntr=0.3,0.1

Type RM Length L Ch R = 1 ,7074    ,833,833,833
BEGIN DESCRIPTION:
NOTT BRANCH 15.0
END DESCRIPTION:
XS GIS Cut Line= 3
      2653562.95     10048372.43      2654701.84     10048427.99
      2655339.76     10048088.22
#Sta/Elev= 30
  4260.6 1994.95  4406.3 1992.53  4485.1 1988.93  4681.7 1983.59  4718.7 1982.78
  4770.6 1981.35  4846.8 1977.84  4886.9 1959.54  4896.9 1949.06  4906.9 1935.15
 4907.67 1932.42  4911.4 1930.67  4916.9  1925.2  4926.9 1921.86  4991.9 1921.72
  5005.8 1921.44  5008.6 1920.94  5011.8 1921.44    5047 1925.92  5067.1 1930.61
  5117.1 1927.32  5147.2 1932.61  5167.2 1936.58  5337.4 1938.24  5395.5 1941.08
  5555.6 1953.55  5823.3 1961.93  6008.8 1973.14  6081.2 1979.56  6123.6 1980.86
#Mann= 10 ,-1 , 0
  4260.6      .1       0  4485.1     .05       0  4681.7      .1       0
  4718.7     .05       0  4770.6      .1       0  4911.4     .16       0
  4991.9      .1       0  5005.8     .07       0  5011.8      .1       0
  5395.5     .16       0
Bank Sta=4907.67,5147.2
XS Rating Curve= 0 ,0
Exp/Cntr=0.3,0.1

Type RM Length L Ch R = 1 ,6241    ,741,741,741
BEGIN DESCRIPTION:
NOTT BRANCH 13.0
END DESCRIPTION:
XS GIS Cut Line= 4
      2653576.82     10049059.93      2654687.95     10049198.82
      2654840.73     10048719.65      2655319.92     10048275.18
#Sta/Elev= 30
  3708.8 1983.46  3863.5 1975.95  4024.8 1972.12  4100.4  1971.6  4105.4 1970.51
    4174 1969.86    4186 1968.68  4590.4 1965.25  4664.7 1966.28  4750.4 1965.39
  4865.4 1967.89  4896.9  1966.6  4912.6 1962.07  4938.9  1934.8  4944.8 1925.25
  4950.1 1922.19  4956.9 1921.38  4959.6 1920.88  4962.9 1921.38  5033.3 1921.95
  5064.8 1925.62  5074.9 1927.29  5159.3 1927.09  5361.4 1941.24  5390.7 1942.07
  5482.6 1949.08  5588.6 1954.89  5764.7 1958.65  5872.1 1961.49  5985.1 1968.93
#Mann= 7 ,-1 , 0
  3708.8     .16       0  4590.4      .1       0  4956.9     .07       0
  4962.9      .1       0  5074.9     .16       0  5361.4      .1       0
  5764.7     .16       0
Bank Sta=4944.8,5064.8
XS Rating Curve= 0 ,0
Exp/Cntr=0.3,0.1

Type RM Length L Ch R = 1 ,5500    ,663,663,663
BEGIN DESCRIPTION:
NOTT BRANCH 11.0
END DESCRIPTION:
XS GIS Cut Line= 2
      2655549.06      10049573.8      2655403.54     10048458.15
#Sta/Elev= 30
  4413.9 1963.61  4468.6 1961.21  4502.5  1961.4  4692.9 1955.07  4746.8 1953.14
  4797.2 1946.75  4817.4 1946.16  4843.1 1942.47  4848.2 1943.17    4888 1935.64
  4917.1 1927.75  4922.1 1928.03  4938.4 1917.99  4948.5 1911.25  4957.7 1908.94
  4965.6 1908.52  4968.4 1908.02  4971.6 1908.52  5029.1 1908.95  5049.3 1915.87
  5059.4 1917.75  5089.6 1920.63  5233.1 1924.87  5281.3 1930.28  5301.4 1935.41
    5307  1939.1  5341.8 1947.29    5381  1950.5  5495.7 1956.11    5539 1959.75
#Mann= 8 ,-1 , 0
  4413.9      .1       0  4468.6     .05       0  4502.5      .1       0
  4692.9     .05       0  4957.7      .1       0  4965.6     .07       0
  4971.6      .1       0  5495.7     .16       0
Bank Sta=4938.4,5059.4
XS Rating Curve= 0 ,0
Exp/Cntr=0.3,0.1

Type RM Length L Ch R = 1 ,4837    ,343,343,343
BEGIN DESCRIPTION:
NOTT BRANCH 10.0
END DESCRIPTION:
XS GIS Cut Line= 3
       2655683.6     10049581.66      2655974.41     10049021.74
      2655957.05     10048188.55
#Sta/Elev= 30
  4001.5 1961.97  4168.2 1956.13  4284.9 1950.12  4359.7 1944.03  4434.1 1933.89
  4456.2 1932.55  4618.9 1928.24  4700.5 1928.52  4770.5 1924.55  4860.5 1921.21
  4900.5  1915.1  4940.5 1911.22  4960.5 1905.88  4977.5 1904.64  4980.3 1904.14
  4983.5 1904.64  5050.5 1905.21  5059.9 1907.53  5070.5  1912.1 5074.55 1915.02
  5080.5 1920.17  5100.5 1959.24  5110.5 1969.25  5156.6 1974.49  5161.6 1973.93
  5210.6 1978.53  5262.6 1981.52  5300.6 1982.04  5400.6 1987.39  5465.8 1989.46
#Mann= 5 ,-1 , 0
  4001.5      .1       0  4977.5     .07       0  4983.5      .1       0
  5059.9     .16       0  5262.6      .1       0
Bank Sta=4900.5,5074.55
XS Rating Curve= 0 ,0
Exp/Cntr=0.3,0.1

Type RM Length L Ch R = 1 ,4494    ,518,518,518
BEGIN DESCRIPTION:
NOTT BRANCH 9.0
END DESCRIPTION:
XS GIS Cut Line= 2
      2655874.56     10049638.09      2656443.14     10048440.18
#Sta/Elev= 30
  4045.7 1961.38  4128.2 1957.38  4175.2 1956.27  4276.9  1952.6  4299.6 1949.28
  4398.1 1942.17  4422.6 1939.35  4471.2 1934.43  4592.9 1928.89    4839 1925.65
  4913.9 1918.37  4936.1 1910.63  4969.3  1905.2  5000.7 1904.73  5003.4 1904.23
  5006.7 1904.73  5026.4 1907.41  5035.7 1910.93  5043.6 1914.47  5049.1 1913.34
  5057.8 1917.49  5066.3 1930.43  5071.9 1925.98    5080 1943.28  5089.1 1953.12
  5109.2 1960.09  5162.8 1964.86  5185.5 1969.52  5234.6 1971.68  5371.7 1977.05
#Mann= 9 ,-1 , 0
  4045.7      .1       0  4128.2     .05       0  4175.2      .1       0
  4398.1     .05       0  4422.6      .1       0  5000.7     .07       0
  5006.7      .1       0  5109.2     .16       0  5234.6      .1       0
Bank Sta=4936.1,5035.7
XS Rating Curve= 0 ,0
Exp/Cntr=0.3,0.1

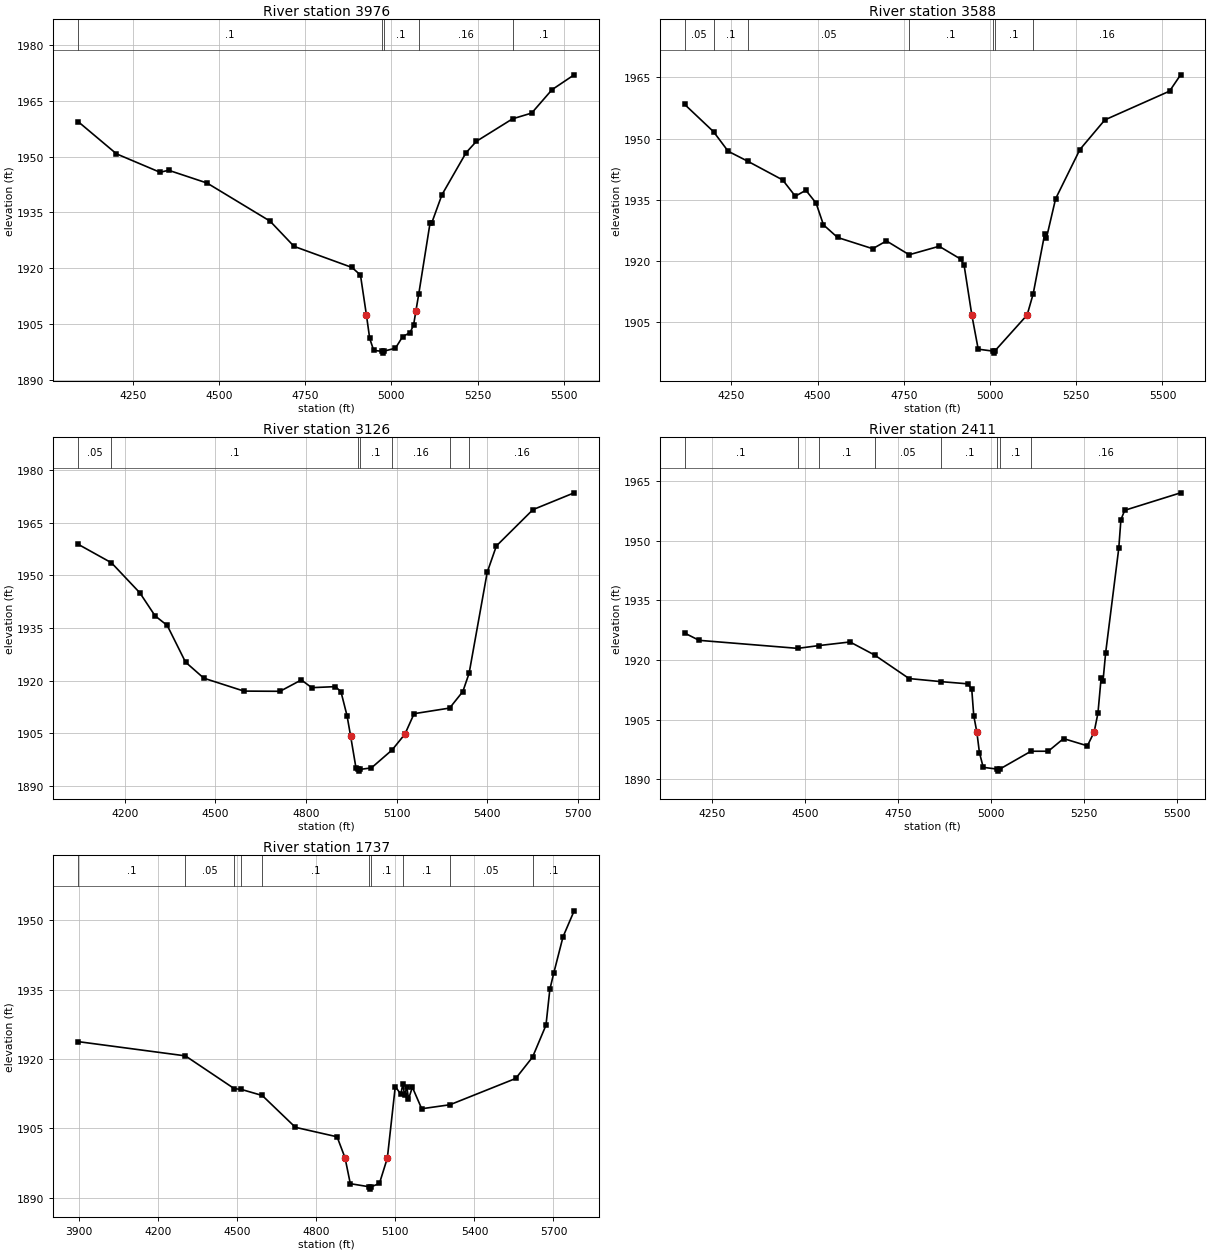
Type RM Length L Ch R = 1 ,3976    ,388,388,388
BEGIN DESCRIPTION:
NOTT BRANCH 8.0
END DESCRIPTION:
XS GIS Cut Line= 3
      2656473.53     10049859.44      2656786.04     10048887.19
      2656794.72     10048470.52
#Sta/Elev= 30
    4092 1959.33    4203 1950.71  4329.1 1945.78  4354.3 1946.31  4465.6 1942.89
  4648.4 1932.67  4717.8 1925.92  4885.8 1920.27  4910.4 1918.23  4927.8 1907.44
  4937.2 1901.24  4948.8 1898.04  4971.6 1897.81  4974.3 1897.31  4977.6 1897.81
  5011.9 1898.64  5032.8 1901.75  5053.8 1902.76  5064.4 1904.81  5070.9 1908.49
  5079.6 1913.26  5112.4 1932.31  5117.5 1932.31  5146.7 1939.76  5216.7 1951.03
  5246.7 1954.08  5351.4  1960.1  5406.8 1961.64  5465.8 1967.91    5530 1971.89
#Mann= 5 ,-1 , 0
    4092      .1       0  4971.6     .07       0  4977.6      .1       0
  5079.6     .16       0  5351.4      .1       0
Bank Sta=4927.8,5070.9
XS Rating Curve= 0 ,0
Exp/Cntr=0.3,0.1

Type RM Length L Ch R = 1 ,3588    ,462,462,462
BEGIN DESCRIPTION:
NOTT BRANCH 7.0
END DESCRIPTION:
XS GIS Cut Line= 2
      2656937.94     10049998.33      2657219.96     10048588.25
#Sta/Elev= 30
  4114.6 1958.38  4198.2  1951.7  4240.7  1946.9  4297.6 1944.45  4398.7 1939.87
  4435.4 1935.88    4466 1937.34  4495.6 1934.19    4517 1928.86  4557.8 1925.77
  4659.8 1923.01  4699.6 1924.92  4765.5 1921.53  4852.5 1923.61  4914.7 1920.47
  4924.9 1918.91 4947.27 1906.72  4965.7 1898.38  5007.6 1897.91  5010.4 1897.41
  5013.6 1897.91  5107.5 1906.75    5125 1911.91  5158.5 1926.65  5163.6 1925.65
  5190.1 1935.25  5260.5 1947.32  5332.9 1954.59  5520.5 1961.64  5552.6 1965.64
#Mann= 7 ,-1 , 0
  4114.6     .05       0  4198.2      .1       0  4297.6     .05       0
  4765.5      .1       0  5007.6     .07       0  5013.6      .1       0
    5125     .16       0
Bank Sta=4947.27,5107.5
XS Rating Curve= 0 ,0
Exp/Cntr=0.3,0.1

Type RM Length L Ch R = 1 ,3126    ,715,715,715
BEGIN DESCRIPTION:
NOTT BRANCH 6.0
END DESCRIPTION:
XS GIS Cut Line= 2
      2657441.42     10050145.86      2657658.41     10048518.46
#Sta/Elev= 30
  4046.2 1958.87  4156.3  1953.6  4250.1 1945.05  4300.6 1938.48  4340.9 1935.74
  4401.4 1925.29    4462  1920.7  4594.7 1917.02  4714.2 1916.96  4784.8  1920.2
  4819.2    1918  4897.4 1918.29    4916 1916.85  4936.1 1910.02 4948.07 1904.16
  4965.5 1895.23  4973.5  1894.7  4976.2  1894.2  4979.5  1894.7  5016.8 1895.12
  5085.2 1900.23  5127.8 1904.75  5158.1 1910.58  5275.8 1912.18  5319.5  1916.9
  5340.3 1922.12  5400.2  1950.9  5430.5  1958.4  5551.5 1968.75    5688 1973.55
#Mann= 7 ,-1 , 0
  4046.2     .05       0  4156.3      .1       0  4973.5     .07       0
  4979.5      .1       0  5085.2     .16       0  5275.8      .1       0
  5340.3     .16       0
Bank Sta=4948.07,5127.8
XS Rating Curve= 0 ,0
Exp/Cntr=0.3,0.1

Type RM Length L Ch R = 1 ,2411    ,674,674,674
BEGIN DESCRIPTION:
NOTT BRANCH 4.0
END DESCRIPTION:
XS GIS Cut Line= 3
       2658300.8     10049907.13      2658335.52     10049399.34
      2658144.83     10048597.58
#Sta/Elev= 30
  4177.4 1926.77  4216.2 1924.95  4481.3 1922.93  4538.1 1923.63  4621.8 1924.54
  4688.2 1921.24  4780.6 1915.34  4867.2 1914.56  4938.8 1914.01  4949.1 1912.61
  4954.4 1906.02 4962.73 1901.91  4969.7 1896.73  4979.9 1893.02  5018.1 1892.57
  5020.8 1892.07  5024.1 1892.57  5108.3 1897.07  5154.7 1897.07  5195.8 1900.25
  5259.9 1898.43    5278 1901.89  5288.3 1906.66  5296.9 1915.59    5302 1914.81
  5308.9 1921.75  5344.2 1948.05    5350 1955.28  5360.3 1957.64  5510.5 1962.03
#Mann= 8 ,-1 , 0
  4177.4      .1       0  4481.3     .05       0  4538.1      .1       0
  4688.2     .05       0  4867.2      .1       0  5018.1     .07       0
  5024.1      .1       0  5108.3     .16       0
Bank Sta=4962.73,5278
XS Rating Curve= 0 ,0
Exp/Cntr=0.3,0.1

Type RM Length L Ch R = 1 ,1737    ,641,641,641
BEGIN DESCRIPTION:
NOTT BRANCH 3.0
END DESCRIPTION:
XS GIS Cut Line= 4
      2658453.56     10049842.07      2658835.52     10049015.66
       2658863.3      10048710.1      2658328.59     10048314.28
#Sta/Elev= 30
  3895.9 1923.76  4302.7 1920.68  4488.3 1913.58  4514.8 1913.42  4594.5  1912.1
  4720.3 1905.21  4878.5 1903.16  4908.7 1898.61  4928.7 1893.01  5001.3 1892.33
  5004.1 1891.83  5007.3 1892.33  5039.2 1893.05  5069.3 1898.55  5099.4 1914.04
  5120.4 1912.38  5127.9 1914.51    5135 1912.16  5143.4 1913.96  5149.6 1911.31
  5164.3  1913.9  5199.7 1909.23  5307.1  1910.1  5556.6 1915.79  5620.5 1920.41
  5671.4 1927.31  5686.1 1935.05  5700.7 1938.54  5736.2 1946.46  5778.4 1952.08
#Mann= 10 ,-1 , 0
  3895.9      .1       0  4302.7     .05       0  4488.3      .1       0
  4514.8     .05       0  4594.5      .1       0  5001.3     .07       0
  5007.3      .1       0  5127.9      .1       0  5307.1     .05       0
  5620.5      .1       0
Bank Sta=4908.7,5069.3
XS Rating Curve= 0 ,0
Exp/Cntr=0.3,0.1