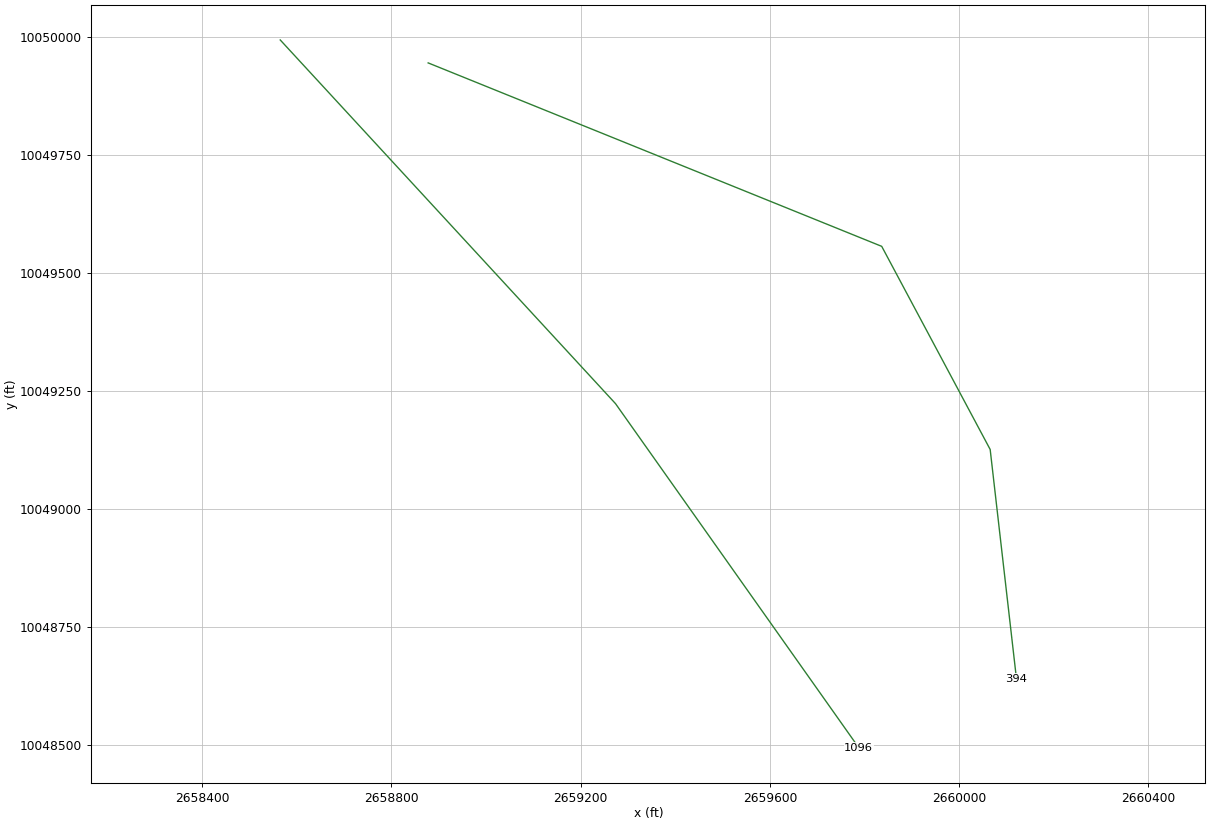
HEC-RAS study NOTT BRANCH.prj: NOTT BRANCH Base Level Engineering

--- NOTT BRANCH.g01 (geometry) --- (continued)

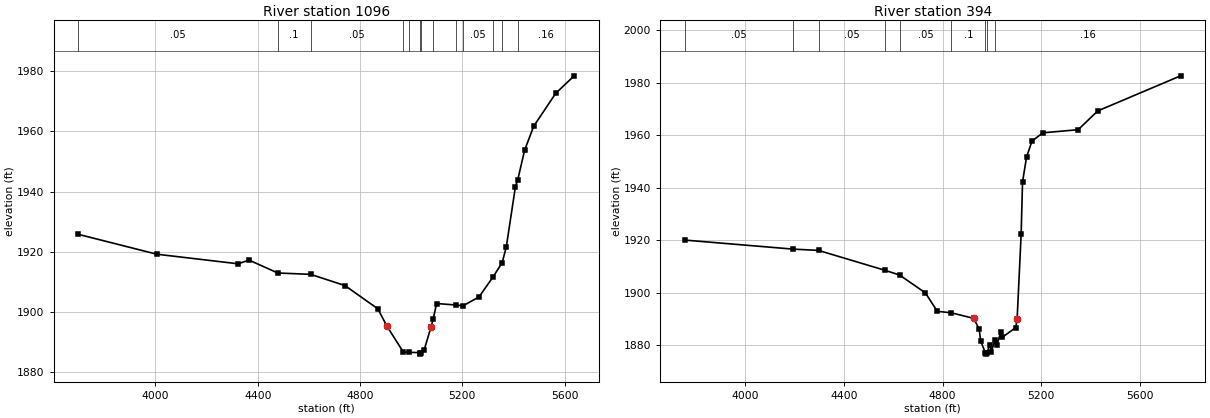
Type RM Length L Ch R = 1 ,1096    ,702,702,702
BEGIN DESCRIPTION:
NOTT BRANCH 2.0
END DESCRIPTION:
XS GIS Cut Line= 3
      2658565.56     10049993.95      2659273.89     10049223.12
      2659787.77     10048493.97
#Sta/Elev= 30
  3698.6 1925.75  4005.2 1919.14  4323.6 1915.95  4365.9 1917.19  4478.4 1912.89
  4606.8 1912.44  4741.3 1908.71  4869.7 1900.98  4905.4 1895.19  4969.6 1886.57
  4990.8  1886.5    5033  1886.4  5035.8  1885.9    5039  1886.4  5050.6 1887.19
  5077.8 1894.94  5086.4 1897.59  5099.5 1902.74  5173.5 1902.25  5203.1 1901.99
  5265.1  1904.9  5319.8  1911.5  5356.2 1916.37  5372.2 1921.61  5407.9 1941.65
  5417.1 1943.96  5443.6 1953.69  5479.3 1961.71  5565.5 1972.67  5637.5 1978.48
#Mann= 13 ,-1 , 0
  3698.6     .05       0  4478.4      .1       0  4606.8     .05       0
  4969.6      .1       0  4990.8     .16       0    5033     .07       0
    5039     .16       0  5086.4      .1       0  5173.5     .16       0
  5203.1     .05       0  5319.8      .1       0  5356.2     .05       0
  5417.1     .16       0
Bank Sta=4905.4,5077.8
XS Rating Curve= 0 ,0
Exp/Cntr=0.3,0.1

Type RM Length L Ch R = 1 ,394     ,0,0,0
BEGIN DESCRIPTION:
NOTT BRANCH 1.0
END DESCRIPTION:
XS GIS Cut Line= 4
       2658878.1     10049945.33      2659836.39     10049556.46
      2660065.55      10049125.9      2660121.11     10048639.79
#Sta/Elev= 30
  3754.4  1920.1  4191.6 1916.67  4296.8 1916.16  4566.3 1908.59  4625.3  1906.8
  4730.4 1899.99  4778.6 1892.97  4835.9 1892.39  4926.6 1890.27  4948.6 1886.11
  4954.3 1881.78  4973.3 1877.16    4976 1876.66  4979.3 1877.16  4992.6 1880.29
  4998.2 1877.66  5012.8 1882.14  5020.2 1880.03  5036.5 1885.22  5042.2 1883.06
  5096.7 1886.78  5102.4 1890.03  5118.7 1922.35  5124.4 1942.31  5140.7 1951.73
  5162.7 1957.81  5206.6 1960.96    5350 1962.14  5429.3 1969.29  5765.6 1982.66
#Mann= 9 ,-1 , 0
  3754.4     .05       0  4191.6      .1       0  4296.8     .05       0
  4566.3      .1       0  4625.3     .05       0  4835.9      .1       0
  4973.3     .07       0  4979.3      .1       0  5012.8     .16       0
Bank Sta=4926.6,5102.4
XS Rating Curve= 0 ,0
Exp/Cntr=0.3,0.1

Chan Stop Cuts=-1
Use User Specified Reach Order=0
Composite Channel Slope=5