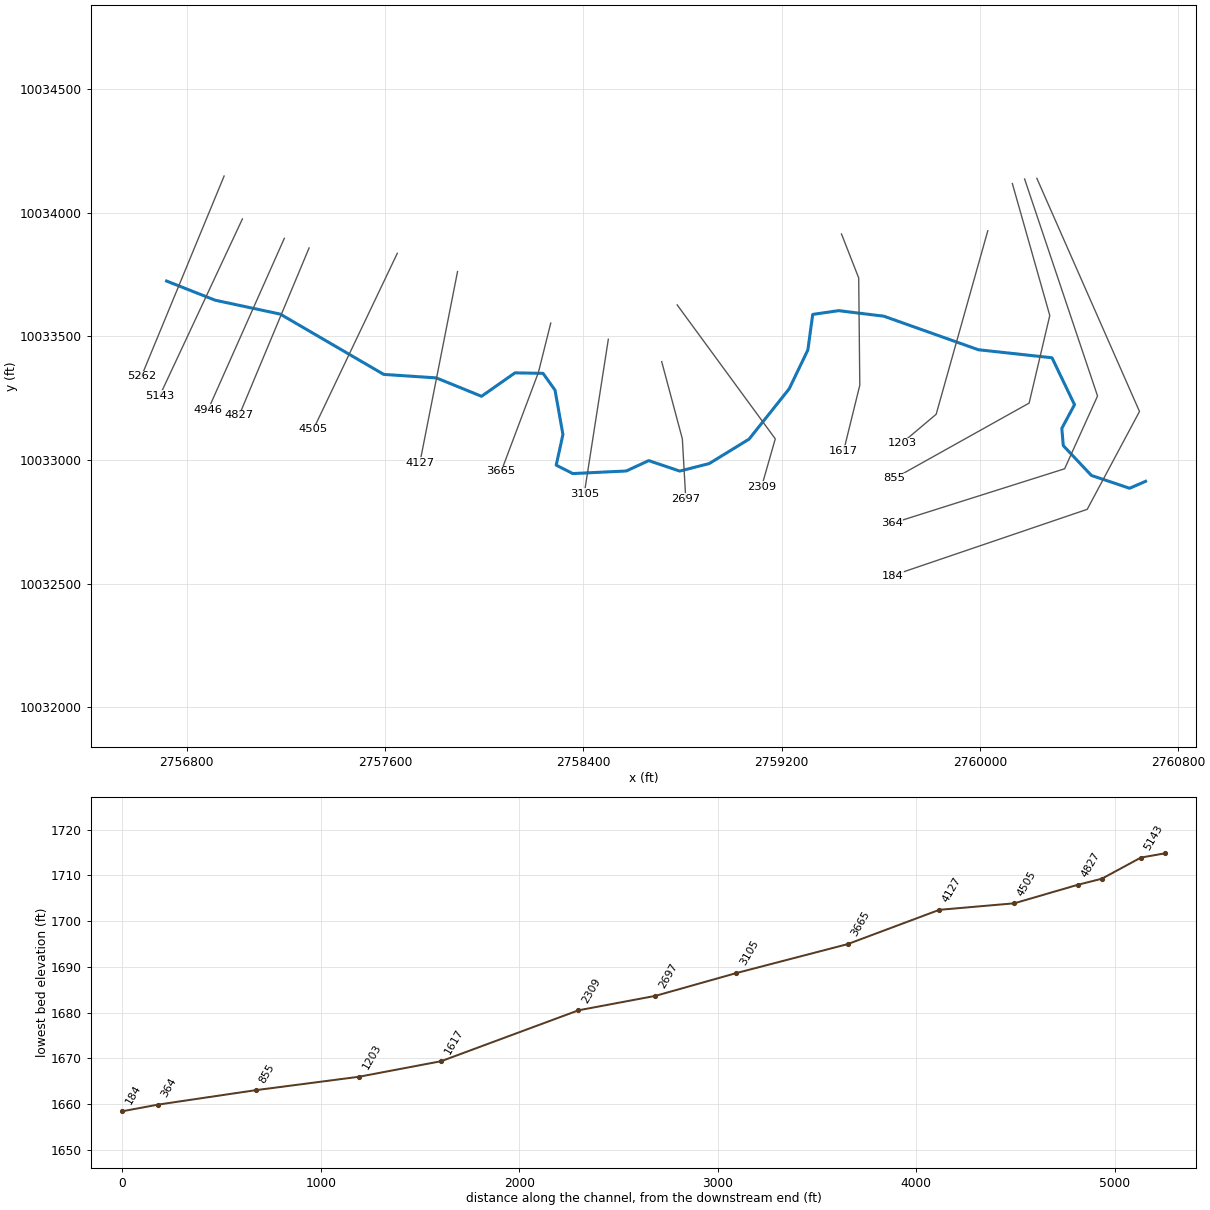
--- PECAN CREEK 2.prj (project) ---

Proj Title=PECAN CREEK 2 Base Level Engineering
Current Plan=p01
Default Exp/Contr=0.3,0.1
English Units
Geom File=g01
Flow File=f01
Plan File=p01
Y Axis Title=Elevation
X Axis Title(PF)=Main Channel Distance
X Axis Title(XS)=Station
BEGIN DESCRIPTION:
PECAN CREEK 2
END DESCRIPTION:
DSS Export Rating Curves= 0
DSS Export Rating Curve Sorted= 0
DSS Export Volume Flow Curves= 0
DXF OffsetX= 0
DXF OffsetY= 0
DXF ScaleX= 1
DXF ScaleY= 10

--- PECAN CREEK 2.p01 (plan) ---

Plan Title=Multiple Run
Short Identifier=Multiple
Geom File=g01
Flow File=f01
Subcritical Flow
K Sum by GR= 0
Std Step Tol= 0.01
Critical Tol= 0.01
Num of Std Step Trials= 20
Max Error Tol= 0.3
Flow Tol Ratio= 0.001
Split Flow NTrial= 30
Split Flow Tol= 0.02
Split Flow Ratio= 0.02
Log Output Level= 0
Friction Slope Method= 1
Unsteady Friction Slope Method= 2
Unsteady Bridges Friction Slope Method= 1
Parabolic Critical Depth
Global Vel Dist=  1 , 1 , 1
Global Log Level= 0
CheckData=True
Encroach Param= -1, 0, 0, 0
BEGIN DESCRIPTION:
Multiple Run
END DESCRIPTION:

--- PECAN CREEK 2.f01 (steady flow) ---

Flow Title=Multiple
Number of Profiles=7
Profile Names=10-year,25-year,50-year,1pct_min,100-year,1pct_plu,500-year
River Rch & RM= PECAN CREEK 2,Reach-1,5262
     818    1185    1503    1396    1888    2553    2990
River Rch & RM= PECAN CREEK 2,Reach-1,4946
     995    1452    1852    1727    2336    3159    3734
Boundary for River Rch & Prof#=PECAN CREEK 2,Reach-1,1
Up Type=0
Dn Type=3
Dn Slope=0.005
Boundary for River Rch & Prof#=PECAN CREEK 2,Reach-1,2
Up Type=0
Dn Type=3
Dn Slope=0.005
Boundary for River Rch & Prof#=PECAN CREEK 2,Reach-1,3
Up Type=0
Dn Type=3
Dn Slope=0.005
Boundary for River Rch & Prof#=PECAN CREEK 2,Reach-1,4
Up Type=0
Dn Type=3
Dn Slope=0.005
Boundary for River Rch & Prof#=PECAN CREEK 2,Reach-1,5
Up Type=0
Dn Type=3
Dn Slope=0.005
Boundary for River Rch & Prof#=PECAN CREEK 2,Reach-1,6
Up Type=0
Dn Type=3
Dn Slope=0.005
Boundary for River Rch & Prof#=PECAN CREEK 2,Reach-1,7
Up Type=0
Dn Type=3
Dn Slope=0.005

--- PECAN CREEK 2.g01 (geometry) ---

Geom Title=Existing Conditions
Program Version=4.10

River Reach=PECAN CREEK 2   ,Reach-1
Reach XY= 30
      2756718.47     10033723.73      2756914.49      10033646.2
      2757176.94     10033590.04      2757594.48     10033346.17
      2757806.76     10033332.06      2757989.21     10033257.61
      2758124.09     10033352.41      2758237.27     10033350.43
      2758285.63     10033282.64      2758317.61     10033103.18
      2758290.42     10032979.19      2758357.23     10032945.12
       2758572.9     10032955.47      2758663.78     10032997.55
      2758788.79     10032955.15      2758907.71     10032985.53
      2759068.35     10033084.24      2759230.35     10033287.66
      2759305.82     10033444.89      2759325.39      10033588.8
       2759429.8     10033604.02      2759612.46     10033581.56
       2759993.8     10033445.88      2760290.89     10033413.44
      2760381.69     10033223.66       2760330.5     10033127.97
      2760336.39      10033058.1      2760449.91     10032937.43
      2760603.91     10032885.73      2760668.47     10032913.73

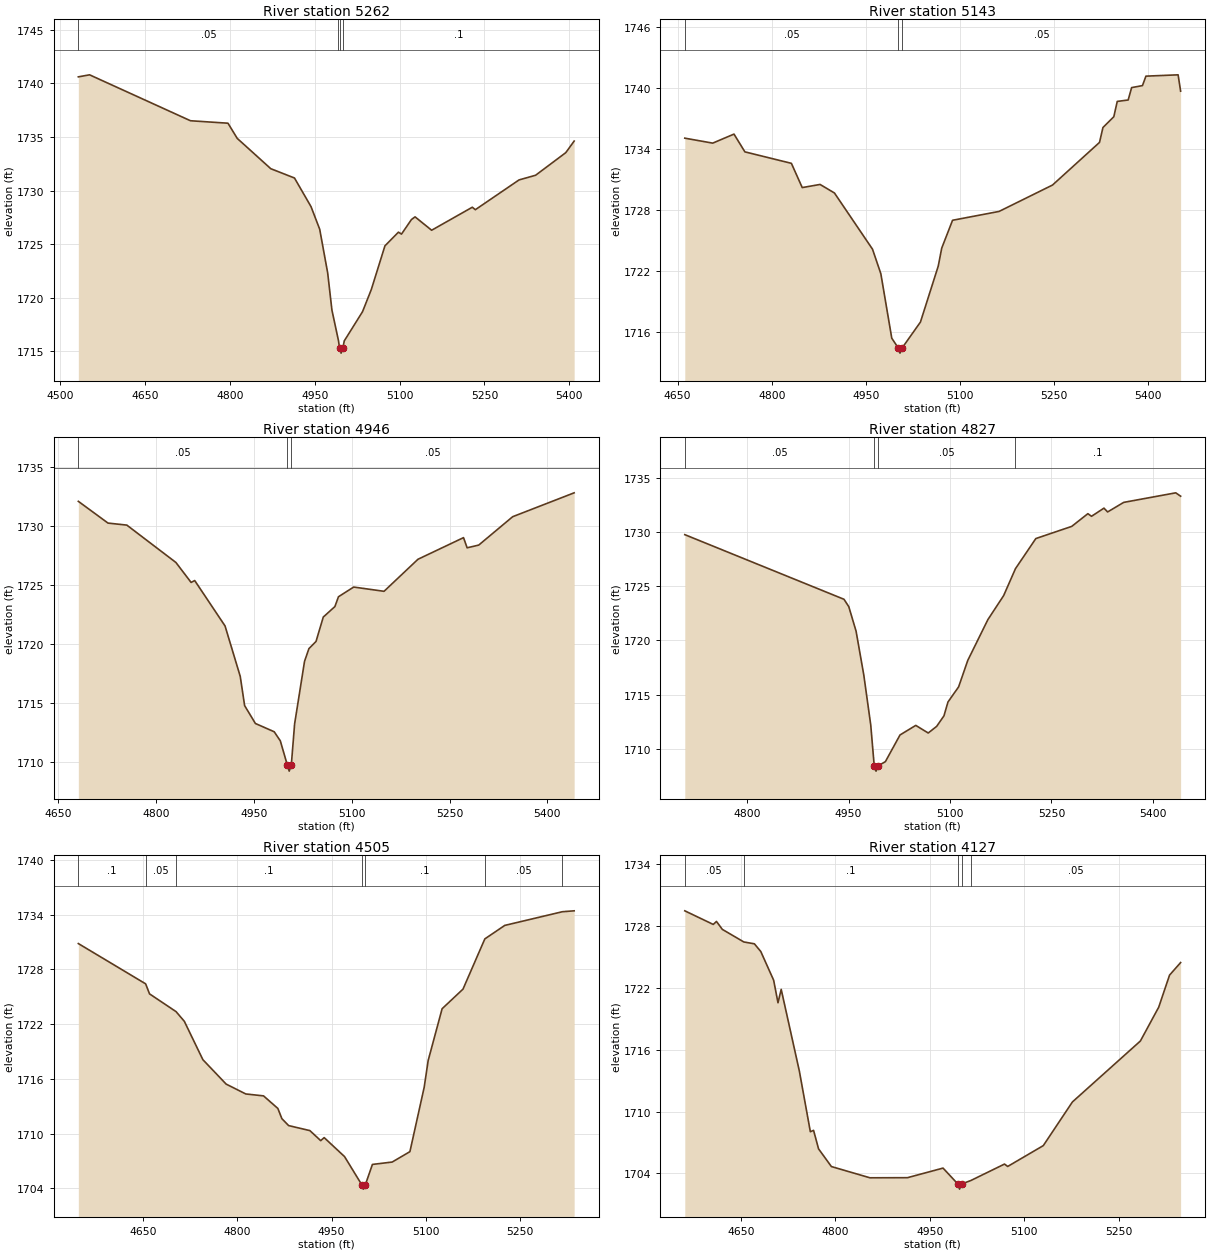
Type RM Length L Ch R = 1 ,5262    ,119,119,119
BEGIN DESCRIPTION:
PECAN CREEK 2 10.0
END DESCRIPTION:
XS GIS Cut Line= 2
       2756950.5     10034148.39       2756616.7     10033337.73
#Sta/Elev= 30
    4532 1740.62  4551.9 1740.81  4730.3 1736.52  4796.6 1736.29    4813 1734.87
  4872.3 1732.04  4914.2 1731.17  4943.5 1728.49  4958.8 1726.38  4972.9  1722.3
  4980.4 1718.83    4992 1715.97  4993.8 1715.31  4996.6 1714.81  4999.8 1715.31
  5002.2 1715.95  5034.5 1718.68  5050.1 1720.76  5074.1 1724.83    5098 1726.11
  5103.4 1725.93    5121 1727.29  5127.4 1727.54  5156.7 1726.29  5228.6 1728.44
    5234 1728.21  5311.2 1730.99  5340.6 1731.43  5393.9 1733.54  5408.7 1734.62
#Mann= 4 ,-1 , 0
    4532     .05       0    4992      .1       0  4993.8     .07       0
  4999.8      .1       0
Bank Sta=4993.8,4999.8
XS Rating Curve= 0 ,0
Exp/Cntr=0.3,0.1

Type RM Length L Ch R = 1 ,5143    ,197,197,197
BEGIN DESCRIPTION:
Mapping XS e03deb2c
END DESCRIPTION:
XS GIS Cut Line= 2
       2757024.3     10033974.82       2756690.1     10033258.67
#Sta/Elev= 30
  4661.4 1735.08  4705.9 1734.59  4739.8 1735.48  4757.2 1733.73  4831.3  1732.6
  4848.6 1730.21    4877 1730.52  4899.9 1729.68  4960.6 1724.14  4973.9 1721.72
  4991.3 1715.37  5001.7  1714.4  5004.4  1713.9  5007.7  1714.4    5037 1716.96
  5065.4 1722.48  5070.9 1724.24  5088.2 1726.99  5162.3 1727.86  5247.5 1730.46
  5322.4 1734.66  5327.9 1736.13  5345.2 1737.19  5350.7  1738.7  5368.1 1738.84
  5373.6 1740.06  5390.9 1740.26  5396.4 1741.19  5447.7 1741.32  5451.7 1739.71
#Mann= 3 ,-1 , 0
  4661.4     .05       0  5001.7     .04       0  5007.7     .05       0
Bank Sta=5001.7,5007.7
XS Rating Curve= 0 ,0
Exp/Cntr=0.3,0.1

Type RM Length L Ch R = 1 ,4946    ,119,119,119
BEGIN DESCRIPTION:
Mapping XS 55688d1c
END DESCRIPTION:
XS GIS Cut Line= 2
      2757193.56     10033896.67      2756885.42     10033202.26
#Sta/Elev= 30
  4681.3 1732.09  4726.8 1730.25  4755.6 1730.08  4830.8 1726.92  4854.1 1725.23
  4859.6 1725.39  4906.1 1721.55  4929.4 1717.28  4936.1 1714.81  4952.6  1713.3
  4981.4  1712.6  4990.8 1711.83  5001.6 1709.77  5004.4 1709.27  5007.6 1709.77
  5012.7 1713.27  5027.9 1718.56  5034.6 1719.63  5045.5 1720.24  5056.6  1722.3
  5074.4 1723.19  5079.9 1724.02  5103.2 1724.84  5149.7 1724.48  5201.7 1727.19
  5271.5 1729.02    5277 1728.16  5294.8 1728.39  5346.8 1730.79    5441 1732.81
#Mann= 3 ,-1 , 0
  4681.3     .05       0  5001.6     .04       0  5007.6     .05       0
Bank Sta=5001.6,5007.6
XS Rating Curve= 0 ,0
Exp/Cntr=0.3,0.1

Type RM Length L Ch R = 1 ,4827    ,322,322,322
BEGIN DESCRIPTION:
Mapping XS 885323b6
END DESCRIPTION:
XS GIS Cut Line= 2
      2757293.41     10033857.65      2757011.29     10033180.57
#Sta/Elev= 30
  4707.7 1729.74  4943.2 1723.79  4950.3 1723.11  4961.1 1720.85  4972.5 1716.82
  4982.8 1712.21  4987.9 1708.47  4990.6 1707.97  4993.9 1708.47  5004.4 1708.84
  5026.1  1711.3  5049.4 1712.18  5067.8 1711.48  5080.3 1712.09  5091.1 1713.06
    5097 1714.33  5112.8 1715.73  5126.3 1718.16  5156.1 1721.92  5179.4 1724.13
  5196.9 1726.61    5227 1729.38  5280.1  1730.5    5304 1731.67  5309.4 1731.43
  5327.8 1732.18  5333.2 1731.83    5357 1732.71    5434 1733.59  5441.2 1733.28
#Mann= 4 ,-1 , 0
  4707.7     .05       0  4987.9     .04       0  4993.9     .05       0
  5196.9      .1       0
Bank Sta=4987.9,4993.9
XS Rating Curve= 0 ,0
Exp/Cntr=0.3,0.1

Type RM Length L Ch R = 1 ,4505    ,378,378,378
BEGIN DESCRIPTION:
PECAN CREEK 2 9.0
END DESCRIPTION:
XS GIS Cut Line= 2
      2757649.31     10033835.94      2757310.77     10033124.15
#Sta/Elev= 30
  4547.4 1730.84  4654.4 1726.42  4660.6 1725.32  4702.8 1723.37  4715.9 1722.31
  4745.4  1718.1  4782.4 1715.42  4813.6 1714.34  4841.8 1714.13  4864.6 1712.75
    4871 1711.63  4881.7 1710.87  4915.5 1710.32  4932.7 1709.22  4938.2 1709.55
  4970.6 1707.47  4997.8  1704.4  5000.6  1703.9  5003.8  1704.4  5014.9 1706.61
  5046.3 1706.87  5074.5 1708.01  5097.2 1715.07  5103.5    1718  5125.7 1723.69
  5158.9 1725.84  5193.6 1731.35  5225.3 1732.83  5316.8 1734.33  5335.6 1734.43
#Mann= 7 ,-1 , 0
  4547.4      .1       0  4654.4     .05       0  4702.8      .1       0
  4997.8     .07       0  5003.8      .1       0  5193.6     .05       0
  5316.8      .1       0
Bank Sta=4997.8,5003.8
XS Rating Curve= 0 ,0
Exp/Cntr=0.3,0.1

Type RM Length L Ch R = 1 ,4127    ,462,462,462
BEGIN DESCRIPTION:
PECAN CREEK 2 8.0
END DESCRIPTION:
XS GIS Cut Line= 2
      2757892.36     10033762.18      2757740.45     10032989.57
#Sta/Elev= 30
  4561.1 1729.47  4606.3 1728.15  4611.4 1728.44  4620.7 1727.67  4654.8 1726.45
  4671.6 1726.27  4681.8 1725.52  4702.2 1722.74  4709.1 1720.55  4714.2 1721.85
    4743 1713.93  4760.5 1708.04  4765.6 1708.17  4773.5 1706.38  4793.9 1704.66
  4855.1 1703.57  4914.7 1703.58  4971.2 1704.51  4994.7 1702.97  4997.5 1702.47
  5000.7 1702.97  5015.2  1703.3  5068.8  1704.9  5073.9 1704.67  5130.4 1706.69
  5176.7 1710.93  5284.6 1716.84  5313.7 1720.12  5330.9 1723.23  5348.5 1724.45
#Mann= 5 ,-1 , 0
  4561.1     .05       0  4654.8      .1       0  4994.7     .07       0
  5000.7      .1       0  5015.2     .05       0
Bank Sta=4994.7,5000.7
XS Rating Curve= 0 ,0
Exp/Cntr=0.3,0.1

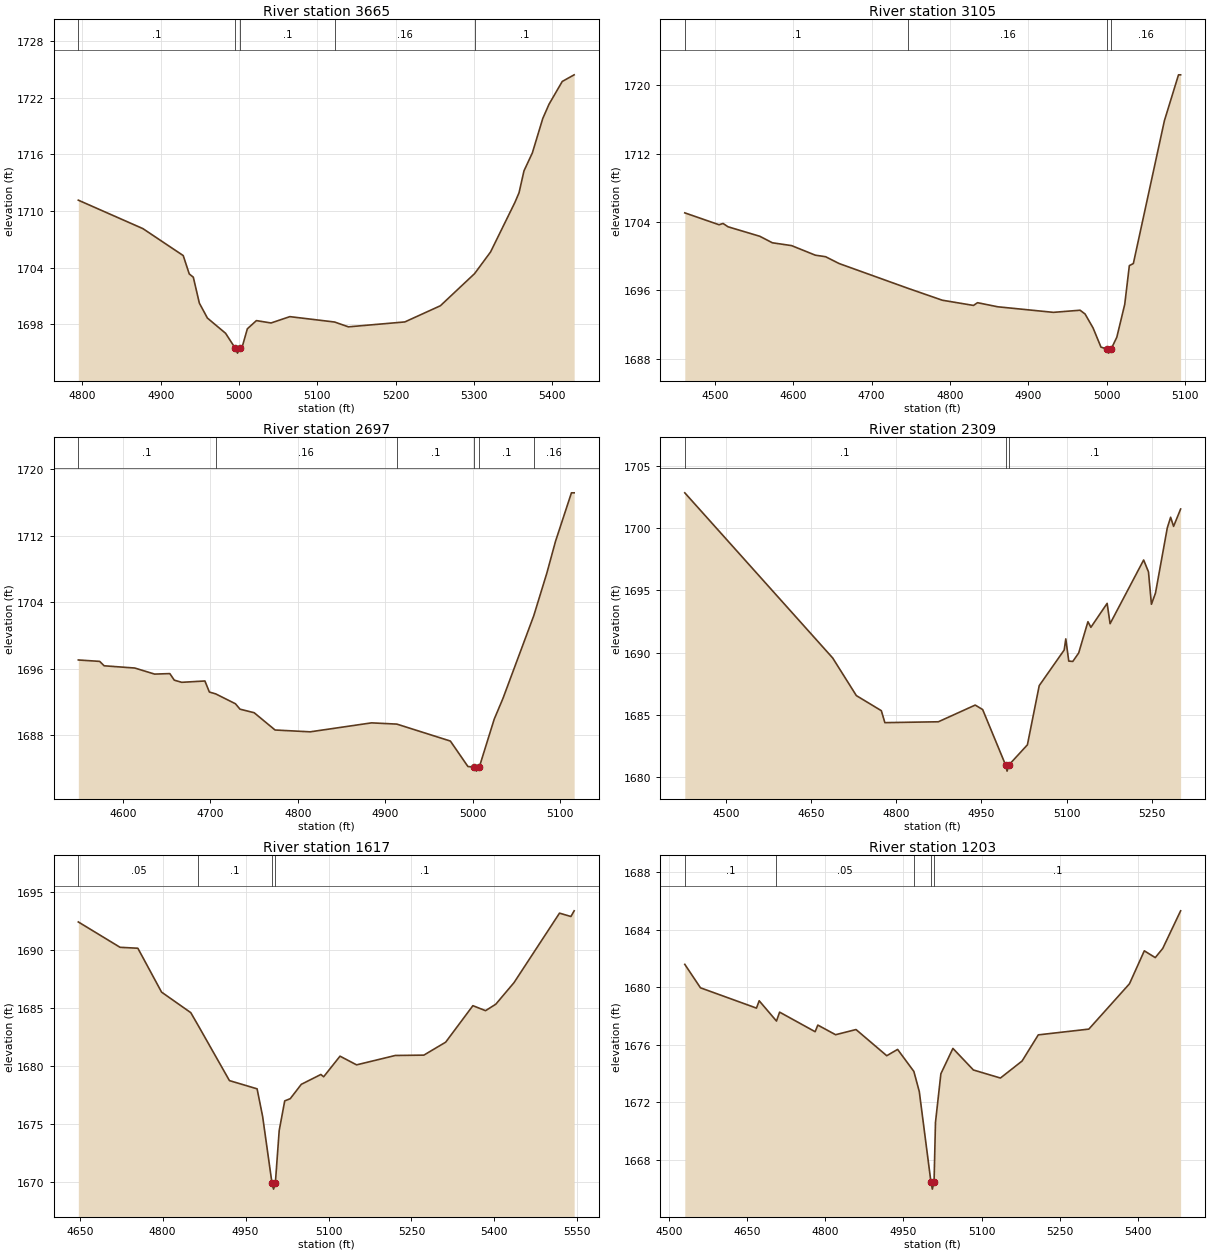
Type RM Length L Ch R = 1 ,3665    ,560,560,560
BEGIN DESCRIPTION:
PECAN CREEK 2 7.0
END DESCRIPTION:
XS GIS Cut Line= 3
      2758268.47     10033553.73      2758218.47     10033353.73
      2758068.45     10032953.69
#Sta/Elev= 30
  4794.8 1711.15  4877.3 1708.14  4928.8 1705.29  4936.5 1703.35  4941.7    1703
  4949.4 1700.26  4959.7 1698.68  4982.9 1697.07  4995.4 1695.47  4998.1 1694.97
  5001.4 1695.47  5003.6 1695.47  5010.7 1697.54  5022.3 1698.41    5041 1698.16
    5065 1698.83  5122.2 1698.26  5139.8 1697.75  5211.9 1698.27  5257.3 1699.98
    5301 1703.38  5321.4 1705.67  5352.5 1710.91  5357.8 1711.94  5364.1 1714.25
  5374.8 1716.15  5388.1 1719.79  5396.1  1721.3    5413 1723.71  5428.2 1724.41
#Mann= 5 ,-1 , 0
  4794.8      .1       0  4995.4     .07       0  5001.4      .1       0
  5122.2     .16       0    5301      .1       0
Bank Sta=4995.4,5001.4
XS Rating Curve= 0 ,0
Exp/Cntr=0.3,0.1

Type RM Length L Ch R = 1 ,3105    ,408,408,408
BEGIN DESCRIPTION:
PECAN CREEK 2 6.0
END DESCRIPTION:
XS GIS Cut Line= 2
      2758500.76      10033488.3      2758403.54     10032863.31
#Sta/Elev= 30
  4461.8 1705.06  4505.5 1703.67  4510.6 1703.82    4517 1703.43  4557.5 1702.32
  4573.5 1701.56    4598 1701.23  4628.3 1700.11  4641.4 1699.93  4658.7 1699.13
  4746.9 1696.22  4790.3 1694.84  4830.1 1694.23  4835.2 1694.55  4861.1 1694.07
    4932 1693.42    4966 1693.67  4972.4 1693.23  4982.6  1691.6  4992.7 1689.35
  4999.8 1689.15  5002.5 1688.65  5005.8 1689.15  5012.9 1690.51    5023 1694.35
  5028.9 1698.89    5034 1699.13  5073.6 1715.84  5091.6 1721.21  5094.3 1721.21
#Mann= 4 ,-1 , 0
  4461.8      .1       0  4746.9     .16       0  4999.8     .07       0
  5005.8     .16       0
Bank Sta=4999.8,5005.8
XS Rating Curve= 0 ,0
Exp/Cntr=0.3,0.1

Type RM Length L Ch R = 1 ,2697    ,388,388,388
BEGIN DESCRIPTION:
PECAN CREEK 2 5.0
END DESCRIPTION:
XS GIS Cut Line= 3
      2758716.05     10033397.98      2758799.37     10033085.52
      2758813.26      10032842.5
#Sta/Elev= 30
    4549 1697.04  4573.4 1696.87  4578.5 1696.34  4613.5 1696.07  4636.2 1695.34
  4653.6  1695.4  4658.7 1694.61  4667.2 1694.35  4693.7 1694.51  4698.8 1693.18
    4706 1692.96  4728.6 1691.77  4733.8 1691.12    4750 1690.69  4773.9 1688.61
    4814 1688.39  4884.2 1689.47  4913.1 1689.32  4974.3 1687.28  4994.4 1684.21
  5001.4 1684.16  5004.1 1683.66  5007.4 1684.16  5024.4 1689.91  5034.4 1692.41
  5069.6 1702.36  5084.5 1707.47  5094.5 1711.33  5112.7 1717.16  5115.8 1717.16
#Mann= 6 ,-1 , 0
    4549      .1       0    4706     .16       0  4913.1      .1       0
  5001.4     .07       0  5007.4      .1       0  5069.6     .16       0
Bank Sta=5001.4,5007.4
XS Rating Curve= 0 ,0
Exp/Cntr=0.3,0.1

Type RM Length L Ch R = 1 ,2309    ,692,692,692
BEGIN DESCRIPTION:
PECAN CREEK 2 4.0
END DESCRIPTION:
XS GIS Cut Line= 3
      2758778.53      10033627.2      2759174.37     10033085.52
      2759118.82      10032891.1
#Sta/Elev= 30
  4427.7 1702.83  4688.1 1689.58  4729.8 1686.56  4773.8 1685.35    4780 1684.39
  4874.2 1684.46  4939.1  1685.8  4952.2 1685.44  4992.5    1681  4995.2  1680.5
  4998.5    1681    5031 1682.61  5051.8 1687.36  5095.8 1690.22  5098.6 1691.11
  5103.8 1689.33  5110.9  1689.3  5121.3 1689.98  5137.6 1692.49  5142.8 1692.04
  5171.4 1693.96  5176.6 1692.33  5235.7 1697.44  5244.2 1696.49  5249.4 1693.89
  5256.5 1694.78  5277.3 1700.01  5283.2 1700.87  5288.4 1700.14  5300.8 1701.53
#Mann= 3 ,-1 , 0
  4427.7      .1       0  4992.5     .07       0  4998.5      .1       0
Bank Sta=4992.5,4998.5
XS Rating Curve= 0 ,0
Exp/Cntr=0.3,0.1

Type RM Length L Ch R = 1 ,1617    ,414,414,414
BEGIN DESCRIPTION:
PECAN CREEK 2 3.0
END DESCRIPTION:
XS GIS Cut Line= 4
      2759441.53     10033914.07      2759510.98      10033736.1
      2759515.32     10033302.07       2759450.4     10033038.03
#Sta/Elev= 30
  4647.4 1692.44  4722.9 1690.25  4755.1 1690.17    4798 1686.38  4850.8 1684.61
  4864.6 1683.47  4920.8 1678.74  4970.8 1678.03  4980.8 1675.65  4997.8 1669.87
  5000.6 1669.37  5003.8 1669.87  5010.8 1674.43  5020.8 1676.99  5030.8 1677.18
  5050.8 1678.42  5086.2 1679.27  5091.2 1679.07  5120.8 1680.85  5150.8  1680.1
  5220.8 1680.91  5272.5 1680.94    5312 1682.06  5361.2 1685.21  5384.1 1684.78
  5402.7 1685.34  5435.6  1687.2  5517.9  1693.2  5538.5 1692.91  5544.4  1693.4
#Mann= 4 ,-1 , 0
  4647.4     .05       0  4864.6      .1       0  4997.8     .07       0
  5003.8      .1       0
Bank Sta=4997.8,5003.8
XS Rating Curve= 0 ,0
Exp/Cntr=0.3,0.1

Type RM Length L Ch R = 1 ,1203    ,521,521,521
BEGIN DESCRIPTION:
PECAN CREEK 2 2.0
END DESCRIPTION:
XS GIS Cut Line= 3
      2760031.81     10033927.04      2759823.48     10033184.88
      2759685.18     10033068.19
#Sta/Elev= 30
  4530.2 1681.59  4560.3 1679.96  4667.8 1678.55    4673 1679.06  4706.2 1677.65
  4712.2 1678.27  4780.4 1676.91  4785.6 1677.37  4819.7  1676.7  4858.9 1677.06
  4917.9 1675.24  4938.7 1675.68  4969.9 1674.15  4980.3 1672.76  5002.7 1666.47
  5005.4 1665.97  5008.7 1666.47  5011.4  1670.6  5021.8 1673.99  5044.9 1675.75
  5084.2 1674.25  5136.1 1673.69  5177.6 1674.87  5208.8 1676.69  5305.8 1677.09
  5383.8 1680.24  5412.3 1682.53  5433.3 1682.06  5447.6 1682.69    5482 1685.31
#Mann= 5 ,-1 , 0
  4530.2      .1       0  4706.2     .05       0  4969.9      .1       0
  5002.7     .07       0  5008.7      .1       0
Bank Sta=5002.7,5008.7
XS Rating Curve= 0 ,0
Exp/Cntr=0.3,0.1

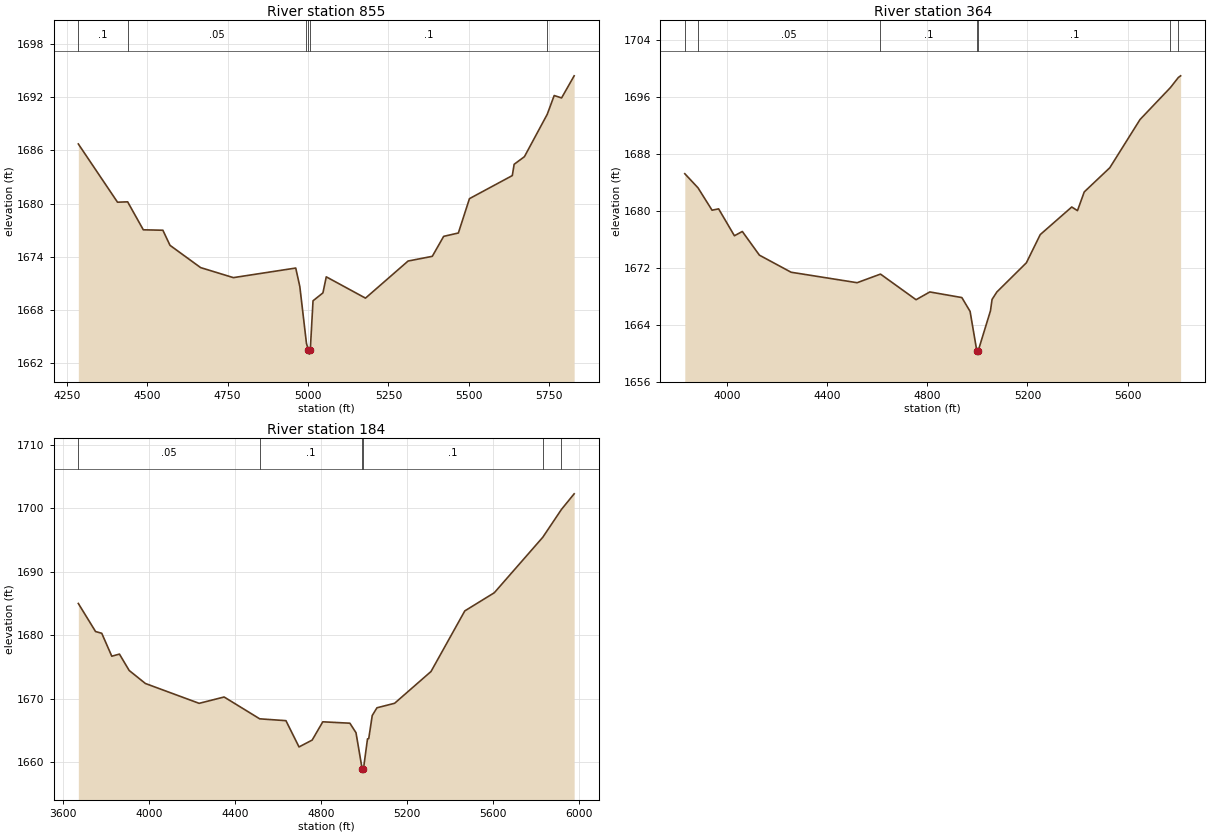
Type RM Length L Ch R = 1 ,855     ,491,491,491
BEGIN DESCRIPTION:
Mapping XS 43f0af70
END DESCRIPTION:
XS GIS Cut Line= 4
      2760130.86     10034118.17       2760281.9      10033584.3
      2760198.57     10033230.14      2759654.31     10032925.45
#Sta/Elev= 30
  4285.4 1686.71  4407.3 1680.15  4438.8 1680.19  4487.5 1677.04  4548.4 1676.99
  4570.6 1675.29  4665.8 1672.78  4767.7 1671.65  4961.7 1672.73  4974.4 1670.65
  4995.1 1664.23    5001 1663.53  5003.8 1663.03    5007 1663.53  5015.5 1669.04
  5046.3 1669.93  5056.7 1671.74  5178.7 1669.34  5311.2 1673.52  5386.5 1674.05
  5421.9  1676.3  5467.6 1676.68  5502.1 1680.55  5635.4 1683.15  5641.1 1684.42
  5673.1 1685.28    5744 1690.05  5765.7 1692.17  5788.7  1691.9  5827.8 1694.39
#Mann= 6 ,-1 , 0
  4285.4      .1       0  4438.8     .05       0  4995.1      .1       0
    5001     .07       0    5007      .1       0    5744     .05       0
Bank Sta=5001,5007
XS Rating Curve= 0 ,0
Exp/Cntr=0.3,0.1

Type RM Length L Ch R = 1 ,364     ,180,180,180
BEGIN DESCRIPTION:
Mapping XS 61908189
END DESCRIPTION:
XS GIS Cut Line= 4
      2760180.35     10034136.37      2760474.61     10033258.78
       2760341.8     10032964.51      2759643.92     10032743.17
#Sta/Elev= 30
  3831.1 1685.24  3883.8 1683.26    3940 1680.11  3966.2  1680.3  4029.3 1676.52
  4060.9 1677.12  4129.2 1673.79  4255.8 1671.39  4519.5 1669.92  4612.8 1671.13
  4754.9 1667.53  4809.9 1668.62  4937.8 1667.83  4970.7 1665.89  4997.4 1660.38
  5000.1 1659.88  5003.4 1660.38  5052.1 1665.97  5058.5 1667.57  5077.5 1668.61
  5195.6 1672.72  5250.9 1676.68  5376.8 1680.56  5399.7 1680.05  5426.7 1682.68
  5528.8 1686.08  5649.6 1692.86    5771 1697.35  5802.7 1698.77  5811.7    1699
#Mann= 7 ,-1 , 0
  3831.1      .1       0  3883.8     .05       0  4612.8      .1       0
  4997.4     .07       0  5003.4      .1       0    5771     .05       0
  5802.7      .1       0
Bank Sta=4997.4,5003.4
XS Rating Curve= 0 ,0
Exp/Cntr=0.3,0.1

Type RM Length L Ch R = 1 ,184     ,0,0,0
BEGIN DESCRIPTION:
PECAN CREEK 2 1.0
END DESCRIPTION:
XS GIS Cut Line= 4
       2760229.8     10034139.03      2760643.88     10033196.28
      2760432.94     10032800.45      2759646.44      10032532.2
#Sta/Elev= 30
  3670.2 1685.01  3750.4 1680.59  3779.3 1680.31    3826  1676.7  3861.7 1677.03
    3907 1674.45  3982.5  1672.4    4233 1669.27  4349.2 1670.27  4514.9 1666.83
  4637.1 1666.54    4698  1662.4  4759.2 1663.48  4808.7 1666.36  4934.9 1666.14
  4963.4 1664.64  4992.1 1658.93  4994.8 1658.43  4998.1 1658.93    5017 1663.67
  5022.7 1663.71    5039 1667.35    5061 1668.57  5143.2 1669.28  5312.8 1674.29
  5470.1 1683.84  5607.5  1686.7  5833.2 1695.44  5920.2 1699.83  5979.4 1702.29
#Mann= 6 ,-1 , 0
  3670.2     .05       0  4514.9      .1       0  4992.1     .07       0
  4998.1      .1       0  5833.2     .05       0  5920.2      .1       0
Bank Sta=4992.1,4998.1
XS Rating Curve= 0 ,0
Exp/Cntr=0.3,0.1

Chan Stop Cuts=-1
Use User Specified Reach Order=0
Composite Channel Slope=5