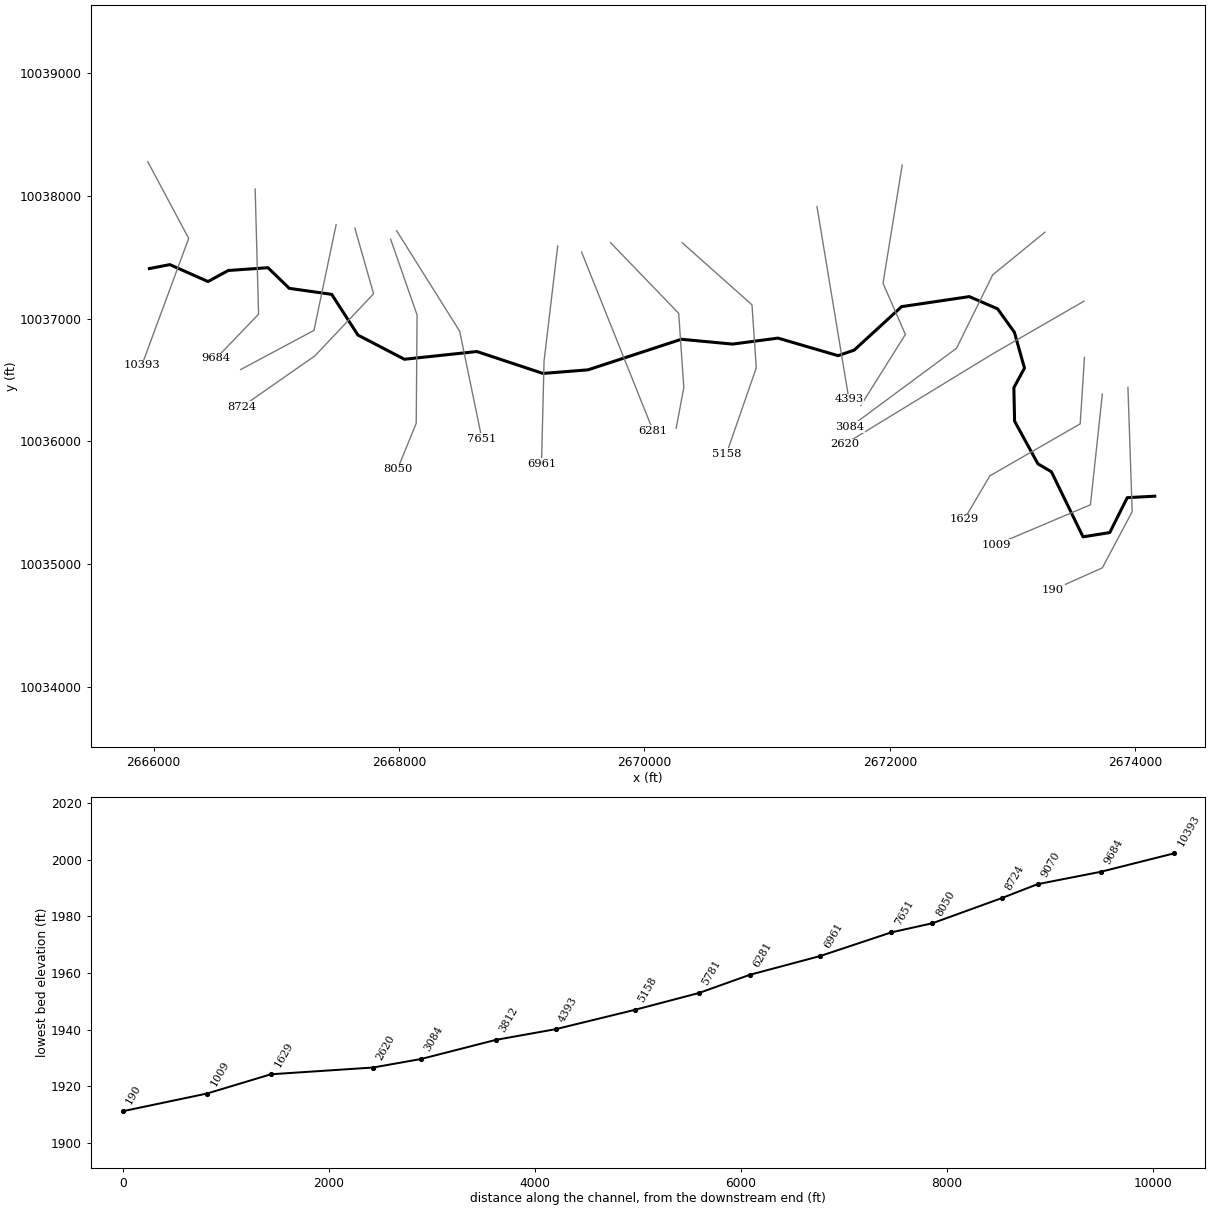
--- SPANISH OAK CREEK.prj (project) ---

Proj Title=SPANISH OAK CREEK Base Level Engineering
Current Plan=p01
Default Exp/Contr=0.3,0.1
English Units
Geom File=g01
Flow File=f01
Plan File=p01
Y Axis Title=Elevation
X Axis Title(PF)=Main Channel Distance
X Axis Title(XS)=Station
BEGIN DESCRIPTION:
SPANISH OAK CREEK
END DESCRIPTION:
DSS Export Rating Curves= 0
DSS Export Rating Curve Sorted= 0
DSS Export Volume Flow Curves= 0
DXF OffsetX= 0
DXF OffsetY= 0
DXF ScaleX= 1
DXF ScaleY= 10

--- SPANISH OAK CREEK.p01 (plan) ---

Plan Title=Multiple Run
Short Identifier=Multiple
Geom File=g01
Flow File=f01
Subcritical Flow
K Sum by GR= 0
Std Step Tol= 0.01
Critical Tol= 0.01
Num of Std Step Trials= 20
Max Error Tol= 0.3
Flow Tol Ratio= 0.001
Split Flow NTrial= 30
Split Flow Tol= 0.02
Split Flow Ratio= 0.02
Log Output Level= 0
Friction Slope Method= 1
Unsteady Friction Slope Method= 2
Unsteady Bridges Friction Slope Method= 1
Parabolic Critical Depth
Global Vel Dist=  1 , 1 , 1
Global Log Level= 0
CheckData=True
Encroach Param= -1, 0, 0, 0
BEGIN DESCRIPTION:
Multiple Run
END DESCRIPTION:

--- SPANISH OAK CREEK.f01 (steady flow) ---

Flow Title=Multiple
Number of Profiles=7
Profile Names=10-year,25-year,50-year,1pct_min,100-year,1pct_plu,500-year
River Rch & RM= SPANISH OAK CREE,Reach-1,10393
    1056    1524    1926    1774    2399    3244    3719
River Rch & RM= SPANISH OAK CREE,Reach-1,9684
    1584    2338    2997    2796    3781    5113    6020
River Rch & RM= SPANISH OAK CREE,Reach-1,4393
    2264    3396    4400    4143    5603    7578    9095
Boundary for River Rch & Prof#=SPANISH OAK CREE,Reach-1,1
Up Type=0
Dn Type=3
Dn Slope=0.005
Boundary for River Rch & Prof#=SPANISH OAK CREE,Reach-1,2
Up Type=0
Dn Type=3
Dn Slope=0.005
Boundary for River Rch & Prof#=SPANISH OAK CREE,Reach-1,3
Up Type=0
Dn Type=3
Dn Slope=0.005
Boundary for River Rch & Prof#=SPANISH OAK CREE,Reach-1,4
Up Type=0
Dn Type=3
Dn Slope=0.005
Boundary for River Rch & Prof#=SPANISH OAK CREE,Reach-1,5
Up Type=0
Dn Type=3
Dn Slope=0.005
Boundary for River Rch & Prof#=SPANISH OAK CREE,Reach-1,6
Up Type=0
Dn Type=3
Dn Slope=0.005
Boundary for River Rch & Prof#=SPANISH OAK CREE,Reach-1,7
Up Type=0
Dn Type=3
Dn Slope=0.005

--- SPANISH OAK CREEK.g01 (geometry) ---

Geom Title=Existing Conditions
Program Version=4.10

River Reach=SPANISH OAK CREE,Reach-1
Reach XY= 30
      2665966.05     10037409.52      2666132.47     10037441.64
      2666443.43     10037303.69      2666608.47     10037393.73
      2666932.16     10037416.49      2667105.59     10037248.18
      2667451.48     10037199.13      2667665.04     10036867.39
      2668043.83     10036670.09      2668634.44     10036733.06
      2669173.22     10036554.45      2669539.44     10036583.75
      2670300.48     10036832.91      2670718.49     10036793.71
      2671087.88     10036842.44      2671577.64     10036699.43
      2671708.69     10036744.33       2672095.7     10037099.03
      2672647.27     10037180.85      2672877.66       10037081.
      2673014.44     10036890.32      2673096.77     10036597.87
      2673010.27     10036438.44      2673016.14     10036165.53
      2673206.39     10035817.35      2673316.06     10035752.96
      2673573.97     10035222.27      2673791.82     10035257.12
      2673934.17     10035541.64      2674158.47     10035553.73

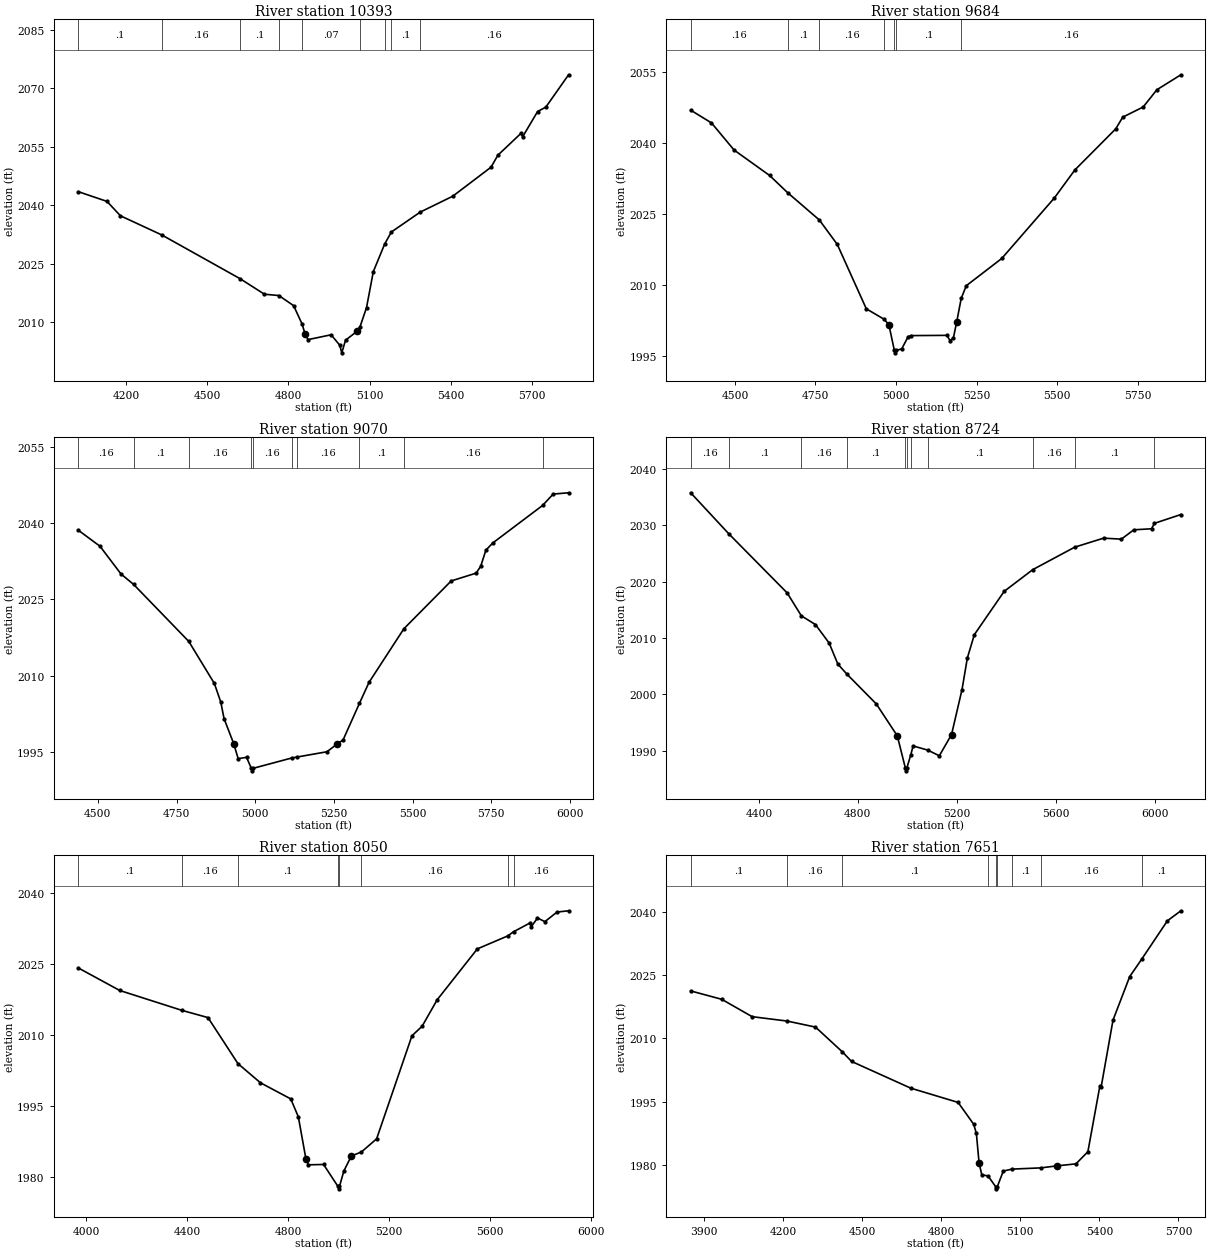
Type RM Length L Ch R = 1 ,10393   ,709,709,709
BEGIN DESCRIPTION:
SPANISH OAK CREEK 22.0
END DESCRIPTION:
XS GIS Cut Line= 3
      2665952.72     10038280.39      2666286.04     10037655.42
      2665904.08     10036620.66
#Sta/Elev= 30
  4023.9  2043.5  4129.8    2041  4179.3 2037.32  4332.5 2032.39  4621.8 2021.17
  4711.4  2017.2  4764.5 2016.87  4819.3 2014.27  4850.5 2009.55  4861.9 2006.94
  4872.6 2005.56  4957.8  2006.8  4989.8 2004.12  4997.1 2002.17  5011.1 2005.41
  5052.9 2007.66  5064.4 2008.81  5088.6 2013.76  5113.7    2023  5155.8 2030.09
  5180.4 2033.16    5287 2038.26  5407.3 2042.34  5548.8 2049.79  5573.9 2052.85
  5659.9  2058.5  5665.2 2057.55  5720.7 2064.05  5751.2 2065.19  5835.2 2073.48
#Mann= 9 ,-1 , 0
  4023.9      .1       0  4332.5     .16       0  4621.8      .1       0
  4764.5     .16       0  4850.5     .07       0  5064.4      .1       0
  5155.8     .16       0  5180.4      .1       0    5287     .16       0
Bank Sta=4861.9,5052.9
XS Rating Curve= 0 ,0
Exp/Cntr=0.3,0.1

Type RM Length L Ch R = 1 ,9684    ,614,614,614
BEGIN DESCRIPTION:
SPANISH OAK CREEK 21.0
END DESCRIPTION:
XS GIS Cut Line= 3
      2666827.71     10038058.22      2666855.48     10037037.36
      2666509.44     10036677.48
#Sta/Elev= 30
  4362.9 2046.92  4427.4 2044.23  4497.4 2038.51  4607.5 2033.14  4663.6  2029.5
  4761.9 2023.74  4817.6 2018.58  4907.6 2004.99  4962.3  2002.8  4977.6 2001.65
  4994.6 1996.19  4997.4 1995.69  5000.6 1996.19  5017.6 1996.54  5037.6 1999.13
  5047.6 1999.33  5157.7 1999.38  5167.7 1998.24  5177.7 1998.84  5187.7 2002.11
    5202 2007.19  5217.7 2009.86  5327.7 2015.61  5490.6 2028.36  5554.4 2034.29
  5681.5 2042.99  5702.9 2045.44  5766.4 2047.59  5808.9 2051.23  5883.4 2054.39
#Mann= 7 ,-1 , 0
  4362.9     .16       0  4663.6      .1       0  4761.9     .16       0
  4962.3      .1       0  4994.6     .07       0  5000.6      .1       0
    5202     .16       0
Bank Sta=4977.6,5187.7
XS Rating Curve= 0 ,0
Exp/Cntr=0.3,0.1

Type RM Length L Ch R = 1 ,9070    ,346,346,346
BEGIN DESCRIPTION:
SPANISH OAK CREEK 19.0
END DESCRIPTION:
XS GIS Cut Line= 3
      2667487.43     10037766.53      2667306.87     10036905.42
      2666709.68     10036585.99
#Sta/Elev= 30
  4438.2  2038.6  4506.9 2035.46  4573.9 2029.99  4613.5 2027.97    4789 2016.75
  4870.2 2008.49  4890.6 2004.83    4901 2001.58  4931.5 1996.68  4945.8 1993.72
  4972.4 1993.97  4987.6 1991.82  4990.4 1991.32  4993.6 1991.82  5115.6 1993.84
  5131.6 1994.02  5227.8 1995.07  5258.5 1996.52  5278.9 1997.38  5330.9 2004.57
  5361.6 2008.73  5472.3 2019.26  5622.4 2028.64  5701.8 2030.18  5716.3 2031.55
  5732.6 2034.69  5754.6 2036.11  5912.5 2043.47  5946.4 2045.72  5995.3 2045.97
#Mann= 10 ,-1 , 0
  4438.2     .16       0  4613.5      .1       0    4789     .16       0
  4987.6     .07       0  4993.6     .16       0  5115.6      .1       0
  5131.6     .16       0  5330.9      .1       0  5472.3     .16       0
  5912.5      .1       0
Bank Sta=4931.5,5258.5
XS Rating Curve= 0 ,0
Exp/Cntr=0.3,0.1

Type RM Length L Ch R = 1 ,8724    ,674,674,674
BEGIN DESCRIPTION:
SPANISH OAK CREEK 18.0
END DESCRIPTION:
XS GIS Cut Line= 4
      2667640.21     10037738.74      2667792.98     10037204.03
      2667313.82     10036697.08      2666716.58      10036280.4
#Sta/Elev= 30
  4124.4 2035.78  4278.9 2028.48  4514.4 2018.01  4571.9 2013.94  4628.8 2012.39
  4684.2 2009.11  4719.4 2005.37  4756.3 2003.58  4874.7 1998.31  4959.7 1992.64
  4992.3 1986.93    4995 1986.43  4998.3 1986.93  5014.3 1989.28  5023.6 1990.85
  5082.8 1990.11  5129.6  1989.1    5179 1992.87  5221.4 2000.86  5242.9 2006.46
  5271.2  2010.6  5391.7 2018.28  5507.4 2022.14  5677.1 2026.13  5793.9 2027.73
  5865.4 2027.55    5916 2029.21  5987.5 2029.39  5999.4 2030.36  6106.3 2031.92
#Mann= 11 ,-1 , 0
  4124.4     .16       0  4278.9      .1       0  4571.9     .16       0
  4756.3      .1       0  4992.3     .07       0  4998.3      .1       0
  5014.3     .16       0  5082.8      .1       0  5507.4     .16       0
  5677.1      .1       0  5999.4     .16       0
Bank Sta=4959.7,5179
XS Rating Curve= 0 ,0
Exp/Cntr=0.3,0.1

Type RM Length L Ch R = 1 ,8050    ,399,399,399
BEGIN DESCRIPTION:
SPANISH OAK CREEK 17.0
END DESCRIPTION:
XS GIS Cut Line= 4
      2667931.88     10037648.44      2668147.15     10037030.42
      2668140.21     10036148.47      2667987.44     10035773.51
#Sta/Elev= 30
  3969.7 2024.15  4133.5  2019.4  4379.4 2015.21    4483 2013.68  4601.6 2003.97
  4690.8 1999.92  4810.8 1996.52  4840.8 1992.74  4870.8 1983.87  4880.8 1982.61
  4940.8 1982.68  4997.8 1978.04  5000.6 1977.54  5003.8 1978.04  5020.8 1981.28
  5050.8 1984.48  5090.4 1985.31  5150.8 1988.09  5290.8 2009.85  5330.8 2011.84
  5390.8 2017.45  5549.7 2028.18  5670.4 2030.92  5692.9 2031.79  5758.3 2033.65
  5763.7 2032.89  5787.8 2034.69  5817.2 2033.93  5865.3 2035.95    5911 2036.22
#Mann= 8 ,-1 , 0
  3969.7      .1       0  4379.4     .16       0  4601.6      .1       0
  4997.8     .07       0  5003.8      .1       0  5090.4     .16       0
  5670.4      .1       0  5692.9     .16       0
Bank Sta=4870.8,5050.8
XS Rating Curve= 0 ,0
Exp/Cntr=0.3,0.1

Type RM Length L Ch R = 1 ,7651    ,690,690,690
BEGIN DESCRIPTION:
SPANISH OAK CREEK 16.0
END DESCRIPTION:
XS GIS Cut Line= 3
      2667980.49     10037717.91      2668494.37     10036898.47
      2668674.93     10036023.45
#Sta/Elev= 30
  3848.9 2021.27  3966.7 2019.28  4082.2 2015.16    4215 2014.12  4322.6 2012.69
  4424.8  2006.8  4459.3 2004.55  4684.3  1998.2    4864 1994.82  4923.1 1989.64
  4933.3 1987.46  4943.5 1980.46  4953.7 1977.69  4977.9 1977.35  5006.7 1974.82
  5009.5 1974.32  5012.7 1974.82  5035.4 1978.53  5067.9    1979  5177.5 1979.29
  5239.6 1979.77  5311.3 1980.25  5356.5 1983.12  5401.7 1998.61  5406.8 1998.44
  5451.9 2014.34  5515.3 2024.67  5561.2 2028.84  5658.3  2037.9  5709.6 2040.28
#Mann= 9 ,-1 , 0
  3848.9      .1       0    4215     .16       0  4424.8      .1       0
  4977.9     .05       0  5006.7    .035       0  5012.7     .05       0
  5067.9      .1       0  5177.5     .16       0  5561.2      .1       0
Bank Sta=4943.5,5239.6
XS Rating Curve= 0 ,0
Exp/Cntr=0.3,0.1

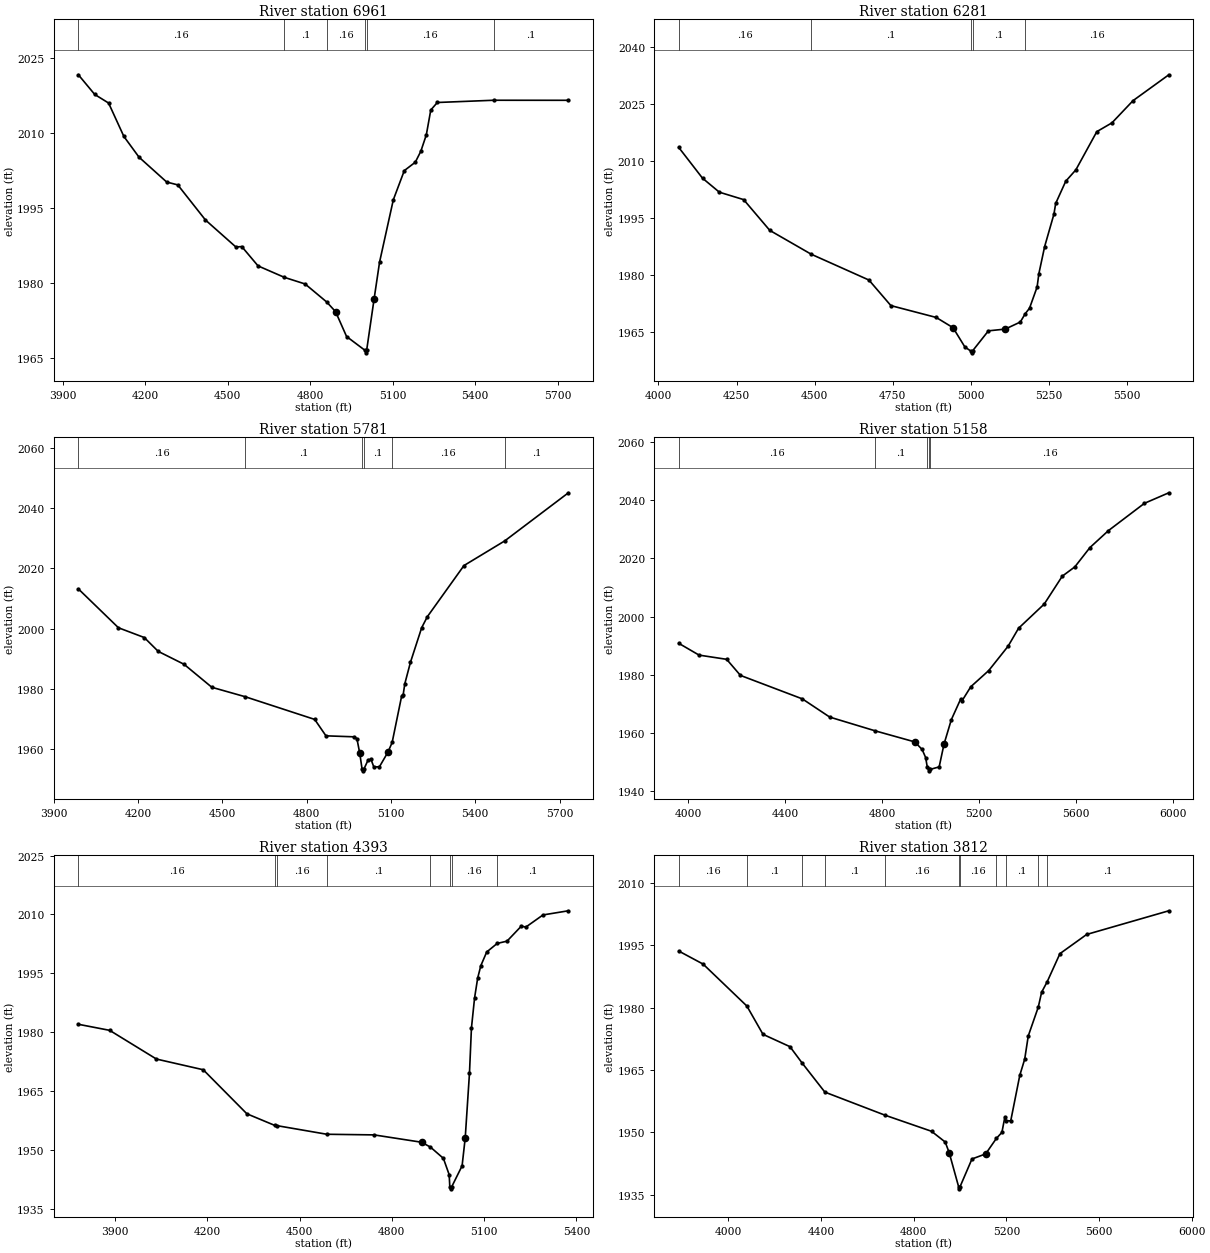
Type RM Length L Ch R = 1 ,6961    ,680,680,680
BEGIN DESCRIPTION:
SPANISH OAK CREEK 14.0
END DESCRIPTION:
XS GIS Cut Line= 3
      2669292.99     10037592.93      2669181.87     10036655.42
      2669161.08     10035816.95
#Sta/Elev= 30
  3956.1 2021.66  4015.7 2017.72  4066.1    2016  4121.7 2009.31  4176.8 2005.16
  4277.5 2000.18  4317.8 1999.61  4418.5 1992.58  4529.3 1987.17  4550.6 1987.26
  4609.8 1983.39  4705.8 1981.09    4781 1979.77  4859.2 1976.18  4891.8 1974.23
  4931.9 1969.25  4998.9 1966.48  5001.6 1965.98  5004.9 1966.48  5031.9 1976.72
  5051.9 1984.15  5101.9 1996.62  5141.9 2002.47  5181.9 2004.15    5202 2006.34
    5222 2009.63  5238.2  2014.6    5262 2016.11  5466.9 2016.56  5738.9 2016.55
#Mann= 6 ,-1 , 0
  3956.1     .16       0  4705.8      .1       0  4859.2     .16       0
  4998.9     .07       0  5004.9     .16       0  5466.9      .1       0
Bank Sta=4891.8,5031.9
XS Rating Curve= 0 ,0
Exp/Cntr=0.3,0.1

Type RM Length L Ch R = 1 ,6281    ,500,500,500
BEGIN DESCRIPTION:
SPANISH OAK CREEK 13.0
END DESCRIPTION:
XS GIS Cut Line= 2
      2669487.42     10037544.32      2670070.21     10036087.35
#Sta/Elev= 30
  4065.1 2013.52  4141.1 2005.43    4195 2001.74  4272.8 1999.78  4356.5 1991.67
  4489.1 1985.39    4674 1978.58  4744.3 1971.84  4889.4 1968.72  4943.3 1966.02
  4981.2 1960.94  4999.7 1959.89  5002.5 1959.39  5005.7 1959.89  5056.6 1965.19
  5110.5 1965.65  5158.7 1967.51  5174.4 1969.69  5188.3 1971.17  5212.5 1976.74
  5218.2 1980.28  5236.7 1987.42  5266.4 1995.95    5272 1998.78  5304.3 2004.64
  5336.6 2007.63  5403.7  2017.7  5452.2 2020.02  5519.7 2025.87  5634.3 2032.69
#Mann= 5 ,-1 , 0
  4065.1     .16       0  4489.1      .1       0  4999.7     .07       0
  5005.7      .1       0  5174.4     .16       0
Bank Sta=4943.3,5110.5
XS Rating Curve= 0 ,0
Exp/Cntr=0.3,0.1

Type RM Length L Ch R = 1 ,5781    ,623,623,623
BEGIN DESCRIPTION:
SPANISH OAK CREEK 12.0
END DESCRIPTION:
XS GIS Cut Line= 4
      2669723.54     10037620.69       2670279.1      10037044.3
      2670320.76     10036440.14      2670258.44     10036107.77
#Sta/Elev= 30
  3987.1 2013.19  4129.9 2000.31  4221.7 1997.08  4271.4 1992.49  4363.2 1988.22
  4462.3 1980.59  4581.5 1977.45  4828.3 1969.95  4868.4 1964.51  4968.6 1964.18
  4978.7 1963.55  4988.7 1958.74  4997.1 1953.41  4999.9 1952.91  5003.1 1953.41
  5018.8 1956.58  5028.8 1956.69  5038.8 1954.19  5058.8 1954.26  5088.9 1959.08
    5104  1962.3  5137.9 1977.72    5143 1977.95  5149.1 1981.77  5169.1 1988.85
  5209.2 2000.35  5229.3 2003.98  5359.6 2020.92  5504.7 2029.09  5731.4 2045.04
#Mann= 6 ,-1 , 0
  3987.1     .16       0  4581.5      .1       0  4997.1     .07       0
  5003.1      .1       0    5104     .16       0  5504.7      .1       0
Bank Sta=4988.7,5088.9
XS Rating Curve= 0 ,0
Exp/Cntr=0.3,0.1

Type RM Length L Ch R = 1 ,5158    ,765,765,765
BEGIN DESCRIPTION:
SPANISH OAK CREEK 10.0
END DESCRIPTION:
XS GIS Cut Line= 4
       2670306.9     10037620.67      2670876.32     10037113.75
      2670911.04     10036599.86      2670668.03      10035898.6
#Sta/Elev= 30
  3961.6  1990.8  4045.2 1986.75  4158.9  1985.3  4215.8 1979.77  4470.8  1971.7
  4583.7 1965.44  4771.9 1960.69  4934.5  1956.9  4964.5  1954.3    4979 1951.53
  4985.4  1948.4  4991.6 1947.46  4994.4 1946.96  4997.6 1947.46  5034.7 1948.31
  5054.7 1956.15  5084.8 1964.54  5123.3 1971.63  5128.3 1970.95    5165 1975.87
    5239 1981.44  5318.8 1989.81  5361.9 1995.98  5467.8 2004.31  5542.1 2013.89
  5593.8 2017.08  5656.1 2023.73  5732.4 2029.56  5880.5 2038.93  5981.2 2042.56
#Mann= 5 ,-1 , 0
  3961.6     .16       0  4771.9      .1       0  4985.4     .16       0
  4991.6     .07       0  4997.6     .16       0
Bank Sta=4934.5,5054.7
XS Rating Curve= 0 ,0
Exp/Cntr=0.3,0.1

Type RM Length L Ch R = 1 ,4393    ,581,581,581
BEGIN DESCRIPTION:
SPANISH OAK CREEK 9.0
END DESCRIPTION:
XS GIS Cut Line= 2
      2671405.83     10037914.08      2671666.25     10036342.92
#Sta/Elev= 30
  3781.3 1982.05    3883 1980.51  4035.1  1973.2  4187.1 1970.48    4329 1959.27
  4419.7 1956.31  4425.4 1956.27  4588.9 1954.06  4742.4  1953.9  4896.7 1952.03
  4925.6 1950.79  4967.6 1947.93  4986.4 1943.78  4988.5 1940.67  4991.2 1940.17
  4994.5 1940.67  5028.4 1946.02  5038.6 1953.16  5052.4 1969.61  5058.8 1981.12
    5069 1988.79  5079.1 1993.83  5089.3 1996.97  5108.4 2000.45  5142.5 2002.63
  5174.4 2003.21    5221 2007.04  5235.4 2006.78  5291.3 2009.88  5373.9 2010.94
#Mann= 8 ,-1 , 0
  3781.3     .16       0  4419.7      .1       0  4425.4     .16       0
  4588.9      .1       0  4925.6     .16       0  4988.5     .07       0
  4994.5     .16       0  5142.5      .1       0
Bank Sta=4896.7,5038.6
XS Rating Curve= 0 ,0
Exp/Cntr=0.3,0.1

Type RM Length L Ch R = 1 ,3812    ,728,728,728
BEGIN DESCRIPTION:
SPANISH OAK CREEK 8.0
END DESCRIPTION:
XS GIS Cut Line= 4
      2672100.27     10038252.63      2671944.03      10037289.1
      2672126.32     10036872.43       2671762.6     10036292.22
#Sta/Elev= 30
  3785.7 1993.64  3890.8  1990.5  4079.6 1980.41  4149.3 1973.59  4265.7 1970.62
  4318.3 1966.68  4416.4 1959.68  4676.2 1954.12  4876.8 1950.25    4936 1947.66
  4953.2 1945.09  4993.9 1936.89  4996.6 1936.39  4999.9 1936.89  5051.5 1943.58
  5110.6  1944.8    5157 1948.54  5180.8 1949.98  5193.4 1953.65  5199.2 1952.82
  5218.8 1952.74    5258 1963.73  5279.2 1967.62  5294.5  1973.2  5337.8 1980.15
  5352.3 1983.74    5376 1986.22  5431.3 1993.02  5546.7 1997.64  5901.4 2003.34
#Mann= 11 ,-1 , 0
  3785.7     .16       0  4079.6      .1       0  4318.3     .16       0
  4416.4      .1       0  4676.2     .16       0  4993.9     .07       0
  4999.9     .16       0    5157     .16       0  5199.2      .1       0
  5337.8     .16       0    5376      .1       0
Bank Sta=4953.2,5110.6
XS Rating Curve= 0 ,0
Exp/Cntr=0.3,0.1

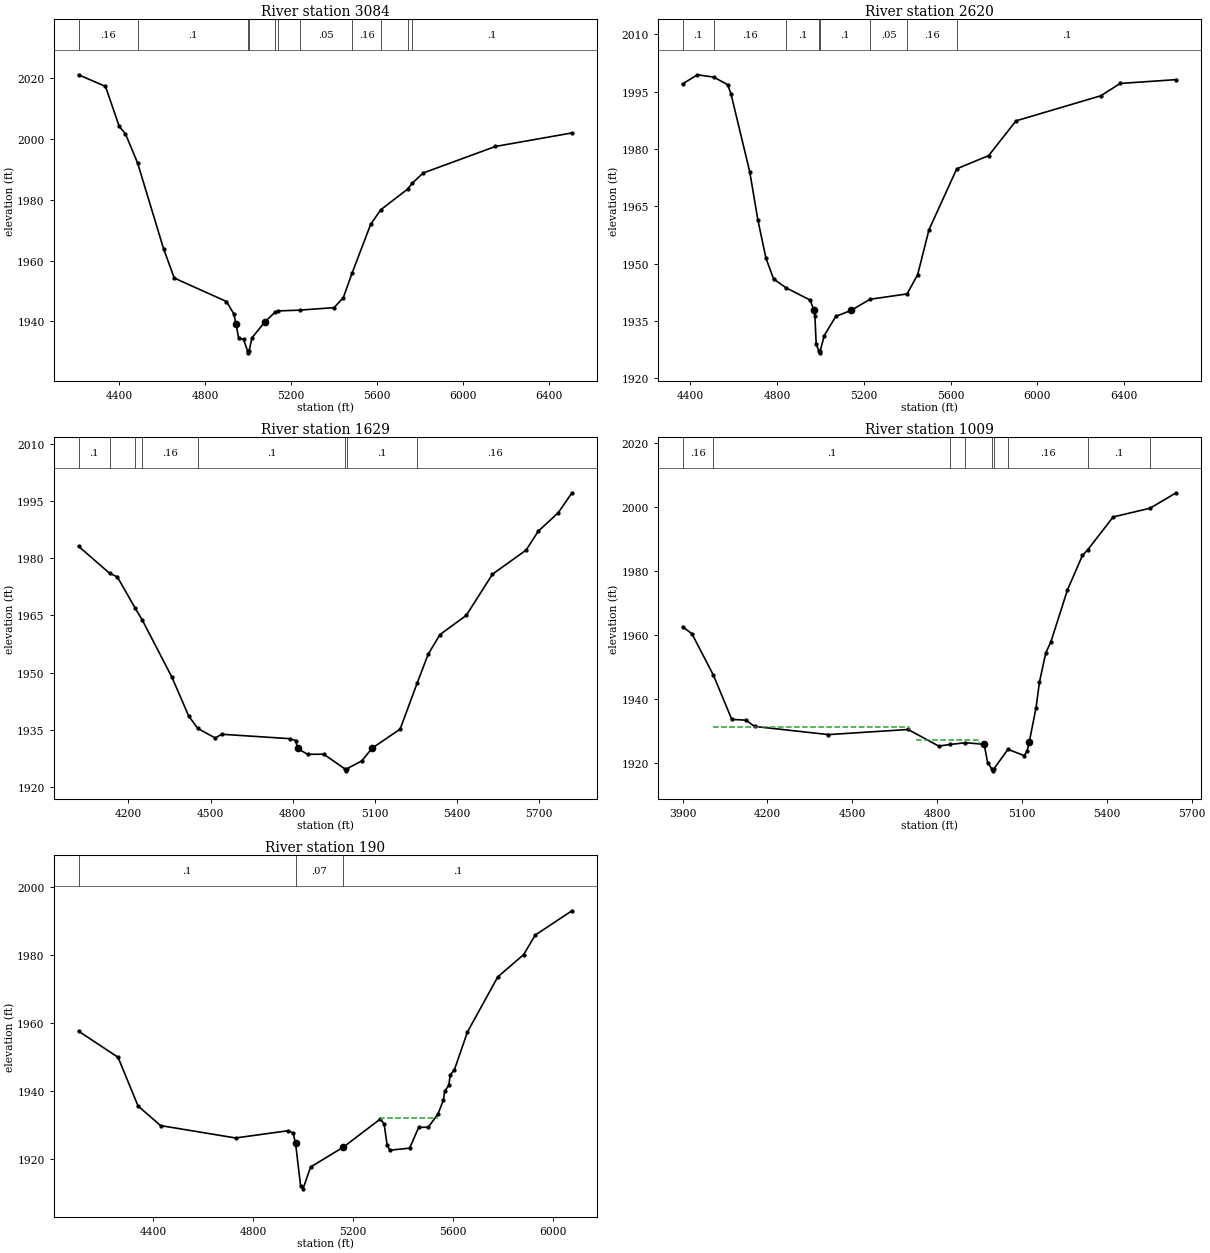
Type RM Length L Ch R = 1 ,3084    ,464,464,464
BEGIN DESCRIPTION:
SPANISH OAK CREEK 6.0
END DESCRIPTION:
XS GIS Cut Line= 4
      2673263.46     10037705.76      2672838.12     10037358.54
      2672542.98     10036759.58      2671675.95     10036117.98
#Sta/Elev= 30
  4210.2 2021.11  4335.6 2017.28  4399.5 2004.13  4428.3  2001.7  4484.7 1992.15
  4605.6 1963.93  4655.5 1954.23  4898.4 1946.52  4932.8 1942.42    4943 1939.05
  4955.3 1934.39  4977.7 1934.06  4997.2 1930.13  4999.9 1929.63  5003.2 1930.13
  5017.1 1934.57  5076.8 1939.79  5124.6 1943.01  5138.3 1943.42  5238.5 1943.68
  5398.9  1944.5    5442 1947.79  5482.9  1955.9  5569.5 1971.95  5616.2  1976.7
  5741.2 1983.51  5762.8 1985.45  5813.6  1988.8  6149.6 1997.53  6505.6 2001.98
#Mann= 11 ,-1 , 0
  4210.2     .16       0  4484.7      .1       0  4997.2     .07       0
  5003.2      .1       0  5124.6     .16       0  5138.3      .1       0
  5238.5     .05       0  5482.9     .16       0  5616.2      .1       0
  5741.2     .16       0  5762.8      .1       0
Bank Sta=4943,5076.8
XS Rating Curve= 0 ,0
Exp/Cntr=0.3,0.1

Type RM Length L Ch R = 1 ,2620    ,991,991,991
BEGIN DESCRIPTION:
SPANISH OAK CREEK 5.0
END DESCRIPTION:
XS GIS Cut Line= 3
       2673581.2     10037143.28       2672841.6     10036716.18
      2671629.82     10035976.61
#Sta/Elev= 30
  4365.7 1997.05  4433.6 1999.42  4508.5 1998.81  4572.9 1996.83  4588.3 1994.42
  4674.8 1973.99  4712.1 1961.42  4749.4 1951.42  4784.6 1945.97  4841.8 1943.67
  4953.4 1940.44  4969.1 1937.97  4974.9 1936.32  4980.9 1928.88  4993.4 1927.14
  4996.2 1926.64  4999.4 1927.14    5018 1931.17  5071.1 1936.17  5142.5 1937.76
  5228.7 1940.66  5399.7 1942.06  5448.5 1947.13  5500.8 1958.89  5628.6 1974.81
  5775.7 1978.27  5901.5 1987.36  6292.6 1993.93  6381.6 1997.15  6639.4 1998.15
#Mann= 8 ,-1 , 0
  4365.7      .1       0  4508.5     .16       0  4841.8      .1       0
  4993.4     .07       0  4999.4      .1       0  5228.7     .05       0
  5399.7     .16       0  5628.6      .1       0
Bank Sta=4969.1,5142.5
XS Rating Curve= 0 ,0
Exp/Cntr=0.3,0.1

Type RM Length L Ch R = 1 ,1629    ,620,620,620
BEGIN DESCRIPTION:
SPANISH OAK CREEK 3.0
END DESCRIPTION:
XS GIS Cut Line= 4
      2673585.52     10036684.94       2673550.8     10036143.26
      2672814.69     10035719.65      2672607.31     10035367.11
#Sta/Elev= 30
  4018.1 1983.11  4132.5 1975.98  4159.6  1975.1  4225.3 1966.84  4251.1 1963.74
  4358.9 1948.81  4420.1 1938.65  4453.3 1935.38  4517.2 1932.86  4540.4 1933.85
  4789.5 1932.69  4811.1  1932.2  4817.4 1930.13  4854.2 1928.59  4913.1 1928.62
  4990.6 1924.76  4993.4 1924.26  4996.6 1924.76  5052.5 1926.89  5089.9 1930.21
  5191.9 1935.18  5254.5 1947.32    5294 1954.76  5337.1 1959.95  5433.4    1965
  5529.1  1975.8  5652.1 1982.12  5695.5 1987.01  5769.3 1991.91  5819.2 1997.13
#Mann= 8 ,-1 , 0
  4018.1      .1       0  4132.5     .16       0  4225.3      .1       0
  4251.1     .16       0  4453.3      .1       0  4990.6     .07       0
  4996.6      .1       0  5254.5     .16       0
Bank Sta=4817.4,5089.9
XS Rating Curve= 0 ,0
Exp/Cntr=0.3,0.1

Type RM Length L Ch R = 1 ,1009    ,819,819,819
BEGIN DESCRIPTION:
SPANISH OAK CREEK 2.0
END DESCRIPTION:
XS GIS Cut Line= 3
      2673731.35     10036386.32      2673634.13     10035483.54
      2672863.38     10035157.19
#Sta/Elev= 30
  3900.1 1962.61  3932.9 1960.38  4008.7 1947.44  4073.7 1933.58    4124 1933.34
  4154.1 1931.38  4415.7 1928.82  4697.3 1930.42  4805.5 1925.22  4846.6 1925.74
  4900.1 1926.27  4966.3 1925.79  4978.4 1920.07  4993.7 1917.97  4996.4 1917.47
  4999.7 1917.97  5050.5 1924.21  5107.7 1922.24  5118.3 1923.66    5126 1926.64
  5149.7 1937.22  5161.8 1945.27  5184.2  1954.4  5202.4 1957.92  5260.7  1974.1
  5313.8 1984.94  5331.9 1986.63  5422.4 1996.98  5553.2 1999.72  5645.1 2004.55
#Mann= 9 ,-1 , 0
  3900.1     .16       0  4008.7      .1       0  4846.6     .16       0
  4900.1      .1       0  4993.7     .07       0  4999.7      .1       0
  5050.5     .16       0  5331.9      .1       0  5553.2     .16       0
#XS Ineff= 2 ,-1
 4007.95 4698.86 1931.09 4726.14 4946.59 1927.18
Permanent Ineff=
       F       F
Bank Sta=4966.3,5126
XS Rating Curve= 0 ,0
Exp/Cntr=0.3,0.1

Type RM Length L Ch R = 1 ,190     ,0,0,0
BEGIN DESCRIPTION:
SPANISH OAK CREEK 1.0
END DESCRIPTION:
XS GIS Cut Line= 4
      2673939.69     10036441.86      2673974.41     10035427.99
      2673731.35     10034969.65      2673328.53     10034789.08
#Sta/Elev= 30
    4102 1957.57  4260.2 1949.88  4340.3 1935.56  4430.3 1929.81  4730.5 1926.17
  4940.6  1928.3  4960.6 1927.62  4970.6 1924.57  4990.6 1912.15  5000.4 1911.22
  5030.7 1917.63    5161 1923.44  5309.3 1931.71    5325 1930.35    5337 1924.06
  5347.6 1922.58  5426.9 1923.18  5463.3 1929.28  5501.6 1929.34  5539.9 1933.13
  5561.9 1937.21  5567.5 1939.91  5583.9 1941.68  5589.5 1944.73  5605.9 1946.14
  5658.4 1957.32  5779.8 1973.51  5883.5 1980.07  5929.8 1985.81  6076.7 1992.94
#Mann= 3 , 0 , 0
    4102      .1       0  4970.6     .07       0    5161      .1       0
#XS Ineff= 1 ,-1
 5311.08 5541.19 1931.91
Permanent Ineff=
       F
Bank Sta=4970.6,5161
XS Rating Curve= 0 ,0
Exp/Cntr=0.3,0.1

Chan Stop Cuts=-1
Use User Specified Reach Order=0
Composite Channel Slope=5