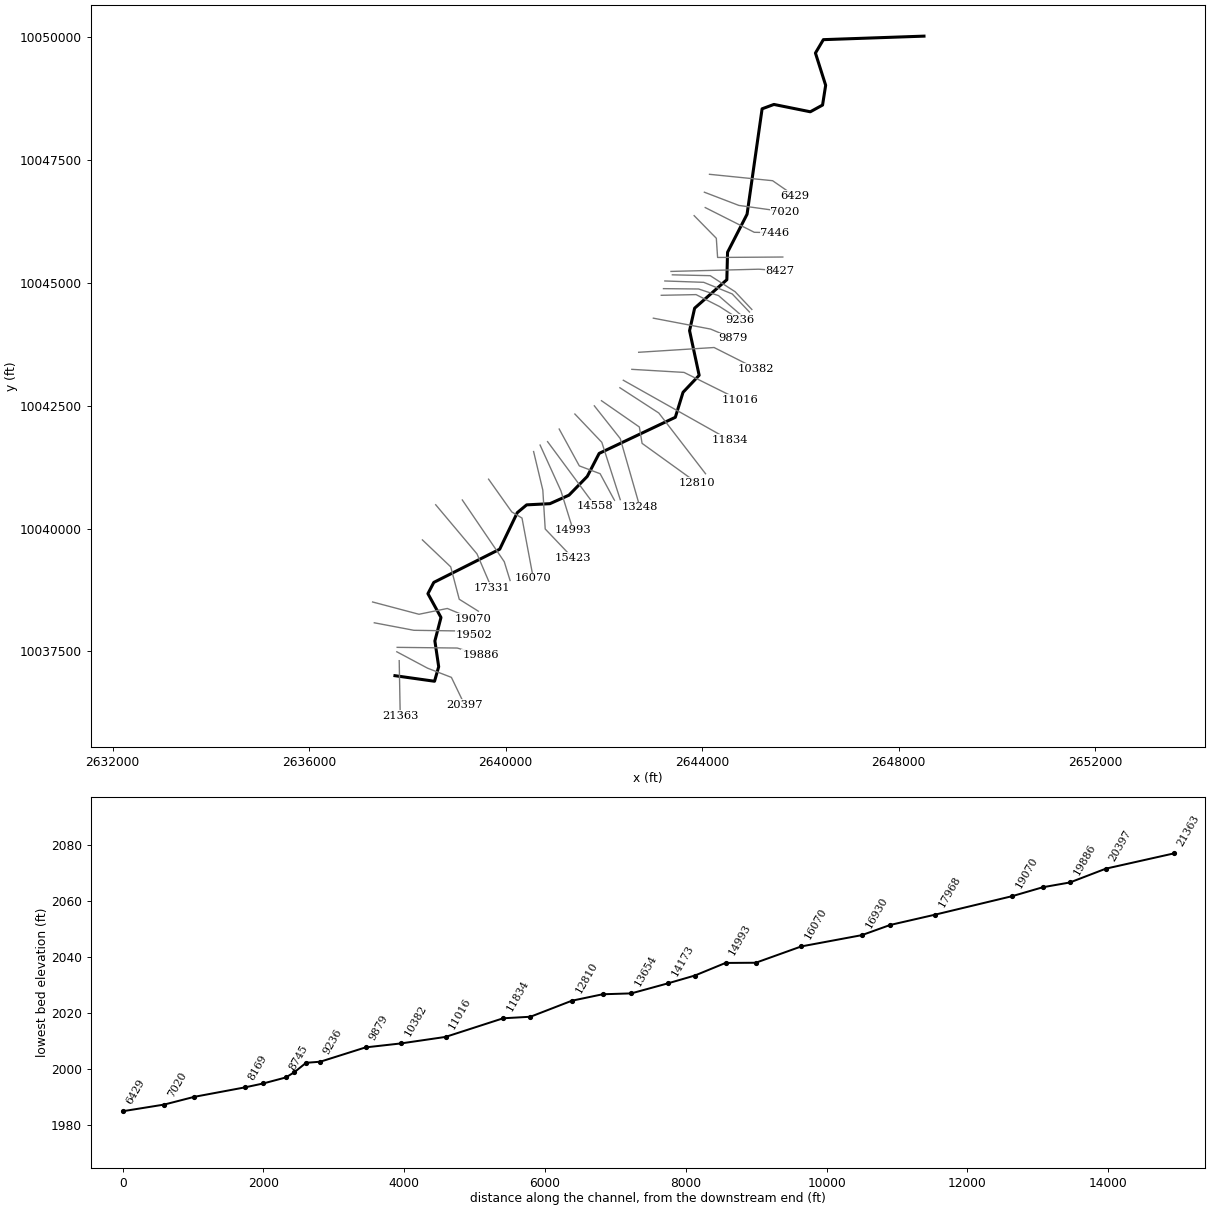
--- STEVENS CREEK.prj (project) ---

Proj Title=STEVENS CREEK Base Level Engineering
Current Plan=p01
Default Exp/Contr=0.3,0.1
English Units
Geom File=g01
Flow File=f01
Plan File=p01
Y Axis Title=Elevation
X Axis Title(PF)=Main Channel Distance
X Axis Title(XS)=Station
BEGIN DESCRIPTION:
STEVENS CREEK
END DESCRIPTION:
DSS Export Rating Curves= 0
DSS Export Rating Curve Sorted= 0
DSS Export Volume Flow Curves= 0
DXF OffsetX= 0
DXF OffsetY= 0
DXF ScaleX= 1
DXF ScaleY= 10

--- STEVENS CREEK.p01 (plan) ---

Plan Title=Multiple Run
Short Identifier=Multiple
Geom File=g01
Flow File=f01
Subcritical Flow
K Sum by GR= 0
Std Step Tol= 0.01
Critical Tol= 0.01
Num of Std Step Trials= 20
Max Error Tol= 0.3
Flow Tol Ratio= 0.001
Split Flow NTrial= 30
Split Flow Tol= 0.02
Split Flow Ratio= 0.02
Log Output Level= 0
Friction Slope Method= 1
Unsteady Friction Slope Method= 2
Unsteady Bridges Friction Slope Method= 1
Parabolic Critical Depth
Global Vel Dist=  1 , 1 , 1
Global Log Level= 0
CheckData=True
Encroach Param= -1, 0, 0, 0
BEGIN DESCRIPTION:
Multiple Run
END DESCRIPTION:

--- STEVENS CREEK.f01 (steady flow) ---

Flow Title=Multiple
Program Version=4.10
Number of Profiles= 7
Profile Names=10-year,25-year,50-year,1pct_min,100-year,1pct_plu,500-year
River Rch & RM=STEVENS CREEK,Reach-1         ,21363
    1757    2601    3342    3123    4224    5713    6751
River Rch & RM=STEVENS CREEK,Reach-1         ,16070
    2391    3590    4656    4388    5934    8025    9645
River Rch & RM=STEVENS CREEK,Reach-1         ,12810
    2683    4041    5250    4953    6698    9059   10914
River Rch & RM=STEVENS CREEK,Reach-1         ,8169
    4124    6326    8320    7936   10732   14514   17876
River Rch & RM=STEVENS CREEK,Reach-1         ,7446
    4124    6326    8320    7936   10732   14514   17876
Boundary for River Rch & Prof#=STEVENS CREEK,Reach-1         , 1
Up Type= 0
Dn Type= 3
Dn Slope=0.011
Boundary for River Rch & Prof#=STEVENS CREEK,Reach-1         , 2
Up Type= 0
Dn Type= 3
Dn Slope=0.011
Boundary for River Rch & Prof#=STEVENS CREEK,Reach-1         , 3
Up Type= 0
Dn Type= 3
Dn Slope=0.011
Boundary for River Rch & Prof#=STEVENS CREEK,Reach-1         , 4
Up Type= 0
Dn Type= 3
Dn Slope=0.011
Boundary for River Rch & Prof#=STEVENS CREEK,Reach-1         , 5
Up Type= 0
Dn Type= 3
Dn Slope=0.011
Boundary for River Rch & Prof#=STEVENS CREEK,Reach-1         , 6
Up Type= 0
Dn Type= 3
Dn Slope=0.011
Boundary for River Rch & Prof#=STEVENS CREEK,Reach-1         , 7
Up Type= 0
Dn Type= 3
Dn Slope=0.011
DSS Import GetInterval= 0
DSS Import GetPeak= 0
DSS Import FillOption= 0

--- STEVENS CREEK.g01 (geometry) ---

Geom Title=Existing Conditions
Program Version=4.10

River Reach=STEVENS CREEK   ,Reach-1
Reach XY= 30
      2637748.47     10037003.73      2638554.19      10036890.4
      2638638.87      10037186.6      2638561.36     10037710.81
      2638685.52     10038188.93      2638419.63     10038673.57
      2638539.27     10038902.99      2639881.05     10039578.58
      2640239.12     10040322.75      2640429.42     10040481.42
      2640902.64     10040505.55      2641291.13     10040678.69
      2641663.67     10041060.93      2641905.66     10041528.81
       2643456.3     10042264.21      2643613.11     10042772.76
      2643941.36     10043118.92      2643746.17     10044028.22
      2643849.27     10044485.14      2644505.07     10045065.14
      2644519.54     10045623.48      2644916.95     10046398.36
      2645222.95     10048544.21       2645463.4     10048633.16
      2646204.11     10048483.77      2646453.68     10048620.64
      2646516.81     10049023.63      2646308.75     10049679.29
      2646469.83     10049952.09      2648518.47     10050023.73

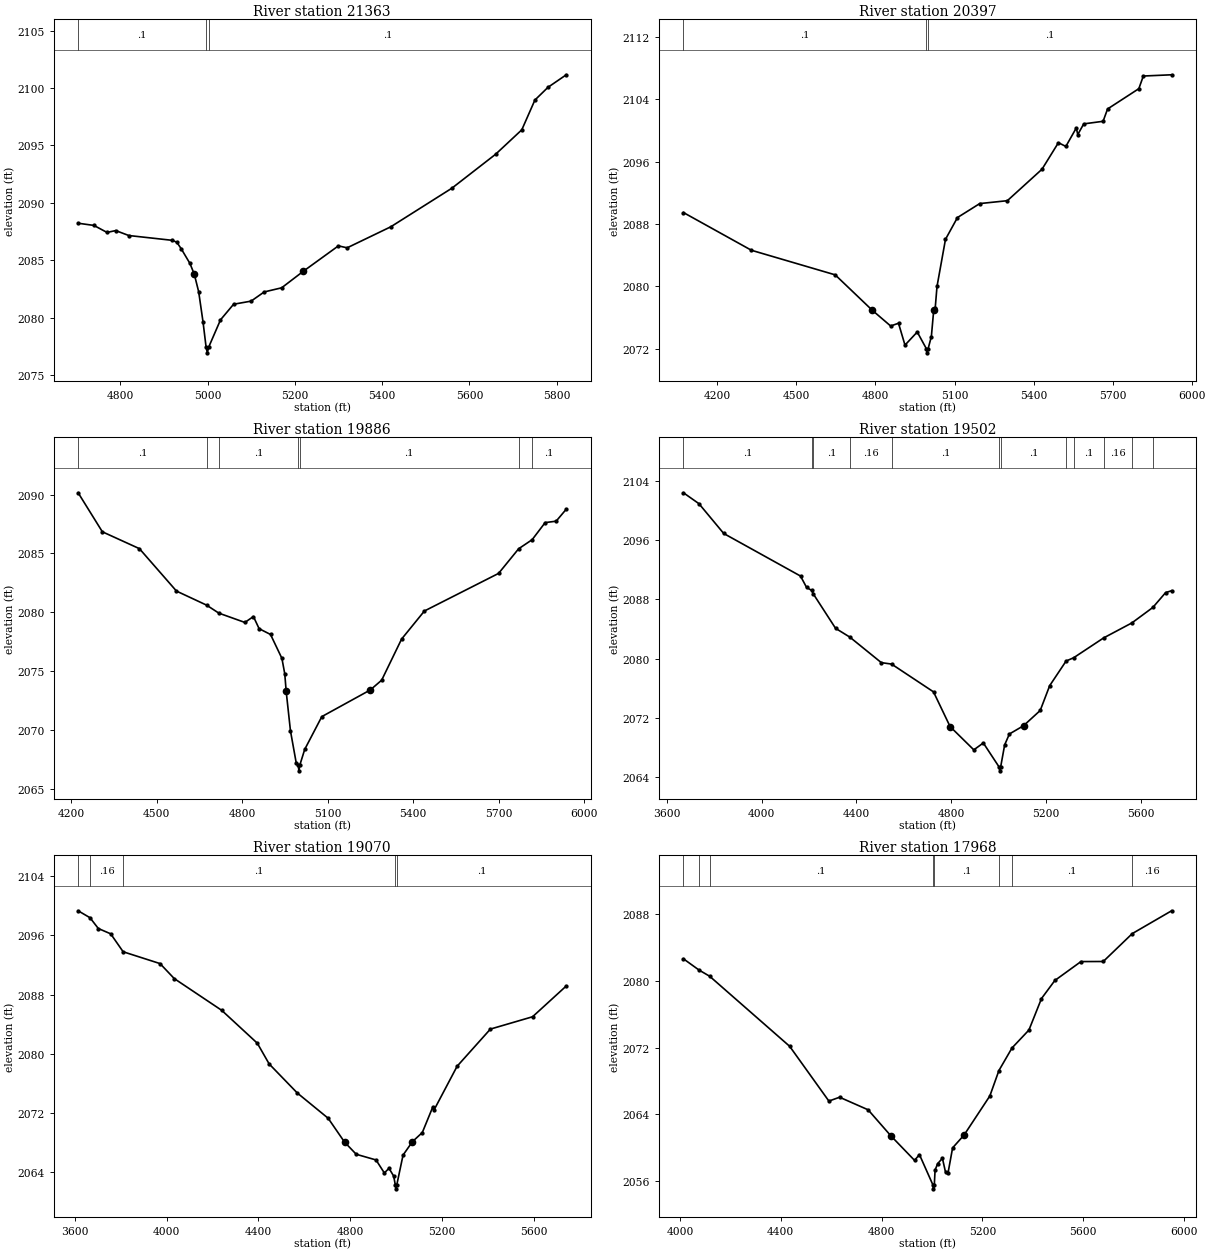
Type RM Length L Ch R = 1 ,21363   ,966,966,966
BEGIN DESCRIPTION:
STEVENS CREEK 46.0
END DESCRIPTION:
XS GIS Cut Line= 2
      2637835.09     10037309.81      2637855.92     10036191.81
#Sta/Elev= 30
  4703.6 2088.23  4739.7 2088.04  4769.7 2087.43  4789.7 2087.59  4819.7 2087.16
  4919.7 2086.74  4929.7 2086.57  4939.7 2086.01  4959.7 2084.73  4969.7 2083.79
  4979.7 2082.27  4989.7 2079.64  4996.7 2077.45  4999.5 2076.95  5002.7 2077.45
  5029.7 2079.82  5059.7 2081.18  5099.8 2081.45  5129.8 2082.25  5169.8 2082.61
  5219.8 2084.06  5299.8 2086.26  5319.8 2086.09  5419.8 2087.92  5559.8 2091.28
  5659.8 2094.23  5719.9 2096.36  5749.9 2098.95  5779.9 2100.06  5821.8 2101.15
#Mann= 3 ,-1 , 0
  4703.6      .1       0  4996.7     .07       0  5002.7      .1       0
Bank Sta=4969.7,5219.8
XS Rating Curve= 0 ,0
Exp/Cntr=0.3,0.1

Type RM Length L Ch R = 1 ,20397   ,511,511,511
BEGIN DESCRIPTION:
STEVENS CREEK 45.0
END DESCRIPTION:
XS GIS Cut Line= 4
      2637786.49     10037490.39      2638411.47     10037157.07
      2638897.58     10036969.57      2639168.01     10036407.91
#Sta/Elev= 30
  4071.2 2089.47  4329.1 2084.64  4647.1 2081.49    4787 2076.98  4857.5 2074.94
  4887.4 2075.29    4912 2072.49  4958.5 2074.17  4993.6    2072  4996.3  2071.5
  4999.6    2072  5012.1 2073.59  5021.2 2077.04  5026.6 2077.19  5033.5    2080
  5065.7 2086.04  5111.1 2088.83  5195.7 2090.62  5300.5 2090.99    5432 2095.02
  5494.3 2098.42  5522.5 2097.94  5562.2 2100.31  5567.7 2099.46  5590.4 2100.83
  5663.8 2101.16  5680.9 2102.74  5799.5 2105.34  5816.6 2106.96  5923.9 2107.12
#Mann= 3 ,-1 , 0
  4071.2      .1       0  4993.6     .07       0  4999.6      .1       0
Bank Sta=4787,5021.2
XS Rating Curve= 0 ,0
Exp/Cntr=0.3,0.1

Type RM Length L Ch R = 1 ,19886   ,384,384,384
BEGIN DESCRIPTION:
STEVENS CREEK 44.0
END DESCRIPTION:
XS GIS Cut Line= 3
      2637793.43     10037580.68      2639015.64     10037566.79
      2639486.41     10037428.33
#Sta/Elev= 30
  4224.7 2090.15  4309.7 2086.84  4439.7 2085.41  4569.8 2081.81  4675.3 2080.62
  4718.4 2079.94  4809.8 2079.15  4839.8 2079.65  4859.8 2078.62  4899.8 2078.13
  4939.8  2076.1  4949.8 2074.79 4954.77  2073.3  4969.8 2069.95  4989.8 2067.26
  4996.8 2067.06  4999.5 2066.56  5002.8 2067.06  5019.8 2068.38  5079.8 2071.16
  5249.8 2073.42  5289.8 2074.25  5359.8 2077.74  5439.8 2080.12  5700.1 2083.31
  5770.5  2085.4  5817.9 2086.17  5863.5 2087.62  5902.1 2087.74  5937.7 2088.76
#Mann= 7 ,-1 , 0
  4224.7      .1       0  4675.3     .16       0  4718.4      .1       0
  4996.8     .07       0  5002.8      .1       0  5770.5     .16       0
  5817.9      .1       0
Bank Sta=4954.77,5249.8
XS Rating Curve= 0 ,0
Exp/Cntr=0.3,0.1

Type RM Length L Ch R = 1 ,19502   ,432,432,432
BEGIN DESCRIPTION:
STEVENS CREEK 43.0
END DESCRIPTION:
XS GIS Cut Line= 4
      2637328.12     10038080.68       2638133.7      10037927.9
       2639071.2     10037914.01      2639362.83     10037837.63
#Sta/Elev= 30
  3670.6 2102.36  3735.9 2100.89  3840.5 2096.87  4164.3 2091.13    4190 2089.59
  4211.1  2089.2  4219.1 2088.68  4312.2 2084.08  4372.1  2082.9  4505.3 2079.45
  4548.3 2079.26  4725.3 2075.51  4795.3 2070.83  4895.3 2067.69  4935.4 2068.62
  5002.4 2065.36  5005.1 2064.86  5008.4 2065.36  5025.4 2068.36  5045.4 2069.83
  5104.9 2070.94  5175.4    2073  5215.4 2076.35  5284.6 2079.67  5316.4 2080.11
  5443.1 2082.79  5562.1 2084.81  5650.3 2086.89  5704.4  2088.9  5729.6 2089.15
#Mann= 12 ,-1 , 0
  3670.6      .1       0  4211.1     .16       0  4219.1      .1       0
  4372.1     .16       0  4548.3      .1       0  5002.4     .07       0
  5008.4      .1       0  5284.6     .16       0  5316.4      .1       0
  5443.1     .16       0  5562.1      .1       0  5650.3     .16       0
Bank Sta=4795.3,5104.9
XS Rating Curve= 0 ,0
Exp/Cntr=0.3,0.1

Type RM Length L Ch R = 1 ,19070   ,1102,1102,1102
BEGIN DESCRIPTION:
STEVENS CREEK 42.0
END DESCRIPTION:
XS GIS Cut Line= 4
      2637293.39      10038504.3      2638237.86     10038254.29
      2638814.25     10038372.34      2639334.32     10038157.38
#Sta/Elev= 30
  3614.4 2099.34  3666.1  2098.4  3702.4 2096.94  3756.3 2096.22  3810.6 2093.79
  3971.4 2092.19  4033.4 2090.16  4240.3 2085.86  4395.5 2081.41  4447.2  2078.6
  4570.1 2074.66  4704.3 2071.25  4775.8 2068.02  4826.8 2066.37  4913.1  2065.6
  4949.3 2063.84  4969.7 2064.47  4990.1 2063.41  4997.3 2062.19  5000.1 2061.69
  5003.3 2062.19  5030.9 2066.26  5071.8 2068.08  5114.8 2069.31  5160.2 2072.75
  5165.3 2072.33  5266.6 2078.29  5411.6 2083.32  5595.5 2084.99  5742.5 2089.16
#Mann= 5 ,-1 , 0
  3614.4      .1       0  3666.1     .16       0  3810.6      .1       0
  4997.3     .07       0  5003.3      .1       0
Bank Sta=4775.8,5071.8
XS Rating Curve= 0 ,0
Exp/Cntr=0.3,0.1

Type RM Length L Ch R = 1 ,17968   ,637,637,637
BEGIN DESCRIPTION:
STEVENS CREEK 40.0
END DESCRIPTION:
XS GIS Cut Line= 4
      2638307.32     10039768.17       2638883.7     10039219.57
      2639057.31     10038559.84      2639446.19     10038316.79
#Sta/Elev= 30
  4014.1 2082.65    4076  2081.3    4118 2080.56  4435.3 2072.15    4591 2065.57
  4633.5 2066.03  4746.7 2064.52  4836.5 2061.41  4930.8 2058.45  4950.3 2059.14
  5003.3 2055.53    5006 2055.03  5009.3 2055.53  5012.3 2057.29  5022.7 2058.06
  5041.4  2058.7  5053.7 2057.03    5064 2056.99  5081.8 2059.95  5127.3 2061.49
  5229.5 2066.18  5265.6 2069.24  5317.5 2071.95  5384.6  2074.1  5434.4 2077.88
  5487.4 2080.05    5591 2082.32  5679.5 2082.33  5794.6 2085.68  5950.6 2088.42
#Mann= 8 ,-1 , 0
  4014.1      .1       0    4076     .16       0    4118      .1       0
  5003.3     .07       0  5009.3      .1       0  5265.6     .16       0
  5317.5      .1       0  5794.6     .16       0
Bank Sta=4836.5,5127.3
XS Rating Curve= 0 ,0
Exp/Cntr=0.3,0.1

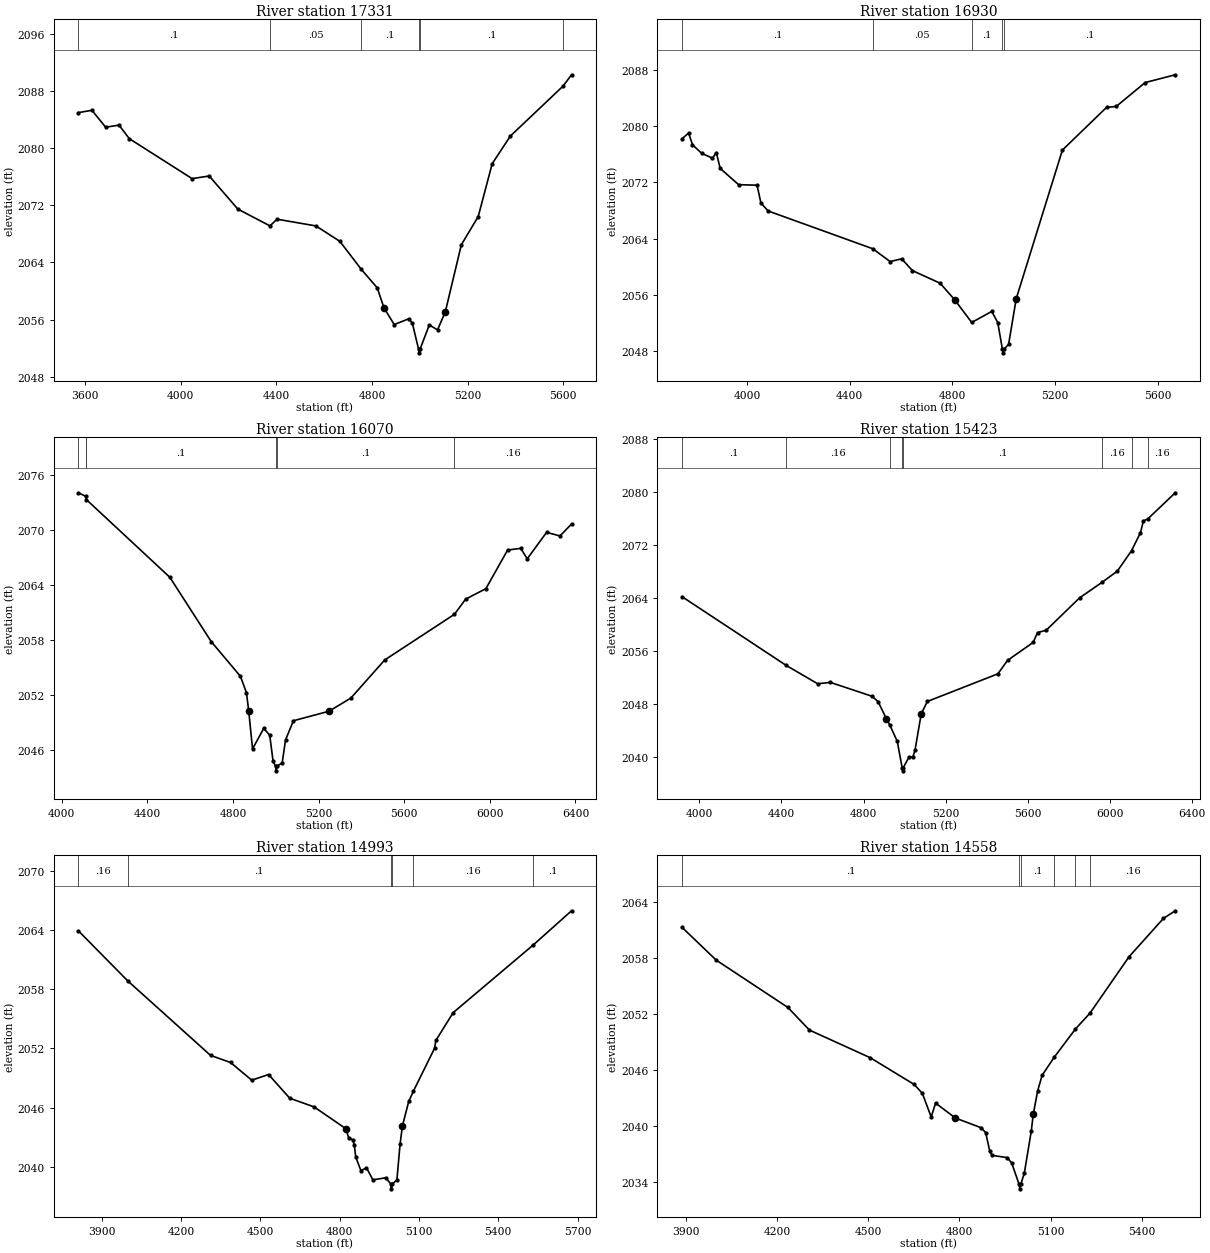
Type RM Length L Ch R = 1 ,17331   ,401,401,401
BEGIN DESCRIPTION:
STEVENS CREEK 38.0
END DESCRIPTION:
XS GIS Cut Line= 3
      2638578.13     10040483.46      2639418.42     10039483.45
      2639717.03     10038789.01
#Sta/Elev= 30
  3572.5 2084.98  3629.2 2085.31  3686.4 2082.94  3742.4 2083.23  3785.3 2081.34
    4048 2075.74  4119.5 2076.11  4239.2 2071.48  4373.7 2069.12  4403.1 2070.06
  4565.7 2069.12  4665.8 2066.96    4756 2063.02  4821.9 2060.46  4850.5 2057.64
  4893.1 2055.31  4954.6 2056.12  4969.1 2055.48  4995.1 2051.85  4997.9 2051.35
  5001.1 2051.85  5039.8 2055.26  5074.3 2054.56    5107 2057.12  5173.8 2066.48
  5244.4 2070.43  5302.9 2077.84  5379.1 2081.71  5598.4 2088.67  5634.6 2090.28
#Mann= 6 ,-1 , 0
  3572.5      .1       0  4373.7     .05       0    4756      .1       0
  4995.1     .07       0  5001.1      .1       0  5598.4     .16       0
Bank Sta=4850.5,5107
XS Rating Curve= 0 ,0
Exp/Cntr=0.3,0.1

Type RM Length L Ch R = 1 ,16930   ,860,860,860
BEGIN DESCRIPTION:
STEVENS CREEK 37.0
END DESCRIPTION:
XS GIS Cut Line= 3
       2639119.8     10040580.69      2639973.97     10039323.73
      2640092.03     10038941.79
#Sta/Elev= 30
  3747.5 2078.25  3772.9 2079.04  3787.9 2077.38  3823.8 2076.15  3865.8 2075.47
  3880.7 2076.26  3895.7 2074.01  3967.5 2071.69  4039.4 2071.61  4054.3 2069.07
  4082.4 2067.94  4489.4 2062.56  4557.3 2060.73  4602.1 2061.12  4644.1 2059.44
  4751.9 2057.64  4808.8 2055.27  4874.8 2052.05  4952.9 2053.62  4976.3 2052.02
  4994.3 2048.22  4997.1 2047.72  5000.3 2048.22  5018.3 2048.93  5048.2 2055.46
  5227.8 2076.62  5399.5  2082.7  5437.4 2082.84  5549.8 2086.24    5667 2087.35
#Mann= 5 ,-1 , 0
  3747.5      .1       0  4489.4     .05       0  4874.8      .1       0
  4994.3     .07       0  5000.3      .1       0
Bank Sta=4808.8,5048.2
XS Rating Curve= 0 ,0
Exp/Cntr=0.3,0.1

Type RM Length L Ch R = 1 ,16070   ,647,647,647
BEGIN DESCRIPTION:
STEVENS CREEK 35.0
END DESCRIPTION:
XS GIS Cut Line= 4
       2639654.5     10041004.33      2640126.75     10040337.62
      2640335.08     10040212.62      2640564.25     10038990.39
#Sta/Elev= 30
    4078  2074.1  4111.5 2073.72    4115 2073.36  4505.1 2064.86  4698.3 2057.83
  4834.9 2054.03    4863 2052.23 4873.58 2050.25  4891.5 2046.09  4943.7 2048.33
  4971.7 2047.59  4987.3 2044.77    4999 2044.19  5001.7 2043.69    5005 2044.19
    5030 2044.56  5045.6 2047.07  5082.5 2049.17  5248.8 2050.21  5350.9 2051.65
  5508.6 2055.81  5834.6 2060.81  5886.8 2062.47  5981.3 2063.61    6083 2067.84
  6144.1 2068.02  6174.6 2066.88  6264.9 2069.77  6327.6 2069.38  6381.5 2070.68
#Mann= 6 ,-1 , 0
    4078      .1       0  4111.5     .05       0    4115      .1       0
    4999     .07       0    5005      .1       0  5834.6     .16       0
Bank Sta=4873.58,5248.8
XS Rating Curve= 0 ,0
Exp/Cntr=0.3,0.1

Type RM Length L Ch R = 1 ,15423   ,430,430,430
BEGIN DESCRIPTION:
STEVENS CREEK 34.0
END DESCRIPTION:
XS GIS Cut Line= 4
       2640571.2     10041566.76       2640758.7     10040782.07
      2640807.31      10039990.4      2641362.04     10039407.93
#Sta/Elev= 30
  3915.4 2064.17  4422.7 2053.79  4576.5 2051.01  4638.2 2051.22  4840.7 2049.13
  4870.8 2048.32  4910.9 2045.76  4928.9 2044.71  4964.6  2042.3    4988 2038.35
  4990.8 2037.85    4994 2038.35  5021.1 2039.89  5041.1 2039.99  5051.1 2040.99
  5081.2 2046.46  5111.2 2048.34  5454.8 2052.51    5502 2054.54  5626.9 2057.26
  5648.3 2058.75  5690.5  2059.1  5853.4    2064  5962.6 2066.34  6037.1 2068.03
  6106.7 2071.13  6150.3 2073.87  6164.5 2075.63  6185.1 2075.91  6319.7 2079.88
#Mann= 8 ,-1 , 0
  3915.4      .1       0  4422.7     .16       0  4928.9      .1       0
    4988     .07       0    4994      .1       0  5962.6     .16       0
  6106.7      .1       0  6185.1     .16       0
Bank Sta=4910.9,5081.2
XS Rating Curve= 0 ,0
Exp/Cntr=0.3,0.1

Type RM Length L Ch R = 1 ,14993   ,435,435,435
BEGIN DESCRIPTION:
STEVENS CREEK 33.0
END DESCRIPTION:
XS GIS Cut Line= 3
      2640703.12     10041698.77      2641126.75     10040768.18
      2641376.74     10039962.65
#Sta/Elev= 30
  3811.3 2063.92  3997.2 2058.87  4311.3  2051.3    4387 2050.58  4467.2 2048.79
  4530.9 2049.36    4611 2046.96  4703.2 2046.08    4824 2043.86  4833.5 2042.97
  4848.9 2042.74  4855.3 2042.24  4860.5 2041.03  4880.3 2039.62  4901.3 2039.92
  4925.7 2038.69  4974.5  2038.9  4993.1 2038.28  4995.8 2037.78  4999.1 2038.28
  5016.4 2038.67  5028.6 2042.35  5037.4 2044.15  5061.2 2046.64  5078.6 2047.66
  5158.9 2052.02  5164.2 2052.83  5229.3 2055.63  5532.5 2062.49  5677.2 2065.95
#Mann= 6 ,-1 , 0
  3811.3     .16       0  3997.2      .1       0  4993.1     .07       0
  4999.1      .1       0  5078.6     .16       0  5532.5      .1       0
Bank Sta=4824,5037.4
XS Rating Curve= 0 ,0
Exp/Cntr=0.3,0.1

Type RM Length L Ch R = 1 ,14558   ,385,385,385
BEGIN DESCRIPTION:
STEVENS CREEK 32.0
END DESCRIPTION:
XS GIS Cut Line= 2
      2640855.91     10041768.18      2641821.22     10040462.58
#Sta/Elev= 30
  3886.7 2061.24  3999.1 2057.74    4235 2052.68    4306 2050.26  4506.4  2047.3
  4650.5 2044.45  4677.5 2043.51  4706.8 2040.97  4721.4 2042.45  4786.2 2040.86
  4871.7 2039.81  4886.4 2039.28  4899.6 2037.31  4907.2 2036.86  4957.3 2036.62
    4972 2036.04  4996.1 2033.78  4998.8 2033.28  5002.1 2033.78  5013.6 2034.98
  5036.4 2039.46  5042.9 2041.25  5057.5 2043.78  5072.2 2045.43  5111.4 2047.33
  5181.1 2050.35  5229.9 2052.08  5358.2  2058.1  5471.7 2062.21  5510.4 2063.02
#Mann= 6 ,-1 , 0
  3886.7      .1       0  4996.1     .07       0  5002.1      .1       0
  5111.4     .16       0  5181.1      .1       0  5229.9     .16       0
Bank Sta=4786.2,5042.9
XS Rating Curve= 0 ,0
Exp/Cntr=0.3,0.1

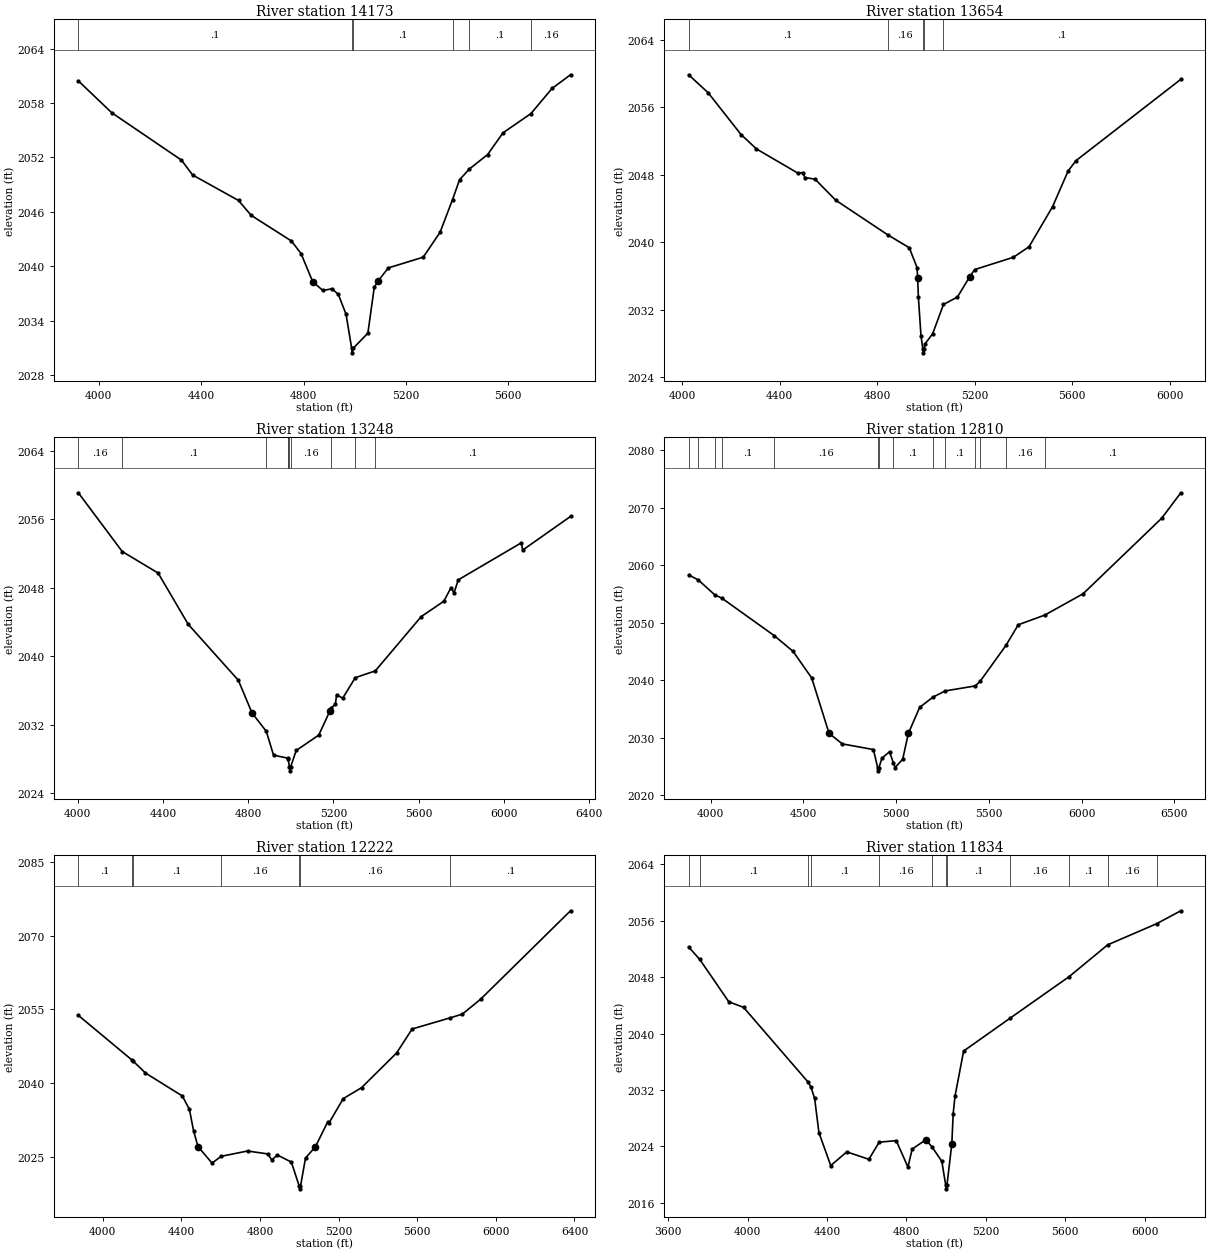
Type RM Length L Ch R = 1 ,14173   ,519,519,519
BEGIN DESCRIPTION:
STEVENS CREEK 31.0
END DESCRIPTION:
XS GIS Cut Line= 4
      2641092.01     10042025.15      2641501.75     10041275.12
      2641925.36      10041115.4      2642217.04     10040573.71
#Sta/Elev= 30
  3920.2 2060.44  4050.6 2056.93  4322.9 2051.71  4366.6 2050.07  4545.9 2047.26
  4595.3 2045.62  4752.8 2042.79  4790.2 2041.41  4835.5 2038.32  4875.4 2037.34
    4911 2037.53  4935.8 2036.91    4966 2034.72  4987.9 2030.97  4990.6 2030.47
  4993.9 2030.97  5051.3 2032.64  5076.2  2037.7    5092 2038.42  5131.2 2039.83
  5267.5 2041.01  5333.2 2043.75  5381.9 2047.35  5409.5 2049.55  5447.9 2050.73
    5519 2052.32    5579 2054.71  5688.5 2056.84  5770.5  2059.6  5842.8 2061.11
#Mann= 6 ,-1 , 0
  3920.2      .1       0  4987.9     .07       0  4993.9      .1       0
  5381.9     .16       0  5447.9      .1       0  5688.5     .16       0
Bank Sta=4835.5,5092
XS Rating Curve= 0 ,0
Exp/Cntr=0.3,0.1

Type RM Length L Ch R = 1 ,13654   ,406,406,406
BEGIN DESCRIPTION:
STEVENS CREEK 30.0
END DESCRIPTION:
XS GIS Cut Line= 3
      2641411.51     10042330.64      2641960.08     10041754.29
      2642334.92     10040588.14
#Sta/Elev= 30
  4025.8 2059.88  4106.2 2057.74  4240.9 2052.79  4304.4 2051.08  4474.3 2048.21
  4495.3 2048.28  4502.6 2047.69    4545 2047.49  4629.6    2045  4843.3 2040.89
  4931.5 2039.36  4963.6 2037.01 4965.91 2035.82  4969.1 2033.47  4979.6 2028.94
  4987.1 2027.39  4989.9 2026.89  4993.1 2027.39  4995.7 2027.93  5027.8 2029.17
    5072 2032.63  5129.3 2033.51  5179.2 2035.89  5200.2 2036.77  5359.2 2038.23
  5423.4 2039.48  5519.7 2044.22  5583.9 2048.47    5616 2049.69  6046.4 2059.34
#Mann= 5 ,-1 , 0
  4025.8      .1       0  4843.3     .16       0  4987.1     .07       0
  4993.1     .16       0    5072      .1       0
Bank Sta=4965.91,5179.2
XS Rating Curve= 0 ,0
Exp/Cntr=0.3,0.1

Type RM Length L Ch R = 1 ,13248   ,438,438,438
BEGIN DESCRIPTION:
STEVENS CREEK 29.0
END DESCRIPTION:
XS GIS Cut Line= 3
      2641807.31     10042497.34      2642335.08     10041830.68
      2642737.74     10040428.33
#Sta/Elev= 30
  4003.5 2059.11  4209.3 2052.24  4377.8 2049.72  4518.8 2043.73  4754.4 2037.17
  4818.5 2033.35  4885.3 2031.21  4919.3 2028.42  4986.3 2028.06    4987 2028.01
  4994.2 2027.08  4996.9 2026.58  5000.2 2027.08  5025.7 2028.96  5131.5 2030.76
  5183.5 2033.56  5188.5 2033.89  5209.9  2034.4  5215.1  2035.5  5243.6 2035.07
  5302.9 2037.48  5396.7 2038.27  5612.1 2044.62  5718.5 2046.42  5752.2 2048.02
  5766.2 2047.38  5785.9 2048.92  6081.7 2053.25  6088.7 2052.41  6312.8 2056.34
#Mann= 10 ,-1 , 0
  4003.5     .16       0  4209.3      .1       0  4885.3     .16       0
  4986.3      .1       0    4987     .16       0  4994.2     .07       0
  5000.2     .16       0  5188.5      .1       0  5302.9     .16       0
  5396.7      .1       0
Bank Sta=4818.5,5183.5
XS Rating Curve= 0 ,0
Exp/Cntr=0.3,0.1

Type RM Length L Ch R = 1 ,12810   ,588,588,588
BEGIN DESCRIPTION:
STEVENS CREEK 28.0
END DESCRIPTION:
XS GIS Cut Line= 4
      2641953.16     10042601.49      2642723.97     10042066.79
      2642779.53     10041733.45      2643897.04     10040928.29
#Sta/Elev= 30
  3881.1 2058.33  3932.7 2057.46  4023.3 2054.82  4058.6 2054.32  4341.7 2047.79
  4444.3 2045.03  4544.8  2040.4  4638.2 2030.78  4709.8 2028.95  4877.5 2027.97
  4900.4 2024.77  4903.2 2024.27  4906.4 2024.77  4923.7 2026.49  4964.2 2027.59
  4984.4  2025.7  4994.1 2024.84  5035.2  2026.3  5065.6 2030.77  5126.5  2035.3
  5197.7 2037.07  5264.4 2038.16  5426.4 2039.03  5453.5 2039.87  5591.5 2046.06
  5658.2 2049.66  5801.1 2051.34  6007.9 2055.05  6431.3 2068.17  6534.5  2072.6
#Mann= 14 ,-1 , 0
  3881.1     .16       0  3932.7      .1       0  4023.3     .16       0
  4058.6      .1       0  4341.7     .16       0  4900.4     .07       0
  4906.4     .16       0  4984.4      .1       0  5197.7     .16       0
  5264.4      .1       0  5426.4     .16       0  5453.5      .1       0
  5591.5     .16       0  5801.1      .1       0
Bank Sta=4638.2,5065.6
XS Rating Curve= 0 ,0
Exp/Cntr=0.3,0.1

Type RM Length L Ch R = 1 ,12222   ,388,388,388
BEGIN DESCRIPTION:
STEVENS CREEK 27.0
END DESCRIPTION:
XS GIS Cut Line= 3
       2642328.1     10042865.42      2643119.81     10042351.51
      2644071.18     10041115.42
#Sta/Elev= 30
  3876.3  2053.8  4150.5 2044.68  4153.9 2044.55  4217.8 2042.08  4405.1 2037.42
  4441.3  2034.7  4462.4 2030.36  4484.8 2027.14  4556.3 2023.78  4603.9 2025.16
  4737.3 2026.23  4839.4 2025.64  4860.3 2024.42  4889.3 2025.41  4959.9 2023.98
  5000.4 2019.04  5003.2 2018.54  5006.4 2019.04  5031.9  2024.8  5082.3  2027.1
  5145.5 2032.19  5152.9 2032.02  5223.6 2036.87  5316.9  2039.1  5495.4 2046.16
  5574.3 2051.03  5767.8  2053.3  5829.7 2054.05  5923.1  2057.1    6380 2075.06
#Mann= 7 ,-1 , 0
  3876.3      .1       0  4150.5     .16       0  4153.9      .1       0
  4603.9     .16       0  5000.4     .07       0  5006.4     .16       0
  5767.8      .1       0
Bank Sta=4484.8,5082.3
XS Rating Curve= 0 ,0
Exp/Cntr=0.3,0.1

Type RM Length L Ch R = 1 ,11834   ,818,818,818
BEGIN DESCRIPTION:
STEVENS CREEK 26.0
END DESCRIPTION:
XS GIS Cut Line= 2
      2642397.58     10043018.18      2644557.33     10041802.89
#Sta/Elev= 30
  3703.6 2052.29  3759.6 2050.52  3905.9 2044.51    3980 2043.73  4305.7 2033.11
  4319.8 2032.39    4338 2030.81  4359.7 2025.96    4419 2021.29  4499.9 2023.23
  4611.1 2022.18  4662.8  2024.6  4748.8 2024.83  4807.8 2021.08  4829.4 2023.64
    4898 2024.95  4929.2 2023.93  4978.3  2021.9  4998.2 2018.49    5001 2017.99
  5004.2 2018.49  5028.9  2024.4  5035.7 2028.66  5044.9 2031.14  5088.2 2037.53
  5323.7 2042.22  5619.5 2048.08  5813.7 2052.59  6060.5 2055.59  6181.8 2057.42
#Mann= 12 ,-1 , 0
  3703.6     .16       0  3759.6      .1       0  4305.7     .16       0
  4319.8      .1       0  4662.8     .16       0  4929.2      .1       0
  4998.2     .07       0  5004.2      .1       0  5323.7     .16       0
  5619.5      .1       0  5813.7     .16       0  6060.5      .1       0
Bank Sta=4898,5028.9
XS Rating Curve= 0 ,0
Exp/Cntr=0.3,0.1

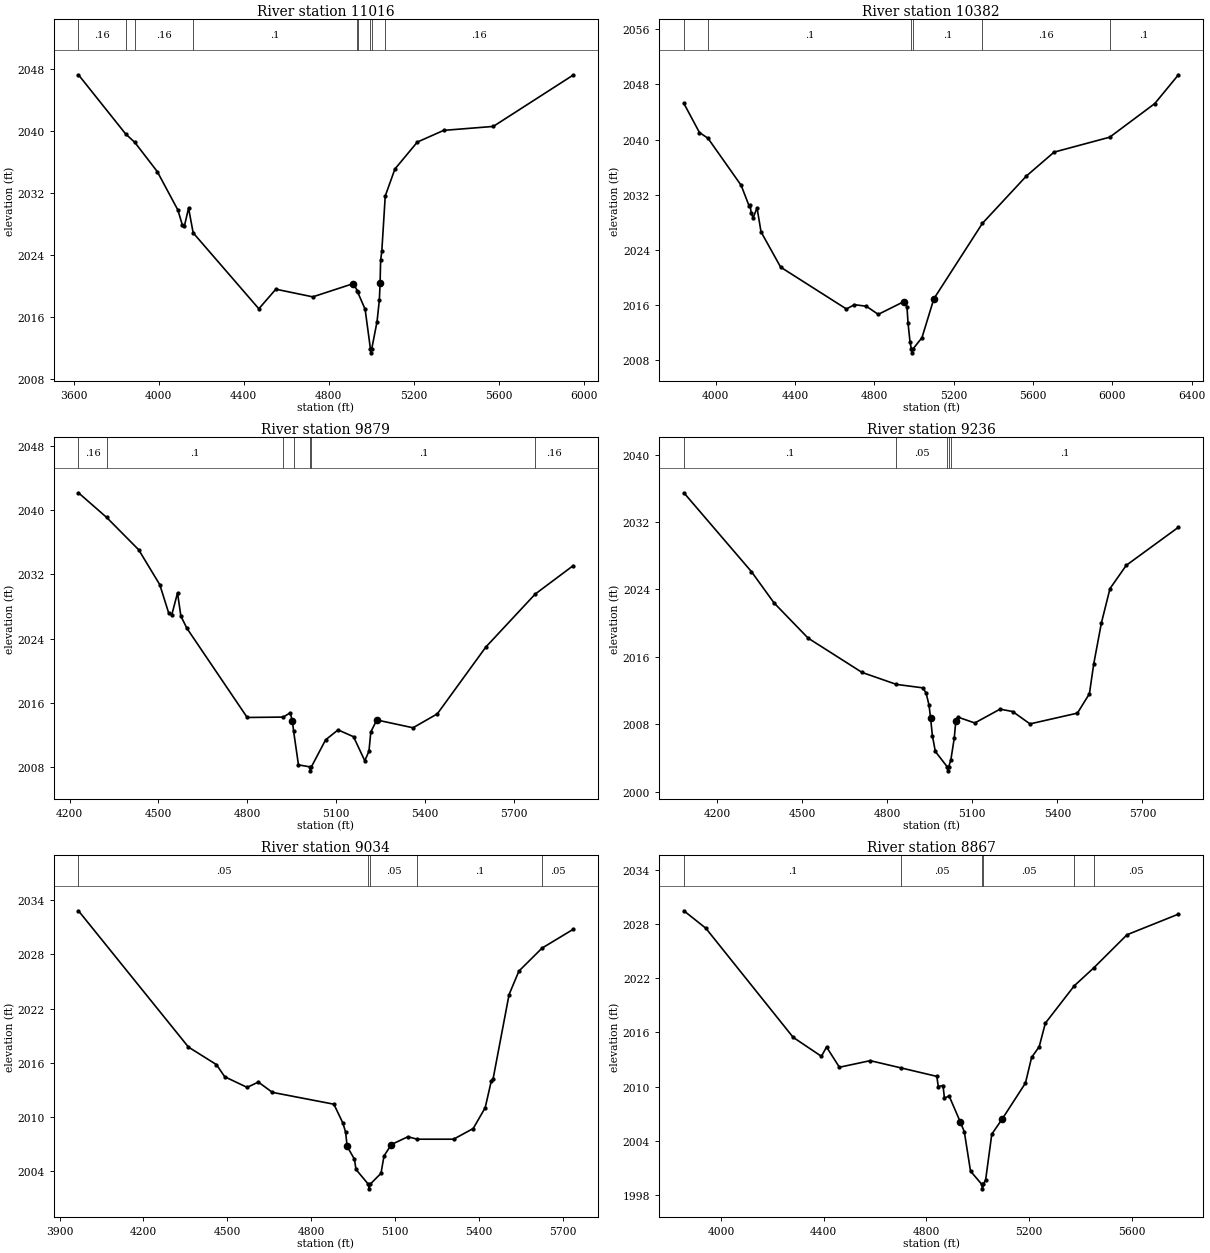
Type RM Length L Ch R = 1 ,11016   ,634,634,634
BEGIN DESCRIPTION:
STEVENS CREEK 24.0
END DESCRIPTION:
XS GIS Cut Line= 3
      2642571.23      10043240.4       2643633.7      10043177.9
      2644764.56     10042615.93
#Sta/Elev= 30
    3622 2047.29  3844.6 2039.62  3887.1 2038.55  3992.9 2034.77    4090 2029.79
  4110.1 2027.92  4120.1 2027.68  4140.1 2030.05  4161.7 2026.85  4470.7 2017.03
  4550.8 2019.56  4724.5 2018.57    4915 2020.28    4934 2019.38  4935.9 2019.18
  4970.8 2016.96  4995.9 2011.83  4998.6 2011.33  5001.9 2011.83  5026.9 2015.37
  5037.8 2018.17 5041.19 2020.31  5043.7 2023.28  5049.3 2024.47  5065.5 2031.61
  5110.9  2035.1  5216.5 2038.59  5340.5  2040.1  5573.8 2040.61  5949.1 2047.24
#Mann= 9 ,-1 , 0
    3622     .16       0  3844.6      .1       0  3887.1     .16       0
  4161.7      .1       0    4934     .16       0  4935.9      .1       0
  4995.9     .07       0  5001.9      .1       0  5065.5     .16       0
Bank Sta=4915,5041.19
XS Rating Curve= 0 ,0
Exp/Cntr=0.3,0.1

Type RM Length L Ch R = 1 ,10382   ,503,503,503
BEGIN DESCRIPTION:
STEVENS CREEK 23.0
END DESCRIPTION:
XS GIS Cut Line= 3
      2642710.08     10043587.62      2644244.81     10043684.84
      2645099.02     10043254.27
#Sta/Elev= 30
  3838.9 2045.25  3917.4 2041.02  3960.6 2040.18  4127.9 2033.34  4167.9 2030.35
  4172.9 2030.51    4178 2029.39    4188 2028.61    4208 2030.06  4228.1 2026.58
  4327.1 2021.45  4658.9 2015.37    4699    2016  4759.1 2015.77  4819.3 2014.59
  4949.5 2016.46  4964.1 2015.69  4969.6 2013.28  4979.6 2010.57  4986.6  2009.5
  4989.3    2009  4992.6  2009.5  5039.7  2011.2  5099.8 2016.86  5344.6 2027.82
  5566.8 2034.71  5706.2 2038.17  5986.6 2040.34  6213.7 2045.22  6333.3 2049.41
#Mann= 6 ,-1 , 0
  3838.9     .16       0  3960.6      .1       0  4986.6     .07       0
  4992.6      .1       0  5344.6     .16       0  5986.6      .1       0
Bank Sta=4949.5,5099.8
XS Rating Curve= 0 ,0
Exp/Cntr=0.3,0.1

Type RM Length L Ch R = 1 ,9879    ,643,643,643
BEGIN DESCRIPTION:
STEVENS CREEK 22.0
END DESCRIPTION:
XS GIS Cut Line= 3
      2643008.73     10044282.06      2644175.36     10044059.84
      2644619.82     10043872.34
#Sta/Elev= 30
    4230 2042.13  4324.8 2039.08  4433.3 2035.05  4504.6 2030.71  4535.1 2027.14
  4545.3 2026.99  4564.5 2029.69  4575.8 2026.81  4596.2 2025.29  4799.8 2014.21
  4921.4 2014.26    4945 2014.79  4952.5 2013.73  4956.3 2012.55  4972.9 2008.32
  5010.6 2008.08  5013.3 2007.58  5016.6 2008.08  5064.5 2011.43  5106.6 2012.67
  5158.8 2011.82  5196.8 2008.83  5210.9 2010.02  5217.2 2012.42  5237.5  2013.9
  5359.7 2012.93  5441.7 2014.66  5605.7 2022.97  5772.4 2029.55    5900 2033.06
#Mann= 7 ,-1 , 0
    4230     .16       0  4324.8      .1       0  4921.4     .05       0
  4956.3      .1       0  5010.6     .07       0  5016.6      .1       0
  5772.4     .16       0
Bank Sta=4952.5,5237.5
XS Rating Curve= 0 ,0
Exp/Cntr=0.3,0.1

Type RM Length L Ch R = 1 ,9236    ,202,202,202
BEGIN DESCRIPTION:
STEVENS CREEK 21.0
END DESCRIPTION:
XS GIS Cut Line= 4
      2643170.12     10044747.84      2643878.41     10044761.73
      2644357.58     10044518.67      2644777.06     10044248.26
#Sta/Elev= 30
  4082.2 2035.46  4320.6  2026.1  4400.6 2022.38  4520.6 2018.21  4710.7 2014.14
  4831.9 2012.72  4924.8 2012.31  4936.5 2011.72    4947 2010.27  4952.6 2008.71
  4958.9 2006.65  4969.3 2004.76  5010.8 2002.96  5013.6 2002.46  5016.8 2002.96
  5024.2 2003.79  5036.1 2006.34  5041.7 2008.43  5048.6 2008.84  5108.5 2008.14
  5197.6 2009.78  5242.1  2009.5  5303.3 2008.03  5470.6 2009.31  5512.9 2011.61
  5528.1 2015.14  5555.1    2020  5585.5 2024.09  5642.9 2026.85    5827 2031.37
#Mann= 5 ,-1 , 0
  4082.2      .1       0  4831.9     .05       0  5010.8    .035       0
  5016.8     .05       0  5024.2      .1       0
Bank Sta=4952.6,5041.7
XS Rating Curve= 0 ,0
Exp/Cntr=0.3,0.1

Type RM Length L Ch R = 1 ,9034    ,167,167,167
BEGIN DESCRIPTION:
STEVENS CREEK 20.0
END DESCRIPTION:
XS GIS Cut Line= 4
      2643215.22     10044883.25       2643930.5     10044876.31
      2644336.75     10044740.89      2644808.95     10044331.19
#Sta/Elev= 30
  3967.6 2032.82  4360.9 2017.75  4460.9 2015.81  4490.9 2014.46  4570.9 2013.29
  4610.9 2013.88  4660.9 2012.74    4881 2011.43  4912.7 2009.38  4923.1 2008.33
  4928.4 2006.76  4954.7 2005.34    4960 2004.22  5004.5 2002.57  5007.3 2002.07
  5010.5 2002.57  5049.6 2003.79  5060.2  2005.7  5086.5 2006.97  5145.7 2007.83
    5179 2007.56  5309.1 2007.56  5379.3 2008.74  5422.1 2011.04    5444    2014
  5450.6 2014.26  5507.6 2023.56  5542.7 2026.15  5625.4 2028.69  5736.3 2030.76
#Mann= 5 ,-1 , 0
  3967.6     .05       0  5004.5     .04       0  5010.5     .05       0
    5179      .1       0  5625.4     .05       0
Bank Sta=4928.4,5086.5
XS Rating Curve= 0 ,0
Exp/Cntr=0.3,0.1

Type RM Length L Ch R = 1 ,8867    ,122,122,122
BEGIN DESCRIPTION:
STEVENS CREEK 18.0
END DESCRIPTION:
XS GIS Cut Line= 4
      2643242.98     10045039.51      2644034.66     10045011.73
      2644614.52     10044775.62      2644965.19     10044407.59
#Sta/Elev= 30
  3855.6 2029.45  3941.1 2027.52  4281.3 2015.45  4391.4 2013.35  4411.4 2014.38
  4461.5 2012.14  4581.5 2012.87  4702.6 2012.06  4841.1 2011.13  4846.5 2010.01
  4865.1 2010.12  4870.5 2008.75  4889.2 2008.94  4932.6 2006.08  4948.1    2005
  4972.2 2000.65    5016 1999.19  5018.7 1998.69    5022 1999.19  5031.1 1999.68
  5055.1 2004.74  5094.6 2006.37  5186.2 2010.39  5210.2 2013.23  5239.7 2014.41
  5263.8 2017.02  5376.4 2021.15  5452.5 2023.14    5582  2026.8  5782.2 2029.08
#Mann= 6 ,-1 , 0
  3855.6      .1       0  4702.6     .05       0    5016     .04       0
    5022     .05       0  5376.4      .1       0  5452.5     .05       0
Bank Sta=4932.6,5094.6
XS Rating Curve= 0 ,0
Exp/Cntr=0.3,0.1

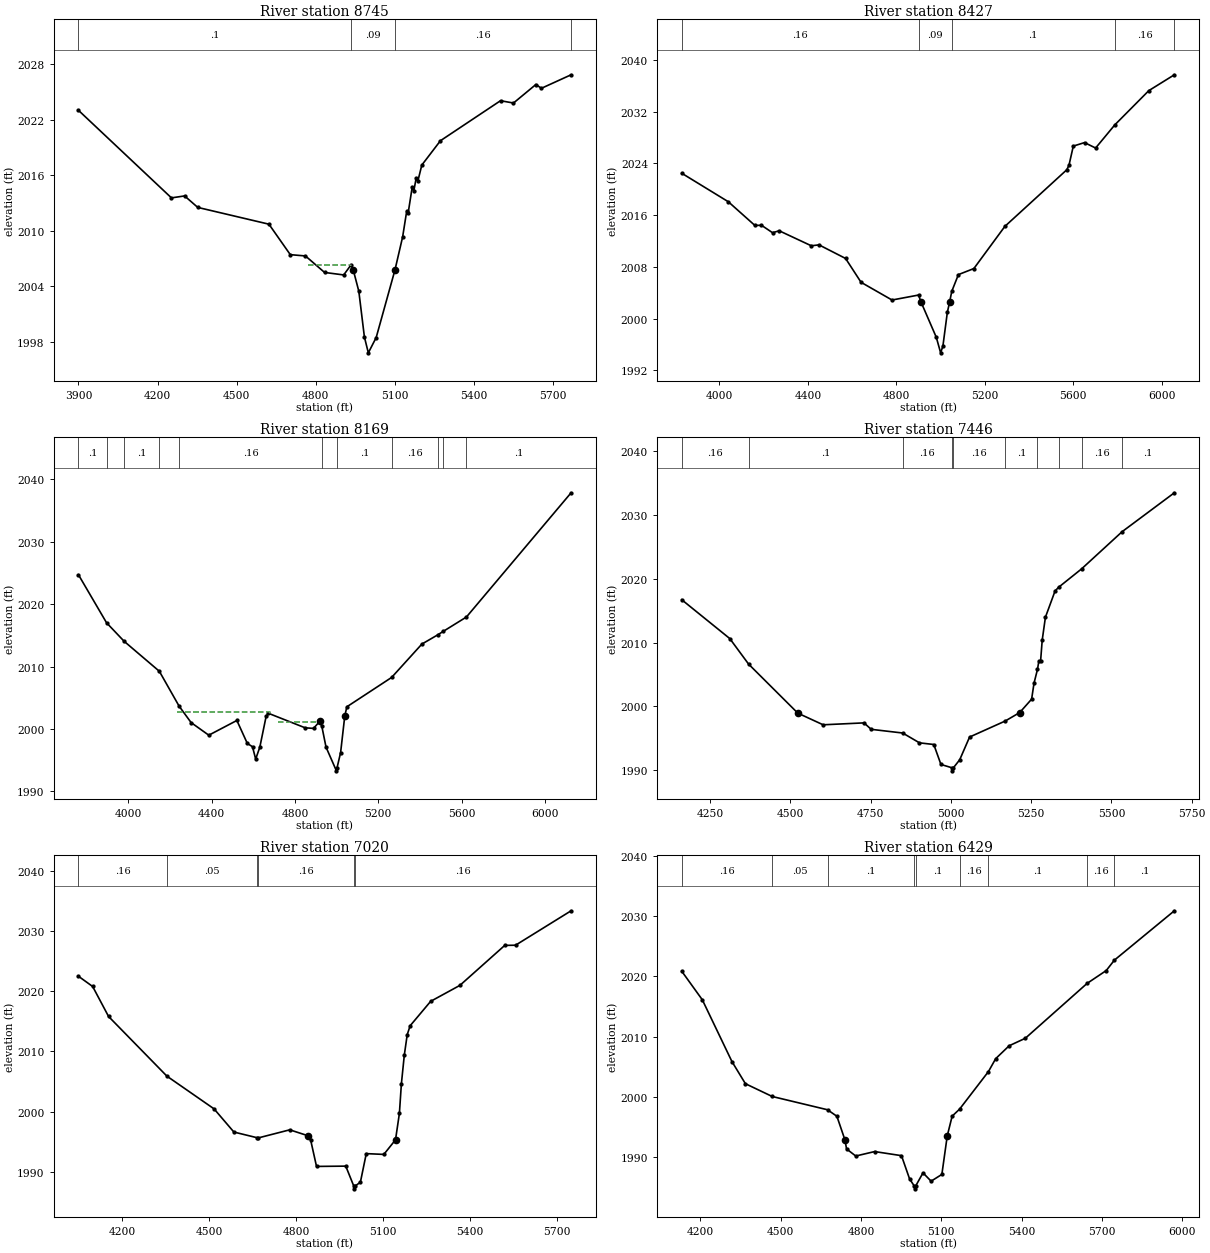
Type RM Length L Ch R = 1 ,8745    ,318,318,318
BEGIN DESCRIPTION:
STEVENS CREEK 19.0
END DESCRIPTION:
XS GIS Cut Line= 4
      2643395.77      10045164.5      2644166.61     10045147.14
      2644673.55     10044820.75      2645013.67     10044459.82
#Sta/Elev= 30
    3900    2023  4252.8 2013.55  4302.8 2013.76  4352.8 2012.52  4622.9 2010.71
    4704 2007.42  4761.5 2007.28  4834.1  2005.5  4906.7 2005.23  4934.9 2006.33
    4943 2005.77  4964.1 2003.47  4985.3 1998.53  5000.2 1996.82    5030 1998.47
  5101.4 2005.78  5130.5 2009.35  5145.7 2012.09  5151.7 2011.97  5166.8 2014.72
  5172.8 2014.29    5182 2015.71    5188 2015.34  5203.2 2017.09  5273.9 2019.72
  5501.9 2024.04  5551.2 2023.79  5636.2 2025.79  5657.2 2025.38  5769.9 2026.84
#Mann= 4 ,-1 , 0
    3900      .1       0  4934.9     .09       0  5101.4     .16       0
  5769.9     .16       0
#XS Ineff= 1 ,-1
 4771.31 4936.08 2006.35
Permanent Ineff=
       F
Bank Sta=4943,5101.4
XS Rating Curve= 0 ,0
Exp/Cntr=0.3,0.1

Type RM Length L Ch R = 1 ,8427    ,258,258,258
BEGIN DESCRIPTION:
Mapping XS 04d712bc
END DESCRIPTION:
XS GIS Cut Line= 3
      2643367.95     10045233.95      2645156.19     10045279.09
      2645593.56     10045247.85
#Sta/Elev= 30
  3829.5 2022.47  4040.1 2018.06  4160.1  2014.4  4190.1 2014.42  4240.1 2013.27
  4270.2 2013.57  4415.3 2011.25  4450.2 2011.39  4570.3 2009.29  4640.3  2005.6
  4780.3 2002.86  4900.4 2003.63  4910.4 2002.63  4980.4  1997.1  5000.1 1994.69
  5010.4 1995.75  5030.4 2000.96  5040.4  2002.5  5050.4  2004.2  5080.4 2006.79
  5150.4 2007.73  5290.5 2014.25  5570.6 2023.01  5580.6 2023.74  5599.9 2026.67
  5650.7 2027.21  5700.8 2026.37  5787.3 2029.94  5941.4 2035.25  6056.8  2037.7
#Mann= 5 ,-1 , 0
  3829.5     .16       0  4900.4     .09       0  5050.4      .1       0
  5787.3     .16       0  6056.8     .16       0
Bank Sta=4910.4,5040.4
XS Rating Curve= 0 ,0
Exp/Cntr=0.3,0.1

Type RM Length L Ch R = 1 ,8169    ,723,723,723
BEGIN DESCRIPTION:
STEVENS CREEK 17.0
END DESCRIPTION:
XS GIS Cut Line= 4
      2643839.43     10046368.87      2644290.81      10045908.8
      2644316.86     10045518.18      2645644.21     10045526.85
#Sta/Elev= 30
  3761.6  2024.7  3896.2 2017.02  3980.3 2014.06  4149.5 2009.25  4244.2 2003.67
  4301.9 2001.03  4386.8 1999.01  4521.5 2001.37  4571.6 1997.69  4596.5 1997.16
  4611.7 1995.18  4631.7 1997.11  4661.8 2002.02  4671.8 2002.53  4849.2 2000.19
  4889.2  2000.1  4919.2 2001.23  4929.2 2000.42  4949.2  1997.1    4999  1993.3
  5002.2  1993.8  5019.2 1996.23  5039.2  2002.1  5049.2 2003.56  5263.9 2008.26
  5409.2 2013.61  5484.1 2015.06  5511.1 2015.63  5622.8 2017.94    6125 2037.84
#Mann= 11 ,-1 , 0
  3761.6      .1       0  3896.2     .16       0  3980.3      .1       0
  4149.5     .16       0  4244.2     .16       0  4929.2     .09       0
  5002.2      .1       0  5263.9     .16       0  5484.1      .1       0
  5511.1     .16       0  5622.8      .1       0
#XS Ineff= 2 ,-1
 4232.95 4681.25  2002.7 4717.05 4914.77 2001.14
Permanent Ineff=
       F       F
Bank Sta=4919.2,5039.2
XS Rating Curve= 0 ,0
Exp/Cntr=0.3,0.1

Type RM Length L Ch R = 1 ,7446    ,426,426,426
BEGIN DESCRIPTION:
STEVENS CREEK 16.0
END DESCRIPTION:
XS GIS Cut Line= 3
      2644065.11      10046533.8      2645063.38     10046030.33
      2645480.05     10046021.65
#Sta/Elev= 30
  4161.3 2016.73    4311 2010.64  4369.7 2006.63  4522.9 1998.95  4601.8 1997.12
  4729.2 1997.42  4751.5 1996.41  4849.7 1995.83    4902 1994.29  4946.6 1994.03
  4968.9  1990.9    5002  1990.4  5004.8  1989.9    5008  1990.4  5027.4 1991.64
  5058.1  1995.2  5169.1 1997.71  5214.3 1999.04  5251.4 2001.14  5258.9 2003.65
  5269.7 2005.82  5273.8 2007.08  5279.3 2007.08  5284.4  2010.4  5294.4 2013.99
  5324.4  2018.1  5335.4 2018.68  5406.9 2021.56  5533.4  2027.4  5696.1  2033.5
#Mann= 10 ,-1 , 0
  4161.3     .16       0  4369.7      .1       0  4849.7     .16       0
    5002     .07       0    5008     .16       0  5169.1      .1       0
  5269.7     .16       0  5335.4      .1       0  5406.9     .16       0
  5533.4      .1       0
Bank Sta=4522.9,5214.3
XS Rating Curve= 0 ,0
Exp/Cntr=0.3,0.1

Type RM Length L Ch R = 1 ,7020    ,591,591,591
BEGIN DESCRIPTION:
STEVENS CREEK 15.0
END DESCRIPTION:
XS GIS Cut Line= 3
      2644047.79     10046846.29      2644750.88      10046577.2
      2645688.36       10046447.
#Sta/Elev= 30
  4049.1 2022.51    4098 2020.81  4152.9 2015.82  4354.2 2005.89  4516.7 2000.45
  4585.2 1996.59  4664.1 1995.66  4668.1  1995.6  4777.9 1996.96  4839.9 1995.99
    4850 1995.26  4870.2 1990.87  4971.1 1990.92  4998.4 1987.64  5001.2 1987.14
  5004.4 1987.64  5021.6 1988.25  5041.8    1993  5102.4 1992.87  5142.7  1995.3
  5156.1 1999.69  5162.9 2004.59    5173 2009.38  5183.1  2012.8  5193.2 2014.28
  5263.9 2018.34  5364.9    2021  5519.5 2027.65  5556.7 2027.68  5748.4 2033.41
#Mann= 6 ,-1 , 0
  4049.1     .16       0  4354.2     .05       0  4664.1      .1       0
  4668.1     .16       0  4998.4     .07       0  5004.4     .16       0
Bank Sta=4839.9,5142.7
XS Rating Curve= 0 ,0
Exp/Cntr=0.3,0.1

Type RM Length L Ch R = 1 ,6429    ,387,387,387
BEGIN DESCRIPTION:
STEVENS CREEK 14.0
END DESCRIPTION:
XS GIS Cut Line= 3
      2644151.92     10047210.89      2645436.65     10047080.68
      2645887.61     10046768.47
#Sta/Elev= 30
  4130.6 2020.83  4207.5 2016.09  4318.1 2005.85  4368.4 2002.18  4468.6 2000.06
  4675.1 1997.86  4710.1 1996.78  4740.3 1992.84  4746.1 1991.37  4780.5 1990.19
    4851 1990.93  4951.3 1990.25  4981.5  1986.4  4998.6 1985.25  5001.3 1984.75
  5004.6 1985.25  5031.7  1987.4  5061.9 1986.02  5102.1 1987.14  5122.2 1993.53
  5140.5  1996.8  5168.2 1997.96  5276.2  2004.2  5303.1 2006.33  5353.4 2008.47
  5413.7 2009.71  5644.5 2018.81    5716 2020.94  5746.3 2022.66  5970.4 2030.85
#Mann= 9 ,-1 , 0
  4130.6     .16       0  4468.6     .05       0  4675.1      .1       0
  4998.6     .07       0  5004.6      .1       0  5168.2     .16       0
  5276.2      .1       0  5644.5     .16       0  5746.3      .1       0
Bank Sta=4740.3,5122.2
XS Rating Curve= 0 ,0
Exp/Cntr=0.3,0.1