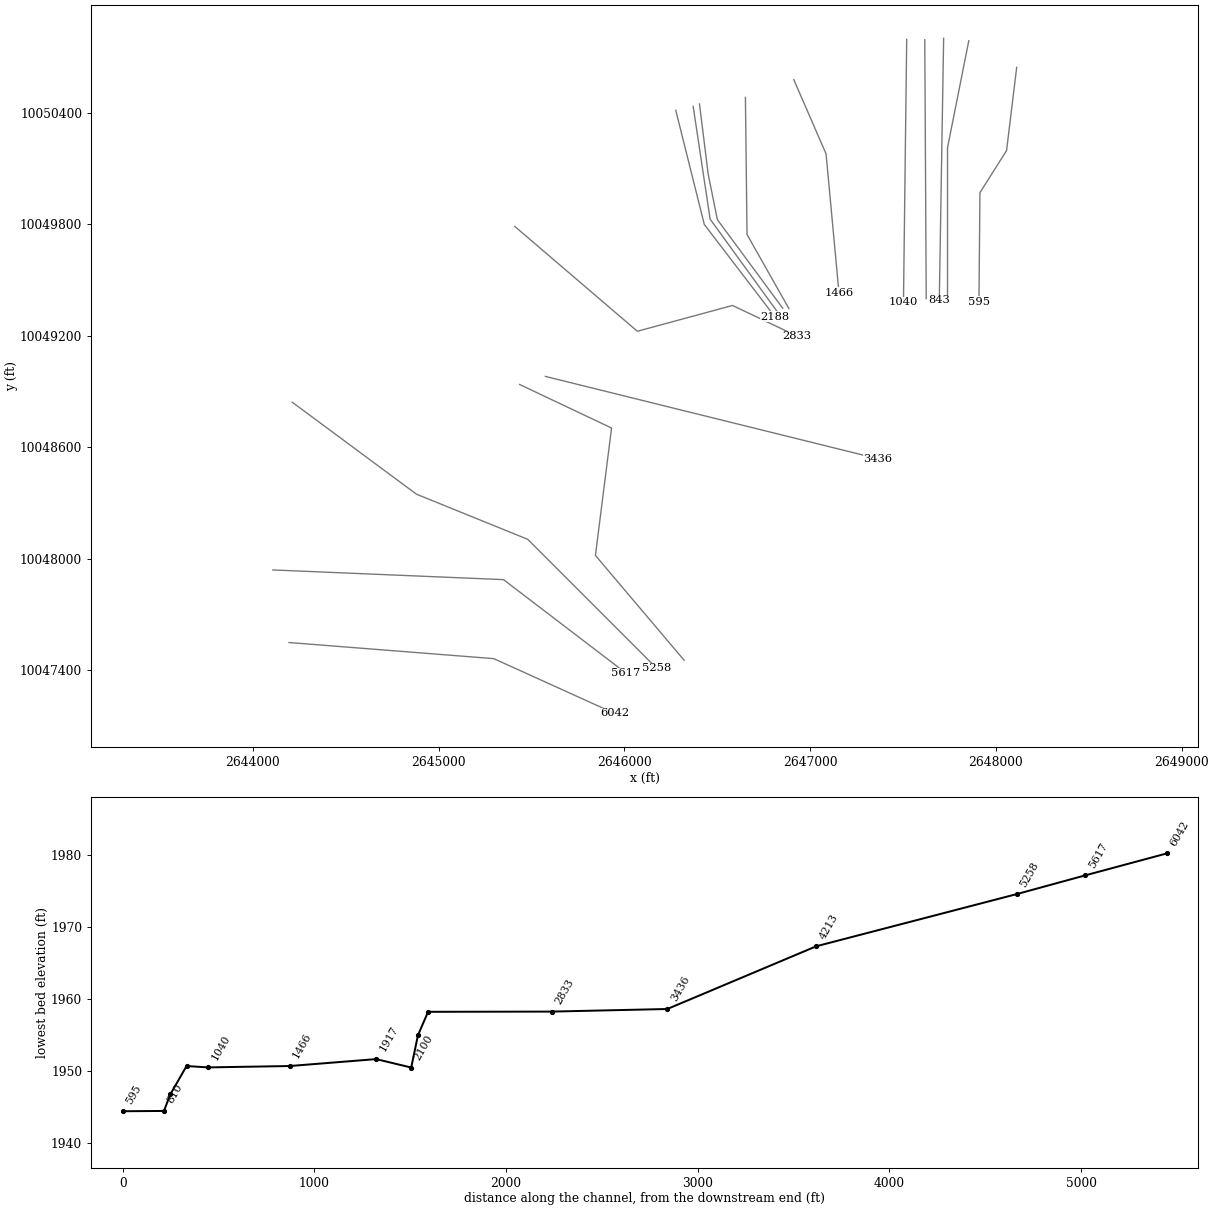
HEC-RAS study STEVENS CREEK.prj: STEVENS CREEK Base Level Engineering

--- STEVENS CREEK.g01 (geometry) --- (continued)

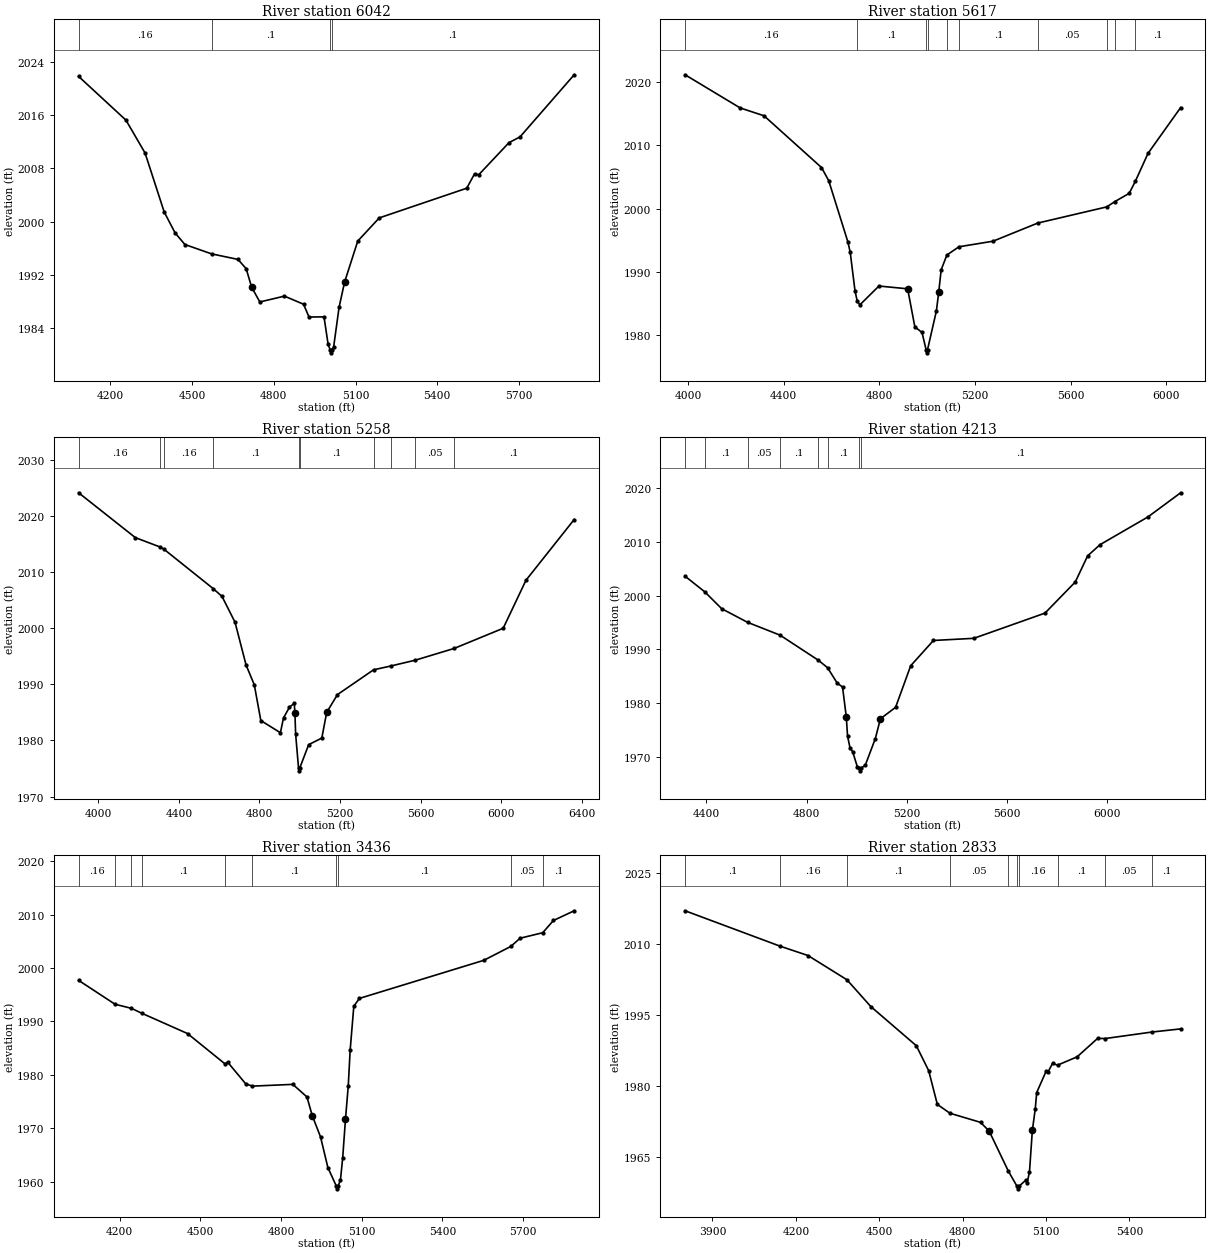
Type RM Length L Ch R = 1 ,6042    ,425,425,425
BEGIN DESCRIPTION:
STEVENS CREEK 13.0
END DESCRIPTION:
XS GIS Cut Line= 3
      2644195.31     10047549.43      2645297.76     10047462.62
      2645947.45     10047168.09
#Sta/Elev= 30
  4083.4 2021.85  4257.1 2015.27  4327.3 2010.32  4397.5 2001.44  4437.7 1998.28
  4473.6 1996.54  4571.7 1995.13  4668.4  1994.3  4698.5  1992.9  4718.5 1990.12
  4748.6 1987.89  4838.9 1988.77  4909.1 1987.55  4929.2 1985.62  4984.2 1985.65
  4999.4 1981.49  5006.4 1980.73  5009.2 1980.23  5012.4 1980.73  5019.4 1981.06
  5039.5 1987.08  5059.6 1990.86  5108.1 1997.06  5187.1 2000.55  5508.2 2005.02
  5536.8 2007.18  5552.4 2007.05  5663.3 2011.88  5703.9 2012.75  5902.6  2022.1
#Mann= 4 ,-1 , 0
  4083.4     .16       0  4571.7      .1       0  5006.4     .07       0
  5012.4      .1       0
Bank Sta=4718.5,5059.6
XS Rating Curve= 0 ,0
Exp/Cntr=0.3,0.1

Type RM Length L Ch R = 1 ,5617    ,359,359,359
BEGIN DESCRIPTION:
STEVENS CREEK 12.0
END DESCRIPTION:
XS GIS Cut Line= 3
      2644108.54     10047940.05      2645349.84     10047887.97
      2646009.57     10047384.49
#Sta/Elev= 30
  3987.9 2021.18    4218 2015.94  4318.1 2014.69  4558.3 2006.51  4588.4 2004.44
  4668.4 1994.77  4678.4  1993.1  4698.5 1986.98  4707.2 1985.47  4718.5 1984.77
  4798.5 1987.76  4918.6 1987.32  4948.7  1981.3  4978.7 1980.41  4995.7 1977.69
  4998.5 1977.19  5001.7 1977.69  5038.8 1983.82  5048.8 1986.88  5058.8 1990.33
  5082.7 1992.67  5133.2 1993.97  5275.5 1994.85  5462.7 1997.72  5751.3 2000.28
  5785.5 2001.13  5845.1 2002.42  5870.8 2004.33    5924 2008.76  6060.2 2015.99
#Mann= 10 ,-1 , 0
  3987.9     .16       0  4707.2      .1       0  4995.7     .07       0
  5001.7      .1       0  5082.7     .16       0  5133.2      .1       0
  5462.7     .05       0  5751.3      .1       0  5785.5     .05       0
  5870.8      .1       0
Bank Sta=4918.6,5048.8
XS Rating Curve= 0 ,0
Exp/Cntr=0.3,0.1

Type RM Length L Ch R = 1 ,5258    ,1045,1045,1045
BEGIN DESCRIPTION:
STEVENS CREEK 11.0
END DESCRIPTION:
XS GIS Cut Line= 4
       2644212.7     10048842.82      2644881.09     10048348.04
      2645480.05     10048104.98      2646174.01     10047411.02
#Sta/Elev= 30
  3902.7 2024.18  4184.2 2016.18  4308.9 2014.48  4325.6 2014.13  4570.3 2007.09
  4614.2  2005.7  4678.9 2001.09  4733.7 1993.46  4774.6 1989.92  4806.9 1983.55
  4904.1 1981.38  4919.5 1984.01    4949 1985.93    4973 1986.63 4976.14 1984.87
  4979.7 1981.14  4994.1 1975.08  4996.9 1974.58  5000.1 1975.08  5044.4 1979.25
  5109.7 1980.43  5133.8 1985.01  5187.3 1988.18  5366.4  1992.6  5450.7 1993.27
  5573.8 1994.32  5766.1 1996.41  6009.8 2000.01  6122.9 2008.58  6362.1 2019.41
#Mann= 10 ,-1 , 0
  3902.7     .16       0  4308.9      .1       0  4325.6     .16       0
  4570.3      .1       0  4994.1     .07       0  5000.1      .1       0
  5366.4     .05       0  5450.7      .1       0  5573.8     .05       0
  5766.1      .1       0
Bank Sta=4976.14,5133.8
XS Rating Curve= 0 ,0
Exp/Cntr=0.3,0.1

Type RM Length L Ch R = 1 ,4213    ,777,777,777
BEGIN DESCRIPTION:
STEVENS CREEK 9.0
END DESCRIPTION:
XS GIS Cut Line= 4
      2645436.61     10048938.33      2645931.44     10048703.94
      2645844.63     10048018.18      2646322.07     10047453.94
#Sta/Elev= 30
  4315.4 2003.64  4394.4 2000.71  4461.3 1997.59  4564.8 1995.04  4694.5 1992.65
  4847.1 1987.98  4884.1 1986.58  4922.5 1983.71  4943.8 1982.98 4958.81 1977.42
  4963.9  1973.8    4974 1971.56  4984.1 1970.95  5002.6 1968.14  5011.3 1967.85
  5014.1 1967.35  5017.3 1967.85  5034.5 1968.39  5074.8 1973.38    5095 1977.06
  5155.5 1979.19  5215.9 1986.95  5306.7 1991.66  5467.9 1992.06  5751.8 1996.76
  5872.7 2002.56  5922.1 2007.44  5971.5 2009.52  6162.6 2014.69  6293.3  2019.2
#Mann= 8 ,-1 , 0
  4315.4     .16       0  4394.4      .1       0  4564.8     .05       0
  4694.5      .1       0  4847.1     .05       0  4884.1      .1       0
  5011.3     .07       0  5017.3      .1       0
Bank Sta=4958.81,5095
XS Rating Curve= 0 ,0
Exp/Cntr=0.3,0.1

Type RM Length L Ch R = 1 ,3436    ,603,603,603
BEGIN DESCRIPTION:
STEVENS CREEK 7.0
END DESCRIPTION:
XS GIS Cut Line= 2
       2645575.5     10048981.73      2647363.62     10048539.04
#Sta/Elev= 30
  4047.5  1997.7  4182.9 1993.23    4244 1992.46    4282 1991.55  4452.3 1987.74
  4591.8 1982.05  4601.3 1982.39  4668.7 1978.32  4693.1 1977.89  4843.8 1978.22
  4896.3 1975.86  4915.9 1972.37  4946.8 1968.37    4974 1962.64  5005.6 1959.15
  5008.4 1958.65  5011.6 1959.15  5020.6 1960.22  5029.2 1964.52  5039.5 1971.73
  5049.8 1977.93  5056.8 1984.58  5070.4 1992.84    5091 1994.32  5553.7 2001.46
  5654.1 2004.06  5688.6  2005.6  5772.7 2006.63  5812.5 2008.92  5889.6 2010.74
#Mann= 10 ,-1 , 0
  4047.5     .16       0  4182.9      .1       0    4244     .16       0
    4282      .1       0  4591.8     .05       0  4693.1      .1       0
  5005.6     .07       0  5011.6      .1       0  5654.1     .05       0
  5772.7      .1       0
Bank Sta=4915.9,5039.5
XS Rating Curve= 0 ,0
Exp/Cntr=0.3,0.1

Type RM Length L Ch R = 1 ,2833    ,645,645,645
BEGIN DESCRIPTION:
STEVENS CREEK 6.0
END DESCRIPTION:
XS GIS Cut Line= 4
      2645410.61       10049789.      2646070.33     10049224.77
      2646582.48     10049363.66      2646929.67     10049198.75
#Sta/Elev= 30
  3801.4    2017  4141.6 2009.56  4243.7 2007.55  4383.6 2002.44  4469.8 1996.77
  4633.4 1988.51  4677.9 1983.24    4709 1976.12  4754.4 1974.25  4864.4 1972.33
  4895.5 1970.49  4964.3 1962.06  4996.1 1958.79  4998.9 1958.29  5002.1 1958.79
  5026.7 1960.09  5031.9 1959.47  5040.6 1961.87  5050.9 1970.62  5061.3 1975.13
  5066.6 1978.63  5101.2 1983.22  5106.4 1982.87  5123.5 1984.76  5141.7 1984.41
    5212 1986.16  5285.7 1990.05  5313.4 1990.03  5481.5  1991.4  5584.5 1992.06
#Mann= 10 ,-1 , 0
  3801.4      .1       0  4141.6     .16       0  4383.6      .1       0
  4754.4     .05       0  4964.3     .16       0  4996.1     .07       0
  5002.1     .16       0  5141.7      .1       0  5313.4     .05       0
  5481.5      .1       0
Bank Sta=4895.5,5050.9
XS Rating Curve= 0 ,0
Exp/Cntr=0.3,0.1

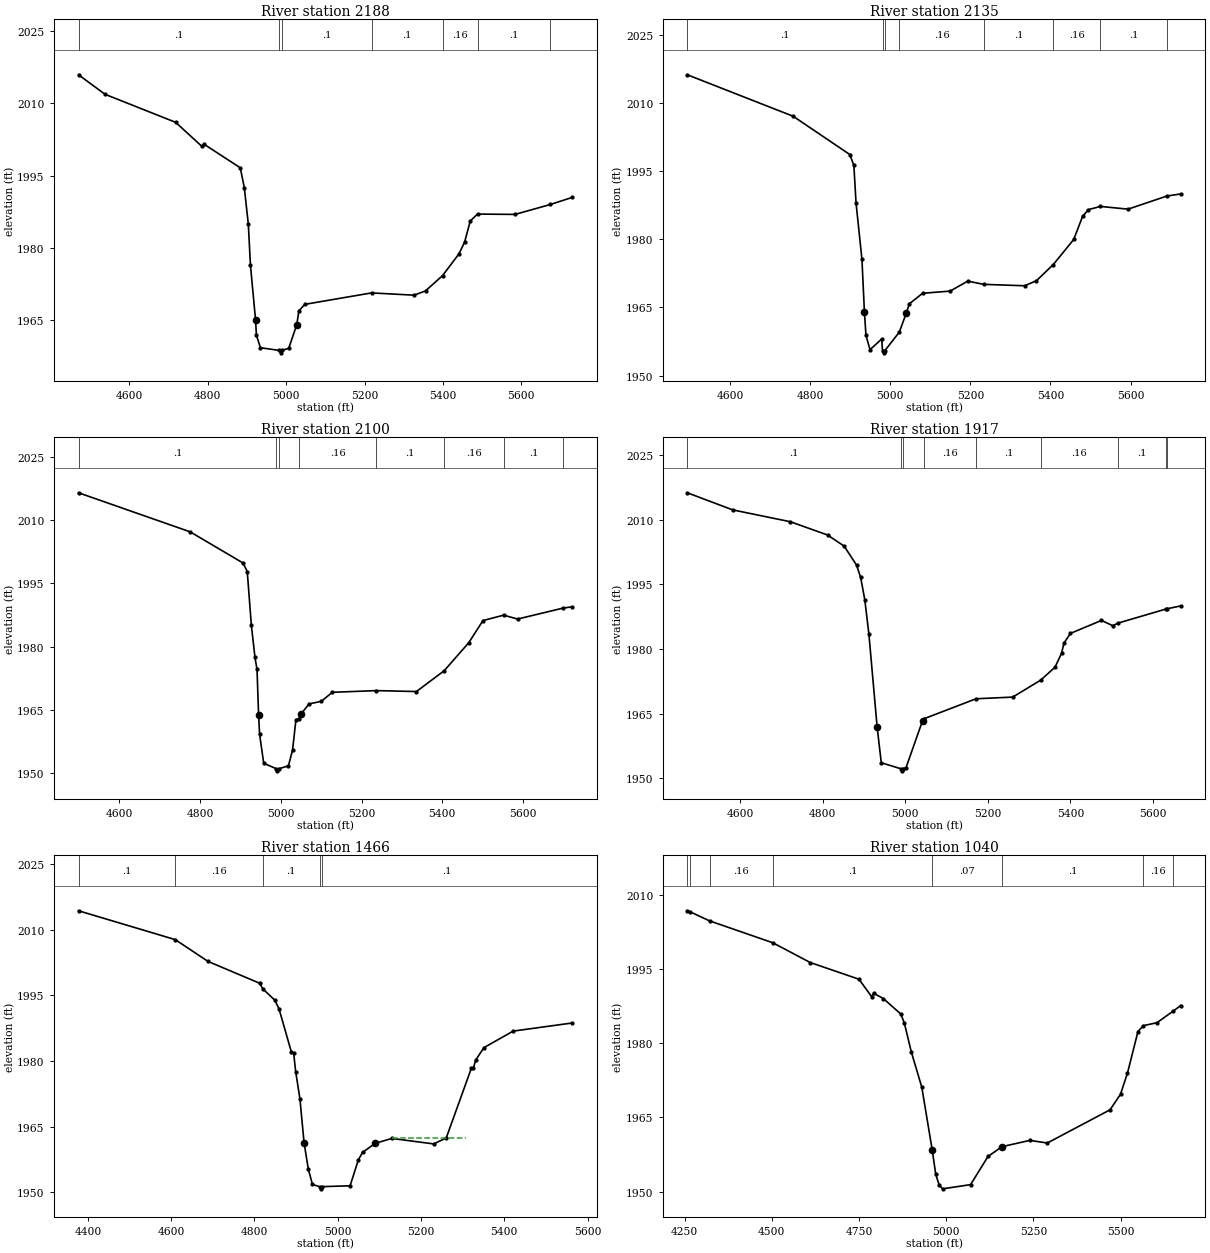
Type RM Length L Ch R = 1 ,2188    ,53,53,53
BEGIN DESCRIPTION:
Mapping XS 96dac1ca
END DESCRIPTION:
XS GIS Cut Line= 3
      2646277.02     10050414.27      2646430.67     10049799.66
      2646810.88     10049302.26
#Sta/Elev= 30
  4469.9 2015.93  4537.6 2011.88  4717.8 2006.07    4785 2001.07  4790.1 2001.54
  4882.8 1996.64  4893.1 1992.52  4903.4  1984.9  4908.7 1976.53 4921.82 1965.07
    4924 1961.92  4934.3 1959.32  4982.8 1958.76  4985.6 1958.26  4988.8 1958.76
  5006.5 1959.19  5027.1 1964.12  5032.4 1966.97  5047.7 1968.32    5218 1970.69
  5326.6 1970.22  5355.7 1971.11  5399.2 1974.28  5440.9 1978.77  5455.4  1981.2
    5470 1985.61  5488.4 1987.04  5584.2 1986.97  5674.5 1989.03  5729.5 1990.48
#Mann= 7 ,-1 , 0
  4469.9      .1       0  4982.8     .07       0  4988.8      .1       0
    5218      .1       0  5399.2     .16       0  5488.4      .1       0
  5674.5     .05       0
Bank Sta=4921.82,5027.1
XS Rating Curve= 0 ,0
Exp/Cntr=0.3,0.1

Type RM Length L Ch R = 1 ,2135    ,35,35,35
BEGIN DESCRIPTION:
Mapping XS 3e32aa3c
END DESCRIPTION:
XS GIS Cut Line= 3
      2646370.77     10050435.09      2646461.92     10049828.31
      2646825.38     10049327.25
#Sta/Elev= 30
  4492.9 2016.23  4757.2  2007.1  4898.8 1998.67  4908.9 1996.29  4914.4 1987.96
  4929.1 1975.61 4935.34 1963.93  4939.2 1958.83  4949.3  1955.7  4978.4 1958.04
  4980.5  1955.5  4983.2    1955  4986.5  1955.5  5022.6 1959.58  5040.3 1963.86
  5047.5  1965.8  5080.8 1968.12  5149.3 1968.59  5193.4 1970.79  5233.3 1970.08
  5335.6 1969.77    5365 1970.88  5407.1 1974.44  5458.1 1979.96  5480.2 1985.03
  5494.9 1986.54  5524.9 1987.24  5593.9 1986.64    5691 1989.53  5725.5 1989.99
#Mann= 8 ,-1 , 0
  4492.9      .1       0  4980.5     .07       0  4986.5      .1       0
  5022.6     .16       0  5233.3      .1       0  5407.1     .16       0
  5524.9      .1       0    5691     .05       0
Bank Sta=4935.34,5040.3
XS Rating Curve= 0 ,0
Exp/Cntr=0.3,0.1

Type RM Length L Ch R = 1 ,2100    ,183,183,183
BEGIN DESCRIPTION:
Mapping XS 087fe042
END DESCRIPTION:
XS GIS Cut Line= 4
      2646404.63     10050448.07       2646451.5     10050070.49
      2646500.98      10049825.7      2646852.53     10049349.16
#Sta/Elev= 30
  4498.8 2016.49  4775.2 2007.23  4906.6 1999.82  4916.8 1997.81    4927 1985.04
  4935.9 1977.45    4941 1974.59 4944.89 1963.84  4947.4 1959.19  4957.6 1952.33
  4988.7 1951.03  4991.5 1950.53  4994.7 1951.03  5018.8 1951.71    5029 1955.45
  5037.4 1962.63  5044.6 1962.93  5049.4 1963.92  5069.8  1966.4  5100.4 1967.03
  5127.5 1969.16  5236.6 1969.56  5335.9 1969.34  5404.7 1974.28  5465.4 1980.91
  5500.9 1986.18    5552 1987.46  5586.5 1986.54  5699.5 1989.14  5721.2 1989.43
#Mann= 8 ,-1 , 0
  4498.8      .1       0  4988.7     .07       0  4994.7      .1       0
  5044.6     .16       0  5236.6      .1       0  5404.7     .16       0
    5552      .1       0  5699.5     .05       0
Bank Sta=4944.89,5049.4
XS Rating Curve= 0 ,0
Exp/Cntr=0.3,0.1

Type RM Length L Ch R = 1 ,1917    ,451,451,451
BEGIN DESCRIPTION:
STEVENS CREEK 4.0
END DESCRIPTION:
XS GIS Cut Line= 3
      2646651.92     10050483.46      2646660.61     10049745.61
      2646885.62      10049347.5
#Sta/Elev= 30
  4472.2 2016.29  4581.9 2012.32  4721.9 2009.56  4811.9 2006.48    4852  2003.9
    4882 1999.52    4892 1996.64    4902  1991.5    4912 1983.48    4932 1961.84
    4942 1953.58    4989  1952.2  4991.7  1951.7    4995  1952.2    5002 1952.45
    5042 1963.35  5046.3 1963.83  5171.5 1968.44  5260.3 1968.83  5328.1 1972.76
  5362.8 1975.77  5378.7 1979.01  5384.6 1981.39  5400.3 1983.63  5475.4 1986.64
  5502.8 1985.41  5515.6 1986.02  5632.7 1989.32  5634.1 1989.34  5667.4 1990.01
#Mann= 9 ,-1 , 0
  4472.2      .1       0    4989     .07       0    4995      .1       0
  5046.3     .16       0  5171.5      .1       0  5328.1     .16       0
  5515.6      .1       0  5632.7     .05       0  5634.1      .1       0
Bank Sta=4932,5042
XS Rating Curve= 0 ,0
Exp/Cntr=0.3,0.1

Type RM Length L Ch R = 1 ,1466    ,426,426,426
BEGIN DESCRIPTION:
STEVENS CREEK 3.0
END DESCRIPTION:
XS GIS Cut Line= 3
      2646912.36      10050578.9      2647085.95     10050179.63
      2647155.39     10049433.13
#Sta/Elev= 30
  4377.5 2014.38  4609.8 2007.78  4688.5 2002.79  4812.9 1997.78  4819.8 1996.53
  4848.9 1993.92    4859 1991.95    4889 1981.96  4894.1 1981.87  4899.1 1977.53
  4909.2 1971.39  4919.2 1961.31  4929.3 1955.32  4939.3 1951.75  4956.4 1951.24
  4959.2 1950.74  4962.4 1951.24  5029.7 1951.44  5049.8 1957.43  5059.8 1959.09
    5090 1961.15  5130.1 1962.28  5230.6 1961.02  5260.7 1962.39  5320.9 1978.31
  5325.9 1978.31    5331 1980.15  5351.1 1983.05  5421.4 1986.84  5562.6 1988.69
#Mann= 5 ,-1 , 0
  4377.5      .1       0  4609.8     .16       0  4819.8      .1       0
  4956.4     .07       0  4962.4      .1       0
#XS Ineff= 1 ,-1
 5129.89 5307.27 1962.35
Permanent Ineff=
       F
Bank Sta=4919.2,5090
XS Rating Curve= 0 ,0
Exp/Cntr=0.3,0.1

Type RM Length L Ch R = 1 ,1040    ,112,112,112
BEGIN DESCRIPTION:
STEVENS CREEK 2.0
END DESCRIPTION:
XS GIS Cut Line= 2
      2647519.98     10050795.96      2647502.62     10049381.07
#Sta/Elev= 30
  4257.6 2006.73  4265.3 2006.53  4321.4 2004.69    4503 2000.26  4609.9 1996.28
  4749.9  1992.9  4786.7 1989.32  4791.7 1990.07  4819.9 1988.99  4869.9 1985.86
  4879.9 1984.06  4899.9 1978.22  4929.9 1971.11  4959.9  1958.4  4969.9 1953.52
  4979.9 1951.31  4989.6 1950.55  5069.9  1951.4  5119.9 1957.09  5159.9 1959.07
  5239.9 1960.34  5289.9 1959.81  5469.9 1966.52  5499.9 1969.67  5519.9 1973.96
  5549.9 1982.33  5565.3 1983.52  5604.3 1984.11  5649.8  1986.4  5672.6 1987.59
#Mann= 8 ,-1 , 0
  4257.6     .16       0  4265.3      .1       0  4321.4     .16       0
    4503      .1       0  4959.9     .07       0  5159.9      .1       0
  5565.3     .16       0  5649.8      .1       0
Bank Sta=4959.9,5159.9
XS Rating Curve= 0 ,0
Exp/Cntr=0.3,0.1

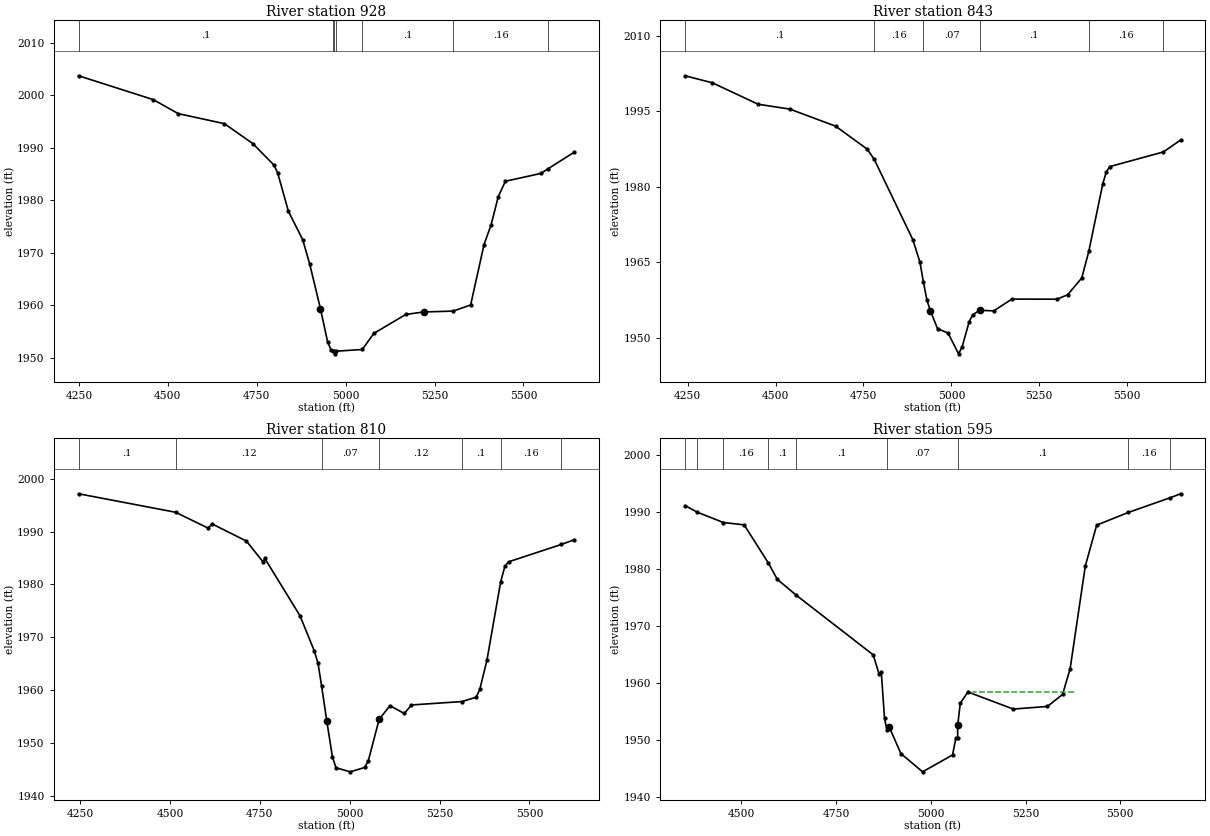
Type RM Length L Ch R = 1 ,928     ,85,85,85
BEGIN DESCRIPTION:
Mapping XS 583cf3b1
END DESCRIPTION:
XS GIS Cut Line= 2
       2647617.3     10050793.63      2647625.11     10049400.36
#Sta/Elev= 30
  4249.4 2003.68  4459.3 1999.14  4529.3 1996.48  4659.3 1994.56  4739.3 1990.76
  4799.3 1986.63  4809.3 1985.12  4839.3 1977.86  4879.3 1972.49  4899.3 1967.79
  4929.3 1959.34  4949.3 1953.06  4959.3 1951.45    4966 1951.25  4966.3 1951.24
  4969.1 1950.74  4972.3 1951.24    5047 1951.57  5079.3 1954.63  5169.3 1958.24
  5219.3 1958.71  5302.9 1958.88  5351.6 1960.05  5389.3 1971.55  5409.3 1975.34
  5429.3 1980.68  5449.3  1983.6  5549.3 1985.09  5569.8    1986  5642.7 1989.12
#Mann= 7 ,-1 , 0
  4249.4      .1       0    4966     .16       0  4966.3     .07       0
  4972.3     .16       0    5047      .1       0  5302.9     .16       0
  5569.8      .1       0
Bank Sta=4929.3,5219.3
XS Rating Curve= 0 ,0
Exp/Cntr=0.3,0.1

Type RM Length L Ch R = 1 ,843     ,33,33,33
BEGIN DESCRIPTION:
Mapping XS 8c88b200
END DESCRIPTION:
XS GIS Cut Line= 2
      2647718.86     10050801.43      2647695.43     10049392.52
#Sta/Elev= 30
  4242.8 2002.06  4320.5 2000.66  4450.5  1996.4  4540.5 1995.44  4670.6 1992.05
  4760.6 1987.48  4780.6 1985.46  4890.6 1969.45  4910.6 1965.01  4920.6 1961.02
  4930.6 1957.45  4940.6 1955.28  4960.6 1951.81  4990.6 1950.93  5020.4  1946.8
  5030.6 1948.18  5050.6 1953.19  5060.6 1954.57  5080.6 1955.45  5120.6 1955.34
  5172.1 1957.68  5300.6 1957.66  5330.6 1958.55  5370.7 1961.87  5390.7 1967.16
  5430.7 1980.65  5440.7 1982.99  5450.7 1984.02  5602.8 1986.92  5651.9  1989.3
#Mann= 6 ,-1 , 0
  4242.8      .1       0  4780.6     .16       0  4920.6     .07       0
  5080.6      .1       0  5390.7     .16       0  5602.8      .1       0
Bank Sta=4940.6,5080.6
XS Rating Curve= 0 ,0
Exp/Cntr=0.3,0.1

Type RM Length L Ch R = 1 ,810     ,215,215,215
BEGIN DESCRIPTION:
Mapping XS 61ec165c
END DESCRIPTION:
XS GIS Cut Line= 3
      2647854.28     10050788.36       2647739.7     10050212.86
       2647739.7     10049421.16
#Sta/Elev= 30
    4246 1997.14  4515.8 1993.64  4605.6 1990.66  4617.8 1991.42  4712.9 1988.18
  4758.9 1984.25    4764 1984.89  4861.9 1974.04  4901.9 1967.34  4911.9 1965.07
  4921.9 1960.75 4936.36 1954.12  4951.9 1947.37  4961.9 1945.28  5001.7 1944.51
  5041.9 1945.34  5051.9 1946.63  5081.9 1954.42  5111.9 1957.03  5151.9 1955.56
  5171.9 1957.17  5311.9 1957.81  5351.9 1958.63  5361.9  1960.1  5381.9 1965.66
  5420.2 1980.53  5431.9 1983.45  5441.9 1984.26  5588.4 1987.54  5624.5 1988.43
#Mann= 7 ,-1 , 0
    4246      .1       0  4515.8     .12       0  4921.9     .07       0
  5081.9     .12       0  5311.9      .1       0  5420.2     .16       0
  5588.4      .1       0
Bank Sta=4936.36,5081.9
XS Rating Curve= 0 ,0
Exp/Cntr=0.3,0.1

Type RM Length L Ch R = 1 ,595     ,31,31,31
BEGIN DESCRIPTION:
Mapping XS 9198cbab
END DESCRIPTION:
XS GIS Cut Line= 4
       2648112.1     10050645.19      2648057.41     10050197.23
      2647914.18     10049970.67      2647908.97     10049382.12
#Sta/Elev= 30
  4351.4 1991.09  4382.7 1989.95  4452.3 1988.12  4507.1 1987.71    4571 1981.05
  4594.7 1978.17    4645 1975.38  4847.9 1964.95  4863.1 1961.64  4869.1 1961.99
  4877.8 1953.83  4884.3 1951.73  4890.2 1952.32  4920.8 1947.68  4978.2 1944.47
  5057.3 1947.43    5066 1950.38  5070.7 1950.38 5070.91 1952.62  5077.7 1956.48
  5097.7 1958.45  5217.7 1955.46  5307.7 1955.92  5347.7 1958.02  5367.7 1962.54
  5407.7 1980.52  5437.7 1987.66  5521.1 1989.88  5631.8 1992.46  5659.3 1993.15
#Mann= 9 ,-1 , 0
  4351.4     .16       0  4382.7      .1       0  4452.3     .16       0
    4571      .1       0    4645      .1       0  4884.3     .07       0
  5070.7      .1       0  5521.1     .16       0  5631.8      .1       0
#XS Ineff= 1 ,-1
 5111.82 5381.82 1958.47
Permanent Ineff=
       F
Bank Sta=4890.2,5070.91
XS Rating Curve= 0 ,0
Exp/Cntr=0.3,0.1