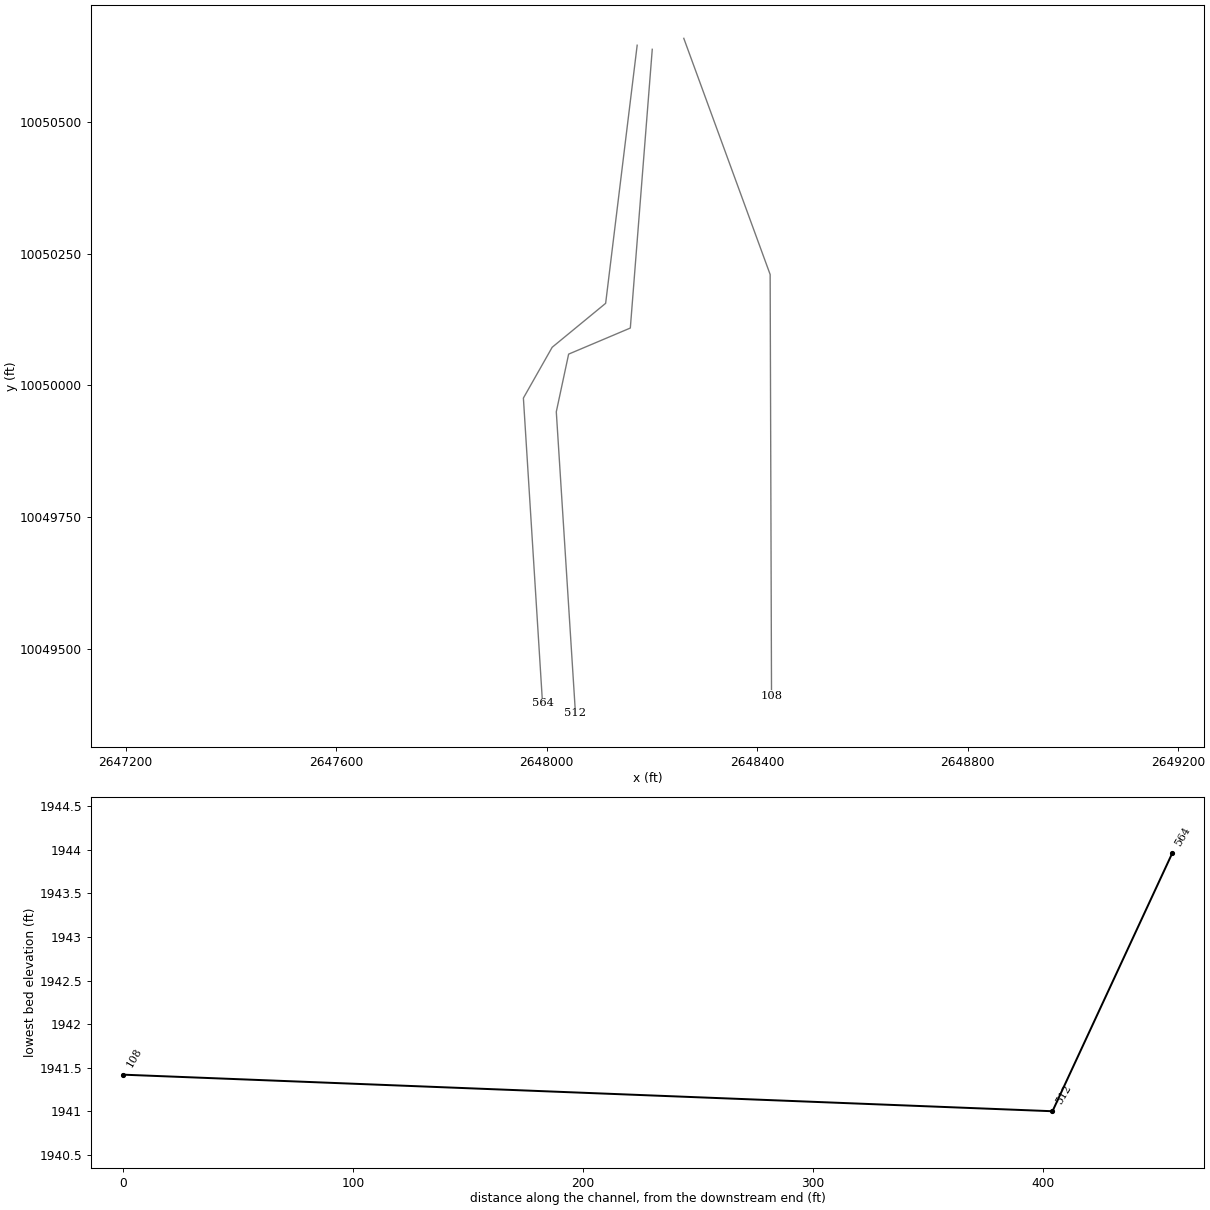
HEC-RAS study STEVENS CREEK.prj: STEVENS CREEK Base Level Engineering

--- STEVENS CREEK.g01 (geometry) --- (continued)

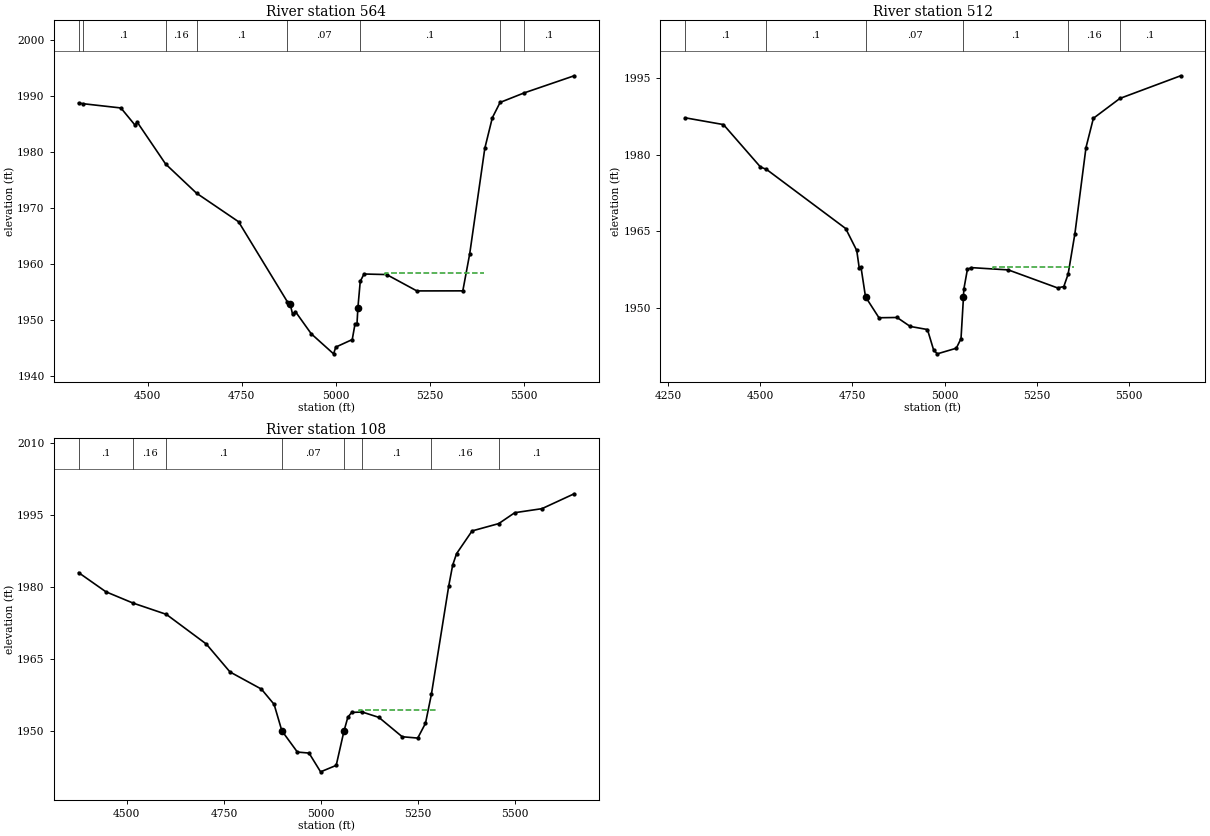
Type RM Length L Ch R = 1 ,564     ,52,52,52
BEGIN DESCRIPTION:
Mapping XS 640ddb25
END DESCRIPTION:
XS GIS Cut Line= 5
      2648171.98      10050645.1      2648112.09     10050155.56
      2648010.53     10050072.23      2647955.84     10049975.88
      2647992.19     10049396.97
#Sta/Elev= 30
  4316.9 1988.78  4327.5 1988.65  4429.1 1987.88  4466.9 1984.79  4471.9  1985.4
  4547.9 1977.86  4629.8 1972.66  4741.4 1967.56  4870.6  1953.3  4878.5 1952.85
  4884.9    1951  4892.4  1951.5  4934.4 1947.54  4993.6 1943.96  4999.6 1945.17
  5043.2 1946.51  5050.6 1949.31  5055.8 1949.31 5058.18 1952.17  5064.4 1956.89
  5074.4 1958.22  5134.6 1958.12  5214.7  1955.2  5336.7 1955.21    5355 1961.82
  5395.1 1980.68  5415.1 1986.14  5435.7 1988.87  5499.5 1990.57  5632.3 1993.63
#Mann= 8 ,-1 , 0
  4316.9     .16       0  4327.5      .1       0  4547.9     .16       0
  4629.8      .1       0  4870.6     .07       0  5064.4      .1       0
  5435.7     .16       0  5499.5      .1       0
#XS Ineff= 1 ,-1
    5130 5392.73  1958.4
Permanent Ineff=
       F
Bank Sta=4878.5,5058.18
XS Rating Curve= 0 ,0
Exp/Cntr=0.3,0.1

Type RM Length L Ch R = 1 ,512     ,404,404,404
BEGIN DESCRIPTION:
Mapping XS eca4c547
END DESCRIPTION:
XS GIS Cut Line= 5
      2648200.64     10050637.34      2648158.97     10050108.69
      2648041.78     10050059.21      2648018.34     10049949.83
      2648054.74     10049377.85
#Sta/Elev= 30
  4296.7 1987.24  4400.6 1985.91  4500.9  1977.6  4517.2 1977.13  4731.7 1965.55
  4761.7 1961.25  4768.3  1957.9  4773.3 1957.95 4785.45 1952.17  4821.9 1948.07
    4871 1948.12  4906.5 1946.37  4953.3 1945.76    4970 1941.75    4980    1941
  5031.4  1942.1  5044.2 1943.98 5050.91 1952.17  5051.8 1953.64  5061.5 1957.54
  5072.2 1957.89  5172.4 1957.44  5305.9 1953.91  5322.7 1954.18  5334.4 1956.62
  5352.7 1964.52  5382.8 1981.42  5402.8 1987.14  5474.6 1991.03  5639.2 1995.47
#Mann= 6 ,-1 , 0
  4296.7      .1       0  4517.2      .1       0 4785.45     .07       0
 5050.91      .1       0  5334.4     .16       0  5474.6      .1       0
#XS Ineff= 1 ,-1
 5131.82    5350  1958.1
Permanent Ineff=
       F
Bank Sta=4785.45,5050.91
XS Rating Curve= 0 ,0
Exp/Cntr=0.3,0.1

Type RM Length L Ch R = 1 ,108     ,0,0,0
BEGIN DESCRIPTION:
STEVENS CREEK 1.0
END DESCRIPTION:
XS GIS Cut Line= 3
      2648260.54     10050658.14      2648424.59     10050210.25
       2648427.2     10049410.74
#Sta/Elev= 30
  4375.8 1983.02  4446.1 1979.02  4515.8 1976.67  4601.7 1974.31  4704.7 1968.11
  4765.7 1962.28  4846.6  1958.7  4879.3 1955.52  4899.3 1949.99  4939.3 1945.55
  4969.3 1945.34  4999.1 1941.42  5039.3 1942.77  5059.3 1949.93  5069.3 1952.83
  5079.3 1953.83  5106.4 1953.91  5149.3 1952.79  5209.3 1948.75  5249.3 1948.47
  5269.3 1951.56  5284.5  1957.6  5329.3  1980.3  5339.3 1984.58  5349.3 1986.98
  5389.3 1991.73  5457.9 1993.26  5499.3 1995.54  5569.3 1996.38  5652.3 1999.49
#Mann= 8 ,-1 , 0
  4375.8      .1       0  4515.8     .16       0  4601.7      .1       0
  4899.3     .07       0  5059.3      .1       0  5106.4      .1       0
  5284.5     .16       0  5457.9      .1       0
#XS Ineff= 1 ,-1
 5098.18 5300.91 1954.27
Permanent Ineff=
       F
Bank Sta=4899.3,5059.3
XS Rating Curve= 0 ,0
Exp/Cntr=0.3,0.1

Chan Stop Cuts=-1
Use User Specified Reach Order=0
Composite Channel Slope=5