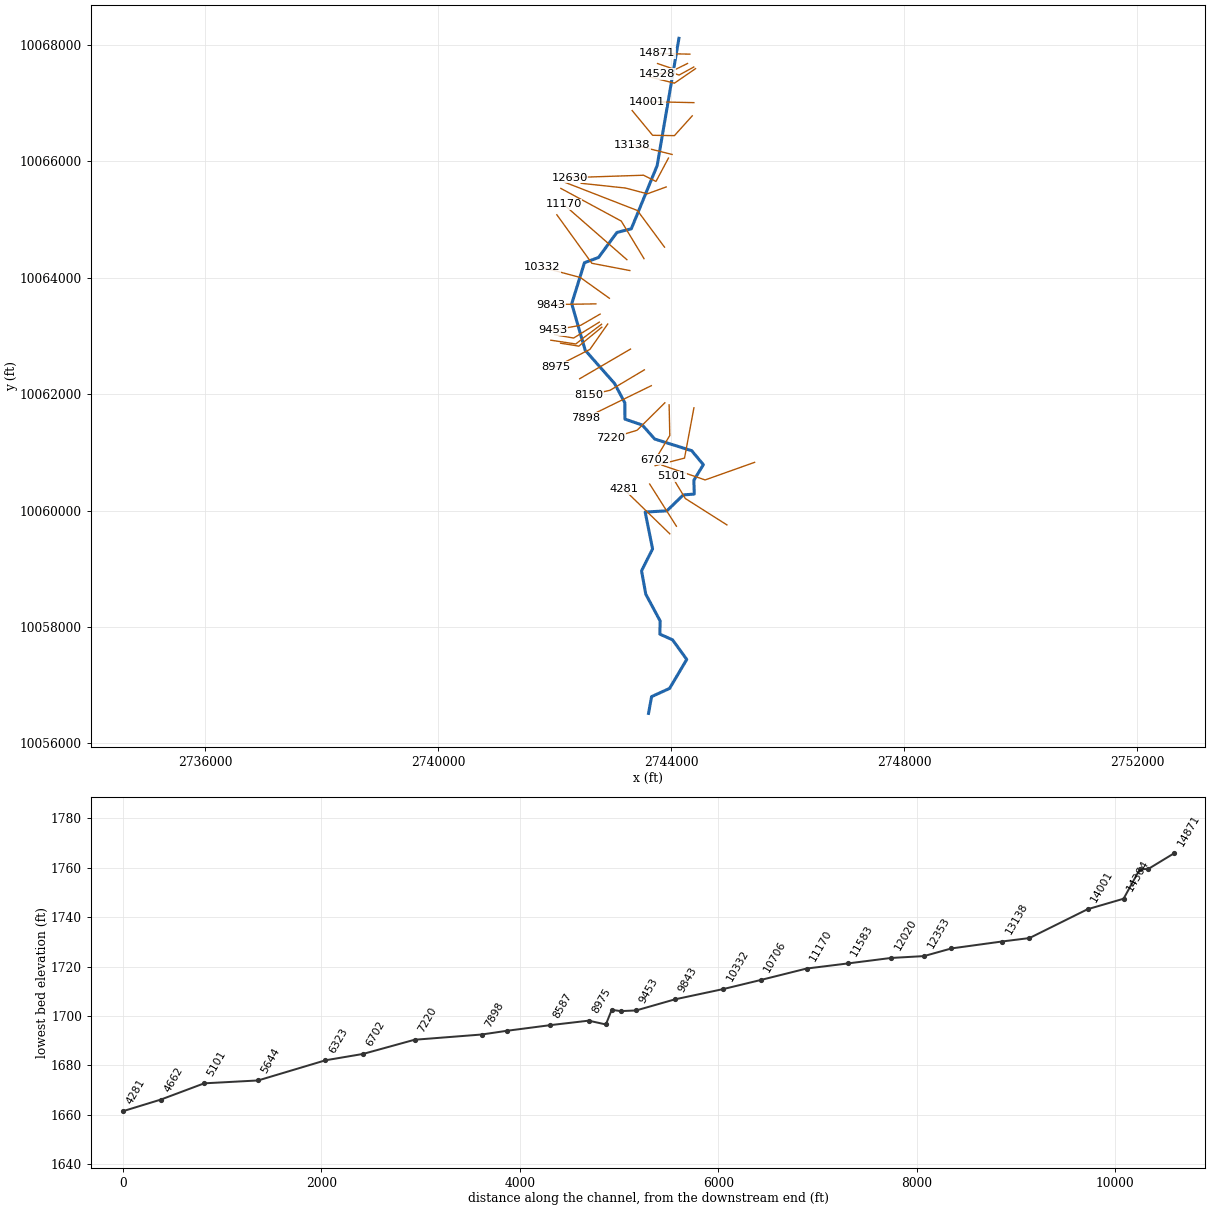
--- STINK CREEK.prj (project) ---

Proj Title=STINK CREEK Base Level Engineering
Current Plan=p01
Default Exp/Contr=0.3,0.1
English Units
Geom File=g01
Flow File=f01
Plan File=p01
Y Axis Title=Elevation
X Axis Title(PF)=Main Channel Distance
X Axis Title(XS)=Station
BEGIN DESCRIPTION:
STINK CREEK
END DESCRIPTION:
DSS Export Rating Curves= 0
DSS Export Rating Curve Sorted= 0
DSS Export Volume Flow Curves= 0
DXF OffsetX= 0
DXF OffsetY= 0
DXF ScaleX= 1
DXF ScaleY= 10

--- STINK CREEK.p01 (plan) ---

Plan Title=Multiple Run
Short Identifier=Multiple
Geom File=g01
Flow File=f01
Subcritical Flow
K Sum by GR= 0
Std Step Tol= 0.01
Critical Tol= 0.01
Num of Std Step Trials= 20
Max Error Tol= 0.3
Flow Tol Ratio= 0.001
Split Flow NTrial= 30
Split Flow Tol= 0.02
Split Flow Ratio= 0.02
Log Output Level= 0
Friction Slope Method= 1
Unsteady Friction Slope Method= 2
Unsteady Bridges Friction Slope Method= 1
Parabolic Critical Depth
Global Vel Dist=  1 , 1 , 1
Global Log Level= 0
CheckData=True
Encroach Param= -1, 0, 0, 0
BEGIN DESCRIPTION:
Multiple Run
END DESCRIPTION:

--- STINK CREEK.f01 (steady flow) ---

Flow Title=Multiple
Program Version=4.10
Number of Profiles= 7
Profile Names=10-year,25-year,50-year,1pct_min,100-year,1pct_plu,500-year
River Rch & RM=STINK CREEK,Reach-1         ,14871
     359     498     614     556     752    1017    1133
River Rch & RM=STINK CREEK,Reach-1         ,12020
    1082    1596    2048    1922    2600    3516    4211
River Rch & RM=STINK CREEK,Reach-1         ,5644
    1364    2030    2619    2469    3340    4516    5457
Boundary for River Rch & Prof#=STINK CREEK,Reach-1         , 1
Up Type= 0
Dn Type= 3
Dn Slope=0.013
Boundary for River Rch & Prof#=STINK CREEK,Reach-1         , 2
Up Type= 0
Dn Type= 3
Dn Slope=0.013
Boundary for River Rch & Prof#=STINK CREEK,Reach-1         , 3
Up Type= 0
Dn Type= 3
Dn Slope=0.013
Boundary for River Rch & Prof#=STINK CREEK,Reach-1         , 4
Up Type= 0
Dn Type= 3
Dn Slope=0.013
Boundary for River Rch & Prof#=STINK CREEK,Reach-1         , 5
Up Type= 0
Dn Type= 3
Dn Slope=0.013
Boundary for River Rch & Prof#=STINK CREEK,Reach-1         , 6
Up Type= 0
Dn Type= 3
Dn Slope=0.013
Boundary for River Rch & Prof#=STINK CREEK,Reach-1         , 7
Up Type= 0
Dn Type= 3
Dn Slope=0.013
DSS Import GetInterval= 0
DSS Import GetPeak= 0
DSS Import FillOption= 0

--- STINK CREEK.g01 (geometry) ---

Geom Title=Existing Conditions
Program Version=4.10

River Reach=STINK CREEK     ,Reach-1
Reach XY= 30
       2744131.2     10068115.33      2743757.44     10065929.11
       2743313.4     10064842.07      2743065.95     10064778.78
      2742750.47     10064348.88      2742508.49     10064258.79
      2742289.95     10063553.51      2742520.94     10062754.85
      2743025.78     10062182.62      2743202.26     10061850.53
      2743203.23     10061570.98      2743501.41     10061469.39
      2743715.43     10061227.97      2744350.62       10061028.
      2744550.63      10060787.7      2744387.74     10060520.44
      2744394.49     10060282.19      2744206.02     10060268.06
      2743924.49     10059994.58      2743551.44      10059972.9
      2743678.74     10059340.54      2743489.12     10058963.23
      2743561.15     10058563.45      2743808.29     10058101.81
      2743804.07     10057875.19      2744021.85     10057776.67
      2744265.49     10057440.18      2743970.68     10056942.25
      2743661.51     10056801.03      2743609.19     10056513.19

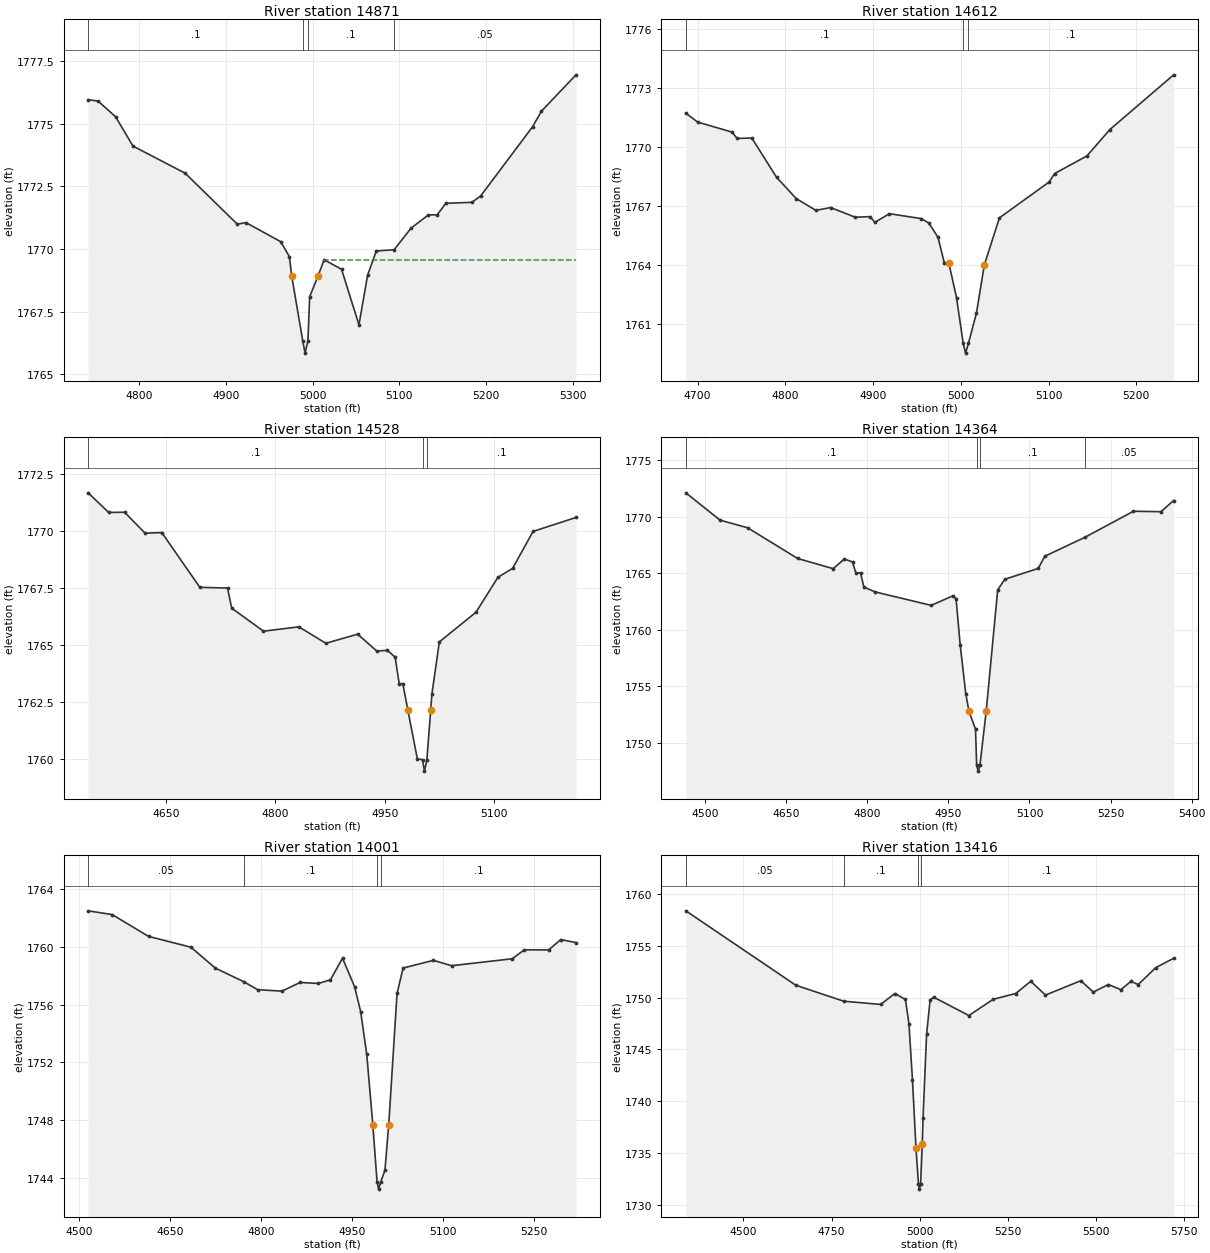
Type RM Length L Ch R = 1 ,14871   ,259,259,259
BEGIN DESCRIPTION:
STINK CREEK 29.0
END DESCRIPTION:
XS GIS Cut Line= 2
      2744320.01     10067843.62      2743758.72     10067854.96
#Sta/Elev= 30
  4741.8 1775.95  4753.3 1775.89  4773.3 1775.27  4793.4  1774.1  4853.4 1773.02
  4913.4 1770.99  4923.4 1771.05  4963.4 1770.29  4973.4 1769.69 4976.02 1768.92
  4988.7 1766.35  4991.4 1765.85  4994.7 1766.35  4996.7  1768.1 5006.25 1768.92
  5013.4 1769.57  5033.4 1769.19  5053.4 1766.98  5063.4 1768.96  5073.4 1769.92
  5093.9 1769.97  5113.4 1770.83  5133.4 1771.36  5143.4 1771.36  5153.4 1771.82
  5183.4 1771.86  5193.4 1772.11  5253.4 1774.88  5263.4 1775.49  5303.2 1776.94
#Mann= 4 ,-1 , 0
  4741.8      .1       0  4988.7     .07       0  4994.7      .1       0
  5093.9     .05       0
#XS Ineff= 2 , 0
                         5013.01         1769.57
Permanent Ineff=
       T       T
Bank Sta=4976.02,5006.25
XS Rating Curve= 0 ,0
Exp/Cntr=0.3,0.1

Type RM Length L Ch R = 1 ,14612   ,84,84,84
BEGIN DESCRIPTION:
Mapping XS 1a26ba9a
END DESCRIPTION:
XS GIS Cut Line= 3
      2744278.65     10067683.23      2744068.25     10067579.07
      2743764.11     10067681.84
#Sta/Elev= 30
  4686.7  1771.7  4700.2 1771.25  4739.5 1770.74  4745.1 1770.42  4761.9 1770.44
    4790 1768.45  4812.4 1767.37  4834.8 1766.77  4851.7 1766.91  4879.7 1766.42
  4896.5 1766.45  4902.1 1766.16  4918.6  1766.6  4954.9 1766.35  4963.5 1766.13
    4974  1765.4  4981.1 1764.12  4986.4 1764.08  4995.1 1762.34  5002.7 1760.02
  5005.4 1759.52  5008.7 1760.02  5017.8 1761.55  5026.8    1764    5044 1766.39
  5100.7 1768.21  5106.9 1768.64  5143.6 1769.53  5169.8 1770.87  5242.5 1773.65
#Mann= 3 ,-1 , 0
  4686.7      .1       0  5002.7     .07       0  5008.7      .1       0
Bank Sta=4986.4,5026.8
XS Rating Curve= 0 ,0
Exp/Cntr=0.3,0.1

Type RM Length L Ch R = 1 ,14528   ,164,164,164
BEGIN DESCRIPTION:
Mapping XS e61bf3c2
END DESCRIPTION:
XS GIS Cut Line= 4
      2744387.02     10067622.83      2744133.53     10067483.93
      2744002.97     10067528.38      2743761.99     10067502.83
#Sta/Elev= 30
  4543.2 1771.66  4571.3  1770.8  4593.1 1770.81  4621.4 1769.89  4644.2 1769.92
  4696.4 1767.52  4734.4 1767.49  4740.1 1766.61  4783.7  1765.6  4832.3 1765.79
  4869.3 1765.07    4913 1765.47  4939.1 1764.73  4953.8 1764.76  4964.4 1764.46
  4969.9  1763.3  4974.9  1763.3 4981.82 1762.14  4994.8 1760.01  5001.9 1759.97
  5004.6 1759.47  5007.9 1759.97 5013.18 1762.15  5014.9 1762.87    5025 1765.13
  5075.3 1766.43  5105.4 1767.96  5125.5 1768.35  5153.6 1769.97  5212.5 1770.58
#Mann= 3 ,-1 , 0
  4543.2      .1       0  5001.9     .07       0  5007.9      .1       0
Bank Sta=4981.82,5013.18
XS Rating Curve= 0 ,0
Exp/Cntr=0.3,0.1

Type RM Length L Ch R = 1 ,14364   ,363,363,363
BEGIN DESCRIPTION:
STINK CREEK 28.0
END DESCRIPTION:
XS GIS Cut Line= 3
      2744416.45     10067594.16      2744053.55     10067344.66
      2743605.67     10067458.05
#Sta/Elev= 30
  4464.3 1772.11  4527.7 1769.69  4578.5 1769.02  4671.1  1766.3  4736.8  1765.4
  4757.7 1766.25  4772.6 1765.99  4778.7 1765.04  4787.5 1765.02  4793.6 1763.77
  4814.5 1763.34  4918.2 1762.15  4959.2 1763.01  4964.3 1762.68  4971.8 1758.65
  4982.1 1754.35 4988.07 1752.77  5000.2 1751.18  5002.3 1747.98  5005.1 1747.48
  5008.3 1747.98 5019.89 1752.77  5041.2 1763.52  5054.3 1764.46  5116.2 1765.42
  5128.4  1766.5  5202.4 1768.17  5292.4 1770.48  5343.2 1770.44  5366.7 1771.43
#Mann= 4 ,-1 , 0
  4464.3      .1       0  5002.3     .07       0  5008.3      .1       0
  5202.4     .05       0
Bank Sta=4988.07,5019.89
XS Rating Curve= 0 ,0
Exp/Cntr=0.3,0.1

Type RM Length L Ch R = 1 ,14001   ,585,585,585
BEGIN DESCRIPTION:
STINK CREEK 27.0
END DESCRIPTION:
XS GIS Cut Line= 2
      2744388.05     10067010.14      2743583.23     10067027.14
#Sta/Elev= 30
  4514.9 1762.49  4554.5 1762.23  4614.5 1760.72  4684.5 1759.97  4724.5 1758.53
  4771.8 1757.58  4794.5 1757.03  4834.6 1756.93  4864.6 1757.53  4894.6 1757.46
  4914.6 1757.71  4934.6 1759.21  4954.6 1757.23  4964.6  1755.5  4974.6 1752.55
  4984.6 1747.68  4991.6 1743.72  4994.3 1743.22  4997.6 1743.72  5004.6 1744.52
 5010.79 1747.63  5024.6 1756.77  5034.6 1758.53  5084.6 1759.06  5114.6 1758.69
  5214.6 1759.17  5234.6 1759.79  5274.7 1759.78  5294.7  1760.5  5319.9 1760.29
#Mann= 4 ,-1 , 0
  4514.9     .05       0  4771.8      .1       0  4991.6     .07       0
  4997.6      .1       0
Bank Sta=4984.6,5010.79
XS Rating Curve= 0 ,0
Exp/Cntr=0.3,0.1

Type RM Length L Ch R = 1 ,13416   ,278,278,278
BEGIN DESCRIPTION:
STINK CREEK 26.0
END DESCRIPTION:
XS GIS Cut Line= 4
       2744359.7     10066783.31      2744053.55     10066443.14
      2743679.33     10066448.81      2743327.82     10066874.03
#Sta/Elev= 30
  4336.6 1758.36  4648.5 1751.19  4784.4 1749.65  4889.3 1749.34  4929.3 1750.39
  4959.4 1749.82  4969.4 1747.48  4979.4 1742.05  4989.4 1735.48  4996.4 1732.04
  4999.1 1731.54  5002.4 1732.04  5007.3 1735.93  5009.4 1738.44  5019.4 1746.45
  5029.4 1749.76  5039.4 1750.04  5139.4 1748.27  5208.2 1749.83    5272 1750.39
    5315 1751.57  5356.7 1750.24    5457 1751.63  5492.2 1750.53  5535.2 1751.26
  5570.4 1750.76    5599 1751.56  5619.8 1751.26  5669.3 1752.88  5720.2 1753.79
#Mann= 4 ,-1 , 0
  4336.6     .05       0  4784.4      .1       0  4996.4     .07       0
  5002.4      .1       0
Bank Sta=4989.4,5007.3
XS Rating Curve= 0 ,0
Exp/Cntr=0.3,0.1

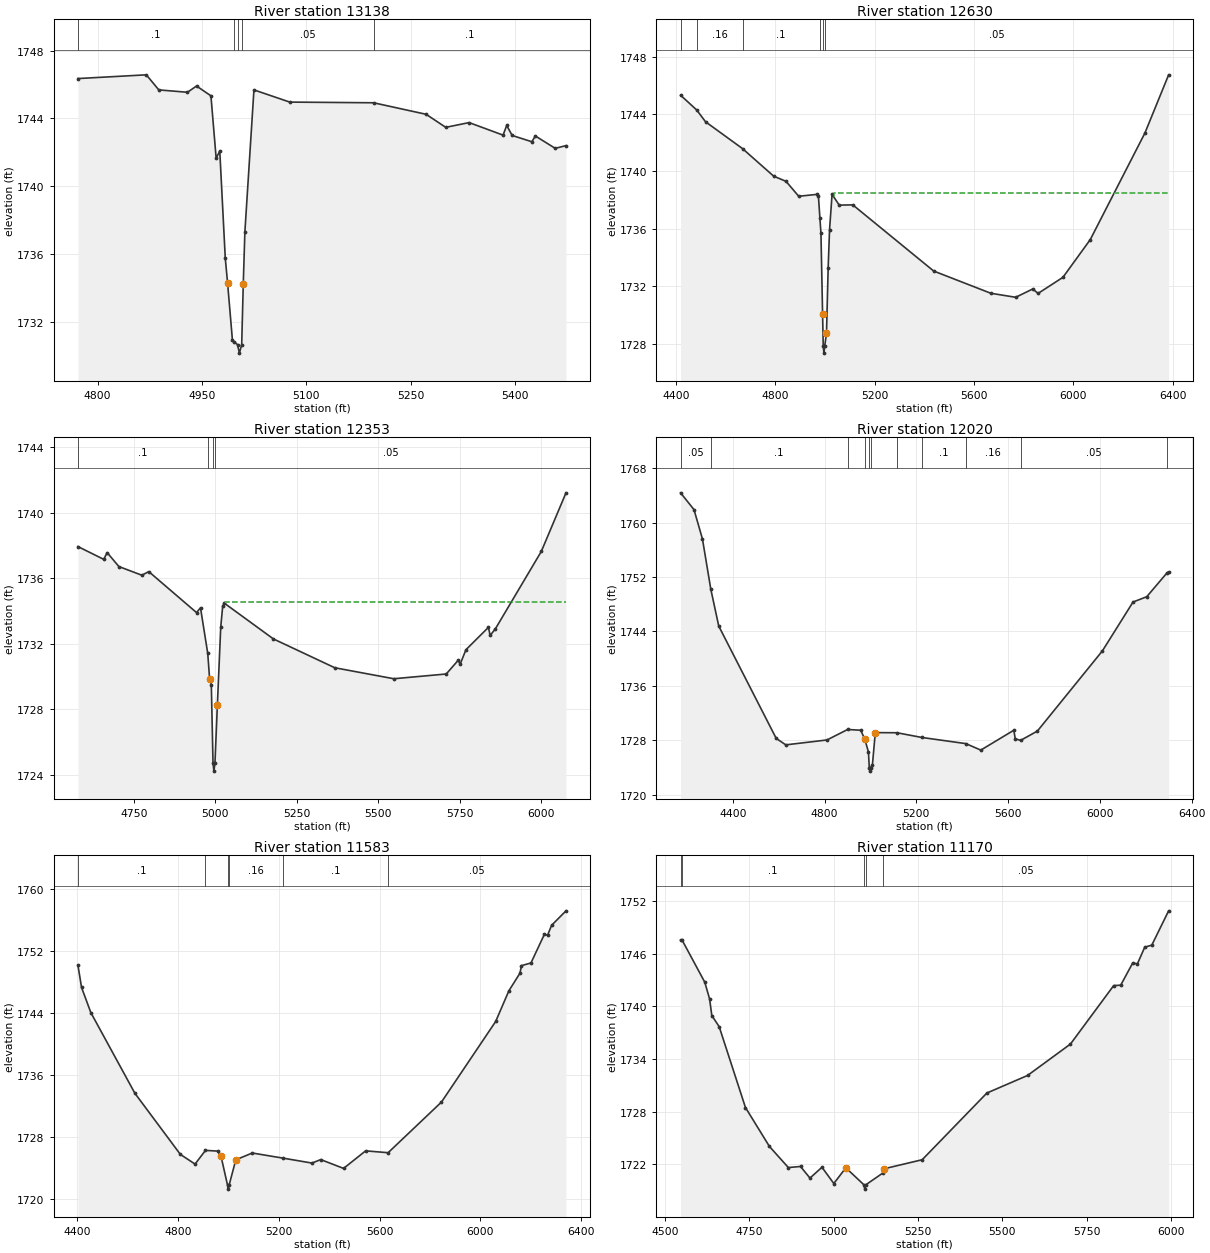
Type RM Length L Ch R = 1 ,13138   ,508,508,508
BEGIN DESCRIPTION:
STINK CREEK 25.0
END DESCRIPTION:
XS GIS Cut Line= 2
      2744013.82     10066119.97      2743333.46     10066290.06
#Sta/Elev= 30
  4771.8 1746.35  4870.1 1746.57    4888 1745.68  4929.2 1745.54  4942.2 1745.91
  4962.9 1745.33  4970.4 1741.65  4975.6 1742.07  4983.5 1735.75 4986.81 1734.28
  4993.8  1730.9    4996 1730.82  5001.1 1730.64  5003.8 1730.14  5007.1 1730.64
 5009.38 1734.25  5011.7 1737.31  5024.7 1745.68  5076.2 1744.96  5196.6 1744.92
  5272.1 1744.24  5300.3 1743.47  5333.9 1743.75  5382.7 1743.01  5387.9 1743.58
  5395.8 1742.99    5424 1742.62  5429.1 1742.96  5457.6 1742.23  5473.1 1742.39
#Mann= 5 ,-1 , 0
  4771.8      .1       0    4996     .05       0  5001.1    .035       0
  5007.1     .05       0  5196.6      .1       0
Bank Sta=4986.81,5009.38
XS Rating Curve= 0 ,0
Exp/Cntr=0.3,0.1

Type RM Length L Ch R = 1 ,12630   ,277,277,277
BEGIN DESCRIPTION:
Mapping XS cf10594c
END DESCRIPTION:
XS GIS Cut Line= 4
      2743950.94     10066056.86       2743737.4     10065655.82
      2743523.86     10065762.59      2742253.24     10065720.93
#Sta/Elev= 30
  4418.8 1745.31  4483.7 1744.28  4519.2 1743.46  4668.1 1741.59  4793.5 1739.67
  4843.1 1739.31  4894.3 1738.27  4968.1  1738.4  4973.6 1738.28  4979.6 1736.75
  4983.8 1735.68  4990.4 1730.06    4993 1727.84  4995.8 1727.34    4999 1727.84
  5006.1 1728.72  5012.8 1733.26  5018.4 1735.93  5028.5  1738.4  5057.5 1737.65
  5111.9 1737.67  5437.5 1733.06  5667.6 1731.51  5767.6 1731.23  5836.3 1731.81
  5857.7  1731.5  5957.7 1732.62  6067.8 1735.25  6287.9 1742.68  6383.2 1746.73
#Mann= 6 ,-1 , 0
  4418.8      .1       0  4483.7     .16       0  4668.1      .1       0
  4979.6     .05       0    4993    .035       0    4999     .05       0
#XS Ineff= 2 , 0
                         5035.27         1738.48
Permanent Ineff=
       T       T
Bank Sta=4990.4,5006.1
XS Rating Curve= 0 ,0
Exp/Cntr=0.3,0.1

Type RM Length L Ch R = 1 ,12353   ,333,333,333
BEGIN DESCRIPTION:
STINK CREEK 24.0
END DESCRIPTION:
XS GIS Cut Line= 4
      2743912.73      10065561.2      2743588.09     10065443.14
      2743214.83      10065542.1      2742453.08     10065623.66
#Sta/Elev= 30
  4578.4 1737.94  4657.4 1737.16  4668.1 1737.57    4704 1736.72  4774.5 1736.19
  4795.8 1736.41  4942.3 1733.91  4954.5  1734.2  4976.7 1731.42  4982.5 1729.86
  4987.7 1729.51  4992.9 1724.73  4995.6 1724.23  4998.9 1724.73  5006.2 1728.24
  5016.6 1733.02  5022.7 1734.32  5027.9 1734.48  5178.3  1732.3  5366.7 1730.54
  5547.7 1729.87  5708.6 1730.16  5745.9 1731.01    5751 1730.74    5769 1731.64
  5838.2 1733.01  5843.2 1732.51  5859.5 1732.92  6000.3 1737.64  6076.1 1741.22
#Mann= 4 ,-1 , 0
  4578.4      .1       0  4976.7     .05       0  4992.9    .035       0
  4998.9     .05       0
#XS Ineff= 2 , 0
                         5028.88         1734.57
Permanent Ineff=
       T       T
Bank Sta=4982.5,5006.2
XS Rating Curve= 0 ,0
Exp/Cntr=0.3,0.1

Type RM Length L Ch R = 1 ,12020   ,437,437,437
BEGIN DESCRIPTION:
STINK CREEK 23.0
END DESCRIPTION:
XS GIS Cut Line= 3
      2743883.48     10064526.67      2743418.52     10065156.07
      2742165.46     10065643.68
#Sta/Elev= 30
  4172.5 1764.37    4231  1761.9  4267.8 1757.59  4304.4 1750.18  4338.8 1744.79
  4589.3 1728.28    4631 1727.33  4810.6 1728.05  4900.6 1729.59  4957.7 1729.48
  4975.7 1728.13  4991.3 1726.28    4995 1723.97  4997.7 1723.47    5001 1723.97
  5008.7 1724.44  5021.2 1729.13  5115.6 1729.11  5223.4 1728.42  5416.3 1727.51
  5480.9 1726.56  5624.9 1729.48  5631.1 1728.23  5654.2 1727.98  5727.7 1729.36
  6011.1 1741.15  6144.4 1748.32  6204.2  1749.1  6293.4 1752.64  6299.6 1752.73
#Mann= 11 ,-1 , 0
  4172.5     .05       0  4304.4      .1       0  4900.6     .16       0
  4975.7      .1       0    4995     .07       0    5001      .1       0
  5115.6     .16       0  5223.4      .1       0  5416.3     .16       0
  5654.2     .05       0  6293.4      .1       0
Bank Sta=4975.7,5021.2
XS Rating Curve= 0 ,0
Exp/Cntr=0.3,0.1

Type RM Length L Ch R = 1 ,11583   ,413,413,413
BEGIN DESCRIPTION:
STINK CREEK 22.0
END DESCRIPTION:
XS GIS Cut Line= 3
       2743531.9     10064328.28      2743140.69     10064974.63
      2742103.29     10065535.85
#Sta/Elev= 30
  4404.1 1750.19  4418.4 1747.32  4455.2 1744.07  4629.8 1733.64  4810.2 1725.73
  4868.4 1724.48  4909.8 1726.25  4957.6 1726.16  4971.5 1725.47  4997.3 1721.74
    5000 1721.24  5003.3 1721.74    5030 1725.03  5095.3 1725.91    5217 1725.25
  5331.7 1724.61  5366.8 1725.06  5457.3 1723.92  5544.8 1726.19  5633.9 1725.95
  5845.4  1732.5  6060.3 1742.92  6112.7 1746.89  6156.5 1749.16  6162.7 1750.14
  6200.3 1750.49  6253.6  1754.2  6265.9 1754.06  6282.1 1755.36  6339.1 1757.23
#Mann= 6 ,-1 , 0
  4404.1      .1       0  4909.8     .16       0  4997.3     .07       0
  5003.3     .16       0    5217      .1       0  5633.9     .05       0
Bank Sta=4971.5,5030
XS Rating Curve= 0 ,0
Exp/Cntr=0.3,0.1

Type RM Length L Ch R = 1 ,11170   ,464,464,464
BEGIN DESCRIPTION:
STINK CREEK 21.0
END DESCRIPTION:
XS GIS Cut Line= 2
      2743237.11     10064311.22      2742148.43     10065263.82
#Sta/Elev= 30
  4546.4 1747.55  4550.7 1747.57  4618.1 1742.76  4632.4 1740.85    4639 1738.96
  4660.8 1737.69  4738.7 1728.48  4809.8 1724.04  4865.8 1721.64  4901.9 1721.76
  4929.9 1720.44  4965.5 1721.67  5000.6 1719.82  5036.2 1721.61  5089.7 1719.68
  5092.4 1719.18  5095.7 1719.68    5145 1720.99  5149.6  1721.5  5262.6 1722.53
  5454.3 1730.13  5574.8 1732.13    5702 1735.71  5830.1 1742.37    5851 1742.42
  5886.7 1744.96  5900.4 1744.84  5922.2 1746.75  5943.1 1746.98    5993 1750.89
#Mann= 5 ,-1 , 0
  4546.4     .05       0  4550.7      .1       0  5089.7     .07       0
  5095.7      .1       0    5145     .05       0
Bank Sta=5036.2,5149.6
XS Rating Curve= 0 ,0
Exp/Cntr=0.3,0.1

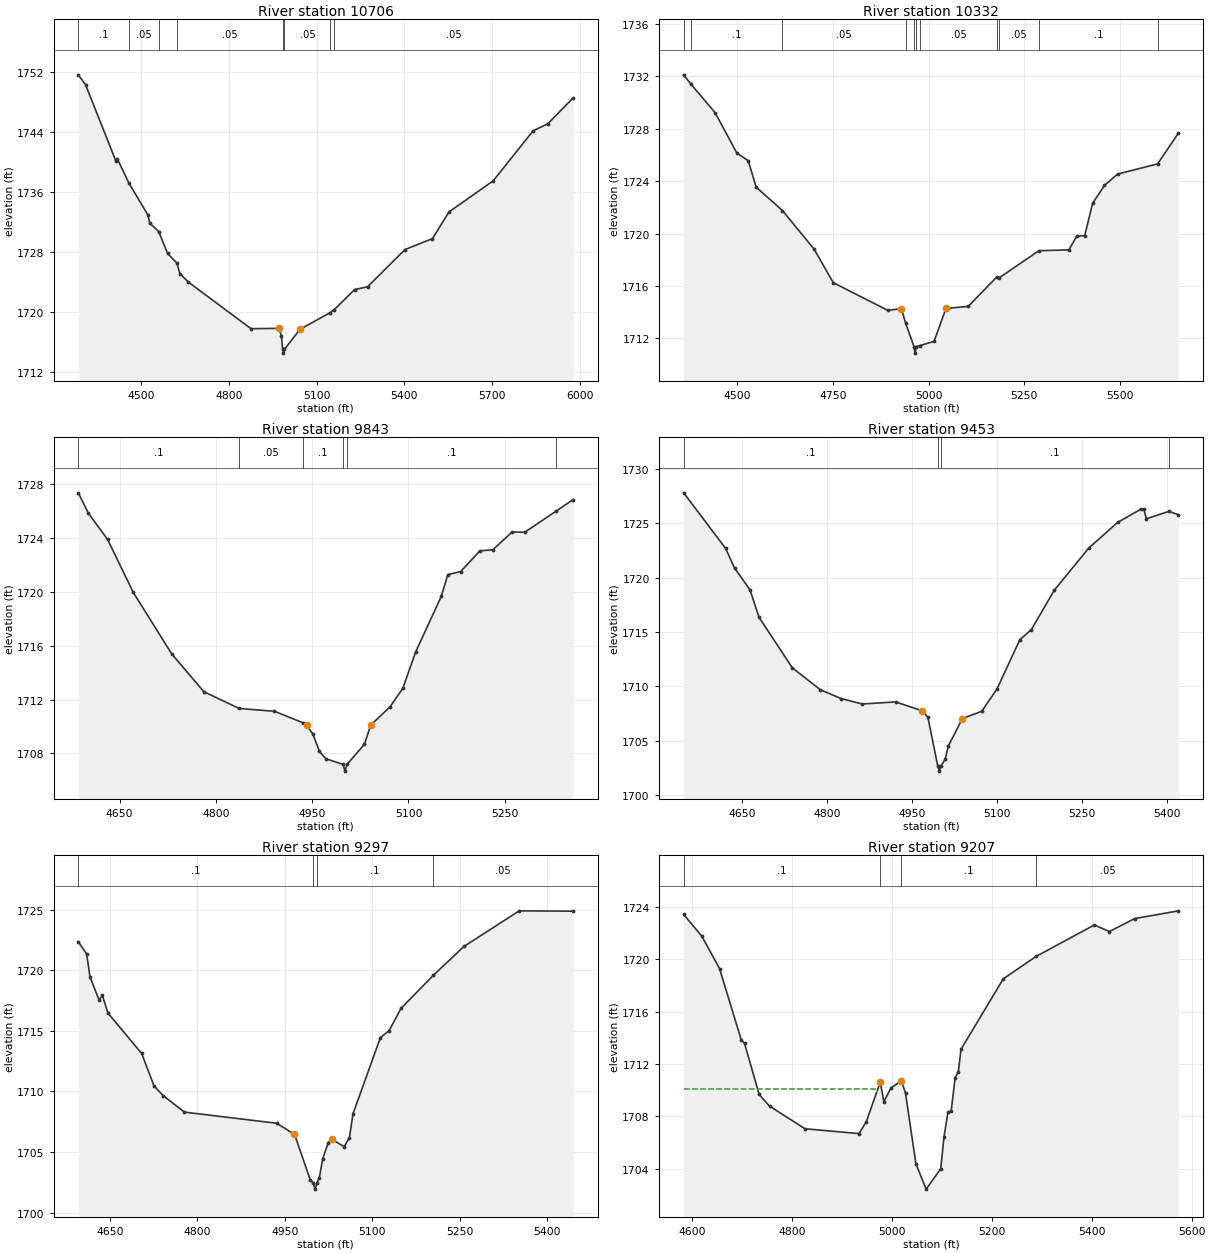
Type RM Length L Ch R = 1 ,10706   ,374,374,374
BEGIN DESCRIPTION:
STINK CREEK 20.0
END DESCRIPTION:
XS GIS Cut Line= 3
      2743288.14     10064124.14      2742636.07     10064248.88
      2742035.04     10065082.38
#Sta/Elev= 30
  4285.4 1751.62  4310.2 1750.31  4414.3 1740.09  4419.4 1740.38  4459.1 1737.14
  4523.5 1732.93  4529.4 1731.87  4560.4 1730.72  4590.5 1727.82  4622.5 1726.52
  4632.8 1725.11  4661.8 1723.99  4875.6 1717.78  4972.3 1717.82  4979.9 1716.74
    4984 1715.02  4986.8 1714.52    4990 1715.02  5043.5  1717.7    5147 1719.93
  5160.6 1720.32    5230    1723  5274.1 1723.36  5401.8 1728.32  5496.2 1729.79
  5552.7 1733.35  5703.6 1737.49  5839.8 1744.14  5890.1 1745.09  5976.9 1748.54
#Mann= 8 ,-1 , 0
  4285.4      .1       0  4459.1     .05       0  4560.4      .1       0
  4622.5     .05       0    4984     .04       0    4990     .05       0
    5147      .1       0  5160.6     .05       0
Bank Sta=4972.3,5043.5
XS Rating Curve= 0 ,0
Exp/Cntr=0.3,0.1

Type RM Length L Ch R = 1 ,10332   ,489,489,489
BEGIN DESCRIPTION:
STINK CREEK 19.0
END DESCRIPTION:
XS GIS Cut Line= 3
       2742936.6     10063647.85      2742437.62     10064005.07
       2741781.7     10064180.36
#Sta/Elev= 30
  4360.1  1732.1  4378.3 1731.42  4442.6  1729.2  4499.1 1726.13  4528.6 1725.56
  4549.5 1723.54  4618.2 1721.75  4700.6 1718.82    4751 1716.25  4893.5 1714.14
  4929.1 1714.27  4939.6 1713.19  4961.7 1711.38  4964.5 1710.88  4967.7 1711.38
  4978.2 1711.46  5014.3 1711.78  5045.3 1714.29  5103.2 1714.44  5178.8 1716.71
  5184.8 1716.63  5288.2 1718.69  5366.2 1718.75  5386.9  1719.8  5407.6 1719.83
  5428.3  1722.3  5459.4 1723.67  5493.5 1724.53  5598.2 1725.31  5652.7 1727.67
#Mann= 11 ,-1 , 0
  4360.1     .05       0  4378.3      .1       0  4618.2     .05       0
  4939.6      .1       0  4961.7    .035       0  4967.7      .1       0
  4978.2     .05       0  5178.8      .1       0  5184.8     .05       0
  5288.2      .1       0  5598.2     .05       0
Bank Sta=4929.1,5045.3
XS Rating Curve= 0 ,0
Exp/Cntr=0.3,0.1

Type RM Length L Ch R = 1 ,9843    ,390,390,390
BEGIN DESCRIPTION:
STINK CREEK 18.0
END DESCRIPTION:
XS GIS Cut Line= 2
      2742704.15     10063551.48      2741933.23     10063540.14
#Sta/Elev= 30
  4585.5 1727.34  4601.2 1725.83  4631.2 1723.88  4671.2 1719.95  4731.2 1715.38
  4781.2 1712.58  4836.3 1711.34  4891.2 1711.13    4935 1710.29  4941.2  1710.1
  4951.2 1709.42  4961.2 1708.16  4971.2 1707.61  4998.2 1707.19    5001 1706.69
  5004.2 1707.19  5031.2 1708.67  5041.2 1710.11  5071.2 1711.46  5091.2 1712.84
  5111.2 1715.54  5151.2 1719.67  5161.2 1721.27  5181.3  1721.5  5211.3 1723.04
  5231.3 1723.11  5261.3 1724.43  5281.3 1724.42  5329.4 1725.96  5356.5 1726.84
#Mann= 6 ,-1 , 0
  4585.5      .1       0  4836.3     .05       0    4935      .1       0
  4998.2     .07       0  5004.2      .1       0  5329.4     .16       0
Bank Sta=4941.2,5041.2
XS Rating Curve= 0 ,0
Exp/Cntr=0.3,0.1

Type RM Length L Ch R = 1 ,9453    ,156,156,156
BEGIN DESCRIPTION:
STINK CREEK 17.0
END DESCRIPTION:
XS GIS Cut Line= 3
      2742777.82     10063375.71      2742443.29     10063182.93
      2741962.42     10063098.07
#Sta/Elev= 30
  4546.3 1727.82  4620.5  1722.7  4636.3 1720.89  4663.6 1718.88  4679.4 1716.37
  4738.3 1711.71  4787.9 1709.69  4824.5 1708.88  4861.8 1708.38  4920.7 1708.57
  4967.8 1707.76  4977.9 1707.16  4995.2  1702.7    4998  1702.2  5001.2  1702.7
  5008.4 1703.28  5013.8  1704.5  5038.8 1707.04    5073 1707.71  5099.8 1709.75
  5140.4  1714.3  5160.7 1715.23  5201.3 1718.86  5262.2 1722.74    5313 1725.09
  5353.6  1726.3    5359 1726.33  5364.1 1725.43  5403.4 1726.11  5420.7 1725.81
#Mann= 4 ,-1 , 0
  4546.3      .1       0  4995.2     .07       0  5001.2      .1       0
  5403.4     .05       0
Bank Sta=4967.8,5038.8
XS Rating Curve= 0 ,0
Exp/Cntr=0.3,0.1

Type RM Length L Ch R = 1 ,9297    ,90,90,90
BEGIN DESCRIPTION:
Mapping XS e5ff428e
END DESCRIPTION:
XS GIS Cut Line= 3
      2742763.59     10063237.51      2742323.02     10062964.05
      2741997.51     10063020.47
#Sta/Elev= 30
    4596 1722.36  4610.3 1721.35  4616.2 1719.45  4631.5 1717.56  4637.4 1717.92
  4646.9 1716.47  4704.8 1713.13    4726 1710.45  4741.4 1709.66    4778 1708.29
  4936.2 1707.37  4966.9 1706.46  4994.1 1702.68  4999.2 1702.43    5002 1701.93
  5005.2 1702.43  5009.5 1702.88  5015.4 1704.45  5024.8 1705.76  5030.7 1706.05
    5052 1705.44  5061.1 1706.17  5067.3 1708.16  5114.3 1714.44  5129.3 1715.02
  5149.6 1716.85  5205.2 1719.59  5257.6 1721.97  5352.6 1724.91  5444.9 1724.88
#Mann= 4 ,-1 , 0
    4596      .1       0  4999.2     .07       0  5005.2      .1       0
  5205.2     .05       0
Bank Sta=4966.9,5030.7
XS Rating Curve= 0 ,0
Exp/Cntr=0.3,0.1

Type RM Length L Ch R = 1 ,9207    ,59,59,59
BEGIN DESCRIPTION:
Mapping XS 7f913565
END DESCRIPTION:
XS GIS Cut Line= 4
      2742802.62      10063200.6      2742505.31     10062977.07
      2742359.91     10062862.05      2741931.85     10062926.91
#Sta/Elev= 30
  4583.4 1723.42  4619.8 1721.76  4655.2 1719.29    4699 1713.81  4705.2 1713.58
  4734.4 1709.69  4755.2 1708.79  4826.3 1707.06  4934.3 1706.69  4948.9  1707.6
  4976.8 1710.62  4984.1 1709.13  4998.5 1710.19  5019.3 1710.71  5027.4 1709.77
  5048.2 1704.38  5068.7 1702.45  5097.9 1704.01  5104.3 1706.41  5112.3 1708.32
  5118.7  1708.4  5126.7 1710.95  5133.1 1711.41  5138.5 1713.13  5223.1 1718.51
  5288.8 1720.22  5405.2 1722.62  5435.5 1722.12  5486.1 1723.11  5573.7  1723.7
#Mann= 4 ,-1 , 0
  4583.4      .1       0  4976.8     .07       0  5019.3      .1       0
  5288.8     .05       0
#XS Ineff= 2 , 0
         4969.63 1710.08 5022.41         1710.27
Permanent Ineff=
       T       T
Bank Sta=4976.8,5019.3
XS Rating Curve= 0 ,0
Exp/Cntr=0.3,0.1

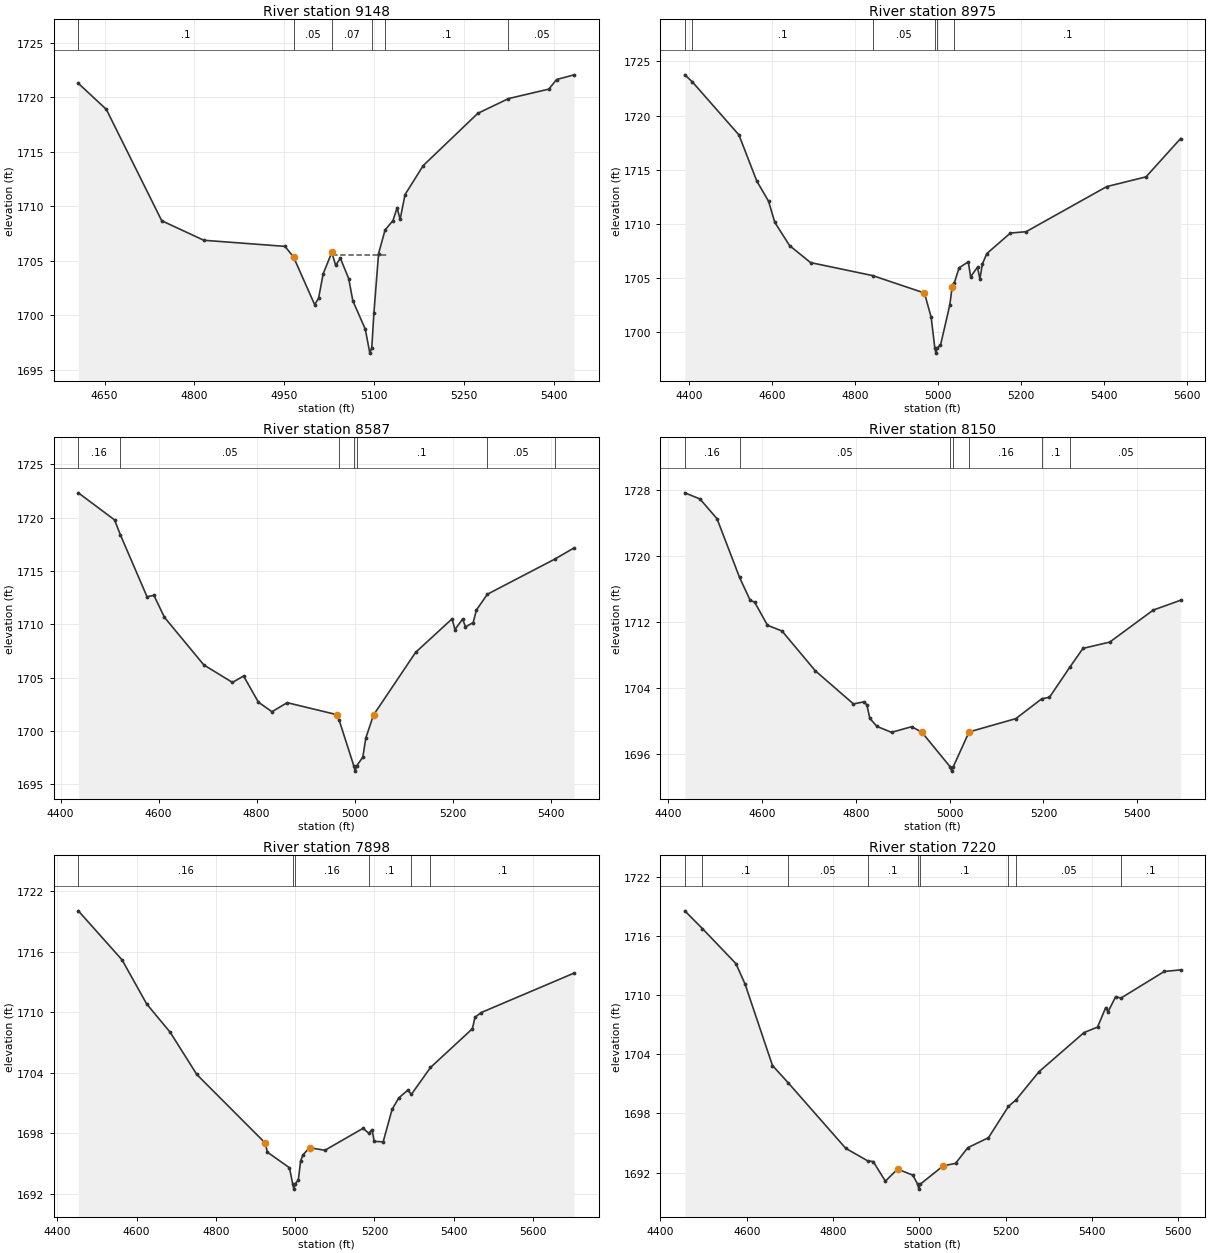
Type RM Length L Ch R = 1 ,9148    ,173,173,173
BEGIN DESCRIPTION:
Mapping XS c81c7cf2
END DESCRIPTION:
XS GIS Cut Line= 3
      2742806.92     10063150.66      2742411.99     10062825.16
      2742099.53     10062875.07
#Sta/Elev= 30
  4606.2 1721.26    4653 1718.87  4745.5 1708.66  4815.8 1706.87  4951.4 1706.31
  4965.7 1705.33  5000.9 1700.97  5007.4 1701.53  5015.2  1703.8  5029.6 1705.76
    5036 1704.57  5043.9 1705.22  5057.8 1703.36  5064.7 1701.32  5085.5 1698.72
  5093.1 1696.52  5096.4 1697.02  5099.9 1700.19  5107.7 1705.65  5118.6 1707.82
  5131.7 1708.67  5138.7 1709.84  5143.7 1708.78  5151.9 1711.06  5182.3 1713.72
  5273.5 1718.51  5324.7 1719.86  5392.1 1720.73  5405.1 1721.61  5434.4 1722.04
#Mann= 6 ,-1 , 0
  4606.2      .1       0  4965.7     .05       0  5029.6     .07       0
  5096.4     .05       0  5118.6      .1       0  5324.7     .05       0
#XS Ineff= 1 ,-1
 5031.54 5122.82 1705.54
Permanent Ineff=
       T
Bank Sta=4965.7,5029.6
XS Rating Curve= 0 ,0
Exp/Cntr=0.3,0.1

Type RM Length L Ch R = 1 ,8975    ,388,388,388
BEGIN DESCRIPTION:
STINK CREEK 16.0
END DESCRIPTION:
XS GIS Cut Line= 3
      2742908.22     10063205.61      2742602.05     10062769.03
      2742013.15     10062468.92
#Sta/Elev= 30
  4389.7 1723.76  4407.9 1723.11  4520.1 1718.21    4563 1713.96  4591.5 1712.08
  4606.4 1710.14  4642.1 1707.99  4692.7 1706.42  4842.2 1705.22  4966.9 1703.61
  4983.1 1701.37  4991.8 1698.56  4994.5 1698.06  4997.8 1698.56  5005.5 1698.78
    5028 1702.52  5033.7  1704.2  5038.8 1704.54  5050.3 1705.94  5072.5 1706.49
  5078.1 1705.11  5094.7    1706  5100.4 1704.91  5106.5 1706.29    5117 1707.25
  5173.9 1709.15  5211.5 1709.27    5406 1713.44  5500.6 1714.34  5583.9 1717.88
#Mann= 6 ,-1 , 0
  4389.7     .05       0  4407.9      .1       0  4842.2     .05       0
  4991.8    .035       0  4997.8     .05       0  5038.8      .1       0
Bank Sta=4966.9,5033.7
XS Rating Curve= 0 ,0
Exp/Cntr=0.3,0.1

Type RM Length L Ch R = 1 ,8587    ,437,437,437
BEGIN DESCRIPTION:
STINK CREEK 15.0
END DESCRIPTION:
XS GIS Cut Line= 2
      2743299.48     10062774.72      2742426.27      10062264.4
#Sta/Elev= 30
  4436.2 1722.34  4510.1  1719.8  4521.8 1718.42  4576.4 1712.59  4590.3 1712.73
  4611.8 1710.67  4692.2  1706.2  4750.6 1704.56  4773.3 1705.16  4803.5 1702.71
  4831.2 1701.81  4862.2 1702.66  4963.9 1701.53  4967.9 1701.07  4998.1 1696.74
  5000.8 1696.24  5004.1 1696.74  5016.5 1697.55  5022.6 1699.35  5038.3  1701.5
  5124.2 1707.38  5198.6 1710.52  5204.4 1709.52  5220.1  1710.5  5225.9 1709.77
  5241.6 1710.17  5248.2 1711.35  5270.6 1712.83  5407.5 1716.11  5447.6 1717.18
#Mann= 7 ,-1 , 0
  4436.2     .16       0  4521.8     .05       0  4967.9      .1       0
  4998.1     .07       0  5004.1      .1       0  5270.6     .05       0
  5407.5      .1       0
Bank Sta=4963.9,5038.3
XS Rating Curve= 0 ,0
Exp/Cntr=0.3,0.1

Type RM Length L Ch R = 1 ,8150    ,252,252,252
BEGIN DESCRIPTION:
STINK CREEK 14.0
END DESCRIPTION:
XS GIS Cut Line= 3
      2743537.58     10062417.49      2742947.91     10062065.96
      2742584.99     10061986.57
#Sta/Elev= 30
  4434.8 1727.66  4467.1 1726.92  4503.6 1724.52  4551.6 1717.42  4574.2 1714.65
  4583.9 1714.41  4611.2 1711.62  4642.3 1710.92  4713.2 1706.11  4794.7 1702.09
  4817.5 1702.35  4823.4 1701.95  4829.6 1700.34  4844.8 1699.37  4875.9 1698.65
  4918.7 1699.33  4940.2 1698.69  5001.4 1694.45  5004.1 1693.95  5007.4 1694.45
  5041.4  1698.7  5041.5  1698.7  5141.2 1700.31  5196.6 1702.72  5212.9 1702.89
  5257.2 1706.61  5284.5 1708.82  5341.5 1709.58  5434.4 1713.46  5492.8 1714.65
#Mann= 7 ,-1 , 0
  4434.8     .16       0  4551.6     .05       0  5001.4    .035       0
  5007.4     .05       0  5041.5     .16       0  5196.6      .1       0
  5257.2     .05       0
Bank Sta=4940.2,5041.4
XS Rating Curve= 0 ,0
Exp/Cntr=0.3,0.1

Type RM Length L Ch R = 1 ,7898    ,678,678,678
BEGIN DESCRIPTION:
STINK CREEK 13.0
END DESCRIPTION:
XS GIS Cut Line= 2
      2743656.62     10062145.32        2742534.     10061595.35
#Sta/Elev= 30
  4453.3 1720.04  4563.7 1715.17  4625.6 1710.81  4685.1 1707.99  4751.9 1703.82
  4923.7 1697.05  4930.1 1696.11  4985.6 1694.57  4993.9 1692.95  4996.6 1692.45
  4999.9 1692.95    5008 1693.37  5013.7 1695.23  5019.3 1695.83  5036.2 1696.56
  5074.8  1696.3  5171.2 1698.48  5185.5 1697.99  5193.7 1698.35  5199.3 1697.19
  5221.8 1697.13  5244.3 1700.35  5261.2 1701.49  5283.7 1702.26  5293.1 1701.85
  5341.2 1704.51  5446.8 1708.35  5453.4 1709.49  5469.3 1709.96  5703.4 1713.87
#Mann= 6 ,-1 , 0
  4453.3     .16       0  4993.9     .07       0  4999.9     .16       0
  5185.5      .1       0  5293.1     .16       0  5341.2      .1       0
Bank Sta=4923.7,5036.2
XS Rating Curve= 0 ,0
Exp/Cntr=0.3,0.1

Type RM Length L Ch R = 1 ,7220    ,518,518,518
BEGIN DESCRIPTION:
STINK CREEK 12.0
END DESCRIPTION:
XS GIS Cut Line= 3
      2743889.13     10061850.51      2743412.85     10061379.89
      2742954.55     10061238.44
#Sta/Elev= 30
  4456.5 1718.55  4497.5 1716.74  4574.9  1713.2  4596.1 1711.13  4659.7 1702.86
  4696.1 1701.11  4829.5 1694.46  4880.3 1693.19  4893.1 1693.12  4921.4 1691.13
  4949.6 1692.35    4985 1691.74  4996.2 1690.82  4998.9 1690.32  5002.2 1690.82
  5055.7 1692.69    5084 1692.93  5112.3 1694.52  5160.4 1695.54  5206.6 1698.71
  5224.5 1699.39  5277.2 1702.22  5381.8  1706.2  5413.2 1706.76  5432.1 1708.74
  5437.3 1708.29  5455.1 1709.84  5467.4  1709.7  5567.9  1712.4  5605.7 1712.56
#Mann= 9 ,-1 , 0
  4456.5     .05       0  4497.5      .1       0  4696.1     .05       0
  4880.3      .1       0  4996.2     .07       0  5002.2      .1       0
  5206.6     .16       0  5224.5     .05       0  5467.4      .1       0
Bank Sta=4949.6,5055.7
XS Rating Curve= 0 ,0
Exp/Cntr=0.3,0.1

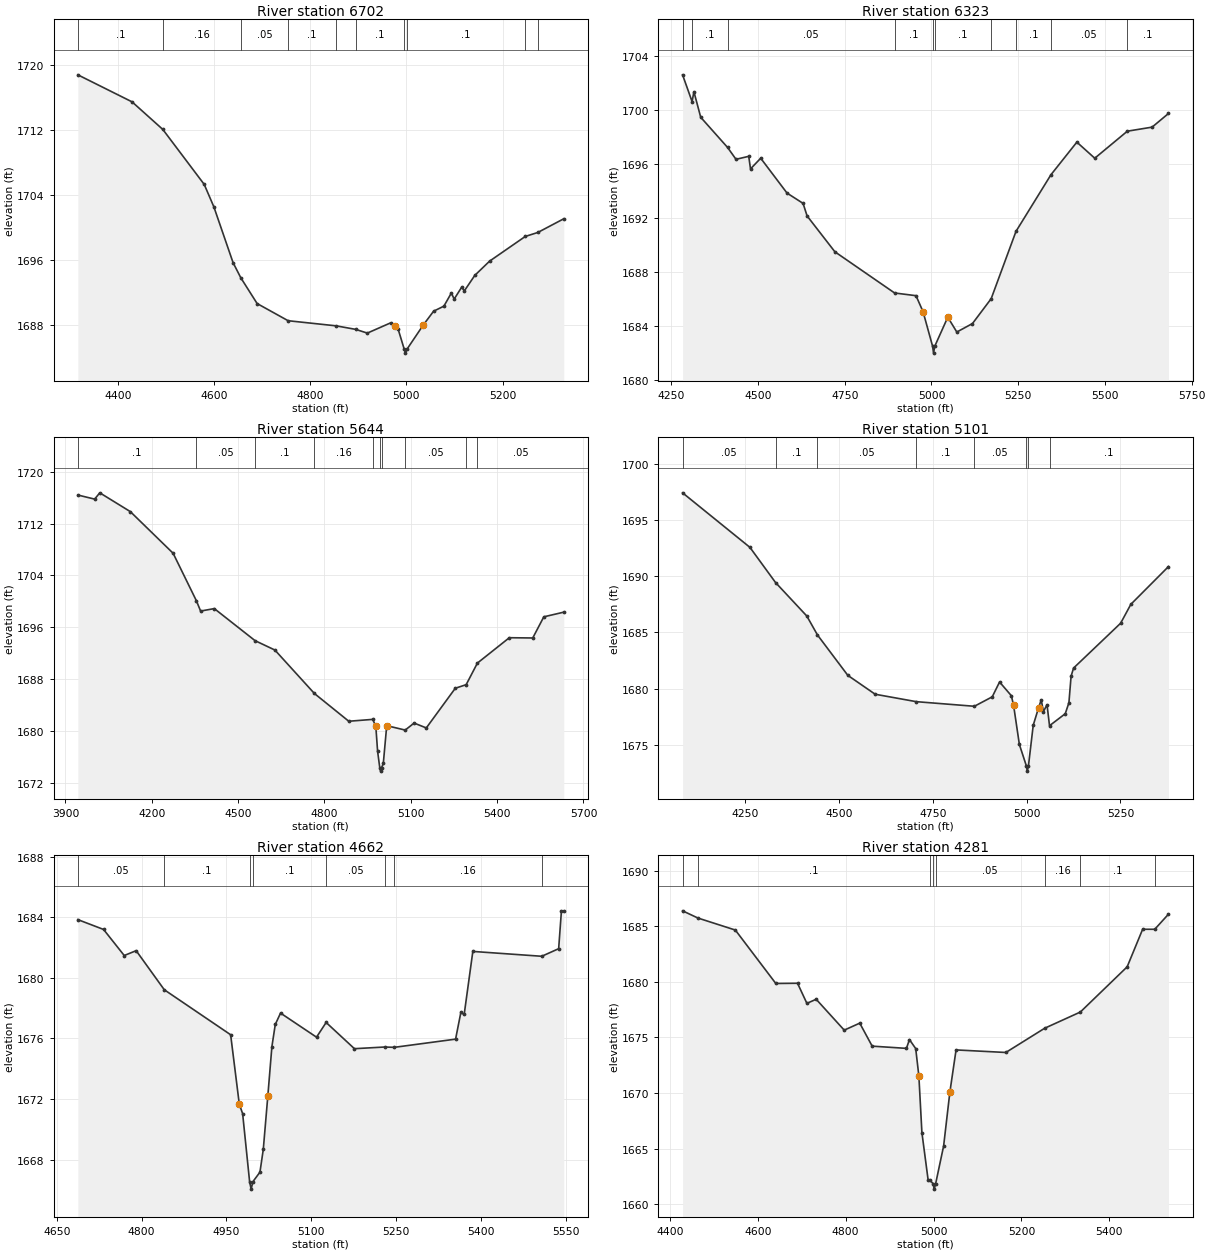
Type RM Length L Ch R = 1 ,6702    ,379,379,379
BEGIN DESCRIPTION:
STINK CREEK 11.0
END DESCRIPTION:
XS GIS Cut Line= 3
      2743962.83     10061816.53      2743974.17     10061289.17
      2743724.72     10060875.31
#Sta/Elev= 30
  4316.7 1718.76  4429.5 1715.44  4493.5 1712.05  4579.6  1705.3  4599.6 1702.55
  4639.6 1695.69  4655.8 1693.82  4689.6 1690.67  4754.1 1688.56  4854.1 1687.93
  4894.4  1687.5  4918.9 1687.04  4967.4  1688.3  4977.1 1687.96    4983 1687.51
  4995.5 1685.08  4998.2 1684.58  5001.5 1685.08  5035.4 1688.05  5056.7 1689.73
  5078.1 1690.35  5093.6 1691.96  5099.5 1691.22    5115 1692.67  5120.8 1692.24
  5142.4 1694.13  5173.2 1695.88  5247.4 1698.91  5273.5  1699.4  5327.4 1701.08
#Mann= 10 ,-1 , 0
  4316.7      .1       0  4493.5     .16       0  4655.8     .05       0
  4754.1      .1       0  4854.1     .05       0  4894.4      .1       0
  4995.5     .07       0  5001.5      .1       0  5247.4     .05       0
  5273.5      .1       0
Bank Sta=4977.1,5035.4
XS Rating Curve= 0 ,0
Exp/Cntr=0.3,0.1

Type RM Length L Ch R = 1 ,6323    ,679,679,679
BEGIN DESCRIPTION:
STINK CREEK 10.0
END DESCRIPTION:
XS GIS Cut Line= 3
      2744388.66     10061765.13       2744227.2     10060900.54
      2743722.73     10060770.52
#Sta/Elev= 30
  4282.7 1702.59  4310.1 1700.61  4315.4 1701.34    4335 1699.45  4412.3 1697.22
  4436.7 1696.34  4473.4 1696.56  4478.5 1695.63  4507.9 1696.42  4583.8 1693.84
    4630 1693.08  4641.6 1692.15  4721.6  1689.5  4893.8 1686.45  4955.5 1686.25
  4975.9 1685.06  5003.4  1682.5  5006.1    1682  5009.4  1682.5  5047.1 1684.66
  5073.1 1683.56  5118.3 1684.19  5172.2 1686.03  5243.7 1691.01  5344.5  1695.2
  5419.1 1697.61  5470.7 1696.42  5564.6 1698.42    5636 1698.72  5683.2 1699.73
#Mann= 10 ,-1 , 0
  4282.7     .05       0  4310.1      .1       0  4412.3     .05       0
  4893.8      .1       0  5003.4     .07       0  5009.4      .1       0
  5172.2     .05       0  5243.7      .1       0  5344.5     .05       0
  5564.6      .1       0
Bank Sta=4975.9,5047.1
XS Rating Curve= 0 ,0
Exp/Cntr=0.3,0.1

Type RM Length L Ch R = 1 ,5644    ,543,543,543
BEGIN DESCRIPTION:
STINK CREEK 9.0
END DESCRIPTION:
XS GIS Cut Line= 3
      2745430.36     10060827.63      2744581.37     10060525.54
      2743836.62     10060780.73
#Sta/Elev= 30
  3943.1  1716.4  4001.5 1715.77  4019.4 1716.74  4125.6 1713.84  4274.2 1707.42
  4354.8 1700.12  4369.7 1698.51  4417.3 1698.89  4558.8 1693.95  4627.8  1692.5
  4765.1  1685.8  4884.6 1681.52  4967.9 1681.81  4978.5 1680.72  4984.7 1676.88
  4992.3 1674.33  4995.1 1673.83  4998.3 1674.33  5004.5 1675.01  5016.4 1680.84
  5080.6 1680.16  5111.6 1681.24  5153.9 1680.49  5254.7 1686.61  5292.4 1687.16
  5331.5 1690.49  5442.4  1694.4  5523.8 1694.36  5562.2 1697.62  5631.5 1698.34
#Mann= 10 ,-1 , 0
  3943.1      .1       0  4354.8     .05       0  4558.8      .1       0
  4765.1     .16       0  4967.9      .1       0  4992.3     .07       0
  4998.3      .1       0  5080.6     .05       0  5292.4      .1       0
  5331.5     .05       0
Bank Sta=4978.5,5016.4
XS Rating Curve= 0 ,0
Exp/Cntr=0.3,0.1

Type RM Length L Ch R = 1 ,5101    ,439,439,439
BEGIN DESCRIPTION:
STINK CREEK 8.0
END DESCRIPTION:
XS GIS Cut Line= 3
      2744955.05     10059752.63      2744240.66     10060206.22
      2744009.09     10060590.28
#Sta/Elev= 30
  4083.3 1697.42  4262.7 1692.57    4331 1689.44  4414.3 1686.46  4442.8 1684.77
  4523.6 1681.18  4596.5  1679.5  4706.1 1678.84  4860.8 1678.43  4908.4 1679.27
  4927.9 1680.59  4959.3 1679.37  4965.2 1678.53  4980.7 1675.03    4999 1673.16
  5001.8 1672.66    5005 1673.16  5017.6 1676.74  5031.7 1678.28  5038.9    1679
  5044.8 1677.96  5054.4 1678.57    5061  1676.7    5103 1677.77  5112.7 1678.75
  5118.5 1681.11  5125.1 1681.83  5250.5 1685.82  5277.7  1687.5    5378 1690.86
#Mann= 8 ,-1 , 0
  4083.3     .05       0    4331      .1       0  4442.8     .05       0
  4706.1      .1       0  4860.8     .05       0    4999     .04       0
    5005     .05       0    5061      .1       0
Bank Sta=4965.2,5031.7
XS Rating Curve= 0 ,0
Exp/Cntr=0.3,0.1

Type RM Length L Ch R = 1 ,4662    ,381,381,381
BEGIN DESCRIPTION:
STINK CREEK 7.0
END DESCRIPTION:
XS GIS Cut Line= 2
      2744087.58     10059729.92      2743628.29     10060455.71
#Sta/Elev= 30
  4687.3 1683.84  4732.8 1683.19  4769.3 1681.47  4790.4 1681.79  4840.1 1679.21
  4957.4 1676.24  4972.7 1671.66  4978.6 1671.03  4990.9 1666.55  4993.6 1666.05
  4996.9 1666.55  5009.2 1667.17  5015.1 1668.67  5023.2 1672.23  5030.3 1675.45
  5036.3 1676.92  5045.6 1677.67  5109.2 1676.08  5126.2 1677.05  5176.2 1675.32
  5229.5 1675.43  5246.8 1675.41    5355 1675.95  5364.3 1677.71  5370.2 1677.58
  5385.5 1681.74  5507.3 1681.42  5537.2 1681.92  5542.1 1684.42  5546.2 1684.42
#Mann= 8 ,-1 , 0
  4687.3     .05       0  4840.1      .1       0  4990.9     .07       0
  4996.9      .1       0  5126.2     .05       0  5229.5      .1       0
  5246.8     .16       0  5507.3      .1       0
Bank Sta=4972.7,5023.2
XS Rating Curve= 0 ,0
Exp/Cntr=0.3,0.1

Type RM Length L Ch R = 1 ,4281    ,503,503,503
BEGIN DESCRIPTION:
STINK CREEK 6.0
END DESCRIPTION:
XS GIS Cut Line= 2
      2743974.15     10059599.55      2743181.34     10060369.71
#Sta/Elev= 30
  4429.1  1686.4  4464.1 1685.75  4549.1 1684.67  4641.2 1679.86  4690.6 1679.88
  4711.9 1678.07    4733 1678.44  4796.8 1675.66  4832.1 1676.29  4860.4 1674.22
  4938.3 1674.02  4945.2 1674.81  4959.4    1674  4966.6 1671.53  4973.5 1666.44
  4987.7 1662.16  4991.2 1662.17  4998.8 1661.85  5001.6 1661.35  5004.8 1661.85
  5022.9 1665.23  5037.1 1670.08  5051.2 1673.88  5164.4 1673.65  5252.7 1675.83
  5333.9 1677.29  5440.4 1681.36  5475.6 1684.74  5503.2 1684.74  5534.4  1686.1
#Mann= 8 ,-1 , 0
  4429.1     .05       0  4464.1      .1       0  4991.2     .05       0
  4998.8    .035       0  5004.8     .05       0  5252.7     .16       0
  5333.9      .1       0  5503.2     .05       0
Bank Sta=4966.6,5037.1
XS Rating Curve= 0 ,0
Exp/Cntr=0.3,0.1