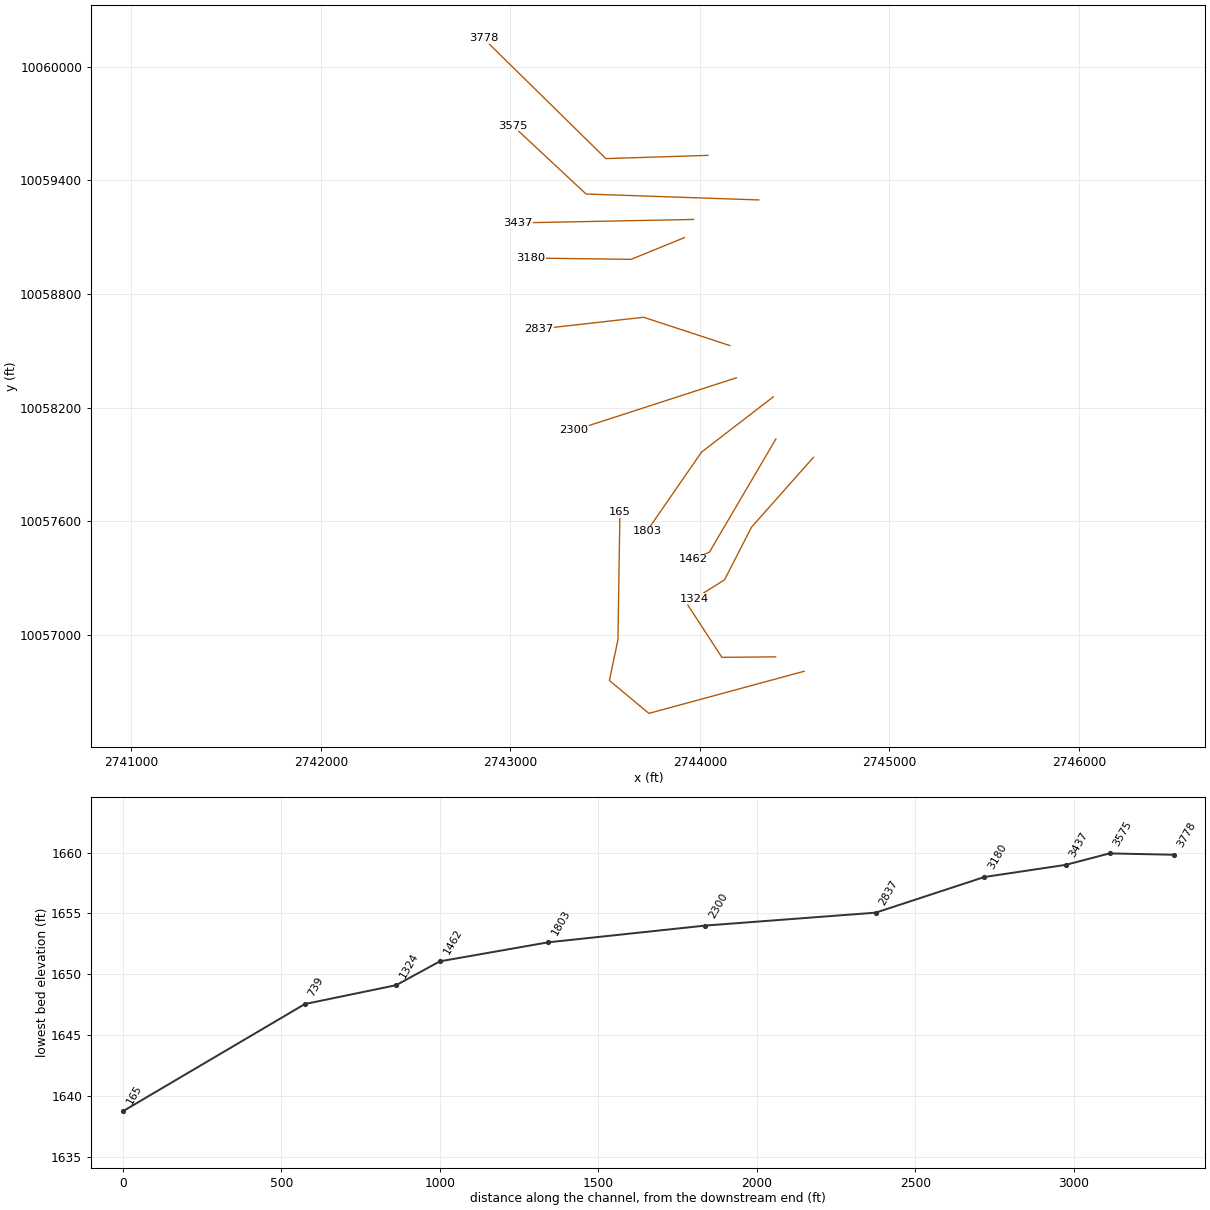
HEC-RAS study STINK CREEK.prj: STINK CREEK Base Level Engineering

--- STINK CREEK.g01 (geometry) --- (continued)

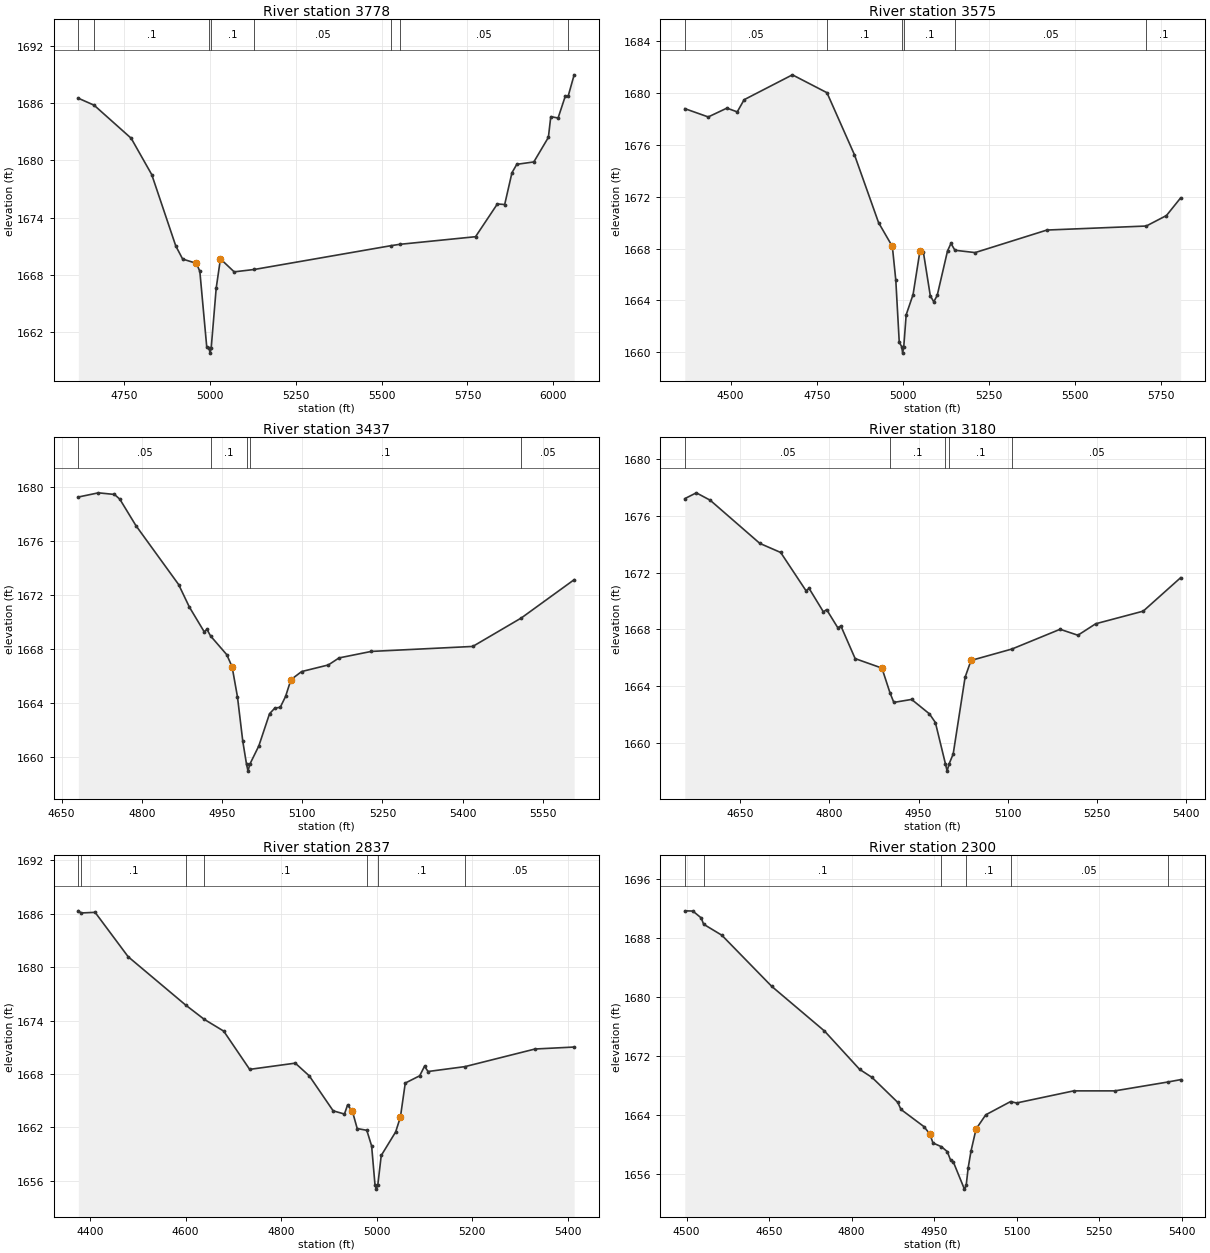
Type RM Length L Ch R = 1 ,3778    ,203,203,203
BEGIN DESCRIPTION:
STINK CREEK 5.0
END DESCRIPTION:
XS GIS Cut Line= 3
      2744042.25      10059531.5      2743503.57     10059514.48
       2742857.6     10060149.11
#Sta/Elev= 30
  4616.4 1686.51  4662.3 1685.78  4770.3 1682.32  4830.3 1678.51  4900.3 1671.04
  4920.3 1669.67  4960.4 1669.22  4970.4 1668.38  4990.4 1660.51  4997.4 1660.32
  5000.1 1659.82  5003.4 1660.32  5018.1 1666.64  5030.4 1669.69  5070.4 1668.33
  5129.1 1668.58  5527.1 1671.07  5552.2 1671.21  5773.6 1672.01  5837.2 1675.44
  5858.5 1675.38  5879.7 1678.71  5893.8 1679.59  5943.4 1679.84  5985.8 1682.41
  5992.8 1684.58  6014.1 1684.44  6035.2 1686.74  6043.3 1686.71  6060.9 1688.96
#Mann= 8 ,-1 , 0
  4616.4     .05       0  4662.3      .1       0  4997.4     .07       0
  5003.4      .1       0  5129.1     .05       0  5527.1      .1       0
  5552.2     .05       0  6043.3      .1       0
Bank Sta=4960.4,5030.4
XS Rating Curve= 0 ,0
Exp/Cntr=0.3,0.1

Type RM Length L Ch R = 1 ,3575    ,138,138,138
BEGIN DESCRIPTION:
STINK CREEK 4.0
END DESCRIPTION:
XS GIS Cut Line= 3
      2744310.54     10059296.37      2743399.08     10059327.62
      2743013.64     10059687.02
#Sta/Elev= 30
  4367.1  1678.8  4435.1 1678.16  4489.3 1678.84  4519.3 1678.55  4539.3 1679.49
  4679.4 1681.41  4779.7 1680.03  4859.5 1675.24  4929.5    1670  4969.5 1668.16
  4979.5 1665.55  4989.5 1660.77  4996.6 1660.43  4999.3 1659.93  5002.6 1660.43
  5009.6 1662.89  5029.6 1664.45  5049.6 1667.82  5059.6 1667.71  5079.6 1664.36
  5089.6 1663.89  5099.6 1664.38  5129.6 1667.82  5139.6  1668.4    5151 1667.87
  5209.7 1667.69  5418.1 1669.43  5706.4 1669.74    5765 1670.55  5806.1 1671.91
#Mann= 6 ,-1 , 0
  4367.1     .05       0  4779.7      .1       0  4996.6     .07       0
  5002.6      .1       0    5151     .05       0  5706.4      .1       0
Bank Sta=4969.5,5049.6
XS Rating Curve= 0 ,0
Exp/Cntr=0.3,0.1

Type RM Length L Ch R = 1 ,3437    ,257,257,257
BEGIN DESCRIPTION:
Mapping XS 1807ae85
END DESCRIPTION:
XS GIS Cut Line= 2
      2743966.02     10059193.42       2743038.9     10059175.19
#Sta/Elev= 30
  4681.2 1679.28  4718.8 1679.59  4748.8 1679.47  4758.8 1679.12  4788.8 1677.17
  4868.8  1672.8  4888.8 1671.14  4916.7  1669.3  4921.7 1669.49  4928.4    1669
  4958.8 1667.61  4968.8 1666.71  4978.8 1664.49  4988.8 1661.19  4995.8 1659.49
  4998.6 1658.99  5001.8 1659.49  5018.8 1660.86  5038.8 1663.24  5048.8 1663.66
  5058.8 1663.71  5068.8 1664.52  5078.8 1665.76  5098.8 1666.36  5148.8 1666.85
  5168.8 1667.37  5228.9 1667.85  5418.9 1668.22  5509.8 1670.33  5608.5 1673.16
#Mann= 5 ,-1 , 0
  4681.2     .05       0  4928.4      .1       0  4995.8     .07       0
  5001.8      .1       0  5509.8     .05       0
Bank Sta=4968.8,5078.8
XS Rating Curve= 0 ,0
Exp/Cntr=0.3,0.1

Type RM Length L Ch R = 1 ,3180    ,343,343,343
BEGIN DESCRIPTION:
Mapping XS 066fe4ba
END DESCRIPTION:
XS GIS Cut Line= 3
      2743918.03     10059097.45      2743636.79     10058982.87
      2743105.52     10058989.82
#Sta/Elev= 30
  4556.4 1677.22  4575.8 1677.63  4599.1 1677.11  4682.8 1674.06  4717.9 1673.42
  4760.4 1670.73  4765.8 1670.88  4789.8 1669.23  4795.2 1669.39  4813.9 1668.12
  4819.3 1668.23  4843.3 1665.93  4888.4 1665.26    4902 1663.51  4908.4 1662.84
  4938.4 1663.05  4968.4 1662.03  4978.4 1661.42  4995.4 1658.49  4998.2 1657.99
  5001.4 1658.49  5008.4  1659.2  5028.4 1664.61  5038.4  1665.8  5107.5 1666.61
  5188.4    1668  5218.4 1667.58  5248.4 1668.39  5328.4 1669.28  5391.4 1671.64
#Mann= 5 ,-1 , 0
  4556.4     .05       0    4902      .1       0  4995.4     .07       0
  5001.4      .1       0  5107.5     .05       0
Bank Sta=4888.4,5038.4
XS Rating Curve= 0 ,0
Exp/Cntr=0.3,0.1

Type RM Length L Ch R = 1 ,2837    ,537,537,537
BEGIN DESCRIPTION:
Mapping XS f544b573
END DESCRIPTION:
XS GIS Cut Line= 3
       2744157.6     10058528.02      2743702.77     10058677.32
      2743147.19     10058614.81
#Sta/Elev= 30
  4375.4 1686.34  4381.3  1686.1  4410.5 1686.17  4479.7 1681.18  4599.8 1675.76
  4638.8 1674.15  4679.7 1672.82    4734 1668.52  4829.5 1669.22  4858.8 1667.79
  4908.8 1663.86  4932.4  1663.5  4938.9 1664.51    4949 1663.82  4959.1 1661.87
  4979.2 1661.67  4989.3 1659.91  4996.3 1655.56  4999.1 1655.06  5002.3 1655.56
  5009.4 1658.84  5039.6 1661.49  5049.6 1663.18  5059.7 1666.98  5089.9  1667.8
    5100 1668.87  5107.4 1668.28  5184.7 1668.83  5331.4 1670.81  5413.2 1671.03
#Mann= 7 ,-1 , 0
  4375.4     .05       0  4381.3      .1       0  4599.8     .05       0
  4638.8      .1       0  4979.2     .05       0  5002.3      .1       0
  5184.7     .05       0
Bank Sta=4949,5049.6
XS Rating Curve= 0 ,0
Exp/Cntr=0.3,0.1

Type RM Length L Ch R = 1 ,2300    ,497,497,497
BEGIN DESCRIPTION:
Mapping XS e5af36f0
END DESCRIPTION:
XS GIS Cut Line= 2
      2744192.34     10058357.87       2743334.7     10058080.09
#Sta/Elev= 30
  4496.6 1691.67  4511.2 1691.64  4526.6  1690.7  4530.7 1689.86  4563.9 1688.37
  4654.6 1681.45  4750.6  1675.4  4814.5 1670.21    4837 1669.12  4883.8 1665.74
  4889.6 1664.79  4931.6 1662.45  4942.2 1661.45  4947.8 1660.25  4963.2 1659.74
  4973.7 1659.09  4979.8 1657.94    4985 1657.65    5005    1654  5008.2  1654.5
  5011.8 1656.87    5017 1659.16  5026.2 1662.14  5043.8 1664.06  5088.9 1665.85
  5099.8 1665.66  5203.7  1667.3  5278.5  1667.3  5374.9  1668.5  5398.1 1668.82
#Mann= 6 ,-1 , 0
  4496.6     .05       0  4530.7      .1       0  4963.2     .05       0
  5008.2      .1       0  5088.9     .05       0  5374.9      .1       0
Bank Sta=4942.2,5026.2
XS Rating Curve= 0 ,0
Exp/Cntr=0.3,0.1

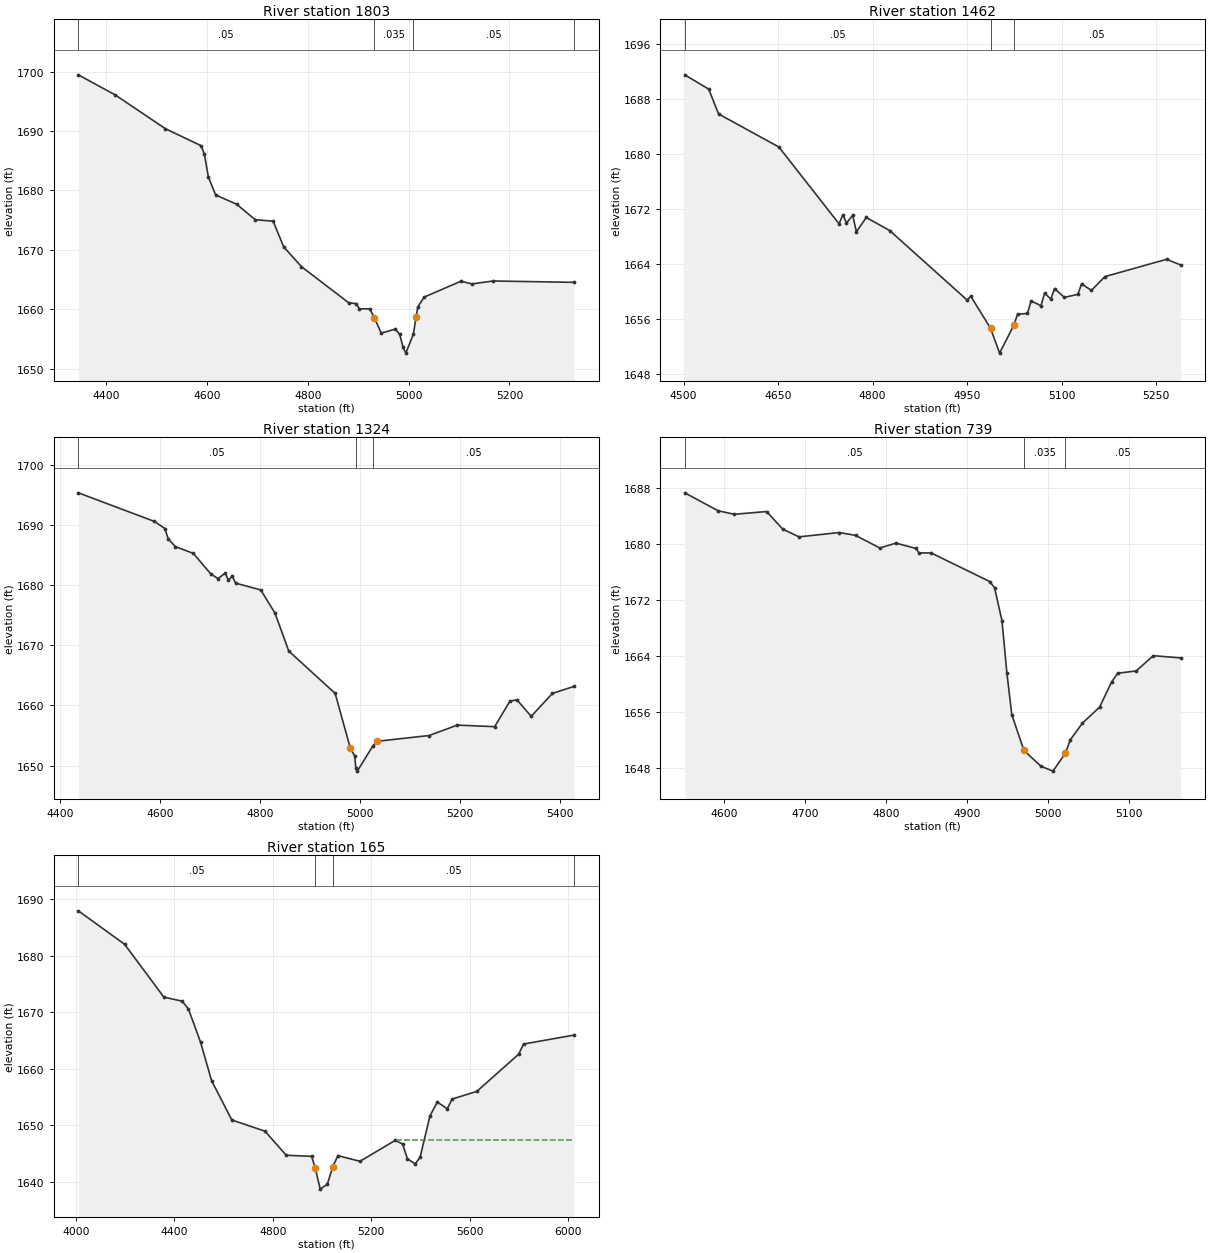
Type RM Length L Ch R = 1 ,1803    ,341,341,341
BEGIN DESCRIPTION:
Mapping XS f4f5fb4f
END DESCRIPTION:
XS GIS Cut Line= 3
      2744386.83     10058257.21      2744008.32     10057965.51
      2743720.12     10057548.84
#Sta/Elev= 30
  4344.1 1699.45  4417.5 1696.06  4517.1 1690.38  4587.8 1687.53  4594.5 1686.08
  4602.3 1682.25  4616.8 1679.23  4658.4 1677.68  4695.5 1675.06  4730.9 1674.83
  4751.8 1670.51  4787.1 1667.17    4881 1661.09  4895.9 1660.95    4902 1660.07
  4922.9 1660.07  4931.7 1658.61  4945.7 1655.98  4973.6 1656.67  4982.2 1655.77
  4988.5 1653.73  4994.3 1652.62  5009.4 1655.81 5014.77 1658.76  5018.2 1660.41
  5030.8 1662.05  5103.8 1664.72  5125.7 1664.27  5167.6 1664.76  5328.6 1664.53
#Mann= 4 ,-1 , 0
  4344.1     .05       0  4931.7    .035       0  5009.4     .05       0
  5328.6     .05       0
Bank Sta=4931.7,5014.77
XS Rating Curve= 0 ,0
Exp/Cntr=0.3,0.1

Type RM Length L Ch R = 1 ,1462    ,138,138,138
BEGIN DESCRIPTION:
Mapping XS 5c02317b
END DESCRIPTION:
XS GIS Cut Line= 3
      2744400.66     10058034.91      2744049.99     10057437.73
      2743963.33      10057399.6
#Sta/Elev= 30
  4501.9 1691.46  4539.9 1689.38  4555.5 1685.78  4651.3 1680.98  4746.8 1669.83
  4752.8 1671.16  4758.6 1669.95  4768.5 1671.07  4774.3 1668.67    4790 1670.75
  4827.1 1668.86  4950.2 1658.76    4956 1659.31  4987.3 1654.67  5001.7 1651.06
  5024.4 1655.14  5030.2 1656.71  5045.9 1656.82  5051.7 1658.63  5067.4 1657.95
  5073.2 1659.77  5083.1 1658.91  5088.9 1660.43  5104.5 1659.15    5126  1659.6
  5131.8 1661.11  5147.5 1660.17  5168.9 1662.17  5266.8 1664.68  5289.1 1663.86
#Mann= 3 , 0 , 0
  4501.9     .05       0  4987.3    .035       0  5024.4     .05       0
Bank Sta=4987.3,5024.4
XS Rating Curve= 0 ,0
Exp/Cntr=0.3,0.1

Type RM Length L Ch R = 1 ,1324    ,288,288,288
BEGIN DESCRIPTION:
Mapping XS ca9046d5
END DESCRIPTION:
XS GIS Cut Line= 4
      2744598.61     10057937.75      2744272.21     10057569.68
      2744129.85      10057291.9      2743971.82     10057192.27
#Sta/Elev= 30
  4436.9  1695.3    4589 1690.55  4609.9 1689.37  4616.6 1687.64  4630.8 1686.38
  4666.8 1685.24  4701.9 1681.81  4716.1 1681.07  4730.3 1681.96    4737  1680.8
  4744.5 1681.46  4751.2 1680.31  4801.4 1679.18  4829.9 1675.34  4857.4 1669.04
  4950.2    1662  4980.5  1652.9    4989 1651.65  4991.6  1649.6  4994.4  1649.1
  5025.4 1653.26  5033.4 1654.05  5137.8 1655.01  5194.4 1656.74  5268.9 1656.48
  5299.5 1660.73  5313.5 1660.93  5341.9  1658.2  5384.5 1662.01  5427.8 1663.17
#Mann= 3 ,-1 , 0
  4436.9     .05       0  4991.6    .035       0  5025.4     .05       0
Bank Sta=4980.5,5033.4
XS Rating Curve= 0 ,0
Exp/Cntr=0.3,0.1

Type RM Length L Ch R = 1 ,739     ,574,574,574
XS GIS Cut Line= 3
      2744399.65     10056885.32       2744115.8     10056882.72
      2743936.13     10057158.73
#Sta/Elev= 30
  4551.1 1687.25  4592.3 1684.69  4612.3 1684.19  4652.3 1684.58  4672.3 1682.06
  4692.3 1680.97  4742.3 1681.59  4762.3 1681.18  4792.3 1679.38  4812.3 1680.08
  4837.1 1679.31  4840.7 1678.68  4855.8 1678.67  4928.3 1674.59  4934.2 1673.71
  4943.4 1668.97  4949.4 1661.59  4955.5 1655.61  4970.5  1650.5  4991.6 1648.25
  5006.4 1647.55  5021.8 1650.11  5027.8    1652  5042.9  1654.4    5064 1656.67
  5079.2 1660.32  5086.7 1661.52  5109.4 1661.84  5130.5 1664.02  5164.3  1663.7
#Mann= 3 , 0 , 0
  4551.1     .05       0  4970.5    .035       0  5021.8     .05       0
Bank Sta=4970.5,5021.8
XS Rating Curve= 0 ,0
Exp/Cntr=0.3,0.1

Type RM Length L Ch R = 1 ,165     ,0,0,0
BEGIN DESCRIPTION:
STINK CREEK 1.0
END DESCRIPTION:
XS GIS Cut Line= 5
      2744549.97     10056809.26      2743730.54     10056587.04
      2743522.21     10056760.65      2743567.35     10056975.93
      2743577.76     10057649.18
#Sta/Elev= 30
  4010.3 1687.96  4198.3 1682.04  4357.6  1672.7    4432 1671.98  4457.4 1670.61
  4506.5 1664.75  4551.5 1657.92  4633.5 1650.97  4768.2 1648.99  4854.6 1644.73
  4957.7 1644.54    4972 1642.51  4992.6 1638.74  5021.5 1639.61  5043.6 1642.72
  5064.4 1644.66  5154.1 1643.66  5297.1 1647.36  5327.1 1646.72  5346.8  1644.1
  5378.3 1643.21  5398.3  1644.4  5438.3  1651.7  5468.3 1654.14  5508.3 1652.95
  5528.3 1654.67  5628.3 1656.02  5798.3 1662.59  5818.3  1664.4  6023.8 1665.99
#Mann= 4 ,-1 , 0
  4010.3     .05       0    4972    .035       0  5043.6     .05       0
  6023.8     .05       0
#XS Ineff= 2 , 0
                          5305.4         1647.35
Permanent Ineff=
       T       T
Bank Sta=4972,5043.6
XS Rating Curve= 0 ,0
Exp/Cntr=0.3,0.1

Chan Stop Cuts=-1
Use User Specified Reach Order=0
Composite Channel Slope=5