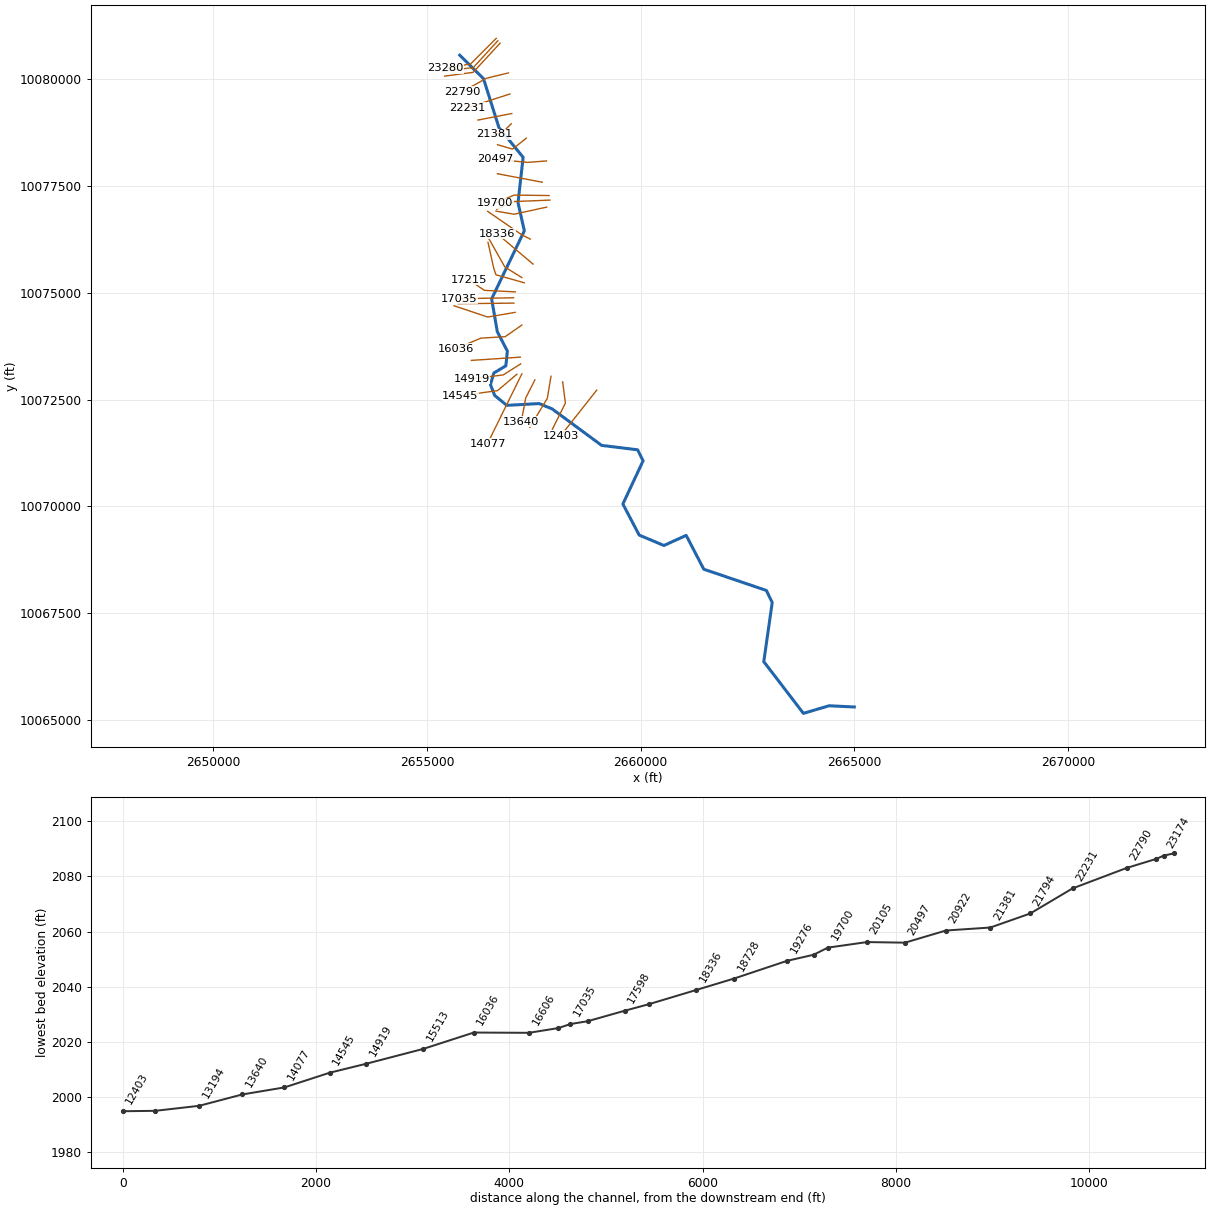
--- STUCKENS BRANCH.prj (project) ---

Proj Title=STUCKENS BRANCH Base Level Engineering
Current Plan=p01
Default Exp/Contr=0.3,0.1
English Units
Geom File=g01
Flow File=f01
Plan File=p01
BEGIN DESCRIPTION:
STUCKENS BRANCH
END DESCRIPTION:

--- STUCKENS BRANCH.p01 (plan) ---

Plan Title=Multiple Run
Short Identifier=Multiple
Geom File=g01
Flow File=f01
Subcritical Flow
K Sum by GR= 0
Std Step Tol= 0.01
Critical Tol= 0.01
Num of Std Step Trials= 20
Max Error Tol= 0.3
Flow Tol Ratio= 0.001
Split Flow NTrial= 30
Split Flow Tol= 0.02
Split Flow Ratio= 0.02
Log Output Level= 0
Friction Slope Method= 1
Unsteady Friction Slope Method= 2
Unsteady Bridges Friction Slope Method= 1
Parabolic Critical Depth
Global Vel Dist=  1 , 1 , 1
Global Log Level= 0
CheckData=True
Encroach Param= -1, 0, 0, 0
BEGIN DESCRIPTION:
Multiple Run
END DESCRIPTION:

--- STUCKENS BRANCH.f01 (steady flow) ---

Flow Title=Multiple
Number of Profiles=7
Profile Names=10-year,25-year,50-year,1pct_min,100-year,1pct_plu,500-year
River Rch & RM= STUCKENS BRANCH,Reach-1,23280
     979    1413    1785    1643    2222    3005    3444
River Rch & RM= STUCKENS BRANCH,Reach-1,22231
    1466    2163    2772    2586    3497    4729    5567
River Rch & RM= STUCKENS BRANCH,Reach-1,19552
    1823    2717    3505    3288    4447    6014    7166
River Rch & RM= STUCKENS BRANCH,Reach-1,16912
    2257    3394    4405    4153    5617    7596    9146
River Rch & RM= STUCKENS BRANCH,Reach-1,10583
    2687    4071    5310    5030    6802    9199   11175
River Rch & RM= STUCKENS BRANCH,Reach-1,6541
    2926    4448    5814    5517    7461   10091   12306
Boundary for River Rch & Prof#=STUCKENS BRANCH,Reach-1,1
Up Type=0
Dn Type=3
Dn Slope=0.005
Boundary for River Rch & Prof#=STUCKENS BRANCH,Reach-1,2
Up Type=0
Dn Type=3
Dn Slope=0.005
Boundary for River Rch & Prof#=STUCKENS BRANCH,Reach-1,3
Up Type=0
Dn Type=3
Dn Slope=0.005
Boundary for River Rch & Prof#=STUCKENS BRANCH,Reach-1,4
Up Type=0
Dn Type=3
Dn Slope=0.005
Boundary for River Rch & Prof#=STUCKENS BRANCH,Reach-1,5
Up Type=0
Dn Type=3
Dn Slope=0.005
Boundary for River Rch & Prof#=STUCKENS BRANCH,Reach-1,6
Up Type=0
Dn Type=3
Dn Slope=0.005
Boundary for River Rch & Prof#=STUCKENS BRANCH,Reach-1,7
Up Type=0
Dn Type=3
Dn Slope=0.005

--- STUCKENS BRANCH.g01 (geometry) ---

Geom Title=Existing Conditions

River Reach=STUCKENS BRANCH,Reach-1
Reach XY= 30
      2655763.97     10080559.23      2656320.46     10080009.72
      2656681.73     10078865.07      2657247.87     10078168.65
      2657128.23     10077106.71      2657276.57     10076449.57
      2656511.34     10074856.37      2656642.39     10074090.68
      2656878.77     10073634.50      2656843.68     10073289.52
      2656562.91     10073120.71      2656482.62     10072849.45
      2656582.44     10072595.54      2656864.56     10072363.34
      2657622.73     10072405.02      2657927.17     10072280.41
      2659085.25     10071426.61      2659928.12     10071322.94
      2660055.73     10071064.88      2659582.60     10070054.37
      2659964.39     10069327.52      2660543.45     10069083.57
      2661064.79     10069320.46      2661475.54     10068528.50
      2662940.85     10068031.56      2663077.91     10067748.99
      2662881.01     10066364.90      2663808.49     10065154.16
      2664408.91     10065332.67      2664998.47     10065303.73

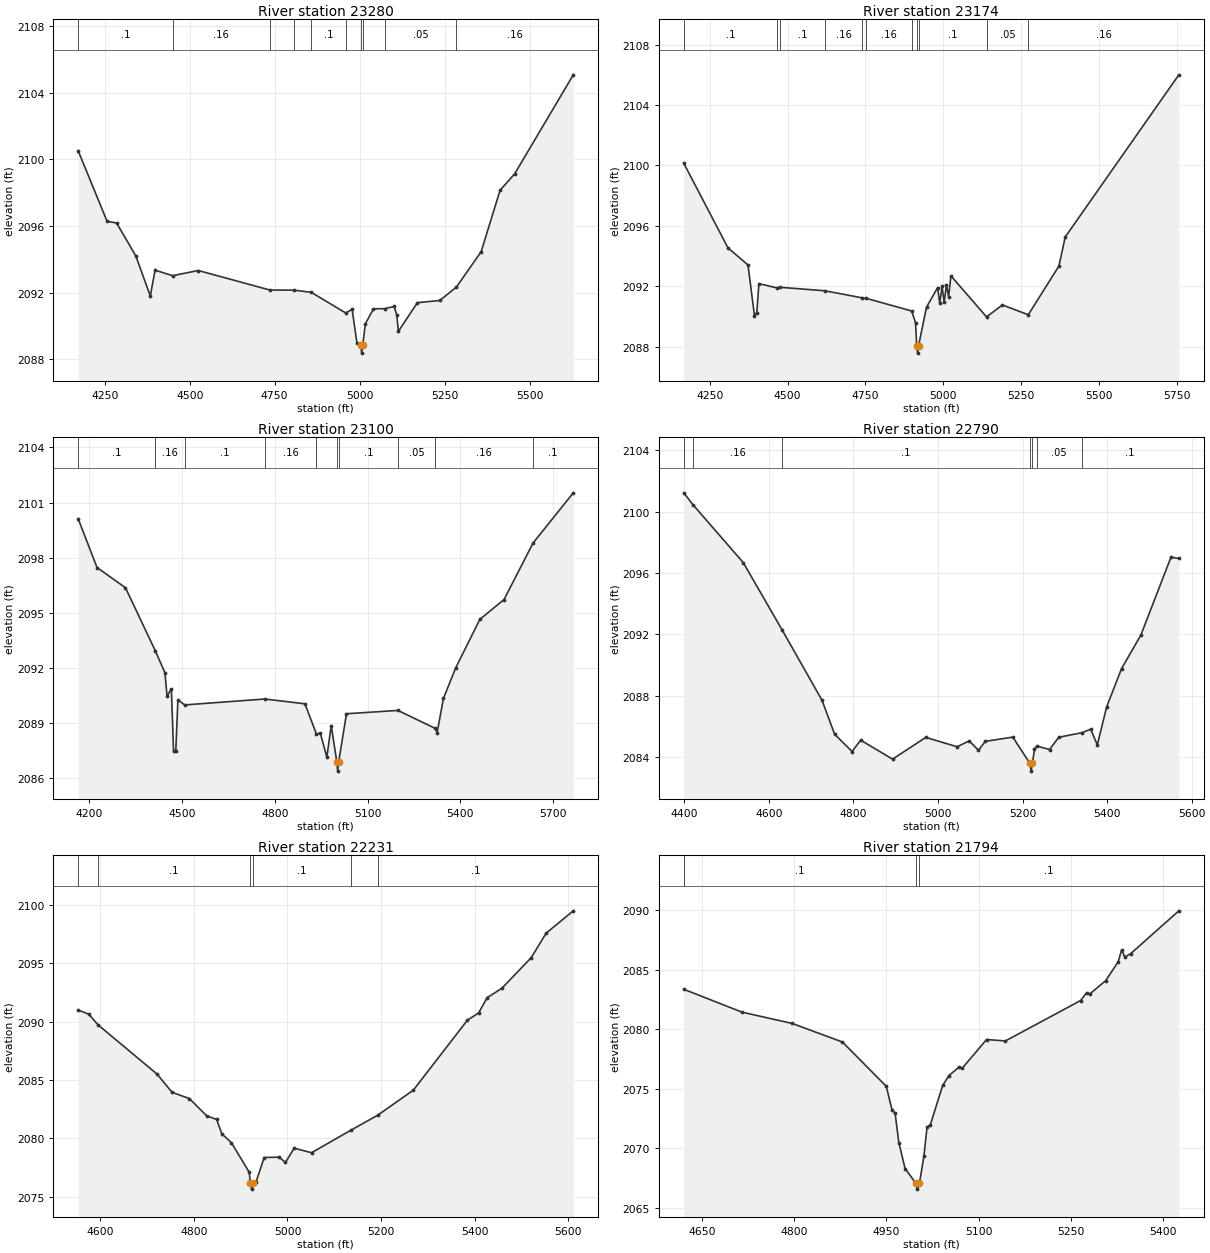
Type RM Length L Ch R = 1,23280,106,106,106
BEGIN DESCRIPTION:
STUCKENS BRANCH 51.0
END DESCRIPTION:
XS GIS Cut Line= 3
      2656618.50     10080953.76      2656018.47     10080353.73
      2655418.51     10080253.74
#Sta/Elev= 30
  4171.8 2100.52  4256.7 2096.29  4285.0 2096.18  4341.5 2094.20  4384.0 2091.80
  4398.1 2093.35  4449.7 2093.02  4525.4 2093.33  4735.6 2092.16  4807.4 2092.15
  4857.7 2092.02  4959.1 2090.78  4977.9 2091.00  4992.1 2088.97  5003.2 2088.87
  5006.0 2088.37  5009.2 2088.87  5016.8 2090.13  5040.6 2091.03  5074.2 2091.04
  5101.5 2091.17  5109.1 2090.67  5114.1 2089.68  5169.9 2091.40  5235.8 2091.53
  5284.9 2092.34  5357.5 2094.46  5413.2 2098.15  5456.3 2099.14  5628.6 2105.08
#Mann=10,-1,0
  4171.8     0.1       0  4449.7    0.16       0  4735.6     0.1       0
  4807.4    0.16       0  4857.7     0.1       0  4959.1    0.16       0
  5003.2    0.07       0  5009.2    0.16       0  5074.2    0.05       0
  5284.9    0.16       0
Bank Sta=5003.2,5009.2
Exp/Cntr=0.3,0.1

Type RM Length L Ch R = 1,23174,74,74,74
BEGIN DESCRIPTION:
Mapping XS 2fae2e90
END DESCRIPTION:
XS GIS Cut Line= 4
      2656656.01     10080897.18      2656064.85     10080251.33
      2655986.72     10080259.14      2655356.50     10080183.62
#Sta/Elev= 30
  4166.7 2100.15  4308.7 2094.54  4372.9 2093.41  4393.8 2090.04  4401.2 2090.26
  4408.0 2092.17  4465.6 2091.89  4475.7 2091.93  4619.2 2091.70  4739.5 2091.23
  4752.2 2091.20  4898.1 2090.36  4910.6 2089.59  4914.4 2088.07  4917.1 2087.57
  4920.4 2088.07  4945.8 2090.61  4981.5 2091.91  4988.3 2090.87  4995.7 2091.99
  5002.5 2090.94  5009.9 2092.10  5016.7 2091.31  5024.1 2092.69  5138.4 2089.97
  5189.5 2090.76  5272.4 2090.11  5370.8 2093.34  5390.9 2095.26  5755.5 2106.00
#Mann=11,-1,0
  4166.7     0.1       0  4465.6    0.16       0  4475.7     0.1       0
  4619.2    0.16       0  4739.5     0.1       0  4752.2    0.16       0
  4898.1     0.1       0  4914.4    0.07       0  4920.4     0.1       0
  5138.4    0.05       0  5272.4    0.16       0
Bank Sta=4914.4,4920.4
Exp/Cntr=0.3,0.1

Type RM Length L Ch R = 1,23100,310,310,310
BEGIN DESCRIPTION:
Mapping XS 10324afd
END DESCRIPTION:
XS GIS Cut Line= 3
      2656708.11     10080839.91      2656077.87     10080157.58
      2655412.37     10080069.19
#Sta/Elev= 30
  4164.7 2100.12  4225.6 2097.47  4317.5 2096.37  4413.8 2092.95  4445.1 2091.75
  4451.9 2090.48  4466.0 2090.87  4472.9 2087.52  4480.2 2087.50  4487.0 2090.27
  4509.0 2090.00  4767.9 2090.32  4897.6 2090.06  4934.6 2088.42  4947.5 2088.45
  4968.4 2087.16  4982.6 2088.88  5000.6 2086.90  5003.3 2086.40  5006.6 2086.90
  5031.9 2089.52  5198.1 2089.70  5317.8 2088.73  5325.0 2088.50  5345.2 2090.35
  5384.5 2092.00  5462.9 2094.65  5541.2 2095.73  5634.9 2098.80  5764.9 2101.53
#Mann=10,-1,0
  4164.7     0.1       0  4413.8    0.16       0  4509.0     0.1       0
  4767.9    0.16       0  4934.6     0.1       0  5000.6    0.07       0
  5006.6     0.1       0  5198.1    0.05       0  5317.8    0.16       0
  5634.9     0.1       0
Bank Sta=5000.6,5006.6
Exp/Cntr=0.3,0.1

Type RM Length L Ch R = 1,22790,559,559,559
BEGIN DESCRIPTION:
STUCKENS BRANCH 50.0
END DESCRIPTION:
XS GIS Cut Line= 3
      2656905.25     10080145.04      2656391.34     10080020.03
      2655829.95     10079708.15
#Sta/Elev= 30
  4398.6 2101.22  4420.6 2100.44  4539.4 2096.67  4631.1 2092.29  4725.6 2087.70
  4755.5 2085.48  4796.7 2084.35  4817.2 2085.09  4892.6 2083.85  4971.1 2085.27
  5045.2 2084.66  5074.0 2085.04  5095.8 2084.43  5111.8 2085.01  5177.0 2085.29
  5217.5 2083.57  5220.2 2083.07  5223.5 2083.57  5228.2 2084.51  5234.1 2084.70
  5263.9 2084.48  5285.7 2085.28  5339.6 2085.57  5361.2 2085.80  5376.9 2084.78
  5398.9 2087.25  5434.1 2089.75  5479.9 2091.94  5551.1 2097.02  5569.7 2096.94
#Mann=7,-1,0
  4398.6     0.1       0  4420.6    0.16       0  4631.1     0.1       0
  5217.5    0.07       0  5223.5     0.1       0  5234.1    0.05       0
  5339.6     0.1       0
Bank Sta=5217.5,5223.5
Exp/Cntr=0.3,0.1

Type RM Length L Ch R = 1,22231,437,437,437
BEGIN DESCRIPTION:
STUCKENS BRANCH 49.0
END DESCRIPTION:
XS GIS Cut Line= 2
      2656939.94     10079651.97      2655933.21     10079325.65
#Sta/Elev= 30
  4552.6 2091.00  4575.2 2090.64  4595.3 2089.72  4721.2 2085.51  4753.2 2083.95
  4790.4 2083.41  4827.6 2081.92  4848.5 2081.63  4859.6 2080.39  4880.0 2079.64
  4918.3 2077.09  4920.6 2076.15  4923.3 2075.65  4926.6 2076.15  4932.6 2076.25
  4950.3 2078.36  4982.3 2078.39  4995.7 2077.94  5014.3 2079.16  5051.5 2078.77
  5135.1 2080.69  5192.7 2081.98  5269.0 2084.13  5384.6 2090.13  5408.6 2090.75
  5426.7 2092.05  5458.2 2092.86  5521.3 2095.50  5552.8 2097.58  5610.9 2099.50
#Mann=6,-1,0
  4552.6    0.16       0  4595.3     0.1       0  4920.6    0.07       0
  4926.6     0.1       0  5135.1    0.05       0  5192.7     0.1       0
Bank Sta=4920.6,4926.6
Exp/Cntr=0.3,0.1

Type RM Length L Ch R = 1,21794,413,413,413
BEGIN DESCRIPTION:
STUCKENS BRANCH 48.0
END DESCRIPTION:
XS GIS Cut Line= 2
      2656981.66     10079193.65      2656191.74     10079041.21
#Sta/Elev= 30
  4620.8 2083.37  4715.7 2081.44  4797.2 2080.49  4878.7 2078.93  4950.0 2075.20
  4959.2 2073.22  4964.3 2072.94  4970.3 2070.47  4980.5 2068.28  4997.9 2067.05
  5000.6 2066.55  5003.9 2067.05  5011.1 2069.33  5016.2 2071.78  5021.3 2071.93
  5041.6 2075.28  5051.8 2076.11  5068.0 2076.81  5073.1 2076.71  5112.9 2079.14
  5143.5 2079.02  5265.7 2082.42  5275.4 2083.07  5280.5 2082.97  5306.4 2084.09
  5326.8 2085.68  5332.4 2086.69  5337.5 2086.08  5347.2 2086.37  5425.3 2089.97
#Mann=3,-1,0
  4620.8     0.1       0  4997.9    0.07       0  5003.9     0.1       0
Bank Sta=4997.9,5003.9
Exp/Cntr=0.3,0.1

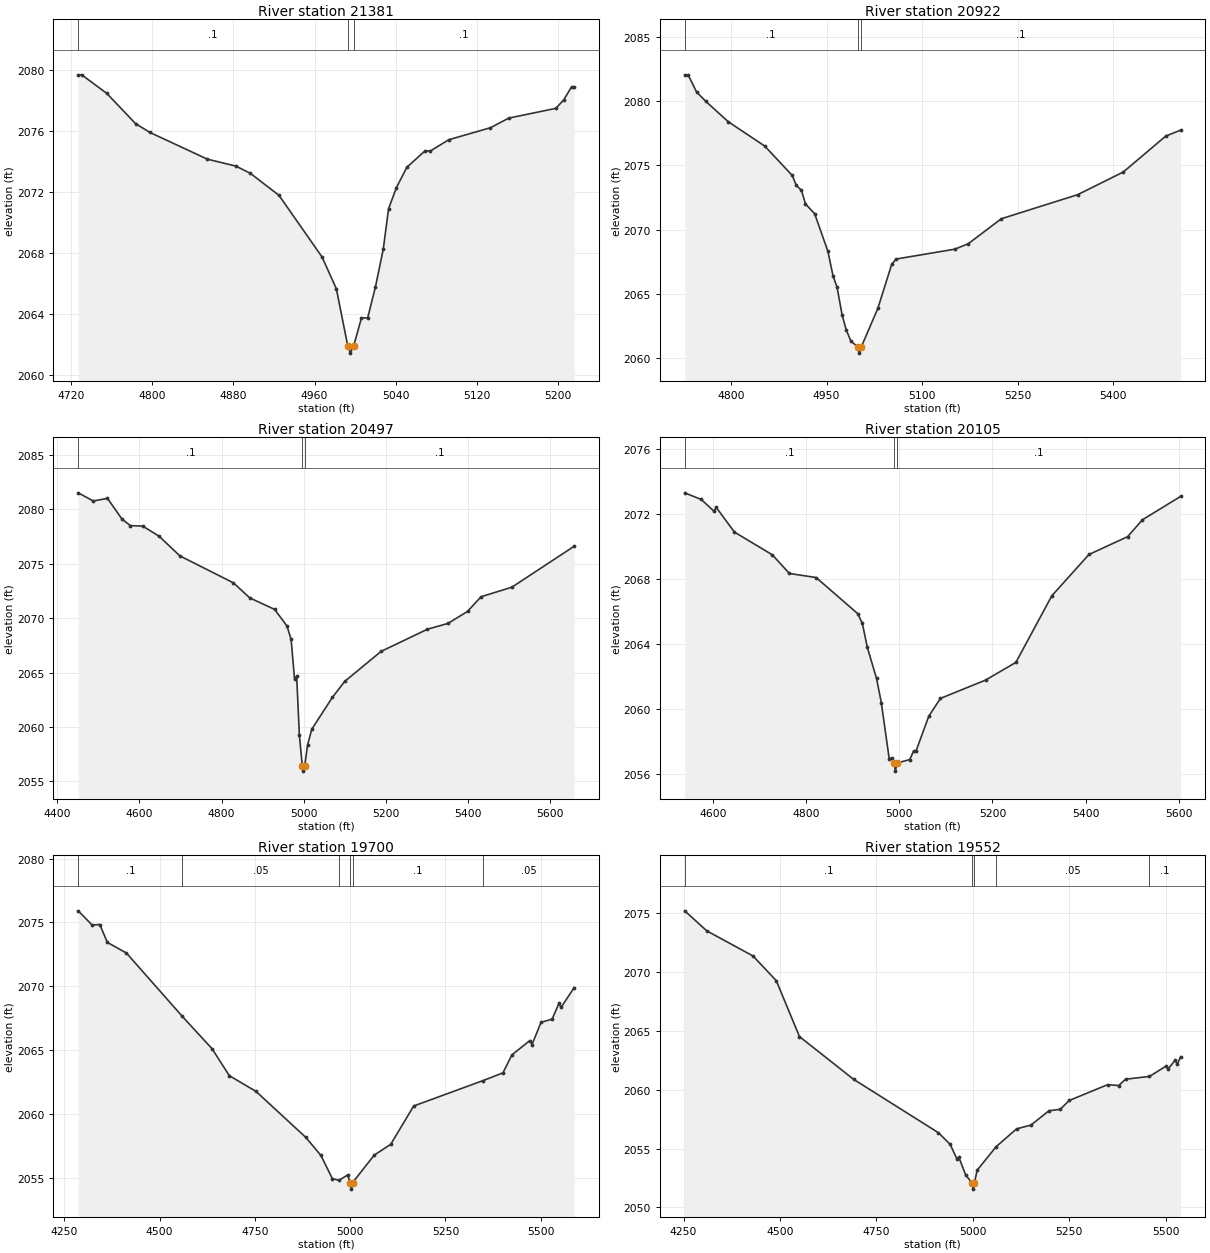
Type RM Length L Ch R = 1,21381,459,459,459
BEGIN DESCRIPTION:
STUCKENS BRANCH 47.0
END DESCRIPTION:
XS GIS Cut Line= 3
      2656968.44     10078953.71      2656768.47     10078753.73
      2656568.43     10078703.72
#Sta/Elev= 30
  4726.9 2079.71  4730.4 2079.71  4755.1 2078.49  4783.4 2076.51  4797.6 2075.93
  4854.1 2074.18  4882.4 2073.72  4896.6 2073.25  4924.9 2071.80  4967.3 2067.76
  4981.4 2065.68  4992.6 2061.95  4995.3 2061.45  4998.6 2061.95  5006.2 2063.76
  5012.3 2063.76  5020.0 2065.80  5027.7 2068.28  5032.9 2070.92  5040.6 2072.30
  5050.9 2073.64  5069.0 2074.73  5074.1 2074.71  5092.2 2075.45  5133.4 2076.24
  5151.4 2076.87  5197.8 2077.51  5205.6 2078.06  5213.3 2078.92  5215.9 2078.92
#Mann=3,-1,0
  4726.9     0.1       0  4992.6    0.07       0  4998.6     0.1       0
Bank Sta=4992.6,4998.6
Exp/Cntr=0.3,0.1

Type RM Length L Ch R = 1,20922,425,425,425
BEGIN DESCRIPTION:
STUCKENS BRANCH 46.0
END DESCRIPTION:
XS GIS Cut Line= 3
      2657321.90     10078617.26      2657002.45     10078360.31
      2656648.32     10078464.47
#Sta/Elev= 30
  4727.1 2082.05  4732.5 2082.05  4745.7 2080.72  4760.1 2079.99  4795.7 2078.39
  4852.9 2076.50  4896.1 2074.21  4902.5 2073.43  4910.5 2073.06  4916.9 2071.99
  4931.3 2071.23  4952.1 2068.30  4960.1 2066.40  4966.5 2065.50  4974.5 2063.33
  4980.9 2062.18  4988.2 2061.31  4998.7 2060.87  5001.5 2060.37  5004.7 2060.87
  5030.5 2063.85  5052.3 2067.28  5059.3 2067.70  5151.6 2068.47  5172.5 2068.89
  5224.6 2070.84  5344.3 2072.71  5416.2 2074.48  5482.9 2077.28  5506.2 2077.74
#Mann=3,-1,0
  4727.1     0.1       0  4998.7    0.07       0  5004.7     0.1       0
Bank Sta=4998.7,5004.7
Exp/Cntr=0.3,0.1

Type RM Length L Ch R = 1,20497,392,392,392
BEGIN DESCRIPTION:
STUCKENS BRANCH 45.0
END DESCRIPTION:
XS GIS Cut Line= 3
      2657795.05     10078084.15      2657354.96     10078050.30
      2656592.72     10078123.14
#Sta/Elev= 30
  4451.2 2081.52  4487.9 2080.77  4522.4 2081.01  4558.1 2079.09  4578.2 2078.51
  4608.2 2078.46  4647.8 2077.54  4698.5 2075.73  4828.9 2073.25  4869.0 2071.86
  4929.3 2070.81  4959.4 2069.28  4969.4 2068.05  4977.8 2064.40  4982.9 2064.67
  4989.5 2059.26  4996.6 2056.45  4999.3 2055.95  5002.6 2056.45  5009.6 2058.38
  5019.7 2059.80  5069.9 2062.73  5100.0 2064.20  5188.4 2066.95  5301.3 2068.99
  5351.2 2069.52  5399.0 2070.63  5431.5 2071.97  5506.8 2072.85  5658.3 2076.61
#Mann=3,-1,0
  4451.2     0.1       0  4996.6    0.07       0  5002.6     0.1       0
Bank Sta=4996.6,5002.6
Exp/Cntr=0.3,0.1

Type RM Length L Ch R = 1,20105,405,405,405
BEGIN DESCRIPTION:
STUCKENS BRANCH 44.0
END DESCRIPTION:
XS GIS Cut Line= 2
      2657693.53     10077586.76      2656646.67     10077784.67
#Sta/Elev= 30
  4538.9 2073.32  4574.6 2072.91  4601.7 2072.19  4606.8 2072.42  4645.8 2070.90
  4727.2 2069.50  4763.9 2068.35  4821.3 2068.10  4910.4 2065.88  4920.6 2065.28
  4931.1 2063.81  4951.1 2061.88  4961.3 2060.39  4978.4 2056.91  4983.5 2056.99
  4988.8 2056.67  4991.6 2056.17  4994.8 2056.67  5022.4 2056.88  5030.7 2057.41
  5035.8 2057.40  5063.1 2059.54  5088.2 2060.65  5185.2 2061.78  5250.4 2062.87
  5327.7 2066.98  5407.4 2069.52  5490.5 2070.62  5522.3 2071.66  5604.3 2073.10
#Mann=3,-1,0
  4538.9     0.1       0  4988.8    0.07       0  4994.8     0.1       0
Bank Sta=4988.8,4994.8
Exp/Cntr=0.3,0.1

Type RM Length L Ch R = 1,19700,148,148,148
BEGIN DESCRIPTION:
STUCKENS BRANCH 43.0
END DESCRIPTION:
XS GIS Cut Line= 3
      2657854.97     10077274.26      2657037.26     10077284.68
      2656592.75     10077094.91
#Sta/Elev= 30
  4286.5 2075.91  4323.0 2074.80  4343.0 2074.84  4363.0 2073.44  4413.0 2072.61
  4559.8 2067.65  4637.8 2065.12  4683.0 2063.02  4753.0 2061.79  4883.1 2058.21
  4923.1 2056.79  4953.1 2054.98  4970.5 2054.84  4993.1 2055.25  5000.1 2054.65
  5002.8 2054.15  5006.1 2054.65  5063.1 2056.81  5106.3 2057.65  5166.6 2060.65
  5348.9 2062.64  5400.8 2063.24  5424.4 2064.65  5471.6 2065.77  5477.0 2065.45
  5500.7 2067.19  5529.7 2067.44  5547.9 2068.68  5553.3 2068.36  5587.6 2069.91
#Mann=6,-1,0
  4286.5     0.1       0  4559.8    0.05       0  4970.5     0.1       0
  5000.1    0.07       0  5006.1     0.1       0  5348.9    0.05       0
Bank Sta=5000.1,5006.1
Exp/Cntr=0.3,0.1

Type RM Length L Ch R = 1,19552,276,276,276
BEGIN DESCRIPTION:
STUCKENS BRANCH 42.0
END DESCRIPTION:
XS GIS Cut Line= 3
      2657875.77     10077167.49      2657042.46     10077133.63
      2656628.37     10076953.93
#Sta/Elev= 30
  4253.0 2075.20  4310.3 2073.50  4430.4 2071.36  4490.5 2069.26  4550.5 2064.52
  4690.7 2060.89  4910.8 2056.35  4940.9 2055.37  4958.6 2054.13  4963.6 2054.27
  4980.9 2052.80  4997.9 2052.06  5000.7 2051.56  5003.9 2052.06  5010.9 2053.16
  5060.1 2055.16  5113.2 2056.68  5150.4 2057.00  5197.3 2058.22  5226.3 2058.34
  5249.7 2059.09  5349.0 2060.43  5377.9 2060.36  5395.9 2060.90  5457.5 2061.13
  5500.7 2062.01  5506.1 2061.77  5524.1 2062.50  5529.6 2062.17  5538.4 2062.80
#Mann=5,-1,0
  4253.0     0.1       0  4997.9    0.07       0  5003.9     0.1       0
  5060.1    0.05       0  5457.5     0.1       0
Bank Sta=4997.9,5003.9
Exp/Cntr=0.3,0.1

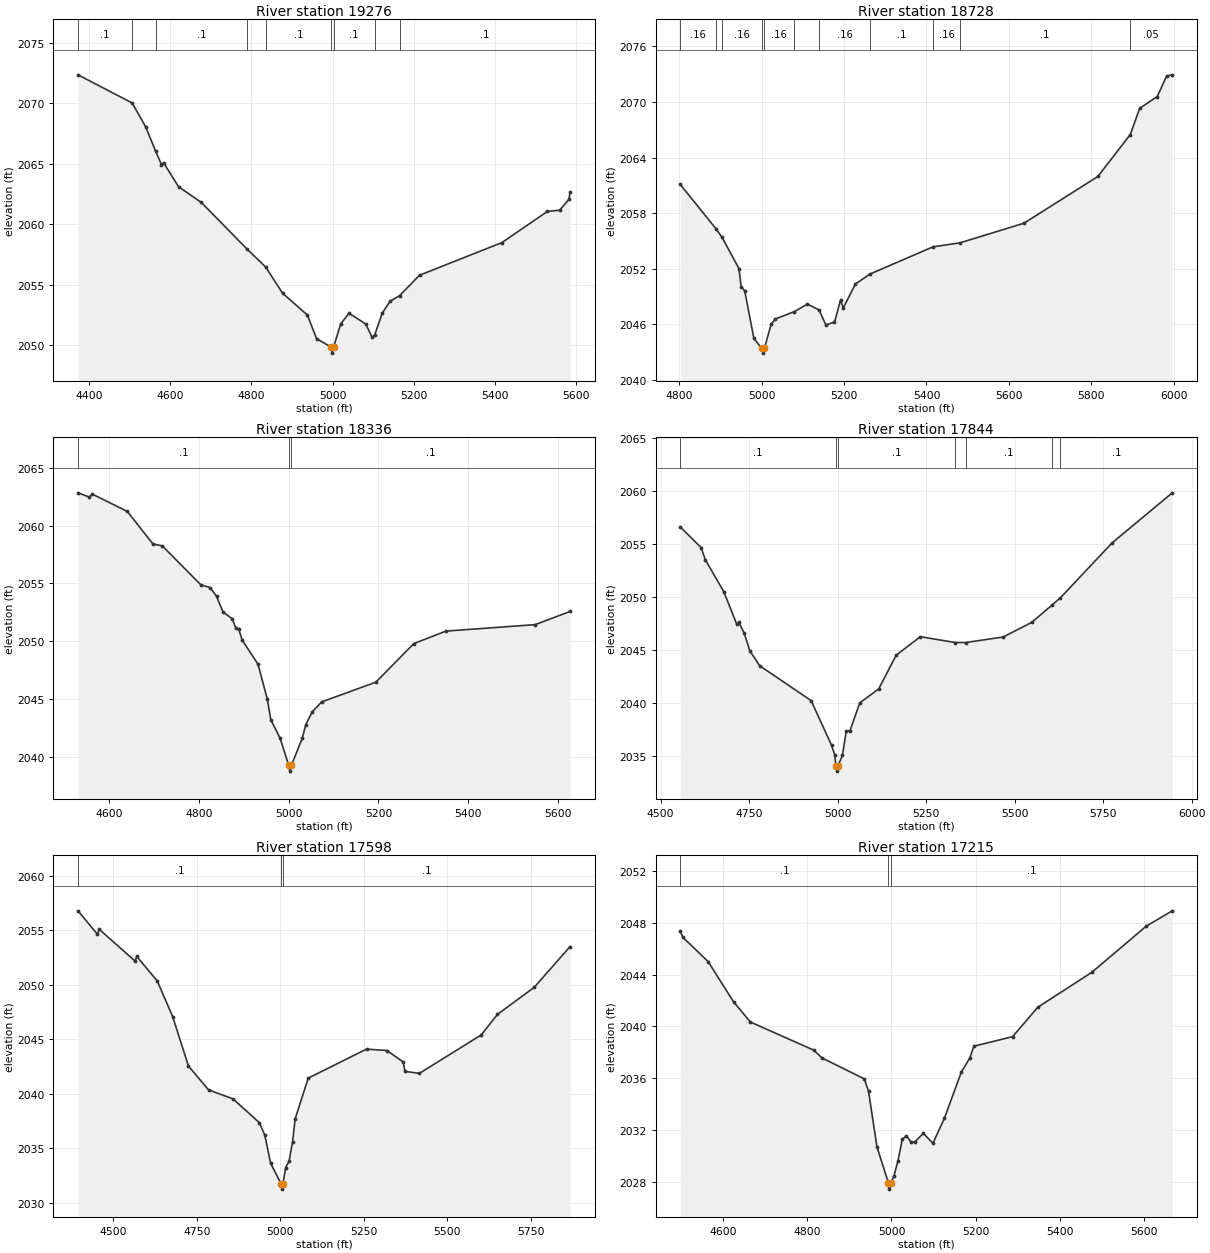
Type RM Length L Ch R = 1,19276,548,548,548
BEGIN DESCRIPTION:
Mapping XS 0978ffc6
END DESCRIPTION:
XS GIS Cut Line= 3
      2657800.27     10077003.42      2657037.26     10076836.76
      2656613.17     10076909.61
#Sta/Elev= 30
  4373.3 2072.35  4506.7 2070.02  4539.9 2068.05  4564.4 2066.03  4578.7 2064.93
  4583.9 2065.08  4620.8 2063.10  4676.8 2061.80  4789.2 2057.95  4835.5 2056.45
  4876.7 2054.30  4938.1 2052.48  4960.7 2050.53  4996.4 2049.84  4999.2 2049.34
  5002.4 2049.84  5020.0 2051.76  5040.5 2052.64  5081.4 2051.75  5097.5 2050.64
  5103.5 2050.84  5122.4 2052.65  5141.4 2053.63  5164.8 2054.09  5214.0 2055.78
  5416.9 2058.48  5528.5 2061.05  5558.9 2061.16  5581.9 2062.05  5584.6 2062.65
#Mann=9,-1,0
  4373.3     0.1       0  4506.7    0.16       0  4564.4     0.1       0
  4789.2    0.16       0  4835.5     0.1       0  4996.4    0.07       0
  5002.4     0.1       0  5103.5    0.16       0  5164.8     0.1       0
Bank Sta=4996.4,5002.4
Exp/Cntr=0.3,0.1

Type RM Length L Ch R = 1,18728,392,392,392
BEGIN DESCRIPTION:
STUCKENS BRANCH 41.0
END DESCRIPTION:
XS GIS Cut Line= 3
      2657418.46     10076253.74      2657218.47     10076353.73
      2656418.48     10076903.72
#Sta/Elev= 30
  4802.3 2061.12  4889.3 2056.32  4903.9 2055.40  4944.8 2052.04  4950.4 2050.04
  4958.8 2049.65  4981.2 2044.49  5000.5 2043.41  5003.3 2042.91  5006.5 2043.41
  5023.1 2046.03  5033.3 2046.60  5078.9 2047.38  5111.1 2048.20  5139.3 2047.57
  5155.8 2045.96  5176.8 2046.25  5191.7 2048.68  5197.7 2047.75  5227.5 2050.36
  5262.8 2051.44  5415.9 2054.38  5481.6 2054.81  5636.8 2056.93  5816.1 2061.97
  5894.9 2066.50  5917.6 2069.32  5960.3 2070.60  5983.2 2072.81  5996.7 2072.94
#Mann=11,-1,0
  4802.3    0.16       0  4889.3     0.1       0  4903.9    0.16       0
  5000.5    0.07       0  5006.5    0.16       0  5078.9     0.1       0
  5139.3    0.16       0  5262.8     0.1       0  5415.9    0.16       0
  5481.6     0.1       0  5894.9    0.05       0
Bank Sta=5000.5,5006.5
Exp/Cntr=0.3,0.1

Type RM Length L Ch R = 1,18336,492,492,492
BEGIN DESCRIPTION:
STUCKENS BRANCH 40.0
END DESCRIPTION:
XS GIS Cut Line= 2
      2657479.98     10075670.08      2656642.41     10076377.59
#Sta/Elev= 30
  4530.7 2062.84  4556.0 2062.47  4562.5 2062.73  4640.5 2061.23  4697.7 2058.41
  4718.5 2058.25  4804.3 2054.88  4825.1 2054.64  4839.4 2053.88  4853.7 2052.53
  4874.6 2051.93  4882.3 2051.13  4888.8 2051.03  4896.6 2050.08  4931.7 2048.01
  4952.6 2044.97  4960.3 2043.20  4981.1 2041.59  5000.2 2039.25  5002.9 2038.75
  5006.2 2039.25  5030.6 2041.62  5038.3 2042.78  5052.6 2043.88  5073.5 2044.74
  5194.3 2046.45  5278.9 2049.79  5350.4 2050.87  5549.3 2051.43  5627.1 2052.57
#Mann=3,-1,0
  4530.7     0.1       0  5000.2    0.07       0  5006.2     0.1       0
Bank Sta=5000.2,5006.2
Exp/Cntr=0.3,0.1

Type RM Length L Ch R = 1,17844,246,246,246
BEGIN DESCRIPTION:
STUCKENS BRANCH 39.0
END DESCRIPTION:
XS GIS Cut Line= 3
      2657218.49     10075353.72      2656818.47     10075603.73
      2656368.47     10076403.73
#Sta/Elev= 30
  4555.6 2056.59  4614.6 2054.64  4627.0 2053.46  4678.9 2050.47  4715.4 2047.40
  4721.3 2047.60  4736.6 2046.55  4752.0 2044.93  4779.7 2043.51  4925.3 2040.22
  4983.1 2036.00  4991.9 2035.11  4995.4 2034.07  4998.2 2033.57  5001.4 2034.07
  5013.8 2035.07  5024.4 2037.31  5035.3 2037.39  5062.7 2040.00  5116.2 2041.32
  5165.3 2044.49  5233.8 2046.24  5332.7 2045.69  5361.6 2045.69  5467.5 2046.21
  5548.4 2047.59  5605.6 2049.22  5629.5 2049.91  5775.3 2055.08  5945.2 2059.80
#Mann=7,-1,0
  4555.6     0.1       0  4995.4    0.07       0  5001.4     0.1       0
  5332.7    0.16       0  5361.6     0.1       0  5605.6    0.16       0
  5629.5     0.1       0
Bank Sta=4995.4,5001.4
Exp/Cntr=0.3,0.1

Type RM Length L Ch R = 1,17598,383,383,383
BEGIN DESCRIPTION:
STUCKENS BRANCH 38.0
END DESCRIPTION:
XS GIS Cut Line= 4
      2657276.64     10075232.24      2656612.59     10075418.86
      2656560.51     10075570.77      2656425.96     10076178.39
#Sta/Elev= 30
  4394.4 2056.78  4452.5 2054.63  4457.7 2055.09  4565.1 2052.17  4570.3 2052.59
  4631.4 2050.35  4677.6 2047.08  4724.9 2042.54  4785.0 2040.35  4858.3 2039.52
  4936.8 2037.35  4953.4 2036.20  4970.9 2033.61  5002.0 2031.74  5004.7 2031.24
  5008.0 2031.74  5015.7 2033.21  5026.1 2033.82  5036.5 2035.57  5044.2 2037.68
  5083.5 2041.43  5258.0 2044.09  5319.0 2043.96  5367.7 2042.91  5372.8 2042.04
  5416.4 2041.87  5601.1 2045.39  5649.9 2047.28  5759.9 2049.76  5867.1 2053.50
#Mann=3,-1,0
  4394.4     0.1       0  5002.0    0.07       0  5008.0     0.1       0
Bank Sta=5002,5008
Exp/Cntr=0.3,0.1

Type RM Length L Ch R = 1,17215,180,180,180
BEGIN DESCRIPTION:
STUCKENS BRANCH 37.0
END DESCRIPTION:
XS GIS Cut Line= 3
      2657064.91     10075020.03      2656342.73     10075054.75
      2655974.63     10075304.78
#Sta/Elev= 30
  4498.5 2047.35  4505.0 2046.88  4565.0 2045.00  4625.1 2041.90  4665.1 2040.34
  4815.3 2038.17  4835.3 2037.56  4935.4 2035.95  4945.5 2035.00  4965.5 2030.70
  4992.5 2027.93  4995.3 2027.43  4998.5 2027.93  5005.5 2028.41  5015.5 2029.62
  5025.6 2031.27  5035.6 2031.56  5045.6 2031.09  5055.6 2031.09  5075.6 2031.74
  5098.4 2030.97  5125.7 2032.91  5165.7 2036.46  5185.7 2037.55  5195.7 2038.47
  5287.6 2039.21  5347.3 2041.48  5476.1 2044.19  5604.9 2047.75  5666.5 2048.93
#Mann=3,-1,0
  4498.5     0.1       0  4992.5    0.07       0  4998.5     0.1       0
Bank Sta=4992.5,4998.5
Exp/Cntr=0.3,0.1

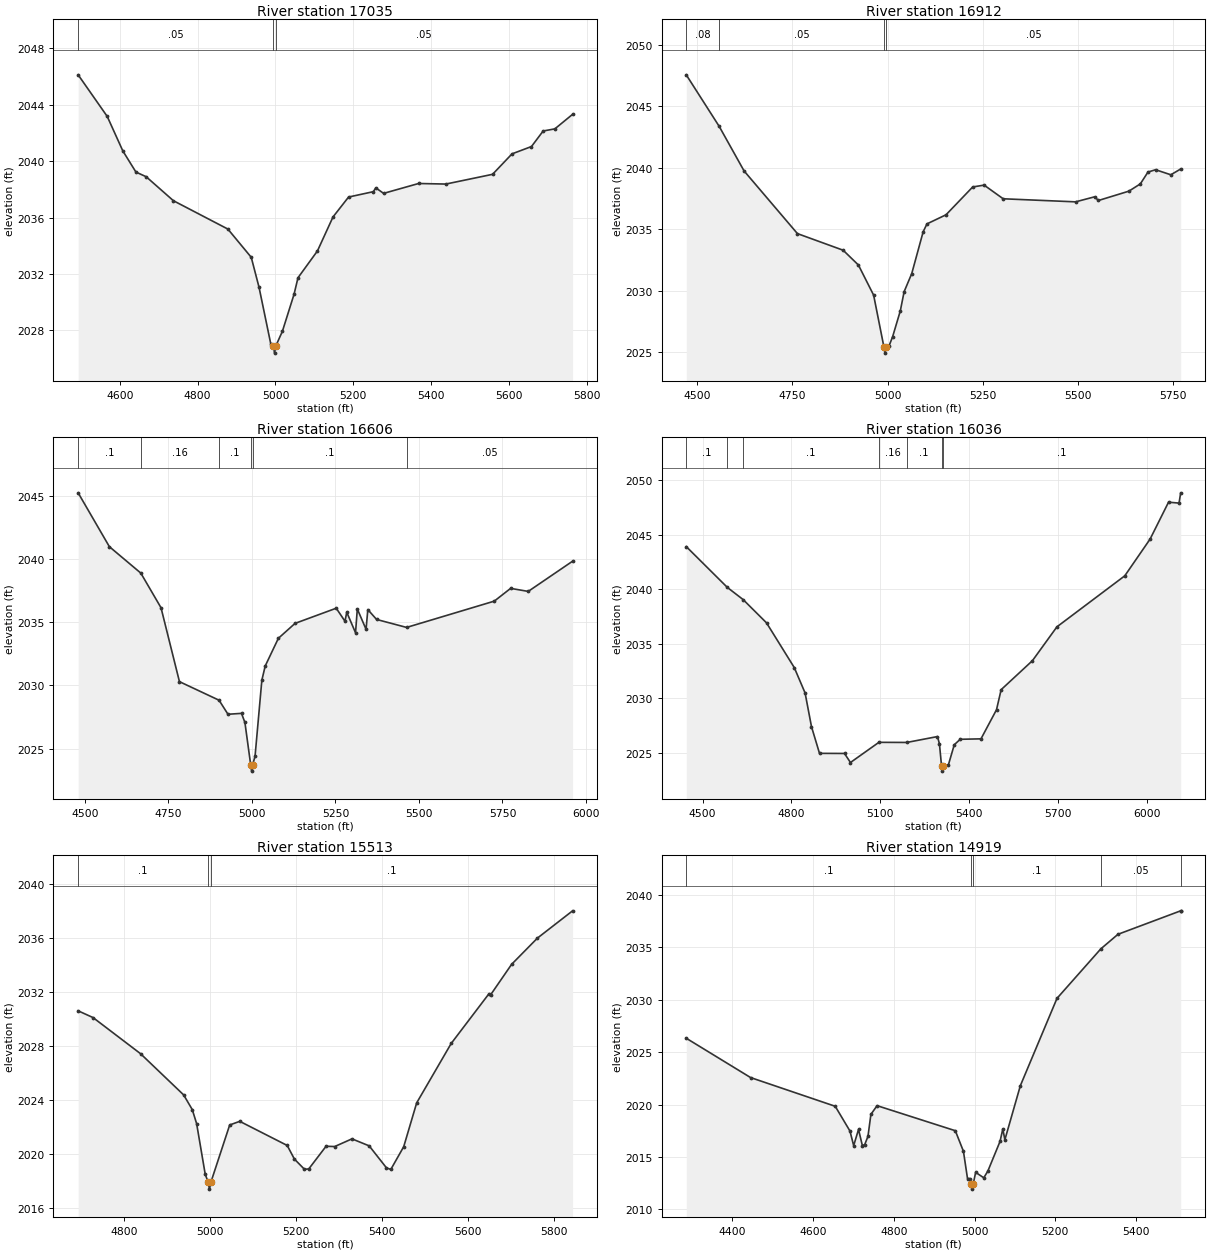
Type RM Length L Ch R = 1,17035,123,123,123
BEGIN DESCRIPTION:
Mapping XS bdbf6ecf
END DESCRIPTION:
XS GIS Cut Line= 2
      2657023.25     10074881.14      2655752.92     10074860.32
#Sta/Elev= 30
  4492.9 2046.11  4567.7 2043.16  4607.7 2040.72  4641.4 2039.22  4667.7 2038.89
  4737.7 2037.19  4877.7 2035.18  4937.7 2033.18  4957.7 2031.06  4987.7 2027.07
  4994.7 2026.89  4997.5 2026.39  5000.7 2026.89  5017.8 2027.94  5047.8 2030.57
  5057.8 2031.73  5107.8 2033.63  5147.8 2036.04  5187.8 2037.45  5251.4 2037.83
  5257.8 2038.10  5277.8 2037.71  5367.8 2038.41  5437.8 2038.37  5557.8 2039.06
  5607.8 2040.51  5657.8 2041.03  5687.8 2042.13  5717.8 2042.28  5763.4 2043.31
#Mann=3,-1,0
  4492.9    0.05       0  4994.7    0.04       0  5000.7    0.05       0
Bank Sta=4994.7,5000.7
Exp/Cntr=0.3,0.1

Type RM Length L Ch R = 1,16912,306,306,306
BEGIN DESCRIPTION:
Mapping XS 202d1333
END DESCRIPTION:
XS GIS Cut Line= 2
      2657030.21     10074756.14      2655732.58     10074742.27
#Sta/Elev= 30
  4471.6 2047.55  4558.1 2043.36  4623.4 2039.74  4763.4 2034.65  4883.4 2033.30
  4923.4 2032.10  4963.4 2029.65  4990.4 2025.44  4993.1 2024.94  4996.4 2025.44
  5003.4 2025.49  5013.4 2026.29  5033.4 2028.37  5043.4 2029.93  5063.4 2031.40
  5093.4 2034.80  5103.4 2035.44  5153.4 2036.18  5223.4 2038.44  5253.4 2038.59
  5303.4 2037.48  5493.4 2037.23  5543.4 2037.64  5553.4 2037.34  5633.4 2038.10
  5663.4 2038.69  5683.4 2039.65  5703.4 2039.84  5743.4 2039.43  5769.3 2039.90
#Mann=4,-1,0
  4471.6    0.08       0  4558.1    0.05       0  4990.4    0.04       0
  4996.4    0.05       0
Bank Sta=4990.4,4996.4
Exp/Cntr=0.3,0.1

Type RM Length L Ch R = 1,16606,570,570,570
BEGIN DESCRIPTION:
STUCKENS BRANCH 36.0
END DESCRIPTION:
XS GIS Cut Line= 3
      2657060.67     10074539.88      2656417.46     10074430.51
      2655632.57     10074693.74
#Sta/Elev= 30
  4479.6 2045.23  4573.1 2040.97  4667.2 2038.88  4727.7 2036.14  4782.9 2030.29
  4901.5 2028.82  4928.2 2027.71  4968.7 2027.78  4978.9 2027.06  4996.2 2023.71
  4998.9 2023.21  5002.2 2023.71  5009.3 2024.40  5029.6 2030.40  5039.7 2031.53
  5079.1 2033.72  5129.0 2034.90  5252.3 2036.10  5278.5 2035.07  5283.8 2035.78
  5310.1 2034.16  5315.4 2036.04  5341.6 2034.43  5346.9 2035.99  5373.2 2035.21
  5463.0 2034.58  5725.5 2036.66  5774.4 2037.67  5827.1 2037.43  5959.9 2039.82
#Mann=6,-1,0
  4479.6     0.1       0  4667.2    0.16       0  4901.5     0.1       0
  4996.2    0.07       0  5002.2     0.1       0  5463.0    0.05       0
Bank Sta=4996.2,5002.2
Exp/Cntr=0.3,0.1

Type RM Length L Ch R = 1,16036,523,523,523
BEGIN DESCRIPTION:
STUCKENS BRANCH 35.0
END DESCRIPTION:
XS GIS Cut Line= 4
      2657217.77     10074242.28      2656828.84     10073971.42
      2656259.39     10073936.70      2655683.28     10073693.76
#Sta/Elev= 30
  4445.1 2043.90  4584.1 2040.15  4637.2 2039.04  4716.1 2036.91  4809.8 2032.81
  4846.4 2030.48  4868.0 2027.39  4895.1 2024.94  4979.5 2024.93  4999.6 2024.10
  5095.6 2025.95  5189.9 2025.94  5293.5 2026.48  5300.1 2025.81  5307.1 2023.81
  5309.9 2023.31  5313.1 2023.81  5330.2 2023.87  5350.2 2025.73  5370.3 2026.23
  5440.4 2026.27  5492.8 2028.94  5508.5 2030.78  5614.2 2033.44  5696.8 2036.54
  5926.0 2041.22  6011.5 2044.59  6073.7 2047.97  6109.2 2047.89  6114.8 2048.83
#Mann=7,-1,0
  4445.1     0.1       0  4584.1    0.16       0  4637.2     0.1       0
  5095.6    0.16       0  5189.9     0.1       0  5307.1    0.07       0
  5313.1     0.1       0
Bank Sta=5307.1,5313.1
Exp/Cntr=0.3,0.1

Type RM Length L Ch R = 1,15513,594,594,594
BEGIN DESCRIPTION:
STUCKENS BRANCH 34.0
END DESCRIPTION:
XS GIS Cut Line= 2
      2657183.01     10073492.26      2656037.15     10073415.87
#Sta/Elev= 30
  4694.2 2030.60  4728.8 2030.10  4839.1 2027.42  4939.3 2024.36  4959.3 2023.27
  4969.4 2022.23  4989.4 2018.47  4996.4 2017.87  4999.2 2017.37  5002.4 2017.87
  5046.2 2022.13  5069.6 2022.40  5179.8 2020.61  5196.5 2019.60  5219.9 2018.84
  5229.9 2018.87  5270.0 2020.55  5290.1 2020.53  5330.2 2021.10  5370.2 2020.58
  5410.3 2018.95  5420.4 2018.83  5450.4 2020.52  5480.5 2023.77  5560.7 2028.18
  5647.5 2031.83  5652.5 2031.80  5701.0 2034.05  5761.1 2036.00  5842.6 2038.02
#Mann=3,-1,0
  4694.2     0.1       0  4996.4    0.07       0  5002.4     0.1       0
Bank Sta=4996.4,5002.4
Exp/Cntr=0.3,0.1

Type RM Length L Ch R = 1,14919,374,374,374
BEGIN DESCRIPTION:
STUCKENS BRANCH 33.0
END DESCRIPTION:
XS GIS Cut Line= 3
      2657189.97     10073332.55      2656780.23     10073075.59
      2656044.10     10072985.31
#Sta/Elev= 30
  4285.5 2026.33  4444.9 2022.58  4654.7 2019.84  4691.2 2017.48  4700.4 2016.09
  4712.4 2017.63  4721.9 2016.10  4727.8 2016.19  4735.8 2016.97  4743.1 2019.07
  4758.4 2019.90  4952.3 2017.51  4972.4 2015.55  4982.5 2012.95  4988.7 2012.94
  4990.7 2012.44  4993.4 2011.94  4996.7 2012.44  5002.7 2013.54  5022.8 2013.02
  5032.9 2013.66  5063.1 2016.49  5070.0 2017.68  5075.1 2016.65  5113.5 2021.81
  5204.2 2030.13  5312.8 2034.85  5355.3 2036.24  5510.7 2038.48  5510.8 2038.48
#Mann=5,-1,0
  4285.5     0.1       0  4990.7    0.07       0  4996.7     0.1       0
  5312.8    0.05       0  5510.7     0.1       0
Bank Sta=4990.7,4996.7
Exp/Cntr=0.3,0.1

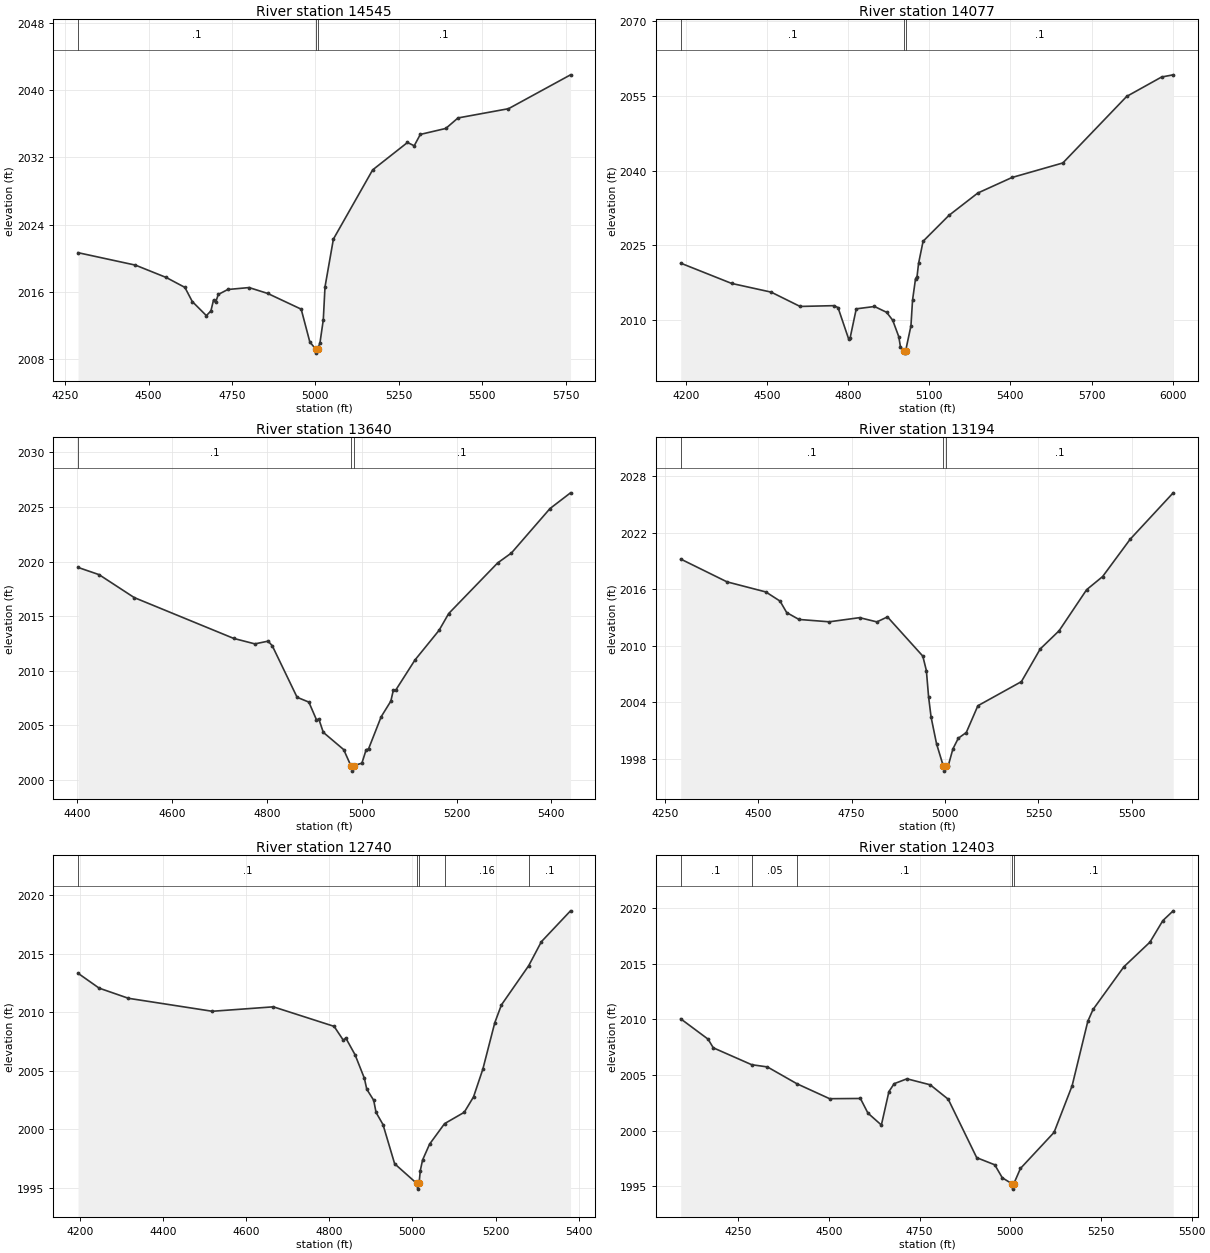
Type RM Length L Ch R = 1,14545,468,468,468
BEGIN DESCRIPTION:
STUCKENS BRANCH 32.0
END DESCRIPTION:
XS GIS Cut Line= 3
      2657102.39     10073091.99      2656649.24     10072709.16
      2655774.28     10072586.76
#Sta/Elev= 30
  4288.3 2020.67  4460.4 2019.19  4552.7 2017.72  4608.7 2016.54  4630.8 2014.86
  4673.1 2013.18  4686.7 2013.74  4694.5 2015.03  4701.0 2014.77  4708.8 2015.70
  4737.4 2016.29  4801.1 2016.52  4857.0 2015.82  4957.4 2013.95  4983.3 2010.05
  5000.5 2009.22  5003.2 2008.72  5006.5 2009.22  5013.6 2009.91  5023.7 2012.68
  5028.8 2016.59  5054.0 2022.29  5171.7 2030.52  5276.1 2033.78  5296.3 2033.39
  5314.6 2034.74  5391.0 2035.45  5427.6 2036.70  5579.0 2037.80  5765.0 2041.83
#Mann=3,-1,0
  4288.3     0.1       0  5000.5    0.07       0  5006.5     0.1       0
Bank Sta=5000.5,5006.5
Exp/Cntr=0.3,0.1

Type RM Length L Ch R = 1,14077,437,437,437
BEGIN DESCRIPTION:
STUCKENS BRANCH 31.0
END DESCRIPTION:
XS GIS Cut Line= 2
      2657219.53     10073102.34      2656414.85     10071469.56
#Sta/Elev= 30
  4181.4 2021.43  4369.4 2017.37  4515.8 2015.62  4622.6 2012.75  4748.4 2012.91
  4762.9 2012.52  4802.2 2006.22  4807.8 2006.49  4830.3 2012.27  4897.7 2012.74
  4942.6 2011.57  4965.0 2009.98  4987.5 2006.68  4993.7 2004.62  5006.9 2003.89
  5009.7 2003.39  5012.9 2003.89  5032.4 2008.85  5038.3 2014.00  5049.3 2018.29
  5054.9 2018.72  5060.6 2021.38  5077.3 2025.82  5172.7 2031.00  5279.5 2035.49
  5406.2 2038.61  5593.9 2041.52  5829.8 2054.86  5958.8 2058.75  6001.7 2059.19
#Mann=3,-1,0
  4181.4     0.1       0  5006.9    0.07       0  5012.9     0.1       0
Bank Sta=5006.9,5012.9
Exp/Cntr=0.3,0.1

Type RM Length L Ch R = 1,13640,446,446,446
BEGIN DESCRIPTION:
STUCKENS BRANCH 30.0
END DESCRIPTION:
XS GIS Cut Line= 3
      2657522.84     10072959.50      2657308.95     10072536.27
      2657204.30     10071981.16
#Sta/Elev= 30
  4401.3 2019.47  4445.6 2018.81  4519.8 2016.71  4729.8 2012.97  4774.4 2012.47
  4802.3 2012.72  4811.1 2012.30  4863.5 2007.58  4888.3 2007.14  4904.3 2005.53
  4909.4 2005.58  4918.8 2004.37  4961.8 2002.79  4976.9 2001.32  4979.6 2000.82
  4982.9 2001.32  5000.2 2001.55  5009.2 2002.78  5014.3 2002.86  5040.9 2005.80
  5061.3 2007.23  5066.7 2008.26  5071.8 2008.25  5112.1 2010.99  5163.0 2013.71
  5183.4 2015.25  5286.6 2019.88  5315.7 2020.79  5397.1 2024.86  5440.4 2026.30
#Mann=3,-1,0
  4401.3     0.1       0  4976.9    0.07       0  4982.9     0.1       0
Bank Sta=4976.9,4982.9
Exp/Cntr=0.3,0.1

Type RM Length L Ch R = 1,13194,454,454,454
BEGIN DESCRIPTION:
STUCKENS BRANCH 29.0
END DESCRIPTION:
XS GIS Cut Line= 3
      2657900.51     10073045.94      2657814.05     10072527.17
      2657404.53     10071849.18
#Sta/Elev= 30
  4292.7 2019.21  4416.6 2016.79  4520.5 2015.72  4558.5 2014.75  4576.3 2013.53
  4609.2 2012.80  4690.3 2012.55  4771.4 2012.99  4817.8 2012.54  4846.0 2013.07
  4940.6 2008.91  4950.2 2007.37  4956.1 2004.58  4962.8 2002.43  4977.4 1999.60
  4995.8 1997.20  4998.5 1996.70  5001.8 1997.20  5008.4 1997.23  5021.2 1999.06
  5035.6 2000.19  5057.0 2000.80  5088.0 2003.64  5204.5 2006.20  5254.9 2009.67
  5305.4 2011.60  5379.1 2015.96  5421.8 2017.35  5495.5 2021.31  5610.7 2026.24
#Mann=3,-1,0
  4292.7     0.1       0  4995.8    0.07       0  5001.8     0.1       0
Bank Sta=4995.8,5001.8
Exp/Cntr=0.3,0.1

Type RM Length L Ch R = 1,12740,337,337,337
BEGIN DESCRIPTION:
STUCKENS BRANCH 28.0
END DESCRIPTION:
XS GIS Cut Line= 3
      2658173.53     10072913.99      2658237.24     10072417.96
      2657932.90     10071804.73
#Sta/Elev= 30
  4195.6 2013.34  4246.3 2012.07  4316.8 2011.20  4518.5 2010.09  4665.4 2010.47
  4811.6 2008.80  4834.0 2007.60  4839.6 2007.81  4862.0 2006.37  4884.4 2004.36
  4890.2 2003.42  4906.8 2002.48  4912.5 2001.44  4929.2 2000.40  4957.2 1997.05
  5010.0 1995.38  5012.8 1994.88  5016.0 1995.38  5018.9 1996.46  5024.4 1997.37
  5041.3 1998.73  5077.3 2000.48  5124.6 2001.45  5147.0 2002.77  5169.3 2005.13
  5198.1 2009.11  5214.0 2010.63  5279.7 2013.99  5310.2 2016.04  5380.3 2018.68
#Mann=5,-1,0
  4195.6     0.1       0  5010.0    0.07       0  5016.0     0.1       0
  5077.3    0.16       0  5279.7     0.1       0
Bank Sta=5010,5016
Exp/Cntr=0.3,0.1

Type RM Length L Ch R = 1,12403,423,423,423
BEGIN DESCRIPTION:
STUCKENS BRANCH 27.0
END DESCRIPTION:
XS GIS Cut Line= 2
      2658969.88     10072718.30      2658128.03     10071653.49
#Sta/Elev= 30
  4091.7 2010.06  4167.1 2008.23  4181.5 2007.45  4287.3 2005.93  4330.6 2005.73
  4412.3 2004.21  4502.1 2002.87  4587.0 2002.89  4607.8 2001.57  4644.8 2000.50
  4665.6 2003.51  4680.0 2004.22  4715.3 2004.66  4779.4 2004.12  4829.1 2002.82
  4907.6 1997.56  4957.3 1996.92  4978.1 1995.75  5004.0 1995.23  5006.7 1994.73
  5010.0 1995.23  5028.1 1996.59  5120.8 1999.84  5170.5 2004.03  5213.8 2009.84
  5228.2 2010.90  5313.1 2014.74  5385.0 2016.96  5420.6 2018.90  5449.1 2019.78
#Mann=5,-1,0
  4091.7     0.1       0  4287.3    0.05       0  4412.3     0.1       0
  5004.0    0.07       0  5010.0     0.1       0
Bank Sta=5004,5010
Exp/Cntr=0.3,0.1