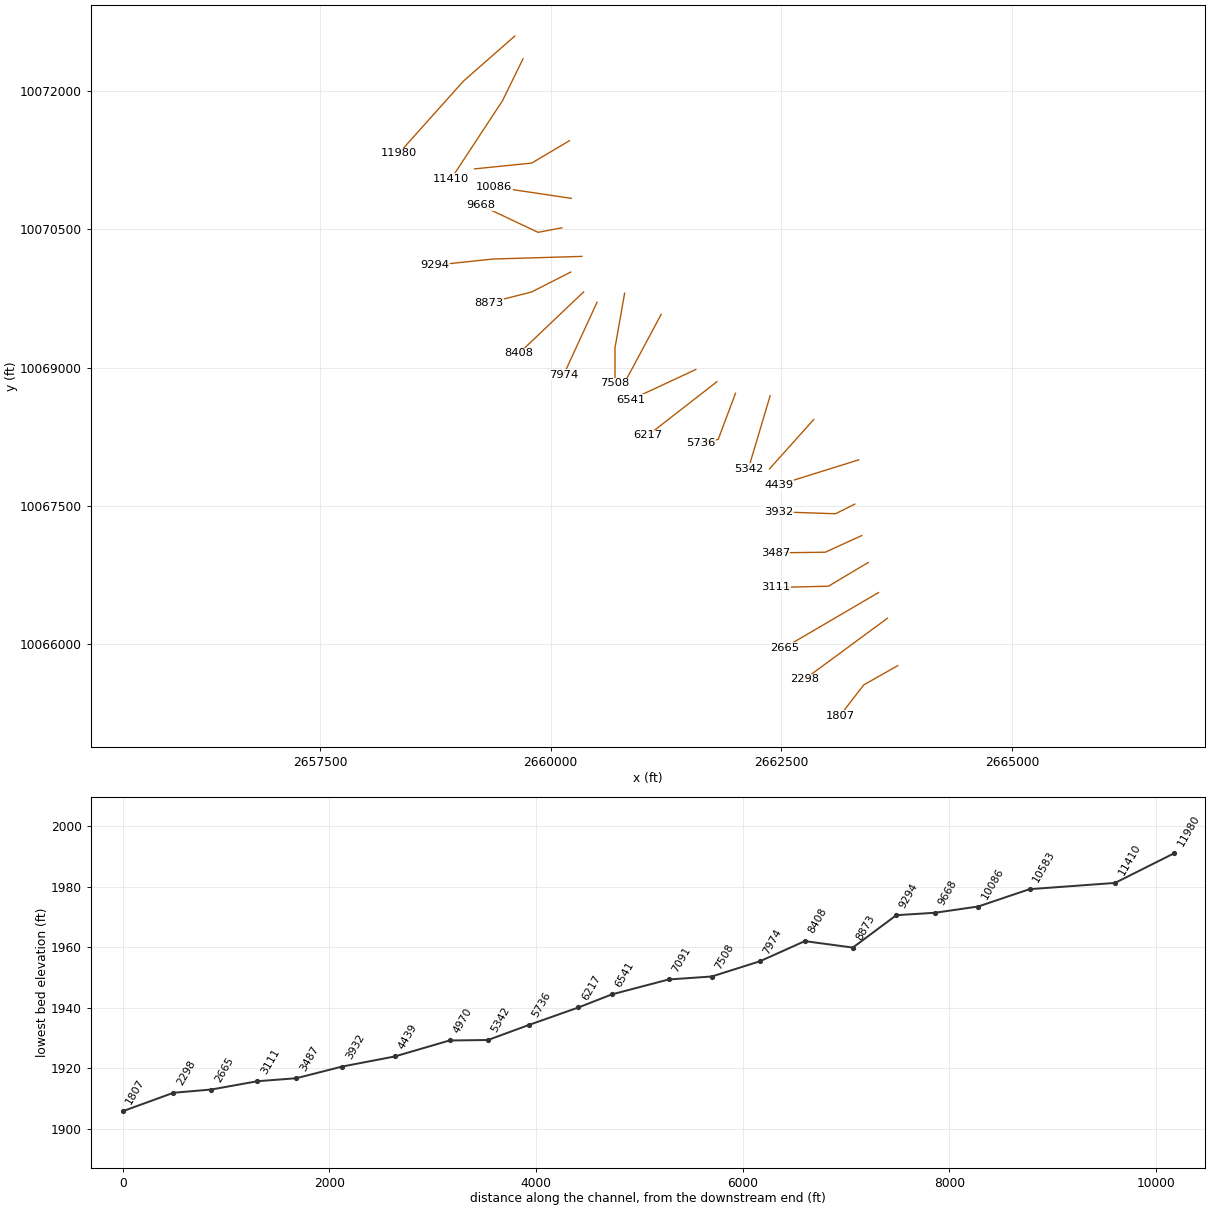
HEC-RAS study STUCKENS BRANCH.prj: STUCKENS BRANCH Base Level Engineering

--- STUCKENS BRANCH.g01 (geometry) --- (continued)

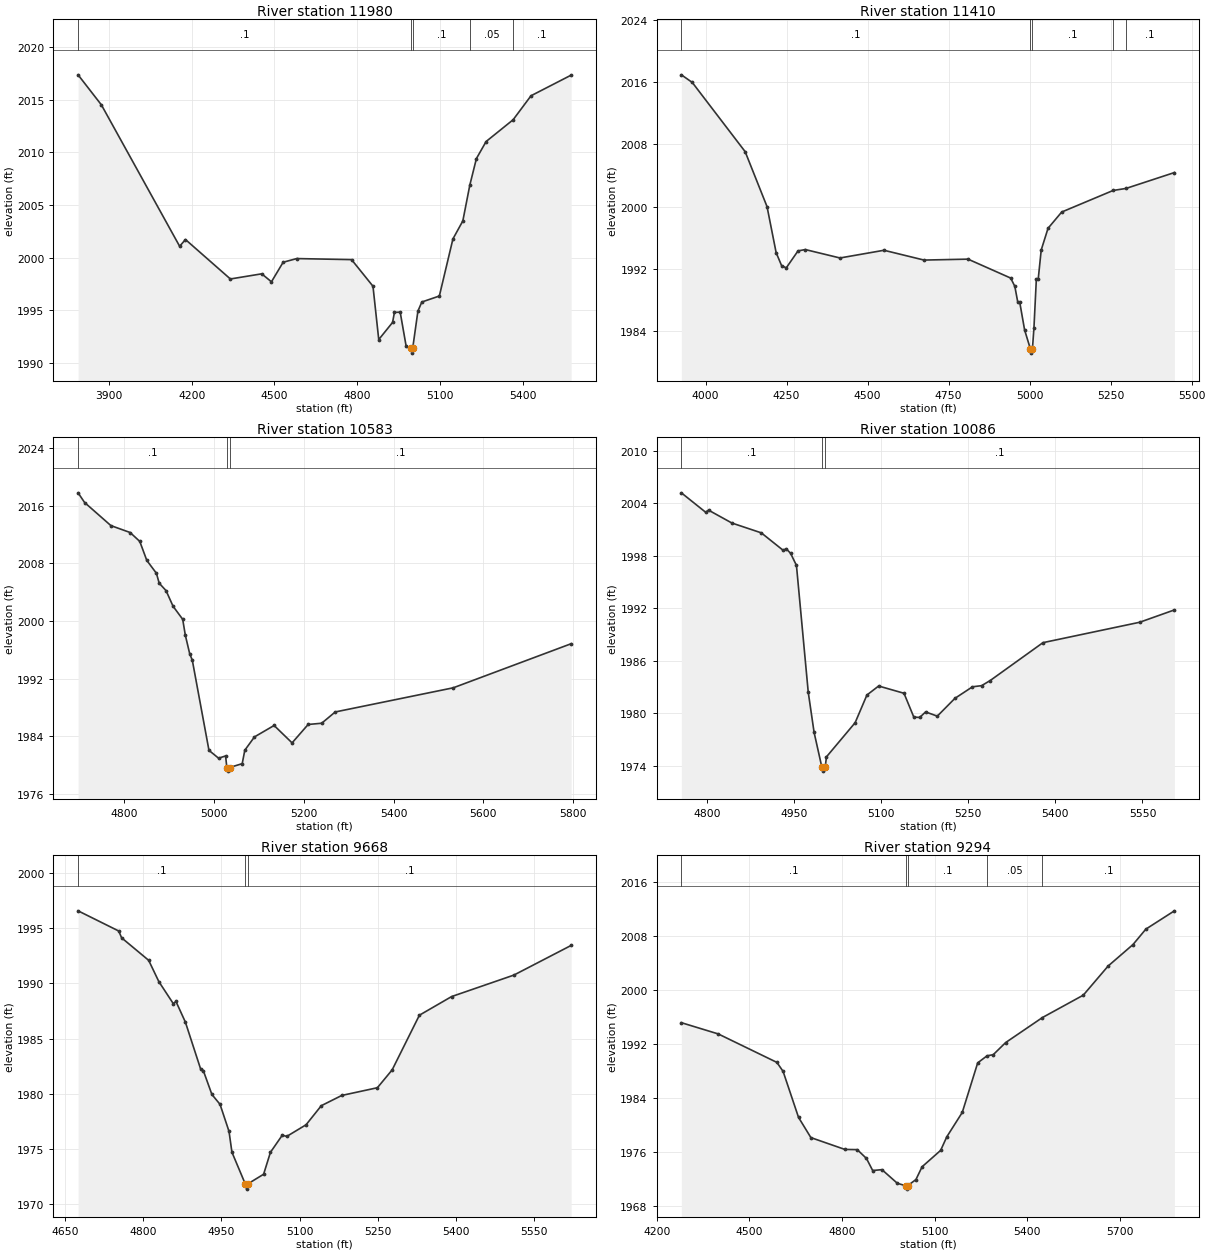
Type RM Length L Ch R = 1,11980,570,570,570
BEGIN DESCRIPTION:
STUCKENS BRANCH 26.0
END DESCRIPTION:
XS GIS Cut Line= 3
      2659611.45     10072590.85      2659056.32     10072103.98
      2658355.58     10071321.33
#Sta/Elev= 30
  3787.5 2017.38  3872.2 2014.52  4156.0 2001.08  4177.2 2001.72  4340.1 1997.97
  4453.9 1998.46  4489.1 1997.70  4531.5 1999.56  4580.9 1999.91  4779.8 1999.81
  4857.5 1997.28  4878.4 1992.21  4928.6 1993.84  4935.3 1994.79  4956.2 1994.82
  4977.9 1991.57  4995.8 1991.42  4998.6 1990.92  5001.8 1991.42  5020.5 1994.91
  5034.7 1995.78  5098.3 1996.35  5147.6 2001.78  5183.5 2003.49  5208.9 2006.90
  5232.8 2009.42  5268.0 2011.04  5366.0 2013.11  5430.9 2015.39  5576.4 2017.35
#Mann=5,-1,0
  3787.5     0.1       0  4995.8    0.07       0  5001.8     0.1       0
  5208.9    0.05       0  5366.0     0.1       0
Bank Sta=4995.8,5001.8
Exp/Cntr=0.3,0.1

Type RM Length L Ch R = 1,11410,827,827,827
BEGIN DESCRIPTION:
STUCKENS BRANCH 25.0
END DESCRIPTION:
XS GIS Cut Line= 3
      2659700.54     10072344.48      2659478.61     10071891.08
      2658920.17     10071041.48
#Sta/Elev= 30
  3925.3 2016.92  3959.0 2015.94  4122.2 2007.05  4189.7 1999.99  4217.8 1994.08
  4234.7 1992.41  4249.0 1992.13  4285.3 1994.31  4307.8 1994.48  4414.8 1993.40
  4550.6 1994.39  4674.2 1993.13  4809.9 1993.25  4941.5 1990.82  4954.3 1989.76
  4963.4 1987.73  4969.4 1987.73  4984.5 1984.16  5002.6 1981.68  5005.3 1981.18
  5008.6 1981.68  5013.3 1984.40  5020.7 1990.64  5026.7 1990.76  5035.8 1994.43
  5056.8 1997.21  5099.0 1999.30  5257.7 2002.07  5297.5 2002.33  5446.8 2004.37
#Mann=5,-1,0
  3925.3     0.1       0  5002.6    0.07       0  5008.6     0.1       0
  5257.7    0.05       0  5297.5     0.1       0
Bank Sta=5002.6,5008.6
Exp/Cntr=0.3,0.1

Type RM Length L Ch R = 1,10583,497,497,497
BEGIN DESCRIPTION:
STUCKENS BRANCH 24.0
END DESCRIPTION:
XS GIS Cut Line= 3
      2660203.81     10071457.52      2659794.12     10071214.48
      2659176.03     10071151.97
#Sta/Elev= 30
  4697.7 2017.83  4712.3 2016.48  4770.8 2013.27  4813.6 2012.31  4835.1 2011.07
  4850.7 2008.43  4872.1 2006.64  4878.3 2005.26  4893.5 2004.23  4909.2 2002.05
  4930.6 2000.24  4936.5 1998.02  4946.2 1995.45  4952.0 1994.55  4989.1 1982.01
  5010.5 1980.92  5026.1 1981.23  5028.9 1979.62  5031.7 1979.12  5034.9 1979.62
  5063.1 1980.16  5068.9 1982.03  5090.4 1983.88  5134.1 1985.47  5174.1 1983.05
  5209.9 1985.61  5240.0 1985.78  5270.2 1987.35  5532.9 1990.71  5795.3 1996.84
#Mann=3,-1,0
  4697.7     0.1       0  5028.9    0.07       0  5034.9     0.1       0
Bank Sta=5028.9,5034.9
Exp/Cntr=0.3,0.1

Type RM Length L Ch R = 1,10086,418,418,418
BEGIN DESCRIPTION:
STUCKENS BRANCH 23.0
END DESCRIPTION:
XS GIS Cut Line= 2
      2660224.64     10070832.54      2659384.39     10070957.53
#Sta/Elev= 30
  4755.5 2005.18  4797.4 2002.96  4802.4 2003.20  4842.6 2001.73  4893.2 2000.61
  4931.0 1998.61  4936.1 1998.80  4943.7 1998.27  4953.8 1996.89  4974.1 1982.42
  4984.2 1977.82  4997.4 1973.90  5000.2 1973.40  5003.4 1973.90  5005.5 1975.03
  5054.9 1978.93  5075.2 1982.09  5095.4 1983.12  5139.1 1982.29  5156.0 1979.57
  5166.1 1979.53  5176.3 1980.16  5196.5 1979.68  5226.8 1981.71  5257.1 1983.03
  5272.8 1983.16  5287.5 1983.74  5378.5 1988.07  5545.2 1990.40  5605.0 1991.81
#Mann=3,-1,0
  4755.5     0.1       0  4997.4    0.07       0  5003.4     0.1       0
Bank Sta=4997.4,5003.4
Exp/Cntr=0.3,0.1

Type RM Length L Ch R = 1,9668,374,374,374
BEGIN DESCRIPTION:
STUCKENS BRANCH 22.0
END DESCRIPTION:
XS GIS Cut Line= 3
      2660120.54     10070513.10      2659863.56     10070464.48
      2659245.47     10070756.16
#Sta/Elev= 30
  4675.5 1996.59  4753.4 1994.76  4759.0 1994.14  4810.8 1992.10  4830.3 1990.17
  4858.0 1988.17  4863.1 1988.37  4881.2 1986.49  4910.4 1982.24  4915.5 1982.10
  4932.0 1979.93  4947.6 1979.03  4964.8 1976.58  4970.4 1974.69  4995.7 1971.84
  4998.4 1971.34  5001.7 1971.84  5031.1 1972.69  5044.2 1974.68  5067.0 1976.24
  5075.4 1976.12  5112.5 1977.18  5141.7 1978.91  5180.9 1979.84  5249.2 1980.54
  5277.5 1982.16  5329.7 1987.12  5391.4 1988.81  5510.8 1990.76  5620.5 1993.45
#Mann=3,-1,0
  4675.5     0.1       0  4995.7    0.07       0  5001.7     0.1       0
Bank Sta=4995.7,5001.7
Exp/Cntr=0.3,0.1

Type RM Length L Ch R = 1,9294,421,421,421
BEGIN DESCRIPTION:
STUCKENS BRANCH 21.0
END DESCRIPTION:
XS GIS Cut Line= 3
      2660337.68     10070203.89      2659373.61     10070175.25
      2658745.03     10070108.58
#Sta/Elev= 30
  4279.5 1995.15  4398.8 1993.49  4588.8 1989.28  4608.9 1987.95  4658.9 1981.15
  4698.9 1978.16  4808.9 1976.41  4849.0 1976.38  4879.0 1975.07  4899.0 1973.29
  4929.0 1973.42  4979.0 1971.40  5006.0 1971.04  5008.8 1970.54  5012.0 1971.04
  5039.0 1971.95  5059.1 1973.85  5119.1 1976.27  5139.1 1978.28  5189.1 1981.88
  5239.1 1989.21  5269.3 1990.25  5289.4 1990.42  5329.6 1992.21  5448.7 1995.91
  5581.0 1999.22  5661.5 2003.53  5741.9 2006.70  5783.5 2008.98  5876.1 2011.69
#Mann=5,-1,0
  4279.5     0.1       0  5006.0    0.07       0  5012.0     0.1       0
  5269.3    0.05       0  5448.7     0.1       0
Bank Sta=5006,5012
Exp/Cntr=0.3,0.1

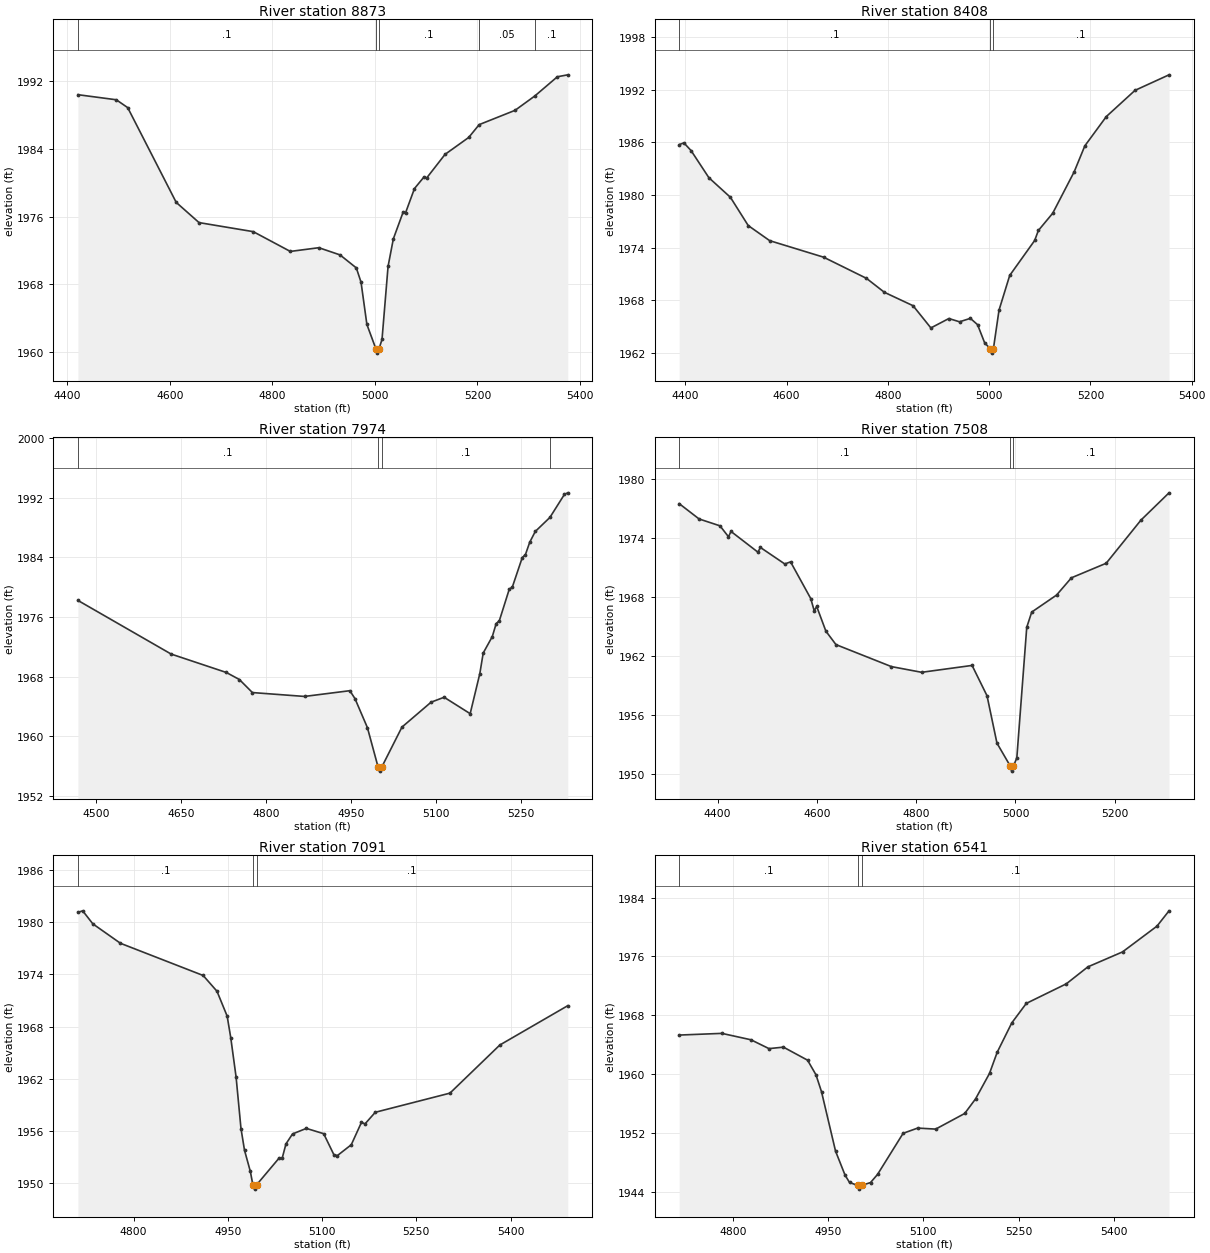
Type RM Length L Ch R = 1,8873,465,465,465
BEGIN DESCRIPTION:
STUCKENS BRANCH 20.0
END DESCRIPTION:
XS GIS Cut Line= 3
      2660217.69     10070033.90      2659794.12     10069818.64
      2659328.79     10069700.58
#Sta/Elev= 30
  4421.0 1990.42  4495.8 1989.82  4518.1 1988.89  4612.7 1977.68  4657.2 1975.29
  4762.9 1974.22  4835.2 1971.88  4890.8 1972.32  4932.1 1971.47  4963.9 1969.93
  4973.1 1968.24  4984.5 1963.24  5002.1 1960.35  5004.9 1959.85  5008.1 1960.35
  5014.0 1961.47  5025.8 1970.11  5036.1 1973.37  5055.0 1976.50  5060.1 1976.48
  5077.3 1979.32  5095.9 1980.69  5101.1 1980.57  5136.9 1983.36  5183.0 1985.36
  5203.5 1986.88  5273.4 1988.57  5312.0 1990.27  5355.9 1992.54  5376.2 1992.77
#Mann=5,-1,0
  4421.0     0.1       0  5002.1    0.07       0  5008.1     0.1       0
  5203.5    0.05       0  5312.0     0.1       0
Bank Sta=5002.1,5008.1
Exp/Cntr=0.3,0.1

Type RM Length L Ch R = 1,8408,434,434,434
BEGIN DESCRIPTION:
STUCKENS BRANCH 19.0
END DESCRIPTION:
XS GIS Cut Line= 2
      2660356.59     10069818.62      2659655.25     10069152.00
#Sta/Elev= 30
  4387.7 1985.73  4397.0 1985.93  4411.2 1985.05  4446.4 1981.96  4488.9 1979.73
  4524.1 1976.51  4566.5 1974.79  4672.9 1972.91  4757.6 1970.50  4793.0 1968.91
  4849.7 1967.38  4884.9 1964.85  4920.4 1965.92  4941.5 1965.55  4962.9 1965.94
  4977.1 1965.22  4991.2 1963.14  5002.4 1962.48  5005.1 1961.98  5008.4 1962.48
  5019.5 1966.88  5040.6 1970.83  5089.9 1974.81  5097.2 1975.95  5125.5 1977.91
  5168.0 1982.64  5189.0 1985.59  5231.5 1988.93  5288.1 1991.91  5355.3 1993.68
#Mann=3,-1,0
  4387.7     0.1       0  5002.4    0.07       0  5008.4     0.1       0
Bank Sta=5002.4,5008.4
Exp/Cntr=0.3,0.1

Type RM Length L Ch R = 1,7974,466,466,466
BEGIN DESCRIPTION:
STUCKENS BRANCH 18.0
END DESCRIPTION:
XS GIS Cut Line= 2
      2660502.44     10069707.51      2660141.33     10068922.80
#Sta/Elev= 30
  4468.5 1978.22  4632.9 1971.03  4730.3 1968.56  4753.2 1967.62  4776.2 1965.87
  4868.1 1965.35  4948.0 1966.12  4957.0 1965.07  4979.0 1961.17  4998.0 1955.84
  5000.8 1955.34  5004.0 1955.84  5039.9 1961.24  5091.3 1964.58  5114.3 1965.24
  5160.2 1963.04  5177.2 1968.40  5183.2 1971.17  5199.2 1973.37  5206.1 1975.12
  5211.6 1975.49  5229.1 1979.71  5234.6 1980.02  5252.1 1983.97  5257.6 1984.35
  5265.2 1986.01  5275.0 1987.46  5300.8 1989.34  5326.5 1992.44  5332.3 1992.64
#Mann=4,-1,0
  4468.5     0.1       0  4998.0    0.07       0  5004.0     0.1       0
  5300.8    0.16       0
Bank Sta=4998,5004
Exp/Cntr=0.3,0.1

Type RM Length L Ch R = 1,7508,417,417,417
BEGIN DESCRIPTION:
STUCKENS BRANCH 17.0
END DESCRIPTION:
XS GIS Cut Line= 3
      2660801.05     10069804.71      2660696.89     10069214.48
      2660696.89     10068827.13
#Sta/Elev= 30
  4322.6 1977.54  4362.7 1975.98  4404.8 1975.28  4421.9 1974.17  4427.0 1974.71
  4481.2 1972.60  4486.2 1973.08  4535.3 1971.40  4547.0 1971.61  4587.6 1967.88
  4594.6 1966.63  4599.6 1967.07  4618.1 1964.56  4638.4 1963.19  4750.1 1960.95
  4811.0 1960.37  4912.6 1961.07  4942.7 1957.98  4962.7 1953.16  4989.7 1950.81
  4992.5 1950.31  4995.7 1950.81  5002.7 1951.65  5022.7 1964.95  5032.7 1966.50
  5082.7 1968.23  5112.7 1969.99  5182.7 1971.47  5252.7 1975.86  5309.3 1978.64
#Mann=3,-1,0
  4322.6     0.1       0  4989.7    0.07       0  4995.7     0.1       0
Bank Sta=4989.7,4995.7
Exp/Cntr=0.3,0.1

Type RM Length L Ch R = 1,7091,550,550,550
BEGIN DESCRIPTION:
STUCKENS BRANCH 16.0
END DESCRIPTION:
XS GIS Cut Line= 2
      2661196.91     10069575.63      2660829.01     10068888.41
#Sta/Elev= 30
  4711.5 1981.13  4719.1 1981.31  4735.3 1979.81  4779.2 1977.58  4910.8 1973.88
  4932.8 1972.07  4949.0 1969.21  4954.7 1966.74  4963.2 1962.22  4971.0 1956.29
  4976.6 1953.80  4985.9 1951.36  4989.9 1949.83  4992.6 1949.33  4995.9 1949.83
  5031.1 1952.85  5036.8 1952.95  5042.6 1954.53  5053.0 1955.67  5075.0 1956.31
  5102.6 1955.70  5118.8 1953.29  5124.5 1953.19  5146.5 1954.43  5162.7 1957.00
  5168.4 1956.83  5184.7 1958.16  5303.5 1960.36  5382.9 1965.89  5491.0 1970.41
#Mann=3,-1,0
  4711.5     0.1       0  4989.9    0.07       0  4995.9     0.1       0
Bank Sta=4989.9,4995.9
Exp/Cntr=0.3,0.1

Type RM Length L Ch R = 1,6541,324,324,324
BEGIN DESCRIPTION:
STUCKENS BRANCH 15.0
END DESCRIPTION:
XS GIS Cut Line= 2
      2661571.85     10068978.35      2660872.01     10068652.68
#Sta/Elev= 30
  4715.2 1965.33  4782.5 1965.56  4828.3 1964.69  4856.7 1963.49  4879.5 1963.69
  4917.5 1961.92  4930.8 1959.93  4939.5 1957.63  4961.6 1949.57  4976.6 1946.31
  4983.6 1945.32  4996.5 1944.91  4999.2 1944.41  5002.5 1944.91  5016.7 1945.30
  5027.8 1946.41  5068.1 1951.99  5091.0 1952.70  5119.4 1952.56  5165.1 1954.68
  5182.2 1956.66  5204.2 1960.12  5216.4 1963.01  5239.3 1966.98  5262.2 1969.63
  5325.3 1972.29  5359.2 1974.59  5413.8 1976.62  5468.1 1980.12  5487.1 1982.20
#Mann=3,-1,0
  4715.2     0.1       0  4996.5    0.07       0  5002.5     0.1       0
Bank Sta=4996.5,5002.5
Exp/Cntr=0.3,0.1

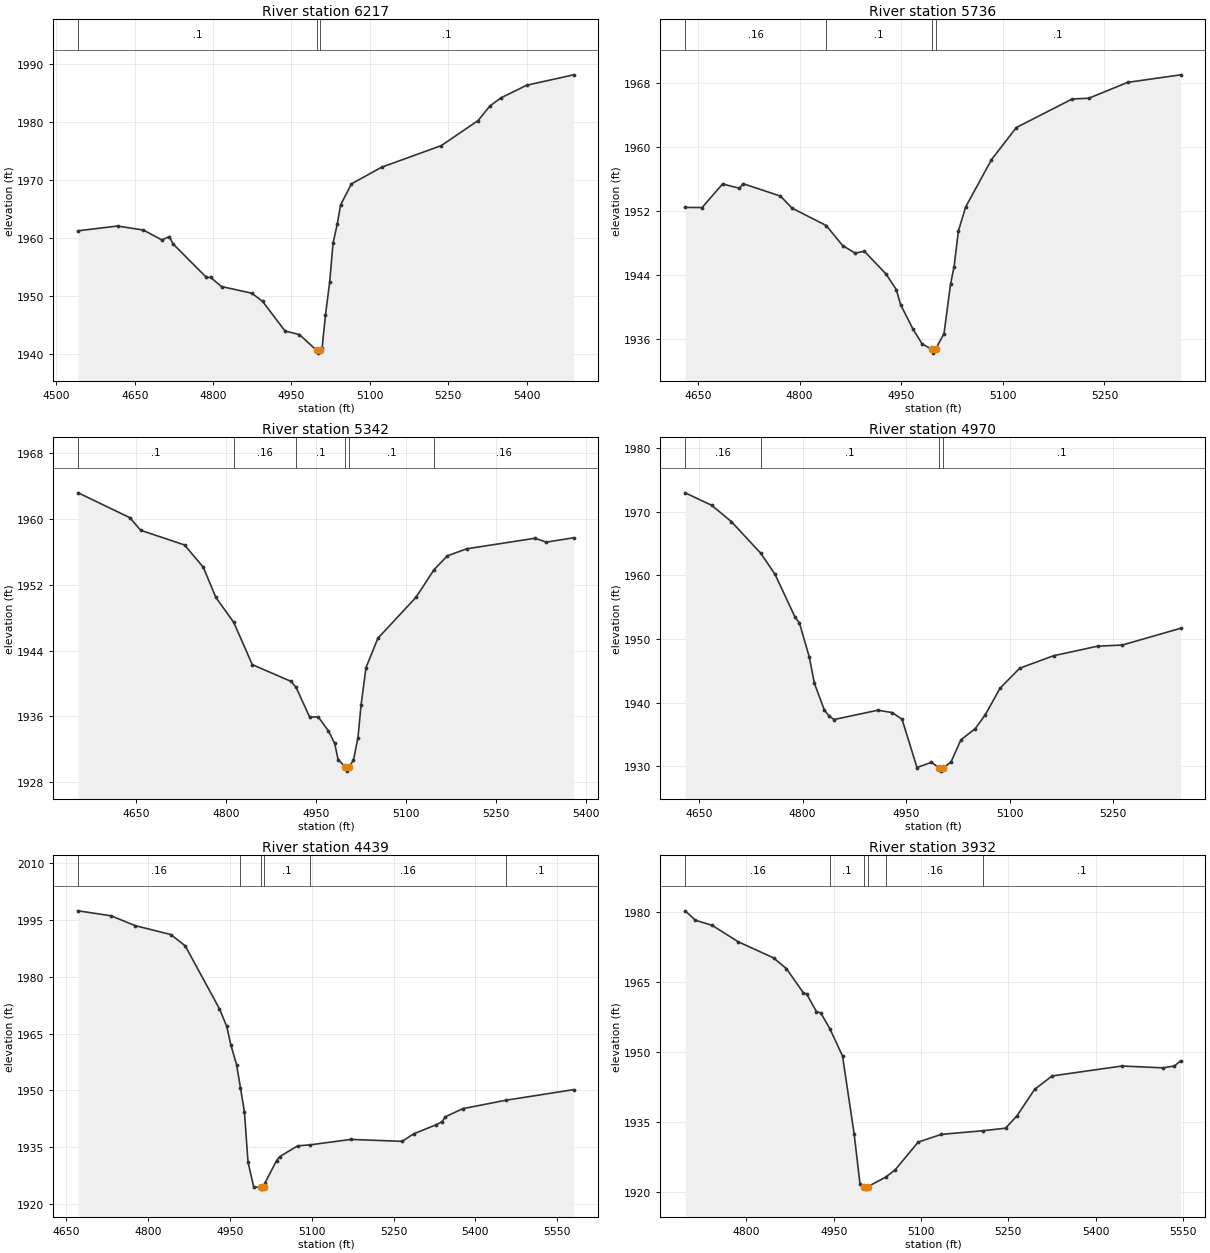
Type RM Length L Ch R = 1,6217,481,481,481
BEGIN DESCRIPTION:
STUCKENS BRANCH 14.0
END DESCRIPTION:
XS GIS Cut Line= 2
      2661801.02     10068846.39      2661052.24     10068264.01
#Sta/Elev= 30
  4541.6 1961.22  4616.9 1962.04  4666.6 1961.34  4701.9 1959.64  4716.4 1960.22
  4722.7 1959.00  4787.0 1953.18  4795.1 1953.17  4816.0 1951.59  4873.9 1950.44
  4894.7 1949.03  4937.6 1943.92  4965.3 1943.29  4997.9 1940.59  5000.7 1940.09
  5003.9 1940.59  5008.7 1941.05  5015.0 1946.62  5023.2 1952.40  5029.5 1959.06
  5037.7 1962.38  5044.0 1965.68  5064.8 1969.32  5122.7 1972.20  5236.7 1975.92
  5307.3 1980.25  5329.9 1982.77  5350.7 1984.15  5400.5 1986.36  5490.2 1988.15
#Mann=3,-1,0
  4541.6     0.1       0  4997.9    0.07       0  5003.9     0.1       0
Bank Sta=4997.9,5003.9
Exp/Cntr=0.3,0.1

Type RM Length L Ch R = 1,5736,394,394,394
BEGIN DESCRIPTION:
STUCKENS BRANCH 13.0
END DESCRIPTION:
XS GIS Cut Line= 3
      2662002.44     10068721.39      2661814.95     10068221.42
      2661621.99     10068180.07
#Sta/Elev= 30
  4631.2 1952.47  4656.1 1952.45  4686.3 1955.39  4711.3 1954.86  4716.6 1955.43
  4771.8 1953.88  4788.9 1952.38  4839.3 1950.21  4863.7 1947.70  4882.1 1946.77
  4895.7 1947.00  4927.7 1944.16  4942.7 1942.23  4949.1 1940.36  4967.6 1937.26
  4981.1 1935.43  4994.8 1934.80  4997.6 1934.30  5000.8 1934.80  5013.2 1936.73
  5022.8 1942.87  5028.1 1945.10  5034.5 1949.56  5045.2 1952.53  5083.3 1958.43
  5120.0 1962.43  5202.5 1965.99  5226.9 1966.08  5284.3 1968.06  5362.5 1969.00
#Mann=4,-1,0
  4631.2    0.16       0  4839.3     0.1       0  4994.8    0.07       0
  5000.8     0.1       0
Bank Sta=4994.8,5000.8
Exp/Cntr=0.3,0.1

Type RM Length L Ch R = 1,5342,372,372,372
BEGIN DESCRIPTION:
STUCKENS BRANCH 12.0
END DESCRIPTION:
XS GIS Cut Line= 2
      2662377.44     10068693.61      2662141.34     10067901.97
#Sta/Elev= 30
  4553.7 1963.17  4639.9 1960.15  4657.9 1958.62  4731.0 1956.84  4762.3 1954.13
  4783.2 1950.47  4813.1 1947.43  4844.0 1942.30  4908.4 1940.27  4917.1 1939.53
  4939.7 1935.92  4953.9 1935.95  4971.0 1934.25  4981.4 1932.72  4987.1 1930.76
  4999.3 1929.86  5002.0 1929.36  5005.3 1929.86  5012.7 1930.70  5020.2 1933.42
  5025.4 1937.40  5033.6 1941.94  5053.4 1945.50  5117.1 1950.49  5147.0 1953.83
  5169.3 1955.52  5201.6 1956.37  5315.4 1957.65  5334.2 1957.18  5379.8 1957.71
#Mann=6,-1,0
  4553.7     0.1       0  4813.1    0.16       0  4917.1     0.1       0
  4999.3    0.07       0  5005.3     0.1       0  5147.0    0.16       0
Bank Sta=4999.3,5005.3
Exp/Cntr=0.3,0.1

Type RM Length L Ch R = 1,4970,531,531,531
BEGIN DESCRIPTION:
STUCKENS BRANCH 11.0
END DESCRIPTION:
XS GIS Cut Line= 2
      2662849.66     10068436.69      2662370.49     10067901.97
#Sta/Elev= 30
  4629.8 1973.01  4668.2 1971.04  4696.6 1968.49  4739.4 1963.48  4760.1 1960.16
  4788.6 1953.53  4795.3 1952.51  4809.5 1947.23  4817.0 1943.03  4831.2 1938.88
  4837.9 1937.91  4845.4 1937.32  4908.9 1938.79  4929.8 1938.42  4944.0 1937.37
  4965.7 1929.77  4986.7 1930.59  4997.9 1929.70  5000.6 1929.20  5003.9 1929.70
  5015.1 1930.66  5029.3 1934.12  5050.2 1935.90  5064.4 1938.03  5086.1 1942.25
  5114.5 1945.40  5163.8 1947.37  5227.4 1948.87  5263.3 1949.05  5347.8 1951.69
#Mann=4,-1,0
  4629.8    0.16       0  4739.4     0.1       0  4997.9    0.07       0
  5003.9     0.1       0
Bank Sta=4997.9,5003.9
Exp/Cntr=0.3,0.1

Type RM Length L Ch R = 1,4439,507,507,507
BEGIN DESCRIPTION:
STUCKENS BRANCH 10.0
END DESCRIPTION:
XS GIS Cut Line= 2
      2663335.82     10067999.21      2662468.36     10067728.56
#Sta/Elev= 30
  4671.6 1997.43  4731.7 1996.12  4776.4 1993.51  4841.4 1991.17  4867.9 1988.18
  4930.7 1971.57  4944.1 1966.88  4951.7 1961.96  4962.1 1956.81  4969.2 1950.73
  4976.6 1944.21  4983.1 1931.05  4993.6 1924.45  5006.1 1924.42  5008.9 1923.92
  5012.1 1924.42  5014.5 1925.62  5035.5 1931.48  5041.6 1932.53  5074.1 1935.35
  5096.7 1935.61  5171.6 1937.05  5265.9 1936.54  5286.9 1938.53  5328.8 1940.96
  5339.3 1941.78  5344.6 1943.00  5377.1 1945.18  5455.4 1947.38  5580.3 1950.20
#Mann=6,-1,0
  4671.6    0.16       0  4969.2     0.1       0  5006.1    0.07       0
  5012.1     0.1       0  5096.7    0.16       0  5455.4     0.1       0
Bank Sta=5006.1,5012.1
Exp/Cntr=0.3,0.1

Type RM Length L Ch R = 1,3932,445,445,445
BEGIN DESCRIPTION:
STUCKENS BRANCH 9.0
END DESCRIPTION:
XS GIS Cut Line= 3
      2663294.11     10067520.03      2663085.78     10067415.87
      2662467.75     10067436.70
#Sta/Elev= 30
  4694.8 1980.20  4712.3 1978.19  4741.3 1977.08  4786.1 1973.56  4846.5 1970.13
  4868.8 1967.81  4897.9 1962.63  4903.4 1962.42  4920.2 1958.64  4927.7 1958.35
  4943.5 1954.92  4965.1 1949.12  4985.1 1932.42  4995.1 1921.74  5002.1 1921.11
  5004.8 1920.61  5008.1 1921.11  5039.3 1923.18  5055.1 1924.68  5095.1 1930.68
  5135.1 1932.34  5207.0 1933.12  5245.2 1933.66  5265.2 1936.37  5295.2 1941.98
  5325.3 1944.85  5445.3 1946.97  5515.4 1946.58  5535.4 1946.98  5546.1 1948.09
#Mann=6,-1,0
  4694.8    0.16       0  4943.5     0.1       0  5002.1    0.07       0
  5008.1     0.1       0  5039.3    0.16       0  5207.0     0.1       0
Bank Sta=5002.1,5008.1
Exp/Cntr=0.3,0.1

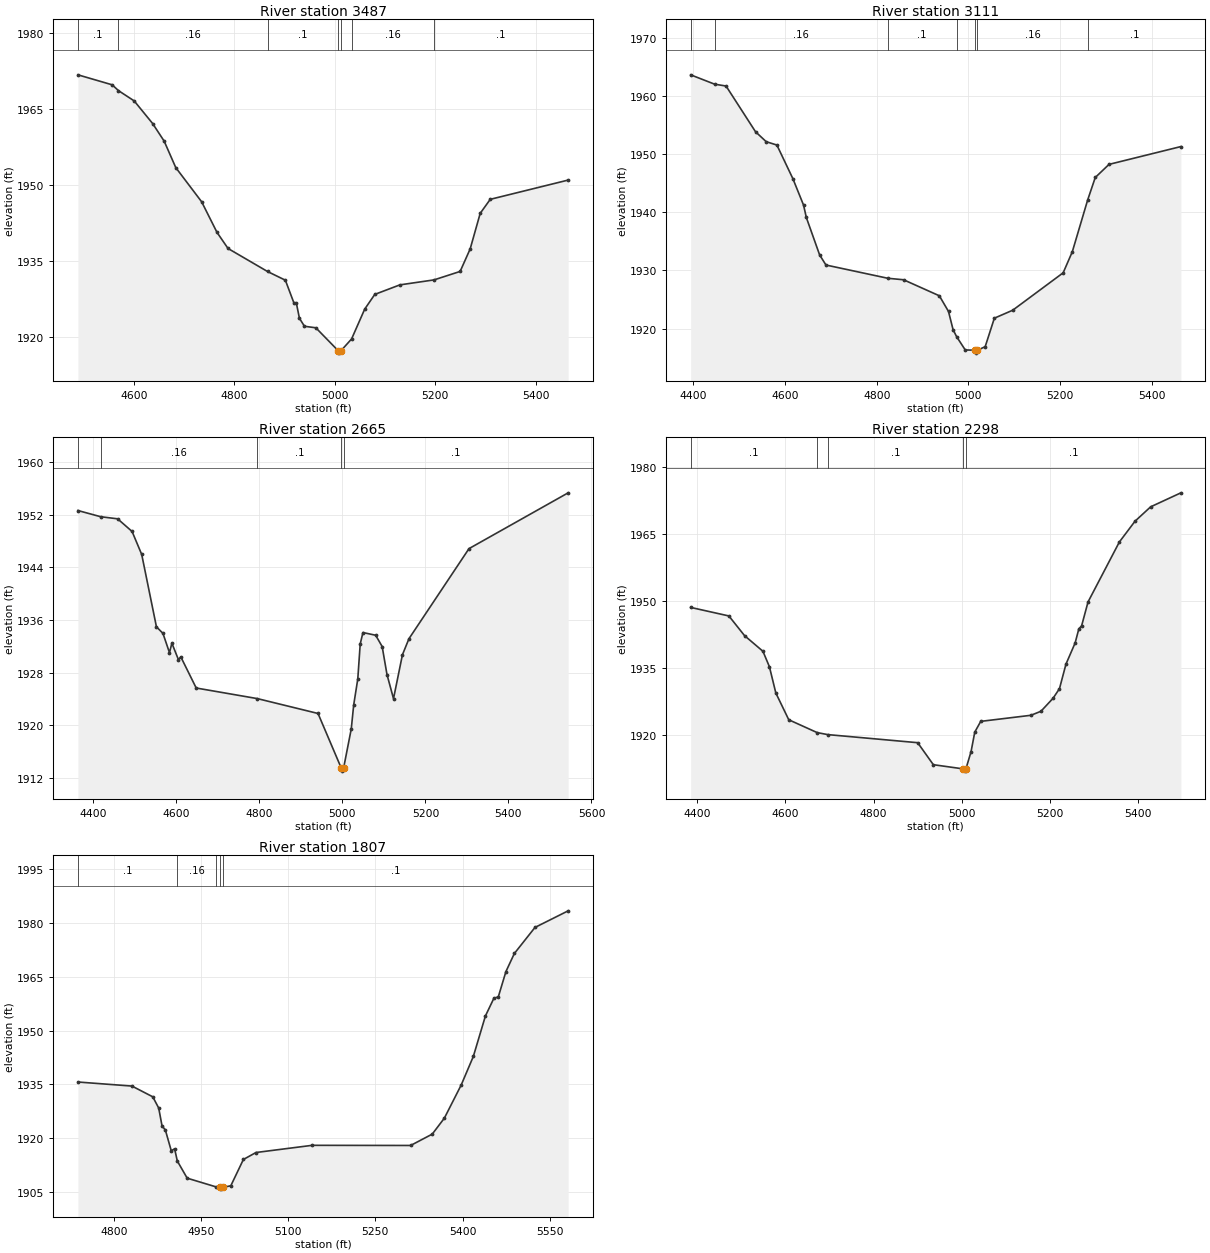
Type RM Length L Ch R = 1,3487,376,376,376
BEGIN DESCRIPTION:
STUCKENS BRANCH 8.0
END DESCRIPTION:
XS GIS Cut Line= 3
      2663370.47     10067179.74      2662974.67     10066999.20
      2662433.25     10066992.26
#Sta/Elev= 30
  4488.3 1971.67  4556.5 1969.70  4569.1 1968.55  4600.4 1966.52  4637.1 1962.06
  4660.1 1958.58  4683.2 1953.36  4734.7 1946.62  4765.3 1940.58  4787.3 1937.40
  4865.9 1932.86  4901.5 1931.14  4918.5 1926.66  4923.3 1926.66  4929.5 1923.63
  4939.5 1922.05  4962.2 1921.75  5006.5 1917.25  5009.3 1916.75  5012.5 1917.25
  5033.4 1919.55  5059.5 1925.43  5079.6 1928.34  5129.6 1930.22  5197.5 1931.20
  5249.6 1932.87  5269.6 1937.32  5289.6 1944.34  5309.6 1947.10  5464.8 1950.90
#Mann=7,-1,0
  4488.3     0.1       0  4569.1    0.16       0  4865.9     0.1       0
  5006.5    0.07       0  5012.5     0.1       0  5033.4    0.16       0
  5197.5     0.1       0
Bank Sta=5006.5,5012.5
Exp/Cntr=0.3,0.1

Type RM Length L Ch R = 1,3111,446,446,446
BEGIN DESCRIPTION:
STUCKENS BRANCH 7.0
END DESCRIPTION:
XS GIS Cut Line= 3
      2663439.98     10066888.11      2663009.39     10066631.14
      2662441.70     10066617.30
#Sta/Elev= 30
  4394.2 1963.71  4446.4 1962.10  4471.4 1961.78  4535.7 1953.90  4559.0 1952.19
  4582.3 1951.61  4617.2 1945.81  4640.5 1941.25  4646.5 1939.13  4675.5 1932.68
  4689.3 1930.94  4824.1 1928.66  4858.6 1928.40  4936.6 1925.64  4956.6 1922.94
  4966.6 1919.79  4974.4 1918.58  4993.1 1916.31  5013.6 1916.26  5016.4 1915.76
  5019.6 1916.26  5036.6 1916.87  5056.6 1921.78  5096.6 1923.15  5206.7 1929.60
  5226.7 1933.24  5260.1 1942.14  5276.7 1946.02  5306.7 1948.28  5463.5 1951.35
#Mann=7,-1,0
  4394.2     0.1       0  4446.4    0.16       0  4824.1     0.1       0
  4974.4    0.16       0  5013.6    0.07       0  5019.6    0.16       0
  5260.1     0.1       0
Bank Sta=5013.6,5019.6
Exp/Cntr=0.3,0.1

Type RM Length L Ch R = 1,2665,367,367,367
BEGIN DESCRIPTION:
STUCKENS BRANCH 6.0
END DESCRIPTION:
XS GIS Cut Line= 2
      2663551.02     10066561.68      2662531.83     10065965.41
#Sta/Elev= 30
  4363.1 1952.63  4417.8 1951.69  4458.7 1951.37  4493.5 1949.45  4516.7 1945.96
  4552.2 1934.96  4567.9 1933.96  4583.6 1931.03  4589.4 1932.47  4605.1 1929.98
  4610.9 1930.39  4648.0 1925.66  4795.3 1924.05  4941.4 1921.79  4997.1 1913.53
  4999.8 1913.03  5003.1 1913.53  5021.5 1919.46  5027.3 1923.08  5037.2 1927.05
  5043.0 1932.35  5049.6 1934.09  5080.2 1933.68  5095.9 1931.96  5107.5 1927.71
  5123.2 1924.04  5144.7 1930.71  5160.4 1933.15  5305.0 1946.84  5543.9 1955.32
#Mann=5,-1,0
  4363.1     0.1       0  4417.8    0.16       0  4795.3     0.1       0
  4997.1    0.07       0  5003.1     0.1       0
Bank Sta=4997.1,5003.1
Exp/Cntr=0.3,0.1

Type RM Length L Ch R = 1,2298,491,491,491
BEGIN DESCRIPTION:
STUCKENS BRANCH 5.0
END DESCRIPTION:
XS GIS Cut Line= 2
      2663648.25     10066283.90      2662752.93     10065624.55
#Sta/Elev= 30
  4384.9 1948.57  4471.6 1946.66  4507.1 1942.26  4548.8 1938.76  4563.5 1935.31
  4578.1 1929.42  4607.4 1923.44  4671.8 1920.57  4695.7 1920.12  4899.8 1918.31
  4935.3 1913.39  5003.2 1912.45  5006.0 1911.95  5009.2 1912.45  5020.9 1916.33
  5029.3 1920.68  5042.8 1923.08  5156.6 1924.44  5179.4 1925.34  5206.8 1928.24
  5221.4 1930.40  5236.1 1935.88  5256.9 1940.62  5265.3 1943.77  5271.6 1944.45
  5286.2 1949.80  5357.2 1963.20  5392.7 1967.85  5428.2 1971.07  5496.8 1974.20
#Mann=5,-1,0
  4384.9     0.1       0  4671.8    0.16       0  4695.7     0.1       0
  5003.2    0.07       0  5009.2     0.1       0
Bank Sta=5003.2,5009.2
Exp/Cntr=0.3,0.1

Type RM Length L Ch R = 1,1807,617,617,617
BEGIN DESCRIPTION:
STUCKENS BRANCH 4.0
END DESCRIPTION:
XS GIS Cut Line= 3
      2663759.40     10065770.03      2663391.34     10065561.70
      2663134.52     10065228.52
#Sta/Elev= 30
  4738.2 1935.67  4831.2 1934.54  4867.0 1931.55  4877.2 1928.42  4882.9 1923.48
  4888.7 1922.29  4898.8 1916.54  4904.6 1917.07  4909.2 1913.69  4926.2 1908.91
  4976.4 1906.46  4982.4 1906.36  4985.1 1905.86  4988.4 1906.36  5001.3 1906.80
  5022.9 1914.11  5044.6 1916.05  5141.3 1918.05  5310.7 1918.01  5347.9 1921.17
  5368.7 1925.60  5397.7 1934.83  5418.6 1942.78  5439.4 1954.05  5453.9 1958.96
  5461.6 1959.38  5474.7 1966.41  5489.2 1971.44  5524.7 1978.69  5581.8 1983.31
#Mann=5,-1,0
  4738.2     0.1       0  4909.2    0.16       0  4976.4     0.1       0
  4982.4    0.07       0  4988.4     0.1       0
Bank Sta=4982.4,4988.4
Exp/Cntr=0.3,0.1