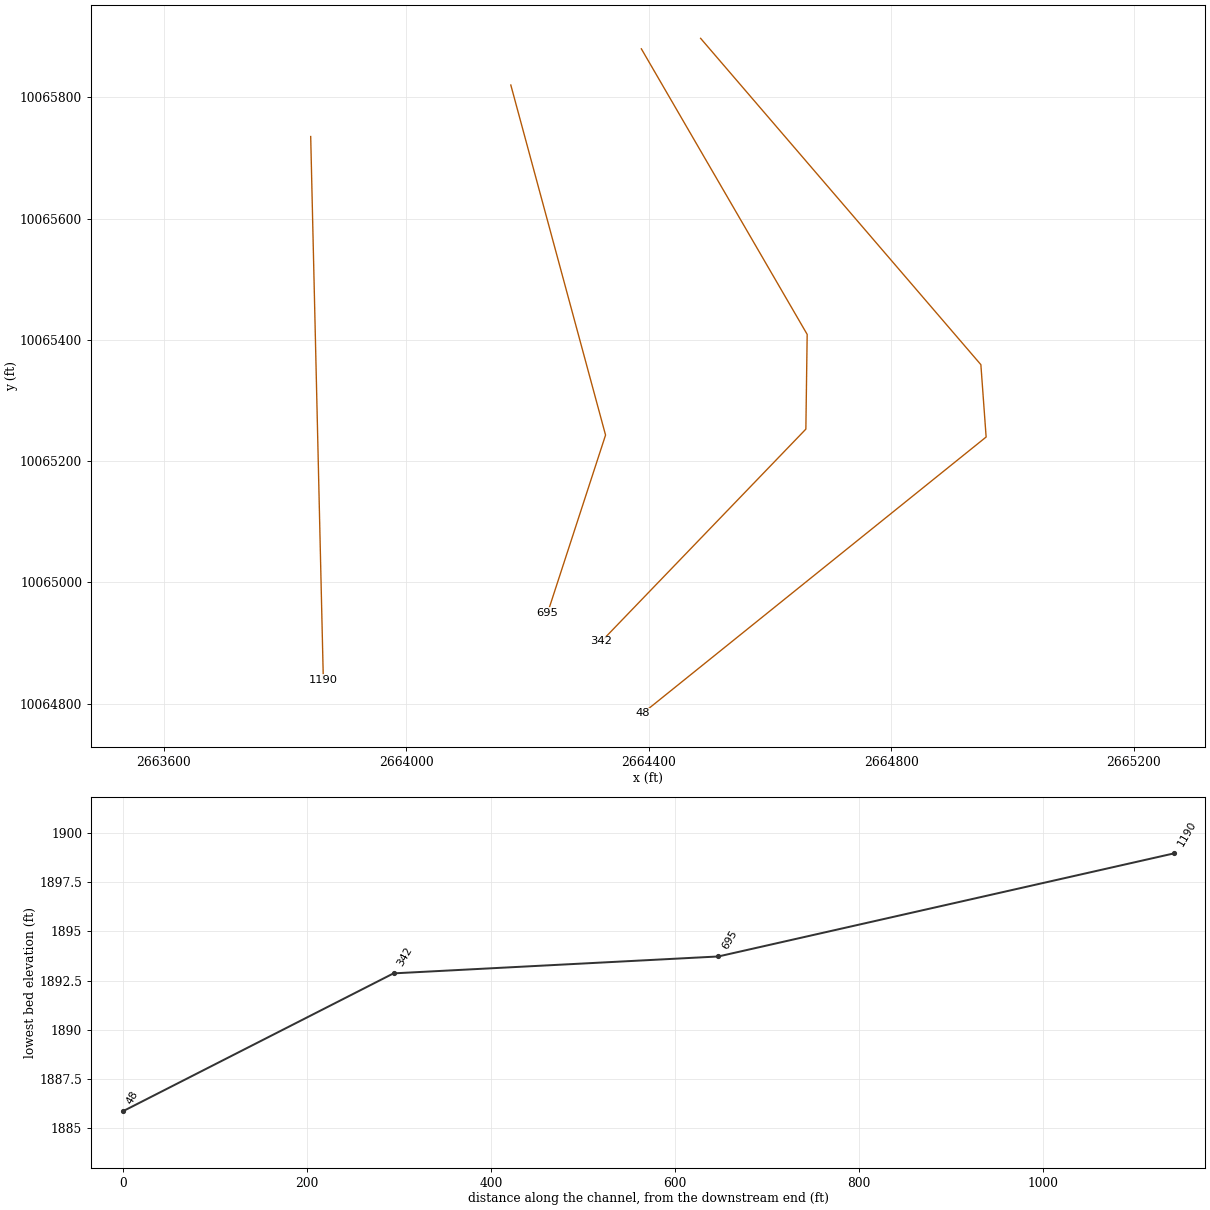
HEC-RAS study STUCKENS BRANCH.prj: STUCKENS BRANCH Base Level Engineering

--- STUCKENS BRANCH.g01 (geometry) --- (continued)

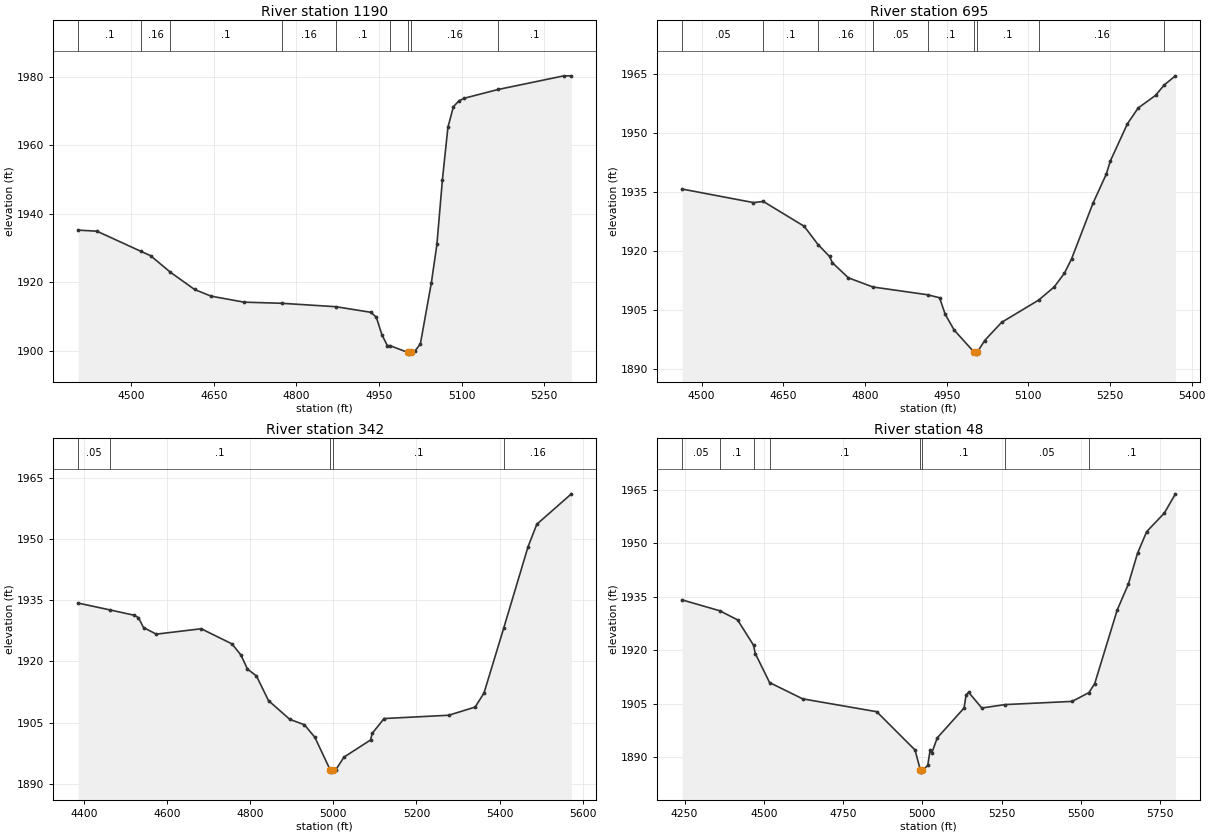
Type RM Length L Ch R = 1,1190,495,495,495
BEGIN DESCRIPTION:
STUCKENS BRANCH 3.0
END DESCRIPTION:
XS GIS Cut Line= 2
      2663842.73     10065735.28      2663863.56     10064839.52
#Sta/Elev= 30
  4403.4 1935.19  4437.6 1934.88  4518.0 1928.96  4535.0 1927.73  4570.9 1922.92
  4615.0 1917.85  4645.0 1915.90  4705.0 1914.15  4773.3 1913.82  4871.6 1912.82
  4935.1 1911.19  4945.1 1909.74  4955.1 1904.68  4965.1 1901.45  4969.9 1901.46
  5002.1 1899.47  5004.9 1898.97  5008.1 1899.47  5015.1 1899.83  5025.1 1901.98
  5045.1 1919.87  5055.1 1931.00  5065.1 1949.89  5075.1 1965.22  5085.1 1971.26
  5095.1 1972.95  5105.1 1973.73  5166.5 1976.28  5285.2 1980.24  5299.4 1980.26
#Mann=9,-1,0
  4403.4     0.1       0  4518.0    0.16       0  4570.9     0.1       0
  4773.3    0.16       0  4871.6     0.1       0  4969.9    0.16       0
  5002.1    0.07       0  5008.1    0.16       0  5166.5     0.1       0
Bank Sta=5002.1,5008.1
Exp/Cntr=0.3,0.1

Type RM Length L Ch R = 1,695,353,353,353
BEGIN DESCRIPTION:
STUCKENS BRANCH 2.0
END DESCRIPTION:
XS GIS Cut Line= 3
      2664172.75     10065820.26      2664329.01     10065242.96
      2664233.53     10064950.00
#Sta/Elev= 30
  4464.0 1935.68  4595.1 1932.24  4613.2 1932.53  4688.3 1926.22  4713.9 1921.55
  4734.8 1918.56  4740.1 1916.96  4769.5 1913.12  4814.6 1910.79  4915.3 1908.81
  4937.0 1908.05  4947.3 1903.86  4963.6 1899.88  5000.4 1894.23  5003.2 1893.73
  5006.4 1894.23  5019.8 1897.19  5050.9 1901.80  5119.0 1907.46  5147.6 1910.81
  5166.4 1914.30  5179.5 1917.95  5219.0 1932.15  5243.3 1939.49  5250.6 1942.79
  5282.1 1952.28  5301.9 1956.29  5333.8 1959.49  5349.6 1962.12  5370.2 1964.45
#Mann=9,-1,0
  4464.0    0.05       0  4613.2     0.1       0  4713.9    0.16       0
  4814.6    0.05       0  4915.3     0.1       0  5000.4    0.07       0
  5006.4     0.1       0  5119.0    0.16       0  5349.6     0.1       0
Bank Sta=5000.4,5006.4
Exp/Cntr=0.3,0.1

Type RM Length L Ch R = 1,342,294,294,294
BEGIN DESCRIPTION:
Mapping XS 22e94667
END DESCRIPTION:
XS GIS Cut Line= 4
      2664388.06     10065879.94      2664661.52     10065408.99
      2664659.35     10065252.74      2664322.13     10064902.55
#Sta/Elev= 30
  4385.9 1934.29  4461.9 1932.63  4521.1 1931.31  4531.1 1930.72  4543.4 1928.29
  4574.1 1926.68  4682.2 1928.00  4756.2 1924.29  4777.8 1921.55  4793.5 1918.11
  4815.0 1916.45  4844.1 1910.39  4895.3 1905.80  4930.5 1904.48  4955.7 1901.39
  4992.7 1893.37  4995.5 1892.87  4998.7 1893.37  5005.7 1893.40  5025.7 1896.55
  5089.5 1900.74  5093.8 1902.39  5122.1 1906.00  5277.7 1906.81  5341.3 1908.81
  5362.6 1912.26  5410.1 1928.19  5468.6 1948.11  5489.7 1953.61  5572.9 1961.06
#Mann=5,-1,0
  4385.9    0.05       0  4461.9     0.1       0  4992.7    0.07       0
  4998.7     0.1       0  5410.1    0.16       0
Bank Sta=4992.7,4998.7
Exp/Cntr=0.3,0.1

Type RM Length L Ch R = 1,48,0,0,0
BEGIN DESCRIPTION:
STUCKENS BRANCH 1.0
END DESCRIPTION:
XS GIS Cut Line= 4
      2664485.77     10065897.24      2664947.98     10065359.08
      2664956.66     10065239.72      2664390.22     10064783.96
#Sta/Elev= 30
  4242.0 1934.18  4360.7 1931.13  4417.0 1928.57  4467.3 1921.47  4473.0 1919.12
  4518.1 1910.98  4622.2 1906.42  4856.0 1902.81  4976.8 1892.07  4993.9 1886.36
  4996.6 1885.86  4999.9 1886.36  5016.9 1887.72  5024.5 1892.14  5029.5 1891.20
  5047.0 1895.49  5131.5 1903.85  5137.9 1907.53  5145.8 1908.26  5187.5 1903.85
  5261.0 1904.81  5472.3 1905.70  5525.3 1908.16  5543.6 1910.70  5614.6 1931.36
  5649.8 1938.63  5678.6 1947.24  5707.4 1953.32  5763.4 1958.55  5798.1 1963.93
#Mann=8,-1,0
  4242.0    0.05       0  4360.7     0.1       0  4467.3    0.16       0
  4518.1     0.1       0  4993.9    0.07       0  4999.9     0.1       0
  5261.0    0.05       0  5525.3     0.1       0
Bank Sta=4993.9,4999.9
Exp/Cntr=0.3,0.1

Chan Stop Cuts=-1