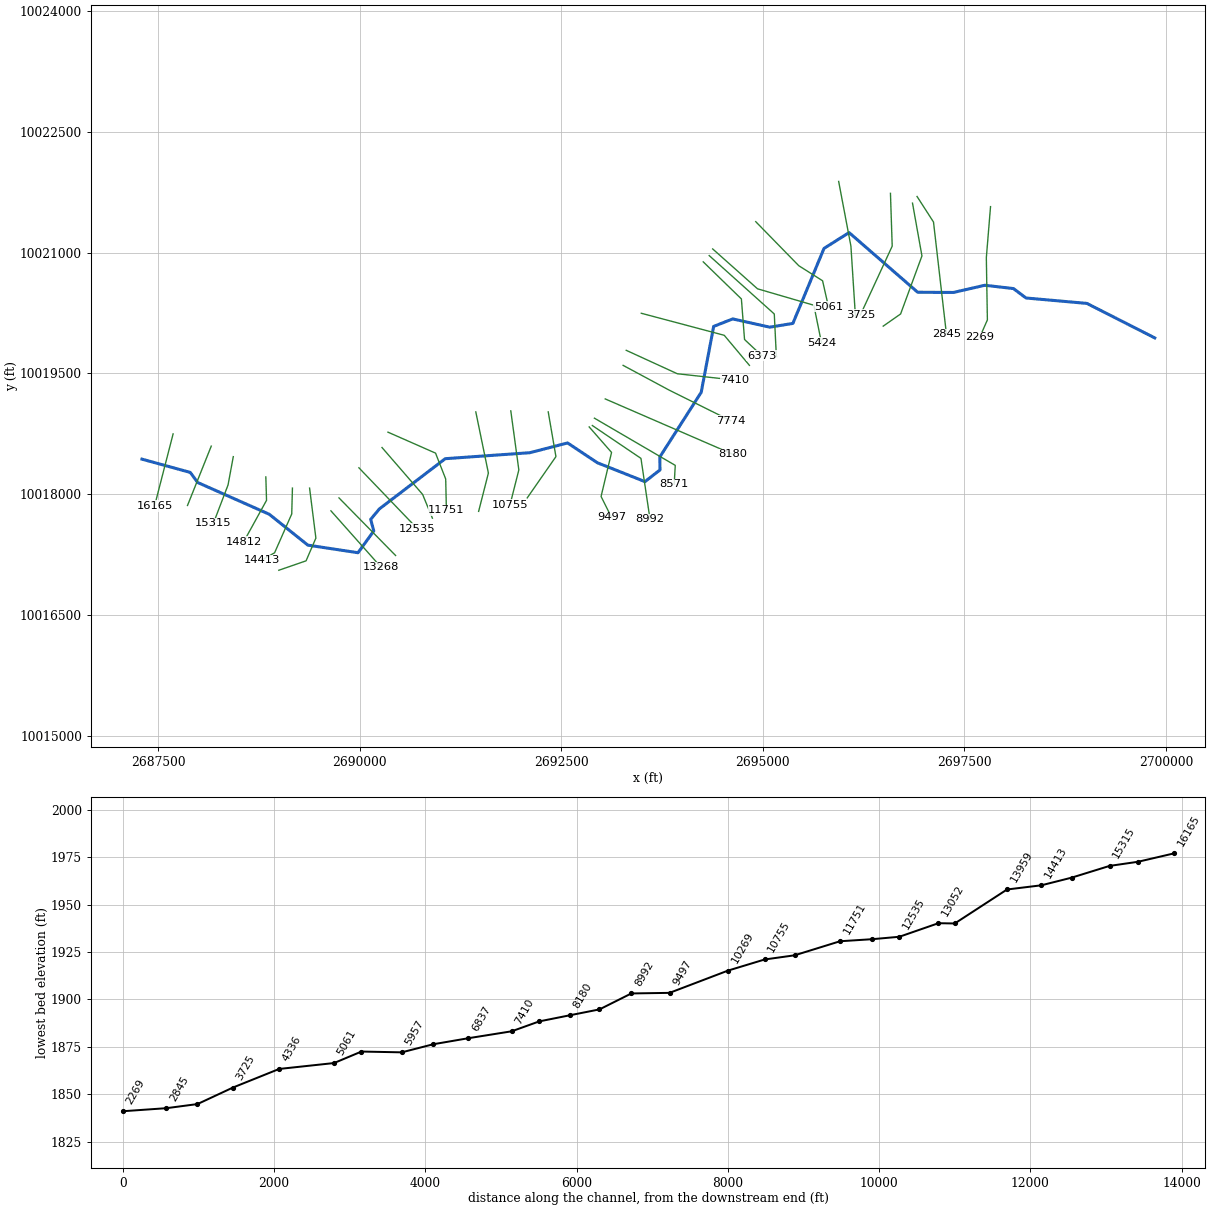
--- TROUGH CREEK.prj (project) ---

Proj Title=TROUGH CREEK Base Level Engineering
Current Plan=p01
Default Exp/Contr=0.3,0.1
English Units
Geom File=g01
Flow File=f01
Plan File=p01
Y Axis Title=Elevation
X Axis Title(PF)=Main Channel Distance
X Axis Title(XS)=Station
BEGIN DESCRIPTION:
TROUGH CREEK
END DESCRIPTION:
DSS Export Rating Curves= 0
DSS Export Rating Curve Sorted= 0
DSS Export Volume Flow Curves= 0
DXF OffsetX= 0
DXF OffsetY= 0
DXF ScaleX= 1
DXF ScaleY= 10

--- TROUGH CREEK.p01 (plan) ---

Plan Title=Multiple Run
Short Identifier=Multiple
Geom File=g01
Flow File=f01
Subcritical Flow
K Sum by GR= 0
Std Step Tol= 0.01
Critical Tol= 0.01
Num of Std Step Trials= 20
Max Error Tol= 0.3
Flow Tol Ratio= 0.001
Split Flow NTrial= 30
Split Flow Tol= 0.02
Split Flow Ratio= 0.02
Log Output Level= 0
Friction Slope Method= 1
Unsteady Friction Slope Method= 2
Unsteady Bridges Friction Slope Method= 1
Parabolic Critical Depth
Global Vel Dist=  1 , 1 , 1
Global Log Level= 0
CheckData=True
Encroach Param= -1, 0, 0, 0
BEGIN DESCRIPTION:
Multiple Run
END DESCRIPTION:

--- TROUGH CREEK.f01 (steady flow) ---

Flow Title=Multiple
Program Version=4.10
Number of Profiles= 7
Profile Names=10-year,25-year,50-year,1pct_min,100-year,1pct_plu,500-year
River Rch & RM=TROUGH CREEK,Reach-1         ,16165
    2046    3062    3965    3735    5051    6831    8198
River Rch & RM=TROUGH CREEK,Reach-1         ,13052
    2699    4093    5345    5073    6861    9279   11310
River Rch & RM=TROUGH CREEK,Reach-1         ,8180
    3217    4900    6415    6100    8250   11157   13649
Boundary for River Rch & Prof#=TROUGH CREEK,Reach-1         , 1
Up Type= 0
Dn Type= 3
Dn Slope=0.018
Boundary for River Rch & Prof#=TROUGH CREEK,Reach-1         , 2
Up Type= 0
Dn Type= 3
Dn Slope=0.018
Boundary for River Rch & Prof#=TROUGH CREEK,Reach-1         , 3
Up Type= 0
Dn Type= 3
Dn Slope=0.018
Boundary for River Rch & Prof#=TROUGH CREEK,Reach-1         , 4
Up Type= 0
Dn Type= 3
Dn Slope=0.018
Boundary for River Rch & Prof#=TROUGH CREEK,Reach-1         , 5
Up Type= 0
Dn Type= 3
Dn Slope=0.018
Boundary for River Rch & Prof#=TROUGH CREEK,Reach-1         , 6
Up Type= 0
Dn Type= 3
Dn Slope=0.018
Boundary for River Rch & Prof#=TROUGH CREEK,Reach-1         , 7
Up Type= 0
Dn Type= 3
Dn Slope=0.018
DSS Import GetInterval= 0
DSS Import GetPeak= 0
DSS Import FillOption= 0

--- TROUGH CREEK.g01 (geometry) ---

Geom Title=Existing Conditions
Program Version=4.10

River Reach=TROUGH CREEK    ,Reach-1
Reach XY= 30
      2687297.73     10018435.38       2687897.3     10018270.57
      2687989.11      10018145.4      2688877.34     10017751.02
      2689355.34     10017368.03      2689978.03     10017273.69
      2690173.58     10017543.91      2690134.73     10017687.45
      2690242.73     10017817.42      2691059.59     10018440.91
      2692108.84     10018515.17      2692576.96     10018636.17
       2692946.9     10018390.25      2693537.31     10018156.23
      2693723.08     10018301.25       2693721.5      10018462.3
      2694234.75     10019265.28      2694389.19      10020082.9
      2694625.92     10020175.89       2695085.3     10020073.34
      2695371.65     10020120.06      2695757.86     10021051.14
      2696068.94     10021247.43      2696919.77     10020506.87
      2697363.19     10020504.39      2697752.45     10020593.68
      2698107.96     10020552.61      2698263.71     10020435.56
      2699018.46     10020368.46      2699860.45     10019940.14

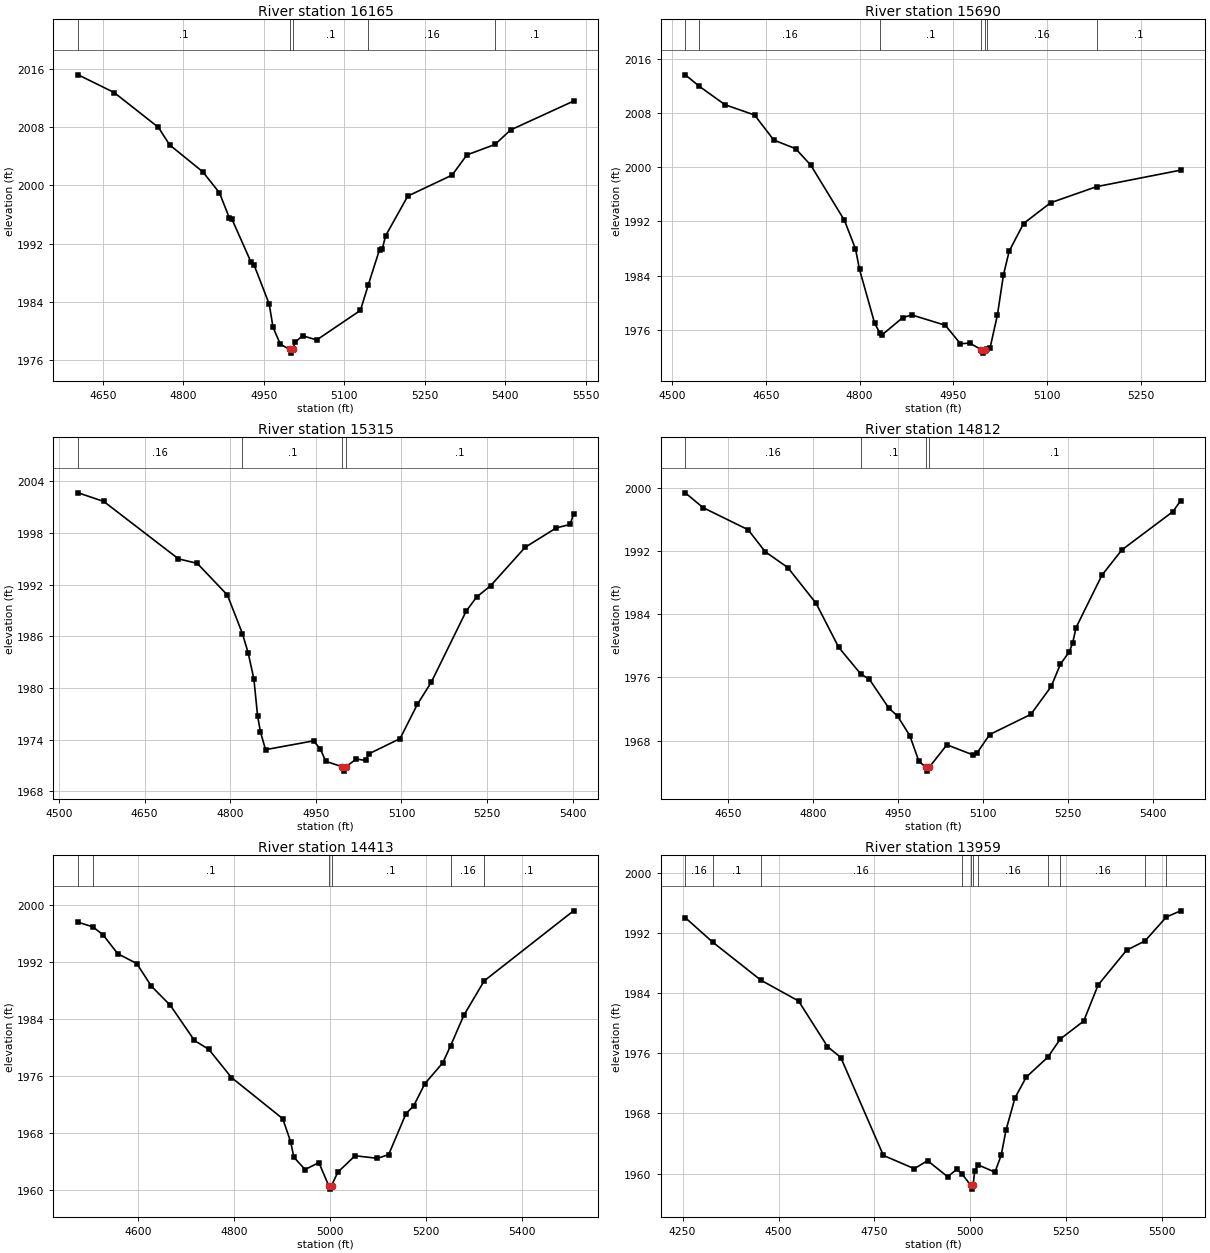
Type RM Length L Ch R = 1 ,16165   ,475,475,475
BEGIN DESCRIPTION:
TROUGH CREEK 36.0
END DESCRIPTION:
XS GIS Cut Line= 2
       2687684.4     10018748.61      2687454.37     10017854.53
#Sta/Elev= 30
  4603.9 2015.17  4670.9 2012.74  4753.5 2007.95  4774.2 2005.56  4836.1 2001.85
  4867.1 1998.98  4885.6 1995.53  4890.7 1995.31  4926.3  1989.4  4931.5  1989.1
    4960 1983.67    4967 1980.51  4980.7 1978.17  4998.3 1977.45  5001.1 1976.95
  5004.3 1977.45  5007.7 1978.41    5022 1979.34  5048.5 1978.76  5129.9 1982.82
  5144.6 1986.33  5165.5 1991.16  5170.6 1991.25  5176.9 1993.07  5218.2 1998.52
  5300.8  2001.4  5328.3 2004.17  5380.8 2005.61  5409.8  2007.6  5527.1 2011.56
#Mann= 5 ,-1 , 0
  4603.9      .1       0  4998.3     .07       0  5004.3      .1       0
  5144.6     .16       0  5380.8      .1       0
Bank Sta=4998.3,5004.3
XS Rating Curve= 0 ,0
Exp/Cntr=0.3,0.1

Type RM Length L Ch R = 1 ,15690   ,375,375,375
BEGIN DESCRIPTION:
TROUGH CREEK 35.0
END DESCRIPTION:
XS GIS Cut Line= 2
       2688157.5     10018596.73      2687862.91     10017860.26
#Sta/Elev= 30
    4521 2013.67  4543.6 2011.96  4584.6 2009.25  4631.9 2007.73  4662.7 2004.03
  4697.7 2002.75  4721.9 2000.32  4775.8 1992.16  4793.5 1987.95    4800  1984.9
  4824.2 1976.94  4832.3 1975.55  4836.6 1975.27  4868.9 1977.76  4883.5 1978.18
  4937.3 1976.65  4961.6 1973.92  4976.6 1974.01  4995.1 1973.03  4997.9 1972.53
  5001.1 1973.03  5003.4  1973.1  5008.9 1973.26  5020.8 1978.17  5030.4 1984.06
  5039.6  1987.6  5062.7 1991.69  5105.8 1994.75  5179.6 1997.14  5314.2 1999.58
#Mann= 7 ,-1 , 0
    4521      .1       0  4543.6     .16       0  4832.3      .1       0
  4995.1     .07       0  5001.1      .1       0  5003.4     .16       0
  5179.6      .1       0
Bank Sta=4995.1,5001.1
XS Rating Curve= 0 ,0
Exp/Cntr=0.3,0.1

Type RM Length L Ch R = 1 ,15315   ,503,503,503
BEGIN DESCRIPTION:
TROUGH CREEK 34.0
END DESCRIPTION:
XS GIS Cut Line= 3
      2688430.94     10018466.53      2688365.84     10018114.96
      2688183.76     10017638.09
#Sta/Elev= 30
  4533.5 2002.64  4578.3 2001.64  4709.2 1994.98  4742.1 1994.46    4795 1990.78
  4821.3 1986.31  4831.3 1984.09  4841.4 1981.04  4847.8 1976.81  4852.9 1974.91
  4861.8 1972.85  4945.9 1973.87  4957.8 1972.93  4967.3  1971.5  4996.4 1970.86
  4999.2 1970.36  5002.4 1970.86  5020.8 1971.76  5037.4  1971.6  5042.7 1972.36
  5097.5 1974.13  5127.9 1978.11  5152.3 1980.68  5213.5 1988.93  5231.8 1990.56
  5256.3 1991.87  5316.7 1996.32  5371.5 1998.58  5395.5 1998.97  5401.5 2000.16
#Mann= 4 ,-1 , 0
  4533.5     .16       0  4821.3      .1       0  4996.4     .07       0
  5002.4      .1       0
Bank Sta=4996.4,5002.4
XS Rating Curve= 0 ,0
Exp/Cntr=0.3,0.1

Type RM Length L Ch R = 1 ,14812   ,399,399,399
BEGIN DESCRIPTION:
TROUGH CREEK 33.0
END DESCRIPTION:
XS GIS Cut Line= 3
      2688834.58     10018214.82      2688843.27     10017923.99
      2688561.14     10017411.82
#Sta/Elev= 30
    4574 1999.34  4605.1 1997.48  4685.1 1994.67  4715.2  1991.9  4755.2 1989.89
  4805.2 1985.37  4845.2  1979.8    4884 1976.45  4899.5 1975.75  4933.8 1972.12
  4949.2 1971.12  4970.9 1968.63    4987 1965.38  4999.3 1964.65    5002 1964.15
  5005.3 1964.65  5036.5 1967.48  5082.2 1966.21  5090.2  1966.5    5112 1968.77
  5184.9 1971.33  5220.9 1974.86    5237 1977.66    5253 1979.25  5258.7 1980.34
  5264.8  1982.3  5310.5 1988.92  5345.9 1992.13  5436.1 1996.97  5449.7 1998.34
#Mann= 4 ,-1 , 0
    4574     .16       0    4884      .1       0  4999.3     .07       0
  5005.3      .1       0
Bank Sta=4999.3,5005.3
XS Rating Curve= 0 ,0
Exp/Cntr=0.3,0.1

Type RM Length L Ch R = 1 ,14413   ,454,454,454
BEGIN DESCRIPTION:
TROUGH CREEK 32.0
END DESCRIPTION:
XS GIS Cut Line= 4
      2689164.45     10018075.87      2689155.77     10017754.72
      2688943.09     10017272.95      2688782.98     10017182.07
#Sta/Elev= 30
  4475.8 1997.55  4506.8 1996.89    4528 1995.76    4558 1993.15    4598 1991.75
    4628 1988.61    4668 1985.88    4718 1980.97    4748 1979.72  4795.1 1975.78
  4901.9 1970.01  4918.4 1966.78  4925.2  1964.6  4948.5 1962.88  4977.3 1963.85
  4997.6 1960.63  5000.4 1960.13  5003.6 1960.63  5016.8 1962.51  5052.7 1964.81
  5099.3 1964.45  5122.6 1964.97  5158.9 1970.73  5174.7  1971.8    5198 1974.91
  5235.4 1977.84  5251.7 1980.23  5279.1 1984.48  5321.7 1989.33  5507.8 1999.15
#Mann= 6 ,-1 , 0
  4475.8     .16       0  4506.8      .1       0  4997.6     .07       0
  5003.6      .1       0  5251.7     .16       0  5321.7      .1       0
Bank Sta=4997.6,5003.6
XS Rating Curve= 0 ,0
Exp/Cntr=0.3,0.1

Type RM Length L Ch R = 1 ,13959   ,691,691,691
BEGIN DESCRIPTION:
TROUGH CREEK 31.0
END DESCRIPTION:
XS GIS Cut Line= 4
      2689377.12     10018075.86      2689455.25     10017455.24
      2689333.72     10017173.12      2688995.22     10017055.95
#Sta/Elev= 30
    4257 1994.07  4328.1 1990.82  4453.9 1985.75  4552.2 1982.97  4627.5 1976.91
  4662.3 1975.44  4773.2 1962.41  4853.8 1960.64  4888.3 1961.71  4940.8 1959.57
  4964.3 1960.55  4977.7 1959.98  5000.9 1958.42  5003.7 1957.92  5006.9 1958.42
  5011.4  1960.4    5021 1961.13  5063.9 1960.18  5080.2 1962.43  5092.9 1965.81
  5116.4  1970.1  5145.5 1972.83  5202.2 1975.52  5234.2 1977.91  5295.3  1980.3
  5332.8  1985.1  5406.9 1989.73    5455 1990.97  5510.7 1994.16  5547.9 1994.98
#Mann= 11 ,-1 , 0
    4257     .16       0  4328.1      .1       0  4453.9     .16       0
  4977.7      .1       0  5000.9     .07       0  5006.9      .1       0
    5021     .16       0  5202.2      .1       0  5234.2     .16       0
    5455      .1       0  5510.7     .16       0
Bank Sta=5000.9,5006.9
XS Rating Curve= 0 ,0
Exp/Cntr=0.3,0.1

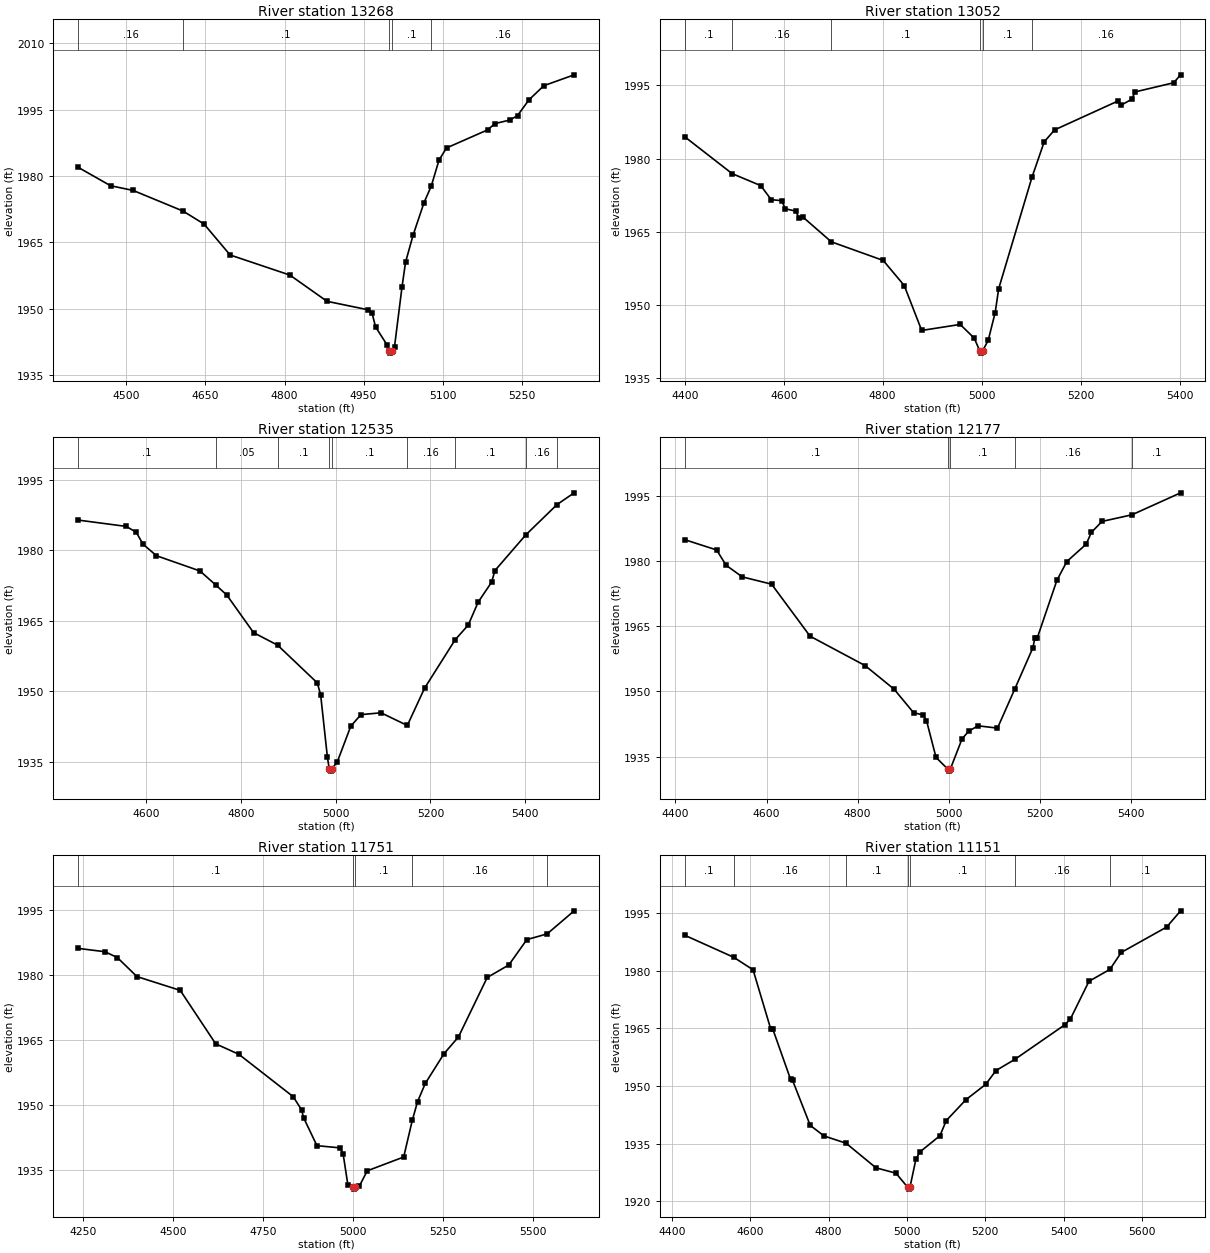
Type RM Length L Ch R = 1 ,13268   ,216,216,216
BEGIN DESCRIPTION:
TROUGH CREEK 30.0
END DESCRIPTION:
XS GIS Cut Line= 2
      2689641.88     10017793.78      2690266.84     10017090.69
#Sta/Elev= 30
  4408.7 1981.96  4470.1 1977.81  4512.8 1976.75  4607.5 1972.09  4647.4 1969.15
  4696.8 1962.17  4810.2 1957.63  4880.7  1951.7  4958.5 1949.79    4966 1949.08
  4972.7 1945.93  4994.4 1941.87  4998.1  1940.5  5000.9    1940  5004.1  1940.5
  5008.7 1941.49  5022.9 1954.97  5029.6 1960.54  5043.8 1966.61  5064.7 1974.02
  5078.4 1977.74  5093.1 1983.61  5107.3 1986.34  5185.1 1990.42  5199.3 1991.85
  5227.8 1992.66    5242 1993.66  5263.7 1997.21  5291.8  2000.4  5349.4 2002.86
#Mann= 5 ,-1 , 0
  4408.7     .16       0  4607.5      .1       0  4998.1     .07       0
  5004.1      .1       0  5078.4     .16       0
Bank Sta=4998.1,5004.1
XS Rating Curve= 0 ,0
Exp/Cntr=0.3,0.1

Type RM Length L Ch R = 1 ,13052   ,517,517,517
BEGIN DESCRIPTION:
TROUGH CREEK 29.0
END DESCRIPTION:
XS GIS Cut Line= 2
       2689741.7     10017954.38       2690443.9     10017239.17
#Sta/Elev= 30
  4399.9 1984.49  4495.8 1976.93  4553.7 1974.47  4574.8 1971.59  4596.1 1971.39
  4603.1 1969.73  4624.4 1969.25  4631.4 1967.75  4638.6 1968.05  4696.3 1962.95
  4801.1 1959.14  4843.6    1954  4878.9 1944.79  4956.7 1946.02    4985 1943.22
  4996.2 1940.64  4998.9 1940.14  5002.2 1940.64  5013.3 1942.75  5027.4 1948.45
  5034.5 1953.34  5101.8 1976.19  5126.5 1983.45  5147.6  1985.9  5274.9 1991.78
    5282 1990.96  5303.2 1992.16  5310.3 1993.68  5388.1 1995.55  5402.2 1997.18
#Mann= 6 ,-1 , 0
  4399.9      .1       0  4495.8     .16       0  4696.3      .1       0
  4996.2     .07       0  5002.2      .1       0  5101.8     .16       0
Bank Sta=4996.2,5002.2
XS Rating Curve= 0 ,0
Exp/Cntr=0.3,0.1

Type RM Length L Ch R = 1 ,12535   ,358,358,358
BEGIN DESCRIPTION:
TROUGH CREEK 28.0
END DESCRIPTION:
XS GIS Cut Line= 2
       2689989.1     10018327.64      2690713.67     10017572.69
#Sta/Elev= 30
  4456.9 1986.48  4558.4 1985.13  4579.4 1983.88  4593.6 1981.35  4621.9 1978.89
  4713.7 1975.64  4746.8 1972.68  4770.3 1970.52  4826.9 1962.49  4877.7 1959.82
  4961.3 1951.79  4968.4 1949.26  4982.6 1936.01  4986.5 1933.48  4989.3 1932.98
  4992.5 1933.48  5003.7    1935    5032 1942.56  5053.4 1945.02  5095.8 1945.41
  5151.3 1942.71  5187.6 1950.64  5252.2 1960.97  5279.8 1964.11  5300.9 1969.02
  5329.2 1973.26  5336.1 1975.72  5401.2 1983.32  5467.2 1989.79  5503.3 1992.29
#Mann= 9 ,-1 , 0
  4456.9      .1       0  4746.8     .05       0  4877.7      .1       0
  4986.5     .07       0  4992.5      .1       0  5151.3     .16       0
  5252.2      .1       0  5401.2     .16       0  5467.2      .1       0
Bank Sta=4986.5,4992.5
XS Rating Curve= 0 ,0
Exp/Cntr=0.3,0.1

Type RM Length L Ch R = 1 ,12177   ,426,426,426
BEGIN DESCRIPTION:
TROUGH CREEK 27.0
END DESCRIPTION:
XS GIS Cut Line= 3
      2690275.56     10018579.37      2690779.03     10017997.77
      2690900.55     10017702.66
#Sta/Elev= 30
  4420.4 1984.87  4490.5 1982.51  4511.4 1978.98  4546.9 1976.32  4611.1 1974.65
  4695.6  1962.7  4816.2 1955.96  4879.9 1950.54  4922.6 1945.15  4943.7  1944.6
  4951.1 1943.32    4972 1934.86  4997.5 1932.21  5000.3 1931.71  5003.5 1932.21
    5029 1939.09  5043.3 1940.85  5064.1 1942.12  5106.9 1941.59  5144.5 1950.49
  5184.8 1960.09    5189 1962.39  5194.5 1962.39  5237.3 1975.54  5259.1 1979.85
  5301.6 1983.85    5313 1986.55  5336.3 1989.06  5401.9 1990.58  5508.8 1995.63
#Mann= 5 ,-1 , 0
  4420.4      .1       0  4997.5     .07       0  5003.5      .1       0
  5144.5     .16       0  5401.9      .1       0
Bank Sta=4997.5,5003.5
XS Rating Curve= 0 ,0
Exp/Cntr=0.3,0.1

Type RM Length L Ch R = 1 ,11751   ,600,600,600
BEGIN DESCRIPTION:
TROUGH CREEK 26.0
END DESCRIPTION:
XS GIS Cut Line= 4
      2690349.32     10018770.35      2690939.62     10018509.93
      2691065.49     10018188.75      2691074.17      10017802.5
#Sta/Elev= 30
  4237.2 1986.24  4311.4 1985.47  4345.7 1984.13  4400.2 1979.73  4520.4 1976.54
  4618.8 1964.19    4683 1961.78  4833.9 1951.98  4857.2 1948.94  4862.7 1947.13
  4899.8 1940.66  4964.2 1940.15  4972.4  1938.8  4985.7 1931.58  4999.2 1931.12
  5001.9 1930.62  5005.2 1931.12  5017.9 1931.38  5039.4 1934.85  5140.5 1938.04
  5164.8 1946.63    5179 1950.81  5200.5 1955.04  5252.4  1961.9  5292.4 1965.76
  5372.4 1979.52  5432.4 1982.41  5482.4 1988.27  5538.7 1989.59  5613.7 1994.92
#Mann= 5 ,-1 , 0
  4237.2      .1       0  4999.2     .07       0  5005.2      .1       0
  5164.8     .16       0  5538.7      .1       0
Bank Sta=4999.2,5005.2
XS Rating Curve= 0 ,0
Exp/Cntr=0.3,0.1

Type RM Length L Ch R = 1 ,11151   ,396,396,396
BEGIN DESCRIPTION:
TROUGH CREEK 25.0
END DESCRIPTION:
XS GIS Cut Line= 3
      2691438.76     10019022.06        2691595.     10018262.53
      2691473.94     10017786.93
#Sta/Elev= 30
  4432.4 1989.18  4557.4 1983.46    4607  1980.2  4652.2 1964.78  4657.3 1964.81
  4702.6 1951.78  4707.7 1951.52  4752.9 1939.78    4788 1937.03  4844.4 1935.14
  4920.7 1928.75  4971.8 1927.35  5001.6 1923.71  5004.4 1923.21  5007.6 1923.71
  5022.8    1931    5033 1932.87  5084.1 1937.09  5100.2 1941.01  5150.5 1946.45
  5200.9 1950.42  5227.2 1954.02    5275  1956.9  5402.7 1965.89  5417.4 1967.46
  5464.6 1977.21    5518  1980.3  5547.1 1984.71  5662.9  1991.3  5698.6 1995.52
#Mann= 7 ,-1 , 0
  4432.4      .1       0  4557.4     .16       0  4844.4      .1       0
  5001.6     .07       0  5007.6      .1       0    5275     .16       0
    5518      .1       0
Bank Sta=5001.6,5007.6
XS Rating Curve= 0 ,0
Exp/Cntr=0.3,0.1

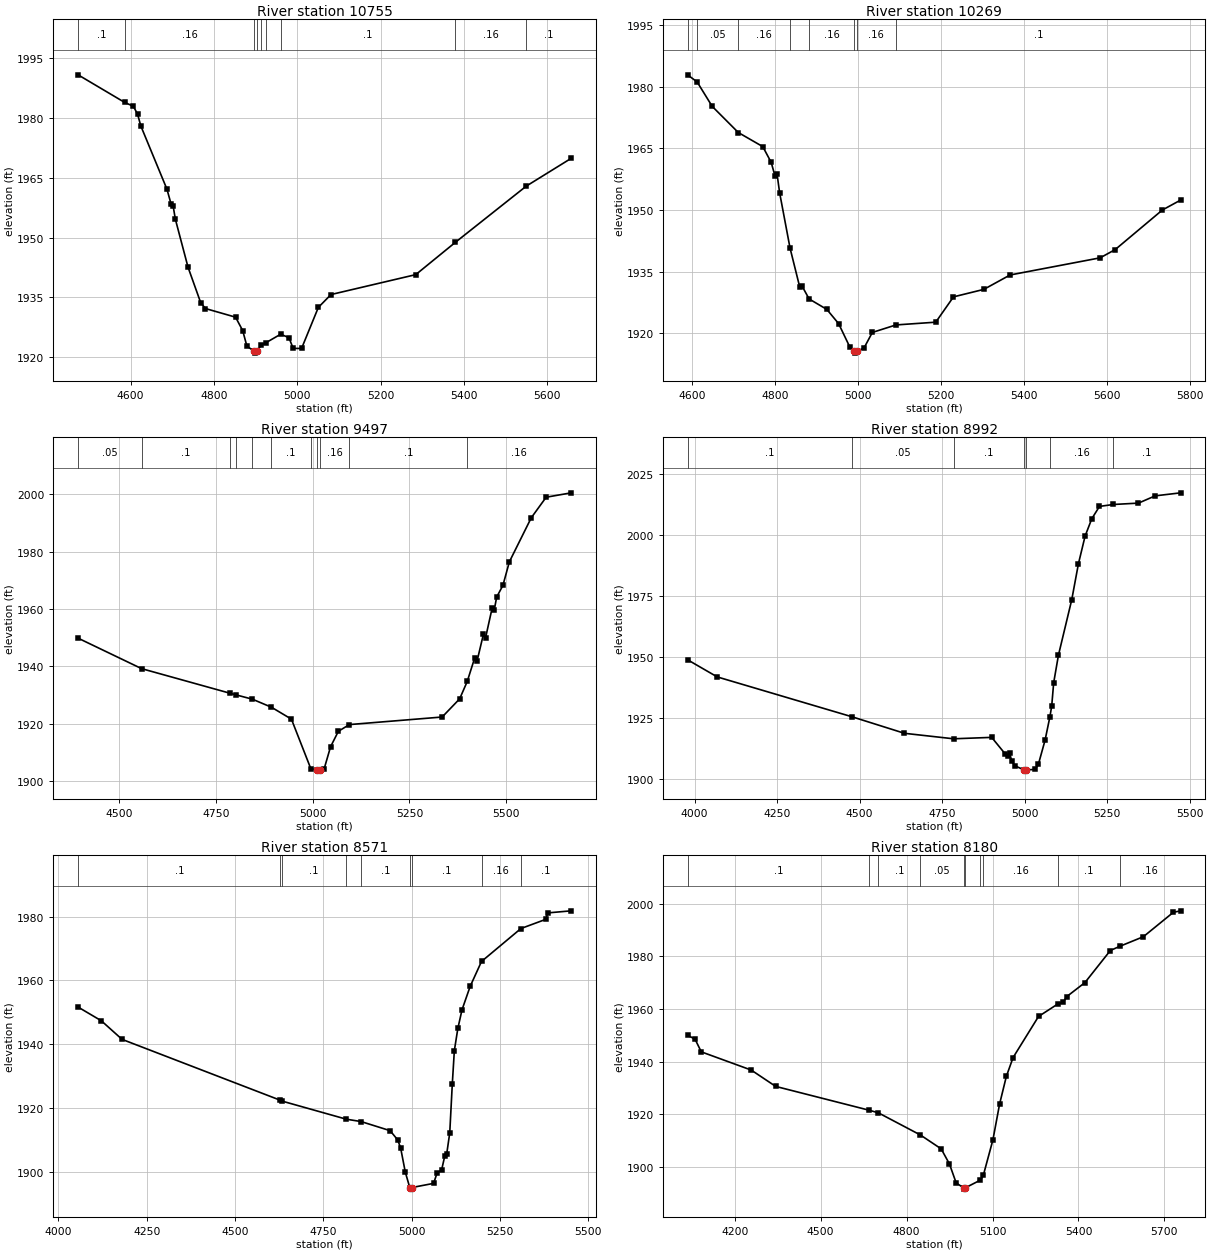
Type RM Length L Ch R = 1 ,10755   ,486,486,486
BEGIN DESCRIPTION:
TROUGH CREEK 24.0
END DESCRIPTION:
XS GIS Cut Line= 3
      2691872.78      10019035.1      2691972.61     10018301.59
      2691864.11     10017871.95
#Sta/Elev= 30
  4474.2 1990.89  4586.2 1983.95  4606.8    1983  4616.9 1981.03  4624.8 1978.05
  4687.5 1962.16  4697.2 1958.51  4702.2    1958  4707.7 1954.62    4738  1942.6
  4768.3 1933.72  4779.7 1932.21  4852.1 1930.04  4869.2 1926.68  4879.3 1922.77
  4896.5 1921.51  4899.2 1921.01  4902.5 1921.51  4914.3 1923.05  4924.3 1923.58
  4960.2 1925.75  4980.2  1924.9  4990.3  1922.2  5010.5 1922.18  5050.8  1932.5
  5081.1 1935.72  5284.5 1940.72  5379.2  1948.8  5549.8 1962.95  5657.6 1969.93
#Mann= 9 ,-1 , 0
  4474.2      .1       0  4586.2     .16       0  4896.5     .07       0
  4902.5     .16       0  4914.3      .1       0  4924.3     .16       0
  4960.2      .1       0  5379.2     .16       0  5549.8      .1       0
Bank Sta=4896.5,4902.5
XS Rating Curve= 0 ,0
Exp/Cntr=0.3,0.1

Type RM Length L Ch R = 1 ,10269   ,772,772,772
BEGIN DESCRIPTION:
TROUGH CREEK 23.0
END DESCRIPTION:
XS GIS Cut Line= 3
      2692337.19     10019022.09      2692432.68     10018466.52
      2692076.76     10017954.36
#Sta/Elev= 30
  4590.1 1982.94  4613.1  1981.2  4649.3 1975.26  4712.2 1968.88  4771.1 1965.45
  4791.4  1961.6  4800.4 1958.34  4805.4 1958.83  4811.7  1954.2  4836.7 1940.76
  4860.3 1931.14  4865.4 1931.52  4882.7 1928.33  4925.3 1925.79  4953.7 1922.32
  4980.2 1916.72  4991.3 1915.63  4994.1 1915.13  4997.3 1915.63  5014.6 1916.33
  5034.9 1920.17  5091.8    1922  5187.6 1922.67  5230.3 1928.84  5303.3 1930.66
  5366.5 1934.17  5583.4 1938.35  5619.7 1940.36  5733.2    1950  5777.5 1952.44
#Mann= 8 ,-1 , 0
  4590.1      .1       0  4613.1     .05       0  4712.2     .16       0
  4836.7      .1       0  4882.7     .16       0  4991.3     .07       0
  4997.3     .16       0  5091.8      .1       0
Bank Sta=4991.3,4997.3
XS Rating Curve= 0 ,0
Exp/Cntr=0.3,0.1

Type RM Length L Ch R = 1 ,9497    ,505,505,505
BEGIN DESCRIPTION:
TROUGH CREEK 21.0
END DESCRIPTION:
XS GIS Cut Line= 4
      2692845.03     10018835.42      2693122.78     10018518.61
      2692992.57     10017971.73      2693122.76     10017711.35
#Sta/Elev= 30
  4393.7 1949.82    4558 1939.17  4785.6 1930.62  4802.2 1930.01  4844.3 1928.51
  4893.4 1925.71  4945.1 1921.55  4995.6 1904.12  5012.3  1903.9  5015.1  1903.4
  5018.3  1903.9  5029.3 1904.01  5046.2 1911.88  5066.4  1917.3  5094.9 1919.65
  5334.7 1922.29  5379.9 1928.63  5399.5  1934.7    5419 1943.02  5424.6 1941.67
  5441.4 1951.22  5446.9 1949.96  5463.7 1960.24  5469.3 1959.64  5475.6 1964.17
  5491.7 1968.23  5508.4 1976.47    5565 1991.85  5603.5 1999.02  5668.3 2000.55
#Mann= 11 ,-1 , 0
  4393.7     .05       0    4558      .1       0  4785.6     .05       0
  4802.2      .1       0  4844.3     .05       0  4893.4      .1       0
  4995.6     .16       0  5012.3     .07       0  5018.3     .16       0
  5094.9      .1       0  5399.5     .16       0
Bank Sta=5012.3,5018.3
XS Rating Curve= 0 ,0
Exp/Cntr=0.3,0.1

Type RM Length L Ch R = 1 ,8992    ,421,421,421
BEGIN DESCRIPTION:
TROUGH CREEK 20.0
END DESCRIPTION:
XS GIS Cut Line= 3
      2692884.08      10018852.8      2693487.36     10018444.82
      2693599.95     10017687.02
#Sta/Elev= 30
  3978.7 1948.78  4068.5 1941.75  4477.2 1925.38  4635.9 1918.61  4784.7 1916.36
  4900.2 1916.94  4940.6 1910.23  4949.2  1909.4  4954.2 1910.73  4960.8 1907.21
  4970.9 1905.25  4998.3 1903.59    5001 1903.09  5004.3 1903.59  5031.6 1903.79
  5041.7  1905.9  5061.9 1915.77  5076.7 1925.47  5082.1 1929.85    5088 1939.34
  5102.4 1950.64  5142.8 1973.44    5163 1988.17  5183.2 1999.52  5203.5 2006.66
  5226.8 2011.72  5269.2 2012.51    5345 2013.07  5395.6 2016.05  5473.1 2017.29
#Mann= 7 ,-1 , 0
  3978.7      .1       0  4477.2     .05       0  4784.7      .1       0
  4998.3     .07       0  5004.3      .1       0  5076.7     .16       0
  5269.2      .1       0
Bank Sta=4998.3,5004.3
XS Rating Curve= 0 ,0
Exp/Cntr=0.3,0.1

Type RM Length L Ch R = 1 ,8571    ,391,391,391
BEGIN DESCRIPTION:
TROUGH CREEK 19.0
END DESCRIPTION:
XS GIS Cut Line= 3
      2692910.14     10018943.94      2693912.71     10018358.02
      2693899.69     10018123.61
#Sta/Elev= 30
  4055.9 1951.66  4121.7 1947.37  4180.4 1941.55  4628.8 1922.48  4633.6 1922.22
  4815.1 1916.57  4856.9 1915.83  4939.1 1912.98  4960.6  1910.1    4969 1907.56
  4982.1 1900.03  4994.8 1895.18  4997.6 1894.68  5000.8 1895.18  5062.3 1896.48
  5072.2 1899.75  5084.8 1900.58  5093.7 1904.95  5099.5 1905.77    5108 1912.29
  5115.2 1927.55    5121 1938.02  5130.9 1944.96  5142.7  1950.8  5165.9 1958.17
  5197.9 1965.93  5309.5 1976.24  5380.2 1979.13  5385.2 1981.13  5451.9 1981.78
#Mann= 9 ,-1 , 0
  4055.9      .1       0  4628.8     .05       0  4633.6      .1       0
  4815.1     .05       0  4856.9      .1       0  4994.8     .07       0
  5000.8      .1       0  5197.9     .16       0  5309.5      .1       0
Bank Sta=4994.8,5000.8
XS Rating Curve= 0 ,0
Exp/Cntr=0.3,0.1

Type RM Length L Ch R = 1 ,8180    ,406,406,406
BEGIN DESCRIPTION:
TROUGH CREEK 18.0
END DESCRIPTION:
XS GIS Cut Line= 2
      2693044.64     10019182.68      2694623.98     10018497.14
#Sta/Elev= 30
  4035.5 1950.04  4061.5 1948.54  4083.3 1943.73  4257.7 1936.81  4343.1  1930.6
  4669.9 1921.54  4701.5 1920.57  4848.5 1912.14  4920.8 1906.88  4949.7 1901.14
  4973.2 1893.93  4999.1 1892.09  5001.9 1891.59  5005.1 1892.09  5057.4    1895
  5067.8 1896.77  5101.4 1910.31  5124.8 1923.94  5148.3 1934.41  5171.8 1941.56
  5260.6 1957.16  5329.4 1962.01  5346.9 1962.55  5358.7 1964.67  5422.7 1970.04
  5511.4 1982.22  5544.1  1983.8  5626.7 1987.46  5731.5 1996.74  5757.2 1997.29
#Mann= 10 ,-1 , 0
  4035.5      .1       0  4669.9     .05       0  4701.5      .1       0
  4848.5     .05       0  4999.1    .035       0  5005.1     .05       0
  5057.4      .1       0  5067.8     .16       0  5329.4      .1       0
  5544.1     .16       0
Bank Sta=4999.1,5005.1
XS Rating Curve= 0 ,0
Exp/Cntr=0.3,0.1

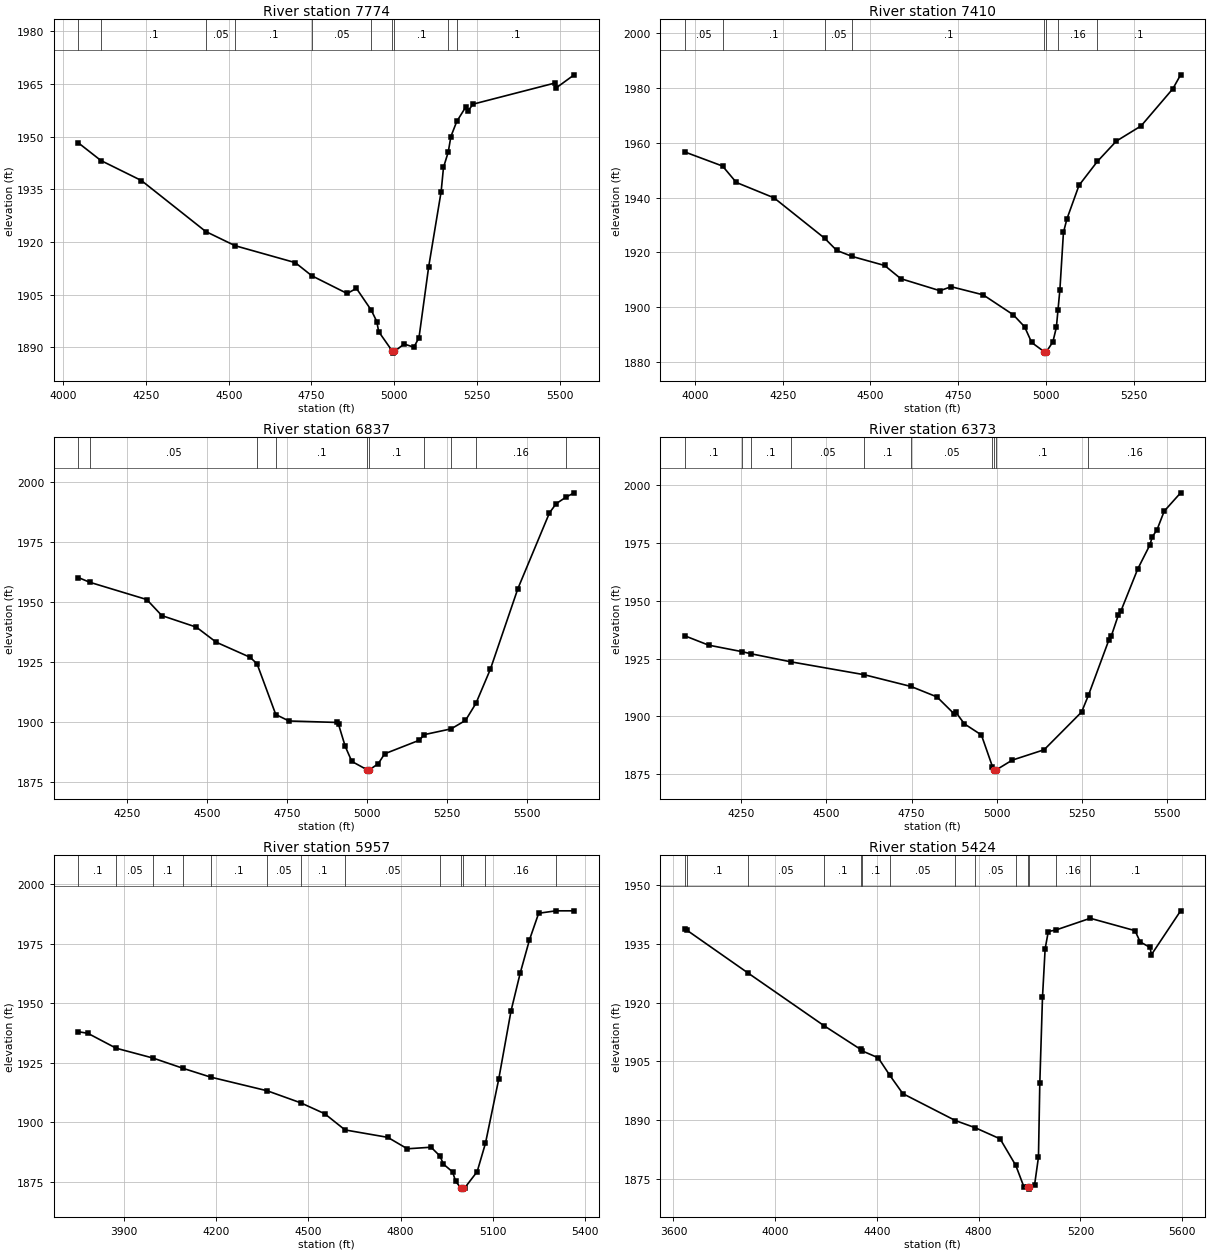
Type RM Length L Ch R = 1 ,7774    ,364,364,364
BEGIN DESCRIPTION:
TROUGH CREEK 17.0
END DESCRIPTION:
XS GIS Cut Line= 3
      2693266.01     10019599.34      2693838.93     10019291.18
       2694598.5     10018913.56
#Sta/Elev= 30
  4045.3 1948.26  4113.6 1943.22    4236 1937.52  4430.4    1923    4519 1918.96
  4701.1 1914.13  4750.9  1910.4  4857.9 1905.34  4885.9  1906.8  4930.7  1900.6
  4947.5 1897.36  4953.1 1894.49  4994.9 1888.85  4997.6 1888.35  5000.9 1888.85
  5030.3 1890.95  5059.5 1890.04    5075 1892.73  5104.3 1912.93    5142 1934.37
  5149.1 1941.25  5163.5 1945.66  5171.5 1950.06  5189.2 1954.35  5216.3 1958.45
  5221.9  1957.2  5238.7 1959.29  5485.1 1965.28  5490.7 1963.98  5544.1 1967.64
#Mann= 10 ,-1 , 0
  4045.3     .05       0  4113.6      .1       0  4430.4     .05       0
    4519      .1       0  4750.9     .05       0  4930.7      .1       0
  4994.9     .07       0  5000.9      .1       0  5163.5     .16       0
  5189.2      .1       0
Bank Sta=4994.9,5000.9
XS Rating Curve= 0 ,0
Exp/Cntr=0.3,0.1

Type RM Length L Ch R = 1 ,7410    ,573,573,573
BEGIN DESCRIPTION:
TROUGH CREEK 16.0
END DESCRIPTION:
XS GIS Cut Line= 3
      2693305.03     10019785.99      2693938.75     10019495.17
      2694650.51     10019417.05
#Sta/Elev= 30
    3971 1956.67  4078.6 1951.52  4117.8 1945.53  4225.3  1939.9  4369.4 1925.15
  4403.9 1920.69  4448.3 1918.46  4540.6 1915.17  4586.6 1910.35  4698.2 1905.95
  4730.3 1907.41  4821.4 1904.44  4907.5 1897.13  4939.6 1892.75  4959.7 1887.02
  4995.6 1883.63  4998.3 1883.13  5001.6 1883.63  5020.1 1887.22  5030.1 1892.53
  5034.7 1898.84  5040.2 1906.38  5050.3 1927.26  5060.3 1932.23  5094.7 1944.48
  5147.1 1953.22  5201.2 1960.65  5271.6 1966.19  5362.1 1979.77  5384.3 1984.87
#Mann= 8 ,-1 , 0
    3971     .05       0  4078.6      .1       0  4369.4     .05       0
  4448.3      .1       0  4995.6     .07       0  5001.6      .1       0
  5034.7     .16       0  5147.1      .1       0
Bank Sta=4995.6,5001.6
XS Rating Curve= 0 ,0
Exp/Cntr=0.3,0.1

Type RM Length L Ch R = 1 ,6837    ,464,464,464
BEGIN DESCRIPTION:
TROUGH CREEK 15.0
END DESCRIPTION:
XS GIS Cut Line= 3
      2693491.66     10020246.05      2694520.35      10019972.6
      2694832.84     10019599.35
#Sta/Elev= 30
  4096.5 1960.27  4132.3 1958.29  4310.5 1951.09  4357.8 1944.38  4465.7 1939.57
  4527.8 1933.29  4633.7    1927  4655.5 1924.29  4714.2 1903.11  4755.4 1900.41
  4904.5  1899.8  4910.6 1898.99  4931.3 1889.88    4952 1883.54  5000.8 1879.98
  5003.5 1879.48  5006.8 1879.98  5034.8 1882.59  5054.8 1886.71  5163.3 1892.38
  5178.4  1894.7  5262.8 1897.12  5307.7 1900.64  5340.4 1907.75  5385.8 1922.08
  5471.6 1955.63  5570.5 1987.27  5591.4 1991.09  5622.4 1993.84  5647.7 1995.62
#Mann= 10 ,-1 , 0
  4096.5      .1       0  4132.3     .05       0  4655.5     .16       0
  4714.2      .1       0  5000.8     .07       0  5006.8      .1       0
  5178.4     .16       0  5262.8      .1       0  5340.4     .16       0
  5622.4      .1       0
Bank Sta=5000.8,5006.8
XS Rating Curve= 0 ,0
Exp/Cntr=0.3,0.1

Type RM Length L Ch R = 1 ,6373    ,416,416,416
BEGIN DESCRIPTION:
TROUGH CREEK 14.0
END DESCRIPTION:
XS GIS Cut Line= 4
      2694259.91     10020884.08      2694733.02     10020423.99
      2694772.09     10019920.52      2694984.08      10019721.5
#Sta/Elev= 30
    4084 1934.89  4153.9 1930.85  4251.7 1928.04  4276.9 1927.16  4395.5 1923.62
  4610.6 1918.05    4748 1912.96  4824.4 1908.43  4874.3 1901.15  4879.3  1901.9
  4904.7 1896.78  4954.8 1891.96  4987.3 1878.22  4991.9  1876.8  4994.7  1876.3
  4997.9  1876.8  5045.1 1881.05  5138.9 1885.55  5248.9 1901.88  5269.1 1909.16
  5328.8    1933  5336.2 1934.81  5357.2 1944.03  5364.5 1945.66  5413.8 1963.84
  5449.5 1974.25  5456.3 1977.68  5470.5 1980.85  5491.5 1988.86  5539.7  1996.8
#Mann= 10 ,-1 , 0
    4084      .1       0  4251.7     .05       0  4276.9      .1       0
  4395.5     .05       0  4610.6      .1       0    4748     .05       0
  4987.3      .1       0  4991.9     .07       0  4997.9      .1       0
  5269.1     .16       0
Bank Sta=4991.9,4997.9
XS Rating Curve= 0 ,0
Exp/Cntr=0.3,0.1

Type RM Length L Ch R = 1 ,5957    ,533,533,533
BEGIN DESCRIPTION:
TROUGH CREEK 13.0
END DESCRIPTION:
XS GIS Cut Line= 3
       2694333.7      10020962.2      2695141.01     10020237.36
      2695167.03     10019708.26
#Sta/Elev= 30
  3750.8  1938.1  3781.6 1937.44  3874.1 1931.17  3993.8 1927.05  4093.1 1922.68
  4181.6 1919.05  4365.6 1913.32  4475.7 1908.22  4553.1 1903.68  4619.3 1896.88
  4758.6 1893.76  4822.2 1888.96  4899.5 1889.62  4928.6 1885.91  4939.5 1882.56
  4969.6 1879.26  4979.6 1875.28  4996.6 1872.53  4999.3 1872.03  5002.6 1872.53
  5009.6 1872.64  5049.6 1879.35  5076.6 1891.25  5119.7 1918.09  5159.8 1946.76
  5189.8  1962.7  5219.9 1976.63  5249.9 1987.82  5306.2 1988.84  5365.5 1988.84
#Mann= 13 ,-1 , 0
  3750.8      .1       0  3874.1     .05       0  3993.8      .1       0
  4093.1     .05       0  4181.6      .1       0  4365.6     .05       0
  4475.7      .1       0  4619.3     .05       0  4928.6      .1       0
  4996.6     .07       0  5002.6      .1       0  5076.6     .16       0
  5306.2      .1       0
Bank Sta=4996.6,5002.6
XS Rating Curve= 0 ,0
Exp/Cntr=0.3,0.1

Type RM Length L Ch R = 1 ,5424    ,363,363,363
BEGIN DESCRIPTION:
TROUGH CREEK 12.0
END DESCRIPTION:
XS GIS Cut Line= 4
      2694377.13     10021044.64      2694932.68     10020549.86
      2695631.46     10020345.86      2695726.77     10019877.96
#Sta/Elev= 30
  3644.6 1938.72  3652.4 1938.44  3894.2 1927.47  4192.7 1914.06  4335.8 1908.06
  4341.3 1907.69    4405 1905.91  4450.6 1901.45  4501.8 1896.78  4708.5 1889.92
  4786.2  1888.1  4884.2 1885.26    4946 1878.48  4977.9 1873.02  4993.4 1872.95
  4996.1 1872.45  4999.4 1872.95  5019.6 1873.42  5035.1 1880.61  5040.4 1899.55
  5050.9  1921.3  5061.3 1933.68  5073.7 1938.08  5103.8 1938.48  5238.7 1941.46
  5414.6 1938.31    5435 1935.44    5474 1934.02  5479.1 1932.18    5594 1943.36
#Mann= 14 ,-1 , 0
  3644.6     .05       0  3652.4      .1       0  3894.2     .05       0
  4192.7      .1       0  4335.8     .05       0  4341.3      .1       0
  4450.6     .05       0  4708.5      .1       0  4786.2     .05       0
    4946      .1       0  4993.4     .07       0  4999.4      .1       0
  5103.8     .16       0  5238.7      .1       0
Bank Sta=4993.4,4999.4
XS Rating Curve= 0 ,0
Exp/Cntr=0.3,0.1

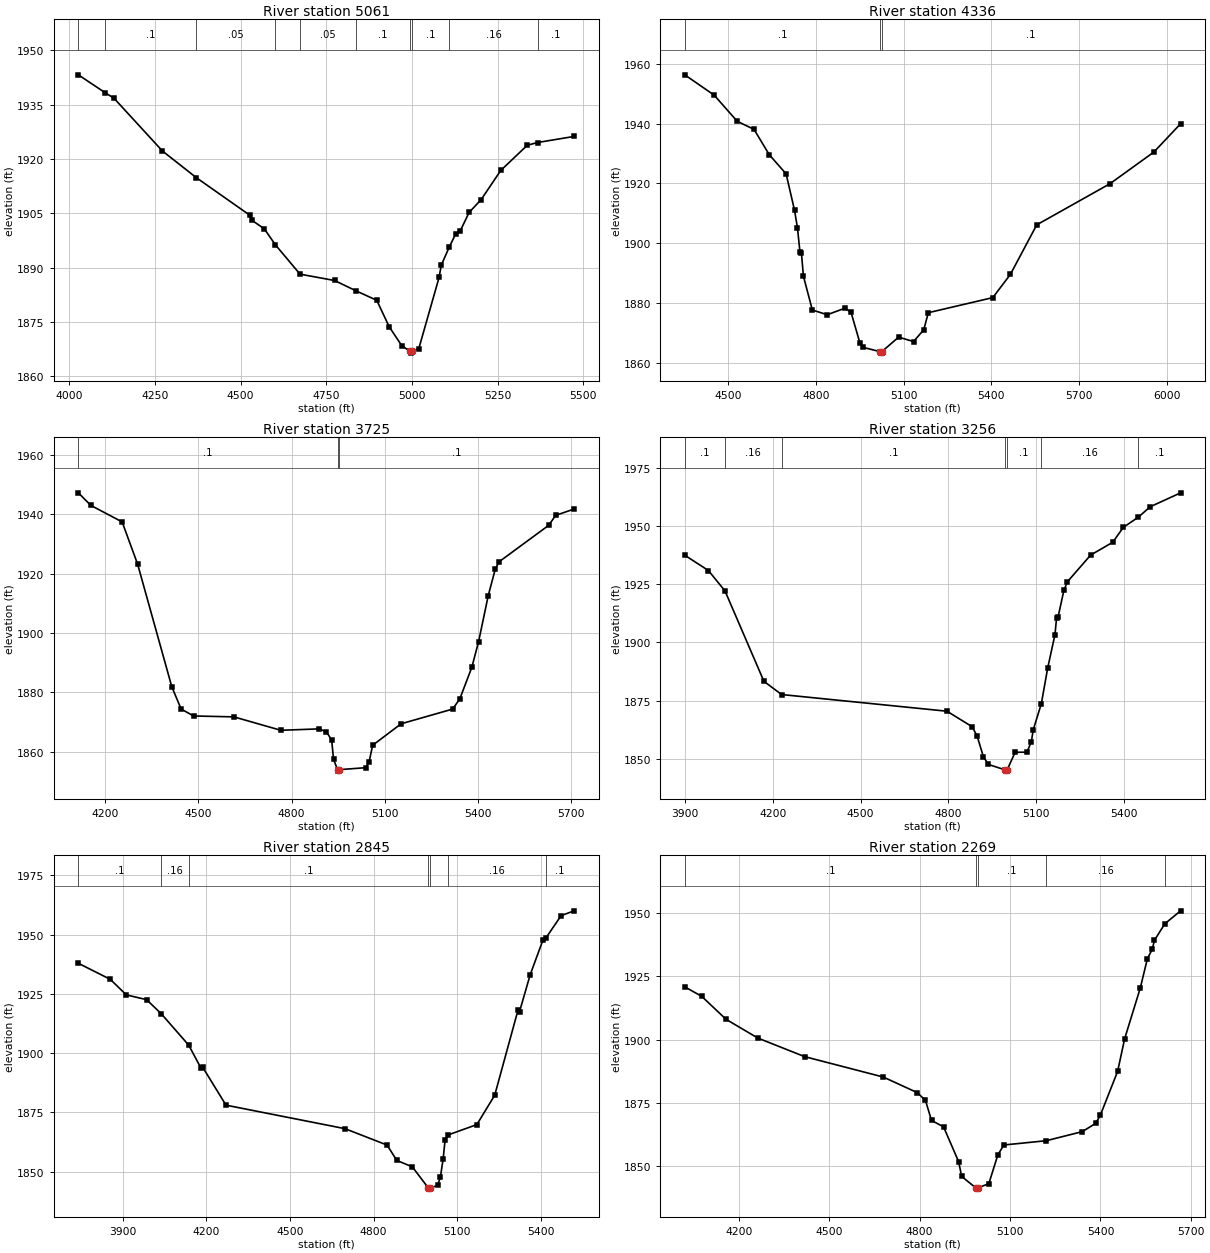
Type RM Length L Ch R = 1 ,5061    ,725,725,725
BEGIN DESCRIPTION:
TROUGH CREEK 11.0
END DESCRIPTION:
XS GIS Cut Line= 4
      2694911.01     10021383.16      2695444.83     10020836.32
      2695739.97     10020649.68       2695813.6     10020324.82
#Sta/Elev= 30
  4026.8 1943.24  4104.6 1938.33  4130.7 1936.79  4272.1 1922.21  4371.2 1914.83
  4526.7 1904.49  4533.7 1903.03  4569.2 1900.73  4601.9 1896.27  4673.5 1888.19
  4774.2 1886.44  4838.3 1883.52  4897.3 1880.98  4933.8 1873.65  4970.2 1868.46
  4994.3 1866.88  4997.1 1866.38  5000.3 1866.88  5020.1 1867.64  5079.3 1887.31
  5085.5 1890.63  5108.7 1895.63  5127.9 1899.34  5140.2 1899.98  5166.8 1905.23
    5202 1908.79  5259.1 1916.82  5336.5 1923.79  5366.7 1924.55  5473.3 1926.23
#Mann= 10 ,-1 , 0
  4026.8     .05       0  4104.6      .1       0  4371.2     .05       0
  4601.9      .1       0  4673.5     .05       0  4838.3      .1       0
  4994.3     .07       0  5000.3      .1       0  5108.7     .16       0
  5366.7      .1       0
Bank Sta=4994.3,5000.3
XS Rating Curve= 0 ,0
Exp/Cntr=0.3,0.1

Type RM Length L Ch R = 1 ,4336    ,611,611,611
BEGIN DESCRIPTION:
TROUGH CREEK 9.0
END DESCRIPTION:
XS GIS Cut Line= 3
      2695939.61     10021882.35      2696091.53     10021079.37
      2696147.96     10020202.61
#Sta/Elev= 30
  4351.3 1956.33  4451.7 1949.54  4530.7 1940.78  4588.1 1938.09  4640.5 1929.57
  4697.9 1923.21  4726.5 1911.05  4736.6  1905.2  4745.2 1897.04  4750.2 1896.71
    4757    1889  4787.5 1877.69  4838.4 1876.11  4899.5 1878.31  4919.8 1876.93
  4950.4  1866.6  4959.6 1865.23  5019.1 1863.77  5021.9 1863.27  5025.1 1863.77
  5082.7 1868.62  5133.6 1867.14  5168.5 1871.08  5184.2 1876.79  5404.7 1881.83
  5464.8 1889.59    5555 1906.17  5805.5 1919.92  5955.8 1930.52  6047.1 1939.98
#Mann= 3 ,-1 , 0
  4351.3      .1       0  5019.1     .07       0  5025.1      .1       0
Bank Sta=5019.1,5025.1
XS Rating Curve= 0 ,0
Exp/Cntr=0.3,0.1

Type RM Length L Ch R = 1 ,3725    ,469,469,469
BEGIN DESCRIPTION:
TROUGH CREEK 8.0
END DESCRIPTION:
XS GIS Cut Line= 3
      2696581.98     10021734.74      2696603.68     10021079.37
      2696208.71     10020224.32
#Sta/Elev= 30
  4113.1 1947.25  4153.5 1943.01  4254.2 1937.45  4304.2 1923.19  4414.3 1881.88
  4444.3  1874.4  4484.3 1872.06  4614.4 1871.75  4765.6 1867.23  4889.6 1867.71
  4912.6 1866.66  4929.3 1863.99  4935.5 1857.42  4948.3 1853.97    4951 1853.47
  4954.3 1853.97  5039.4 1854.63  5050.2  1856.7  5061.4 1862.18    5153 1869.42
  5319.1 1874.38    5342 1877.76  5380.9 1888.43  5402.9 1897.15  5433.8 1912.59
  5456.7  1921.6    5469 1924.03  5628.3 1936.27  5651.2 1939.65  5710.7  1941.8
#Mann= 3 ,-1 , 0
  4113.1      .1       0  4948.3     .07       0  4954.3      .1       0
Bank Sta=4948.3,4954.3
XS Rating Curve= 0 ,0
Exp/Cntr=0.3,0.1

Type RM Length L Ch R = 1 ,3256    ,411,411,411
BEGIN DESCRIPTION:
TROUGH CREEK 7.0
END DESCRIPTION:
XS GIS Cut Line= 4
      2696855.42      10021613.2      2696972.61     10020957.84
      2696707.85     10020237.36      2696492.18     10020086.39
#Sta/Elev= 30
  3898.2  1937.4  3978.9 1930.85  4035.7 1922.11    4169 1883.28  4229.4 1877.62
  4795.4 1870.46  4881.5  1863.8  4898.6 1859.75  4919.9 1850.94  4937.1 1847.62
  4995.1 1845.25  4997.8 1844.75  5001.1 1845.25  5028.5 1852.84  5069.1 1852.88
  5084.2 1857.46  5090.4 1862.47  5118.2  1873.7  5139.8 1888.93  5164.9 1903.35
  5170.3  1910.5  5175.6    1911  5195.4 1922.34  5207.6 1926.05  5286.9 1937.48
  5362.7 1942.98  5398.4 1949.33  5450.1 1953.76  5490.8 1958.21  5594.8 1964.19
#Mann= 7 ,-1 , 0
  3898.2      .1       0  4035.7     .16       0  4229.4      .1       0
  4995.1     .07       0  5001.1      .1       0  5118.2     .16       0
  5450.1      .1       0
Bank Sta=4995.1,5001.1
XS Rating Curve= 0 ,0
Exp/Cntr=0.3,0.1

Type RM Length L Ch R = 1 ,2845    ,576,576,576
BEGIN DESCRIPTION:
TROUGH CREEK 6.0
END DESCRIPTION:
XS GIS Cut Line= 3
      2696911.83     10021695.71      2697115.84     10021378.85
      2697276.24     10019987.22
#Sta/Elev= 30
  3741.6 1937.88  3856.2  1931.1  3913.6 1924.54  3986.3 1922.53  4039.4 1916.52
  4137.5  1903.3    4182 1893.49  4187.1 1894.09    4271 1878.01  4697.4  1868.1
  4848.4 1861.18  4883.7 1854.67    4939    1852  4996.4 1843.08  4999.1 1842.58
  5002.4 1843.08  5029.6 1844.13  5039.6 1847.58  5049.7 1855.43  5056.6  1863.4
  5067.5 1865.45  5170.5 1869.82  5234.5 1882.22  5318.4  1918.3  5323.5  1917.5
  5361.7 1933.06  5407.4 1947.69  5418.1 1948.56  5472.5 1957.98  5519.3 1960.01
#Mann= 7 ,-1 , 0
  3741.6      .1       0  4039.4     .16       0  4137.5      .1       0
  4996.4     .07       0  5002.4      .1       0  5067.5     .16       0
  5418.1      .1       0
Bank Sta=4996.4,5002.4
XS Rating Curve= 0 ,0
Exp/Cntr=0.3,0.1

Type RM Length L Ch R = 1 ,2269    ,595,595,595
BEGIN DESCRIPTION:
TROUGH CREEK 5.0
END DESCRIPTION:
XS GIS Cut Line= 4
       2697823.3     10021569.78      2697771.22     10020936.14
      2697784.24     10020163.57      2697689.21     10019947.61
#Sta/Elev= 30
  4021.4 1920.85  4077.6  1917.1  4157.9 1908.06  4263.4 1900.64  4418.8  1893.3
  4679.6 1885.24  4792.6 1879.07  4819.6    1876  4839.6  1868.1  4879.6 1865.56
  4929.6  1851.8  4939.6 1845.98  4986.6 1841.47  4989.4 1840.97  4992.6 1841.47
  5029.6 1843.08  5059.6  1854.5  5079.6  1858.4  5220.1 1860.09  5339.7 1863.68
  5384.4 1866.96  5399.7 1870.22  5456.8 1887.45  5480.1 1900.34  5532.3 1920.52
  5555.6 1932.01  5571.7 1935.69    5579 1939.23  5613.2 1945.75  5665.8 1950.88
#Mann= 5 ,-1 , 0
  4021.4      .1       0  4986.6     .07       0  4992.6      .1       0
  5220.1     .16       0  5613.2      .1       0
Bank Sta=4986.6,4992.6
XS Rating Curve= 0 ,0
Exp/Cntr=0.3,0.1