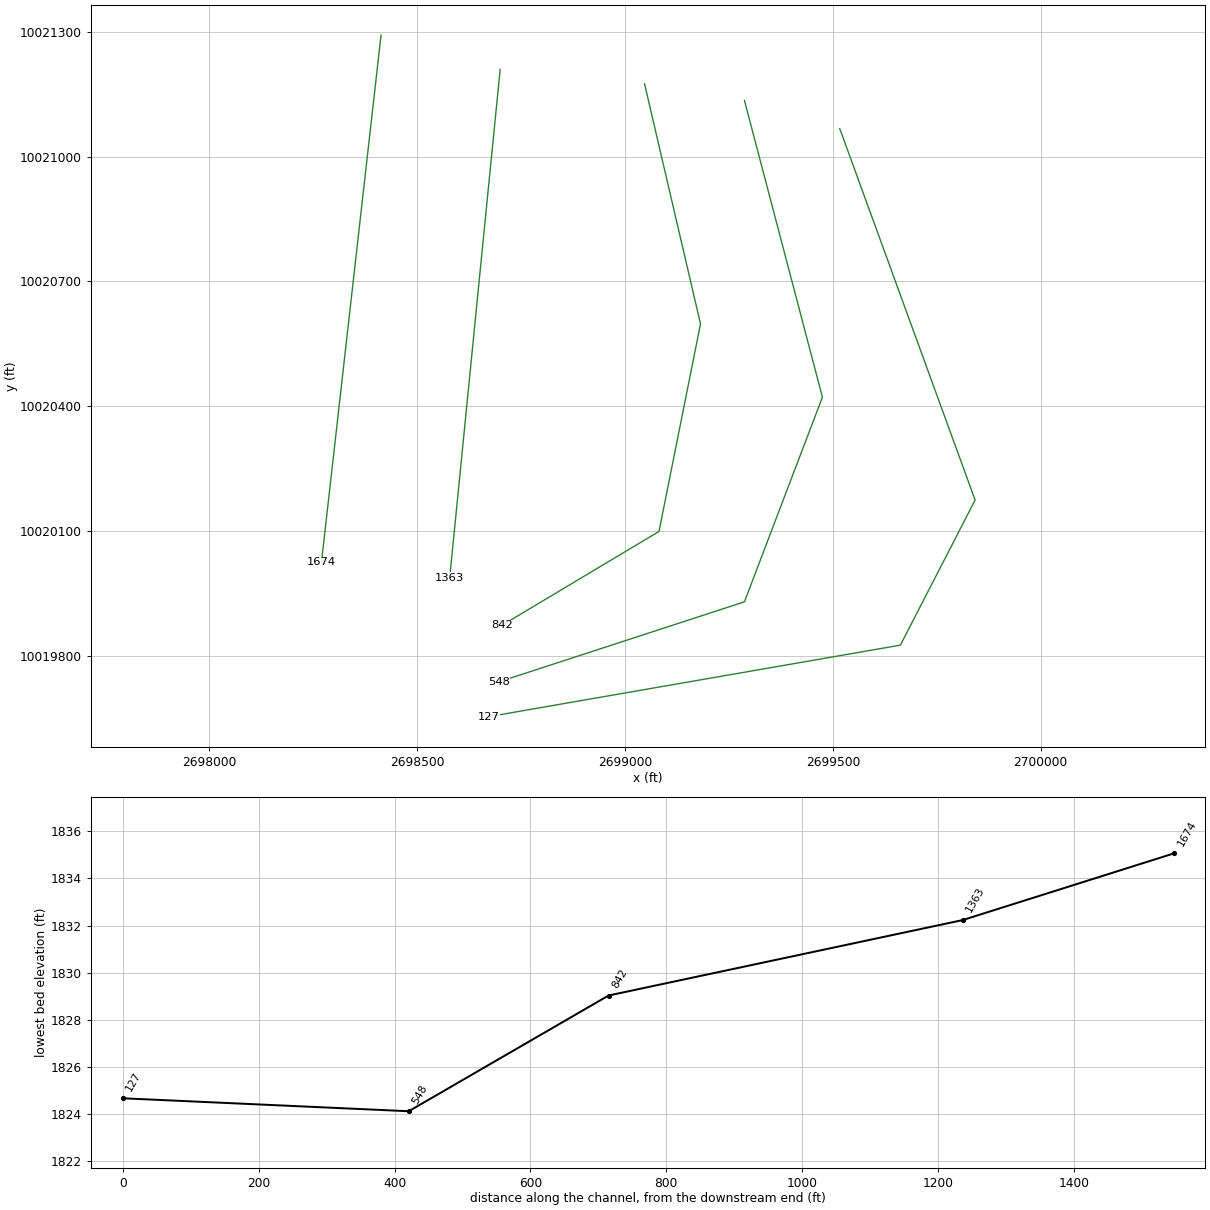
HEC-RAS study TROUGH CREEK.prj: TROUGH CREEK Base Level Engineering

--- TROUGH CREEK.g01 (geometry) --- (continued)

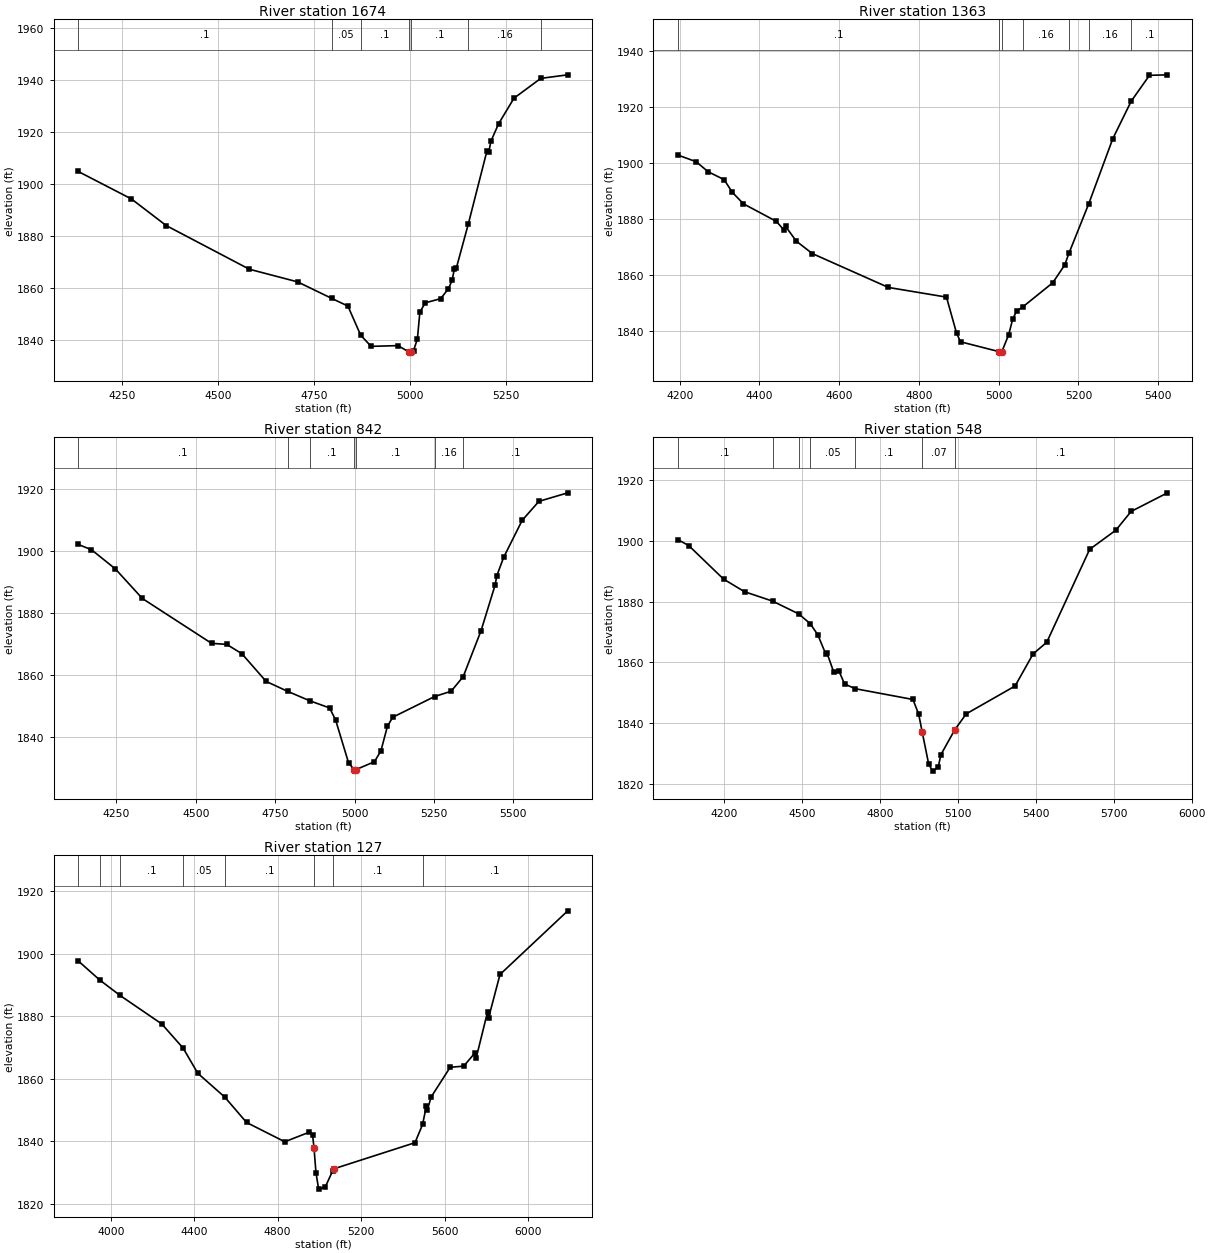
Type RM Length L Ch R = 1 ,1674    ,311,311,311
BEGIN DESCRIPTION:
TROUGH CREEK 4.0
END DESCRIPTION:
XS GIS Cut Line= 2
      2698413.58     10021292.06      2698270.35     10020024.73
#Sta/Elev= 30
  4135.3 1904.91  4274.5  1894.3  4365.1 1884.07  4581.5  1867.3  4707.2 1862.44
  4796.1 1856.09  4838.1 1853.15  4871.4 1841.97  4898.5 1837.66  4968.9 1837.95
  4996.1 1835.56  4998.8 1835.06  5002.1 1835.56  5009.2 1836.02  5019.2 1840.58
  5025.5 1850.75  5039.3 1854.38  5079.6 1855.98  5099.7 1859.76  5109.8 1863.12
  5115.3 1867.46  5120.4 1867.67  5151.6 1884.62  5200.1 1912.66  5205.1 1912.21
  5210.4 1916.42  5230.6 1923.21  5270.8 1933.05  5340.6 1940.65  5410.7 1942.01
#Mann= 7 ,-1 , 0
  4135.3      .1       0  4796.1     .05       0  4871.4      .1       0
  4996.1     .07       0  5002.1      .1       0  5151.6     .16       0
  5340.6      .1       0
Bank Sta=4996.1,5002.1
XS Rating Curve= 0 ,0
Exp/Cntr=0.3,0.1

Type RM Length L Ch R = 1 ,1363    ,521,521,521
BEGIN DESCRIPTION:
TROUGH CREEK 3.0
END DESCRIPTION:
XS GIS Cut Line= 2
      2698700.04     10021209.58      2698578.66     10019987.19
#Sta/Elev= 30
  4195.1 1902.94  4241.2 1900.55  4271.3 1896.97  4311.5 1894.14  4331.6 1889.67
  4359.8 1885.52  4442.2 1879.27  4460.6 1876.31  4465.6 1877.45  4492.4  1872.2
  4532.6 1867.76  4723.5 1855.67  4869.1 1852.22  4894.4 1839.35  4904.4 1836.27
  5001.9 1832.73  5004.7 1832.23  5007.9 1832.73    5025 1838.74  5035.1 1844.31
  5045.1 1847.27  5060.9 1848.77  5135.6 1857.33  5165.7 1863.69  5176.6 1867.99
    5226 1885.55  5286.3 1908.77  5332.5 1922.16  5378.3 1931.38  5423.5 1931.56
#Mann= 7 ,-1 , 0
  4195.1      .1       0  5001.9     .07       0  5007.9      .1       0
  5060.9     .16       0  5176.6      .1       0    5226     .16       0
  5332.5      .1       0
Bank Sta=5001.9,5007.9
XS Rating Curve= 0 ,0
Exp/Cntr=0.3,0.1

Type RM Length L Ch R = 1 ,842     ,294,294,294
BEGIN DESCRIPTION:
TROUGH CREEK 2.0
END DESCRIPTION:
XS GIS Cut Line= 4
      2699047.26     10021174.85      2699181.81      10020597.6
      2699081.98     10020098.47      2698704.34     10019872.75
#Sta/Elev= 30
  4129.3 1902.08  4171.5 1900.37  4246.6  1894.2  4331.8 1884.65  4549.7  1870.2
  4597.4 1869.86  4645.1 1866.86  4721.4 1857.94  4788.8 1854.75  4859.5 1851.67
  4921.2 1849.39  4940.1 1845.55  4980.9 1831.73  4998.3 1829.53  5001.1 1829.03
  5004.3 1829.53  5062.5 1832.06  5082.9 1835.58  5103.3 1843.47    5120 1846.39
    5252 1853.07  5303.9 1854.76  5341.9 1859.48  5398.2 1874.31    5442 1888.87
  5447.8    1892  5469.2  1897.9  5527.6 1909.83  5580.1 1915.94    5671 1918.69
#Mann= 7 ,-1 , 0
  4129.3      .1       0  4788.8     .05       0  4859.5      .1       0
  4998.3     .07       0  5004.3      .1       0    5252     .16       0
  5341.9      .1       0
Bank Sta=4998.3,5004.3
XS Rating Curve= 0 ,0
Exp/Cntr=0.3,0.1

Type RM Length L Ch R = 1 ,548     ,421,421,421
BEGIN DESCRIPTION:
Mapping XS 824ca0a4
END DESCRIPTION:
XS GIS Cut Line= 4
      2699287.46     10021134.93      2699474.95     10020421.43
      2699287.45     10019929.24      2698696.28     10019736.53
#Sta/Elev= 30
  4020.7 1900.47  4063.3 1898.44  4197.1 1887.41  4277.8 1883.26  4385.6 1880.17
  4486.2 1875.96    4531 1872.72  4560.3 1869.01  4590.3 1862.78  4595.5 1863.03
  4621.6 1856.71  4642.3 1856.97    4663 1852.85  4704.3 1851.29  4926.5 1847.74
  4948.6 1842.88  4961.9  1837.1  4986.7  1826.6  5001.8 1824.12  5023.5 1825.36
  5034.2 1829.55  5087.7 1837.77  5131.8    1843  5319.9 1852.18  5389.2 1862.75
  5441.8 1866.59  5607.1 1897.23  5708.1 1903.55  5766.7 1909.72  5906.9 1915.86
#Mann= 7 ,-1 , 0
  4020.7      .1       0  4385.6     .05       0  4486.2      .1       0
    4531     .05       0  4704.3      .1       0  4961.9     .07       0
  5087.7      .1       0
Bank Sta=4961.9,5087.7
XS Rating Curve= 0 ,0
Exp/Cntr=0.3,0.1

Type RM Length L Ch R = 1 ,127     ,0,0,0
BEGIN DESCRIPTION:
TROUGH CREEK 1.0
END DESCRIPTION:
XS GIS Cut Line= 4
      2699516.62     10021067.27      2699842.14     10020174.03
      2699662.45     10019825.07      2698673.16     10019653.25
#Sta/Elev= 30
    3843 1897.71  3946.3 1891.59  4043.3 1886.66  4244.3  1877.5  4346.9 1869.76
    4417 1861.72  4546.2 1854.11  4650.9 1845.98  4833.9 1839.82  4951.5 1842.88
    4967 1842.12    4974 1837.93  4983.5 1829.96  4996.2 1824.67  5027.8 1825.32
    5064 1830.59  5072.2 1831.23  5458.1 1839.52  5494.7 1845.37  5512.7 1851.32
  5517.8 1850.05  5535.3 1854.11  5626.7 1863.63  5691.7    1864  5746.3  1868.3
  5751.4 1866.61    5806 1881.36    5811 1879.49  5865.6 1893.31  6190.3 1913.67
#Mann= 8 ,-1 , 0
    3843      .1       0  3946.3     .05       0  4043.3      .1       0
  4346.9     .05       0  4546.2      .1       0    4974     .07       0
    5064      .1       0  5494.7      .1       0
Bank Sta=4974,5072.2
XS Rating Curve= 0 ,0
Exp/Cntr=0.3,0.1

Chan Stop Cuts=-1
Use User Specified Reach Order=0
Composite Channel Slope=5