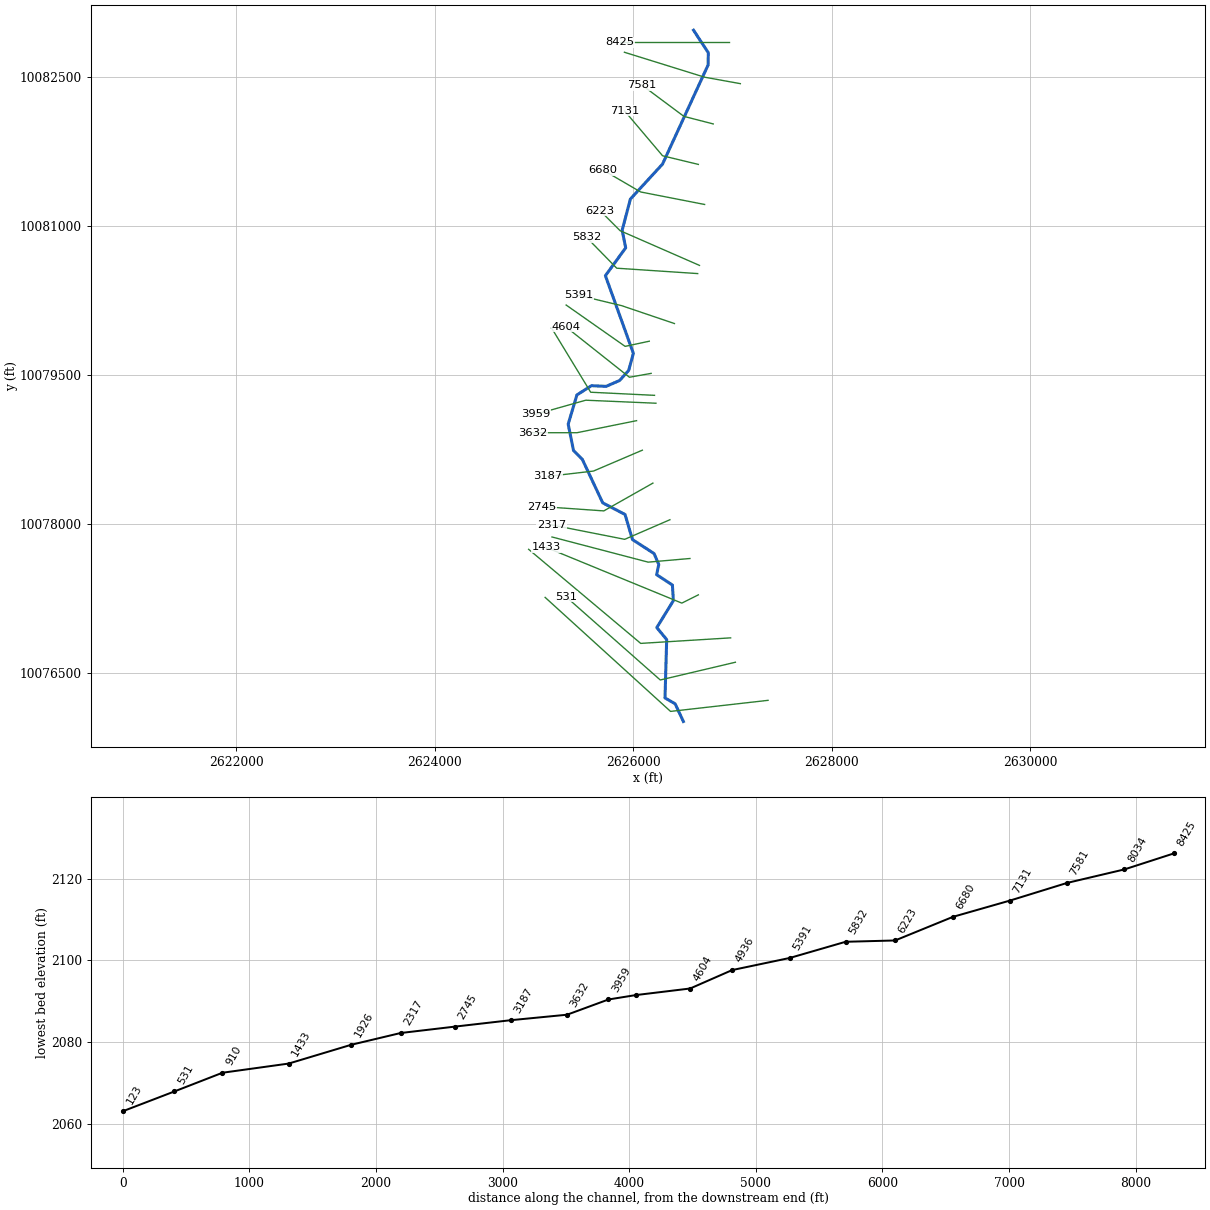
--- UNT 0001 IN HEWA.prj (project) ---

Proj Title=UNT 0001 IN HEWA Base Level Engineering
Current Plan=p01
Default Exp/Contr=0.3,0.1
English Units
Geom File=g01
Flow File=f01
Plan File=p01
BEGIN DESCRIPTION:
UNT 0001 IN HEWA
END DESCRIPTION:

--- UNT 0001 IN HEWA.p01 (plan) ---

Plan Title=Multiple Run
Short Identifier=Multiple
Geom File=g01
Flow File=f01
Subcritical Flow
K Sum by GR= 0
Std Step Tol= 0.01
Critical Tol= 0.01
Num of Std Step Trials= 20
Max Error Tol= 0.3
Flow Tol Ratio= 0.001
Split Flow NTrial= 30
Split Flow Tol= 0.02
Split Flow Ratio= 0.02
Log Output Level= 0
Friction Slope Method= 1
Unsteady Friction Slope Method= 2
Unsteady Bridges Friction Slope Method= 1
Parabolic Critical Depth
Global Vel Dist=  1 , 1 , 1
Global Log Level= 0
CheckData=True
Encroach Param= -1, 0, 0, 0
BEGIN DESCRIPTION:
Multiple Run
END DESCRIPTION:

--- UNT 0001 IN HEWA.f01 (steady flow) ---

Flow Title=Multiple
Number of Profiles=7
Profile Names=10-year,25-year,50-year,1pct_min,100-year,1pct_plu,500-year
River Rch & RM= UNT 0001 IN HEWA,Reach-1,8425
    1540    2275    2918    2724    3684    4982    5874
River Rch & RM= UNT 0001 IN HEWA,Reach-1,3959
    1782    2649    3411    3193    4319    5841    6930
Boundary for River Rch & Prof#=UNT 0001 IN HEWA,Reach-1,1
Up Type=0
Dn Type=3
Dn Slope=0.005
Boundary for River Rch & Prof#=UNT 0001 IN HEWA,Reach-1,2
Up Type=0
Dn Type=3
Dn Slope=0.005
Boundary for River Rch & Prof#=UNT 0001 IN HEWA,Reach-1,3
Up Type=0
Dn Type=3
Dn Slope=0.005
Boundary for River Rch & Prof#=UNT 0001 IN HEWA,Reach-1,4
Up Type=0
Dn Type=3
Dn Slope=0.005
Boundary for River Rch & Prof#=UNT 0001 IN HEWA,Reach-1,5
Up Type=0
Dn Type=3
Dn Slope=0.005
Boundary for River Rch & Prof#=UNT 0001 IN HEWA,Reach-1,6
Up Type=0
Dn Type=3
Dn Slope=0.005
Boundary for River Rch & Prof#=UNT 0001 IN HEWA,Reach-1,7
Up Type=0
Dn Type=3
Dn Slope=0.005

--- UNT 0001 IN HEWA.g01 (geometry) ---

Geom Title=Existing Conditions

River Reach=UNT 0001 IN HEWA,Reach-1
Reach XY= 30
      2626608.47     10082973.73      2626756.87     10082747.61
      2626755.87     10082624.90      2626295.96     10081624.75
      2625971.98     10081272.38      2625889.20     10080958.37
      2625924.66     10080780.97      2625720.20     10080500.23
      2626002.23     10079717.25      2625954.53     10079545.11
      2625863.40     10079443.98      2625727.86     10079384.85
      2625579.57     10079391.39      2625433.11     10079298.47
      2625345.13     10079003.46      2625398.65     10078738.79
      2625488.13     10078648.23      2625693.19     10078210.89
      2625918.08     10078093.79      2625993.00     10077840.82
      2626210.67     10077699.90      2626258.11     10077589.48
      2626236.39     10077487.14      2626395.55     10077382.65
      2626405.02     10077225.23      2626238.12     10076953.71
      2626337.68     10076833.50      2626320.97     10076244.68
      2626423.02     10076185.90      2626506.05     10076007.60

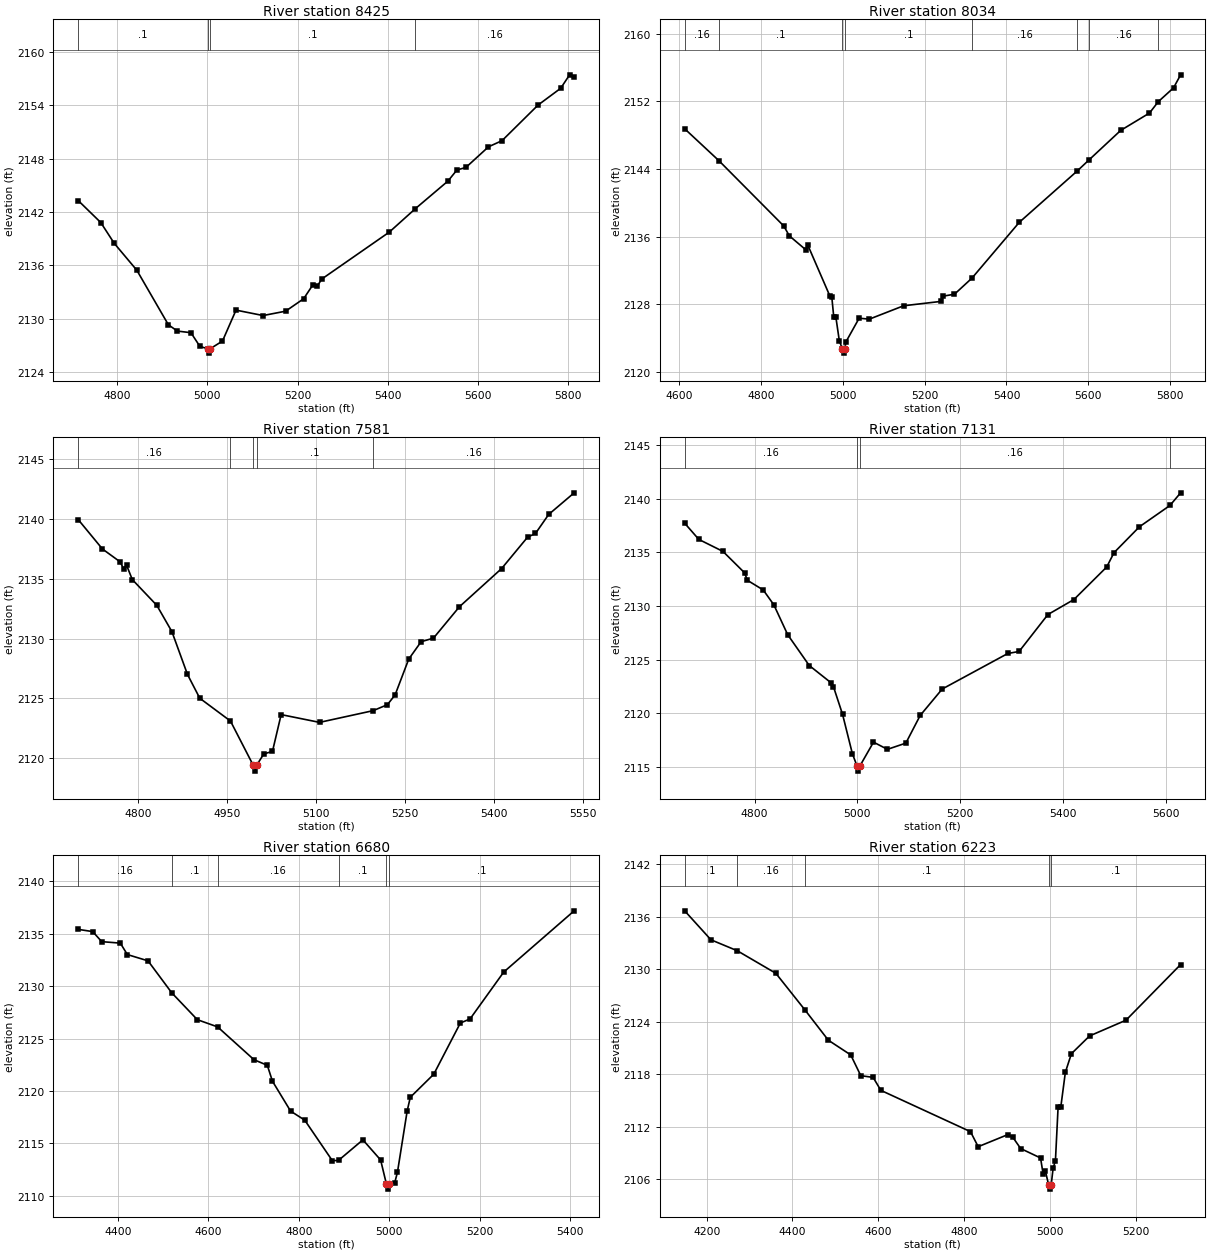
Type RM Length L Ch R = 1,8425,391,391,391
BEGIN DESCRIPTION:
UNT 0001 IN HEWA 19.0
END DESCRIPTION:
XS GIS Cut Line= 3
      2626968.48     10082853.73      2626668.47     10082853.73
      2625868.48     10082853.73
#Sta/Elev= 30
  4713.5 2143.30  4763.5 2140.83  4793.5 2138.48  4843.5 2135.46  4913.5 2129.32
  4933.5 2128.61  4963.5 2128.43  4983.5 2126.88  5000.5 2126.63  5003.3 2126.13
  5006.5 2126.63  5033.5 2127.49  5063.5 2130.97  5123.5 2130.36  5173.5 2130.85
  5213.5 2132.25  5233.5 2133.78  5243.5 2133.64  5253.5 2134.46  5403.5 2139.75
  5461.6 2142.40  5533.5 2145.49  5553.5 2146.74  5573.5 2147.03  5623.5 2149.35
  5653.5 2150.04  5733.5 2154.05  5783.5 2155.93  5803.5 2157.45  5813.5 2157.24
#Mann=4,-1,0
  4713.5     0.1       0  5000.5    0.07       0  5006.5     0.1       0
  5461.6    0.16       0
Bank Sta=5000.5,5006.5
Exp/Cntr=0.3,0.1

Type RM Length L Ch R = 1,8034,453,453,453
BEGIN DESCRIPTION:
UNT 0001 IN HEWA 18.0
END DESCRIPTION:
XS GIS Cut Line= 3
      2627080.14     10082435.33      2626719.90     10082500.43
      2625911.94     10082751.70
#Sta/Elev= 30
  4613.4 2148.75  4696.8 2144.99  4855.7 2137.25  4869.2 2136.09  4909.2 2134.45
  4914.3 2135.00  4967.8 2129.03  4972.9 2128.91  4977.7 2126.53  4982.8 2126.53
  4991.4 2123.67  4998.9 2122.72  5001.7 2122.22  5004.9 2122.72  5007.3 2123.53
  5039.8 2126.35  5064.8 2126.24  5148.5 2127.82  5240.4 2128.34  5245.6 2128.96
  5272.9 2129.19  5315.6 2131.09  5431.3 2137.69  5573.1 2143.77  5601.1 2145.04
  5679.2 2148.56  5749.5 2150.61  5771.1 2151.96  5808.3 2153.59  5825.6 2155.13
#Mann=8,-1,0
  4613.4    0.16       0  4696.8     0.1       0  4998.9    0.07       0
  5004.9     0.1       0  5315.6    0.16       0  5573.1     0.1       0
  5601.1    0.16       0  5771.1     0.1       0
Bank Sta=4998.9,5004.9
Exp/Cntr=0.3,0.1

Type RM Length L Ch R = 1,7581,450,450,450
BEGIN DESCRIPTION:
UNT 0001 IN HEWA 17.0
END DESCRIPTION:
XS GIS Cut Line= 3
      2626806.69     10082029.51      2626511.56     10082105.46
      2626086.24     10082422.29
#Sta/Elev= 30
  4699.7 2139.97  4740.5 2137.51  4770.1 2136.44  4776.1 2135.87  4781.2 2136.14
  4790.8 2134.95  4832.1 2132.79  4857.5 2130.59  4883.7 2127.01  4904.4 2125.02
  4956.1 2123.11  4994.3 2119.42  4997.1 2118.92  5000.3 2119.42  5012.2 2120.36
  5026.8 2120.57  5041.4 2123.65  5106.1 2123.00  5196.3 2123.98  5220.3 2124.48
  5233.3 2125.30  5256.2 2128.29  5277.1 2129.75  5297.9 2130.05  5341.7 2132.68
  5412.6 2135.87  5456.4 2138.50  5469.7 2138.81  5491.9 2140.40  5534.8 2142.21
#Mann=5,-1,0
  4699.7    0.16       0  4956.1     0.1       0  4994.3    0.07       0
  5000.3     0.1       0  5196.3    0.16       0
Bank Sta=4994.3,5000.3
Exp/Cntr=0.3,0.1

Type RM Length L Ch R = 1,7131,451,451,451
BEGIN DESCRIPTION:
UNT 0001 IN HEWA 16.0
END DESCRIPTION:
XS GIS Cut Line= 3
      2626656.96     10081621.52      2626296.72     10081708.33
      2625913.06     10082161.35
#Sta/Elev= 30
  4664.2 2137.72  4691.7 2136.21  4738.7 2135.09  4780.6 2133.10  4786.1 2132.40
  4816.9 2131.50  4837.5 2130.12  4864.5 2127.33  4906.4 2124.46  4948.3 2122.87
  4953.5 2122.48  4971.2 2119.90  4990.2 2116.25  4999.1 2115.12  5001.8 2114.62
  5005.1 2115.12  5031.3 2117.32  5058.4 2116.65  5094.2 2117.23  5122.1 2119.81
  5164.9 2122.27  5292.4 2125.58  5314.4 2125.77  5370.4 2129.21  5421.0 2130.61
  5484.7 2133.64  5499.0 2134.98  5548.4 2137.39  5607.6 2139.37  5628.4 2140.55
#Mann=4,-1,0
  4664.2    0.16       0  4999.1    0.07       0  5005.1    0.16       0
  5607.6    0.16       0
Bank Sta=4999.1,5005.1
Exp/Cntr=0.3,0.1

Type RM Length L Ch R = 1,6680,457,457,457
BEGIN DESCRIPTION:
UNT 0001 IN HEWA 15.0
END DESCRIPTION:
XS GIS Cut Line= 3
      2626719.88     10081217.88      2626075.37     10081343.75
      2625695.56     10081565.12
#Sta/Elev= 30
  4312.3 2135.41  4344.3 2135.20  4364.3 2134.24  4405.4 2134.10  4420.9 2133.01
  4466.6 2132.41  4519.1 2129.36  4575.6 2126.80  4620.5 2126.11  4700.9 2122.98
  4730.3 2122.45  4741.7 2120.93  4781.8 2118.08  4813.0 2117.22  4874.1 2113.35
  4887.7 2113.38  4941.6 2115.34  4980.8 2113.42  4993.5 2111.14  4996.3 2110.64
  4999.5 2111.14  5011.7 2111.21  5018.0 2112.25  5039.5 2118.10  5046.4 2119.40
  5098.3 2121.60  5157.0 2126.48  5178.5 2126.87  5252.9 2131.34  5408.6 2137.18
#Mann=6,-1,0
  4312.3    0.16       0  4519.1     0.1       0  4620.5    0.16       0
  4887.7     0.1       0  4993.5    0.07       0  4999.5     0.1       0
Bank Sta=4993.5,4999.5
Exp/Cntr=0.3,0.1

Type RM Length L Ch R = 1,6223,391,391,391
BEGIN DESCRIPTION:
UNT 0001 IN HEWA 14.0
END DESCRIPTION:
XS GIS Cut Line= 3
      2626668.47     10080603.73      2625868.47     10080953.73
      2625668.44     10081153.76
#Sta/Elev= 30
  4148.8 2136.68  4210.0 2133.37  4271.3 2132.12  4361.3 2129.54  4428.7 2125.38
  4483.7 2121.89  4535.9 2120.21  4559.3 2117.84  4588.1 2117.64  4606.1 2116.16
  4815.0 2111.44  4833.0 2109.72  4902.0 2111.10  4914.0 2110.78  4932.0 2109.51
  4978.4 2108.43  4984.2 2106.65  4989.7 2106.91  4997.2 2105.37  4999.9 2104.87
  5003.2 2105.37  5007.6 2107.23  5013.1 2108.14  5019.3 2114.26  5025.6 2114.26
  5036.2 2118.22  5050.3 2120.35  5092.7 2122.38  5177.6 2124.18  5304.9 2130.54
#Mann=5,-1,0
  4148.8     0.1       0  4271.3    0.16       0  4428.7     0.1       0
  4997.2    0.07       0  5003.2     0.1       0
Bank Sta=4997.2,5003.2
Exp/Cntr=0.3,0.1

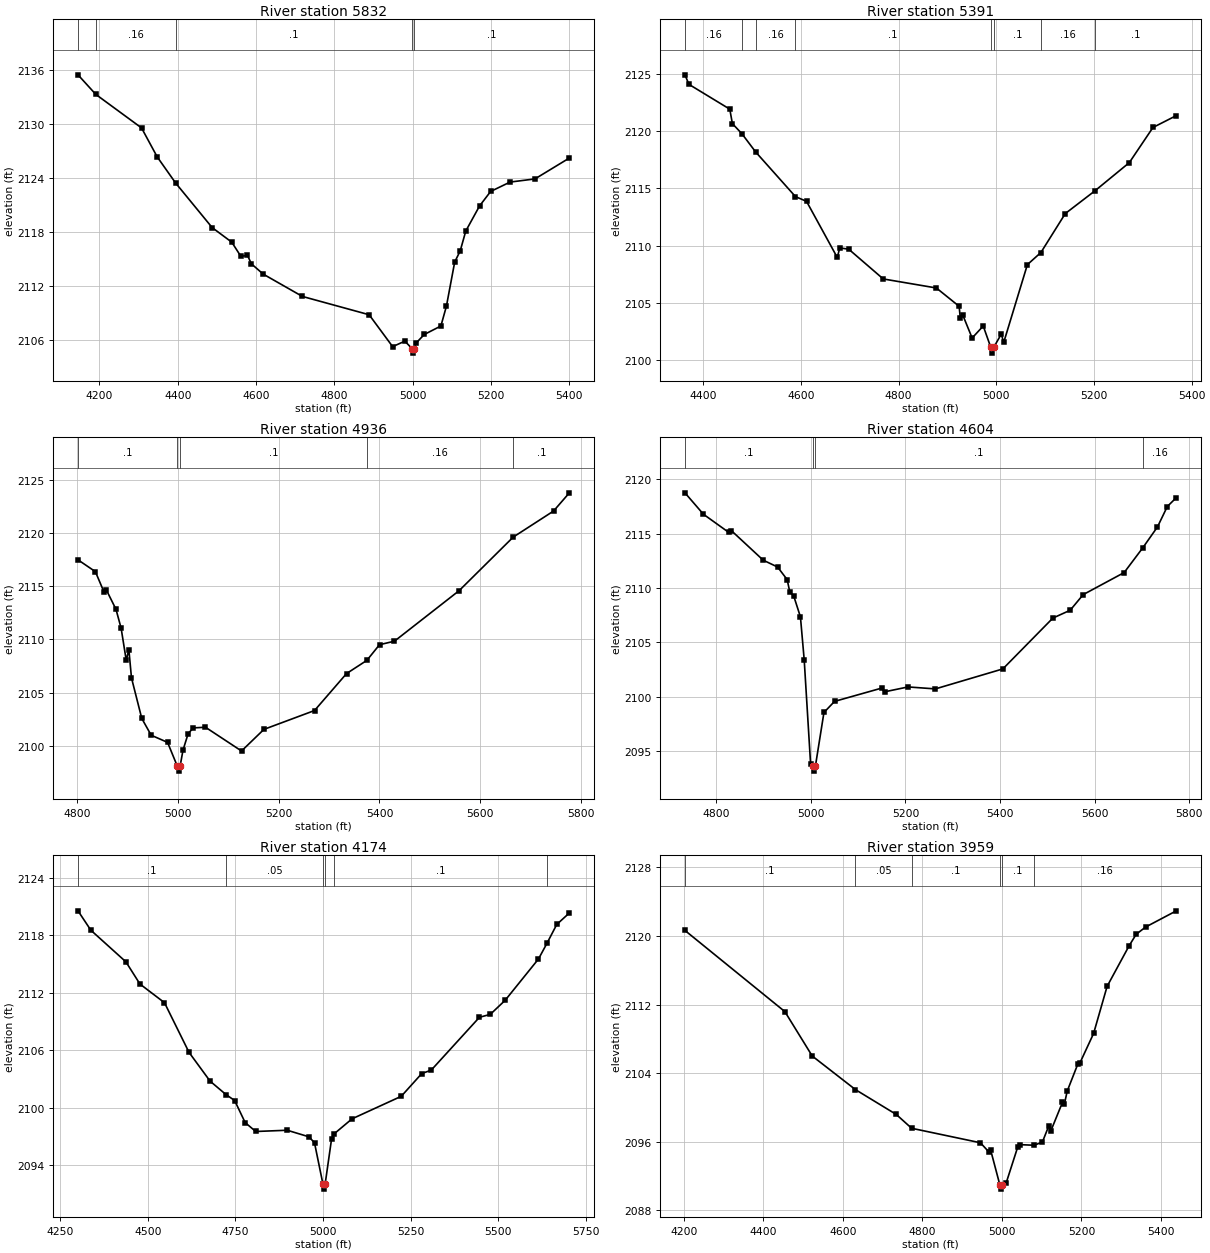
Type RM Length L Ch R = 1,5832,441,441,441
BEGIN DESCRIPTION:
UNT 0001 IN HEWA 13.0
END DESCRIPTION:
XS GIS Cut Line= 3
      2626650.44     10080521.26      2625834.48     10080575.52
      2625528.51     10080888.00
#Sta/Elev= 30
  4145.2 2135.43  4190.7 2133.26  4307.5 2129.54  4347.6 2126.32  4394.5 2123.43
  4487.9 2118.48  4538.0 2116.86  4561.2 2115.29  4578.1 2115.40  4588.1 2114.46
  4618.2 2113.32  4718.4 2110.84  4888.8 2108.81  4948.9 2105.27  4980.1 2105.88
  4998.4 2105.05  5001.1 2104.55  5004.4 2105.05  5008.4 2105.65  5029.7 2106.62
  5072.1 2107.56  5086.2 2109.75  5107.4 2114.66  5121.5 2115.90  5135.7 2118.10
  5171.0 2120.89  5199.2 2122.49  5248.8 2123.53  5312.4 2123.88  5400.3 2126.20
#Mann=5,-1,0
  4145.2     0.1       0  4190.7    0.16       0  4394.5     0.1       0
  4998.4    0.07       0  5004.4     0.1       0
Bank Sta=4998.4,5004.4
Exp/Cntr=0.3,0.1

Type RM Length L Ch R = 1,5391,455,455,455
BEGIN DESCRIPTION:
UNT 0001 IN HEWA 12.0
END DESCRIPTION:
XS GIS Cut Line= 3
      2626416.07     10080017.79      2625884.39     10080197.91
      2625451.93     10080301.70
#Sta/Elev= 30
  4362.6 2124.91  4370.7 2124.08  4454.4 2121.91  4459.7 2120.65  4479.3 2119.76
  4507.4 2118.17  4588.9 2114.27  4611.5 2113.86  4674.4 2108.96  4679.6 2109.79
  4697.9 2109.68  4768.6 2107.08  4877.4 2106.29  4924.0 2104.69  4926.2 2103.71
  4931.3 2103.94  4950.6 2101.92  4973.3 2102.97  4988.8 2101.10  4991.5 2100.60
  4994.8 2101.10  5010.2 2102.26  5015.3 2101.54  5063.7 2108.33  5091.4 2109.39
  5141.3 2112.79  5201.5 2114.76  5272.4 2117.24  5320.8 2120.31  5368.7 2121.35
#Mann=8,-1,0
  4362.6    0.16       0  4479.3     0.1       0  4507.4    0.16       0
  4588.9     0.1       0  4988.8    0.07       0  4994.8     0.1       0
  5091.4    0.16       0  5201.5     0.1       0
Bank Sta=4988.8,4994.8
Exp/Cntr=0.3,0.1

Type RM Length L Ch R = 1,4936,332,332,332
BEGIN DESCRIPTION:
UNT 0001 IN HEWA 11.0
END DESCRIPTION:
XS GIS Cut Line= 3
      2626162.18     10079839.84      2625919.12     10079787.76
      2625324.46     10080204.45
#Sta/Elev= 30
  4802.0 2117.48  4836.5 2116.37  4853.4 2114.48  4858.5 2114.63  4877.4 2112.83
  4887.6 2111.05  4897.7 2108.05  4902.9 2109.05  4908.1 2106.40  4928.5 2102.59
  4947.2 2101.01  4979.7 2100.34  4998.7 2098.14  5001.5 2097.64  5004.7 2098.14
  5010.3 2099.61  5020.6 2101.17  5030.8 2101.70  5054.9 2101.76  5126.4 2099.53
  5170.8 2101.56  5271.2 2103.33  5334.7 2106.80  5375.0 2108.04  5400.1 2109.51
  5429.7 2109.84  5557.9 2114.58  5665.2 2119.61  5745.3 2122.06  5776.7 2123.77
#Mann=5,-1,0
  4802.0     0.1       0  4998.7    0.07       0  5004.7     0.1       0
  5375.0    0.16       0  5665.2     0.1       0
Bank Sta=4998.7,5004.7
Exp/Cntr=0.3,0.1

Type RM Length L Ch R = 1,4604,430,430,430
BEGIN DESCRIPTION:
Mapping XS 1aa38254
END DESCRIPTION:
XS GIS Cut Line= 3
      2626181.25     10079515.69      2625962.52     10079476.63
      2625322.65     10079983.84
#Sta/Elev= 30
  4734.0 2118.76  4773.0 2116.79  4826.8 2115.11  4831.9 2115.29  4899.4 2112.56
  4929.8 2111.93  4950.1 2110.77  4955.7 2109.61  4963.7 2109.29  4978.1 2107.34
  4986.1 2103.37  4999.6 2093.79  5003.9 2093.64  5006.7 2093.14  5009.9 2093.64
  5027.8 2098.54  5050.2 2099.56  5149.6 2100.78  5155.9 2100.44  5205.6 2100.89
  5263.3 2100.71  5406.0 2102.55  5511.7 2107.23  5548.3 2107.95  5575.8 2109.39
  5662.4 2111.42  5701.6 2113.69  5732.8 2115.62  5753.6 2117.50  5772.7 2118.32
#Mann=4,-1,0
  4734.0     0.1       0  5003.9    0.07       0  5009.9     0.1       0
  5701.6    0.16       0
Bank Sta=5003.9,5009.9
Exp/Cntr=0.3,0.1

Type RM Length L Ch R = 1,4174,215,215,215
BEGIN DESCRIPTION:
UNT 0001 IN HEWA 10.0
END DESCRIPTION:
XS GIS Cut Line= 4
      2626215.09     10079294.34      2625571.89     10079325.59
      2625178.66     10079971.42      2625176.05     10079971.42
#Sta/Elev= 30
  4300.8 2120.55  4337.5 2118.53  4437.6 2115.23  4477.6 2112.92  4547.7 2110.97
  4617.8 2105.79  4677.9 2102.79  4723.3 2101.39  4748.0 2100.77  4778.0 2098.47
  4808.2 2097.54  4898.1 2097.67  4960.6 2096.98  4976.0 2096.35  5000.2 2092.03
  5002.9 2091.53  5006.2 2092.03  5024.5 2096.72  5030.8 2097.26  5083.1 2098.86
  5223.6 2101.21  5282.1 2103.58  5309.2 2103.94  5446.8 2109.45  5477.7 2109.75
  5520.4 2111.23  5615.3 2115.53  5639.3 2117.15  5667.5 2119.13  5703.5 2120.33
#Mann=6,-1,0
  4300.8     0.1       0  4723.3    0.05       0  5000.2    0.04       0
  5006.2    0.05       0  5030.8     0.1       0  5639.3    0.16       0
Bank Sta=5000.2,5006.2
Exp/Cntr=0.3,0.1

Type RM Length L Ch R = 1,3959,327,327,327
BEGIN DESCRIPTION:
UNT 0001 IN HEWA 9.0
END DESCRIPTION:
XS GIS Cut Line= 3
      2626229.49     10079214.84      2625521.98     10079245.22
      2625014.16     10079101.99
#Sta/Elev= 30
  4203.0 2120.64  4454.3 2111.17  4523.1 2105.99  4631.8 2102.07  4734.5 2099.17
  4773.1 2097.56  4946.0 2095.87  4966.7 2094.83  4971.9 2095.00  4994.9 2090.96
  4997.7 2090.46  5000.9 2090.96  5011.1 2091.22  5039.5 2095.32  5045.1 2095.65
  5080.9 2095.58  5101.8 2095.94  5118.3 2097.87  5123.5 2097.29  5152.3 2100.57
  5157.5 2100.42  5164.2 2101.88  5191.5 2105.11  5196.7 2105.22  5230.7 2108.62
  5264.7 2114.12  5320.0 2118.85  5337.9 2120.20  5361.6 2121.04  5438.8 2122.93
#Mann=6,-1,0
  4203.0     0.1       0  4631.8    0.05       0  4773.1     0.1       0
  4994.9    0.07       0  5000.9     0.1       0  5080.9    0.16       0
Bank Sta=4994.9,5000.9
Exp/Cntr=0.3,0.1

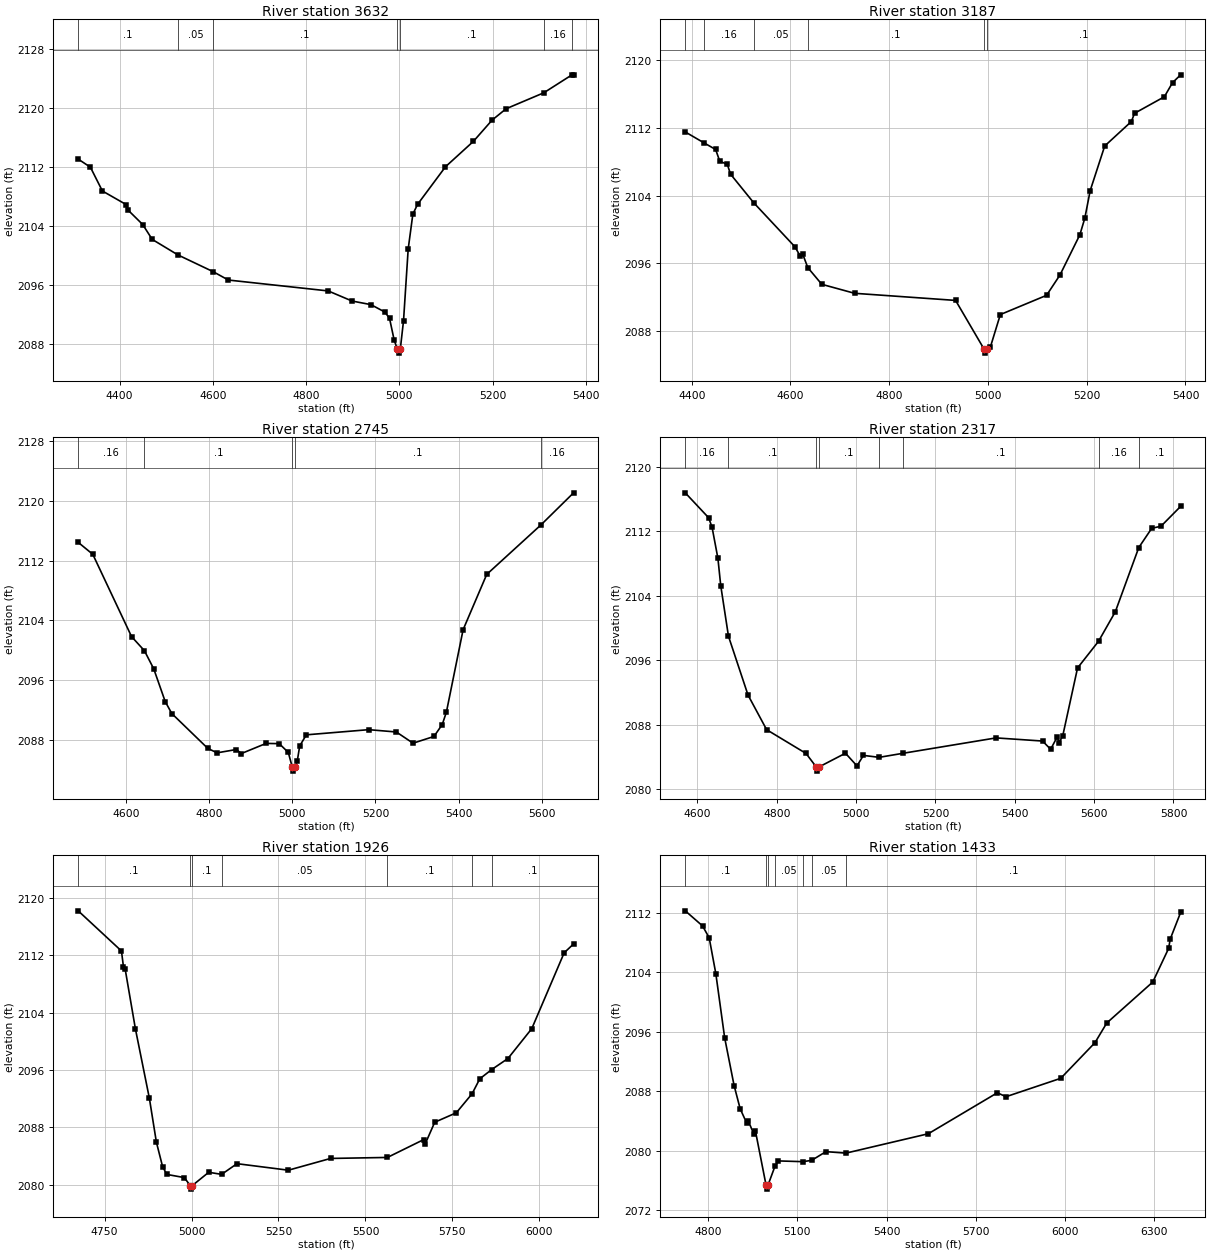
Type RM Length L Ch R = 1,3632,445,445,445
BEGIN DESCRIPTION:
UNT 0001 IN HEWA 8.0
END DESCRIPTION:
XS GIS Cut Line= 3
      2626034.15     10079039.06      2625433.01     10078917.53
      2624983.81     10078917.53
#Sta/Elev= 30
  4311.3 2113.10  4337.5 2112.00  4363.2 2108.77  4414.0 2106.93  4419.1 2106.12
  4449.7 2104.21  4470.1 2102.19  4525.3 2100.08  4600.3 2097.82  4633.4 2096.67
  4847.6 2095.19  4898.6 2093.82  4939.1 2093.33  4969.1 2092.32  4979.1 2091.46
  4989.1 2088.49  4996.1 2087.24  4998.9 2086.74  5002.1 2087.24  5009.1 2091.15
  5019.1 2100.89  5029.1 2105.62  5039.1 2106.94  5099.1 2112.06  5159.1 2115.52
  5199.1 2118.40  5229.1 2119.94  5310.0 2122.11  5370.4 2124.55  5373.8 2124.55
#Mann=7,-1,0
  4311.3     0.1       0  4525.3    0.05       0  4600.3     0.1       0
  4996.1    0.07       0  5002.1     0.1       0  5310.0    0.16       0
  5370.4     0.1       0
Bank Sta=4996.1,5002.1
Exp/Cntr=0.3,0.1

Type RM Length L Ch R = 1,3187,442,442,442
BEGIN DESCRIPTION:
UNT 0001 IN HEWA 7.0
END DESCRIPTION:
XS GIS Cut Line= 3
      2626092.75     10078741.76      2625600.11     10078531.25
      2625135.70     10078476.99
#Sta/Elev= 30
  4386.9 2111.50  4424.3 2110.23  4448.4 2109.43  4456.8 2108.04  4472.0 2107.68
  4478.6 2106.52  4525.3 2103.16  4609.1 2097.94  4619.1 2096.91  4624.5 2097.12
  4635.1 2095.49  4663.4 2093.52  4729.8 2092.46  4934.4 2091.62  4991.8 2085.90
  4994.5 2085.40  4997.8 2085.90  5004.8 2086.11  5025.0 2089.95  5118.6 2092.22
  5145.8 2094.62  5186.1 2099.37  5196.1 2101.32  5207.0 2104.58  5236.4 2109.84
  5290.4 2112.73  5296.8 2113.70  5357.2 2115.65  5373.8 2117.32  5390.2 2118.24
#Mann=6,-1,0
  4386.9     0.1       0  4424.3    0.16       0  4525.3    0.05       0
  4635.1     0.1       0  4991.8    0.07       0  4997.8     0.1       0
Bank Sta=4991.8,4997.8
Exp/Cntr=0.3,0.1

Type RM Length L Ch R = 1,2745,428,428,428
BEGIN DESCRIPTION:
UNT 0001 IN HEWA 6.0
END DESCRIPTION:
XS GIS Cut Line= 3
      2626199.02     10078409.69      2625704.27     10078129.77
      2625083.64     10078173.17
#Sta/Elev= 30
  4485.6 2114.46  4520.7 2112.86  4613.9 2101.84  4644.7 2099.96  4667.3 2097.51
  4694.7 2093.15  4710.6 2091.54  4797.2 2086.87  4819.4 2086.28  4865.4 2086.72
  4878.0 2086.19  4937.2 2087.54  4968.8 2087.51  4990.6 2086.33  5000.3 2084.33
  5003.0 2083.83  5006.3 2084.33  5012.3 2085.24  5018.0 2087.20  5033.9 2088.69
  5183.8 2089.38  5250.3 2089.07  5290.4 2087.57  5340.6 2088.47  5360.6 2090.07
  5370.6 2091.74  5410.7 2102.76  5467.5 2110.17  5597.9 2116.80  5676.2 2121.09
#Mann=5,-1,0
  4485.6    0.16       0  4644.7     0.1       0  5000.3    0.07       0
  5006.3     0.1       0  5597.9    0.16       0
Bank Sta=5000.3,5006.3
Exp/Cntr=0.3,0.1

Type RM Length L Ch R = 1,2317,391,391,391
BEGIN DESCRIPTION:
UNT 0001 IN HEWA 5.0
END DESCRIPTION:
XS GIS Cut Line= 3
      2626370.53     10078040.80      2625914.78     10077843.31
      2625176.97     10077988.70
#Sta/Elev= 30
  4569.4 2116.78  4628.3 2113.69  4637.0 2112.50  4651.7 2108.65  4658.8 2105.28
  4678.3 2099.00  4727.6 2091.70  4774.5 2087.41  4873.9 2084.46  4899.8 2082.77
  4902.6 2082.27  4905.8 2082.77  4973.2 2084.49  5002.2 2082.92  5018.5 2084.22
  5058.2 2083.98  5118.1 2084.48  5352.8 2086.39  5470.0 2086.00  5490.4 2084.98
  5506.8 2086.50  5511.9 2085.80  5521.0 2086.67  5558.2 2095.06  5611.1 2098.37
  5653.5 2102.04  5712.6 2110.00  5745.2 2112.38  5768.6 2112.64  5818.1 2115.10
#Mann=8,-1,0
  4569.4    0.16       0  4678.3     0.1       0  4899.8    0.07       0
  4905.8     0.1       0  5058.2    0.05       0  5118.1     0.1       0
  5611.1    0.16       0  5712.6     0.1       0
Bank Sta=4899.8,4905.8
Exp/Cntr=0.3,0.1

Type RM Length L Ch R = 1,1926,493,493,493
BEGIN DESCRIPTION:
UNT 0001 IN HEWA 4.0
END DESCRIPTION:
XS GIS Cut Line= 3
      2626572.37     10077650.17      2626151.32     10077613.28
      2625182.32     10077866.91
#Sta/Elev= 30
  4674.1 2118.21  4798.5 2112.61  4804.3 2110.39  4809.3 2110.04  4838.6 2101.75
  4878.8 2092.06  4898.9 2085.95  4916.8 2082.52  4929.0 2081.44  4979.2 2081.00
  4996.2 2079.89  4999.0 2079.39  5002.2 2079.89  5049.4 2081.74  5086.5 2081.45
  5130.7 2082.94  5278.4 2082.03  5399.7 2083.67  5563.2 2083.81  5667.1 2086.29
  5672.3 2085.75  5699.2 2088.72  5761.3 2090.04  5806.7 2092.70  5828.8 2094.78
  5863.0 2096.07  5909.7 2097.61  5978.3 2101.78  6071.4 2112.36  6098.4 2113.59
#Mann=7,-1,0
  4674.1     0.1       0  4996.2    0.07       0  5002.2     0.1       0
  5086.5    0.05       0  5563.2     0.1       0  5806.7    0.16       0
  5863.0     0.1       0
Bank Sta=4996.2,5002.2
Exp/Cntr=0.3,0.1

Type RM Length L Ch R = 1,1433,523,523,523
BEGIN DESCRIPTION:
UNT 0001 IN HEWA 3.0
END DESCRIPTION:
XS GIS Cut Line= 3
      2626656.97     10077283.85      2626490.30     10077200.52
      2625122.01     10077762.40
#Sta/Elev= 30
  4723.2 2112.30  4781.2 2110.27  4803.6 2108.67  4825.9 2103.85  4855.7 2095.19
  4887.4 2088.76  4907.8 2085.63  4929.5 2083.73  4934.9 2084.02  4953.4 2082.25
  4958.8 2082.70  4995.0 2075.31  4997.8 2074.81  5001.0 2075.31  5024.5 2077.86
  5036.2 2078.61  5117.7 2078.51  5147.9 2078.68  5196.2 2079.86  5263.4 2079.66
  5540.3 2082.27  5772.3 2087.79  5801.6 2087.26  5985.7 2089.74  6100.7 2094.54
  6140.3 2097.19  6295.0 2102.71  6348.3 2107.24  6353.7 2108.50  6388.7 2112.09
#Mann=7,-1,0
  4723.2     0.1       0  4995.0    0.07       0  5001.0     0.1       0
  5024.5    0.05       0  5117.7     0.1       0  5147.9    0.05       0
  5263.4     0.1       0
Bank Sta=4995,5001
Exp/Cntr=0.3,0.1

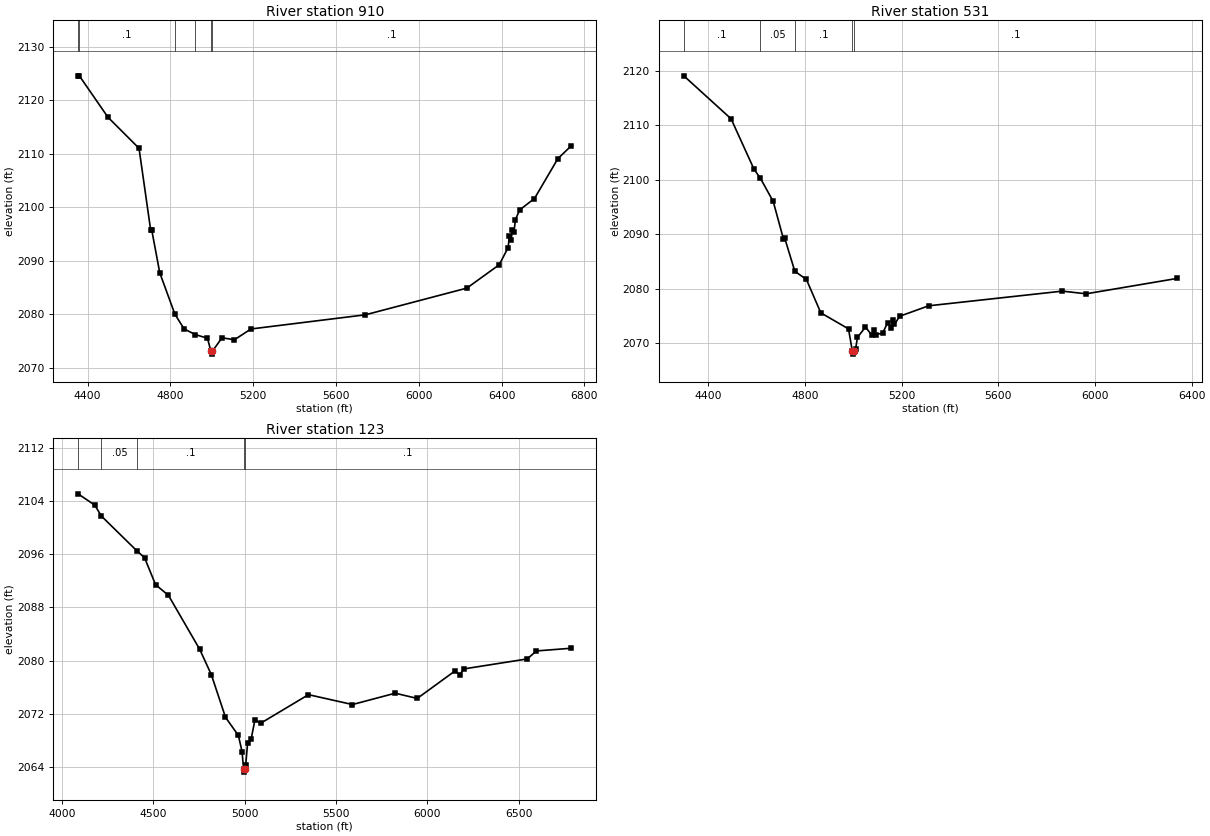
Type RM Length L Ch R = 1,910,379,379,379
BEGIN DESCRIPTION:
UNT 0001 IN HEWA 2.0
END DESCRIPTION:
XS GIS Cut Line= 3
      2626982.29     10076850.32      2626076.05     10076794.55
      2624946.71     10077742.64
#Sta/Elev= 30
  4354.2 2124.58  4360.9 2124.55  4498.3 2116.85  4648.6 2111.04  4704.6 2095.82
  4709.7 2095.83  4748.8 2087.76  4822.0 2080.02  4866.2 2077.29  4920.6 2076.22
  4979.2 2075.54  4996.2 2073.07  4999.0 2072.57  5002.2 2073.07  5049.3 2075.62
  5109.5 2075.26  5189.3 2077.27  5742.1 2079.92  6232.3 2084.91  6388.4 2089.27
  6431.3 2092.46  6437.9 2094.61  6445.7 2093.89  6452.2 2095.77  6460.0 2095.42
  6466.5 2097.67  6487.3 2099.53  6558.8 2101.65  6672.0 2109.11  6736.7 2111.51
#Mann=6,-1,0
  4354.2    0.16       0  4360.9     0.1       0  4822.0    0.05       0
  4920.6     0.1       0  4996.2    0.07       0  5002.2     0.1       0
Bank Sta=4996.2,5002.2
Exp/Cntr=0.3,0.1

Type RM Length L Ch R = 1,531,408,408,408
BEGIN DESCRIPTION:
Mapping XS dc46788d
END DESCRIPTION:
XS GIS Cut Line= 4
      2627030.17     10076604.60      2626273.27     10076425.79
      2625370.49     10077222.67      2625328.84     10077264.32
#Sta/Elev= 30
  4298.8 2119.08  4494.5 2111.19  4589.3 2101.94  4615.9 2100.27  4668.8 2096.02
  4711.1 2089.14  4716.2 2089.32  4758.2 2083.21  4806.0 2081.72  4865.7 2075.59
  4980.3 2072.64  4996.3 2068.51  4999.0 2068.01  5002.3 2068.51  5009.5 2068.93
  5017.5 2071.08  5050.6 2072.99  5076.4 2071.49  5085.3 2072.37  5092.8 2071.60
  5121.3 2071.87  5142.2 2073.76  5156.4 2072.89  5163.1 2074.34  5170.6 2073.45
  5191.5 2074.95  5312.0 2076.88  5865.0 2079.57  5963.7 2079.08  6339.6 2081.90
#Mann=5,-1,0
  4298.8     0.1       0  4615.9    0.05       0  4758.2     0.1       0
  4996.3    0.07       0  5002.3     0.1       0
Bank Sta=4996.3,5002.3
Exp/Cntr=0.3,0.1

Type RM Length L Ch R = 1,123,0,0,0
BEGIN DESCRIPTION:
UNT 0001 IN HEWA 1.0
END DESCRIPTION:
XS GIS Cut Line= 3
      2627359.47     10076220.69      2626376.53     10076109.15
      2625112.86     10077258.17
#Sta/Elev= 30
  4089.4 2105.13  4181.0 2103.42  4216.4 2101.79  4414.0 2096.45  4452.7 2095.51
  4513.1 2091.44  4583.6 2089.82  4754.6 2081.68  4818.2 2077.86  4895.5 2071.44
  4966.0 2068.70  4986.1 2066.26  4994.4 2063.67  4997.2 2063.17  5000.4 2063.67
  5006.2 2064.24  5016.3 2067.53  5036.4 2068.24  5056.6 2071.04  5087.8 2070.54
  5349.3 2074.85  5589.9 2073.36  5823.7 2075.07  5944.0 2074.28  6149.4 2078.40
  6177.8 2077.87  6198.7 2078.73  6546.1 2080.24  6595.4 2081.44  6786.6 2081.85
#Mann=5,-1,0
  4089.4     0.1       0  4216.4    0.05       0  4414.0     0.1       0
  4994.4    0.07       0  5000.4     0.1       0
Bank Sta=4994.4,5000.4
Exp/Cntr=0.3,0.1

Chan Stop Cuts=-1