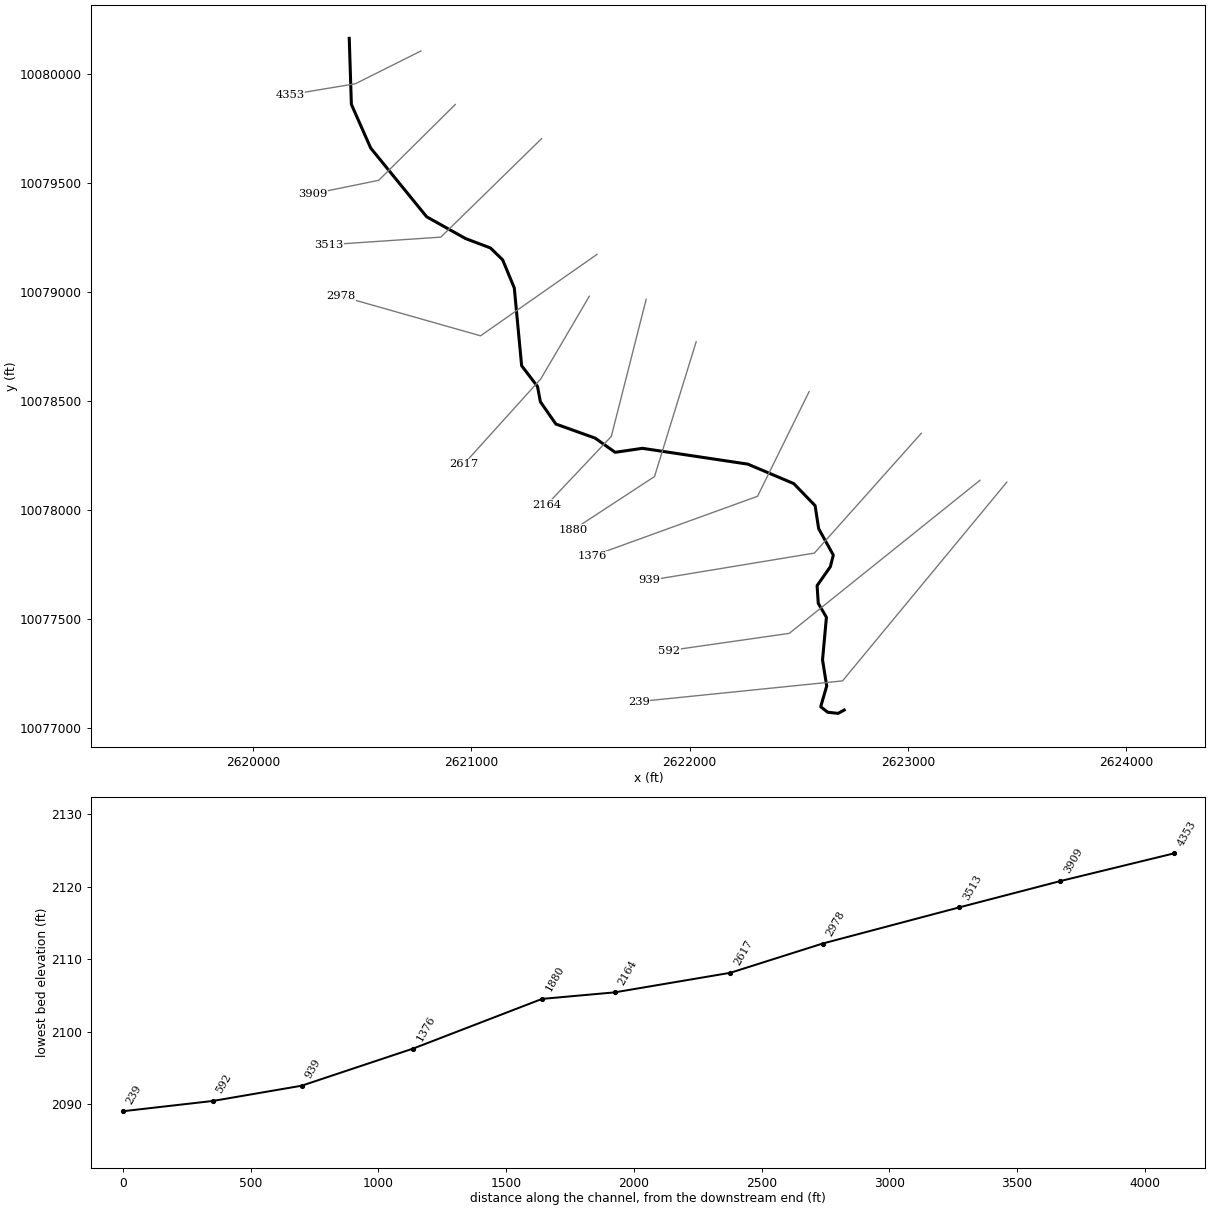
--- UNT 0002 IN HEWA.prj (project) ---

Proj Title=UNT 0002 IN HEWA Base Level Engineering
Current Plan=p01
Default Exp/Contr=0.3,0.1
English Units
Geom File=g01
Flow File=f01
Plan File=p01
BEGIN DESCRIPTION:
UNT 0002 IN HEWA
END DESCRIPTION:

--- UNT 0002 IN HEWA.p01 (plan) ---

Plan Title=Multiple Run
Short Identifier=Multiple
Geom File=g01
Flow File=f01
Subcritical Flow
K Sum by GR= 0
Std Step Tol= 0.01
Critical Tol= 0.01
Num of Std Step Trials= 20
Max Error Tol= 0.3
Flow Tol Ratio= 0.001
Split Flow NTrial= 30
Split Flow Tol= 0.02
Split Flow Ratio= 0.02
Log Output Level= 0
Friction Slope Method= 1
Unsteady Friction Slope Method= 2
Unsteady Bridges Friction Slope Method= 1
Parabolic Critical Depth
Global Vel Dist=  1 , 1 , 1
Global Log Level= 0
CheckData=True
Encroach Param= -1, 0, 0, 0
BEGIN DESCRIPTION:
Multiple Run
END DESCRIPTION:

--- UNT 0002 IN HEWA.f01 (steady flow) ---

Flow Title=Multiple
Number of Profiles=7
Profile Names=10-year,25-year,50-year,1pct_min,100-year,1pct_plu,500-year
River Rch & RM= UNT 0002 IN HEWA,Reach-1,4353
    1053    1530    1941    1795    2428    3283    3798
River Rch & RM= UNT 0002 IN HEWA,Reach-1,2617
    1744    2600    3354    3148    4257    5757    6864
Boundary for River Rch & Prof#=UNT 0002 IN HEWA,Reach-1,1
Up Type=0
Dn Type=3
Dn Slope=0.005
Boundary for River Rch & Prof#=UNT 0002 IN HEWA,Reach-1,2
Up Type=0
Dn Type=3
Dn Slope=0.005
Boundary for River Rch & Prof#=UNT 0002 IN HEWA,Reach-1,3
Up Type=0
Dn Type=3
Dn Slope=0.005
Boundary for River Rch & Prof#=UNT 0002 IN HEWA,Reach-1,4
Up Type=0
Dn Type=3
Dn Slope=0.005
Boundary for River Rch & Prof#=UNT 0002 IN HEWA,Reach-1,5
Up Type=0
Dn Type=3
Dn Slope=0.005
Boundary for River Rch & Prof#=UNT 0002 IN HEWA,Reach-1,6
Up Type=0
Dn Type=3
Dn Slope=0.005
Boundary for River Rch & Prof#=UNT 0002 IN HEWA,Reach-1,7
Up Type=0
Dn Type=3
Dn Slope=0.005

--- UNT 0002 IN HEWA.g01 (geometry) ---

Geom Title=Existing Conditions

River Reach=UNT 0002 IN HEWA,Reach-1
Reach XY= 30
      2620440.38     10080161.87      2620450.13     10079859.25
      2620538.80     10079658.87      2620795.02     10079344.19
      2620973.67     10079244.22      2621087.51     10079201.27
      2621143.44     10079146.73      2621196.71     10079018.00
      2621230.36     10078661.72      2621303.19     10078566.15
      2621316.30     10078496.40      2621387.19     10078394.39
      2621566.91     10078329.96      2621658.98     10078264.82
      2621783.87     10078283.08      2622267.15     10078210.55
      2622477.60     10078121.28      2622575.15     10078020.38
      2622591.49     10077915.00      2622658.68     10077793.60
      2622645.01     10077740.55      2622584.31     10077653.68
      2622589.68     10077572.88      2622627.07     10077508.83
      2622609.27     10077313.69      2622628.32     10077193.86
      2622600.86     10077098.92      2622632.76     10077073.67
      2622680.59     10077068.44      2622708.47     10077083.73

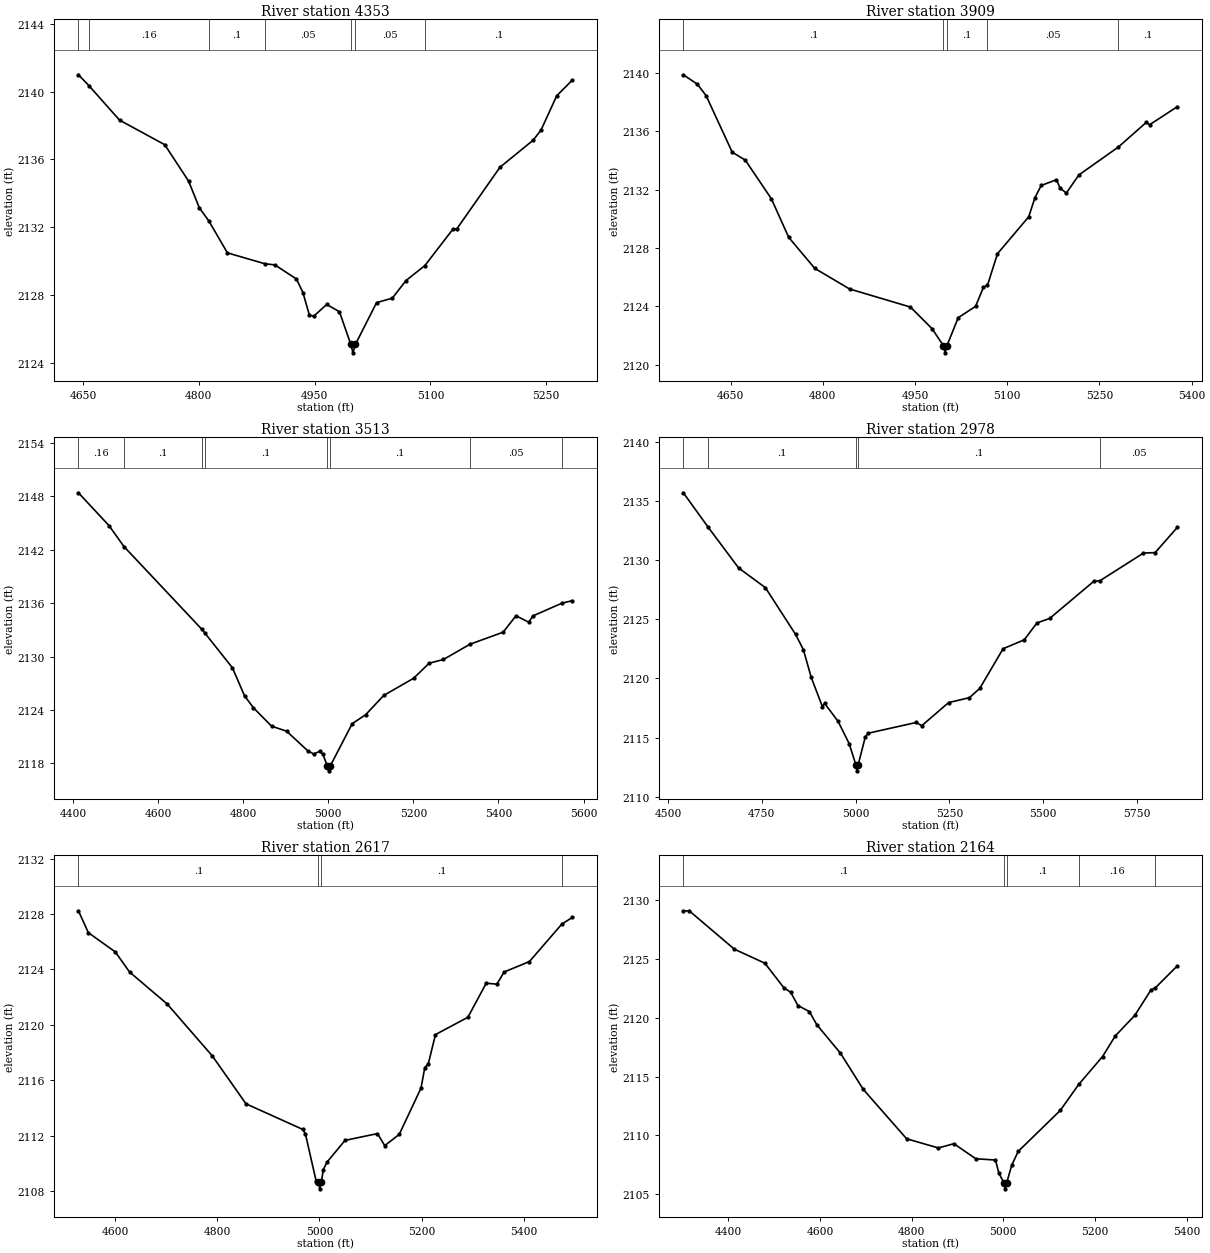
Type RM Length L Ch R = 1,4353,444,444,444
BEGIN DESCRIPTION:
UNT 0002 IN HEWA 10.0
END DESCRIPTION:
XS GIS Cut Line= 3
      2620768.51     10080103.75      2620468.47     10079953.73
      2620168.46     10079903.73
#Sta/Elev= 30
  4644.2 2140.99  4657.8 2140.35  4697.4 2138.32  4756.0 2136.87  4786.8 2134.73
  4800.8 2133.15  4813.2 2132.37  4837.1 2130.50  4885.4 2129.86  4898.6 2129.79
  4926.5 2128.96  4934.9 2128.16  4943.3 2126.83  4948.9 2126.77  4965.7 2127.46
  4982.2 2127.03  4996.9 2125.11  4999.7 2124.61  5002.9 2125.11  5030.3 2127.57
  5050.6 2127.83  5068.4 2128.87  5092.8 2129.75  5129.2 2131.90  5134.3 2131.92
  5190.0 2135.54  5233.1 2137.14  5243.2 2137.73  5263.5 2139.75  5283.8 2140.68
#Mann=7,-1,0
  4644.2     0.1       0  4657.8    0.16       0  4813.2     0.1       0
  4885.4    0.05       0  4996.9    0.04       0  5002.9    0.05       0
  5092.8     0.1       0
Bank Sta=4996.9,5002.9
Exp/Cntr=0.3,0.1

Type RM Length L Ch R = 1,3909,396,396,396
BEGIN DESCRIPTION:
UNT 0002 IN HEWA 9.0
END DESCRIPTION:
XS GIS Cut Line= 3
      2620926.06     10079858.50      2620575.37     10079511.28
      2620271.66     10079449.16
#Sta/Elev= 30
  4573.1 2139.87  4596.0 2139.22  4610.1 2138.44  4652.6 2134.56  4673.8 2134.02
  4716.2 2131.37  4744.5 2128.72  4786.9 2126.59  4843.5 2125.18  4942.5 2123.94
  4977.8 2122.45  4996.0 2121.30  4998.8 2120.80  5002.0 2121.30  5020.2 2123.21
  5048.5 2123.99  5061.3 2125.30  5067.8 2125.43  5084.1 2127.60  5134.9 2130.13
  5145.1 2131.45  5155.3 2132.28  5180.0 2132.67  5185.9 2132.10  5196.1 2131.76
  5216.5 2133.00  5280.6 2134.91  5326.3 2136.61  5331.4 2136.44  5376.6 2137.68
#Mann=5,-1,0
  4573.1     0.1       0  4996.0    0.07       0  5002.0     0.1       0
  5067.8    0.05       0  5280.6     0.1       0
Bank Sta=4996,5002
Exp/Cntr=0.3,0.1

Type RM Length L Ch R = 1,3513,535,535,535
BEGIN DESCRIPTION:
UNT 0002 IN HEWA 8.0
END DESCRIPTION:
XS GIS Cut Line= 3
      2621321.89     10079702.24      2620860.09     10079250.86
      2620346.22     10079216.14
#Sta/Elev= 30
  4412.8 2148.41  4484.9 2144.71  4519.8 2142.37  4703.1 2133.06  4709.4 2132.68
  4774.8 2128.74  4803.1 2125.60  4824.2 2124.25  4866.7 2122.19  4902.1 2121.62
  4951.6 2119.43  4965.7 2119.06  4979.8 2119.36  4987.0 2119.07  4998.1 2117.67
  5000.9 2117.17  5004.1 2117.67  5056.2 2122.47  5087.7 2123.47  5130.3 2125.64
  5200.5 2127.57  5237.0 2129.26  5270.7 2129.68  5332.8 2131.39  5411.0 2132.75
  5441.1 2134.59  5471.1 2133.87  5481.1 2134.58  5549.3 2136.01  5573.6 2136.29
#Mann=8,-1,0
  4412.8    0.16       0  4519.8     0.1       0  4703.1    0.16       0
  4709.4     0.1       0  4998.1    0.07       0  5004.1     0.1       0
  5332.8    0.05       0  5549.3     0.1       0
Bank Sta=4998.1,5004.1
Exp/Cntr=0.3,0.1

Type RM Length L Ch R = 1,2978,361,361,361
BEGIN DESCRIPTION:
UNT 0002 IN HEWA 7.0
END DESCRIPTION:
XS GIS Cut Line= 3
      2621576.00     10079171.98      2621042.11     10078798.69
      2620401.65     10078980.45
#Sta/Elev= 30
  4540.7 2135.70  4607.0 2132.78  4688.1 2129.34  4759.6 2127.67  4839.8 2123.73
  4860.8 2122.43  4881.7 2120.08  4911.4 2117.62  4917.5 2117.88  4953.2 2116.37
  4982.9 2114.48  5000.8 2112.68  5003.5 2112.18  5006.8 2112.68  5025.8 2115.04
  5033.4 2115.36  5161.6 2116.27  5176.5 2116.00  5247.9 2117.95  5303.6 2118.37
  5331.1 2119.15  5393.4 2122.51  5449.7 2123.26  5483.6 2124.69  5517.5 2125.07
  5634.8 2128.20  5651.6 2128.26  5767.7 2130.60  5798.8 2130.64  5857.9 2132.77
#Mann=5,-1,0
  4540.7    0.16       0  4607.0     0.1       0  5000.8    0.07       0
  5006.8     0.1       0  5651.6    0.05       0
Bank Sta=5000.8,5006.8
Exp/Cntr=0.3,0.1

Type RM Length L Ch R = 1,2617,453,453,453
BEGIN DESCRIPTION:
UNT 0002 IN HEWA 6.0
END DESCRIPTION:
XS GIS Cut Line= 3
      2621540.64     10078980.02      2621318.42     10078601.56
      2620964.29     10078209.23
#Sta/Elev= 30
  4527.9 2128.23  4547.3 2126.65  4600.1 2125.26  4628.0 2123.81  4701.7 2121.50
  4790.3 2117.74  4856.1 2114.29  4966.8 2112.45  4972.4 2112.13  4993.3 2108.74
  4997.8 2108.65  5000.5 2108.15  5003.8 2108.65  5007.5 2109.54  5015.0 2110.09
  5050.1 2111.65  5113.6 2112.14  5127.8 2111.27  5156.2 2112.08  5198.8 2115.42
  5206.3 2116.91  5213.0 2117.16  5227.2 2119.29  5290.7 2120.54  5326.6 2123.00
  5347.5 2122.93  5361.7 2123.81  5411.1 2124.56  5474.7 2127.27  5495.3 2127.75
#Mann=4,-1,0
  4527.9     0.1       0  4997.8    0.07       0  5003.8     0.1       0
  5474.7    0.16       0
Bank Sta=4997.8,5003.8
Exp/Cntr=0.3,0.1

Type RM Length L Ch R = 1,2164,284,284,284
BEGIN DESCRIPTION:
UNT 0002 IN HEWA 5.0
END DESCRIPTION:
XS GIS Cut Line= 3
      2621801.06     10078966.14      2621641.34     10078337.67
      2621346.19     10078025.16
#Sta/Elev= 30
  4301.6 2129.08  4314.4 2129.11  4413.0 2125.84  4479.5 2124.65  4520.8 2122.57
  4535.8 2122.18  4551.7 2121.05  4576.8 2120.53  4593.0 2119.41  4644.6 2116.99
  4694.4 2113.91  4789.0 2109.71  4858.2 2108.93  4892.2 2109.29  4940.0 2108.01
  4983.0 2107.90  4990.2 2106.81  5001.4 2105.95  5004.2 2105.45  5007.4 2105.95
  5018.6 2107.48  5032.7 2108.64  5124.6 2112.13  5164.6 2114.33  5216.8 2116.71
  5244.7 2118.47  5287.2 2120.21  5322.8 2122.40  5331.9 2122.55  5379.9 2124.42
#Mann=5,-1,0
  4301.6     0.1       0  5001.4    0.07       0  5007.4     0.1       0
  5164.6    0.16       0  5331.9     0.1       0
Bank Sta=5001.4,5007.4
Exp/Cntr=0.3,0.1

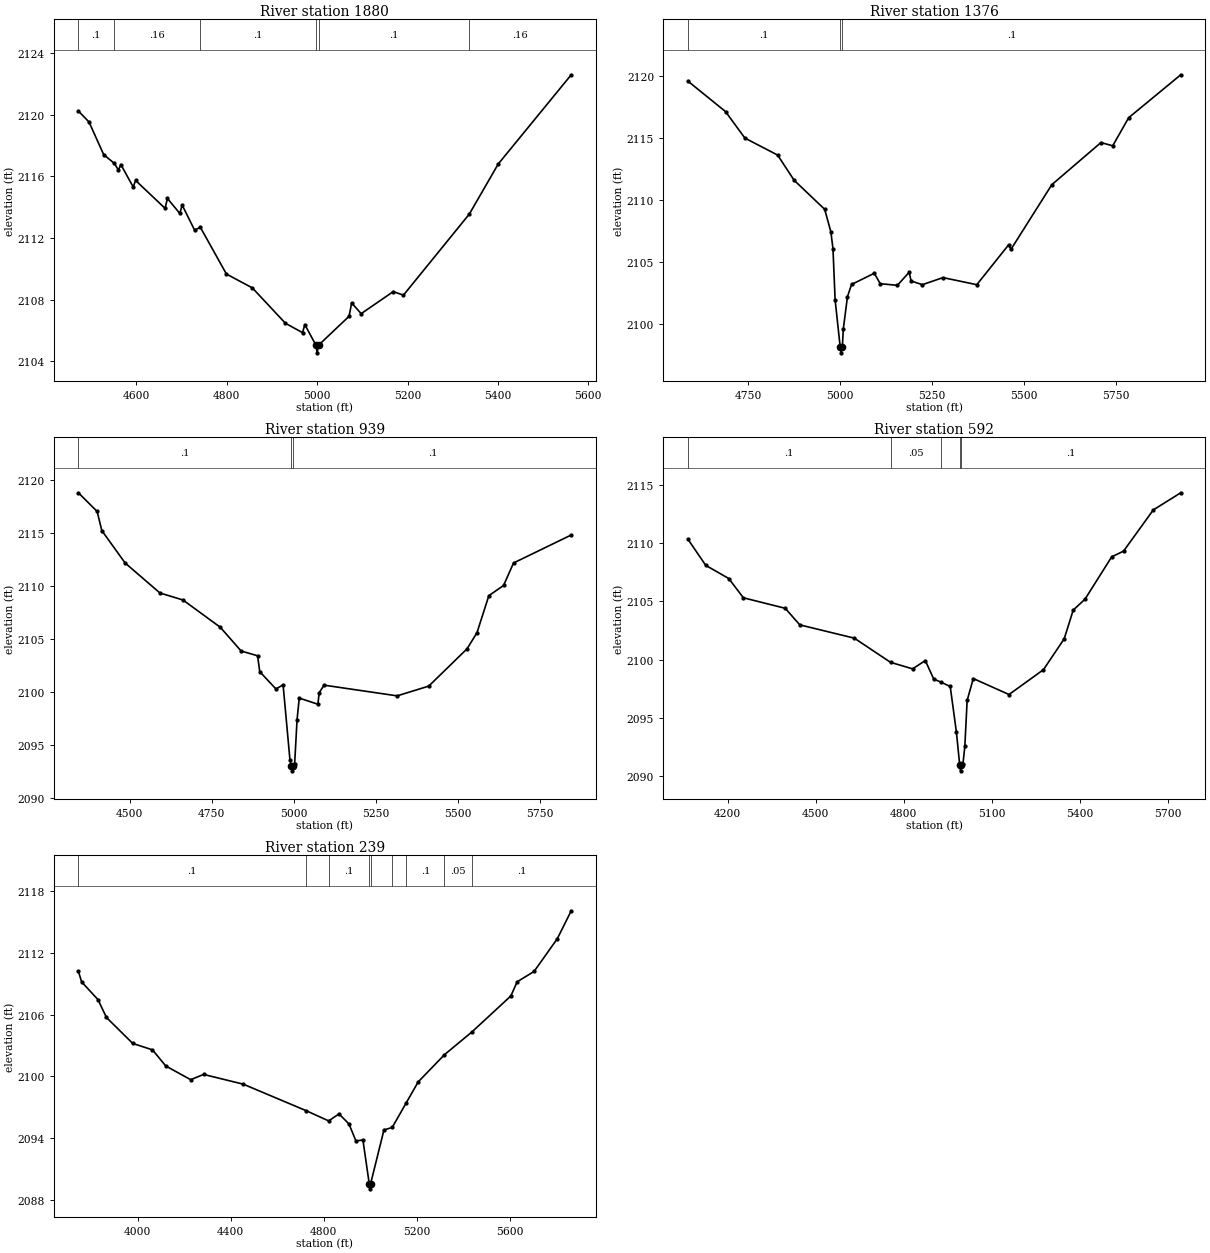
Type RM Length L Ch R = 1,1880,504,504,504
BEGIN DESCRIPTION:
UNT 0002 IN HEWA 4.0
END DESCRIPTION:
XS GIS Cut Line= 3
      2622030.23     10078771.69      2621839.26     10078153.64
      2621467.69     10077910.56
#Sta/Elev= 30
  4471.4 2120.23  4494.9 2119.52  4527.5 2117.40  4550.8 2116.84  4560.1 2116.40
  4565.4 2116.76  4592.8 2115.30  4598.0 2115.73  4663.3 2113.92  4668.5 2114.56
  4695.9 2113.59  4701.2 2114.13  4728.6 2112.51  4741.4 2112.69  4799.1 2109.66
  4856.5 2108.76  4929.6 2106.47  4967.5 2105.86  4972.7 2106.38  4997.1 2105.05
  4999.9 2104.55  5003.1 2105.05  5070.6 2106.92  5076.3 2107.79  5097.3 2107.09
  5168.4 2108.52  5190.9 2108.29  5336.8 2113.55  5400.6 2116.79  5562.3 2122.58
#Mann=6,-1,0
  4471.4     0.1       0  4550.8    0.16       0  4741.4     0.1       0
  4997.1    0.07       0  5003.1     0.1       0  5336.8    0.16       0
Bank Sta=4997.1,5003.1
Exp/Cntr=0.3,0.1

Type RM Length L Ch R = 1,1376,437,437,437
BEGIN DESCRIPTION:
UNT 0002 IN HEWA 3.0
END DESCRIPTION:
XS GIS Cut Line= 3
      2622547.60     10078542.55      2622311.48     10078063.36
      2621554.55     10077789.06
#Sta/Elev= 30
  4586.4 2119.56  4688.6 2117.11  4741.2 2114.98  4830.3 2113.61  4874.9 2111.59
  4958.1 2109.25  4975.0 2107.42  4980.6 2106.08  4986.4 2101.97  5000.1 2098.21
  5002.8 2097.71  5006.1 2098.21  5008.7 2099.63  5019.9 2102.22  5031.1 2103.21
  5092.9 2104.11  5109.0 2103.27  5155.7 2103.14  5187.6 2104.19  5192.9 2103.49
  5223.5 2103.19  5279.5 2103.76  5371.4 2103.19  5458.0 2106.40  5464.2 2106.03
  5575.2 2111.23  5708.8 2114.62  5740.7 2114.36  5784.2 2116.62  5925.7 2120.07
#Mann=3,-1,0
  4586.4     0.1       0  5000.1    0.07       0  5006.1     0.1       0
Bank Sta=5000.1,5006.1
Exp/Cntr=0.3,0.1

Type RM Length L Ch R = 1,939,347,347,347
BEGIN DESCRIPTION:
UNT 0002 IN HEWA 2.0
END DESCRIPTION:
XS GIS Cut Line= 3
      2623061.47     10078351.55      2622571.89     10077802.95
      2621814.94     10077677.94
#Sta/Elev= 30
  4344.0 2118.80  4401.2 2117.04  4415.4 2115.24  4486.5 2112.18  4592.7 2109.35
  4662.9 2108.69  4776.6 2106.12  4840.2 2103.88  4890.3 2103.43  4897.0 2101.93
  4946.3 2100.30  4968.1 2100.69  4989.0 2093.61  4993.5 2093.08  4996.2 2092.58
  4999.5 2093.08  5003.2 2093.18  5010.7 2097.42  5017.4 2099.44  5074.2 2098.86
  5078.1 2099.94  5092.9 2100.66  5315.9 2099.65  5412.1 2100.57  5528.7 2104.08
  5559.1 2105.60  5595.4 2109.10  5640.2 2110.06  5670.6 2112.18  5846.5 2114.82
#Mann=3,-1,0
  4344.0     0.1       0  4993.5    0.07       0  4999.5     0.1       0
Bank Sta=4993.5,4999.5
Exp/Cntr=0.3,0.1

Type RM Length L Ch R = 1,592,353,353,353
BEGIN DESCRIPTION:
Mapping XS 6e3a36b6
END DESCRIPTION:
XS GIS Cut Line= 3
      2623330.88     10078136.72      2622456.78     10077435.10
      2621905.76     10077356.17
#Sta/Elev= 30
  4065.2 2110.33  4125.9 2108.09  4204.3 2106.96  4254.0 2105.31  4396.4 2104.41
  4446.0 2102.99  4631.6 2101.85  4754.8 2099.78  4830.0 2099.22  4873.2 2099.93
  4901.8 2098.35  4926.4 2098.08  4958.0 2097.71  4978.9 2093.83  4990.3 2090.98
  4993.0 2090.48  4996.3 2090.98  5001.2 2091.04  5007.7 2092.57  5015.6 2096.51
  5036.5 2098.39  5158.1 2097.02  5275.3 2099.15  5346.0 2101.80  5376.7 2104.26
  5416.7 2105.19  5507.6 2108.82  5548.0 2109.31  5649.1 2112.84  5742.7 2114.31
#Mann=5,-1,0
  4065.2     0.1       0  4754.8    0.05       0  4926.4     0.1       0
  4990.3    0.07       0  4996.3     0.1       0
Bank Sta=4990.3,4996.3
Exp/Cntr=0.3,0.1

Type RM Length L Ch R = 1,239,0,0,0
BEGIN DESCRIPTION:
UNT 0002 IN HEWA 1.0
END DESCRIPTION:
XS GIS Cut Line= 3
      2623453.67     10078127.96      2622700.88     10077217.31
      2621766.92     10077122.30
#Sta/Elev= 30
  3744.8 2110.23  3758.8 2109.19  3829.1 2107.47  3865.6 2105.73  3978.9 2103.20
  4063.6 2102.58  4120.9 2101.01  4227.8 2099.68  4283.7 2100.19  4454.4 2099.24
  4723.0 2096.68  4821.5 2095.67  4866.1 2096.35  4909.0 2095.37  4938.8 2093.72
  4969.0 2093.81  4996.1 2089.56  4998.9 2089.06  5002.1 2089.56  5059.4 2094.79
  5094.9 2095.03  5155.9 2097.45  5206.9 2099.47  5319.8 2102.11  5438.7 2104.34
  5605.6 2107.83  5632.4 2109.20  5705.3 2110.21  5804.9 2113.38  5865.1 2116.11
#Mann=9,-1,0
  3744.8     0.1       0  4723.0    0.05       0  4821.5     0.1       0
  4996.1    0.07       0  5002.1     0.1       0  5094.9    0.05       0
  5155.9     0.1       0  5319.8    0.05       0  5438.7     0.1       0
Bank Sta=4996.1,5002.1
Exp/Cntr=0.3,0.1

Chan Stop Cuts=-1