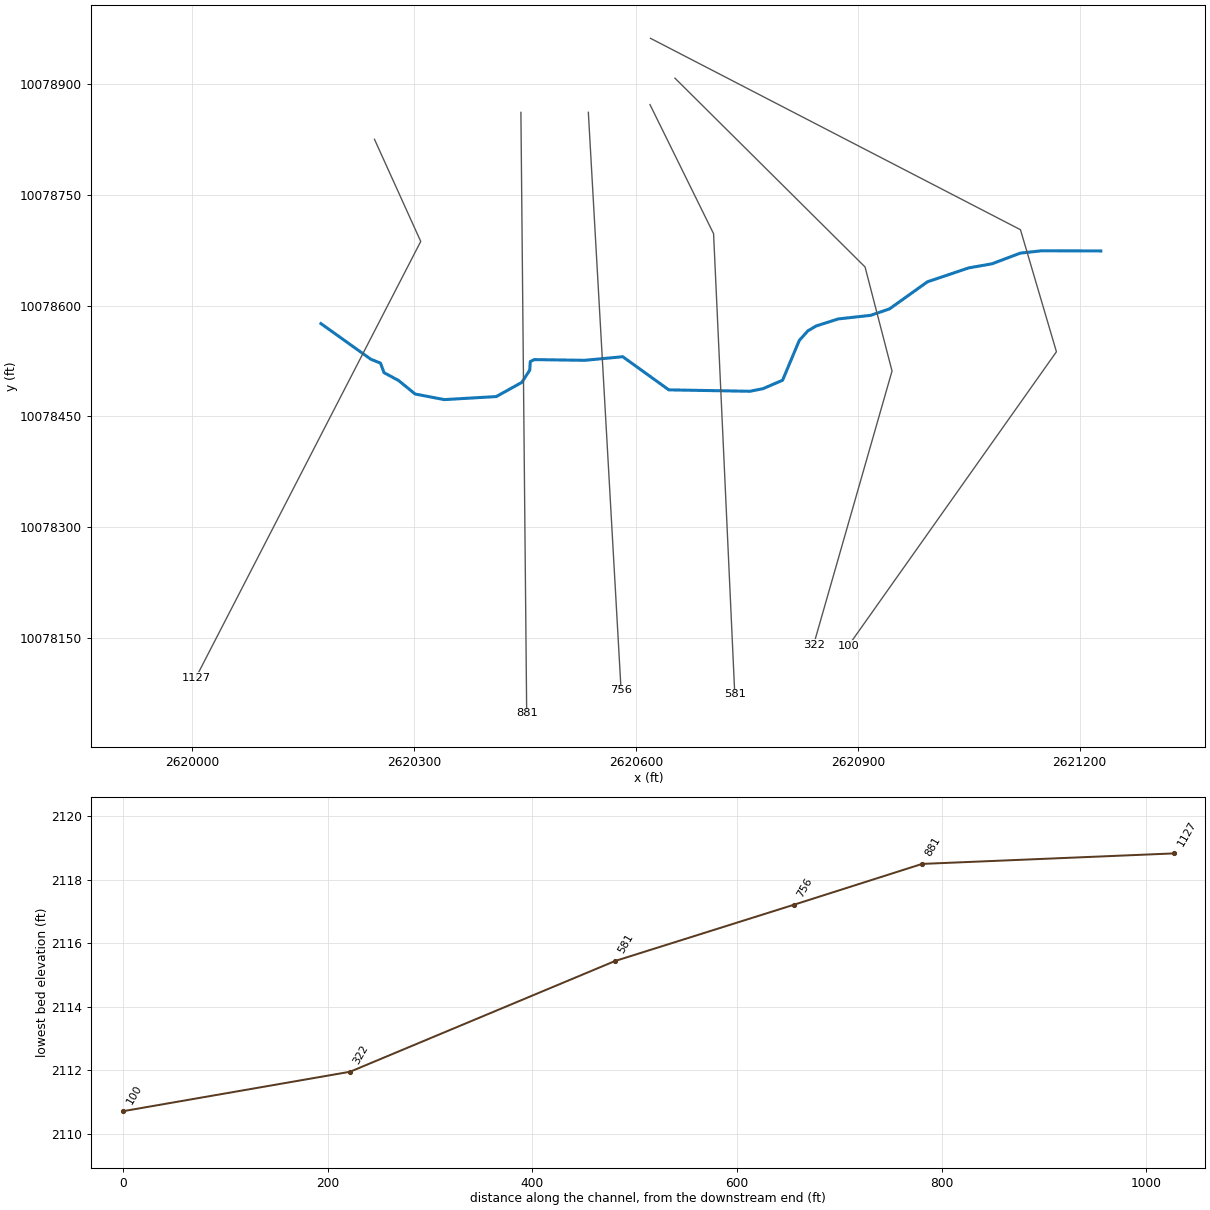
--- UNT 0003 IN HEWA.prj (project) ---

Proj Title=UNT 0003 IN HEWA Base Level Engineering
Current Plan=p01
Default Exp/Contr=0.3,0.1
English Units
Geom File=g01
Flow File=f01
Plan File=p01
Y Axis Title=Elevation
X Axis Title(PF)=Main Channel Distance
X Axis Title(XS)=Station
BEGIN DESCRIPTION:
UNT 0003 IN HEWA
END DESCRIPTION:
DSS Export Rating Curves= 0
DSS Export Rating Curve Sorted= 0
DSS Export Volume Flow Curves= 0
DXF OffsetX= 0
DXF OffsetY= 0
DXF ScaleX= 1
DXF ScaleY= 10

--- UNT 0003 IN HEWA.p01 (plan) ---

Plan Title=Multiple Run
Short Identifier=Multiple
Geom File=g01
Flow File=f01
Subcritical Flow
K Sum by GR= 0
Std Step Tol= 0.01
Critical Tol= 0.01
Num of Std Step Trials= 20
Max Error Tol= 0.3
Flow Tol Ratio= 0.001
Split Flow NTrial= 30
Split Flow Tol= 0.02
Split Flow Ratio= 0.02
Log Output Level= 0
Friction Slope Method= 1
Unsteady Friction Slope Method= 2
Unsteady Bridges Friction Slope Method= 1
Parabolic Critical Depth
Global Vel Dist=  1 , 1 , 1
Global Log Level= 0
CheckData=True
Encroach Param= -1, 0, 0, 0
BEGIN DESCRIPTION:
Multiple Run
END DESCRIPTION:

--- UNT 0003 IN HEWA.f01 (steady flow) ---

Flow Title=Multiple
Number of Profiles=7
Profile Names=10-year,25-year,50-year,1pct_min,100-year,1pct_plu,500-year
River Rch & RM= UNT 0003 IN HEWA,Reach-1,1127
     934    1345    1696    1560    2109    2852    3261
Boundary for River Rch & Prof#=UNT 0003 IN HEWA,Reach-1,1
Up Type=0
Dn Type=3
Dn Slope=0.005
Boundary for River Rch & Prof#=UNT 0003 IN HEWA,Reach-1,2
Up Type=0
Dn Type=3
Dn Slope=0.005
Boundary for River Rch & Prof#=UNT 0003 IN HEWA,Reach-1,3
Up Type=0
Dn Type=3
Dn Slope=0.005
Boundary for River Rch & Prof#=UNT 0003 IN HEWA,Reach-1,4
Up Type=0
Dn Type=3
Dn Slope=0.005
Boundary for River Rch & Prof#=UNT 0003 IN HEWA,Reach-1,5
Up Type=0
Dn Type=3
Dn Slope=0.005
Boundary for River Rch & Prof#=UNT 0003 IN HEWA,Reach-1,6
Up Type=0
Dn Type=3
Dn Slope=0.005
Boundary for River Rch & Prof#=UNT 0003 IN HEWA,Reach-1,7
Up Type=0
Dn Type=3
Dn Slope=0.005

--- UNT 0003 IN HEWA.g01 (geometry) ---

Geom Title=Existing Conditions
Program Version=4.10

River Reach=UNT 0003 IN HEWA,Reach-1
Reach XY= 30
      2620174.41     10078575.49      2620241.79     10078527.39
       2620254.9      10078522.1      2620259.69     10078509.18
      2620279.09     10078498.77      2620301.71     10078480.35
      2620341.15      10078472.8      2620411.36     10078476.91
      2620445.88     10078496.06      2620456.64     10078512.73
      2620457.34     10078524.18      2620462.68     10078526.87
      2620530.95     10078525.92      2620582.34     10078530.78
      2620644.59     10078485.97      2620754.13     10078484.07
       2620771.9     10078487.58      2620798.35     10078498.98
      2620820.88     10078552.68      2620832.46     10078565.69
      2620843.83     10078572.35      2620873.65     10078581.86
      2620917.22     10078586.69      2620942.79     10078595.35
      2620994.19     10078632.04      2621049.75     10078650.76
      2621081.48     10078656.38      2621119.66     10078670.79
      2621148.28     10078673.95      2621228.47     10078673.73

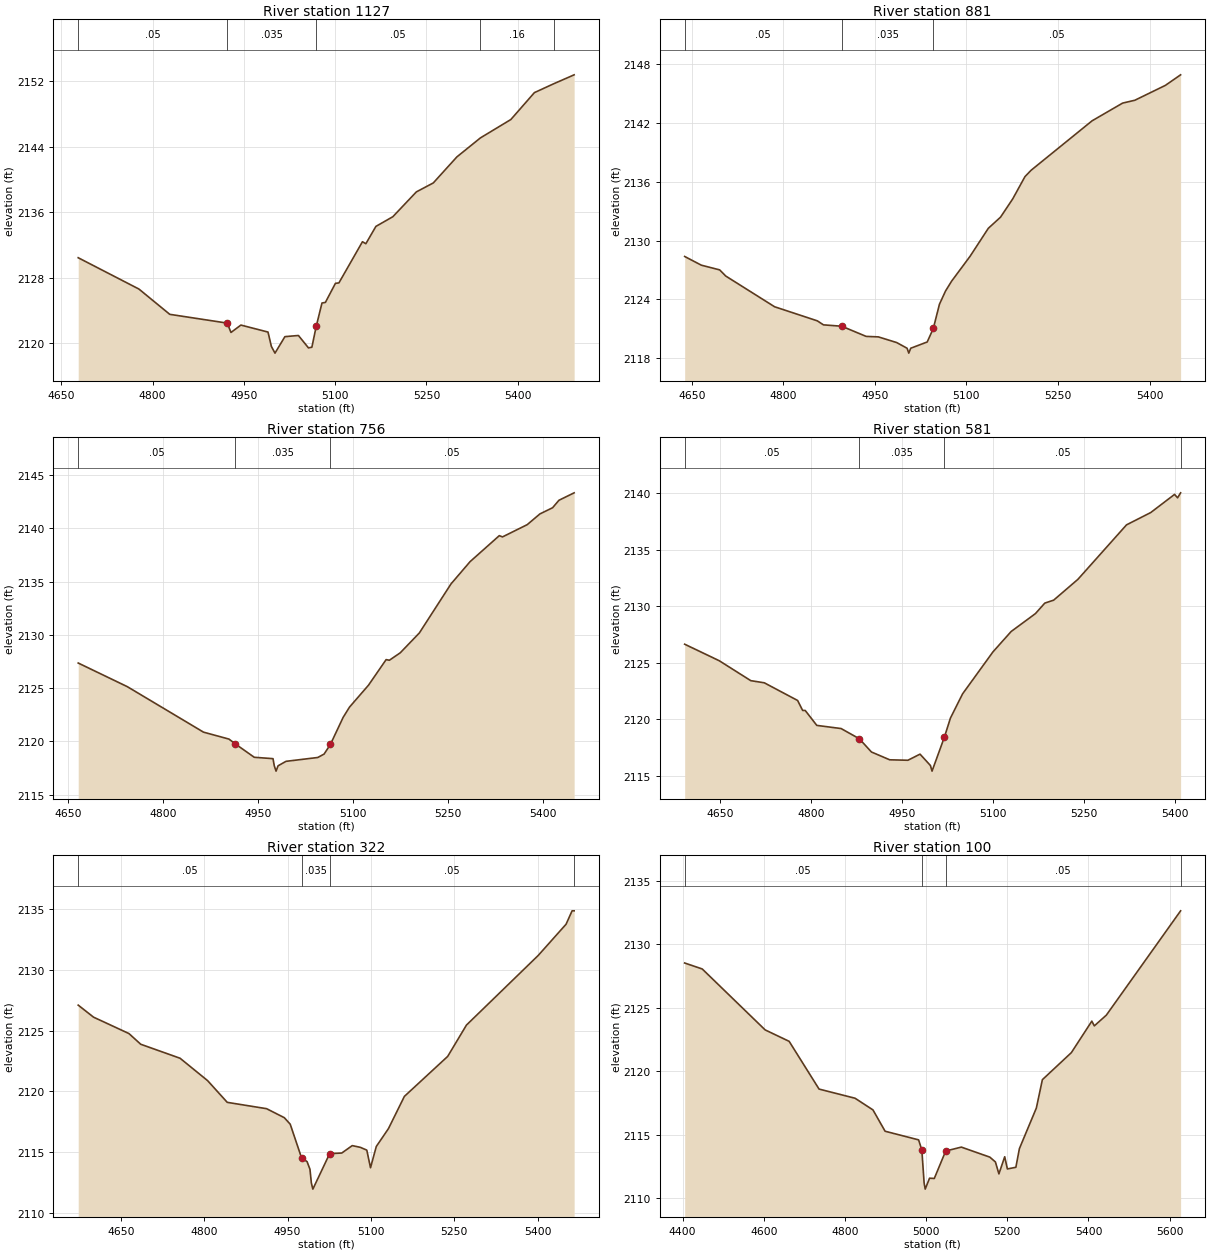
Type RM Length L Ch R = 1 ,1127    ,246,246,246
BEGIN DESCRIPTION:
UNT 0003 IN HEWA 1.0
END DESCRIPTION:
XS GIS Cut Line= 3
      2620246.74     10078824.66      2620309.26     10078686.61
      2620005.39     10078097.06
#Sta/Elev= 30
  4677.9 2130.45  4777.7 2126.63  4828.3 2123.55  4922.7 2122.48  4928.9 2121.34
  4945.2 2122.24  4989.7 2121.39  4995.3 2119.63  5001.2 2118.82  5017.5 2120.83
  5039.7 2120.97  5056.2 2119.46  5061.8 2119.54  5068.9 2122.07  5078.4 2124.93
    5084    2125  5100.5 2127.33  5106.2 2127.38  5144.9  2132.4  5150.5 2132.16
    5167 2134.27  5194.8 2135.45  5233.5 2138.48  5261.3 2139.57    5300 2142.74
  5338.7 2145.06  5388.7  2147.3  5427.4 2150.58  5458.8 2151.65  5492.7 2152.75
#Mann= 5 ,-1 , 0
  4677.9     .05       0  4922.7    .035       0  5068.9     .05       0
  5338.7     .16       0  5458.8      .1       0
Bank Sta=4922.7,5068.9
XS Rating Curve= 0 ,0
Exp/Cntr=0.3,0.1

Type RM Length L Ch R = 1 ,881     ,125,125,125
BEGIN DESCRIPTION:
UNT 0003 IN HEWA 2.0
END DESCRIPTION:
XS GIS Cut Line= 2
      2620444.67     10078861.06      2620452.48      10078048.7
#Sta/Elev= 30
  4638.5 2128.37  4665.8 2127.48  4695.8    2127  4705.8 2126.37  4785.8 2123.23
  4855.8 2121.79  4865.8 2121.38  4895.8 2121.24  4935.8  2120.2  4955.8 2120.15
  4985.8 2119.57  5002.8 2118.99  5005.6 2118.49  5008.8 2118.99  5035.8 2119.63
  5045.8 2121.01  5055.8 2123.48  5065.8 2124.84  5075.8 2125.85  5105.9 2128.38
  5135.9 2131.25  5155.9 2132.39  5175.9 2134.26  5195.9 2136.53  5205.9 2137.18
  5305.9 2142.24  5355.9 2144.05  5375.9 2144.34  5425.9 2145.86  5450.9 2146.94
#Mann= 3 , 0 , 0
  4638.5     .05       0  4895.8    .035       0  5045.8     .05       0
Bank Sta=4895.8,5045.8
XS Rating Curve= 0 ,0
Exp/Cntr=0.3,0.1

Type RM Length L Ch R = 1 ,756     ,175,175,175
BEGIN DESCRIPTION:
UNT 0003 IN HEWA 3.0
END DESCRIPTION:
XS GIS Cut Line= 2
      2620535.82     10078861.13      2620580.09     10078079.79
#Sta/Elev= 30
  4666.5 2127.36    4744 2125.14  4864.2 2120.87  4904.3 2120.22  4914.3 2119.77
  4944.3 2118.51  4973.9 2118.38  4975.9 2117.71  4978.7 2117.21  4981.9 2117.71
  4994.4 2118.13  5044.5 2118.49  5054.5 2118.81  5064.5 2119.72  5084.6 2122.26
  5094.6 2123.22  5124.6 2125.28  5152.4 2127.68  5157.5 2127.62  5174.7 2128.32
  5204.8 2130.18  5254.8 2134.79  5284.9 2136.88    5331 2139.32    5336  2139.2
    5375 2140.35  5395.1 2141.36  5415.1 2141.94  5425.1 2142.64  5449.1 2143.34
#Mann= 3 , 0 , 0
  4666.5     .05       0  4914.3    .035       0  5064.5     .05       0
Bank Sta=4914.3,5064.5
XS Rating Curve= 0 ,0
Exp/Cntr=0.3,0.1

Type RM Length L Ch R = 1 ,581     ,259,259,259
BEGIN DESCRIPTION:
UNT 0003 IN HEWA 4.0
END DESCRIPTION:
XS GIS Cut Line= 3
      2620619.13     10078871.54      2620705.09     10078697.02
      2620733.74     10078074.62
#Sta/Elev= 30
  4591.9 2126.65  4648.9 2125.19  4700.9 2123.43  4723.2 2123.24  4778.1 2121.68
  4786.4  2120.8  4790.6  2120.8  4809.7 2119.48  4849.8  2119.2  4879.8  2118.3
  4899.8 2117.13  4929.9 2116.44  4959.9  2116.4  4979.9 2116.94    4997 2115.94
  4999.7 2115.44    5020 2118.43    5030 2120.12    5050 2122.26  5100.1 2125.97
  5130.1 2127.77  5170.1 2129.35  5185.6 2130.28  5200.2 2130.54  5240.2 2132.38
  5320.3 2137.19  5360.3 2138.28  5399.5 2139.88  5404.5 2139.58  5409.5 2140.02
#Mann= 4 ,-1 , 0
  4591.9     .05       0  4879.8    .035       0    5020     .05       0
  5409.5      .1       0
Bank Sta=4879.8,5020
XS Rating Curve= 0 ,0
Exp/Cntr=0.3,0.1

Type RM Length L Ch R = 1 ,322     ,222,222,222
BEGIN DESCRIPTION:
Mapping XS 3a5ceda0
END DESCRIPTION:
XS GIS Cut Line= 4
       2620652.9     10078907.27      2620909.83     10078652.08
      2620946.29     10078511.46      2620840.37     10078141.62
#Sta/Elev= 30
  4573.4  2127.1    4601 2126.11  4664.7 2124.76  4685.9 2123.88  4756.6 2122.73
  4806.1 2120.89  4841.5  2119.1  4912.2 2118.58  4944.1 2117.84  4954.8  2117.3
  4975.1 2114.54  4985.1 2114.22  4990.3 2113.59  4992.8 2112.46  4995.5 2111.96
  5025.7 2114.88  5047.5 2114.93  5066.3 2115.54  5080.8  2115.4  5092.5 2115.17
  5099.2 2113.72  5109.6 2115.47  5131.5 2116.94  5160.1 2119.59    5238 2122.88
  5271.8 2125.46  5400.9 2131.19    5451 2133.76  5461.8 2134.86  5465.5 2134.86
#Mann= 4 ,-1 , 0
  4573.4     .05       0  4975.1    .035       0  5025.7     .05       0
  5465.5      .1       0
Bank Sta=4975.1,5025.7
XS Rating Curve= 0 ,0
Exp/Cntr=0.3,0.1

Type RM Length L Ch R = 1 ,100     ,0,0,0
BEGIN DESCRIPTION:
UNT 0003 IN HEWA 5.0
END DESCRIPTION:
XS GIS Cut Line= 4
      2620619.87     10078961.12       2621119.9     10078702.43
      2621168.51      10078537.5      2620887.27     10078139.94
#Sta/Elev= 30
  4405.1 2128.53  4448.4 2128.06  4603.4 2123.26  4662.5 2122.36  4736.2  2118.6
  4824.8 2117.88    4869 2116.96  4898.9 2115.28  4981.5  2114.6 4989.43 2113.79
    4995 2111.22  4997.7 2110.72  5008.4 2111.58  5020.1 2111.56  5048.2 2113.72
  5086.7 2114.03  5156.9 2113.24  5170.7 2112.86  5179.3 2111.92  5193.6 2113.27
  5200.2 2112.31  5221.1 2112.44  5229.8 2113.91  5271.6 2117.11  5286.4 2119.34
  5357.8 2121.47  5408.2 2123.95  5414.4 2123.58  5443.9 2124.42    5627 2132.64
#Mann= 4 ,-1 , 0
  4405.1     .05       0 4989.43    .035       0  5048.2     .05       0
    5627      .1       0
Bank Sta=4989.43,5048.2
XS Rating Curve= 0 ,0
Exp/Cntr=0.3,0.1

Chan Stop Cuts=-1
Use User Specified Reach Order=0
Composite Channel Slope=5