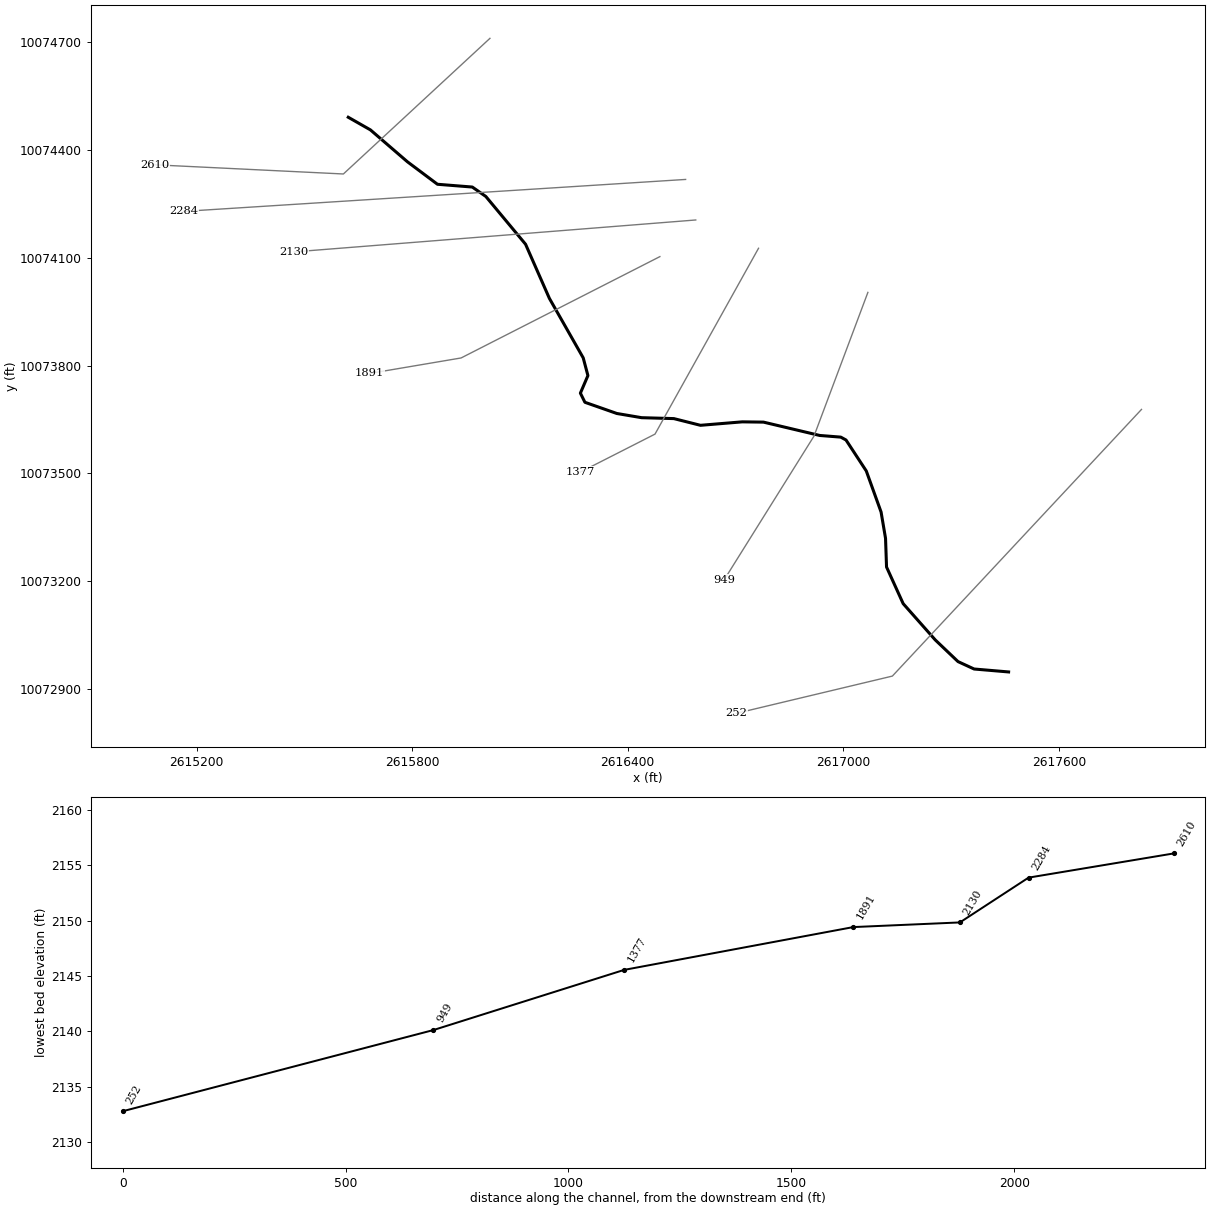
--- UNT 0004 IN HEWA.prj (project) ---

Proj Title=UNT 0004 IN HEWA Base Level Engineering
Current Plan=p01
Default Exp/Contr=0.3,0.1
English Units
Geom File=g01
Flow File=f01
Plan File=p01
Y Axis Title=Elevation
X Axis Title(PF)=Main Channel Distance
X Axis Title(XS)=Station
BEGIN DESCRIPTION:
UNT 0004 IN HEWA
END DESCRIPTION:
DSS Export Rating Curves= 0
DSS Export Rating Curve Sorted= 0
DSS Export Volume Flow Curves= 0
DXF OffsetX= 0
DXF OffsetY= 0
DXF ScaleX= 1
DXF ScaleY= 10

--- UNT 0004 IN HEWA.p01 (plan) ---

Plan Title=Multiple Run
Short Identifier=Multiple
Geom File=g01
Flow File=f01
Subcritical Flow
K Sum by GR= 0
Std Step Tol= 0.01
Critical Tol= 0.01
Num of Std Step Trials= 20
Max Error Tol= 0.3
Flow Tol Ratio= 0.001
Split Flow NTrial= 30
Split Flow Tol= 0.02
Split Flow Ratio= 0.02
Log Output Level= 0
Friction Slope Method= 1
Unsteady Friction Slope Method= 2
Unsteady Bridges Friction Slope Method= 1
Parabolic Critical Depth
Global Vel Dist=  1 , 1 , 1
Global Log Level= 0
CheckData=True
Encroach Param= -1, 0, 0, 0
BEGIN DESCRIPTION:
Multiple Run
END DESCRIPTION:

--- UNT 0004 IN HEWA.f01 (steady flow) ---

Flow Title=Multiple
Program Version=4.10
Number of Profiles= 7
Profile Names=10-year,25-year,50-year,1pct_min,100-year,1pct_plu,500-year
River Rch & RM=UNT 0004 IN HEWA,Reach-1         ,2610
     993    1431    1806    1660    2245    3037    3472
Boundary for River Rch & Prof#=UNT 0004 IN HEWA,Reach-1         , 1
Up Type= 0
Dn Type= 3
Dn Slope=0.5
Boundary for River Rch & Prof#=UNT 0004 IN HEWA,Reach-1         , 2
Up Type= 0
Dn Type= 3
Dn Slope=0.5
Boundary for River Rch & Prof#=UNT 0004 IN HEWA,Reach-1         , 3
Up Type= 0
Dn Type= 3
Dn Slope=0.5
Boundary for River Rch & Prof#=UNT 0004 IN HEWA,Reach-1         , 4
Up Type= 0
Dn Type= 3
Dn Slope=0.5
Boundary for River Rch & Prof#=UNT 0004 IN HEWA,Reach-1         , 5
Up Type= 0
Dn Type= 3
Dn Slope=0.5
Boundary for River Rch & Prof#=UNT 0004 IN HEWA,Reach-1         , 6
Up Type= 0
Dn Type= 3
Dn Slope=0.5
Boundary for River Rch & Prof#=UNT 0004 IN HEWA,Reach-1         , 7
Up Type= 0
Dn Type= 3
Dn Slope=0.5
DSS Import GetInterval= 0
DSS Import GetPeak= 0
DSS Import FillOption= 0

--- UNT 0004 IN HEWA.g01 (geometry) ---

Geom Title=Existing Conditions
Program Version=4.10

River Reach=UNT 0004 IN HEWA,Reach-1
Reach XY= 30
      2615621.99      10074491.3      2615683.61      10074456.2
      2615786.74     10074367.32       2615870.3     10074304.76
      2615967.27     10074297.06       2616004.9     10074270.86
      2616115.51     10074137.87      2616181.88     10073987.09
      2616276.03     10073821.54      2616289.12     10073772.21
      2616268.16     10073723.36      2616280.75     10073697.86
      2616369.66     10073666.68      2616438.56       10073655.
      2616528.37     10073652.45      2616602.45     10073633.79
       2616718.7      10073643.4      2616777.95     10073642.64
      2616934.31     10073605.53      2616993.02     10073600.88
      2617007.61     10073592.86      2617064.04     10073506.64
      2617105.22     10073392.39      2617117.63      10073319.1
      2617120.41      10073239.3      2617166.71     10073137.31
      2617256.03     10073036.35      2617319.39     10072976.01
      2617364.15     10072955.38      2617460.23      10072947.2

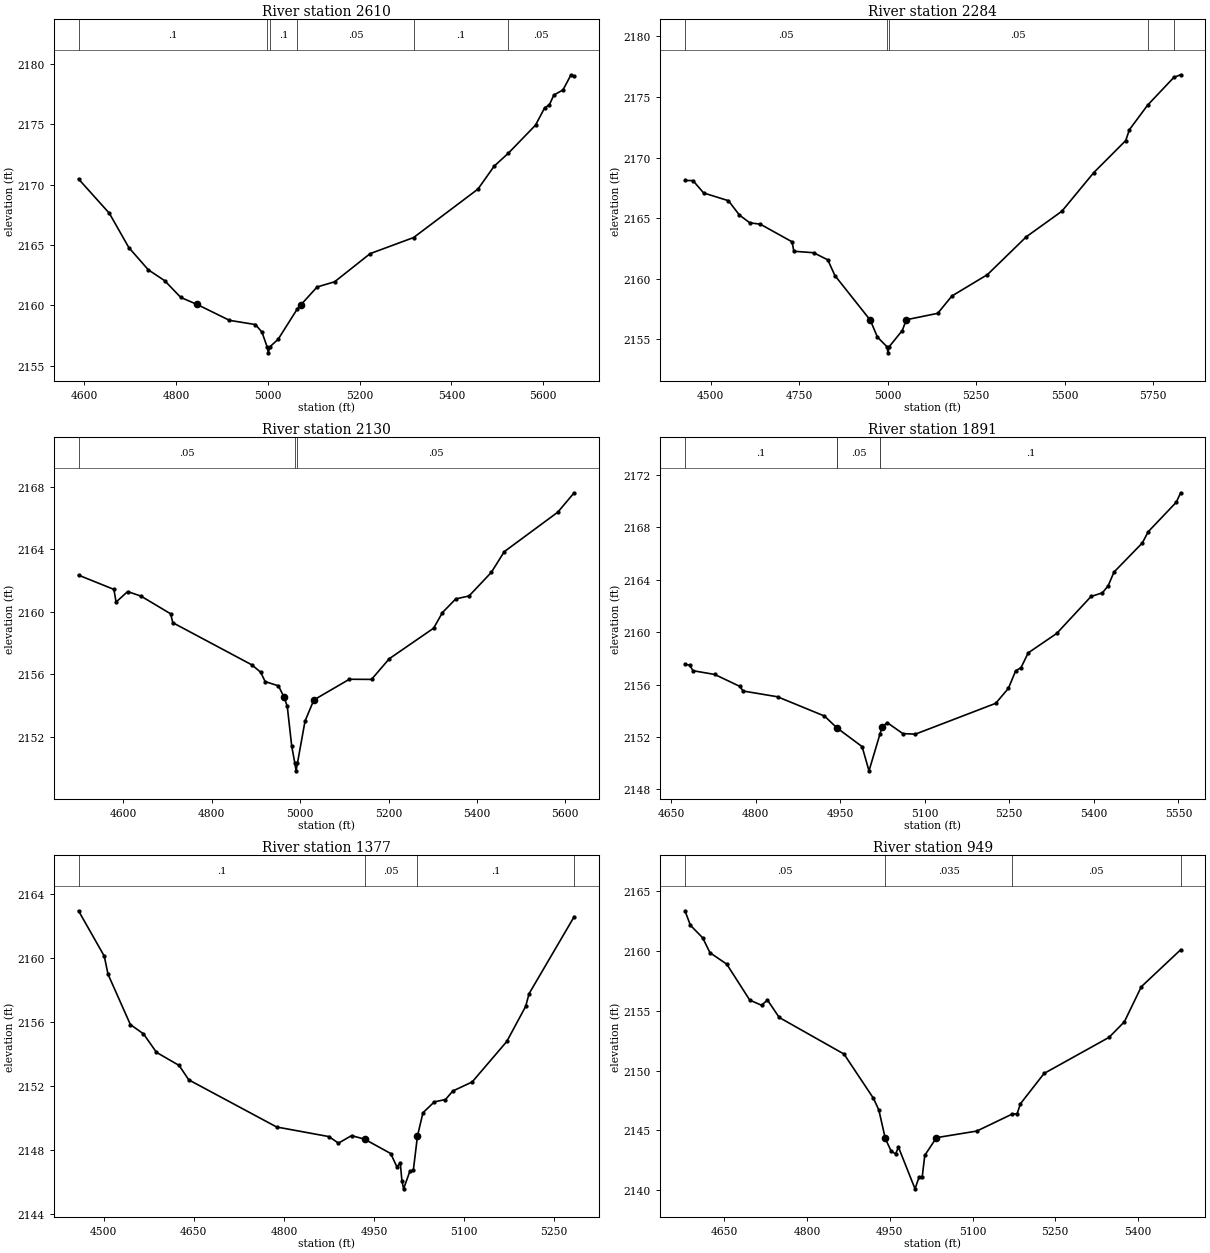
Type RM Length L Ch R = 1 ,2610    ,326,326,326
BEGIN DESCRIPTION:
UNT 0004 IN HEWA 5.0
END DESCRIPTION:
XS GIS Cut Line= 3
      2616016.39     10074711.02      2615608.41     10074333.42
      2615084.24     10074358.95
#Sta/Elev= 30
  4587.1 2170.47  4654.3 2167.63  4696.8 2164.79  4739.3 2162.95    4775 2162.05
  4810.2 2160.66  4845.4 2160.09  4916.2 2158.77  4972.9 2158.42  4987.1 2157.79
  4998.3 2156.58    5001 2156.08  5004.3 2156.58  5022.3  2157.2  5064.1 2159.71
  5072.1 2160.06  5107.3 2161.53  5145.5 2161.96    5223 2164.29  5317.7 2165.62
    5458 2169.63  5493.4 2171.53    5524 2172.59  5583.5 2174.92  5603.5 2176.36
  5613.5 2176.59  5623.5 2177.41  5643.5 2177.84  5660.9 2179.09  5667.8 2178.96
#Mann= 6 ,-1 , 0
  4587.1      .1       0  4998.3     .07       0  5004.3      .1       0
  5064.1     .05       0  5317.7      .1       0    5524     .05       0
Bank Sta=4845.4,5072.1
XS Rating Curve= 0 ,0
Exp/Cntr=0.3,0.1

Type RM Length L Ch R = 1 ,2284    ,154,154,154
BEGIN DESCRIPTION:
Mapping XS de695c85
END DESCRIPTION:
XS GIS Cut Line= 2
       2616561.1     10074318.23      2615163.53     10074229.25
#Sta/Elev= 30
  4426.9 2168.11  4449.6  2168.1  4479.6 2167.08  4549.8 2166.44  4580.6 2165.26
  4609.9 2164.62    4640  2164.5  4729.4 2163.05  4734.5 2162.27  4790.3 2162.15
  4830.4 2161.56  4850.4 2160.27  4950.6 2156.58  4970.6 2155.19  4997.7 2154.39
  5000.4 2153.89  5003.7 2154.39  5040.8 2155.73  5052.2 2156.62    5141 2157.15
  5181.1 2158.58  5281.3 2160.34  5391.5 2163.47  5491.7 2165.57  5581.9 2168.76
  5672.1  2171.4  5682.6  2172.3  5733.9 2174.32  5808.3 2176.62  5827.3 2176.83
#Mann= 5 ,-1 , 0
  4426.9     .05       0  4997.7     .04       0  5003.7     .05       0
  5733.9      .1       0  5808.3     .08       0
Bank Sta=4950.6,5052.2
XS Rating Curve= 0 ,0
Exp/Cntr=0.3,0.1

Type RM Length L Ch R = 1 ,2130    ,239,239,239
BEGIN DESCRIPTION:
Mapping XS 706f6c84
END DESCRIPTION:
XS GIS Cut Line= 2
      2616589.32     10074205.38      2615471.45     10074116.56
#Sta/Elev= 30
  4498.5 2162.34  4578.5 2161.43  4583.5 2160.62  4609.7 2161.29  4639.8    2161
  4706.9 2159.87  4711.9  2159.3  4890.6 2156.61  4910.7 2156.14  4920.7 2155.54
  4950.8 2155.27  4963.5 2154.55  4970.8 2153.96  4980.9 2151.41  4987.9 2150.34
  4990.7 2149.84  4993.9 2150.34    5011 2153.02    5031 2154.37  5111.3 2155.69
  5161.4 2155.68  5201.6    2157  5301.9 2158.95  5321.9 2159.95    5352 2160.82
  5382.1 2161.01  5432.3 2162.51  5461.8 2163.84  5582.8 2166.36  5619.9  2167.6
#Mann= 3 ,-1 , 0
  4498.5     .05       0  4987.9     .04       0  4993.9     .05       0
Bank Sta=4963.5,5031
XS Rating Curve= 0 ,0
Exp/Cntr=0.3,0.1

Type RM Length L Ch R = 1 ,1891    ,514,514,514
BEGIN DESCRIPTION:
UNT 0004 IN HEWA 4.0
END DESCRIPTION:
XS GIS Cut Line= 3
      2616489.47     10074103.38       2615936.1     10073821.27
      2615681.76     10073778.16
#Sta/Elev= 30
  4674.8 2157.54  4683.3 2157.48  4688.9 2157.06  4727.7 2156.77  4772.2 2155.86
  4777.8 2155.51  4838.9 2155.07  4922.2  2153.6  4944.5 2152.69  4988.9 2151.27
  5001.2 2149.42  5020.8 2152.25  5023.9 2152.73  5033.4  2153.1  5061.2 2152.26
  5083.5 2152.22  5225.9 2154.57  5248.4 2155.71  5261.3 2157.05  5270.8 2157.29
  5283.6 2158.42  5334.1  2159.9    5395 2162.72  5415.2    2163  5425.4 2163.54
  5435.7 2164.58  5485.9  2166.8  5496.4 2167.66  5546.2 2169.91  5553.9 2170.63
#Mann= 5 ,-1 , 0
  4674.8      .1       0  4944.5     .16       0  4944.5     .05       0
  5020.8     .16       0  5020.8      .1       0
Bank Sta=4944.5,5023.9
XS Rating Curve= 0 ,0
Exp/Cntr=0.3,0.1

Type RM Length L Ch R = 1 ,1377    ,428,428,428
BEGIN DESCRIPTION:
UNT 0004 IN HEWA 3.0
END DESCRIPTION:
XS GIS Cut Line= 3
      2616764.08     10074126.65      2616475.88     10073609.27
      2616268.43     10073503.71
#Sta/Elev= 30
  4458.1 2162.95    4501 2160.11  4507.2 2158.98  4544.4 2155.83  4566.2 2155.25
  4587.9 2154.09  4625.6 2153.27  4641.6 2152.37  4787.9 2149.42  4874.8 2148.82
  4890.8 2148.41  4912.5 2148.88  4934.2 2148.66  4977.7 2147.76    4988 2146.93
  4993.7 2147.17  4996.4 2146.05  4999.2 2145.55  5009.7 2146.66  5015.4 2146.71
  5022.3 2148.86  5031.4 2150.31  5050.3 2150.99  5068.9 2151.14  5081.1 2151.67
  5113.4 2152.24  5170.9 2154.77  5202.4 2156.97    5208 2157.76  5283.1 2162.58
#Mann= 4 ,-1 , 0
  4458.1      .1       0  4934.2     .05       0  5022.3      .1       0
  5283.1      .1       0
Bank Sta=4934.2,5022.3
XS Rating Curve= 0 ,0
Exp/Cntr=0.3,0.1

Type RM Length L Ch R = 1 ,949     ,697,697,697
BEGIN DESCRIPTION:
UNT 0004 IN HEWA 2.0
END DESCRIPTION:
XS GIS Cut Line= 3
      2617068.48     10074003.77      2616918.47     10073603.73
      2616668.49     10073203.77
#Sta/Elev= 30
  4578.5 2163.36  4588.3 2162.15  4610.6  2161.1  4623.9 2159.85  4654.2  2158.9
    4696 2155.89  4717.4 2155.46  4728.1  2155.9  4749.4 2154.44  4866.9 2151.38
  4920.3 2147.68  4930.1  2146.7  4941.7 2144.33  4952.3 2143.27  4960.4 2143.03
  4965.7 2143.59  4995.7 2140.11  5003.1  2141.1  5008.7  2141.1  5013.4 2142.91
  5034.6 2144.39  5107.7 2144.94  5171.4 2146.35  5180.9 2146.39  5186.8 2147.22
  5229.8 2149.76  5347.7 2152.78  5375.4 2154.08  5406.1 2157.01  5477.4  2160.1
#Mann= 4 ,-1 , 0
  4578.5     .05       0  4941.7    .035       0  5171.4     .05       0
  5477.4     .16       0
Bank Sta=4941.7,5034.6
XS Rating Curve= 0 ,0
Exp/Cntr=0.3,0.1

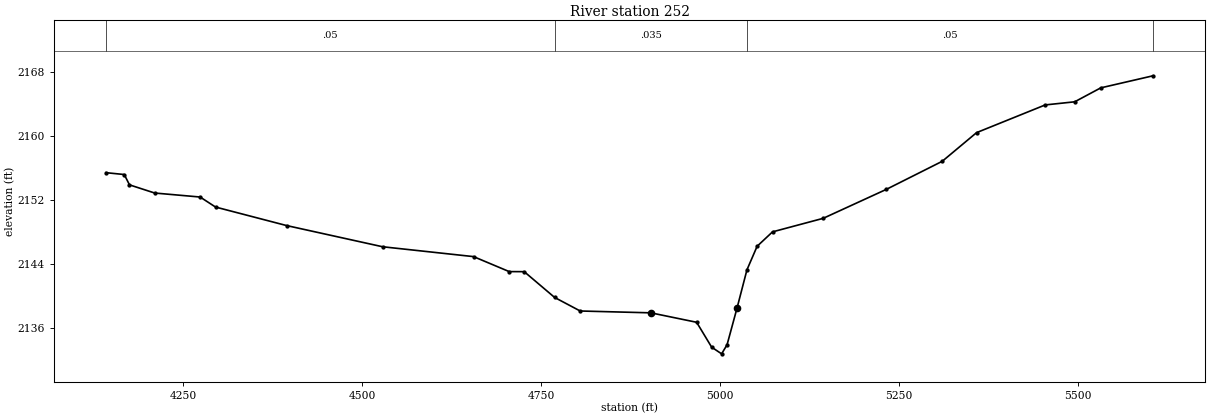
Type RM Length L Ch R = 1 ,252     ,0,0,0
BEGIN DESCRIPTION:
UNT 0004 IN HEWA 1.0
END DESCRIPTION:
XS GIS Cut Line= 3
      2617830.13       10073678.      2617136.65     10072935.69
      2616701.91     10072831.87
#Sta/Elev= 30
  4142.3 2155.39  4167.7 2155.16    4175 2153.87  4210.2 2152.85  4273.7 2152.35
  4295.2  2151.1  4394.4 2148.79  4528.7 2146.14  4655.7 2144.91  4705.5 2143.04
  4726.5 2143.03    4769 2139.81  4804.7 2138.12  4903.4 2137.89  4967.4 2136.71
  4988.4  2133.6  5002.3 2132.77  5009.9  2133.9    5024 2138.54  5037.7 2143.26
  5051.9  2146.2  5073.4    2148  5144.2 2149.69  5232.3  2153.3  5310.5 2156.81
  5358.5 2160.39  5454.4 2163.85  5495.6 2164.24    5532 2165.98  5605.1 2167.49
#Mann= 4 ,-1 , 0
  4142.3     .05       0    4769    .035       0  5037.7     .05       0
  5605.1     .16       0
Bank Sta=4903.4,5024
XS Rating Curve= 0 ,0
Exp/Cntr=0.3,0.1

Chan Stop Cuts=-1
Use User Specified Reach Order=0
Composite Channel Slope=5