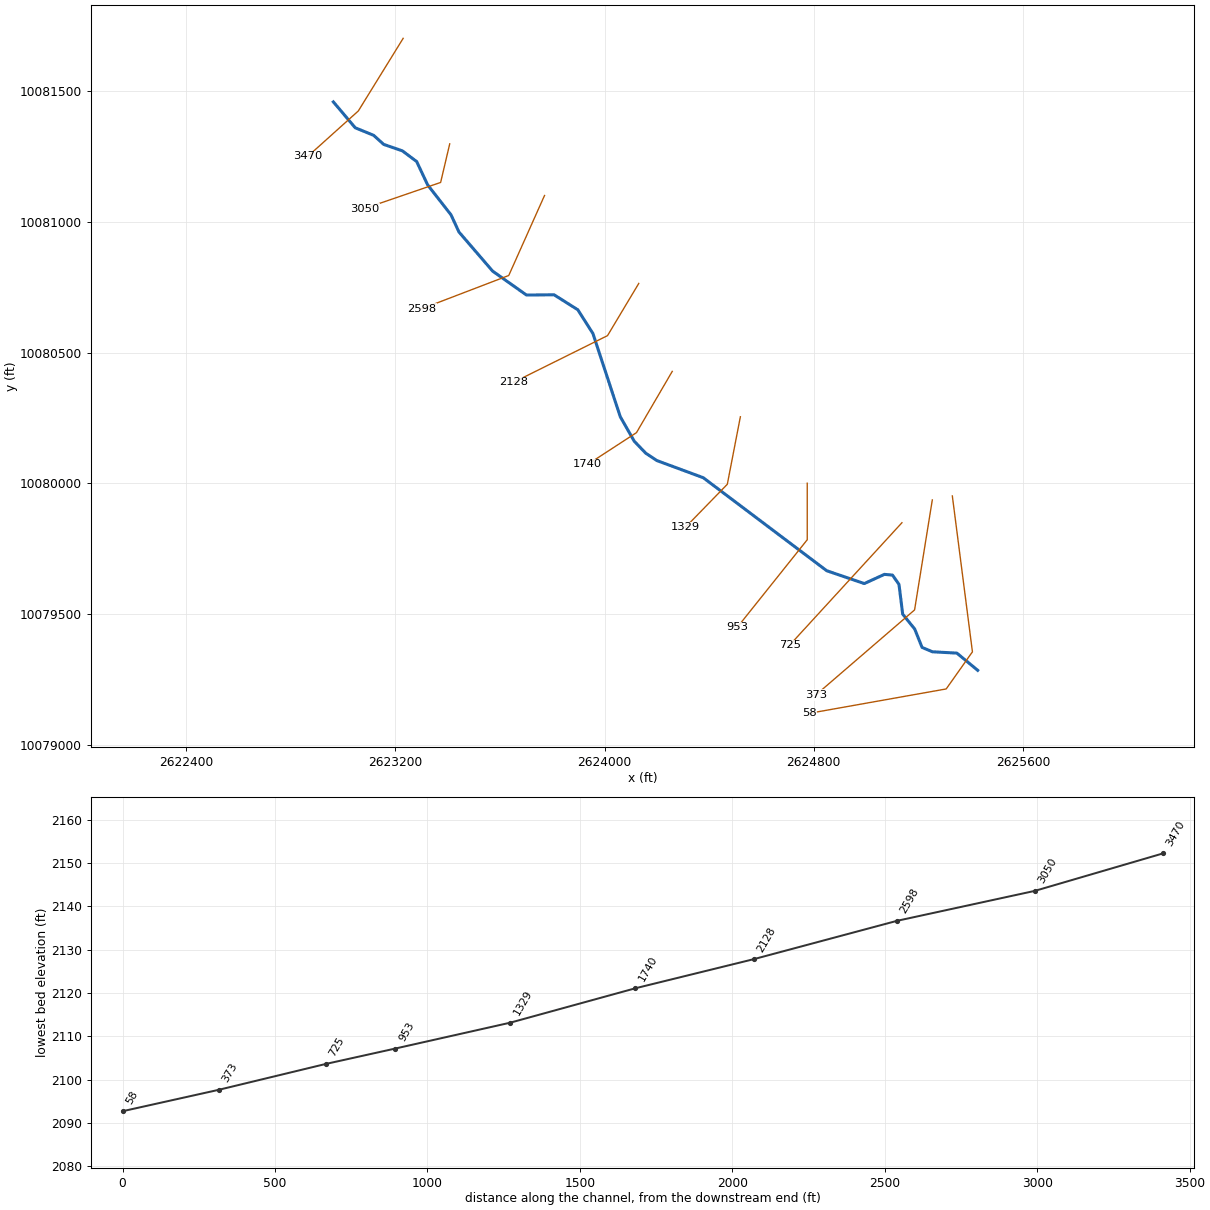
--- UNT 0005 IN HEWA.prj (project) ---

Proj Title=UNT 0005 IN HEWA Base Level Engineering
Current Plan=p01
Default Exp/Contr=0.3,0.1
English Units
Geom File=g01
Flow File=f01
Plan File=p01
Y Axis Title=Elevation
X Axis Title(PF)=Main Channel Distance
X Axis Title(XS)=Station
BEGIN DESCRIPTION:
UNT 0005 IN HEWA
END DESCRIPTION:
DSS Export Rating Curves= 0
DSS Export Rating Curve Sorted= 0
DSS Export Volume Flow Curves= 0
DXF OffsetX= 0
DXF OffsetY= 0
DXF ScaleX= 1
DXF ScaleY= 10

--- UNT 0005 IN HEWA.p01 (plan) ---

Plan Title=Multiple Run
Short Identifier=Multiple
Geom File=g01
Flow File=f01
Subcritical Flow
K Sum by GR= 0
Std Step Tol= 0.01
Critical Tol= 0.01
Num of Std Step Trials= 20
Max Error Tol= 0.3
Flow Tol Ratio= 0.001
Split Flow NTrial= 30
Split Flow Tol= 0.02
Split Flow Ratio= 0.02
Log Output Level= 0
Friction Slope Method= 1
Unsteady Friction Slope Method= 2
Unsteady Bridges Friction Slope Method= 1
Parabolic Critical Depth
Global Vel Dist=  1 , 1 , 1
Global Log Level= 0
CheckData=True
Encroach Param= -1, 0, 0, 0
BEGIN DESCRIPTION:
Multiple Run
END DESCRIPTION:

--- UNT 0005 IN HEWA.f01 (steady flow) ---

Flow Title=Multiple
Program Version=4.10
Number of Profiles= 7
Profile Names=10-year,25-year,50-year,1pct_min,100-year,1pct_plu,500-year
River Rch & RM=UNT 0005 IN HEWA,Reach-1         ,3470
     397     541     657     585     791    1070    1143
River Rch & RM=UNT 0005 IN HEWA,Reach-1         ,58
    1782    2649    3411    3193    4319    5841    6930
Boundary for River Rch & Prof#=UNT 0005 IN HEWA,Reach-1         , 1
Up Type= 0
Dn Type= 3
Dn Slope=0.017
Boundary for River Rch & Prof#=UNT 0005 IN HEWA,Reach-1         , 2
Up Type= 0
Dn Type= 3
Dn Slope=0.017
Boundary for River Rch & Prof#=UNT 0005 IN HEWA,Reach-1         , 3
Up Type= 0
Dn Type= 3
Dn Slope=0.017
Boundary for River Rch & Prof#=UNT 0005 IN HEWA,Reach-1         , 4
Up Type= 0
Dn Type= 3
Dn Slope=0.017
Boundary for River Rch & Prof#=UNT 0005 IN HEWA,Reach-1         , 5
Up Type= 0
Dn Type= 3
Dn Slope=0.017
Boundary for River Rch & Prof#=UNT 0005 IN HEWA,Reach-1         , 6
Up Type= 0
Dn Type= 3
Dn Slope=0.017
Boundary for River Rch & Prof#=UNT 0005 IN HEWA,Reach-1         , 7
Up Type= 0
Dn Type= 3
Dn Slope=0.017
DSS Import GetInterval= 0
DSS Import GetPeak= 0
DSS Import FillOption= 0

--- UNT 0005 IN HEWA.g01 (geometry) ---

Geom Title=Existing Conditions
Program Version=4.10

River Reach=UNT 0005 IN HEWA,Reach-1
Reach XY= 30
      2622963.47     10081458.73      2623047.06     10081359.65
      2623117.33     10081330.92      2623155.86     10081296.16
       2623227.5     10081271.36       2623281.9     10081230.55
      2623323.85     10081141.25      2623413.26     10081026.57
      2623443.51     10080961.11      2623572.25     10080811.45
       2623701.7     10080719.88      2623807.17     10080720.86
      2623897.93     10080663.57      2623955.73      10080572.6
      2624060.27     10080254.48      2624113.58     10080160.79
      2624157.92     10080114.67      2624199.78     10080086.92
      2624377.42     10080021.19       2624849.2     10079665.51
      2624993.05     10079616.26      2625070.03     10079651.45
      2625101.02      10079648.6      2625125.72     10079613.06
      2625139.88     10079499.32      2625185.69     10079442.51
      2625213.84     10079372.14      2625253.67      10079355.3
      2625347.04     10079350.23      2625426.69     10079284.41

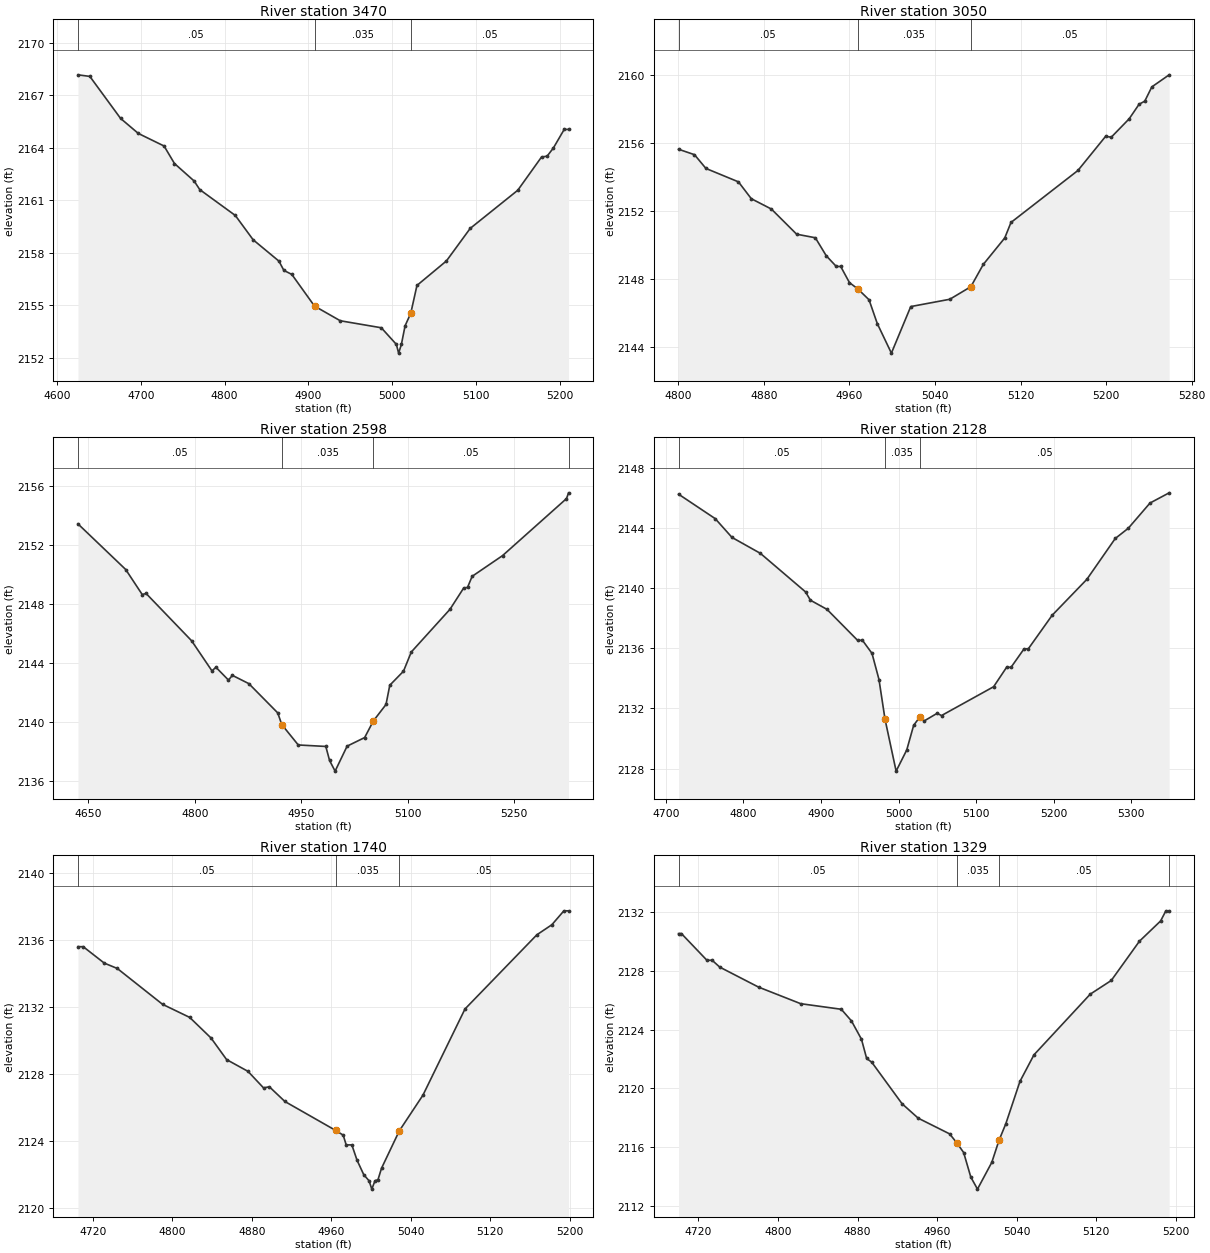
Type RM Length L Ch R = 1 ,3470    ,420,420,420
BEGIN DESCRIPTION:
UNT 0005 IN HEWA 8.0
END DESCRIPTION:
XS GIS Cut Line= 3
      2623230.31     10081701.82      2623058.87     10081424.04
      2622865.75     10081250.45
#Sta/Elev= 30
  4624.7 2168.17  4638.9 2168.08  4675.6 2165.68  4696.8 2164.82  4727.6  2164.1
    4740  2163.1  4763.5  2162.1  4770.2 2161.61  4812.7 2160.13    4834 2158.74
  4864.8 2157.52  4870.7 2156.99  4880.2 2156.76  4907.3 2154.95  4938.1 2154.11
  4987.1 2153.71  5005.1 2152.76  5007.8 2152.26  5011.1 2152.76  5015.5 2153.82
  5022.3 2154.54  5029.7 2156.13  5064.9 2157.53  5093.3 2159.39  5150.1 2161.57
  5178.5 2163.47  5185.2 2163.52  5192.7 2163.99  5205.6 2165.05  5210.8 2165.05
#Mann= 3 , 0 , 0
  4624.7     .05       0  4907.3    .035       0  5022.3     .05       0
Bank Sta=4907.3,5022.3
XS Rating Curve= 0 ,0
Exp/Cntr=0.3,0.1

Type RM Length L Ch R = 1 ,3050    ,452,452,452
BEGIN DESCRIPTION:
UNT 0005 IN HEWA 7.0
END DESCRIPTION:
XS GIS Cut Line= 3
      2623408.27      10081298.2      2623373.54      10081150.6
      2623083.11      10081050.9
#Sta/Elev= 30
  4800.2 2155.61  4815.1 2155.29  4825.8 2154.48  4856.2 2153.69  4868.2  2152.7
    4887 2152.09  4910.6 2150.61  4928.1  2150.4  4938.3 2149.34  4947.7 2148.71
  4951.8 2148.71    4960 2147.76  4967.8 2147.39  4978.3 2146.75    4986 2145.35
  4999.2 2143.61  5017.3 2146.35  5053.8 2146.78  5073.5 2147.52  5085.1 2148.83
  5105.2 2150.39    5111  2151.3  5173.6 2154.36  5199.5 2156.37  5204.8 2156.32
  5221.5  2157.4  5230.8 2158.26  5236.1 2158.44  5242.7 2159.28  5258.9 2159.99
#Mann= 3 , 0 , 0
  4800.2     .05       0  4967.8    .035       0  5073.5     .05       0
Bank Sta=4967.8,5073.5
XS Rating Curve= 0 ,0
Exp/Cntr=0.3,0.1

Type RM Length L Ch R = 1 ,2598    ,470,470,470
BEGIN DESCRIPTION:
UNT 0005 IN HEWA 6.0
END DESCRIPTION:
XS GIS Cut Line= 3
      2623770.67     10081100.68      2623633.96      10080794.7
      2623301.65     10080667.39
#Sta/Elev= 30
  4635.5 2153.42  4702.8 2150.33    4726 2148.64  4731.5 2148.71  4795.6 2145.51
  4824.3 2143.47  4829.8 2143.72  4847.5 2142.85    4853 2143.17  4876.2 2142.61
  4916.9 2140.63  4922.6 2139.84  4945.8 2138.46  4984.6 2138.36  4989.9 2137.41
  4997.7 2136.69  5014.6 2138.38  5039.3 2138.96  5051.5 2140.08  5069.4  2141.2
  5074.7  2142.5    5094 2143.45    5105 2144.75  5159.5 2147.64  5178.8 2149.08
  5184.2 2149.12  5190.7 2149.87  5233.5 2151.27  5323.6 2155.13  5326.5 2155.52
#Mann= 4 ,-1 , 0
  4635.5     .05       0  4922.6    .035       0  5051.5     .05       0
  5326.5      .1       0
Bank Sta=4922.6,5051.5
XS Rating Curve= 0 ,0
Exp/Cntr=0.3,0.1

Type RM Length L Ch R = 1 ,2128    ,388,388,388
BEGIN DESCRIPTION:
UNT 0005 IN HEWA 5.0
END DESCRIPTION:
XS GIS Cut Line= 3
      2624130.92     10080764.32      2624011.56     10080564.67
      2623653.46      10080386.7
#Sta/Elev= 30
  4716.3 2146.27  4763.6 2144.64  4785.2 2143.39  4821.8 2142.33  4880.1 2139.76
  4886.3 2139.21  4907.7  2138.6  4947.1 2136.54  4953.4 2136.54  4965.7 2135.67
  4974.7 2133.93  4982.5 2131.28  4996.8 2127.83  5010.5 2129.24  5019.4 2130.88
  5027.3 2131.43  5032.9 2131.17  5049.7 2131.68  5055.3 2131.53  5122.5 2133.45
  5139.3 2134.75  5144.9 2134.74  5161.7 2135.97  5167.3 2135.98    5198 2138.21
  5242.7  2140.6  5279.3 2143.32  5296.1    2144  5324.1 2145.68  5348.8 2146.36
#Mann= 3 , 0 , 0
  4716.3     .05       0  4982.5    .035       0  5027.3     .05       0
Bank Sta=4982.5,5027.3
XS Rating Curve= 0 ,0
Exp/Cntr=0.3,0.1

Type RM Length L Ch R = 1 ,1740    ,411,411,411
BEGIN DESCRIPTION:
UNT 0005 IN HEWA 4.0
END DESCRIPTION:
XS GIS Cut Line= 3
      2624258.95     10080427.93      2624122.24     10080193.57
      2623935.63     10080072.06
#Sta/Elev= 30
  4704.9 2135.58  4710.2 2135.58  4731.4  2134.6  4744.5 2134.28  4790.1 2132.14
  4817.4 2131.36  4838.9 2130.13  4854.6 2128.84  4876.1 2128.14  4891.8 2127.15
  4897.6 2127.22  4913.3 2126.34  4964.5 2124.61    4972 2124.33    4975 2123.75
  4980.7 2123.75  4985.9 2122.84  4992.7 2121.97    4998 2121.61  5000.8 2121.11
    5004 2121.61    5007 2121.67  5010.6 2122.36  5028.5 2124.59  5052.3 2126.72
  5094.6 2131.86    5167 2136.29  5182.1 2136.89  5194.2 2137.72  5198.9 2137.72
#Mann= 3 , 0 , 0
  4704.9     .05       0  4964.5    .035       0  5028.5     .05       0
Bank Sta=4964.5,5028.5
XS Rating Curve= 0 ,0
Exp/Cntr=0.3,0.1

Type RM Length L Ch R = 1 ,1329    ,376,376,376
BEGIN DESCRIPTION:
UNT 0005 IN HEWA 3.0
END DESCRIPTION:
XS GIS Cut Line= 3
      2624519.38     10080254.33      2624469.46     10079996.09
      2624308.89     10079831.17
#Sta/Elev= 30
  4700.1 2130.54    4703 2130.54  4728.7 2128.72  4733.8 2128.73  4741.5 2128.26
  4780.5  2126.9  4822.9 2125.77  4863.7 2125.39  4873.9  2124.6    4884 2123.35
  4889.2 2122.04  4894.3 2121.79  4924.8 2118.96    4941 2117.98  4972.6 2116.91
  4979.7 2116.31  4986.7 2115.64  4993.9 2113.97  5000.6 2113.15    5015 2114.97
  5022.2 2116.46  5029.1  2117.6  5043.3 2120.48  5057.4 2122.29    5114 2126.42
  5135.1 2127.35  5163.4 2130.02  5184.7  2131.4    5190 2132.09  5193.3 2132.09
#Mann= 4 ,-1 , 0
  4700.1     .05       0  4979.7    .035       0  5022.2     .05       0
  5193.3     .16       0
Bank Sta=4979.7,5022.2
XS Rating Curve= 0 ,0
Exp/Cntr=0.3,0.1

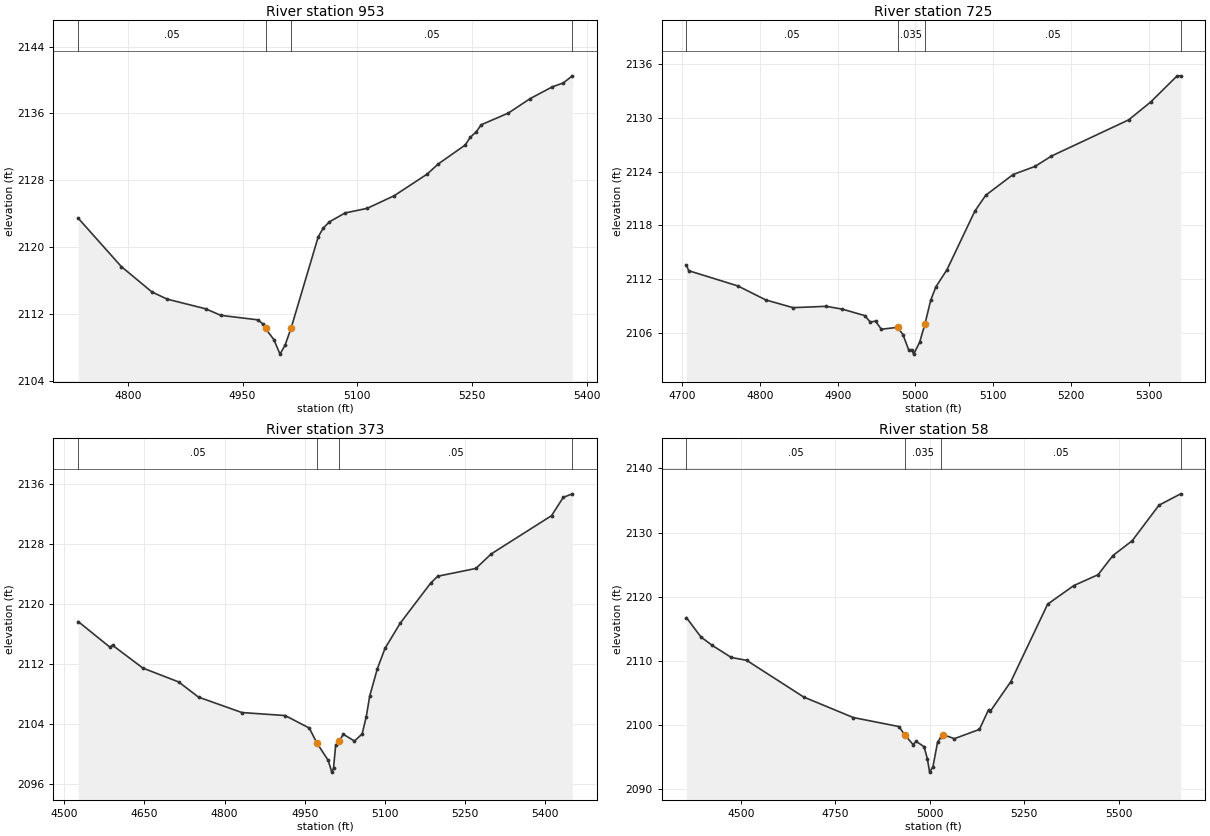
Type RM Length L Ch R = 1 ,953     ,228,228,228
BEGIN DESCRIPTION:
UNT 0005 IN HEWA 2.0
END DESCRIPTION:
XS GIS Cut Line= 3
      2624775.02     10080000.08      2624775.02     10079783.92
      2624507.07     10079448.33
#Sta/Elev= 30
  4735.2 2123.47  4791.6 2117.67  4831.6 2114.63  4851.6 2113.77  4901.6 2112.62
  4921.6 2111.83  4970.3 2111.29  4977.2 2110.74    4980 2110.26  4991.1  2108.9
  4998.9 2107.19  5005.6 2108.28  5013.6 2110.37  5048.8 2121.22  5055.2 2122.25
  5063.2 2123.01    5084 2124.09  5112.8 2124.64  5148.1 2126.15  5191.3 2128.75
  5205.7 2129.96  5240.9 2132.22  5247.3 2133.13  5255.3  2133.8  5261.7 2134.64
  5297.1 2136.04  5325.8 2137.78  5354.6 2139.18    5369 2139.65  5380.8  2140.5
#Mann= 4 ,-1 , 0
  4735.2     .05       0    4980    .035       0  5013.6     .05       0
  5380.8     .16       0
Bank Sta=4980,5013.6
XS Rating Curve= 0 ,0
Exp/Cntr=0.3,0.1

Type RM Length L Ch R = 1 ,725     ,352,352,352
BEGIN DESCRIPTION:
Mapping XS 7b0c8034
END DESCRIPTION:
XS GIS Cut Line= 2
      2625136.99     10079849.02       2624707.3     10079380.26
#Sta/Elev= 30
  4705.5 2113.56  4708.3 2112.95  4771.8 2111.24  4807.6 2109.68  4842.7 2108.82
  4885.3 2108.97  4906.2 2108.65  4934.6 2107.94    4942 2107.22  4948.8 2107.31
  4956.2 2106.41  4977.1 2106.62    4984 2105.82  4991.3 2104.13  4995.1 2104.13
  4997.9 2103.63  5005.5 2104.96  5012.3 2106.98  5019.7 2109.64  5026.5 2111.16
  5040.7 2113.06  5076.4 2119.58  5090.6 2121.38  5125.8 2123.69  5154.1  2124.6
  5175.1 2125.75  5274.4 2129.79  5302.7 2131.78  5336.8 2134.71  5341.4 2134.71
#Mann= 4 ,-1 , 0
  4705.5     .05       0  4977.1    .035       0  5012.3     .05       0
  5341.4     .16       0
Bank Sta=4977.1,5012.3
XS Rating Curve= 0 ,0
Exp/Cntr=0.3,0.1

Type RM Length L Ch R = 1 ,373     ,315,315,315
BEGIN DESCRIPTION:
Mapping XS 5d36a873
END DESCRIPTION:
XS GIS Cut Line= 3
      2625253.07     10079936.11      2625185.36     10079515.53
      2624807.79     10079190.03
#Sta/Elev= 30
  4526.1 2117.66  4585.4 2114.26  4590.4 2114.51  4647.2 2111.47  4714.1 2109.63
  4751.3 2107.61  4832.4 2105.56  4913.4 2105.16  4958.5  2103.5  4972.8  2101.5
  4993.7 2099.23  5000.6 2097.64  5003.8 2098.14  5007.9 2101.26  5014.5 2101.79
  5022.2 2102.67    5043 2101.77  5057.3 2102.71    5065 2104.98  5071.6 2107.77
  5085.8 2111.39  5100.1 2114.08  5128.6 2117.44  5185.6 2122.77  5198.9 2123.68
  5270.1 2124.71  5298.7 2126.64  5411.7 2131.73  5433.6 2134.16  5450.6 2134.63
#Mann= 4 ,-1 , 0
  4526.1     .05       0  4972.8    .035       0  5014.5     .05       0
  5450.6      .1       0
Bank Sta=4972.8,5014.5
XS Rating Curve= 0 ,0
Exp/Cntr=0.3,0.1

Type RM Length L Ch R = 1 ,58      ,0,0,0
BEGIN DESCRIPTION:
UNT 0005 IN HEWA 1.0
END DESCRIPTION:
XS GIS Cut Line= 4
      2625329.65     10079951.49      2625406.47     10079355.12
      2625306.21     10079213.19      2624781.83     10079119.74
#Sta/Elev= 30
  4356.5 2116.75  4394.6 2113.75  4424.8 2112.43  4475.2 2110.55  4515.6 2110.11
  4666.8 2104.39  4797.9  2101.2  4918.9 2099.79  4934.1 2098.49    4956    2097
  4964.3 2097.48  4985.2 2096.66  4993.9 2094.77  4999.8  2092.7  5008.5  2093.5
  5020.9 2097.36  5029.6 2098.13  5035.7 2098.54  5065.3 2097.91  5131.6 2099.35
  5155.8 2102.42  5160.9 2102.22  5214.8  2106.8  5312.1 2118.85  5381.5 2121.75
  5445.6 2123.44  5484.8 2126.42  5535.6 2128.71  5606.7 2134.26  5664.2 2136.03
#Mann= 4 ,-1 , 0
  4356.5     .05       0  4934.1    .035       0  5029.6     .05       0
  5664.2      .1       0
Bank Sta=4934.1,5035.7
XS Rating Curve= 0 ,0
Exp/Cntr=0.3,0.1

Chan Stop Cuts=-1
Use User Specified Reach Order=0
Composite Channel Slope=5