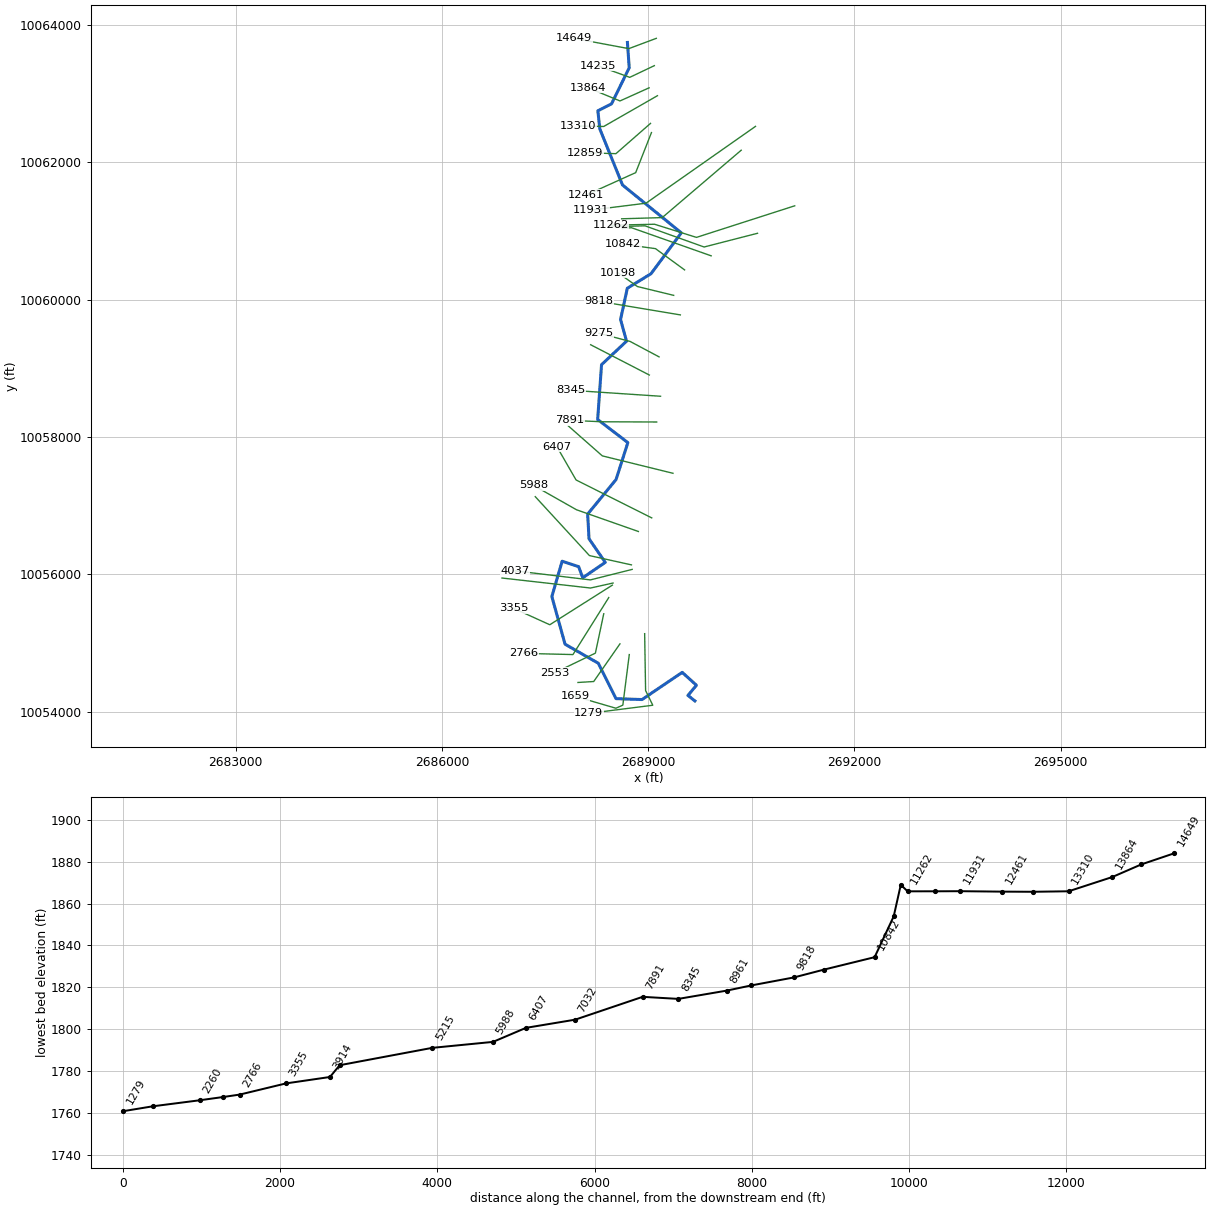
--- UNT 0007 IN HEWA.prj (project) ---

Proj Title=UNT 0007 IN HEWA Base Level Engineering
Current Plan=p01
Default Exp/Contr=0.3,0.1
English Units
Geom File=g01
Flow File=f01
Plan File=p01
BEGIN DESCRIPTION:
UNT 0007 IN HEWA
END DESCRIPTION:

--- UNT 0007 IN HEWA.p01 (plan) ---

Plan Title=Multiple Run
Short Identifier=Multiple
Geom File=g01
Flow File=f01
Subcritical Flow
K Sum by GR= 0
Std Step Tol= 0.01
Critical Tol= 0.01
Num of Std Step Trials= 20
Max Error Tol= 0.3
Flow Tol Ratio= 0.001
Split Flow NTrial= 30
Split Flow Tol= 0.02
Split Flow Ratio= 0.02
Log Output Level= 0
Friction Slope Method= 1
Unsteady Friction Slope Method= 2
Unsteady Bridges Friction Slope Method= 1
Parabolic Critical Depth
Global Vel Dist=  1 , 1 , 1
Global Log Level= 0
CheckData=True
Encroach Param= -1, 0, 0, 0
BEGIN DESCRIPTION:
Multiple Run
END DESCRIPTION:

--- UNT 0007 IN HEWA.f01 (steady flow) ---

Flow Title=Multiple
Number of Profiles=7
Profile Names=10-year,25-year,50-year,1pct_min,100-year,1pct_plu,500-year
River Rch & RM= UNT 0007 IN HEWA,Reach-1,14649
    2132    3218    4188    3967    5365    7255    8806
River Rch & RM= UNT 0007 IN HEWA,Reach-1,11085
    2654    4030    5266    5002    6764    9148   11168
Boundary for River Rch & Prof#=UNT 0007 IN HEWA,Reach-1,1
Up Type=0
Dn Type=3
Dn Slope=0.005
Boundary for River Rch & Prof#=UNT 0007 IN HEWA,Reach-1,2
Up Type=0
Dn Type=3
Dn Slope=0.005
Boundary for River Rch & Prof#=UNT 0007 IN HEWA,Reach-1,3
Up Type=0
Dn Type=3
Dn Slope=0.005
Boundary for River Rch & Prof#=UNT 0007 IN HEWA,Reach-1,4
Up Type=0
Dn Type=3
Dn Slope=0.005
Boundary for River Rch & Prof#=UNT 0007 IN HEWA,Reach-1,5
Up Type=0
Dn Type=3
Dn Slope=0.005
Boundary for River Rch & Prof#=UNT 0007 IN HEWA,Reach-1,6
Up Type=0
Dn Type=3
Dn Slope=0.005
Boundary for River Rch & Prof#=UNT 0007 IN HEWA,Reach-1,7
Up Type=0
Dn Type=3
Dn Slope=0.005

--- UNT 0007 IN HEWA.g01 (geometry) ---

Geom Title=Existing Conditions

River Reach=UNT 0007 IN HEWA,Reach-1
Reach XY= 30
      2688698.47     10063743.73      2688724.67     10063375.31
      2688467.62     10062850.32      2688268.23     10062748.81
      2688297.18     10062484.31      2688626.78     10061669.15
      2689482.25     10060972.28      2689041.77     10060377.30
      2688696.71     10060165.54      2688598.58     10059710.87
      2688685.46     10059395.02      2688321.77     10059052.96
      2688265.44     10058255.09      2688704.68     10057918.59
      2688532.94     10057380.81      2688120.09     10056877.96
      2688139.77     10056519.10      2688375.81     10056174.91
      2688048.35     10055950.70      2687988.95     10056112.94
      2687748.76     10056191.77      2687599.03     10055678.26
      2687790.84     10054984.34      2688274.74     10054706.86
      2688532.37     10054191.67      2688911.31     10054178.23
      2689495.33     10054574.03      2689702.34     10054386.65
      2689578.43     10054237.97      2689679.65     10054158.47

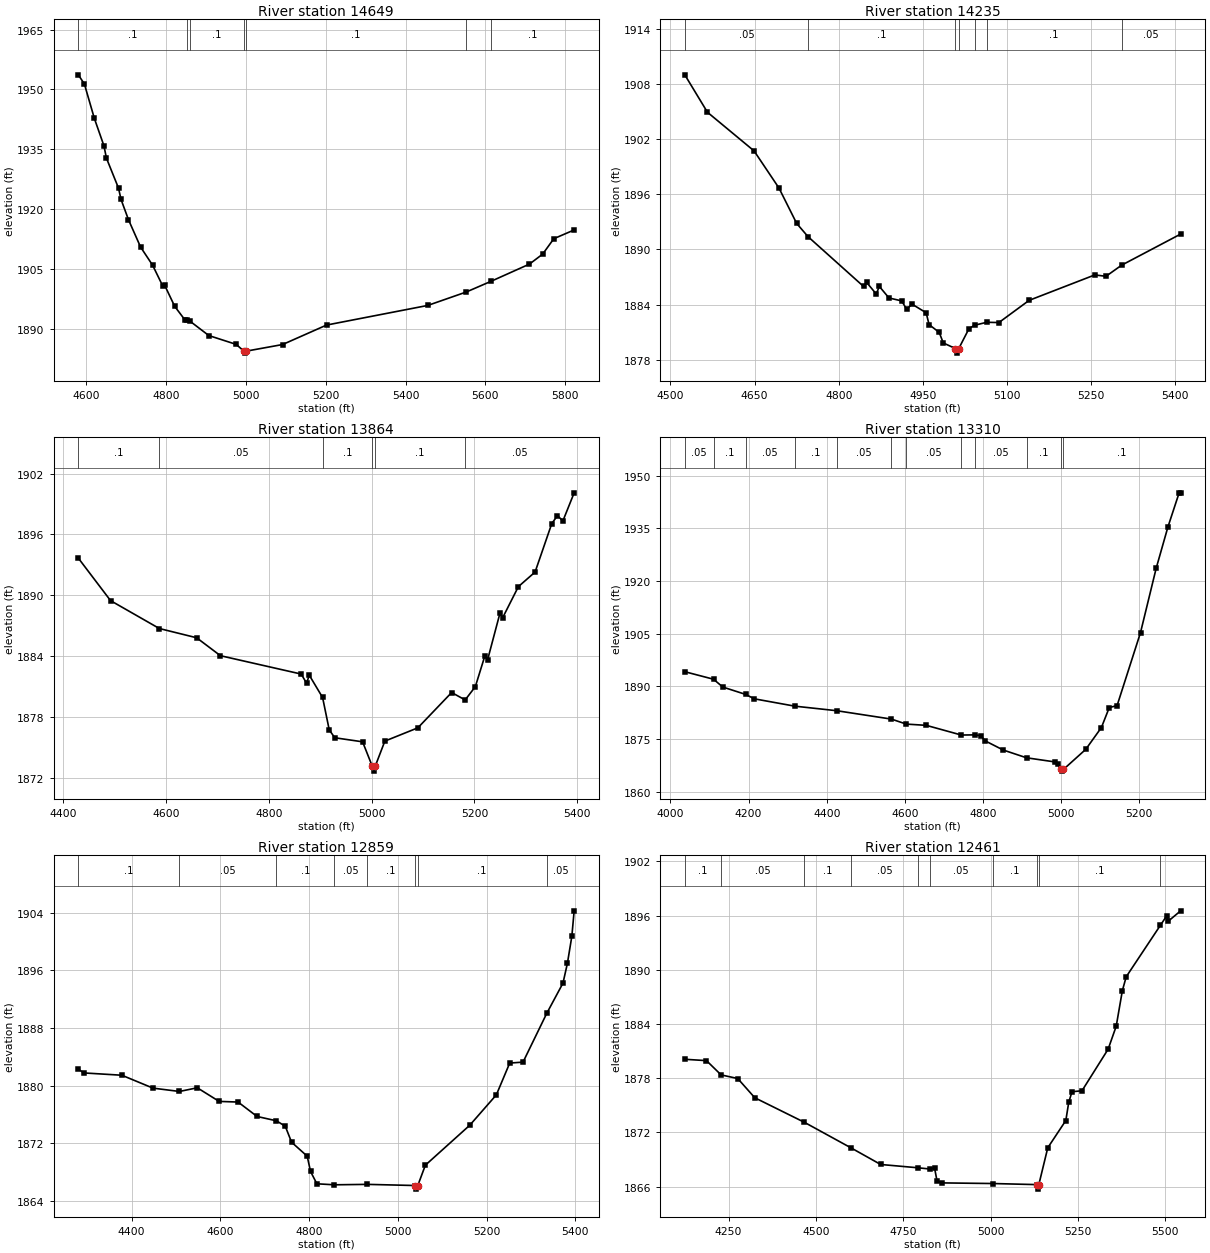
Type RM Length L Ch R = 1,14649,414,414,414
BEGIN DESCRIPTION:
UNT 0007 IN HEWA 27.0
END DESCRIPTION:
XS GIS Cut Line= 3
      2689118.50     10063803.74      2688718.47     10063653.73
      2687918.44     10063803.74
#Sta/Elev= 30
  4581.0 1953.66  4596.2 1951.35  4621.1 1942.75  4645.1 1935.88  4651.3 1932.81
  4681.6 1925.28  4687.8 1922.48  4706.5 1917.38  4736.8 1910.53  4767.0 1905.97
  4792.0 1900.84  4797.3 1900.92  4822.2 1895.68  4847.1 1892.38  4853.2 1892.37
  4860.9 1891.93  4907.7 1888.36  4976.2 1886.15  4995.4 1884.46  4998.2 1883.96
  5001.4 1884.46  5092.2 1886.11  5202.4 1890.99  5455.9 1895.91  5551.9 1899.26
  5613.7 1901.93  5710.3 1906.26  5743.3 1908.75  5771.3 1912.62  5822.2 1914.81
#Mann=7,-1,0
  4581.0     0.1       0  4853.2    0.05       0  4860.9     0.1       0
  4995.4    0.07       0  5001.4     0.1       0  5551.9    0.05       0
  5613.7     0.1       0
Bank Sta=4995.4,5001.4
Exp/Cntr=0.3,0.1

Type RM Length L Ch R = 1,14235,371,371,371
BEGIN DESCRIPTION:
UNT 0007 IN HEWA 26.0
END DESCRIPTION:
XS GIS Cut Line= 3
      2689089.98     10063406.05      2688732.39     10063235.93
      2688274.05     10063402.59
#Sta/Elev= 30
  4525.7 1909.03  4566.1 1904.95  4649.2 1900.74  4693.5 1896.70  4725.1 1892.84
  4745.3 1891.40  4844.2 1885.98  4849.7 1886.42  4866.9 1885.15  4872.4 1885.98
  4889.6 1884.72  4912.3 1884.40  4921.1 1883.48  4930.6 1884.05  4955.8 1883.11
  4961.1 1881.82  4979.1 1880.97  4986.4 1879.82  5008.0 1879.21  5010.7 1878.71
  5014.0 1879.21  5032.3 1881.39  5042.2 1881.75  5063.9 1882.07  5085.5 1882.04
  5139.4 1884.46  5256.4 1887.23  5276.4 1887.08  5304.2 1888.29  5409.4 1891.68
#Mann=7,-1,0
  4525.7    0.05       0  4745.3     0.1       0  5008.0    0.07       0
  5014.0     0.1       0  5042.2    0.05       0  5063.9     0.1       0
  5304.2    0.05       0
Bank Sta=5008,5014
Exp/Cntr=0.3,0.1

Type RM Length L Ch R = 1,13864,554,554,554
BEGIN DESCRIPTION:
Mapping XS 3682d32d
END DESCRIPTION:
XS GIS Cut Line= 3
      2689013.63     10063083.15      2688590.03     10062892.18
      2688128.22     10063083.15
#Sta/Elev= 30
  4429.5 1893.66  4492.2 1889.47  4587.1 1886.72  4659.6 1885.81  4705.9 1884.04
  4863.0 1882.23  4873.3 1881.34  4878.8 1882.11  4904.6 1879.92  4917.5 1876.73
  4928.3 1875.95  4982.4 1875.55  5001.1 1873.16  5003.8 1872.66  5007.1 1873.16
  5025.7 1875.62  5089.9 1876.93  5155.6 1880.41  5181.9 1879.68  5201.7 1880.99
  5220.2 1884.02  5225.6 1883.65  5249.5 1888.22  5254.9 1887.79  5285.4 1890.85
  5317.9 1892.29  5350.3 1897.06  5361.4 1897.85  5372.0 1897.33  5393.9 1900.10
#Mann=6,-1,0
  4429.5     0.1       0  4587.1    0.05       0  4904.6     0.1       0
  5001.1    0.07       0  5007.1     0.1       0  5181.9    0.05       0
Bank Sta=5001.1,5007.1
Exp/Cntr=0.3,0.1

Type RM Length L Ch R = 1,13310,451,451,451
BEGIN DESCRIPTION:
UNT 0007 IN HEWA 25.0
END DESCRIPTION:
XS GIS Cut Line= 3
      2689135.19     10062968.58      2688353.91     10062520.65
      2687985.85     10062527.59
#Sta/Elev= 30
  4036.9 1894.20  4110.4 1892.06  4134.1 1889.83  4192.5 1887.74  4214.7 1886.48
  4318.2 1884.39  4425.6 1883.09  4565.7 1880.70  4603.6 1879.28  4654.8 1878.92
  4744.5 1876.16  4778.2 1876.21  4793.9 1875.99  4805.9 1874.48  4851.5 1871.90
  4911.3 1869.68  4982.9 1868.52  4992.9 1867.99  4999.9 1866.38  5002.7 1865.88
  5005.9 1866.38  5062.9 1872.09  5102.9 1878.30  5123.0 1883.99  5143.0 1884.54
  5203.0 1905.37  5243.0 1923.65  5273.0 1935.40  5301.8 1945.16  5305.6 1945.16
#Mann=12,-1,0
  4036.9    0.05       0  4110.4     0.1       0  4192.5    0.05       0
  4318.2     0.1       0  4425.6    0.05       0  4565.7     0.1       0
  4603.6    0.05       0  4744.5     0.1       0  4778.2    0.05       0
  4911.3     0.1       0  4999.9    0.07       0  5005.9     0.1       0
Bank Sta=4999.9,5005.9
Exp/Cntr=0.3,0.1

Type RM Length L Ch R = 1,12859,398,398,398
BEGIN DESCRIPTION:
UNT 0007 IN HEWA 24.0
END DESCRIPTION:
XS GIS Cut Line= 3
      2689034.46     10062565.78      2688531.00     10062124.82
      2688083.29     10062138.70
#Sta/Elev= 30
  4280.0 1882.27  4292.7 1881.76  4378.1 1881.44  4448.3 1879.65  4507.9 1879.19
  4548.0 1879.70  4597.3 1877.81  4640.0 1877.72  4682.7 1875.72  4726.4 1875.12
  4746.3 1874.36  4760.5 1872.15  4795.7 1870.21  4803.2 1868.09  4817.5 1866.38
  4857.1 1866.24  4931.0 1866.30  5038.9 1866.14  5041.6 1865.64  5044.9 1866.14
  5061.9 1868.96  5161.9 1874.50  5221.9 1878.72  5252.0 1883.13  5282.0 1883.26
  5335.3 1890.01  5372.0 1894.22  5382.0 1896.97  5392.0 1900.73  5397.2 1904.25
#Mann=8,-1,0
  4280.0     0.1       0  4507.9    0.05       0  4726.4     0.1       0
  4857.1    0.05       0  4931.0     0.1       0  5038.9    0.07       0
  5044.9     0.1       0  5335.3    0.05       0
Bank Sta=5038.9,5044.9
Exp/Cntr=0.3,0.1

Type RM Length L Ch R = 1,12461,530,530,530
BEGIN DESCRIPTION:
UNT 0007 IN HEWA 23.0
END DESCRIPTION:
XS GIS Cut Line= 3
      2689047.94     10062432.01      2688818.75     10061848.64
      2688096.55     10061522.26
#Sta/Elev= 30
  4124.9 1880.09  4187.0 1879.94  4228.8 1878.36  4276.4 1877.96  4325.2 1875.83
  4467.2 1873.11  4601.6 1870.26  4685.6 1868.44  4793.2 1868.07  4825.8 1867.94
  4839.8 1868.05  4846.9 1866.62  4861.7 1866.40  5006.5 1866.33  5132.3 1866.21
  5135.0 1865.71  5138.3 1866.21  5163.9 1870.29  5215.6 1873.31  5223.9 1875.32
  5233.2 1876.50  5261.8 1876.60  5336.7 1881.21  5359.8 1883.75  5377.4 1887.69
  5388.5 1889.23  5486.5 1894.94  5503.9 1895.95  5509.4 1895.40  5544.2 1896.53
#Mann=10,-1,0
  4124.9     0.1       0  4228.8    0.05       0  4467.2     0.1       0
  4601.6    0.05       0  4793.2     0.1       0  4825.8    0.05       0
  5006.5     0.1       0  5132.3   0.033       0  5138.3     0.1       0
  5486.5    0.05       0
Bank Sta=5132.3,5138.3
Exp/Cntr=0.3,0.1

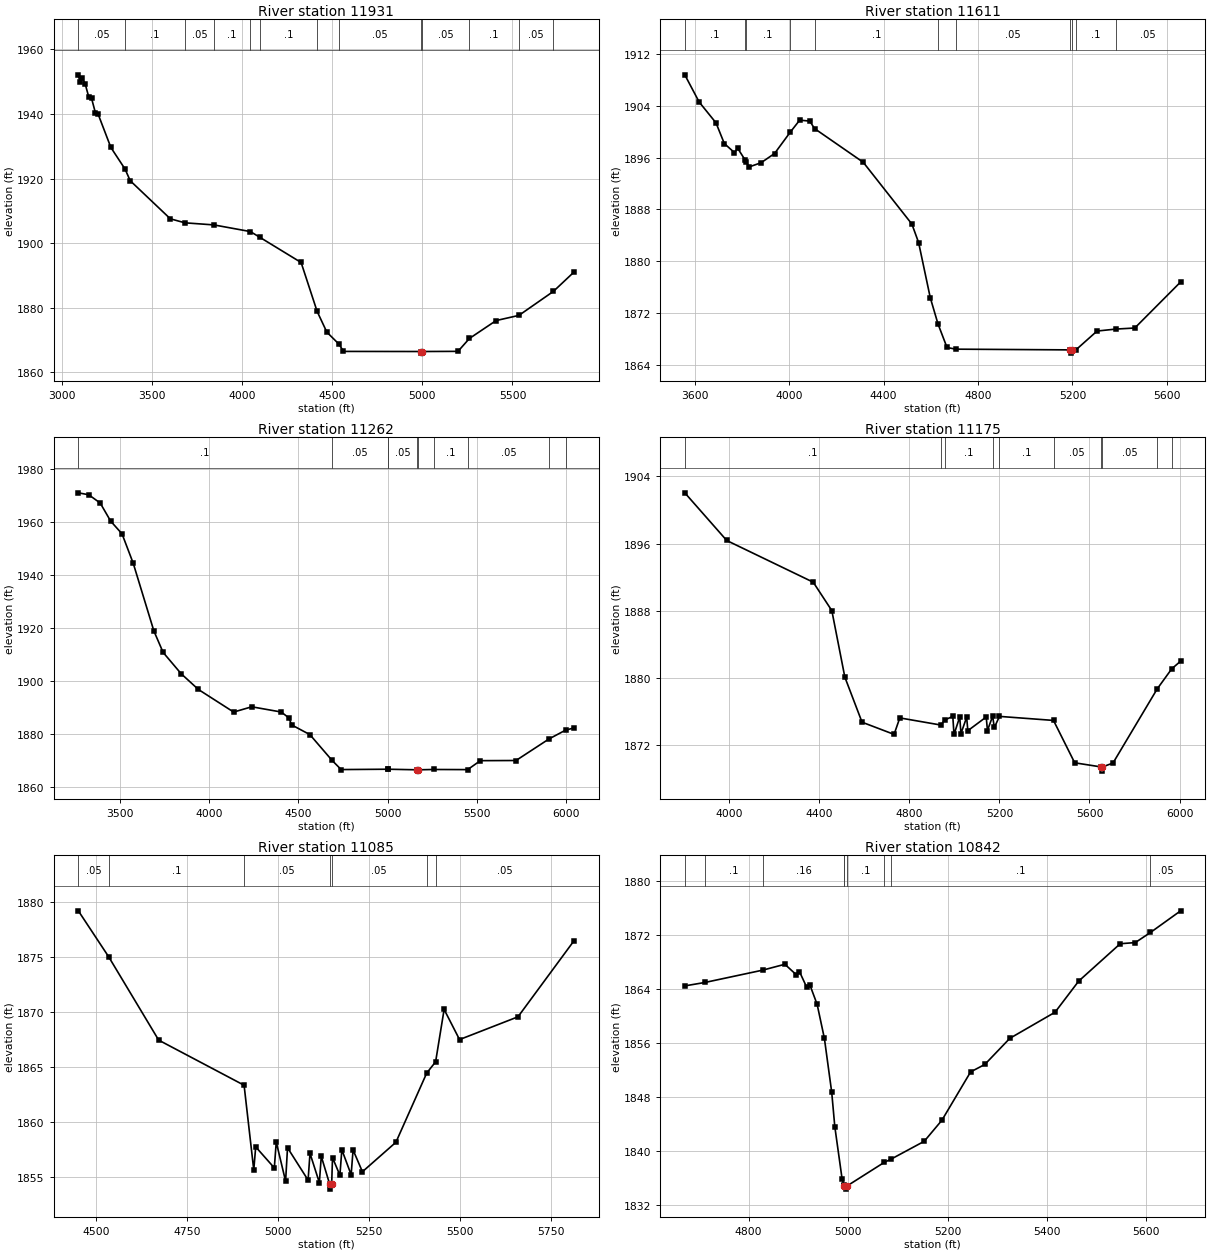
Type RM Length L Ch R = 1,11931,320,320,320
BEGIN DESCRIPTION:
UNT 0007 IN HEWA 22.0
END DESCRIPTION:
XS GIS Cut Line= 3
      2690561.77     10062522.22      2688968.47     10061403.73
      2688168.49     10061303.74
#Sta/Elev= 30
  3089.6 1952.14  3097.7 1949.99  3112.5 1951.08  3127.3 1949.37  3148.3 1945.12
  3163.1 1944.84  3184.0 1940.46  3198.8 1940.06  3270.3 1929.63  3349.2 1922.92
  3377.5 1919.34  3600.5 1907.53  3681.5 1906.29  3842.6 1905.64  4044.7 1903.58
  4096.0 1901.85  4326.5 1894.00  4415.4 1878.85  4469.4 1872.42  4536.8 1868.70
  4561.8 1866.45  4990.2 1866.42  4992.9 1865.92  4996.2 1866.42  5197.5 1866.47
  5260.9 1870.46  5409.2 1876.01  5535.7 1877.61  5727.3 1885.05  5842.5 1891.09
#Mann=13,-1,0
  3089.6    0.05       0  3349.2     0.1       0  3681.5    0.05       0
  3842.6     0.1       0  4044.7    0.05       0  4096.0     0.1       0
  4415.4    0.16       0  4536.8    0.05       0  4990.2   0.033       0
  4996.2    0.05       0  5260.9     0.1       0  5535.7    0.05       0
  5727.3     0.1       0
Bank Sta=4990.2,4996.2
Exp/Cntr=0.3,0.1

Type RM Length L Ch R = 1,11611,349,349,349
BEGIN DESCRIPTION:
UNT 0007 IN HEWA 21.0
END DESCRIPTION:
XS GIS Cut Line= 3
      2690353.51     10062175.05      2689204.61     10061194.26
      2688614.37     10061176.90
#Sta/Elev= 30
  3557.4 1908.74  3618.3 1904.55  3689.6 1901.34  3724.8 1898.16  3767.6 1896.76
  3781.9 1897.40  3812.0 1895.68  3815.8 1895.32  3831.3 1894.57  3880.7 1895.20
  3937.8 1896.62  4003.7 1899.88  4044.3 1901.76  4087.1 1901.61  4107.2 1900.46
  4313.5 1895.27  4519.7 1885.75  4548.2 1882.90  4597.6 1874.41  4630.3 1870.37
  4668.5 1866.74  4705.4 1866.48  5191.2 1866.37  5194.0 1865.87  5197.2 1866.37
  5215.6 1866.40  5304.3 1869.27  5382.7 1869.57  5464.3 1869.74  5658.5 1876.83
#Mann=11,-1,0
  3557.4     0.1       0  3812.0    0.05       0  3815.8     0.1       0
  4003.7    0.05       0  4107.2     0.1       0  4630.3    0.16       0
  4705.4    0.05       0  5191.2   0.033       0  5197.2    0.05       0
  5215.6     0.1       0  5382.7    0.05       0
Bank Sta=5191.2,5197.2
Exp/Cntr=0.3,0.1

Type RM Length L Ch R = 1,11262,87,87,87
BEGIN DESCRIPTION:
Mapping XS ca9f929c
END DESCRIPTION:
XS GIS Cut Line= 4
      2691131.77     10061365.75      2689702.93     10060906.16
      2689093.17     10061097.28      2688452.46     10061083.64
#Sta/Elev= 30
  3265.9 1970.93  3324.3 1970.20  3388.5 1967.08  3447.4 1960.23  3511.0 1955.44
  3574.0 1944.29  3689.6 1918.77  3741.4 1910.68  3842.9 1902.61  3939.2 1896.69
  4137.0 1888.16  4238.5 1890.15  4404.2 1888.17  4445.9 1885.99  4463.1 1883.28
  4564.6 1879.64  4689.1 1869.90  4740.0 1866.45  5001.7 1866.58  5002.8 1866.58
  5166.7 1866.36  5169.5 1865.86  5172.7 1866.36  5258.3 1866.48  5449.4 1866.43
  5520.6 1869.81  5720.6 1869.87  5906.1 1878.03  5998.8 1881.34  6046.7 1882.19
#Mann=10,-1,0
  3265.9     0.1       0  4689.1    0.05       0  5001.7     0.1       0
  5002.8    0.05       0  5166.7   0.033       0  5172.7    0.05       0
  5258.3     0.1       0  5449.4    0.05       0  5906.1     0.1       0
  5998.8    0.05       0
Bank Sta=5166.7,5172.7
Exp/Cntr=0.3,0.1

Type RM Length L Ch R = 1,11175,90,90,90
BEGIN DESCRIPTION:
Mapping XS 94eb8abd
END DESCRIPTION:
XS GIS Cut Line= 4
      2690590.71     10060965.85      2689813.76     10060766.19
      2688954.38     10061074.35      2688468.31     10061061.33
#Sta/Elev= 30
  3803.2 1902.05  3989.4 1896.38  4373.4 1891.42  4456.0 1888.04  4513.8 1880.13
  4590.1 1874.77  4732.3 1873.32  4757.8 1875.28  4940.4 1874.43  4956.9 1875.03
  4993.1 1875.46  4998.4 1873.31  5023.9 1875.39  5029.2 1873.42  5054.6 1875.35
  5059.9 1873.76  5141.5 1875.39  5146.9 1873.78  5169.9 1875.48  5177.6 1874.14
  5200.2 1875.46  5440.2 1874.98  5534.3 1869.94  5651.3 1869.45  5654.1 1868.95
  5657.3 1869.45  5704.3 1869.91  5900.6 1878.73  5965.2 1881.12  6004.6 1882.03
#Mann=10,-1,0
  3803.2     0.1       0  4940.4    0.05       0  4956.9     0.1       0
  5169.9    0.05       0  5200.2     0.1       0  5440.2    0.05       0
  5651.3    0.07       0  5657.3    0.05       0  5900.6     0.1       0
  5965.2    0.05       0
Bank Sta=5651.3,5657.3
Exp/Cntr=0.3,0.1

Type RM Length L Ch R = 1,11085,243,243,243
BEGIN DESCRIPTION:
UNT 0007 IN HEWA 20.0
END DESCRIPTION:
XS GIS Cut Line= 3
      2689916.75     10060637.69      2688756.43     10061047.22
      2688624.51     10061033.57
#Sta/Elev= 30
  4451.0 1879.19  4534.3 1875.02  4671.9 1867.44  4906.7 1863.34  4933.3 1855.64
  4938.6 1857.74  4989.8 1855.83  4995.1 1858.18  5020.8 1854.62  5026.1 1857.66
  5082.6 1854.72  5087.9 1857.15  5113.6 1854.49  5118.9 1856.88  5141.5 1854.40
  5144.2 1853.90  5147.5 1854.40  5149.8 1856.76  5170.1 1855.16  5175.4 1857.48
  5201.0 1855.21  5206.3 1857.46  5232.0 1855.48  5324.1 1858.16  5408.8 1864.45
  5433.2 1865.47  5456.6 1870.23  5499.0 1867.49  5659.7 1869.56  5814.1 1876.49
#Mann=7,-1,0
  4451.0    0.05       0  4534.3     0.1       0  4906.7    0.05       0
  5141.5   0.035       0  5147.5    0.05       0  5408.8     0.1       0
  5433.2    0.05       0
Bank Sta=5141.5,5147.5
Exp/Cntr=0.3,0.1

Type RM Length L Ch R = 1,10842,644,644,644
BEGIN DESCRIPTION:
UNT 0007 IN HEWA 19.0
END DESCRIPTION:
XS GIS Cut Line= 3
      2689530.04     10060432.88      2689106.82     10060742.34
      2688638.12     10060806.05
#Sta/Elev= 30
  4671.6 1864.49  4712.3 1865.00  4828.2 1866.82  4872.9 1867.69  4896.1 1866.12
  4902.2 1866.61  4916.9 1864.27  4923.1 1864.65  4937.8 1861.75  4952.4 1856.71
  4967.1 1848.75  4973.3 1843.67  4988.0 1835.91  4992.1 1835.02  4992.6 1834.91
  4995.4 1834.41  4998.6 1834.91  5073.0 1838.38  5085.5 1838.81  5153.2 1841.49
  5188.7 1844.60  5246.5 1851.76  5275.0 1852.86  5325.4 1856.73  5416.3 1860.59
  5463.9 1865.20  5547.4 1870.73  5577.7 1870.90  5608.3 1872.40  5668.9 1875.60
#Mann=9,-1,0
  4671.6    0.05       0  4712.3     0.1       0  4828.2    0.16       0
  4992.1     0.1       0  4992.6    0.07       0  4998.6     0.1       0
  5073.0    0.05       0  5085.5     0.1       0  5608.3    0.05       0
Bank Sta=4992.6,4998.6
Exp/Cntr=0.3,0.1

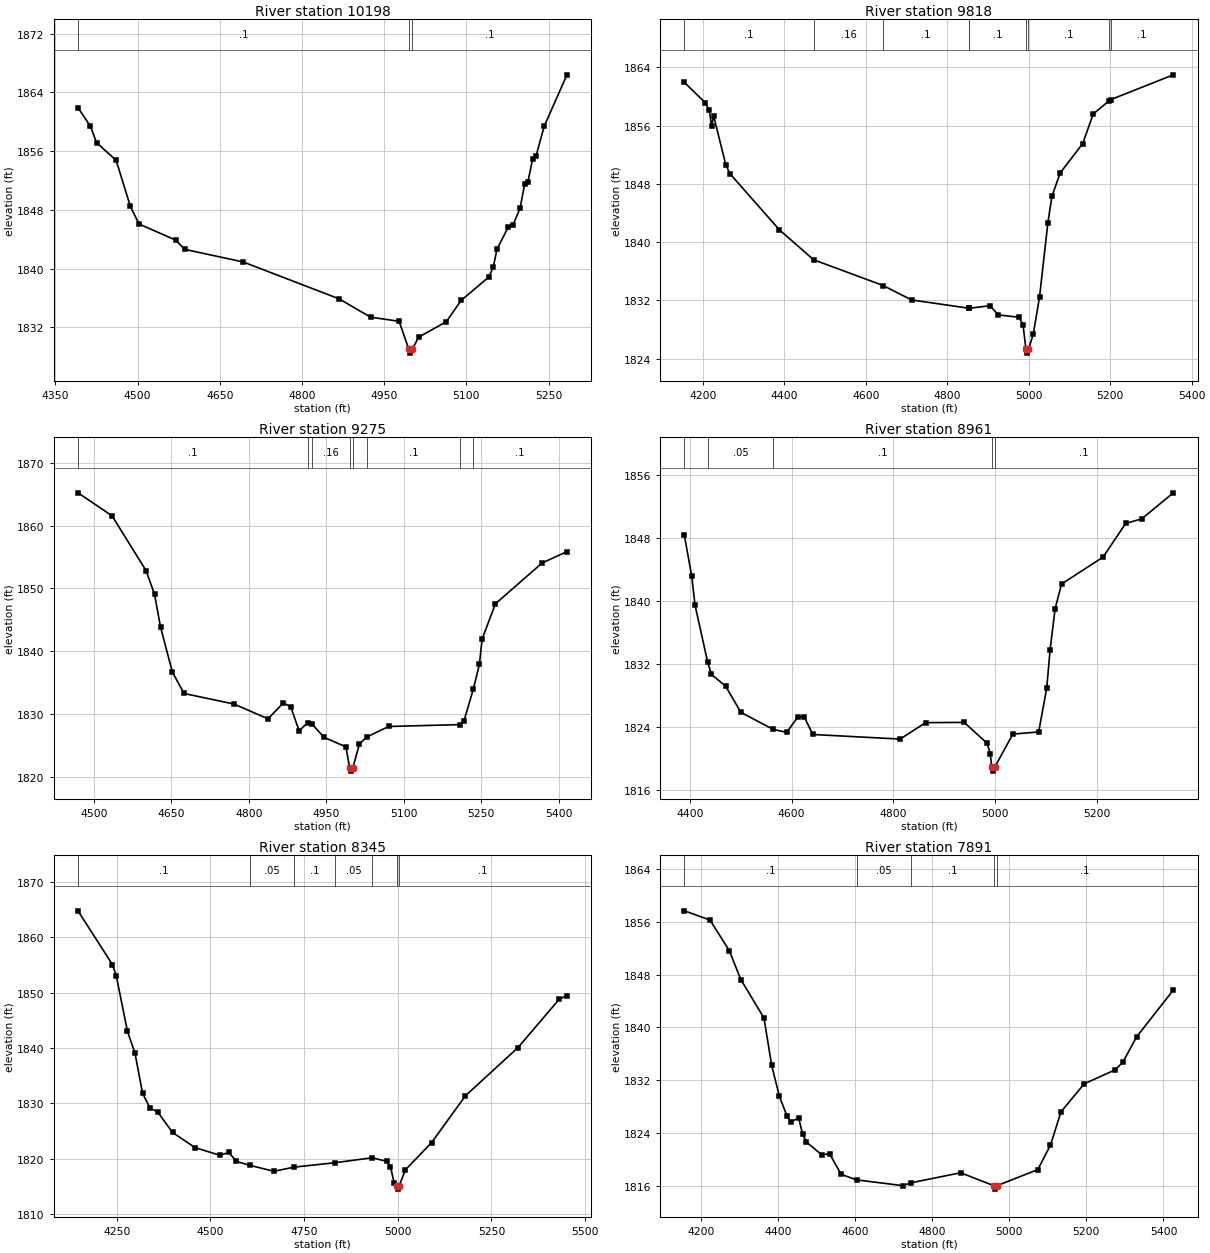
Type RM Length L Ch R = 1,10198,380,380,380
BEGIN DESCRIPTION:
UNT 0007 IN HEWA 18.0
END DESCRIPTION:
XS GIS Cut Line= 3
      2689371.30     10060062.31      2688843.50     10060190.79
      2688558.74     10060392.20
#Sta/Elev= 30
  4391.4 1861.93  4414.2 1859.38  4425.2 1857.16  4461.0 1854.75  4486.9 1848.49
  4502.7 1846.08  4569.3 1843.89  4586.2 1842.62  4692.8 1840.90  4867.7 1835.88
  4925.1 1833.38  4977.2 1832.82  4995.1 1828.98  4997.9 1828.48  5001.1 1828.98
  5012.9 1830.66  5063.3 1832.76  5090.4 1835.66  5140.9 1838.85  5149.0 1840.19
  5155.7 1842.63  5176.6 1845.69  5185.2 1845.99  5198.0 1848.23  5206.1 1851.47
  5212.2 1851.84  5220.9 1854.94  5227.0 1855.33  5241.8 1859.37  5283.4 1866.40
#Mann=3,-1,0
  4391.4     0.1       0  4995.1    0.07       0  5001.1     0.1       0
Bank Sta=4995.1,5001.1
Exp/Cntr=0.3,0.1

Type RM Length L Ch R = 1,9818,543,543,543
BEGIN DESCRIPTION:
UNT 0007 IN HEWA 17.0
END DESCRIPTION:
XS GIS Cut Line= 2
      2689468.46     10059777.60      2688284.49     10059975.51
#Sta/Elev= 30
  4154.7 1861.93  4205.4 1859.16  4215.5 1858.14  4221.4 1855.98  4226.5 1857.32
  4256.1 1850.65  4266.2 1849.41  4387.9 1841.69  4471.8 1837.58  4642.7 1834.04
  4712.4 1832.06  4854.0 1830.92  4854.5 1830.92  4905.0 1831.27  4925.2 1830.01
  4975.9 1829.69  4986.1 1828.65  4993.2 1825.26  4996.0 1824.76  4999.2 1825.26
  5011.1 1827.35  5026.6 1832.48  5046.9 1842.61  5057.0 1846.30  5077.3 1849.50
  5132.6 1853.54  5158.4 1857.60  5197.5 1859.41  5202.0 1859.58  5355.1 1862.97
#Mann=9,-1,0
  4154.7     0.1       0  4471.8    0.16       0  4642.7     0.1       0
  4854.0    0.05       0  4854.5     0.1       0  4993.2    0.07       0
  4999.2     0.1       0  5197.5    0.16       0  5202.0     0.1       0
Bank Sta=4993.2,4999.2
Exp/Cntr=0.3,0.1

Type RM Length L Ch R = 1,9275,314,314,314
BEGIN DESCRIPTION:
UNT 0007 IN HEWA 16.0
END DESCRIPTION:
XS GIS Cut Line= 3
      2689159.49     10059166.47      2688735.86     10059392.18
      2688284.45     10059510.24
#Sta/Elev= 30
  4469.2 1865.20  4535.2 1861.54  4601.1 1852.81  4617.4 1849.05  4629.0 1843.86
  4651.7 1836.76  4674.3 1833.29  4771.2 1831.61  4837.1 1829.26  4866.9 1831.80
  4881.0 1831.17  4897.3 1827.36  4914.1 1828.67  4922.5 1828.40  4945.5 1826.31
  4987.9 1824.80  4995.2 1821.44  4997.9 1820.94  5001.2 1821.44  5014.2 1825.29
  5028.3 1826.36  5070.5 1828.04  5209.4 1828.34  5216.3 1828.89  5234.7 1834.01
  5246.3 1837.92  5251.6 1841.94  5277.3 1847.55  5367.7 1854.04  5415.8 1855.85
#Mann=8,-1,0
  4469.2     0.1       0  4914.1    0.05       0  4922.5    0.16       0
  4995.2    0.07       0  5001.2    0.16       0  5028.3     0.1       0
  5209.4    0.16       0  5234.7     0.1       0
Bank Sta=4995.2,5001.2
Exp/Cntr=0.3,0.1

Type RM Length L Ch R = 1,8961,616,616,616
BEGIN DESCRIPTION:
UNT 0007 IN HEWA 15.0
END DESCRIPTION:
XS GIS Cut Line= 2
      2689017.07     10058902.61      2688163.24     10059343.41
#Sta/Elev= 30
  4389.4 1848.29  4403.7 1843.16  4410.3 1839.46  4434.8 1832.33  4442.4 1830.70
  4470.2 1829.22  4500.4 1825.89  4564.0 1823.73  4590.4 1823.36  4612.9 1825.35
  4625.3 1825.26  4641.8 1823.09  4813.4 1822.51  4863.3 1824.59  4939.3 1824.62
  4984.3 1821.97  4990.6 1820.63  4993.2 1818.95  4996.0 1818.45  4999.2 1818.95
  5034.9 1823.14  5085.6 1823.41  5101.4 1828.95  5108.1 1833.83  5117.9 1839.02
  5130.6 1842.15  5212.2 1845.55  5256.5 1849.81  5288.2 1850.40  5350.3 1853.69
#Mann=5,-1,0
  4389.4     0.1       0  4434.8    0.05       0  4564.0     0.1       0
  4993.2    0.07       0  4999.2     0.1       0
Bank Sta=4993.2,4999.2
Exp/Cntr=0.3,0.1

Type RM Length L Ch R = 1,8345,454,454,454
BEGIN DESCRIPTION:
UNT 0007 IN HEWA 14.0
END DESCRIPTION:
XS GIS Cut Line= 2
      2689180.31     10058593.57      2687878.20     10058680.37
#Sta/Elev= 30
  4146.4 1864.79  4238.4 1855.07  4248.5 1853.07  4278.5 1842.99  4298.6 1839.06
  4318.6 1831.84  4338.7 1829.15  4358.7 1828.48  4398.8 1824.74  4458.9 1822.00
  4524.4 1820.63  4549.1 1821.12  4569.2 1819.51  4604.7 1818.81  4669.4 1817.72
  4723.6 1818.48  4832.4 1819.27  4931.6 1820.17  4970.1 1819.52  4980.4 1818.56
  4990.1 1815.65  4997.1 1815.00  4999.9 1814.50  5003.1 1815.00  5020.2 1817.98
  5090.3 1822.92  5180.5 1831.37  5320.8 1840.08  5431.4 1848.86  5451.4 1849.46
#Mann=7,-1,0
  4146.4     0.1       0  4604.7    0.05       0  4723.6     0.1       0
  4832.4    0.05       0  4931.6     0.1       0  4997.1    0.07       0
  5003.1     0.1       0
Bank Sta=4997.1,5003.1
Exp/Cntr=0.3,0.1

Type RM Length L Ch R = 1,7891,859,859,859
BEGIN DESCRIPTION:
UNT 0007 IN HEWA 13.0
END DESCRIPTION:
XS GIS Cut Line= 3
      2689124.79     10058218.57      2688329.61     10058222.04
      2687857.35     10058242.87
#Sta/Elev= 30
  4157.7 1857.67  4224.0 1856.27  4274.0 1851.65  4304.0 1847.25  4364.0 1841.43
  4384.0 1834.23  4404.0 1829.55  4424.0 1826.52  4434.0 1825.69  4454.0 1826.27
  4464.0 1823.85  4474.0 1822.62  4514.0 1820.68  4534.0 1820.86  4564.0 1817.72
  4604.3 1816.88  4724.0 1816.01  4744.6 1816.43  4874.0 1817.96  4961.0 1815.98
  4963.8 1815.48  4967.0 1815.98  5074.1 1818.44  5107.0 1822.17  5134.2 1827.19
  5194.3 1831.44  5274.3 1833.55  5294.4 1834.71  5330.5 1838.58  5425.6 1845.67
#Mann=5,-1,0
  4157.7     0.1       0  4604.3    0.05       0  4744.6     0.1       0
  4961.0    0.07       0  4967.0     0.1       0
Bank Sta=4961,4967
Exp/Cntr=0.3,0.1

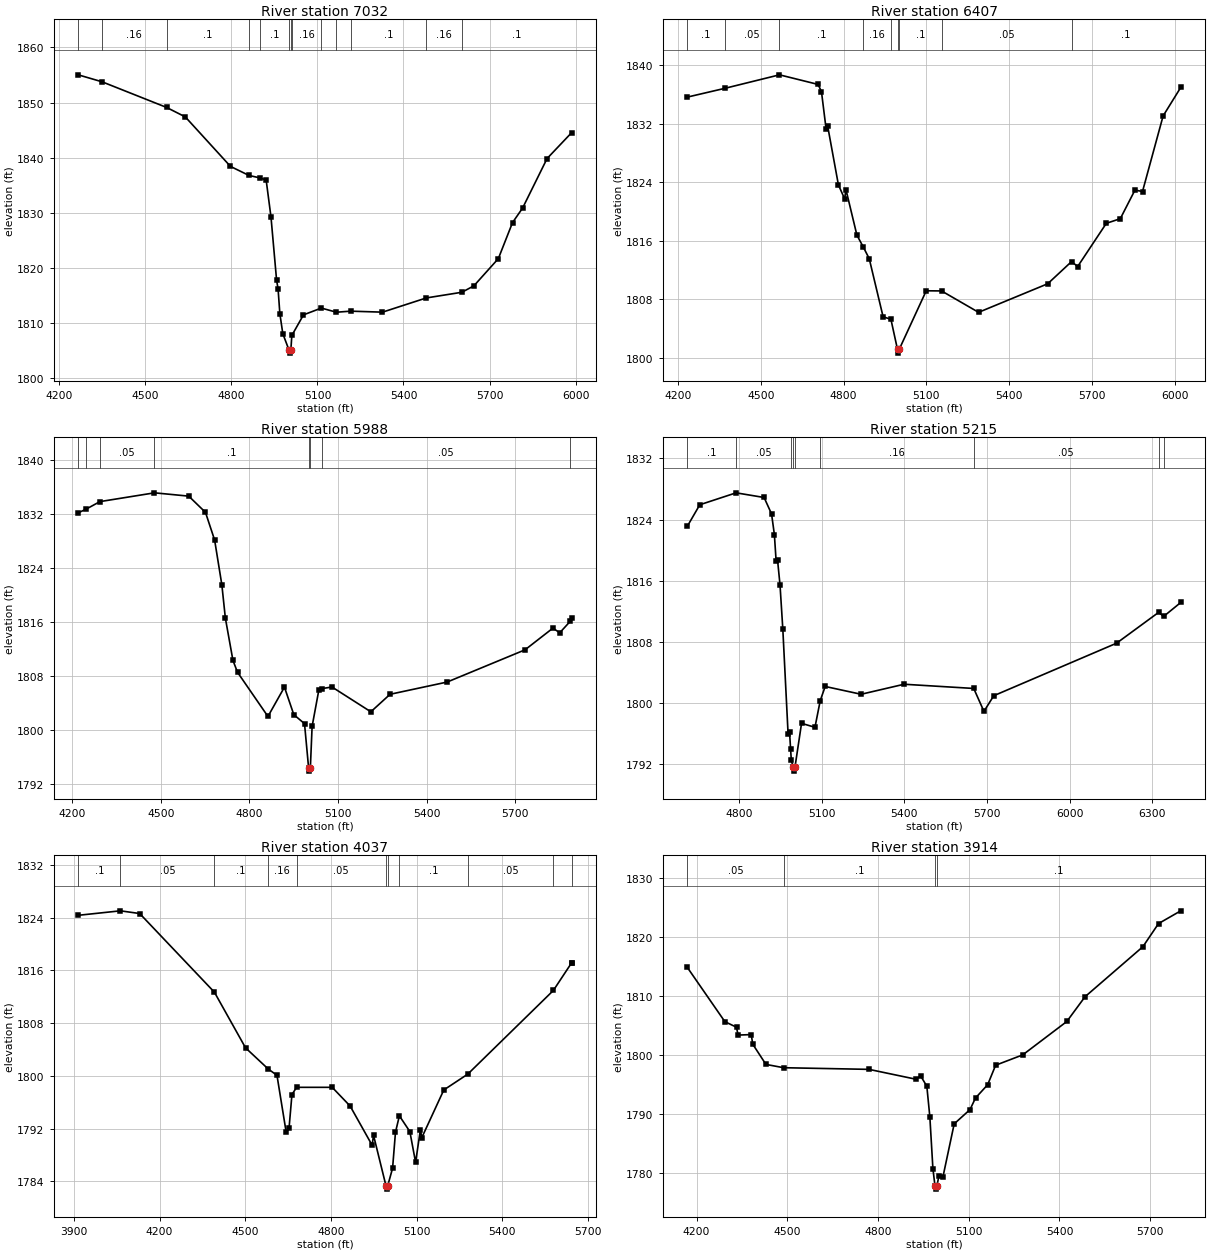
Type RM Length L Ch R = 1,7032,625,625,625
BEGIN DESCRIPTION:
UNT 0007 IN HEWA 12.0
END DESCRIPTION:
XS GIS Cut Line= 3
      2689361.00     10057472.13      2688333.25     10057725.59
      2687836.74     10058163.08
#Sta/Elev= 30
  4265.9 1855.04  4348.8 1853.78  4573.9 1849.13  4639.3 1847.41  4796.8 1838.43
  4861.5 1836.79  4901.0 1836.33  4921.2 1835.95  4938.0 1829.27  4957.6 1817.77
  4962.7 1816.25  4968.9 1811.75  4979.2 1808.11  5001.2 1805.07  5003.9 1804.57
  5007.2 1805.07  5010.7 1807.77  5051.3 1811.51  5113.5 1812.74  5166.2 1811.99
  5216.2 1812.18  5326.8 1812.00  5479.7 1814.58  5603.7 1815.61  5645.4 1816.77
  5730.7 1821.71  5780.1 1828.24  5815.3 1830.88  5900.6 1839.86  5986.2 1844.55
#Mann=13,-1,0
  4265.9     0.1       0  4348.8    0.16       0  4573.9     0.1       0
  4861.5    0.16       0  4901.0     0.1       0  5001.2    0.07       0
  5007.2     0.1       0  5010.7    0.16       0  5113.5     0.1       0
  5166.2    0.16       0  5216.2     0.1       0  5479.7    0.16       0
  5603.7     0.1       0
Bank Sta=5001.2,5007.2
Exp/Cntr=0.3,0.1

Type RM Length L Ch R = 1,6407,419,419,419
BEGIN DESCRIPTION:
UNT 0007 IN HEWA 11.0
END DESCRIPTION:
XS GIS Cut Line= 3
      2689051.98     10056822.83      2687951.31     10057374.90
      2687673.54     10057857.51
#Sta/Elev= 30
  4233.8 1835.62  4369.1 1836.81  4567.8 1838.66  4707.6 1837.35  4719.9 1836.37
  4736.6 1831.30  4742.2 1831.70  4781.3 1823.64  4803.6 1821.75  4809.2 1822.91
  4848.3 1816.78  4871.5 1815.15  4893.0 1813.57  4943.3 1805.63  4971.6 1805.29
  4995.5 1801.17  4998.2 1800.67  5001.5 1801.17  5099.6 1809.18  5155.1 1809.16
  5289.3 1806.24  5539.9 1810.14  5626.4 1813.17  5648.4 1812.49  5752.3 1818.39
  5802.9 1819.02  5856.1 1822.93  5883.4 1822.73  5958.1 1833.05  6022.0 1836.94
#Mann=9,-1,0
  4233.8     0.1       0  4369.1    0.05       0  4567.8     0.1       0
  4871.5    0.16       0  4971.6     0.1       0  4995.5    0.07       0
  5001.5     0.1       0  5155.1    0.05       0  5626.4     0.1       0
Bank Sta=4995.5,5001.5
Exp/Cntr=0.3,0.1

Type RM Length L Ch R = 1,5988,773,773,773
BEGIN DESCRIPTION:
UNT 0007 IN HEWA 10.0
END DESCRIPTION:
XS GIS Cut Line= 3
      2688857.56     10056624.90      2687958.25     10056940.87
      2687333.40     10057294.95
#Sta/Elev= 30
  4219.8 1832.19  4245.9 1832.72  4293.3 1833.85  4478.2 1835.15  4594.2 1834.66
  4650.9 1832.26  4681.9 1828.16  4706.4 1821.53  4718.2 1816.63  4743.9 1810.36
  4759.4 1808.60  4862.5 1802.06  4918.4 1806.40  4950.1 1802.33  4986.4 1800.99
  5000.2 1794.47  5002.9 1793.97  5006.2 1794.47  5012.1 1800.59  5035.0 1805.99
  5045.3 1806.18  5079.4 1806.42  5211.1 1802.75  5276.2 1805.34  5469.4 1807.15
  5733.4 1811.92  5827.9 1815.13  5850.9 1814.44  5886.3 1816.13  5891.2 1816.66
#Mann=8,-1,0
  4219.8    0.05       0  4245.9     0.1       0  4293.3    0.05       0
  4478.2     0.1       0  5000.2    0.07       0  5006.2     0.1       0
  5045.3    0.05       0  5886.3     0.1       0
Bank Sta=5000.2,5006.2
Exp/Cntr=0.3,0.1

Type RM Length L Ch R = 1,5215,1178,1178,1178
BEGIN DESCRIPTION:
UNT 0007 IN HEWA 9.0
END DESCRIPTION:
XS GIS Cut Line= 3
      2688756.89     10056138.78      2688145.75     10056274.20
      2687357.54     10057131.86
#Sta/Elev= 30
  4612.2 1823.14  4657.4 1825.95  4789.2 1827.51  4890.8 1826.90  4917.9 1824.75
  4928.1 1822.06  4934.4 1818.62  4939.5 1818.77  4948.6 1815.46  4958.8 1809.66
  4978.0 1795.91  4983.1 1796.25  4987.1 1793.95  4989.6 1792.51  4996.8 1791.62
  4999.6 1791.12  5002.8 1791.62  5026.7 1797.37  5075.4 1796.85  5094.5 1800.33
  5112.5 1802.19  5242.9 1801.17  5398.9 1802.48  5651.7 1801.93  5688.7 1798.93
  5724.4 1800.98  6170.2 1807.85  6322.4 1811.87  6341.3 1811.36  6403.0 1813.17
#Mann=9,-1,0
  4612.2     0.1       0  4789.2    0.05       0  4987.1     0.1       0
  4996.8    0.07       0  5002.8     0.1       0  5094.5    0.16       0
  5651.7    0.05       0  6322.4     0.1       0  6341.3    0.05       0
Bank Sta=4996.8,5002.8
Exp/Cntr=0.3,0.1

Type RM Length L Ch R = 1,4037,123,123,123
BEGIN DESCRIPTION:
Mapping XS ccd16074
END DESCRIPTION:
XS GIS Cut Line= 3
      2688767.28     10056072.81      2688159.64     10055920.03
      2687065.92     10056051.98
#Sta/Elev= 30
  3915.0 1824.36  4062.8 1825.04  4130.3 1824.63  4392.0 1812.70  4501.1 1804.26
  4580.0 1801.07  4611.2 1800.09  4643.5 1791.44  4653.5 1792.09  4663.6 1797.17
  4679.9 1798.27  4804.6 1798.27  4867.4 1795.43  4944.4 1789.49  4949.4 1790.99
  4993.0 1783.33  4995.7 1782.83  4999.0 1783.33  5016.1 1786.01  5026.2 1791.45
  5039.9 1793.95  5076.6 1791.56  5096.7 1786.89  5113.5 1791.84  5118.5 1790.64
  5195.5 1797.87  5279.4 1800.27  5579.2 1812.96  5643.1 1817.15  5643.2 1817.15
#Mann=11,-1,0
  3915.0     0.1       0  4062.8    0.05       0  4392.0     0.1       0
  4580.0    0.16       0  4679.9    0.05       0  4993.0    0.04       0
  4999.0    0.05       0  5039.9     0.1       0  5279.4    0.05       0
  5579.2     0.1       0  5643.1    0.05       0
Bank Sta=4993,4999
Exp/Cntr=0.3,0.1

Type RM Length L Ch R = 1,3914,559,559,559
BEGIN DESCRIPTION:
UNT 0007 IN HEWA 8.0
END DESCRIPTION:
XS GIS Cut Line= 3
      2688489.54     10055874.60      2688161.86     10055801.78
      2686874.04     10055947.40
#Sta/Elev= 30
  4169.3 1814.77  4293.5 1805.58  4331.9 1804.64  4337.0 1803.31  4380.6 1803.39
  4385.7 1801.76  4429.2 1798.34  4487.8 1797.78  4770.0 1797.50  4924.4 1795.84
  4941.1 1796.37  4961.3 1794.64  4971.3 1789.44  4981.4 1780.68  4988.4 1777.71
  4991.2 1777.21  4994.4 1777.71  5001.5 1779.50  5014.2 1779.19  5051.8 1788.27
  5104.0 1790.68  5122.3 1792.65  5162.5 1794.90  5188.8 1798.20  5278.6 1799.96
  5424.2 1805.61  5484.6 1809.81  5675.8 1818.28  5727.5 1822.20  5801.0 1824.36
#Mann=4,-1,0
  4169.3    0.05       0  4487.8     0.1       0  4988.4    0.07       0
  4994.4     0.1       0
Bank Sta=4988.4,4994.4
Exp/Cntr=0.3,0.1

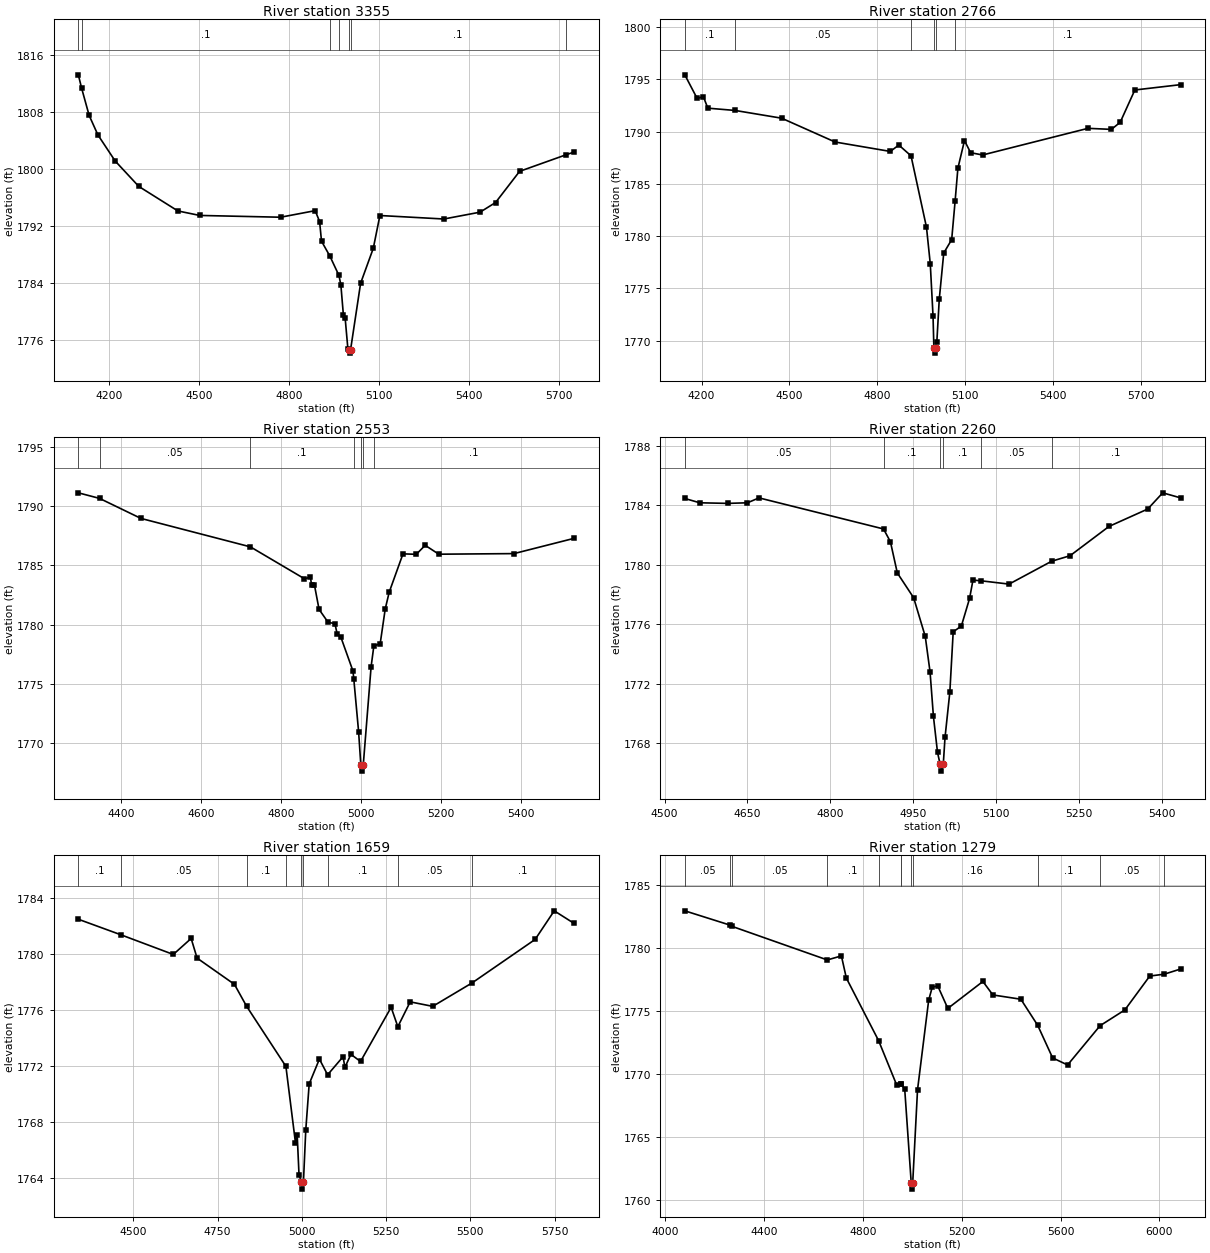
Type RM Length L Ch R = 1,3355,589,589,589
BEGIN DESCRIPTION:
UNT 0007 IN HEWA 7.0
END DESCRIPTION:
XS GIS Cut Line= 3
      2688478.90     10055843.56      2687569.19     10055267.18
      2687042.45     10055506.29
#Sta/Elev= 30
  4096.6 1813.16  4107.5 1811.30  4132.6 1807.48  4161.9 1804.74  4219.6 1801.08
  4298.4 1797.52  4428.9 1794.08  4501.8 1793.45  4771.9 1793.20  4887.4 1794.12
  4902.1 1792.59  4908.5 1789.84  4936.3 1787.76  4966.7 1785.04  4973.1 1783.72
  4981.4 1779.56  4987.3 1779.12  4996.7 1774.68  4999.6 1774.65  5002.3 1774.15
  5005.6 1774.65  5039.0 1783.94  5081.4 1788.85  5103.4 1793.44  5317.0 1792.95
  5437.9 1793.91  5489.6 1795.26  5569.8 1799.63  5724.0 1801.94  5752.0 1802.34
#Mann=7,-1,0
  4096.6    0.05       0  4107.5     0.1       0  4936.3    0.16       0
  4966.7     0.1       0  4999.6    0.07       0  5005.6     0.1       0
  5724.0    0.05       0
Bank Sta=4999.6,5005.6
Exp/Cntr=0.3,0.1

Type RM Length L Ch R = 1,2766,213,213,213
BEGIN DESCRIPTION:
UNT 0007 IN HEWA 6.0
END DESCRIPTION:
XS GIS Cut Line= 3
      2688426.82     10055662.98      2687906.00     10054833.15
      2687192.14     10054850.48
#Sta/Elev= 30
  4142.9 1795.44  4185.1 1793.18  4206.3 1793.35  4221.6 1792.25  4315.1 1792.03
  4473.7 1791.29  4656.4 1789.01  4844.9 1788.11  4874.0 1788.72  4915.7 1787.69
  4968.5 1780.86  4981.5 1777.35  4990.9 1772.36  4993.8 1769.31  4996.6 1768.81
  4999.8 1769.31  5003.9 1769.89  5012.2 1773.97  5027.5 1778.39  5054.6 1779.67
  5066.2 1783.32  5075.8 1786.50  5098.3 1789.15  5119.3 1787.99  5160.2 1787.77
  5520.3 1790.32  5600.3 1790.22  5630.3 1790.90  5680.3 1793.99  5836.7 1794.50
#Mann=6,-1,0
  4142.9     0.1       0  4315.1    0.05       0  4915.7    0.16       0
  4993.8    0.07       0  4999.8    0.16       0  5066.2     0.1       0
Bank Sta=4993.8,4999.8
Exp/Cntr=0.3,0.1

Type RM Length L Ch R = 1,2553,293,293,293
BEGIN DESCRIPTION:
UNT 0007 IN HEWA 5.0
END DESCRIPTION:
XS GIS Cut Line= 3
      2688353.92     10055426.92      2688232.39     10054853.98
      2687642.78     10054569.58
#Sta/Elev= 30
  4292.7 1791.13  4345.8 1790.66  4449.3 1788.97  4723.1 1786.57  4858.2 1783.88
  4873.4 1784.01  4876.0 1783.35  4883.3 1783.35  4894.9 1781.29  4917.5 1780.20
  4934.6 1780.09  4940.2 1779.21  4949.4 1778.95  4979.8 1776.08  4981.8 1775.40
  4993.8 1770.97  4999.4 1768.14  5002.2 1767.64  5005.4 1768.14  5025.1 1776.47
  5032.0 1778.22  5047.7 1778.38  5060.4 1781.33  5070.3 1782.74  5104.8 1785.98
  5138.1 1785.94  5160.3 1786.70  5194.4 1785.95  5382.4 1786.00  5533.0 1787.29
#Mann=7,-1,0
  4292.7     0.1       0  4345.8    0.05       0  4723.1     0.1       0
  4981.8    0.05       0  4999.4   0.035       0  5005.4    0.05       0
  5032.0     0.1       0
Bank Sta=4999.4,5005.4
Exp/Cntr=0.3,0.1

Type RM Length L Ch R = 1,2260,601,601,601
BEGIN DESCRIPTION:
UNT 0007 IN HEWA 4.0
END DESCRIPTION:
XS GIS Cut Line= 3
      2688590.02     10054989.39      2688208.08     10054440.79
      2687978.96     10054426.90
#Sta/Elev= 30
  4536.5 1784.45  4563.6 1784.16  4614.2 1784.12  4650.0 1784.16  4670.9 1784.49
  4896.4 1782.40  4908.9 1781.54  4921.4 1779.44  4951.0 1777.77  4972.0 1775.17
  4980.7 1772.78  4986.8 1769.79  4994.2 1767.37  4998.7 1766.61  5001.4 1766.11
  5004.7 1766.61  5007.8 1768.38  5016.5 1771.42  5022.6 1775.48  5037.4 1775.87
  5052.3 1777.73  5058.4 1778.96  5073.6 1778.91  5123.8 1778.69  5201.0 1780.23
  5234.3 1780.60  5304.8 1782.57  5374.9 1783.74  5402.1 1784.83  5434.5 1784.49
#Mann=6,-1,0
  4536.5    0.05       0  4896.4     0.1       0  4998.7    0.07       0
  5004.7     0.1       0  5073.6    0.05       0  5201.0     0.1       0
Bank Sta=4998.7,5004.7
Exp/Cntr=0.3,0.1

Type RM Length L Ch R = 1,1659,380,380,380
BEGIN DESCRIPTION:
UNT 0007 IN HEWA 3.0
END DESCRIPTION:
XS GIS Cut Line= 4
      2688725.44     10054833.16      2688631.69     10054097.04
      2688531.00     10054051.90      2687937.28     10054225.50
#Sta/Elev= 30
  4337.1 1782.45  4464.7 1781.33  4618.8 1779.94  4671.8 1781.08  4689.4 1779.68
  4800.2 1777.81  4836.2 1776.25  4952.9 1771.96  4981.3 1766.51  4986.4 1767.08
  4991.8 1764.25  4998.9 1763.71  5001.6 1763.21  5004.9 1763.71  5011.9 1767.44
  5022.0 1770.71  5052.3 1772.48  5076.6 1771.36  5122.5 1772.65  5128.0 1771.89
  5145.7 1772.82  5174.3 1772.31  5265.1 1776.17  5285.0 1774.79  5321.6 1776.56
  5388.5 1776.24  5505.2 1777.91  5692.3 1781.01  5749.0 1783.05  5808.1 1782.15
#Mann=9,-1,0
  4337.1     0.1       0  4464.7    0.05       0  4836.2     0.1       0
  4952.9    0.16       0  4998.9    0.07       0  5004.9    0.16       0
  5076.6     0.1       0  5285.0    0.05       0  5505.2     0.1       0
Bank Sta=4998.9,5004.9
Exp/Cntr=0.3,0.1

Type RM Length L Ch R = 1,1279,548,548,548
BEGIN DESCRIPTION:
UNT 0007 IN HEWA 2.0
END DESCRIPTION:
XS GIS Cut Line= 4
      2688949.09     10055137.42      2688962.74     10054309.23
      2689067.40     10054095.36      2688134.58     10053977.05
#Sta/Elev= 30
  4079.4 1782.96  4263.4 1781.82  4268.6 1781.74  4656.1 1779.06  4713.2 1779.38
  4733.2 1777.62  4863.8 1772.65  4936.9 1769.13  4954.8 1769.21  4955.0 1769.21
  4969.5 1768.79  4995.8 1761.36  4998.6 1760.86  5001.8 1761.36  5021.3 1768.75
  5066.4 1775.86  5080.8 1776.90  5103.1 1777.00  5143.9 1775.21  5285.9 1777.35
  5326.2 1776.28  5439.5 1775.94  5507.6 1773.87  5568.1 1771.28  5628.6 1770.72
  5760.2 1773.84  5860.4 1775.09  5961.2 1777.78  6020.0 1777.93  6086.1 1778.34
#Mann=12,-1,0
  4079.4    0.05       0  4263.4     0.1       0  4268.6    0.05       0
  4656.1     0.1       0  4863.8    0.05       0  4954.8     0.1       0
  4955.0    0.16       0  4995.8    0.07       0  5001.8    0.16       0
  5507.6     0.1       0  5760.2    0.05       0  6020.0     0.1       0
Bank Sta=4995.8,5001.8
Exp/Cntr=0.3,0.1