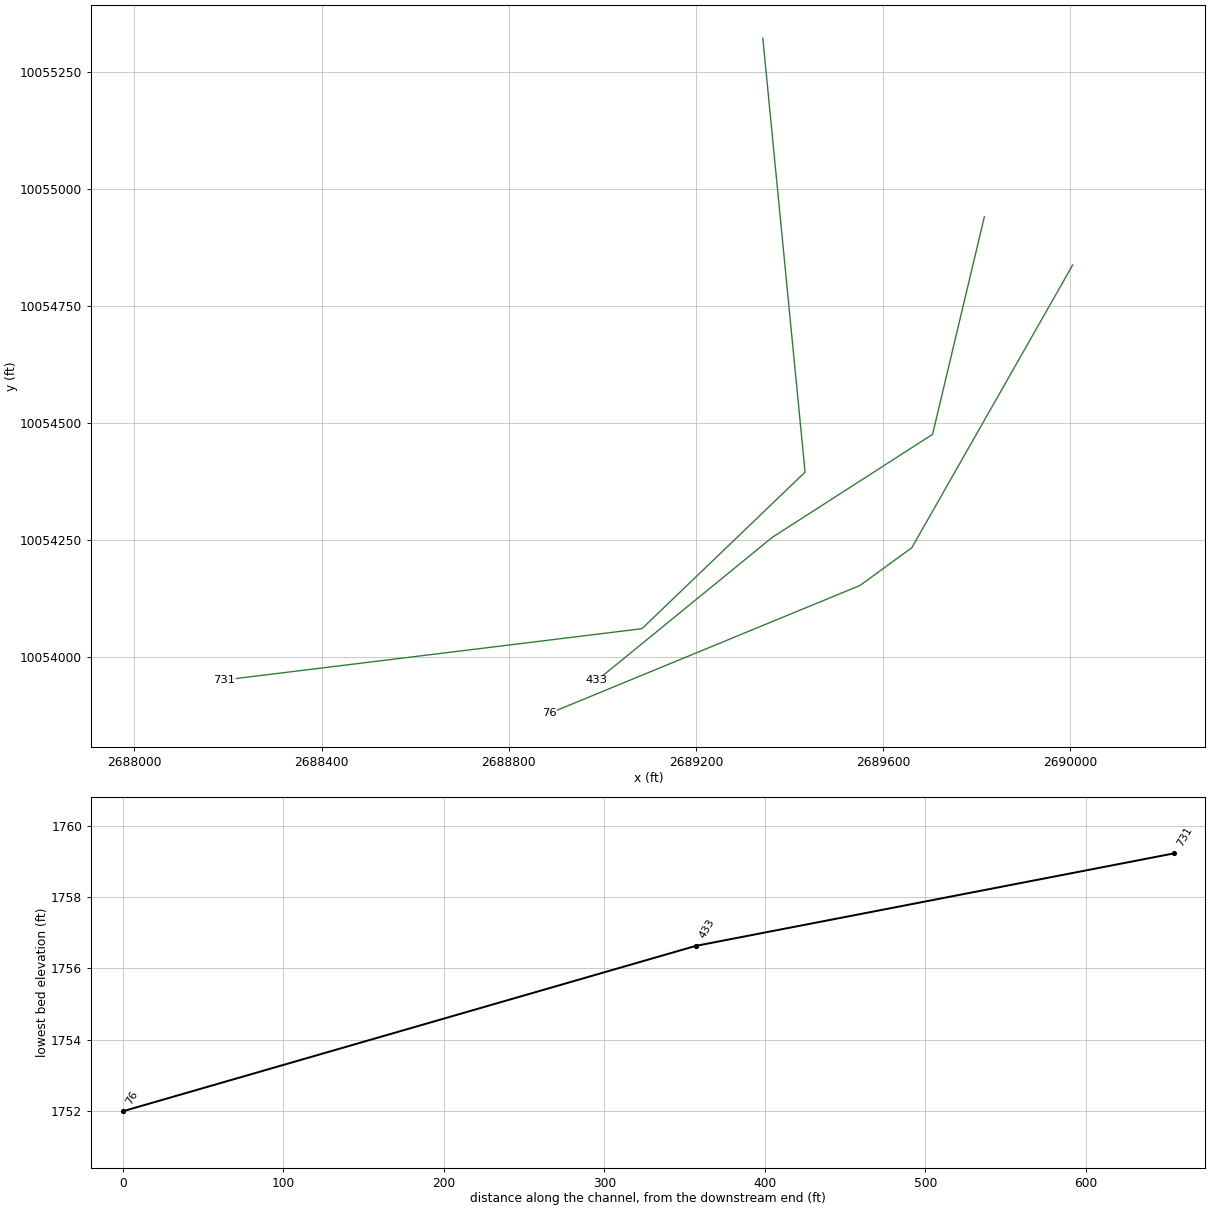
HEC-RAS study UNT 0007 IN HEWA.prj: UNT 0007 IN HEWA Base Level Engineering

--- UNT 0007 IN HEWA.g01 (geometry) --- (continued)

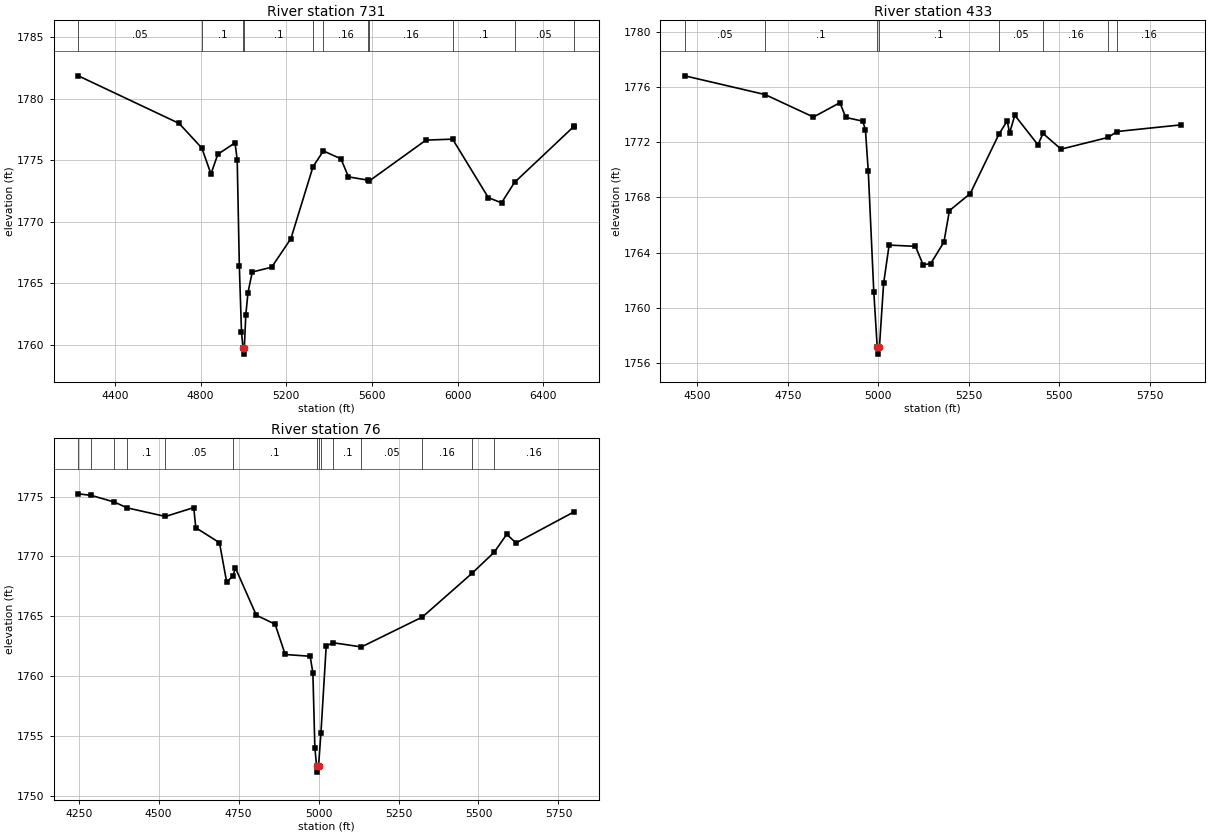
Type RM Length L Ch R = 1,731,298,298,298
BEGIN DESCRIPTION:
Mapping XS 1a0f6135
END DESCRIPTION:
XS GIS Cut Line= 4
      2689343.16     10055321.79      2689433.45     10054394.67
      2689084.85     10054060.03      2688191.89     10053950.41
#Sta/Elev= 30
  4229.5 1781.86  4699.8 1777.99  4805.8 1775.99  4848.6 1773.88  4880.6 1775.48
  4961.0 1776.41  4971.1 1775.01  4981.1 1766.35  4991.1 1761.02  4998.2 1759.72
  5000.9 1759.22  5004.2 1759.72  5011.2 1762.40  5021.3 1764.22  5041.4 1765.90
  5131.8 1766.29  5221.9 1768.62  5324.8 1774.46  5373.3 1775.75  5455.2 1775.11
  5490.5 1773.64  5582.2 1773.37  5585.2 1773.28  5852.2 1776.63  5976.5 1776.71
  6143.3 1771.95  6204.8 1771.53  6265.6 1773.19  6541.8 1777.73  6543.9 1777.80
#Mann=11,-1,0
  4229.5    0.05       0  4805.8     0.1       0  4998.2    0.07       0
  5004.2     0.1       0  5324.8    0.05       0  5373.3    0.16       0
  5582.2     0.1       0  5585.2    0.16       0  5976.5     0.1       0
  6265.6    0.05       0  6541.8     0.1       0
Bank Sta=4998.2,5004.2
Exp/Cntr=0.3,0.1

Type RM Length L Ch R = 1,433,357,357,357
BEGIN DESCRIPTION:
Mapping XS 91f43235
END DESCRIPTION:
XS GIS Cut Line= 4
      2689816.63     10054940.27      2689705.94     10054475.39
      2689363.50     10054255.34      2688988.52     10053949.37
#Sta/Elev= 30
  4465.8 1776.82  4687.5 1775.46  4820.9 1773.83  4894.0 1774.87  4910.3 1773.80
  4957.3 1773.53  4964.5 1772.89  4972.4 1769.88  4987.6 1761.14  4997.1 1757.13
  4999.9 1756.63  5003.1 1757.13  5014.7 1761.76  5029.9 1764.54  5102.6 1764.45
  5123.7 1763.11  5144.8 1763.20  5181.2 1764.76  5196.4 1767.04  5253.8 1768.28
  5333.2 1772.59  5356.0 1773.56  5362.4 1772.66  5376.8 1773.96  5440.7 1771.82
  5454.8 1772.64  5504.6 1771.50  5634.4 1772.35  5659.3 1772.78  5834.7 1773.26
#Mann=8,-1,0
  4465.8    0.05       0  4687.5     0.1       0  4997.1    0.07       0
  5003.1     0.1       0  5333.2    0.05       0  5454.8    0.16       0
  5634.4     0.1       0  5659.3    0.16       0
Bank Sta=4997.1,5003.1
Exp/Cntr=0.3,0.1

Type RM Length L Ch R = 1,76,0,0,0
BEGIN DESCRIPTION:
UNT 0007 IN HEWA 1.0
END DESCRIPTION:
XS GIS Cut Line= 4
      2690005.40     10054837.33      2689661.67     10054233.21
      2689551.00     10054152.48      2688886.94     10053879.04
#Sta/Elev= 30
  4248.9 1775.23  4289.2 1775.10  4361.9 1774.54  4401.2 1774.06  4521.3 1773.34
  4609.7 1774.08  4616.1 1772.40  4690.2 1771.15  4712.7 1767.86  4732.5 1768.39
  4740.1 1769.04  4805.3 1765.10  4864.0 1764.35  4895.7 1761.82  4973.7 1761.67
  4982.2 1760.29  4988.4 1754.03  4993.9 1752.50  4996.6 1752.00  4999.9 1752.50
  5007.5 1755.30  5023.9 1762.54  5045.5 1762.80  5134.0 1762.45  5324.7 1764.95
  5479.1 1768.58  5549.3 1770.36  5588.2 1771.85  5617.5 1771.13  5799.1 1773.73
#Mann=14,-1,0
  4248.9    0.05       0  4289.2     0.1       0  4361.9    0.05       0
  4401.2     0.1       0  4521.3    0.05       0  4732.5     0.1       0
  4993.9    0.07       0  4999.9     0.1       0  5007.5    0.05       0
  5045.5     0.1       0  5134.0    0.05       0  5324.7    0.16       0
  5479.1     0.1       0  5549.3    0.16       0
Bank Sta=4993.9,4999.9
Exp/Cntr=0.3,0.1

Chan Stop Cuts=-1