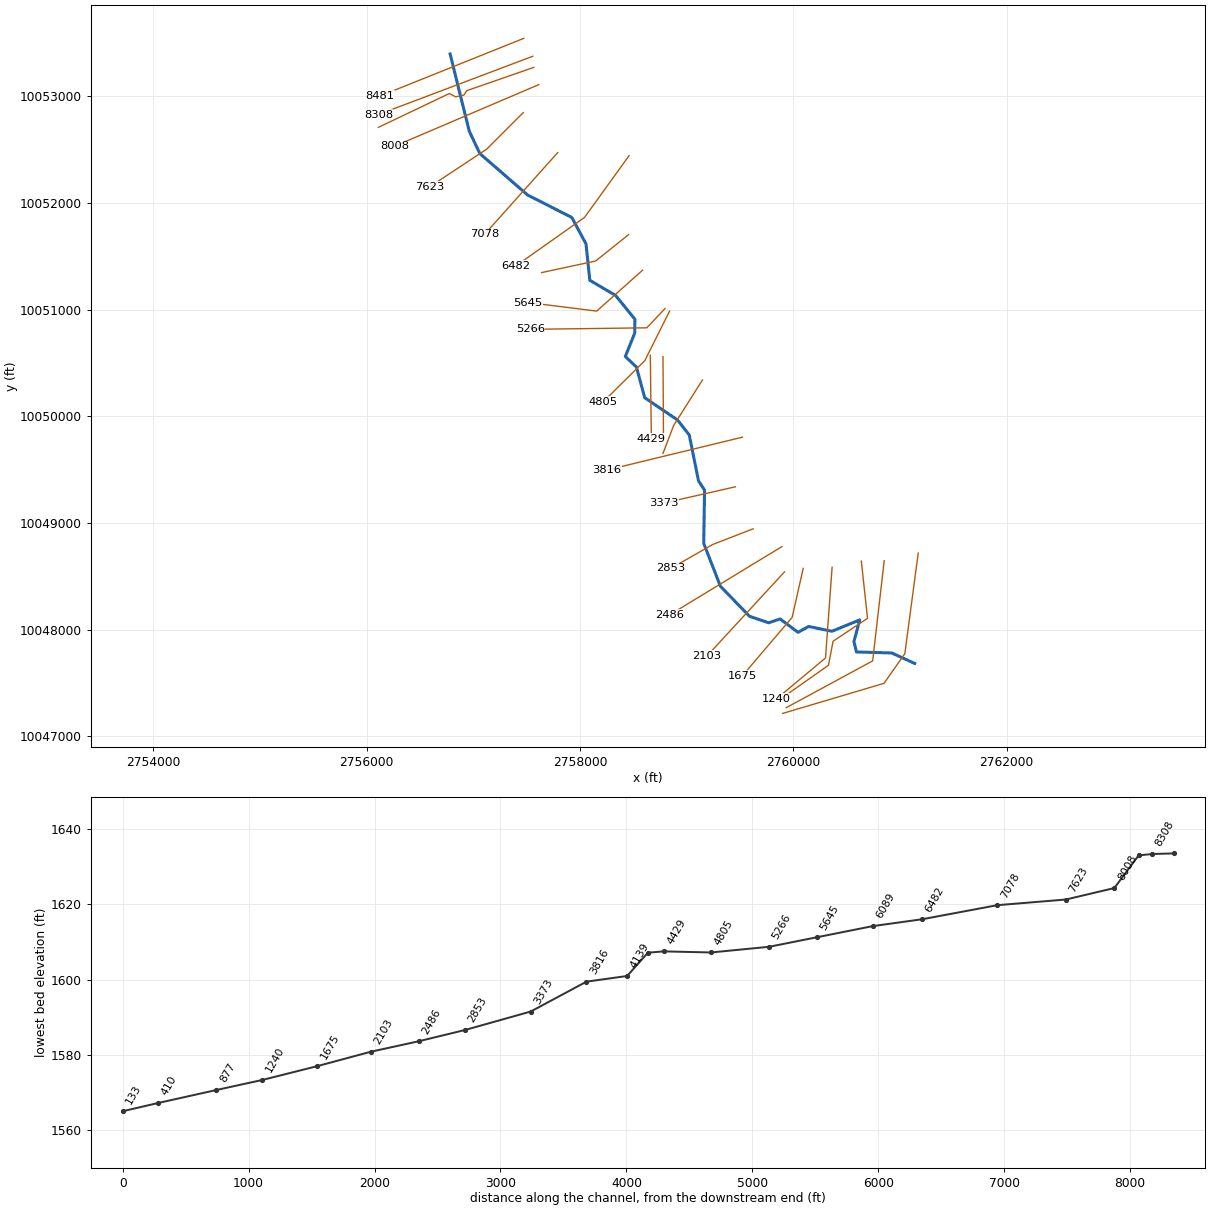
--- UNT 0008 IN HEWA.prj (project) ---

Proj Title=UNT 0008 IN HEWA Base Level Engineering
Current Plan=p01
Default Exp/Contr=0.3,0.1
English Units
Geom File=g01
Flow File=f01
Plan File=p01
BEGIN DESCRIPTION:
UNT 0008 IN HEWA
END DESCRIPTION:

--- UNT 0008 IN HEWA.p01 (plan) ---

Plan Title=Multiple Run
Short Identifier=Multiple
Geom File=g01
Flow File=f01
Subcritical Flow
K Sum by GR= 0
Std Step Tol= 0.01
Critical Tol= 0.01
Num of Std Step Trials= 20
Max Error Tol= 0.3
Flow Tol Ratio= 0.001
Split Flow NTrial= 30
Split Flow Tol= 0.02
Split Flow Ratio= 0.02
Log Output Level= 0
Friction Slope Method= 1
Unsteady Friction Slope Method= 2
Unsteady Bridges Friction Slope Method= 1
Parabolic Critical Depth
Global Vel Dist=  1 , 1 , 1
Global Log Level= 0
CheckData=True
Encroach Param= -1, 0, 0, 0
BEGIN DESCRIPTION:
Multiple Run
END DESCRIPTION:

--- UNT 0008 IN HEWA.f01 (steady flow) ---

Flow Title=Multiple
Number of Profiles=7
Profile Names=10-year,25-year,50-year,1pct_min,100-year,1pct_plu,500-year
River Rch & RM= UNT 0008 IN HEWA,Reach-1,8481
    1050    1535    1958    1825    2468    3338    3943
Boundary for River Rch & Prof#=UNT 0008 IN HEWA,Reach-1,1
Up Type=0
Dn Type=3
Dn Slope=0.005
Boundary for River Rch & Prof#=UNT 0008 IN HEWA,Reach-1,2
Up Type=0
Dn Type=3
Dn Slope=0.005
Boundary for River Rch & Prof#=UNT 0008 IN HEWA,Reach-1,3
Up Type=0
Dn Type=3
Dn Slope=0.005
Boundary for River Rch & Prof#=UNT 0008 IN HEWA,Reach-1,4
Up Type=0
Dn Type=3
Dn Slope=0.005
Boundary for River Rch & Prof#=UNT 0008 IN HEWA,Reach-1,5
Up Type=0
Dn Type=3
Dn Slope=0.005
Boundary for River Rch & Prof#=UNT 0008 IN HEWA,Reach-1,6
Up Type=0
Dn Type=3
Dn Slope=0.005
Boundary for River Rch & Prof#=UNT 0008 IN HEWA,Reach-1,7
Up Type=0
Dn Type=3
Dn Slope=0.005

--- UNT 0008 IN HEWA.g01 (geometry) ---

Geom Title=Existing Conditions

River Reach=UNT 0008 IN HEWA,Reach-1
Reach XY= 30
      2756782.14     10053398.58      2756961.32     10052674.91
      2757060.68     10052464.61      2757509.25     10052075.78
      2757923.29     10051865.54      2758056.15     10051617.77
      2758091.95     10051276.28      2758333.82     10051133.91
      2758514.63     10050911.59      2758512.81     10050780.02
      2758425.09     10050561.54      2758529.20     10050462.44
      2758606.44     10050175.81      2758915.00     10049965.83
      2759023.93     10049826.57      2759111.49     10049394.98
      2759167.99     10049308.53      2759160.04     10048809.54
      2759316.38     10048407.54      2759589.27     10048125.96
      2759769.02     10048064.53      2759876.83     10048100.31
      2760044.37     10047975.26      2760143.51     10048030.13
      2760362.91     10047985.51      2760622.76     10048091.84
      2760568.85     10047889.22      2760592.32     10047791.26
      2760922.88     10047781.84      2761138.47     10047683.73

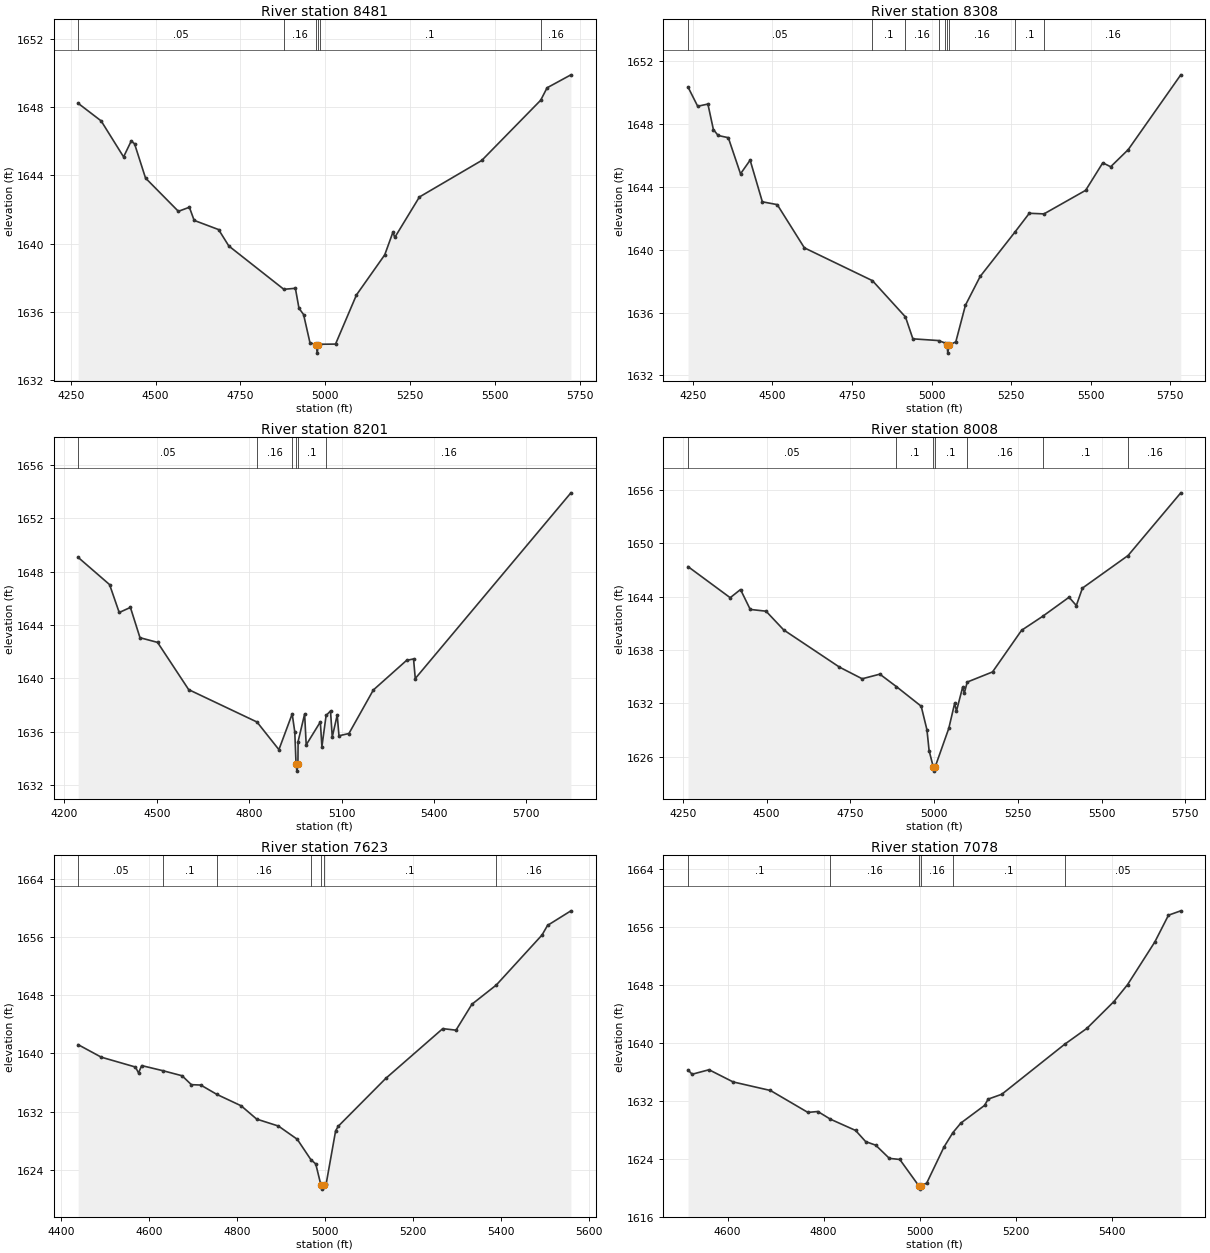
Type RM Length L Ch R = 1,8481,173,173,173
BEGIN DESCRIPTION:
UNT 0008 IN HEWA 18.0
END DESCRIPTION:
XS GIS Cut Line= 2
      2757472.74     10053545.36      2756124.32     10053004.09
#Sta/Elev= 30
  4271.6 1648.22  4339.3 1647.19  4405.5 1645.08  4428.0 1646.01  4437.8 1645.85
  4470.2 1643.84  4567.1 1641.89  4599.5 1642.13  4613.6 1641.36  4685.7 1640.82
  4715.8 1639.86  4878.1 1637.32  4912.1 1637.38  4922.7 1636.21  4936.3 1635.84
  4955.1 1634.19  4973.6 1634.08  4976.4 1633.58  4979.6 1634.08  4984.1 1634.10
  5030.5 1634.11  5092.2 1636.99  5175.6 1639.34  5199.8 1640.67  5205.2 1640.36
  5277.8 1642.73  5461.5 1644.87  5635.4 1648.40  5654.3 1649.13  5724.6 1649.89
#Mann=6,-1,0
  4271.6    0.05       0  4878.1    0.16       0  4973.6    0.07       0
  4979.6    0.16       0  4984.1     0.1       0  5635.4    0.16       0
Bank Sta=4973.6,4979.6
Exp/Cntr=0.3,0.1

Type RM Length L Ch R = 1,8308,107,107,107
BEGIN DESCRIPTION:
Mapping XS 73b3fa9a
END DESCRIPTION:
XS GIS Cut Line= 2
      2757556.85     10053377.23      2756108.98     10052830.38
#Sta/Elev= 30
  4235.1 1650.35  4265.4 1649.13  4297.5 1649.27  4314.7 1647.65  4329.6 1647.27
  4361.6 1647.13  4399.9 1644.83  4430.1 1645.70  4468.5 1643.05  4515.3 1642.87
  4600.5 1640.12  4814.4 1638.03  4918.1 1635.72  4941.3 1634.33  5021.9 1634.22
  5041.8 1634.07  5048.4 1633.92  5051.1 1633.42  5054.4 1633.92  5076.2 1634.14
  5106.4 1636.47  5152.7 1638.30  5261.0 1641.10  5307.0 1642.32  5353.1 1642.28
  5484.0 1643.78  5537.8 1645.53  5562.6 1645.28  5617.7 1646.37  5782.8 1651.13
#Mann=9,-1,0
  4235.1    0.05       0  4814.4     0.1       0  4918.1    0.16       0
  5021.9     0.1       0  5041.8    0.16       0  5048.4    0.07       0
  5054.4    0.16       0  5261.0     0.1       0  5353.1    0.16       0
Bank Sta=5048.4,5054.4
Exp/Cntr=0.3,0.1

Type RM Length L Ch R = 1,8201,193,193,193
BEGIN DESCRIPTION:
Mapping XS 226b3310
END DESCRIPTION:
XS GIS Cut Line= 6
      2757567.30     10053273.08      2756937.09     10053054.33
      2756911.05     10053012.66      2756832.93     10052997.04
      2756775.63     10053028.29      2756108.93     10052710.57
#Sta/Elev= 30
  4245.0 1649.07  4347.0 1647.03  4378.2 1644.94  4414.6 1645.32  4445.7 1643.05
  4502.7 1642.70  4603.7 1639.16  4825.6 1636.73  4896.7 1634.66  4939.8 1637.34
  4948.2 1635.99  4952.4 1633.55  4955.1 1633.05  4958.4 1633.55  4959.0 1635.27
  4980.2 1637.33  4985.3 1635.02  5031.2 1636.74  5036.3 1634.89  5049.9 1637.22
  5064.2 1637.56  5069.9 1635.61  5086.0 1637.26  5091.7 1635.70  5124.0 1635.87
  5203.2 1639.13  5311.1 1641.35  5333.8 1641.46  5339.4 1639.99  5844.7 1653.91
#Mann=6,-1,0
  4245.0    0.05       0  4825.6    0.16       0  4939.8     0.1       0
  4952.4    0.07       0  4958.4     0.1       0  5049.9    0.16       0
Bank Sta=4952.4,4958.4
Exp/Cntr=0.3,0.1

Type RM Length L Ch R = 1,8008,385,385,385
BEGIN DESCRIPTION:
Mapping XS edca6a36
END DESCRIPTION:
XS GIS Cut Line= 2
      2757614.16     10053111.62      2756261.76     10052534.24
#Sta/Elev= 30
  4265.6 1647.39  4391.4 1643.89  4422.2 1644.81  4451.2 1642.57  4498.4 1642.37
  4551.1 1640.26  4717.6 1636.07  4785.3 1634.76  4838.0 1635.28  4887.0 1633.89
  4961.4 1631.67  4978.6 1629.01  4985.0 1626.67  4997.3 1624.86  5000.0 1624.36
  5003.3 1624.86  5043.8 1629.18  5061.3 1632.00  5066.7 1631.13  5084.9 1633.78
  5090.3 1633.17  5098.8 1634.39  5174.3 1635.53  5261.0 1640.22  5323.8 1641.79
  5402.6 1643.94  5424.4 1643.01  5442.6 1644.97  5578.8 1648.64  5736.1 1655.70
#Mann=7,-1,0
  4265.6    0.05       0  4887.0     0.1       0  4997.3    0.07       0
  5003.3     0.1       0  5098.8    0.16       0  5323.8     0.1       0
  5578.8    0.16       0
Bank Sta=4997.3,5003.3
Exp/Cntr=0.3,0.1

Type RM Length L Ch R = 1,7623,545,545,545
BEGIN DESCRIPTION:
UNT 0008 IN HEWA 17.0
END DESCRIPTION:
XS GIS Cut Line= 3
      2757467.67     10052848.75      2757125.79     10052506.87
      2756594.06     10052155.55
#Sta/Elev= 30
  4439.0 1641.21  4491.5 1639.49  4569.3 1638.13  4576.3 1637.31  4583.4 1638.33
  4632.0 1637.62  4675.3 1636.93  4696.5 1635.70  4717.8 1635.65  4754.8 1634.35
  4809.7 1632.79  4845.0 1630.96  4894.5 1630.00  4937.3 1628.18  4968.2 1625.38
  4979.4 1624.78  4991.4 1621.81  4994.2 1621.31  4997.4 1621.81  5003.2 1622.07
  5024.6 1629.34  5030.5 1629.97  5138.9 1636.58  5268.3 1643.42  5298.4 1643.21
  5334.6 1646.78  5390.1 1649.43  5494.1 1656.32  5506.6 1657.64  5559.8 1659.65
#Mann=7,-1,0
  4439.0    0.05       0  4632.0     0.1       0  4754.8    0.16       0
  4968.2     0.1       0  4991.4    0.07       0  4997.4     0.1       0
  5390.1    0.16       0
Bank Sta=4991.4,4997.4
Exp/Cntr=0.3,0.1

Type RM Length L Ch R = 1,7078,596,596,596
BEGIN DESCRIPTION:
UNT 0008 IN HEWA 15.0
END DESCRIPTION:
XS GIS Cut Line= 2
      2757790.49     10052473.61      2757106.83     10051709.24
#Sta/Elev= 30
  4517.8 1636.23  4526.3 1635.64  4561.5 1636.26  4611.6 1634.58  4689.3 1633.40
  4767.1 1630.38  4788.0 1630.50  4814.2 1629.44  4866.5 1627.89  4887.5 1626.35
  4908.4 1625.86  4936.8 1624.04  4958.5 1623.89  4997.6 1620.30  5000.4 1619.80
  5003.6 1620.30  5014.5 1620.63  5050.5 1625.61  5069.0 1627.59  5085.6 1628.91
  5134.9 1631.34  5142.4 1632.21  5170.8 1632.88  5301.4 1639.76  5348.0 1641.97
  5404.1 1645.66  5432.5 1647.99  5489.3 1653.88  5517.7 1657.57  5543.3 1658.17
#Mann=6,-1,0
  4517.8     0.1       0  4814.2    0.16       0  4997.6    0.07       0
  5003.6    0.16       0  5069.0     0.1       0  5301.4    0.05       0
Bank Sta=4997.6,5003.6
Exp/Cntr=0.3,0.1

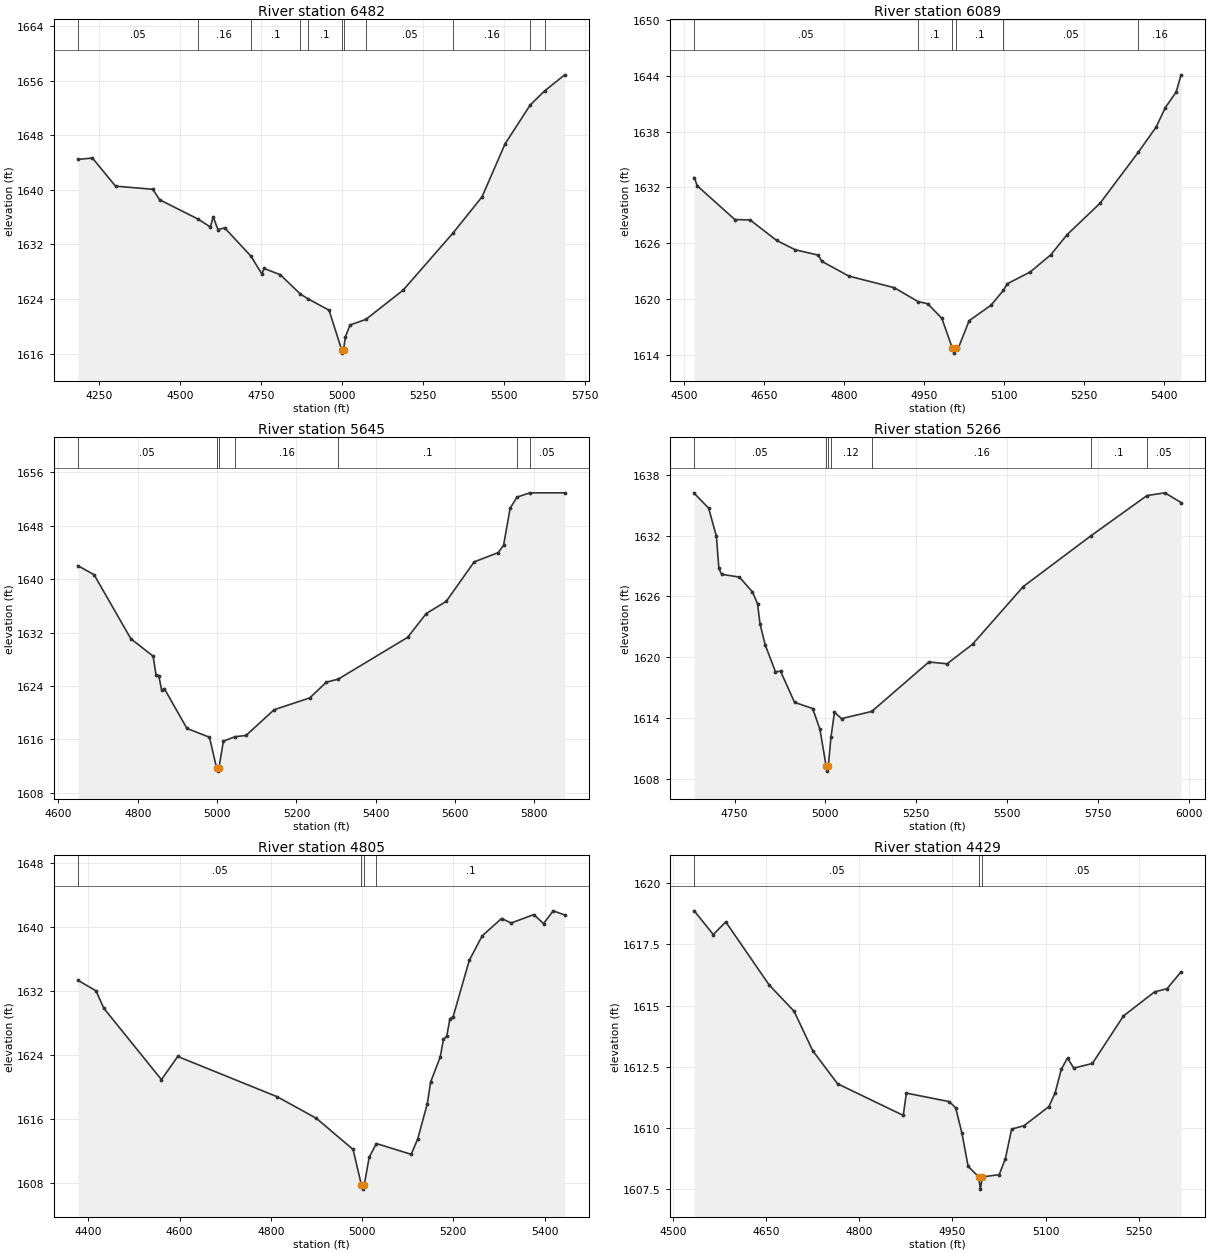
Type RM Length L Ch R = 1,6482,393,393,393
BEGIN DESCRIPTION:
UNT 0008 IN HEWA 14.0
END DESCRIPTION:
XS GIS Cut Line= 3
      2758459.98     10052445.17      2758042.15     10051865.89
      2757396.45     10051410.11
#Sta/Elev= 30
  4183.2 1644.46  4228.3 1644.66  4299.5 1640.54  4414.8 1640.08  4435.7 1638.55
  4553.0 1635.75  4592.8 1634.56  4601.3 1636.05  4616.0 1634.18  4636.9 1634.42
  4717.7 1630.30  4752.1 1627.65  4758.4 1628.48  4808.7 1627.55  4871.2 1624.71
  4894.5 1624.02  4959.5 1622.35  4998.3 1616.56  5001.0 1616.06  5004.3 1616.56
  5009.9 1618.45  5024.4 1620.19  5073.4 1621.01  5188.5 1625.30  5341.9 1633.63
  5432.2 1638.97  5503.6 1646.75  5581.2 1652.44  5625.4 1654.49  5687.8 1656.86
#Mann=11,-1,0
  4183.2    0.05       0  4553.0    0.16       0  4717.7     0.1       0
  4871.2    0.16       0  4894.5     0.1       0  4998.3    0.07       0
  5004.3     0.1       0  5073.4    0.05       0  5341.9    0.16       0
  5581.2    0.05       0  5625.4     0.1       0
Bank Sta=4998.3,5004.3
Exp/Cntr=0.3,0.1

Type RM Length L Ch R = 1,6089,444,444,444
BEGIN DESCRIPTION:
UNT 0008 IN HEWA 13.0
END DESCRIPTION:
XS GIS Cut Line= 3
      2758455.23     10051704.47      2758146.60     10051457.57
      2757639.43     10051348.55
#Sta/Elev= 30
  4518.6 1633.06  4524.3 1632.17  4594.8 1628.56  4623.6 1628.51  4673.2 1626.32
  4708.4 1625.31  4751.6 1624.74  4758.0 1624.08  4809.0 1622.49  4894.1 1621.25
  4938.7 1619.76  4956.9 1619.53  4983.5 1617.96  5003.3 1614.73  5006.0 1614.23
  5009.3 1614.73  5014.2 1614.75  5034.7 1617.71  5075.6 1619.36  5099.1 1620.97
  5106.3 1621.67  5149.3 1622.93  5188.1 1624.78  5218.8 1626.95  5280.2 1630.29
  5352.6 1635.80  5385.9 1638.49  5402.9 1640.55  5423.4 1642.24  5432.6 1644.08
#Mann=6,-1,0
  4518.6    0.05       0  4938.7     0.1       0  5003.3    0.07       0
  5009.3     0.1       0  5099.1    0.05       0  5352.6    0.16       0
Bank Sta=5003.3,5009.3
Exp/Cntr=0.3,0.1

Type RM Length L Ch R = 1,5645,379,379,379
BEGIN DESCRIPTION:
UNT 0008 IN HEWA 12.0
END DESCRIPTION:
XS GIS Cut Line= 3
      2758588.17     10051372.12      2758156.10     10050987.52
      2757511.96     10051068.04
#Sta/Elev= 30
  4649.0 1642.01  4689.8 1640.67  4782.5 1631.08  4838.7 1628.47  4846.2 1625.61
  4852.9 1625.57  4860.4 1623.34  4867.1 1623.60  4923.9 1617.66  4980.8 1616.33
  4998.7 1611.76  5001.5 1611.26  5004.7 1611.76  5015.9 1615.75  5045.1 1616.41
  5072.8 1616.60  5143.8 1620.45  5233.7 1622.22  5275.5 1624.57  5305.7 1625.04
  5480.6 1631.29  5527.4 1634.85  5577.8 1636.67  5648.3 1642.58  5708.8 1643.97
  5722.4 1645.06  5739.0 1650.62  5756.4 1652.28  5788.7 1652.92  5876.6 1652.92
#Mann=7,-1,0
  4649.0    0.05       0  4998.7   0.035       0  5004.7    0.05       0
  5045.1    0.16       0  5305.7     0.1       0  5756.4    0.16       0
  5788.7    0.05       0
Bank Sta=4998.7,5004.7
Exp/Cntr=0.3,0.1

Type RM Length L Ch R = 1,5266,461,461,461
BEGIN DESCRIPTION:
UNT 0008 IN HEWA 11.0
END DESCRIPTION:
XS GIS Cut Line= 3
      2758797.07     10051011.26      2758626.15     10050830.84
      2757534.07     10050816.59
#Sta/Elev= 30
  4638.8 1636.19  4678.4 1634.73  4699.8 1631.95  4706.7 1628.76  4714.0 1628.19
  4763.3 1627.91  4798.9 1626.45  4813.1 1625.28  4819.9 1623.30  4834.1 1621.22
  4862.4 1618.56  4876.6 1618.60  4915.0 1615.53  4965.0 1614.92  4985.0 1612.86
  5002.0 1609.23  5004.8 1608.73  5008.0 1609.23  5015.3 1612.08  5025.0 1614.55
  5044.5 1613.92  5127.6 1614.63  5285.0 1619.52  5335.1 1619.34  5405.1 1621.27
  5545.1 1626.98  5732.3 1632.02  5885.6 1635.97  5935.1 1636.24  5979.5 1635.28
#Mann=7,-1,0
  4638.8    0.05       0  5002.0    0.04       0  5008.0    0.05       0
  5015.3    0.12       0  5127.6    0.16       0  5732.3     0.1       0
  5885.6    0.05       0
Bank Sta=5002,5008
Exp/Cntr=0.3,0.1

Type RM Length L Ch R = 1,4805,376,376,376
BEGIN DESCRIPTION:
UNT 0008 IN HEWA 10.0
END DESCRIPTION:
XS GIS Cut Line= 3
      2758839.80     10050987.52      2758607.15     10050522.22
      2758218.37     10050138.18
#Sta/Elev= 30
  4377.3 1633.34  4417.2 1632.01  4434.0 1629.85  4560.4 1620.91  4596.1 1623.81
  4814.1 1618.77  4900.0 1616.07  4980.3 1612.18  4998.6 1607.72  5001.3 1607.22
  5004.6 1607.72  5015.7 1611.22  5031.4 1612.92  5107.6 1611.57  5121.8 1613.48
  5143.0 1617.92  5150.1 1620.60  5171.3 1623.75  5178.3 1625.96  5185.5 1626.34
  5192.5 1628.53  5199.6 1628.80  5234.9 1635.83  5263.2 1638.89  5305.6 1641.06
  5326.9 1640.50  5376.3 1641.55  5397.6 1640.42  5418.8 1642.02  5444.0 1641.50
#Mann=4,-1,0
  4377.3    0.05       0  4998.6    0.04       0  5004.6    0.05       0
  5031.4     0.1       0
Bank Sta=4998.6,5004.6
Exp/Cntr=0.3,0.1

Type RM Length L Ch R = 1,4429,125,125,125
BEGIN DESCRIPTION:
Mapping XS f9e44cc9
END DESCRIPTION:
XS GIS Cut Line= 2
      2758659.38     10050574.46      2758668.88     10049791.02
#Sta/Elev= 30
  4534.5 1618.87  4565.2 1617.90  4585.2 1618.42  4655.2 1615.84  4695.2 1614.77
  4725.2 1613.16  4765.2 1611.81  4870.9 1610.52  4875.9 1611.43  4945.3 1611.08
  4955.3 1610.82  4965.3 1609.80  4975.3 1608.44  4992.3 1608.01  4995.0 1607.51
  4998.3 1608.01  5025.3 1608.10  5035.3 1608.76  5045.3 1609.96  5065.3 1610.10
  5105.3 1610.88  5115.3 1611.44  5125.3 1612.41  5135.3 1612.86  5145.3 1612.45
  5175.3 1612.64  5225.3 1614.58  5275.3 1615.56  5295.3 1615.69  5318.0 1616.38
#Mann=3,-1,0
  4534.5    0.05       0  4992.3    0.04       0  4998.3    0.05       0
Bank Sta=4992.3,4998.3
Exp/Cntr=0.3,0.1

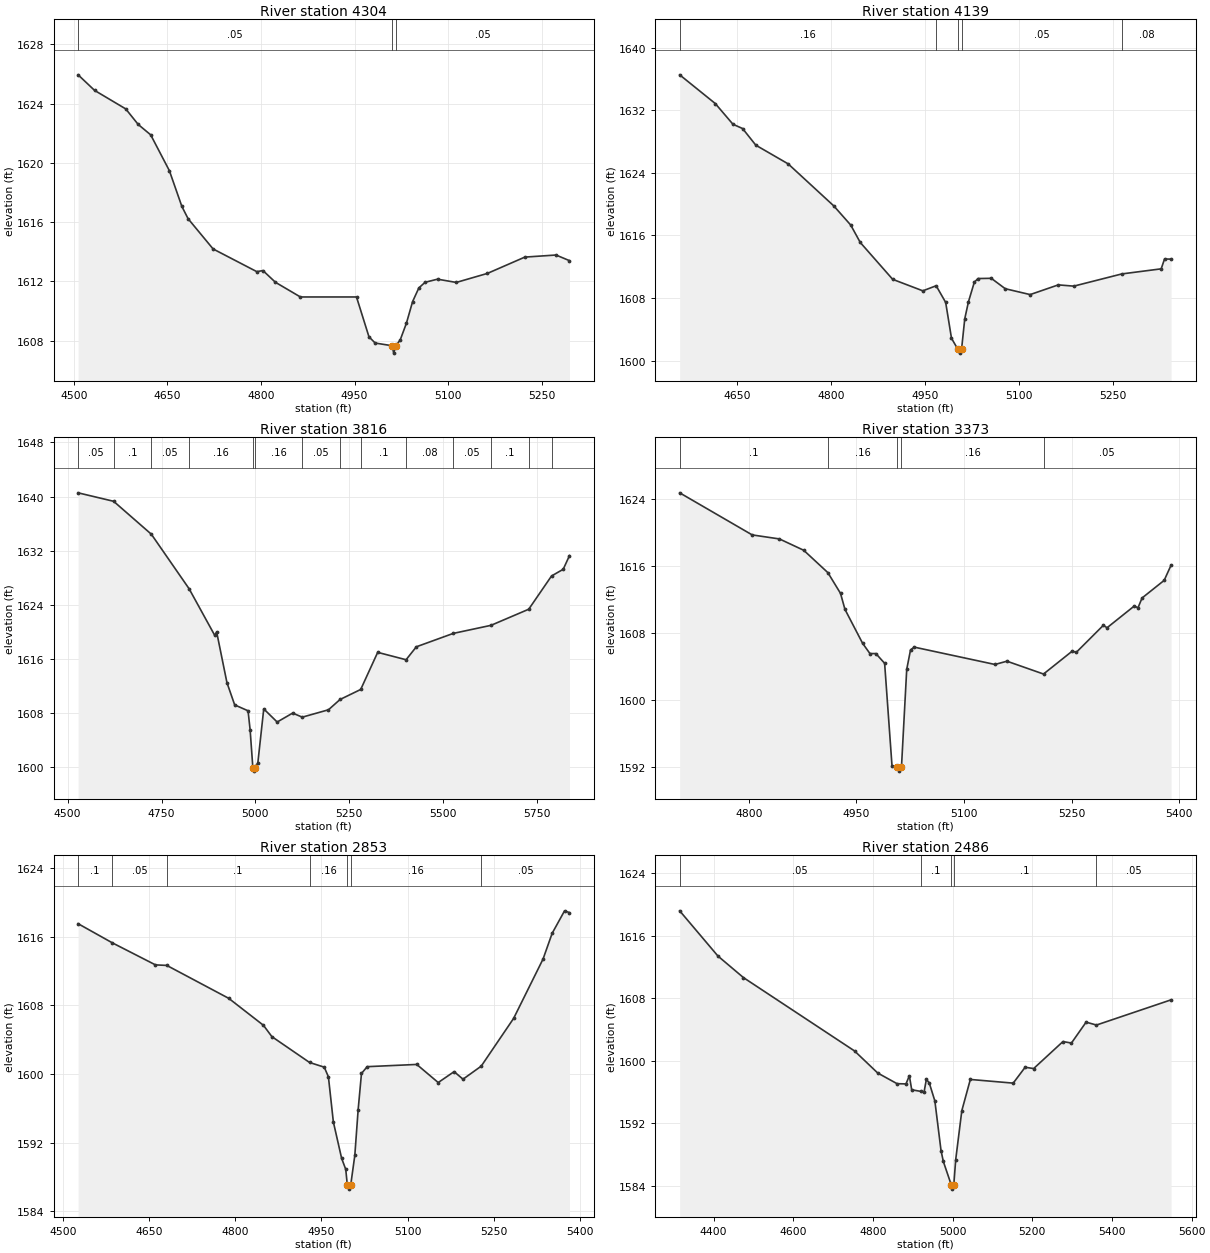
Type RM Length L Ch R = 1,4304,165,165,165
BEGIN DESCRIPTION:
Mapping XS 122c1de6
END DESCRIPTION:
XS GIS Cut Line= 2
      2758778.08     10050560.18      2758782.83     10049772.09
#Sta/Elev= 30
  4506.7 1625.94  4533.1 1624.89  4583.1 1623.64  4603.1 1622.59  4623.1 1621.89
  4653.1 1619.47  4673.1 1617.06  4683.1 1616.23  4723.2 1614.19  4793.2 1612.66
  4803.2 1612.73  4823.2 1611.94  4863.2 1610.95  4953.2 1610.95  4973.2 1608.26
  4983.2 1607.84  5010.2 1607.66  5012.9 1607.16  5016.2 1607.66  5023.2 1608.04
  5033.2 1609.17  5043.2 1610.64  5053.2 1611.56  5063.2 1611.94  5083.2 1612.15
  5113.2 1611.93  5163.2 1612.54  5223.2 1613.64  5273.2 1613.78  5294.8 1613.40
#Mann=3,-1,0
  4506.7    0.05       0  5010.2    0.04       0  5016.2    0.05       0
Bank Sta=5010.2,5016.2
Exp/Cntr=0.3,0.1

Type RM Length L Ch R = 1,4139,323,323,323
BEGIN DESCRIPTION:
Mapping XS d4b156cd
END DESCRIPTION:
XS GIS Cut Line= 3
      2759148.41     10050341.79      2758877.79     10049914.48
      2758778.09     10049653.36
#Sta/Elev= 30
  4557.8 1636.52  4614.7 1632.85  4643.0 1630.20  4658.3 1629.66  4679.5 1627.53
  4731.2 1625.14  4804.1 1619.77  4831.2 1617.32  4846.4 1615.10  4898.2 1610.39
  4946.4 1608.92  4967.7 1609.57  4982.9 1607.44  4992.2 1602.86  5002.3 1601.46
  5005.0 1600.96  5008.3 1601.46  5013.4 1605.35  5019.3 1607.52  5028.7 1610.03
  5034.6 1610.49  5055.8 1610.52  5078.1 1609.19  5117.9 1608.44  5162.9 1609.68
  5187.7 1609.52  5264.4 1611.08  5327.3 1611.73  5332.7 1612.99  5343.1 1612.97
#Mann=5,-1,0
  4557.8    0.16       0  4967.7    0.05       0  5002.3    0.04       0
  5008.3    0.05       0  5264.4    0.08       0
Bank Sta=5002.3,5008.3
Exp/Cntr=0.3,0.1

Type RM Length L Ch R = 1,3816,443,443,443
BEGIN DESCRIPTION:
UNT 0008 IN HEWA 8.0
END DESCRIPTION:
XS GIS Cut Line= 2
      2759523.48     10049805.27      2758252.23     10049496.95
#Sta/Elev= 30
  4528.0 1640.55  4622.5 1639.30  4722.9 1634.44  4823.4 1626.39  4891.7 1619.50
  4896.8 1620.00  4924.2 1612.52  4944.8 1609.23  4980.4 1608.36  4985.9 1605.56
  4993.2 1599.95  4996.0 1599.45  4999.2 1599.95  5006.5 1600.69  5022.2 1608.64
  5057.9 1606.70  5099.1 1608.02  5124.8 1607.42  5194.5 1608.51  5225.3 1610.03
  5280.3 1611.51  5325.5 1616.99  5401.1 1615.90  5428.4 1617.81  5526.7 1619.79
  5627.1 1620.98  5727.6 1623.36  5788.3 1628.27  5819.4 1629.26  5836.1 1631.28
#Mann=14,-1,0
  4528.0    0.05       0  4622.5     0.1       0  4722.9    0.05       0
  4823.4    0.16       0  4993.2    0.07       0  4999.2    0.16       0
  5124.8    0.05       0  5225.3    0.08       0  5280.3     0.1       0
  5401.1    0.08       0  5526.7    0.05       0  5627.1     0.1       0
  5727.6    0.05       0  5788.3     0.1       0
Bank Sta=4993.2,4999.2
Exp/Cntr=0.3,0.1

Type RM Length L Ch R = 1,3373,520,520,520
BEGIN DESCRIPTION:
UNT 0008 IN HEWA 7.0
END DESCRIPTION:
XS GIS Cut Line= 2
      2759457.08     10049339.99      2758789.06     10049188.38
#Sta/Elev= 30
  4703.7 1624.69  4804.8 1619.67  4842.8 1619.19  4876.6 1617.84  4910.3 1615.17
  4927.9 1612.70  4934.1 1610.79  4958.6 1606.76  4968.9 1605.52  4977.2 1605.52
  4989.4 1604.36  4999.7 1592.12  5006.9 1592.00  5009.7 1591.50  5012.9 1592.00
  5020.2 1603.64  5025.5 1605.95  5030.6 1606.29  5143.2 1604.22  5159.9 1604.61
  5210.9 1603.08  5251.2 1605.83  5256.4 1605.65  5294.3 1608.89  5299.5 1608.60
  5337.4 1611.19  5342.6 1610.98  5348.3 1612.15  5379.1 1614.25  5388.7 1616.06
#Mann=5,-1,0
  4703.7     0.1       0  4910.3    0.16       0  5006.9    0.07       0
  5012.9    0.16       0  5210.9    0.05       0
Bank Sta=5006.9,5012.9
Exp/Cntr=0.3,0.1

Type RM Length L Ch R = 1,2853,367,367,367
BEGIN DESCRIPTION:
UNT 0008 IN HEWA 6.0
END DESCRIPTION:
XS GIS Cut Line= 3
      2759623.22     10048945.90      2759243.38     10048798.71
      2758854.06     10048575.56
#Sta/Elev= 30
  4526.1 1617.53  4585.7 1615.30  4660.9 1612.73  4680.6 1612.67  4788.6 1608.83
  4849.0 1605.69  4863.7 1604.37  4929.3 1601.36  4955.0 1600.81  4962.2 1599.68
  4970.8 1594.43  4985.2 1590.19  4992.4 1588.90  4995.1 1587.10  4997.9 1586.60
  5001.1 1587.10  5008.2 1590.54  5014.0 1595.86  5019.8 1600.08  5029.8 1600.87
  5116.1 1601.13  5153.5 1599.02  5181.2 1600.29  5196.7 1599.41  5228.4 1600.93
  5284.9 1606.50  5336.2 1613.42  5352.0 1616.41  5373.6 1619.03  5382.2 1618.82
#Mann=7,-1,0
  4526.1     0.1       0  4585.7    0.05       0  4680.6     0.1       0
  4929.3    0.16       0  4995.1    0.07       0  5001.1    0.16       0
  5228.4    0.05       0
Bank Sta=4995.1,5001.1
Exp/Cntr=0.3,0.1

Type RM Length L Ch R = 1,2486,383,383,383
BEGIN DESCRIPTION:
UNT 0008 IN HEWA 5.0
END DESCRIPTION:
XS GIS Cut Line= 2
      2759893.84     10048779.72      2758839.83     10048138.76
#Sta/Elev= 30
  4314.7 1619.16  4410.8 1613.38  4474.8 1610.63  4753.7 1601.26  4811.9 1598.44
  4860.4 1597.08  4882.8 1597.05  4891.3 1598.09  4897.2 1596.30  4919.6 1596.10
  4928.1 1595.98  4934.0 1597.63  4941.3 1597.17  4955.3 1594.88  4970.8 1588.54
  4976.6 1587.14  4996.8 1584.11  4999.6 1583.61  5002.8 1584.11  5007.6 1587.35
  5023.0 1593.63  5044.4 1597.62  5152.0 1597.15  5182.0 1599.18  5203.3 1599.01
  5276.9 1602.46  5298.2 1602.27  5335.0 1604.94  5361.0 1604.57  5548.3 1607.79
#Mann=5,-1,0
  4314.7    0.05       0  4919.6     0.1       0  4996.8    0.07       0
  5002.8     0.1       0  5361.0    0.05       0
Bank Sta=4996.8,5002.8
Exp/Cntr=0.3,0.1

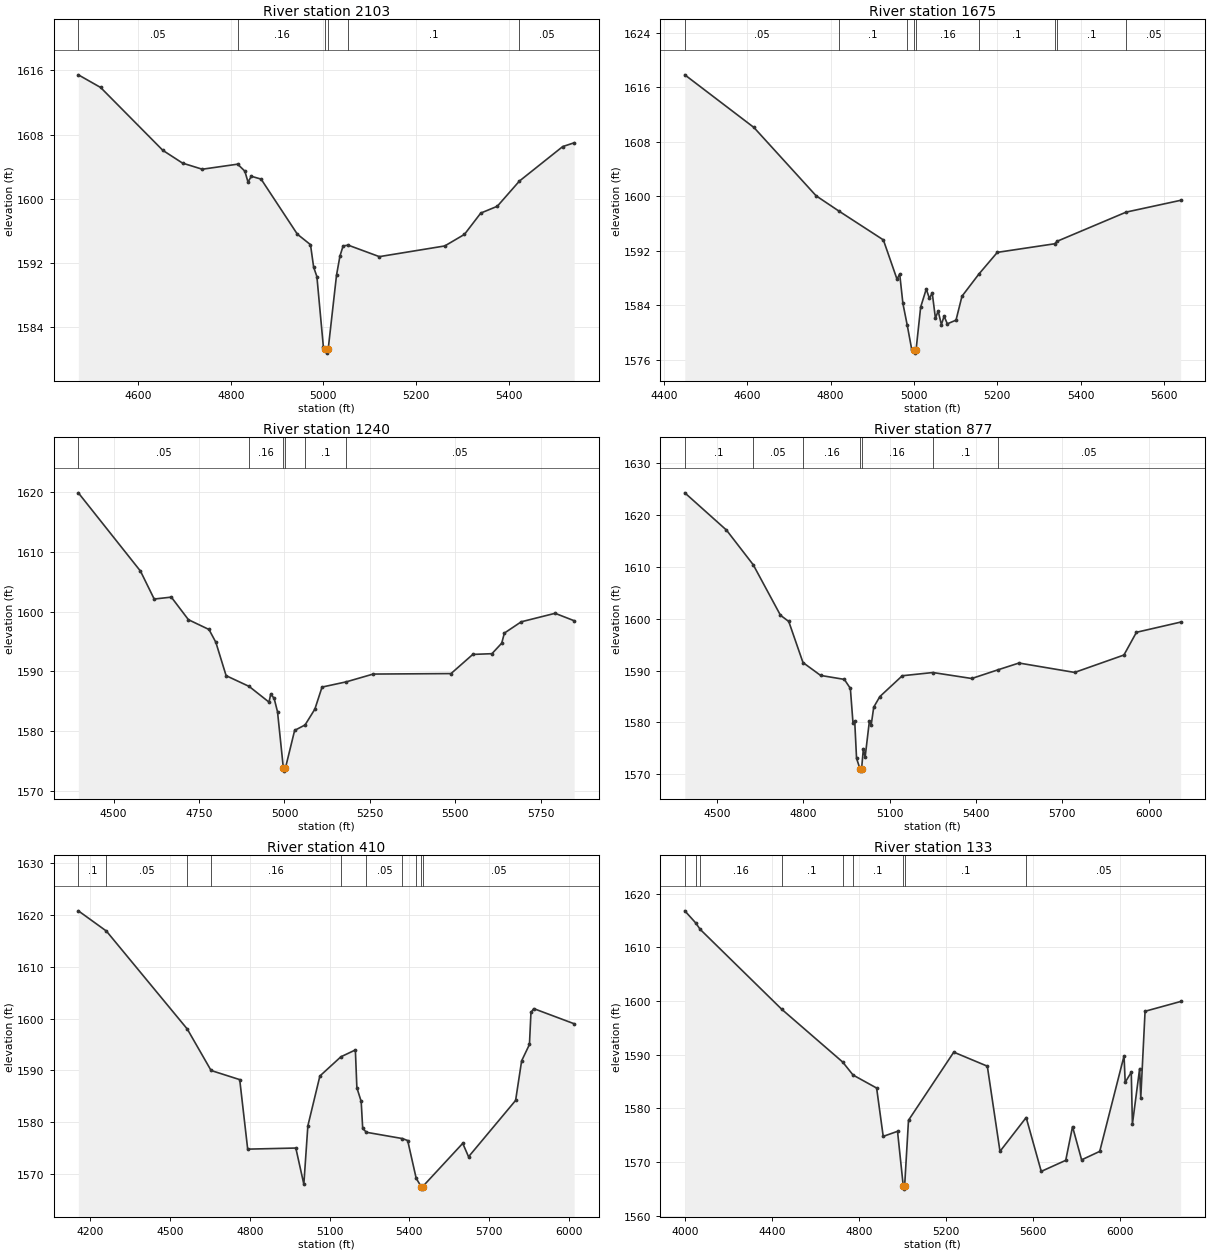
Type RM Length L Ch R = 1,2103,428,428,428
BEGIN DESCRIPTION:
UNT 0008 IN HEWA 4.0
END DESCRIPTION:
XS GIS Cut Line= 2
      2759917.61     10048542.34      2759192.30     10047755.41
#Sta/Elev= 30
  4471.1 1615.44  4519.1 1613.87  4653.5 1606.04  4696.1 1604.45  4738.6 1603.69
  4815.0 1604.32  4830.5 1603.45  4837.3 1602.10  4844.6 1602.81  4865.6 1602.46
  4943.9 1595.60  4972.2 1594.30  4979.0 1591.50  4986.0 1590.33  5000.0 1581.58
  5004.4 1581.30  5007.1 1580.80  5010.4 1581.30  5028.4 1590.51  5035.8 1592.89
  5042.6 1594.14  5053.6 1594.24  5120.8 1592.81  5262.0 1594.14  5304.5 1595.58
  5339.7 1598.23  5375.4 1599.08  5423.2 1602.22  5516.6 1606.51  5541.3 1606.98
#Mann=6,-1,0
  4471.1    0.05       0  4815.0    0.16       0  5004.4    0.07       0
  5010.4    0.16       0  5053.6     0.1       0  5423.2    0.05       0
Bank Sta=5004.4,5010.4
Exp/Cntr=0.3,0.1

Type RM Length L Ch R = 1,1675,435,435,435
BEGIN DESCRIPTION:
UNT 0008 IN HEWA 3.0
END DESCRIPTION:
XS GIS Cut Line= 3
      2760093.27     10048575.57      2759988.81     10048115.01
      2759523.54     10047569.02
#Sta/Elev= 30
  4450.3 1617.79  4616.2 1610.06  4765.4 1600.03  4820.1 1597.79  4926.7 1593.56
  4959.4 1587.80  4965.9 1588.55  4973.6 1584.23  4984.0 1581.03  4994.5 1577.56
  4999.2 1577.44  5001.9 1576.94  5005.2 1577.44  5016.2 1583.70  5029.6 1586.34
  5037.3 1584.96  5043.9 1585.80  5051.6 1582.07  5058.2 1583.12  5065.9 1581.12
  5072.4 1582.37  5080.2 1581.24  5101.0 1581.78  5115.3 1585.29  5155.8 1588.54
  5200.1 1591.73  5337.5 1592.99  5344.0 1593.37  5509.3 1597.64  5639.9 1599.37
#Mann=9,-1,0
  4450.3    0.05       0  4820.1     0.1       0  4984.0    0.16       0
  4999.2    0.07       0  5005.2    0.16       0  5155.8     0.1       0
  5337.5    0.05       0  5344.0     0.1       0  5509.3    0.05       0
Bank Sta=4999.2,5005.2
Exp/Cntr=0.3,0.1

Type RM Length L Ch R = 1,1240,363,363,363
BEGIN DESCRIPTION:
UNT 0008 IN HEWA 2.0
END DESCRIPTION:
XS GIS Cut Line= 3
      2760363.90     10048585.10      2760302.17     10047735.17
      2759842.53     10047351.34
#Sta/Elev= 30
  4396.8 1619.87  4578.6 1606.77  4618.8 1602.09  4668.9 1602.41  4719.0 1598.63
  4779.2 1596.99  4799.2 1594.85  4829.3 1589.26  4896.7 1587.46  4954.8 1584.83
  4959.8 1586.17  4969.7 1585.48  4979.7 1583.22  4996.8 1573.78  4999.5 1573.28
  5002.8 1573.78  5029.8 1580.10  5060.3 1581.01  5089.0 1583.66  5110.0 1587.35
  5181.1 1588.23  5259.7 1589.53  5487.4 1589.61  5551.2 1592.82  5607.2 1592.94
  5635.8 1594.70  5643.6 1596.39  5693.0 1598.28  5792.0 1599.70  5847.8 1598.46
#Mann=6,-1,0
  4396.8    0.05       0  4896.7    0.16       0  4996.8    0.07       0
  5002.8    0.16       0  5060.3     0.1       0  5181.1    0.05       0
Bank Sta=4996.8,5002.8
Exp/Cntr=0.3,0.1

Type RM Length L Ch R = 1,877,467,467,467
BEGIN DESCRIPTION:
Mapping XS 1b44fb73
END DESCRIPTION:
XS GIS Cut Line= 5
      2760637.74     10048642.79      2760696.34     10048106.74
      2760372.99     10047891.90      2760329.59     10047666.21
      2759867.38     10047340.71
#Sta/Elev= 30
  4388.6 1624.22  4533.4 1617.04  4626.3 1610.37  4721.0 1600.64  4749.8 1599.44
  4799.2 1591.53  4860.5 1589.05  4942.8 1588.29  4963.8 1586.55  4972.9 1579.93
  4978.9 1580.28  4985.3 1573.09  4996.9 1571.12  4999.7 1570.62  5002.9 1571.12
  5009.0 1574.94  5015.0 1573.26  5030.0 1580.31  5036.0 1579.45  5045.0 1582.94
  5066.1 1584.97  5144.2 1588.99  5250.5 1589.61  5385.5 1588.46  5476.5 1590.13
  5549.6 1591.44  5742.9 1589.63  5914.2 1592.98  5957.7 1597.36  6111.2 1599.32
#Mann=7,-1,0
  4388.6     0.1       0  4626.3    0.05       0  4799.2    0.16       0
  4996.9    0.07       0  5002.9    0.16       0  5250.5     0.1       0
  5476.5    0.05       0
Bank Sta=4996.9,5002.9
Exp/Cntr=0.3,0.1

Type RM Length L Ch R = 1,410,277,277,277
BEGIN DESCRIPTION:
Mapping XS fcfd81a3
END DESCRIPTION:
XS GIS Cut Line= 3
      2760852.58     10048647.06      2760744.08     10047707.44
      2759934.63     10047269.07
#Sta/Elev= 30
  4154.4 1620.78  4260.0 1616.88  4564.5 1597.99  4654.1 1590.00  4761.9 1588.24
  4791.9 1574.84  4973.1 1575.05  5003.3 1568.07  5018.4 1579.33  5063.7 1588.94
  5142.7 1592.64  5197.2 1593.96  5202.9 1586.67  5219.1 1584.04  5224.8 1578.84
  5238.7 1578.09  5374.1 1576.88  5394.1 1576.50  5426.2 1569.21  5444.8 1567.63
  5447.6 1567.13  5450.8 1567.63  5601.4 1575.96  5623.3 1573.37  5800.4 1584.23
  5823.1 1591.86  5852.5 1595.02  5858.2 1601.18  5868.6 1601.93  6020.8 1599.01
#Mann=10,-1,0
  4154.4     0.1       0  4260.0    0.05       0  4564.5     0.1       0
  4654.1    0.16       0  5142.7     0.1       0  5238.7    0.05       0
  5374.1     0.1       0  5426.2    0.05       0  5444.8    0.07       0
  5450.8    0.05       0
Bank Sta=5444.8,5450.8
Exp/Cntr=0.3,0.1

Type RM Length L Ch R = 1,133,0,0,0
BEGIN DESCRIPTION:
UNT 0008 IN HEWA 1.0
END DESCRIPTION:
XS GIS Cut Line= 4
      2761171.60     10048718.72      2761045.73     10047774.71
      2760850.42     10047496.94      2759901.66     10047215.34
#Sta/Elev= 30
  3996.9 1616.78  4046.8 1614.54  4067.7 1613.33  4442.3 1598.48  4723.4 1588.63
  4771.2 1586.21  4879.6 1583.79  4909.9 1574.79  4975.8 1575.73  5002.4 1565.47
  5005.2 1564.97  5008.4 1565.47  5026.3 1577.79  5234.6 1590.47  5389.0 1587.86
  5447.3 1572.00  5567.8 1578.30  5637.1 1568.27  5749.8 1570.33  5781.1 1576.60
  5822.9 1570.42  5906.3 1572.00  6018.2 1589.78  6023.4 1584.86  6051.4 1586.73
  6056.6 1577.05  6089.9 1587.41  6095.1 1581.97  6114.9 1598.08  6278.5 1599.90
#Mann=9,-1,0
  3996.9     0.1       0  4046.8    0.05       0  4067.7    0.16       0
  4442.3     0.1       0  4723.4    0.16       0  4771.2     0.1       0
  5002.4    0.07       0  5008.4     0.1       0  5567.8    0.05       0
Bank Sta=5002.4,5008.4
Exp/Cntr=0.3,0.1

Chan Stop Cuts=-1