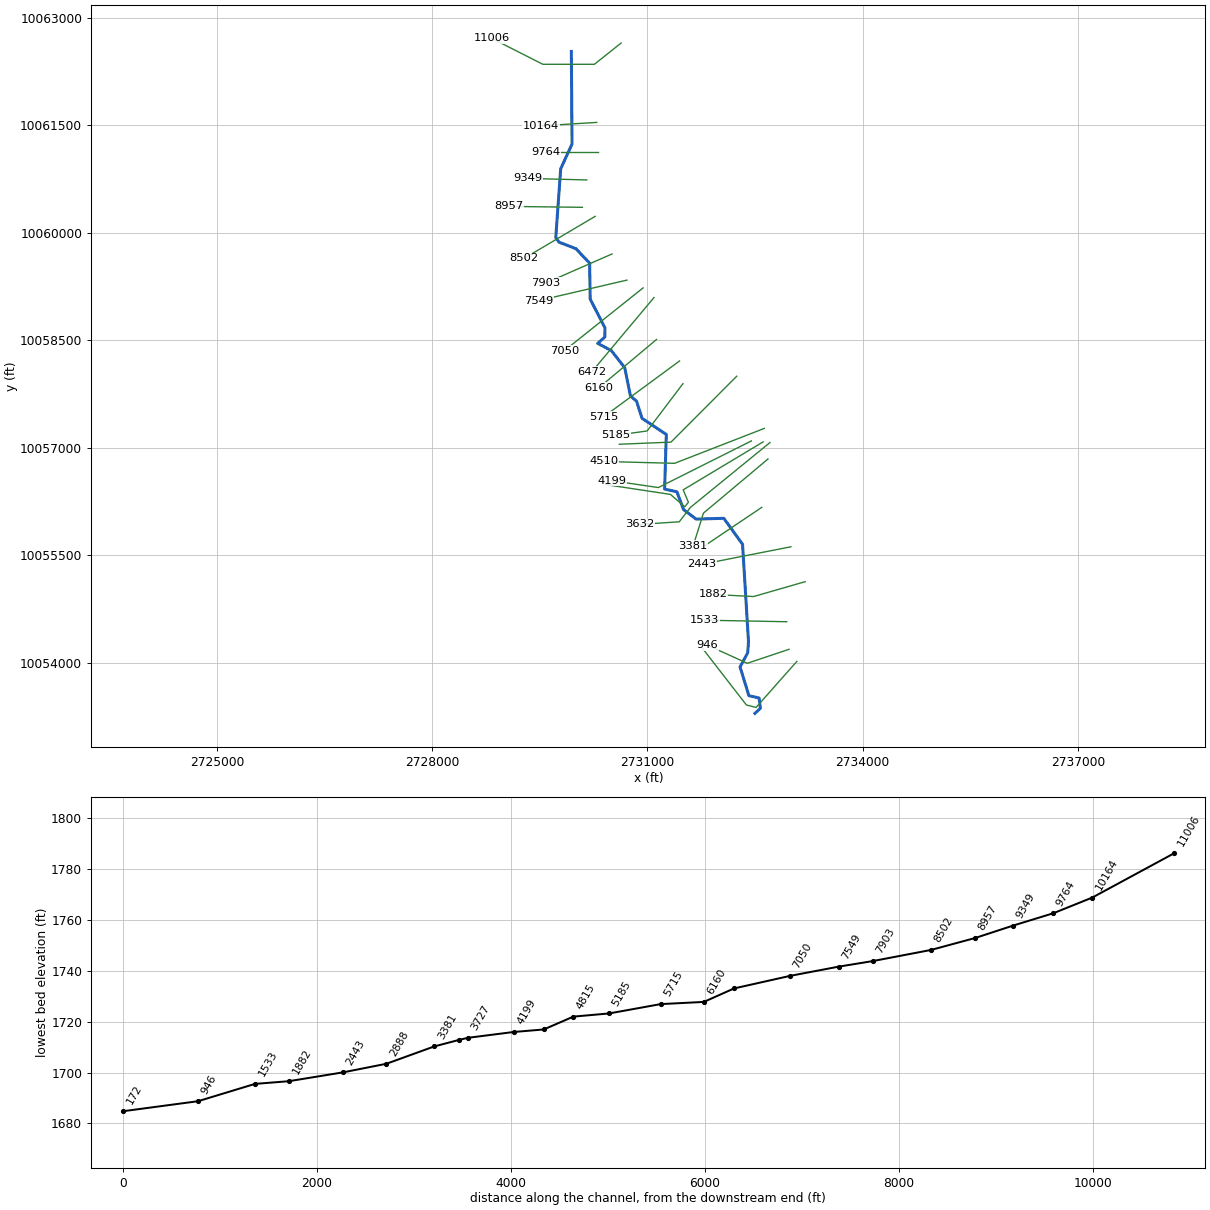
--- UNT 0009 IN HEWA.prj (project) ---

Proj Title=UNT 0009 IN HEWA Base Level Engineering
Current Plan=p01
Default Exp/Contr=0.3,0.1
English Units
Geom File=g01
Flow File=f01
Plan File=p01
Y Axis Title=Elevation
X Axis Title(PF)=Main Channel Distance
X Axis Title(XS)=Station
BEGIN DESCRIPTION:
UNT 0009 IN HEWA
END DESCRIPTION:
DSS Export Rating Curves= 0
DSS Export Rating Curve Sorted= 0
DSS Export Volume Flow Curves= 0
DXF OffsetX= 0
DXF OffsetY= 0
DXF ScaleX= 1
DXF ScaleY= 10

--- UNT 0009 IN HEWA.p01 (plan) ---

Plan Title=Multiple Run
Short Identifier=Multiple
Geom File=g01
Flow File=f01
Subcritical Flow
K Sum by GR= 0
Std Step Tol= 0.01
Critical Tol= 0.01
Num of Std Step Trials= 20
Max Error Tol= 0.3
Flow Tol Ratio= 0.001
Split Flow NTrial= 30
Split Flow Tol= 0.02
Split Flow Ratio= 0.02
Log Output Level= 0
Friction Slope Method= 1
Unsteady Friction Slope Method= 2
Unsteady Bridges Friction Slope Method= 1
Parabolic Critical Depth
Global Vel Dist=  1 , 1 , 1
Global Log Level= 0
CheckData=True
Encroach Param= -1, 0, 0, 0
BEGIN DESCRIPTION:
Multiple Run
END DESCRIPTION:

--- UNT 0009 IN HEWA.f01 (steady flow) ---

Flow Title=Multiple
Program Version=4.10
Number of Profiles= 7
Profile Names=10-year,25-year,50-year,1pct_min,100-year,1pct_plu,500-year
River Rch & RM=UNT 0009 IN HEWA,Reach-1         ,11006
     794    1156    1472    1372    1856    2510    2964
River Rch & RM=UNT 0009 IN HEWA,Reach-1         ,4510
    1202    1784    2300    2168    2931    3964    4786
Boundary for River Rch & Prof#=UNT 0009 IN HEWA,Reach-1         , 1
Up Type= 0
Dn Type= 3
Dn Slope=0.005
Boundary for River Rch & Prof#=UNT 0009 IN HEWA,Reach-1         , 2
Up Type= 0
Dn Type= 3
Dn Slope=0.005
Boundary for River Rch & Prof#=UNT 0009 IN HEWA,Reach-1         , 3
Up Type= 0
Dn Type= 3
Dn Slope=0.005
Boundary for River Rch & Prof#=UNT 0009 IN HEWA,Reach-1         , 4
Up Type= 0
Dn Type= 3
Dn Slope=0.005
Boundary for River Rch & Prof#=UNT 0009 IN HEWA,Reach-1         , 5
Up Type= 0
Dn Type= 3
Dn Slope=0.005
Boundary for River Rch & Prof#=UNT 0009 IN HEWA,Reach-1         , 6
Up Type= 0
Dn Type= 3
Dn Slope=0.005
Boundary for River Rch & Prof#=UNT 0009 IN HEWA,Reach-1         , 7
Up Type= 0
Dn Type= 3
Dn Slope=0.005
DSS Import GetInterval= 0
DSS Import GetPeak= 0
DSS Import FillOption= 0

--- UNT 0009 IN HEWA.g01 (geometry) ---

Geom Title=Existing Conditions
Program Version=4.10

River Reach=UNT 0009 IN HEWA,Reach-1
Reach XY= 30
      2729938.35     10062531.16      2729947.82     10061238.44
      2729789.82     10060893.22      2729721.13     10059934.77
      2729765.69     10059869.06      2730001.18     10059778.91
       2730193.4     10059576.35      2730201.07     10059074.92
      2730406.81     10058673.44      2730405.06     10058544.94
      2730304.93     10058456.98      2730495.89     10058356.33
      2730682.92     10058116.33       2730762.5     10057724.17
      2730848.17     10057648.74      2730923.95      10057411.2
      2731262.27     10057186.46      2731238.89     10056423.59
      2731410.52     10056385.81      2731502.74     10056137.25
      2731678.65     10056004.63      2732064.53     10056015.55
      2732325.65     10055652.57      2732408.56     10054291.83
       2732397.6     10054139.31       2732290.7     10053941.86
      2732413.93     10053540.96      2732556.23     10053507.71
      2732574.16     10053364.53      2732498.47     10053293.73

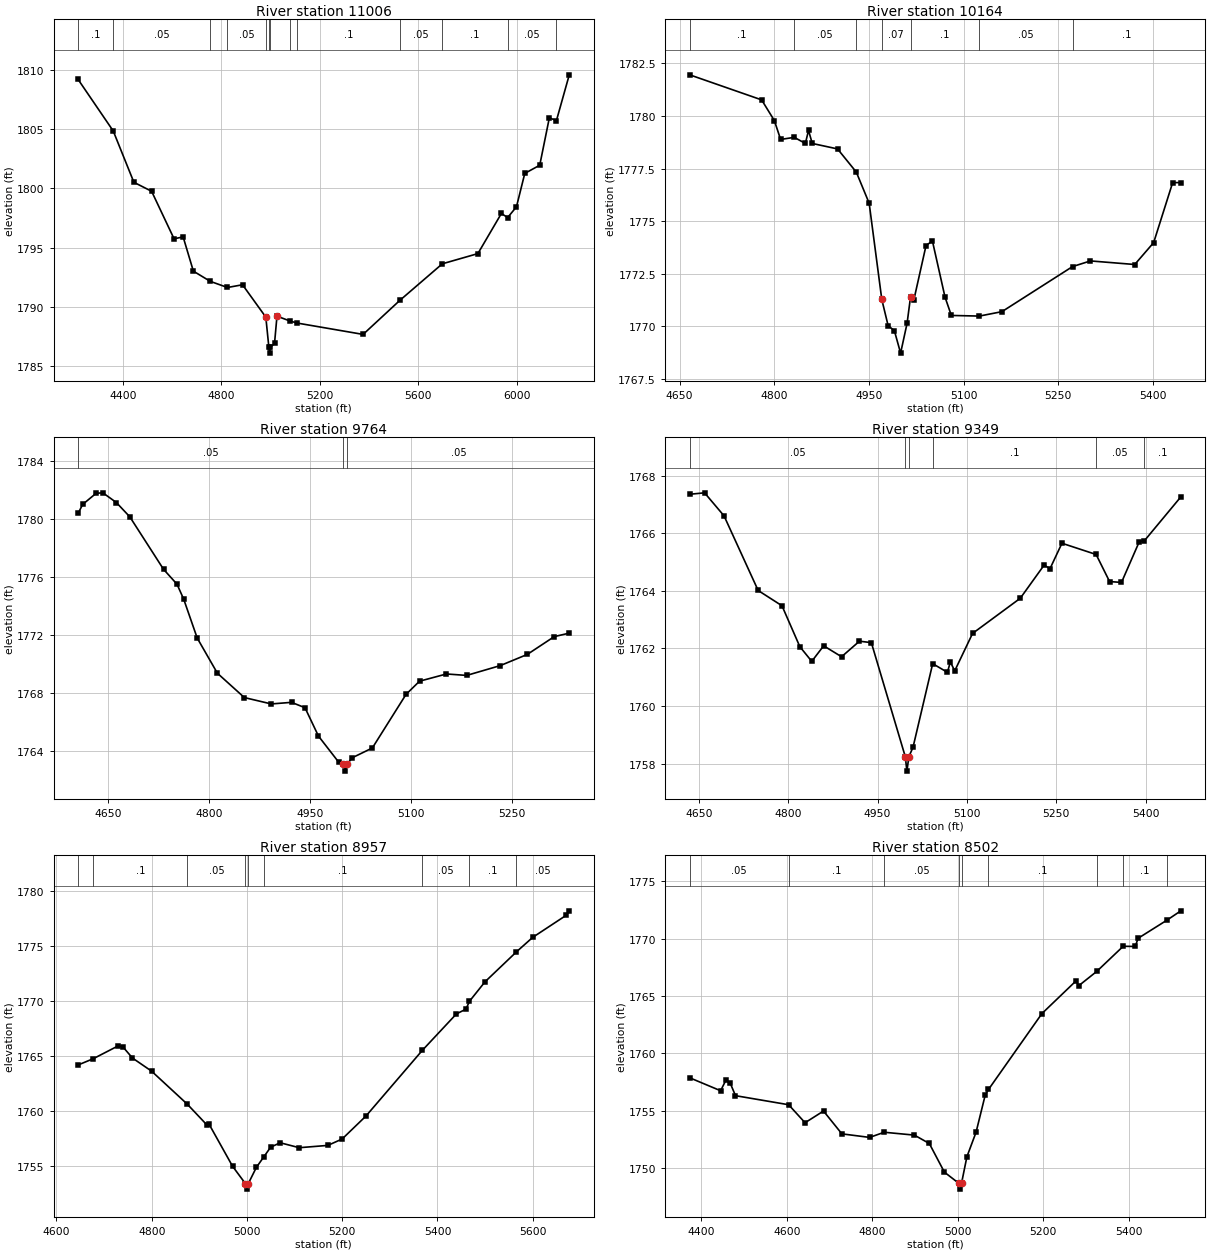
Type RM Length L Ch R = 1 ,11006   ,842,842,842
BEGIN DESCRIPTION:
UNT 0009 IN HEWA 22.0
END DESCRIPTION:
XS GIS Cut Line= 4
       2730632.8     10062648.34      2730259.52     10062351.01
      2729541.21     10062351.01      2728827.25     10062713.42
#Sta/Elev= 30
  4217.5 1809.19  4360.3 1804.84  4444.2 1800.51  4516.3 1799.75  4607.5 1795.74
  4644.4  1795.9    4686 1793.01  4754.5 1792.15  4824.5 1791.63  4885.8 1791.86
  4980.4 1789.13  4992.8 1786.59  4995.5 1786.09  4998.8 1786.59  5015.8 1786.91
  5025.8 1789.21    5079  1788.8  5107.3 1788.63  5375.8 1787.67    5525 1790.54
  5697.8 1793.63  5842.3 1794.49  5937.9 1797.88  5963.2 1797.53  5999.1 1798.44
  6032.9 1801.26  6093.7 1801.95  6132.7 1805.95  6161.6 1805.72  6213.7 1809.58
#Mann= 13 ,-1 , 0
  4217.5      .1       0  4360.3     .05       0  4754.5      .1       0
  4824.5     .05       0  4980.4      .1       0  4992.8     .07       0
  4998.8      .1       0    5079     .05       0  5107.3      .1       0
    5525     .05       0  5697.8      .1       0  5963.2     .05       0
  6161.6      .1       0
Bank Sta=4980.4,5025.8
XS Rating Curve= 0 ,0
Exp/Cntr=0.3,0.1

Type RM Length L Ch R = 1 ,10164   ,400,400,400
BEGIN DESCRIPTION:
UNT 0009 IN HEWA 21.0
END DESCRIPTION:
XS GIS Cut Line= 2
      2730292.29     10061540.23      2729515.46     10061492.49
#Sta/Elev= 30
  4665.9 1781.95  4779.9 1780.76    4800 1779.78    4810 1778.88  4831.6 1778.98
  4849.2 1778.69  4854.2 1779.31  4860.1 1778.69  4900.2 1778.43  4929.9 1777.33
  4950.3 1775.85  4970.3 1771.28  4980.3 1770.04  4990.3 1769.79  5000.1 1768.73
  5010.4 1770.15  5015.8 1771.39  5020.9 1771.23  5040.4 1773.84  5050.5 1774.06
  5070.5 1771.39  5080.5 1770.52  5124.9 1770.49  5160.7  1770.7  5272.5 1772.84
  5300.9 1773.11  5371.1 1772.94  5401.1 1773.98  5431.2 1776.83  5444.2 1776.83
#Mann= 7 ,-1 , 0
  4665.9      .1       0  4831.6     .05       0  4929.9      .1       0
  4970.3     .07       0  5015.8      .1       0  5124.9     .05       0
  5272.5      .1       0
Bank Sta=4970.3,5015.8
XS Rating Curve= 0 ,0
Exp/Cntr=0.3,0.1

Type RM Length L Ch R = 1 ,9764    ,415,415,415
BEGIN DESCRIPTION:
UNT 0009 IN HEWA 20.0
END DESCRIPTION:
XS GIS Cut Line= 2
       2730305.3      10061127.9       2729576.2      10061127.9
#Sta/Elev= 30
  4605.5 1780.39  4612.3 1781.01  4632.3 1781.78  4642.3 1781.81  4662.3 1781.14
  4682.3 1780.15  4732.3 1776.53  4752.3  1775.5  4762.3 1774.46  4782.3 1771.78
  4812.3 1769.35  4852.3 1767.67  4892.3 1767.23  4922.3 1767.34  4942.3 1766.97
  4962.3 1765.01  4992.3 1763.21  4999.3 1763.09  5002.1 1762.59  5005.3 1763.09
  5012.3 1763.51  5042.3 1764.19  5092.3 1767.89  5112.3  1768.8  5152.3  1769.3
  5182.3  1769.2  5232.3 1769.88  5272.3 1770.65  5312.3 1771.88  5334.6 1772.12
#Mann= 3 ,-1 , 0
  4605.5     .05       0  4999.3     .04       0  5005.3     .05       0
Bank Sta=4999.3,5005.3
XS Rating Curve= 0 ,0
Exp/Cntr=0.3,0.1

Type RM Length L Ch R = 1 ,9349    ,392,392,392
BEGIN DESCRIPTION:
UNT 0009 IN HEWA 19.0
END DESCRIPTION:
XS GIS Cut Line= 2
      2730153.43     10060737.28      2729328.82     10060758.98
#Sta/Elev= 30
  4634.4 1767.35  4659.4  1767.4  4692.1  1766.6  4749.4 1764.01  4789.4 1763.48
  4819.4 1762.06  4839.4 1761.55  4859.4 1762.09  4889.5 1761.71  4919.5 1762.25
  4939.5  1762.2  4996.5 1758.24  4999.2 1757.74  5002.5 1758.24  5009.5 1758.57
  5042.5 1761.47  5067.2 1761.17  5072.2 1761.53  5079.5 1761.22  5109.5 1762.52
  5189.6 1763.74  5229.6 1764.89  5239.6 1764.77  5259.6 1765.65    5317 1765.26
  5339.6 1764.32  5359.6 1764.29  5389.6 1765.71  5397.8 1765.73  5459.3 1767.26
#Mann= 6 ,-1 , 0
  4634.4     .05       0  4996.5    .035       0  5002.5     .05       0
  5042.5      .1       0    5317     .05       0  5397.8      .1       0
Bank Sta=4996.5,5002.5
XS Rating Curve= 0 ,0
Exp/Cntr=0.3,0.1

Type RM Length L Ch R = 1 ,8957    ,455,455,455
BEGIN DESCRIPTION:
UNT 0009 IN HEWA 18.0
END DESCRIPTION:
XS GIS Cut Line= 2
       2730092.7     10060355.33      2729061.58     10060368.33
#Sta/Elev= 30
  4645.5 1764.15  4677.3 1764.72  4729.7 1765.89  4739.7 1765.79  4759.7 1764.78
  4799.7 1763.59  4874.8 1760.58  4915.1 1758.73  4920.1 1758.79  4969.8 1754.93
  4996.8 1753.35  4999.5 1752.85  5002.8 1753.35  5019.8 1754.83  5035.1 1755.77
  5049.8 1756.67  5069.8 1757.07  5109.8 1756.62  5169.8 1756.83  5199.8 1757.41
  5249.8  1759.5  5368.4 1765.49  5439.8  1768.8  5459.8 1769.23  5467.2 1769.95
  5499.8 1771.72  5565.9 1774.45  5599.8 1775.76  5669.8 1777.76  5676.7 1778.18
#Mann= 9 ,-1 , 0
  4645.5     .05       0  4677.3      .1       0  4874.8     .05       0
  4996.8    .035       0  5002.8     .05       0  5035.1      .1       0
  5368.4     .05       0  5467.2      .1       0  5565.9     .05       0
Bank Sta=4996.8,5002.8
XS Rating Curve= 0 ,0
Exp/Cntr=0.3,0.1

Type RM Length L Ch R = 1 ,8502    ,599,599,599
BEGIN DESCRIPTION:
UNT 0009 IN HEWA 17.0
END DESCRIPTION:
XS GIS Cut Line= 2
      2730270.64     10060229.47      2729282.21     10059644.22
#Sta/Elev= 30
  4372.9 1757.87  4445.2 1756.74  4457.7 1757.67  4467.5 1757.42    4480 1756.31
  4604.3 1755.52  4642.7 1753.95  4685.9 1754.97  4728.8 1752.98  4793.8 1752.67
  4827.8 1753.12  4898.4 1752.87  4933.3 1752.14  4968.6 1749.64  5002.6 1748.66
  5005.4 1748.16  5008.6 1748.66  5021.2 1750.98  5042.7 1753.13  5064.1 1756.37
  5071.7 1756.85  5196.7 1763.47  5276.7 1766.33  5282.5 1765.89    5325 1767.15
  5386.8 1769.34  5415.1 1769.32  5421.4 1770.03  5488.4  1771.6  5521.6 1772.43
#Mann= 9 ,-1 , 0
  4372.9     .05       0  4604.3      .1       0  4827.8     .05       0
  5002.6    .035       0  5008.6     .05       0  5071.7      .1       0
    5325     .05       0  5386.8      .1       0  5488.4     .05       0
Bank Sta=5002.6,5008.6
XS Rating Curve= 0 ,0
Exp/Cntr=0.3,0.1

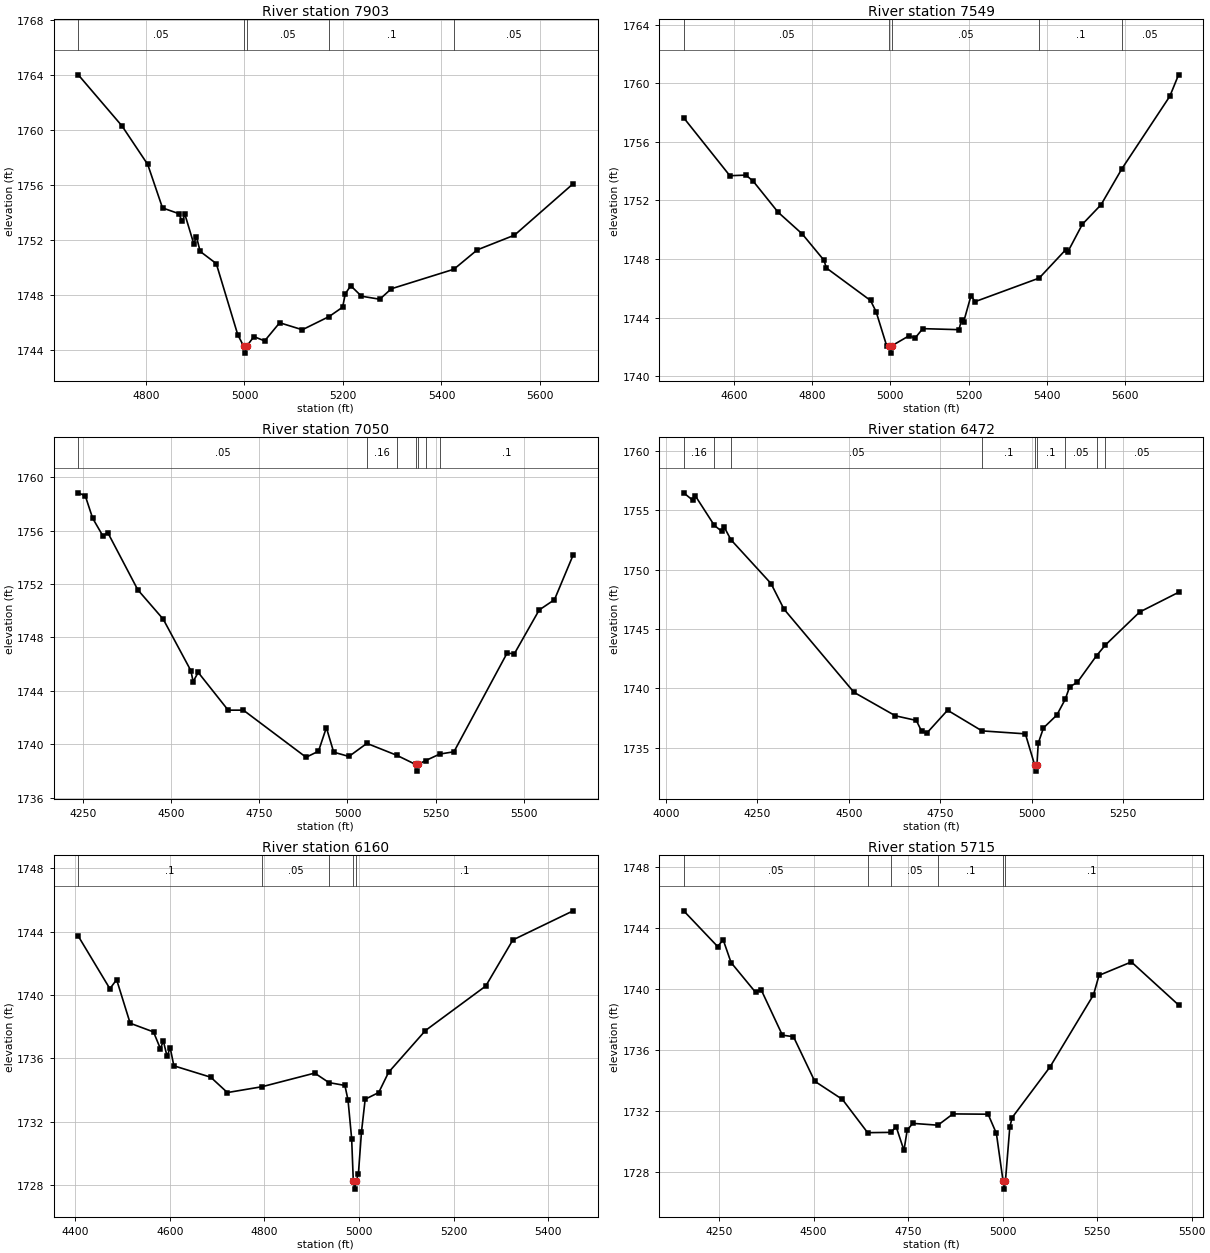
Type RM Length L Ch R = 1 ,7903    ,354,354,354
BEGIN DESCRIPTION:
UNT 0009 IN HEWA 16.0
END DESCRIPTION:
XS GIS Cut Line= 2
      2730505.02      10059704.3      2729584.87     10059300.65
#Sta/Elev= 30
  4662.6 1764.03  4751.4 1760.31  4803.6 1757.51  4833.6 1754.35  4866.3 1753.94
  4873.7 1753.38  4879.1 1753.88  4897.1 1751.74  4902.5 1752.26    4910 1751.19
  4942.8  1750.3  4986.4 1745.13  4998.4 1744.29  5001.2 1743.79  5004.4 1744.29
  5019.2 1744.99    5041 1744.68  5071.5    1746  5117.5 1745.49  5171.9 1746.45
  5199.3 1747.13  5204.8 1748.11  5215.8 1748.69  5237.6 1747.93  5274.8 1747.71
  5298.2 1748.47  5425.2 1749.89  5472.7  1751.3  5548.3 1752.37  5667.4 1756.11
#Mann= 5 ,-1 , 0
  4662.6     .05       0  4998.4    .035       0  5004.4     .05       0
  5171.9      .1       0  5425.2     .05       0
Bank Sta=4998.4,5004.4
XS Rating Curve= 0 ,0
Exp/Cntr=0.3,0.1

Type RM Length L Ch R = 1 ,7549    ,499,499,499
BEGIN DESCRIPTION:
UNT 0009 IN HEWA 15.0
END DESCRIPTION:
XS GIS Cut Line= 2
       2730713.3      10059339.7      2729482.11     10059053.58
#Sta/Elev= 30
  4472.3 1757.64  4590.2 1753.69  4631.3 1753.73    4650 1753.31  4713.4  1751.2
    4775 1749.72  4830.7 1747.92  4836.6  1747.4  4949.5 1745.18  4963.7 1744.42
  4990.6  1742.1  4997.9 1742.09  5000.6 1741.59  5003.9 1742.09    5049 1742.79
  5062.5 1742.59    5083 1743.26  5175.4 1743.19    5182 1743.86  5187.1  1743.7
  5206.2 1745.51  5216.5  1745.1  5380.4 1746.71    5448 1748.64  5453.1 1748.48
  5490.6 1750.38  5538.3 1751.71  5591.7 1754.17    5714 1759.11  5736.3 1760.57
#Mann= 5 ,-1 , 0
  4472.3     .05       0  4997.9    .035       0  5003.9     .05       0
  5380.4      .1       0  5591.7     .05       0
Bank Sta=4997.9,5003.9
XS Rating Curve= 0 ,0
Exp/Cntr=0.3,0.1

Type RM Length L Ch R = 1 ,7050    ,578,578,578
BEGIN DESCRIPTION:
UNT 0009 IN HEWA 14.0
END DESCRIPTION:
XS GIS Cut Line= 2
        2730939.     10059231.18      2729842.21     10058355.48
#Sta/Elev= 30
  4236.5 1758.84  4256.4 1758.61  4277.2 1756.94    4306 1755.62  4320.5 1755.84
  4405.3 1751.57  4477.4 1749.37  4555.8 1745.51  4562.2 1744.69  4576.6 1745.38
  4661.5 1742.55  4704.7 1742.55  4882.5 1739.02  4917.7 1739.47  4940.1 1741.24
  4960.9  1739.4  5004.1 1739.08    5055 1740.06  5139.6 1739.17  5193.3 1738.48
    5196 1737.98  5199.3 1738.48  5221.7 1738.77  5261.7 1739.26  5301.9 1739.43
  5452.5 1746.82  5473.3 1746.78  5543.7 1750.06    5587 1750.83    5640 1754.18
#Mann= 7 ,-1 , 0
  4236.5     .05       0    5055     .16       0  5139.6     .05       0
  5193.3    .035       0  5199.3     .05       0  5221.7     .16       0
  5261.7      .1       0
Bank Sta=5193.3,5199.3
XS Rating Curve= 0 ,0
Exp/Cntr=0.3,0.1

Type RM Length L Ch R = 1 ,6472    ,312,312,312
BEGIN DESCRIPTION:
UNT 0009 IN HEWA 13.0
END DESCRIPTION:
XS GIS Cut Line= 2
      2731090.97     10059096.69      2730223.18     10058059.68
#Sta/Elev= 30
  4048.6 1756.48  4073.9 1755.84  4080.5 1756.22  4132.3 1753.74    4152 1753.25
  4158.5 1753.64  4177.6 1752.53  4287.2 1748.84  4322.5 1746.69  4513.8 1739.68
    4627  1737.7  4684.2 1737.31  4698.5 1736.41  4712.8 1736.24  4769.6 1738.17
  4863.6 1736.43  4982.2 1736.18  5007.8 1733.54  5010.6 1733.04  5013.8 1733.54
  5017.4 1735.39  5031.7 1736.68  5068.1 1737.76    5091 1739.08  5103.2 1740.14
    5124 1740.51  5176.6 1742.76  5200.5 1743.65  5294.5 1746.44  5400.8  1748.1
#Mann= 9 ,-1 , 0
  4048.6     .16       0  4132.3      .1       0  4177.6     .05       0
  4863.6      .1       0  5007.8     .07       0  5013.8      .1       0
    5091     .05       0  5176.6      .1       0  5200.5     .05       0
Bank Sta=5007.8,5013.8
XS Rating Curve= 0 ,0
Exp/Cntr=0.3,0.1

Type RM Length L Ch R = 1 ,6160    ,445,445,445
BEGIN DESCRIPTION:
UNT 0009 IN HEWA 12.0
END DESCRIPTION:
XS GIS Cut Line= 2
      2731125.69     10058510.74      2730323.53     10057838.65
#Sta/Elev= 30
  4406.4 1743.72  4473.2  1740.4  4487.5 1740.97  4516.1 1738.22  4565.5 1737.67
  4579.9 1736.62  4586.4 1737.09  4594.2 1736.12  4600.7 1736.68  4608.5 1735.53
  4686.5 1734.81  4721.7 1733.84  4795.1 1734.21  4906.4 1735.07  4936.4 1734.47
  4970.2 1734.29  4976.8 1733.37  4984.5 1730.93    4988 1728.24  4990.8 1727.74
    4994 1728.24  4998.8 1728.72  5005.3 1731.36  5013.1 1733.42  5041.7 1733.84
  5062.6 1735.12  5140.6 1737.76  5268.1 1740.57  5325.4 1743.48  5452.9 1745.32
#Mann= 5 ,-1 , 0
  4406.4      .1       0  4795.1     .05       0  4936.4      .1       0
    4988     .07       0    4994      .1       0
Bank Sta=4988,4994
XS Rating Curve= 0 ,0
Exp/Cntr=0.3,0.1

Type RM Length L Ch R = 1 ,5715    ,530,530,530
BEGIN DESCRIPTION:
UNT 0009 IN HEWA 11.0
END DESCRIPTION:
XS GIS Cut Line= 2
      2731446.85     10058211.24      2730392.84     10057434.83
#Sta/Elev= 30
  4156.3 1745.12  4246.1 1742.78  4260.8 1743.22  4281.6 1741.73  4346.4 1739.78
    4361 1739.96  4417.4 1736.97  4446.7 1736.87    4503 1733.95  4576.2 1732.76
  4642.9 1730.58  4704.8  1730.6  4718.2 1730.98    4739 1729.42  4747.5 1730.74
  4762.1 1731.19  4828.8 1731.07  4868.6 1731.81  4961.6 1731.79  4983.5 1730.53
  5001.3 1727.38  5004.1 1726.88  5007.3 1727.38    5019 1730.95  5025.2 1731.57
  5125.4 1734.89  5240.3 1739.61    5255 1740.89  5340.6 1741.77  5465.4 1738.95
#Mann= 6 ,-1 , 0
  4156.3     .05       0  4642.9      .1       0  4704.8     .05       0
  4828.8      .1       0  5001.3     .07       0  5007.3      .1       0
Bank Sta=5001.3,5007.3
XS Rating Curve= 0 ,0
Exp/Cntr=0.3,0.1

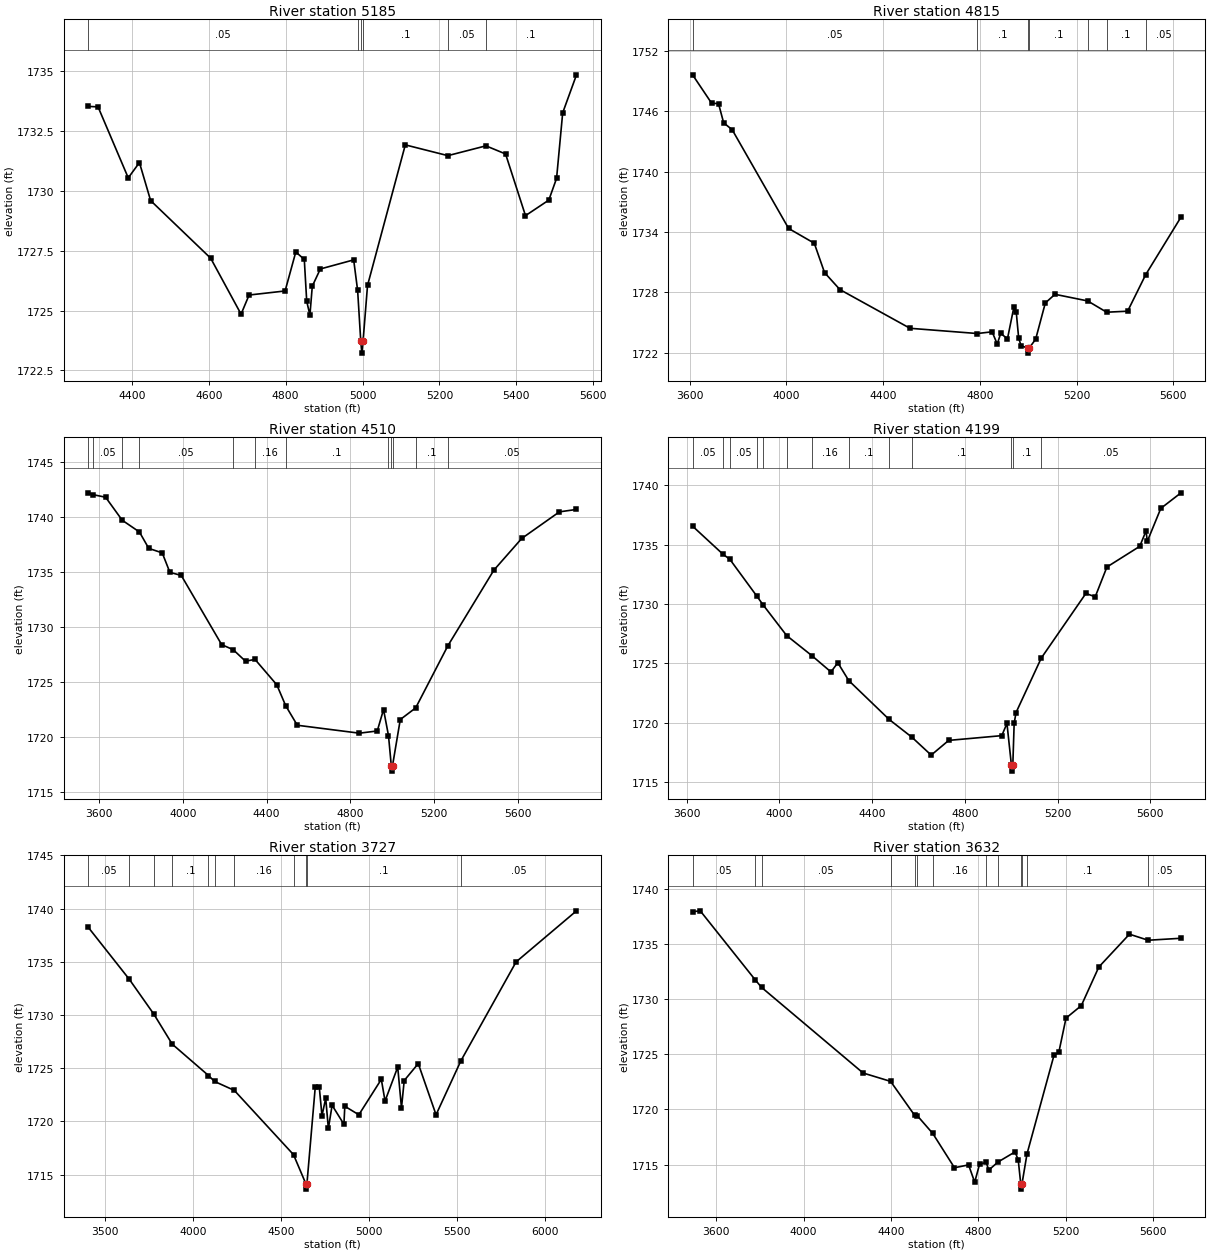
Type RM Length L Ch R = 1 ,5185    ,370,370,370
BEGIN DESCRIPTION:
UNT 0009 IN HEWA 10.0
END DESCRIPTION:
XS GIS Cut Line= 3
      2731494.59     10057894.41      2730995.45     10057234.67
      2730557.12     10057173.91
#Sta/Elev= 30
  4286.4 1733.54  4312.3 1733.52  4390.8 1730.55  4419.9 1731.19    4449  1729.6
  4605.1 1727.19  4684.1 1724.85    4705 1725.65  4798.6 1725.82  4826.4 1727.45
  4848.5 1727.14  4854.8 1725.39  4863.1 1724.81  4869.3 1726.02  4890.2 1726.74
  4976.9 1727.12  4987.2 1725.84  4995.3 1723.72  4998.1 1723.22  5001.3 1723.72
  5012.9 1726.05  5111.1 1731.93  5221.8 1731.48  5320.8 1731.89  5371.8 1731.55
  5423.6 1728.97  5484.2 1729.62  5504.4 1730.53  5520.3 1733.27  5556.2 1734.86
#Mann= 6 ,-1 , 0
  4286.4     .05       0  4987.2      .1       0  4995.3     .07       0
  5001.3      .1       0  5221.8     .05       0  5320.8      .1       0
Bank Sta=4995.3,5001.3
XS Rating Curve= 0 ,0
Exp/Cntr=0.3,0.1

Type RM Length L Ch R = 1 ,4815    ,305,305,305
BEGIN DESCRIPTION:
UNT 0009 IN HEWA 9.0
END DESCRIPTION:
XS GIS Cut Line= 3
       2732244.9     10057998.87      2731327.58     10057078.79
      2730607.93     10057049.16
#Sta/Elev= 30
    3612 1749.64  3690.9 1746.81  3719.2 1746.78  3740.4 1744.87  3775.7 1744.18
  4009.1 1734.36  4115.2 1732.89  4157.6 1729.97  4221.2 1728.28  4511.1 1724.43
  4789.1 1723.91  4850.5 1724.08  4871.8 1722.86  4885.9 1723.92    4914 1723.39
  4940.4 1726.52  4950.4 1726.01  4960.4 1723.44  4970.4  1722.7  4997.4 1722.46
  5000.2 1721.96  5003.4 1722.46  5030.5 1723.34  5070.5 1726.95  5110.5 1727.81
  5245.7 1727.15  5324.1 1726.03  5410.8 1726.13  5485.7 1729.77  5631.5 1735.49
#Mann= 7 ,-1 , 0
    3612     .05       0  4789.1      .1       0  4997.4     .07       0
  5003.4      .1       0  5245.7     .05       0  5324.1      .1       0
  5485.7     .05       0
Bank Sta=4997.4,5003.4
XS Rating Curve= 0 ,0
Exp/Cntr=0.3,0.1

Type RM Length L Ch R = 1 ,4510    ,311,311,311
BEGIN DESCRIPTION:
UNT 0009 IN HEWA 8.0
END DESCRIPTION:
XS GIS Cut Line= 3
      2732628.56     10057270.26      2731378.35     10056783.11
      2730386.75     10056808.98
#Sta/Elev= 30
  3547.3 1742.22  3571.9 1742.05    3631 1741.82  3710.3 1739.73  3792.6 1738.66
  3837.2 1737.17  3901.6 1736.76  3938.1 1734.99  3992.5 1734.71  4185.5 1728.42
  4240.6 1727.96  4299.6 1726.91  4344.7 1727.08  4448.9 1724.77  4491.4 1722.87
    4547 1721.09  4843.3 1720.37    4929 1720.57    4959 1722.52  4982.7 1720.15
    4996 1717.42  4998.7 1716.92    5002 1717.42    5039 1721.61  5112.6 1722.67
  5266.5 1728.32  5486.1 1735.19  5619.2 1738.07  5799.3 1740.49    5881 1740.71
#Mann= 12 ,-1 , 0
  3547.3      .1       0  3571.9     .05       0  3710.3      .1       0
  3792.6     .05       0  4240.6      .1       0  4344.7     .16       0
  4491.4      .1       0  4982.7     .16       0    4996     .07       0
    5002     .16       0  5112.6      .1       0  5266.5     .05       0
Bank Sta=4996,5002
XS Rating Curve= 0 ,0
Exp/Cntr=0.3,0.1

Type RM Length L Ch R = 1 ,4199    ,472,472,472
BEGIN DESCRIPTION:
Mapping XS 242202d5
END DESCRIPTION:
XS GIS Cut Line= 3
      2732448.74     10057095.65      2731151.83     10056444.92
       2730502.3      10056540.3
#Sta/Elev= 30
  3625.2 1736.56  3756.1  1734.2  3785.9 1733.77    3903 1730.65  3929.4 1729.93
  4031.2 1727.34  4139.3 1725.66  4222.2 1724.28    4252 1725.05  4299.1 1723.55
  4473.1 1720.28  4571.4 1718.78  4654.8 1717.27  4730.4 1718.51  4959.4 1718.91
  4981.7 1719.94    5001 1716.42  5003.8 1715.92    5007 1716.42  5012.8 1719.94
  5020.8 1720.85  5129.9 1725.45  5322.2 1730.89  5362.6 1730.61  5413.1 1733.12
  5554.6 1734.86  5582.1 1736.17  5587.1 1735.27  5645.6 1738.06  5732.7 1739.37
#Mann= 13 ,-1 , 0
  3625.2     .05       0  3756.1      .1       0  3785.9     .05       0
    3903      .1       0  3929.4     .05       0  4031.2      .1       0
  4139.3     .16       0  4299.1      .1       0  4473.1     .16       0
  4571.4      .1       0    5001     .07       0    5007      .1       0
  5129.9     .05       0
Bank Sta=5001,5007
XS Rating Curve= 0 ,0
Exp/Cntr=0.3,0.1

Type RM Length L Ch R = 1 ,3727    ,95,95,95
BEGIN DESCRIPTION:
Mapping XS bad8dc51
END DESCRIPTION:
XS GIS Cut Line= 6
      2732612.56       10057082.      2731497.66     10056413.07
      2731570.47     10056240.15      2731520.41     10056176.44
      2731320.19     10056349.36      2730419.18     10056485.88
#Sta/Elev= 30
  3402.5 1738.26  3636.9 1733.35    3777 1730.06  3880.7 1727.26  4086.8 1724.31
  4121.6 1723.75  4233.7 1722.91  4570.1 1716.87  4640.4 1714.13  4643.2 1713.63
  4646.4 1714.13  4693.8 1723.24  4716.6 1723.21  4731.9 1720.53  4753.1 1722.17
  4768.3 1719.33  4789.5 1721.51  4856.6 1719.73  4861.7 1721.42  4941.5 1720.62
  5069.2 1723.95  5090.4 1721.91  5162.4  1725.1  5183.8 1721.27  5199.4 1723.84
  5279.2 1725.43  5380.3 1720.62  5521.1 1725.68  5835.4 1734.99  6178.6 1739.79
#Mann= 11 ,-1 , 0
  3402.5     .05       0  3636.9      .1       0    3777     .05       0
  3880.7      .1       0  4086.8     .05       0  4121.6      .1       0
  4233.7     .16       0  4570.1      .1       0  4640.4     .07       0
  4646.4      .1       0  5521.1     .05       0
Bank Sta=4640.4,4646.4
XS Rating Curve= 0 ,0
Exp/Cntr=0.3,0.1

Type RM Length L Ch R = 1 ,3632    ,251,251,251
BEGIN DESCRIPTION:
UNT 0009 IN HEWA 7.0
END DESCRIPTION:
XS GIS Cut Line= 4
      2732708.06     10057072.86      2731597.77     10056167.34
      2731443.06     10055967.12      2730892.92     10055930.75
#Sta/Elev= 30
  3491.6 1737.95  3526.6 1738.03  3778.7 1731.76  3807.6 1731.08  4272.6 1723.31
  4398.6 1722.55  4508.3 1719.48  4521.5 1719.42  4591.8 1717.82  4691.2 1714.71
  4755.7 1714.97  4783.8  1713.4  4806.1 1715.04  4837.1 1715.19  4847.7 1714.49
  4890.4 1715.23  4968.6 1716.15  4983.1 1715.43  4994.6 1713.27  4997.3 1712.77
  5000.6 1713.27  5023.3 1715.96    5147 1724.92    5169 1725.18    5202 1728.29
  5272.2 1729.43  5352.3 1732.93  5492.6 1735.91  5578.4 1735.36  5728.7 1735.54
#Mann= 13 ,-1 , 0
  3491.6     .05       0  3778.7      .1       0  3807.6     .05       0
  4398.6      .1       0  4508.3     .16       0  4521.5      .1       0
  4591.8     .16       0  4837.1      .1       0  4890.4     .16       0
  4994.6     .07       0  5000.6     .16       0  5023.3      .1       0
  5578.4     .05       0
Bank Sta=4994.6,5000.6
XS Rating Curve= 0 ,0
Exp/Cntr=0.3,0.1

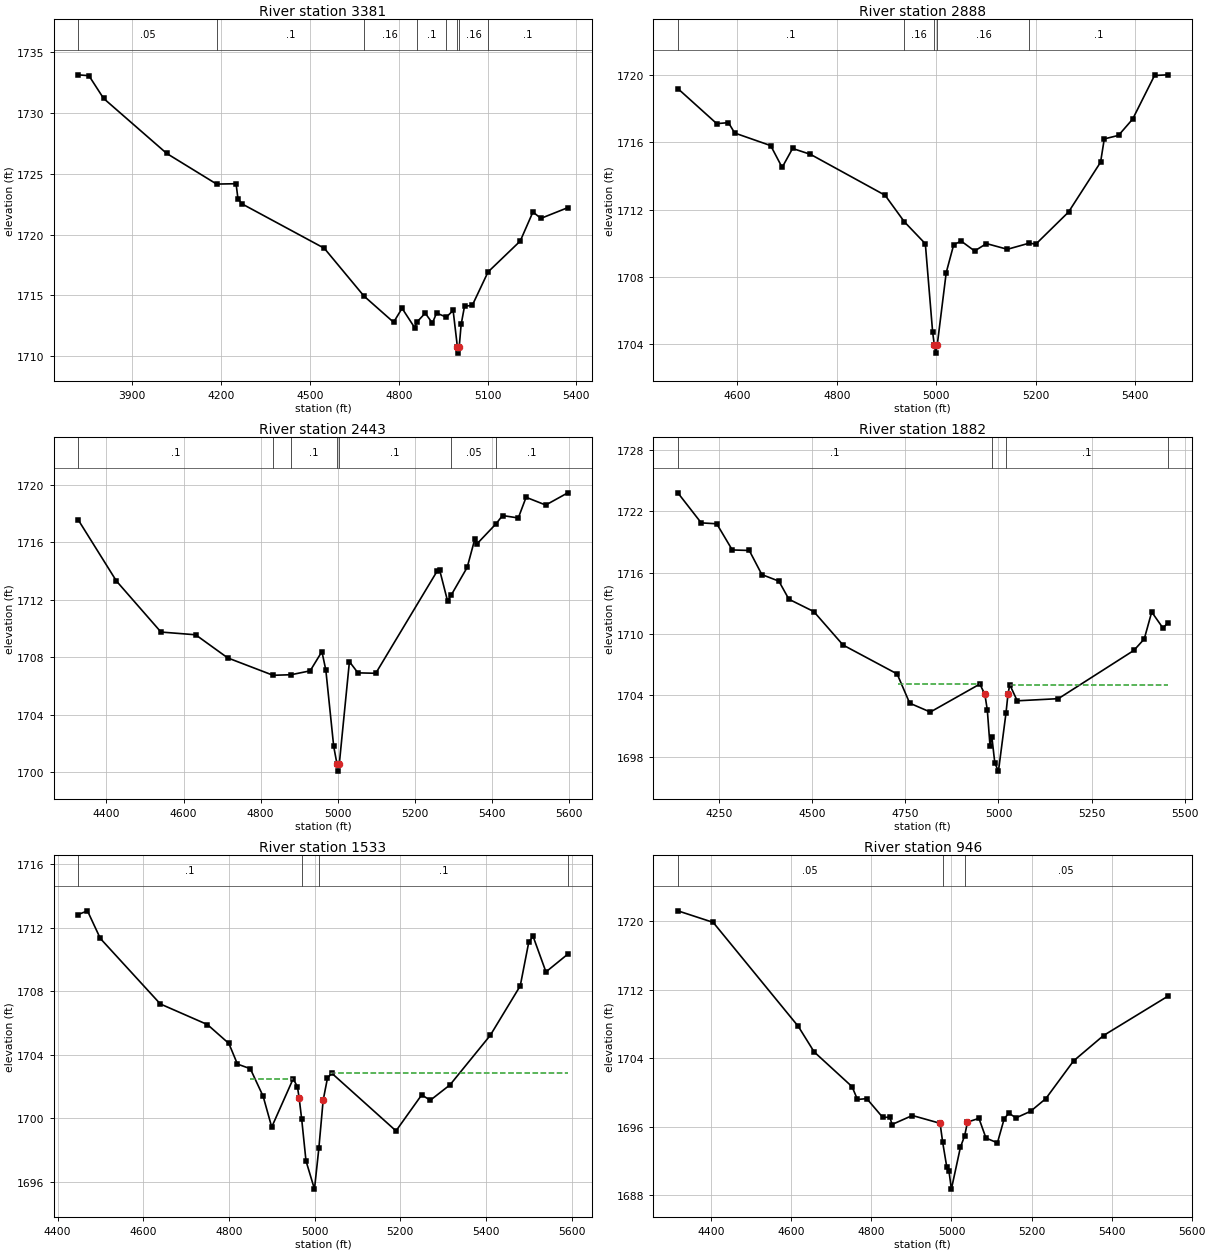
Type RM Length L Ch R = 1 ,3381    ,493,493,493
BEGIN DESCRIPTION:
UNT 0009 IN HEWA 6.0
END DESCRIPTION:
XS GIS Cut Line= 3
      2732680.35      10056843.5      2731780.55     10056088.18
      2731636.62       10055631.
#Sta/Elev= 30
  3716.8 1733.15  3753.6 1733.08  3803.1 1731.21  4016.4 1726.68  4184.9 1724.16
  4250.5 1724.19  4257.1 1722.93  4271.4 1722.52  4548.4 1718.88  4682.3 1714.95
  4782.6 1712.79  4811.2 1713.94  4854.1 1712.33  4860.4 1712.78  4889.3 1713.54
  4913.6 1712.72  4927.7 1713.55  4960.6 1713.21  4983.6 1713.76  4998.1 1710.75
  5000.8 1710.25  5004.1 1710.75  5010.7 1712.61  5022.1 1714.11  5048.3 1714.18
  5101.6 1716.93  5210.2 1719.47  5253.1 1721.86  5280.2 1721.34  5370.9 1722.22
#Mann= 8 ,-1 , 0
  3716.8     .05       0  4184.9      .1       0  4682.3     .16       0
  4860.4      .1       0  4960.6     .16       0  4998.1     .07       0
  5004.1     .16       0  5101.6      .1       0
Bank Sta=4998.1,5004.1
XS Rating Curve= 0 ,0
Exp/Cntr=0.3,0.1

Type RM Length L Ch R = 1 ,2888    ,445,445,445
BEGIN DESCRIPTION:
UNT 0009 IN HEWA 5.0
END DESCRIPTION:
XS GIS Cut Line= 2
      2732593.35     10056168.61      2731776.64      10055618.5
#Sta/Elev= 30
  4480.3 1719.21  4558.5 1717.12    4582 1717.18  4594.7 1716.56    4667 1715.81
    4690 1714.51    4711 1715.64    4747 1715.29    4897 1712.85  4935.7 1711.27
  4977.9 1709.96  4992.6 1704.69  4995.9 1703.94  4998.6 1703.44  5001.9 1703.94
  5019.9 1708.24  5034.9  1709.9  5049.9 1710.12    5077 1709.53  5100.8 1709.97
  5142.8 1709.63  5187.3    1710  5199.8 1709.93  5265.8 1711.85  5330.2 1714.82
  5337.7 1716.21  5366.3 1716.42  5394.7 1717.39  5438.7 1719.99    5465 1720.03
#Mann= 5 ,-1 , 0
  4480.3      .1       0  4935.7     .16       0  4995.9     .07       0
  5001.9     .16       0  5187.3      .1       0
Bank Sta=4995.9,5001.9
XS Rating Curve= 0 ,0
Exp/Cntr=0.3,0.1

Type RM Length L Ch R = 1 ,2443    ,561,561,561
BEGIN DESCRIPTION:
UNT 0009 IN HEWA 4.0
END DESCRIPTION:
XS GIS Cut Line= 2
      2732999.72     10055618.27       2731752.2       10055373.
#Sta/Elev= 30
  4326.2 1717.59  4425.9 1713.31  4541.5 1709.76  4631.5 1709.57  4714.8 1707.96
  4832.6 1706.75  4879.3 1706.79  4928.8 1707.06  4959.3  1708.4  4969.5 1707.11
  4989.9  1701.8  4998.4 1700.58  5001.2 1700.08  5004.4 1700.58  5030.7  1707.7
  5052.8 1706.92  5099.1 1706.89  5258.4    1714  5265.1 1714.06  5285.5 1711.92
  5294.9 1712.33  5336.4 1714.26  5356.1 1716.22  5361.2 1715.88  5411.2 1717.29
  5428.2 1717.87  5469.1  1717.7  5489.3 1719.14  5540.3  1718.6  5597.6 1719.45
#Mann= 7 ,-1 , 0
  4326.2      .1       0  4832.6     .16       0  4879.3      .1       0
  4998.4     .07       0  5004.4      .1       0  5294.9     .05       0
  5411.2      .1       0
Bank Sta=4998.4,5004.4
XS Rating Curve= 0 ,0
Exp/Cntr=0.3,0.1

Type RM Length L Ch R = 1 ,1882    ,349,349,349
BEGIN DESCRIPTION:
UNT 0009 IN HEWA 3.0
END DESCRIPTION:
XS GIS Cut Line= 3
       2733198.7     10055131.43      2732479.06     10054924.01
      2731915.97     10054953.64
#Sta/Elev= 30
  4140.6 1723.82  4203.3 1720.88  4244.9 1720.79  4286.5 1718.23  4332.1 1718.18
  4365.8 1715.82  4411.4 1715.18  4438.3 1713.41  4505.1  1712.2  4583.4 1708.93
  4728.4  1706.1  4762.1 1703.24  4817.3 1702.37  4950.2 1705.11 4963.64 1704.09
  4970.2 1702.55  4977.3 1699.09  4982.3 1699.94  4990.3 1697.37    5000 1696.59
  5020.3  1702.3 5025.45 1704.09  5030.3 1705.05  5050.3 1703.47  5160.5 1703.68
  5362.9  1708.4  5390.8 1709.52  5410.8 1712.16  5440.9 1710.59  5453.4 1711.07
#Mann= 4 ,-1 , 0
  4140.6      .1       0  4982.3     .05       0  5020.3      .1       0
  5453.4     .05       0
#XS Ineff= 2 ,-1
 4731.72 4950.61 1705.13 5030.51  5453.4 1705.06
Permanent Ineff=
       T       T
Bank Sta=4963.64,5025.45
XS Rating Curve= 0 ,0
Exp/Cntr=0.3,0.1

Type RM Length L Ch R = 1 ,1533    ,587,587,587
BEGIN DESCRIPTION:
UNT 0009 IN HEWA 2.0
END DESCRIPTION:
XS GIS Cut Line= 2
       2732940.5     10054572.64      2731797.49     10054593.81
#Sta/Elev= 30
  4447.7 1712.83  4469.7 1713.07  4499.7 1711.33  4639.8  1707.2  4749.8  1705.9
  4799.8 1704.71  4819.8 1703.41  4849.8 1703.12  4879.8 1701.38  4899.8 1699.44
  4949.8 1702.48  4959.8 1701.99 4963.86 1701.26  4969.8 1699.93  4979.8 1697.31
  4999.6 1695.53  5009.8  1698.1  5019.8 1701.12  5029.8 1702.51  5039.8 1702.84
  5189.9  1699.2  5249.9 1701.47  5269.9 1701.13  5315.9  1702.1  5409.9 1705.22
  5479.9 1708.34  5499.9 1711.11  5509.9 1711.46  5539.9 1709.22  5590.9 1710.34
#Mann= 4 ,-1 , 0
  4447.7      .1       0  4969.8     .05       0  5009.8      .1       0
  5590.9     .05       0
#XS Ineff= 2 ,-1
 4848.64 4949.55 1702.48 5038.86  5590.9 1702.86
Permanent Ineff=
       T       T
Bank Sta=4963.86,5019.8
XS Rating Curve= 0 ,0
Exp/Cntr=0.3,0.1

Type RM Length L Ch R = 1 ,946     ,774,774,774
BEGIN DESCRIPTION:
Mapping XS 3992ec11
END DESCRIPTION:
XS GIS Cut Line= 3
      2732973.81     10054187.96      2732392.25     10053992.66
       2731836.7     10054244.39
#Sta/Elev= 30
  4316.5  1721.2  4404.8 1719.85  4617.5 1707.71    4657 1704.74  4751.6 1700.69
  4765.2 1699.19  4788.4 1699.29  4828.5 1697.09  4846.2 1697.13  4851.5 1696.27
  4902.3 1697.32 4971.59 1696.41    4978 1694.21  4988.3 1691.31  4993.8 1690.82
  4999.8 1688.73  5022.4 1693.62  5032.9 1694.95    5040 1696.55  5068.6 1696.99
  5086.2 1694.69  5114.8 1694.13  5131.7 1696.94  5143.4  1697.6    5161 1697.04
  5197.6 1697.81  5235.7 1699.29    5305 1703.69  5379.8 1706.65  5539.9 1711.22
#Mann= 3 ,-1 , 0
  4316.5     .05       0    4978    .035       0  5032.9     .05       0
Bank Sta=4971.59,5040
XS Rating Curve= 0 ,0
Exp/Cntr=0.3,0.1

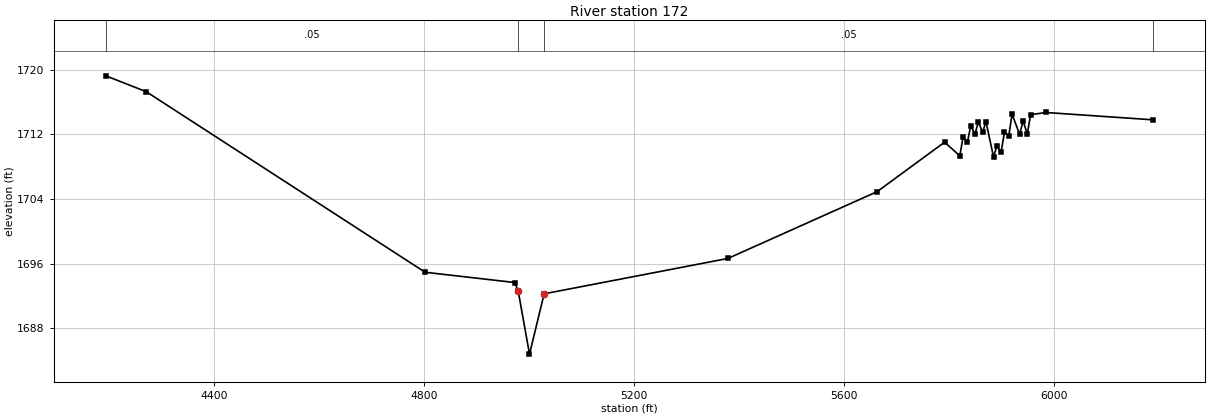
Type RM Length L Ch R = 1 ,172     ,0,0,0
BEGIN DESCRIPTION:
UNT 0009 IN HEWA 1.0
END DESCRIPTION:
XS GIS Cut Line= 4
      2733082.38     10054018.73      2732513.77     10053376.34
      2732379.22     10053411.06      2731768.11     10054199.88
#Sta/Elev= 30
  4194.1 1719.26  4271.1 1717.29  4802.2 1694.93  4972.8 1693.66  4979.5  1692.6
    5001 1684.79  5028.9 1692.26  5378.9 1696.64  5663.1 1704.91  5791.7 1711.04
  5820.7 1709.35    5827 1711.72  5835.2 1711.03  5841.5 1713.09  5849.6 1712.02
    5856 1713.58  5864.1 1712.25  5870.5 1713.57  5884.9 1709.23  5891.3 1710.55
  5899.4 1709.84  5905.8 1712.28  5913.9 1711.79  5920.2 1714.51  5934.7    1712
  5941.1 1713.68  5949.2 1712.08  5955.6 1714.44  5984.5 1714.72  6188.8 1713.81
#Mann= 4 ,-1 , 0
  4194.1     .05       0  4979.5    .035       0  5028.9     .05       0
  6188.8      .1       0
Bank Sta=4979.5,5028.9
XS Rating Curve= 0 ,0
Exp/Cntr=0.3,0.1

Chan Stop Cuts=-1
Use User Specified Reach Order=0
Composite Channel Slope=5