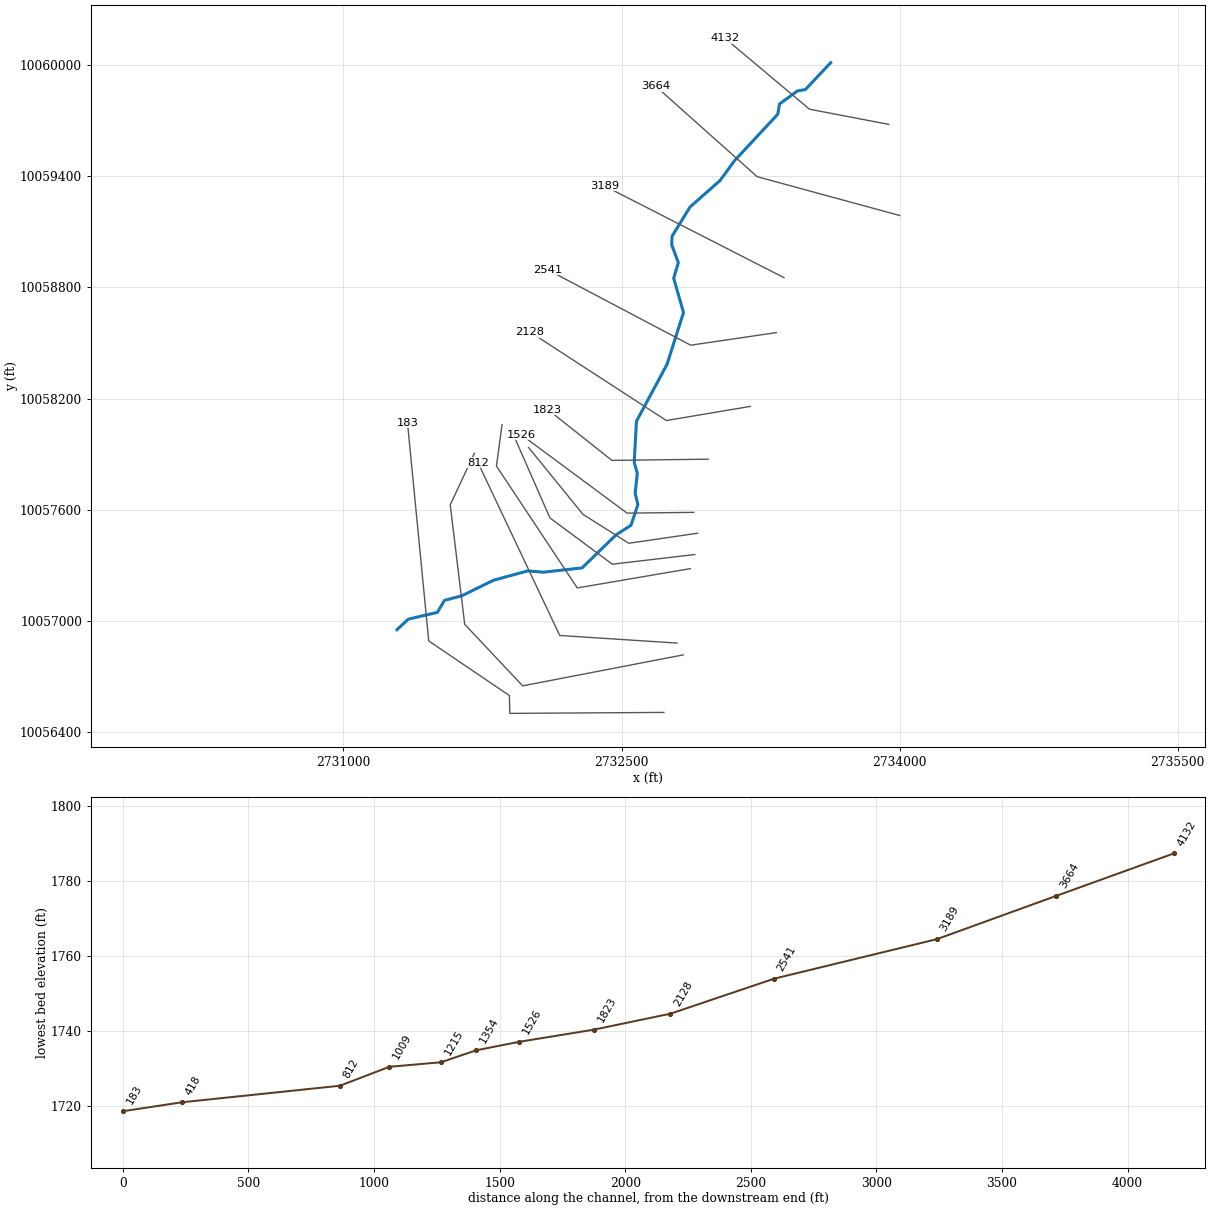
--- UNT 0010 IN HEWA.prj (project) ---

Proj Title=UNT 0010 IN HEWA Base Level Engineering
Current Plan=p01
Default Exp/Contr=0.3,0.1
English Units
Geom File=g01
Flow File=f01
Plan File=p01
Y Axis Title=Elevation
X Axis Title(PF)=Main Channel Distance
X Axis Title(XS)=Station
BEGIN DESCRIPTION:
UNT 0010 IN HEWA
END DESCRIPTION:
DSS Export Rating Curves= 0
DSS Export Rating Curve Sorted= 0
DSS Export Volume Flow Curves= 0
DXF OffsetX= 0
DXF OffsetY= 0
DXF ScaleX= 1
DXF ScaleY= 10

--- UNT 0010 IN HEWA.p01 (plan) ---

Plan Title=Multiple Run
Short Identifier=Multiple
Geom File=g01
Flow File=f01
Subcritical Flow
K Sum by GR= 0
Std Step Tol= 0.01
Critical Tol= 0.01
Num of Std Step Trials= 20
Max Error Tol= 0.3
Flow Tol Ratio= 0.001
Split Flow NTrial= 30
Split Flow Tol= 0.02
Split Flow Ratio= 0.02
Log Output Level= 0
Friction Slope Method= 1
Unsteady Friction Slope Method= 2
Unsteady Bridges Friction Slope Method= 1
Parabolic Critical Depth
Global Vel Dist=  1 , 1 , 1
Global Log Level= 0
CheckData=True
Encroach Param= -1, 0, 0, 0
BEGIN DESCRIPTION:
Multiple Run
END DESCRIPTION:

--- UNT 0010 IN HEWA.f01 (steady flow) ---

Flow Title=Multiple
Program Version=4.10
Number of Profiles= 7
Profile Names=10-year,25-year,50-year,1pct_min,100-year,1pct_plu,500-year
River Rch & RM=UNT 0010 IN HEWA,Reach-1         ,4132
     326     449     552     499     675     913    1011
Boundary for River Rch & Prof#=UNT 0010 IN HEWA,Reach-1         , 1
Up Type= 0
Dn Type= 3
Dn Slope=0.016
Boundary for River Rch & Prof#=UNT 0010 IN HEWA,Reach-1         , 2
Up Type= 0
Dn Type= 3
Dn Slope=0.016
Boundary for River Rch & Prof#=UNT 0010 IN HEWA,Reach-1         , 3
Up Type= 0
Dn Type= 3
Dn Slope=0.016
Boundary for River Rch & Prof#=UNT 0010 IN HEWA,Reach-1         , 4
Up Type= 0
Dn Type= 3
Dn Slope=0.016
Boundary for River Rch & Prof#=UNT 0010 IN HEWA,Reach-1         , 5
Up Type= 0
Dn Type= 3
Dn Slope=0.016
Boundary for River Rch & Prof#=UNT 0010 IN HEWA,Reach-1         , 6
Up Type= 0
Dn Type= 3
Dn Slope=0.016
Boundary for River Rch & Prof#=UNT 0010 IN HEWA,Reach-1         , 7
Up Type= 0
Dn Type= 3
Dn Slope=0.016
DSS Import GetInterval= 0
DSS Import GetPeak= 0
DSS Import FillOption= 0

--- UNT 0010 IN HEWA.g01 (geometry) ---

Geom Title=Existing Conditions
Program Version=4.10

River Reach=UNT 0010 IN HEWA,Reach-1
Reach XY= 30
      2733627.91     10060012.23      2733491.77     10059867.63
       2733448.1     10059859.61      2733351.93     10059789.57
      2733342.52     10059734.17       2733109.4     10059483.83
      2733031.65      10059377.1      2732869.27     10059233.89
      2732772.54     10059076.53      2732770.61     10059029.42
      2732806.18     10058933.76       2732781.1     10058849.35
      2732833.98     10058664.33      2732745.19     10058385.09
      2732580.35     10058078.27      2732568.27     10057856.62
      2732584.86     10057797.92      2732573.37     10057689.01
      2732587.92     10057629.12        2732551.      10057517.1
      2732471.03     10057466.06      2732287.02     10057287.22
      2732078.21      10057264.1      2731993.89     10057271.13
      2731809.73     10057220.69      2731637.32     10057136.45
      2731544.47     10057112.07      2731506.58     10057047.29
       2731349.7     10057010.75      2731288.47     10056953.73

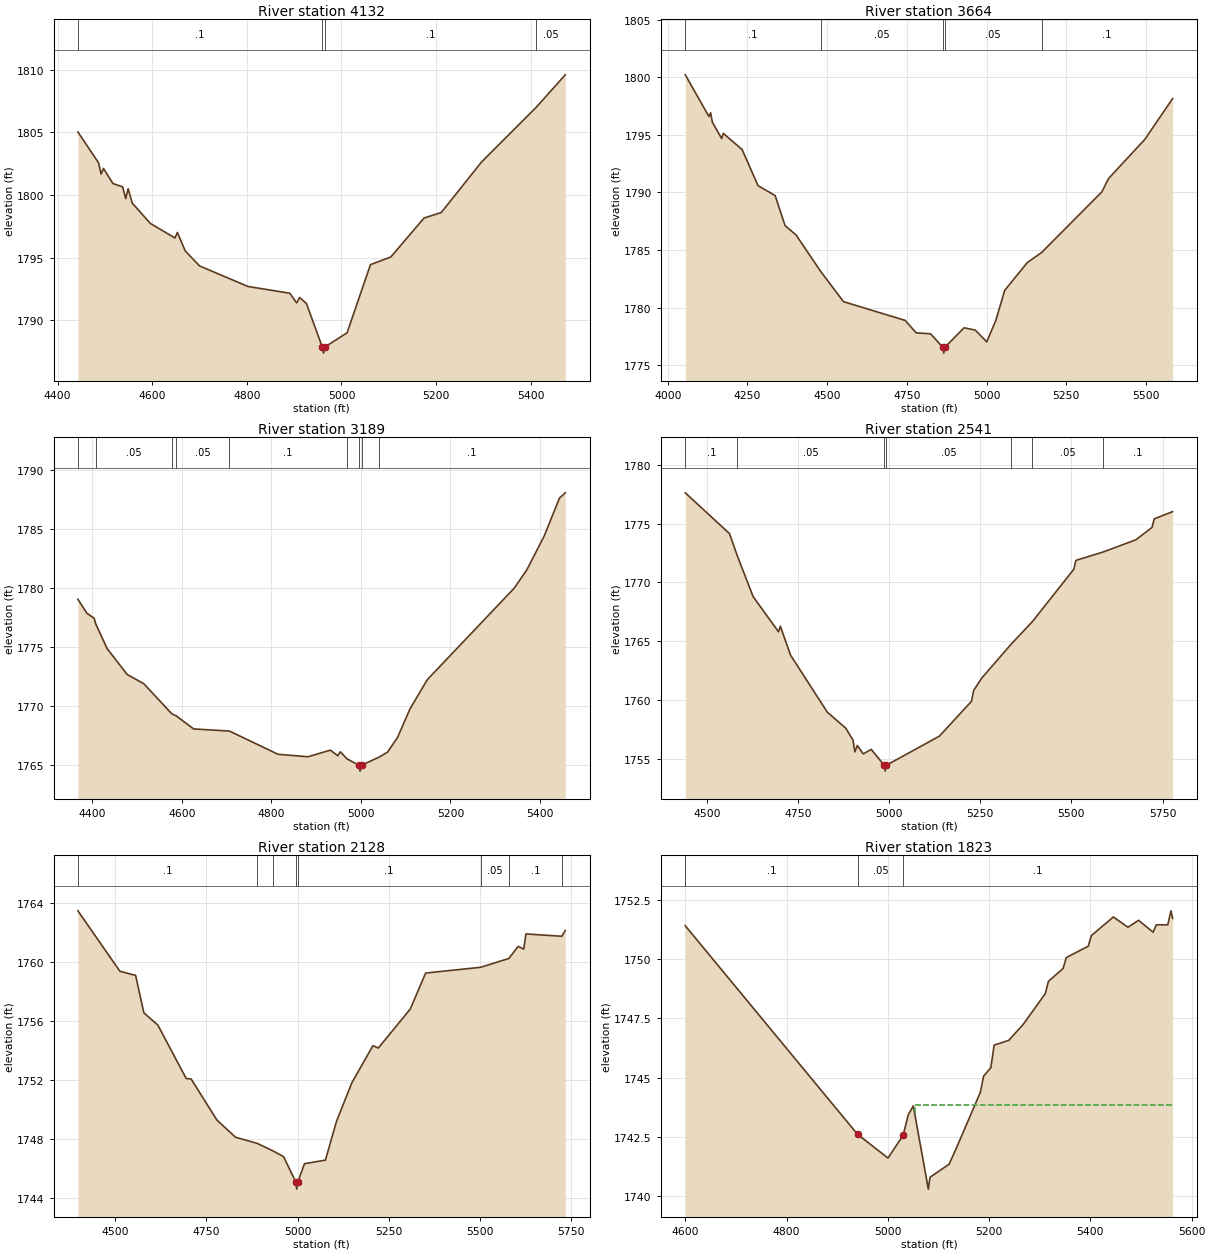
Type RM Length L Ch R = 1 ,4132    ,468,468,468
BEGIN DESCRIPTION:
UNT 0010 IN HEWA 6.0
END DESCRIPTION:
XS GIS Cut Line= 3
      2733941.28     10059679.46      2733513.58     10059761.37
       2733058.5     10060143.63
#Sta/Elev= 30
    4443 1805.04  4486.6 1802.58    4492 1801.68  4497.1 1802.13  4517.1 1800.92
  4537.5 1800.66    4544 1799.72  4549.1 1800.51  4557.9 1799.36  4596.1 1797.74
  4648.1 1796.58  4653.2 1797.02  4669.9 1795.54  4700.1 1794.35  4802.2 1792.71
  4890.8 1792.17  4905.1  1791.4  4911.6 1791.83  4925.9 1791.35  4959.3 1787.89
  4962.1 1787.39  4965.3 1787.89  5011.8 1789.01  5061.2 1794.45  5104.1 1795.06
  5174.4 1798.17  5210.8 1798.61  5295.4 1802.62  5410.8 1806.98  5472.8  1809.6
#Mann= 4 ,-1 , 0
    4443      .1       0  4959.3     .07       0  4965.3      .1       0
  5410.8     .05       0
Bank Sta=4959.3,4965.3
XS Rating Curve= 0 ,0
Exp/Cntr=0.3,0.1

Type RM Length L Ch R = 1 ,3664    ,475,475,475
BEGIN DESCRIPTION:
UNT 0010 IN HEWA 5.0
END DESCRIPTION:
XS GIS Cut Line= 3
      2734000.51       10059188.      2733231.45     10059397.33
      2732685.43      10059884.2
#Sta/Elev= 30
  4055.1 1800.21  4129.3 1796.59  4134.5 1796.92  4140.1  1796.1  4169.1 1794.68
  4174.3 1795.13  4233.4 1793.72  4283.2 1790.59    4337 1789.73  4368.1 1787.12
  4402.5 1786.31  4479.7 1783.15  4551.2 1780.52  4744.8 1778.89  4779.4 1777.81
  4824.4 1777.73  4863.1 1776.55  4865.8 1776.05  4869.1 1776.55  4929.6 1778.25
  4964.7 1778.05  5000.7 1777.03  5029.1 1778.89  5057.1  1781.5  5127.8 1783.91
    5173 1784.79  5361.8 1790.05  5382.8 1791.21  5496.4  1794.6  5583.7 1798.15
#Mann= 5 ,-1 , 0
  4055.1      .1       0  4479.7     .05       0  4863.1    .035       0
  4869.1     .05       0    5173      .1       0
Bank Sta=4863.1,4869.1
XS Rating Curve= 0 ,0
Exp/Cntr=0.3,0.1

Type RM Length L Ch R = 1 ,3189    ,648,648,648
BEGIN DESCRIPTION:
UNT 0010 IN HEWA 4.0
END DESCRIPTION:
XS GIS Cut Line= 2
      2733376.49     10058852.58      2732407.09     10059347.87
#Sta/Elev= 30
  4367.8 1779.07    4388 1777.88  4404.1 1777.46  4407.4    1777    4433 1774.89
  4477.9 1772.69  4515.2  1771.9  4577.1 1769.37  4587.4 1769.18  4626.3 1768.07
  4706.3 1767.89  4814.8 1765.92  4881.7 1765.71  4931.7 1766.27  4948.3  1765.8
    4954 1766.13  4968.6 1765.54  4995.4 1764.99  4998.1 1764.49  5001.4 1764.99
  5040.7 1765.68  5059.4  1766.1  5081.7 1767.34  5109.5 1769.76  5148.3 1772.25
  5342.6 1780.02  5370.5 1781.56  5409.3 1784.43  5443.6 1787.66  5456.4  1788.1
#Mann= 9 ,-1 , 0
  4367.8      .1       0  4407.4     .05       0  4577.1      .1       0
  4587.4     .05       0  4706.3      .1       0  4968.6     .05       0
  4995.4    .035       0  5001.4     .05       0  5040.7      .1       0
Bank Sta=4995.4,5001.4
XS Rating Curve= 0 ,0
Exp/Cntr=0.3,0.1

Type RM Length L Ch R = 1 ,2541    ,413,413,413
BEGIN DESCRIPTION:
UNT 0010 IN HEWA 3.0
END DESCRIPTION:
XS GIS Cut Line= 3
      2733334.16     10058556.23      2732872.76      10058488.5
      2732102.84     10058894.61
#Sta/Elev= 30
  4440.8 1777.62    4562 1774.15  4583.4 1772.27  4626.8 1768.79  4696.6 1765.79
  4701.6 1766.27  4729.6  1763.8  4830.6 1758.94  4881.2 1757.58  4900.9 1756.57
    4906 1755.57  4912.7 1756.11    4929  1755.4    4951 1755.78  4986.4 1754.43
  4989.2 1753.93  4992.4 1754.43  5137.9 1756.91    5226 1759.88  5231.7 1760.79
  5253.7 1761.84  5334.7 1764.74    5393 1766.66  5506.7 1771.12  5512.3 1771.87
  5587.8 1772.59  5677.2 1773.63  5721.3 1774.68  5726.9  1775.4  5777.6 1776.02
#Mann= 7 ,-1 , 0
  4440.8      .1       0  4583.4     .05       0  4986.4    .035       0
  4992.4     .05       0  5334.7      .1       0    5393     .05       0
  5587.8      .1       0
Bank Sta=4986.4,4992.4
XS Rating Curve= 0 ,0
Exp/Cntr=0.3,0.1

Type RM Length L Ch R = 1 ,2128    ,305,305,305
BEGIN DESCRIPTION:
UNT 0010 IN HEWA 2.0
END DESCRIPTION:
XS GIS Cut Line= 3
      2733194.47     10058158.29      2732741.52     10058082.09
      2732006.27     10058559.58
#Sta/Elev= 30
  4397.5 1763.49  4512.7 1759.38  4555.7  1759.1  4578.4 1756.55  4616.5 1755.73
  4694.4 1752.09  4707.8 1752.06  4778.8 1749.26  4829.5  1748.1  4889.2 1747.68
  4931.4 1747.18  4961.3 1746.78  4994.5 1745.07  4997.3 1744.57  5000.5 1745.07
  5018.7  1746.3    5076 1746.54  5106.3 1749.17  5148.5  1751.8  5206.2 1754.32
    5221 1754.16  5308.6 1756.81  5350.8 1759.26  5501.4 1759.65  5578.8 1760.25
  5604.5 1761.07  5619.7 1760.89  5625.7 1761.92    5724 1761.76  5733.5 1762.15
#Mann= 8 ,-1 , 0
  4397.5      .1       0  4889.2     .05       0  4931.4      .1       0
  4994.5     .07       0  5000.5      .1       0  5501.4     .05       0
  5578.8      .1       0    5724     .05       0
Bank Sta=4994.5,5000.5
XS Rating Curve= 0 ,0
Exp/Cntr=0.3,0.1

Type RM Length L Ch R = 1 ,1823    ,297,297,297
BEGIN DESCRIPTION:
Mapping XS 736e0464
END DESCRIPTION:
XS GIS Cut Line= 3
      2732968.68     10057873.62      2732447.86     10057867.11
      2732102.03     10058141.62
#Sta/Elev= 30
    4600  1751.4  4940.2 1742.61  5000.3 1741.61  5030.3 1742.57  5040.3 1743.43
  5050.3 1743.81    5080  1740.3  5083.3  1740.8  5120.9 1741.35  5132.9 1741.91
  5182.7 1744.38  5189.1 1745.06  5203.5 1745.42  5209.9 1746.37  5238.7 1746.57
  5267.6 1747.25  5310.9 1748.54  5317.2 1749.06  5346.1  1749.6  5352.5 1750.06
  5395.8 1750.54  5402.1 1750.99  5445.4 1751.77  5474.3 1751.34  5495.1 1751.63
  5523.9 1751.13  5530.3 1751.44  5552.8 1751.44  5559.2 1752.03  5562.4 1751.71
#Mann= 3 , 0 , 0
    4600      .1       0  4940.2     .05       0  5030.3      .1       0
#XS Ineff= 2 , 0
                         5052.85         1743.85
Permanent Ineff=
       T       T
Bank Sta=4940.2,5030.3
XS Rating Curve= 0 ,0
Exp/Cntr=0.3,0.1

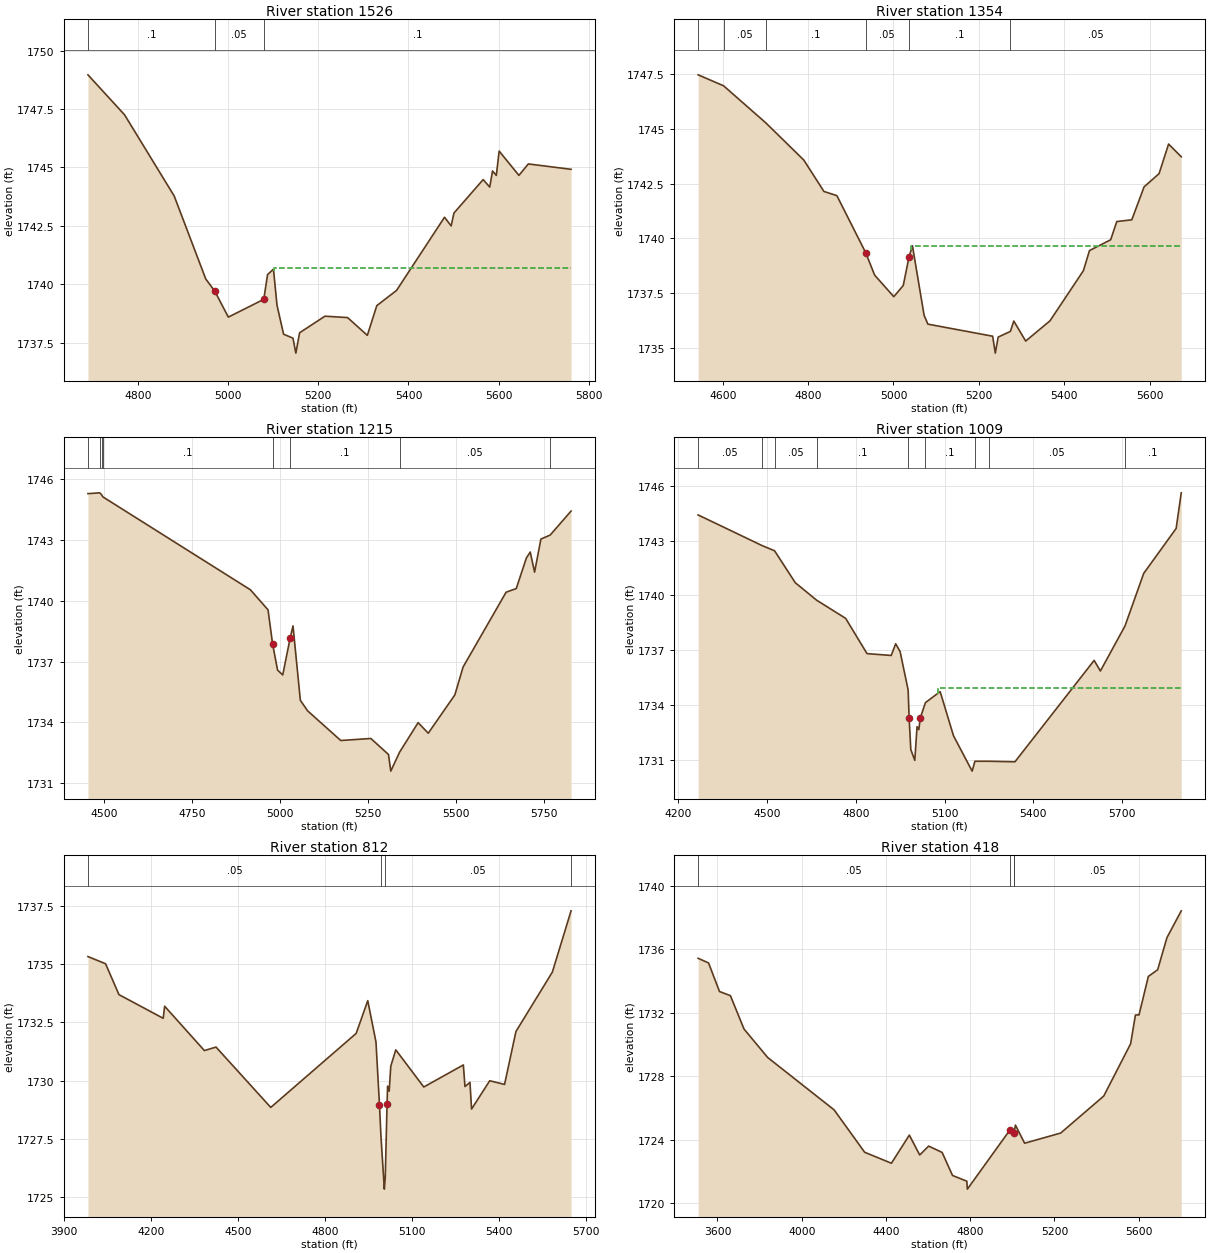
Type RM Length L Ch R = 1 ,1526    ,172,172,172
BEGIN DESCRIPTION:
Mapping XS 4cc484c0
END DESCRIPTION:
XS GIS Cut Line= 3
      2732889.65     10057586.79      2732529.86     10057582.56
      2731958.38     10058005.87
#Sta/Elev= 30
  4689.4 1748.96  4770.6 1747.25  4880.6 1743.78  4950.6 1740.23  4970.6 1739.71
  5000.6  1738.6  5079.2 1739.36  5087.6 1740.42  5100.7 1740.65  5108.5 1739.11
  5123.1 1737.87  5143.9  1737.7  5150.3 1737.06  5158.6 1737.93  5214.9 1738.64
    5265 1738.58  5308.8 1737.82  5329.7 1739.09  5373.5 1739.74  5479.9 1742.87
  5494.6  1742.5  5500.8 1743.05  5565.5 1744.48  5580.1 1744.16  5586.3 1744.85
  5594.7 1744.66    5601  1745.7  5644.8 1744.66  5665.7 1745.15  5760.4 1744.92
#Mann= 3 , 0 , 0
  4689.4      .1       0  4970.6     .05       0  5079.2      .1       0
#XS Ineff= 2 , 0
                         5101.14         1740.69
Permanent Ineff=
       T       T
Bank Sta=4970.6,5079.2
XS Rating Curve= 0 ,0
Exp/Cntr=0.3,0.1

Type RM Length L Ch R = 1 ,1354    ,139,139,139
BEGIN DESCRIPTION:
Mapping XS 9092c421
END DESCRIPTION:
XS GIS Cut Line= 4
      2732910.14     10057474.32      2732539.01     10057420.06
      2732291.61     10057576.31      2731998.65     10057936.54
#Sta/Elev= 30
  4542.3 1747.45    4602 1746.95    4701 1745.26  4789.9 1743.57  4837.1 1742.14
  4867.4 1741.95  4934.7 1739.36  4955.9 1738.33  5000.8 1737.35  5022.9 1737.86
  5036.3 1739.15  5044.4 1739.67  5071.8  1736.5  5080.6  1736.1  5232.4 1735.55
  5238.6 1734.78  5245.3 1735.51    5274 1735.77  5281.9 1736.24  5309.8 1735.33
  5366.7 1736.25  5444.9 1738.53  5459.3 1739.45  5508.9 1739.94  5523.2 1740.77
  5558.4 1740.85  5587.2 1742.35  5622.3 1742.95  5644.6  1744.3  5674.3 1743.72
#Mann= 6 ,-1 , 0
  4542.3      .1       0    4602     .05       0    4701      .1       0
  4934.7     .05       0  5036.3      .1       0    5274     .05       0
#XS Ineff= 2 , 0
                         5041.24         1739.67
Permanent Ineff=
       T       T
Bank Sta=4934.7,5036.3
XS Rating Curve= 0 ,0
Exp/Cntr=0.3,0.1

Type RM Length L Ch R = 1 ,1215    ,206,206,206
BEGIN DESCRIPTION:
Mapping XS 5832f64a
END DESCRIPTION:
XS GIS Cut Line= 4
      2732894.89     10057359.29      2732450.03     10057307.21
      2732113.66     10057556.78      2731910.22     10058019.93
#Sta/Elev= 30
  4453.7 1745.28  4487.4 1745.32  4492.3 1745.23  4496.2 1745.12  4915.3 1740.54
  4965.4 1739.55  4978.3 1737.87  4992.5 1736.58  5007.1 1736.34  5028.1 1738.15
  5036.3 1738.76  5057.2 1735.09    5078 1734.57    5172 1733.11  5257.5 1733.21
  5307.6 1732.42  5314.1  1731.6    5339 1732.53  5391.8 1733.99  5420.6 1733.47
  5496.2 1735.36  5519.5 1736.73  5641.7 1740.42  5670.6  1740.6  5699.4 1742.11
  5710.3  1742.4  5722.7 1741.41  5740.6 1743.04  5767.1 1743.24  5826.3 1744.42
#Mann= 8 ,-1 , 0
  4453.7     .05       0  4487.4      .1       0  4492.3     .05       0
  4496.2      .1       0  4978.3     .05       0  5028.1      .1       0
    5339     .05       0  5767.1      .1       0
#XS Ineff= 2 , 0
                         5038.34         1738.33
Permanent Ineff=
       T       T
Bank Sta=4978.3,5028.1
XS Rating Curve= 0 ,0
Exp/Cntr=0.3,0.1

Type RM Length L Ch R = 1 ,1009    ,197,197,197
BEGIN DESCRIPTION:
Mapping XS 3e74046e
END DESCRIPTION:
XS GIS Cut Line= 4
      2732871.03     10057283.34      2732261.23     10057179.18
      2731825.03     10057836.73      2731855.31     10058059.48
#Sta/Elev= 30
  4267.4  1744.4  4483.9 1742.72  4525.6 1742.44  4595.7 1740.69  4668.2 1739.73
  4765.9 1738.74  4838.1 1736.81  4919.8 1736.71  4934.9 1737.35  4949.9 1736.92
    4977 1734.82 4980.34  1733.3    4986 1731.56  4999.5 1730.97  5007.1 1732.81
  5013.1 1732.65 5018.18  1733.3  5035.5 1734.13  5085.2 1734.73  5130.4 1732.31
  5193.3 1730.38  5202.6 1730.92  5251.9 1730.92  5337.9 1730.89  5605.5 1736.44
  5626.6 1735.86  5709.7 1738.32    5773  1741.2  5882.6 1743.66  5899.9 1745.61
#Mann= 9 ,-1 , 0
  4267.4     .05       0  4483.9      .1       0  4525.6     .05       0
  4668.2      .1       0    4977     .05       0  5035.5      .1       0
  5202.6      .1       0  5251.9     .05       0  5709.7      .1       0
#XS Ineff= 2 , 0
                         5076.68         1734.93
Permanent Ineff=
       T       T
Bank Sta=4980.34,5018.18
XS Rating Curve= 0 ,0
Exp/Cntr=0.3,0.1

Type RM Length L Ch R = 1 ,812     ,629,629,629
BEGIN DESCRIPTION:
Mapping XS c4134a1a
END DESCRIPTION:
XS GIS Cut Line= 3
      2732799.14     10056881.76      2732166.58     10056922.72
      2731725.18     10057855.57
#Sta/Elev= 30
  3982.2 1735.34    4043 1735.03  4089.1  1733.7  4241.7 1732.68  4246.7  1733.2
  4383.7 1731.29  4423.8 1731.44  4612.6 1728.84  4907.2 1732.03  4947.1 1733.44
  4975.4 1731.66  4987.5 1728.94  4992.6  1727.6  5004.2 1725.32  5007.4 1725.82
 5013.64 1728.99  5015.4 1729.76  5020.9 1729.54  5026.5 1730.62  5043.7 1731.32
  5140.2 1729.72  5276.7 1730.67  5282.3 1729.74  5299.5 1729.92    5305 1728.77
  5367.7 1729.99  5418.8 1729.83    5458 1732.11  5583.6 1734.67  5648.1 1737.31
#Mann= 4 ,-1 , 0
  3982.2     .05       0  4992.6    .035       0  5007.4     .05       0
  5648.1     .05       0
Bank Sta=4987.5,5013.64
XS Rating Curve= 0 ,0
Exp/Cntr=0.3,0.1

Type RM Length L Ch R = 1 ,418     ,235,235,235
BEGIN DESCRIPTION:
Mapping XS 71dd0d85
END DESCRIPTION:
XS GIS Cut Line= 5
      2732832.34     10056818.07      2731966.47     10056650.97
      2731653.97       10056983.      2731575.85     10057627.53
      2731706.04     10057905.28
#Sta/Elev= 30
  3508.2 1735.43  3557.7 1735.14  3609.6 1733.34  3661.4 1733.08    3726 1730.98
  3838.1 1729.19  4153.8 1725.89  4298.9 1723.22  4425.9 1722.53  4510.9  1724.3
  4560.2 1723.05  4602.7 1723.61  4666.6 1723.21    4716 1721.76  4783.8  1721.4
  4786.5  1720.9  4987.8 1724.61  5007.9 1724.41  5008.1 1724.43  5014.7 1724.93
  5058.3 1723.79  5229.5 1724.43    5434 1726.76  5561.6 1730.05  5584.4 1731.86
  5601.5 1731.87  5645.7 1734.29  5689.9 1734.71    5734 1736.73    5802 1738.42
#Mann= 4 ,-1 , 0
  3508.2     .05       0  4987.8    .035       0  5007.9      .1       0
  5008.1     .05       0
Bank Sta=4987.8,5008.1
XS Rating Curve= 0 ,0
Exp/Cntr=0.3,0.1

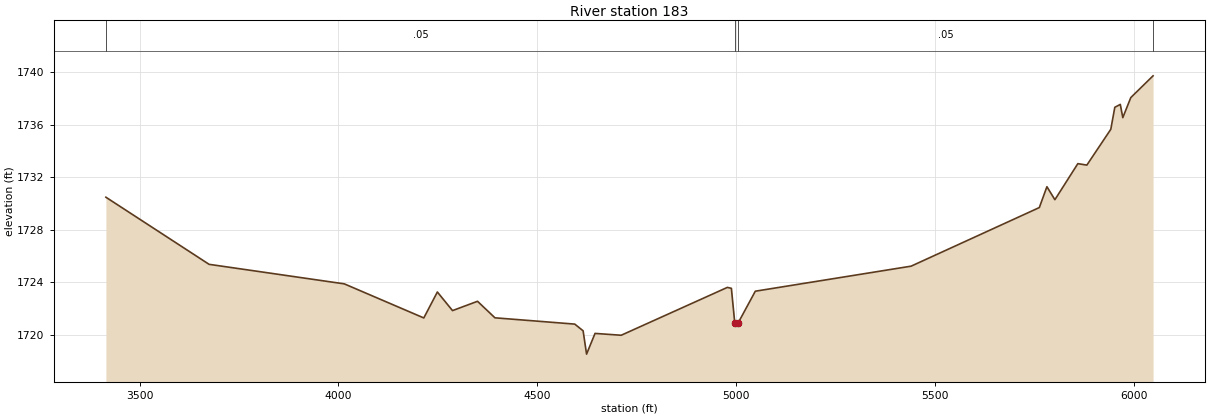
Type RM Length L Ch R = 1 ,183     ,0,0,0
BEGIN DESCRIPTION:
UNT 0010 IN HEWA 1.0
END DESCRIPTION:
XS GIS Cut Line= 5
      2732728.11     10056507.77      2731897.37     10056502.56
      2731894.77     10056598.92      2731459.87     10056893.19
      2731345.36     10058069.49
#Sta/Elev= 30
    3415 1730.48  3674.6 1725.36  4014.7 1723.87  4214.7 1721.27  4248.8 1723.25
  4286.9 1721.83  4349.8 1722.54  4393.7 1721.28  4594.4  1720.8  4615.4 1720.29
  4624.1 1718.51  4645.4 1720.09  4711.2 1719.95  4978.3  1723.6  4988.4 1723.53
 4996.99 1720.86 5004.91 1720.86  5048.6 1723.31  5440.5 1725.22    5763 1729.69
  5782.1 1731.28  5802.2 1730.29  5859.9 1733.04  5882.6 1732.93  5942.8 1735.66
  5952.9 1737.34  5966.7 1737.56    5973 1736.55  5993.1 1738.08  6049.1 1739.74
#Mann= 4 ,-1 , 0
    3415     .05       0 4996.99    .035       0 5004.91     .05       0
  6049.1     .05       0
Bank Sta=4996.99,5004.91
XS Rating Curve= 0 ,0
Exp/Cntr=0.3,0.1

Chan Stop Cuts=-1
Use User Specified Reach Order=0
Composite Channel Slope=5