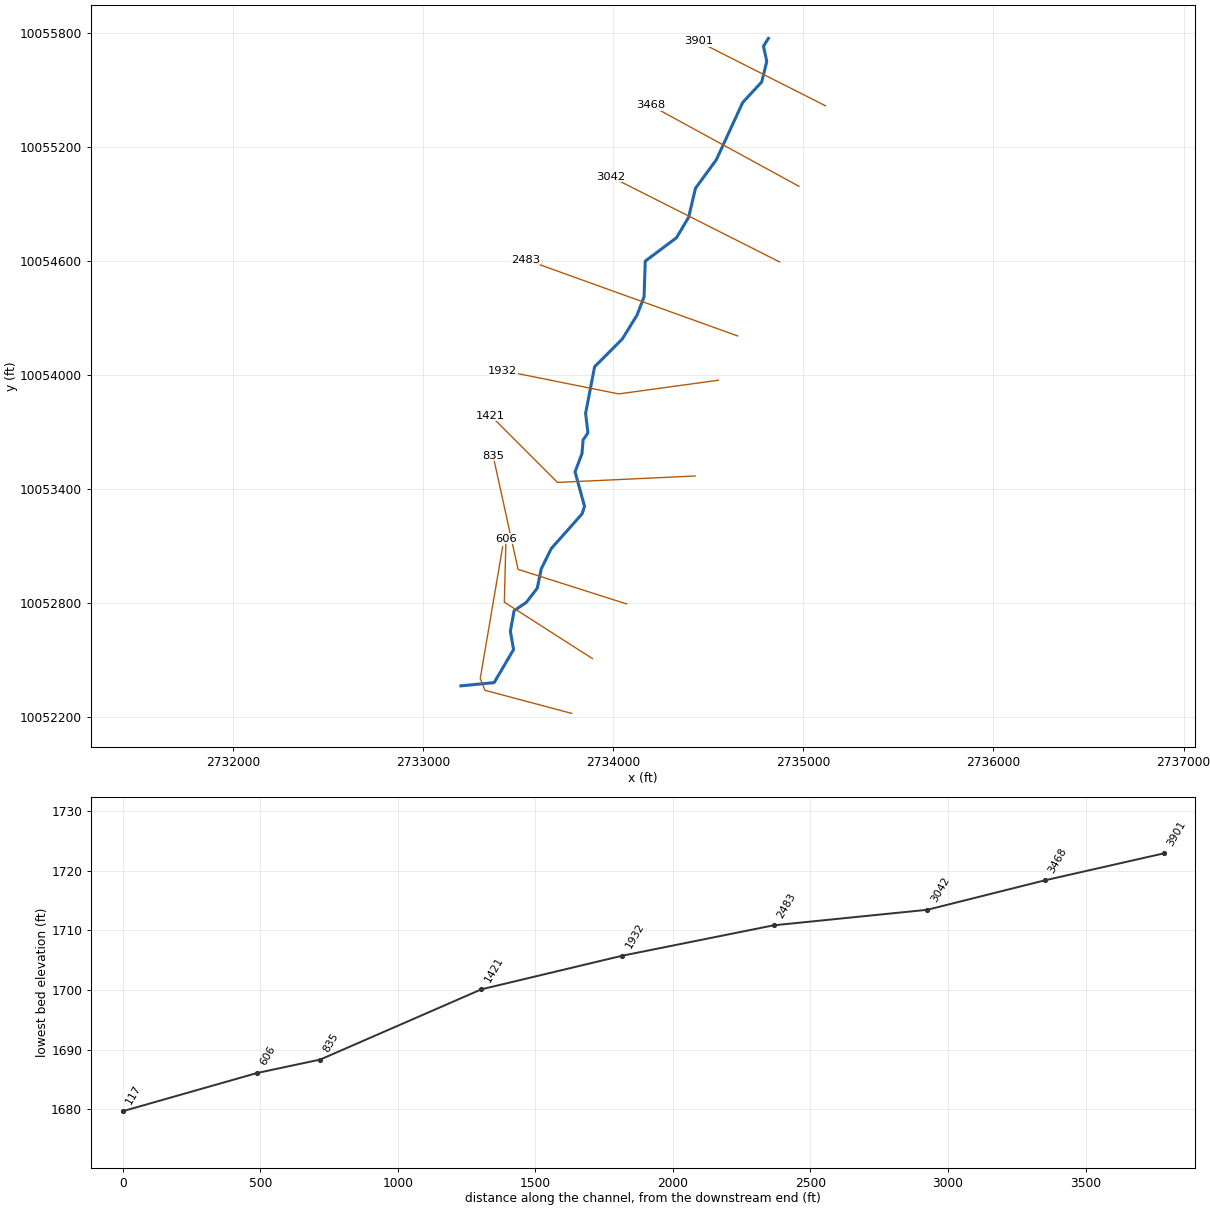
--- UNT 0012 IN HEWA.prj (project) ---

Proj Title=UNT 0012 IN HEWA Base Level Engineering
Current Plan=p01
Default Exp/Contr=0.3,0.1
English Units
Geom File=g01
Flow File=f01
Plan File=p01
BEGIN DESCRIPTION:
UNT 0012 IN HEWA
END DESCRIPTION:

--- UNT 0012 IN HEWA.p01 (plan) ---

Plan Title=Multiple Run
Short Identifier=Multiple
Geom File=g01
Flow File=f01
Subcritical Flow
K Sum by GR= 0
Std Step Tol= 0.01
Critical Tol= 0.01
Num of Std Step Trials= 20
Max Error Tol= 0.3
Flow Tol Ratio= 0.001
Split Flow NTrial= 30
Split Flow Tol= 0.02
Split Flow Ratio= 0.02
Log Output Level= 0
Friction Slope Method= 1
Unsteady Friction Slope Method= 2
Unsteady Bridges Friction Slope Method= 1
Parabolic Critical Depth
Global Vel Dist=  1 , 1 , 1
Global Log Level= 0
CheckData=True
Encroach Param= -1, 0, 0, 0
BEGIN DESCRIPTION:
Multiple Run
END DESCRIPTION:

--- UNT 0012 IN HEWA.f01 (steady flow) ---

Flow Title=Multiple
Number of Profiles=7
Profile Names=10-year,25-year,50-year,1pct_min,100-year,1pct_plu,500-year
River Rch & RM= UNT 0012 IN HEWA,Reach-1,3901
     439     617     766     699     945    1278    1442
Boundary for River Rch & Prof#=UNT 0012 IN HEWA,Reach-1,1
Up Type=0
Dn Type=3
Dn Slope=0.005
Boundary for River Rch & Prof#=UNT 0012 IN HEWA,Reach-1,2
Up Type=0
Dn Type=3
Dn Slope=0.005
Boundary for River Rch & Prof#=UNT 0012 IN HEWA,Reach-1,3
Up Type=0
Dn Type=3
Dn Slope=0.005
Boundary for River Rch & Prof#=UNT 0012 IN HEWA,Reach-1,4
Up Type=0
Dn Type=3
Dn Slope=0.005
Boundary for River Rch & Prof#=UNT 0012 IN HEWA,Reach-1,5
Up Type=0
Dn Type=3
Dn Slope=0.005
Boundary for River Rch & Prof#=UNT 0012 IN HEWA,Reach-1,6
Up Type=0
Dn Type=3
Dn Slope=0.005
Boundary for River Rch & Prof#=UNT 0012 IN HEWA,Reach-1,7
Up Type=0
Dn Type=3
Dn Slope=0.005

--- UNT 0012 IN HEWA.g01 (geometry) ---

Geom Title=Existing Conditions

River Reach=UNT 0012 IN HEWA,Reach-1
Reach XY= 30
      2734816.27     10055770.00      2734790.29     10055728.11
      2734807.67     10055648.98      2734781.08     10055540.55
      2734681.07     10055432.66      2734542.50     10055131.60
      2734432.72     10054981.41      2734396.81     10054829.42
      2734332.93     10054721.15      2734168.48     10054598.25
      2734162.17     10054409.87      2734125.55     10054314.75
      2734048.04     10054188.93      2733901.98     10054042.28
      2733854.63     10053797.53      2733866.85     10053694.58
      2733841.46     10053657.47      2733835.48     10053585.00
      2733799.09     10053489.51      2733848.90     10053307.81
      2733835.84     10053268.07      2733674.05     10053086.18
      2733621.05     10052978.22      2733600.37     10052877.63
      2733542.58     10052802.82      2733478.49     10052758.94
      2733458.73     10052650.89      2733475.76     10052555.03
      2733373.59     10052380.84      2733198.47     10052363.73

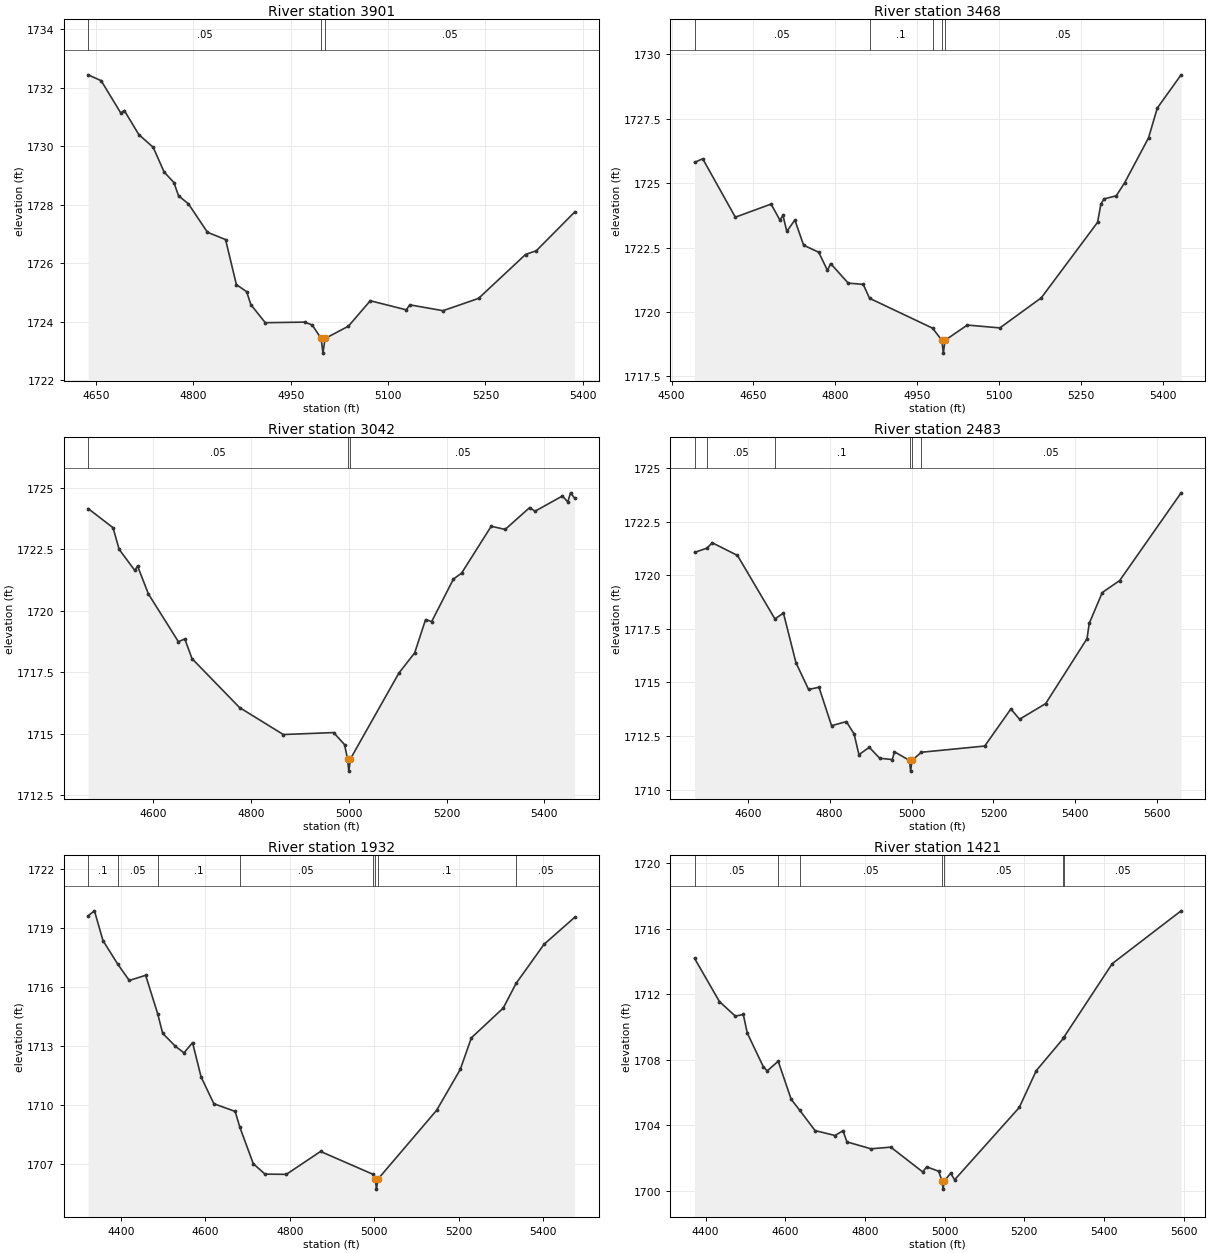
Type RM Length L Ch R = 1,3901,433,433,433
BEGIN DESCRIPTION:
UNT 0012 IN HEWA 8.0
END DESCRIPTION:
XS GIS Cut Line= 2
      2735116.41     10055415.09      2734447.56     10055753.75
#Sta/Elev= 30
  4637.8 1732.44  4657.9 1732.24  4688.0 1731.14  4693.6 1731.22  4715.9 1730.40
  4738.2 1729.96  4754.9 1729.12  4770.0 1728.76  4777.1 1728.31  4792.4 1728.03
  4821.7 1727.06  4849.6 1726.81  4866.3 1725.27  4882.1 1725.03  4888.5 1724.59
  4910.8 1723.97  4971.8 1723.99  4983.2 1723.89  4996.9 1723.43  4999.7 1722.93
  5002.9 1723.43  5038.9 1723.85  5072.6 1724.72  5128.0 1724.41  5133.6 1724.58
  5184.7 1724.38  5239.4 1724.80  5311.8 1726.30  5328.5 1726.43  5387.5 1727.75
#Mann=3,-1,0
  4637.8    0.05       0  4996.9   0.035       0  5002.9    0.05       0
Bank Sta=4996.9,5002.9
Exp/Cntr=0.3,0.1

Type RM Length L Ch R = 1,3468,426,426,426
BEGIN DESCRIPTION:
UNT 0012 IN HEWA 7.0
END DESCRIPTION:
XS GIS Cut Line= 2
      2734976.77     10054991.73      2734194.11     10055419.01
#Sta/Elev= 30
  4542.3 1725.81  4557.2 1725.95  4617.0 1723.68  4682.5 1724.19  4698.6 1723.57
  4704.3 1723.75  4711.3 1723.13  4726.1 1723.57  4742.2 1722.59  4769.8 1722.32
  4785.9 1721.61  4791.6 1721.88  4823.9 1721.12  4851.4 1721.07  4863.0 1720.53
  4978.5 1719.37  4995.5 1718.90  4998.2 1718.40  5001.5 1718.90  5042.1 1719.49
  5101.9 1719.38  5177.8 1720.55  5280.9 1723.48  5287.0 1724.19  5292.7 1724.39
  5315.1 1724.51  5330.6 1725.02  5374.3 1726.76  5390.4 1727.92  5434.0 1729.21
#Mann=5,-1,0
  4542.3    0.05       0  4863.0     0.1       0  4978.5    0.05       0
  4995.5   0.035       0  5001.5    0.05       0
Bank Sta=4995.5,5001.5
Exp/Cntr=0.3,0.1

Type RM Length L Ch R = 1,3042,559,559,559
BEGIN DESCRIPTION:
UNT 0012 IN HEWA 6.0
END DESCRIPTION:
XS GIS Cut Line= 2
      2734875.15     10054593.80      2733986.09     10055042.56
#Sta/Elev= 30
  4466.2 1724.16  4517.2 1723.38  4529.7 1722.50  4561.8 1721.64  4567.4 1721.82
  4589.7 1720.68  4651.0 1718.74  4664.1 1718.85  4678.9 1718.05  4776.1 1716.06
  4865.7 1714.96  4968.8 1715.04  4991.1 1714.55  4997.2 1713.97  4999.9 1713.47
  5003.2 1713.97  5102.6 1717.47  5134.6 1718.28  5157.0 1719.64  5169.5 1719.56
  5214.0 1721.29  5230.7 1721.53  5291.4 1723.44  5319.9 1723.31  5370.1 1724.20
  5381.0 1724.05  5437.0 1724.67  5448.1 1724.43  5453.7 1724.80  5462.1 1724.58
#Mann=3,-1,0
  4466.2    0.05       0  4997.2   0.035       0  5003.2    0.05       0
Bank Sta=4997.2,5003.2
Exp/Cntr=0.3,0.1

Type RM Length L Ch R = 1,2483,551,551,551
BEGIN DESCRIPTION:
UNT 0012 IN HEWA 5.0
END DESCRIPTION:
XS GIS Cut Line= 2
      2734654.97     10054204.35      2733537.42     10054606.50
#Sta/Elev= 30
  4470.3 1721.06  4500.2 1721.26  4513.6 1721.51  4575.0 1720.92  4666.4 1717.96
  4687.2 1718.23  4717.9 1715.91  4748.6 1714.67  4774.0 1714.77  4804.7 1712.98
  4840.8 1713.17  4859.8 1712.59  4871.5 1711.63  4896.9 1711.97  4922.3 1711.46
  4953.0 1711.40  4958.3 1711.76  4995.0 1711.36  4997.7 1710.86  5001.0 1711.36
  5023.8 1711.74  5178.6 1712.03  5242.4 1713.76  5263.7 1713.28  5327.4 1714.01
  5428.4 1717.04  5433.7 1717.75  5465.6 1719.19  5508.1 1719.75  5658.0 1723.84
#Mann=6,-1,0
  4470.3     0.1       0  4500.2    0.05       0  4666.4     0.1       0
  4995.0    0.07       0  5001.0     0.1       0  5023.8    0.05       0
Bank Sta=4995,5001
Exp/Cntr=0.3,0.1

Type RM Length L Ch R = 1,1932,511,511,511
BEGIN DESCRIPTION:
UNT 0012 IN HEWA 4.0
END DESCRIPTION:
XS GIS Cut Line= 3
      2734553.37     10053971.50      2734028.47     10053899.54
      2733418.82     10054022.31
#Sta/Elev= 30
  4322.8 1719.61  4337.8 1719.86  4358.0 1718.35  4392.9 1717.16  4420.2 1716.33
  4459.0 1716.59  4487.5 1714.64  4499.3 1713.65  4529.6 1712.99  4549.8 1712.66
  4570.0 1713.18  4590.2 1711.44  4620.5 1710.08  4670.9 1709.69  4682.1 1708.88
  4713.8 1707.04  4741.6 1706.51  4792.1 1706.50  4873.0 1707.66  4996.3 1706.51
  5002.6 1706.25  5005.4 1705.75  5008.6 1706.25  5147.9 1709.75  5203.8 1711.82
  5230.0 1713.42  5305.5 1714.93  5335.9 1716.18  5402.0 1718.16  5474.5 1719.53
#Mann=8,-1,0
  4322.8     0.1       0  4392.9    0.05       0  4487.5     0.1       0
  4682.1    0.05       0  4996.3     0.1       0  5002.6    0.07       0
  5008.6     0.1       0  5335.9    0.05       0
Bank Sta=5002.6,5008.6
Exp/Cntr=0.3,0.1

Type RM Length L Ch R = 1,1421,586,586,586
BEGIN DESCRIPTION:
UNT 0012 IN HEWA 3.0
END DESCRIPTION:
XS GIS Cut Line= 3
      2734430.67     10053467.73      2733706.73     10053433.87
      2733355.39     10053785.21
#Sta/Elev= 30
  4372.2 1714.19  4434.5 1711.56  4474.5 1710.67  4494.5 1710.77  4504.5 1709.64
  4544.6 1707.59  4554.6 1707.33  4582.2 1707.92  4614.7 1705.60  4636.2 1704.93
  4674.7 1703.69  4724.8 1703.39  4744.8 1703.68  4754.8 1703.00  4814.9 1702.58
  4864.9 1702.68  4945.0 1701.17  4955.0 1701.48  4985.1 1701.21  4993.4 1700.62
  4996.2 1700.12  4999.4 1700.62  5015.1 1701.09  5025.1 1700.69  5187.5 1705.10
  5230.0 1707.34  5298.5 1709.32  5300.2 1709.41  5420.9 1713.87  5593.8 1717.09
#Mann=7,-1,0
  4372.2    0.05       0  4582.2     0.1       0  4636.2    0.05       0
  4993.4   0.035       0  4999.4    0.05       0  5298.5     0.1       0
  5300.2    0.05       0
Bank Sta=4993.4,4999.4
Exp/Cntr=0.3,0.1

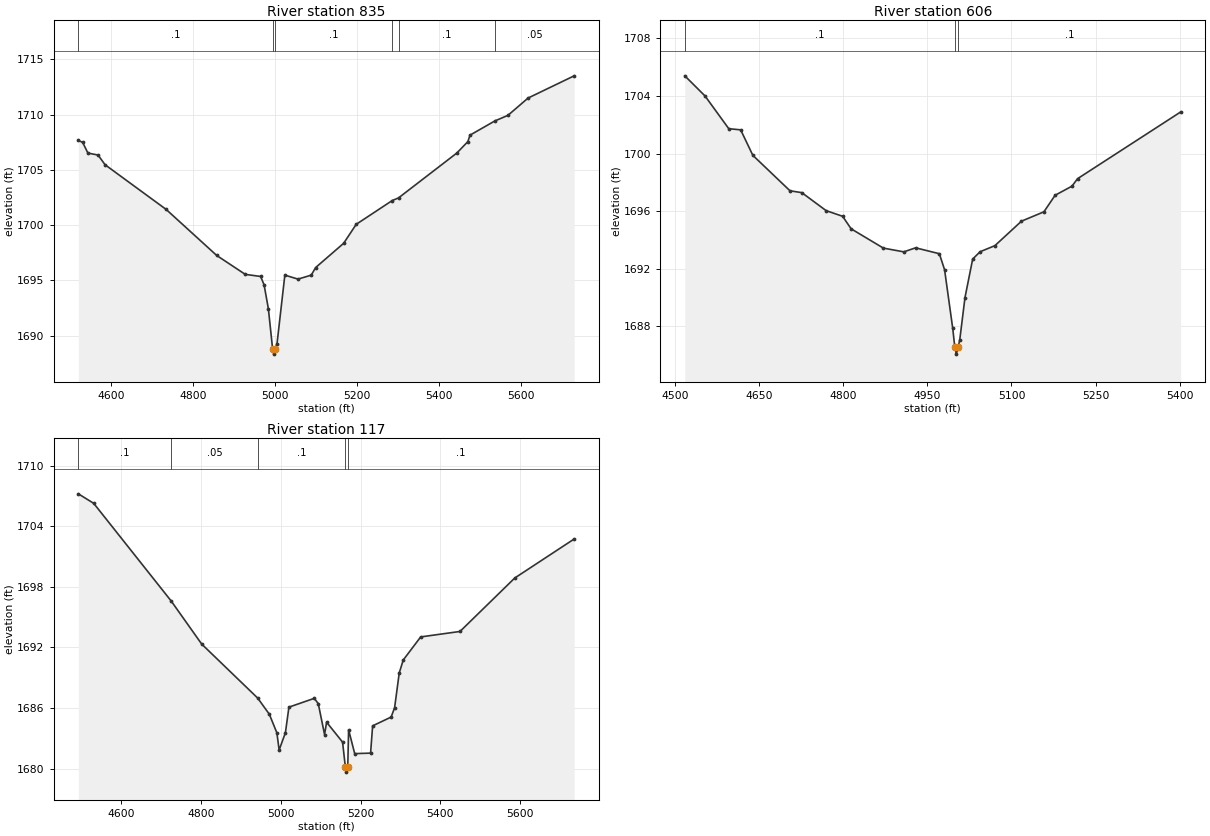
Type RM Length L Ch R = 1,835,229,229,229
BEGIN DESCRIPTION:
UNT 0012 IN HEWA 2.0
END DESCRIPTION:
XS GIS Cut Line= 3
      2734070.80     10052794.63      2733499.30     10052976.66
      2733368.05     10053573.61
#Sta/Elev= 30
  4519.8 1707.68  4530.4 1707.49  4543.2 1706.53  4567.9 1706.35  4585.2 1705.47
  4734.2 1701.43  4857.8 1697.26  4927.5 1695.55  4965.0 1695.36  4973.5 1694.60
  4984.0 1692.43  4994.2 1688.83  4996.9 1688.33  5000.2 1688.83  5005.0 1689.25
  5024.2 1695.48  5056.4 1695.12  5088.6 1695.48  5099.5 1696.17  5167.8 1698.36
  5198.5 1700.08  5286.4 1702.23  5301.8 1702.47  5444.2 1706.53  5471.3 1707.57
  5476.4 1708.15  5537.3 1709.44  5569.0 1709.94  5618.3 1711.51  5730.8 1713.52
#Mann=6,-1,0
  4519.8     0.1       0  4994.2    0.07       0  5000.2     0.1       0
  5286.4    0.16       0  5301.8     0.1       0  5537.3    0.05       0
Bank Sta=4994.2,5000.2
Exp/Cntr=0.3,0.1

Type RM Length L Ch R = 1,606,489,489,489
BEGIN DESCRIPTION:
Mapping XS 5b35a802
END DESCRIPTION:
XS GIS Cut Line= 3
      2733890.64     10052507.18      2733427.10     10052804.05
      2733435.78     10053137.38
#Sta/Elev= 30
  4517.6 1705.40  4553.7 1704.00  4596.0 1701.73  4617.2 1701.65  4638.9 1699.88
  4705.1 1697.42  4726.2 1697.29  4769.6 1696.04  4798.9 1695.65  4814.1 1694.78
  4871.6 1693.44  4908.0 1693.18  4929.1 1693.46  4971.4 1693.05  4980.7 1691.94
  4995.2 1687.88  4998.9 1686.58  5001.6 1686.08  5004.9 1686.58  5007.8 1687.08
  5017.1 1690.01  5030.8 1692.68  5044.1 1693.19  5070.4 1693.61  5117.8 1695.31
  5157.8 1695.96  5177.8 1697.11  5207.8 1697.74  5217.8 1698.26  5401.5 1702.89
#Mann=3,-1,0
  4517.6     0.1       0  4998.9    0.07       0  5004.9     0.1       0
Bank Sta=4998.9,5004.9
Exp/Cntr=0.3,0.1

Type RM Length L Ch R = 1,117,0,0,0
BEGIN DESCRIPTION:
UNT 0012 IN HEWA 1.0
END DESCRIPTION:
XS GIS Cut Line= 4
      2733781.23     10052218.99      2733324.67     10052340.51
      2733300.37     10052403.01      2733418.42     10053095.70
#Sta/Elev= 30
  4493.0 1707.20  4531.5 1706.26  4725.5 1696.60  4802.1 1692.33  4942.3 1686.99
  4971.5 1685.39  4990.4 1683.55  4996.1 1681.85  5011.8 1683.56  5020.6 1686.09
  5084.0 1686.96  5094.1 1686.44  5109.9 1683.38  5115.0 1684.60  5155.0 1682.63
  5162.0 1680.16  5164.8 1679.66  5168.0 1680.16  5170.1 1683.85  5185.4 1681.49
  5225.2 1681.54  5230.3 1684.24  5276.7 1685.11  5285.4 1686.04  5297.0 1689.48
  5307.1 1690.76  5350.7 1693.04  5449.2 1693.58  5586.4 1698.87  5735.2 1702.73
#Mann=5,-1,0
  4493.0     0.1       0  4725.5    0.05       0  4942.3     0.1       0
  5162.0    0.07       0  5168.0     0.1       0
Bank Sta=5162,5168
Exp/Cntr=0.3,0.1

Chan Stop Cuts=-1