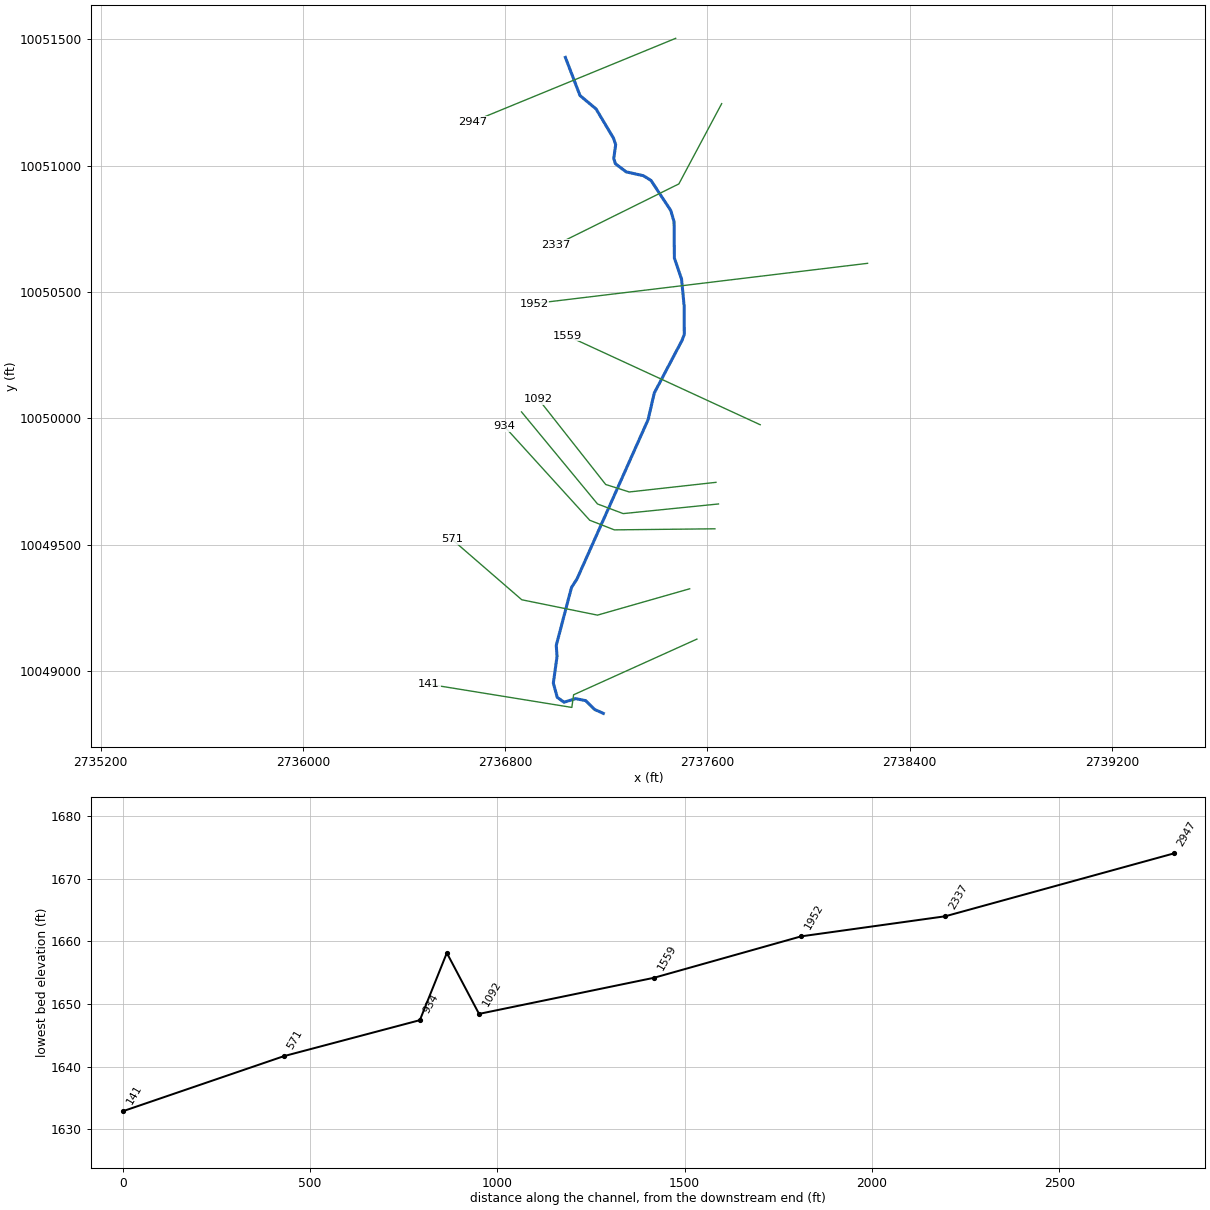
--- UNT 0013 IN HEWA.prj (project) ---

Proj Title=UNT 0013 IN HEWA Base Level Engineering
Current Plan=p01
Default Exp/Contr=0.3,0.1
English Units
Geom File=g01
Flow File=f01
Plan File=p01
BEGIN DESCRIPTION:
UNT 0013 IN HEWA
END DESCRIPTION:

--- UNT 0013 IN HEWA.p01 (plan) ---

Plan Title=Multiple Run
Short Identifier=Multiple
Geom File=g01
Flow File=f01
Subcritical Flow
K Sum by GR= 0
Std Step Tol= 0.01
Critical Tol= 0.01
Num of Std Step Trials= 20
Max Error Tol= 0.3
Flow Tol Ratio= 0.001
Split Flow NTrial= 30
Split Flow Tol= 0.02
Split Flow Ratio= 0.02
Log Output Level= 0
Friction Slope Method= 1
Unsteady Friction Slope Method= 2
Unsteady Bridges Friction Slope Method= 1
Parabolic Critical Depth
Global Vel Dist=  1 , 1 , 1
Global Log Level= 0
CheckData=True
Encroach Param= -1, 0, 0, 0
BEGIN DESCRIPTION:
Multiple Run
END DESCRIPTION:

--- UNT 0013 IN HEWA.f01 (steady flow) ---

Flow Title=Multiple
Number of Profiles=7
Profile Names=10-year,25-year,50-year,1pct_min,100-year,1pct_plu,500-year
River Rch & RM= UNT 0013 IN HEWA,Reach-1,2947
     609     864    1079     988    1336    1806    2053
Boundary for River Rch & Prof#=UNT 0013 IN HEWA,Reach-1,1
Up Type=0
Dn Type=3
Dn Slope=0.005
Boundary for River Rch & Prof#=UNT 0013 IN HEWA,Reach-1,2
Up Type=0
Dn Type=3
Dn Slope=0.005
Boundary for River Rch & Prof#=UNT 0013 IN HEWA,Reach-1,3
Up Type=0
Dn Type=3
Dn Slope=0.005
Boundary for River Rch & Prof#=UNT 0013 IN HEWA,Reach-1,4
Up Type=0
Dn Type=3
Dn Slope=0.005
Boundary for River Rch & Prof#=UNT 0013 IN HEWA,Reach-1,5
Up Type=0
Dn Type=3
Dn Slope=0.005
Boundary for River Rch & Prof#=UNT 0013 IN HEWA,Reach-1,6
Up Type=0
Dn Type=3
Dn Slope=0.005
Boundary for River Rch & Prof#=UNT 0013 IN HEWA,Reach-1,7
Up Type=0
Dn Type=3
Dn Slope=0.005

--- UNT 0013 IN HEWA.g01 (geometry) ---

Geom Title=Existing Conditions

River Reach=UNT 0013 IN HEWA,Reach-1
Reach XY= 30
      2737038.30     10051428.03      2737096.18     10051277.15
      2737159.75     10051224.09      2737228.50     10051108.70
      2737237.27     10051083.28      2737229.75     10051028.44
      2737236.17     10051007.38      2737278.86     10050975.32
      2737347.08     10050960.06      2737377.01     10050941.40
      2737455.19     10050822.38      2737468.06     10050778.56
      2737469.44     10050634.14      2737497.81     10050551.11
      2737508.09     10050444.17      2737508.63     10050332.76
      2737499.76     10050309.07      2737389.84     10050100.71
      2737365.60     10049995.76      2737084.31     10049365.44
      2737062.57     10049331.97      2737002.23     10049102.54
      2737005.42     10049059.32      2736990.63     10048953.46
      2737006.19     10048896.95      2737033.10     10048877.89
      2737078.81     10048892.01      2737118.55     10048884.11
      2737154.30     10048848.96      2737188.47     10048833.73

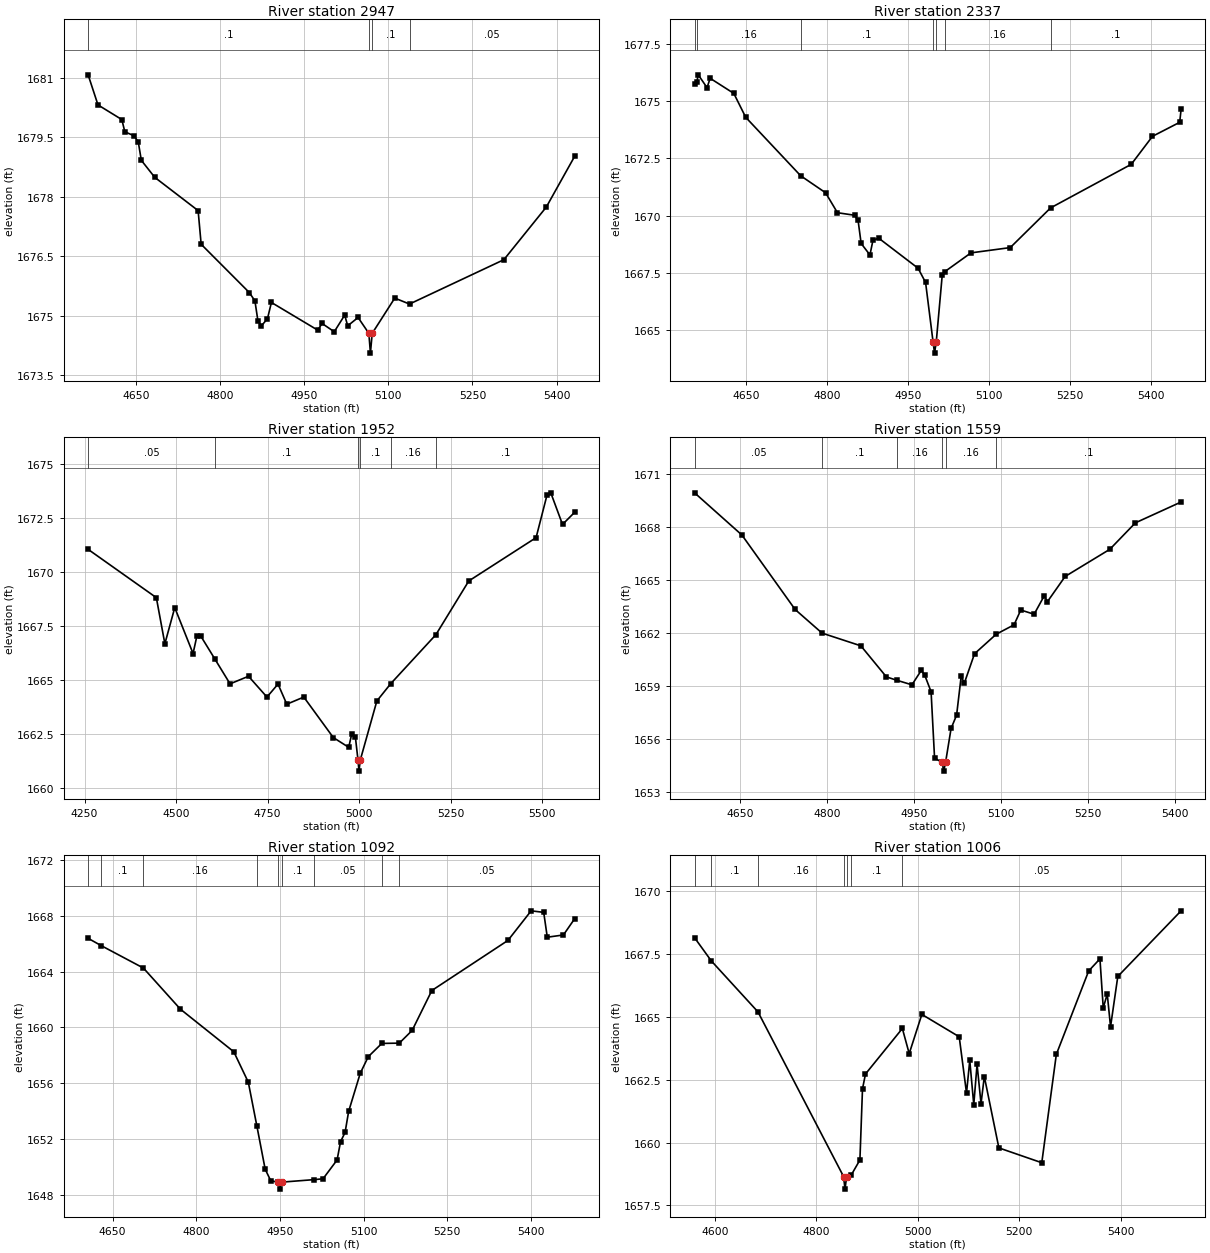
Type RM Length L Ch R = 1,2947,610,610,610
BEGIN DESCRIPTION:
UNT 0013 IN HEWA 6.0
END DESCRIPTION:
XS GIS Cut Line= 2
      2737474.43     10051503.46      2736671.74     10051173.93
#Sta/Elev= 30
  4564.6 1681.08  4582.2 1680.32  4624.7 1679.95  4630.1 1679.64  4646.7 1679.54
  4654.1 1679.38  4659.5 1678.92  4683.5 1678.49  4760.8 1677.65  4766.2 1676.80
  4852.1 1675.58  4862.1 1675.37  4867.5 1674.86  4873.7 1674.74  4884.5 1674.92
  4891.5 1675.33  4974.2 1674.63  4981.8 1674.80  5003.6 1674.59  5022.2 1675.01
  5027.6 1674.74  5046.1 1674.95  5065.3 1674.55  5068.1 1674.05  5071.3 1674.55
  5111.5 1675.44  5137.8 1675.29  5306.1 1676.41  5381.8 1677.74  5432.3 1679.02
#Mann=4,-1,0
  4564.6     0.1       0  5065.3    0.07       0  5071.3     0.1       0
  5137.8    0.05       0
Bank Sta=5065.3,5071.3
Exp/Cntr=0.3,0.1

Type RM Length L Ch R = 1,2337,385,385,385
BEGIN DESCRIPTION:
UNT 0013 IN HEWA 5.0
END DESCRIPTION:
XS GIS Cut Line= 3
      2737656.45     10051245.20      2737487.12     10050927.72
      2737001.88     10050687.20
#Sta/Elev= 30
  4555.0 1675.73  4559.0 1675.82  4561.8 1676.14  4578.1 1675.58  4583.8 1675.99
  4627.7 1675.33  4649.7 1674.29  4751.6 1671.74  4797.7 1671.00  4819.7 1670.13
  4851.3 1670.02  4857.9 1669.80  4863.6 1668.79  4879.9 1668.29  4885.5 1668.93
  4896.2 1669.02  4969.1 1667.71  4983.0 1667.09  4996.8 1664.51  4999.6 1664.01
  5002.8 1664.51  5013.8 1667.40  5018.5 1667.56  5067.1 1668.38  5139.9 1668.61
  5214.6 1670.34  5364.1 1672.24  5403.4 1673.46  5453.8 1674.07  5456.4 1674.63
#Mann=7,-1,0
  4555.0     0.1       0  4559.0    0.16       0  4751.6     0.1       0
  4996.8    0.07       0  5002.8     0.1       0  5018.5    0.16       0
  5214.6     0.1       0
Bank Sta=4996.8,5002.8
Exp/Cntr=0.3,0.1

Type RM Length L Ch R = 1,1952,393,393,393
BEGIN DESCRIPTION:
UNT 0013 IN HEWA 4.0
END DESCRIPTION:
XS GIS Cut Line= 2
      2738233.50     10050613.64      2736913.88     10050454.38
#Sta/Elev= 30
  4259.6 1671.04  4446.0 1668.81  4469.3 1666.68  4496.3 1668.35  4546.3 1666.23
  4556.8 1667.04  4566.9 1667.05  4605.4 1665.99  4647.4 1664.83  4697.8 1665.18
  4748.2 1664.22  4778.4 1664.82  4802.4 1663.89  4848.9 1664.22  4929.5 1662.35
  4971.5 1661.90  4979.8 1662.51  4989.9 1662.36  4997.0 1661.30  4999.7 1660.80
  5003.0 1661.30  5048.5 1664.04  5086.5 1664.84  5209.8 1667.10  5299.6 1669.58
  5483.5 1671.58  5513.7 1673.57  5523.7 1673.65  5555.7 1672.19  5588.8 1672.75
#Mann=6,-1,0
  4259.6    0.05       0  4605.4     0.1       0  4997.0    0.07       0
  5003.0     0.1       0  5086.5    0.16       0  5209.8     0.1       0
Bank Sta=4997,5003
Exp/Cntr=0.3,0.1

Type RM Length L Ch R = 1,1559,467,467,467
BEGIN DESCRIPTION:
UNT 0013 IN HEWA 3.0
END DESCRIPTION:
XS GIS Cut Line= 2
      2737808.87     10049975.20      2737046.88     10050326.57
#Sta/Elev= 30
  4571.9 1669.95  4653.5 1667.56  4745.3 1663.34  4791.8 1662.00  4858.7 1661.28
  4902.7 1659.52  4920.6 1659.33  4946.8 1659.07  4962.9 1659.89  4968.8 1659.62
  4979.8 1658.68  4985.8 1654.92  4998.8 1654.68  5001.6 1654.18  5004.8 1654.68
  5014.3 1656.60  5023.8 1657.35  5031.7 1659.55  5037.2 1659.17  5054.7 1660.83
  5092.2 1661.94  5122.9 1662.47  5134.5 1663.31  5157.5 1663.07  5174.9 1664.11
  5180.4 1663.78  5211.0 1665.21  5288.1 1666.75  5332.2 1668.25  5411.0 1669.43
#Mann=6,-1,0
  4571.9    0.05       0  4791.8     0.1       0  4920.6    0.16       0
  4998.8    0.07       0  5004.8    0.16       0  5092.2     0.1       0
Bank Sta=4998.8,5004.8
Exp/Cntr=0.3,0.1

Type RM Length L Ch R = 1,1092,86,86,86
BEGIN DESCRIPTION:
Mapping XS a6e8b5d4
END DESCRIPTION:
XS GIS Cut Line= 4
      2737633.80     10049747.47      2737290.86     10049709.36
      2737197.73     10049739.00      2736932.24     10050076.13
#Sta/Elev= 30
  4606.3 1666.38  4629.6 1665.86  4705.4 1664.25  4771.8 1661.30  4867.4 1658.25
  4893.4 1656.07  4908.8 1652.92  4923.6 1649.84  4933.6 1649.01  4947.0 1648.91
  4949.8 1648.41  4953.0 1648.91  5011.1 1649.09  5027.3 1649.15  5052.5 1650.50
  5058.7 1651.81  5066.8 1652.47  5073.2 1653.98  5094.0 1656.71  5108.4 1657.90
  5132.7 1658.85  5164.0 1658.87  5187.0 1659.78  5222.3 1662.64  5358.7 1666.23
  5400.3 1668.35  5422.8 1668.24  5429.2 1666.46  5458.1 1666.62  5478.2 1667.78
#Mann=9,-1,0
  4606.3    0.05       0  4629.6     0.1       0  4705.4    0.16       0
  4908.8     0.1       0  4947.0    0.07       0  4953.0     0.1       0
  5011.1    0.05       0  5132.7     0.1       0  5164.0    0.05       0
Bank Sta=4947,4953
Exp/Cntr=0.3,0.1

Type RM Length L Ch R = 1,1006,72,72,72
BEGIN DESCRIPTION:
Mapping XS c60c591d
END DESCRIPTION:
XS GIS Cut Line= 4
      2737643.79     10049661.94      2737266.99     10049623.84
      2737165.39     10049661.94      2736864.84     10050025.98
#Sta/Elev= 30
  4559.8 1668.15  4592.7 1667.23  4684.8 1665.20  4853.6 1658.65  4856.4 1658.15
  4859.6 1658.65  4868.4 1658.70  4885.8 1659.31  4890.9 1662.14  4896.8 1662.73
  4969.5 1664.54  4983.0 1663.54  5007.9 1665.10  5081.6 1664.21  5096.0 1661.97
  5102.4 1663.27  5110.3 1661.51  5116.8 1663.11  5124.6 1661.55  5131.1 1662.63
  5159.8 1659.79  5244.4 1659.20  5273.1 1663.51  5336.9 1666.83  5359.1 1667.31
  5365.6 1665.36  5373.5 1665.91  5380.0 1664.61  5394.3 1666.61  5519.1 1669.22
#Mann=7,-1,0
  4559.8    0.05       0  4592.7     0.1       0  4684.8    0.16       0
  4853.6   0.035       0  4859.6    0.16       0  4868.4     0.1       0
  4969.5    0.05       0
Bank Sta=4853.6,4859.6
Exp/Cntr=0.3,0.1

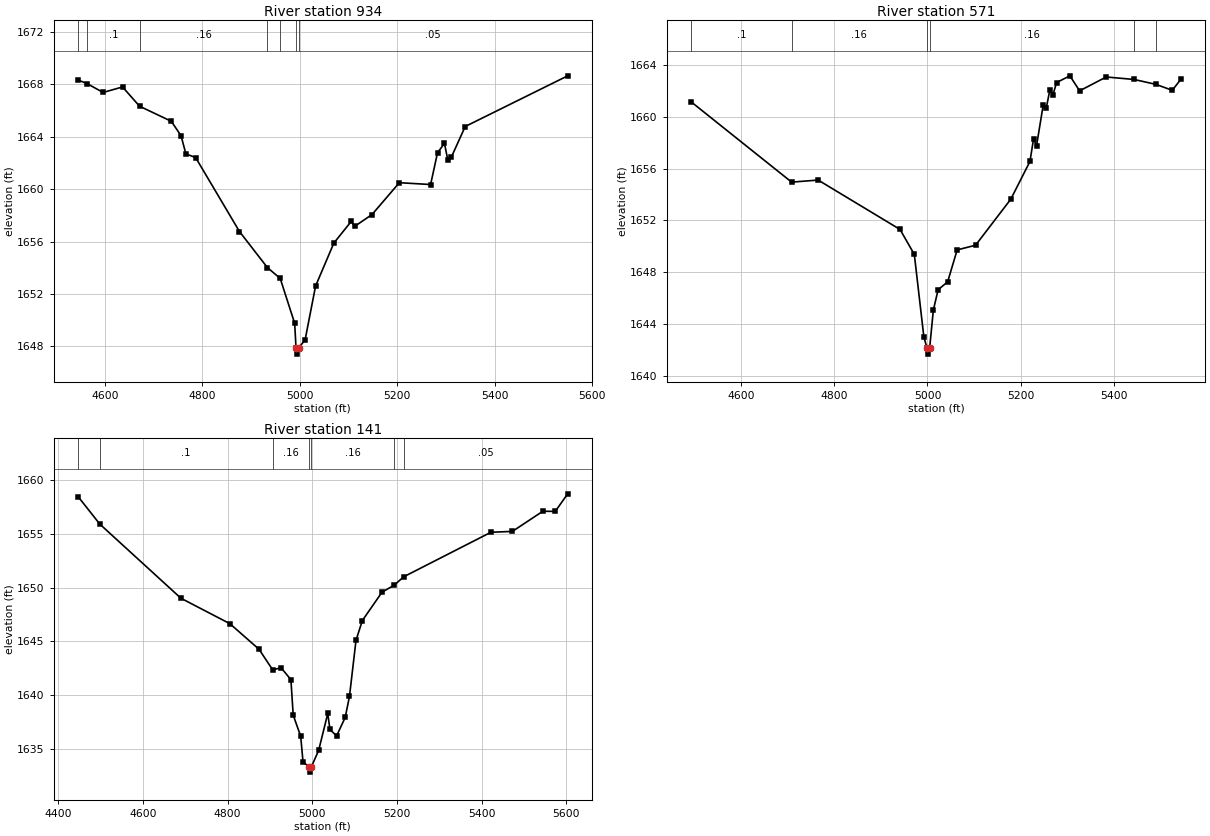
Type RM Length L Ch R = 1,934,363,363,363
BEGIN DESCRIPTION:
UNT 0013 IN HEWA 2.0
END DESCRIPTION:
XS GIS Cut Line= 4
      2737629.89     10049563.72      2737231.93     10049559.49
      2737134.56     10049597.59      2736796.50     10049969.45
#Sta/Elev= 30
  4545.1 1668.34  4563.5 1668.07  4596.5 1667.39  4636.5 1667.81  4671.4 1666.34
  4736.5 1665.19  4756.5 1664.09  4766.5 1662.70  4786.5 1662.42  4876.5 1656.77
  4933.8 1654.02  4960.1 1653.19  4989.8 1649.76  4992.5 1647.91  4995.3 1647.41
  4998.5 1647.91  5011.2 1648.50  5032.7 1652.61  5070.2 1655.89  5106.0 1657.55
  5112.7 1657.16  5148.6 1658.07  5204.6 1660.50  5268.8 1660.36  5283.0 1662.79
  5297.2 1663.50  5304.0 1662.26  5311.4 1662.45  5339.8 1664.79  5550.2 1668.66
#Mann=7,-1,0
  4545.1    0.05       0  4563.5     0.1       0  4671.4    0.16       0
  4933.8     0.1       0  4960.1    0.05       0  4992.5   0.035       0
  4998.5    0.05       0
Bank Sta=4992.5,4998.5
Exp/Cntr=0.3,0.1

Type RM Length L Ch R = 1,571,430,430,430
BEGIN DESCRIPTION:
Mapping XS be4541f9
END DESCRIPTION:
XS GIS Cut Line= 4
      2737529.89     10049326.43      2737165.34     10049222.27
      2736865.86     10049283.04      2736590.28     10049521.72
#Sta/Elev= 30
  4493.9 1661.16  4709.0 1654.96  4765.8 1655.12  4941.3 1651.30  4971.9 1649.37
  4992.3 1643.00  4998.8 1642.16  5001.5 1641.66  5004.8 1642.16  5012.7 1645.07
  5022.9 1646.64  5043.3 1647.25  5063.7 1649.72  5103.1 1650.08  5178.6 1653.64
  5219.7 1656.56  5227.3 1658.29  5233.9 1657.79  5248.2 1660.95  5254.8 1660.71
  5262.4 1662.11  5269.0 1661.71  5276.7 1662.66  5305.2 1663.18  5326.1 1662.02
  5383.1 1663.09  5442.7 1662.90  5489.5 1662.52  5524.6 1662.06  5543.2 1662.92
#Mann=6,-1,0
  4493.9     0.1       0  4709.0    0.16       0  4998.8    0.07       0
  5004.8    0.16       0  5442.7     0.1       0  5489.5    0.05       0
Bank Sta=4998.8,5004.8
Exp/Cntr=0.3,0.1

Type RM Length L Ch R = 1,141,0,0,0
BEGIN DESCRIPTION:
UNT 0013 IN HEWA 1.0
END DESCRIPTION:
XS GIS Cut Line= 4
      2737558.32     10049127.40      2737070.81     10048907.25
      2737063.86     10048857.25      2736499.43     10048948.78
#Sta/Elev= 30
  4446.4 1658.46  4497.8 1655.90  4689.6 1649.01  4805.2 1646.65  4874.2 1644.27
  4906.4 1642.36  4926.3 1642.55  4949.5 1641.45  4954.9 1638.16  4972.6 1636.19
  4978.1 1633.81  4992.0 1633.36  4994.7 1632.86  4998.0 1633.36  5015.2 1634.90
  5036.6 1638.31  5041.7 1636.82  5057.5 1636.23  5077.8 1637.94  5087.9 1639.90
  5103.3 1645.10  5118.3 1646.94  5164.9 1649.58  5193.1 1650.21  5216.3 1651.01
  5422.2 1655.14  5472.9 1655.22  5544.8 1657.09  5574.2 1657.08  5603.6 1658.71
#Mann=7,-1,0
  4446.4    0.05       0  4497.8     0.1       0  4906.4    0.16       0
  4992.0    0.07       0  4998.0    0.16       0  5193.1     0.1       0
  5216.3    0.05       0
Bank Sta=4992,4998
Exp/Cntr=0.3,0.1

Chan Stop Cuts=-1