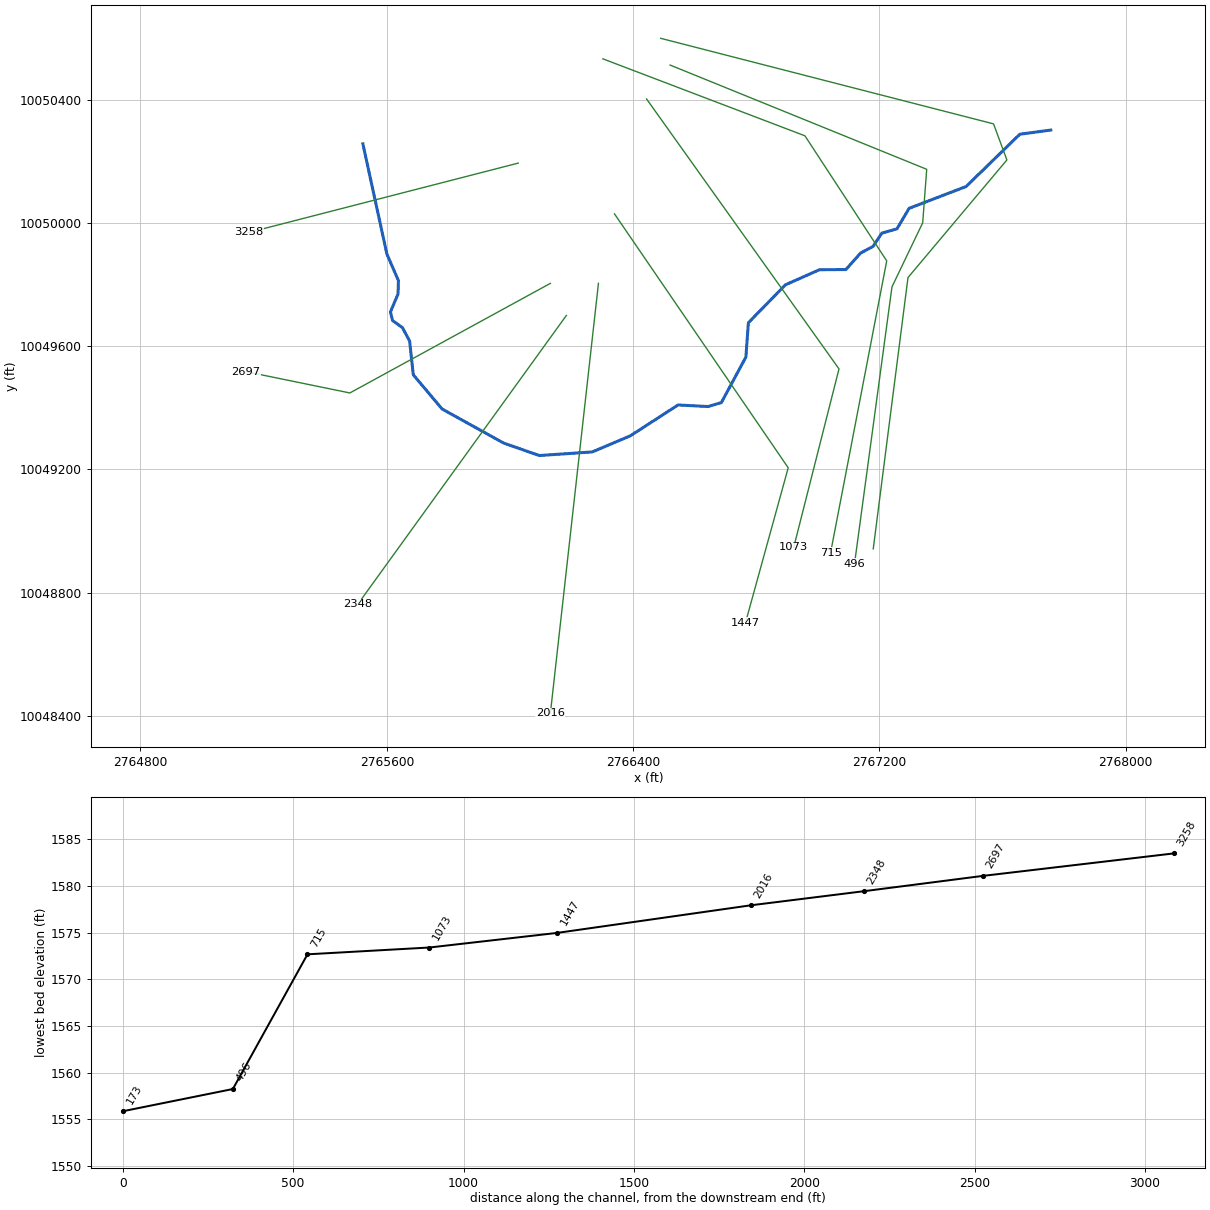
--- UNT 0014 IN HEWA.prj (project) ---

Proj Title=UNT 0014 IN HEWA Base Level Engineering
Current Plan=p01
Default Exp/Contr=0.3,0.1
English Units
Geom File=g01
Flow File=f01
Plan File=p01
BEGIN DESCRIPTION:
UNT 0014 IN HEWA
END DESCRIPTION:

--- UNT 0014 IN HEWA.p01 (plan) ---

Plan Title=Multiple Run
Short Identifier=Multiple
Geom File=g01
Flow File=f01
Subcritical Flow
K Sum by GR= 0
Std Step Tol= 0.01
Critical Tol= 0.01
Num of Std Step Trials= 20
Max Error Tol= 0.3
Flow Tol Ratio= 0.001
Split Flow NTrial= 30
Split Flow Tol= 0.02
Split Flow Ratio= 0.02
Log Output Level= 0
Friction Slope Method= 1
Unsteady Friction Slope Method= 2
Unsteady Bridges Friction Slope Method= 1
Parabolic Critical Depth
Global Vel Dist=  1 , 1 , 1
Global Log Level= 0
CheckData=True
Encroach Param= -1, 0, 0, 0
BEGIN DESCRIPTION:
Multiple Run
END DESCRIPTION:

--- UNT 0014 IN HEWA.f01 (steady flow) ---

Flow Title=Multiple
Number of Profiles=7
Profile Names=10-year,25-year,50-year,1pct_min,100-year,1pct_plu,500-year
River Rch & RM= UNT 0014 IN HEWA,Reach-1,3258
     643     908    1132    1032    1395    1887    2129
Boundary for River Rch & Prof#=UNT 0014 IN HEWA,Reach-1,1
Up Type=0
Dn Type=3
Dn Slope=0.005
Boundary for River Rch & Prof#=UNT 0014 IN HEWA,Reach-1,2
Up Type=0
Dn Type=3
Dn Slope=0.005
Boundary for River Rch & Prof#=UNT 0014 IN HEWA,Reach-1,3
Up Type=0
Dn Type=3
Dn Slope=0.005
Boundary for River Rch & Prof#=UNT 0014 IN HEWA,Reach-1,4
Up Type=0
Dn Type=3
Dn Slope=0.005
Boundary for River Rch & Prof#=UNT 0014 IN HEWA,Reach-1,5
Up Type=0
Dn Type=3
Dn Slope=0.005
Boundary for River Rch & Prof#=UNT 0014 IN HEWA,Reach-1,6
Up Type=0
Dn Type=3
Dn Slope=0.005
Boundary for River Rch & Prof#=UNT 0014 IN HEWA,Reach-1,7
Up Type=0
Dn Type=3
Dn Slope=0.005

--- UNT 0014 IN HEWA.g01 (geometry) ---

Geom Title=Existing Conditions

River Reach=UNT 0014 IN HEWA,Reach-1
Reach XY= 30
      2765522.26     10050257.32      2765600.23     10049899.46
      2765637.75     10049813.15      2765636.42     10049769.76
      2765611.89     10049711.72      2765618.47     10049683.73
      2765650.61     10049660.63      2765674.15     10049616.67
      2765685.94     10049507.40      2765779.48     10049396.28
      2765979.27     10049285.67      2766095.35     10049245.09
      2766267.20     10049256.80      2766390.95     10049309.11
      2766545.76     10049409.32      2766643.44     10049404.23
      2766686.52     10049417.00      2766766.16     10049564.74
      2766774.31     10049676.43      2766894.57     10049799.54
      2767005.26     10049848.63      2767090.90     10049849.09
      2767138.90     10049902.86      2767179.22     10049924.23
      2767207.60     10049967.42      2767256.96     10049981.33
      2767296.17     10050047.88      2767481.36     10050118.75
      2767655.87     10050288.60      2767756.41     10050302.14

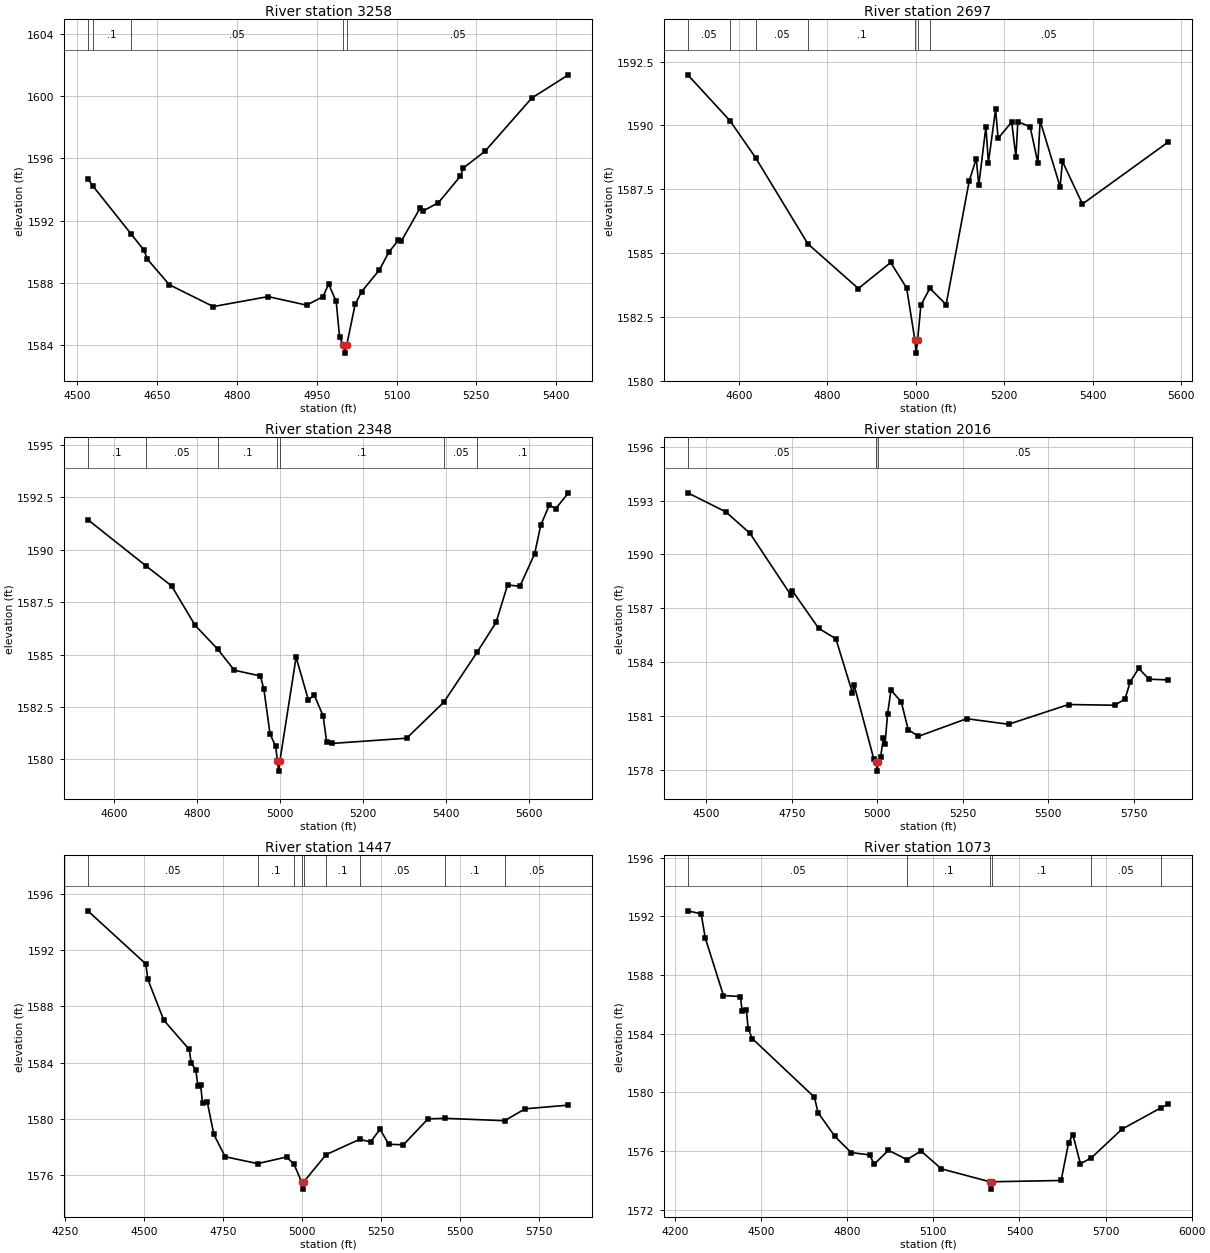
Type RM Length L Ch R = 1,3258,561,561,561
BEGIN DESCRIPTION:
UNT 0014 IN HEWA 7.0
END DESCRIPTION:
XS GIS Cut Line= 2
      2766026.89     10050194.86      2765151.82     10049969.60
#Sta/Elev= 30
  4519.5 1594.69  4529.3 1594.21  4600.4 1591.16  4625.3 1590.09  4631.5 1589.52
  4672.8 1587.88  4755.4 1586.48  4858.6 1587.12  4930.9 1586.57  4961.9 1587.12
  4972.2 1587.93  4986.5 1586.81  4992.9 1584.52  5000.2 1583.99  5002.9 1583.49
  5006.2 1583.99  5022.1 1586.62  5034.2 1587.43  5067.9 1588.84  5085.8 1589.99
  5103.5 1590.74  5108.6 1590.66  5144.2 1592.80  5149.4 1592.61  5178.7 1593.15
  5220.0 1594.85  5225.6 1595.38  5266.3 1596.45  5354.3 1599.87  5423.1 1601.36
#Mann=5,-1,0
  4519.5    0.05       0  4529.3     0.1       0  4600.4    0.05       0
  5000.2   0.035       0  5006.2    0.05       0
Bank Sta=5000.2,5006.2
Exp/Cntr=0.3,0.1

Type RM Length L Ch R = 1,2697,349,349,349
BEGIN DESCRIPTION:
UNT 0014 IN HEWA 6.0
END DESCRIPTION:
XS GIS Cut Line= 3
      2766131.07     10049804.24      2765480.04     10049448.34
      2765142.43     10049517.59
#Sta/Elev= 30
  4484.5 1591.98  4580.1 1590.18  4638.0 1588.73  4756.1 1585.36  4870.2 1583.61
  4943.3 1584.63  4979.4 1583.63  4998.2 1581.58  5000.9 1581.08  5004.2 1581.58
  5011.6 1582.96  5031.9 1583.62  5068.7 1582.98  5120.7 1587.81  5136.8 1588.70
  5142.5 1587.66  5158.6 1589.94  5164.3 1588.54  5180.5 1590.63  5186.2 1589.49
  5216.9 1590.13  5226.5 1588.76  5230.8 1590.15  5258.7 1589.94  5276.1 1588.53
  5281.2 1590.18  5326.5 1587.59  5331.6 1588.59  5376.9 1586.92  5571.1 1589.35
#Mann=7,-1,0
  4484.5    0.05       0  4580.1     0.1       0  4638.0    0.05       0
  4756.1     0.1       0  4998.2    0.07       0  5004.2     0.1       0
  5031.9    0.05       0
Bank Sta=4998.2,5004.2
Exp/Cntr=0.3,0.1

Type RM Length L Ch R = 1,2348,332,332,332
BEGIN DESCRIPTION:
UNT 0014 IN HEWA 5.0
END DESCRIPTION:
XS GIS Cut Line= 2
      2766183.15     10049700.06      2765506.09     10048762.59
#Sta/Elev= 30
  4537.6 1591.43  4678.1 1589.22  4739.3 1588.27  4795.8 1586.39  4850.0 1585.26
  4890.2 1584.25  4952.8 1583.98  4961.3 1583.34  4976.0 1581.22  4989.5 1580.62
  4993.9 1579.94  4996.7 1579.44  4999.9 1579.94  5038.8 1584.87  5068.1 1582.85
  5082.8 1583.05  5103.7 1582.08  5112.2 1580.85  5125.2 1580.76  5304.8 1581.01
  5394.4 1582.73  5474.7 1585.12  5519.9 1586.53  5547.7 1588.32  5577.2 1588.25
  5612.7 1589.80  5627.4 1591.16  5648.3 1592.14  5663.0 1591.94  5694.0 1592.71
#Mann=7,-1,0
  4537.6     0.1       0  4678.1    0.05       0  4850.0     0.1       0
  4993.9    0.07       0  4999.9     0.1       0  5394.4    0.05       0
  5474.7     0.1       0
Bank Sta=4993.9,4999.9
Exp/Cntr=0.3,0.1

Type RM Length L Ch R = 1,2016,569,569,569
BEGIN DESCRIPTION:
UNT 0014 IN HEWA 4.0
END DESCRIPTION:
XS GIS Cut Line= 2
      2766287.33     10049804.29      2766131.19     10048407.69
#Sta/Elev= 30
  4445.9 1593.43  4557.1 1592.37  4627.6 1591.18  4747.0 1587.75  4752.0 1587.97
  4828.8 1585.88  4879.1 1585.30  4927.6 1582.28  4932.6 1582.71  4989.8 1578.61
  4996.9 1578.43  4999.6 1577.93  5002.9 1578.43  5009.9 1578.72  5017.8 1579.76
  5022.9 1579.46  5030.1 1581.10  5040.1 1582.44  5070.3 1581.79  5090.4 1580.24
  5120.6 1579.87  5261.5 1580.85  5384.0 1580.54  5559.5 1581.64  5694.2 1581.60
  5724.4 1581.94  5740.1 1582.92  5764.6 1583.65  5794.8 1583.05  5851.2 1583.01
#Mann=3,-1,0
  4445.9    0.05       0  4996.9   0.035       0  5002.9    0.05       0
Bank Sta=4996.9,5002.9
Exp/Cntr=0.3,0.1

Type RM Length L Ch R = 1,1447,374,374,374
BEGIN DESCRIPTION:
UNT 0014 IN HEWA 3.0
END DESCRIPTION:
XS GIS Cut Line= 3
      2766339.44     10050029.90      2766903.65     10049205.28
      2766764.77     10048701.85
#Sta/Elev= 30
  4320.9 1594.82  4504.6 1591.03  4510.7 1589.94  4561.4 1587.02  4642.1 1584.93
  4648.1 1583.97  4663.0 1583.46  4669.1 1582.33  4678.0 1582.43  4684.0 1581.08
  4698.9 1581.20  4719.9 1578.87  4755.8 1577.28  4858.3 1576.79  4950.1 1577.26
  4973.6 1576.75  4997.9 1575.47  5000.7 1574.97  5003.9 1575.47  5075.2 1577.43
  5181.3 1578.52  5216.2 1578.34  5246.0 1579.24  5273.5 1578.17  5319.9 1578.13
  5397.7 1579.98  5451.2 1580.02  5640.1 1579.85  5705.5 1580.70  5842.3 1580.96
#Mann=9,-1,0
  4320.9    0.05       0  4858.3     0.1       0  4973.6    0.05       0
  4997.9   0.035       0  5003.9    0.05       0  5075.2     0.1       0
  5181.3    0.05       0  5451.2     0.1       0  5640.1    0.05       0
Bank Sta=4997.9,5003.9
Exp/Cntr=0.3,0.1

Type RM Length L Ch R = 1,1073,358,358,358
BEGIN DESCRIPTION:
UNT 0014 IN HEWA 2.0
END DESCRIPTION:
XS GIS Cut Line= 3
      2766443.56     10050403.22      2767068.58     10049526.46
      2766921.49     10048946.76
#Sta/Elev= 30
  4243.9 1592.37  4290.8 1592.16  4304.7 1590.53  4368.3 1586.60  4427.3 1586.53
  4433.4 1585.56  4448.2 1585.62  4454.3 1584.33  4469.1 1583.66  4685.4 1579.67
  4697.7 1578.63  4756.7 1577.00  4813.3 1575.90  4878.4 1575.74  4893.2 1575.10
  4943.3 1576.06  5007.5 1575.42  5056.7 1576.01  5128.0 1574.79  5297.1 1573.91
  5299.8 1573.41  5303.1 1573.91  5545.0 1574.00  5571.1 1576.57  5586.0 1577.12
  5612.3 1575.14  5650.4 1575.54  5756.8 1577.49  5891.8 1578.94  5918.7 1579.20
#Mann=6,-1,0
  4243.9    0.05       0  5007.5     0.1       0  5297.1   0.035       0
  5303.1     0.1       0  5650.4    0.05       0  5891.8     0.1       0
Bank Sta=5297.1,5303.1
Exp/Cntr=0.3,0.1

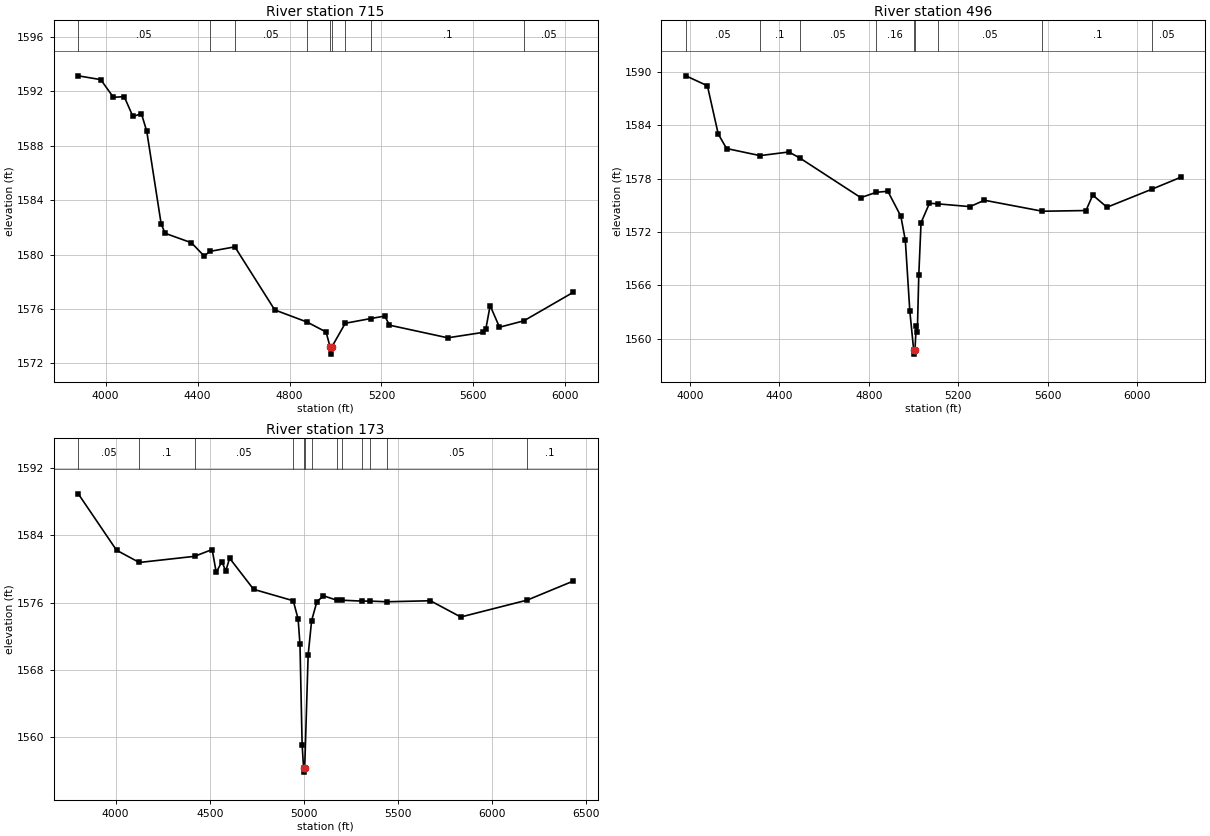
Type RM Length L Ch R = 1,715,219,219,219
BEGIN DESCRIPTION:
Mapping XS 604ab83d
END DESCRIPTION:
XS GIS Cut Line= 4
      2766301.68     10050533.50      2766957.93     10050283.50
      2767223.55     10049877.25      2767041.26     10048929.35
#Sta/Elev= 30
  3880.9 1593.15  3978.8 1592.87  4033.7 1591.57  4080.8 1591.62  4118.6 1590.16
  4155.7 1590.36  4178.8 1589.08  4241.3 1582.28  4258.4 1581.57  4373.4 1580.87
  4428.3 1579.90  4454.5 1580.24  4562.2 1580.57  4735.8 1575.93  4876.3 1575.04
  4959.0 1574.31  4977.1 1573.18  4979.8 1572.68  4983.1 1573.18  5042.6 1574.95
  5154.4 1575.30  5214.7 1575.48  5235.0 1574.81  5488.6 1573.88  5642.4 1574.28
  5654.6 1574.56  5672.9 1576.25  5713.7 1574.66  5819.7 1575.13  6033.8 1577.22
#Mann=9,-1,0
  3880.9    0.05       0  4454.5     0.1       0  4562.2    0.05       0
  4876.3     0.1       0  4977.1    0.07       0  4983.1     0.1       0
  5042.6    0.05       0  5154.4     0.1       0  5819.7    0.05       0
Bank Sta=4977.1,4983.1
Exp/Cntr=0.3,0.1

Type RM Length L Ch R = 1,496,323,323,323
BEGIN DESCRIPTION:
Mapping XS ab906148
END DESCRIPTION:
XS GIS Cut Line= 5
      2766520.12     10050513.25      2767353.46     10050174.71
      2767340.43     10050001.09      2767240.61     10049792.76
      2767119.08     10048894.33
#Sta/Elev= 30
  3983.0 1589.57  4079.2 1588.45  4127.4 1583.03  4164.7 1581.39  4314.3 1580.59
  4443.3 1581.00  4493.5 1580.30  4764.6 1575.86  4833.5 1576.46  4885.5 1576.58
  4943.6 1573.77  4963.7 1571.06  4983.7 1563.10  5000.8 1558.75  5003.5 1558.25
  5006.8 1558.75  5012.4 1561.43  5017.4 1560.77  5023.8 1567.14  5033.9 1573.04
  5071.5 1575.23  5109.3 1575.16  5252.8 1574.85  5316.9 1575.57  5576.5 1574.33
  5771.0 1574.41  5801.3 1576.15  5865.0 1574.78  6066.4 1576.82  6194.2 1578.15
#Mann=9,-1,0
  3983.0    0.05       0  4314.3     0.1       0  4493.5    0.05       0
  4833.5    0.16       0  5000.8    0.07       0  5006.8    0.16       0
  5109.3    0.05       0  5576.5     0.1       0  6066.4    0.05       0
Bank Sta=5000.8,5006.8
Exp/Cntr=0.3,0.1

Type RM Length L Ch R = 1,173,0,0,0
BEGIN DESCRIPTION:
UNT 0014 IN HEWA 1.0
END DESCRIPTION:
XS GIS Cut Line= 5
      2766489.70     10050600.06      2767570.47     10050322.28
      2767613.87     10050205.09      2767292.69     10049823.14
      2767179.84     10048942.04
#Sta/Elev= 30
  3801.4 1588.95  4004.5 1582.25  4125.5 1580.79  4418.8 1581.52  4512.6 1582.33
  4534.1 1579.61  4564.2 1580.89  4584.8 1579.77  4605.2 1581.30  4732.6 1577.60
  4943.3 1576.24  4969.1 1574.07  4979.0 1571.06  4990.4 1559.15  4998.1 1556.37
  5000.8 1555.87  5004.1 1556.37  5022.4 1569.78  5040.9 1573.89  5068.8 1576.12
  5103.9 1576.83  5173.9 1576.31  5204.5 1576.30  5307.3 1576.20  5350.3 1576.20
  5440.6 1576.12  5671.8 1576.24  5833.1 1574.31  6186.3 1576.32  6429.6 1578.57
#Mann=13,-1,0
  3801.4    0.05       0  4125.5     0.1       0  4418.8    0.05       0
  4943.3    0.16       0  4998.1    0.07       0  5004.1    0.16       0
  5040.9     0.1       0  5173.9    0.05       0  5204.5     0.1       0
  5307.3    0.05       0  5350.3    0.16       0  5440.6    0.05       0
  6186.3     0.1       0
Bank Sta=4998.1,5004.1
Exp/Cntr=0.3,0.1

Chan Stop Cuts=-1