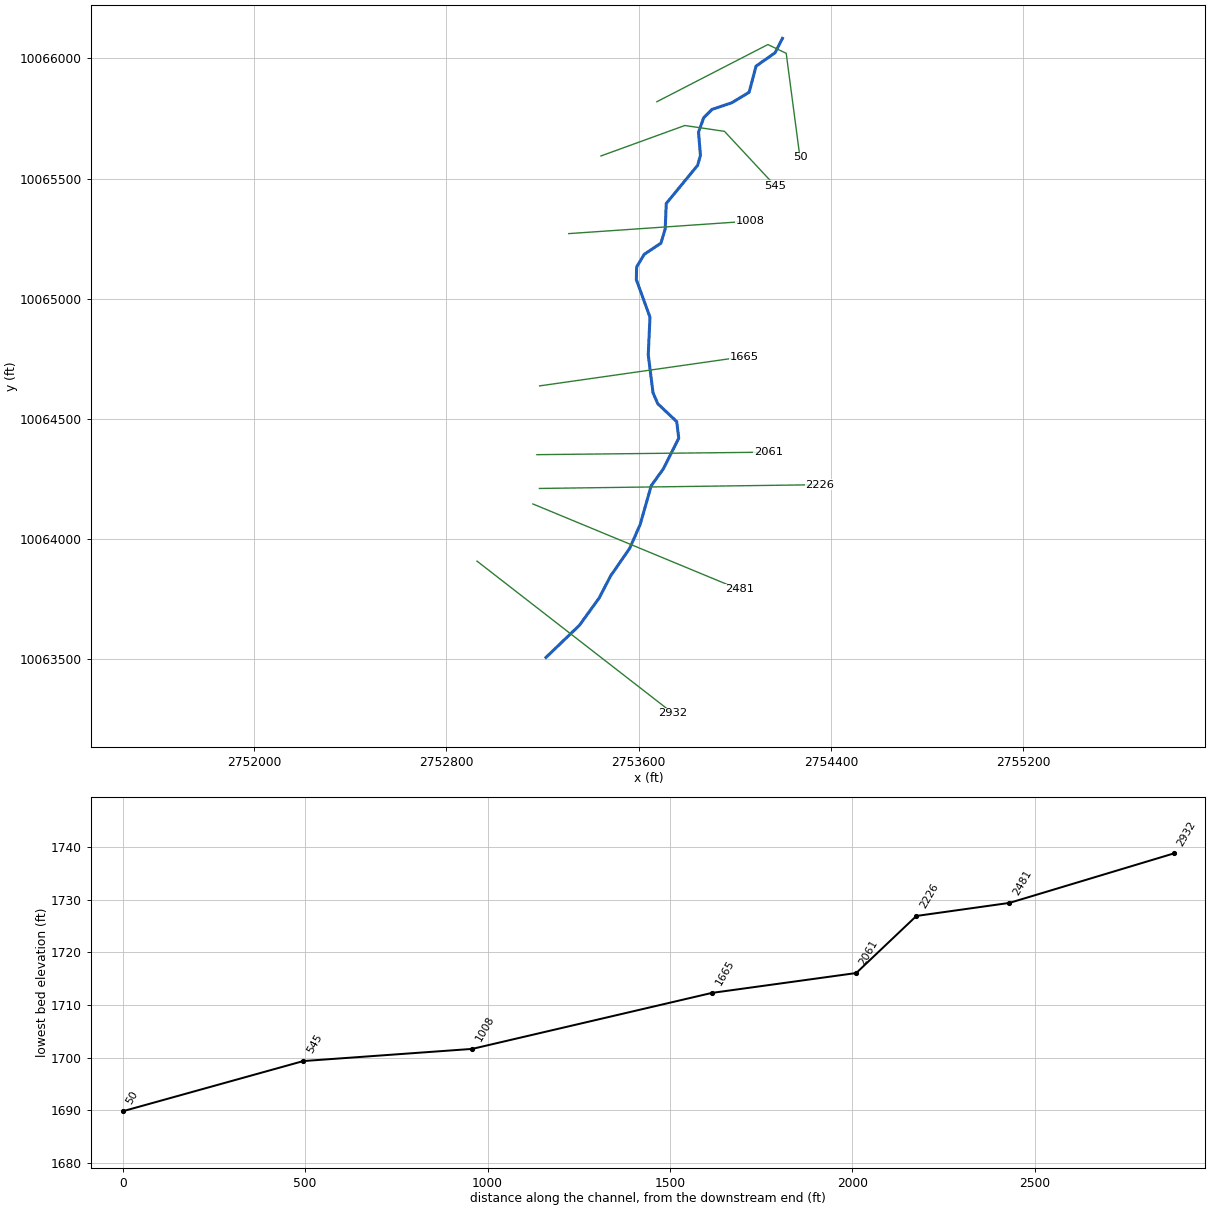
--- UNT 0015 IN HEWA.prj (project) ---

Proj Title=UNT 0015 IN HEWA Base Level Engineering
Current Plan=p01
Default Exp/Contr=0.3,0.1
English Units
Geom File=g01
Flow File=f01
Plan File=p01
BEGIN DESCRIPTION:
UNT 0015 IN HEWA
END DESCRIPTION:

--- UNT 0015 IN HEWA.p01 (plan) ---

Plan Title=Multiple Run
Short Identifier=Multiple
Geom File=g01
Flow File=f01
Subcritical Flow
K Sum by GR= 0
Std Step Tol= 0.01
Critical Tol= 0.01
Num of Std Step Trials= 20
Max Error Tol= 0.3
Flow Tol Ratio= 0.001
Split Flow NTrial= 30
Split Flow Tol= 0.02
Split Flow Ratio= 0.02
Log Output Level= 0
Friction Slope Method= 1
Unsteady Friction Slope Method= 2
Unsteady Bridges Friction Slope Method= 1
Parabolic Critical Depth
Global Vel Dist=  1 , 1 , 1
Global Log Level= 0
CheckData=True
Encroach Param= -1, 0, 0, 0
BEGIN DESCRIPTION:
Multiple Run
END DESCRIPTION:

--- UNT 0015 IN HEWA.f01 (steady flow) ---

Flow Title=Multiple
Number of Profiles=7
Profile Names=10-year,25-year,50-year,1pct_min,100-year,1pct_plu,500-year
River Rch & RM= UNT 0015 IN HEWA,Reach-1,2932
     280     381     464     414     561     758     821
Boundary for River Rch & Prof#=UNT 0015 IN HEWA,Reach-1,1
Up Type=0
Dn Type=3
Dn Slope=0.005
Boundary for River Rch & Prof#=UNT 0015 IN HEWA,Reach-1,2
Up Type=0
Dn Type=3
Dn Slope=0.005
Boundary for River Rch & Prof#=UNT 0015 IN HEWA,Reach-1,3
Up Type=0
Dn Type=3
Dn Slope=0.005
Boundary for River Rch & Prof#=UNT 0015 IN HEWA,Reach-1,4
Up Type=0
Dn Type=3
Dn Slope=0.005
Boundary for River Rch & Prof#=UNT 0015 IN HEWA,Reach-1,5
Up Type=0
Dn Type=3
Dn Slope=0.005
Boundary for River Rch & Prof#=UNT 0015 IN HEWA,Reach-1,6
Up Type=0
Dn Type=3
Dn Slope=0.005
Boundary for River Rch & Prof#=UNT 0015 IN HEWA,Reach-1,7
Up Type=0
Dn Type=3
Dn Slope=0.005

--- UNT 0015 IN HEWA.g01 (geometry) ---

Geom Title=Existing Conditions
Program Version=4.10

River Reach=UNT 0015 IN HEWA,Reach-1
Reach XY= 30
      2753214.43     10063507.45      2753353.41     10063640.77
      2753435.82     10063754.83      2753483.36     10063846.42
      2753562.82     10063961.36      2753606.12      10064059.7
      2753652.33     10064222.04      2753702.47     10064291.42
      2753766.93     10064419.27      2753758.56     10064488.65
      2753679.57     10064563.29      2753659.96     10064608.63
      2753640.08     10064766.74       2753647.3     10064923.24
      2753590.45     10065079.44      2753591.69     10065132.26
      2753623.84     10065185.33      2753692.83     10065231.42
      2753710.63     10065291.17      2753714.97     10065396.43
      2753845.41      10065555.1      2753857.24     10065596.58
       2753849.3     10065693.32      2753870.69     10065753.05
      2753905.85     10065788.16      2753987.74     10065815.61
      2754059.82     10065859.27      2754088.82     10065968.22
      2754167.97     10066023.81      2754198.47     10066083.73

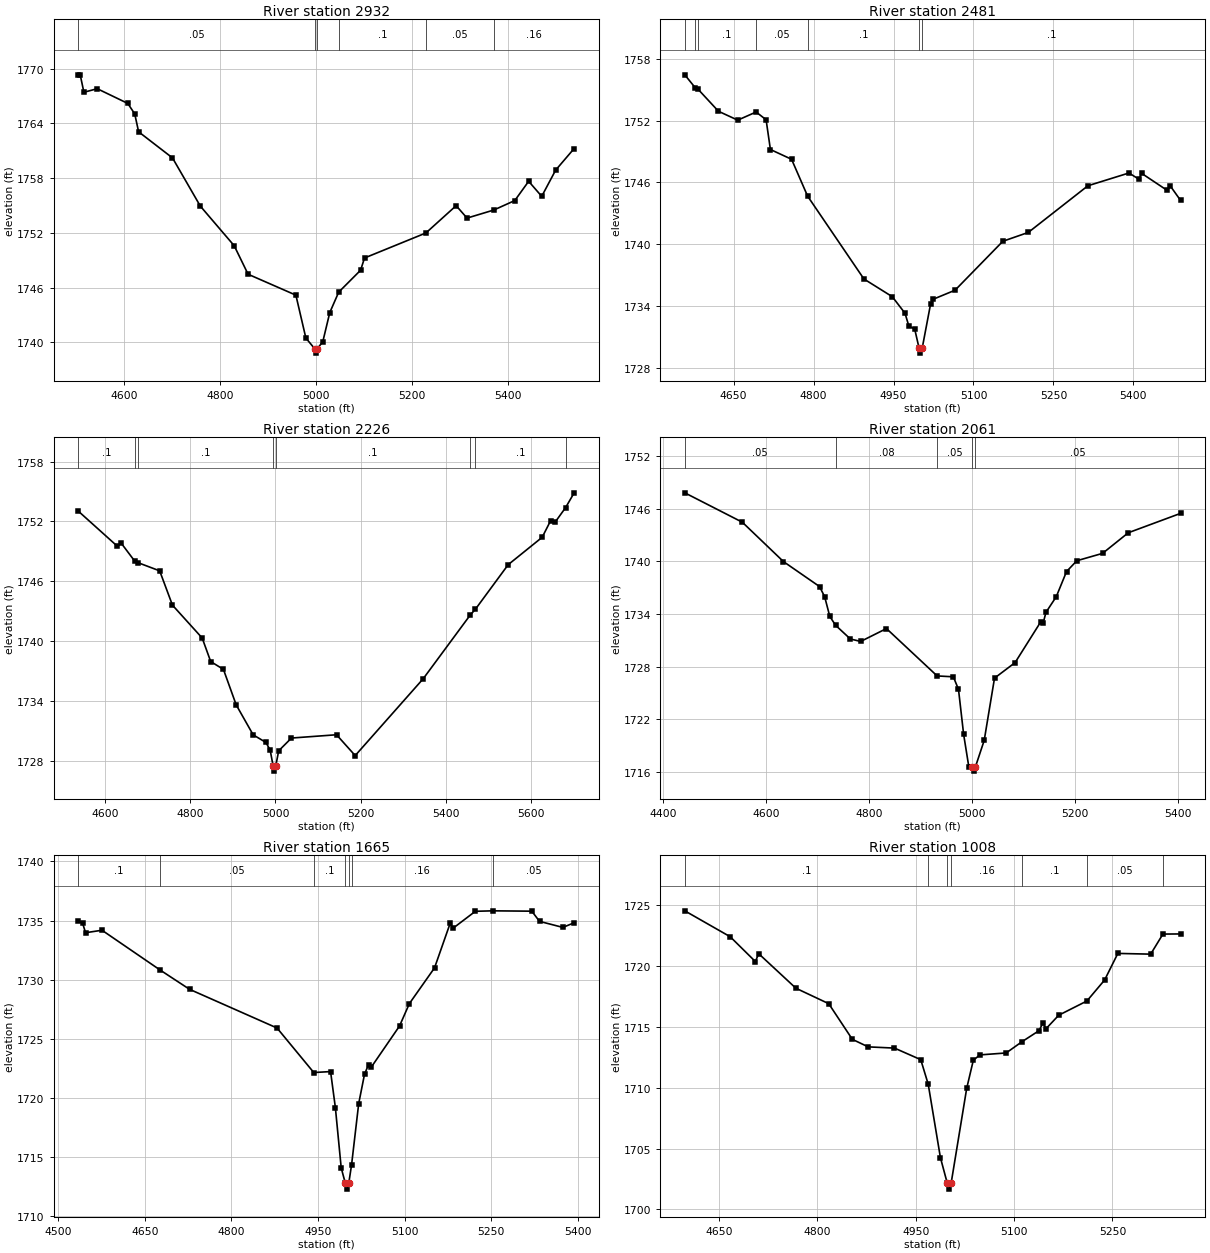
Type RM Length L Ch R = 1 ,2932    ,451,451,451
BEGIN DESCRIPTION:
UNT 0015 IN HEWA 5.0
END DESCRIPTION:
XS GIS Cut Line= 2
      2752927.38     10063908.25      2753743.33     10063274.59
#Sta/Elev= 30
  4505.1 1769.31    4509 1769.31  4516.7  1767.4  4544.5 1767.79  4608.1 1766.18
  4622.6 1765.03  4630.7 1763.07  4701.3 1760.21  4759.3 1754.93  4829.9 1750.59
  4858.8 1747.47  4958.4 1745.18  4979.2 1740.48  4997.3 1739.33    5000 1738.83
  5003.3 1739.33  5014.5 1740.09    5029 1743.27  5047.6 1745.51  5093.2 1747.91
  5101.4 1749.25  5229.3 1751.99  5292.3 1754.98    5315 1753.62  5370.6  1754.5
  5414.5 1755.54  5443.4 1757.65  5470.6    1756  5499.6 1758.87  5538.2 1761.24
#Mann= 6 ,-1 , 0
  4505.1     .05       0  4997.3     .04       0  5003.3     .05       0
  5047.6      .1       0  5229.3     .05       0  5370.6     .16       0
Bank Sta=4997.3,5003.3
XS Rating Curve= 0 ,0
Exp/Cntr=0.3,0.1

Type RM Length L Ch R = 1 ,2481    ,255,255,255
BEGIN DESCRIPTION:
UNT 0015 IN HEWA 4.0
END DESCRIPTION:
XS GIS Cut Line= 2
      2753160.07     10064146.07      2754019.39     10063790.19
#Sta/Elev= 30
  4558.5 1756.44    4578 1755.19  4582.5 1755.09  4621.7  1752.9  4657.8 1752.04
  4692.3 1752.83    4711 1752.08  4719.1 1749.19  4758.8 1748.24  4788.9 1744.66
  4894.5 1736.62  4947.7  1734.9  4971.6 1733.29  4978.9 1732.03  4989.7 1731.77
  4997.9 1729.92  5000.6 1729.42  5003.9 1729.92  5019.4 1734.15  5024.8 1734.66
  5065.5 1735.53  5155.1 1740.28  5202.9 1741.14  5314.7 1745.67  5391.7 1746.91
  5410.2 1746.31  5415.6 1746.87  5463.4 1745.22  5468.8 1745.68  5488.6 1744.24
#Mann= 7 ,-1 , 0
  4558.5      .1       0    4578     .08       0  4582.5      .1       0
  4692.3     .05       0  4788.9      .1       0  4997.9     .07       0
  5003.9      .1       0
Bank Sta=4997.9,5003.9
XS Rating Curve= 0 ,0
Exp/Cntr=0.3,0.1

Type RM Length L Ch R = 1 ,2226    ,165,165,165
BEGIN DESCRIPTION:
Mapping XS 423e3347
END DESCRIPTION:
XS GIS Cut Line= 2
      2753187.12     10064210.58      2754353.62      10064226.2
#Sta/Elev= 30
  4536.1 1753.03  4627.4 1749.53  4637.5 1749.79  4669.4 1747.98  4675.9 1747.87
  4727.5 1747.04  4757.5  1743.6  4827.5  1740.3  4847.5 1737.94  4877.5 1737.15
  4907.5 1733.59  4947.5 1730.58  4977.5 1729.82  4987.5 1729.04  4994.5 1727.44
  4997.2 1726.94  5000.5 1727.44  5007.5 1728.98  5037.5 1730.26  5143.6 1730.59
  5187.5  1728.5  5347.5 1736.21  5458.6 1742.63  5470.4 1743.19  5547.5 1747.66
  5627.5 1750.41  5647.5 1752.09  5657.5  1751.9  5682.6 1753.39  5702.7 1754.87
#Mann= 8 ,-1 , 0
  4536.1      .1       0  4669.4     .05       0  4675.9      .1       0
  4994.5     .07       0  5000.5      .1       0  5458.6     .05       0
  5470.4      .1       0  5682.6     .05       0
Bank Sta=4994.5,5000.5
XS Rating Curve= 0 ,0
Exp/Cntr=0.3,0.1

Type RM Length L Ch R = 1 ,2061    ,396,396,396
BEGIN DESCRIPTION:
Mapping XS 18f18a11
END DESCRIPTION:
XS GIS Cut Line= 2
      2753176.64     10064351.21      2754140.18     10064361.62
#Sta/Elev= 30
  4441.9 1747.81  4553.7 1744.46  4633.7 1739.97  4703.7 1737.13  4713.7 1735.97
  4723.7 1733.72    4735 1732.71  4763.7 1731.15  4783.7 1730.87  4833.8 1732.34
  4932.3 1726.94  4963.8 1726.84  4973.8 1725.41  4983.8 1720.28  4993.8 1716.61
  5000.8 1716.59  5003.5 1716.09  5006.8 1716.59  5023.8  1719.6  5043.8 1726.69
  5083.8 1728.46  5133.4 1733.08  5138.4 1732.97  5143.8 1734.19  5163.8 1735.97
  5183.8 1738.84  5203.8 1740.07  5253.8 1740.91  5303.8 1743.26  5405.5 1745.47
#Mann= 5 ,-1 , 0
  4441.9     .05       0    4735     .08       0  4932.3     .05       0
  5000.8     .04       0  5006.8     .05       0
Bank Sta=5000.8,5006.8
XS Rating Curve= 0 ,0
Exp/Cntr=0.3,0.1

Type RM Length L Ch R = 1 ,1665    ,657,657,657
BEGIN DESCRIPTION:
UNT 0015 IN HEWA 3.0
END DESCRIPTION:
XS GIS Cut Line= 2
      2753187.85     10064637.41      2754037.82     10064758.84
#Sta/Elev= 30
    4535 1734.96  4542.5 1734.76  4547.5 1733.97    4576 1734.18  4676.6 1730.82
  4727.6 1729.19  4879.1 1725.92  4942.7 1722.16  4971.8 1722.24  4980.1  1719.2
  4990.2 1714.11  4997.3 1712.81    5000 1712.31  5003.3 1712.81  5008.2 1714.38
  5020.5 1719.54  5030.6 1722.02  5037.5 1722.82  5042.5 1722.63  5091.2 1726.09
  5108.2 1727.98  5151.8    1731  5178.9 1734.77  5183.9 1734.35  5222.5 1735.78
  5252.4 1735.82  5320.3 1735.79  5333.6 1734.93    5374 1734.42  5393.6 1734.81
#Mann= 7 ,-1 , 0
    4535      .1       0  4676.6     .05       0  4942.7      .1       0
  4997.3     .07       0  5003.3      .1       0  5008.2     .16       0
  5252.4     .05       0
Bank Sta=4997.3,5003.3
XS Rating Curve= 0 ,0
Exp/Cntr=0.3,0.1

Type RM Length L Ch R = 1 ,1008    ,463,463,463
BEGIN DESCRIPTION:
UNT 0015 IN HEWA 2.0
END DESCRIPTION:
XS GIS Cut Line= 2
      2753309.34     10065271.09      2754064.05     10065323.14
#Sta/Elev= 30
  4597.6 1724.54  4666.9 1722.41  4705.3 1720.37  4710.3 1721.02  4767.1 1718.18
  4817.2 1716.91  4853.2 1713.98  4877.4 1713.36  4917.5 1713.26  4957.6 1712.31
    4969 1710.29  4987.6 1704.26    4998 1702.17  5000.8 1701.67    5004 1702.17
  5027.7 1709.95  5037.8 1712.26  5047.8  1712.7  5087.9 1712.86  5112.5  1713.8
    5138 1714.69  5143.9 1715.31  5148.9 1714.86  5168.1 1715.96  5211.1 1717.13
  5238.2 1718.86  5258.3 1721.04  5308.4 1720.98  5327.1 1722.63  5354.1 1722.64
#Mann= 7 ,-1 , 0
  4597.6      .1       0    4969     .16       0    4998     .07       0
    5004     .16       0  5112.5      .1       0  5211.1     .05       0
  5327.1     .08       0
Bank Sta=4998,5004
XS Rating Curve= 0 ,0
Exp/Cntr=0.3,0.1

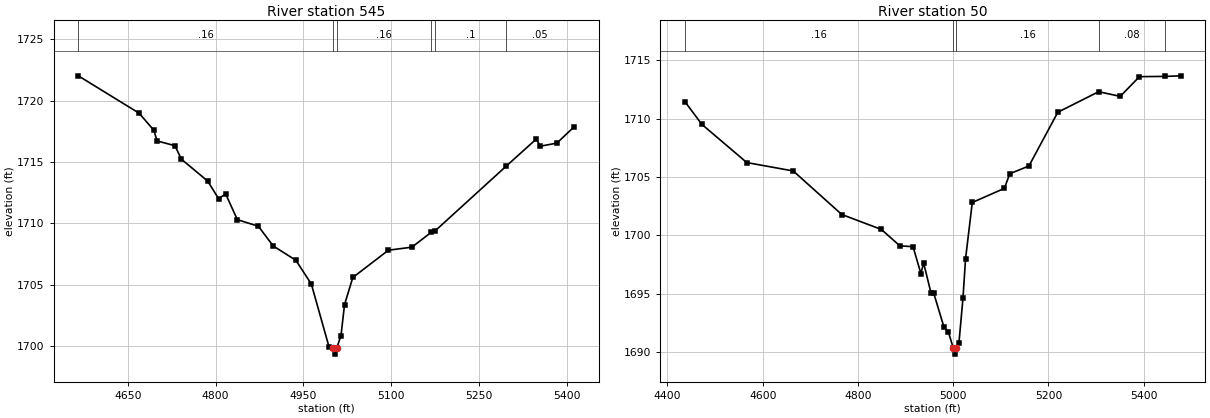
Type RM Length L Ch R = 1 ,545     ,495,495,495
BEGIN DESCRIPTION:
Mapping XS 180ee3ad
END DESCRIPTION:
XS GIS Cut Line= 4
      2753443.33     10065594.28      2753792.31     10065721.02
      2753957.24     10065696.71       2754167.3     10065471.03
#Sta/Elev= 30
  4565.7 1722.02  4669.4 1718.98  4694.7 1717.58    4700 1716.72  4730.7 1716.33
  4741.4 1715.24  4786.5 1713.45  4805.2 1712.01  4817.1 1712.41  4837.1 1710.31
    4873 1709.77  4898.3 1708.17    4937    1707  4963.4 1705.07  4993.7 1699.93
  5000.8 1699.86  5003.6 1699.36  5006.8 1699.86    5014 1700.87  5020.1  1703.4
  5034.2  1705.6  5094.9 1707.82  5135.1 1708.07  5168.1 1709.28  5174.8  1709.4
  5296.3 1714.68  5347.3 1716.87  5354.1 1716.29  5382.4 1716.54    5412 1717.87
#Mann= 6 ,-1 , 0
  4565.7     .16       0  5000.8     .07       0  5006.8     .16       0
  5168.1     .05       0  5174.8      .1       0  5296.3     .05       0
Bank Sta=5000.8,5006.8
XS Rating Curve= 0 ,0
Exp/Cntr=0.3,0.1

Type RM Length L Ch R = 1 ,50      ,0,0,0
BEGIN DESCRIPTION:
UNT 0015 IN HEWA 1.0
END DESCRIPTION:
XS GIS Cut Line= 4
        2753676.     10065819.99      2754137.79     10066057.82
      2754214.18     10066021.37      2754271.39     10065588.01
#Sta/Elev= 30
  4436.4 1711.46  4472.3  1709.5  4566.6 1706.23  4664.1 1705.51  4766.1 1701.78
  4849.2  1700.5  4887.9  1699.1  4915.7 1699.02  4932.2 1696.72  4937.9 1697.63
  4953.4 1695.06    4959 1695.06  4980.6 1692.14  4989.8 1691.73  5000.3 1690.32
  5003.1 1689.82  5006.3 1690.32    5012 1690.74  5020.5  1694.6    5026    1698
  5040.1 1702.81  5107.5 1704.02  5118.8 1705.27  5159.1 1705.94  5219.7 1710.54
  5305.5  1712.3  5350.8  1711.9  5391.1 1713.59  5444.5 1713.61  5477.6 1713.66
#Mann= 5 ,-1 , 0
  4436.4     .16       0  5000.3     .07       0  5006.3     .16       0
  5305.5     .08       0  5444.5     .05       0
Bank Sta=5000.3,5006.3
XS Rating Curve= 0 ,0
Exp/Cntr=0.3,0.1

Chan Stop Cuts=-1
Use User Specified Reach Order=0
Composite Channel Slope=5