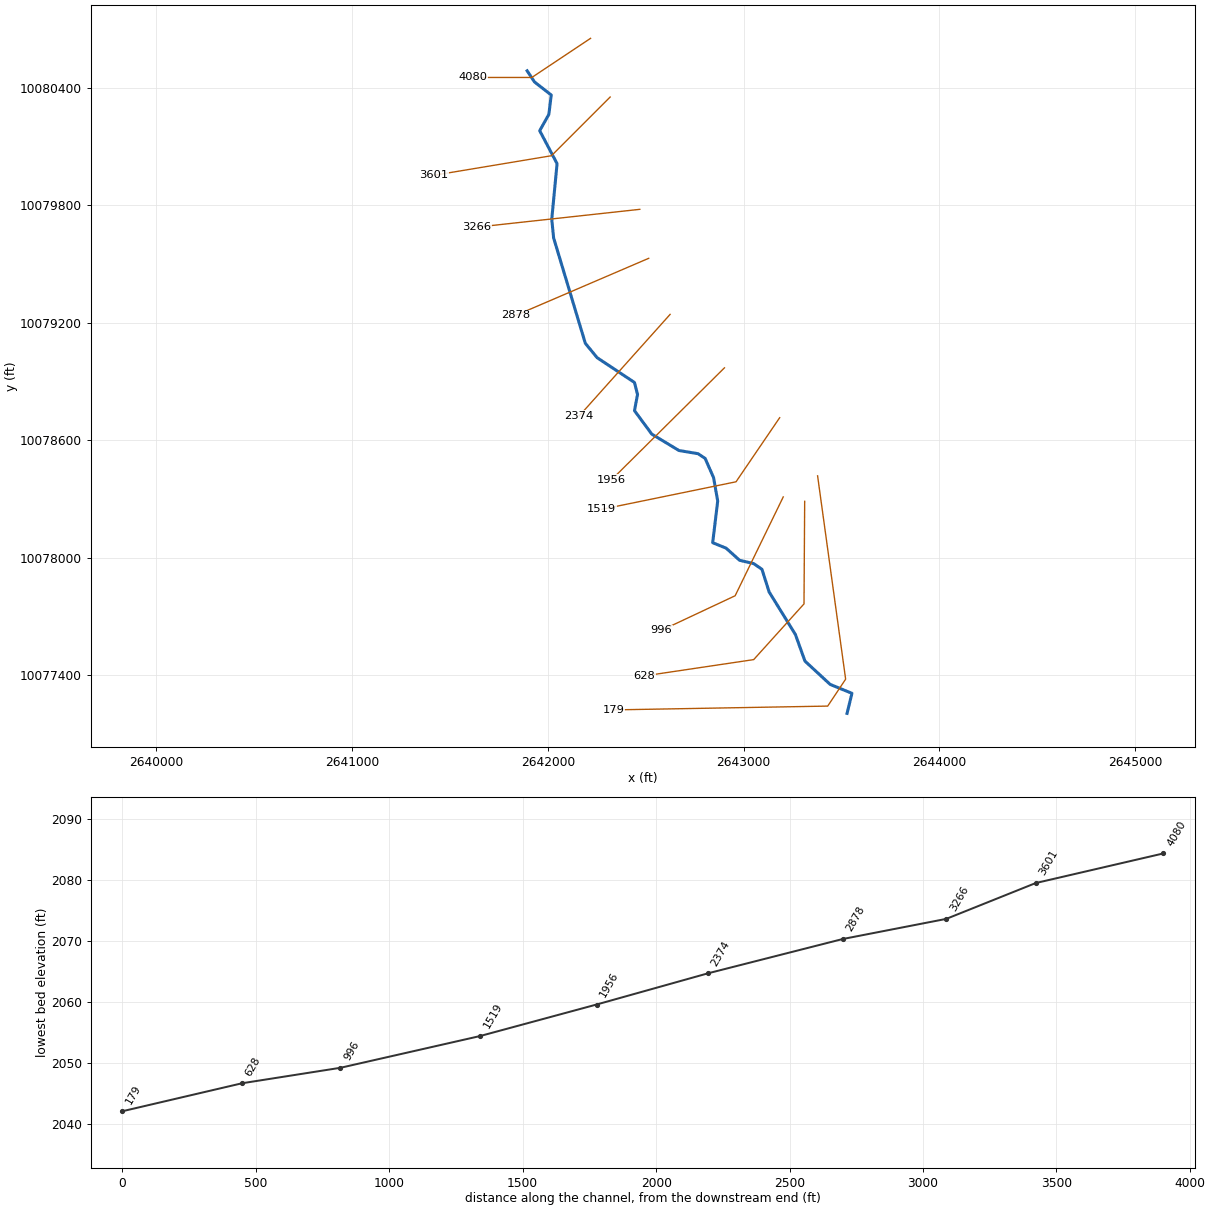
--- UNT 0016 IN HEWA.prj (project) ---

Proj Title=UNT 0016 IN HEWA Base Level Engineering
Current Plan=p01
Default Exp/Contr=0.3,0.1
English Units
Geom File=g01
Flow File=f01
Plan File=p01
Y Axis Title=Elevation
X Axis Title(PF)=Main Channel Distance
X Axis Title(XS)=Station
BEGIN DESCRIPTION:
UNT 0016 IN HEWA
END DESCRIPTION:
DSS Export Rating Curves= 0
DSS Export Rating Curve Sorted= 0
DSS Export Volume Flow Curves= 0
DXF OffsetX= 0
DXF OffsetY= 0
DXF ScaleX= 1
DXF ScaleY= 10

--- UNT 0016 IN HEWA.p01 (plan) ---

Plan Title=Multiple Run
Short Identifier=Multiple
Geom File=g01
Flow File=f01
Subcritical Flow
K Sum by GR= 0
Std Step Tol= 0.01
Critical Tol= 0.01
Num of Std Step Trials= 20
Max Error Tol= 0.3
Flow Tol Ratio= 0.001
Split Flow NTrial= 30
Split Flow Tol= 0.02
Split Flow Ratio= 0.02
Log Output Level= 0
Friction Slope Method= 1
Unsteady Friction Slope Method= 2
Unsteady Bridges Friction Slope Method= 1
Parabolic Critical Depth
Global Vel Dist=  1 , 1 , 1
Global Log Level= 0
CheckData=True
Encroach Param= -1, 0, 0, 0
BEGIN DESCRIPTION:
Multiple Run
END DESCRIPTION:

--- UNT 0016 IN HEWA.f01 (steady flow) ---

Flow Title=Multiple
Program Version=4.10
Number of Profiles= 7
Profile Names=10-year,25-year,50-year,1pct_min,100-year,1pct_plu,500-year
River Rch & RM=UNT 0016 IN HEWA,Reach-1         ,4080
     743    1054    1316    1199    1621    2192    2458
Boundary for River Rch & Prof#=UNT 0016 IN HEWA,Reach-1         , 1
Up Type= 0
Dn Type= 3
Dn Slope=0.01
Boundary for River Rch & Prof#=UNT 0016 IN HEWA,Reach-1         , 2
Up Type= 0
Dn Type= 3
Dn Slope=0.01
Boundary for River Rch & Prof#=UNT 0016 IN HEWA,Reach-1         , 3
Up Type= 0
Dn Type= 3
Dn Slope=0.01
Boundary for River Rch & Prof#=UNT 0016 IN HEWA,Reach-1         , 4
Up Type= 0
Dn Type= 3
Dn Slope=0.01
Boundary for River Rch & Prof#=UNT 0016 IN HEWA,Reach-1         , 5
Up Type= 0
Dn Type= 3
Dn Slope=0.01
Boundary for River Rch & Prof#=UNT 0016 IN HEWA,Reach-1         , 6
Up Type= 0
Dn Type= 3
Dn Slope=0.01
Boundary for River Rch & Prof#=UNT 0016 IN HEWA,Reach-1         , 7
Up Type= 0
Dn Type= 3
Dn Slope=0.01
DSS Import GetInterval= 0
DSS Import GetPeak= 0
DSS Import FillOption= 0

--- UNT 0016 IN HEWA.g01 (geometry) ---

Geom Title=Existing Conditions
Program Version=4.10

River Reach=UNT 0016 IN HEWA,Reach-1
Reach XY= 30
      2641894.46     10080487.73       2641932.1     10080430.67
      2642017.48     10080364.25      2642005.38     10080265.03
      2641958.67     10080181.63       2642047.3     10080013.22
      2642020.15      10079728.8      2642029.74     10079633.62
      2642191.65     10079095.03      2642252.08     10079021.38
      2642442.58     10078895.07      2642458.35      10078833.7
      2642442.72     10078750.93        2642531.     10078631.09
      2642669.86      10078547.1      2642767.46     10078530.86
      2642803.68     10078506.62      2642846.58     10078408.67
      2642867.76     10078289.09      2642842.13     10078076.06
      2642910.89     10078047.98      2642979.49     10077986.19
      2643051.55     10077969.15      2643093.77       10077940.
      2643130.33     10077824.51      2643264.58     10077606.83
      2643313.41      10077470.9      2643442.31     10077351.59
       2643553.4     10077306.32      2643528.47     10077203.73

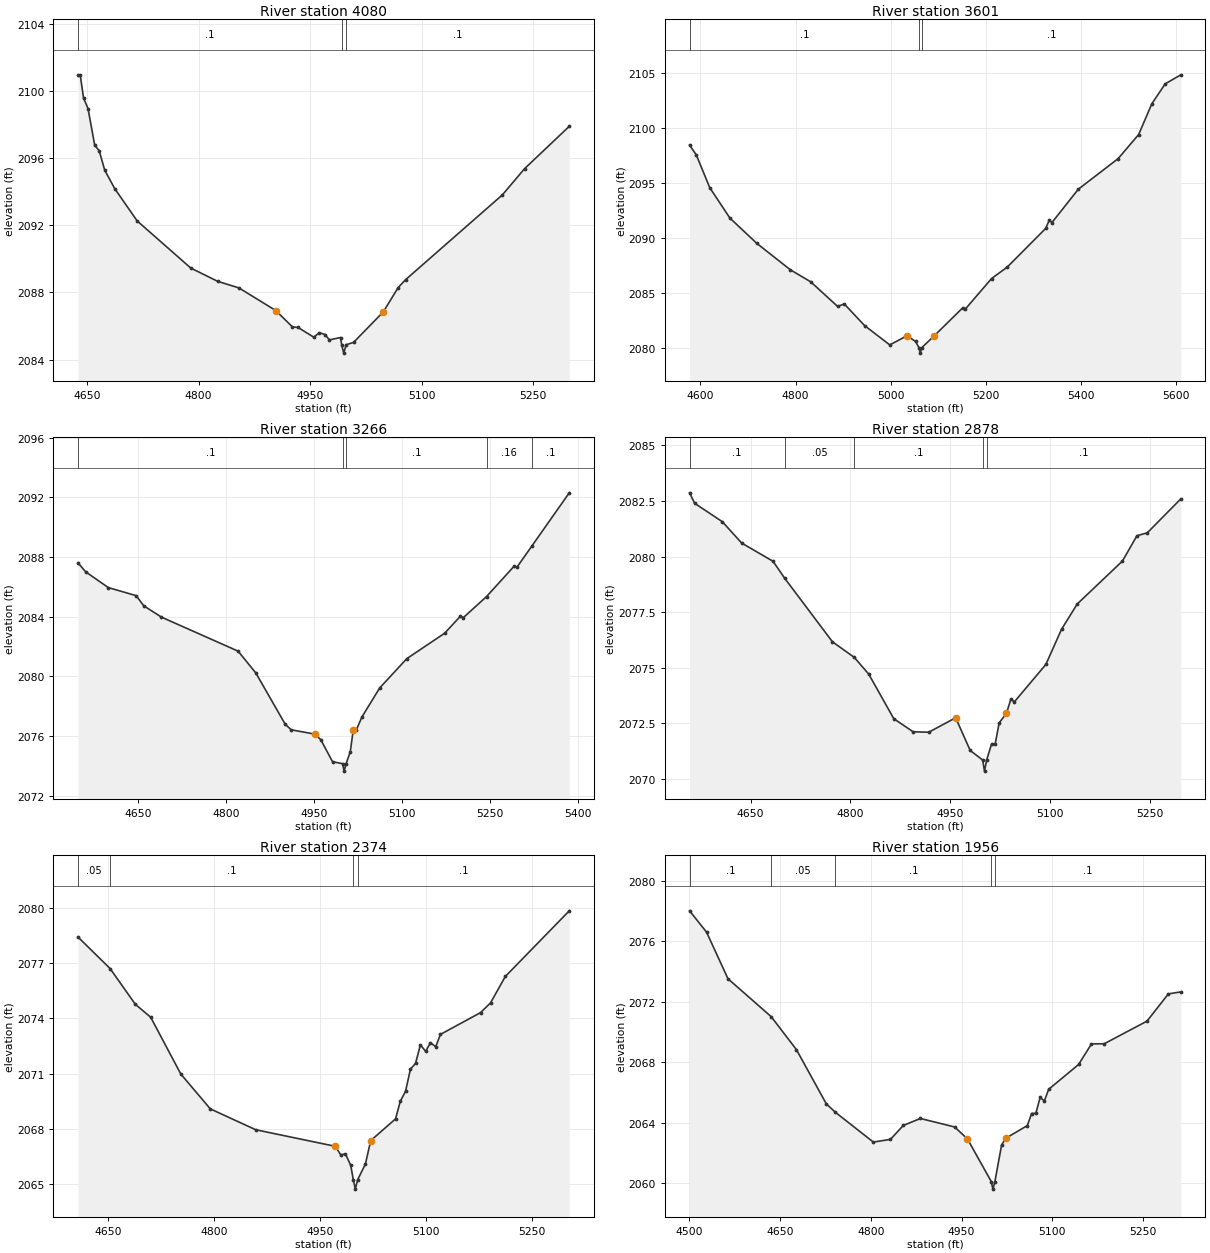
Type RM Length L Ch R = 1 ,4080    ,479,479,479
BEGIN DESCRIPTION:
UNT 0016 IN HEWA 8.0
END DESCRIPTION:
XS GIS Cut Line= 3
      2642218.44     10080653.71      2641918.47     10080453.73
      2641618.49     10080453.73
#Sta/Elev= 30
  4637.9 2100.97  4640.9 2100.97  4645.4 2099.58  4651.4 2098.96  4660.4 2096.77
  4666.4 2096.45  4673.9 2095.28  4687.4 2094.18  4717.5 2092.26  4789.6 2089.45
  4825.7 2088.66  4854.2 2088.27  4903.8 2086.92  4926.3 2085.94  4933.8 2085.91
  4954.9 2085.33  4962.4  2085.6  4969.9 2085.49  4975.9 2085.17  4990.9 2085.31
  4992.4 2084.88  4995.2 2084.38  4998.4 2084.88  5008.4 2085.02  5048.4 2086.84
  5068.4 2088.29  5078.4 2088.76  5208.4 2093.81  5238.4 2095.38  5298.4  2097.9
#Mann= 3 ,-1 , 0
  4637.9      .1       0  4992.4     .07       0  4998.4      .1       0
Bank Sta=4903.8,5048.4
XS Rating Curve= 0 ,0
Exp/Cntr=0.3,0.1

Type RM Length L Ch R = 1 ,3601    ,335,335,335
BEGIN DESCRIPTION:
UNT 0016 IN HEWA 7.0
END DESCRIPTION:
XS GIS Cut Line= 3
      2642318.44      10080353.7      2642018.47     10080053.73
      2641418.47     10079953.73
#Sta/Elev= 30
  4577.1 2098.44  4591.2 2097.55  4619.5 2094.57  4661.9  2091.8  4718.5  2089.5
  4789.2 2087.09  4831.6 2086.01  4888.2 2083.77  4902.3 2083.99  4944.8 2082.03
  4997.8 2080.27  5034.3  2081.1    5052 2080.58  5059.2 2080.02  5061.9 2079.52
  5065.2 2080.02    5090 2081.04  5150.9 2083.63  5155.9 2083.49  5211.7  2086.3
  5244.6 2087.34  5325.7 2090.87  5333.3 2091.64  5338.4 2091.38  5394.2 2094.43
  5477.8 2097.21  5520.9  2099.4  5548.8 2102.21  5576.7 2104.01  5609.6 2104.83
#Mann= 3 ,-1 , 0
  4577.1      .1       0  5059.2     .07       0  5065.2      .1       0
Bank Sta=5034.3,5090
XS Rating Curve= 0 ,0
Exp/Cntr=0.3,0.1

Type RM Length L Ch R = 1 ,3266    ,388,388,388
BEGIN DESCRIPTION:
UNT 0016 IN HEWA 6.0
END DESCRIPTION:
XS GIS Cut Line= 2
      2642469.87     10079779.76      2641637.23     10079688.76
#Sta/Elev= 30
  4547.7 2087.61  4560.7 2087.01  4599.4 2085.95  4646.9 2085.41  4659.8 2084.73
    4690 2083.97  4820.7 2081.69  4850.9 2080.23  4901.2 2076.78  4911.3 2076.42
  4951.5 2076.13  4961.6 2075.76  4981.7 2074.28  4998.8 2074.15  5001.5 2073.65
  5004.8 2074.15  5011.9 2074.94  5017.1 2076.43  5022.2 2076.41    5032 2077.29
  5062.2 2079.23  5108.4 2081.19  5172.8 2082.89  5199.7 2084.03  5204.8 2083.94
  5244.3 2085.35    5291 2087.37    5296 2087.31  5321.8 2088.75  5385.3  2092.3
#Mann= 5 ,-1 , 0
  4547.7      .1       0  4998.8     .07       0  5004.8      .1       0
  5244.3     .16       0  5321.8      .1       0
Bank Sta=4951.5,5017.1
XS Rating Curve= 0 ,0
Exp/Cntr=0.3,0.1

Type RM Length L Ch R = 1 ,2878    ,504,504,504
BEGIN DESCRIPTION:
UNT 0016 IN HEWA 5.0
END DESCRIPTION:
XS GIS Cut Line= 2
      2642515.45      10079529.5      2641837.91     10079238.48
#Sta/Elev= 30
  4558.5 2082.87  4566.1  2082.4  4607.7 2081.57  4636.7 2080.61  4683.8 2079.79
  4701.2 2079.03  4772.9 2076.17  4805.6 2075.47  4827.3 2074.72    4865 2072.71
    4894 2072.12  4917.5  2072.1  4957.9 2072.75  4979.7 2071.28  4998.4 2070.85
  5001.2 2070.35  5004.4 2070.85  5011.7 2071.56  5017.2 2071.57  5023.2 2072.52
  5034.1 2072.95  5040.7 2073.58  5046.1 2073.47  5093.3 2075.15  5116.8 2076.73
  5140.4 2077.87  5208.2  2079.8    5230 2080.94  5245.5 2081.07  5295.9  2082.6
#Mann= 5 ,-1 , 0
  4558.5      .1       0  4701.2     .05       0  4805.6      .1       0
  4998.4     .07       0  5004.4      .1       0
Bank Sta=4957.9,5034.1
XS Rating Curve= 0 ,0
Exp/Cntr=0.3,0.1

Type RM Length L Ch R = 1 ,2374    ,418,418,418
BEGIN DESCRIPTION:
UNT 0016 IN HEWA 4.0
END DESCRIPTION:
XS GIS Cut Line= 2
      2642624.61     10079242.78      2642160.52     10078724.09
#Sta/Elev= 30
  4606.8 2078.41  4652.3  2076.7  4688.1 2074.76  4709.8 2074.06  4752.5 2070.98
  4794.3 2069.09  4858.6 2067.96  4971.5 2067.06    4979  2066.6  4985.7 2066.65
  4993.2 2066.03  4996.9 2065.24  4999.7 2064.74  5002.9 2065.24  5014.1 2066.11
  5021.5 2067.37  5056.7 2068.55  5063.4  2069.5  5070.9 2070.05  5077.7 2071.23
  5085.1 2071.57  5091.9 2072.56  5099.4 2072.21  5106.1 2072.68  5113.6 2072.46
  5120.3 2073.13  5177.1 2074.31  5191.3 2074.84  5212.2 2076.27  5302.8 2079.83
#Mann= 4 ,-1 , 0
  4606.8     .05       0  4652.3      .1       0  4996.9     .07       0
  5002.9      .1       0
Bank Sta=4971.5,5021.5
XS Rating Curve= 0 ,0
Exp/Cntr=0.3,0.1

Type RM Length L Ch R = 1 ,1956    ,437,437,437
BEGIN DESCRIPTION:
UNT 0016 IN HEWA 3.0
END DESCRIPTION:
XS GIS Cut Line= 2
      2642902.21     10078969.78      2642325.49     10078397.61
#Sta/Elev= 30
  4500.3 2078.02  4528.4 2076.61  4563.8 2073.53  4635.3 2071.02  4676.9 2068.85
  4726.4 2065.26  4741.4  2064.7  4804.2 2062.73  4832.5 2062.91  4853.7 2063.83
    4882 2064.29  4938.6 2063.73  4959.8 2062.94  4999.2 2060.12  5001.9 2059.62
  5005.2 2060.12  5016.3 2062.54  5023.4 2062.99  5058.8 2063.82  5065.9 2064.62
  5072.9 2064.63    5080 2065.68    5087 2065.45  5094.1 2066.22  5143.6 2067.86
  5164.9 2069.22    5186 2069.23  5256.8 2070.73  5292.1 2072.53  5312.7 2072.66
#Mann= 5 ,-1 , 0
  4500.3      .1       0  4635.3     .05       0  4741.4      .1       0
  4999.2     .07       0  5005.2      .1       0
Bank Sta=4959.8,5023.4
XS Rating Curve= 0 ,0
Exp/Cntr=0.3,0.1

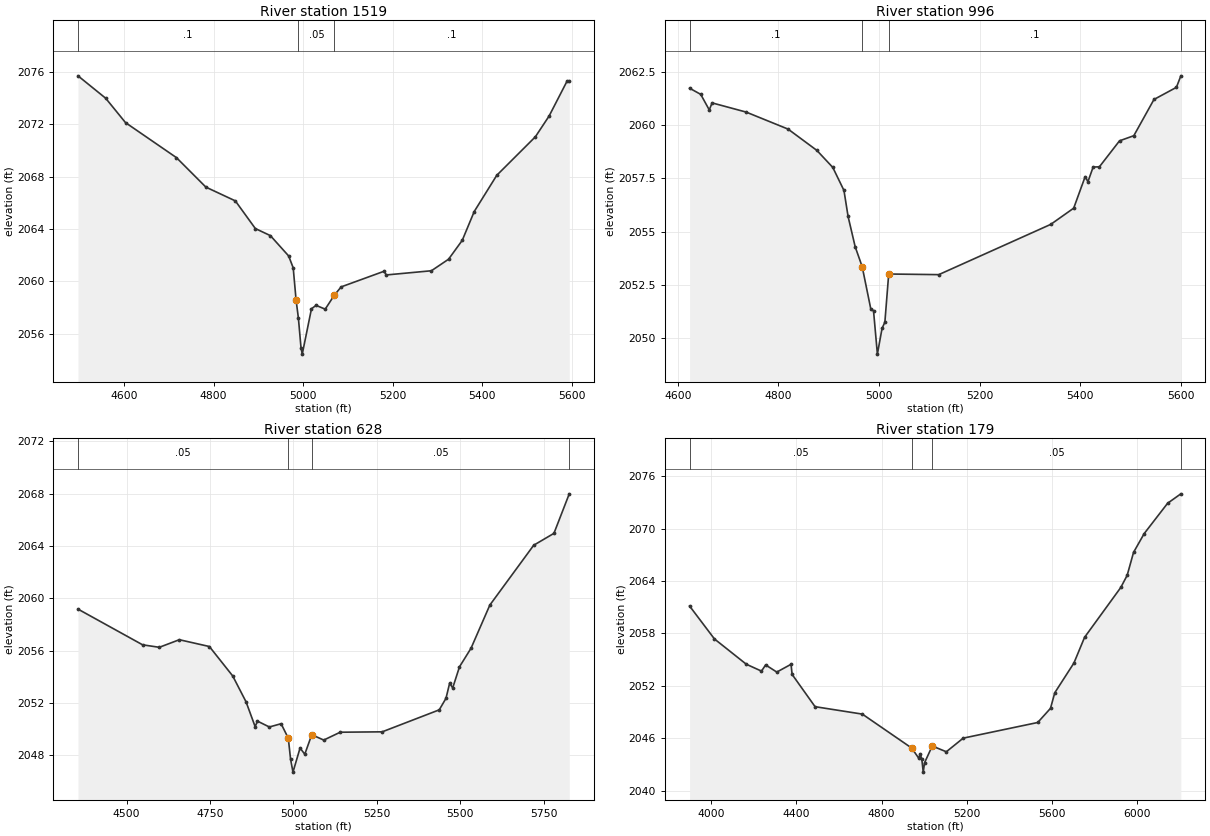
Type RM Length L Ch R = 1 ,1519    ,523,523,523
BEGIN DESCRIPTION:
UNT 0016 IN HEWA 2.0
END DESCRIPTION:
XS GIS Cut Line= 3
      2643184.32     10078714.94      2642961.37     10078387.33
      2642274.28     10078246.27
#Sta/Elev= 30
  4496.9 2075.68  4558.8 2073.97  4603.1 2072.11  4716.9 2069.44  4782.7 2067.19
  4848.5 2066.14  4893.2 2064.03  4926.8 2063.49  4967.6 2061.94  4977.8 2061.03
  4984.3 2058.55  4989.4  2057.2  4995.2 2054.95    4998 2054.45  5018.6 2057.91
  5028.9 2058.17  5049.3 2057.88  5069.7 2058.95    5085 2059.58  5180.7 2060.77
  5185.8 2060.49  5286.6 2060.81  5324.9 2061.69  5355.5 2063.13  5382.3 2065.33
  5432.6 2068.09  5518.9 2071.03  5549.5 2072.61  5589.9 2075.29  5594.6 2075.29
#Mann= 3 ,-1 , 0
  4496.9      .1       0  4989.4     .05       0  5069.7      .1       0
Bank Sta=4984.3,5069.7
XS Rating Curve= 0 ,0
Exp/Cntr=0.3,0.1

Type RM Length L Ch R = 1 ,996     ,368,368,368
BEGIN DESCRIPTION:
Mapping XS 2bfee346
END DESCRIPTION:
XS GIS Cut Line= 3
      2643202.56     10078310.01      2642956.82     10077804.87
      2642580.53     10077628.06
#Sta/Elev= 30
  4623.1 2061.73  4645.3 2061.44  4662.3 2060.71  4667.9 2061.04  4735.5 2060.61
  4819.1 2059.81  4876.4 2058.81  4908.1 2058.01  4930.3 2056.93  4938.5 2055.71
  4952.6 2054.29  4966.6 2053.35  4983.6 2051.38  4989.1 2051.29  4996.8 2049.25
  5006.1 2050.46  5011.7 2050.75  5019.3 2053.01  5118.9 2052.98  5341.8 2055.34
  5387.4  2056.1  5410.2 2057.58  5415.7 2057.34  5426.1 2058.03  5438.5 2058.04
  5478.6 2059.26    5507  2059.5  5547.1  2061.2  5591.8 2061.77  5600.6 2062.31
#Mann= 4 ,-1 , 0
  4623.1      .1       0  4966.6     .05       0  5019.3      .1       0
  5600.6      .1       0
Bank Sta=4966.6,5019.3
XS Rating Curve= 0 ,0
Exp/Cntr=0.3,0.1

Type RM Length L Ch R = 1 ,628     ,449,449,449
BEGIN DESCRIPTION:
Mapping XS 23a356d9
END DESCRIPTION:
XS GIS Cut Line= 4
      2643311.97     10078287.48       2643308.5     10077763.21
      2643051.56     10077478.49      2642493.02     10077395.23
#Sta/Elev= 30
  4354.1 2059.18  4547.8 2056.45  4597.9 2056.26  4657.9 2056.84  4747.9 2056.32
  4817.9 2054.07  4857.9 2052.09  4885.2 2050.19  4891.9 2050.62  4927.7 2050.17
  4962.9 2050.42  4984.5 2049.31  4991.3 2047.71  4998.5 2046.72  5019.7 2048.56
  5033.9 2048.09  5054.8 2049.58  5090.7 2049.17    5140 2049.77    5266  2049.8
  5436.9 2051.48  5457.1 2052.36    5468 2053.51  5477.3 2053.16  5497.6 2054.77
  5532.2 2056.19  5588.6 2059.49    5720 2064.06  5780.7 2064.97  5826.6 2067.99
#Mann= 4 ,-1 , 0
  4354.1     .05       0  4984.5    .035       0  5054.8     .05       0
  5826.6      .1       0
Bank Sta=4984.5,5054.8
XS Rating Curve= 0 ,0
Exp/Cntr=0.3,0.1

Type RM Length L Ch R = 1 ,179     ,0,0,0
BEGIN DESCRIPTION:
UNT 0016 IN HEWA 1.0
END DESCRIPTION:
XS GIS Cut Line= 4
      2643377.94     10078417.67      2643521.17     10077378.59
      2643429.61     10077240.96       2642336.3     10077221.55
#Sta/Elev= 30
  3898.3 2061.14  4015.2 2057.37  4164.7 2054.48  4236.1 2053.69  4255.6  2054.4
    4308 2053.58  4374.9 2054.47    4380 2053.31  4487.8 2049.62  4709.8 2048.77
    4942 2044.88  4975.1 2043.71  4981.1 2044.23  4989.1 2043.63  4995.9 2042.13
  5002.2 2043.21  5038.2 2045.12  5104.4 2044.46  5183.7 2046.02  5533.7 2047.81
  5593.7 2049.43  5613.7 2051.21  5703.8 2054.62  5753.8 2057.56  5923.8 2063.26
  5953.8 2064.65  5983.8 2067.28  6033.8 2069.43  6143.8  2072.9    6206 2073.98
#Mann= 4 ,-1 , 0
  3898.3     .05       0    4942    .035       0  5038.2     .05       0
    6206      .1       0
Bank Sta=4942,5038.2
XS Rating Curve= 0 ,0
Exp/Cntr=0.3,0.1

Chan Stop Cuts=-1
Use User Specified Reach Order=0
Composite Channel Slope=5