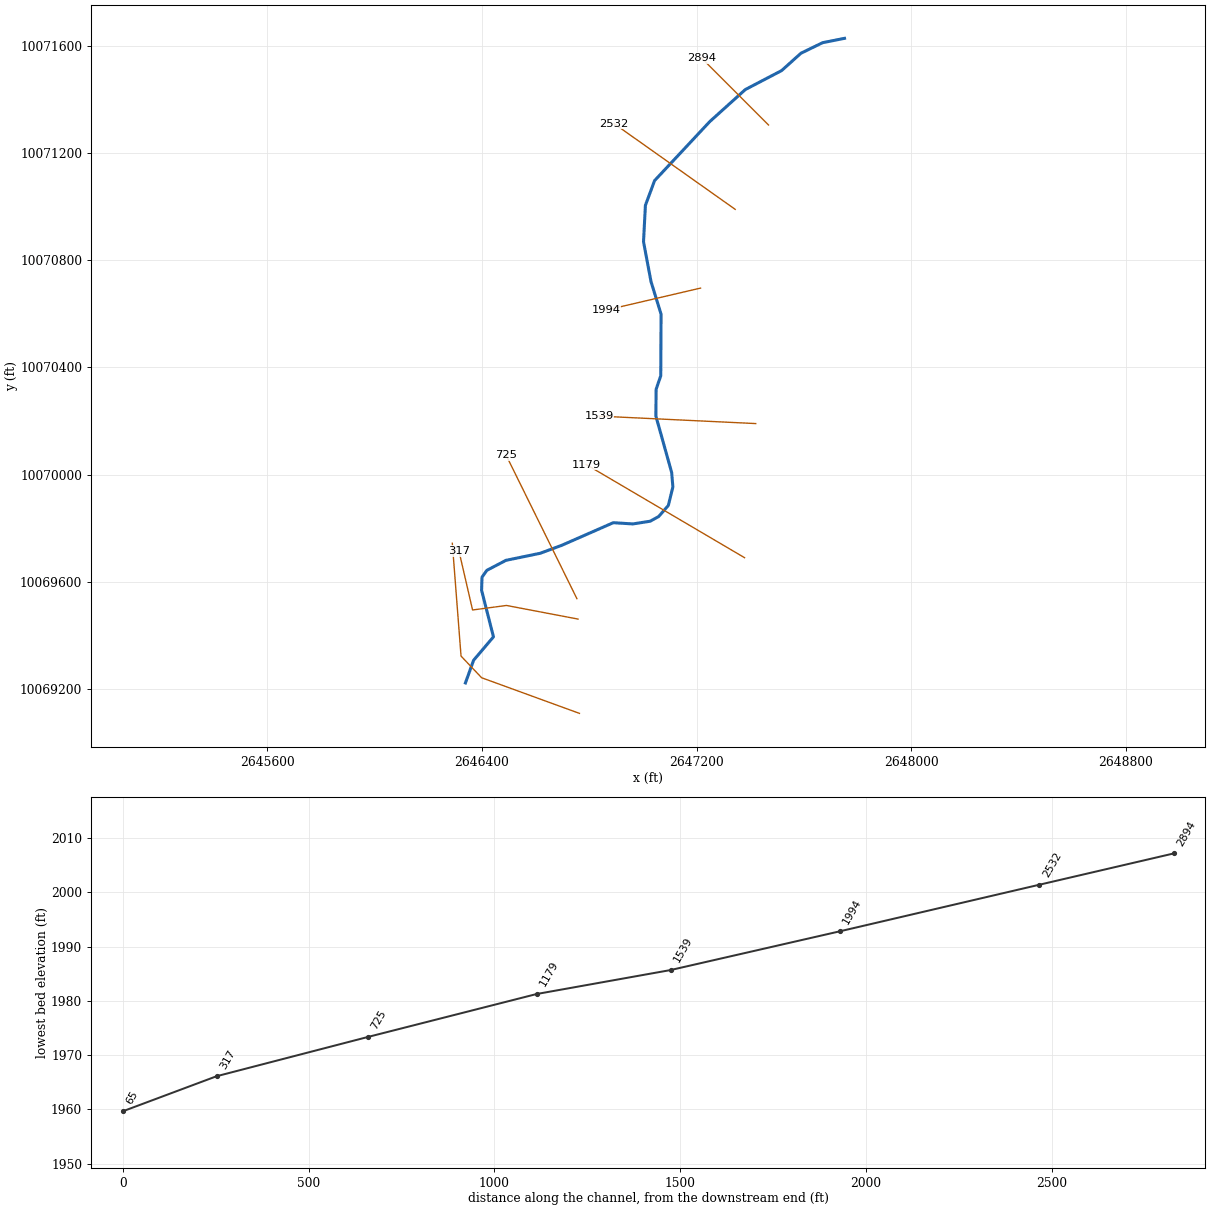
--- UNT 0017 IN HEWA.prj (project) ---

Proj Title=UNT 0017 IN HEWA Base Level Engineering
Current Plan=p01
Default Exp/Contr=0.3,0.1
English Units
Geom File=g01
Flow File=f01
Plan File=p01
BEGIN DESCRIPTION:
UNT 0017 IN HEWA
END DESCRIPTION:

--- UNT 0017 IN HEWA.p01 (plan) ---

Plan Title=Multiple Run
Short Identifier=Multiple
Geom File=g01
Flow File=f01
Subcritical Flow
K Sum by GR= 0
Std Step Tol= 0.01
Critical Tol= 0.01
Num of Std Step Trials= 20
Max Error Tol= 0.3
Flow Tol Ratio= 0.001
Split Flow NTrial= 30
Split Flow Tol= 0.02
Split Flow Ratio= 0.02
Log Output Level= 0
Friction Slope Method= 1
Unsteady Friction Slope Method= 2
Unsteady Bridges Friction Slope Method= 1
Parabolic Critical Depth
Global Vel Dist=  1 , 1 , 1
Global Log Level= 0
CheckData=True
Encroach Param= -1, 0, 0, 0
BEGIN DESCRIPTION:
Multiple Run
END DESCRIPTION:

--- UNT 0017 IN HEWA.f01 (steady flow) ---

Flow Title=Multiple
Number of Profiles=7
Profile Names=10-year,25-year,50-year,1pct_min,100-year,1pct_plu,500-year
River Rch & RM= UNT 0017 IN HEWA,Reach-1,2894
    1169    1718    2195    2046    2767    3742    4395
Boundary for River Rch & Prof#=UNT 0017 IN HEWA,Reach-1,1
Up Type=0
Dn Type=3
Dn Slope=0.005
Boundary for River Rch & Prof#=UNT 0017 IN HEWA,Reach-1,2
Up Type=0
Dn Type=3
Dn Slope=0.005
Boundary for River Rch & Prof#=UNT 0017 IN HEWA,Reach-1,3
Up Type=0
Dn Type=3
Dn Slope=0.005
Boundary for River Rch & Prof#=UNT 0017 IN HEWA,Reach-1,4
Up Type=0
Dn Type=3
Dn Slope=0.005
Boundary for River Rch & Prof#=UNT 0017 IN HEWA,Reach-1,5
Up Type=0
Dn Type=3
Dn Slope=0.005
Boundary for River Rch & Prof#=UNT 0017 IN HEWA,Reach-1,6
Up Type=0
Dn Type=3
Dn Slope=0.005
Boundary for River Rch & Prof#=UNT 0017 IN HEWA,Reach-1,7
Up Type=0
Dn Type=3
Dn Slope=0.005

--- UNT 0017 IN HEWA.g01 (geometry) ---

Geom Title=Existing Conditions

River Reach=UNT 0017 IN HEWA,Reach-1
Reach XY= 30
      2647751.79     10071626.83      2647669.81     10071610.48
      2647589.41     10071571.28      2647517.22     10071506.53
      2647381.93     10071435.87      2647249.45     10071316.43
      2647043.67     10071096.29      2647009.48     10071004.32
      2647002.41     10070868.71      2647030.42     10070719.54
      2647067.85     10070598.48      2647066.71     10070368.80
      2647049.37     10070318.42      2647048.50     10070218.77
      2647107.49     10070007.63      2647111.83     10069954.14
      2647094.83     10069885.17      2647058.68     10069843.88
      2647027.31     10069826.57      2646963.00     10069816.47
      2646889.71     10069821.01      2646697.29     10069736.57
      2646617.11     10069707.01      2646489.67     10069680.74
      2646418.23     10069643.39      2646400.29     10069618.05
      2646398.71     10069569.21      2646443.02     10069395.38
      2646368.97     10069308.22      2646338.47     10069223.73

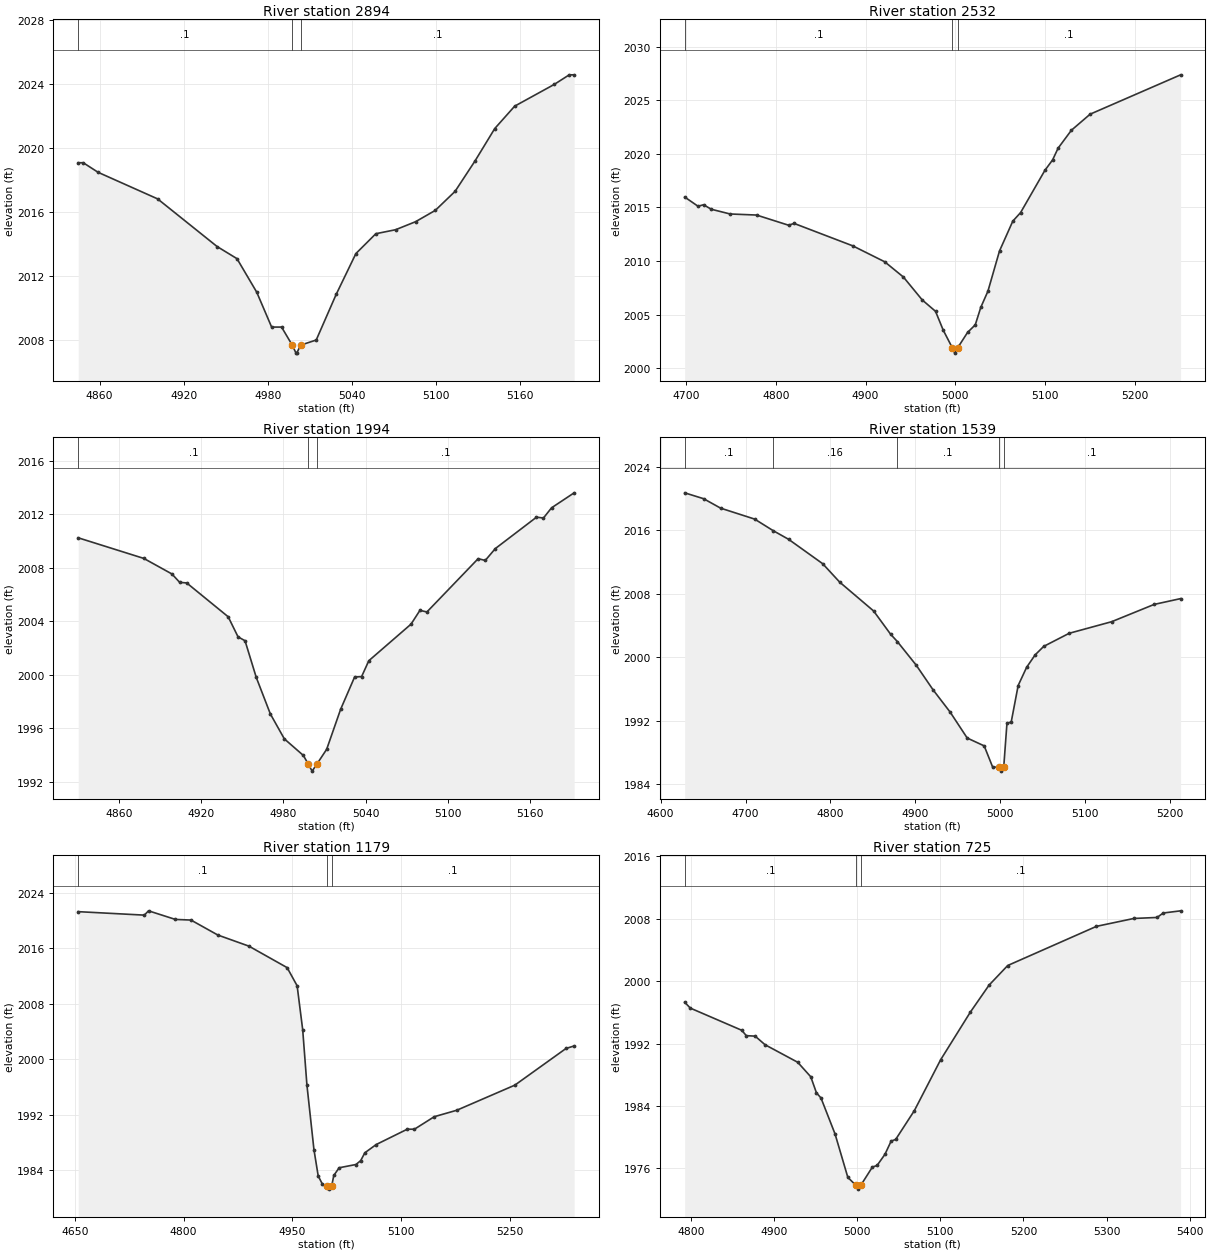
Type RM Length L Ch R = 1,2894,362,362,362
BEGIN DESCRIPTION:
UNT 0017 IN HEWA 6.0
END DESCRIPTION:
XS GIS Cut Line= 3
      2647468.49     10071303.71      2647368.47     10071403.73
      2647218.46     10071553.74
#Sta/Elev= 27
  4844.8 2019.08  4848.4 2019.08  4859.0 2018.48  4901.4 2016.82  4943.8 2013.84
  4958.0 2013.08  4972.1 2010.98  4982.7 2008.80  4989.8 2008.80  4997.4 2007.67
  5000.1 2007.17  5000.6 2007.17  5003.4 2007.67  5014.5 2007.99  5028.7 2010.84
  5042.8 2013.40  5057.0 2014.64  5071.1 2014.89  5085.3 2015.39  5099.4 2016.10
  5113.5 2017.29  5127.7 2019.19  5141.8 2021.22  5156.0 2022.62  5184.2 2023.98
  5194.9 2024.58  5198.4 2024.58
#Mann=3,-1,0
  4844.8     0.1       0  4997.4    0.07       0  5003.4     0.1       0
Bank Sta=4997.4,5003.4
Exp/Cntr=0.3,0.1

Type RM Length L Ch R = 1,2532,538,538,538
BEGIN DESCRIPTION:
UNT 0017 IN HEWA 5.0
END DESCRIPTION:
XS GIS Cut Line= 2
      2647344.32     10070989.22      2646893.25     10071308.44
#Sta/Elev= 30
  4698.5 2015.96  4713.4 2015.10  4719.5 2015.24  4728.2 2014.82  4749.1 2014.38
  4778.6 2014.28  4814.3 2013.33  4820.4 2013.50  4885.7 2011.41  4921.4 2009.92
  4942.3 2008.49  4963.2 2006.36  4978.0 2005.30  4986.6 2003.54  4996.7 2001.90
  4999.4 2001.40  5002.7 2001.90  5013.7 2003.33  5022.3 2004.04  5028.4 2005.66
  5036.4 2007.18  5049.3 2010.93  5064.1 2013.71  5072.8 2014.51  5099.8 2018.44
  5108.5 2019.43  5114.6 2020.52  5129.4 2022.19  5150.3 2023.69  5251.1 2027.36
#Mann=3,-1,0
  4698.5     0.1       0  4996.7    0.07       0  5002.7     0.1       0
Bank Sta=4996.7,5002.7
Exp/Cntr=0.3,0.1

Type RM Length L Ch R = 1,1994,455,455,455
BEGIN DESCRIPTION:
UNT 0017 IN HEWA 4.0
END DESCRIPTION:
XS GIS Cut Line= 2
      2647215.08     10070695.69      2646862.44     10070613.47
#Sta/Elev= 30
  4830.2 2010.23  4878.1 2008.69  4898.6 2007.53  4904.3 2006.90  4909.4 2006.86
  4939.7 2004.33  4946.9 2002.83  4952.0 2002.54  4960.2 1999.80  4970.5 1997.07
  4980.7 1995.21  4994.6 1993.97  4998.3 1993.30  5001.0 1992.80  5004.3 1993.30
  5011.6 1994.43  5021.8 1997.42  5032.0 1999.83  5037.1 1999.86  5042.4 2001.05
  5073.2 2003.78  5079.7 2004.81  5084.8 2004.69  5122.2 2008.67  5127.4 2008.54
  5134.8 2009.43  5164.8 2011.77  5169.9 2011.71  5175.8 2012.47  5192.3 2013.59
#Mann=3,-1,0
  4830.2     0.1       0  4998.3    0.07       0  5004.3     0.1       0
Bank Sta=4998.3,5004.3
Exp/Cntr=0.3,0.1

Type RM Length L Ch R = 1,1539,360,360,360
BEGIN DESCRIPTION:
UNT 0017 IN HEWA 3.0
END DESCRIPTION:
XS GIS Cut Line= 2
      2647420.74     10070190.59      2646837.40     10070218.37
#Sta/Elev= 30
  4628.3 2020.74  4650.6 2020.00  4670.6 2018.81  4710.7 2017.43  4732.4 2015.98
  4750.7 2014.88  4790.8 2011.81  4810.8 2009.49  4850.8 2005.85  4870.8 2002.92
  4878.7 2002.00  4900.9 1999.03  4920.9 1995.90  4940.9 1993.11  4961.0 1989.84
  4981.0 1988.85  4991.0 1986.17  4998.0 1986.17  5000.7 1985.67  5004.0 1986.17
  5007.8 1991.70  5012.8 1991.85  5021.0 1996.46  5031.0 1998.76  5041.0 2000.32
  5051.1 2001.39  5081.1 2003.04  5131.1 2004.50  5181.2 2006.68  5212.3 2007.41
#Mann=5,-1,0
  4628.3     0.1       0  4732.4    0.16       0  4878.7     0.1       0
  4998.0    0.07       0  5004.0     0.1       0
Bank Sta=4998,5004
Exp/Cntr=0.3,0.1

Type RM Length L Ch R = 1,1179,454,454,454
BEGIN DESCRIPTION:
UNT 0017 IN HEWA 2.0
END DESCRIPTION:
XS GIS Cut Line= 2
      2647379.03     10069690.61      2646788.78     10070037.82
#Sta/Elev= 30
  4654.4 2021.26  4745.7 2020.76  4751.5 2021.38  4788.6 2020.14  4810.1 2020.05
  4847.2 2017.89  4890.1 2016.29  4942.9 2013.19  4956.7 2010.57  4964.4 2004.21
  4970.2 1996.27  4979.9 1986.96  4985.8 1983.15  4991.6 1981.98  4998.5 1981.76
  5001.3 1981.26  5004.5 1981.76  5007.3 1983.23  5014.7 1984.34  5037.9 1984.81
  5044.4 1985.36  5050.2 1986.50  5065.9 1987.69  5108.8 1989.90  5118.7 1989.90
  5146.0 1991.70  5177.1 1992.63  5257.3 1996.25  5328.0 2001.54  5339.2 2001.90
#Mann=3,-1,0
  4654.4     0.1       0  4998.5    0.07       0  5004.5     0.1       0
Bank Sta=4998.5,5004.5
Exp/Cntr=0.3,0.1

Type RM Length L Ch R = 1,725,408,408,408
BEGIN DESCRIPTION:
Mapping XS 5279fa73
END DESCRIPTION:
XS GIS Cut Line= 2
      2646754.08     10069537.79      2646490.19     10070072.52
#Sta/Elev= 30
  4792.7 1997.31  4799.5 1996.55  4861.3 1993.71  4866.8 1993.02  4877.4 1992.96
  4889.3 1991.86  4928.6 1989.61  4944.3 1987.75  4951.1 1985.70  4956.6 1985.03
  4973.5 1980.42  4988.9 1974.85  4998.5 1973.85  5001.3 1973.35  5004.5 1973.85
  5018.4 1976.18  5024.0 1976.38  5033.5 1977.81  5040.9 1979.50  5046.4 1979.72
  5068.9 1983.42  5100.4 1989.92  5136.2 1996.04  5158.7 1999.50  5181.1 2002.01
  5287.8 2007.03  5332.7 2008.04  5360.7 2008.17  5368.1 2008.74  5389.0 2009.02
#Mann=3,-1,0
  4792.7     0.1       0  4998.5    0.07       0  5004.5     0.1       0
Bank Sta=4998.5,5004.5
Exp/Cntr=0.3,0.1

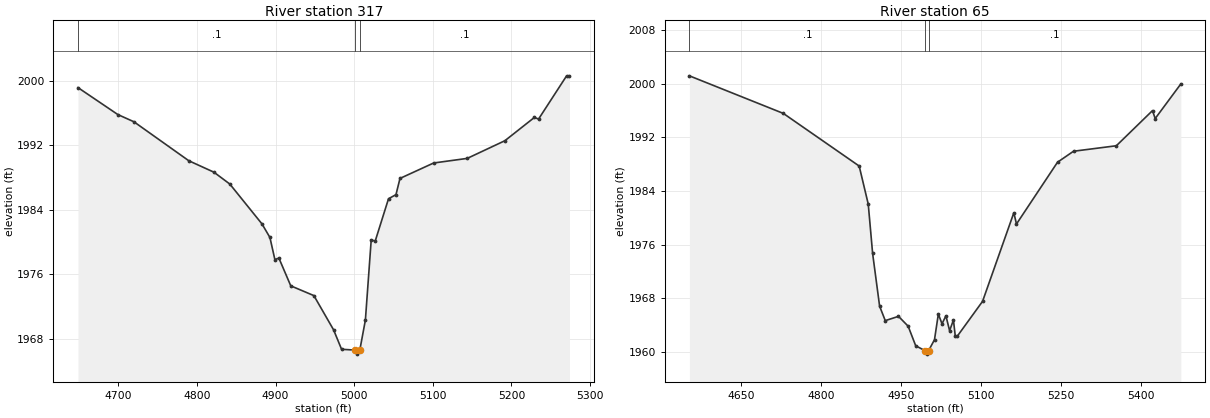
Type RM Length L Ch R = 1,317,252,252,252
BEGIN DESCRIPTION:
Mapping XS 3082fb0b
END DESCRIPTION:
XS GIS Cut Line= 4
      2646758.31     10069461.72      2646491.39     10069512.50
      2646365.09     10069495.57      2646314.30     10069715.65
#Sta/Elev= 30
  4648.7 1999.12  4699.4 1995.78  4719.8 1994.89  4789.6 1990.06  4821.6 1988.64
  4841.8 1987.17  4882.7 1982.23  4892.8 1980.55  4899.1 1977.81  4904.2 1978.00
  4919.3 1974.56  4948.7 1973.35  4973.8 1969.10  4983.9 1966.70  5001.1 1966.60
  5003.8 1966.10  5007.1 1966.60  5014.2 1970.32  5021.6 1980.25  5026.7 1980.11
  5043.6 1985.35  5053.1 1985.86  5058.2 1987.87  5101.0 1989.78  5143.7 1990.35
  5191.6 1992.54  5229.2 1995.43  5234.4 1995.22  5270.1 2000.58  5273.7 2000.58
#Mann=3,-1,0
  4648.7     0.1       0  5001.1    0.07       0  5007.1     0.1       0
Bank Sta=5001.1,5007.1
Exp/Cntr=0.3,0.1

Type RM Length L Ch R = 1,65,0,0,0
BEGIN DESCRIPTION:
UNT 0017 IN HEWA 1.0
END DESCRIPTION:
XS GIS Cut Line= 4
      2646763.52     10069110.16      2646398.94     10069242.97
      2646322.12     10069323.70      2646289.57     10069744.29
#Sta/Elev= 30
  4553.4 2001.20  4729.5 1995.59  4871.7 1987.73  4888.7 1982.05  4896.9 1974.68
  4910.0 1966.81  4920.6 1964.65  4945.4 1965.29  4963.5 1963.82  4977.7 1960.89
  4995.7 1960.15  4998.5 1959.65  5001.7 1960.15  5012.9 1961.81  5020.1 1965.63
  5027.0 1964.18  5034.3 1965.37  5041.2 1963.15  5048.4 1964.74  5051.9 1962.30
  5055.4 1962.30  5103.0 1967.53  5161.6 1980.75  5166.6 1979.08  5243.5 1988.30
  5273.5 1989.94  5353.8 1990.76  5421.6 1996.01  5426.6 1994.82  5474.7 1999.99
#Mann=3,-1,0
  4553.4     0.1       0  4995.7    0.07       0  5001.7     0.1       0
Bank Sta=4995.7,5001.7
Exp/Cntr=0.3,0.1

Chan Stop Cuts=-1