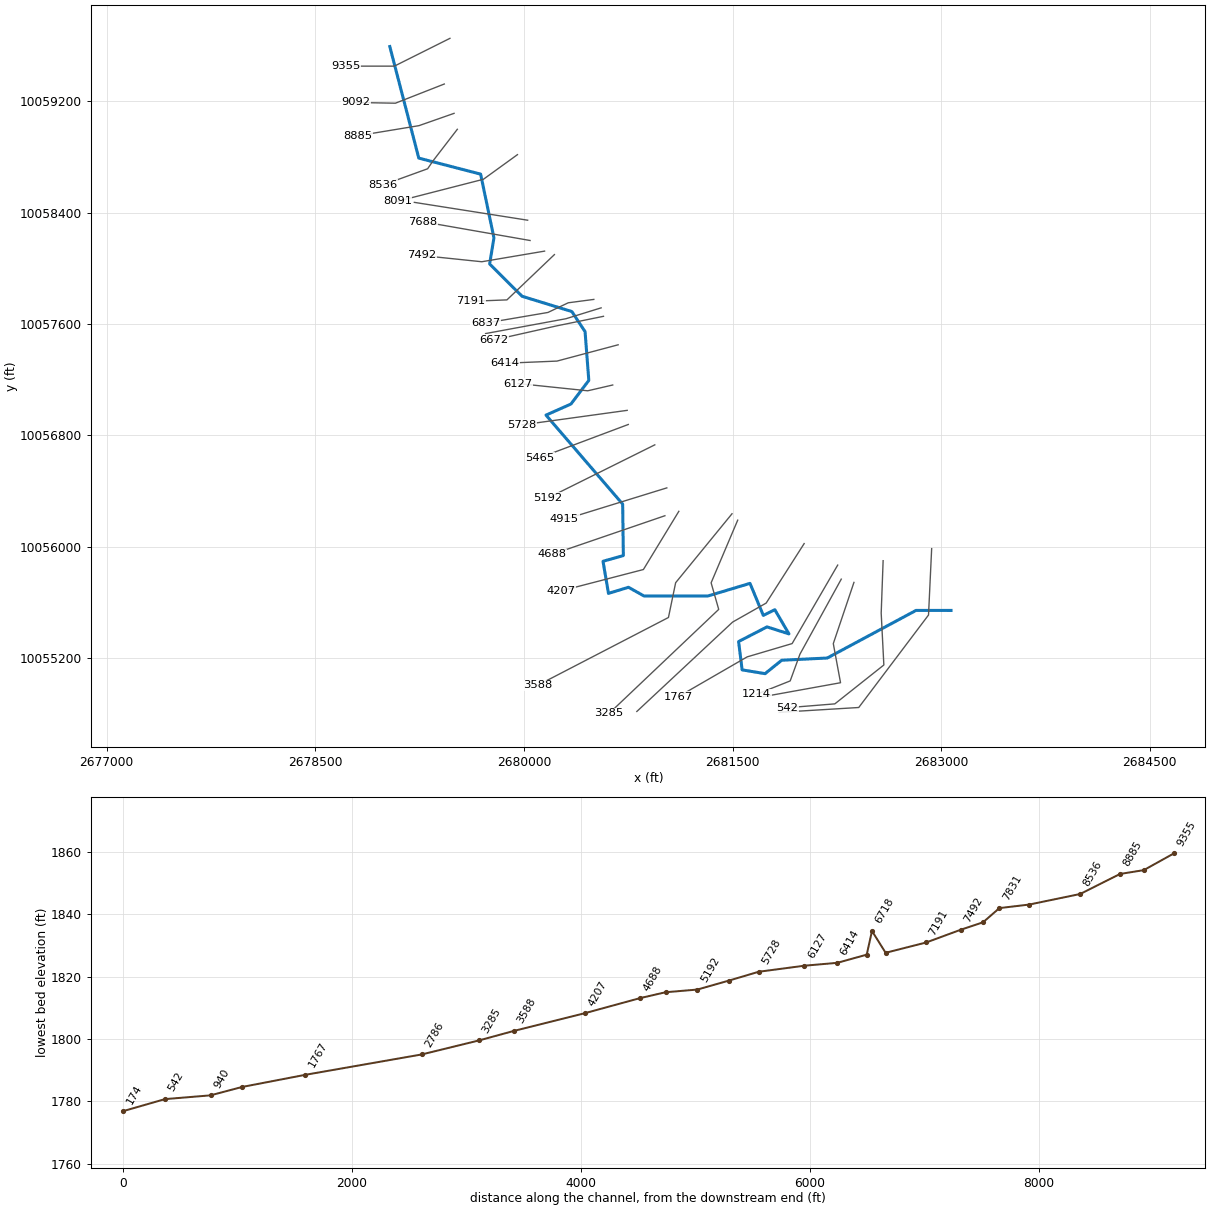
--- UNT 0018 IN HEWA.prj (project) ---

Proj Title=UNT 0018 IN HEWA Base Level Engineering
Current Plan=p01
Default Exp/Contr=0.3,0.1
English Units
Geom File=g01
Flow File=f01
Plan File=p01
Y Axis Title=Elevation
X Axis Title(PF)=Main Channel Distance
X Axis Title(XS)=Station
BEGIN DESCRIPTION:
UNT 0018 IN HEWA
END DESCRIPTION:
DSS Export Rating Curves= 0
DSS Export Rating Curve Sorted= 0
DSS Export Volume Flow Curves= 0
DXF OffsetX= 0
DXF OffsetY= 0
DXF ScaleX= 1
DXF ScaleY= 10

--- UNT 0018 IN HEWA.p01 (plan) ---

Plan Title=Multiple Run
Short Identifier=Multiple
Geom File=g01
Flow File=f01
Subcritical Flow
K Sum by GR= 0
Std Step Tol= 0.01
Critical Tol= 0.01
Num of Std Step Trials= 20
Max Error Tol= 0.3
Flow Tol Ratio= 0.001
Split Flow NTrial= 30
Split Flow Tol= 0.02
Split Flow Ratio= 0.02
Log Output Level= 0
Friction Slope Method= 1
Unsteady Friction Slope Method= 2
Unsteady Bridges Friction Slope Method= 1
Parabolic Critical Depth
Global Vel Dist=  1 , 1 , 1
Global Log Level= 0
CheckData=True
Encroach Param= -1, 0, 0, 0
BEGIN DESCRIPTION:
Multiple Run
END DESCRIPTION:

--- UNT 0018 IN HEWA.f01 (steady flow) ---

Flow Title=Multiple
Number of Profiles=7
Profile Names=10-year,25-year,50-year,1pct_min,100-year,1pct_plu,500-year
River Rch & RM= UNT 0018 IN HEWA,Reach-1,9355
    1586    2342    3005    2805    3794    5131    6050
Boundary for River Rch & Prof#=UNT 0018 IN HEWA,Reach-1,1
Up Type=0
Dn Type=3
Dn Slope=0.005
Boundary for River Rch & Prof#=UNT 0018 IN HEWA,Reach-1,2
Up Type=0
Dn Type=3
Dn Slope=0.005
Boundary for River Rch & Prof#=UNT 0018 IN HEWA,Reach-1,3
Up Type=0
Dn Type=3
Dn Slope=0.005
Boundary for River Rch & Prof#=UNT 0018 IN HEWA,Reach-1,4
Up Type=0
Dn Type=3
Dn Slope=0.005
Boundary for River Rch & Prof#=UNT 0018 IN HEWA,Reach-1,5
Up Type=0
Dn Type=3
Dn Slope=0.005
Boundary for River Rch & Prof#=UNT 0018 IN HEWA,Reach-1,6
Up Type=0
Dn Type=3
Dn Slope=0.005
Boundary for River Rch & Prof#=UNT 0018 IN HEWA,Reach-1,7
Up Type=0
Dn Type=3
Dn Slope=0.005

--- UNT 0018 IN HEWA.g01 (geometry) ---

Geom Title=Existing Conditions
Program Version=4.10

River Reach=UNT 0018 IN HEWA,Reach-1
Reach XY= 30
      2679036.04     10059594.57      2679244.34      10058792.6
      2679688.99     10058677.34      2679784.72     10058218.74
      2679753.84      10058031.2      2679986.79     10057799.35
      2680344.85     10057689.29      2680439.98     10057544.58
      2680466.84     10057194.49      2680338.28     10057024.34
      2680158.99      10056944.7      2680710.26     10056304.94
      2680715.16     10055934.77      2680568.99     10055893.84
      2680608.15     10055662.99      2680752.16     10055706.94
       2680863.7     10055644.23      2681323.13     10055644.18
      2681625.77       10055735.       2681721.5      10055504.7
      2681804.04     10055545.74       2681905.7     10055371.83
      2681748.02      10055422.1      2681543.74     10055316.64
       2681569.2     10055113.13      2681734.05     10055085.79
        2681854.     10055182.27      2682181.24     10055198.26
      2682819.77     10055540.73      2683071.42     10055540.38

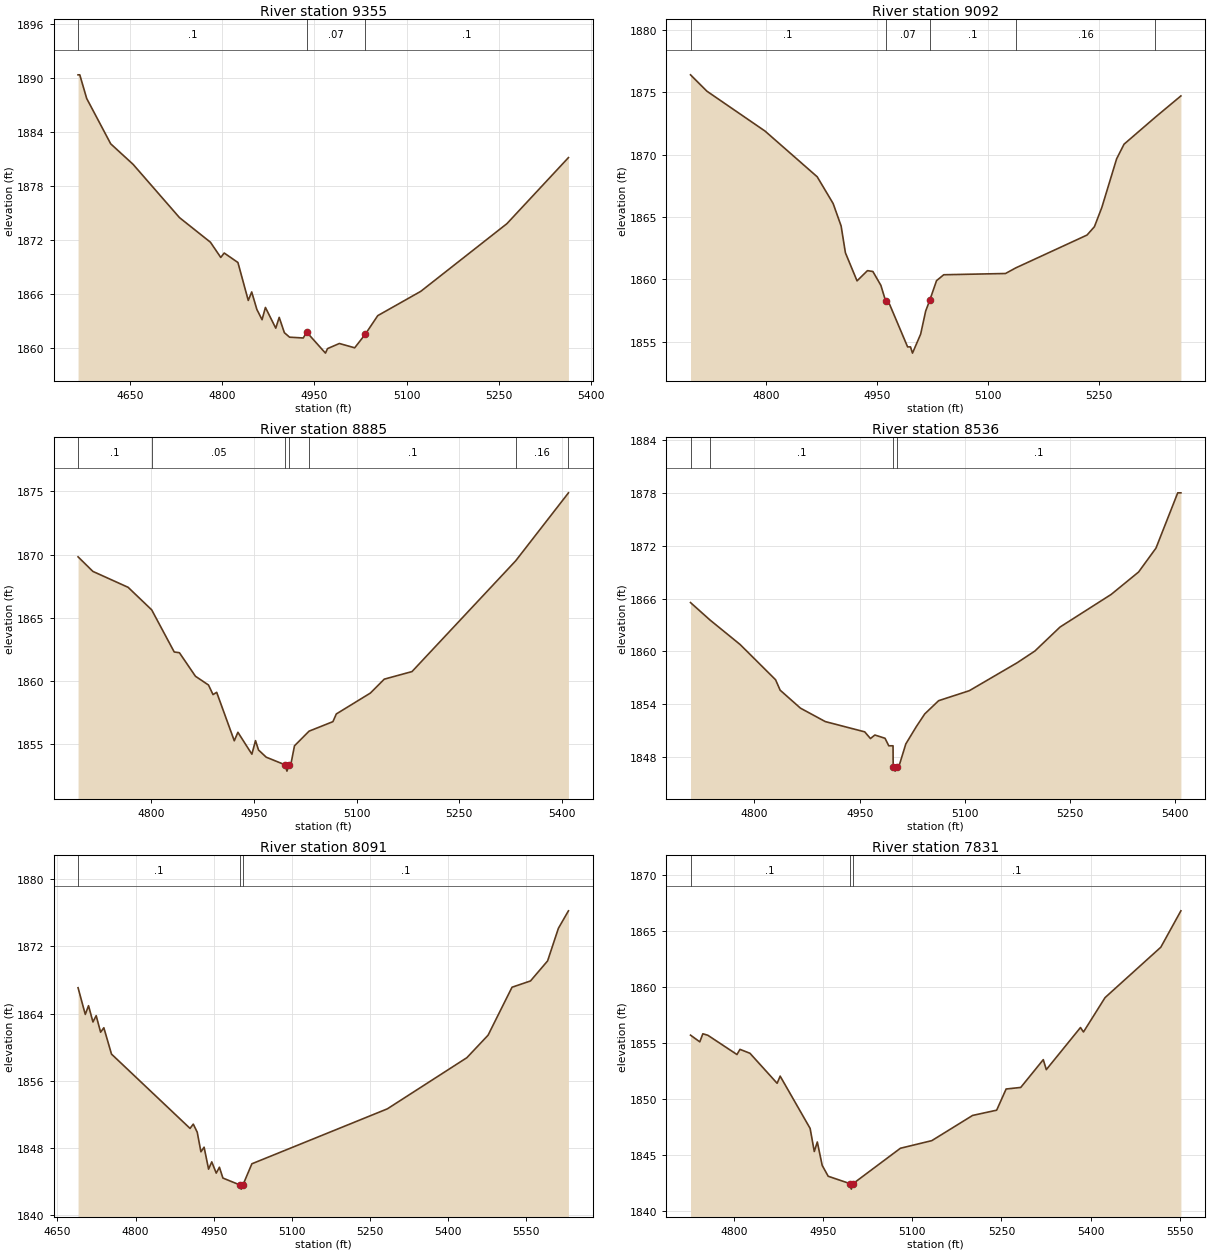
Type RM Length L Ch R = 1 ,9355    ,263,263,263
BEGIN DESCRIPTION:
UNT 0018 IN HEWA 18.0
END DESCRIPTION:
XS GIS Cut Line= 3
      2679468.45     10059653.73      2679068.47     10059453.73
      2678718.47     10059453.73
#Sta/Elev= 30
  4565.8 1890.35  4568.6 1890.35  4579.8 1887.73  4618.9 1882.69  4655.2 1880.42
  4730.7  1874.5    4781 1871.77  4797.8 1870.08  4803.4 1870.57  4825.7 1869.52
  4842.5 1865.31  4848.1 1866.25  4856.5 1864.31  4864.9 1863.17  4870.4 1864.53
  4887.2 1862.23  4892.8 1863.43  4901.2 1861.73  4909.6 1861.23  4931.9 1861.14
  4937.5 1861.79    4968 1859.46  4971.3 1859.96  4990.6 1860.53  5015.5 1860.05
    5033 1861.58    5053 1863.62    5123 1866.32    5263 1873.83    5363 1881.16
#Mann= 3 , 0 , 0
  4565.8      .1       0  4937.5     .07       0    5033      .1       0
Bank Sta=4937.5,5033
XS Rating Curve= 0 ,0
Exp/Cntr=0.3,0.1

Type RM Length L Ch R = 1 ,9092    ,207,207,207
BEGIN DESCRIPTION:
Mapping XS f1044a6f
END DESCRIPTION:
XS GIS Cut Line= 3
      2679427.78     10059325.33      2679076.22     10059187.32
      2678791.64     10059192.49
#Sta/Elev= 30
  4698.4  1876.4  4720.5 1875.09  4799.1 1871.89  4869.5 1868.23    4891 1866.09
  4901.8 1864.29  4907.6 1862.14  4923.3 1859.89  4937.4 1860.71  4944.7 1860.64
  4955.5 1859.53  4961.8  1858.3  4967.2 1858.02  4991.6  1854.6  4995.5  1854.6
  4998.2  1854.1  5009.2 1855.62    5016 1857.47  5021.4 1858.32  5030.7 1859.91
  5040.4 1860.38  5123.8 1860.48  5137.7 1860.93  5233.9 1863.56  5243.9 1864.23
  5253.9 1865.77  5273.9 1869.67  5283.9 1870.84  5326.3 1873.01  5360.7 1874.71
#Mann= 5 ,-1 , 0
  4698.4      .1       0  4961.8     .07       0  5021.4      .1       0
  5137.7     .16       0  5326.3      .1       0
Bank Sta=4961.8,5021.4
XS Rating Curve= 0 ,0
Exp/Cntr=0.3,0.1

Type RM Length L Ch R = 1 ,8885    ,349,349,349
BEGIN DESCRIPTION:
UNT 0018 IN HEWA 17.0
END DESCRIPTION:
XS GIS Cut Line= 3
      2679498.11      10059114.4      2679245.49     10059025.86
      2678803.14       10058953.
#Sta/Elev= 30
  4693.3 1869.82  4714.9 1868.67  4766.4 1867.41  4800.8 1865.63  4833.7  1862.3
  4841.3 1862.24  4864.7 1860.38  4883.7 1859.69  4890.4 1858.93  4895.7 1859.11
  4921.4 1855.28  4926.7 1855.95  4947.1 1854.22  4952.4 1855.29  4956.8 1854.55
  4968.1 1853.98  4995.5 1853.38  4998.3 1852.88  5001.5 1853.38  5004.2 1853.47
  5009.3 1854.88  5030.6 1856.04  5065.4 1856.79  5070.4  1857.4  5120.1 1859.05
  5140.4 1860.15  5180.9 1860.75  5332.2  1869.5  5408.8 1874.84  5409.3 1874.88
#Mann= 7 ,-1 , 0
  4693.3      .1       0  4800.8     .05       0  4995.5    .035       0
  5001.5     .05       0  5030.6      .1       0  5332.2     .16       0
  5408.8      .1       0
Bank Sta=4995.5,5001.5
XS Rating Curve= 0 ,0
Exp/Cntr=0.3,0.1

Type RM Length L Ch R = 1 ,8536    ,445,445,445
BEGIN DESCRIPTION:
UNT 0018 IN HEWA 16.0
END DESCRIPTION:
XS GIS Cut Line= 4
      2679521.51     10058999.78      2679347.06     10058773.25
      2679307.99     10058715.96      2678985.06     10058598.77
#Sta/Elev= 30
    4709 1865.54  4736.7 1863.57  4779.7 1860.79  4830.2  1856.8  4836.7 1855.62
  4865.7 1853.58  4901.1 1852.06  4957.2  1850.9  4965.4 1850.14  4971.7 1850.54
  4986.2 1850.17  4991.5 1849.32  4997.6 1849.32  4997.8 1846.95  5000.6 1846.45
  5003.8 1846.95  5006.9 1847.23  5015.8 1849.53  5030.6 1851.47  5042.8 1852.93
  5062.6 1854.43  5106.3 1855.56  5174.4 1858.72  5199.7 1860.05  5235.6 1862.77
  5308.4 1866.46  5347.5    1869  5372.3 1871.71  5403.3 1877.97  5407.8 1877.97
#Mann= 4 ,-1 , 0
    4709     .05       0  4736.7      .1       0  4997.8     .07       0
  5003.8      .1       0
Bank Sta=4997.8,5003.8
XS Rating Curve= 0 ,0
Exp/Cntr=0.3,0.1

Type RM Length L Ch R = 1 ,8091    ,260,260,260
BEGIN DESCRIPTION:
UNT 0018 IN HEWA 15.0
END DESCRIPTION:
XS GIS Cut Line= 3
      2679953.83     10058817.52      2679709.04     10058640.44
      2679089.74     10058481.48
#Sta/Elev= 30
  4689.7 1867.08  4703.6  1863.9  4709.8 1864.94  4718.3    1863  4724.5 1863.75
    4733 1861.78  4739.2 1862.31  4753.9 1859.17  4904.7 1850.31  4910.9 1850.82
  4918.5 1849.86  4925.6 1847.52  4931.7 1848.07  4940.3 1845.45  4946.4 1846.32
    4955 1844.98  4961.1 1845.68  4967.8 1844.39  5000.3 1843.57    5003 1843.07
  5006.3 1843.57  5023.4 1846.09  5283.5 1852.64  5436.2 1858.74  5476.9 1861.42
  5522.9 1867.14  5558.4 1867.89  5591.2 1870.28  5611.9 1874.16  5631.2 1876.25
#Mann= 3 ,-1 , 0
  4689.7      .1       0  5000.3     .07       0  5006.3      .1       0
Bank Sta=5000.3,5006.3
XS Rating Curve= 0 ,0
Exp/Cntr=0.3,0.1

Type RM Length L Ch R = 1 ,7831    ,143,143,143
BEGIN DESCRIPTION:
Mapping XS 5fdd105e
END DESCRIPTION:
XS GIS Cut Line= 2
      2680027.23     10058346.05      2679212.37     10058474.35
#Sta/Elev= 30
  4726.9 1855.69  4742.5 1855.09  4747.6 1855.81    4756 1855.68    4805 1853.96
  4810.1 1854.42  4826.9 1854.07  4872.6 1851.39  4877.7 1852.03  4928.1 1847.36
  4935.1  1845.3  4940.2 1846.15  4948.4 1844.06  4958.5 1843.09  4994.6 1842.44
  4997.4 1841.94  5000.6 1842.44    5080 1845.59  5132.8 1846.27  5201.4 1848.52
  5241.9 1848.99  5257.8 1850.88  5282.4 1851.02  5320.3  1853.5  5325.4 1852.61
  5382.9 1856.37  5387.9 1855.97  5424.2 1859.04    5518 1863.54  5551.8 1866.79
#Mann= 3 ,-1 , 0
  4726.9      .1       0  4994.6     .07       0  5000.6      .1       0
Bank Sta=4994.6,5000.6
XS Rating Curve= 0 ,0
Exp/Cntr=0.3,0.1

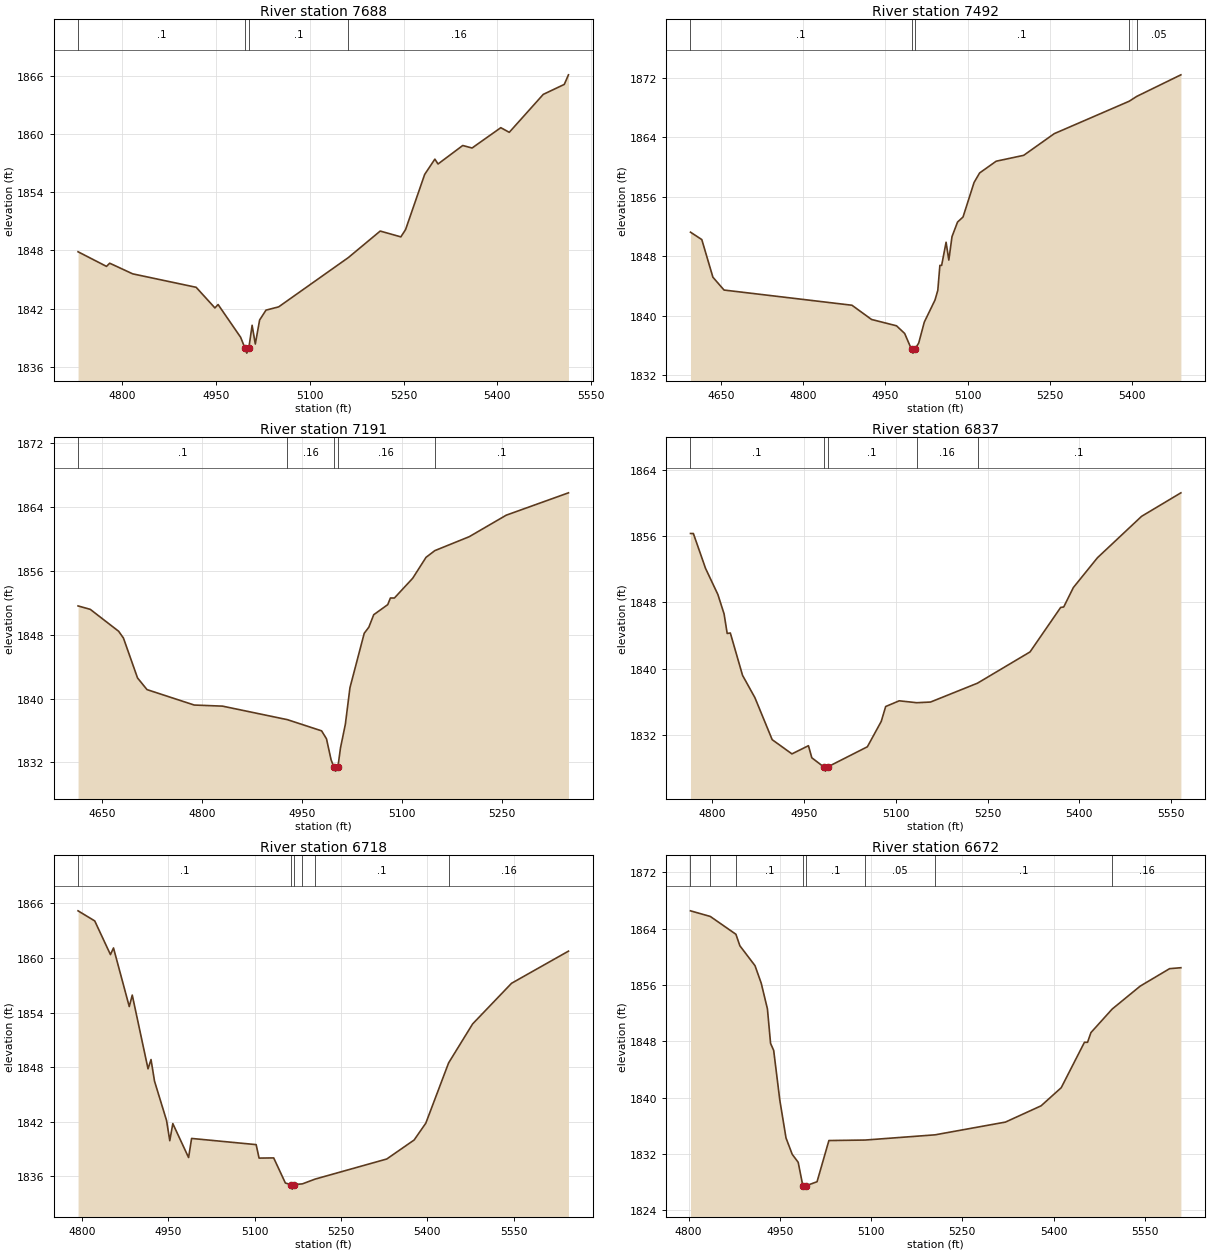
Type RM Length L Ch R = 1 ,7688    ,196,196,196
BEGIN DESCRIPTION:
Mapping XS 4a8365cb
END DESCRIPTION:
XS GIS Cut Line= 2
      2680044.55     10058200.22      2679271.88     10058335.36
#Sta/Elev= 30
  4729.3 1847.86  4774.8 1846.35  4779.9 1846.68  4816.7 1845.58  4918.2 1844.19
  4948.2 1842.06  4953.3 1842.41  4989.3 1839.03  4996.4 1837.89  4999.2 1837.39
  5002.4 1837.89  5007.7 1840.27  5012.8 1838.33  5019.7 1840.81  5029.9 1841.83
  5050.2 1842.17  5161.6 1847.26  5212.6    1850  5245.6  1849.4  5253.2 1850.16
  5283.7 1855.85    5300 1857.43  5305.1 1856.93  5344.6 1858.84  5359.5 1858.58
  5405.5 1860.68    5419  1860.2  5473.4 1864.12    5507 1865.15  5513.7 1866.14
#Mann= 4 ,-1 , 0
  4729.3      .1       0  4996.4     .07       0  5002.4      .1       0
  5161.6     .16       0
Bank Sta=4996.4,5002.4
XS Rating Curve= 0 ,0
Exp/Cntr=0.3,0.1

Type RM Length L Ch R = 1 ,7492    ,301,301,301
BEGIN DESCRIPTION:
UNT 0018 IN HEWA 14.0
END DESCRIPTION:
XS GIS Cut Line= 3
      2680148.77     10058123.84      2679697.33     10058047.44
      2679263.43     10058092.57
#Sta/Elev= 30
  4594.5 1851.23  4615.1 1850.24  4635.4 1845.18  4655.7 1843.46  4888.9 1841.42
  4924.6 1839.51  4970.1 1838.66    4985 1837.63  4997.5 1835.49  5000.2 1834.99
  5003.5 1835.49  5010.6 1836.35  5020.8 1839.16  5040.3 1842.12  5045.4 1843.42
  5049.2 1846.77  5052.4 1846.77  5060.5 1849.88  5065.5 1847.49  5071.3 1850.64
  5081.4 1852.59  5091.4 1853.27  5111.5  1857.9  5121.6 1859.18  5151.8 1860.76
    5202 1861.55  5257.7 1864.46  5394.5 1868.82    5408 1869.46  5488.6 1872.36
#Mann= 5 ,-1 , 0
  4594.5      .1       0  4997.5     .07       0  5003.5      .1       0
  5394.5     .16       0    5408     .05       0
Bank Sta=4997.5,5003.5
XS Rating Curve= 0 ,0
Exp/Cntr=0.3,0.1

Type RM Length L Ch R = 1 ,7191    ,354,354,354
BEGIN DESCRIPTION:
UNT 0018 IN HEWA 13.0
END DESCRIPTION:
XS GIS Cut Line= 3
      2680219.47     10058098.79      2679878.31     10057773.25
      2679615.27     10057762.84
#Sta/Elev= 30
  4614.6 1851.59  4632.9 1851.16  4675.4 1848.42  4682.6 1847.57  4703.7 1842.58
  4717.9 1841.12  4788.6 1839.19  4831.1 1839.05  4928.2 1837.36  4979.5 1835.96
  4986.8 1834.97  4993.7 1832.35  4997.9 1831.42  5000.7 1830.92  5003.9 1831.42
  5007.8 1833.82  5015.1 1836.78    5022 1841.36  5043.4 1848.17  5050.3 1848.93
  5057.6 1850.49  5078.6 1851.75  5082.6 1852.58  5088.6 1852.58    5116 1855.05
    5136 1857.67  5149.2 1858.51  5200.7 1860.25  5256.1 1862.94  5349.4 1865.74
#Mann= 5 ,-1 , 0
  4614.6      .1       0  4928.2     .16       0  4997.9     .07       0
  5003.9     .16       0  5149.2      .1       0
Bank Sta=4997.9,5003.9
XS Rating Curve= 0 ,0
Exp/Cntr=0.3,0.1

Type RM Length L Ch R = 1 ,6837    ,119,119,119
BEGIN DESCRIPTION:
Mapping XS e67781eb
END DESCRIPTION:
XS GIS Cut Line= 4
      2680502.87     10057776.61      2680318.86     10057752.31
      2680173.03     10057682.86      2679725.13     10057606.48
#Sta/Elev= 30
  4764.4 1856.31  4769.1 1856.31    4789  1852.1  4809.2 1848.94  4819.3  1846.6
  4824.4 1844.24  4829.5  1844.3  4849.5 1839.18  4869.7 1836.49  4897.9 1831.42
  4930.2  1829.7  4957.2 1830.69  4962.7 1829.23  4982.4 1828.12  4985.1 1827.62
  4988.4 1828.12  5053.5 1830.56  5076.2 1833.63  5083.4 1835.42  5105.5 1836.11
  5134.2 1835.88  5156.7 1835.96  5233.5 1838.24  5319.3 1842.01  5369.4 1847.38
  5374.4 1847.44  5390.1 1849.78  5429.5 1853.38  5501.6 1858.38  5565.9 1861.22
#Mann= 5 ,-1 , 0
  4764.4      .1       0  4982.4     .07       0  4988.4      .1       0
  5134.2     .16       0  5233.5      .1       0
Bank Sta=4982.4,4988.4
XS Rating Curve= 0 ,0
Exp/Cntr=0.3,0.1

Type RM Length L Ch R = 1 ,6718    ,46,46,46
BEGIN DESCRIPTION:
UNT 0018 IN HEWA 12.0
END DESCRIPTION:
XS GIS Cut Line= 3
       2680555.4     10057715.96      2680302.79     10057637.84
      2679724.68     10057531.07
#Sta/Elev= 30
    4793 1865.19    4822 1864.08  4849.3 1860.38  4854.6 1861.11    4882 1854.67
  4887.2 1855.93  4914.6 1847.83  4919.8 1848.85  4925.9 1846.47  4946.8 1842.15
  4952.4 1839.93  4957.7 1841.81  4985.1 1838.08  4990.3 1840.18  5102.5  1839.5
  5107.6 1838.02    5133 1838.04  5153.3 1835.28  5162.6 1835.11  5165.4 1834.61
  5168.6 1835.11    5183 1835.19  5204.9 1835.71  5329.5 1837.92  5377.1 1840.01
  5397.4 1841.86    5437 1848.48  5478.7 1852.76  5546.4 1857.23  5645.3 1860.76
#Mann= 6 ,-1 , 0
    4793      .1       0  5162.6     .07       0  5168.6      .1       0
    5183     .05       0  5204.9      .1       0    5437     .16       0
Bank Sta=5162.6,5168.6
XS Rating Curve= 0 ,0
Exp/Cntr=0.3,0.1

Type RM Length L Ch R = 1 ,6672    ,258,258,258
BEGIN DESCRIPTION:
Mapping XS 3449a780
END DESCRIPTION:
XS GIS Cut Line= 3
      2680572.38     10057655.09      2680232.06     10057585.64
      2679784.18     10057484.95
#Sta/Elev= 30
    4803 1866.54  4835.6 1865.74  4877.7 1863.21  4884.2 1861.58  4909.1 1858.75
  4919.3 1856.27  4929.5 1852.62  4934.7 1847.71  4939.8 1846.72  4949.9 1839.64
  4960.1 1834.28  4970.3 1831.96  4980.1 1830.83  4987.7 1827.52  4990.5 1827.02
  4993.7 1827.52  5011.1 1828.07  5030.6 1833.92  5090.4 1833.99  5205.2 1834.73
  5320.9 1836.54  5379.5 1838.85  5412.6 1841.42  5450.8 1847.87  5455.9 1847.87
  5461.5 1849.25  5496.4 1852.59  5542.5 1855.85  5590.9 1858.33  5609.4 1858.46
#Mann= 8 ,-1 , 0
    4803      .1       0  4835.6     .16       0  4877.7      .1       0
  4987.7     .07       0  4993.7      .1       0  5090.4     .05       0
  5205.2      .1       0  5496.4     .16       0
Bank Sta=4987.7,4993.7
XS Rating Curve= 0 ,0
Exp/Cntr=0.3,0.1

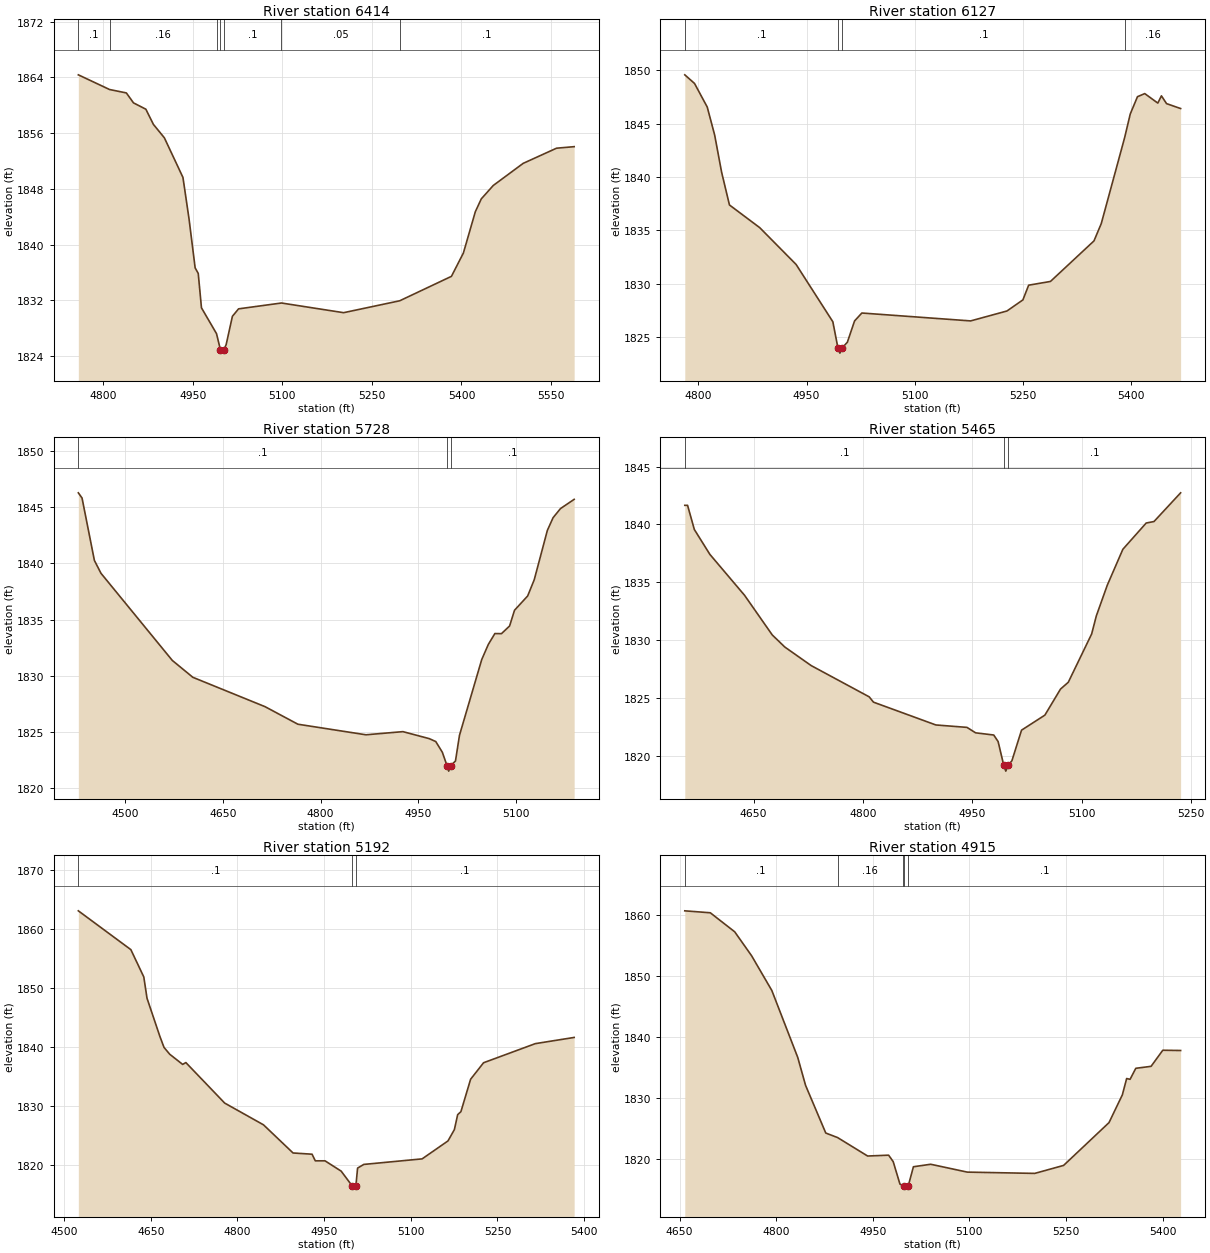
Type RM Length L Ch R = 1 ,6414    ,287,287,287
BEGIN DESCRIPTION:
Mapping XS 9fc8577f
END DESCRIPTION:
XS GIS Cut Line= 3
      2680677.74     10057450.33      2680237.68     10057333.15
       2679863.1     10057317.54
#Sta/Elev= 30
  4758.4 1864.38  4810.7 1862.27  4838.8 1861.78  4850.8 1860.35  4871.5 1859.44
  4884.1 1857.26  4902.5 1855.33  4933.6 1849.64  4943.9 1843.61    4954 1836.65
  4959.2 1835.85  4964.6 1830.91  4989.8  1827.2  4996.3  1824.9  4999.1  1824.4
  5002.3  1824.9    5006 1825.64  5016.4 1829.69  5026.7 1830.76  5098.6  1831.6
  5202.6 1830.21  5296.6 1831.92  5383.2 1835.43  5403.2 1838.78  5423.2 1844.71
  5433.2 1846.56  5453.2 1848.48  5503.3 1851.66  5559.2 1853.84  5588.7 1854.06
#Mann= 7 ,-1 , 0
  4758.4      .1       0  4810.7     .16       0  4989.8      .1       0
  4996.3     .07       0  5002.3      .1       0  5098.6     .05       0
  5296.6      .1       0
Bank Sta=4996.3,5002.3
XS Rating Curve= 0 ,0
Exp/Cntr=0.3,0.1

Type RM Length L Ch R = 1 ,6127    ,399,399,399
BEGIN DESCRIPTION:
UNT 0018 IN HEWA 11.0
END DESCRIPTION:
XS GIS Cut Line= 3
      2680638.75     10057161.28      2680459.04     10057119.61
      2679959.02     10057171.69
#Sta/Elev= 30
  4781.3 1849.57  4794.8 1848.76  4812.4 1846.55  4822.7 1843.92  4832.3 1840.45
  4843.2 1837.37  4885.2 1835.24  4935.6 1831.79  4986.5 1826.42  4993.5 1823.98
  4996.3 1823.48  4999.5 1823.98  5006.6  1824.5  5016.6  1826.5  5026.7 1827.24
  5177.5  1826.5  5227.8 1827.43  5249.9 1828.47  5257.9 1829.85  5288.1  1830.2
  5348.4    1834  5358.5 1835.62  5390.9 1843.68  5398.7  1845.9  5408.7 1847.52
  5418.8 1847.81  5436.9 1846.92  5441.9  1847.6    5449 1846.87  5468.5 1846.41
#Mann= 4 ,-1 , 0
  4781.3      .1       0  4993.5     .07       0  4999.5      .1       0
  5390.9     .16       0
Bank Sta=4993.5,4999.5
XS Rating Curve= 0 ,0
Exp/Cntr=0.3,0.1

Type RM Length L Ch R = 1 ,5728    ,263,263,263
BEGIN DESCRIPTION:
UNT 0018 IN HEWA 10.0
END DESCRIPTION:
XS GIS Cut Line= 2
      2680742.92     10056978.99      2679987.67     10056874.81
#Sta/Elev= 30
  4427.6 1846.28  4433.3 1845.82  4452.3 1840.27  4462.4 1839.13  4572.1 1831.38
  4603.7 1829.88  4714.7 1827.27  4765.2 1825.71  4869.9 1824.77  4926.7 1825.05
  4967.1 1824.43  4977.2 1824.17  4987.3 1823.22  4994.4 1822.04  4997.1 1821.54
  5000.4 1822.04  5007.5 1822.44  5013.7 1824.73  5047.9 1831.46    5058  1832.8
  5068.1 1833.77  5078.2 1833.76  5090.7 1834.44  5098.3 1835.84  5118.5 1837.11
  5128.6 1838.55  5148.8 1842.94  5157.6 1844.07    5169 1844.88    5190  1845.7
#Mann= 3 ,-1 , 0
  4427.6      .1       0  4994.4     .07       0  5000.4      .1       0
Bank Sta=4994.4,5000.4
XS Rating Curve= 0 ,0
Exp/Cntr=0.3,0.1

Type RM Length L Ch R = 1 ,5465    ,273,273,273
BEGIN DESCRIPTION:
Mapping XS f35d0c82
END DESCRIPTION:
XS GIS Cut Line= 2
      2680750.68     10056877.41      2680114.28     10056638.43
#Sta/Elev= 30
  4555.7 1841.65  4559.5 1841.65  4568.8 1839.56  4590.1 1837.41  4637.7 1833.87
  4675.6 1830.45  4692.9  1829.4    4729  1827.8  4808.5  1825.1  4814.4 1824.64
  4899.9 1822.67  4942.6 1822.46  4954.4 1821.99  4979.3  1821.8  4985.3 1821.23
    4993 1819.18  4995.8 1818.68    4999 1819.18  5004.2 1819.58  5017.4 1822.22
  5049.4 1823.52  5070.8 1825.77  5081.5 1826.36  5113.5 1830.53  5119.9 1832.09
  5134.9 1834.74  5156.3 1837.85  5188.3 1840.12    5199 1840.25  5235.5 1842.73
#Mann= 3 ,-1 , 0
  4555.7      .1       0    4993     .07       0    4999      .1       0
Bank Sta=4993,4999
XS Rating Curve= 0 ,0
Exp/Cntr=0.3,0.1

Type RM Length L Ch R = 1 ,5192    ,277,277,277
BEGIN DESCRIPTION:
UNT 0018 IN HEWA 9.0
END DESCRIPTION:
XS GIS Cut Line= 2
      2680941.25     10056730.98      2680172.84     10056349.04
#Sta/Elev= 30
  4524.6 1863.03  4615.5 1856.45  4637.9 1851.82  4643.5  1848.2  4665.9 1841.69
  4672.9 1839.87  4682.7 1838.72  4705.1 1836.99  4710.7  1837.3  4777.9 1830.43
  4845.1 1826.74  4896.2 1821.97  4929.1 1821.76  4934.7 1820.64  4951.5 1820.64
  4979.5 1818.89  4998.9 1816.34  5001.6 1815.84  5004.9 1816.34  5007.9 1819.41
  5018.7 1820.03  5119.6 1820.97  5164.3 1824.01  5175.4 1825.93  5181.1 1828.47
  5186.7 1828.97  5203.5 1834.47  5225.9 1837.27  5315.5 1840.51  5382.7 1841.56
#Mann= 3 ,-1 , 0
  4524.6      .1       0  4998.9     .07       0  5004.9      .1       0
Bank Sta=4998.9,5004.9
XS Rating Curve= 0 ,0
Exp/Cntr=0.3,0.1

Type RM Length L Ch R = 1 ,4915    ,227,227,227
BEGIN DESCRIPTION:
UNT 0018 IN HEWA 8.0
END DESCRIPTION:
XS GIS Cut Line= 2
      2681027.67     10056421.53      2680292.01     10056194.47
#Sta/Elev= 30
  4658.1 1860.63  4697.7 1860.31  4735.6 1857.19  4761.9 1853.25  4793.3 1847.55
  4833.5 1836.58  4845.6 1832.01    4877 1824.18  4895.3 1823.44    4942 1820.41
  4974.6 1820.55  4981.7 1819.49  4992.2  1815.8  4997.2 1815.56    4999 1815.48
  5001.8 1814.98    5005 1815.48  5013.1 1818.65  5039.9 1819.06  5096.8 1817.77
  5201.5 1817.56  5246.3 1818.87  5316.8 1825.89  5337.5 1830.44  5344.2 1833.12
  5349.5 1832.99  5358.4  1834.8  5382.1 1835.12  5400.3 1837.76    5428 1837.72
#Mann= 5 ,-1 , 0
  4658.1      .1       0  4895.3     .16       0  4997.2      .1       0
    4999     .07       0    5005      .1       0
Bank Sta=4999,5005
XS Rating Curve= 0 ,0
Exp/Cntr=0.3,0.1

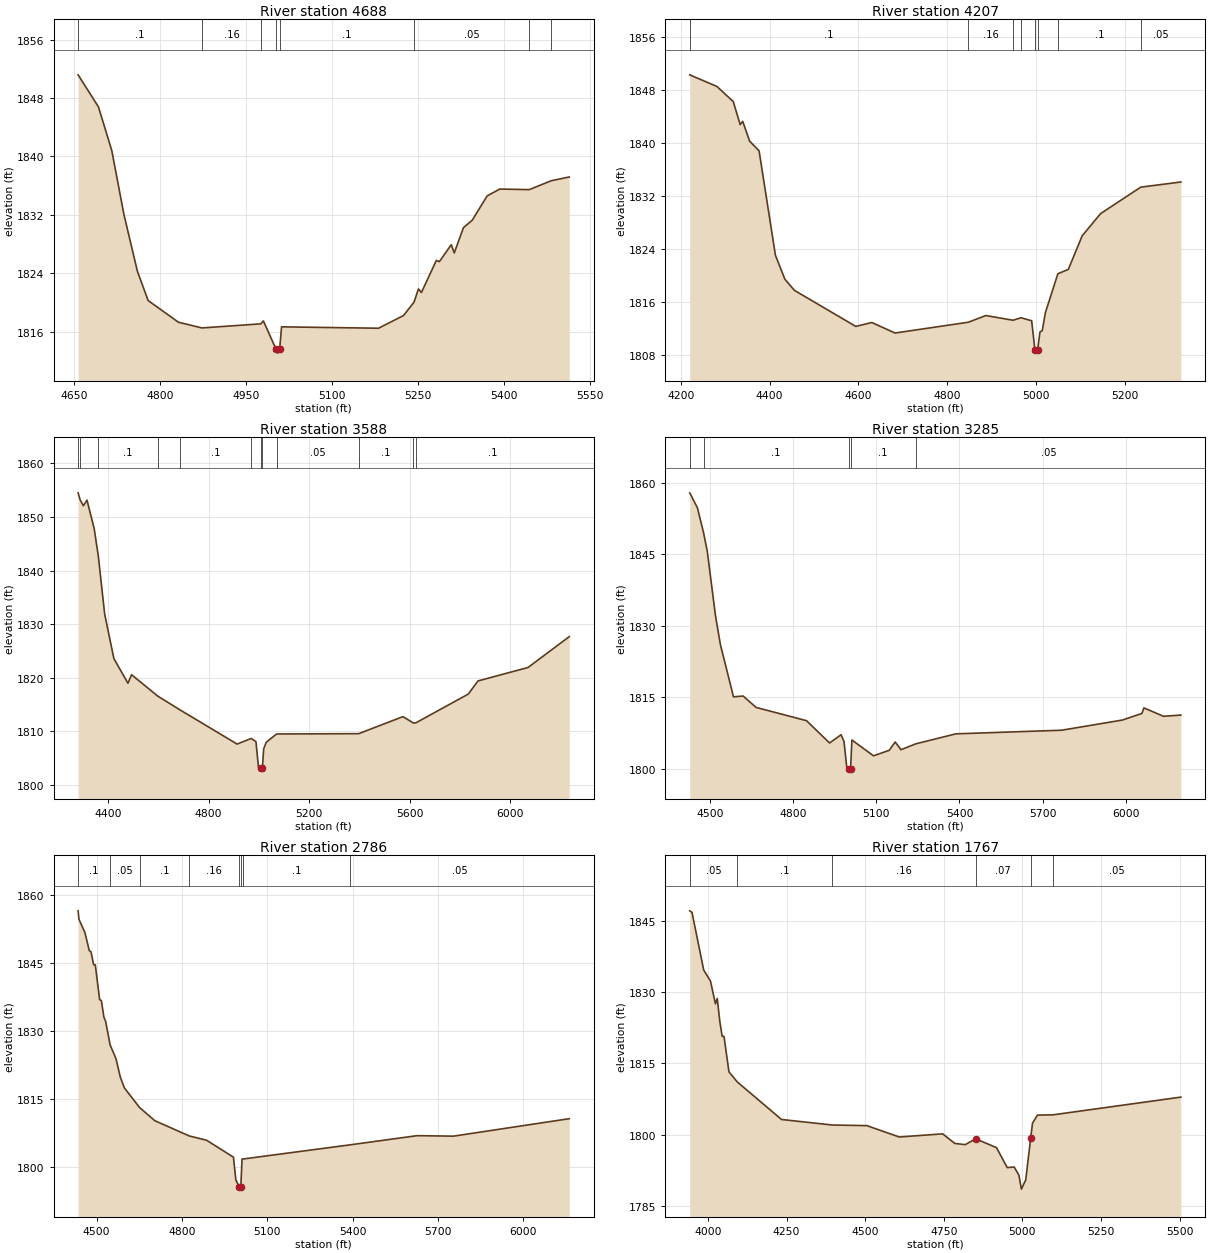
Type RM Length L Ch R = 1 ,4688    ,481,481,481
BEGIN DESCRIPTION:
UNT 0018 IN HEWA 7.0
END DESCRIPTION:
XS GIS Cut Line= 2
      2681013.99      10056221.3      2680204.03     10055943.73
#Sta/Elev= 30
    4657 1851.17  4692.5 1846.78  4715.7 1840.81  4736.8 1832.08  4760.4 1824.27
  4779.1 1820.26    4832 1817.29  4872.9 1816.51  4975.6 1817.07    4980 1817.47
  5002.3 1813.56  5005.1 1813.06  5008.3 1813.56  5011.7 1816.66  5180.8 1816.47
  5224.3 1818.21  5242.6 1820.04  5250.3 1821.85  5255.5 1821.36  5281.5 1825.75
  5286.8 1825.59  5307.5  1827.9  5312.8 1826.79  5328.8 1830.24  5344.1 1831.26
  5370.1 1834.59  5392.2 1835.53  5443.6 1835.45  5481.9 1836.67  5513.2 1837.18
#Mann= 8 ,-1 , 0
    4657      .1       0  4872.9     .16       0  4975.6      .1       0
  5002.3     .07       0  5008.3      .1       0  5242.6     .05       0
  5443.6      .1       0  5481.9     .05       0
Bank Sta=5002.3,5008.3
XS Rating Curve= 0 ,0
Exp/Cntr=0.3,0.1

Type RM Length L Ch R = 1 ,4207    ,619,619,619
BEGIN DESCRIPTION:
UNT 0018 IN HEWA 6.0
END DESCRIPTION:
XS GIS Cut Line= 3
      2681114.12     10056253.13      2680859.31     10055834.52
      2680263.32     10055679.84
#Sta/Elev= 30
    4220 1850.31  4281.3 1848.55  4318.1 1846.26  4333.6 1842.78  4339.4 1843.27
  4354.9 1840.28  4376.2 1838.82    4413 1823.03  4434.3 1819.41  4455.7 1817.73
  4593.9 1812.28    4630 1812.87  4682.3 1811.28  4847.3 1812.91  4886.6 1813.92
  4948.1 1813.21  4965.8 1813.59  4989.9 1813.13  4997.2 1808.74    5000 1808.24
  5003.2 1808.74  5008.6 1811.44  5013.7 1811.63  5020.9 1814.38  5048.9 1820.24
  5072.5  1820.9  5103.5 1825.96  5144.9 1829.32  5235.5 1833.33  5325.8 1834.11
#Mann= 8 ,-1 , 0
    4220      .1       0  4847.3     .16       0  4948.1      .1       0
  4965.8     .05       0  4997.2    .035       0  5003.2     .05       0
  5048.9      .1       0  5235.5     .05       0
Bank Sta=4997.2,5003.2
XS Rating Curve= 0 ,0
Exp/Cntr=0.3,0.1

Type RM Length L Ch R = 1 ,3588    ,303,303,303
BEGIN DESCRIPTION:
UNT 0018 IN HEWA 5.0
END DESCRIPTION:
XS GIS Cut Line= 4
       2681496.4     10056235.49      2681091.16     10055739.72
      2681039.43     10055489.67      2680099.55     10055002.49
#Sta/Elev= 30
  4280.4  1854.5  4288.1 1853.24  4301.4 1852.09  4315.8 1853.14  4344.5 1847.81
  4360.9 1842.67  4386.1 1831.88  4422.8 1823.57  4478.8 1818.97  4493.1 1820.56
    4598 1816.55  4687.6 1813.95  4913.1 1807.62    4969 1808.66  4988.1 1808.08
  4998.3 1803.22  5007.8 1803.07  5010.6 1802.57  5013.8 1803.07  5018.7 1806.69
    5029 1807.96  5070.4  1809.5    5397 1809.56  5573.1 1812.74  5614.4 1811.55
  5624.4 1811.58    5833 1816.95  5871.7  1819.4  6070.8 1821.91  6234.7 1827.66
#Mann= 12 ,-1 , 0
  4280.4      .1       0  4288.1     .05       0  4360.9      .1       0
    4598     .05       0  4687.6      .1       0    4969     .16       0
  5007.8     .07       0  5013.8     .16       0  5070.4     .05       0
    5397      .1       0  5614.4     .05       0  5624.4      .1       0
Bank Sta=5007.8,5013.8
XS Rating Curve= 0 ,0
Exp/Cntr=0.3,0.1

Type RM Length L Ch R = 1 ,3285    ,499,499,499
BEGIN DESCRIPTION:
Mapping XS 2444edbb
END DESCRIPTION:
XS GIS Cut Line= 4
      2681537.31     10056189.42      2681346.21     10055738.96
      2681400.81     10055547.84      2680613.04     10054800.28
#Sta/Elev= 30
  4425.6 1857.92  4453.5 1854.77  4475.7 1849.53  4489.1 1845.63  4518.7 1832.13
  4536.4  1826.1  4583.8 1815.12  4618.3  1815.3  4665.6  1812.9  4847.6 1810.12
  4930.8 1805.44  4972.4 1807.17  4982.9 1805.75  4993.2 1800.18  5000.6 1800.04
  5003.3 1799.54  5006.6 1800.04  5011.5 1806.07  5089.5 1802.75  5146.4 1803.91
  5167.8 1805.65  5188.9 1804.03  5242.4 1805.27  5387.1 1807.36  5768.9 1808.12
  5988.2 1810.25    6059 1811.64  6066.2 1812.81    6137 1811.04  6199.7  1811.3
#Mann= 5 ,-1 , 0
  4425.6     .05       0  4475.7      .1       0  5000.6     .07       0
  5006.6      .1       0  5242.4     .05       0
Bank Sta=5000.6,5006.6
XS Rating Curve= 0 ,0
Exp/Cntr=0.3,0.1

Type RM Length L Ch R = 1 ,2786    ,1019,1019,1019
BEGIN DESCRIPTION:
UNT 0018 IN HEWA 4.0
END DESCRIPTION:
XS GIS Cut Line= 4
      2682015.13     10056021.11       2681742.1     10055593.35
      2681500.92     10055456.83      2680812.21     10054814.01
#Sta/Elev= 30
  4434.8 1856.43  4437.8 1854.58  4458.9 1851.62  4474.1 1847.65  4480.1 1847.43
  4489.4 1844.55  4495.3  1844.5  4510.5 1836.84  4516.5 1836.65  4525.7 1832.94
  4531.7 1832.05  4547.3 1826.88  4568.1 1823.82  4583.3 1819.74  4597.8 1817.37
  4650.7 1813.07  4704.5 1810.15  4825.9 1806.78  4886.2 1805.85  4980.9 1802.11
  4989.5  1797.1  5000.9 1795.56  5003.6 1795.06  5006.9 1795.56  5011.1 1801.69
  5014.2  1801.7  5390.3 1804.82  5626.6 1806.85  5754.1 1806.74  6161.5 1810.59
#Mann= 8 ,-1 , 0
  4434.8      .1       0  4547.3     .05       0  4650.7      .1       0
  4825.9     .16       0  5000.9     .07       0  5006.9     .16       0
  5014.2      .1       0  5390.3     .05       0
Bank Sta=5000.9,5006.9
XS Rating Curve= 0 ,0
Exp/Cntr=0.3,0.1

Type RM Length L Ch R = 1 ,1767    ,553,553,553
BEGIN DESCRIPTION:
UNT 0018 IN HEWA 3.0
END DESCRIPTION:
XS GIS Cut Line= 4
      2682256.31     10055866.39      2681928.67     10055302.12
      2681605.58     10055206.56      2681109.59     10054919.88
#Sta/Elev= 30
    3942 1847.08  3949.3 1846.76  3986.5 1834.62    4008 1832.32  4023.8  1827.5
  4029.6 1828.64  4037.6 1823.86  4045.3 1820.67  4051.1 1820.66  4066.8  1813.2
  4093.5 1811.06  4234.2 1803.17  4396.1 1802.01  4505.6 1801.88  4608.4 1799.49
  4746.7 1800.15  4785.2 1798.14  4818.4 1797.88  4851.7 1799.11    4918 1797.24
    4952 1793.05  4974.3 1793.17  4989.3 1791.42  4997.1 1788.52  5010.9 1790.47
  5026.6 1799.28  5032.4 1802.39  5048.2 1804.09  5098.3 1804.16  5504.3 1807.88
#Mann= 6 ,-1 , 0
    3942     .05       0  4093.5      .1       0  4396.1     .16       0
  4851.7     .07       0  5026.6      .1       0  5098.3     .05       0
Bank Sta=4851.7,5026.6
XS Rating Curve= 0 ,0
Exp/Cntr=0.3,0.1

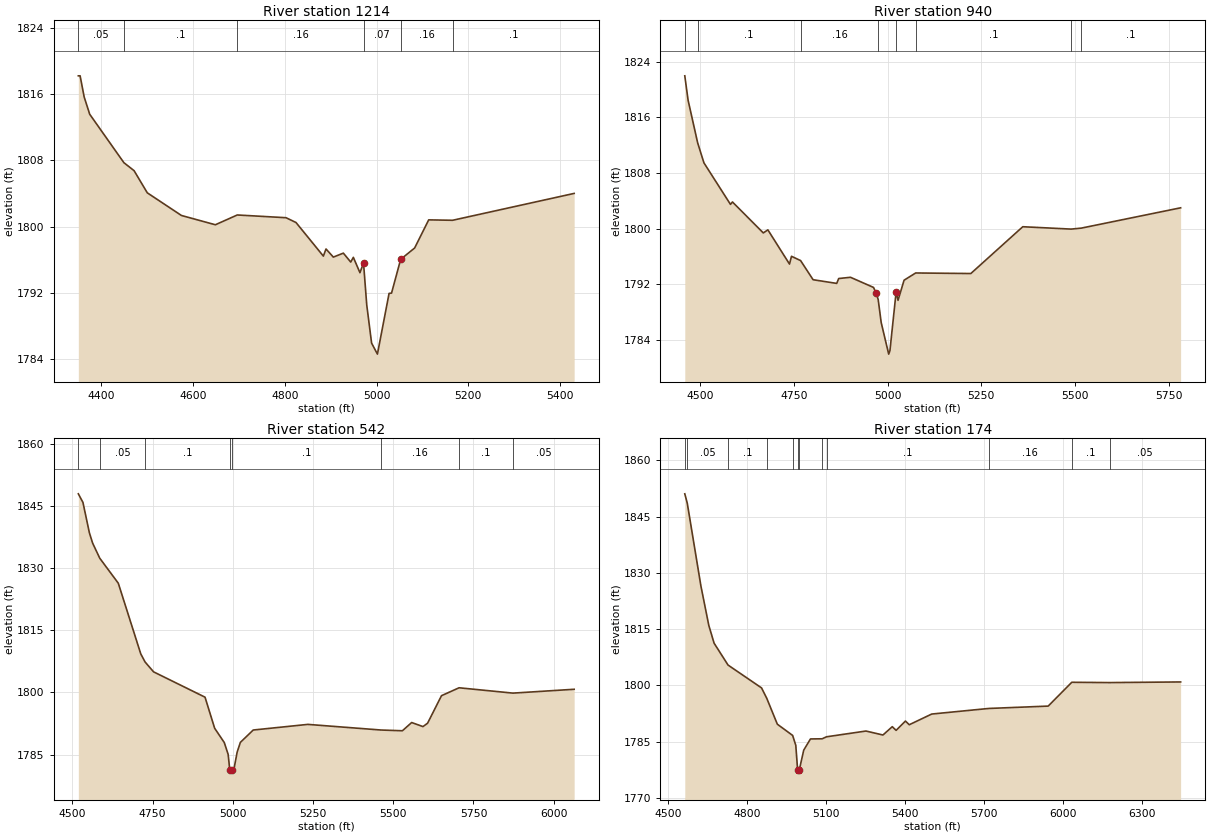
Type RM Length L Ch R = 1 ,1214    ,274,274,274
BEGIN DESCRIPTION:
Mapping XS fb090fed
END DESCRIPTION:
XS GIS Cut Line= 4
      2682281.97     10055765.46      2681985.08     10055226.38
      2681914.77     10055033.67      2681672.59     10054937.32
#Sta/Elev= 30
  4349.8 1818.18  4353.7 1818.18  4362.5 1815.64  4374.6 1813.55  4449.1 1807.71
  4471.4 1806.74  4500.2 1804.07  4574.6 1801.34  4648.6 1800.22  4696.4  1801.4
  4802.7 1801.07  4824.5 1800.49  4884.1 1796.44  4889.9  1797.3  4905.9 1796.32
  4927.7  1796.8  4943.8 1795.72  4949.5 1796.29  4963.9 1794.44  4971.7 1795.61
  4978.7 1790.56  4989.3 1785.95    5002 1784.62  5027.4 1791.94  5032.8 1791.98
  5052.7 1796.05  5083.2 1797.42  5113.8 1800.81  5165.9 1800.76    5431    1804
#Mann= 6 ,-1 , 0
  4349.8     .05       0  4449.1      .1       0  4696.4     .16       0
  4971.7     .07       0  5052.7     .16       0  5165.9      .1       0
Bank Sta=4971.7,5052.7
XS Rating Curve= 0 ,0
Exp/Cntr=0.3,0.1

Type RM Length L Ch R = 1 ,940     ,398,398,398
BEGIN DESCRIPTION:
UNT 0018 IN HEWA 2.0
END DESCRIPTION:
XS GIS Cut Line= 4
      2682373.11     10055742.04      2682224.66      10055301.9
      2682276.74     10055020.65      2681714.27     10054919.09
#Sta/Elev= 30
  4459.5 1821.97  4468.3 1818.46  4493.8 1812.33  4510.5 1809.46  4581.3 1803.48
  4586.6 1803.83  4668.8 1799.38    4681 1799.82  4738.7  1794.9    4744 1796.02
  4768.3  1795.4  4801.6 1792.65  4864.6 1792.12  4869.9 1792.82  4901.3    1793
  4962.8 1791.54  4970.1 1790.68  4975.2 1789.79  4983.2 1786.49  5003.2 1781.95
  5006.5 1782.45    5023  1790.9  5028.1 1789.69  5044.2 1792.58  5075.1 1793.62
  5222.2 1793.54  5360.7 1800.27  5489.5 1799.93  5516.8 1800.07  5781.6 1802.99
#Mann= 8 ,-1 , 0
  4459.5     .05       0  4493.8      .1       0  4768.3     .16       0
  4975.2     .07       0    5023     .16       0  5075.1      .1       0
  5489.5     .05       0  5516.8      .1       0
Bank Sta=4970.1,5023
XS Rating Curve= 0 ,0
Exp/Cntr=0.3,0.1

Type RM Length L Ch R = 1 ,542     ,368,368,368
BEGIN DESCRIPTION:
Mapping XS f211512c
END DESCRIPTION:
XS GIS Cut Line= 5
      2682582.92     10055898.12      2682569.03     10055521.37
      2682588.13     10055148.11       2682235.7      10054868.6
      2681892.68     10054840.88
#Sta/Elev= 30
  4518.9 1848.02  4533.3 1845.94  4553.3 1838.61  4563.3 1836.13  4585.6 1832.46
  4643.4 1826.41  4713.4 1809.33  4726.8 1807.37  4753.4 1804.98  4913.6 1798.86
  4943.6 1791.35  4973.6 1787.89  4985.7 1785.02  4990.7 1781.24  4993.4 1780.74
  4996.7 1781.24  5003.7 1781.48  5013.7 1785.58  5023.7 1787.93  5063.8 1790.92
    5234 1792.28  5461.6 1790.92  5528.5 1790.74  5557.4 1792.73  5592.6 1791.75
    5607 1792.57  5650.3 1799.22    5705 1801.13    5873 1799.84  6063.6 1800.77
#Mann= 8 ,-1 , 0
  4518.9      .1       0  4585.6     .05       0  4726.8      .1       0
  4990.7     .07       0  4996.7      .1       0  5461.6     .16       0
    5705      .1       0    5873     .05       0
Bank Sta=4990.7,4996.7
XS Rating Curve= 0 ,0
Exp/Cntr=0.3,0.1

Type RM Length L Ch R = 1 ,174     ,0,0,0
BEGIN DESCRIPTION:
UNT 0018 IN HEWA 1.0
END DESCRIPTION:
XS GIS Cut Line= 4
      2682931.88     10055984.88      2682909.31     10055507.48
      2682407.57     10054842.55      2681836.35     10054807.83
#Sta/Elev= 30
  4562.8 1851.08  4572.3 1848.54    4624 1826.51    4654 1815.98  4674.1 1811.25
    4727 1805.42  4854.3 1799.32  4873.8  1796.6  4914.3 1789.64  4972.5 1786.64
  4984.4 1783.99  4991.4 1777.36  4994.2 1776.86  4997.4 1777.36  5014.5 1782.72
  5040.1 1785.71  5084.4 1785.75    5101 1786.28  5250.9 1787.82  5315.4 1786.76
  5350.8 1788.98  5365.4    1788  5400.8 1790.48  5415.3  1789.5  5500.7 1792.35
  5717.1 1793.84    5943 1794.47  6032.6 1800.82  6176.5 1800.74    6446 1800.91
#Mann= 12 ,-1 , 0
  4562.8      .1       0  4572.3     .05       0    4727      .1       0
  4873.8     .16       0  4972.5      .1       0  4991.4     .07       0
  4997.4      .1       0  5084.4     .16       0    5101      .1       0
  5717.1     .16       0  6032.6      .1       0  6176.5     .05       0
Bank Sta=4991.4,4997.4
XS Rating Curve= 0 ,0
Exp/Cntr=0.3,0.1

Chan Stop Cuts=-1
Use User Specified Reach Order=0
Composite Channel Slope=5