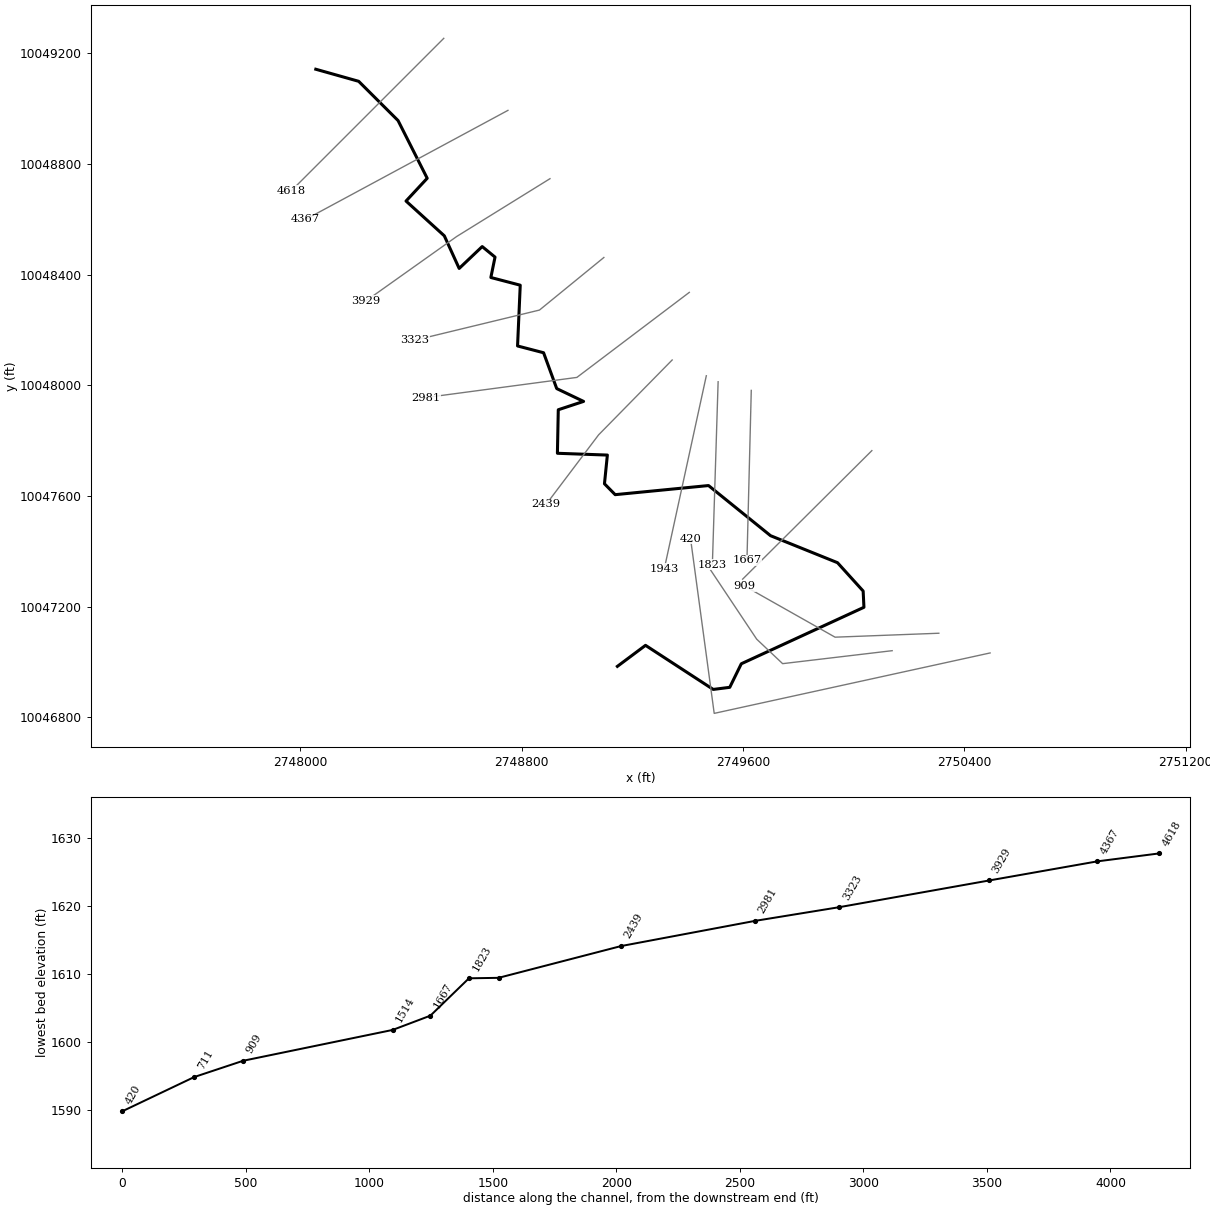
--- UNT 0019 IN HEWA.prj (project) ---

Proj Title=UNT 0019 IN HEWA Base Level Engineering
Current Plan=p01
Default Exp/Contr=0.3,0.1
English Units
Geom File=g01
Flow File=f01
Plan File=p01
Y Axis Title=Elevation
X Axis Title(PF)=Main Channel Distance
X Axis Title(XS)=Station
BEGIN DESCRIPTION:
UNT 0019 IN HEWA
END DESCRIPTION:
DSS Export Rating Curves= 0
DSS Export Rating Curve Sorted= 0
DSS Export Volume Flow Curves= 0
DXF OffsetX= 0
DXF OffsetY= 0
DXF ScaleX= 1
DXF ScaleY= 10

--- UNT 0019 IN HEWA.p01 (plan) ---

Plan Title=Multiple Run
Short Identifier=Multiple
Geom File=g01
Flow File=f01
Subcritical Flow
K Sum by GR= 0
Std Step Tol= 0.01
Critical Tol= 0.01
Num of Std Step Trials= 20
Max Error Tol= 0.3
Flow Tol Ratio= 0.001
Split Flow NTrial= 30
Split Flow Tol= 0.02
Split Flow Ratio= 0.02
Log Output Level= 0
Friction Slope Method= 1
Unsteady Friction Slope Method= 2
Unsteady Bridges Friction Slope Method= 1
Parabolic Critical Depth
Global Vel Dist=  1 , 1 , 1
Global Log Level= 0
CheckData=True
Encroach Param= -1, 0, 0, 0
BEGIN DESCRIPTION:
Multiple Run
END DESCRIPTION:

--- UNT 0019 IN HEWA.f01 (steady flow) ---

Flow Title=Multiple
Program Version=4.10
Number of Profiles= 7
Profile Names=10-year,25-year,50-year,1pct_min,100-year,1pct_plu,500-year
River Rch & RM=UNT 0019 IN HEWA,Reach-1         ,4618
     535     743     916     825    1116    1509    1664
Boundary for River Rch & Prof#=UNT 0019 IN HEWA,Reach-1         , 1
Up Type= 0
Dn Type= 3
Dn Slope=0.015
Boundary for River Rch & Prof#=UNT 0019 IN HEWA,Reach-1         , 2
Up Type= 0
Dn Type= 3
Dn Slope=0.015
Boundary for River Rch & Prof#=UNT 0019 IN HEWA,Reach-1         , 3
Up Type= 0
Dn Type= 3
Dn Slope=0.015
Boundary for River Rch & Prof#=UNT 0019 IN HEWA,Reach-1         , 4
Up Type= 0
Dn Type= 3
Dn Slope=0.015
Boundary for River Rch & Prof#=UNT 0019 IN HEWA,Reach-1         , 5
Up Type= 0
Dn Type= 3
Dn Slope=0.015
Boundary for River Rch & Prof#=UNT 0019 IN HEWA,Reach-1         , 6
Up Type= 0
Dn Type= 3
Dn Slope=0.015
Boundary for River Rch & Prof#=UNT 0019 IN HEWA,Reach-1         , 7
Up Type= 0
Dn Type= 3
Dn Slope=0.015
DSS Import GetInterval= 0
DSS Import GetPeak= 0
DSS Import FillOption= 0

--- UNT 0019 IN HEWA.g01 (geometry) ---

Geom Title=Existing Conditions
Program Version=4.10

River Reach=UNT 0019 IN HEWA,Reach-1
Reach XY= 30
      2748055.95     10049142.03      2748210.97     10049098.38
      2748353.29      10048956.5      2748458.58     10048747.96
      2748382.06     10048665.62      2748520.45     10048539.96
      2748574.14      10048422.1      2748657.35     10048501.14
      2748703.71     10048463.07      2748688.62     10048389.39
      2748794.83     10048361.54      2748785.13      10048141.9
      2748879.17     10048117.41      2748926.66     10047987.88
      2749023.74     10047941.53      2748932.31     10047911.37
      2748929.17     10047754.07      2749109.72      10047747.6
      2749099.23     10047643.86      2749137.98     10047604.52
       2749475.3     10047637.46      2749699.49     10047456.22
      2749941.41     10047358.66      2750034.15     10047256.18
      2750036.97     10047197.47       2749593.8     10046993.38
      2749552.01     10046908.22       2749492.3      10046900.6
      2749247.61     10047059.95      2749145.91     10046983.98

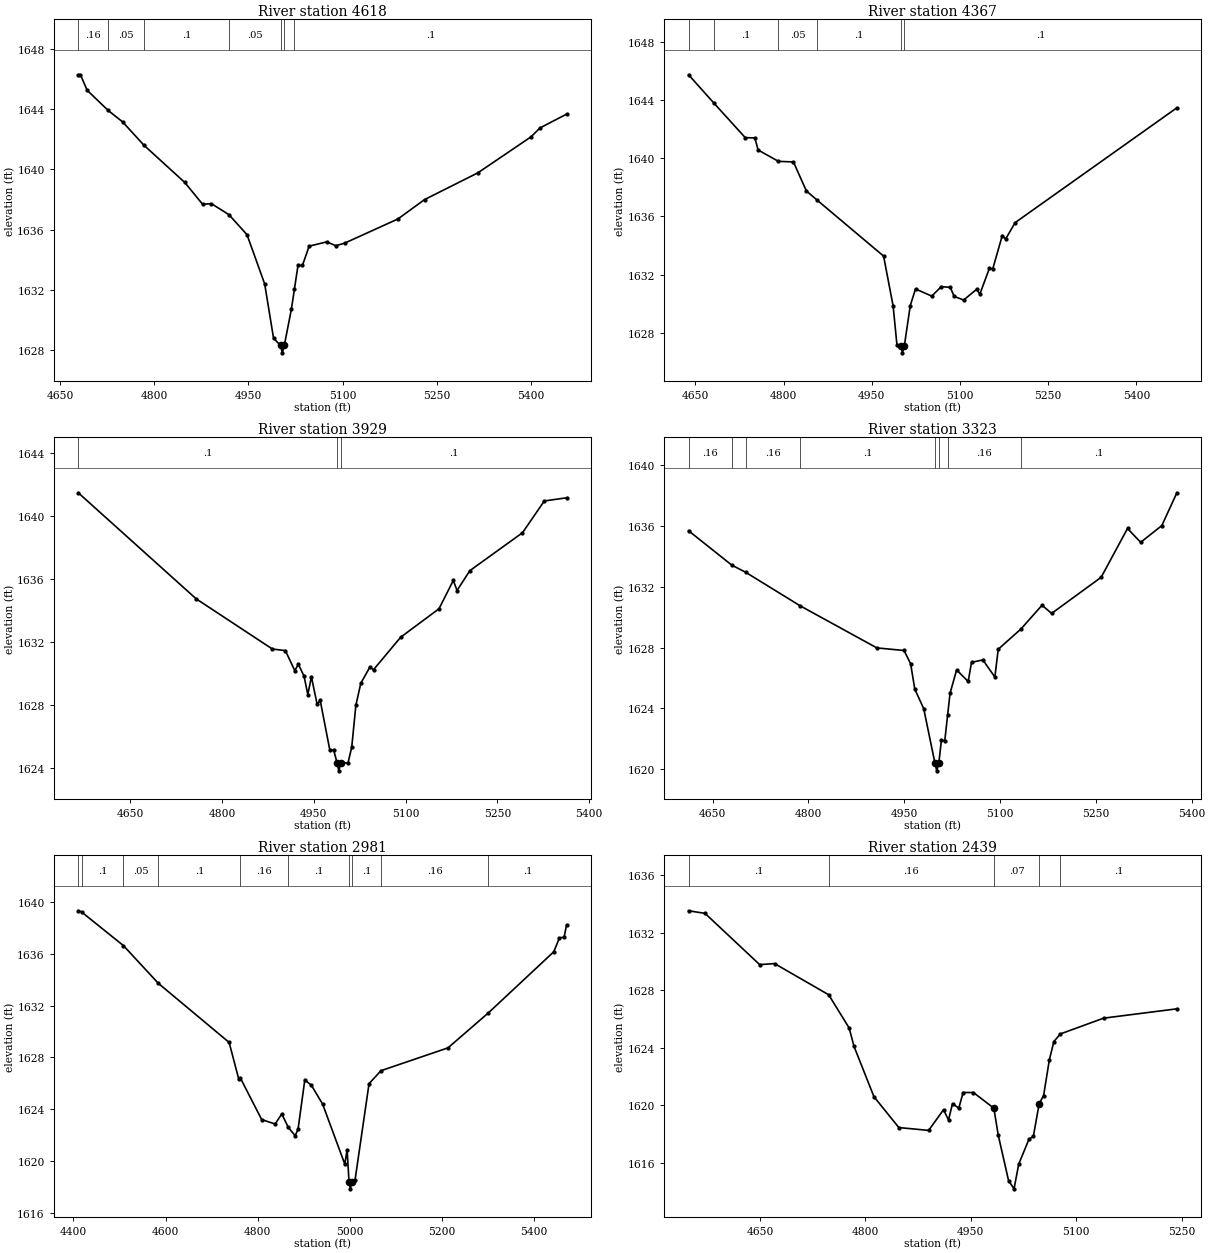
Type RM Length L Ch R = 1 ,4618    ,251,251,251
BEGIN DESCRIPTION:
UNT 0019 IN HEWA 9.0
END DESCRIPTION:
XS GIS Cut Line= 3
      2748518.44     10049253.71      2748268.47     10049003.73
      2747968.45     10048703.72
#Sta/Elev= 30
    4679  1646.3  4682.5  1646.3  4693.1 1645.27  4726.5 1643.93  4749.7 1643.16
  4783.6 1641.61  4848.7 1639.13    4877 1637.68  4891.1 1637.72  4918.9 1636.99
  4947.7 1635.66  4975.9 1632.38  4990.1 1628.75  5001.2 1628.29    5004 1627.79
  5007.2 1628.29  5018.4 1630.68  5023.4 1632.06    5029 1633.61  5036.1 1633.61
  5046.7 1634.89  5074.9 1635.18  5089.1 1634.92  5103.2 1635.09  5188.1  1636.7
  5230.5 1637.99  5315.4 1639.77  5400.2 1642.17  5414.4 1642.76  5456.8 1643.68
#Mann= 7 ,-1 , 0
    4679     .16       0  4726.5     .05       0  4783.6      .1       0
  4918.9     .05       0  5001.2    .035       0  5007.2     .05       0
  5023.4      .1       0
Bank Sta=5001.2,5007.2
XS Rating Curve= 0 ,0
Exp/Cntr=0.3,0.1

Type RM Length L Ch R = 1 ,4367    ,438,438,438
BEGIN DESCRIPTION:
UNT 0019 IN HEWA 8.0
END DESCRIPTION:
XS GIS Cut Line= 2
      2748750.41     10048993.39      2748019.25     10048599.32
#Sta/Elev= 30
  4638.4 1645.73  4681.8 1643.77  4734.8 1641.41  4751.1 1641.39  4756.7 1640.56
  4791.3 1639.78  4816.8 1639.74  4838.7 1637.75  4857.2 1637.11  4970.1 1633.27
  4986.3 1629.85  4992.8 1627.18  4999.5 1627.12  5002.2 1626.62  5005.5 1627.12
  5015.5 1629.87  5024.4 1631.01    5052 1630.52  5068.2 1631.17  5083.6 1631.12
  5090.1  1630.5  5106.3 1630.25  5128.2 1630.98  5133.9 1630.66  5150.1 1632.43
  5155.8 1632.39    5172 1634.68  5177.7 1634.44  5193.9 1635.57    5469 1643.46
#Mann= 6 ,-1 , 0
  4638.4     .05       0  4681.8      .1       0  4791.3     .05       0
  4857.2      .1       0  4999.5     .07       0  5005.5      .1       0
Bank Sta=4999.5,5005.5
XS Rating Curve= 0 ,0
Exp/Cntr=0.3,0.1

Type RM Length L Ch R = 1 ,3929    ,606,606,606
BEGIN DESCRIPTION:
UNT 0019 IN HEWA 7.0
END DESCRIPTION:
XS GIS Cut Line= 3
      2748902.33     10048746.48      2748565.23     10048537.58
      2748237.62     10048304.93
#Sta/Elev= 30
  4564.8 1641.48  4757.6 1634.74  4882.2 1631.55  4903.4 1631.45  4918.8 1630.18
  4924.7 1630.58    4934 1629.82  4940.1 1628.66    4946 1629.78  4955.4 1628.03
  4960.3  1628.3  4976.2 1625.11  4982.4 1625.13    4988 1624.31  4990.8 1623.81
    4994 1624.31  5005.8 1624.31  5011.9 1625.31  5018.7 1627.98  5026.7 1629.37
  5041.4 1630.39  5047.6 1630.24  5091.9  1632.3  5154.6 1634.11    5178 1635.91
  5184.1 1635.27    5205 1636.53  5291.1 1638.94  5326.8 1640.96  5363.2 1641.16
#Mann= 3 ,-1 , 0
  4564.8      .1       0    4988     .07       0    4994      .1       0
Bank Sta=4988,4994
XS Rating Curve= 0 ,0
Exp/Cntr=0.3,0.1

Type RM Length L Ch R = 1 ,3323    ,342,342,342
BEGIN DESCRIPTION:
UNT 0019 IN HEWA 6.0
END DESCRIPTION:
XS GIS Cut Line= 3
      2749097.02     10048461.63      2748864.35     10048271.69
      2748413.33      10048162.5
#Sta/Elev= 30
  4612.4 1635.69    4680 1633.43  4701.7 1632.96  4787.1 1630.75  4907.2 1627.98
  4949.7 1627.81    4960 1626.94  4966.5 1625.27  4980.5 1623.98  4998.1 1620.39
  5000.9 1619.89  5004.1 1620.39  5008.3 1621.94  5013.4 1621.85    5018 1623.59
  5021.7 1624.99    5032 1626.53  5050.1 1625.77  5055.3 1627.03  5073.1 1627.19
  5091.9 1626.06  5097.1 1627.89  5132.8 1629.23  5165.7 1630.79  5180.7 1630.25
  5258.3 1632.63  5299.5 1635.84  5320.1 1634.93  5353.2 1636.03  5376.8 1638.19
#Mann= 8 ,-1 , 0
  4612.4     .16       0    4680      .1       0  4701.7     .16       0
  4787.1      .1       0  4998.1     .07       0  5004.1      .1       0
    5018     .16       0  5132.8      .1       0
Bank Sta=4998.1,5004.1
XS Rating Curve= 0 ,0
Exp/Cntr=0.3,0.1

Type RM Length L Ch R = 1 ,2981    ,542,542,542
BEGIN DESCRIPTION:
Mapping XS 05794143
END DESCRIPTION:
XS GIS Cut Line= 3
      2749405.86      10048335.6      2748999.59     10048028.29
      2748453.13     10047955.43
#Sta/Elev= 30
  4410.5 1639.31  4417.6 1639.22  4508.7 1636.62  4584.6 1633.71  4738.2 1629.16
    4759 1626.34  4762.7 1626.41  4808.9 1623.21  4838.1 1622.87  4852.6 1623.65
  4866.5 1622.62  4881.7 1621.96    4888 1622.49  4902.6 1626.28  4917.1 1625.84
  4941.2 1624.41  4989.4 1619.78  4994.5 1620.87  4998.7 1618.37  5001.5 1617.87
  5004.7 1618.37  5011.8 1618.57  5042.1 1625.98    5068 1626.98  5213.6 1628.74
  5301.1 1631.43  5443.4 1636.15  5455.7 1637.22  5465.8 1637.27  5471.2 1638.23
#Mann= 10 ,-1 , 0
  4410.5     .05       0  4417.6      .1       0  4508.7     .05       0
  4584.6      .1       0  4762.7     .16       0  4866.5      .1       0
  4998.7     .07       0  5004.7      .1       0    5068     .16       0
  5301.1      .1       0
Bank Sta=4998.7,5004.7
XS Rating Curve= 0 ,0
Exp/Cntr=0.3,0.1

Type RM Length L Ch R = 1 ,2439    ,496,496,496
BEGIN DESCRIPTION:
UNT 0019 IN HEWA 5.0
END DESCRIPTION:
XS GIS Cut Line= 3
       2749343.9     10048091.28      2749078.01     10047820.64
      2748888.07     10047568.97
#Sta/Elev= 30
  4548.5 1633.54  4571.9 1633.36  4649.6 1629.79  4670.9 1629.86  4747.8 1627.69
  4776.9 1625.38  4783.9 1624.09  4812.2 1620.59  4847.6 1618.44    4890 1618.24
  4911.2 1619.68  4918.3 1618.97    4924 1620.11  4932.9 1619.79  4939.1 1620.88
  4953.7 1620.88  4982.8 1619.79  4989.1  1617.9  5003.7 1614.75  5011.5 1614.17
  5018.2 1615.89  5032.8 1617.63    5039 1617.83  5047.3  1620.1  5053.6 1620.67
  5061.8 1623.17  5068.2 1624.43  5077.4 1624.96    5139 1626.06  5243.2 1626.71
#Mann= 5 ,-1 , 0
  4548.5      .1       0  4747.8     .16       0  4982.8     .07       0
  5047.3     .16       0  5077.4      .1       0
Bank Sta=4982.8,5047.3
XS Rating Curve= 0 ,0
Exp/Cntr=0.3,0.1

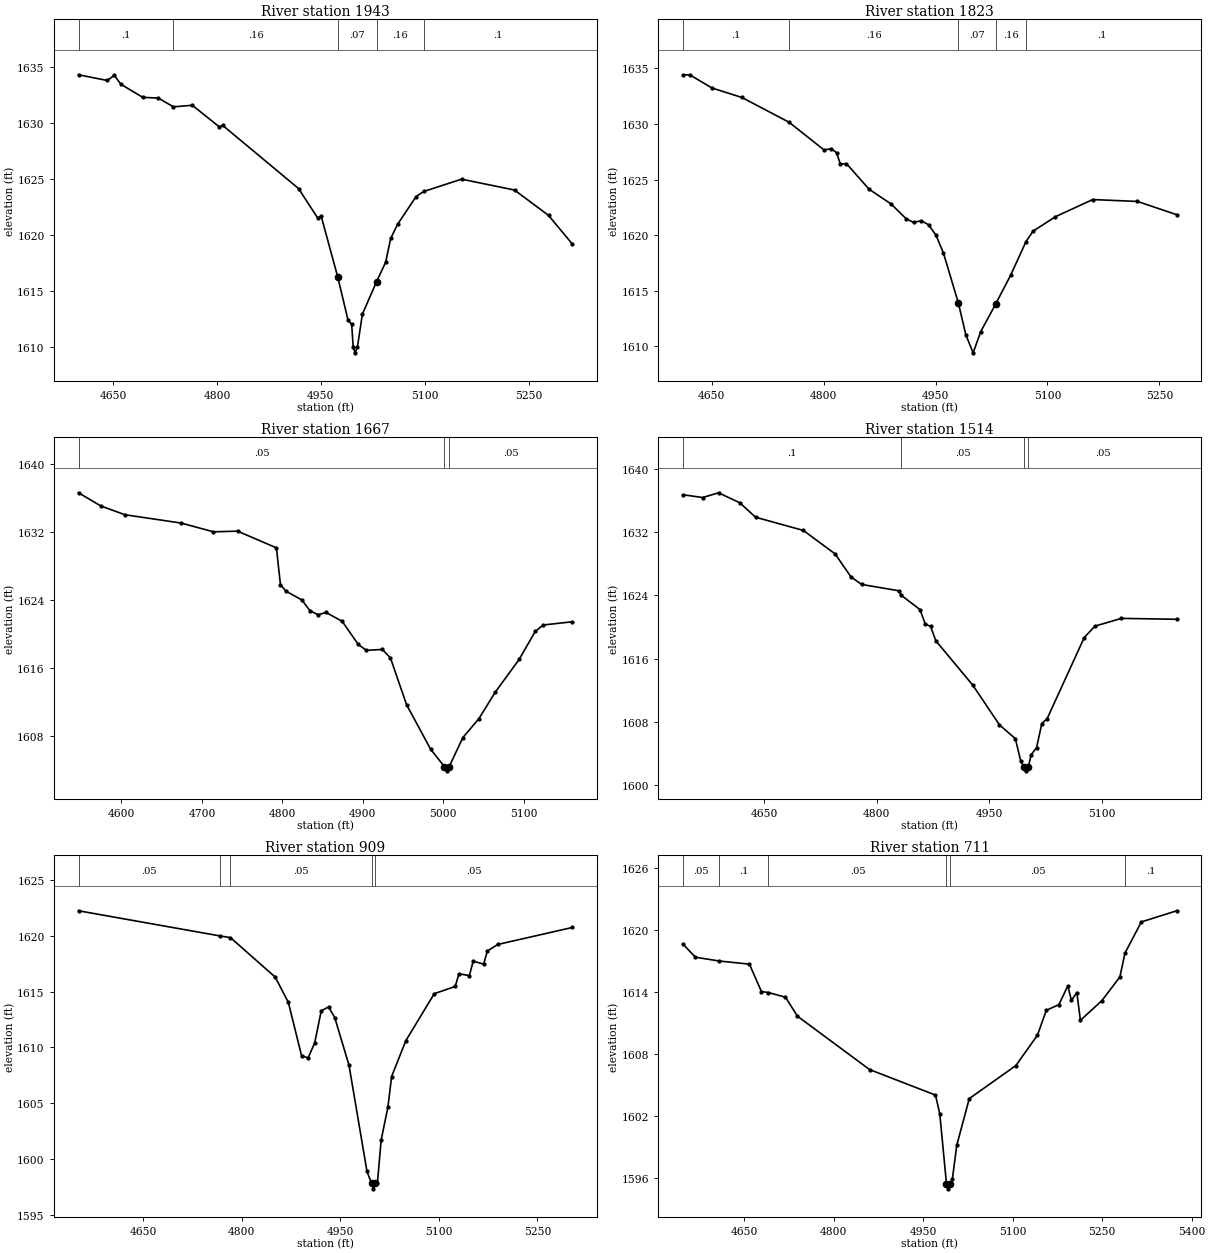
Type RM Length L Ch R = 1 ,1943    ,120,120,120
BEGIN DESCRIPTION:
UNT 0019 IN HEWA 4.0
END DESCRIPTION:
XS GIS Cut Line= 2
      2749467.33     10048034.26      2749315.67     10047337.58
#Sta/Elev= 30
  4600.1  1634.3  4641.6 1633.79  4651.8 1634.25  4661.1 1633.46  4692.7 1632.29
  4715.3 1632.22  4737.2 1631.44  4764.4 1631.58  4803.3 1629.66  4808.4 1629.78
  4917.9 1624.15  4945.4 1621.53  4950.5 1621.69 4974.56 1616.23  4989.4 1612.39
  4994.5 1612.06  4996.8    1610  4999.5  1609.5  5002.8    1610    5010 1612.95
  5030.5 1615.85  5043.6 1617.58  5050.9 1619.71  5061.2    1621  5087.6 1623.44
  5098.5 1623.89  5153.3 1624.99  5229.7 1624.02  5278.8 1621.76  5313.1 1619.21
#Mann= 5 ,-1 , 0
  4600.1      .1       0  4737.2     .16       0 4974.56     .07       0
  5030.5     .16       0  5098.5      .1       0
Bank Sta=4974.56,5030.5
XS Rating Curve= 0 ,0
Exp/Cntr=0.3,0.1

Type RM Length L Ch R = 1 ,1823    ,156,156,156
BEGIN DESCRIPTION:
Mapping XS ac0f0859
END DESCRIPTION:
XS GIS Cut Line= 2
      2749510.01     10048012.68      2749489.18      10047351.2
#Sta/Elev= 30
  4611.5 1634.39  4620.4 1634.41  4650.5 1633.22  4690.5 1632.37  4753.8 1630.14
  4800.5 1627.66  4810.5 1627.77  4817.4  1627.4  4822.4 1626.38  4830.6 1626.43
  4860.6 1624.15  4890.6 1622.79  4910.6 1621.48  4920.6 1621.14  4930.6  1621.3
  4940.6 1620.94  4950.6    1620  4960.6 1618.39  4980.6 1613.91  4990.6 1611.05
  5000.4 1609.43  5010.6 1611.34  5030.7 1613.83  5050.7 1616.41  5071.3 1619.43
  5080.7 1620.36  5110.7 1621.66  5160.7  1623.2  5220.7 1623.03  5273.3 1621.84
#Mann= 5 ,-1 , 0
  4611.5      .1       0  4753.8     .16       0  4980.6     .07       0
  5030.7     .16       0  5071.3      .1       0
Bank Sta=4980.6,5030.7
XS Rating Curve= 0 ,0
Exp/Cntr=0.3,0.1

Type RM Length L Ch R = 1 ,1667    ,153,153,153
BEGIN DESCRIPTION:
Mapping XS cfff4392
END DESCRIPTION:
XS GIS Cut Line= 2
       2749629.8     10047981.38       2749614.2     10047367.78
#Sta/Elev= 30
  4546.6 1636.62  4574.3 1635.07  4604.3 1634.04  4674.3 1633.06  4714.3 1632.03
  4744.3 1632.11  4792.6 1630.15  4797.6 1625.83  4804.3 1625.07  4824.3 1624.02
  4834.3 1622.76  4844.3 1622.29  4854.3 1622.55  4874.4 1621.51  4894.4 1618.79
  4904.4  1618.1  4924.4 1618.21  4934.4  1617.2  4954.4 1611.71  4984.4 1606.47
  5001.4 1604.44  5004.1 1603.94  5007.4 1604.44  5024.4 1607.85  5044.4 1610.08
  5064.4 1613.15  5094.4 1617.04  5114.4 1620.33  5124.4 1621.08  5160.4 1621.46
#Mann= 3 ,-1 , 0
  4546.6     .05       0  5001.4     .04       0  5007.4     .05       0
Bank Sta=5001.4,5007.4
XS Rating Curve= 0 ,0
Exp/Cntr=0.3,0.1

Type RM Length L Ch R = 1 ,1514    ,605,605,605
BEGIN DESCRIPTION:
UNT 0019 IN HEWA 3.0
END DESCRIPTION:
XS GIS Cut Line= 2
      2750065.59     10047763.67      2749598.58     10047299.15
#Sta/Elev= 30
  4541.4 1636.72  4567.6 1636.37  4588.8 1636.97  4617.1 1635.71  4638.3 1633.88
    4702 1632.21  4744.4 1629.24  4765.6 1626.33  4779.7 1625.39  4829.2 1624.59
  4832.6 1624.02  4857.5 1622.22  4864.6 1620.39  4871.7 1620.09  4878.7 1618.27
  4928.2 1612.64  4963.6 1607.65  4984.8  1605.9  4991.9  1603.1    4996 1602.34
  4998.7 1601.84    5002 1602.34    5006 1603.89  5013.1 1604.77  5020.1 1607.81
  5027.2 1608.43  5076.7 1618.68  5090.9 1620.12  5126.2  1621.1  5200.1 1620.99
#Mann= 4 ,-1 , 0
  4541.4      .1       0  4832.6     .05       0    4996     .04       0
    5002     .05       0
Bank Sta=4996,5002
XS Rating Curve= 0 ,0
Exp/Cntr=0.3,0.1

Type RM Length L Ch R = 1 ,909     ,198,198,198
BEGIN DESCRIPTION:
UNT 0019 IN HEWA 2.0
END DESCRIPTION:
XS GIS Cut Line= 3
      2750307.68     10047103.69      2749932.64     10047089.45
      2749605.06     10047274.61
#Sta/Elev= 30
  4551.4 1622.26  4766.1 1620.01  4782.7 1619.85  4850.8 1616.31  4870.8 1614.04
  4890.9 1609.26  4900.9 1609.06  4910.9 1610.41  4920.9 1613.29    4932 1613.63
  4941.4 1612.68  4963.1 1608.41  4990.5 1598.87  4997.4 1597.81  5000.2 1597.31
  5003.4 1597.81  5006.4 1597.84  5012.1  1601.7  5022.3 1604.62    5028 1607.39
  5049.7 1610.61  5092.9 1614.82  5124.8 1615.47  5130.5 1616.61  5146.4 1616.44
  5152.2 1617.74  5168.1 1617.47  5173.8 1618.65  5189.7 1619.24    5303 1620.76
#Mann= 5 ,-1 , 0
  4551.4     .05       0  4766.1      .1       0  4782.7     .05       0
  4997.4     .03       0  5003.4     .05       0
Bank Sta=4997.4,5003.4
XS Rating Curve= 0 ,0
Exp/Cntr=0.3,0.1

Type RM Length L Ch R = 1 ,711     ,291,291,291
BEGIN DESCRIPTION:
Mapping XS 63c59daa
END DESCRIPTION:
XS GIS Cut Line= 4
      2750138.98     10047040.63      2749743.11     10046993.75
      2749649.36     10047082.29      2749483.05     10047331.75
#Sta/Elev= 30
  4547.5 1618.62  4568.4 1617.35  4607.6 1616.99  4658.8 1616.68  4678.9 1614.03
  4690.7 1613.93  4719.2 1613.48  4739.3 1611.64  4860.2 1606.47  4970.6    1604
  4977.8 1602.19    4989 1595.42  4991.7 1594.92    4995 1595.42  4998.9 1595.85
  5006.2 1599.12  5027.2 1603.66  5105.3 1606.86  5141.4 1609.79  5156.4 1612.21
  5177.4 1612.76  5192.4 1614.58  5198.4 1613.17  5207.5 1613.93  5213.5 1611.24
  5249.5 1613.15  5279.6 1615.44  5288.2 1617.76  5315.6 1620.77  5374.9 1621.85
#Mann= 6 ,-1 , 0
  4547.5     .05       0  4607.6      .1       0  4690.7     .05       0
    4989     .03       0    4995     .05       0  5288.2      .1       0
Bank Sta=4989,4995
XS Rating Curve= 0 ,0
Exp/Cntr=0.3,0.1

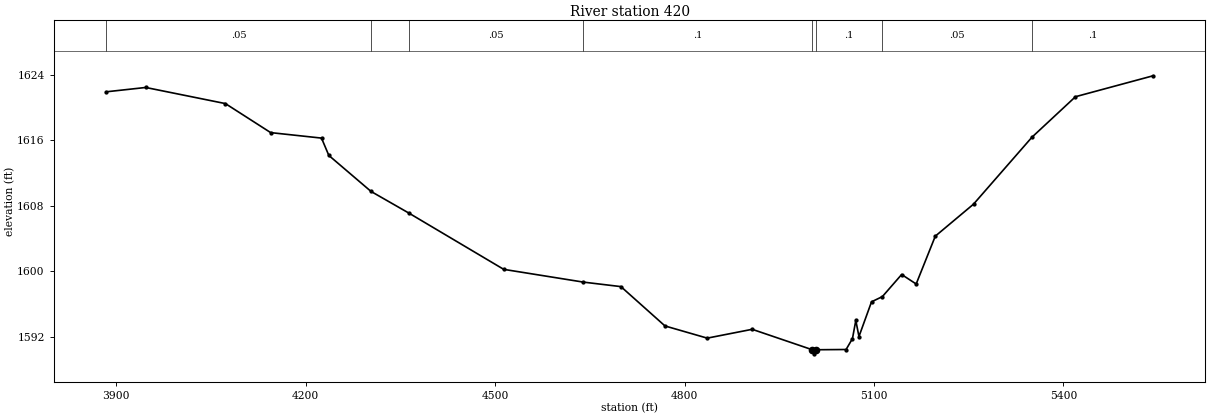
Type RM Length L Ch R = 1 ,420     ,0,0,0
BEGIN DESCRIPTION:
UNT 0019 IN HEWA 1.0
END DESCRIPTION:
XS GIS Cut Line= 3
      2750492.94     10047032.48      2749495.83     10046814.07
      2749410.36     10047445.56
#Sta/Elev= 30
  3884.1 1621.93  3946.7 1622.46  4072.9 1620.49  4144.6 1616.94  4225.1 1616.27
  4236.7 1614.15  4303.5 1609.75  4363.7 1607.09  4513.7 1600.22  4639.9 1598.66
  4699.3 1598.11  4769.1  1593.3    4836 1591.81  4907.2 1592.89  5002.4 1590.39
  5005.2 1589.89  5008.4 1590.39  5055.9 1590.42    5066 1591.75  5071.3 1593.97
  5076.3 1592.01  5096.2 1596.25  5113.4 1596.89  5143.9 1599.59  5166.9 1598.43
  5197.2 1604.28  5257.7 1608.19  5350.3 1616.38  5419.2 1621.33  5542.1 1623.89
#Mann= 8 ,-1 , 0
  3884.1     .05       0  4303.5      .1       0  4363.7     .05       0
  4639.9      .1       0  5002.4     .07       0  5008.4      .1       0
  5113.4     .05       0  5350.3      .1       0
Bank Sta=5002.4,5008.4
XS Rating Curve= 0 ,0
Exp/Cntr=0.3,0.1

Chan Stop Cuts=-1
Use User Specified Reach Order=0
Composite Channel Slope=5