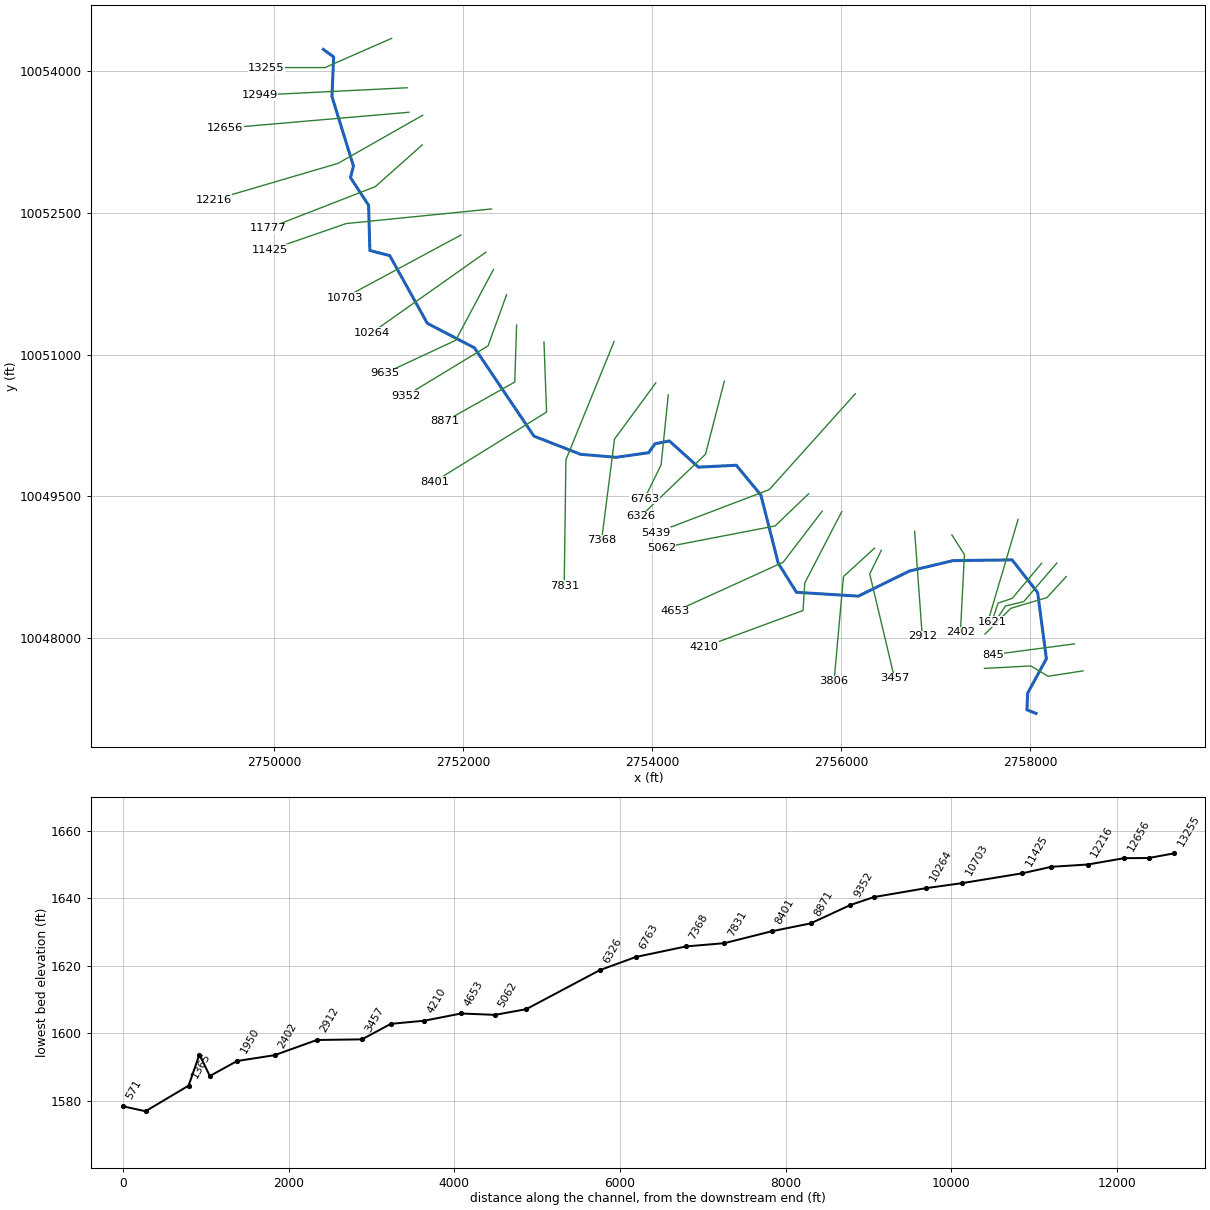
--- UNT 0020 IN HEWA.prj (project) ---

Proj Title=UNT 0020 IN HEWA Base Level Engineering
Current Plan=p01
Default Exp/Contr=0.3,0.1
English Units
Geom File=g01
Flow File=f01
Plan File=p01
BEGIN DESCRIPTION:
UNT 0020 IN HEWA
END DESCRIPTION:

--- UNT 0020 IN HEWA.p01 (plan) ---

Plan Title=Multiple Run
Short Identifier=Multiple
Geom File=g01
Flow File=f01
Subcritical Flow
K Sum by GR= 0
Std Step Tol= 0.01
Critical Tol= 0.01
Num of Std Step Trials= 20
Max Error Tol= 0.3
Flow Tol Ratio= 0.001
Split Flow NTrial= 30
Split Flow Tol= 0.02
Split Flow Ratio= 0.02
Log Output Level= 0
Friction Slope Method= 1
Unsteady Friction Slope Method= 2
Unsteady Bridges Friction Slope Method= 1
Parabolic Critical Depth
Global Vel Dist=  1 , 1 , 1
Global Log Level= 0
CheckData=True
Encroach Param= -1, 0, 0, 0
BEGIN DESCRIPTION:
Multiple Run
END DESCRIPTION:

--- UNT 0020 IN HEWA.f01 (steady flow) ---

Flow Title=Multiple
Number of Profiles=7
Profile Names=10-year,25-year,50-year,1pct_min,100-year,1pct_plu,500-year
River Rch & RM= UNT 0020 IN HEWA,Reach-1,13255
    1285    1903    2448    2301    3112    4209    5056
River Rch & RM= UNT 0020 IN HEWA,Reach-1,7368
    1516    2258    2916    2748    3717    5027    6073
Boundary for River Rch & Prof#=UNT 0020 IN HEWA,Reach-1,1
Up Type=0
Dn Type=3
Dn Slope=0.005
Boundary for River Rch & Prof#=UNT 0020 IN HEWA,Reach-1,2
Up Type=0
Dn Type=3
Dn Slope=0.005
Boundary for River Rch & Prof#=UNT 0020 IN HEWA,Reach-1,3
Up Type=0
Dn Type=3
Dn Slope=0.005
Boundary for River Rch & Prof#=UNT 0020 IN HEWA,Reach-1,4
Up Type=0
Dn Type=3
Dn Slope=0.005
Boundary for River Rch & Prof#=UNT 0020 IN HEWA,Reach-1,5
Up Type=0
Dn Type=3
Dn Slope=0.005
Boundary for River Rch & Prof#=UNT 0020 IN HEWA,Reach-1,6
Up Type=0
Dn Type=3
Dn Slope=0.005
Boundary for River Rch & Prof#=UNT 0020 IN HEWA,Reach-1,7
Up Type=0
Dn Type=3
Dn Slope=0.005

--- UNT 0020 IN HEWA.g01 (geometry) ---

Geom Title=Existing Conditions

River Reach=UNT 0020 IN HEWA,Reach-1
Reach XY= 30
      2750518.47     10054233.73      2750627.33     10054154.10
      2750609.57     10053734.27      2750836.93     10052998.25
      2750805.64     10052876.15      2750997.27     10052583.29
      2751010.58     10052104.36      2751220.84     10052050.51
      2751618.47     10051333.73      2752117.76     10051073.46
      2752746.71     10050139.11      2753239.71     10049946.74
      2753616.42     10049915.01      2753960.17     10049963.62
      2754026.15     10050057.37      2754178.92     10050088.62
      2754486.22     10049810.84      2754887.54     10049830.67
      2755148.03     10049514.73      2755331.10     10048794.82
      2755523.83     10048485.69      2756178.06     10048444.88
      2756719.65     10048710.88      2757179.64     10048820.91
      2757805.54     10048828.81      2758075.77     10048483.73
      2758168.53     10047782.75      2757970.41     10047418.10
      2757962.49     10047240.43      2758058.47     10047203.73

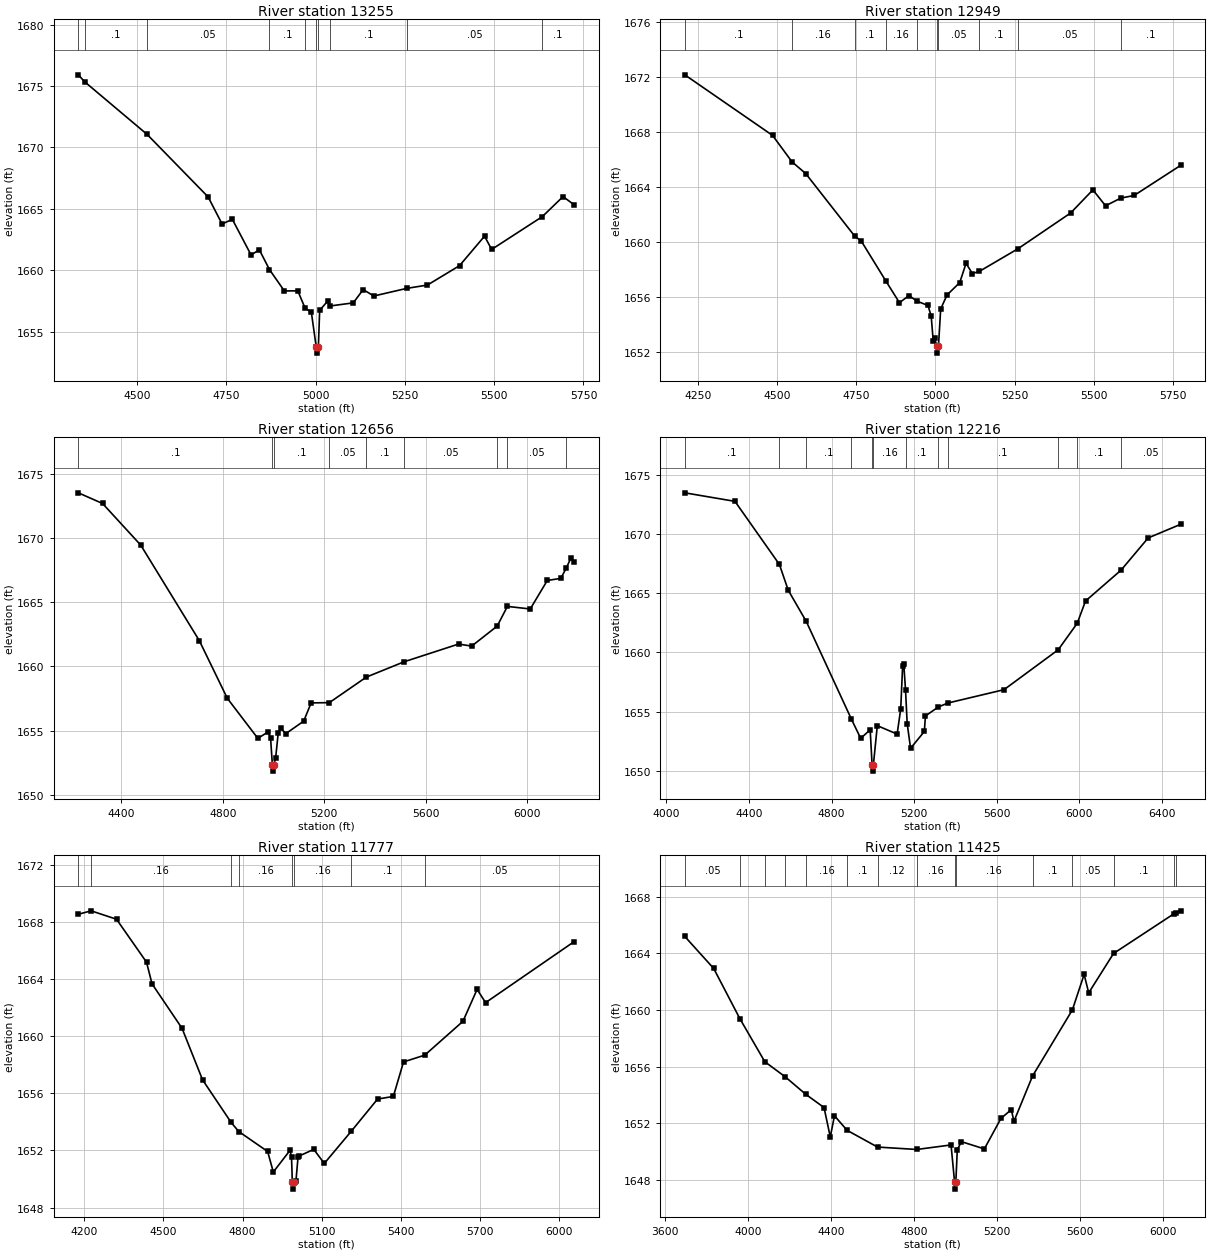
Type RM Length L Ch R = 1,13255,306,306,306
BEGIN DESCRIPTION:
UNT 0020 IN HEWA 29.0
END DESCRIPTION:
XS GIS Cut Line= 3
      2751241.56     10054350.83      2750536.24     10054041.40
      2749917.35     10054041.40
#Sta/Elev= 30
  4334.9 1675.91  4352.4 1675.35  4527.6 1671.06  4698.6 1665.97  4737.6 1663.77
  4766.4 1664.15  4818.8 1661.25  4842.0 1661.67  4870.4 1660.06  4912.1 1658.32
  4949.8 1658.33  4970.0 1656.93  4987.7 1656.59  5001.4 1653.76  5004.2 1653.26
  5007.4 1653.76  5011.0 1656.74  5034.4 1657.53  5040.8 1657.10  5105.1 1657.35
  5132.9 1658.43  5162.9 1657.91  5254.9 1658.53  5312.9 1658.80  5402.9 1660.38
  5472.9 1662.78  5492.9 1661.70  5634.8 1664.37  5692.9 1666.00  5724.0 1665.33
#Mann=10,-1,0
  4334.9    0.05       0  4352.4     0.1       0  4527.6    0.05       0
  4870.4     0.1       0  4970.0    0.05       0  5001.4    0.04       0
  5007.4    0.05       0  5040.8     0.1       0  5254.9    0.05       0
  5634.8     0.1       0
Bank Sta=5001.4,5007.4
Exp/Cntr=0.3,0.1

Type RM Length L Ch R = 1,12949,293,293,293
BEGIN DESCRIPTION:
UNT 0020 IN HEWA 28.0
END DESCRIPTION:
XS GIS Cut Line= 2
      2751405.37     10053827.53      2749841.78     10053750.25
#Sta/Elev= 30
  4208.5 1672.14  4485.7 1667.73  4547.3 1665.80  4590.1 1664.96  4744.4 1660.42
  4766.1 1660.03  4843.0 1657.15  4886.2 1655.56  4916.3 1656.08  4941.6 1655.67
  4976.3 1655.36  4986.4 1654.59  4992.9 1652.78  4997.9 1653.01  5003.4 1652.39
  5006.1 1651.89  5009.4 1652.39  5016.4 1655.10  5036.4 1656.12  5076.5 1657.02
  5096.5 1658.42  5116.5 1657.68  5138.7 1657.84  5260.1 1659.48  5426.9 1662.09
  5497.0 1663.77  5537.0 1662.61  5585.0 1663.17  5627.1 1663.36  5774.0 1665.55
#Mann=10,-1,0
  4208.5     0.1       0  4547.3    0.16       0  4744.4     0.1       0
  4843.0    0.16       0  4941.6    0.05       0  5003.4    0.04       0
  5009.4    0.05       0  5138.7     0.1       0  5260.1    0.05       0
  5585.0     0.1       0
Bank Sta=5003.4,5009.4
Exp/Cntr=0.3,0.1

Type RM Length L Ch R = 1,12656,440,440,440
BEGIN DESCRIPTION:
UNT 0020 IN HEWA 27.0
END DESCRIPTION:
XS GIS Cut Line= 2
      2751423.63     10053568.15      2749475.99     10053399.78
#Sta/Elev= 30
  4230.5 1673.51  4326.0 1672.68  4476.6 1669.44  4707.4 1662.01  4817.8 1657.52
  4938.3 1654.40  4978.4 1654.90  4988.5 1654.42  4995.5 1652.35  4998.3 1651.85
  5001.5 1652.35  5008.6 1652.91  5018.6 1654.82  5028.6 1655.18  5048.7 1654.77
  5119.0 1655.74  5148.4 1657.16  5220.1 1657.18  5366.2 1659.17  5514.9 1660.36
  5729.7 1661.74  5781.4 1661.58  5882.0 1663.14  5922.1 1664.67  6012.3 1664.47
  6079.5 1666.69  6132.7 1666.85  6155.2 1667.69  6172.9 1668.45  6185.4 1668.11
#Mann=9,-1,0
  4230.5     0.1       0  4995.5    0.07       0  5001.5     0.1       0
  5220.1    0.05       0  5366.2     0.1       0  5514.9    0.05       0
  5882.0     0.1       0  5922.1    0.05       0  6155.2     0.1       0
Bank Sta=4995.5,5001.5
Exp/Cntr=0.3,0.1

Type RM Length L Ch R = 1,12216,439,439,439
BEGIN DESCRIPTION:
UNT 0020 IN HEWA 26.0
END DESCRIPTION:
XS GIS Cut Line= 3
      2751569.19     10053536.29      2750672.76     10053026.65
      2749357.64     10052639.85
#Sta/Elev= 30
  4089.1 1673.48  4332.1 1672.76  4547.4 1667.43  4590.2 1665.25  4677.4 1662.62
  4895.7 1654.38  4941.2 1652.74  4987.2 1653.46  4996.5 1650.47  4999.3 1649.97
  5002.5 1650.47  5021.7 1653.81  5117.8 1653.10  5135.2 1655.24  5144.4 1658.89
  5149.6 1659.06  5158.3 1656.86  5166.4 1653.99  5182.9 1651.90  5249.6 1653.32
  5254.8 1654.63  5316.5 1655.38  5362.8 1655.72  5635.5 1656.85  5898.0 1660.22
  5990.2 1662.46  6030.4 1664.34  6202.6 1666.95  6333.9 1669.67  6491.1 1670.82
#Mann=12,-1,0
  4089.1     0.1       0  4547.4    0.16       0  4677.4     0.1       0
  4895.7    0.16       0  4996.5    0.07       0  5002.5    0.16       0
  5158.3     0.1       0  5316.5    0.05       0  5362.8     0.1       0
  5898.0    0.05       0  5990.2     0.1       0  6202.6    0.05       0
Bank Sta=4996.5,5002.5
Exp/Cntr=0.3,0.1

Type RM Length L Ch R = 1,11777,352,352,352
BEGIN DESCRIPTION:
UNT 0020 IN HEWA 25.0
END DESCRIPTION:
XS GIS Cut Line= 3
      2751564.66     10053222.33      2751068.65     10052780.92
      2749935.57     10052339.52
#Sta/Elev= 30
  4177.4 1668.57  4225.9 1668.81  4322.2 1668.22  4435.9 1665.21  4456.8 1663.69
  4570.6 1660.57  4648.3 1656.96  4756.7 1653.97  4785.7 1653.33  4895.2 1651.93
  4916.7 1650.49  4980.4 1652.02  4985.8 1651.51  4988.8 1649.79  4991.6 1649.29
  4994.8 1649.79  5002.6 1649.88  5010.3 1651.51  5015.7 1651.62  5070.1 1652.08
  5109.9 1651.09  5212.3 1653.35  5312.1 1655.61  5371.8 1655.79  5410.4 1658.21
  5491.1 1658.69  5635.7 1661.06  5689.4 1663.30  5721.6 1662.37  6057.4 1666.65
#Mann=8,-1,0
  4177.4     0.1       0  4225.9    0.16       0  4756.7     0.1       0
  4785.7    0.16       0  4988.8    0.07       0  4994.8    0.16       0
  5212.3     0.1       0  5491.1    0.05       0
Bank Sta=4988.8,4994.8
Exp/Cntr=0.3,0.1

Type RM Length L Ch R = 1,11425,722,722,722
BEGIN DESCRIPTION:
UNT 0020 IN HEWA 24.0
END DESCRIPTION:
XS GIS Cut Line= 3
      2752297.24     10052544.30      2750759.22     10052389.58
      2749958.34     10052112.01
#Sta/Elev= 30
  3693.8 1665.20  3833.3 1662.94  3959.5 1659.40  4079.8 1656.36  4178.5 1655.29
  4277.3 1654.06  4365.9 1653.12  4396.1 1651.04  4416.2 1652.54  4477.5 1651.51
  4624.1 1650.33  4813.7 1650.16  4979.0 1650.48  4996.1 1647.86  4998.9 1647.36
  5002.1 1647.86  5009.2 1650.15  5029.3 1650.71  5139.8 1650.20  5220.2 1652.36
  5269.8 1652.97  5282.7 1652.15  5372.5 1655.35  5564.8 1660.02  5621.4 1662.52
  5643.5 1661.22  5763.4 1664.00  6054.7 1666.80  6064.4 1666.88  6087.2 1667.01
#Mann=15,-1,0
  3693.8    0.05       0  3959.5     0.1       0  4079.8    0.16       0
  4178.5     0.1       0  4277.3    0.16       0  4477.5     0.1       0
  4624.1    0.12       0  4813.7    0.16       0  4996.1    0.07       0
  5002.1    0.16       0  5372.5     0.1       0  5564.8    0.05       0
  5763.4     0.1       0  6054.7    0.05       0  6064.4     0.1       0
Bank Sta=4996.1,5002.1
Exp/Cntr=0.3,0.1

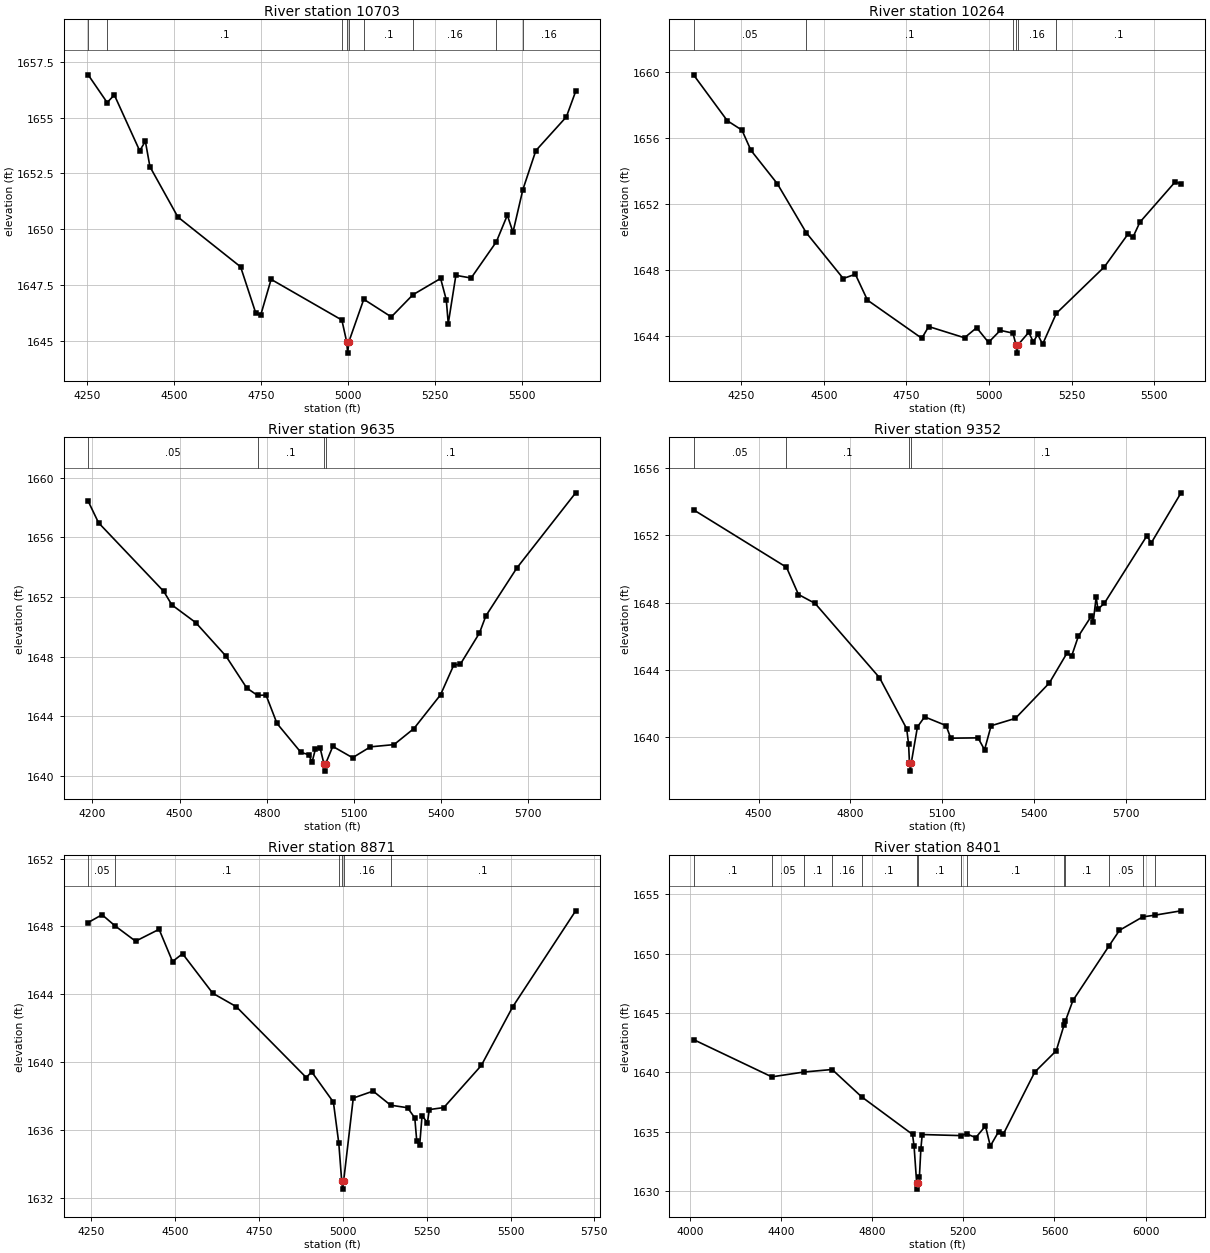
Type RM Length L Ch R = 1,10703,439,439,439
BEGIN DESCRIPTION:
UNT 0020 IN HEWA 23.0
END DESCRIPTION:
XS GIS Cut Line= 2
      2751974.54     10052268.49      2750742.47     10051604.72
#Sta/Elev= 30
  4254.3 1656.91  4308.8 1655.67  4329.4 1656.01  4402.3 1653.51  4418.5 1653.94
  4431.6 1652.80  4511.8 1650.55  4691.9 1648.32  4735.7 1646.24  4749.6 1646.16
  4779.5 1647.76  4982.6 1645.94  4996.5 1644.96  4999.3 1644.46  5002.5 1644.96
  5045.5 1646.87  5124.5 1646.08  5186.4 1647.07  5266.1 1647.80  5282.4 1646.84
  5288.0 1645.78  5309.9 1647.94  5353.7 1647.82  5426.1 1649.44  5457.6 1650.63
  5473.8 1649.87  5502.3 1651.78  5539.5 1653.52  5627.1 1655.03  5653.8 1656.17
#Mann=9,-1,0
  4254.3    0.05       0  4308.8     0.1       0  4982.6    0.16       0
  4996.5    0.07       0  5002.5    0.16       0  5045.5     0.1       0
  5186.4    0.16       0  5426.1     0.1       0  5502.3    0.16       0
Bank Sta=4996.5,5002.5
Exp/Cntr=0.3,0.1

Type RM Length L Ch R = 1,10264,629,629,629
BEGIN DESCRIPTION:
UNT 0020 IN HEWA 22.0
END DESCRIPTION:
XS GIS Cut Line= 2
      2752238.54     10052086.51      2751033.06     10051235.85
#Sta/Elev= 30
  4105.6 1659.82  4207.8 1657.04  4252.1 1656.47  4279.2 1655.25  4359.3 1653.22
  4446.5 1650.26  4558.7 1647.48  4595.3 1647.74  4632.0 1646.17  4796.4 1643.86
  4817.3 1644.57  4925.7 1643.89  4962.4 1644.50  4998.3 1643.61  5034.0 1644.34
  5072.3 1644.17  5081.5 1643.46  5084.3 1642.96  5087.5 1643.46  5120.2 1644.22
  5133.8 1643.64  5147.3 1644.09  5162.1 1643.50  5203.6 1645.37  5349.2 1648.19
  5420.7 1650.18  5435.4 1649.98  5456.4 1650.89  5563.5 1653.34  5581.0 1653.20
#Mann=6,-1,0
  4105.6    0.05       0  4446.5     0.1       0  5072.3    0.16       0
  5081.5    0.07       0  5087.5    0.16       0  5203.6     0.1       0
Bank Sta=5081.5,5087.5
Exp/Cntr=0.3,0.1

Type RM Length L Ch R = 1,9635,283,283,283
BEGIN DESCRIPTION:
UNT 0020 IN HEWA 21.0
END DESCRIPTION:
XS GIS Cut Line= 3
      2752318.44     10051903.69      2751918.47     10051153.73
      2751168.47     10050803.73
#Sta/Elev= 30
  4185.3 1658.43  4221.0 1656.98  4445.6 1652.37  4473.2 1651.47  4555.4 1650.28
  4659.5 1648.03  4731.0 1645.89  4768.3 1645.39  4797.3 1645.42  4835.1 1643.51
  4917.3 1641.57  4944.9 1641.41  4955.6 1640.90  4967.3 1641.79  4983.2 1641.89
  4996.5 1640.81  4999.2 1640.31  5002.5 1640.81  5027.1 1641.97  5095.2 1641.21
  5156.6 1641.94  5237.8 1642.09  5306.4 1643.17  5397.8 1645.43  5443.6 1647.44
  5465.6 1647.47  5531.8 1649.58  5553.9 1650.73  5660.3 1653.94  5862.9 1658.99
#Mann=4,-1,0
  4185.3    0.05       0  4768.3     0.1       0  4996.5    0.07       0
  5002.5     0.1       0
Bank Sta=4996.5,5002.5
Exp/Cntr=0.3,0.1

Type RM Length L Ch R = 1,9352,481,481,481
BEGIN DESCRIPTION:
UNT 0020 IN HEWA 20.0
END DESCRIPTION:
XS GIS Cut Line= 3
      2752456.93     10051635.99      2752261.26     10051094.50
      2751392.83     10050567.07
#Sta/Elev= 30
  4287.8 1653.52  4591.3 1650.10  4630.4 1648.48  4684.7 1647.95  4895.0 1643.53
  4983.8 1640.49  4990.0 1639.57  4992.8 1638.47  4995.6 1637.97  4998.8 1638.47
  5018.9 1640.60  5042.3 1641.20  5112.5 1640.68  5127.6 1639.93  5216.7 1639.95
  5238.0 1639.24  5259.4 1640.67  5338.8 1641.11  5449.3 1643.21  5507.4 1645.00
  5522.0 1644.80  5544.2 1645.99  5586.9 1647.20  5592.8 1646.83  5602.4 1648.33
  5608.2 1647.60  5629.6 1647.97  5767.7 1651.96  5782.7 1651.56  5879.6 1654.53
#Mann=4,-1,0
  4287.8    0.05       0  4591.3     0.1       0  4992.8    0.07       0
  4998.8     0.1       0
Bank Sta=4992.8,4998.8
Exp/Cntr=0.3,0.1

Type RM Length L Ch R = 1,8871,470,470,470
BEGIN DESCRIPTION:
UNT 0020 IN HEWA 19.0
END DESCRIPTION:
XS GIS Cut Line= 3
      2752563.00     10051315.09      2752544.01     10050712.14
      2751803.37     10050294.34
#Sta/Elev= 30
  4240.7 1648.23  4282.1 1648.69  4321.1 1648.03  4382.1 1647.13  4452.2 1647.83
  4492.2 1645.93  4522.2 1646.39  4612.2 1644.06  4682.3 1643.27  4891.0 1639.09
  4907.0 1639.43  4971.9 1637.64  4988.0 1635.22  4996.6 1633.01  4999.3 1632.51
  5002.6 1633.01  5031.2 1637.88  5090.4 1638.29  5142.5 1637.46  5193.0 1637.31
  5214.6 1636.71  5220.4 1635.36  5229.2 1635.11  5236.3 1636.85  5252.2 1636.42
  5257.9 1637.20  5301.2 1637.32  5412.9 1639.80  5506.3 1643.25  5694.3 1648.92
#Mann=6,-1,0
  4240.7    0.05       0  4321.1     0.1       0  4988.0    0.16       0
  4996.6    0.07       0  5002.6    0.16       0  5142.5     0.1       0
Bank Sta=4996.6,5002.6
Exp/Cntr=0.3,0.1

Type RM Length L Ch R = 1,8401,570,570,570
BEGIN DESCRIPTION:
UNT 0020 IN HEWA 18.0
END DESCRIPTION:
XS GIS Cut Line= 3
      2752852.82     10051135.41      2752880.12     10050393.73
      2751693.00     10049656.89
#Sta/Elev= 30
  4016.1 1642.77  4359.6 1639.63  4501.6 1640.04  4624.3 1640.25  4753.6 1637.95
  4977.2 1634.78  4983.9 1633.78  4995.4 1630.67  4998.2 1630.17  5001.4 1630.67
  5007.4 1631.23  5013.8 1633.59  5019.7 1634.77  5189.1 1634.68  5214.3 1634.83
  5254.6 1634.51  5297.2 1635.49  5318.5 1633.80  5355.1 1635.02  5376.3 1634.83
  5513.5 1640.03  5607.8 1641.83  5641.6 1643.97  5648.1 1644.34  5681.1 1646.07
  5838.6 1650.64  5885.4 1651.98  5987.3 1653.11  6039.1 1653.25  6155.5 1653.62
#Mann=14,-1,0
  4016.1     0.1       0  4359.6    0.05       0  4501.6     0.1       0
  4624.3    0.16       0  4753.6     0.1       0  4995.4    0.07       0
  5001.4     0.1       0  5189.1    0.16       0  5214.3     0.1       0
  5641.6    0.05       0  5648.1     0.1       0  5838.6    0.05       0
  5987.3    0.16       0  6039.1    0.05       0
Bank Sta=4995.4,5001.4
Exp/Cntr=0.3,0.1

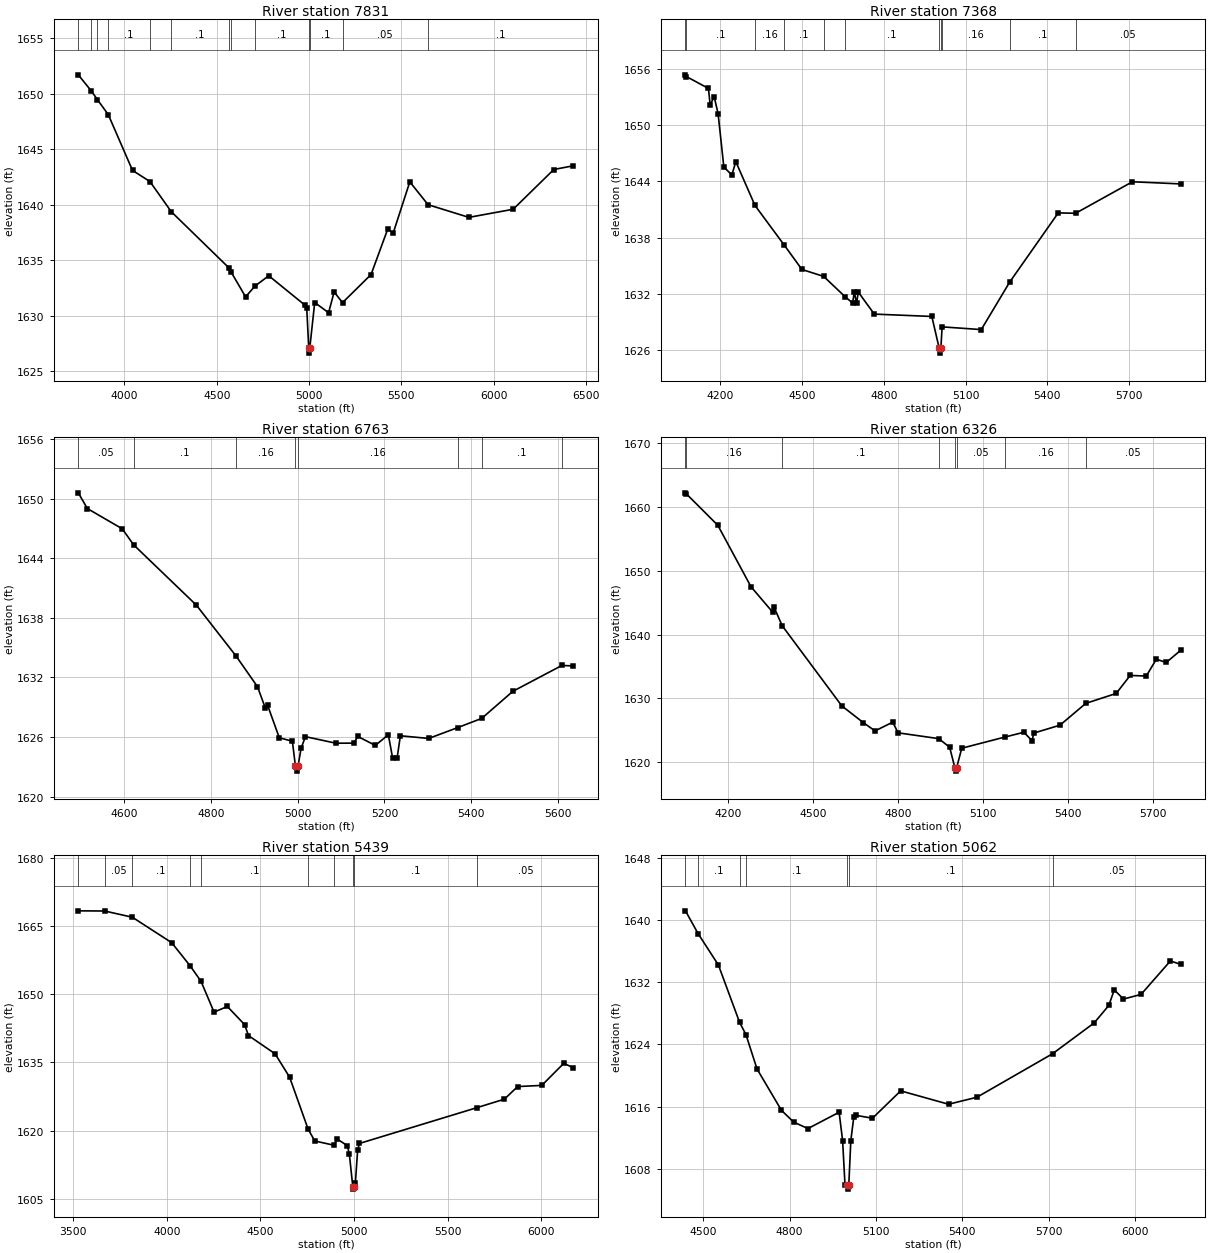
Type RM Length L Ch R = 1,7831,463,463,463
BEGIN DESCRIPTION:
UNT 0020 IN HEWA 17.0
END DESCRIPTION:
XS GIS Cut Line= 3
      2753594.53     10051139.96      2753084.89     10049888.63
      2753066.72     10048557.09
#Sta/Elev= 30
  3750.0 1651.72  3821.3 1650.25  3853.6 1649.48  3912.3 1648.14  4043.7 1643.11
  4137.9 1642.11  4253.8 1639.39  4567.4 1634.31  4578.1 1633.95  4656.3 1631.72
  4707.2 1632.69  4781.9 1633.62  4977.3 1630.98  4987.6 1630.73  4998.4 1627.15
  5001.1 1626.65  5004.4 1627.15  5030.8 1631.21  5106.1 1630.29  5136.0 1632.16
  5181.6 1631.20  5336.1 1633.73  5426.1 1637.81  5456.1 1637.47  5546.1 1642.08
  5645.0 1640.02  5866.1 1638.88  6106.1 1639.61  6326.1 1643.19  6432.8 1643.53
#Mann=13,-1,0
  3750.0    0.05       0  3821.3     0.1       0  3853.6    0.05       0
  3912.3     0.1       0  4137.9    0.05       0  4253.8     0.1       0
  4567.4    0.16       0  4578.1    0.12       0  4707.2     0.1       0
  4998.4    0.07       0  5004.4     0.1       0  5181.6    0.05       0
  5645.0     0.1       0
Bank Sta=4998.4,5004.4
Exp/Cntr=0.3,0.1

Type RM Length L Ch R = 1,7368,605,605,605
BEGIN DESCRIPTION:
UNT 0020 IN HEWA 16.0
END DESCRIPTION:
XS GIS Cut Line= 3
      2754035.93     10050703.15      2753599.09     10050107.05
      2753462.65     10049038.25
#Sta/Elev= 30
  4072.3 1655.35  4075.4 1655.17  4156.6 1653.90  4162.8 1652.13  4177.5 1653.03
  4192.1 1651.18  4213.0 1645.53  4242.3 1644.67  4257.0 1646.09  4327.3 1641.42
  4434.0 1637.22  4499.4 1634.60  4579.2 1633.86  4658.4 1631.68  4685.4 1631.02
  4691.6 1632.18  4700.0 1631.00  4706.2 1632.19  4764.9 1629.84  4976.0 1629.59
  5003.2 1626.18  5006.0 1625.68  5009.2 1626.18  5013.7 1628.48  5157.4 1628.19
  5261.8 1633.26  5439.7 1640.63  5503.5 1640.59  5711.9 1643.95  5888.8 1643.72
#Mann=11,-1,0
  4072.3    0.05       0  4075.4     0.1       0  4327.3    0.16       0
  4434.0     0.1       0  4579.2    0.16       0  4658.4     0.1       0
  5003.2    0.07       0  5009.2     0.1       0  5013.7    0.16       0
  5261.8     0.1       0  5503.5    0.05       0
Bank Sta=5003.2,5009.2
Exp/Cntr=0.3,0.1

Type RM Length L Ch R = 1,6763,437,437,437
BEGIN DESCRIPTION:
UNT 0020 IN HEWA 15.0
END DESCRIPTION:
XS GIS Cut Line= 3
      2754167.81     10050574.44      2754091.85     10049833.77
      2753916.45     10049478.24
#Sta/Elev= 30
  4494.6 1650.58  4515.4 1649.00  4595.8 1646.96  4622.2 1645.34  4766.7 1639.27
  4857.9 1634.16  4907.5 1631.06  4925.9 1628.87  4930.9 1629.18  4957.7 1625.92
  4987.9 1625.57  4994.9 1623.06  4997.7 1622.56  5000.9 1623.06  5008.0 1624.87
  5018.0 1626.03  5088.4 1625.37  5129.5 1625.38  5138.7 1626.05  5178.9 1625.15
  5209.0 1626.22  5218.7 1623.91  5229.1 1623.84  5236.7 1626.12  5301.9 1625.85
  5369.3 1626.95  5424.2 1627.87  5495.7 1630.59  5608.9 1633.20  5635.6 1633.15
#Mann=8,-1,0
  4494.6    0.05       0  4622.2     0.1       0  4857.9    0.16       0
  4994.9    0.07       0  5000.9    0.16       0  5369.3    0.05       0
  5424.2     0.1       0  5608.9    0.05       0
Bank Sta=4994.9,5000.9
Exp/Cntr=0.3,0.1

Type RM Length L Ch R = 1,6326,887,887,887
BEGIN DESCRIPTION:
UNT 0020 IN HEWA 13.0
END DESCRIPTION:
XS GIS Cut Line= 3
      2754761.30     10050721.61      2754561.90     10049947.72
      2753878.22     10049292.53
#Sta/Elev= 30
  4051.3 1662.17  4054.6 1662.00  4165.4 1657.09  4282.3 1647.48  4358.5 1643.52
  4363.7 1644.27  4392.2 1641.39  4602.6 1628.84  4678.9 1626.21  4719.6 1624.93
  4782.3 1626.30  4800.9 1624.63  4944.5 1623.72  4982.9 1622.37  5001.3 1619.14
  5004.1 1618.64  5007.3 1619.14  5025.4 1622.22  5178.4 1623.98  5244.6 1624.72
  5272.9 1623.42  5280.1 1624.60  5372.0 1625.83  5462.9 1629.24  5570.1 1630.79
  5619.5 1633.61  5676.1 1633.51  5711.6 1636.14  5746.8 1635.64  5797.4 1637.54
#Mann=8,-1,0
  4051.3    0.05       0  4054.6    0.16       0  4392.2     0.1       0
  4944.5    0.05       0  5001.3    0.04       0  5007.3    0.05       0
  5178.4    0.16       0  5462.9    0.05       0
Bank Sta=5001.3,5007.3
Exp/Cntr=0.3,0.1

Type RM Length L Ch R = 1,5439,377,377,377
BEGIN DESCRIPTION:
UNT 0020 IN HEWA 12.0
END DESCRIPTION:
XS GIS Cut Line= 3
      2756147.72     10050588.70      2755236.10     10049572.63
      2754039.66     10049116.84
#Sta/Elev= 30
  3526.7 1668.45  3667.5 1668.41  3815.3 1667.04  4025.5 1661.43  4123.8 1656.34
  4182.3 1652.90  4252.0 1646.11  4323.0 1647.35  4415.0 1643.36  4435.9 1640.94
  4577.9 1636.92  4655.7 1631.75  4754.7 1620.27  4790.2 1617.69  4892.7 1616.75
  4910.7 1618.08  4964.2 1616.66  4974.9 1614.71  4993.3 1607.57  4996.0 1607.07
  4999.3 1607.57  5007.0 1608.49  5019.1 1615.70  5028.4 1617.14  5658.8 1625.07
  5802.9 1626.91  5873.7 1629.69  6002.9 1629.95  6119.9 1634.80  6172.1 1633.85
#Mann=10,-1,0
  3526.7     0.1       0  3667.5    0.05       0  3815.3     0.1       0
  4123.8    0.05       0  4182.3     0.1       0  4754.7    0.16       0
  4892.7     0.1       0  4993.3    0.07       0  4999.3     0.1       0
  5658.8    0.05       0
Bank Sta=4993.3,4999.3
Exp/Cntr=0.3,0.1

Type RM Length L Ch R = 1,5062,409,409,409
BEGIN DESCRIPTION:
UNT 0020 IN HEWA 11.0
END DESCRIPTION:
XS GIS Cut Line= 3
      2755653.91     10049529.89      2755297.83     10049188.05
      2754093.45     10048955.71
#Sta/Elev= 30
  4438.2 1641.19  4481.8 1638.27  4552.6 1634.22  4625.9 1626.87  4648.3 1625.26
  4686.8 1620.84  4771.7 1615.52  4814.2 1614.01  4863.6 1613.18  4971.9 1615.28
  4984.1 1611.62  4992.3 1605.96  4999.5 1605.89  5002.2 1605.39  5005.5 1605.89
  5012.6 1611.64  5022.8 1614.64  5030.8 1614.88  5087.8 1614.51  5185.8 1618.03
  5352.2 1616.31  5450.6 1617.21  5713.2 1622.80  5857.9 1626.77  5908.9 1629.02
  5927.7 1631.02  5959.8 1629.84  6020.9 1630.44  6122.7 1634.74  6158.4 1634.31
#Mann=7,-1,0
  4438.2    0.16       0  4481.8     0.1       0  4625.9    0.16       0
  4648.3     0.1       0  4999.5    0.07       0  5005.5     0.1       0
  5713.2    0.05       0
Bank Sta=4999.5,5005.5
Exp/Cntr=0.3,0.1

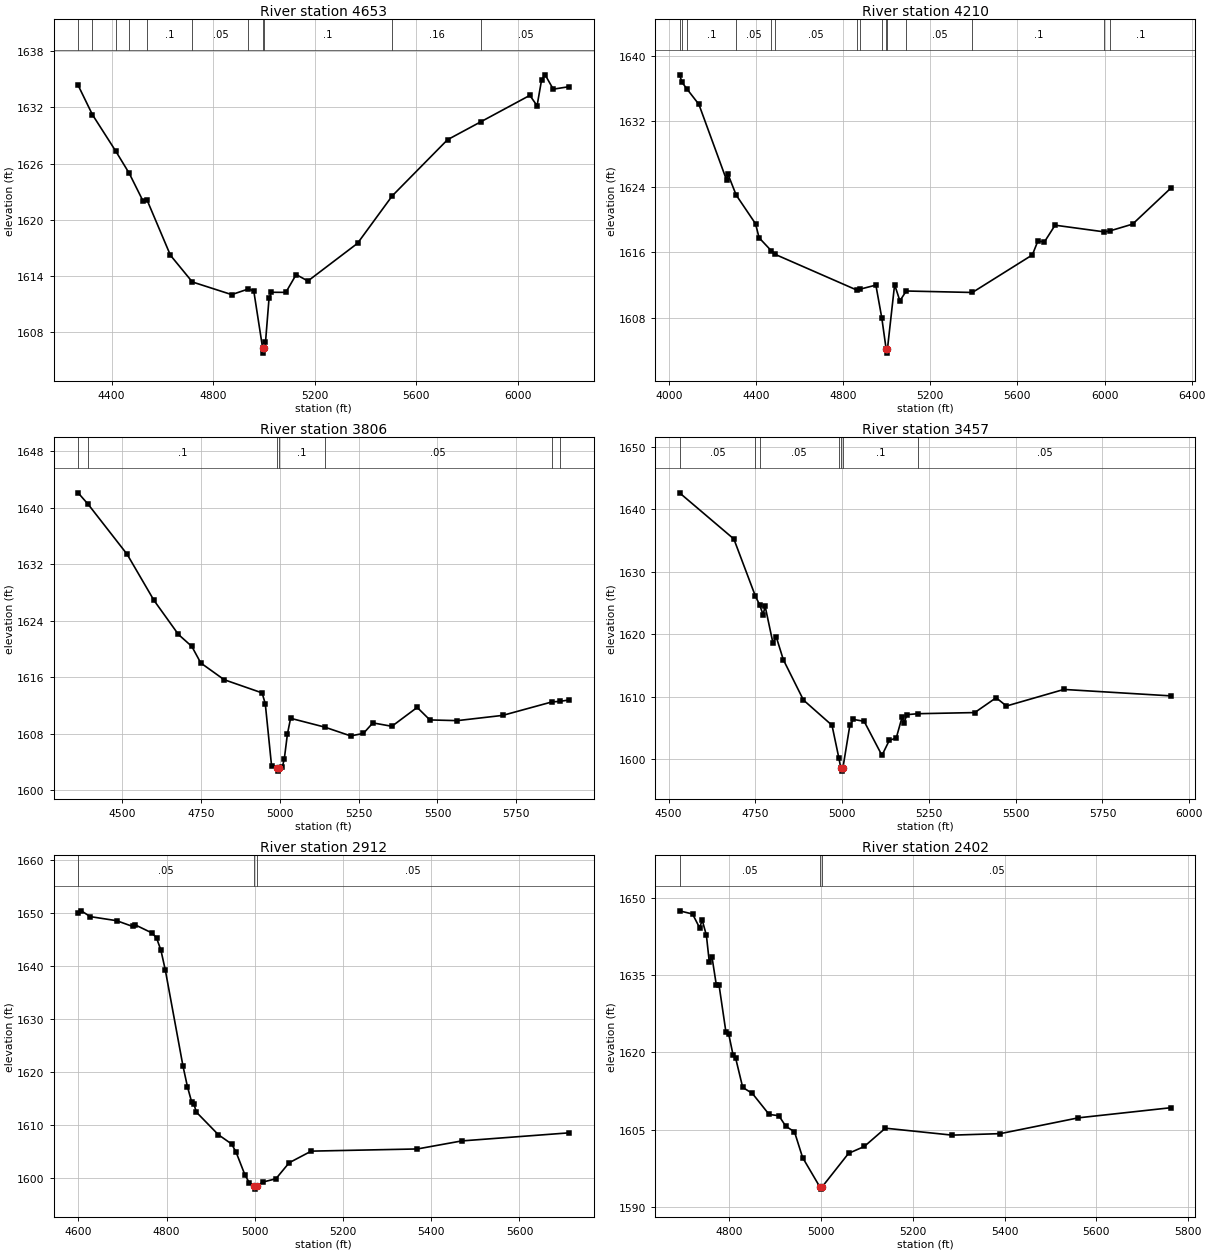
Type RM Length L Ch R = 1,4653,443,443,443
BEGIN DESCRIPTION:
UNT 0020 IN HEWA 10.0
END DESCRIPTION:
XS GIS Cut Line= 3
      2755796.38     10049344.75      2755383.29     10048803.46
      2754241.66     10048284.37
#Sta/Elev= 30
  4268.4 1634.37  4324.6 1631.24  4416.5 1627.35  4469.9 1624.97  4524.0 1622.03
  4540.4 1622.10  4632.0 1616.24  4718.3 1613.39  4873.5 1612.04  4938.9 1612.64
  4960.4 1612.43  4995.5 1606.30  4998.3 1605.80  5001.5 1606.30  5006.5 1606.94
  5020.5 1611.65  5029.6 1612.29  5086.7 1612.28  5127.4 1614.18  5173.5 1613.49
  5369.0 1617.51  5505.7 1622.57  5723.6 1628.56  5856.7 1630.50  6047.8 1633.29
  6076.3 1632.18  6093.9 1634.92  6108.0 1635.48  6140.0 1633.95  6203.4 1634.22
#Mann=11,-1,0
  4268.4     0.1       0  4324.6    0.16       0  4416.5     0.1       0
  4469.9    0.05       0  4540.4     0.1       0  4718.3    0.05       0
  4938.9     0.1       0  4995.5    0.07       0  5001.5     0.1       0
  5505.7    0.16       0  5856.7    0.05       0
Bank Sta=4995.5,5001.5
Exp/Cntr=0.3,0.1

Type RM Length L Ch R = 1,4210,404,404,404
BEGIN DESCRIPTION:
UNT 0020 IN HEWA 9.0
END DESCRIPTION:
XS GIS Cut Line= 4
      2756003.38     10049339.55      2755612.04     10048584.18
      2755593.84     10048292.95      2754550.23     10047907.59
#Sta/Elev= 30
  4049.1 1637.66  4060.7 1636.74  4082.6 1635.95  4138.0 1634.05  4265.2 1624.79
  4270.8 1625.56  4309.2 1622.97  4397.9 1619.47  4414.4 1617.75  4469.8 1616.18
  4485.2 1615.76  4863.3 1611.36  4875.8 1611.46  4950.4 1611.97  4977.7 1607.94
  4997.5 1604.16  5000.2 1603.66  5003.5 1604.16  5036.4 1612.03  5060.6 1610.05
  5090.0 1611.25  5393.4 1611.07  5668.7 1615.66  5693.8 1617.34  5724.2 1617.25
  5773.0 1619.29  5999.8 1618.47  6026.8 1618.61  6128.8 1619.42  6304.1 1623.81
#Mann=15,-1,0
  4049.1     0.1       0  4060.7    0.05       0  4082.6     0.1       0
  4309.2    0.05       0  4469.8     0.1       0  4485.2    0.05       0
  4863.3     0.1       0  4875.8    0.05       0  4977.7     0.1       0
  4997.5    0.07       0  5003.5     0.1       0  5090.0    0.05       0
  5393.4     0.1       0  5999.8    0.05       0  6026.8     0.1       0
Bank Sta=4997.5,5003.5
Exp/Cntr=0.3,0.1

Type RM Length L Ch R = 1,3806,349,349,349
BEGIN DESCRIPTION:
UNT 0020 IN HEWA 8.0
END DESCRIPTION:
XS GIS Cut Line= 3
      2756349.21     10048952.76      2756021.58     10048652.44
      2755921.73     10047542.97
#Sta/Elev= 30
  4360.0 1642.08  4392.2 1640.44  4515.5 1633.39  4600.6 1626.88  4678.3 1622.05
  4720.8 1620.36  4749.2 1618.02  4823.2 1615.66  4943.7 1613.79  4953.8 1612.25
  4973.8 1603.45  4990.9 1603.23  4993.7 1602.73  4996.9 1603.23  5007.8 1603.32
  5014.0 1604.41  5024.0 1607.97  5034.1 1610.20  5141.9 1608.96  5224.7 1607.71
  5265.0 1608.06  5295.1 1609.55  5355.4 1609.07  5435.7 1611.74  5475.9 1609.97
  5562.8 1609.87  5706.8 1610.61  5862.7 1612.51  5889.5 1612.60  5918.4 1612.80
#Mann=7,-1,0
  4360.0    0.05       0  4392.2     0.1       0  4990.9    0.07       0
  4996.9     0.1       0  5141.9    0.05       0  5862.7     0.1       0
  5889.5    0.05       0
Bank Sta=4990.9,4996.9
Exp/Cntr=0.3,0.1

Type RM Length L Ch R = 1,3457,545,545,545
BEGIN DESCRIPTION:
UNT 0020 IN HEWA 7.0
END DESCRIPTION:
XS GIS Cut Line= 3
      2756422.04     10048930.05      2756299.16     10048679.74
      2756562.07     10047574.32
#Sta/Elev= 30
  4531.6 1642.62  4688.1 1635.24  4749.7 1626.17  4762.2 1624.73  4772.5 1623.13
  4778.1 1624.51  4800.6 1618.64  4810.4 1619.55  4830.6 1615.94  4888.6 1609.49
  4970.8 1605.46  4990.4 1600.28  4996.2 1598.63  4999.0 1598.13  5002.2 1598.63
  5022.2 1605.44  5032.5 1606.39  5063.3 1606.10  5114.7 1600.65  5136.0 1603.06
  5155.8 1603.41  5173.0 1606.82  5178.2 1605.81  5186.7 1607.16  5218.8 1607.31
  5382.0 1607.49  5443.6 1609.86  5473.3 1608.54  5638.9 1611.19  5946.7 1610.16
#Mann=7,-1,0
  4531.6    0.05       0  4749.7     0.1       0  4762.2    0.05       0
  4990.4     0.1       0  4996.2    0.07       0  5002.2     0.1       0
  5218.8    0.05       0
Bank Sta=4996.2,5002.2
Exp/Cntr=0.3,0.1

Type RM Length L Ch R = 1,2912,510,510,510
BEGIN DESCRIPTION:
UNT 0020 IN HEWA 6.0
END DESCRIPTION:
XS GIS Cut Line= 2
      2756774.44     10049131.04      2756855.16     10048020.07
#Sta/Elev= 30
  4599.2 1649.96  4606.5 1650.38  4626.6 1649.29  4686.7 1648.52  4722.8 1647.44
  4727.8 1647.77  4766.9 1646.20  4777.0 1645.28  4787.0 1642.95  4797.0 1639.20
  4837.1 1621.09  4847.2 1617.21  4856.9 1614.30  4862.0 1613.94  4867.2 1612.46
  4917.3 1608.19  4947.4 1606.44  4957.5 1604.89  4977.5 1600.62  4987.5 1599.13
  4998.1 1598.44  5000.9 1597.94  5004.1 1598.44  5017.6 1599.26  5047.7 1599.89
  5077.8 1602.91  5127.9 1605.10  5368.5 1605.51  5468.8 1607.02  5713.1 1608.55
#Mann=3,-1,0
  4599.2    0.05       0  4998.1   0.035       0  5004.1    0.05       0
Bank Sta=4998.1,5004.1
Exp/Cntr=0.3,0.1

Type RM Length L Ch R = 1,2402,452,452,452
BEGIN DESCRIPTION:
UNT 0020 IN HEWA 5.0
END DESCRIPTION:
XS GIS Cut Line= 3
      2757168.52     10049093.10      2757301.47     10048884.18
      2757258.74     10048062.82
#Sta/Elev= 30
  4691.9 1647.46  4720.3 1646.84  4735.5 1644.19  4741.4 1645.63  4750.4 1642.71
  4756.7 1637.57  4762.6 1638.50  4771.9 1633.15  4777.8 1633.15  4793.1 1623.85
  4799.0 1623.56  4808.3 1619.57  4814.2 1618.85  4829.5 1613.19  4850.6 1612.01
  4887.1 1607.93  4908.2 1607.70  4923.5 1605.63  4942.3 1604.57  4960.0 1599.57
  4997.1 1593.94  4999.8 1593.44  5003.1 1593.94  5060.1 1600.38  5094.4 1601.72
  5140.3 1605.27  5285.7 1603.92  5390.6 1604.21  5560.8 1607.28  5762.0 1609.24
#Mann=3,-1,0
  4691.9    0.05       0  4997.1    0.03       0  5003.1    0.05       0
Bank Sta=4997.1,5003.1
Exp/Cntr=0.3,0.1

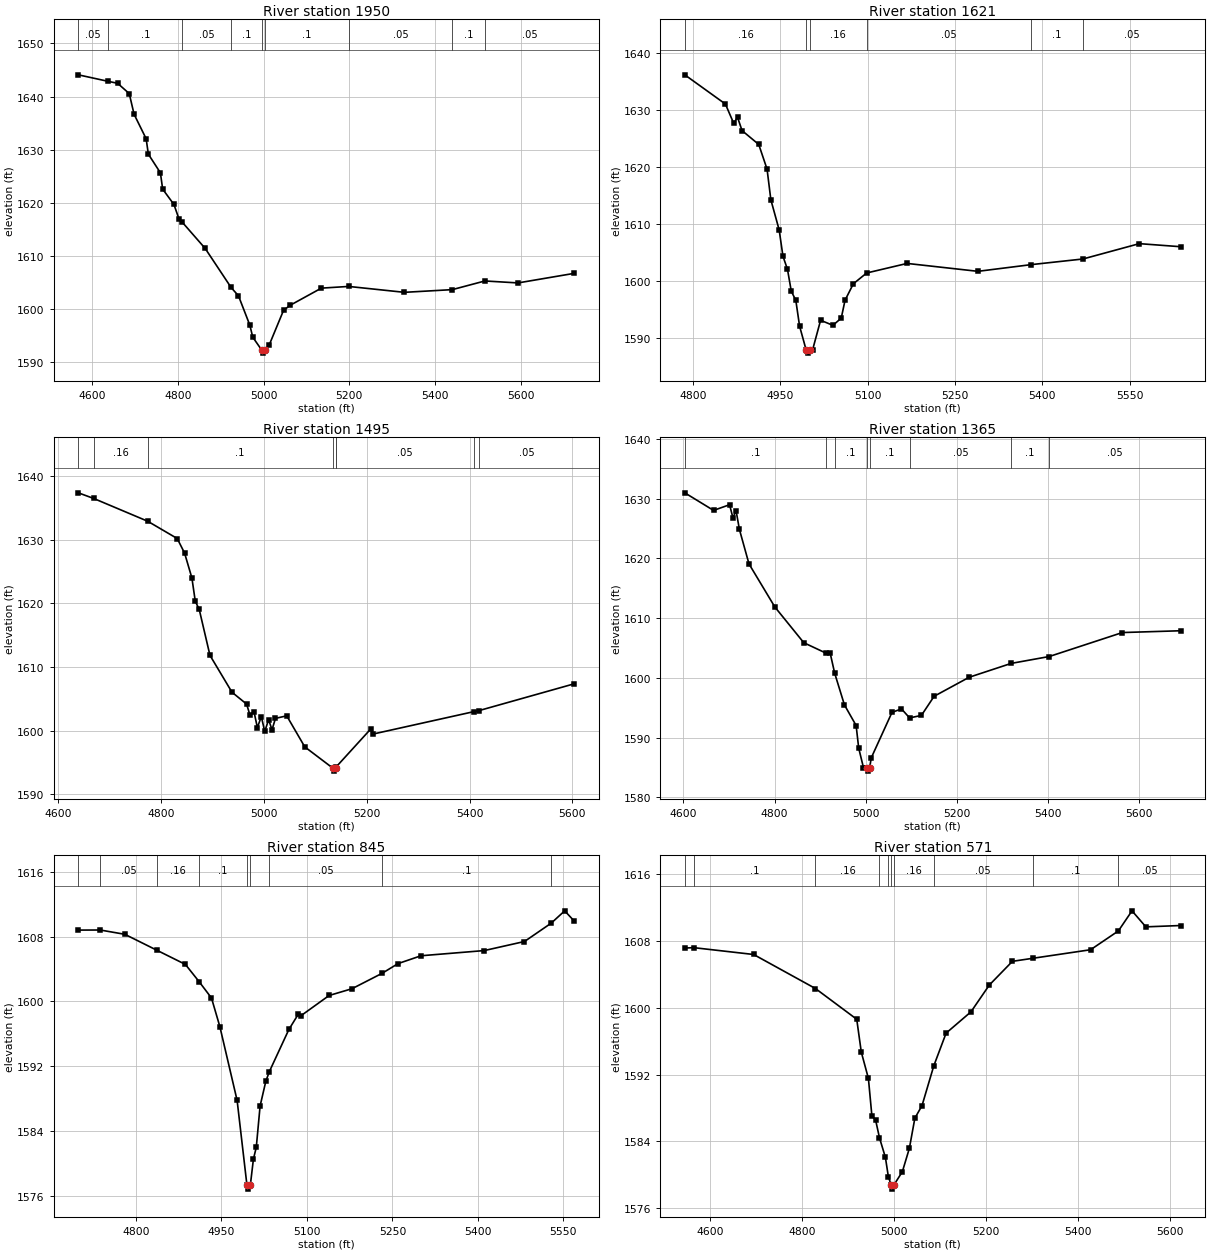
Type RM Length L Ch R = 1,1950,329,329,329
BEGIN DESCRIPTION:
UNT 0020 IN HEWA 4.0
END DESCRIPTION:
XS GIS Cut Line= 2
      2757869.08     10049257.69      2757541.62     10048147.99
#Sta/Elev= 30
  4567.7 1644.08  4637.5 1642.85  4659.3 1642.49  4686.5 1640.55  4697.8 1636.66
  4725.9 1632.06  4731.1 1629.15  4759.2 1625.64  4764.5 1622.57  4790.8 1619.68
  4803.0 1616.86  4810.7 1616.30  4863.8 1611.40  4924.2 1604.06  4941.4 1602.49
  4968.0 1596.95  4974.7 1594.71  4996.3 1592.21  4999.1 1591.71  5002.3 1592.21
  5013.2 1593.26  5046.5 1599.75  5061.9 1600.71  5134.8 1603.94  5198.4 1604.26
  5328.6 1603.15  5440.4 1603.66  5516.4 1605.29  5593.6 1604.92  5724.7 1606.72
#Mann=9,-1,0
  4567.7    0.05       0  4637.5     0.1       0  4810.7    0.05       0
  4924.2     0.1       0  4996.3    0.07       0  5002.3     0.1       0
  5198.4    0.05       0  5440.4     0.1       0  5516.4    0.05       0
Bank Sta=4996.3,5002.3
Exp/Cntr=0.3,0.1

Type RM Length L Ch R = 1,1621,126,126,126
BEGIN DESCRIPTION:
Mapping XS 95ad9ff9
END DESCRIPTION:
XS GIS Cut Line= 4
      2758117.85     10048792.77      2757807.55     10048421.72
      2757657.81     10048371.80      2757590.54     10048172.17
#Sta/Elev= 30
  4785.6 1636.22  4855.4 1631.08  4869.7 1627.68  4876.2 1628.76  4884.0 1626.41
  4912.7 1623.97  4927.0 1619.62  4933.5 1614.24  4947.8 1608.93  4954.3 1604.31
  4962.1 1601.99  4968.6 1598.16  4976.4 1596.55  4982.9 1592.00  4994.3 1587.76
  4997.0 1587.26  5000.3 1587.76  5005.1 1587.78  5019.0 1593.04  5040.2 1592.15
  5054.5 1593.42  5061.0 1596.56  5075.3 1599.46  5098.2 1601.36  5167.7 1603.04
  5289.4 1601.65  5381.1 1602.83  5469.8 1603.82  5566.8 1606.52  5637.8 1605.98
#Mann=6,-1,0
  4785.6    0.16       0  4994.3    0.07       0  5000.3    0.16       0
  5098.2    0.05       0  5381.1     0.1       0  5469.8    0.05       0
Bank Sta=4994.3,5000.3
Exp/Cntr=0.3,0.1

Type RM Length L Ch R = 1,1495,130,130,130
BEGIN DESCRIPTION:
Mapping XS 02326578
END DESCRIPTION:
XS GIS Cut Line= 4
      2758278.44     10048794.95      2757929.08     10048386.99
      2757735.93     10048341.42      2757610.05     10048150.43
#Sta/Elev= 30
  4639.1 1637.36  4668.8 1636.48  4773.9 1632.90  4831.4 1630.18  4845.7 1627.90
  4860.0 1623.97  4866.5 1620.34  4874.2 1619.04  4895.1 1611.82  4937.9 1606.03
  4966.4 1604.16  4973.0 1602.40  4980.7 1602.99  4987.3 1600.47  4995.0 1602.21
  5001.6 1599.87  5009.2 1601.71  5015.8 1600.13  5022.5 1601.92  5044.4 1602.32
  5079.5 1597.44  5133.6 1594.13  5136.3 1593.63  5139.6 1594.13  5141.1 1594.34
  5207.4 1600.22  5212.5 1599.46  5407.9 1602.97  5417.4 1603.12  5603.4 1607.35
#Mann=8,-1,0
  4639.1     0.1       0  4668.8    0.16       0  4773.9     0.1       0
  5133.6    0.07       0  5139.6     0.1       0  5141.1    0.05       0
  5407.9     0.1       0  5417.4    0.05       0
Bank Sta=5133.6,5139.6
Exp/Cntr=0.3,0.1

Type RM Length L Ch R = 1,1365,520,520,520
BEGIN DESCRIPTION:
UNT 0020 IN HEWA 3.0
END DESCRIPTION:
XS GIS Cut Line= 4
      2758378.70     10048652.42      2758173.94     10048429.46
      2757791.71     10048315.70      2757518.70     10048042.70
#Sta/Elev= 30
  4603.1 1630.96  4666.2 1628.02  4701.3 1628.97  4708.7 1626.77  4715.5 1627.99
  4722.9 1624.84  4743.9 1619.07  4800.6 1611.87  4864.1 1605.89  4913.3 1604.13
  4922.0 1604.14  4931.9 1600.78  4953.3 1595.48  4978.9 1592.04  4984.6 1588.24
  4995.0 1585.00  5002.4 1584.91  5005.2 1584.41  5008.4 1584.91  5012.1 1586.63
  5057.6 1594.24  5078.4 1594.82  5096.2 1593.31  5122.1 1593.73  5150.0 1596.93
  5226.8 1600.11  5319.1 1602.43  5402.5 1603.58  5562.9 1607.59  5690.7 1607.89
#Mann=8,-1,0
  4603.1     0.1       0  4913.3    0.16       0  4931.9     0.1       0
  5002.4    0.07       0  5008.4     0.1       0  5096.2    0.05       0
  5319.1     0.1       0  5402.5    0.05       0
Bank Sta=5002.4,5008.4
Exp/Cntr=0.3,0.1

Type RM Length L Ch R = 1,845,274,274,274
BEGIN DESCRIPTION:
UNT 0020 IN HEWA 2.0
END DESCRIPTION:
XS GIS Cut Line= 2
      2758464.76     10047939.34      2757602.03     10047825.57
#Sta/Elev= 30
  4698.8 1608.82  4737.2 1608.83  4780.4 1608.30  4836.1 1606.35  4886.7 1604.58
  4911.1 1602.42  4932.5 1600.43  4947.2 1596.89  4977.5 1587.77  4994.7 1577.32
  4997.4 1576.82  5000.7 1577.32  5006.1 1580.54  5011.1 1581.98  5017.8 1587.09
  5027.9 1590.16  5034.0 1591.33  5068.3 1596.54  5084.6 1598.40  5089.7 1598.25
  5138.9 1600.74  5179.2 1601.58  5231.9 1603.48  5259.9 1604.68  5300.3 1605.65
  5411.2 1606.29  5481.8 1607.41  5528.8 1609.68  5552.4 1611.20  5569.0 1609.94
#Mann=9,-1,0
  4698.8     0.1       0  4737.2    0.05       0  4836.1    0.16       0
  4911.1     0.1       0  4994.7    0.07       0  5000.7     0.1       0
  5034.0    0.05       0  5231.9     0.1       0  5528.8    0.05       0
Bank Sta=4994.7,5000.7
Exp/Cntr=0.3,0.1

Type RM Length L Ch R = 1,571,366,366,366
BEGIN DESCRIPTION:
Mapping XS 87108b78
END DESCRIPTION:
XS GIS Cut Line= 4
      2758556.55     10047653.83      2758186.74     10047596.54
      2758004.45     10047705.92      2757512.84     10047679.91
#Sta/Elev= 30
  4544.4 1607.17  4563.5 1607.22  4694.2 1606.40  4828.8 1602.32  4918.6 1598.64
  4928.5 1594.71  4944.0 1591.55  4951.6 1587.05  4959.6 1586.58  4968.1 1584.44
  4981.0 1582.09  4987.4 1579.79  4993.5 1578.79  4996.3 1578.29  4999.5 1578.79
  5017.9 1580.38  5033.2 1583.19  5045.1 1586.79  5060.7 1588.30  5086.3 1593.06
  5113.1 1596.98  5167.2 1599.53  5207.3 1602.75  5257.4 1605.58  5301.3 1605.94
  5427.6 1606.97  5488.0 1609.22  5517.7 1611.63  5547.8 1609.71  5623.5 1609.87
#Mann=10,-1,0
  4544.4    0.05       0  4563.5     0.1       0  4828.8    0.16       0
  4968.1     0.1       0  4987.4    0.16       0  4993.5    0.07       0
  4999.5    0.16       0  5086.3    0.05       0  5301.3     0.1       0
  5488.0    0.05       0
Bank Sta=4993.5,4999.5
Exp/Cntr=0.3,0.1