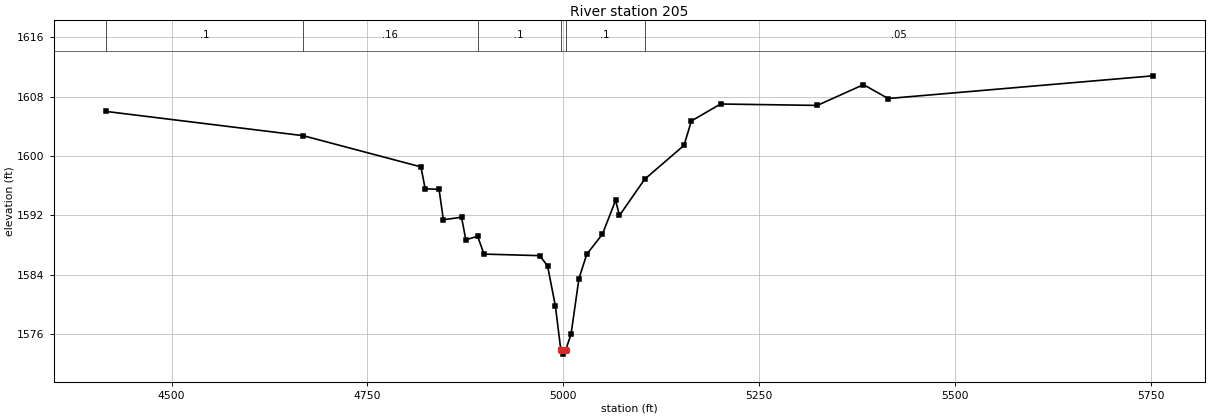
HEC-RAS study UNT 0020 IN HEWA.prj: UNT 0020 IN HEWA Base Level Engineering

--- UNT 0020 IN HEWA.g01 (geometry) --- (continued)

Type RM Length L Ch R = 1,205,0,0,0
BEGIN DESCRIPTION:
UNT 0020 IN HEWA 1.0
END DESCRIPTION:
XS GIS Cut Line= 4
      2758507.08     10047544.47      2758035.70     10047333.52
      2757814.35     10047325.71      2757296.08     10047625.21
#Sta/Elev= 30
  4416.2 1606.03  4667.9 1602.76  4818.3 1598.55  4823.7 1595.59  4841.4 1595.53
  4846.9 1591.42  4870.1 1591.76  4875.6 1588.71  4890.6 1589.20  4898.8 1586.79
  4969.9 1586.58  4979.9 1585.20  4989.9 1579.76  4996.9 1573.80  4999.7 1573.30
  5002.9 1573.80  5009.9 1576.01  5019.9 1583.45  5029.9 1586.77  5049.9 1589.47
  5066.7 1594.03  5071.7 1592.00  5103.8 1596.88  5154.1 1601.46  5163.4 1604.74
  5200.7 1607.03  5324.2 1606.84  5383.1 1609.64  5414.6 1607.77  5752.7 1610.83
#Mann=6,-1,0
  4416.2     0.1       0  4667.9    0.16       0  4890.6     0.1       0
  4996.9    0.07       0  5002.9     0.1       0  5103.8    0.05       0
Bank Sta=4996.9,5002.9
Exp/Cntr=0.3,0.1

Chan Stop Cuts=-1