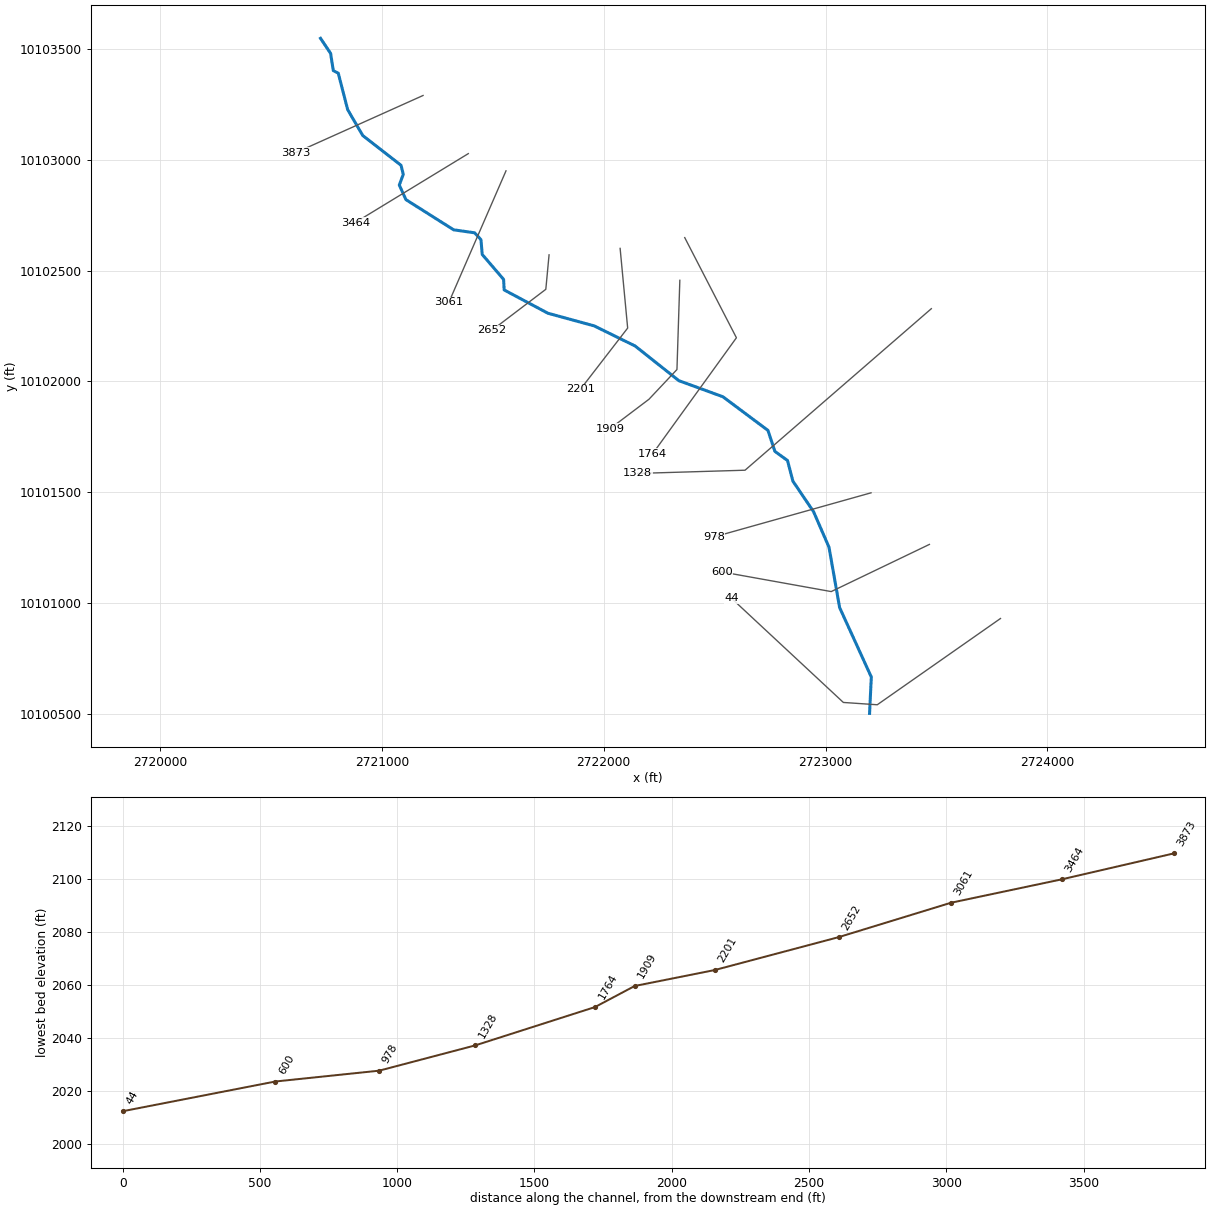
--- UNT 0025 IN HEWA.prj (project) ---

Proj Title=UNT 0025 IN HEWA Base Level Engineering
Current Plan=p01
Default Exp/Contr=0.3,0.1
English Units
Geom File=g01
Flow File=f01
Plan File=p01
BEGIN DESCRIPTION:
UNT 0025 IN HEWA
END DESCRIPTION:

--- UNT 0025 IN HEWA.p01 (plan) ---

Plan Title=Multiple Run
Short Identifier=Multiple
Geom File=g01
Flow File=f01
Subcritical Flow
K Sum by GR= 0
Std Step Tol= 0.01
Critical Tol= 0.01
Num of Std Step Trials= 20
Max Error Tol= 0.3
Flow Tol Ratio= 0.001
Split Flow NTrial= 30
Split Flow Tol= 0.02
Split Flow Ratio= 0.02
Log Output Level= 0
Friction Slope Method= 1
Unsteady Friction Slope Method= 2
Unsteady Bridges Friction Slope Method= 1
Parabolic Critical Depth
Global Vel Dist=  1 , 1 , 1
Global Log Level= 0
CheckData=True
Encroach Param= -1, 0, 0, 0
BEGIN DESCRIPTION:
Multiple Run
END DESCRIPTION:

--- UNT 0025 IN HEWA.f01 (steady flow) ---

Flow Title=Multiple
Number of Profiles=7
Profile Names=10-year,25-year,50-year,1pct_min,100-year,1pct_plu,500-year
River Rch & RM= UNT 0025 IN HEWA,Reach-1,3873
     416     580     718     653     883    1194    1338
Boundary for River Rch & Prof#=UNT 0025 IN HEWA,Reach-1,1
Up Type=0
Dn Type=3
Dn Slope=0.005
Boundary for River Rch & Prof#=UNT 0025 IN HEWA,Reach-1,2
Up Type=0
Dn Type=3
Dn Slope=0.005
Boundary for River Rch & Prof#=UNT 0025 IN HEWA,Reach-1,3
Up Type=0
Dn Type=3
Dn Slope=0.005
Boundary for River Rch & Prof#=UNT 0025 IN HEWA,Reach-1,4
Up Type=0
Dn Type=3
Dn Slope=0.005
Boundary for River Rch & Prof#=UNT 0025 IN HEWA,Reach-1,5
Up Type=0
Dn Type=3
Dn Slope=0.005
Boundary for River Rch & Prof#=UNT 0025 IN HEWA,Reach-1,6
Up Type=0
Dn Type=3
Dn Slope=0.005
Boundary for River Rch & Prof#=UNT 0025 IN HEWA,Reach-1,7
Up Type=0
Dn Type=3
Dn Slope=0.005

--- UNT 0025 IN HEWA.g01 (geometry) ---

Geom Title=Existing Conditions

River Reach=UNT 0025 IN HEWA,Reach-1
Reach XY= 30
      2720723.26     10103547.05      2720768.61     10103479.25
      2720780.71     10103401.47      2720803.10     10103390.01
      2720845.60     10103225.53      2720913.69     10103108.76
      2721086.17     10102974.64      2721096.33     10102933.84
      2721078.29     10102885.64      2721108.14     10102819.87
      2721323.41     10102683.76      2721418.09     10102670.22
      2721446.56     10102639.31      2721452.12     10102572.65
      2721548.49     10102460.30      2721551.09     10102412.72
      2721748.29     10102307.71      2721957.18     10102250.60
      2722141.60     10102159.96      2722338.47     10102003.75
      2722537.38     10101931.11      2722740.39     10101779.43
      2722771.63     10101684.99      2722828.47     10101643.73
      2722852.75     10101550.79      2722946.09     10101412.74
      2723015.62     10101252.67      2723063.41     10100980.89
      2723206.34     10100667.71      2723198.47     10100503.73

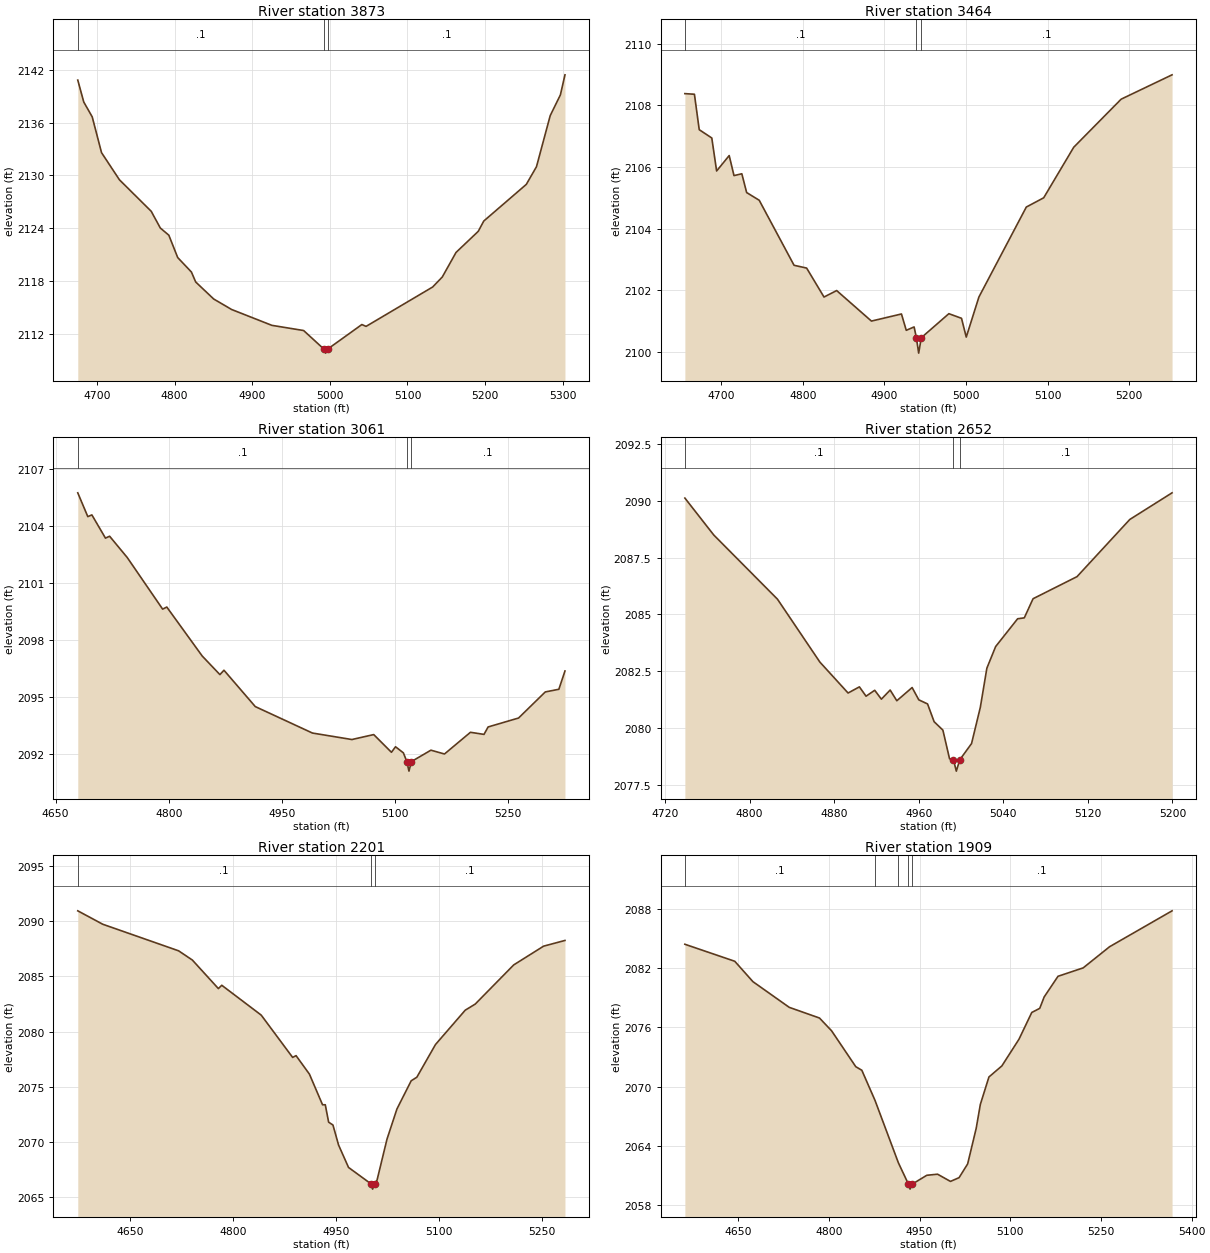
Type RM Length L Ch R = 1,3873,409,409,409
BEGIN DESCRIPTION:
UNT 0025 IN HEWA 9.0
END DESCRIPTION:
XS GIS Cut Line= 2
      2721185.48     10103289.41      2720613.07     10103032.31
#Sta/Elev= 30
  4675.4 2140.83  4683.1 2138.34  4694.0 2136.65  4706.0 2132.58  4729.1 2129.49
  4770.0 2125.91  4781.7 2124.01  4792.7 2123.19  4804.1 2120.65  4821.8 2119.00
  4827.3 2117.87  4850.4 2115.94  4873.6 2114.74  4925.4 2112.94  4966.3 2112.35
  4991.9 2110.28  4994.7 2109.78  4997.9 2110.28  5041.3 2113.03  5046.7 2112.82
  5132.5 2117.30  5144.9 2118.44  5162.6 2121.23  5191.2 2123.63  5198.3 2124.80
  5253.1 2128.97  5266.2 2130.98  5283.9 2136.79  5297.0 2139.15  5302.9 2141.43
#Mann=3,-1,0
  4675.4     0.1       0  4991.9    0.07       0  4997.9     0.1       0
Bank Sta=4991.9,4997.9
Exp/Cntr=0.3,0.1

Type RM Length L Ch R = 1,3464,403,403,403
BEGIN DESCRIPTION:
UNT 0025 IN HEWA 8.0
END DESCRIPTION:
XS GIS Cut Line= 2
      2721389.43     10103027.29      2720879.66     10102716.57
#Sta/Elev= 30
  4655.6 2108.38  4667.3 2108.36  4673.2 2107.21  4688.6 2106.94  4694.5 2105.87
  4709.9 2106.37  4715.8 2105.72  4725.4 2105.78  4731.3 2105.17  4746.7 2104.92
  4789.4 2102.81  4804.8 2102.72  4826.1 2101.78  4841.6 2101.99  4884.2 2101.00
  4921.0 2101.23  4926.9 2100.70  4936.5 2100.81  4939.3 2100.46  4942.1 2099.96
  4945.3 2100.46  4979.1 2101.24  4994.6 2101.09  5000.4 2100.48  5015.9 2101.78
  5074.0 2104.70  5095.3 2105.00  5132.1 2106.64  5190.2 2108.20  5252.6 2108.99
#Mann=3,-1,0
  4655.6     0.1       0  4939.3    0.07       0  4945.3     0.1       0
Bank Sta=4939.3,4945.3
Exp/Cntr=0.3,0.1

Type RM Length L Ch R = 1,3061,409,409,409
BEGIN DESCRIPTION:
UNT 0025 IN HEWA 7.0
END DESCRIPTION:
XS GIS Cut Line= 2
      2721559.33     10102949.62      2721302.01     10102357.30
#Sta/Elev= 30
  4679.4 2105.74  4692.7 2104.49  4698.1 2104.58  4716.1 2103.36  4721.6 2103.46
  4745.0 2102.34  4791.9 2099.63  4797.4 2099.74  4844.3 2097.17  4867.8 2096.19
  4873.2 2096.42  4914.7 2094.51  4990.5 2093.12  5042.8 2092.78  5071.7 2093.04
  5095.2 2092.11  5100.6 2092.40  5111.0 2092.08  5115.6 2091.62  5118.4 2091.12
  5121.6 2091.62  5147.5 2092.22  5165.5 2092.02  5199.9 2093.16  5217.9 2093.05
  5223.3 2093.44  5263.7 2093.91  5299.1 2095.28  5317.1 2095.42  5325.2 2096.38
#Mann=3,-1,0
  4679.4     0.1       0  5115.6    0.07       0  5121.6     0.1       0
Bank Sta=5115.6,5121.6
Exp/Cntr=0.3,0.1

Type RM Length L Ch R = 1,2652,451,451,451
BEGIN DESCRIPTION:
UNT 0025 IN HEWA 6.0
END DESCRIPTION:
XS GIS Cut Line= 3
      2721753.50     10102570.91      2721738.93     10102415.58
      2721496.19     10102231.10
#Sta/Elev= 30
  4738.7 2090.11  4766.0 2088.49  4826.3 2085.67  4866.4 2082.91  4893.1 2081.55
  4903.8 2081.82  4910.1 2081.41  4918.3 2081.67  4924.6 2081.28  4932.9 2081.68
  4939.2 2081.21  4953.7 2081.79  4960.0 2081.25  4968.3 2081.07  4974.5 2080.29
  4982.8 2079.92  4989.1 2078.66  4992.8 2078.62  4995.5 2078.12  4998.8 2078.62
  5009.9 2079.33  5018.2 2080.92  5024.4 2082.64  5032.7 2083.59  5053.5 2084.81
  5059.8 2084.85  5068.1 2085.69  5109.7 2086.66  5159.6 2089.17  5199.6 2090.34
#Mann=3,-1,0
  4738.7     0.1       0  4992.8    0.07       0  4998.8     0.1       0
Bank Sta=4992.8,4998.8
Exp/Cntr=0.3,0.1

Type RM Length L Ch R = 1,2201,292,292,292
BEGIN DESCRIPTION:
UNT 0025 IN HEWA 5.0
END DESCRIPTION:
XS GIS Cut Line= 3
      2722073.90     10102600.07      2722107.89     10102240.82
      2721894.30     10101964.12
#Sta/Elev= 30
  4573.5 2090.96  4610.0 2089.74  4720.5 2087.33  4740.6 2086.49  4778.5 2083.90
  4783.5 2084.20  4841.0 2081.49  4886.8 2077.65  4891.8 2077.81  4911.3 2076.13
  4930.4 2073.35  4934.4 2073.35  4939.3 2071.77  4945.6 2071.51  4953.8 2069.69
  4968.3 2067.66  5000.6 2066.19  5003.4 2065.69  5006.6 2066.19  5009.9 2066.51
  5024.4 2070.23  5038.9 2072.97  5059.7 2075.53  5067.9 2075.85  5095.1 2078.82
  5138.5 2081.94  5153.0 2082.49  5209.2 2086.05  5252.7 2087.75  5283.9 2088.27
#Mann=3,-1,0
  4573.5     0.1       0  5000.6    0.07       0  5006.6     0.1       0
Bank Sta=5000.6,5006.6
Exp/Cntr=0.3,0.1

Type RM Length L Ch R = 1,1909,145,145,145
BEGIN DESCRIPTION:
Mapping XS c1644965
END DESCRIPTION:
XS GIS Cut Line= 4
      2722343.11     10102456.22      2722330.09     10102053.88
      2722203.79     10101919.77      2722029.19     10101787.85
#Sta/Elev= 30
  4562.0 2084.41  4644.5 2082.69  4674.5 2080.63  4734.6 2078.03  4784.6 2076.95
  4804.6 2075.66  4844.6 2072.03  4854.6 2071.67  4876.5 2068.61  4915.0 2062.32
  4931.7 2060.15  4934.4 2059.65  4937.7 2060.15  4962.1 2061.05  4979.8 2061.16
  5001.2 2060.43  5015.4 2060.81  5029.6 2062.20  5043.7 2065.79  5050.6 2068.22
  5064.8 2070.99  5086.2 2072.11  5114.5 2074.81  5135.6 2077.51  5148.8 2077.93
  5156.1 2079.08  5179.0 2081.17  5220.6 2082.02  5264.3 2084.16  5367.6 2087.79
#Mann=5,-1,0
  4562.0     0.1       0  4876.5    0.16       0  4915.0     0.1       0
  4931.7    0.07       0  4937.7     0.1       0
Bank Sta=4931.7,4937.7
Exp/Cntr=0.3,0.1

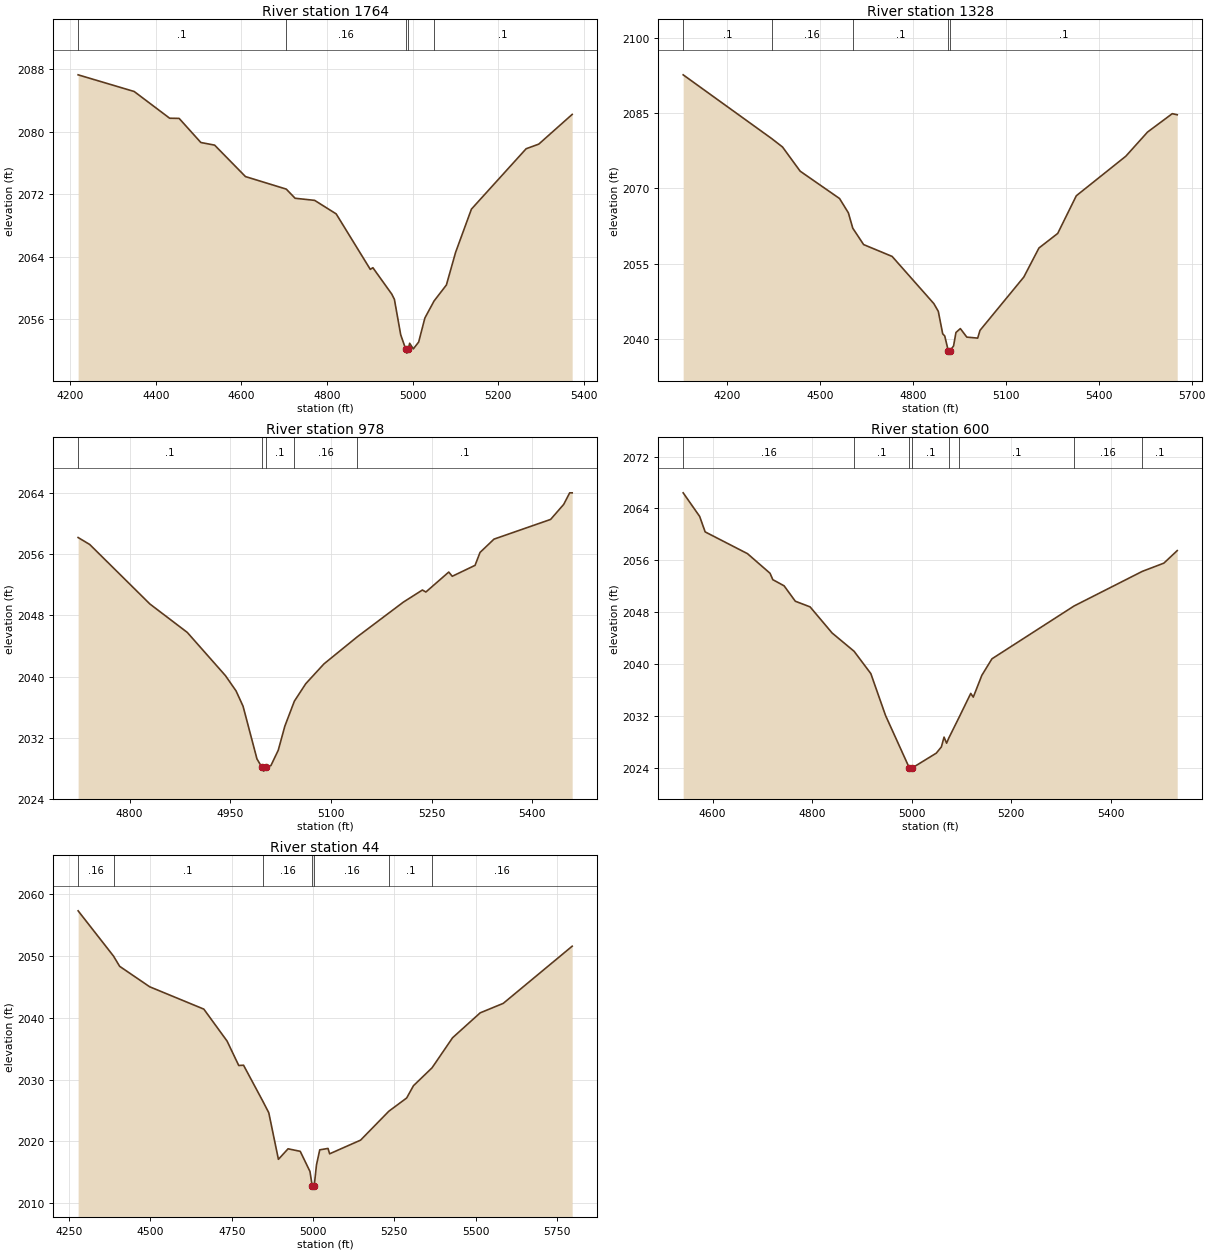
Type RM Length L Ch R = 1,1764,436,436,436
BEGIN DESCRIPTION:
UNT 0025 IN HEWA 4.0
END DESCRIPTION:
XS GIS Cut Line= 3
      2722365.18     10102648.61      2722598.21     10102197.13
      2722219.55     10101672.84
#Sta/Elev= 30
  4218.2 2087.25  4349.2 2085.12  4432.2 2081.70  4454.3 2081.68  4505.0 2078.60
  4537.3 2078.26  4609.4 2074.24  4704.7 2072.64  4725.4 2071.47  4771.1 2071.20
  4821.4 2069.47  4901.1 2062.38  4907.2 2062.59  4951.4 2059.21  4957.5 2058.54
  4972.2 2054.02  4984.0 2052.17  4986.7 2051.67  4990.0 2052.17  4993.1 2052.93
  5001.7 2052.21  5014.2 2053.09  5028.7 2056.16  5050.1 2058.33  5079.0 2060.38
  5100.5 2064.55  5137.5 2070.08  5265.4 2077.80  5294.9 2078.39  5373.0 2082.19
#Mann=5,-1,0
  4218.2     0.1       0  4704.7    0.16       0  4984.0    0.07       0
  4990.0    0.16       0  5050.1     0.1       0
Bank Sta=4984,4990
Exp/Cntr=0.3,0.1

Type RM Length L Ch R = 1,1328,350,350,350
BEGIN DESCRIPTION:
UNT 0025 IN HEWA 3.0
END DESCRIPTION:
XS GIS Cut Line= 3
      2723476.93     10102328.23      2722637.04     10101600.00
      2722152.49     10101585.47
#Sta/Elev= 30
  4057.1 2092.65  4343.2 2079.94  4378.1 2078.27  4435.1 2073.45  4562.4 2068.00
  4590.9 2065.15  4605.2 2062.08  4640.2 2058.82  4732.3 2056.46  4867.2 2047.05
  4881.5 2045.51  4895.7 2041.04  4902.3 2040.61  4913.6 2037.69  4916.3 2037.19
  4919.6 2037.69  4930.8 2038.62  4938.5 2041.30  4952.7 2042.08  4973.6 2040.38
  5008.7 2040.18  5016.3 2041.73  5157.8 2052.35  5206.7 2058.14  5267.3 2061.04
  5327.4 2068.55  5487.4 2076.43  5557.5 2081.24  5637.5 2084.91  5653.5 2084.69
#Mann=5,-1,0
  4057.1     0.1       0  4343.2    0.16       0  4605.2     0.1       0
  4913.6    0.07       0  4919.6     0.1       0
Bank Sta=4913.6,4919.6
Exp/Cntr=0.3,0.1

Type RM Length L Ch R = 1,978,378,378,378
BEGIN DESCRIPTION:
UNT 0025 IN HEWA 2.0
END DESCRIPTION:
XS GIS Cut Line= 2
      2723205.08     10101498.07      2722496.30     10101299.03
#Sta/Elev= 30
  4723.2 2058.20  4740.5 2057.29  4830.2 2049.50  4885.9 2045.78  4942.8 2040.12
  4958.6 2038.12  4969.0 2036.12  4989.7 2029.23  4997.1 2028.13  4999.9 2027.63
  5003.1 2028.13  5010.5 2028.36  5021.4 2030.36  5031.3 2033.53  5045.4 2036.78
  5062.4 2039.07  5089.5 2041.66  5139.2 2045.21  5207.9 2049.75  5236.2 2051.33
  5241.4 2051.07  5275.5 2053.68  5280.7 2053.13  5314.7 2054.56  5322.1 2056.25
  5342.9 2057.99  5427.3 2060.57  5446.8 2062.54  5455.7 2064.05  5459.4 2064.05
#Mann=5,-1,0
  4723.2     0.1       0  4997.1    0.07       0  5003.1     0.1       0
  5045.4    0.16       0  5139.2     0.1       0
Bank Sta=4997.1,5003.1
Exp/Cntr=0.3,0.1

Type RM Length L Ch R = 1,600,556,556,556
BEGIN DESCRIPTION:
Mapping XS a02b90d2
END DESCRIPTION:
XS GIS Cut Line= 3
      2723468.28     10101265.49      2723025.60     10101052.84
      2722532.12     10101141.58
#Sta/Elev= 30
  4540.8 2066.41  4573.9 2062.78  4585.0 2060.39  4670.0 2057.04  4715.3 2054.02
  4720.9 2053.03  4743.5 2052.09  4766.1 2049.71  4795.8 2048.84  4840.1 2044.81
  4884.2 2042.00  4917.8 2038.56  4947.3 2032.12  4995.1 2024.04  4997.8 2023.54
  5001.1 2024.04  5049.3 2026.31  5059.5 2027.27  5064.9 2028.78  5070.0 2027.84
  5074.3 2028.62  5095.6 2031.91  5118.5 2035.51  5123.6 2034.94  5140.8 2038.30
  5161.1 2040.84  5326.1 2048.98  5463.1 2054.31  5506.5 2055.58  5533.3 2057.51
#Mann=8,-1,0
  4540.8    0.16       0  4884.2     0.1       0  4995.1    0.07       0
  5001.1     0.1       0  5074.3    0.16       0  5095.6     0.1       0
  5326.1    0.16       0  5463.1     0.1       0
Bank Sta=4995.1,5001.1
Exp/Cntr=0.3,0.1

Type RM Length L Ch R = 1,44,0,0,0
BEGIN DESCRIPTION:
UNT 0025 IN HEWA 1.0
END DESCRIPTION:
XS GIS Cut Line= 4
      2723788.70     10100931.48      2723233.11     10100542.57
      2723080.33     10100552.99      2722576.87     10101021.73
#Sta/Elev= 30
  4277.6 2057.29  4386.5 2049.97  4405.3 2048.32  4497.7 2045.01  4664.2 2041.40
  4735.7 2036.23  4771.5 2032.29  4786.3 2032.33  4844.8 2026.59  4863.9 2024.65
  4893.5 2017.12  4923.2 2018.82  4960.6 2018.41  4990.5 2015.16  4997.5 2012.80
  5000.3 2012.30  5003.5 2012.80  5010.6 2016.23  5020.6 2018.65  5046.0 2018.88
  5051.0 2018.01  5146.2 2020.22  5233.2 2024.90  5287.8 2027.03  5308.8 2029.02
  5365.9 2031.91  5429.0 2036.77  5514.0 2040.80  5584.9 2042.33  5796.8 2051.57
#Mann=7,-1,0
  4277.6    0.16       0  4386.5     0.1       0  4844.8    0.16       0
  4997.5    0.07       0  5003.5    0.16       0  5233.2     0.1       0
  5365.9    0.16       0
Bank Sta=4997.5,5003.5
Exp/Cntr=0.3,0.1

Chan Stop Cuts=-1