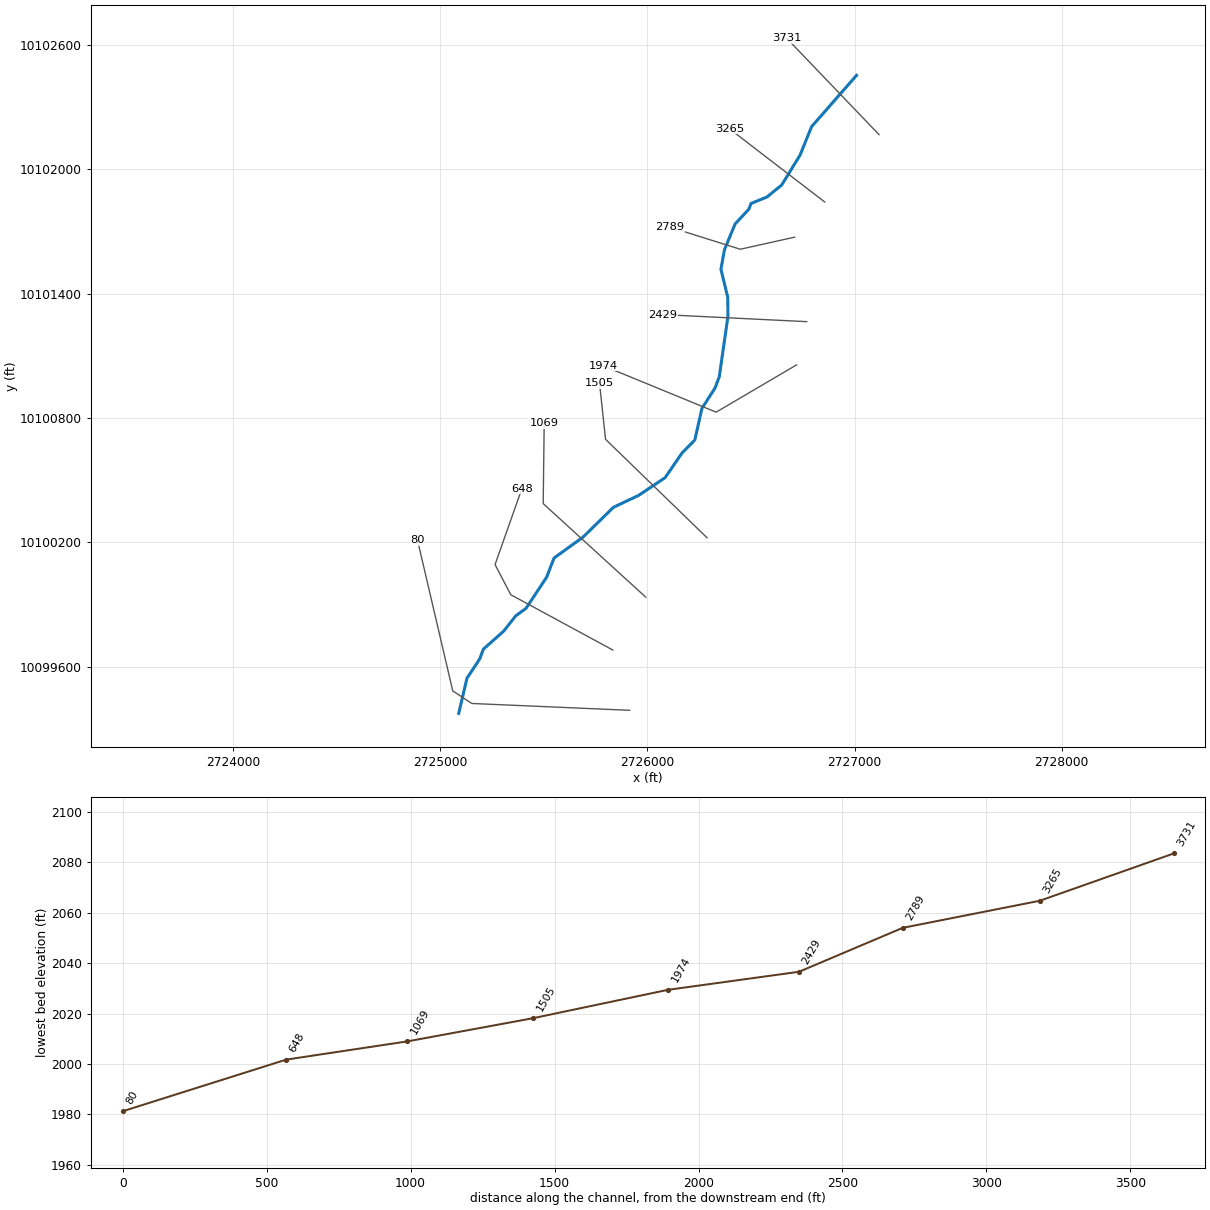
--- UNT 0026 IN HEWA.prj (project) ---

Proj Title=UNT 0026 IN HEWA Base Level Engineering
Current Plan=p01
Default Exp/Contr=0.3,0.1
English Units
Geom File=g01
Flow File=f01
Plan File=p01
BEGIN DESCRIPTION:
UNT 0026 IN HEWA
END DESCRIPTION:

--- UNT 0026 IN HEWA.p01 (plan) ---

Plan Title=Multiple Run
Short Identifier=Multiple
Geom File=g01
Flow File=f01
Subcritical Flow
K Sum by GR= 0
Std Step Tol= 0.01
Critical Tol= 0.01
Num of Std Step Trials= 20
Max Error Tol= 0.3
Flow Tol Ratio= 0.001
Split Flow NTrial= 30
Split Flow Tol= 0.02
Split Flow Ratio= 0.02
Log Output Level= 0
Friction Slope Method= 1
Unsteady Friction Slope Method= 2
Unsteady Bridges Friction Slope Method= 1
Parabolic Critical Depth
Global Vel Dist=  1 , 1 , 1
Global Log Level= 0
CheckData=True
Encroach Param= -1, 0, 0, 0
BEGIN DESCRIPTION:
Multiple Run
END DESCRIPTION:

--- UNT 0026 IN HEWA.f01 (steady flow) ---

Flow Title=Multiple
Program Version=4.10
Number of Profiles= 7
Profile Names=10-year,25-year,50-year,1pct_min,100-year,1pct_plu,500-year
River Rch & RM=UNT 0026 IN HEWA,Reach-1         ,3731
     236     316     382     340     460     622     665
River Rch & RM=UNT 0026 IN HEWA,Reach-1         ,1505
     591     846    1066     985    1333    1802    2090
Boundary for River Rch & Prof#=UNT 0026 IN HEWA,Reach-1         , 1
Up Type= 0
Dn Type= 3
Dn Slope=0.038
Boundary for River Rch & Prof#=UNT 0026 IN HEWA,Reach-1         , 2
Up Type= 0
Dn Type= 3
Dn Slope=0.038
Boundary for River Rch & Prof#=UNT 0026 IN HEWA,Reach-1         , 3
Up Type= 0
Dn Type= 3
Dn Slope=0.038
Boundary for River Rch & Prof#=UNT 0026 IN HEWA,Reach-1         , 4
Up Type= 0
Dn Type= 3
Dn Slope=0.038
Boundary for River Rch & Prof#=UNT 0026 IN HEWA,Reach-1         , 5
Up Type= 0
Dn Type= 3
Dn Slope=0.038
Boundary for River Rch & Prof#=UNT 0026 IN HEWA,Reach-1         , 6
Up Type= 0
Dn Type= 3
Dn Slope=0.038
Boundary for River Rch & Prof#=UNT 0026 IN HEWA,Reach-1         , 7
Up Type= 0
Dn Type= 3
Dn Slope=0.038
DSS Import GetInterval= 0
DSS Import GetPeak= 0
DSS Import FillOption= 0

--- UNT 0026 IN HEWA.g01 (geometry) ---

Geom Title=Existing Conditions
Program Version=4.10

River Reach=UNT 0026 IN HEWA,Reach-1
Reach XY= 30
      2727008.99     10102453.95      2726792.19     10102206.48
      2726736.64     10102069.32      2726647.66     10101924.36
      2726576.48     10101866.63      2726499.51     10101835.42
      2726489.26      10101807.8       2726422.9     10101736.61
      2726371.54     10101612.44      2726354.48     10101517.51
      2726387.32      10101383.6       2726388.6     10101292.33
      2726346.56     10100999.14      2726326.11     10100944.71
        2726263.     10100846.57      2726228.47     10100693.73
      2726166.34     10100630.37      2726084.83     10100511.37
       2725957.4      10100426.3      2725835.64     10100368.69
      2725688.67     10100224.73       2725548.8     10100123.74
      2725513.16     10100031.22      2725413.55     10099880.94
      2725364.16     10099844.78      2725305.16     10099770.37
      2725207.27     10099683.36      2725190.55     10099637.67
      2725128.47     10099543.73      2725088.47     10099373.73

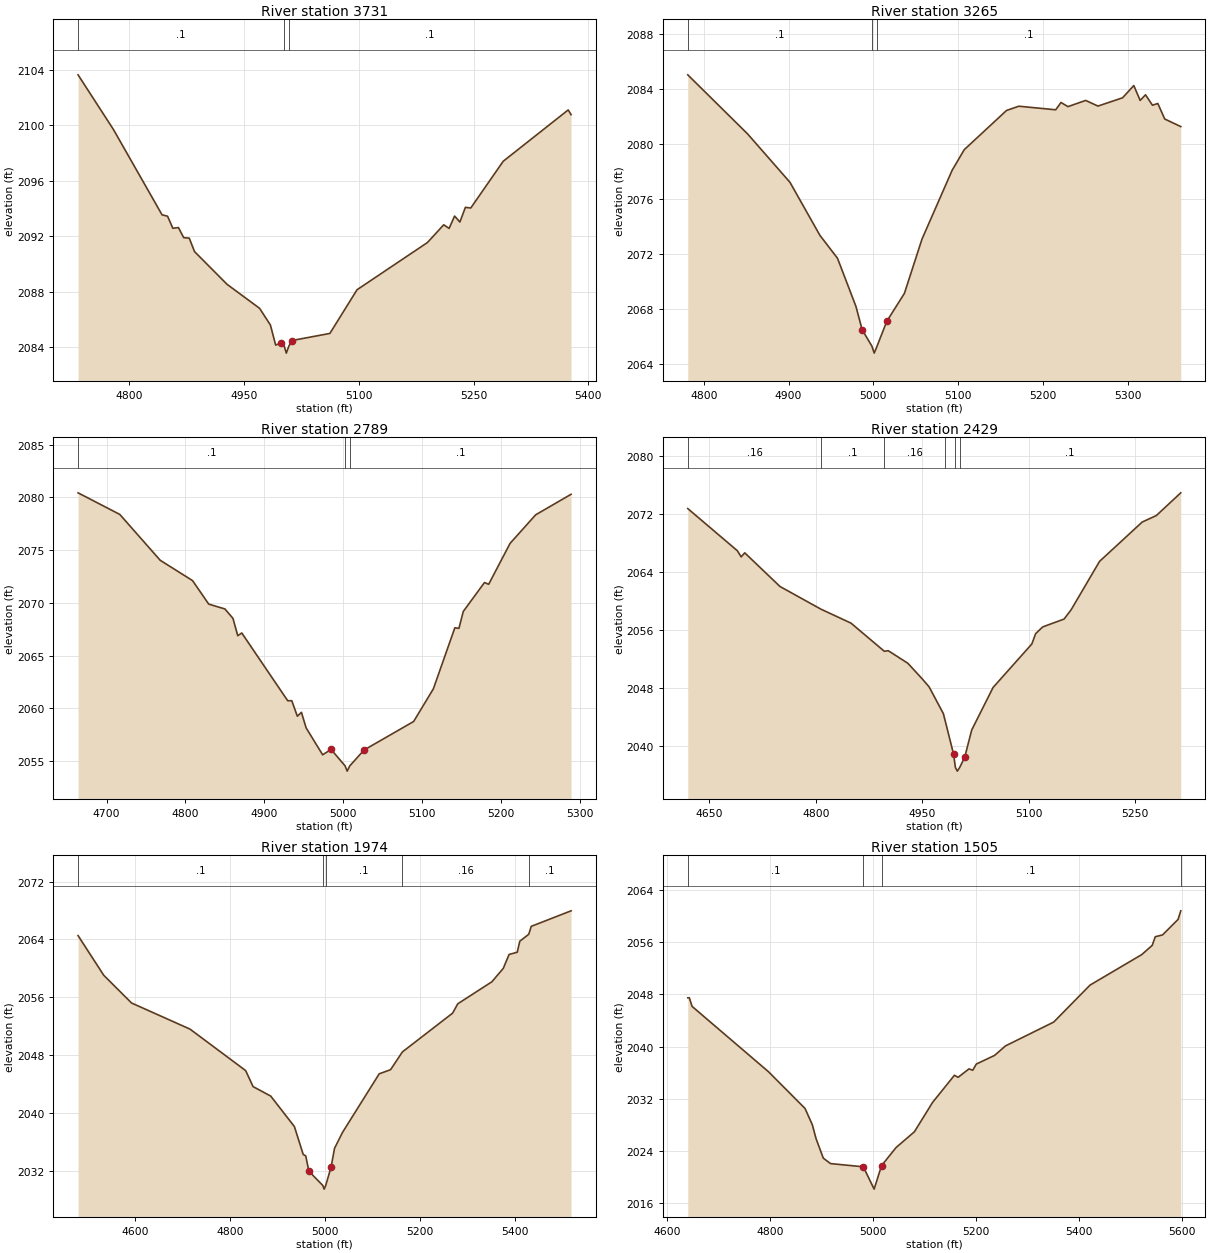
Type RM Length L Ch R = 1 ,3731    ,466,466,466
BEGIN DESCRIPTION:
UNT 0026 IN HEWA 8.0
END DESCRIPTION:
XS GIS Cut Line= 2
      2727117.88     10102167.99      2726672.36     10102632.88
#Sta/Elev= 30
  4733.4 2103.64  4779.6  2099.7  4843.1 2093.55  4850.3 2093.45  4857.2 2092.58
  4864.5 2092.63  4871.4  2091.9  4878.6 2091.87  4885.5  2090.9    4928 2088.54
  4970.5 2086.81  4984.6 2085.61  4991.5 2084.16  4998.8 2084.32  5002.7 2084.08
  5005.4 2083.58  5008.7 2084.08  5012.9 2084.49  5062.3    2085  5097.8 2088.15
  5189.7 2091.55    5211 2092.83    5218 2092.57  5225.2 2093.46  5232.1 2093.03
  5239.3 2094.09  5246.3 2094.04  5288.7 2097.41  5373.6 2101.11  5377.3 2100.77
#Mann= 3 ,-1 , 0
  4733.4      .1       0  5002.7     .07       0  5008.7      .1       0
Bank Sta=4998.8,5012.9
XS Rating Curve= 0 ,0
Exp/Cntr=0.3,0.1

Type RM Length L Ch R = 1 ,3265    ,476,476,476
BEGIN DESCRIPTION:
UNT 0026 IN HEWA 7.0
END DESCRIPTION:
XS GIS Cut Line= 2
      2726855.75     10101842.71       2726394.5     10102197.15
#Sta/Elev= 30
  4781.1    2085  4851.8  2080.7  4901.7 2077.19    4937 2073.34  4957.8 2071.67
  4979.5 2068.18  4986.8 2066.49  4998.4 2065.28  5001.1 2064.78  5004.4 2065.28
  5015.9 2067.09  5036.7 2069.12  5057.5 2073.07    5093 2078.06  5107.3 2079.56
  5157.2 2082.41  5171.7 2082.72  5215.2 2082.46  5221.5 2082.99  5229.7 2082.69
  5250.6 2083.14  5265.1 2082.73  5294.1 2083.33  5307.4 2084.22  5314.9 2083.14
  5321.2 2083.55  5329.4 2082.79  5335.7 2082.92  5343.9 2081.79  5362.8 2081.24
#Mann= 3 ,-1 , 0
  4781.1      .1       0  4998.4     .07       0  5004.4      .1       0
Bank Sta=4986.8,5015.9
XS Rating Curve= 0 ,0
Exp/Cntr=0.3,0.1

Type RM Length L Ch R = 1 ,2789    ,360,360,360
BEGIN DESCRIPTION:
UNT 0026 IN HEWA 6.0
END DESCRIPTION:
XS GIS Cut Line= 3
      2726710.12     10101672.83      2726447.93     10101614.57
       2726108.1     10101721.37
#Sta/Elev= 30
  4663.9 2080.44  4716.8 2078.39    4768 2074.04    4809 2072.11  4829.5 2069.88
    4850 2069.42  4860.2 2068.53  4866.3 2066.88  4871.4 2067.14  4929.6 2060.71
  4934.8 2060.71  4941.8 2059.24    4947 2059.61  4952.9 2058.14  4973.9 2055.58
  4984.6 2056.09  5002.3 2054.53    5005 2054.03  5008.3 2054.53  5026.3 2056.03
  5089.2 2058.74  5114.2 2061.84  5141.4 2067.63  5146.6 2067.58  5152.1 2069.18
    5179 2071.93  5184.3 2071.76  5211.4 2075.64  5243.8 2078.35  5288.7  2080.3
#Mann= 3 ,-1 , 0
  4663.9      .1       0  5002.3     .07       0  5008.3      .1       0
Bank Sta=4984.6,5026.3
XS Rating Curve= 0 ,0
Exp/Cntr=0.3,0.1

Type RM Length L Ch R = 1 ,2429    ,455,455,455
BEGIN DESCRIPTION:
UNT 0026 IN HEWA 5.0
END DESCRIPTION:
XS GIS Cut Line= 2
      2726768.31     10101265.04      2726074.14     10101299.02
#Sta/Elev= 30
  4619.4 2072.79  4689.3 2066.98  4694.7 2066.13  4699.7 2066.69  4749.4 2062.05
  4807.2 2058.92  4849.5    2057  4896.5 2053.12    4902  2053.2  4929.6 2051.47
  4949.6 2049.35  4959.6 2048.22  4979.7 2044.53    4982 2043.65 4994.09 2038.95
  4996.7  2037.1  4999.4  2036.6  5002.7  2037.1  5009.7 2038.48  5019.7 2042.27
  5049.8 2048.13  5104.4 2054.12  5109.8 2055.55  5119.8 2056.48  5149.9 2057.56
  5159.9 2058.85  5199.9 2065.51    5260 2070.93    5280 2071.83  5314.4 2074.96
#Mann= 6 ,-1 , 0
  4619.4     .16       0  4807.2      .1       0  4896.5     .16       0
    4982      .1       0  4996.7     .07       0  5002.7      .1       0
Bank Sta=4994.09,5009.7
XS Rating Curve= 0 ,0
Exp/Cntr=0.3,0.1

Type RM Length L Ch R = 1 ,1974    ,469,469,469
BEGIN DESCRIPTION:
UNT 0026 IN HEWA 4.0
END DESCRIPTION:
XS GIS Cut Line= 3
      2726719.81     10101056.29      2726331.42     10100828.12
      2725787.74     10101051.41
#Sta/Elev= 30
  4479.9 2064.53    4534 2059.04  4592.6  2055.2  4715.6 2051.59  4832.8 2045.85
  4848.5 2043.63  4885.6 2042.32  4935.5  2038.1    4954 2034.25  4959.4 2034.03
    4966 2031.92  4995.4 2029.94  4998.2 2029.44  5001.4 2029.94  5012.8 2032.51
    5020 2035.08  5036.8 2037.29  5114.1  2045.4    5138 2045.97  5162.9 2048.43
  5268.7  2053.8  5279.5 2055.09  5351.4 2058.14  5375.4    2060  5387.6 2061.92
  5404.8 2062.23  5410.2 2063.76    5429 2064.71  5434.2 2065.81  5518.1 2067.96
#Mann= 5 ,-1 , 0
  4479.9      .1       0  4995.4     .07       0  5001.4      .1       0
  5162.9     .16       0    5429      .1       0
Bank Sta=4966,5012.8
XS Rating Curve= 0 ,0
Exp/Cntr=0.3,0.1

Type RM Length L Ch R = 1 ,1505    ,436,436,436
BEGIN DESCRIPTION:
UNT 0026 IN HEWA 3.0
END DESCRIPTION:
XS GIS Cut Line= 3
      2726287.76     10100221.26      2725797.41     10100697.04
      2725768.29     10100968.85
#Sta/Elev= 30
  4640.8 2047.48  4643.8 2047.48  4649.2 2046.16  4797.6 2036.14  4868.3 2030.53
  4882.5 2028.03  4889.7 2025.91  4903.8 2022.91  4917.9 2022.08  4981.5 2021.59
  5002.4 2018.17  5016.8 2021.77  5045.1 2024.55  5080.5 2026.95  5115.8 2031.45
  5158.2 2035.61  5165.4  2035.3  5186.5 2036.59  5193.7 2036.38  5200.7 2037.33
  5236.1 2038.65  5257.3 2040.11  5350.9 2043.76  5421.3 2049.42  5521.8  2054.1
    5542 2055.51  5547.9 2056.83  5562.1 2057.11  5592.2 2059.49  5597.4  2060.8
#Mann= 4 ,-1 , 0
  4640.8      .1       0  4981.5     .05       0  5016.8      .1       0
  5597.4      .1       0
Bank Sta=4981.5,5016.8
XS Rating Curve= 0 ,0
Exp/Cntr=0.3,0.1

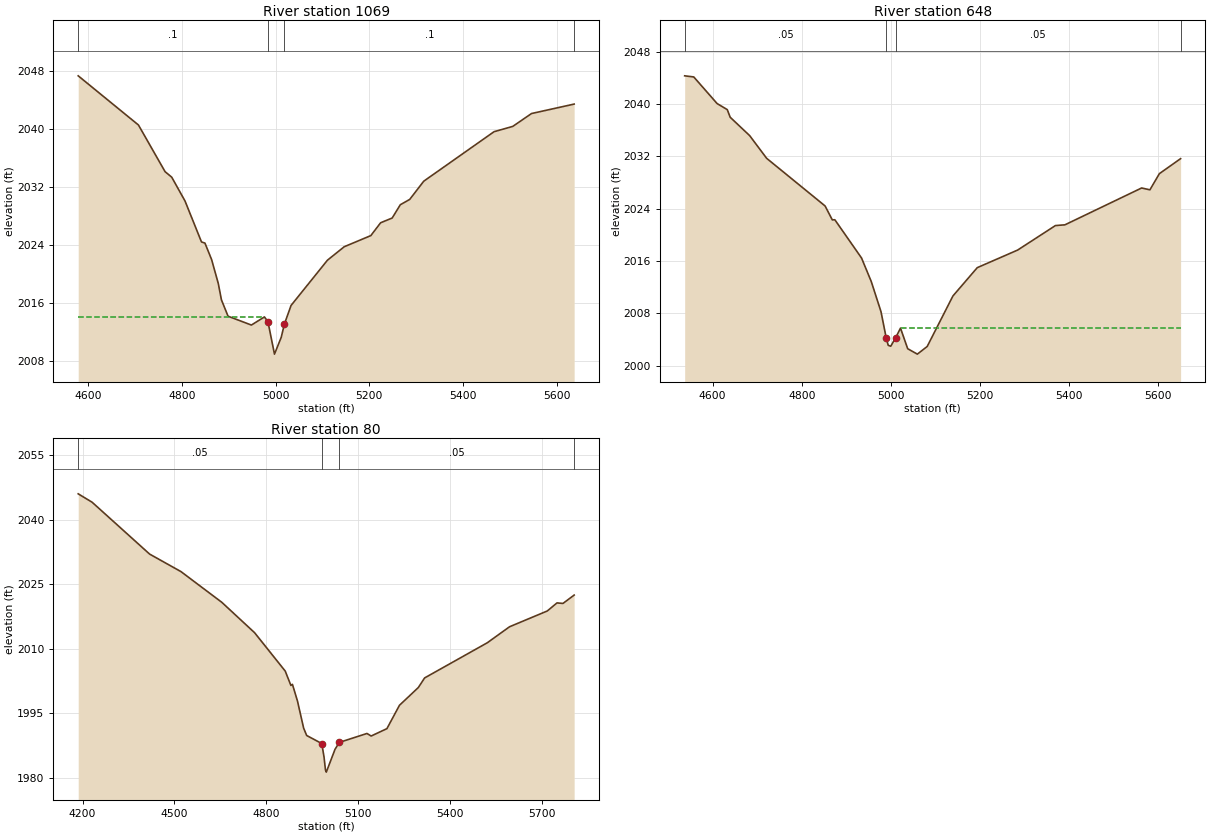
Type RM Length L Ch R = 1 ,1069    ,421,421,421
BEGIN DESCRIPTION:
UNT 0026 IN HEWA 2.0
END DESCRIPTION:
XS GIS Cut Line= 3
       2725991.6     10099934.86      2725496.42     10100386.35
      2725501.28     10100774.71
#Sta/Elev= 30
  4578.9 2047.28  4707.5 2040.51  4764.3 2034.09  4778.5 2033.33  4806.9 2030.05
    4842 2024.42  4849.4 2024.26  4863.6    2022  4877.8 2018.72  4884.6 2016.45
  4898.7  2014.2  4948.5 2012.98  4976.4  2014.1  4983.9 2013.43  4997.8 2008.98
  5012.2 2011.29    5019 2013.12  5033.2 2015.68  5110.9 2021.91  5146.7 2023.76
  5203.4 2025.29  5224.4 2027.06    5249 2027.71  5266.4 2029.54  5286.4 2030.27
  5316.4 2032.78  5466.4 2039.59  5506.4 2040.32  5546.4 2042.09  5637.4 2043.39
#Mann= 4 ,-1 , 0
  4578.9      .1       0  4983.9     .05       0    5019      .1       0
  5637.4      .1       0
#XS Ineff= 2 , 0
         4976.38  2014.1
Permanent Ineff=
       T       T
Bank Sta=4983.9,5019
XS Rating Curve= 0 ,0
Exp/Cntr=0.3,0.1

Type RM Length L Ch R = 1 ,648     ,568,568,568
BEGIN DESCRIPTION:
Mapping XS 986b3818
END DESCRIPTION:
XS GIS Cut Line= 4
      2725832.55     10099679.63      2725339.94     10099946.55
      2725263.98     10100091.95      2725393.44     10100458.75
#Sta/Elev= 30
  4537.2 2044.32  4557.6 2044.15  4610.1 2040.07  4632.8 2039.15  4639.4 2037.98
  4683.1 2035.17  4721.2  2031.7  4852.4 2024.41  4868.6 2022.28  4874.3  2022.3
  4934.2 2016.45  4956.1 2012.84  4977.9 2008.24 4989.73 2004.18  4994.1 2003.09
  4999.8 2002.95 5010.58 2004.22  5021.7 2005.72  5037.8 2002.57  5059.5 2001.74
  5081.6 2002.91  5139.4 2010.64    5194 2014.97  5284.6 2017.66  5369.5 2021.41
  5390.7 2021.52    5563 2027.16  5581.6 2026.88  5602.8 2029.35  5650.5 2031.65
#Mann= 4 ,-1 , 0
  4537.2     .05       0 4989.73    .035       0 5010.58     .05       0
  5650.5     .16       0
#XS Ineff= 2 , 0
                         5021.82         2005.74
Permanent Ineff=
       T       T
Bank Sta=4989.73,5010.58
XS Rating Curve= 0 ,0
Exp/Cntr=0.3,0.1

Type RM Length L Ch R = 1 ,80      ,0,0,0
BEGIN DESCRIPTION:
UNT 0026 IN HEWA 1.0
END DESCRIPTION:
XS GIS Cut Line= 4
      2725913.91     10099388.54       2725151.8     10099421.53
      2725059.78     10099482.29      2724889.77     10100209.18
#Sta/Elev= 30
  4185.8 2045.98  4231.3 2044.02  4418.9 2031.97  4521.6 2027.88  4654.7 2020.75
  4761.8 2013.68  4861.9 2004.75  4880.4 2001.41  4885.4 2001.67  4901.9 1997.78
  4921.9 1991.51  4931.9 1989.77  4981.2  1987.9  4988.6 1984.76  4993.3 1981.75
    4996 1981.25  5024.5 1986.56  5038.4 1988.16  5128.8 1990.24  5142.5 1989.65
  5193.9 1991.36    5235  1996.8  5296.6 2000.93  5317.1 2003.16  5521.6 2011.33
  5594.4 2015.06  5717.6 2018.73  5749.4 2020.61    5769 2020.49  5805.4 2022.43
#Mann= 4 ,-1 , 0
  4185.8     .05       0  4981.2    .035       0  5038.4     .05       0
  5805.4      .1       0
Bank Sta=4981.2,5038.4
XS Rating Curve= 0 ,0
Exp/Cntr=0.3,0.1

Chan Stop Cuts=-1
Use User Specified Reach Order=0
Composite Channel Slope=5