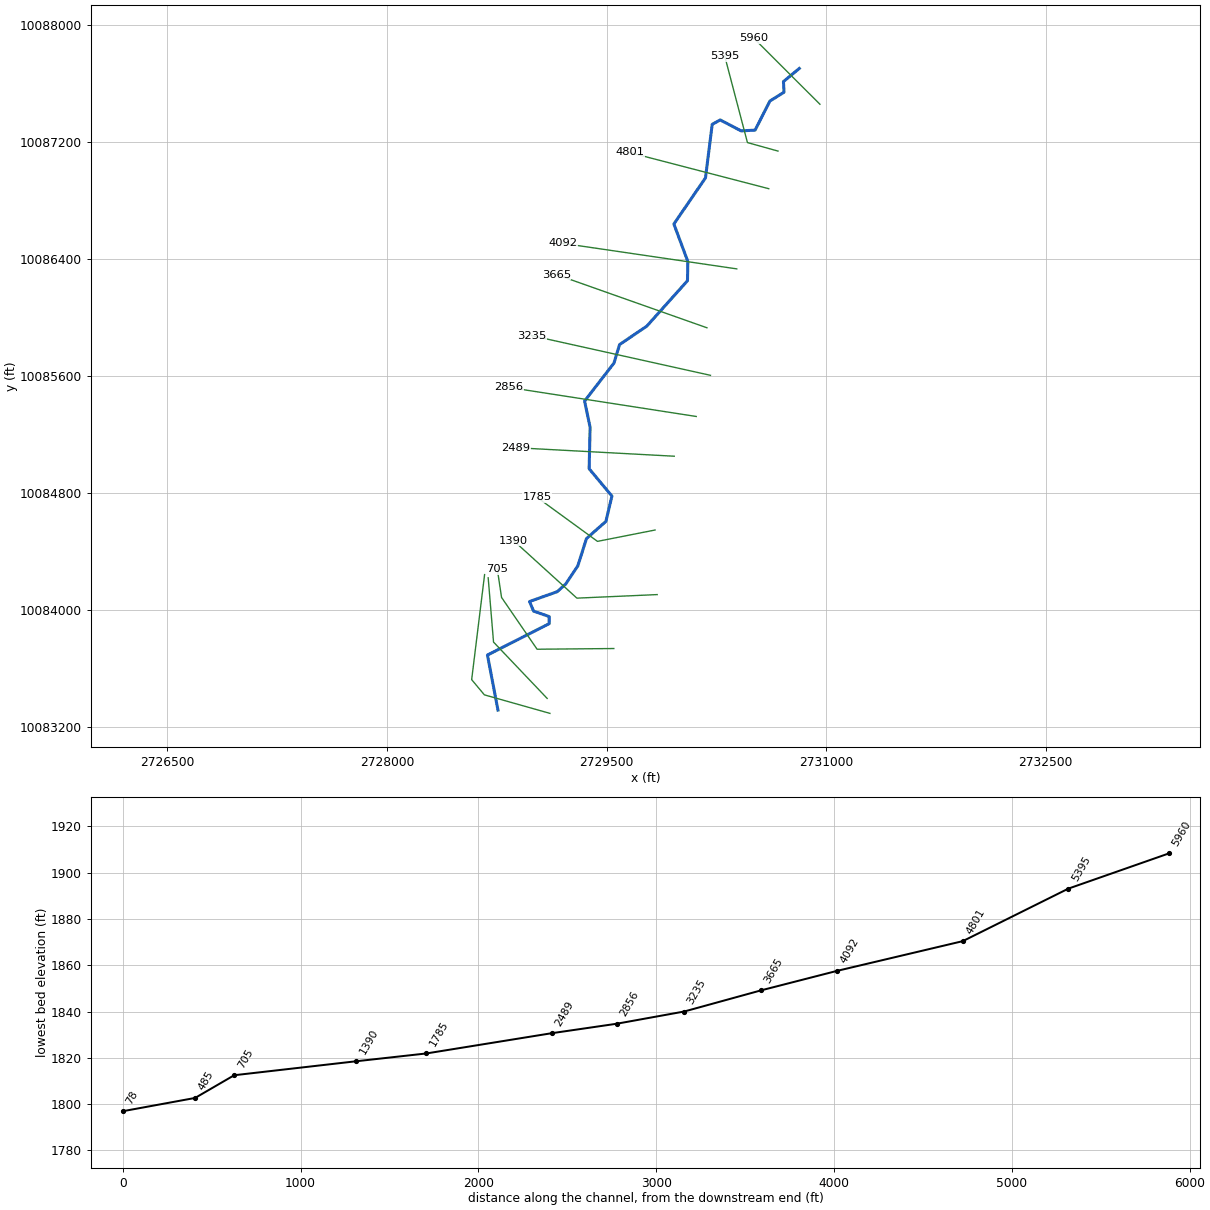
--- UNT 0029 IN HEWA.prj (project) ---

Proj Title=UNT 0029 IN HEWA Base Level Engineering
Current Plan=p01
Default Exp/Contr=0.3,0.1
English Units
Geom File=g01
Flow File=f01
Plan File=p01
BEGIN DESCRIPTION:
UNT 0029 IN HEWA
END DESCRIPTION:

--- UNT 0029 IN HEWA.p01 (plan) ---

Plan Title=Multiple Run
Short Identifier=Multiple
Geom File=g01
Flow File=f01
Subcritical Flow
K Sum by GR= 0
Std Step Tol= 0.01
Critical Tol= 0.01
Num of Std Step Trials= 20
Max Error Tol= 0.3
Flow Tol Ratio= 0.001
Split Flow NTrial= 30
Split Flow Tol= 0.02
Split Flow Ratio= 0.02
Log Output Level= 0
Friction Slope Method= 1
Unsteady Friction Slope Method= 2
Unsteady Bridges Friction Slope Method= 1
Parabolic Critical Depth
Global Vel Dist=  1 , 1 , 1
Global Log Level= 0
CheckData=True
Encroach Param= -1, 0, 0, 0
BEGIN DESCRIPTION:
Multiple Run
END DESCRIPTION:

--- UNT 0029 IN HEWA.f01 (steady flow) ---

Flow Title=Multiple
Number of Profiles=7
Profile Names=10-year,25-year,50-year,1pct_min,100-year,1pct_plu,500-year
River Rch & RM= UNT 0029 IN HEWA,Reach-1,5960
     838    1219    1551    1446    1955    2644    3118
Boundary for River Rch & Prof#=UNT 0029 IN HEWA,Reach-1,1
Up Type=0
Dn Type=3
Dn Slope=0.005
Boundary for River Rch & Prof#=UNT 0029 IN HEWA,Reach-1,2
Up Type=0
Dn Type=3
Dn Slope=0.005
Boundary for River Rch & Prof#=UNT 0029 IN HEWA,Reach-1,3
Up Type=0
Dn Type=3
Dn Slope=0.005
Boundary for River Rch & Prof#=UNT 0029 IN HEWA,Reach-1,4
Up Type=0
Dn Type=3
Dn Slope=0.005
Boundary for River Rch & Prof#=UNT 0029 IN HEWA,Reach-1,5
Up Type=0
Dn Type=3
Dn Slope=0.005
Boundary for River Rch & Prof#=UNT 0029 IN HEWA,Reach-1,6
Up Type=0
Dn Type=3
Dn Slope=0.005
Boundary for River Rch & Prof#=UNT 0029 IN HEWA,Reach-1,7
Up Type=0
Dn Type=3
Dn Slope=0.005

--- UNT 0029 IN HEWA.g01 (geometry) ---

Geom Title=Existing Conditions

River Reach=UNT 0029 IN HEWA,Reach-1
Reach XY= 30
      2730817.22     10087703.46      2730708.78     10087613.57
      2730712.78     10087541.01      2730616.08     10087480.29
      2730515.03     10087281.33      2730419.61     10087276.29
      2730276.92     10087350.99      2730222.03     10087320.98
      2730176.05     10086954.67      2729960.24     10086639.25
      2730055.62     10086382.54      2730053.17     10086251.22
      2729775.21     10085940.43      2729589.26     10085814.35
      2729550.84     10085687.46      2729350.25     10085427.93
      2729387.99     10085248.48      2729381.38     10084964.91
      2729536.98     10084777.97      2729495.87     10084604.71
      2729362.94     10084486.84      2729304.20     10084300.79
      2729220.93     10084176.12      2729163.43     10084123.82
      2728974.19     10084056.48      2729001.60     10083991.12
      2729108.63     10083953.52      2729108.24     10083904.86
      2728686.63     10083690.35      2728758.47     10083313.73

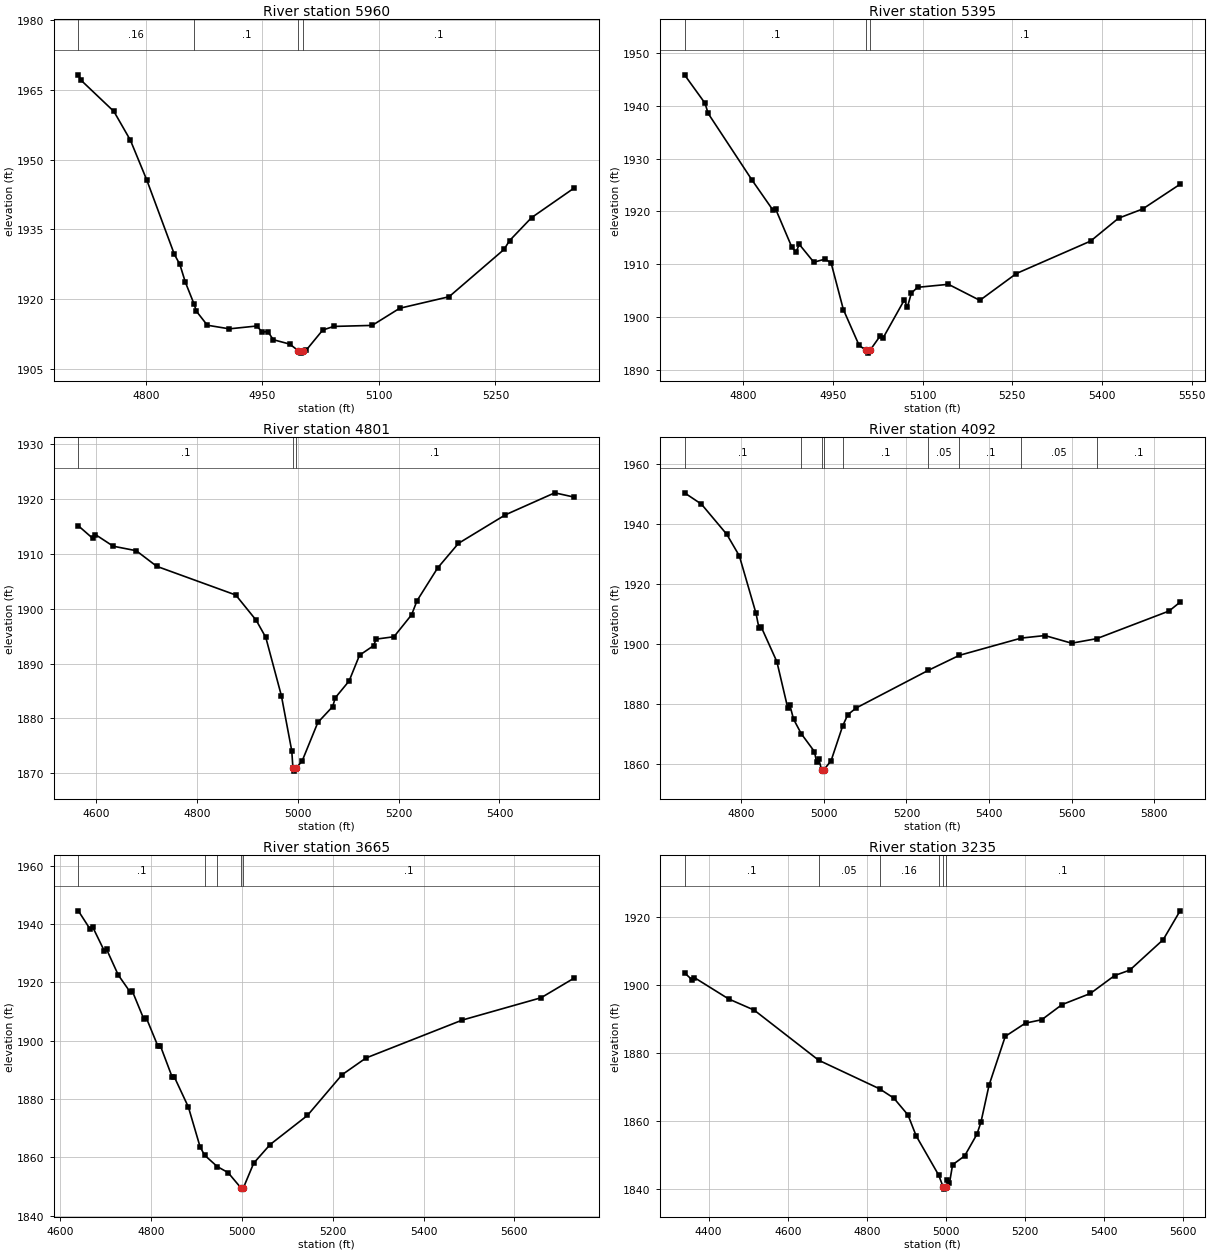
Type RM Length L Ch R = 1,5960,565,565,565
BEGIN DESCRIPTION:
UNT 0029 IN HEWA 13.0
END DESCRIPTION:
XS GIS Cut Line= 2
      2730957.92     10087458.42      2730506.99     10087909.34
#Sta/Elev= 30
  4713.3 1968.27  4716.7 1967.12  4759.1 1960.38  4780.3 1954.19  4801.5 1945.57
  4836.9 1929.60  4843.9 1927.46  4851.0 1923.62  4862.4 1918.83  4865.2 1917.36
  4879.3 1914.34  4907.6 1913.56  4942.9 1914.17  4950.0 1912.85  4957.1 1912.98
  4964.2 1911.22  4985.4 1910.27  4996.5 1908.83  4999.3 1908.33  5002.5 1908.83
  5006.6 1908.98  5027.8 1913.30  5041.9 1914.08  5091.4 1914.30  5126.8 1917.99
  5190.4 1920.48  5261.1 1930.66  5268.2 1932.56  5296.5 1937.51  5351.0 1943.85
#Mann=4,-1,0
  4713.3    0.16       0  4862.4     0.1       0  4996.5    0.07       0
  5002.5     0.1       0
Bank Sta=4996.5,5002.5
Exp/Cntr=0.3,0.1

Type RM Length L Ch R = 1,5395,594,594,594
BEGIN DESCRIPTION:
UNT 0029 IN HEWA 12.0
END DESCRIPTION:
XS GIS Cut Line= 3
      2730671.44     10087138.05      2730462.72     10087196.29
      2730307.37     10087788.57
#Sta/Elev= 30
  4701.7 1945.90  4735.9 1940.53  4741.3 1938.57  4814.8 1925.91  4849.0 1920.34
  4854.2 1920.43  4881.3 1913.20  4888.4 1912.30  4893.6 1913.76  4918.0 1910.36
  4936.4 1910.94  4946.8 1910.28  4967.4 1901.39  4993.8 1894.59  5005.8 1893.62
  5008.5 1893.12  5011.8 1893.62  5029.0 1896.38  5034.2 1896.07  5069.4 1903.20
  5074.5 1901.83  5081.2 1904.51  5091.5 1905.60  5143.2 1906.17  5195.7 1903.13
  5256.9 1908.22  5381.0 1914.37  5427.7 1918.71  5468.0 1920.45  5530.7 1925.15
#Mann=3,-1,0
  4701.7     0.1       0  5005.8    0.07       0  5011.8     0.1       0
Bank Sta=5005.8,5011.8
Exp/Cntr=0.3,0.1

Type RM Length L Ch R = 1,4801,709,709,709
BEGIN DESCRIPTION:
UNT 0029 IN HEWA 10.0
END DESCRIPTION:
XS GIS Cut Line= 2
      2730608.36     10086880.74      2729656.84     10087128.33
#Sta/Elev= 30
  4564.5 1915.09  4593.2 1912.79  4598.4 1913.49  4633.7 1911.37  4679.4 1910.55
  4720.0 1907.71  4876.9 1902.48  4917.4 1897.88  4936.4 1894.77  4967.4 1884.13
  4988.0 1874.08  4990.3 1870.91  4993.0 1870.41  4996.3 1870.91  5008.7 1872.29
  5039.7 1879.27  5069.1 1882.16  5074.3 1883.77  5101.7 1886.82  5122.4 1891.52
  5150.2 1893.25  5155.4 1894.45  5190.7 1894.88  5225.7 1898.88  5236.4 1901.43
  5277.4 1907.41  5318.7 1911.89  5411.7 1917.08  5509.7 1921.09  5547.7 1920.32
#Mann=3,-1,0
  4564.5     0.1       0  4990.3    0.07       0  4996.3     0.1       0
Bank Sta=4990.3,4996.3
Exp/Cntr=0.3,0.1

Type RM Length L Ch R = 1,4092,427,427,427
BEGIN DESCRIPTION:
UNT 0029 IN HEWA 9.0
END DESCRIPTION:
XS GIS Cut Line= 2
      2730389.89     10086332.17      2729201.95     10086506.72
#Sta/Elev= 30
  4662.3 1950.45  4703.3 1946.67  4764.8 1936.58  4795.1 1929.40  4835.6 1910.17
  4842.8 1905.18  4847.9 1905.73  4886.1 1894.06  4912.6 1878.48  4917.6 1879.48
  4926.5 1874.87  4945.1 1870.02  4977.1 1864.04  4982.4 1860.45  4987.4 1861.58
  4994.3 1858.02  4997.0 1857.52  5000.3 1858.02  5017.5 1861.02  5045.5 1872.61
  5057.9 1876.37  5078.1 1878.60  5253.3 1891.20  5328.1 1896.18  5478.3 1901.95
  5535.5 1902.79  5600.2 1900.24  5661.1 1901.76  5836.2 1910.98  5863.0 1913.94
#Mann=9,-1,0
  4662.3     0.1       0  4945.1    0.16       0  4994.3    0.07       0
  5000.3    0.16       0  5045.5     0.1       0  5253.3    0.05       0
  5328.1     0.1       0  5478.3    0.05       0  5661.1     0.1       0
Bank Sta=4994.3,5000.3
Exp/Cntr=0.3,0.1

Type RM Length L Ch R = 1,3665,430,430,430
BEGIN DESCRIPTION:
UNT 0029 IN HEWA 8.0
END DESCRIPTION:
XS GIS Cut Line= 2
      2730185.97     10085929.25      2729156.78     10086293.35
#Sta/Elev= 30
  4639.6 1944.54  4665.8 1938.21  4671.1 1939.04  4696.7 1930.84  4702.0 1931.29
  4727.6 1922.53  4753.2 1916.83  4758.5 1917.03  4784.1 1907.34  4789.4 1907.81
  4815.0 1898.11  4820.3 1898.29  4845.9 1887.71  4851.2 1887.53  4882.1 1877.23
  4907.7 1863.66  4917.6 1860.77  4945.6 1856.84  4969.5 1854.77  4997.4 1849.60
  5000.1 1849.10  5003.4 1849.60  5026.0 1858.02  5062.2 1864.40  5144.3 1874.37
  5220.4 1888.31  5273.4 1894.08  5485.5 1907.08  5659.0 1914.73  5731.3 1921.42
#Mann=5,-1,0
  4639.6     0.1       0  4917.6    0.16       0  4945.6     0.1       0
  4997.4    0.07       0  5003.4     0.1       0
Bank Sta=4997.4,5003.4
Exp/Cntr=0.3,0.1

Type RM Length L Ch R = 1,3235,379,379,379
BEGIN DESCRIPTION:
UNT 0029 IN HEWA 7.0
END DESCRIPTION:
XS GIS Cut Line= 2
      2730210.23     10085603.98      2728986.88     10085875.84
#Sta/Elev= 30
  4339.1 1903.48  4358.6 1901.44  4363.8 1902.12  4450.8 1895.83  4515.1 1892.57
  4678.3 1877.85  4832.2 1869.46  4868.3 1866.73  4904.3 1861.76  4924.8 1855.65
  4981.9 1844.10  4993.5 1840.50  4996.3 1840.00  4999.5 1840.50  5004.0 1842.56
  5009.1 1841.74  5017.0 1847.16  5047.5 1849.75  5078.5 1856.11  5088.7 1859.66
  5109.2 1870.52  5150.2 1884.85  5201.4 1888.75  5242.4 1889.73  5293.6 1894.17
  5365.3 1897.44  5426.8 1902.71  5465.0 1904.29  5549.7 1913.26  5592.3 1921.71
#Mann=6,-1,0
  4339.1     0.1       0  4678.3    0.05       0  4832.2    0.16       0
  4981.9     0.1       0  4993.5    0.07       0  4999.5     0.1       0
Bank Sta=4993.5,4999.5
Exp/Cntr=0.3,0.1

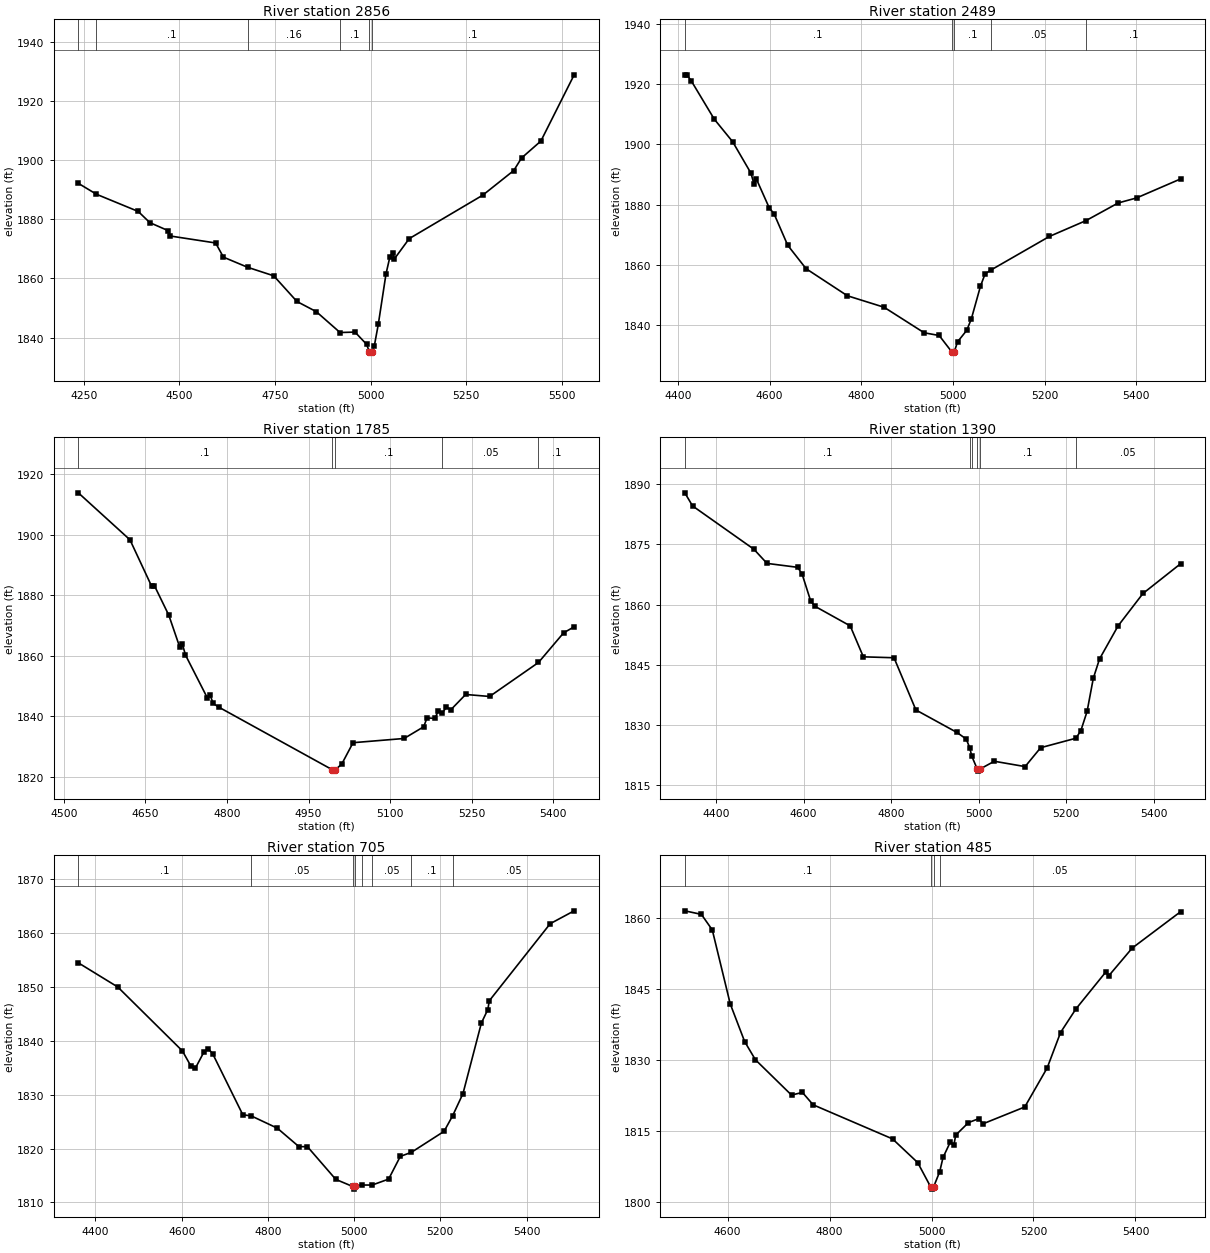
Type RM Length L Ch R = 1,2856,367,367,367
BEGIN DESCRIPTION:
UNT 0029 IN HEWA 6.0
END DESCRIPTION:
XS GIS Cut Line= 2
      2730113.14     10085322.41      2728832.49     10085521.30
#Sta/Elev= 30
  4235.9 1892.17  4283.3 1888.47  4392.4 1882.66  4422.8 1878.87  4470.5 1876.17
  4475.5 1874.36  4594.8 1871.99  4615.1 1867.20  4678.3 1863.77  4746.6 1860.88
  4807.3 1852.19  4857.9 1848.75  4920.0 1841.69  4959.1 1841.84  4989.2 1837.72
  4996.6 1835.22  4999.4 1834.72  5002.6 1835.22  5009.7 1837.28  5019.9 1844.42
  5040.1 1861.53  5050.2 1867.24  5057.2 1868.69  5062.2 1866.64  5100.8 1873.46
  5293.1 1888.17  5374.1 1896.51  5394.3 1900.73  5444.9 1906.47  5531.9 1928.88
#Mann=6,-1,0
  4235.9    0.05       0  4283.3     0.1       0  4678.3    0.16       0
  4920.0     0.1       0  4996.6    0.07       0  5002.6     0.1       0
Bank Sta=4996.6,5002.6
Exp/Cntr=0.3,0.1

Type RM Length L Ch R = 1,2489,704,704,704
BEGIN DESCRIPTION:
UNT 0029 IN HEWA 5.0
END DESCRIPTION:
XS GIS Cut Line= 2
      2729962.68     10085050.54      2728882.44     10085108.67
#Sta/Elev= 30
  4414.9 1923.12  4419.5 1923.12  4429.1 1921.09  4479.2 1908.38  4519.3 1900.88
  4559.3 1890.41  4565.8 1886.81  4570.8 1888.58  4599.4 1878.81  4609.4 1877.01
  4639.4 1866.47  4679.5 1858.68  4769.6 1849.68  4849.7 1845.86  4937.2 1837.37
  4969.9 1836.47  4997.0 1831.11  4999.7 1830.61  5003.0 1831.11  5010.0 1834.37
  5030.0 1838.18  5040.0 1841.94  5060.0 1852.85  5070.1 1856.97  5083.8 1858.32
  5210.3 1869.39  5290.4 1874.67  5360.5 1880.53  5400.5 1882.19  5496.7 1888.52
#Mann=5,-1,0
  4414.9     0.1       0  4997.0    0.07       0  5003.0     0.1       0
  5083.8    0.05       0  5290.4     0.1       0
Bank Sta=4997,5003
Exp/Cntr=0.3,0.1

Type RM Length L Ch R = 1,1785,395,395,395
BEGIN DESCRIPTION:
UNT 0029 IN HEWA 4.0
END DESCRIPTION:
XS GIS Cut Line= 3
      2729831.59     10084545.66      2729438.39     10084467.99
      2729025.95     10084768.82
#Sta/Elev= 30
  4526.9 1913.87  4621.8 1898.34  4661.7 1882.96  4666.8 1883.15  4693.2 1873.41
  4713.0 1863.01  4718.1 1863.90  4723.8 1860.26  4764.2 1846.02  4769.3 1846.91
  4774.7 1844.25  4784.9 1843.04  4993.3 1822.37  4996.0 1821.87  4999.3 1822.37
  5010.9 1824.15  5031.8 1831.27  5125.6 1832.66  5161.6 1836.53  5167.8 1839.47
  5182.4 1839.29  5188.6 1841.87  5195.8 1841.08  5203.3 1842.99  5211.8 1842.21
  5238.8 1847.21  5282.8 1846.55  5372.6 1857.78  5418.8 1867.58  5438.2 1869.58
#Mann=5,-1,0
  4526.9     0.1       0  4993.3    0.07       0  4999.3     0.1       0
  5195.8    0.05       0  5372.6     0.1       0
Bank Sta=4993.3,4999.3
Exp/Cntr=0.3,0.1

Type RM Length L Ch R = 1,1390,685,685,685
BEGIN DESCRIPTION:
UNT 0029 IN HEWA 3.0
END DESCRIPTION:
XS GIS Cut Line= 3
      2729846.20     10084103.89      2729297.61     10084079.62
      2728865.58     10084472.81
#Sta/Elev= 30
  4328.3 1887.86  4346.1 1884.59  4486.2 1873.80  4516.2 1870.27  4586.3 1869.29
  4596.3 1867.64  4616.3 1860.81  4626.3 1859.55  4706.4 1854.69  4736.4 1846.98
  4806.5 1846.75  4856.5 1833.74  4950.5 1828.12  4971.5 1826.49  4979.5 1824.35
  4984.2 1822.23  4996.8 1818.99  4999.6 1818.49  5002.8 1818.99  5035.7 1820.95
  5106.1 1819.62  5141.7 1824.33  5222.3 1826.69  5233.6 1828.59  5247.8 1833.37
  5262.0 1841.63  5276.2 1846.44  5318.8 1854.72  5375.5 1862.77  5461.6 1870.19
#Mann=6,-1,0
  4328.3     0.1       0  4979.5    0.05       0  4984.2     0.1       0
  4996.8    0.07       0  5002.8     0.1       0  5222.3    0.05       0
Bank Sta=4996.8,5002.8
Exp/Cntr=0.3,0.1

Type RM Length L Ch R = 1,705,220,220,220
BEGIN DESCRIPTION:
UNT 0029 IN HEWA 2.0
END DESCRIPTION:
XS GIS Cut Line= 4
      2729550.00     10083734.94      2729025.75     10083730.08
      2728783.01     10084084.47      2728753.88     10084278.67
#Sta/Elev= 30
  4360.2 1854.49  4451.7 1850.00  4601.7 1838.12  4621.7 1835.26  4631.7 1834.92
  4651.7 1837.95  4661.7 1838.54  4671.8 1837.61  4741.8 1826.26  4761.1 1826.07
  4821.8 1823.78  4871.8 1820.36  4891.7 1820.34  4957.4 1814.27  4996.4 1812.96
  4999.1 1812.46  5002.4 1812.96  5017.1 1813.22  5041.8 1813.22  5080.0 1814.32
  5107.1 1818.54  5132.9 1819.30  5208.6 1823.19  5228.4 1826.07  5252.5 1830.21
  5295.2 1843.32  5310.1 1845.81  5313.6 1847.45  5454.8 1861.76  5510.4 1864.15
#Mann=8,-1,0
  4360.2     0.1       0  4761.1    0.05       0  4996.4    0.04       0
  5002.4    0.05       0  5017.1     0.1       0  5041.8    0.05       0
  5132.9     0.1       0  5228.4    0.05       0
Bank Sta=4996.4,5002.4
Exp/Cntr=0.3,0.1

Type RM Length L Ch R = 1,485,407,407,407
BEGIN DESCRIPTION:
Mapping XS 17b7b509
END DESCRIPTION:
XS GIS Cut Line= 3
      2729094.47     10083393.73      2728728.16     10083779.14
      2728691.70     10084218.41
#Sta/Elev= 30
  4516.1 1861.58  4548.6 1860.83  4570.0 1857.54  4605.2 1841.88  4633.5 1833.89
  4654.6 1830.04  4725.4 1822.56  4746.8 1823.12  4767.8 1820.50  4923.5 1813.28
  4972.9 1808.26  4998.2 1803.14  5001.0 1802.64  5004.2 1803.14  5016.1 1806.34
  5022.6 1809.35  5036.8 1812.59  5043.7 1811.91  5047.5 1814.08  5072.5 1816.73
  5092.6 1817.56  5101.1 1816.48  5182.9 1820.04  5226.8 1828.30  5253.1 1835.81
  5283.2 1840.80  5342.4 1848.70  5347.4 1847.79  5393.6 1853.69  5488.6 1861.40
#Mann=4,-1,0
  4516.1     0.1       0  4998.2    0.07       0  5004.2     0.1       0
  5016.1    0.05       0
Bank Sta=4998.2,5004.2
Exp/Cntr=0.3,0.1

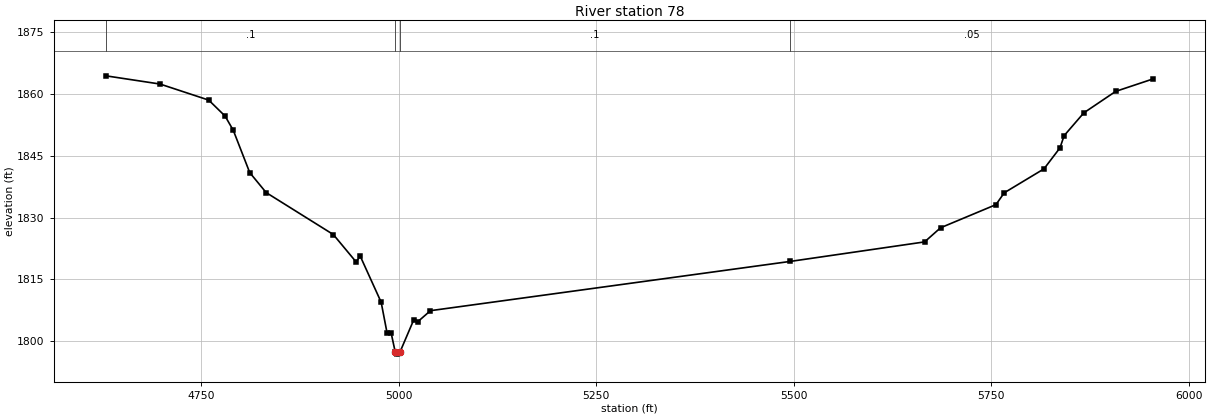
Type RM Length L Ch R = 1,78,0,0,0
BEGIN DESCRIPTION:
UNT 0029 IN HEWA 1.0
END DESCRIPTION:
XS GIS Cut Line= 4
      2729113.61     10083291.28      2728665.66     10083418.03
      2728578.86     10083522.20      2728667.15     10084240.66
#Sta/Elev= 30
  4629.7 1864.33  4698.2 1862.34  4759.8 1858.45  4780.5 1854.58  4790.9 1851.12
  4811.7 1840.88  4832.5 1836.04  4917.5 1825.87  4946.3 1819.24  4951.5 1820.65
  4978.0 1809.47  4985.4 1802.10  4990.6 1802.05  4995.8 1797.40  4998.5 1796.90
  5001.8 1797.40  5019.4 1805.29  5024.6 1804.80  5040.4 1807.43  5495.9 1819.37
  5665.6 1824.09  5685.8 1827.51  5755.9 1833.12  5766.4 1835.99  5816.7 1841.79
  5836.9 1846.87  5842.2 1849.84  5867.1 1855.36  5907.4 1860.56  5954.7 1863.58
#Mann=4,-1,0
  4629.7     0.1       0  4995.8    0.07       0  5001.8     0.1       0
  5495.9    0.05       0
Bank Sta=4995.8,5001.8
Exp/Cntr=0.3,0.1

Chan Stop Cuts=-1