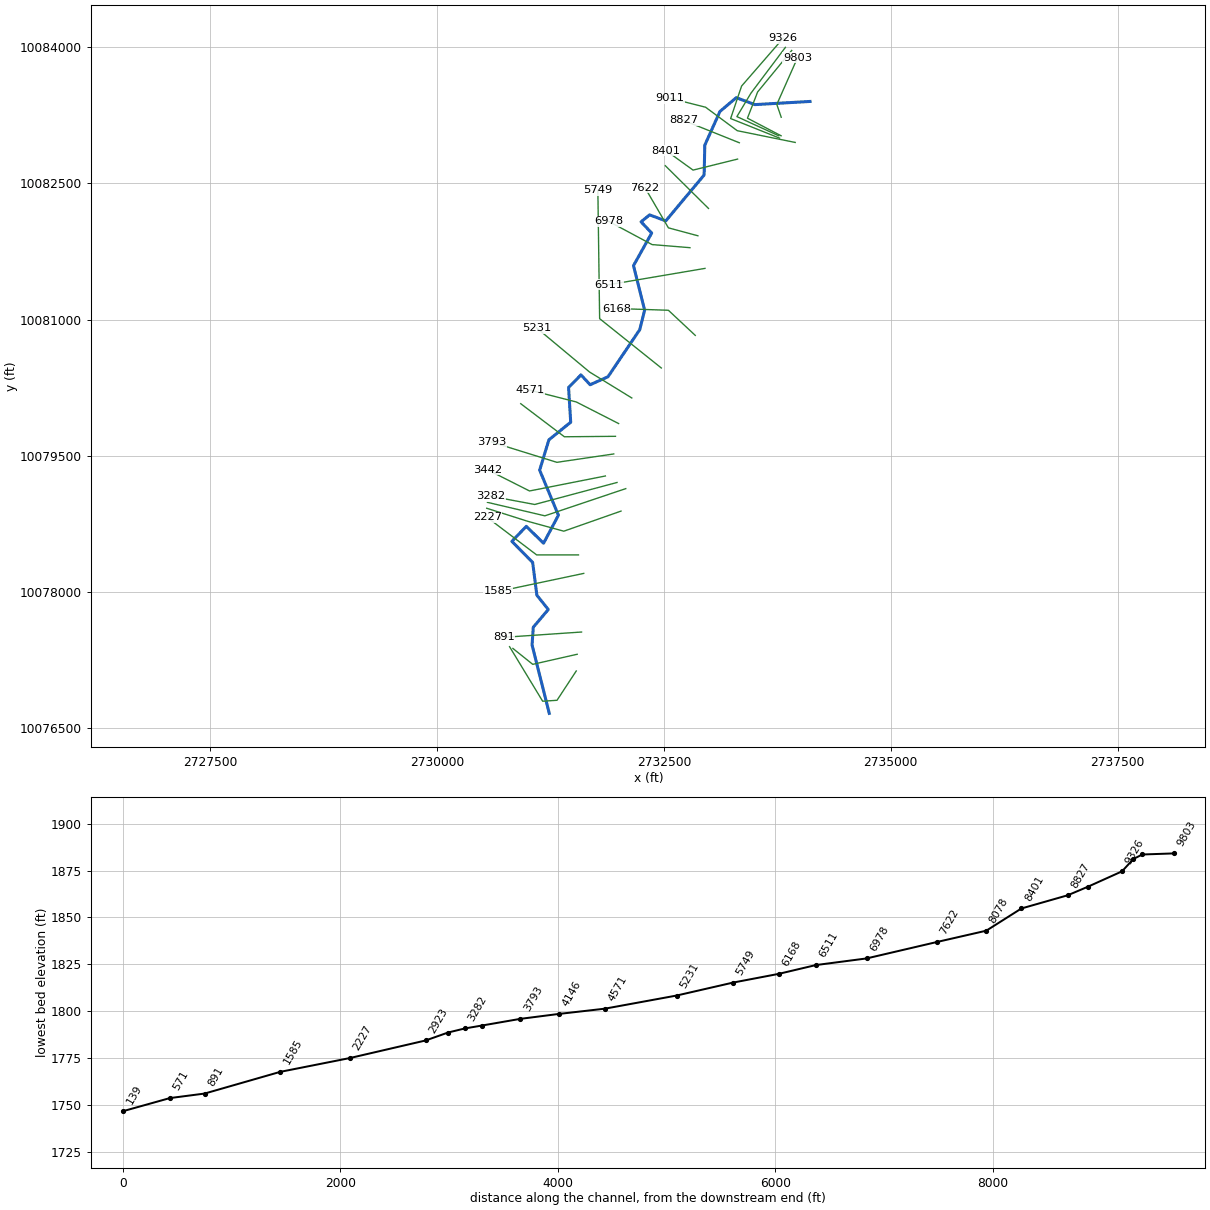
--- UNT 0030 IN HEWA.prj (project) ---

Proj Title=UNT 0030 IN HEWA Base Level Engineering
Current Plan=p01
Default Exp/Contr=0.3,0.1
English Units
Geom File=g01
Flow File=f01
Plan File=p01
BEGIN DESCRIPTION:
UNT 0030 IN HEWA
END DESCRIPTION:

--- UNT 0030 IN HEWA.p01 (plan) ---

Plan Title=Multiple Run
Short Identifier=Multiple
Geom File=g01
Flow File=f01
Subcritical Flow
K Sum by GR= 0
Std Step Tol= 0.01
Critical Tol= 0.01
Num of Std Step Trials= 20
Max Error Tol= 0.3
Flow Tol Ratio= 0.001
Split Flow NTrial= 30
Split Flow Tol= 0.02
Split Flow Ratio= 0.02
Log Output Level= 0
Friction Slope Method= 1
Unsteady Friction Slope Method= 2
Unsteady Bridges Friction Slope Method= 1
Parabolic Critical Depth
Global Vel Dist=  1 , 1 , 1
Global Log Level= 0
CheckData=True
Encroach Param= -1, 0, 0, 0
BEGIN DESCRIPTION:
Multiple Run
END DESCRIPTION:

--- UNT 0030 IN HEWA.f01 (steady flow) ---

Flow Title=Multiple
Number of Profiles=7
Profile Names=10-year,25-year,50-year,1pct_min,100-year,1pct_plu,500-year
River Rch & RM= UNT 0030 IN HEWA,Reach-1,9803
     861    1254    1597    1489    2014    2723    3215
River Rch & RM= UNT 0030 IN HEWA,Reach-1,5231
     950    1387    1768    1650    2231    3017    3566
Boundary for River Rch & Prof#=UNT 0030 IN HEWA,Reach-1,1
Up Type=0
Dn Type=3
Dn Slope=0.005
Boundary for River Rch & Prof#=UNT 0030 IN HEWA,Reach-1,2
Up Type=0
Dn Type=3
Dn Slope=0.005
Boundary for River Rch & Prof#=UNT 0030 IN HEWA,Reach-1,3
Up Type=0
Dn Type=3
Dn Slope=0.005
Boundary for River Rch & Prof#=UNT 0030 IN HEWA,Reach-1,4
Up Type=0
Dn Type=3
Dn Slope=0.005
Boundary for River Rch & Prof#=UNT 0030 IN HEWA,Reach-1,5
Up Type=0
Dn Type=3
Dn Slope=0.005
Boundary for River Rch & Prof#=UNT 0030 IN HEWA,Reach-1,6
Up Type=0
Dn Type=3
Dn Slope=0.005
Boundary for River Rch & Prof#=UNT 0030 IN HEWA,Reach-1,7
Up Type=0
Dn Type=3
Dn Slope=0.005

--- UNT 0030 IN HEWA.g01 (geometry) ---

Geom Title=Existing Conditions

River Reach=UNT 0030 IN HEWA,Reach-1
Reach XY= 30
      2734109.79     10083403.73      2733503.02     10083368.74
      2733298.03     10083445.37      2733117.80     10083293.16
      2732951.28     10082922.57      2732943.98     10082593.75
      2732521.43     10082087.94      2732343.48     10082154.35
      2732249.30     10082077.97      2732366.17     10081954.20
      2732165.72     10081594.85      2732288.55     10081104.72
      2732234.87     10080890.45      2731884.90     10080371.34
      2731688.21     10080283.42      2731587.25     10080392.20
      2731450.82     10080252.76      2731474.23     10079870.74
      2731233.87     10079676.41      2731132.37     10079342.90
      2731338.96     10078846.05      2731175.13     10078537.65
      2730985.33     10078723.72      2730826.12     10078558.61
      2731055.08     10078327.01      2731101.53     10077964.99
      2731227.34     10077807.90      2731061.82     10077612.27
      2731048.67     10077416.44      2731238.47     10076663.73

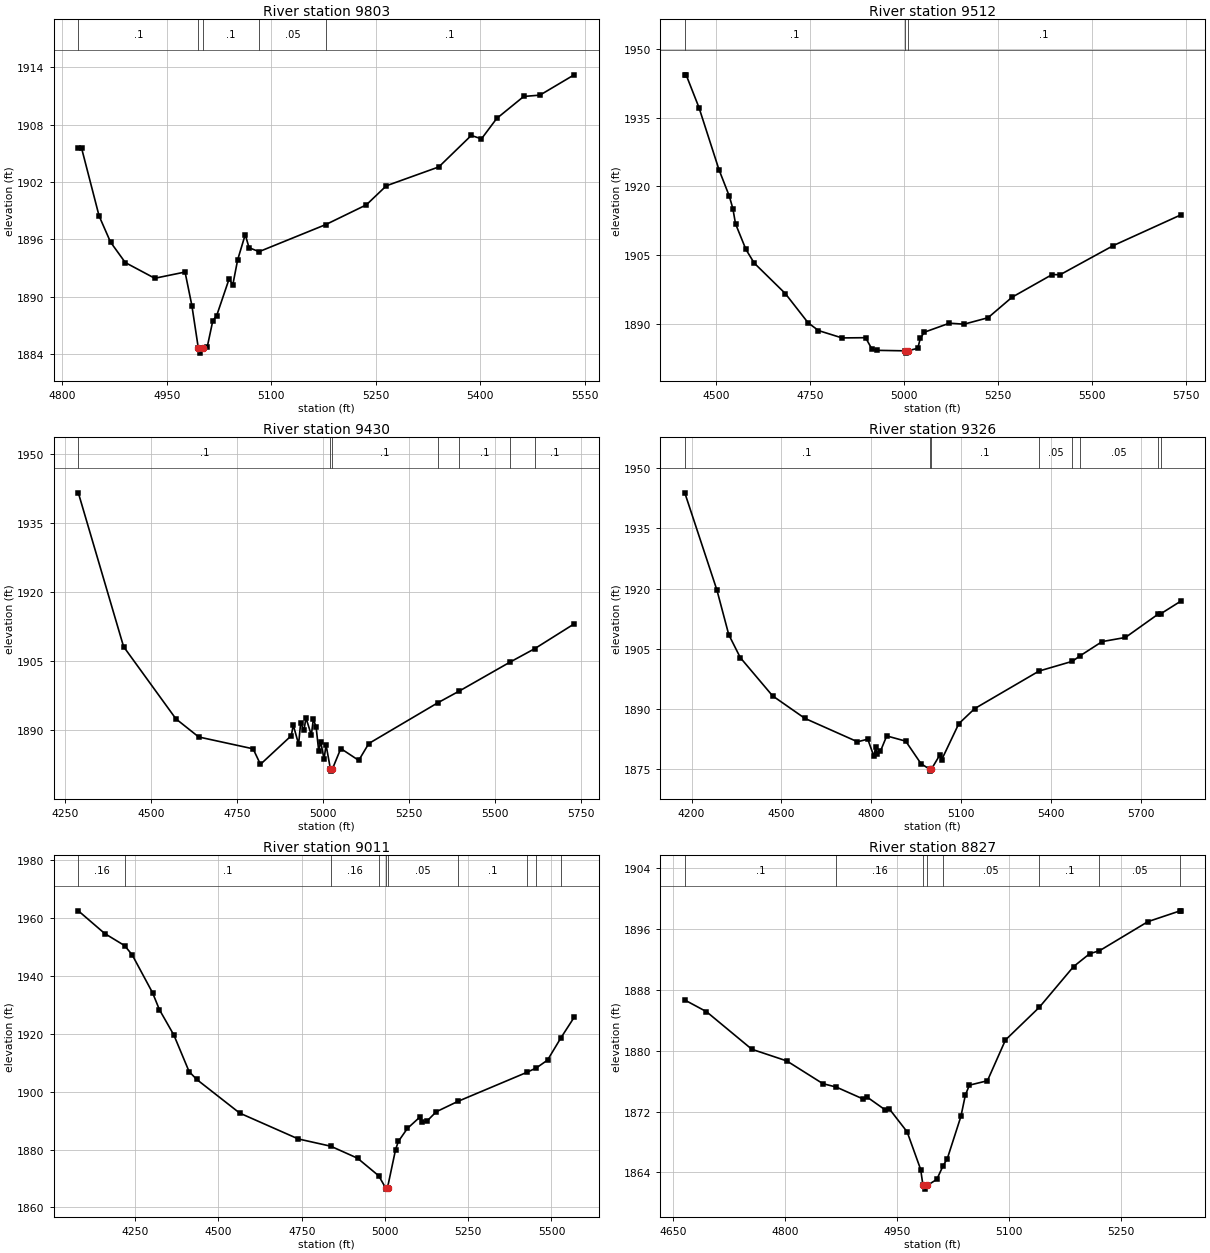
Type RM Length L Ch R = 1,9803,291,291,291
BEGIN DESCRIPTION:
UNT 0030 IN HEWA 22.0
END DESCRIPTION:
XS GIS Cut Line= 3
      2733793.00     10083230.06      2733744.45     10083370.84
      2733972.61     10083885.41
#Sta/Elev= 30
  4822.8 1905.56  4827.4 1905.56  4852.6 1898.46  4869.0 1895.73  4890.2 1893.59
  4932.5 1891.95  4976.0 1892.60  4985.8 1889.10  4995.1 1884.63  4997.8 1884.13
  5001.1 1884.63  5007.7 1884.72  5015.9 1887.53  5021.4 1888.05  5039.2 1891.87
  5044.6 1891.28  5051.5 1893.87  5062.4 1896.51  5067.9 1895.14  5082.3 1894.73
  5178.1 1897.56  5236.3 1899.62  5265.0 1901.61  5340.3 1903.58  5386.9 1906.87
  5401.5 1906.51  5423.4 1908.64  5462.2 1910.94  5485.5 1911.08  5534.6 1913.20
#Mann=5,-1,0
  4822.8     0.1       0  4995.1    0.07       0  5001.1     0.1       0
  5082.3    0.05       0  5178.1     0.1       0
Bank Sta=4995.1,5001.1
Exp/Cntr=0.3,0.1

Type RM Length L Ch R = 1,9512,82,82,82
BEGIN DESCRIPTION:
UNT 0030 IN HEWA 21.0
END DESCRIPTION:
XS GIS Cut Line= 4
      2733791.85     10083025.48      2733421.09     10083219.48
      2733533.18     10083508.33      2733908.27     10083965.33
#Sta/Elev= 30
  4417.4 1944.33  4420.9 1944.33  4455.1 1937.19  4508.3 1923.63  4536.0 1917.80
  4545.4 1915.08  4552.4 1911.79  4580.1 1906.19  4602.2 1903.21  4684.8 1896.57
  4745.4 1890.19  4773.1 1888.48  4835.9 1886.87  4898.5 1886.92  4915.5 1884.42
  4928.5 1884.16  5004.5 1884.05  5007.2 1883.55  5010.5 1884.05  5037.4 1884.61
  5044.2 1886.78  5054.9 1888.12  5121.7 1890.09  5160.5 1889.87  5224.4 1891.28
  5288.3 1895.76  5395.2 1900.72  5416.0 1900.66  5558.1 1907.05  5736.9 1913.72
#Mann=3,-1,0
  4417.4     0.1       0  5004.5    0.07       0  5010.5     0.1       0
Bank Sta=5004.5,5010.5
Exp/Cntr=0.3,0.1

Type RM Length L Ch R = 1,9430,104,104,104
BEGIN DESCRIPTION:
Mapping XS 1d0896e3
END DESCRIPTION:
XS GIS Cut Line= 4
      2733766.01     10083025.47      2733304.69     10083236.73
      2733459.89     10083495.40      2733838.85     10083999.24
#Sta/Elev= 30
  4289.5 1941.48  4420.9 1908.11  4572.8 1892.45  4638.9 1888.52  4796.9 1885.95
  4818.2 1882.58  4907.7 1888.79  4913.5 1891.10  4929.0 1886.94  4934.9 1891.56
  4944.6 1889.97  4950.4 1892.67  4966.0 1888.91  4971.8 1892.42  4980.0 1890.59
  4987.3 1885.52  4993.2 1887.49  5002.9 1883.71  5008.7 1886.80  5021.3 1881.61
  5024.0 1881.11  5027.3 1881.61  5051.5 1886.01  5103.6 1883.44  5132.8 1887.10
  5332.8 1895.92  5394.5 1898.44  5542.4 1904.74  5614.9 1907.69  5729.0 1913.05
#Mann=7,-1,0
  4289.5     0.1       0  5021.3    0.07       0  5027.3     0.1       0
  5332.8    0.05       0  5394.5     0.1       0  5542.4    0.05       0
  5614.9     0.1       0
Bank Sta=5021.3,5027.3
Exp/Cntr=0.3,0.1

Type RM Length L Ch R = 1,9326,315,315,315
BEGIN DESCRIPTION:
Mapping XS 5c8ed5e8
END DESCRIPTION:
XS GIS Cut Line= 4
      2733774.65     10082999.60      2733235.71     10083215.17
      2733356.42     10083573.00      2733813.31     10084098.85
#Sta/Elev= 30
  4177.3 1943.81  4284.5 1919.61  4324.0 1908.52  4362.6 1902.79  4470.3 1893.29
  4578.0 1887.69  4753.6 1881.86  4787.9 1882.51  4808.5 1878.23  4813.8 1880.47
  4819.6 1878.83  4830.1 1879.50  4851.2 1883.32  4914.5 1882.02  4965.9 1876.38
  4994.3 1875.06  4997.1 1874.56  5000.3 1875.06  5028.8 1878.62  5034.1 1877.32
  5091.8 1886.37  5144.6 1890.11  5359.4 1899.46  5470.9 1901.89  5494.8 1903.17
  5570.0 1906.79  5647.8 1907.82  5757.4 1913.65  5765.6 1913.71  5832.0 1916.83
#Mann=8,-1,0
  4177.3     0.1       0  4994.3    0.07       0  5000.3     0.1       0
  5359.4    0.05       0  5470.9     0.1       0  5494.8    0.05       0
  5757.4     0.1       0  5765.6    0.05       0
Bank Sta=4994.3,5000.3
Exp/Cntr=0.3,0.1

Type RM Length L Ch R = 1,9011,184,184,184
BEGIN DESCRIPTION:
UNT 0030 IN HEWA 20.0
END DESCRIPTION:
XS GIS Cut Line= 4
      2733947.07     10082952.19      2733309.00     10083081.53
      2732959.80     10083340.20      2732568.71     10083439.04
#Sta/Elev= 30
  4079.2 1962.58  4158.4 1954.73  4218.3 1950.54  4241.0 1947.33  4302.2 1934.22
  4322.7 1928.39  4366.2 1919.59  4411.8 1906.99  4434.9 1904.24  4563.8 1892.62
  4739.7 1883.68  4837.1 1881.17  4917.6 1877.02  4981.1 1870.95  5001.7 1866.82
  5004.4 1866.32  5007.7 1866.82  5031.9 1880.00  5040.3 1882.83  5067.3 1887.30
  5104.2 1891.17  5111.2 1889.38  5125.8 1889.81  5154.0 1893.07  5220.0 1896.72
  5425.9 1906.70  5454.9 1908.26  5488.2 1910.94  5528.8 1918.72  5568.2 1925.75
#Mann=10,-1,0
  4079.2    0.16       0  4218.3     0.1       0  4837.1    0.16       0
  4981.1    0.05       0  5001.7    0.04       0  5007.7    0.05       0
  5220.0     0.1       0  5425.9    0.05       0  5454.9     0.1       0
  5528.8    0.05       0
Bank Sta=5001.7,5007.7
Exp/Cntr=0.3,0.1

Type RM Length L Ch R = 1,8827,426,426,426
BEGIN DESCRIPTION:
UNT 0030 IN HEWA 19.0
END DESCRIPTION:
XS GIS Cut Line= 2
      2733331.83     10082948.48      2732715.29     10083196.06
#Sta/Elev= 30
  4666.0 1886.65  4695.0 1885.12  4755.8 1880.18  4802.6 1878.65  4851.0 1875.66
  4869.0 1875.21  4904.8 1873.65  4910.1 1873.91  4934.3 1872.23  4939.7 1872.39
  4963.9 1869.33  4982.1 1864.37  4985.1 1862.30  4987.9 1861.80  4991.1 1862.30
  5003.7 1863.08  5012.1 1864.87  5017.7 1865.79  5036.0 1871.36  5041.9 1874.14
  5047.3 1875.46  5071.5 1876.04  5095.7 1881.40  5141.0 1885.69  5186.9 1891.04
  5208.6 1892.74  5221.6 1893.12  5286.6 1896.95  5329.8 1898.37  5330.4 1898.37
#Mann=8,-1,0
  4666.0     0.1       0  4869.0    0.16       0  4985.1    0.07       0
  4991.1    0.16       0  5012.1    0.05       0  5141.0     0.1       0
  5221.6    0.05       0  5329.8     0.1       0
Bank Sta=4985.1,4991.1
Exp/Cntr=0.3,0.1

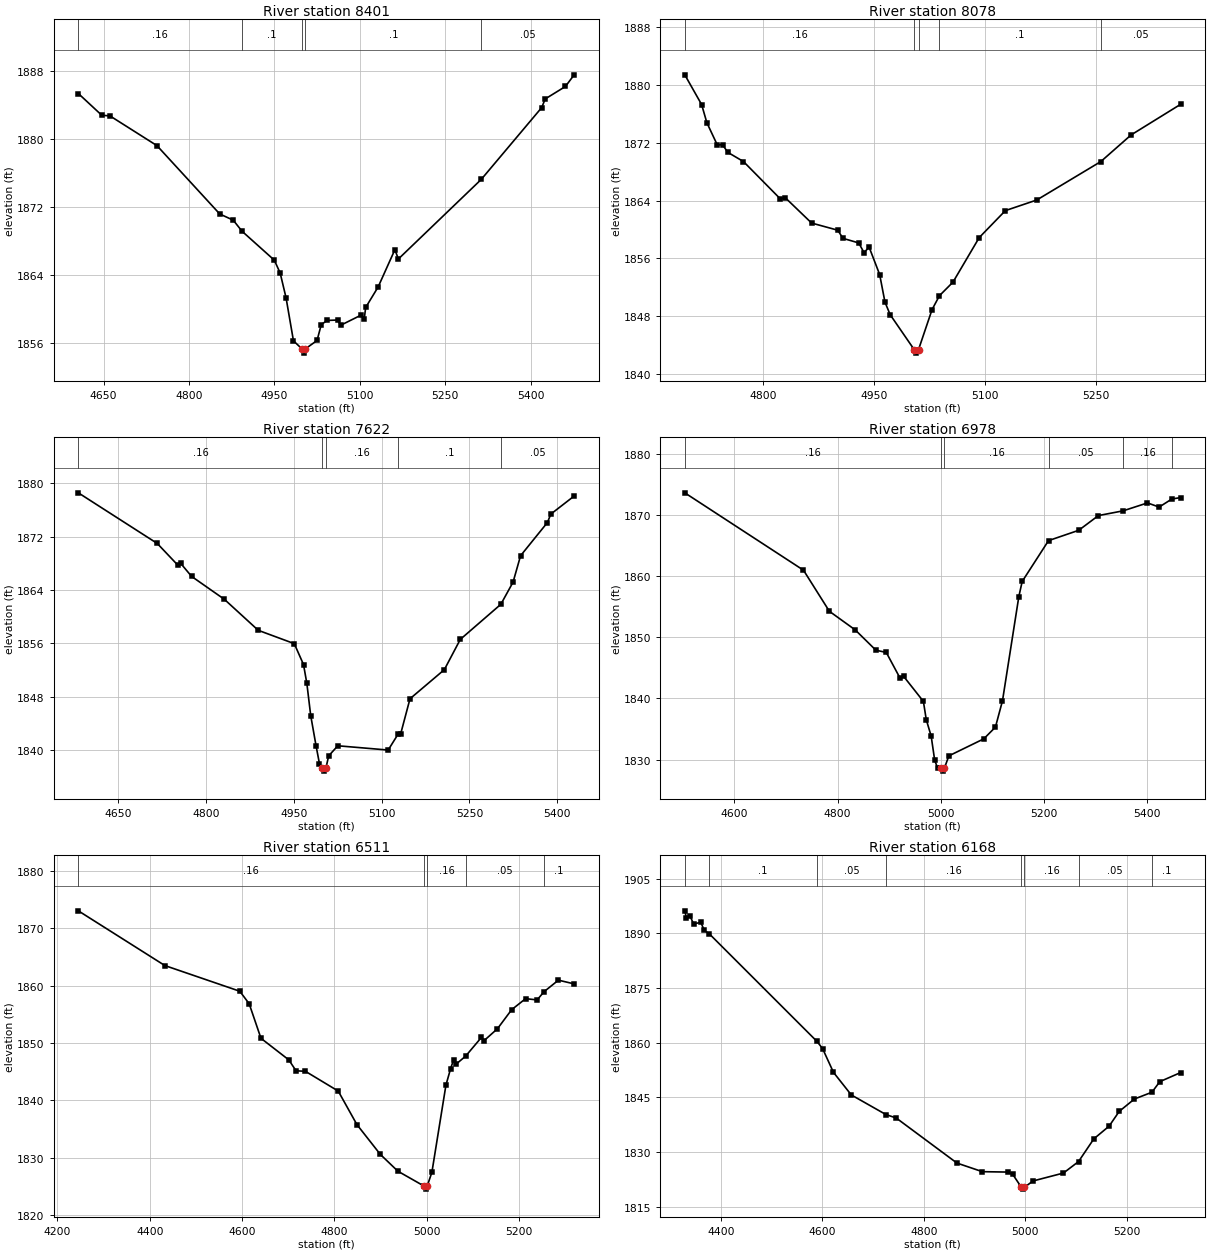
Type RM Length L Ch R = 1,8401,323,323,323
BEGIN DESCRIPTION:
UNT 0030 IN HEWA 18.0
END DESCRIPTION:
XS GIS Cut Line= 3
      2733312.40     10082768.86      2732822.07     10082647.50
      2732525.90     10082861.13
#Sta/Elev= 30
  4605.8 1885.33  4646.9 1882.77  4661.4 1882.69  4743.8 1879.19  4854.0 1871.14
  4877.7 1870.41  4893.1 1869.11  4949.8 1865.70  4960.1 1864.18  4970.4 1861.27
  4983.4 1856.20  4998.3 1855.25  5001.1 1854.75  5004.3 1855.25  5024.8 1856.24
  5032.2 1858.11  5042.5 1858.60  5061.1 1858.65  5066.2 1858.03  5102.5 1859.24
  5107.6 1858.79  5110.2 1860.13  5132.0 1862.54  5161.4 1866.93  5167.6 1865.84
  5313.0 1875.21  5419.1 1883.67  5425.3 1884.69  5460.8 1886.16  5476.1 1887.53
#Mann=5,-1,0
  4605.8    0.16       0  4893.1     0.1       0  4998.3    0.07       0
  5004.3     0.1       0  5313.0    0.05       0
Bank Sta=4998.3,5004.3
Exp/Cntr=0.3,0.1

Type RM Length L Ch R = 1,8078,456,456,456
BEGIN DESCRIPTION:
UNT 0030 IN HEWA 17.0
END DESCRIPTION:
XS GIS Cut Line= 2
      2732991.97     10082225.16      2732516.21     10082696.07
#Sta/Elev= 30
  4694.4 1881.41  4717.1 1877.30  4724.2 1874.78  4738.3 1871.70  4745.3 1871.75
  4752.5 1870.68  4773.6 1869.41  4823.2 1864.26  4830.2 1864.39  4865.6 1860.90
  4900.9 1859.91  4908.0 1858.78  4929.2 1858.15  4936.3 1856.82  4943.3 1857.55
  4957.5 1853.77  4964.6 1849.97  4971.6 1848.23  5004.0 1843.40  5006.8 1842.90
  5010.0 1843.40  5028.2 1848.92  5038.2 1850.85  5056.5 1852.73  5091.9 1858.89
  5127.2 1862.62  5169.6 1864.09  5256.1 1869.41  5296.9 1873.09  5363.8 1877.33
#Mann=5,-1,0
  4694.4    0.16       0  5004.0    0.07       0  5010.0    0.16       0
  5038.2     0.1       0  5256.1    0.05       0
Bank Sta=5004,5010
Exp/Cntr=0.3,0.1

Type RM Length L Ch R = 1,7622,644,644,644
BEGIN DESCRIPTION:
UNT 0030 IN HEWA 16.0
END DESCRIPTION:
XS GIS Cut Line= 3
      2732875.45     10081924.16      2732550.21     10082011.54
      2732293.17     10082452.88
#Sta/Elev= 30
  4581.4 1878.56  4716.3 1870.97  4751.1 1867.75  4756.3 1867.99  4775.0 1866.03
  4831.1 1862.59  4888.9 1857.95  4950.5 1855.95  4966.3 1852.82  4972.0 1849.99
  4978.6 1845.17  4987.8 1840.61  4993.6 1837.93  4998.7 1837.34  5001.5 1836.84
  5004.7 1837.34  5009.3 1839.13  5024.9 1840.64  5111.0 1840.00  5128.6 1842.48
  5132.5 1842.47  5148.3 1847.69  5207.0 1852.05  5234.3 1856.59  5303.6 1861.85
  5324.5 1865.18  5337.3 1869.13  5383.2 1874.11  5389.0 1875.37  5428.9 1878.08
#Mann=5,-1,0
  4581.4    0.16       0  4998.7    0.07       0  5004.7    0.16       0
  5128.6     0.1       0  5303.6    0.05       0
Bank Sta=4998.7,5004.7
Exp/Cntr=0.3,0.1

Type RM Length L Ch R = 1,6978,467,467,467
BEGIN DESCRIPTION:
UNT 0030 IN HEWA 15.0
END DESCRIPTION:
XS GIS Cut Line= 3
      2732788.06     10081793.08      2732370.59     10081827.06
      2731891.74     10082083.42
#Sta/Elev= 30
  4503.7 1873.64  4734.0 1860.98  4784.2 1854.26  4834.4 1851.21  4874.5 1847.89
  4894.6 1847.53  4921.1 1843.36  4928.4 1843.60  4966.6 1839.52  4972.2 1836.53
  4981.7 1833.84  4988.5 1829.91  4994.2 1828.61  5001.4 1828.61  5004.1 1828.11
  5007.4 1828.61  5016.1 1830.61  5083.8 1833.39  5106.4 1835.31  5120.1 1839.63
  5151.8 1856.67  5158.3 1859.14  5209.4 1865.82  5268.0 1867.51  5306.2 1869.92
  5354.0 1870.69  5401.4 1871.99  5424.0 1871.31  5448.7 1872.63  5465.7 1872.86
#Mann=6,-1,0
  4503.7    0.16       0  5001.4    0.07       0  5007.4    0.16       0
  5209.4    0.05       0  5354.0    0.16       0  5448.7     0.1       0
Bank Sta=5001.4,5007.4
Exp/Cntr=0.3,0.1

Type RM Length L Ch R = 1,6511,343,343,343
BEGIN DESCRIPTION:
UNT 0030 IN HEWA 14.0
END DESCRIPTION:
XS GIS Cut Line= 2
      2732953.18     10081564.92      2731894.82     10081385.29
#Sta/Elev= 30
  4245.5 1873.01  4432.9 1863.48  4595.1 1859.01  4615.4 1856.83  4640.9 1850.82
  4701.2 1847.06  4716.9 1845.16  4737.2 1845.07  4808.2 1841.63  4848.7 1835.79
  4899.4 1830.60  4937.4 1827.68  4994.7 1825.06  4997.5 1824.56  5000.7 1825.06
  5011.0 1827.50  5041.4 1842.67  5051.6 1845.56  5058.0 1847.07  5063.1 1846.30
  5084.0 1847.71  5118.3 1850.98  5123.4 1850.37  5153.0 1852.49  5183.7 1855.80
  5213.9 1857.72  5238.9 1857.50  5253.6 1858.92  5284.9 1860.94  5319.0 1860.29
#Mann=5,-1,0
  4245.5    0.16       0  4994.7    0.07       0  5000.7    0.16       0
  5084.0    0.05       0  5253.6     0.1       0
Bank Sta=4994.7,5000.7
Exp/Cntr=0.3,0.1

Type RM Length L Ch R = 1,6168,419,419,419
BEGIN DESCRIPTION:
UNT 0030 IN HEWA 13.0
END DESCRIPTION:
XS GIS Cut Line= 3
      2732846.35     10080827.00      2732550.21     10081103.72
      2731977.34     10081123.14
#Sta/Elev= 30
  4328.3 1896.22  4331.5 1894.27  4338.9 1894.69  4345.7 1892.62  4359.9 1893.07
  4366.7 1890.85  4376.8 1889.89  4589.1 1860.39  4600.2 1858.42  4621.7 1851.89
  4656.9 1845.70  4725.4 1840.30  4745.4 1839.38  4865.4 1827.00  4915.5 1824.64
  4965.5 1824.53  4975.5 1823.90  4992.5 1820.35  4995.2 1819.85  4998.5 1820.35
  5015.5 1822.09  5075.5 1824.26  5105.3 1827.41  5135.6 1833.66  5165.6 1837.12
  5185.6 1841.18  5215.6 1844.58  5250.2 1846.44  5265.7 1849.34  5306.8 1851.84
#Mann=8,-1,0
  4328.3    0.16       0  4376.8     0.1       0  4589.1    0.05       0
  4725.4    0.16       0  4992.5    0.07       0  4998.5    0.16       0
  5105.3    0.05       0  5250.2     0.1       0
Bank Sta=4992.5,4998.5
Exp/Cntr=0.3,0.1

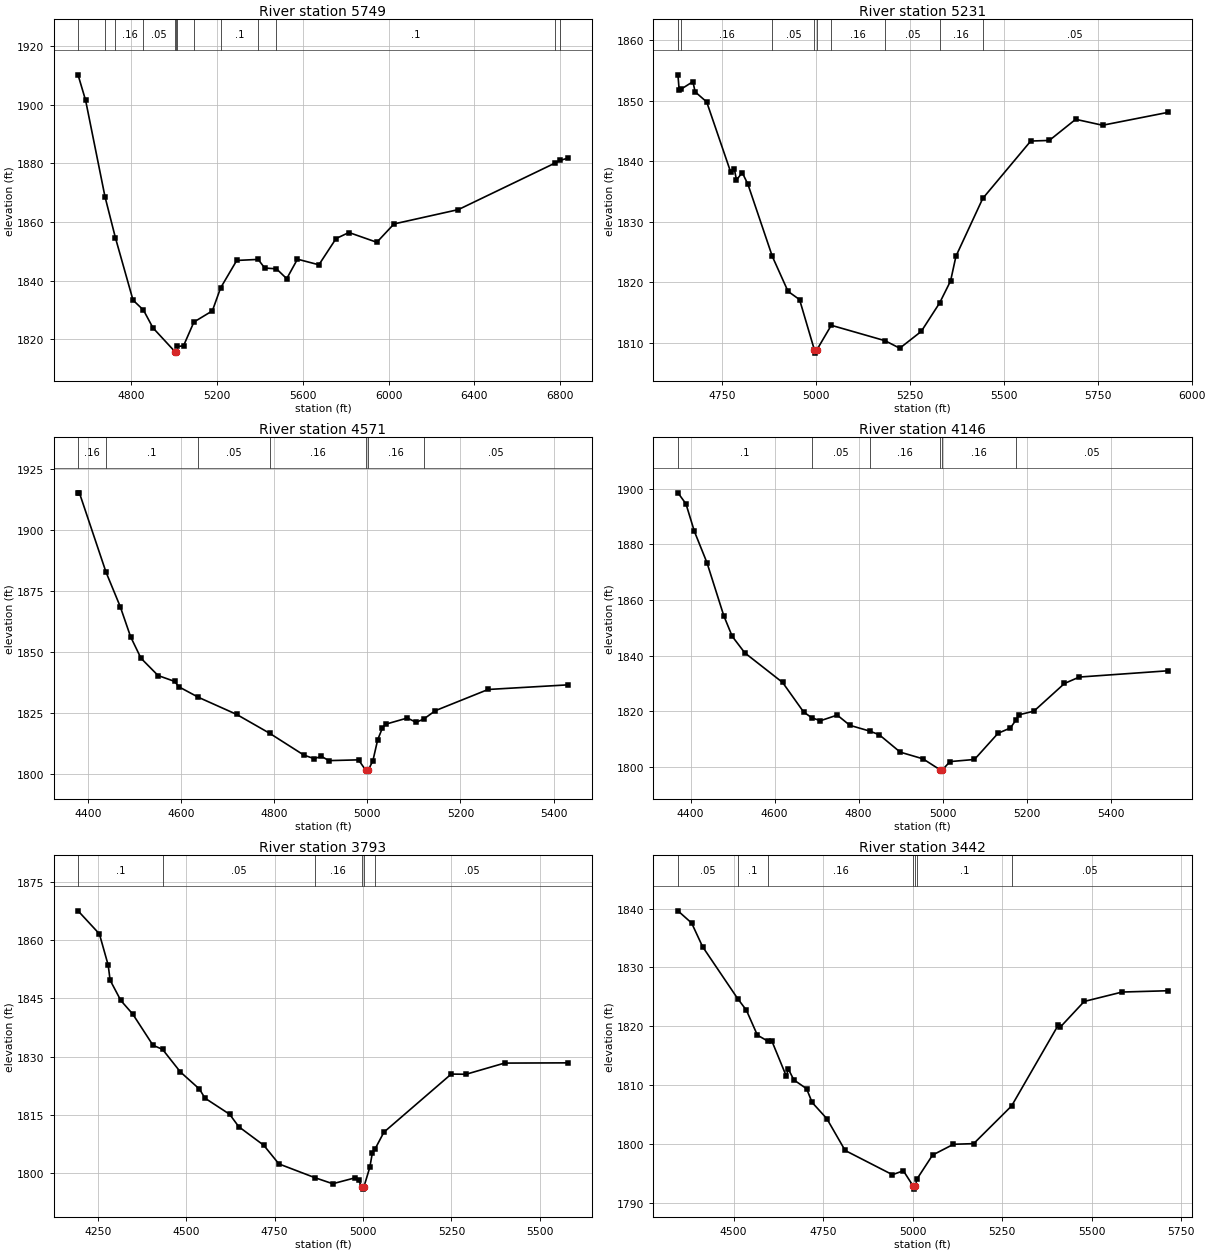
Type RM Length L Ch R = 1,5749,518,518,518
BEGIN DESCRIPTION:
UNT 0030 IN HEWA 12.0
END DESCRIPTION:
XS GIS Cut Line= 3
      2732472.57     10080467.74      2731792.89     10081011.48
      2731773.47     10082424.23
#Sta/Elev= 30
  4552.1 1910.24  4587.5 1901.50  4677.6 1868.68  4726.2 1854.64  4808.4 1833.31
  4857.1 1829.90  4901.3 1823.84  5003.9 1815.71  5006.7 1815.21  5009.9 1815.71
  5015.2 1817.48  5043.8 1817.70  5092.2 1825.83  5178.2 1829.64  5216.5 1837.46
  5291.9 1846.86  5391.6 1847.21  5422.2 1844.27  5477.1 1843.99  5524.8 1840.63
  5574.8 1847.29  5674.8 1845.37  5754.8 1854.33  5814.8 1856.40  5944.8 1853.06
  6024.8 1859.32  6324.9 1864.22  6777.2 1880.17  6799.8 1881.05  6835.4 1881.79
#Mann=13,-1,0
  4552.1    0.16       0  4677.6     0.1       0  4726.2    0.16       0
  4857.1    0.05       0  5003.9    0.04       0  5009.9    0.05       0
  5015.2    0.16       0  5092.2    0.05       0  5216.5     0.1       0
  5391.6    0.16       0  5477.1     0.1       0  6777.2    0.16       0
  6799.8     0.1       0
Bank Sta=5003.9,5009.9
Exp/Cntr=0.3,0.1

Type RM Length L Ch R = 1,5231,660,660,660
BEGIN DESCRIPTION:
UNT 0030 IN HEWA 11.0
END DESCRIPTION:
XS GIS Cut Line= 3
      2732147.24     10080137.68      2731681.23     10080424.07
      2731099.13     10080909.16
#Sta/Elev= 30
  4631.7 1854.29  4634.9 1851.85  4641.0 1851.96  4671.6 1853.16  4677.5 1851.48
  4708.3 1849.81  4772.2 1838.22  4781.7 1838.81  4787.6 1836.92  4803.0 1838.13
  4818.1 1836.21  4883.1 1824.29  4924.9 1818.52  4955.7 1817.15  4995.3 1808.81
  4998.0 1808.31  5001.3 1808.81  5040.1 1812.91  5183.5 1810.36  5222.5 1809.12
  5279.8 1811.90  5328.7 1816.60  5357.9 1820.24  5372.2 1824.32  5443.6 1833.87
  5571.4 1843.35  5620.8 1843.45  5691.1 1846.94  5762.7 1845.96  5936.4 1848.08
#Mann=9,-1,0
  4631.7     0.1       0  4641.0    0.16       0  4883.1    0.05       0
  4995.3    0.04       0  5001.3    0.05       0  5040.1    0.16       0
  5183.5    0.05       0  5328.7    0.16       0  5443.6    0.05       0
Bank Sta=4995.3,5001.3
Exp/Cntr=0.3,0.1

Type RM Length L Ch R = 1,4571,425,425,425
BEGIN DESCRIPTION:
UNT 0030 IN HEWA 10.0
END DESCRIPTION:
XS GIS Cut Line= 3
      2732001.65     10079856.07      2731535.59     10080093.96
      2731022.25     10080224.72
#Sta/Elev= 30
  4377.9 1915.41  4380.8 1915.41  4438.0 1882.91  4468.7 1868.71  4490.9 1856.40
  4513.2 1847.59  4549.9 1840.50  4585.5 1838.09  4594.8 1835.86  4636.8 1831.56
  4718.8 1824.56  4789.5 1816.85  4863.2 1807.89  4885.4 1806.41  4901.2 1807.34
  4917.1 1805.61  4980.8 1805.92  4995.9 1801.80  4998.6 1801.30  5001.9 1801.80
  5011.7 1805.53  5022.0 1814.14  5032.3 1819.05  5039.8 1820.57  5085.8 1823.08
  5104.6 1821.31  5121.0 1822.65  5145.9 1826.08  5259.4 1834.78  5430.9 1836.67
#Mann=7,-1,0
  4377.9    0.16       0  4438.0     0.1       0  4636.8    0.05       0
  4789.5    0.16       0  4995.9    0.07       0  5001.9    0.16       0
  5121.0    0.05       0
Bank Sta=4995.9,5001.9
Exp/Cntr=0.3,0.1

Type RM Length L Ch R = 1,4146,353,353,353
BEGIN DESCRIPTION:
UNT 0030 IN HEWA 9.0
END DESCRIPTION:
XS GIS Cut Line= 3
      2731967.61     10079715.30      2731404.52     10079710.44
      2730923.88     10080074.56
#Sta/Elev= 30
  4370.0 1898.50  4389.1 1894.54  4409.1 1884.66  4439.1 1873.40  4479.2 1854.31
  4499.2 1846.93  4529.2 1840.98  4619.2 1830.34  4669.2 1819.73  4688.8 1817.64
  4709.2 1816.59  4749.2 1818.62  4779.2 1814.95  4826.2 1812.88  4849.2 1811.56
  4899.2 1805.30  4953.3 1802.90  4993.8 1798.98  4996.6 1798.48  4999.8 1798.98
  5017.7 1801.91  5075.9 1802.67  5132.1 1812.09  5161.2 1813.97  5174.5 1816.79
  5182.0 1818.73  5217.4 1820.03  5290.2 1829.99  5325.5 1832.29  5536.1 1834.54
#Mann=6,-1,0
  4370.0     0.1       0  4688.8    0.05       0  4826.2    0.16       0
  4993.8    0.07       0  4999.8    0.16       0  5174.5    0.05       0
Bank Sta=4993.8,4999.8
Exp/Cntr=0.3,0.1

Type RM Length L Ch R = 1,3793,351,351,351
BEGIN DESCRIPTION:
UNT 0030 IN HEWA 8.0
END DESCRIPTION:
XS GIS Cut Line= 3
      2731948.20     10079521.11      2731321.99     10079428.87
      2730603.47     10079652.20
#Sta/Elev= 30
  4193.9 1867.60  4254.3 1861.65  4279.2 1853.59  4284.6 1849.73  4314.9 1844.49
  4348.9 1840.95  4405.9 1832.94  4432.9 1831.89  4483.2 1826.08  4537.3 1821.65
  4552.9 1819.31  4622.6 1815.16  4648.5 1811.95  4719.2 1807.16  4762.0 1802.36
  4864.1 1798.80  4914.3 1797.25  4977.2 1798.77  4987.6 1798.21  4996.1 1796.36
  4998.9 1795.86  5002.1 1796.36  5019.1 1801.49  5026.4 1805.25  5034.0 1806.22
  5059.0 1810.54  5249.4 1825.52  5291.3 1825.47  5400.2 1828.35  5579.3 1828.41
#Mann=6,-1,0
  4193.9     0.1       0  4432.9    0.05       0  4864.1    0.16       0
  4996.1    0.07       0  5002.1    0.16       0  5034.0    0.05       0
Bank Sta=4996.1,5002.1
Exp/Cntr=0.3,0.1

Type RM Length L Ch R = 1,3442,160,160,160
BEGIN DESCRIPTION:
UNT 0030 IN HEWA 7.0
END DESCRIPTION:
XS GIS Cut Line= 3
      2731856.05     10079278.39      2731021.00     10079113.32
      2730559.83     10079346.33
#Sta/Elev= 30
  4344.6 1839.61  4382.9 1837.53  4413.5 1833.51  4511.9 1824.65  4535.8 1822.72
  4566.4 1818.49  4597.0 1817.42  4607.2 1817.44  4647.5 1811.47  4652.6 1812.76
  4668.3 1810.88  4703.9 1809.38  4719.3 1807.05  4760.3 1804.30  4811.5 1798.89
  4943.6 1794.77  4974.1 1795.44  5001.7 1792.82  5004.5 1792.32  5007.7 1792.82
  5012.0 1794.03  5055.7 1798.11  5114.0 1799.94  5170.4 1800.05  5276.4 1806.46
  5406.6 1820.19  5412.2 1819.84  5479.1 1824.21  5585.0 1825.81  5712.5 1826.03
#Mann=7,-1,0
  4344.6    0.05       0  4511.9     0.1       0  4597.0    0.16       0
  5001.7    0.07       0  5007.7    0.16       0  5012.0     0.1       0
  5276.4    0.05       0
Bank Sta=5001.7,5007.7
Exp/Cntr=0.3,0.1

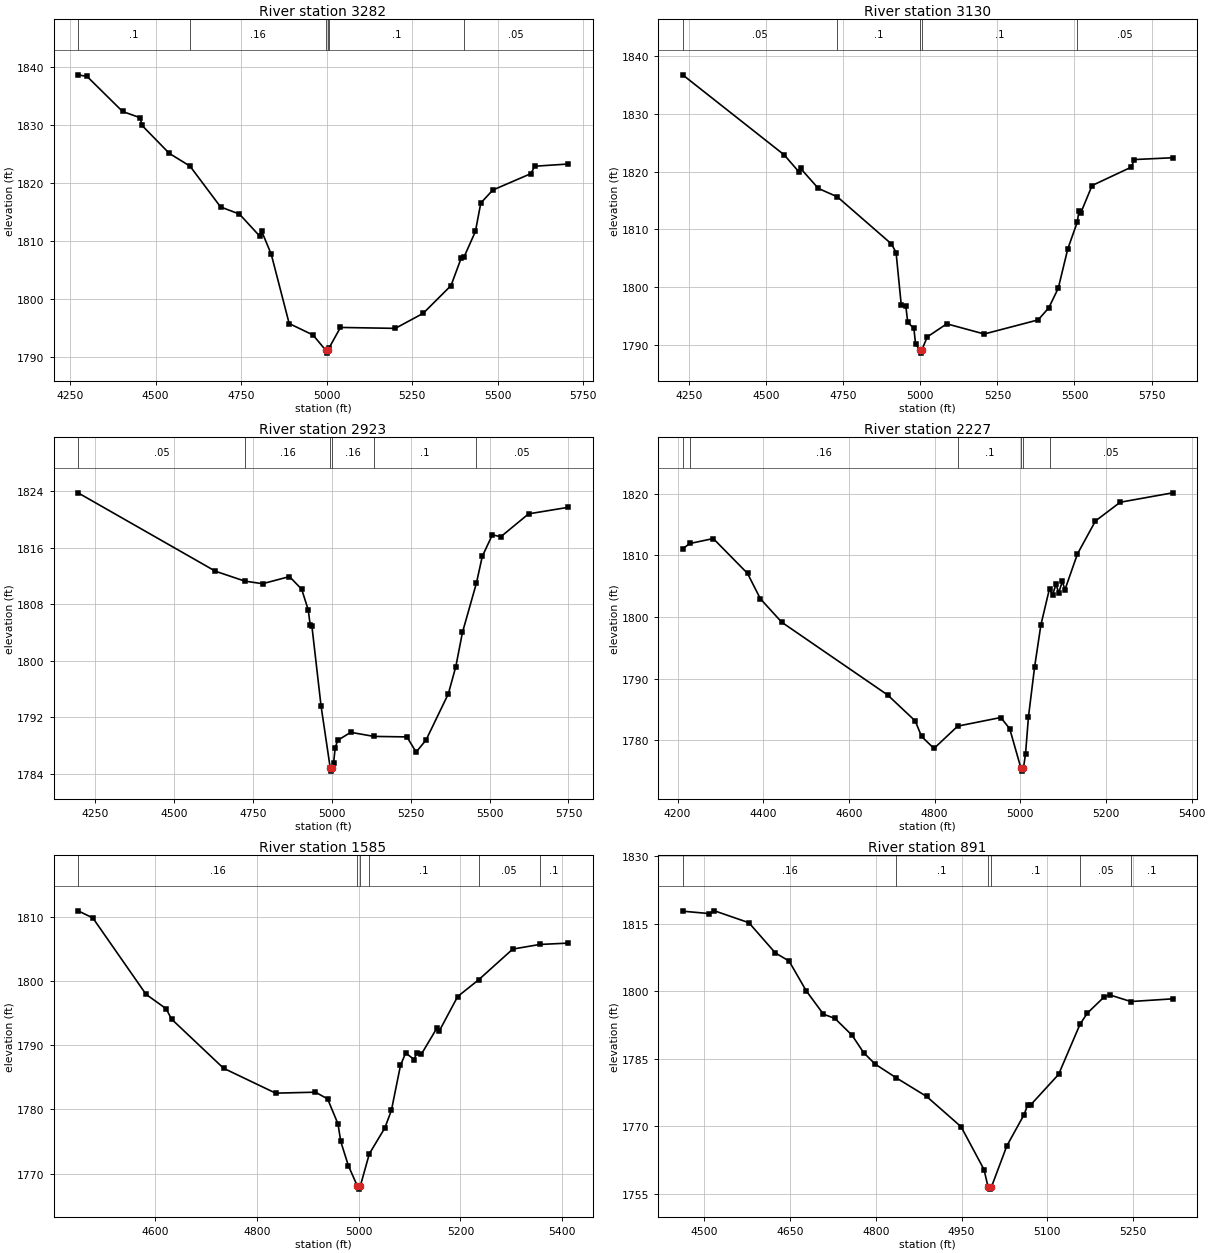
Type RM Length L Ch R = 1,3282,152,152,152
BEGIN DESCRIPTION:
Mapping XS 9c7b21cf
END DESCRIPTION:
XS GIS Cut Line= 3
      2731984.22     10079206.82      2731077.95     10078964.62
      2730592.25     10079055.53
#Sta/Elev= 30
  4273.1 1838.62  4299.5 1838.34  4403.3 1832.31  4454.6 1831.24  4459.8 1829.93
  4539.9 1825.10  4600.3 1822.91  4689.8 1815.88  4744.8 1814.66  4804.9 1810.81
  4810.0 1811.68  4838.0 1807.71  4890.2 1795.82  4959.9 1793.85  4997.0 1791.23
  4999.8 1790.73  5003.0 1791.23  5006.0 1791.54  5040.1 1795.15  5200.4 1794.99
  5281.9 1797.58  5363.2 1802.35  5392.6 1807.02  5401.9 1807.35  5434.5 1811.66
  5450.3 1816.56  5485.3 1818.79  5597.2 1821.63  5607.4 1822.89  5705.3 1823.27
#Mann=6,-1,0
  4273.1     0.1       0  4600.3    0.16       0  4997.0    0.07       0
  5003.0    0.16       0  5006.0     0.1       0  5401.9    0.05       0
Bank Sta=4997,5003
Exp/Cntr=0.3,0.1

Type RM Length L Ch R = 1,3130,207,207,207
BEGIN DESCRIPTION:
Mapping XS 37854b95
END DESCRIPTION:
XS GIS Cut Line= 3
      2732080.56     10079139.11      2731189.93     10078839.62
      2730557.14     10078988.06
#Sta/Elev= 30
  4228.9 1836.75  4558.2 1822.90  4606.1 1819.95  4611.4 1820.56  4669.1 1817.09
  4730.6 1815.64  4906.3 1807.48  4921.2 1806.00  4938.0 1796.91  4952.8 1796.71
  4959.1 1793.91  4979.0 1792.88  4984.3 1790.21  4998.3 1789.09  5001.0 1788.59
  5004.3 1789.09  5022.4 1791.40  5085.7 1793.66  5207.2 1791.90  5382.1 1794.34
  5416.6 1796.43  5447.4 1799.83  5478.2 1806.62  5509.1 1811.28  5514.5 1813.23
  5519.7 1812.77  5557.0 1817.59  5683.6 1820.76  5694.6 1822.09  5818.5 1822.40
#Mann=5,-1,0
  4228.9    0.05       0  4730.6     0.1       0  4998.3    0.07       0
  5004.3     0.1       0  5509.1    0.05       0
Bank Sta=4998.3,5004.3
Exp/Cntr=0.3,0.1

Type RM Length L Ch R = 1,2923,696,696,696
BEGIN DESCRIPTION:
UNT 0030 IN HEWA 6.0
END DESCRIPTION:
XS GIS Cut Line= 4
      2732028.48     10078891.71      2731398.27     10078670.35
      2730999.83     10078779.73      2730549.28     10078922.96
#Sta/Elev= 30
  4194.7 1823.78  4630.4 1812.67  4723.4 1811.27  4780.0 1810.90  4865.1 1811.91
  4903.9 1810.12  4924.7 1807.18  4931.0 1805.01  4936.2 1804.94  4965.4 1793.55
  4994.3 1784.84  4997.0 1784.34  5000.3 1784.84  5005.0 1785.49  5010.2 1787.63
  5018.0 1788.70  5059.5 1789.84  5133.0 1789.26  5237.6 1789.19  5266.9 1787.04
  5298.3 1788.75  5369.0 1795.30  5392.7 1799.15  5413.7 1803.99  5458.1 1810.99
  5476.6 1814.77  5508.5 1817.82  5535.5 1817.56  5623.5 1820.80  5748.6 1821.72
#Mann=6,-1,0
  4194.7    0.05       0  4723.4    0.16       0  4994.3    0.07       0
  5000.3    0.16       0  5133.0     0.1       0  5458.1    0.05       0
Bank Sta=4994.3,5000.3
Exp/Cntr=0.3,0.1

Type RM Length L Ch R = 1,2227,642,642,642
BEGIN DESCRIPTION:
UNT 0030 IN HEWA 4.0
END DESCRIPTION:
XS GIS Cut Line= 3
      2731559.87     10078409.40      2731098.68     10078409.40
      2730554.93     10078822.06
#Sta/Elev= 30
  4211.9 1811.10  4228.8 1811.95  4283.3 1812.75  4363.3 1807.09  4393.3 1802.96
  4443.3 1799.15  4690.4 1787.34  4754.8 1783.12  4769.4 1780.62  4798.5 1778.65
  4853.9 1782.28  4954.5 1783.68  4975.3 1781.86  5001.4 1775.47  5004.2 1774.97
  5007.4 1775.47  5012.3 1777.82  5019.0 1783.74  5033.5 1791.94  5048.1 1798.72
  5068.2 1804.63  5075.2 1803.58  5083.4 1805.34  5089.7 1803.92  5098.0 1805.79
  5104.3 1804.45  5133.4 1810.25  5175.5 1815.61  5233.2 1818.65  5355.7 1820.18
#Mann=6,-1,0
  4211.9    0.05       0  4228.8    0.16       0  4853.9     0.1       0
  5001.4    0.07       0  5007.4     0.1       0  5068.2    0.05       0
Bank Sta=5001.4,5007.4
Exp/Cntr=0.3,0.1

Type RM Length L Ch R = 1,1585,694,694,694
BEGIN DESCRIPTION:
UNT 0030 IN HEWA 3.0
END DESCRIPTION:
XS GIS Cut Line= 2
      2731618.14     10078205.51      2730676.34     10078006.47
#Sta/Elev= 30
  4448.8 1810.93  4477.8 1809.83  4582.4 1797.92  4621.9 1795.68  4632.4 1794.07
  4734.6 1786.41  4836.9 1782.53  4915.2 1782.68  4939.1 1781.63  4959.5 1777.73
  4964.9 1775.00  4979.9 1771.22  4997.4 1768.08  5000.1 1767.58  5003.4 1768.08
  5021.0 1773.08  5051.5 1777.11  5064.4 1779.85  5082.2 1786.84  5092.4 1788.79
  5109.0 1787.77  5114.1 1788.80  5123.0 1788.56  5153.6 1792.64  5158.7 1792.25
  5194.6 1797.58  5235.5 1800.17  5302.8 1804.97  5355.7 1805.69  5411.4 1805.90
#Mann=6,-1,0
  4448.8    0.16       0  4997.4    0.07       0  5003.4    0.16       0
  5021.0     0.1       0  5235.5    0.05       0  5355.7     0.1       0
Bank Sta=4997.4,5003.4
Exp/Cntr=0.3,0.1

Type RM Length L Ch R = 1,891,320,320,320
BEGIN DESCRIPTION:
UNT 0030 IN HEWA 2.0
END DESCRIPTION:
XS GIS Cut Line= 2
      2731593.90     10077559.84      2730739.48     10077501.58
#Sta/Elev= 30
  4462.5 1817.76  4508.0 1817.24  4518.1 1817.84  4578.2 1815.20  4624.5 1808.48
  4648.4 1806.70  4678.4 1800.08  4708.5 1794.88  4728.5 1793.95  4758.6 1790.19
  4778.7 1786.35  4798.7 1783.81  4835.8 1780.74  4888.9 1776.60  4949.1 1769.88
  4989.2 1760.36  4996.2 1756.52  4998.9 1756.02  5002.2 1756.52  5029.2 1765.66
  5059.3 1772.59  5065.6 1774.78  5070.6 1774.72  5119.5 1781.50  5157.0 1792.65
  5169.6 1795.09  5199.6 1798.77  5209.2 1799.15  5245.8 1797.69  5318.9 1798.29
#Mann=6,-1,0
  4462.5    0.16       0  4835.8     0.1       0  4996.2    0.07       0
  5002.2     0.1       0  5157.0    0.05       0  5245.8     0.1       0
Bank Sta=4996.2,5002.2
Exp/Cntr=0.3,0.1

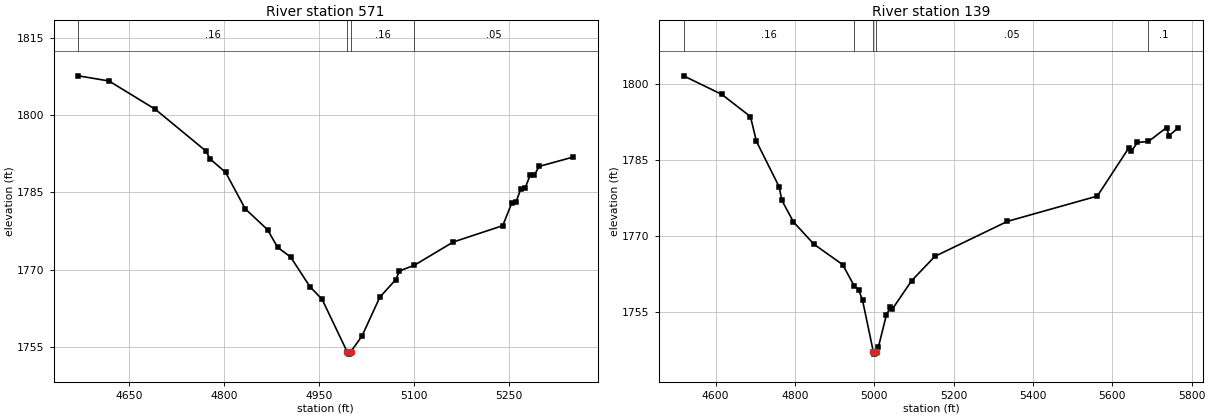
Type RM Length L Ch R = 1,571,432,432,432
BEGIN DESCRIPTION:
Mapping XS c8974acb
END DESCRIPTION:
XS GIS Cut Line= 3
      2731545.72     10077314.85      2731056.13     10077203.74
      2730837.61     10077378.90
#Sta/Elev= 30
  4569.3 1807.63  4617.8 1806.63  4691.0 1801.14  4771.6 1792.98  4777.2 1791.55
  4802.3 1788.87  4833.1 1781.83  4868.5 1777.76  4884.4 1774.34  4904.9 1772.46
  4935.6 1766.68  4954.7 1764.25  4994.2 1754.10  4996.9 1753.60  5000.2 1754.10
  5017.7 1757.08  5046.0 1764.66  5071.3 1768.07  5077.0 1769.75  5100.6 1770.85
  5161.9 1775.36  5240.3 1778.54  5254.7 1782.97  5261.1 1783.09  5269.1 1785.75
  5275.5 1785.78  5283.5 1788.29  5289.9 1788.29  5297.9 1790.05  5351.4 1791.85
#Mann=4,-1,0
  4569.3    0.16       0  4994.2    0.07       0  5000.2    0.16       0
  5100.6    0.05       0
Bank Sta=4994.2,5000.2
Exp/Cntr=0.3,0.1

Type RM Length L Ch R = 1,139,0,0,0
BEGIN DESCRIPTION:
UNT 0030 IN HEWA 1.0
END DESCRIPTION:
XS GIS Cut Line= 4
      2731535.29     10077130.82      2731323.49     10076807.91
      2731165.51     10076797.49      2730800.91     10077398.20
#Sta/Elev= 30
  4519.1 1801.67  4615.4 1798.00  4687.8 1793.60  4702.9 1788.69  4760.1 1779.71
  4766.8 1777.05  4796.3 1772.75  4847.6 1768.35  4920.3 1764.30  4949.9 1760.01
  4960.4 1759.38  4970.4 1757.23  4997.5 1747.09  5000.3 1746.59  5003.5 1747.09
  5010.5 1748.04  5030.6 1754.38  5040.1 1755.83  5045.2 1755.47  5094.3 1761.14
  5152.8 1765.94  5335.7 1772.87  5562.2 1777.87  5642.0 1787.45  5647.8 1786.73
  5663.3 1788.48  5691.2 1788.68  5737.0 1791.44  5742.8 1789.80  5766.3 1791.39
#Mann=5,-1,0
  4519.1    0.16       0  4949.9    0.05       0  4997.5    0.04       0
  5003.5    0.05       0  5691.2     0.1       0
Bank Sta=4997.5,5003.5
Exp/Cntr=0.3,0.1

Chan Stop Cuts=-1