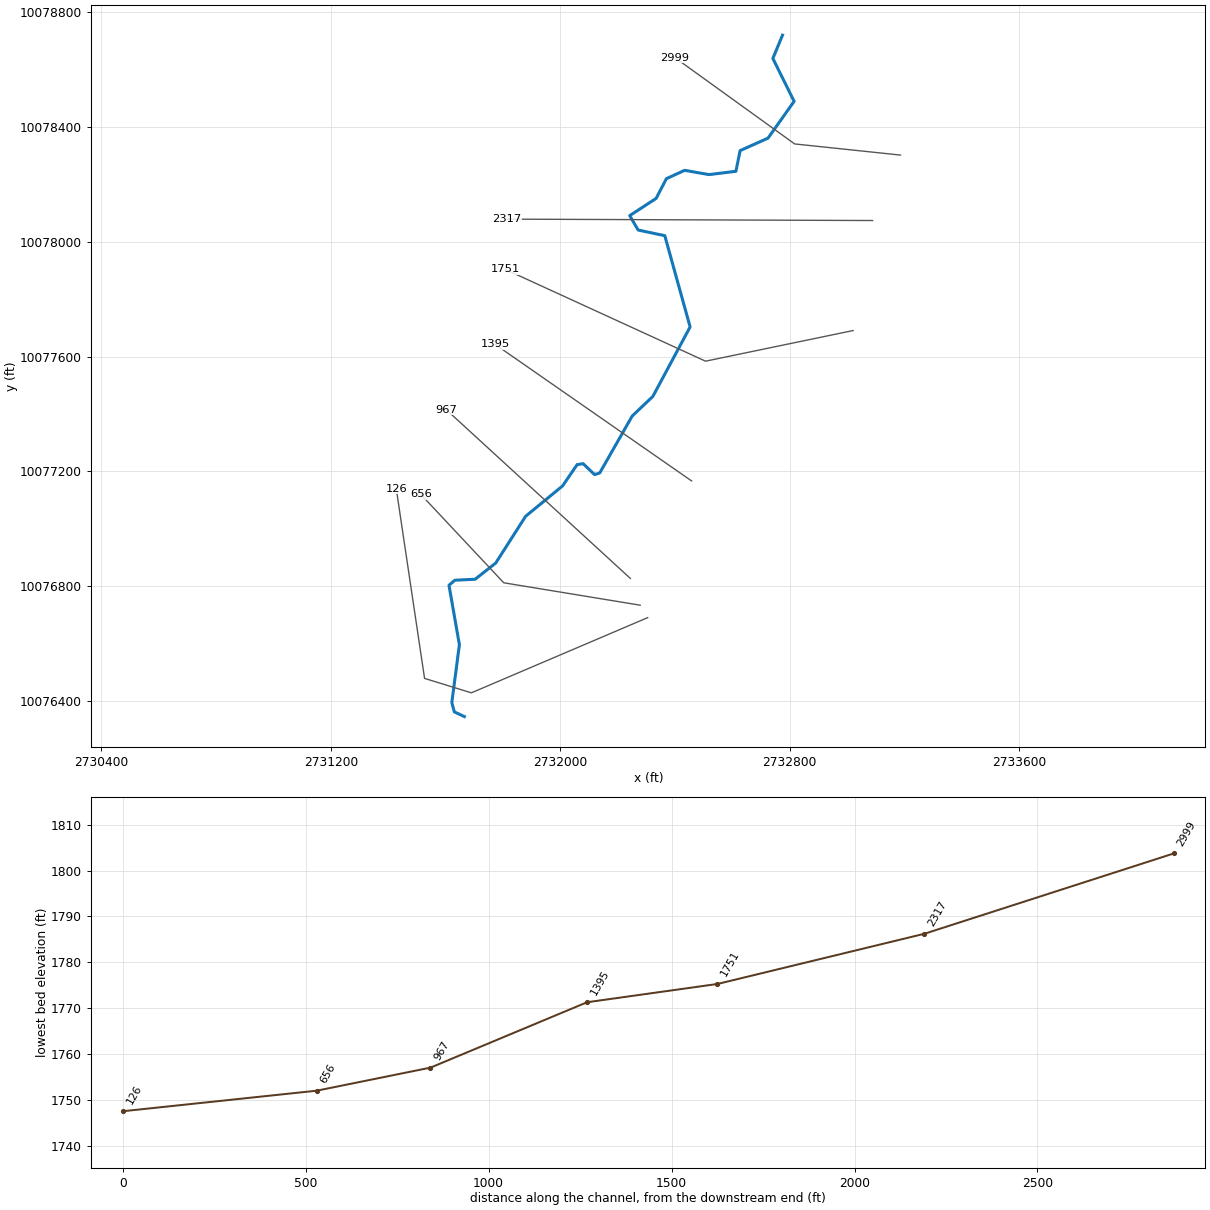
--- UNT 0031 IN HEWA.prj (project) ---

Proj Title=UNT 0031 IN HEWA Base Level Engineering
Current Plan=p01
Default Exp/Contr=0.3,0.1
English Units
Geom File=g01
Flow File=f01
Plan File=p01
Y Axis Title=Elevation
X Axis Title(PF)=Main Channel Distance
X Axis Title(XS)=Station
BEGIN DESCRIPTION:
UNT 0031 IN HEWA
END DESCRIPTION:
DSS Export Rating Curves= 0
DSS Export Rating Curve Sorted= 0
DSS Export Volume Flow Curves= 0
DXF OffsetX= 0
DXF OffsetY= 0
DXF ScaleX= 1
DXF ScaleY= 10

--- UNT 0031 IN HEWA.p01 (plan) ---

Plan Title=Multiple Run
Short Identifier=Multiple
Geom File=g01
Flow File=f01
Subcritical Flow
K Sum by GR= 0
Std Step Tol= 0.01
Critical Tol= 0.01
Num of Std Step Trials= 20
Max Error Tol= 0.3
Flow Tol Ratio= 0.001
Split Flow NTrial= 30
Split Flow Tol= 0.02
Split Flow Ratio= 0.02
Log Output Level= 0
Friction Slope Method= 1
Unsteady Friction Slope Method= 2
Unsteady Bridges Friction Slope Method= 1
Parabolic Critical Depth
Global Vel Dist=  1 , 1 , 1
Global Log Level= 0
CheckData=True
Encroach Param= -1, 0, 0, 0
BEGIN DESCRIPTION:
Multiple Run
END DESCRIPTION:

--- UNT 0031 IN HEWA.f01 (steady flow) ---

Flow Title=Multiple
Program Version=4.10
Number of Profiles= 7
Profile Names=10-year,25-year,50-year,1pct_min,100-year,1pct_plu,500-year
River Rch & RM=UNT 0031 IN HEWA,Reach-1         ,2999
     470     662     825     754    1020    1380    1565
Boundary for River Rch & Prof#=UNT 0031 IN HEWA,Reach-1         , 1
Up Type= 0
Dn Type= 3
Dn Slope=0.008
Boundary for River Rch & Prof#=UNT 0031 IN HEWA,Reach-1         , 2
Up Type= 0
Dn Type= 3
Dn Slope=0.008
Boundary for River Rch & Prof#=UNT 0031 IN HEWA,Reach-1         , 3
Up Type= 0
Dn Type= 3
Dn Slope=0.008
Boundary for River Rch & Prof#=UNT 0031 IN HEWA,Reach-1         , 4
Up Type= 0
Dn Type= 3
Dn Slope=0.008
Boundary for River Rch & Prof#=UNT 0031 IN HEWA,Reach-1         , 5
Up Type= 0
Dn Type= 3
Dn Slope=0.008
Boundary for River Rch & Prof#=UNT 0031 IN HEWA,Reach-1         , 6
Up Type= 0
Dn Type= 3
Dn Slope=0.008
Boundary for River Rch & Prof#=UNT 0031 IN HEWA,Reach-1         , 7
Up Type= 0
Dn Type= 3
Dn Slope=0.008
DSS Import GetInterval= 0
DSS Import GetPeak= 0
DSS Import FillOption= 0

--- UNT 0031 IN HEWA.g01 (geometry) ---

Geom Title=Existing Conditions
Program Version=4.10

River Reach=UNT 0031 IN HEWA,Reach-1
Reach XY= 30
      2732774.91     10078720.76      2732741.24     10078639.47
      2732815.38     10078489.95      2732724.43     10078361.74
      2732627.09     10078318.14      2732612.46     10078246.04
      2732518.47     10078234.53      2732433.59     10078249.49
      2732369.92     10078220.08      2732334.31     10078151.55
      2732242.14     10078091.48      2732271.63     10078041.28
      2732364.49     10078021.62      2732452.77     10077703.54
      2732322.91     10077461.28      2732250.81     10077392.84
      2732137.56     10077194.32      2732119.65     10077188.68
      2732079.77     10077226.86      2732058.76     10077223.31
      2732007.94       10077149.      2731879.29     10077043.39
      2731775.21     10076880.49      2731703.25     10076823.87
      2731632.52     10076820.53      2731612.16      10076802.8
      2731648.41     10076595.61      2731622.01     10076393.94
      2731630.75     10076361.46      2731665.75     10076345.09

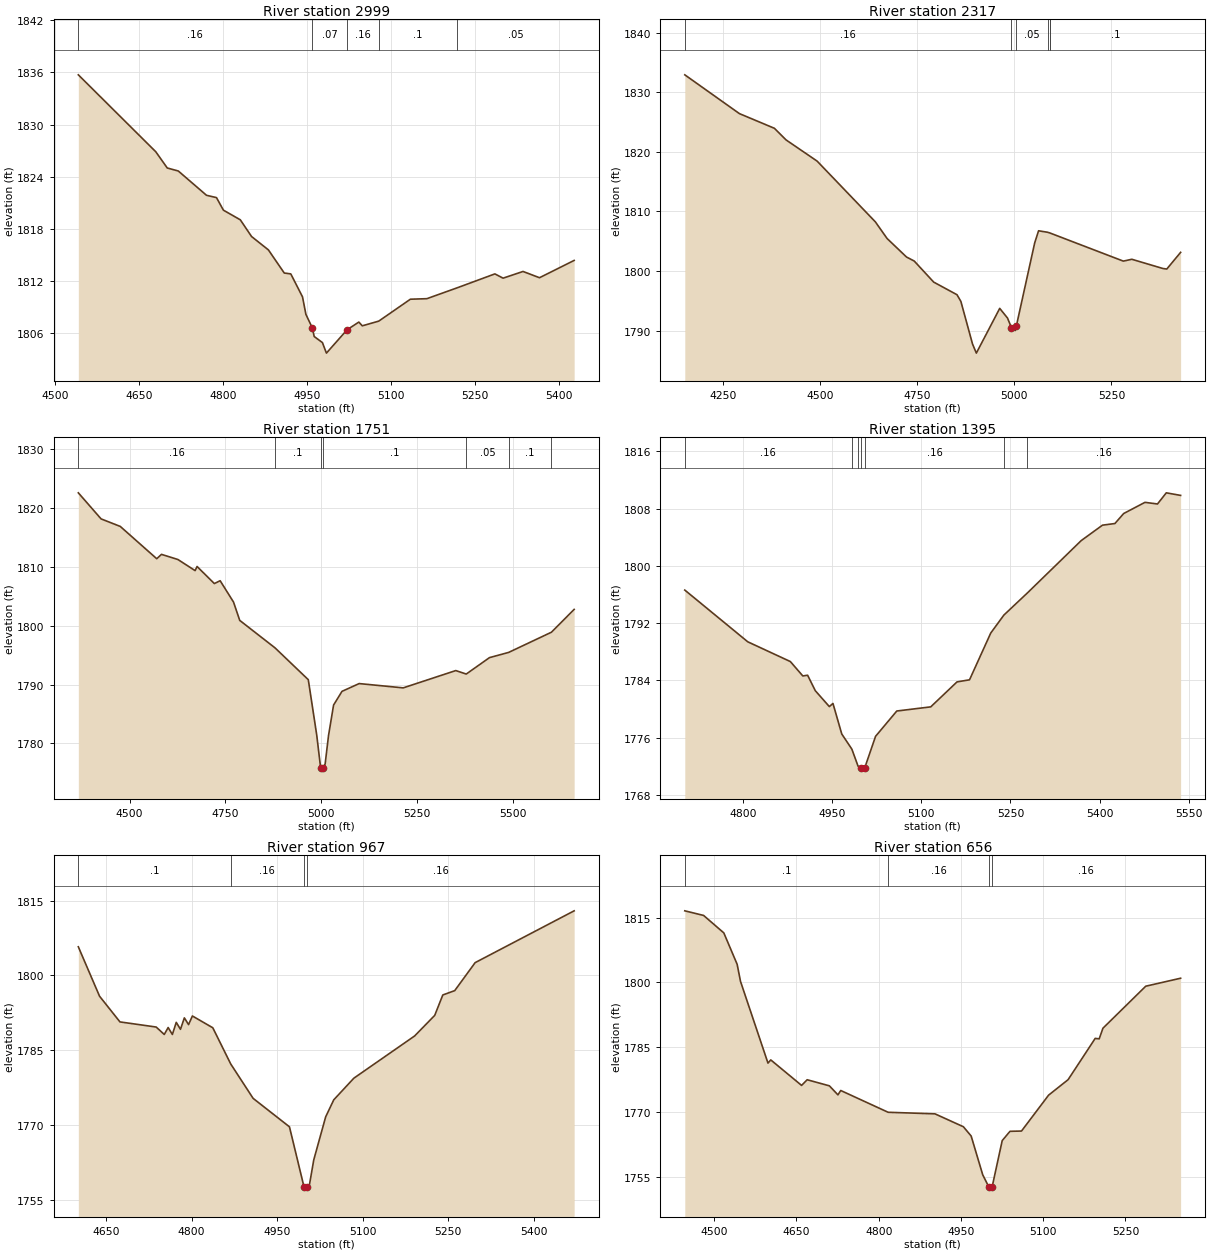
Type RM Length L Ch R = 1 ,2999    ,682,682,682
BEGIN DESCRIPTION:
UNT 0031 IN HEWA 6.0
END DESCRIPTION:
XS GIS Cut Line= 3
      2733186.13      10078302.6      2732817.22     10078341.43
      2732399.75      10078642.4
#Sta/Elev= 30
  4541.9 1835.72  4680.3 1826.87  4700.7 1825.01  4720.5 1824.66  4770.8 1821.87
  4788.7  1821.6    4801 1820.16  4831.2 1819.05  4851.3 1817.13  4881.4 1815.59
  4909.7 1812.93  4921.4 1812.83  4942.3 1810.19  4948.4 1808.17 4959.63 1806.65
  4963.2 1805.63  4977.9 1804.93    4985 1803.72    5022 1806.41  5042.9 1807.29
  5049.1 1806.86  5078.5  1807.4    5135 1809.92  5164.4 1809.98    5219 1811.24
  5285.9 1812.83  5300.6 1812.34  5336.2 1813.11  5365.6 1812.39  5427.5 1814.38
#Mann= 5 ,-1 , 0
  4541.9     .16       0 4959.63     .07       0    5022     .16       0
  5078.5      .1       0    5219     .05       0
Bank Sta=4959.63,5022
XS Rating Curve= 0 ,0
Exp/Cntr=0.3,0.1

Type RM Length L Ch R = 1 ,2317    ,566,566,566
BEGIN DESCRIPTION:
UNT 0031 IN HEWA 5.0
END DESCRIPTION:
XS GIS Cut Line= 2
      2733089.06     10078074.43      2731812.87     10078079.28
#Sta/Elev= 30
  4151.9 1832.93  4292.5 1826.42  4382.5 1823.96  4412.5 1822.01  4492.5 1818.45
  4642.5 1808.25  4672.5 1805.47  4722.5 1802.36  4742.5 1801.68  4792.5 1798.15
  4852.5 1796.03  4862.5 1794.91  4892.5 1787.76  4902.3 1786.23  4962.5 1793.74
  4982.5 1792.12  4992.5 1790.53  4992.7 1790.52  5002.5 1790.02 5005.09 1790.72
  5052.5 1804.73  5062.5 1806.76  5085.8 1806.51  5091.4  1806.4  5091.7 1806.39
  5280.6 1801.67  5302.5 1801.98  5382.5 1800.43  5392.5 1800.34  5428.1 1803.14
#Mann= 6 ,-1 , 0
  4151.9     .16       0  4992.5    .035       0 5005.09     .05       0
  5085.8      .1       0  5091.4     .05       0  5091.7      .1       0
Bank Sta=4992.7,5005.09
XS Rating Curve= 0 ,0
Exp/Cntr=0.3,0.1

Type RM Length L Ch R = 1 ,1751    ,356,356,356
BEGIN DESCRIPTION:
UNT 0031 IN HEWA 4.0
END DESCRIPTION:
XS GIS Cut Line= 3
      2733021.07      10077690.9      2732506.52     10077584.11
      2731807.46     10077904.51
#Sta/Elev= 30
  4366.1  1822.6  4425.5 1818.17  4475.6 1816.89  4570.8  1811.4  4583.2 1812.14
    4626 1811.27    4671 1809.38  4676.1 1810.08  4721.2 1807.18  4736.4 1807.66
  4771.3 1804.03  4787.5 1800.92  4879.6 1796.25  4966.5 1790.84  4988.5 1781.44
  4998.8  1775.8  5001.6  1775.3  5004.8  1775.8  5010.5 1776.53  5019.3 1781.34
  5032.5 1786.53  5054.5 1788.86  5099.3 1790.18  5214.3 1789.45  5351.5 1792.39
  5378.9  1791.8  5439.5 1794.59  5489.7 1795.48  5601.3 1798.91  5660.6 1802.79
#Mann= 7 ,-1 , 0
  4366.1     .16       0  4879.6      .1       0  4998.8     .07       0
  5004.8      .1       0  5378.9     .05       0  5489.7      .1       0
  5601.3     .05       0
Bank Sta=4998.8,5004.8
XS Rating Curve= 0 ,0
Exp/Cntr=0.3,0.1

Type RM Length L Ch R = 1 ,1395    ,428,428,428
BEGIN DESCRIPTION:
UNT 0031 IN HEWA 3.0
END DESCRIPTION:
XS GIS Cut Line= 2
      2732458.01     10077166.59       2731773.5     10077642.34
#Sta/Elev= 30
  4702.5 1796.63  4808.4  1789.4    4880 1786.64  4900.9 1784.63    4909 1784.73
  4921.9 1782.57  4945.5 1780.35  4951.6 1780.79  4966.4 1776.52  4983.4  1774.4
  4993.8 1772.02  4999.2 1771.83    5002 1771.33  5005.2 1771.83  5023.2 1776.19
  5058.9 1779.73    5116 1780.31  5160.2  1783.8  5181.2 1784.09  5216.9 1790.63
    5239 1793.14  5278.5 1796.23  5368.9 1803.54  5404.7  1805.7  5425.6 1805.93
  5440.4 1807.33  5476.2 1808.89  5497.2 1808.66    5512 1810.22  5536.1 1809.86
#Mann= 7 ,-1 , 0
  4702.5     .16       0  4983.4      .1       0  4993.8     .16       0
  4999.2     .07       0  5005.2     .16       0    5239      .1       0
  5278.5     .16       0
Bank Sta=4999.2,5005.2
XS Rating Curve= 0 ,0
Exp/Cntr=0.3,0.1

Type RM Length L Ch R = 1 ,967     ,311,311,311
BEGIN DESCRIPTION:
UNT 0031 IN HEWA 2.0
END DESCRIPTION:
XS GIS Cut Line= 2
      2732244.41     10076826.75      2731603.52     10077414.23
#Sta/Elev= 30
  4601.5 1805.75  4638.7 1795.83  4674.5 1790.67    4738 1789.64  4752.2 1788.15
    4759 1789.54  4766.4 1788.15  4773.2 1790.58  4780.6 1789.18  4787.4 1791.48
  4794.8 1790.13  4801.5 1791.86  4837.3 1789.49  4868.7 1782.23    4908 1775.32
  4971.7 1769.61  4997.1  1757.6  4999.8  1757.1  5003.1  1757.6  5006.9 1758.07
  5014.3 1762.97  5035.2 1771.61  5049.4 1775.03  5084.6 1779.37  5191.2 1787.85
  5226.4 1791.98  5240.6 1796.08  5261.5 1796.95  5297.3 1802.57  5470.9 1812.97
#Mann= 4 ,-1 , 0
  4601.5      .1       0  4868.7     .16       0  4997.1     .07       0
  5003.1     .16       0
Bank Sta=4997.1,5003.1
XS Rating Curve= 0 ,0
Exp/Cntr=0.3,0.1

Type RM Length L Ch R = 1 ,656     ,530,530,530
BEGIN DESCRIPTION:
Mapping XS b2f63289
END DESCRIPTION:
XS GIS Cut Line= 3
      2732278.68      10076733.4      2731803.01     10076811.52
      2731514.09     10077119.47
#Sta/Elev= 30
  4446.3 1816.58  4480.6 1815.51  4517.5 1811.46  4541.8 1804.18  4547.9 1800.23
    4598 1781.29  4603.1 1782.03  4659.3 1776.12  4669.5 1777.43    4710 1776.02
  4725.6 1773.93  4730.7 1774.94  4817.2 1769.89  4902.5 1769.53  4954.4 1766.54
  4968.6 1764.38  4989.6 1755.43  5000.8 1752.58  5003.5 1752.08  5006.8 1752.58
  5025.2 1763.32  5039.4 1765.48  5060.4 1765.54  5109.8 1773.86  5145.4 1777.45
  5194.8 1787.01  5202.1 1786.91  5208.9 1789.37    5287 1799.11  5350.6 1800.96
#Mann= 4 ,-1 , 0
  4446.3      .1       0  4817.2     .16       0  5000.8     .07       0
  5006.8     .16       0
Bank Sta=5000.8,5006.8
XS Rating Curve= 0 ,0
Exp/Cntr=0.3,0.1

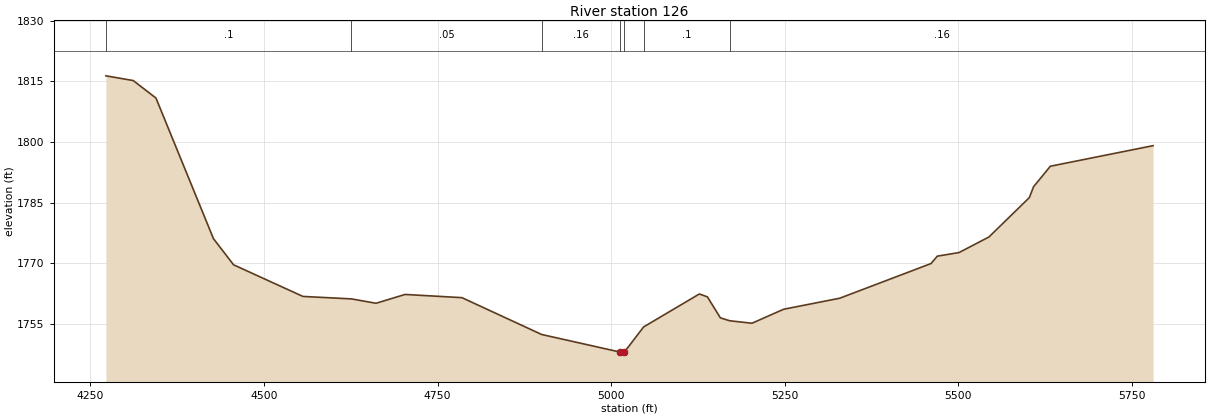
Type RM Length L Ch R = 1 ,126     ,0,0,0
BEGIN DESCRIPTION:
UNT 0031 IN HEWA 1.0
END DESCRIPTION:
XS GIS Cut Line= 4
      2732304.74     10076689.99      2731690.17     10076427.84
      2731526.97     10076478.19      2731428.22     10077140.02
#Sta/Elev= 30
  4272.3 1816.35  4311.7 1815.18  4344.4 1810.86  4427.2 1776.13  4456.2 1769.67
  4556.1 1761.86    4626 1761.25  4661.4 1760.17  4703.1 1762.35    4785 1761.56
  4899.9 1752.46    5013 1748.11  5015.8 1747.61    5019 1748.11  5046.7 1754.32
    5127 1762.47  5138.6 1761.75  5157.3 1756.56  5170.7 1755.85  5202.8 1755.24
  5248.3 1758.69  5329.2 1761.42  5460.6 1769.98  5469.7 1771.81    5501  1772.7
    5544 1776.54  5602.2 1786.26  5608.3 1788.95  5632.5 1794.02  5780.4  1799.1
#Mann= 7 ,-1 , 0
  4272.3      .1       0    4626     .05       0  4899.9     .16       0
    5013     .07       0    5019     .16       0  5046.7      .1       0
  5170.7     .16       0
Bank Sta=5013,5019
XS Rating Curve= 0 ,0
Exp/Cntr=0.3,0.1

Chan Stop Cuts=-1
Use User Specified Reach Order=0
Composite Channel Slope=5