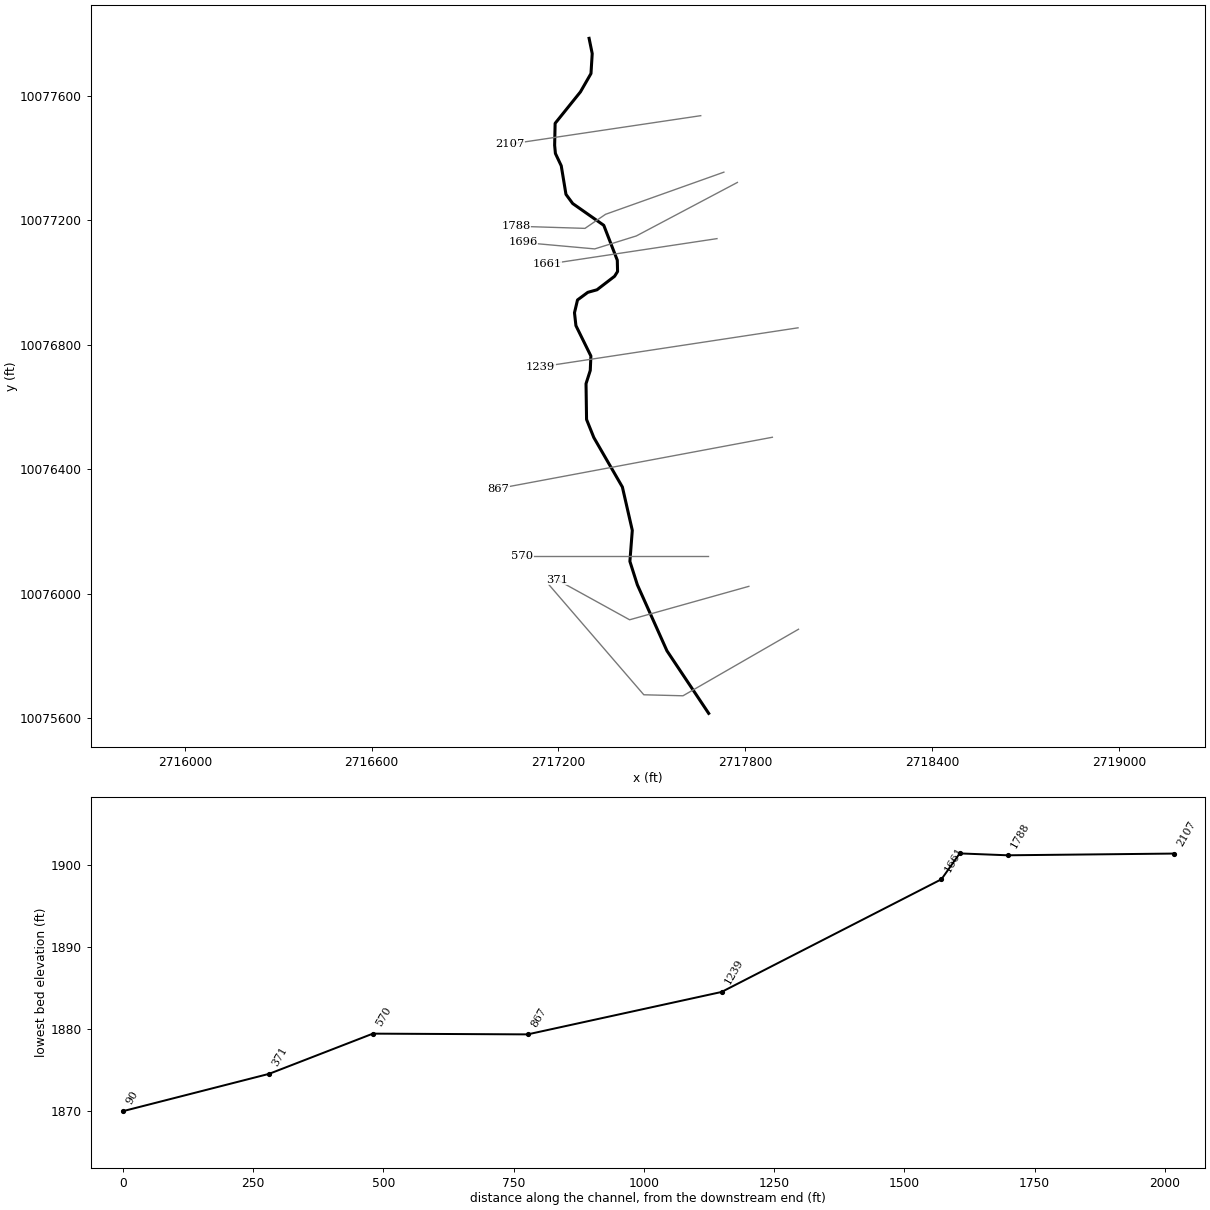
--- UNT 0033 IN HEWA.prj (project) ---

Proj Title=UNT 0033 IN HEWA Base Level Engineering
Current Plan=p01
Default Exp/Contr=0.3,0.1
English Units
Geom File=g01
Flow File=f01
Plan File=p01
Y Axis Title=Elevation
X Axis Title(PF)=Main Channel Distance
X Axis Title(XS)=Station
BEGIN DESCRIPTION:
UNT 0033 IN HEWA
END DESCRIPTION:
DSS Export Rating Curves= 0
DSS Export Rating Curve Sorted= 0
DSS Export Volume Flow Curves= 0
DXF OffsetX= 0
DXF OffsetY= 0
DXF ScaleX= 1
DXF ScaleY= 10

--- UNT 0033 IN HEWA.p01 (plan) ---

Plan Title=Multiple Run
Short Identifier=Multiple
Geom File=g01
Flow File=f01
Subcritical Flow
K Sum by GR= 0
Std Step Tol= 0.01
Critical Tol= 0.01
Num of Std Step Trials= 20
Max Error Tol= 0.3
Flow Tol Ratio= 0.001
Split Flow NTrial= 30
Split Flow Tol= 0.02
Split Flow Ratio= 0.02
Log Output Level= 0
Friction Slope Method= 1
Unsteady Friction Slope Method= 2
Unsteady Bridges Friction Slope Method= 1
Parabolic Critical Depth
Global Vel Dist=  1 , 1 , 1
Global Log Level= 0
CheckData=True
Encroach Param= -1, 0, 0, 0
BEGIN DESCRIPTION:
Multiple Run
END DESCRIPTION:

--- UNT 0033 IN HEWA.f01 (steady flow) ---

Flow Title=Multiple
Number of Profiles=7
Profile Names=10-year,25-year,50-year,1pct_min,100-year,1pct_plu,500-year
River Rch & RM= UNT 0033 IN HEWA,Reach-1,2107
    1101    1610    2054    1912    2585    3496    4103
Boundary for River Rch & Prof#=UNT 0033 IN HEWA,Reach-1,1
Up Type=0
Dn Type=3
Dn Slope=0.005
Boundary for River Rch & Prof#=UNT 0033 IN HEWA,Reach-1,2
Up Type=0
Dn Type=3
Dn Slope=0.005
Boundary for River Rch & Prof#=UNT 0033 IN HEWA,Reach-1,3
Up Type=0
Dn Type=3
Dn Slope=0.005
Boundary for River Rch & Prof#=UNT 0033 IN HEWA,Reach-1,4
Up Type=0
Dn Type=3
Dn Slope=0.005
Boundary for River Rch & Prof#=UNT 0033 IN HEWA,Reach-1,5
Up Type=0
Dn Type=3
Dn Slope=0.005
Boundary for River Rch & Prof#=UNT 0033 IN HEWA,Reach-1,6
Up Type=0
Dn Type=3
Dn Slope=0.005
Boundary for River Rch & Prof#=UNT 0033 IN HEWA,Reach-1,7
Up Type=0
Dn Type=3
Dn Slope=0.005

--- UNT 0033 IN HEWA.g01 (geometry) ---

Geom Title=Existing Conditions
Program Version=4.10

River Reach=UNT 0033 IN HEWA,Reach-1
Reach XY= 30
      2717298.47     10077783.73      2717308.48     10077734.66
      2717304.54     10077670.68      2717270.64     10077611.69
      2717189.35     10077510.66      2717187.81     10077440.11
      2717190.29     10077413.88        2717209.     10077374.39
       2717224.2     10077282.56      2717245.82     10077253.09
      2717345.62      10077183.1      2717389.07     10077070.99
      2717389.94     10077034.76      2717380.35     10077019.45
       2717323.8     10076976.02      2717294.38     10076967.86
      2717261.26     10076943.37      2717251.55     10076902.24
      2717256.17     10076860.84      2717304.21     10076763.32
      2717302.25     10076717.02      2717288.62     10076674.38
      2717290.34     10076559.35      2717313.74      10076501.2
       2717405.4     10076342.46      2717437.25     10076203.27
      2717429.52     10076103.61      2717453.42     10076028.56
      2717548.59     10075816.23      2717682.61     10075615.39

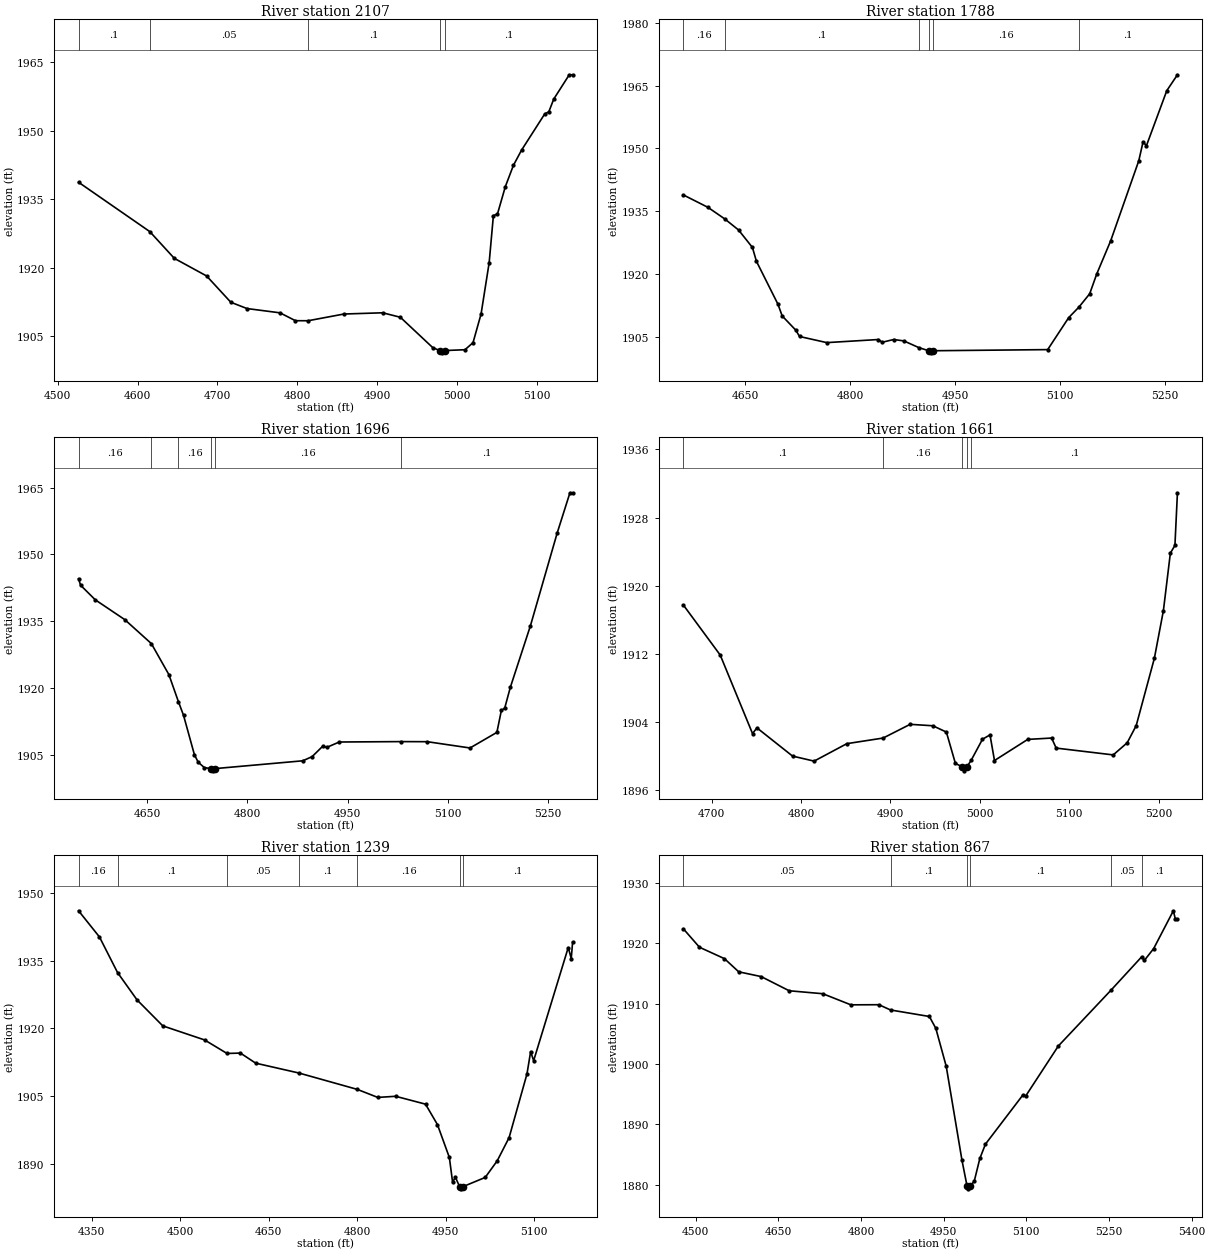
Type RM Length L Ch R = 1 ,2107    ,319,319,319
BEGIN DESCRIPTION:
UNT 0033 IN HEWA 5.0
END DESCRIPTION:
XS GIS Cut Line= 2
      2717657.09      10077535.3      2717045.14     10077444.16
#Sta/Elev= 30
  4526.1 1938.72  4615.3 1927.93    4646 1922.08  4686.5 1918.22  4716.8 1912.47
    4737  1911.1  4778.4 1910.16  4797.7 1908.44  4813.5 1908.43  4858.4  1909.9
    4907 1910.17  4929.1 1909.19  4969.6 1902.56  4978.4 1901.91  4981.1 1901.41
  4984.4 1901.91    5010 1902.09  5020.1 1903.64  5030.2 1909.93  5040.3 1921.13
  5045.6 1931.42  5050.7 1931.78  5060.6 1937.79  5070.7 1942.43  5080.8 1945.73
  5109.9 1953.67    5115 1954.13  5121.2 1956.92  5140.6 1962.23  5144.8 1962.23
#Mann= 5 ,-1 , 0
  4526.1      .1       0  4615.3     .05       0  4813.5      .1       0
  4978.4     .07       0  4984.4      .1       0
Bank Sta=4978.4,4984.4
XS Rating Curve= 0 ,0
Exp/Cntr=0.3,0.1

Type RM Length L Ch R = 1 ,1788    ,92,92,92
BEGIN DESCRIPTION:
Mapping XS 1e969400
END DESCRIPTION:
XS GIS Cut Line= 4
      2717731.39     10077353.84      2717351.23     10077218.44
      2717285.26      10077173.3      2717063.26     10077180.24
#Sta/Elev= 30
  4562.1 1938.88  4597.1 1935.93  4621.1 1933.17  4640.9 1930.52  4660.7 1926.35
  4666.4 1923.06  4697.2 1912.79  4703.2 1910.01  4722.7  1906.6    4728  1905.1
  4766.9 1903.64  4840.7 1904.38    4846 1903.72  4862.4 1904.38  4876.9 1904.05
  4898.5 1902.44  4912.5  1901.7  4915.3  1901.2  4918.5  1901.7  5082.4 1901.97
  5112.4  1909.6  5127.1 1912.13  5142.4  1915.3  5152.4    1920  5172.4 1927.95
  5212.5 1947.04  5218.5 1951.48  5223.5 1950.67  5252.5 1963.77  5267.7 1967.56
#Mann= 6 ,-1 , 0
  4562.1     .16       0  4621.1      .1       0  4898.5     .16       0
  4912.5     .07       0  4918.5     .16       0  5127.1      .1       0
Bank Sta=4912.5,4918.5
XS Rating Curve= 0 ,0
Exp/Cntr=0.3,0.1

Type RM Length L Ch R = 1 ,1696    ,35,35,35
BEGIN DESCRIPTION:
Mapping XS 5a643737
END DESCRIPTION:
XS GIS Cut Line= 4
      2717774.83     10077320.86      2717450.19     10077148.99
      2717316.51     10077107.33       2717085.6     10077128.16
#Sta/Elev= 30
  4547.3 1944.53  4550.3 1943.09  4572.3 1939.81  4616.4 1935.37  4656.2 1929.99
  4682.4 1923.04  4696.8 1916.91  4704.4 1913.87  4720.7 1905.02  4726.4 1903.35
  4735.5 1902.16  4745.4 1901.93  4748.1 1901.43  4751.4 1901.93  4882.6 1903.68
  4896.7 1904.61  4912.8 1906.98  4918.6 1906.69  4937.4  1907.9  5029.5 1907.99
    5069 1907.97    5133 1906.56  5173.2 1910.06  5179.9 1914.98  5184.9 1915.49
  5193.3 1920.16  5223.4 1933.99  5263.5 1954.84  5282.5 1963.83  5286.5 1963.83
#Mann= 6 ,-1 , 0
  4547.3     .16       0  4656.2      .1       0  4696.8     .16       0
  4745.4     .07       0  4751.4     .16       0  5029.5      .1       0
Bank Sta=4745.4,4751.4
XS Rating Curve= 0 ,0
Exp/Cntr=0.3,0.1

Type RM Length L Ch R = 1 ,1661    ,422,422,422
BEGIN DESCRIPTION:
UNT 0033 IN HEWA 4.0
END DESCRIPTION:
XS GIS Cut Line= 2
      2717709.24     10077140.35      2717162.92     10077057.97
#Sta/Elev= 30
  4668.4 1917.73  4709.6 1911.86  4745.7 1902.65  4750.7 1903.31  4790.5    1900
  4814.6 1899.41  4851.2 1901.46  4891.8 1902.12    4922 1903.73  4947.4 1903.56
  4962.5 1902.82  4972.6 1899.14  4979.7 1898.77  4982.4 1898.27  4985.7 1898.77
  4990.4 1899.54  5002.9 1901.98  5011.3 1902.49  5016.3 1899.48  5053.5 1901.96
  5080.2 1902.12  5085.3 1900.94  5149.1 1900.14  5164.7 1901.56  5174.8 1903.58
  5195.1 1911.48  5205.2 1917.07    5213 1923.83  5218.1 1924.73  5220.9 1930.91
#Mann= 5 ,-1 , 0
  4668.4      .1       0  4891.8     .16       0  4979.7     .07       0
  4985.7     .16       0  4990.4      .1       0
Bank Sta=4979.7,4985.7
XS Rating Curve= 0 ,0
Exp/Cntr=0.3,0.1

Type RM Length L Ch R = 1 ,1239    ,372,372,372
BEGIN DESCRIPTION:
UNT 0033 IN HEWA 3.0
END DESCRIPTION:
XS GIS Cut Line= 2
       2717969.6     10076853.88      2717142.08     10076728.24
#Sta/Elev= 30
  4327.8 1946.03  4363.2 1940.24  4393.8 1932.37  4426.9 1926.31  4470.5 1920.56
  4541.3 1917.45  4579.3 1914.46    4602 1914.54  4627.9 1912.31  4701.1 1910.13
  4800.2  1906.5  4834.7 1904.73    4865 1904.98  4915.6 1903.24  4935.8 1898.72
    4956 1891.44  4961.4 1886.05  4966.4 1887.02  4973.3    1885    4976  1884.5
  4979.3    1885  5016.7 1887.02    5037 1890.68  5057.2 1895.83  5087.5 1909.93
  5093.7 1914.86  5098.8 1912.86  5157.4  1937.9  5162.5 1935.47  5164.8 1939.09
#Mann= 7 ,-1 , 0
  4327.8     .16       0  4393.8      .1       0  4579.3     .05       0
  4701.1      .1       0  4800.2     .16       0  4973.3     .07       0
  4979.3      .1       0
Bank Sta=4973.3,4979.3
XS Rating Curve= 0 ,0
Exp/Cntr=0.3,0.1

Type RM Length L Ch R = 1 ,867     ,297,297,297
BEGIN DESCRIPTION:
UNT 0033 IN HEWA 2.0
END DESCRIPTION:
XS GIS Cut Line= 2
      2717887.19     10076502.33      2717006.09     10076337.39
#Sta/Elev= 30
  4477.7 1922.39  4506.9 1919.34  4552.2 1917.45  4578.1 1915.27  4618.8 1914.48
  4669.7 1912.13  4730.7 1911.64  4781.6  1909.8  4832.5 1909.82  4853.5 1908.95
    4924 1907.87  4935.7 1905.91  4954.6 1899.62  4983.2 1884.04  4992.3 1879.82
    4995 1879.32  4998.3 1879.82  5005.4 1880.57  5015.6 1884.35  5025.8 1886.73
  5093.5 1894.84  5098.6 1894.67    5158 1902.98  5253.8 1912.25  5309.5 1917.78
  5314.1 1917.16    5331 1919.12  5366.7 1925.38  5370.5 1923.94  5374.1 1923.94
#Mann= 6 ,-1 , 0
  4477.7     .05       0  4853.5      .1       0  4992.3     .07       0
  4998.3      .1       0  5253.8     .05       0  5309.5      .1       0
Bank Sta=4992.3,4998.3
XS Rating Curve= 0 ,0
Exp/Cntr=0.3,0.1

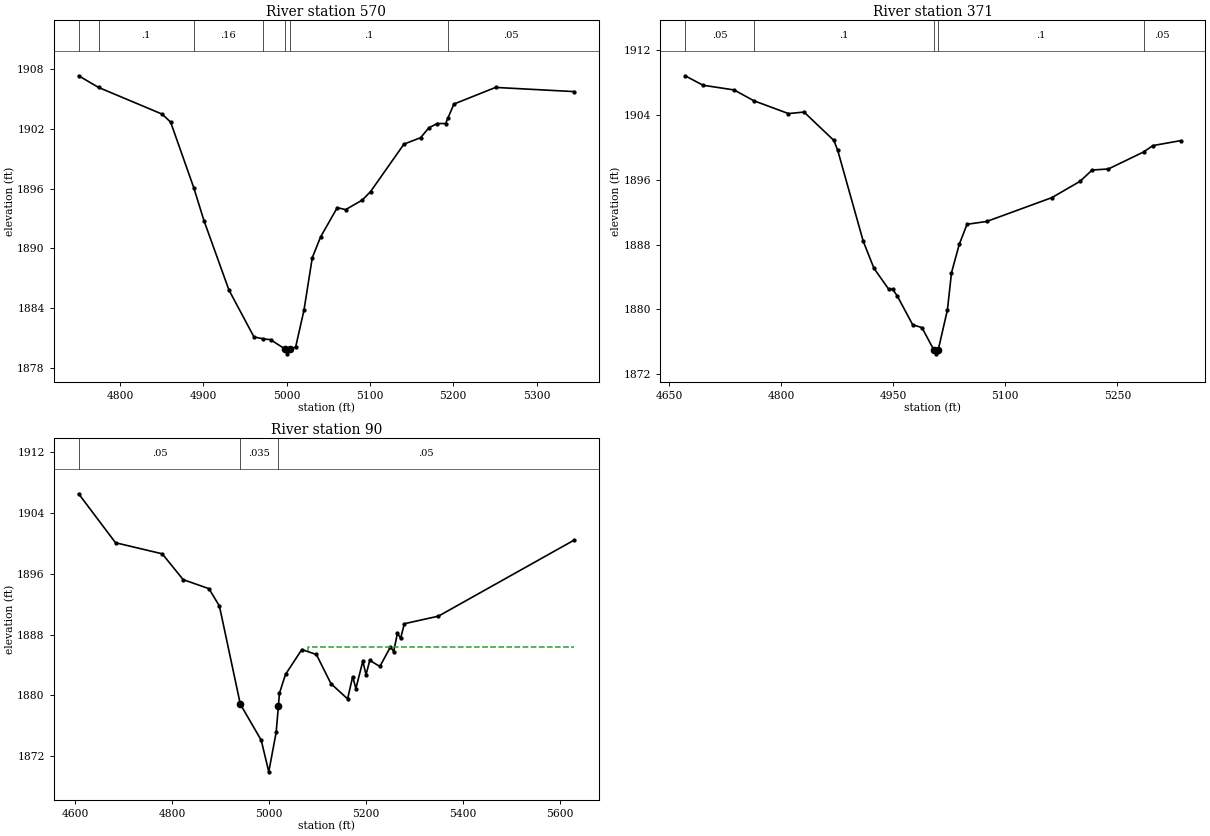
Type RM Length L Ch R = 1 ,570     ,199,199,199
BEGIN DESCRIPTION:
Mapping XS 0d0680ec
END DESCRIPTION:
XS GIS Cut Line= 2
      2717678.86     10076120.38      2717084.16     10076120.38
#Sta/Elev= 30
  4750.4 1907.35  4774.3 1906.18  4850.8 1903.49  4860.8 1902.69  4888.5 1896.12
  4900.8  1892.8  4930.8 1885.82  4960.8 1881.11  4971.7 1880.92  4980.8 1880.83
  4997.8 1879.91  5000.5 1879.41  5003.8 1879.91  5010.8 1880.08  5020.8 1883.78
  5030.8 1889.07  5040.8 1891.16  5060.8  1894.1  5070.8  1893.9  5090.8 1894.86
  5100.8 1895.72  5140.8 1900.48  5160.8 1901.13  5170.8 1902.13  5180.8 1902.55
  5190.8 1902.55  5193.8 1903.14  5200.8 1904.51  5250.8 1906.18  5345.1 1905.76
#Mann= 7 ,-1 , 0
  4750.4     .05       0  4774.3      .1       0  4888.5     .16       0
  4971.7      .1       0  4997.8     .07       0  5003.8      .1       0
  5193.8     .05       0
Bank Sta=4997.8,5003.8
XS Rating Curve= 0 ,0
Exp/Cntr=0.3,0.1

Type RM Length L Ch R = 1 ,371     ,281,281,281
BEGIN DESCRIPTION:
Mapping XS 3fccf765
END DESCRIPTION:
XS GIS Cut Line= 3
      2717811.66     10076023.45      2717428.63     10075916.03
       2717196.4     10076044.08
#Sta/Elev= 30
  4671.6 1908.84  4695.7 1907.67  4737.2 1907.09  4763.7 1905.75  4809.9 1904.17
  4830.7 1904.36  4870.6 1900.86  4875.8 1899.63  4909.9 1888.42  4924.2 1885.08
    4944 1882.48  4949.2 1882.48  4955.3 1881.68  4976.1 1878.09  4988.5 1877.74
  5004.3    1875    5007  1874.5  5010.3    1875  5022.6 1879.94    5028 1884.51
  5038.4 1888.02  5048.8  1890.5  5075.2 1890.85  5162.3 1893.79  5200.1 1895.81
  5216.2  1897.2  5237.9 1897.33    5285 1899.43  5297.5 1900.22  5334.6 1900.83
#Mann= 5 ,-1 , 0
  4671.6     .05       0  4763.7      .1       0  5004.3     .07       0
  5010.3      .1       0    5285     .05       0
Bank Sta=5004.3,5010.3
XS Rating Curve= 0 ,0
Exp/Cntr=0.3,0.1

Type RM Length L Ch R = 1 ,90      ,0,0,0
BEGIN DESCRIPTION:
UNT 0033 IN HEWA 1.0
END DESCRIPTION:
XS GIS Cut Line= 4
      2717971.15     10075885.64      2717600.07     10075671.89
       2717474.2     10075675.14      2717169.33     10076028.83
#Sta/Elev= 30
  4607.7 1906.56  4683.7 1900.11    4780 1898.65  4823.1 1895.25  4876.2 1894.06
  4897.8 1891.77  4940.9 1878.84    4984 1874.09  4999.5 1869.93  5014.7 1875.13
 5019.32 1878.57  5021.4 1880.26    5034 1882.77  5067.6 1886.04  5097.6 1885.39
  5127.6 1881.55  5161.9 1879.54  5172.4 1882.47    5179  1880.9  5193.3 1884.51
  5199.9 1882.72  5207.6 1884.62  5228.4 1883.81  5250.3 1886.39  5256.9 1885.77
  5264.6 1888.21  5271.2 1887.52  5278.8 1889.44  5349.1 1890.44  5628.8 1900.46
#Mann= 3 , 0 , 0
  4607.7     .05       0  4940.9    .035       0 5019.32     .05       0
#XS Ineff= 2 , 0
                         5079.32          1886.4
Permanent Ineff=
       T       T
Bank Sta=4940.9,5019.32
XS Rating Curve= 0 ,0
Exp/Cntr=0.3,0.1

Chan Stop Cuts=-1
Use User Specified Reach Order=0
Composite Channel Slope=5