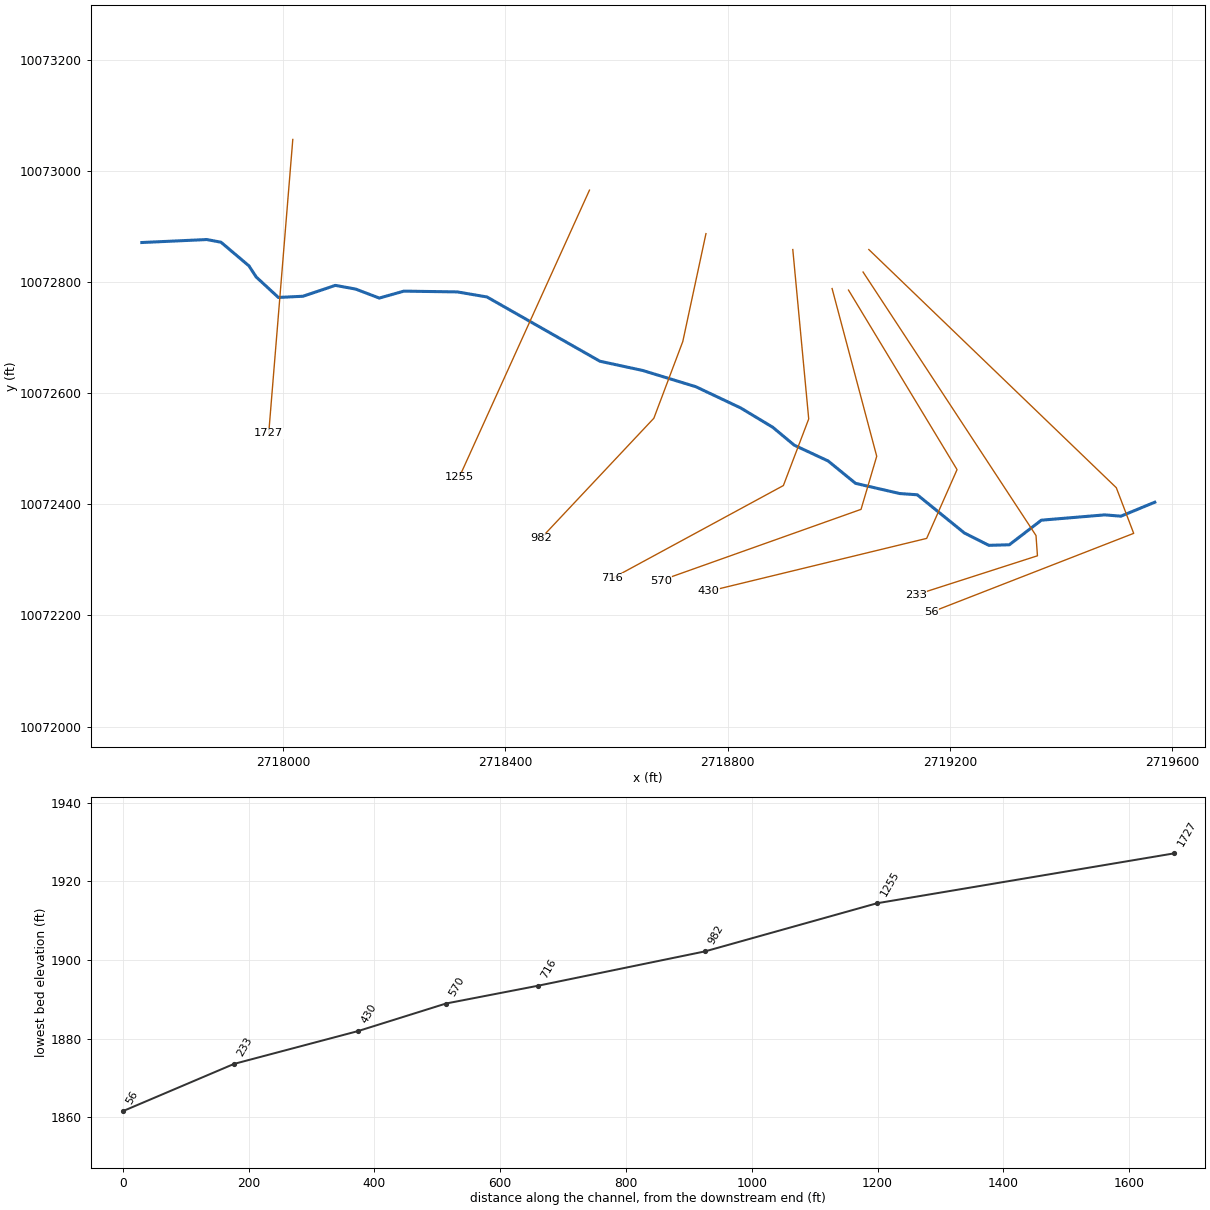
--- UNT 0034 IN HEWA.prj (project) ---

Proj Title=UNT 0034 IN HEWA Base Level Engineering
Current Plan=p01
Default Exp/Contr=0.3,0.1
English Units
Geom File=g01
Flow File=f01
Plan File=p01
BEGIN DESCRIPTION:
UNT 0034 IN HEWA
END DESCRIPTION:

--- UNT 0034 IN HEWA.p01 (plan) ---

Plan Title=Multiple Run
Short Identifier=Multiple
Geom File=g01
Flow File=f01
Subcritical Flow
K Sum by GR= 0
Std Step Tol= 0.01
Critical Tol= 0.01
Num of Std Step Trials= 20
Max Error Tol= 0.3
Flow Tol Ratio= 0.001
Split Flow NTrial= 30
Split Flow Tol= 0.02
Split Flow Ratio= 0.02
Log Output Level= 0
Friction Slope Method= 1
Unsteady Friction Slope Method= 2
Unsteady Bridges Friction Slope Method= 1
Parabolic Critical Depth
Global Vel Dist=  1 , 1 , 1
Global Log Level= 0
CheckData=True
Encroach Param= -1, 0, 0, 0
BEGIN DESCRIPTION:
Multiple Run
END DESCRIPTION:

--- UNT 0034 IN HEWA.f01 (steady flow) ---

Flow Title=Multiple
Number of Profiles=7
Profile Names=10-year,25-year,50-year,1pct_min,100-year,1pct_plu,500-year
River Rch & RM= UNT 0034 IN HEWA,Reach-1,1727
     172     224     264     230     310     420     427
Boundary for River Rch & Prof#=UNT 0034 IN HEWA,Reach-1,1
Up Type=0
Dn Type=3
Dn Slope=0.005
Boundary for River Rch & Prof#=UNT 0034 IN HEWA,Reach-1,2
Up Type=0
Dn Type=3
Dn Slope=0.005
Boundary for River Rch & Prof#=UNT 0034 IN HEWA,Reach-1,3
Up Type=0
Dn Type=3
Dn Slope=0.005
Boundary for River Rch & Prof#=UNT 0034 IN HEWA,Reach-1,4
Up Type=0
Dn Type=3
Dn Slope=0.005
Boundary for River Rch & Prof#=UNT 0034 IN HEWA,Reach-1,5
Up Type=0
Dn Type=3
Dn Slope=0.005
Boundary for River Rch & Prof#=UNT 0034 IN HEWA,Reach-1,6
Up Type=0
Dn Type=3
Dn Slope=0.005
Boundary for River Rch & Prof#=UNT 0034 IN HEWA,Reach-1,7
Up Type=0
Dn Type=3
Dn Slope=0.005

--- UNT 0034 IN HEWA.g01 (geometry) ---

Geom Title=Existing Conditions

River Reach=UNT 0034 IN HEWA,Reach-1
Reach XY= 30
      2717745.69     10072870.81      2717862.50     10072876.18
      2717888.11     10072871.40      2717938.45     10072828.87
      2717951.47     10072808.90      2717991.40     10072772.01
      2718035.67     10072774.18      2718093.83     10072793.71
      2718130.35     10072787.14      2718173.04     10072770.88
      2718217.20     10072783.38      2718313.45     10072781.99
      2718366.84     10072772.88      2718569.95     10072657.32
      2718647.18     10072640.63      2718742.54     10072611.49
      2718823.29     10072573.31      2718881.03     10072538.54
      2718919.58     10072506.41      2718980.75     10072477.87
      2719030.11     10072437.63      2719109.69     10072419.31
      2719141.11     10072417.10      2719225.78     10072348.44
      2719269.85     10072326.17      2719306.76     10072327.18
      2719364.41     10072371.40      2719478.61     10072380.96
      2719507.53     10072378.59      2719568.47     10072403.73

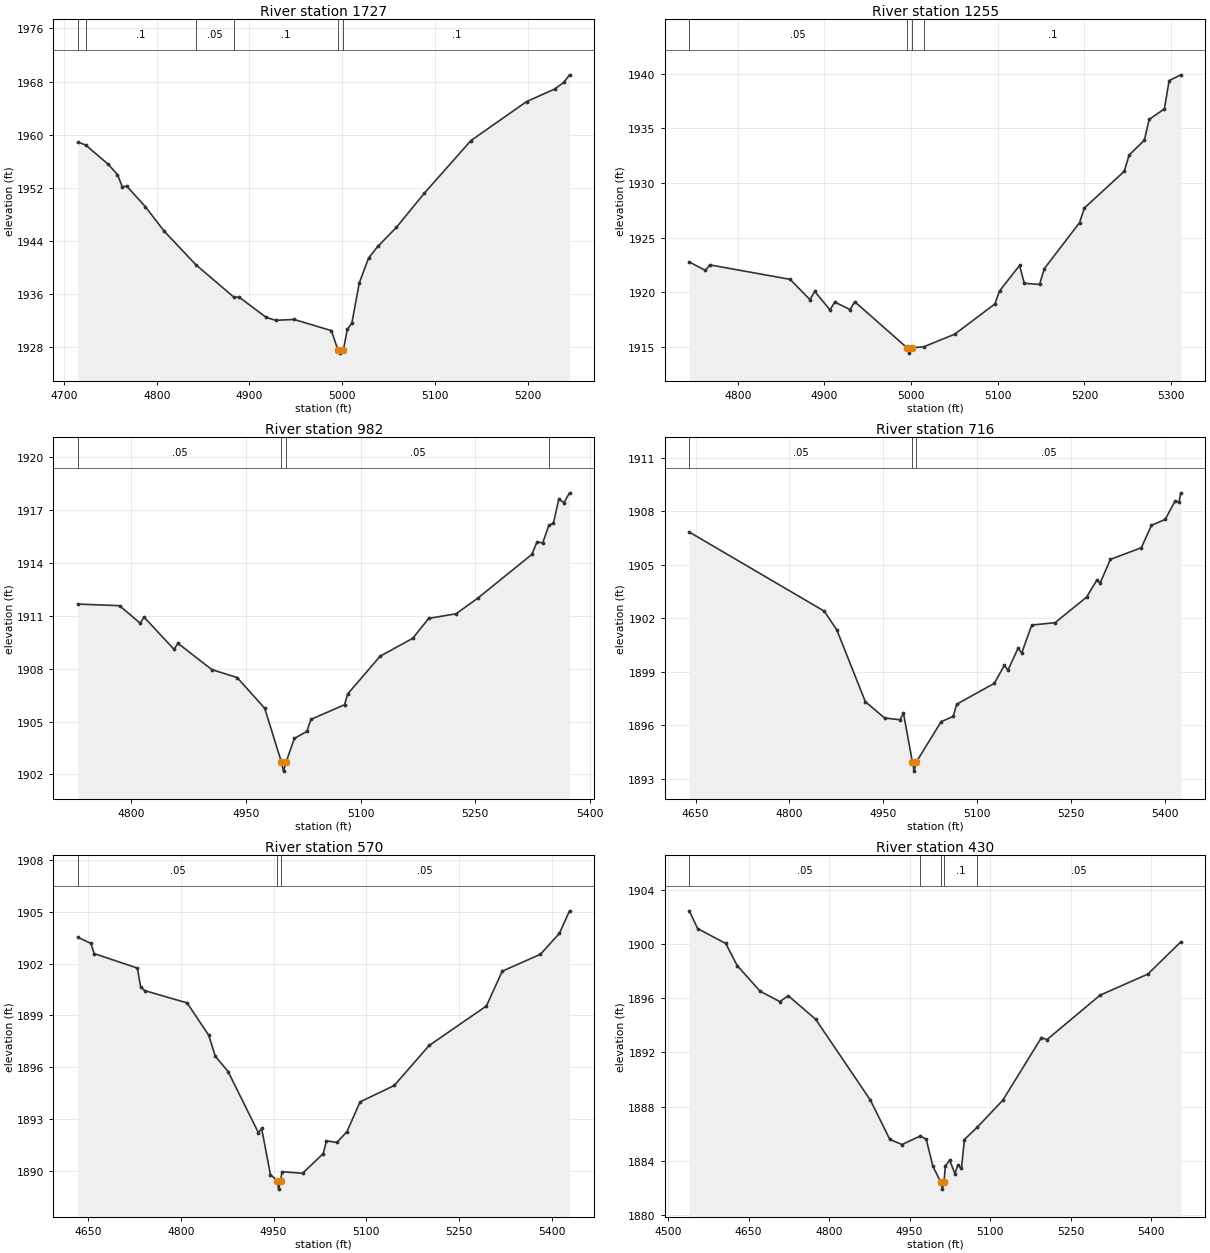
Type RM Length L Ch R = 1,1727,472,472,472
BEGIN DESCRIPTION:
UNT 0034 IN HEWA 6.0
END DESCRIPTION:
XS GIS Cut Line= 2
      2718017.37     10073056.19      2717974.05     10072527.66
#Sta/Elev= 30
  4715.0 1958.89  4723.4 1958.42  4747.6 1955.53  4757.6 1953.98  4762.7 1952.17
  4767.7 1952.23  4787.7 1949.14  4807.8 1945.49  4842.0 1940.42  4882.9 1935.55
  4889.1 1935.49  4918.1 1932.46  4928.2 1932.03  4948.2 1932.15  4988.4 1930.47
  4995.4 1927.58  4998.2 1927.08  5001.4 1927.58  5005.5 1930.64  5010.5 1931.63
  5018.5 1937.67  5028.5 1941.40  5038.5 1943.16  5058.6 1946.04  5088.7 1951.18
  5138.9 1959.10  5199.1 1964.99  5229.2 1966.86  5239.2 1967.87  5245.3 1969.01
#Mann=6,-1,0
  4715.0    0.05       0  4723.4     0.1       0  4842.0    0.05       0
  4882.9     0.1       0  4995.4    0.07       0  5001.4     0.1       0
Bank Sta=4995.4,5001.4
Exp/Cntr=0.3,0.1

Type RM Length L Ch R = 1,1255,273,273,273
BEGIN DESCRIPTION:
UNT 0034 IN HEWA 5.0
END DESCRIPTION:
XS GIS Cut Line= 2
      2718551.23     10072965.02      2718316.89     10072448.60
#Sta/Elev= 30
  4744.1 1922.76  4762.4 1921.99  4767.9 1922.49  4860.3 1921.17  4883.3 1919.31
  4888.8 1920.07  4906.4 1918.37  4911.9 1919.09  4929.5 1918.40  4935.0 1919.12
  4995.1 1914.91  4997.8 1914.41  5001.1 1914.91  5014.6 1914.99  5050.4 1916.15
  5096.6 1918.91  5102.0 1920.10  5125.1 1922.44  5130.6 1920.81  5148.2 1920.70
  5153.7 1922.15  5194.4 1926.37  5199.9 1927.70  5246.0 1931.07  5251.5 1932.55
  5269.1 1933.91  5274.6 1935.81  5292.2 1936.78  5297.7 1939.37  5311.2 1939.90
#Mann=4,-1,0
  4744.1    0.05       0  4995.1   0.035       0  5001.1    0.05       0
  5014.6     0.1       0
Bank Sta=4995.1,5001.1
Exp/Cntr=0.3,0.1

Type RM Length L Ch R = 1,982,266,266,266
BEGIN DESCRIPTION:
UNT 0034 IN HEWA 4.0
END DESCRIPTION:
XS GIS Cut Line= 4
      2718760.85     10072886.79      2718719.19     10072692.82
      2718667.11     10072554.80      2718463.72     10072338.53
#Sta/Elev= 30
  4730.5 1911.65  4784.8 1911.56  4811.8 1910.57  4816.9 1910.91  4856.1 1909.09
  4861.2 1909.43  4905.5 1907.94  4938.6 1907.49  4974.7 1905.75  4996.6 1902.69
  4999.3 1902.19  5002.6 1902.69  5013.4 1904.04  5029.8 1904.44  5035.1 1905.12
  5079.1 1905.95  5083.2 1906.56  5125.7 1908.70  5168.2 1909.71  5189.2 1910.84
  5224.9 1911.10  5253.2 1911.98  5324.0 1914.46  5330.9 1915.18  5338.2 1915.11
  5346.3 1916.11  5352.3 1916.23  5359.2 1917.58  5366.2 1917.40  5373.3 1917.95
#Mann=4,-1,0
  4730.5    0.05       0  4996.6   0.035       0  5002.6    0.05       0
  5346.3     0.1       0
Bank Sta=4996.6,5002.6
Exp/Cntr=0.3,0.1

Type RM Length L Ch R = 1,716,146,146,146
BEGIN DESCRIPTION:
Mapping XS d0bd9779
END DESCRIPTION:
XS GIS Cut Line= 4
      2718917.11     10072858.17      2718945.76     10072553.49
      2718900.18     10072433.70      2718591.85     10072266.58
#Sta/Elev= 30
  4640.1 1906.84  4855.5 1902.41  4875.6 1901.36  4921.2 1897.33  4951.9 1896.42
  4976.7 1896.32  4982.0 1896.70  4996.4 1893.94  4999.1 1893.44  5002.4 1893.94
  5042.2 1896.21  5061.6 1896.51  5067.0 1897.19  5127.1 1898.36  5143.2 1899.37
  5148.9 1899.10  5165.1 1900.33  5170.8 1900.06  5187.0 1901.63  5224.1 1901.76
  5274.4 1903.19  5290.6 1904.13  5296.3 1904.00  5312.5 1905.31  5361.9 1905.96
  5378.1 1907.22  5400.0 1907.55  5416.1 1908.60  5421.8 1908.50  5425.0 1909.04
#Mann=3,-1,0
  4640.1    0.05       0  4996.4   0.035       0  5002.4    0.05       0
Bank Sta=4996.4,5002.4
Exp/Cntr=0.3,0.1

Type RM Length L Ch R = 1,570,140,140,140
BEGIN DESCRIPTION:
Mapping XS c0d1cdb5
END DESCRIPTION:
XS GIS Cut Line= 4
      2718987.83     10072788.03      2719068.12     10072486.37
      2719039.91     10072390.88      2718679.62     10072262.82
#Sta/Elev= 30
  4634.0 1903.53  4654.9 1903.18  4660.1 1902.59  4730.0 1901.75  4735.2 1900.65
  4741.9 1900.44  4810.3 1899.73  4845.3 1897.85  4855.8 1896.64  4876.5 1895.75
  4925.5 1892.20  4930.7 1892.45  4944.9 1889.77  4955.4 1889.43  4958.1 1888.93
  4961.4 1889.43  4963.6 1889.94  4996.9 1889.85  5030.2 1890.99  5035.4 1891.73
  5052.4 1891.64  5068.5 1892.26  5089.7 1893.99  5144.9 1894.94  5201.3 1897.26
  5293.8 1899.55  5319.4 1901.57  5381.1 1902.55  5411.9 1903.77  5428.1 1905.07
#Mann=3,-1,0
  4634.0    0.05       0  4955.4    0.04       0  4961.4    0.05       0
Bank Sta=4955.4,4961.4
Exp/Cntr=0.3,0.1

Type RM Length L Ch R = 1,430,197,197,197
BEGIN DESCRIPTION:
Mapping XS f8c92d46
END DESCRIPTION:
XS GIS Cut Line= 4
      2719017.38     10072785.25      2719212.68     10072462.35
      2719158.00     10072338.65      2718766.08     10072243.60
#Sta/Elev= 30
  4539.5 1902.45  4555.0 1901.14  4607.4 1900.04  4628.7 1898.41  4671.4 1896.52
  4708.3 1895.75  4723.8 1896.19  4775.0 1894.45  4877.0 1888.48  4913.1 1885.59
  4935.7 1885.21  4970.0 1885.84  4981.0 1885.60  4993.2 1883.63  5008.1 1882.42
  5010.8 1881.92  5014.1 1882.42  5016.5 1883.62  5024.7 1884.05  5034.4 1883.07
  5039.8 1883.69  5046.6 1883.46  5052.1 1885.58  5075.6 1886.47  5123.7 1888.48
  5195.7 1893.10  5206.0 1892.95  5305.0 1896.23  5393.8 1897.78  5455.4 1900.16
#Mann=5,-1,0
  4539.5    0.05       0  4970.0     0.1       0  5008.1    0.07       0
  5014.1     0.1       0  5075.6    0.05       0
Bank Sta=5008.1,5014.1
Exp/Cntr=0.3,0.1

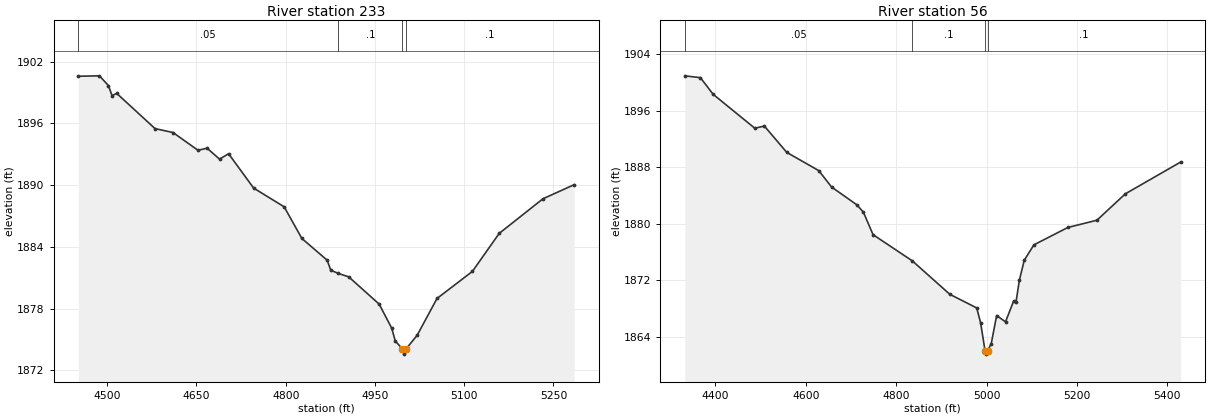
Type RM Length L Ch R = 1,233,177,177,177
BEGIN DESCRIPTION:
Mapping XS de3aa573
END DESCRIPTION:
XS GIS Cut Line= 4
      2719043.57     10072817.75      2719354.75     10072343.82
      2719357.36     10072307.36      2719138.59     10072237.05
#Sta/Elev= 30
  4451.5 1900.59  4487.0 1900.63  4502.1 1899.68  4508.1 1898.71  4516.1 1898.92
  4580.4 1895.50  4610.6 1895.12  4652.7 1893.39  4667.8 1893.60  4688.9 1892.53
  4704.0 1893.06  4746.1 1889.72  4797.4 1887.90  4827.2 1884.82  4869.7 1882.71
  4875.7 1881.74  4888.2 1881.43  4905.9 1881.09  4957.1 1878.44  4978.2 1876.10
  4984.2 1874.85  4996.3 1874.08  4999.0 1873.58  5002.3 1874.08  5021.0 1875.42
  5054.3 1878.99  5113.8 1881.62  5158.9 1885.32  5232.4 1888.68  5284.8 1890.05
#Mann=4,-1,0
  4451.5    0.05       0  4888.2     0.1       0  4996.3    0.07       0
  5002.3     0.1       0
Bank Sta=4996.3,5002.3
Exp/Cntr=0.3,0.1

Type RM Length L Ch R = 1,56,0,0,0
BEGIN DESCRIPTION:
UNT 0034 IN HEWA 3.0
END DESCRIPTION:
XS GIS Cut Line= 4
      2719053.97     10072858.15      2719499.29     10072429.76
      2719530.54     10072347.73      2719165.99     10072205.81
#Sta/Elev= 30
  4332.4 1900.95  4366.9 1900.69  4395.2 1898.33  4487.3 1893.53  4508.4 1893.84
  4558.0 1890.11  4628.8 1887.53  4657.1 1885.21  4713.4 1882.67  4727.6 1881.63
  4748.9 1878.46  4835.8 1874.75  4918.7 1870.02  4978.2 1868.09  4986.8 1865.99
  4996.6 1862.05  4999.3 1861.55  5002.6 1862.05  5010.3 1863.03  5022.3 1867.01
  5041.9 1866.12  5059.7 1869.03  5065.0 1868.87  5072.5 1871.99  5083.3 1874.83
  5104.7 1877.02  5179.8 1879.48  5244.2 1880.51  5307.1 1884.25  5429.3 1888.74
#Mann=4,-1,0
  4332.4    0.05       0  4835.8     0.1       0  4996.6    0.07       0
  5002.6     0.1       0
Bank Sta=4996.6,5002.6
Exp/Cntr=0.3,0.1

Chan Stop Cuts=-1