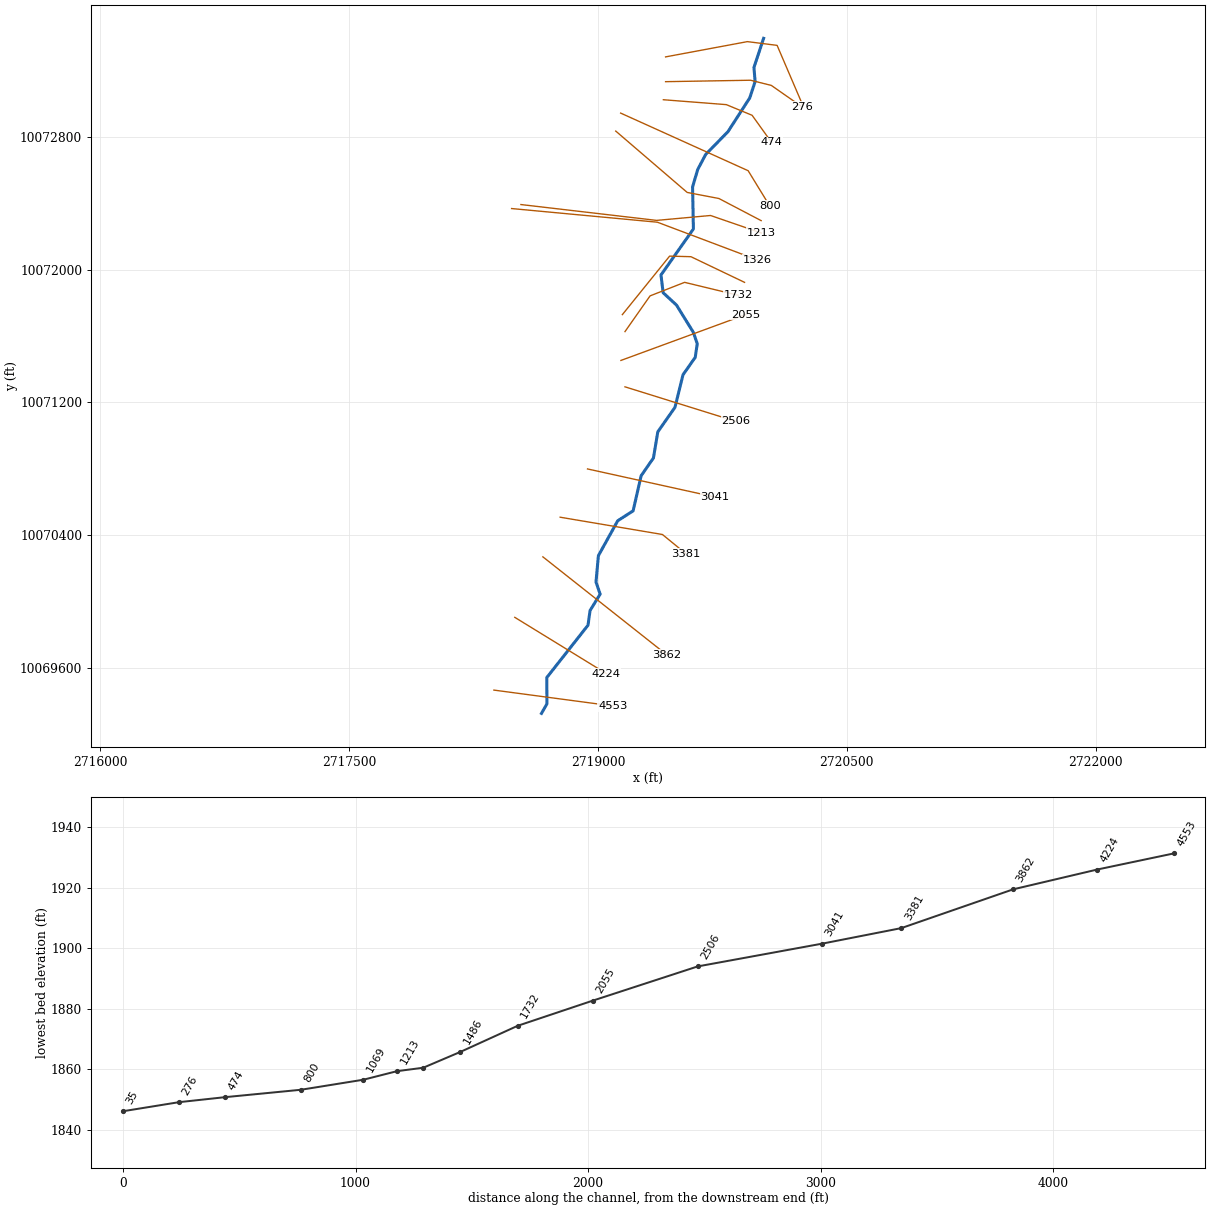
--- UNT 0035 IN HEWA.prj (project) ---

Proj Title=UNT 0035 IN HEWA Base Level Engineering
Current Plan=p01
Default Exp/Contr=0.3,0.1
English Units
Geom File=g01
Flow File=f01
Plan File=p01
BEGIN DESCRIPTION:
UNT 0035 IN HEWA
END DESCRIPTION:

--- UNT 0035 IN HEWA.p01 (plan) ---

Plan Title=Multiple Run
Short Identifier=Multiple
Geom File=g01
Flow File=f01
Subcritical Flow
K Sum by GR= 0
Std Step Tol= 0.01
Critical Tol= 0.01
Num of Std Step Trials= 20
Max Error Tol= 0.3
Flow Tol Ratio= 0.001
Split Flow NTrial= 30
Split Flow Tol= 0.02
Split Flow Ratio= 0.02
Log Output Level= 0
Friction Slope Method= 1
Unsteady Friction Slope Method= 2
Unsteady Bridges Friction Slope Method= 1
Parabolic Critical Depth
Global Vel Dist=  1 , 1 , 1
Global Log Level= 0
CheckData=True
Encroach Param= -1, 0, 0, 0
BEGIN DESCRIPTION:
Multiple Run
END DESCRIPTION:

--- UNT 0035 IN HEWA.f01 (steady flow) ---

Flow Title=Multiple
Number of Profiles=7
Profile Names=10-year,25-year,50-year,1pct_min,100-year,1pct_plu,500-year
River Rch & RM= UNT 0035 IN HEWA,Reach-1,4553
     777    1122    1419    1313    1776    2402    2788
River Rch & RM= UNT 0035 IN HEWA,Reach-1,1326
    1332    1981    2556    2407    3255    4402    5293
River Rch & RM= UNT 0035 IN HEWA,Reach-1,1069
    1379    2054    2651    2498    3378    4569    5498
Boundary for River Rch & Prof#=UNT 0035 IN HEWA,Reach-1,1
Up Type=0
Dn Type=3
Dn Slope=0.005
Boundary for River Rch & Prof#=UNT 0035 IN HEWA,Reach-1,2
Up Type=0
Dn Type=3
Dn Slope=0.005
Boundary for River Rch & Prof#=UNT 0035 IN HEWA,Reach-1,3
Up Type=0
Dn Type=3
Dn Slope=0.005
Boundary for River Rch & Prof#=UNT 0035 IN HEWA,Reach-1,4
Up Type=0
Dn Type=3
Dn Slope=0.005
Boundary for River Rch & Prof#=UNT 0035 IN HEWA,Reach-1,5
Up Type=0
Dn Type=3
Dn Slope=0.005
Boundary for River Rch & Prof#=UNT 0035 IN HEWA,Reach-1,6
Up Type=0
Dn Type=3
Dn Slope=0.005
Boundary for River Rch & Prof#=UNT 0035 IN HEWA,Reach-1,7
Up Type=0
Dn Type=3
Dn Slope=0.005

--- UNT 0035 IN HEWA.g01 (geometry) ---

Geom Title=Existing Conditions

River Reach=UNT 0035 IN HEWA,Reach-1
Reach XY= 30
      2718660.08     10069326.41      2718692.87     10069383.61
      2718692.01     10069542.23      2718940.48     10069857.61
      2718953.03     10069946.57      2719013.61     10070044.79
      2718988.60     10070117.78      2719003.03     10070276.56
      2719119.57     10070486.94      2719212.25     10070546.79
      2719260.49     10070758.13      2719334.70     10070865.30
      2719360.93     10071022.64      2719464.60     10071170.63
      2719512.80     10071366.61      2719586.56     10071471.72
      2719598.61     10071553.69      2719575.19     10071622.36
      2719473.58     10071786.51      2719393.08     10071860.96
      2719380.10     10071967.90      2719575.50     10072244.98
      2719570.47     10072498.14      2719601.13     10072602.63
      2719649.48     10072694.20      2719783.50     10072831.06
      2719915.18     10073035.10      2719947.34     10073133.42
      2719940.24     10073217.84      2719998.47     10073393.73

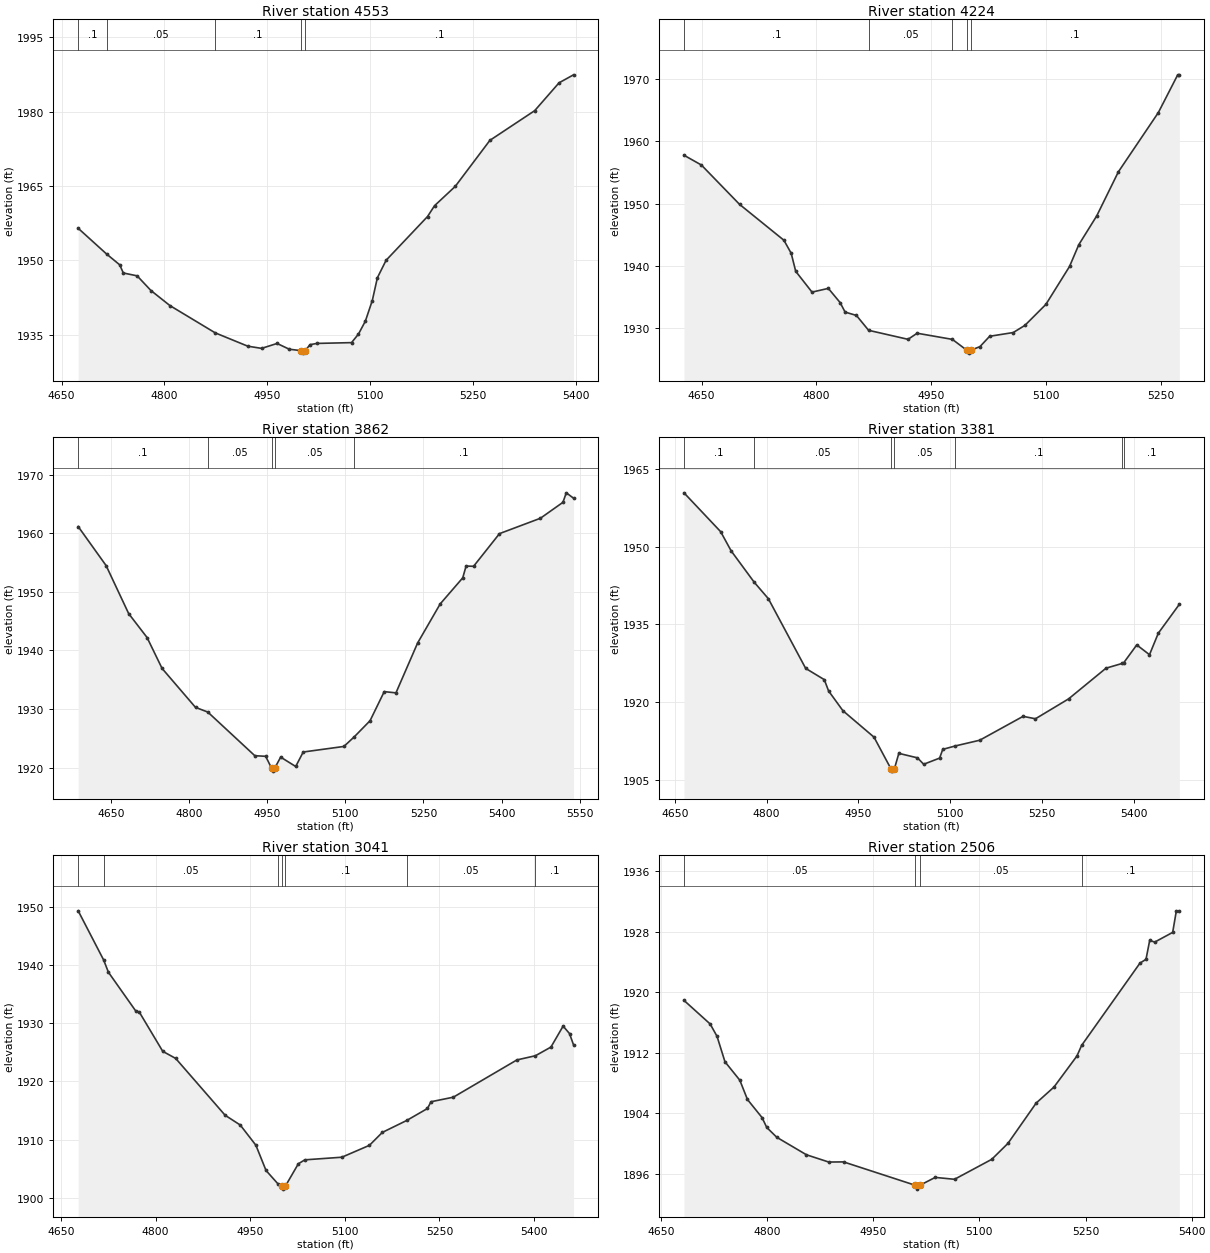
Type RM Length L Ch R = 1,4553,329,329,329
BEGIN DESCRIPTION:
UNT 0035 IN HEWA 8.0
END DESCRIPTION:
XS GIS Cut Line= 2
      2718373.26     10069466.73      2719089.43     10069371.24
#Sta/Elev= 30
  4674.3 1956.46  4715.8 1951.26  4734.9 1949.08  4740.1 1947.44  4760.3 1946.86
  4780.4 1943.90  4808.1 1940.86  4874.2 1935.35  4921.7 1932.66  4941.8 1932.22
  4964.4 1933.21  4982.2 1932.05  4999.4 1931.76  5002.1 1931.26  5005.4 1931.76
  5012.5 1932.97  5022.6 1933.22  5073.0 1933.38  5083.1 1935.10  5093.2 1937.72
  5103.3 1941.88  5110.7 1946.47  5123.4 1950.00  5183.9 1958.84  5194.1 1961.02
  5224.3 1964.92  5274.8 1974.21  5340.2 1980.21  5375.7 1985.83  5396.8 1987.44
#Mann=5,-1,0
  4674.3     0.1       0  4715.8    0.05       0  4874.2     0.1       0
  4999.4    0.07       0  5005.4     0.1       0
Bank Sta=4999.4,5005.4
Exp/Cntr=0.3,0.1

Type RM Length L Ch R = 1,4224,362,362,362
BEGIN DESCRIPTION:
UNT 0035 IN HEWA 7.0
END DESCRIPTION:
XS GIS Cut Line= 2
      2718499.14     10069905.10      2719050.37     10069566.55
#Sta/Elev= 30
  4627.1 1957.77  4649.8 1956.20  4699.6 1949.88  4757.6 1944.10  4767.1 1942.01
  4773.0 1939.11  4794.3 1935.76  4815.6 1936.36  4831.0 1934.08  4837.5 1932.55
  4852.3 1932.01  4868.2 1929.62  4919.7 1928.17  4931.6 1929.15  4977.6 1928.16
  4996.1 1926.45  4998.9 1925.95  5002.1 1926.45  5013.6 1926.99  5026.3 1928.66
  5057.1 1929.26  5072.3 1930.41  5099.7 1933.78  5130.6 1939.88  5142.7 1943.38
  5166.1 1948.01  5194.4 1955.10  5246.6 1964.63  5271.9 1970.70  5274.0 1970.70
#Mann=5,-1,0
  4627.1     0.1       0  4868.2    0.05       0  4977.6     0.1       0
  4996.1    0.07       0  5002.1     0.1       0
Bank Sta=4996.1,5002.1
Exp/Cntr=0.3,0.1

Type RM Length L Ch R = 1,3862,481,481,481
BEGIN DESCRIPTION:
UNT 0035 IN HEWA 6.0
END DESCRIPTION:
XS GIS Cut Line= 2
      2718668.45     10070269.65      2719414.19     10069680.00
#Sta/Elev= 30
  4587.3 1961.13  4640.9 1954.47  4684.2 1946.28  4719.5 1942.20  4748.3 1936.93
  4812.5 1930.28  4836.0 1929.49  4926.3 1922.04  4947.1 1921.94  4958.5 1919.91
  4961.3 1919.41  4964.5 1919.91  4975.9 1921.80  5004.8 1920.20  5019.2 1922.67
  5097.3 1923.62  5117.4 1925.28  5147.5 1928.01  5174.7 1932.97  5197.2 1932.76
  5238.8 1941.27  5282.1 1947.93  5325.4 1952.38  5331.8 1954.39  5346.2 1954.35
  5395.9 1959.92  5474.4 1962.54  5517.7 1965.26  5524.1 1966.88  5538.0 1965.97
#Mann=5,-1,0
  4587.3     0.1       0  4836.0    0.05       0  4958.5   0.035       0
  4964.5    0.05       0  5117.4     0.1       0
Bank Sta=4958.5,4964.5
Exp/Cntr=0.3,0.1

Type RM Length L Ch R = 1,3381,340,340,340
BEGIN DESCRIPTION:
UNT 0035 IN HEWA 5.0
END DESCRIPTION:
XS GIS Cut Line= 3
      2718772.55     10070508.40      2719388.89     10070404.23
      2719531.08     10070287.89
#Sta/Elev= 30
  4665.1 1960.47  4725.0 1952.95  4742.1 1949.24  4779.7 1943.18  4802.9 1939.98
  4863.8 1926.50  4894.2 1924.32  4901.2 1922.14  4924.6 1918.31  4975.4 1913.19
  5002.8 1907.12  5005.5 1906.62  5008.8 1907.12  5015.9 1910.06  5046.3 1909.19
  5056.5 1907.95  5082.5 1909.14  5087.6 1910.83  5108.0 1911.49  5148.0 1912.60
  5218.8 1917.22  5239.0 1916.75  5293.1 1920.60  5354.2 1926.54  5380.4 1927.45
  5383.3 1927.62  5404.4 1931.04  5425.2 1929.15  5439.6 1933.31  5473.9 1938.89
#Mann=7,-1,0
  4665.1     0.1       0  4779.7    0.05       0  5002.8    0.04       0
  5008.8    0.05       0  5108.0     0.1       0  5380.4    0.05       0
  5383.3     0.1       0
Bank Sta=5002.8,5008.8
Exp/Cntr=0.3,0.1

Type RM Length L Ch R = 1,3041,535,535,535
BEGIN DESCRIPTION:
UNT 0035 IN HEWA 4.0
END DESCRIPTION:
XS GIS Cut Line= 2
      2718937.50     10070799.20      2719704.60     10070630.18
#Sta/Elev= 30
  4677.2 1949.30  4717.6 1940.85  4725.1 1938.76  4768.8 1932.05  4773.9 1931.95
  4811.3 1925.17  4831.8 1923.95  4910.2 1914.19  4934.2 1912.51  4959.0 1909.04
  4975.1 1904.70  4994.2 1902.38  4999.7 1902.00  5002.5 1901.50  5005.7 1902.00
  5026.3 1905.85  5036.6 1906.53  5095.3 1906.98  5139.0 1909.02  5159.5 1911.24
  5198.3 1913.30  5231.1 1915.35  5236.7 1916.51  5272.1 1917.29  5372.9 1923.69
  5402.3 1924.41  5426.9 1925.90  5446.2 1929.50  5456.4 1928.21  5462.7 1926.28
#Mann=7,-1,0
  4677.2     0.1       0  4717.6    0.05       0  4994.2     0.1       0
  4999.7    0.07       0  5005.7     0.1       0  5198.3    0.05       0
  5402.3     0.1       0
Bank Sta=4999.7,5005.7
Exp/Cntr=0.3,0.1

Type RM Length L Ch R = 1,2506,451,451,451
BEGIN DESCRIPTION:
UNT 0035 IN HEWA 3.0
END DESCRIPTION:
XS GIS Cut Line= 2
      2719163.18     10071294.00      2719831.56     10071085.67
#Sta/Elev= 30
  4682.5 1918.94  4719.5 1915.82  4729.2 1914.19  4740.4 1910.83  4761.4 1908.39
  4772.2 1905.84  4792.8 1903.45  4799.5 1902.14  4813.7 1900.84  4855.6 1898.53
  4887.1 1897.57  4908.0 1897.59  5009.7 1894.49  5012.5 1893.99  5015.7 1894.49
  5037.6 1895.54  5064.9 1895.29  5117.5 1897.93  5140.4 1900.04  5180.3 1905.37
  5205.4 1907.48  5237.9 1911.59  5244.5 1912.99  5327.0 1923.87  5335.5 1924.37
  5340.7 1926.86  5347.9 1926.65  5373.2 1927.93  5378.4 1930.78  5382.6 1930.78
#Mann=4,-1,0
  4682.5    0.05       0  5009.7   0.035       0  5015.7    0.05       0
  5244.5     0.1       0
Bank Sta=5009.7,5015.7
Exp/Cntr=0.3,0.1

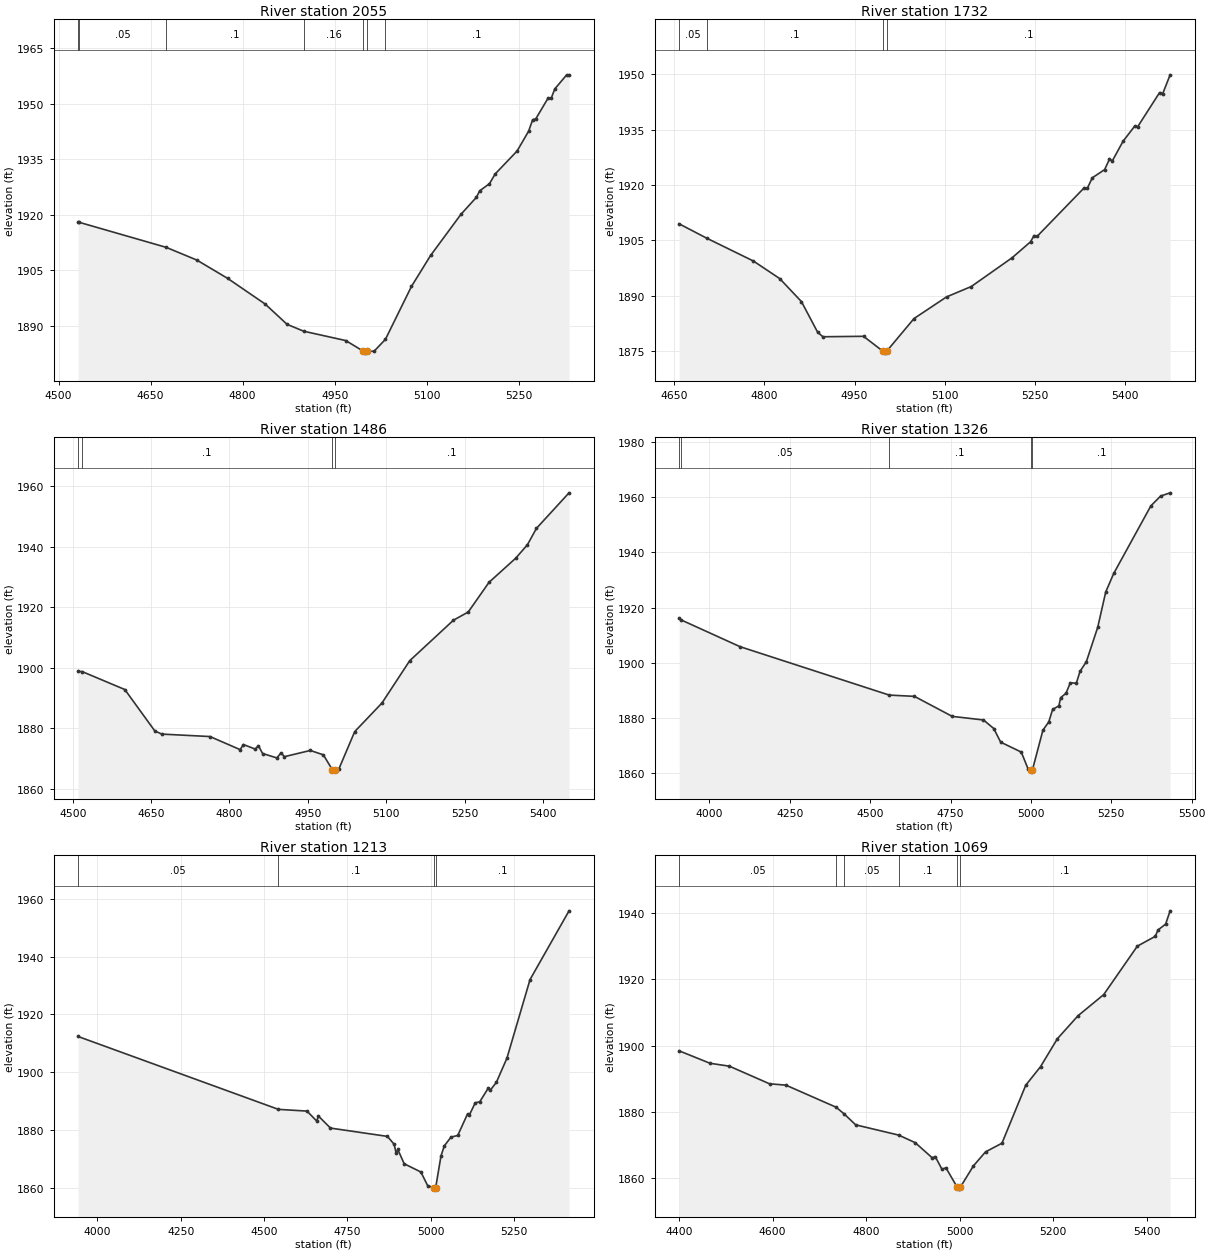
Type RM Length L Ch R = 1,2055,323,323,323
BEGIN DESCRIPTION:
Mapping XS dd4ed67b
END DESCRIPTION:
XS GIS Cut Line= 2
      2719138.95     10071453.01      2719890.20     10071728.87
#Sta/Elev= 30
  4531.8 1918.05  4532.5 1918.05  4675.5 1911.24  4725.4 1907.81  4775.7 1902.86
  4836.7 1895.96  4872.5 1890.47  4899.8 1888.61  4968.1 1886.10  4997.0 1883.21
  4999.8 1882.71  5003.0 1883.21  5014.3 1883.22  5032.8 1886.43  5075.3 1900.72
  5106.5 1909.07  5156.1 1920.19  5181.1 1924.74  5186.5 1926.50  5202.4 1928.41
  5211.7 1931.04  5247.5 1937.24  5266.3 1942.60  5272.7 1945.64  5278.0 1945.93
  5297.8 1951.46  5303.2 1951.54  5308.9 1953.98  5328.3 1957.78  5332.1 1957.77
#Mann=7,-1,0
  4531.8     0.1       0  4532.5    0.05       0  4675.5     0.1       0
  4899.8    0.16       0  4997.0    0.07       0  5003.0    0.16       0
  5032.8     0.1       0
Bank Sta=4997,5003
Exp/Cntr=0.3,0.1

Type RM Length L Ch R = 1,1732,246,246,246
BEGIN DESCRIPTION:
UNT 0035 IN HEWA 2.0
END DESCRIPTION:
XS GIS Cut Line= 4
      2719163.25     10071626.64      2719314.27     10071841.89
      2719522.60     10071923.48      2719844.53     10071845.60
#Sta/Elev= 30
  4657.9 1909.46  4703.5 1905.59  4781.4 1899.39  4825.4 1894.62  4861.6 1888.37
  4888.6 1880.07  4897.3 1878.85  4965.0 1878.97  4997.5 1874.91  5000.3 1874.41
  5003.5 1874.91  5049.1 1883.78  5103.3 1889.65  5144.6 1892.47  5212.4 1900.24
  5243.2 1904.58  5249.1 1906.27  5254.2 1906.06  5332.8 1919.25  5337.9 1919.09
  5346.1 1921.93  5366.7 1924.16  5374.6 1926.93  5379.8 1926.61  5397.5 1931.87
  5416.5 1935.88  5421.6 1935.74  5458.3 1945.05  5463.4 1944.72  5475.8 1949.85
#Mann=4,-1,0
  4657.9    0.05       0  4703.5     0.1       0  4997.5    0.07       0
  5003.5     0.1       0
Bank Sta=4997.5,5003.5
Exp/Cntr=0.3,0.1

Type RM Length L Ch R = 1,1486,160,160,160
BEGIN DESCRIPTION:
Mapping XS 01af0861
END DESCRIPTION:
XS GIS Cut Line= 4
      2719147.45     10071729.04      2719432.19     10072081.49
      2719560.66     10072078.02      2719883.49     10071923.55
#Sta/Elev= 30
  4510.3 1898.79  4518.0 1898.75  4599.7 1892.81  4657.2 1879.09  4670.6 1878.06
  4762.8 1877.25  4820.3 1872.93  4826.8 1874.61  4849.1 1873.11  4855.5 1874.18
  4863.4 1871.64  4890.7 1870.18  4898.7 1871.85  4905.1 1870.59  4954.7 1872.65
  4979.7 1871.20  4996.7 1866.31  4999.4 1865.81  5002.7 1866.31  5009.7 1866.67
  5039.7 1878.89  5091.9 1888.36  5144.9 1902.34  5228.7 1915.76  5256.9 1918.45
  5296.7 1928.28  5347.6 1936.23  5370.2 1940.71  5387.4 1946.12  5449.8 1957.89
#Mann=4,-1,0
  4510.3    0.05       0  4518.0     0.1       0  4996.7    0.07       0
  5002.7     0.1       0
Bank Sta=4996.7,5002.7
Exp/Cntr=0.3,0.1

Type RM Length L Ch R = 1,1326,113,113,113
BEGIN DESCRIPTION:
UNT 0035 IN HEWA 1.0
END DESCRIPTION:
XS GIS Cut Line= 3
      2718480.06     10072368.17      2719358.58     10072285.81
      2719961.52     10072058.33
#Sta/Elev= 30
  3906.2 1916.08  3910.4 1915.60  4095.4 1905.79  4559.5 1888.20  4637.8 1887.74
  4755.3 1880.47  4852.6 1879.16  4884.6 1876.05  4906.0 1871.11  4970.1 1867.50
  4991.5 1861.32  4998.9 1861.08  5001.6 1860.58  5004.9 1861.08  5037.4 1875.44
  5055.7 1878.49  5067.6 1882.98  5087.1 1884.30  5092.5 1887.25  5109.1 1888.86
  5122.7 1892.68  5141.2 1892.49  5152.9 1896.84  5172.4 1900.30  5207.9 1912.85
  5232.8 1925.68  5257.6 1932.38  5373.1 1956.93  5403.3 1960.49  5433.0 1961.67
#Mann=5,-1,0
  3906.2     0.1       0  3910.4    0.05       0  4559.5     0.1       0
  4998.9    0.07       0  5004.9     0.1       0
Bank Sta=4998.9,5004.9
Exp/Cntr=0.3,0.1

Type RM Length L Ch R = 1,1213,144,144,144
BEGIN DESCRIPTION:
Mapping XS e55271b8
END DESCRIPTION:
XS GIS Cut Line= 4
      2718536.36     10072392.26      2719354.06     10072296.77
      2719678.71     10072326.29      2719984.70     10072220.83
#Sta/Elev= 30
  3942.2 1912.35  4543.2 1887.09  4628.9 1886.49  4658.2 1883.04  4663.3 1884.77
  4699.4 1880.60  4870.3 1877.72  4890.4 1874.99  4896.5 1871.87  4901.5 1873.18
  4920.5 1868.24  4970.7 1865.37  4990.8 1860.69  5009.0 1859.94  5011.7 1859.44
  5015.0 1859.94  5031.0 1870.96  5041.0 1874.45  5061.1 1877.48  5081.2 1878.04
  5110.8 1885.55  5116.1 1885.11  5133.5 1889.33  5147.3 1889.73  5173.3 1894.54
  5178.6 1893.68  5197.0 1896.44  5228.7 1904.80  5298.1 1932.08  5415.1 1955.91
#Mann=4,-1,0
  3942.2    0.05       0  4543.2     0.1       0  5009.0    0.07       0
  5015.0     0.1       0
Bank Sta=5009,5015
Exp/Cntr=0.3,0.1

Type RM Length L Ch R = 1,1069,269,269,269
BEGIN DESCRIPTION:
Mapping XS 4be6182d
END DESCRIPTION:
XS GIS Cut Line= 4
      2719107.52     10072834.98      2719538.09     10072465.17
      2719729.06     10072428.72      2719983.83     10072295.27
#Sta/Elev= 30
  4400.3 1898.39  4466.1 1894.64  4507.8 1893.75  4593.4 1888.44  4628.5 1888.03
  4735.9 1881.36  4752.5 1879.40  4777.7 1876.04  4869.8 1872.94  4905.0 1870.65
  4941.2 1866.10  4947.8 1866.45  4962.1 1862.63  4970.6 1863.08  4995.0 1857.13
  4997.7 1856.63  5001.0 1857.13  5029.3 1863.64  5055.2 1867.87  5090.4 1870.50
  5141.3 1888.02  5172.9 1893.62  5208.9 1902.05  5253.0 1908.99  5307.9 1915.37
  5379.8 1930.00  5418.3 1932.98  5423.9 1934.87  5440.3 1936.66  5449.9 1940.67
#Mann=6,-1,0
  4400.3    0.05       0  4735.9     0.1       0  4752.5    0.05       0
  4869.8     0.1       0  4995.0    0.07       0  5001.0     0.1       0
Bank Sta=4995,5001
Exp/Cntr=0.3,0.1

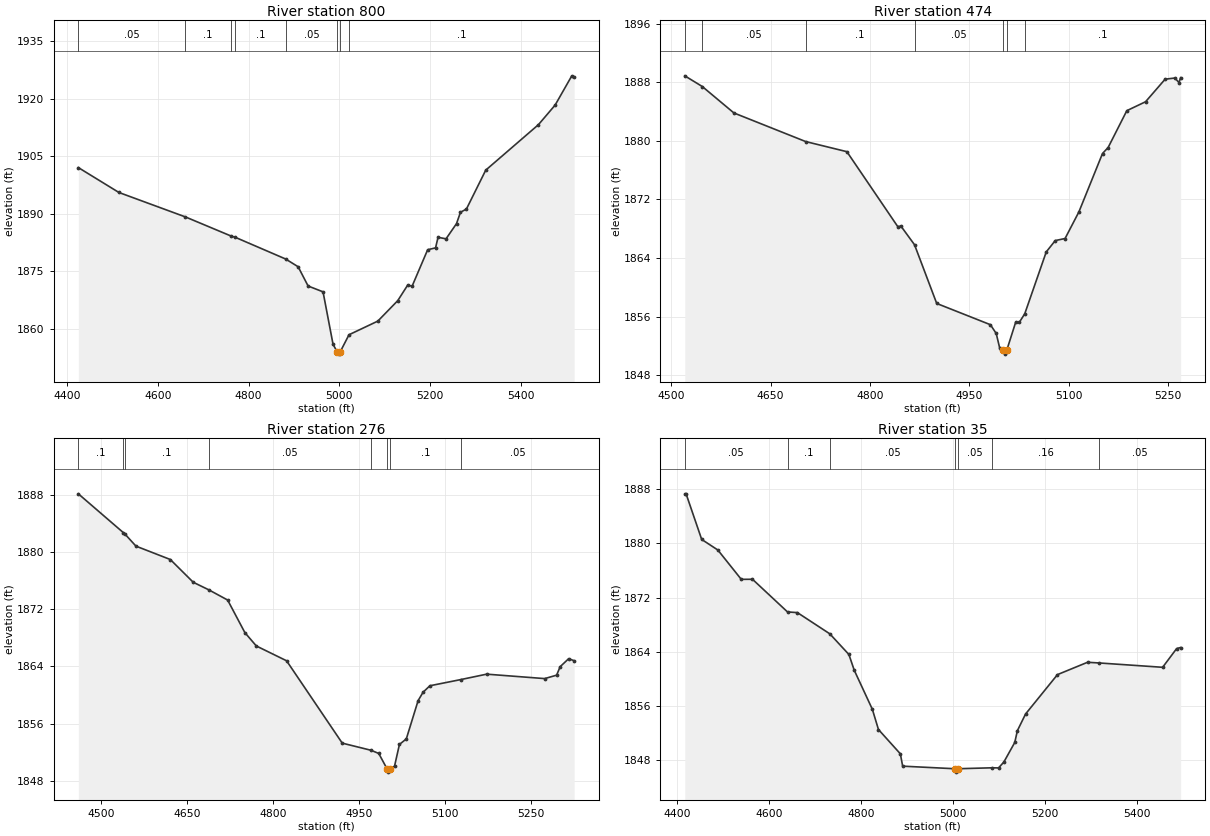
Type RM Length L Ch R = 1,800,326,326,326
BEGIN DESCRIPTION:
UNT 0034 IN HEWA 2.0
END DESCRIPTION:
XS GIS Cut Line= 3
      2719137.12     10072943.31      2719905.39     10072596.07
      2720035.61     10072383.37
#Sta/Elev= 30
  4424.7 1902.01  4514.1 1895.51  4660.6 1889.13  4760.2 1884.19  4771.0 1883.78
  4881.5 1878.14  4909.0 1876.12  4931.0 1871.09  4963.9 1869.57  4985.9 1855.90
  4995.3 1853.81  4998.0 1853.31  5001.3 1853.81  5021.1 1858.37  5084.6 1861.93
  5128.5 1867.27  5150.5 1871.35  5160.1 1871.04  5194.4 1880.56  5211.8 1881.05
  5217.3 1883.81  5234.9 1883.41  5258.0 1887.38  5266.7 1890.34  5279.8 1891.18
  5322.4 1901.34  5438.5 1913.21  5475.3 1918.33  5512.0 1925.96  5517.2 1925.63
#Mann=8,-1,0
  4424.7    0.05       0  4660.6     0.1       0  4760.2    0.05       0
  4771.0     0.1       0  4881.5    0.05       0  4995.3    0.04       0
  5001.3    0.05       0  5021.1     0.1       0
Bank Sta=4995.3,5001.3
Exp/Cntr=0.3,0.1

Type RM Length L Ch R = 1,474,198,198,198
BEGIN DESCRIPTION:
Mapping XS 53f0dd35
END DESCRIPTION:
XS GIS Cut Line= 4
      2719394.57     10073023.77      2719773.86     10072994.26
      2719929.24     10072930.02      2720045.74     10072767.79
#Sta/Elev= 30
  4520.6 1888.88  4547.0 1887.42  4594.7 1883.81  4703.1 1879.90  4765.2 1878.52
  4841.9 1868.30  4846.9 1868.34  4867.3 1865.81  4900.8 1857.79  4981.8 1854.89
  4990.6 1853.69  4996.0 1851.64  5000.4 1851.37  5003.2 1850.87  5006.4 1851.37
  5019.9 1855.21  5025.3 1855.19  5033.7 1856.39  5066.1 1864.83  5079.7 1866.38
  5094.5 1866.66  5115.4 1870.30  5151.0 1878.27  5159.5 1879.09  5187.7 1884.12
  5216.0 1885.34  5245.5 1888.42  5260.2 1888.58  5266.4 1887.96  5268.9 1888.63
#Mann=7,-1,0
  4520.6     0.1       0  4547.0    0.05       0  4703.1     0.1       0
  4867.3    0.05       0  5000.4    0.04       0  5006.4    0.05       0
  5033.7     0.1       0
Bank Sta=5000.4,5006.4
Exp/Cntr=0.3,0.1

Type RM Length L Ch R = 1,276,241,241,241
BEGIN DESCRIPTION:
Mapping XS 7a00559b
END DESCRIPTION:
XS GIS Cut Line= 4
      2719407.86     10073132.61      2719920.03     10073141.29
      2720045.03     10073110.04      2720229.03     10072981.58
#Sta/Elev= 30
  4459.6 1888.11  4538.0 1882.70  4540.5 1882.53  4560.2 1880.80  4620.2 1878.93
  4660.2 1875.75  4687.2 1874.70  4720.2 1873.27  4750.3 1868.72  4770.3 1866.85
  4823.1 1864.78  4920.3 1853.27  4970.7 1852.27  4984.0 1851.83  4998.2 1849.72
  5000.9 1849.22  5004.2 1849.72  5011.5 1850.04  5020.1 1853.09  5032.1 1853.86
  5052.7 1859.21  5061.4 1860.39  5073.3 1861.29  5127.0 1862.15  5172.4 1862.91
  5273.6 1862.29  5294.5 1862.77  5300.6 1863.95  5315.5 1865.07  5325.1 1864.79
#Mann=8,-1,0
  4459.6     0.1       0  4538.0    0.05       0  4540.5     0.1       0
  4687.2    0.05       0  4970.7     0.1       0  4998.2    0.07       0
  5004.2     0.1       0  5127.0    0.05       0
Bank Sta=4998.2,5004.2
Exp/Cntr=0.3,0.1

Type RM Length L Ch R = 1,35,0,0,0
BEGIN DESCRIPTION:
UNT 0034 IN HEWA 1.0
END DESCRIPTION:
XS GIS Cut Line= 4
      2719407.87     10073281.91      2719900.94     10073373.93
      2720079.75     10073351.36      2720235.58     10072987.76
#Sta/Elev= 30
  4417.6 1887.30  4420.4 1887.30  4454.3 1880.57  4489.4 1879.01  4540.3 1874.68
  4564.7 1874.69  4640.8 1869.87  4662.3 1869.77  4732.7 1866.64  4774.2 1863.59
  4785.7 1861.28  4825.1 1855.51  4838.4 1852.52  4886.0 1848.93  4891.0 1847.11
  5004.4 1846.73  5007.2 1846.23  5010.4 1846.73  5085.9 1846.87  5099.4 1846.85
  5111.0 1847.73  5134.6 1850.61  5140.3 1852.35  5158.1 1854.81  5227.4 1860.62
  5292.7 1862.44  5318.0 1862.34  5455.9 1861.70  5486.3 1864.46  5495.0 1864.62
#Mann=7,-1,0
  4417.6    0.05       0  4640.8     0.1       0  4732.7    0.05       0
  5004.4   0.035       0  5010.4    0.05       0  5085.9    0.16       0
  5318.0    0.05       0
Bank Sta=5004.4,5010.4
Exp/Cntr=0.3,0.1

Chan Stop Cuts=-1