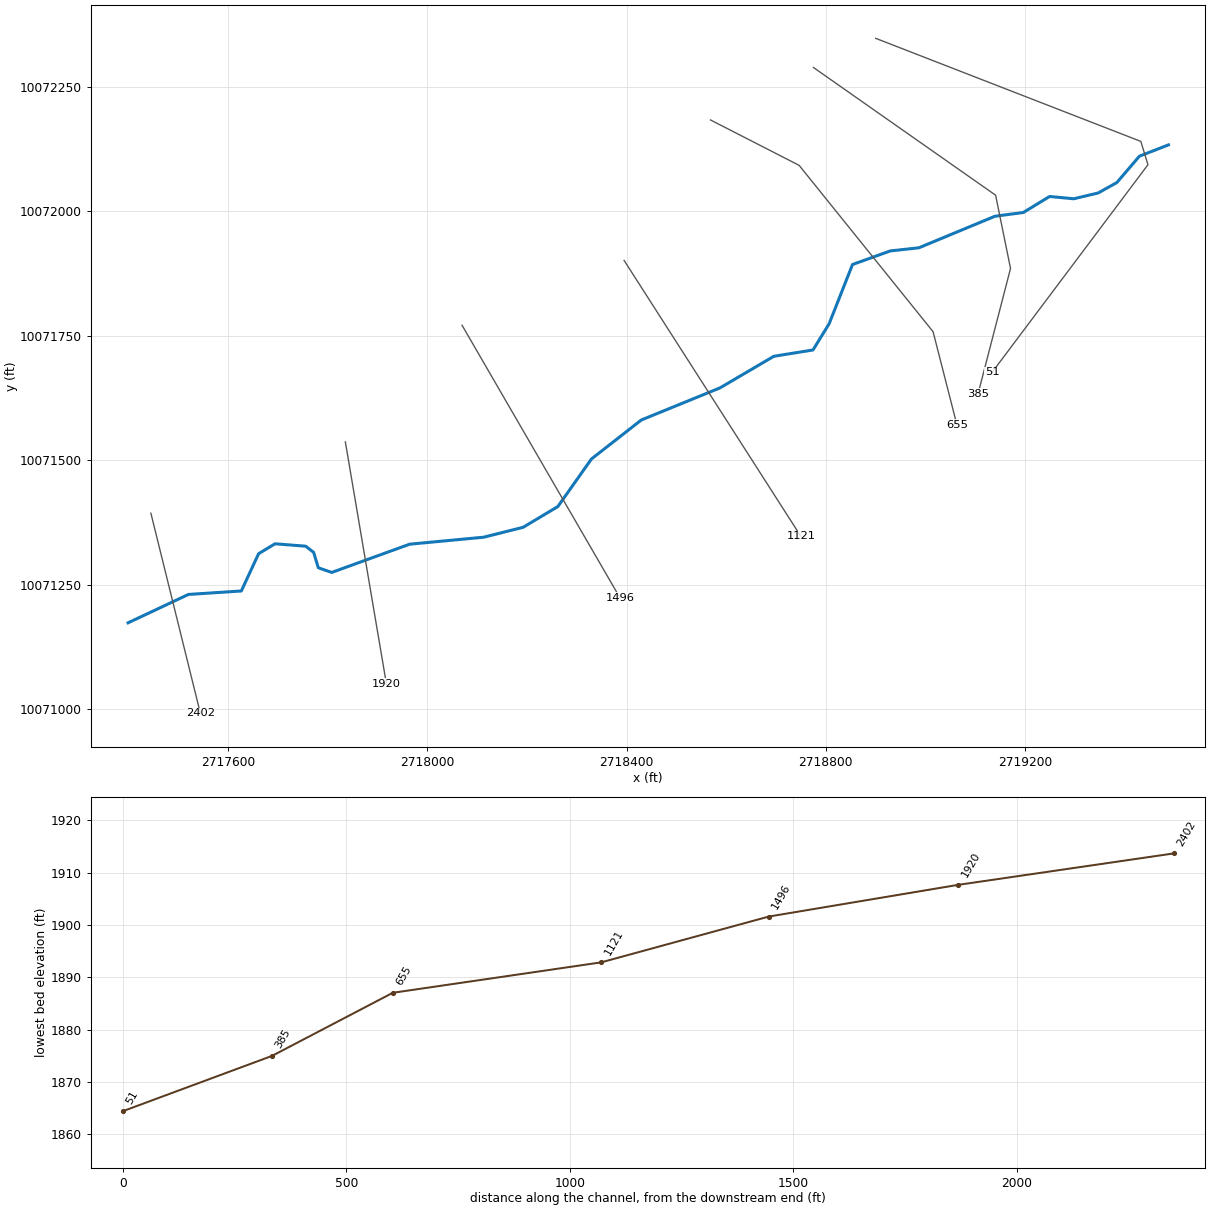
--- UNT 0036 IN HEWA.prj (project) ---

Proj Title=UNT 0036 IN HEWA Base Level Engineering
Current Plan=p01
Default Exp/Contr=0.3,0.1
English Units
Geom File=g01
Flow File=f01
Plan File=p01
Y Axis Title=Elevation
X Axis Title(PF)=Main Channel Distance
X Axis Title(XS)=Station
BEGIN DESCRIPTION:
UNT 0036 IN HEWA
END DESCRIPTION:
DSS Export Rating Curves= 0
DSS Export Rating Curve Sorted= 0
DSS Export Volume Flow Curves= 0
DXF OffsetX= 0
DXF OffsetY= 0
DXF ScaleX= 1
DXF ScaleY= 10

--- UNT 0036 IN HEWA.p01 (plan) ---

Plan Title=Multiple Run
Short Identifier=Multiple
Geom File=g01
Flow File=f01
Subcritical Flow
K Sum by GR= 0
Std Step Tol= 0.01
Critical Tol= 0.01
Num of Std Step Trials= 20
Max Error Tol= 0.3
Flow Tol Ratio= 0.001
Split Flow NTrial= 30
Split Flow Tol= 0.02
Split Flow Ratio= 0.02
Log Output Level= 0
Friction Slope Method= 1
Unsteady Friction Slope Method= 2
Unsteady Bridges Friction Slope Method= 1
Parabolic Critical Depth
Global Vel Dist=  1 , 1 , 1
Global Log Level= 0
CheckData=True
Encroach Param= -1, 0, 0, 0
BEGIN DESCRIPTION:
Multiple Run
END DESCRIPTION:

--- UNT 0036 IN HEWA.f01 (steady flow) ---

Flow Title=Multiple
Program Version=4.10
Number of Profiles= 7
Profile Names=10-year,25-year,50-year,1pct_min,100-year,1pct_plu,500-year
River Rch & RM=UNT 0036 IN HEWA,Reach-1         ,2402
     734    1046    1310    1200    1623    2195    2490
Boundary for River Rch & Prof#=UNT 0036 IN HEWA,Reach-1         , 1
Up Type= 0
Dn Type= 3
Dn Slope=0.032
Boundary for River Rch & Prof#=UNT 0036 IN HEWA,Reach-1         , 2
Up Type= 0
Dn Type= 3
Dn Slope=0.032
Boundary for River Rch & Prof#=UNT 0036 IN HEWA,Reach-1         , 3
Up Type= 0
Dn Type= 3
Dn Slope=0.032
Boundary for River Rch & Prof#=UNT 0036 IN HEWA,Reach-1         , 4
Up Type= 0
Dn Type= 3
Dn Slope=0.032
Boundary for River Rch & Prof#=UNT 0036 IN HEWA,Reach-1         , 5
Up Type= 0
Dn Type= 3
Dn Slope=0.032
Boundary for River Rch & Prof#=UNT 0036 IN HEWA,Reach-1         , 6
Up Type= 0
Dn Type= 3
Dn Slope=0.032
Boundary for River Rch & Prof#=UNT 0036 IN HEWA,Reach-1         , 7
Up Type= 0
Dn Type= 3
Dn Slope=0.032
DSS Import GetInterval= 0
DSS Import GetPeak= 0
DSS Import FillOption= 0

--- UNT 0036 IN HEWA.g01 (geometry) ---

Geom Title=Existing Conditions
Program Version=4.10

River Reach=UNT 0036 IN HEWA,Reach-1
Reach XY= 30
      2717398.65      10071173.7      2717519.76     10071230.66
      2717626.14     10071237.69      2717660.82     10071312.56
       2717693.8     10071332.42      2717755.29     10071327.62
      2717771.34     10071315.31      2717780.74     10071284.29
      2717807.66     10071274.88      2717964.33     10071331.65
      2718112.71     10071345.63      2718192.21     10071365.57
      2718261.85      10071407.2      2718329.42     10071502.83
      2718429.51     10071581.09      2718587.68     10071645.62
      2718695.71     10071709.07       2718774.4     10071721.75
      2718806.75     10071774.29      2718853.79     10071893.43
      2718929.67     10071920.71      2718987.12     10071926.98
      2719139.86     10071990.37      2719196.79     10071997.89
      2719249.62     10072030.06      2719298.14     10072025.45
      2719347.11     10072037.07      2719384.73     10072057.99
      2719430.09     10072111.02      2719488.47     10072133.73

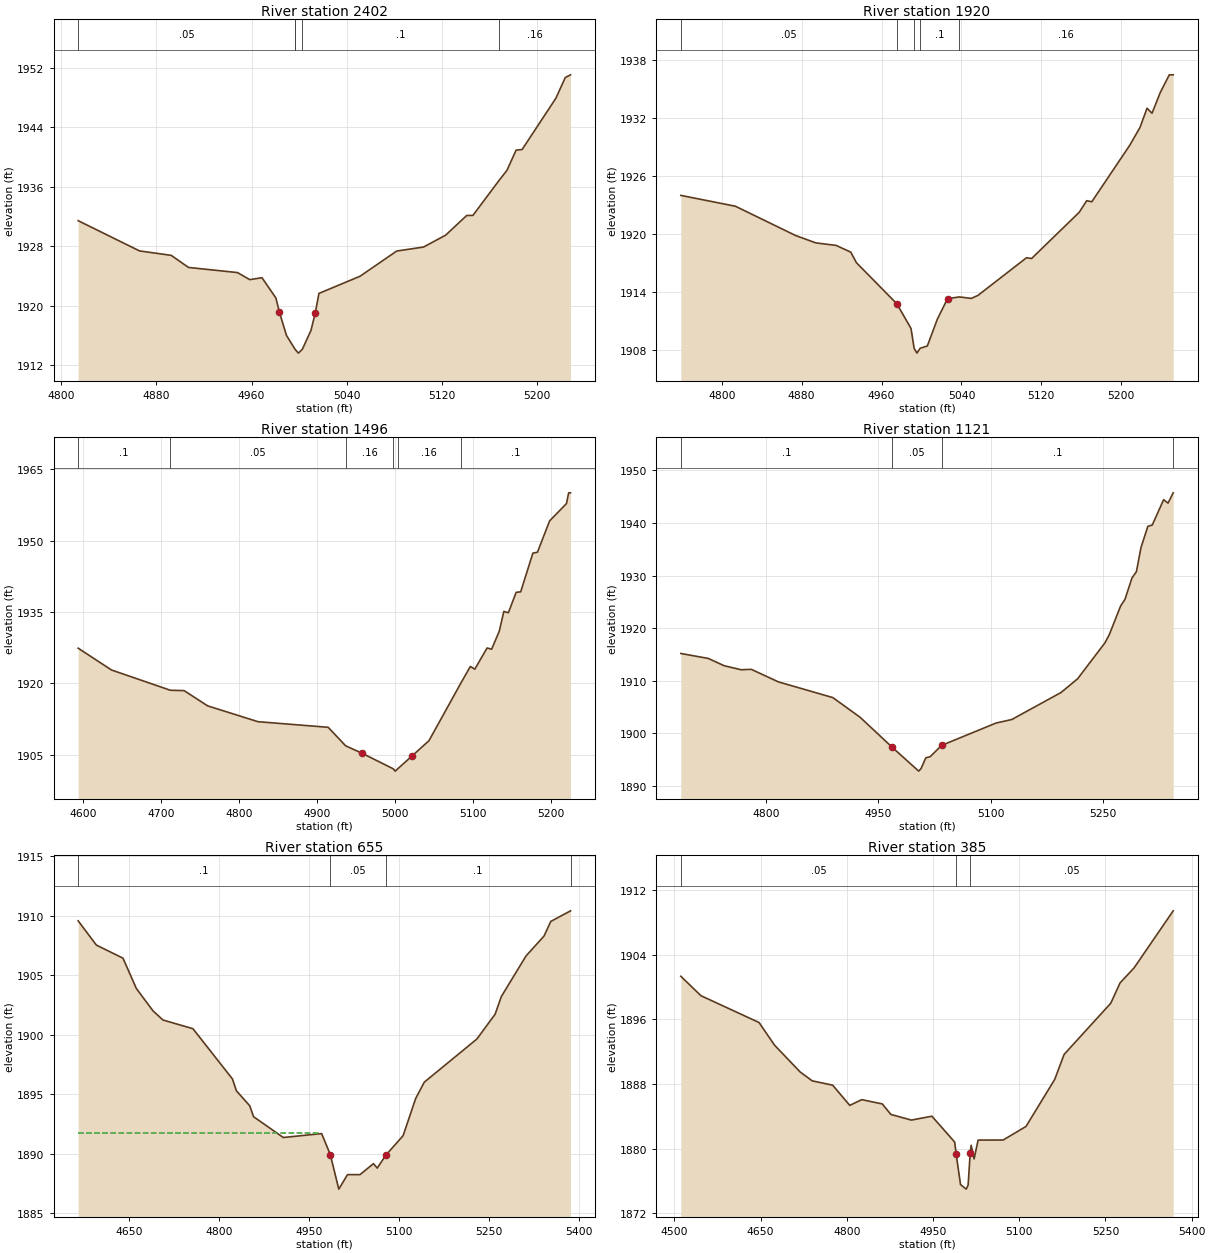
Type RM Length L Ch R = 1 ,2402    ,482,482,482
BEGIN DESCRIPTION:
UNT 0036 IN HEWA 5.0
END DESCRIPTION:
XS GIS Cut Line= 2
      2717444.46     10071393.79      2717543.87      10070991.8
#Sta/Elev= 30
  4814.2 1931.44  4865.8 1927.38  4892.5 1926.78    4907 1925.16  4948.2 1924.47
  4958.5 1923.52  4968.8 1923.78  4980.5 1921.06 4983.52 1919.12  4989.4 1916.03
  4996.5  1914.2  4996.7 1914.15  4999.4 1913.65  5002.7 1914.15    5010  1916.7
 5013.64 1919.07  5016.7 1921.67  5051.2 1923.97  5082.1 1927.36  5104.7  1927.9
  5123.3  1929.5    5141 1932.14  5146.2 1932.15  5168.3 1936.87  5174.8 1938.19
  5182.5 1940.91  5187.6    1941    5216 1947.89  5223.9 1950.67  5228.3 1951.03
#Mann= 5 ,-1 , 0
  4814.2     .05       0  4996.5      .1       0  4996.7     .07       0
  5002.7      .1       0  5168.3     .16       0
Bank Sta=4983.52,5013.64
XS Rating Curve= 0 ,0
Exp/Cntr=0.3,0.1

Type RM Length L Ch R = 1 ,1920    ,424,424,424
BEGIN DESCRIPTION:
UNT 0036 IN HEWA 4.0
END DESCRIPTION:
XS GIS Cut Line= 2
      2717835.08     10071537.03      2717917.53     10071050.97
#Sta/Elev= 30
    4759 1923.99  4813.6 1922.87    4874 1919.83  4894.2 1919.07  4914.5 1918.81
  4929.2 1918.11  4934.8 1917.02  4975.3 1912.76  4989.5  1910.2  4992.6 1908.15
  4995.4 1907.65  4998.6 1908.15  5005.8 1908.39  5015.9 1911.18  5026.1  1913.3
  5037.9 1913.47  5049.9 1913.32  5056.5 1913.63  5105.1 1917.53  5110.2 1917.45
  5157.9 1922.24  5165.4 1923.44  5170.5 1923.33  5208.6  1929.2  5218.8 1931.04
  5225.8 1933.02  5230.8  1932.5  5239.1 1934.66  5248.1 1936.48    5252 1936.48
#Mann= 5 ,-1 , 0
    4759     .05       0  4975.3      .1       0  4992.6     .07       0
  4998.6      .1       0  5037.9     .16       0
Bank Sta=4975.3,5026.1
XS Rating Curve= 0 ,0
Exp/Cntr=0.3,0.1

Type RM Length L Ch R = 1 ,1496    ,375,375,375
BEGIN DESCRIPTION:
Mapping XS 79834a05
END DESCRIPTION:
XS GIS Cut Line= 2
      2718069.46      10071771.4      2718386.29     10071224.55
#Sta/Elev= 30
  4593.3  1927.4  4636.1 1922.82  4711.6 1918.57  4729.3 1918.49  4759.5 1915.29
  4824.1 1911.97  4914.2 1910.79  4936.6 1906.91  4957.5 1905.36  4997.6 1902.09
  5000.3 1901.59  5003.6 1902.09  5022.1 1904.81  5043.6 1907.98  5084.1 1919.94
  5096.7 1923.56  5102.4 1922.99  5118.2 1927.44    5124 1927.18  5133.8 1930.94
  5139.7 1935.11  5145.5 1934.84  5155.5 1939.12  5161.3 1939.23    5177 1947.36
  5182.8 1947.53  5198.5 1954.13  5220.1 1957.76  5222.9 1960.01  5225.3 1960.01
#Mann= 6 ,-1 , 0
  4593.3      .1       0  4711.6     .05       0  4936.6     .16       0
  4997.6     .07       0  5003.6     .16       0  5084.1      .1       0
Bank Sta=4957.5,5022.1
XS Rating Curve= 0 ,0
Exp/Cntr=0.3,0.1

Type RM Length L Ch R = 1 ,1121    ,466,466,466
BEGIN DESCRIPTION:
UNT 0036 IN HEWA 3.0
END DESCRIPTION:
XS GIS Cut Line= 2
      2718394.97     10071901.63      2718750.02      10071347.4
#Sta/Elev= 30
  4685.9 1915.19  4722.6 1914.25  4743.7 1912.87  4766.5  1912.1  4780.1 1912.18
  4816.4 1909.79  4889.1 1906.81  4925.5 1903.08  4968.4 1897.38  5003.9 1892.84
  5007.1 1893.34  5013.4 1895.38  5019.3 1895.59  5034.5 1897.73  5107.2 1901.97
  5128.4 1902.65  5194.1 1907.77  5216.3 1910.38  5252.7 1917.18  5258.6 1918.74
  5273.8 1924.21  5279.7  1925.5    5289 1929.54  5294.9 1930.72    5301 1935.29
  5310.2 1939.34  5316.1 1939.59  5331.3 1944.41  5337.2 1943.76  5344.1 1945.71
#Mann= 4 ,-1 , 0
  4685.9      .1       0  4968.4     .05       0  5034.5      .1       0
  5344.1      .1       0
Bank Sta=4968.4,5034.5
XS Rating Curve= 0 ,0
Exp/Cntr=0.3,0.1

Type RM Length L Ch R = 1 ,655     ,270,270,270
BEGIN DESCRIPTION:
UNT 0036 IN HEWA 2.0
END DESCRIPTION:
XS GIS Cut Line= 4
      2718568.59     10072183.74      2718746.53      10072092.6
      2719015.63      10071758.4      2719063.36     10071571.81
#Sta/Elev= 30
  4564.8 1909.59  4595.2 1907.55  4639.6 1906.45  4661.9  1903.9  4689.7 1902.02
  4706.3 1901.25  4756.3 1900.52  4822.3 1896.29  4828.8  1895.3  4851.1 1894.04
  4857.5 1893.12  4907.1 1891.37  4971.1  1891.7  4985.5 1889.94  4999.7 1887.03
  5014.3 1888.25  5035.1 1888.25  5057.5 1889.17  5063.9  1888.8  5078.3 1889.89
  5107.1 1891.53  5127.9 1894.64  5142.3 1896.02  5230.1 1899.65  5260.6 1901.74
  5270.9 1903.22  5312.2 1906.64  5342.2 1908.31  5353.5 1909.54  5386.4 1910.43
#Mann= 4 ,-1 , 0
  4564.8      .1       0  4985.5     .05       0  5078.3      .1       0
  5386.4      .1       0
#XS Ineff= 2 , 0
         4964.67 1891.78
Permanent Ineff=
       T       T
Bank Sta=4985.5,5078.3
XS Rating Curve= 0 ,0
Exp/Cntr=0.3,0.1

Type RM Length L Ch R = 1 ,385     ,334,334,334
BEGIN DESCRIPTION:
Mapping XS 52e7d402
END DESCRIPTION:
XS GIS Cut Line= 4
      2718775.29     10072289.16      2719141.21     10072032.62
      2719171.16     10071885.49      2719106.07     10071634.22
#Sta/Elev= 30
  4511.3 1901.34  4546.3 1898.93  4647.4 1895.61  4674.4  1892.8  4718.9 1889.49
  4739.8 1888.39  4775.5 1887.85  4805.2 1885.35  4826.1 1886.06  4861.8 1885.53
  4876.7 1884.23  4912.4 1883.53  4948.1 1884.01  4987.7 1880.81 4990.34 1879.31
  4997.9 1875.55  5007.8 1874.98  5011.1 1875.48 5014.77 1879.46  5016.4 1880.41
  5021.5 1878.72  5028.5 1881.05  5072.1 1881.06  5111.8 1882.74  5161.8 1888.57
  5178.1 1891.66  5259.3    1898  5275.4 1900.51  5299.9 1902.38  5367.9 1909.44
#Mann= 3 , 0 , 0
  4511.3     .05       0 4990.34    .035       0 5014.77     .05       0
Bank Sta=4990.34,5014.77
XS Rating Curve= 0 ,0
Exp/Cntr=0.3,0.1

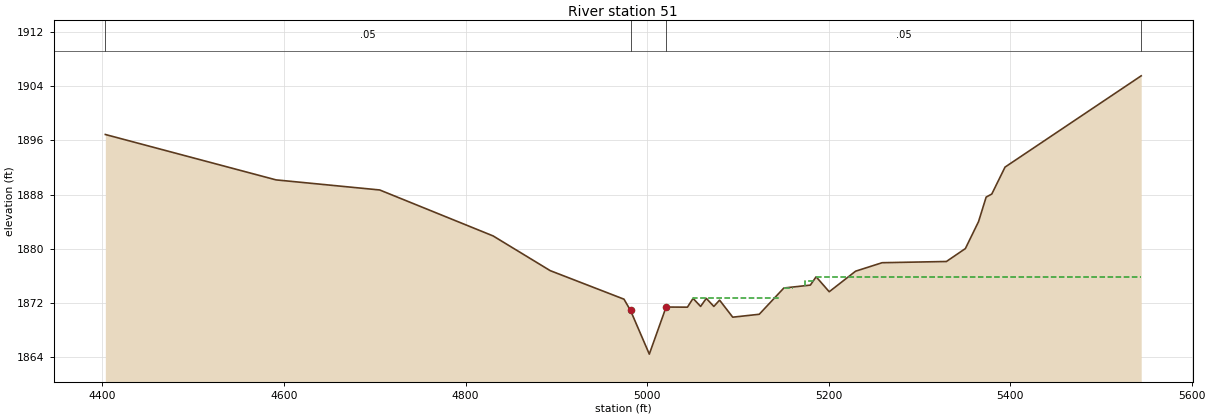
Type RM Length L Ch R = 1 ,51      ,0,0,0
BEGIN DESCRIPTION:
UNT 0036 IN HEWA 1.0
END DESCRIPTION:
XS GIS Cut Line= 4
      2718900.34     10072347.72      2719432.88      10072140.7
       2719447.2     10072093.82       2719134.5     10071677.32
#Sta/Elev= 30
  4403.2 1896.87  4591.3 1890.16  4705.5 1888.67  4830.4 1881.88  4893.3 1876.75
  4974.6 1872.53  4981.8 1870.86  5002.5 1864.41    5021 1871.37  5044.5 1871.35
  5050.7 1872.65    5059 1871.46  5065.3 1872.65  5073.6 1871.46  5079.9 1872.39
  5094.4 1869.87  5123.6  1870.3  5150.7 1874.18  5179.9 1874.61  5186.3 1875.84
  5200.7 1873.63  5229.8 1876.67    5259 1877.92  5329.8  1878.1  5350.7 1880.01
  5365.2 1883.99  5373.6 1887.62  5379.8 1888.07  5394.4 1892.05  5544.4 1905.54
#Mann= 4 ,-1 , 0
  4403.2     .05       0  4981.8    .035       0    5021     .05       0
  5544.4     .05       0
#XS Ineff= 4 ,-1
 5050.59 5145.54 1872.69 5150.66  5161.3 1874.18 5173.51 5183.89 1875.24
 5186.25  5544.4 1875.85
Permanent Ineff=
       T       T       T       T
Bank Sta=4981.8,5021
XS Rating Curve= 0 ,0
Exp/Cntr=0.3,0.1

Chan Stop Cuts=-1
Use User Specified Reach Order=0
Composite Channel Slope=5