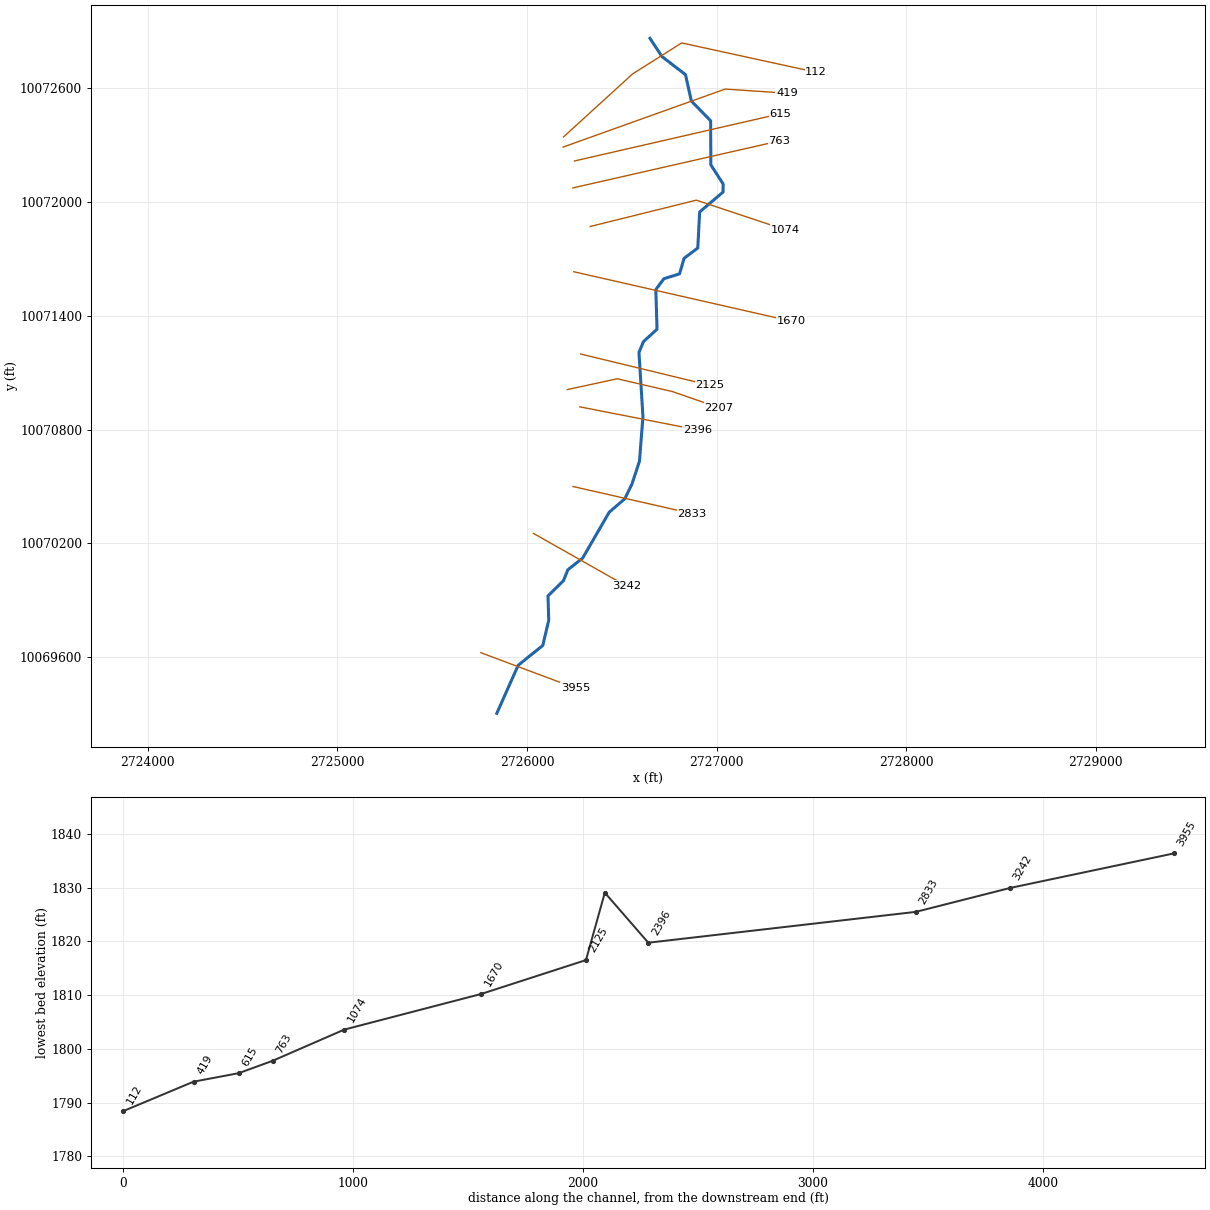
--- UNT 0037 IN HEWA.prj (project) ---

Proj Title=UNT 0037 IN HEWA Base Level Engineering
Current Plan=p01
Default Exp/Contr=0.3,0.1
English Units
Geom File=g01
Flow File=f01
Plan File=p01
Y Axis Title=Elevation
X Axis Title(PF)=Main Channel Distance
X Axis Title(XS)=Station
BEGIN DESCRIPTION:
UNT 0037 IN HEWA
END DESCRIPTION:
DSS Export Rating Curves= 0
DSS Export Rating Curve Sorted= 0
DSS Export Volume Flow Curves= 0
DXF OffsetX= 0
DXF OffsetY= 0
DXF ScaleX= 1
DXF ScaleY= 10

--- UNT 0037 IN HEWA.p01 (plan) ---

Plan Title=Multiple Run
Short Identifier=Multiple
Geom File=g01
Flow File=f01
Subcritical Flow
K Sum by GR= 0
Std Step Tol= 0.01
Critical Tol= 0.01
Num of Std Step Trials= 20
Max Error Tol= 0.3
Flow Tol Ratio= 0.001
Split Flow NTrial= 30
Split Flow Tol= 0.02
Split Flow Ratio= 0.02
Log Output Level= 0
Friction Slope Method= 1
Unsteady Friction Slope Method= 2
Unsteady Bridges Friction Slope Method= 1
Parabolic Critical Depth
Global Vel Dist=  1 , 1 , 1
Global Log Level= 0
CheckData=True
Encroach Param= -1, 0, 0, 0
BEGIN DESCRIPTION:
Multiple Run
END DESCRIPTION:

--- UNT 0037 IN HEWA.f01 (steady flow) ---

Flow Title=Multiple
Program Version=4.10
Number of Profiles= 7
Profile Names=10-year,25-year,50-year,1pct_min,100-year,1pct_plu,500-year
River Rch & RM=UNT 0037 IN HEWA,Reach-1         ,3955
     767    1112    1412    1313    1775    2401    2819
Boundary for River Rch & Prof#=UNT 0037 IN HEWA,Reach-1         , 1
Up Type= 0
Dn Type= 3
Dn Slope=0.018
Boundary for River Rch & Prof#=UNT 0037 IN HEWA,Reach-1         , 2
Up Type= 0
Dn Type= 3
Dn Slope=0.018
Boundary for River Rch & Prof#=UNT 0037 IN HEWA,Reach-1         , 3
Up Type= 0
Dn Type= 3
Dn Slope=0.018
Boundary for River Rch & Prof#=UNT 0037 IN HEWA,Reach-1         , 4
Up Type= 0
Dn Type= 3
Dn Slope=0.018
Boundary for River Rch & Prof#=UNT 0037 IN HEWA,Reach-1         , 5
Up Type= 0
Dn Type= 3
Dn Slope=0.018
Boundary for River Rch & Prof#=UNT 0037 IN HEWA,Reach-1         , 6
Up Type= 0
Dn Type= 3
Dn Slope=0.018
Boundary for River Rch & Prof#=UNT 0037 IN HEWA,Reach-1         , 7
Up Type= 0
Dn Type= 3
Dn Slope=0.018
DSS Import GetInterval= 0
DSS Import GetPeak= 0
DSS Import FillOption= 0

--- UNT 0037 IN HEWA.g01 (geometry) ---

Geom Title=Existing Conditions
Program Version=4.10

River Reach=UNT 0037 IN HEWA,Reach-1
Reach XY= 30
      2725840.53     10069302.87      2725953.23     10069556.59
      2726083.16     10069661.18      2726114.53     10069794.36
      2726110.53     10069922.72      2726192.01     10070002.68
      2726215.26     10070060.38       2726293.4     10070121.92
      2726433.62     10070364.14      2726515.52     10070434.54
      2726553.45     10070512.72      2726593.15     10070633.52
      2726611.43      10070868.4      2726590.43     10071207.22
      2726614.24     10071263.76      2726685.71     10071329.27
      2726679.39     10071538.49      2726722.13     10071595.72
      2726804.57     10071621.33      2726828.55     10071703.56
      2726900.64     10071757.52      2726910.69     10071947.99
      2727034.03     10072052.89      2727034.61       10072095.
       2726969.6       10072196.      2726968.46     10072428.68
      2726866.73     10072533.13      2726835.89     10072672.13
      2726711.96     10072767.38      2726648.47     10072863.73

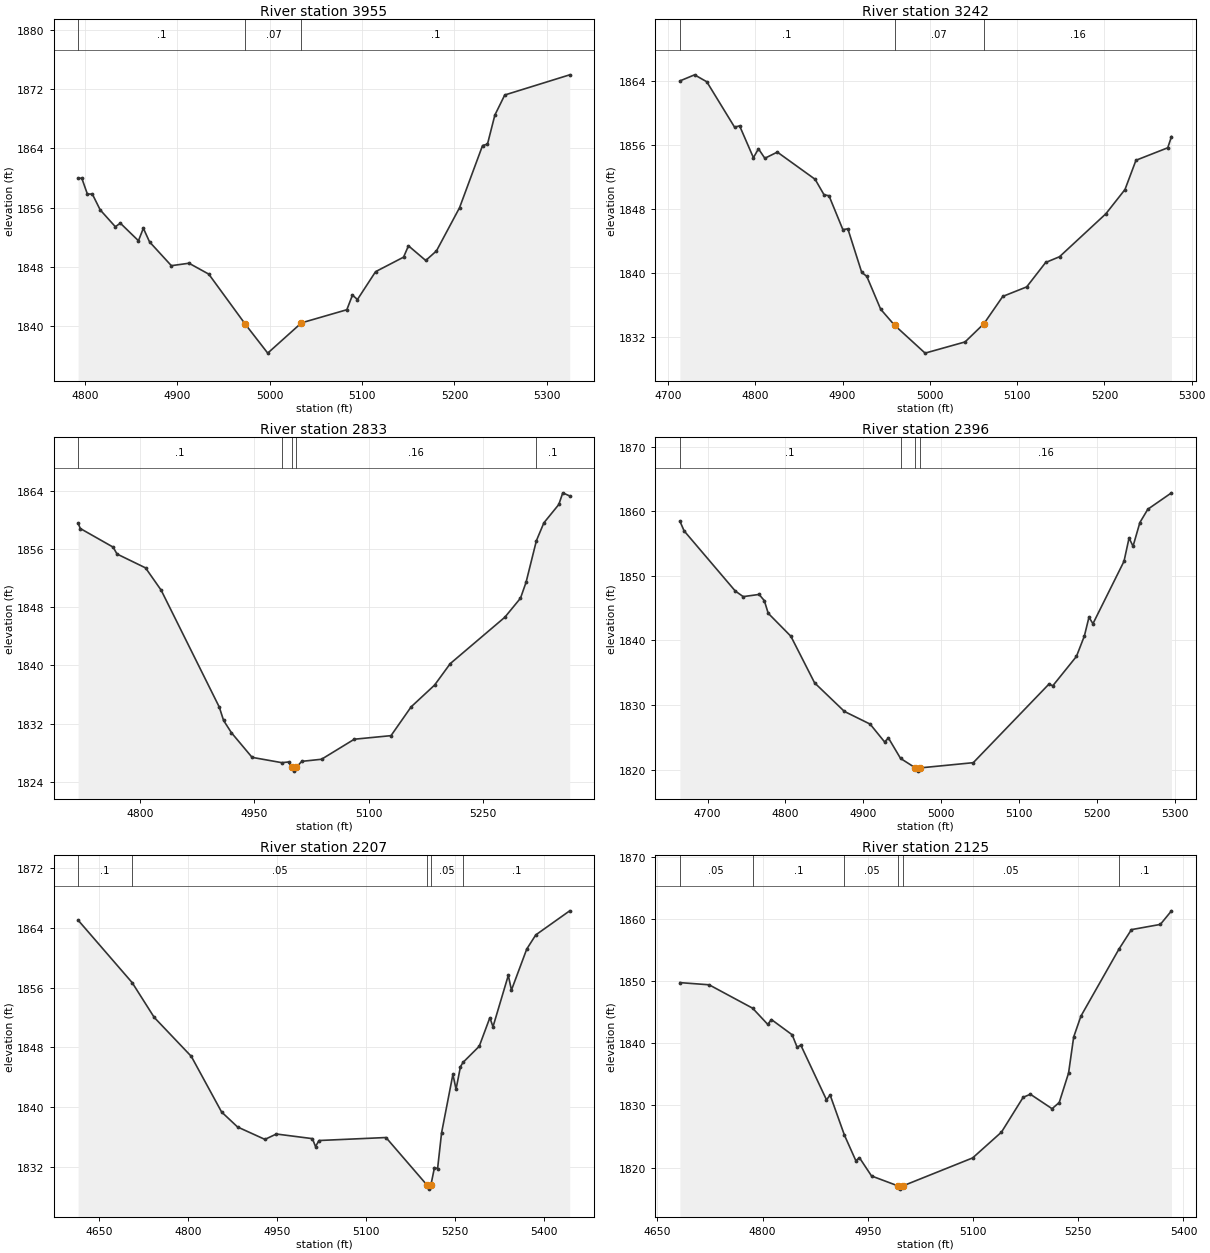
Type RM Length L Ch R = 1 ,3955    ,713,713,713
BEGIN DESCRIPTION:
UNT 0037 IN HEWA 8.0
END DESCRIPTION:
XS GIS Cut Line= 2
      2725756.05     10069622.99      2726254.36     10069436.67
#Sta/Elev= 30
  4792.7 1859.95  4796.7 1859.95  4802.7 1857.82  4808.1 1857.81  4816.6 1855.68
    4833 1853.41  4838.4 1853.89    4858 1851.52  4863.3 1853.21    4870 1851.37
  4893.6 1848.16  4912.7 1848.49  4934.1 1847.02  4973.8 1840.24  4997.9 1836.37
  5034.4 1840.45  5083.5 1842.22  5089.6 1844.19    5095  1843.6  5114.6 1847.35
  5144.9 1849.31  5150.2 1850.84  5168.9 1848.86  5180.5 1850.15  5205.5 1855.98
  5230.4 1864.36  5235.7 1864.54  5243.7 1868.46  5254.4 1871.17  5324.7 1873.89
#Mann= 3 , 0 , 0
  4792.7      .1       0  4973.8     .07       0  5034.4      .1       0
Bank Sta=4973.8,5034.4
XS Rating Curve= 0 ,0
Exp/Cntr=0.3,0.1

Type RM Length L Ch R = 1 ,3242    ,409,409,409
BEGIN DESCRIPTION:
UNT 0037 IN HEWA 7.0
END DESCRIPTION:
XS GIS Cut Line= 2
      2726033.84     10070252.33       2726523.9     10069974.78
#Sta/Elev= 30
  4713.7 1863.96  4730.5 1864.72  4744.5 1863.85  4776.3 1858.18  4782.1 1858.34
  4797.9 1854.36  4803.7 1855.47    4811 1854.29  4825.3 1855.06  4868.6 1851.66
  4878.8 1849.73  4884.5  1849.6  4900.4 1845.37  4906.1 1845.47    4922 1840.02
  4927.8 1839.53  4943.7 1835.42  4959.6 1833.42  4994.6 1829.93  5040.4 1831.33
    5062 1833.61  5083.6 1837.02    5111 1838.21  5132.7 1841.26  5148.6 1841.98
  5201.7 1847.35  5223.6 1850.38  5236.2 1854.04  5272.6  1855.6  5276.9 1857.01
#Mann= 3 , 0 , 0
  4713.7      .1       0  4959.6     .07       0    5062     .16       0
Bank Sta=4959.6,5062
XS Rating Curve= 0 ,0
Exp/Cntr=0.3,0.1

Type RM Length L Ch R = 1 ,2833    ,1163,1163,1163
BEGIN DESCRIPTION:
UNT 0037 IN HEWA 6.0
END DESCRIPTION:
XS GIS Cut Line= 2
      2726242.18     10070499.72      2726871.49      10070356.5
#Sta/Elev= 30
  4718.6 1859.51  4721.5 1858.79  4764.5 1856.24  4769.7 1855.29  4807.1 1853.39
  4827.6 1850.33  4903.9 1834.29  4909.6 1832.44  4919.9 1830.76    4947 1827.38
  4986.1 1826.65  4995.1 1826.75  4998.9 1825.99  5001.7 1825.49  5004.9 1825.99
  5012.2 1826.83  5038.2 1827.12  5081.2 1829.87  5129.4 1830.36  5155.8 1834.31
  5186.6  1837.3  5207.1 1840.24  5278.9 1846.62  5299.4 1849.23  5306.7 1851.41
  5320.3 1857.13  5330.1 1859.57  5349.7 1862.09  5354.9 1863.69    5364 1863.26
#Mann= 5 ,-1 , 0
  4718.6      .1       0  4986.1     .16       0  4998.9     .07       0
  5004.9     .16       0  5320.3      .1       0
Bank Sta=4998.9,5004.9
XS Rating Curve= 0 ,0
Exp/Cntr=0.3,0.1

Type RM Length L Ch R = 1 ,2396    ,189,189,189
BEGIN DESCRIPTION:
UNT 0037 IN HEWA 5.0
END DESCRIPTION:
XS GIS Cut Line= 2
      2726278.67     10070919.85       2726898.3     10070798.53
#Sta/Elev= 30
  4664.4 1858.49  4669.8 1856.99  4735.5 1847.67  4745.7  1846.8  4766.1 1847.14
  4772.8 1846.18  4777.8 1844.22  4806.9 1840.66  4837.4 1833.43  4875.7    1829
  4908.7 1827.04  4927.2 1824.29  4932.3 1824.87  4947.8 1821.72  4966.9 1820.25
  4969.6 1819.75  4972.9 1820.25  5041.2 1821.06  5138.3 1833.23  5143.4 1832.99
  5173.7 1837.53  5183.9  1840.7  5189.8 1843.61  5194.9  1842.6  5234.8 1852.28
  5241.3 1855.89  5246.4 1854.61  5255.2 1858.29  5265.4 1860.35  5295.8 1862.89
#Mann= 4 ,-1 , 0
  4664.4      .1       0  4947.8     .16       0  4966.9     .07       0
  4972.9     .16       0
Bank Sta=4966.9,4972.9
XS Rating Curve= 0 ,0
Exp/Cntr=0.3,0.1

Type RM Length L Ch R = 1 ,2207    ,82,82,82
BEGIN DESCRIPTION:
Mapping XS b854934e
END DESCRIPTION:
XS GIS Cut Line= 4
      2726212.04     10071010.66      2726475.97     10071067.96
      2726767.63     10071000.25      2727012.47     10070915.17
#Sta/Elev= 30
  4614.7 1865.02  4705.9 1856.66    4743 1852.02  4805.5 1846.81  4856.6 1839.37
  4883.5 1837.37  4929.6 1835.71  4948.9 1836.43  5009.7 1835.81  5014.9 1834.75
  5020.8 1835.56  5133.7 1835.96  5203.3 1829.56    5206 1829.06  5209.3 1829.56
  5215.4 1831.94  5220.7 1831.81  5227.4 1836.58  5246.5  1844.4  5251.8 1842.42
  5259.2 1845.42  5263.5    1846  5290.9 1848.16  5308.8 1851.98  5314.1 1850.77
  5339.9 1857.64  5345.2 1855.67    5371 1861.16  5386.2 1863.05  5443.4 1866.27
#Mann= 5 ,-1 , 0
  4614.7      .1       0  4705.9     .05       0  5203.3     .04       0
  5209.3     .05       0  5263.5      .1       0
Bank Sta=5203.3,5209.3
XS Rating Curve= 0 ,0
Exp/Cntr=0.3,0.1

Type RM Length L Ch R = 1 ,2125    ,455,455,455
BEGIN DESCRIPTION:
UNT 0037 IN HEWA 4.0
END DESCRIPTION:
XS GIS Cut Line= 2
        2726283.      10071198.5      2726963.94     10071033.69
#Sta/Elev= 30
  4682.3  1849.8  4723.9 1849.45  4785.9 1845.68  4807.5 1843.07  4812.7 1843.85
  4842.3 1841.39  4849.4 1839.37  4854.5 1839.75  4891.2 1830.91  4896.4 1831.68
  4916.8 1825.21    4933 1821.11  4938.2 1821.58  4955.4 1818.64  4993.6 1817.02
  4996.3 1816.52  4999.6 1817.02  5099.5 1821.55  5140.6 1825.71  5171.5 1831.32
  5181.8 1831.81  5212.7 1829.48  5222.9 1830.48  5236.2 1835.23  5243.5 1841.04
  5253.8  1844.4  5307.9 1855.18  5325.8 1858.34    5367 1859.18  5382.9 1861.37
#Mann= 6 ,-1 , 0
  4682.3     .05       0  4785.9      .1       0  4916.8     .05       0
  4993.6     .04       0  4999.6     .05       0  5307.9      .1       0
Bank Sta=4993.6,4999.6
XS Rating Curve= 0 ,0
Exp/Cntr=0.3,0.1

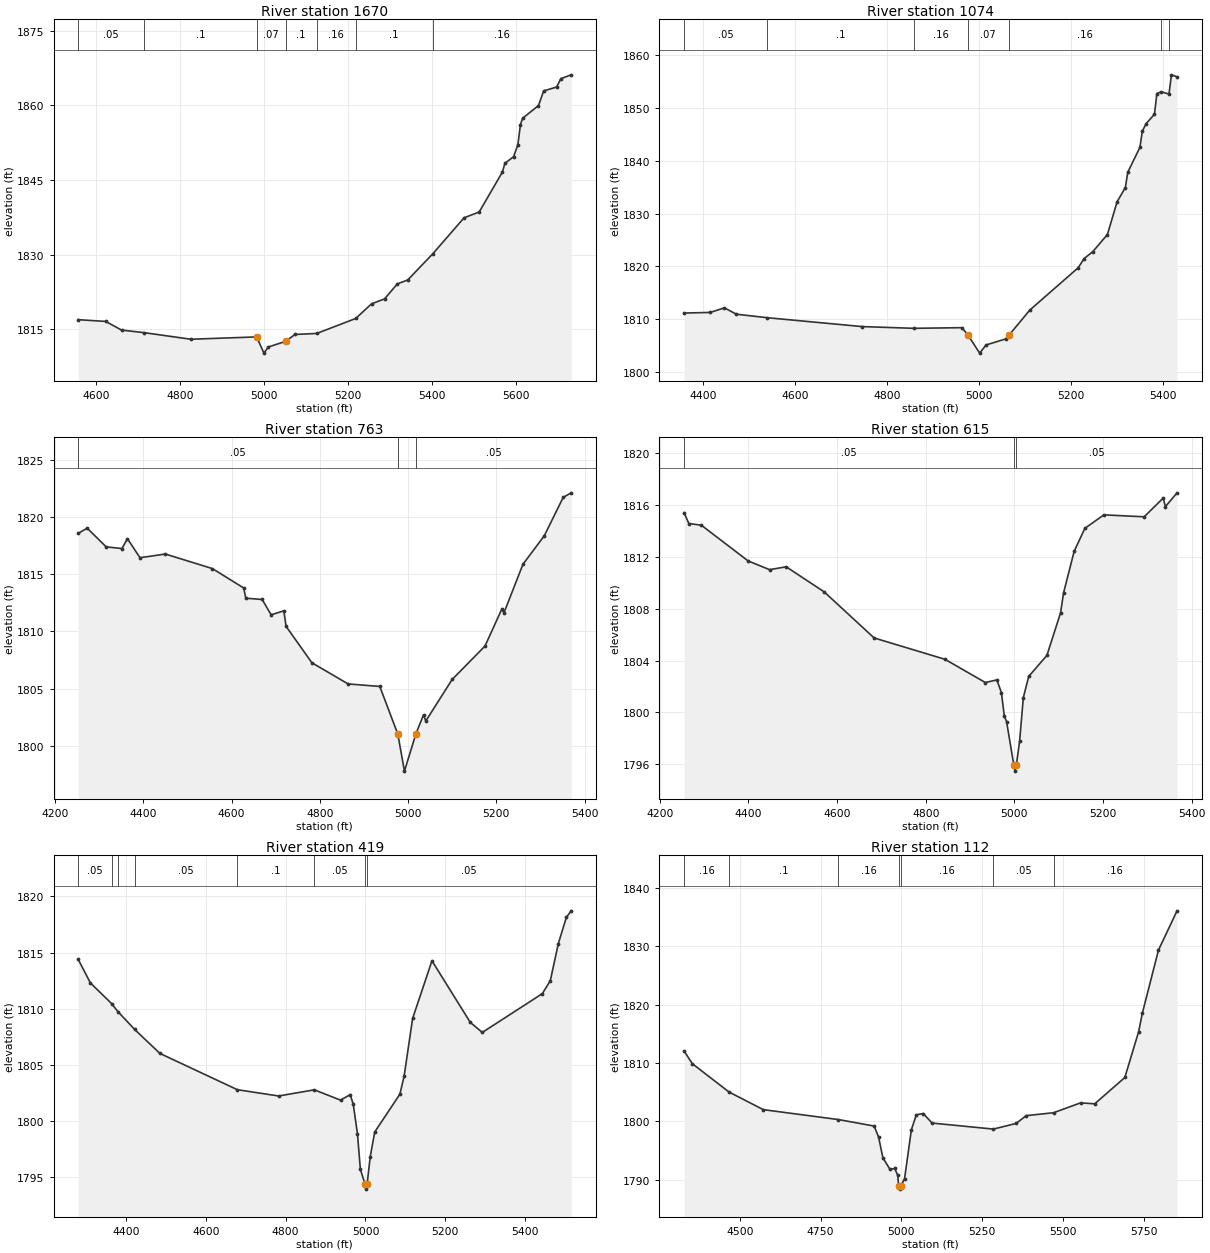
Type RM Length L Ch R = 1 ,1670    ,596,596,596
BEGIN DESCRIPTION:
UNT 0037 IN HEWA 3.0
END DESCRIPTION:
XS GIS Cut Line= 2
      2726246.55     10071632.53      2727392.33     10071372.12
#Sta/Elev= 30
    4557 1816.94  4622.4 1816.59  4660.4 1814.85  4713.6 1814.34  4825.6 1813.01
  4982.4 1813.48  4999.7 1810.22  5010.2 1811.45  5051.2 1812.58  5073.7 1813.97
  5125.5 1814.17  5218.4 1817.18  5256.3 1820.13  5287.1 1821.11  5317.8 1824.14
  5342.3 1824.91    5402 1830.16  5476.7 1837.41  5512.7 1838.57  5567.9 1846.57
  5574.2 1848.37  5594.7 1849.67    5605 1852.09    5611 1856.09  5616.1 1857.39
  5654.1 1859.96  5666.5 1862.91  5697.2 1863.67  5707.5 1865.37    5732 1866.13
#Mann= 7 ,-1 , 0
    4557     .05       0  4713.6      .1       0  4982.4     .07       0
  5051.2      .1       0  5125.5     .16       0  5218.4      .1       0
    5402     .16       0
Bank Sta=4982.4,5051.2
XS Rating Curve= 0 ,0
Exp/Cntr=0.3,0.1

Type RM Length L Ch R = 1 ,1074    ,311,311,311
BEGIN DESCRIPTION:
UNT 0037 IN HEWA 2.0
END DESCRIPTION:
XS GIS Cut Line= 3
      2726333.32     10071871.24      2726893.23     10072010.14
      2727361.99     10071853.88
#Sta/Elev= 30
  4359.4 1811.17  4416.2 1811.29  4447.1 1812.15  4473.2 1810.95  4539.9 1810.29
  4745.9 1808.61  4858.2 1808.28  4962.9  1808.4  4975.5  1807.1  5001.6 1803.58
  5015.6 1805.13  5057.8 1806.26  5065.1 1806.96  5110.5 1811.73  5215.9 1819.77
  5228.5 1821.49  5247.5 1822.81  5279.1 1826.04  5300.2 1832.25  5318.1 1834.93
  5323.4 1837.85  5349.7 1842.54    5355 1845.62  5363.4 1847.07  5381.3 1848.81
  5386.6 1852.75  5396.1 1853.07  5412.9 1852.65  5418.2 1856.29  5430.4 1855.91
#Mann= 7 ,-1 , 0
  4359.4     .05       0  4539.9      .1       0  4858.2     .16       0
  4975.5     .07       0  5065.1     .16       0  5396.1      .1       0
  5412.9     .16       0
Bank Sta=4975.5,5065.1
XS Rating Curve= 0 ,0
Exp/Cntr=0.3,0.1

Type RM Length L Ch R = 1 ,763     ,148,148,148
BEGIN DESCRIPTION:
Mapping XS 81b44cd3
END DESCRIPTION:
XS GIS Cut Line= 2
      2726241.83     10072074.61      2727331.56     10072322.63
#Sta/Elev= 30
  4252.1 1818.56  4272.5 1819.01  4315.5 1817.38  4351.2 1817.23  4363.7 1818.09
  4392.2 1816.43  4449.8 1816.75  4556.3 1815.48  4627.1 1813.79  4632.2 1812.89
  4669.1 1812.78  4689.6 1811.44  4718.3 1811.79  4723.4 1810.43  4781.9 1807.25
    4864  1805.4  4935.8 1805.18  4976.8    1801  4991.7 1797.78  5017.8 1801.05
    5035  1802.7  5040.1 1802.16  5099.9 1805.79  5174.3 1808.71  5212.3 1811.93
  5217.4 1811.62  5260.4 1815.86  5308.6 1818.34  5351.6  1821.7  5369.7  1822.1
#Mann= 3 , 0 , 0
  4252.1     .05       0  4976.8     .05       0  5017.8     .05       0
Bank Sta=4976.8,5017.8
XS Rating Curve= 0 ,0
Exp/Cntr=0.3,0.1

Type RM Length L Ch R = 1 ,615     ,196,196,196
BEGIN DESCRIPTION:
Mapping XS 094441b3
END DESCRIPTION:
XS GIS Cut Line= 2
      2726250.38     10072216.86      2727334.72     10072465.58
#Sta/Elev= 30
  4254.6 1815.41  4265.5 1814.58  4293.7 1814.45  4399.3 1811.69  4447.6 1811.02
  4485.1 1811.24  4570.7 1809.31  4683.5 1805.75  4843.5  1804.1  4934.4 1802.31
  4960.6 1802.51  4970.8 1801.52  4977.3 1799.72  4982.4  1799.3  4998.6 1795.97
  5001.3 1795.47  5004.6 1795.97  5011.9 1797.81  5020.2 1801.14  5032.4 1802.78
  5073.4  1804.4  5104.2 1807.68  5111.1 1809.24    5135 1812.44  5159.1 1814.21
    5202 1815.25  5292.9  1815.1  5335.7 1816.54  5340.9 1815.89  5367.1 1816.95
#Mann= 3 ,-1 , 0
  4254.6     .05       0  4998.6     .04       0  5004.6     .05       0
Bank Sta=4998.6,5004.6
XS Rating Curve= 0 ,0
Exp/Cntr=0.3,0.1

Type RM Length L Ch R = 1 ,419     ,307,307,307
BEGIN DESCRIPTION:
Mapping XS df78eaa5
END DESCRIPTION:
XS GIS Cut Line= 3
      2726190.02     10072290.14      2727045.14     10072596.07
      2727370.62     10072574.37
#Sta/Elev= 30
  4280.7 1814.39  4311.2 1812.29  4364.5 1810.44  4380.1 1809.73    4422 1808.14
  4485.2    1806  4679.3 1802.76  4782.4  1802.2    4872 1802.75  4937.5 1801.83
  4961.7 1802.32  4969.4 1801.47    4980 1798.82  4987.2 1795.68  4998.3 1794.39
    5001 1793.89  5004.3 1794.39  5011.9 1796.77  5023.2 1798.99  5086.2 1802.36
  5096.8 1803.97  5118.1 1809.12  5166.5 1814.26  5262.4 1808.77  5292.5 1807.87
  5442.8 1811.33  5462.8 1812.48  5482.9 1815.79  5502.9 1818.13  5515.1 1818.72
#Mann= 8 ,-1 , 0
  4280.7     .05       0  4364.5     .16       0  4380.1      .1       0
    4422     .05       0  4679.3      .1       0    4872     .05       0
  4998.3     .04       0  5004.3     .05       0
Bank Sta=4998.3,5004.3
XS Rating Curve= 0 ,0
Exp/Cntr=0.3,0.1

Type RM Length L Ch R = 1 ,112     ,0,0,0
BEGIN DESCRIPTION:
UNT 0037 IN HEWA 1.0
END DESCRIPTION:
XS GIS Cut Line= 4
      2726192.37     10072343.55      2726556.37     10072675.71
      2726815.75     10072839.52      2727524.56     10072685.04
#Sta/Elev= 30
  4327.7 1812.07  4353.2 1809.89  4466.9 1805.03  4572.8 1802.01  4805.3 1800.31
  4915.7  1799.2  4929.4 1797.32  4942.8 1793.76  4964.9 1791.76  4979.3 1791.94
  4988.5 1790.78  4991.6 1788.89  4994.3 1788.39  4997.6 1788.89  5009.8 1790.18
    5031 1798.59  5046.3 1801.13  5067.5 1801.34    5095 1799.71  5284.6 1798.68
  5355.2 1799.65  5385.9 1800.98  5470.6 1801.48  5554.2 1803.17  5598.1 1803.01
  5691.2 1807.52  5733.9 1815.37  5745.3 1818.52  5795.3 1829.36  5852.7 1836.08
#Mann= 7 ,-1 , 0
  4327.7     .16       0  4466.9      .1       0  4805.3     .16       0
  4991.6     .07       0  4997.6     .16       0  5284.6     .05       0
  5470.6     .16       0
Bank Sta=4991.6,4997.6
XS Rating Curve= 0 ,0
Exp/Cntr=0.3,0.1

Chan Stop Cuts=-1
Use User Specified Reach Order=0
Composite Channel Slope=5