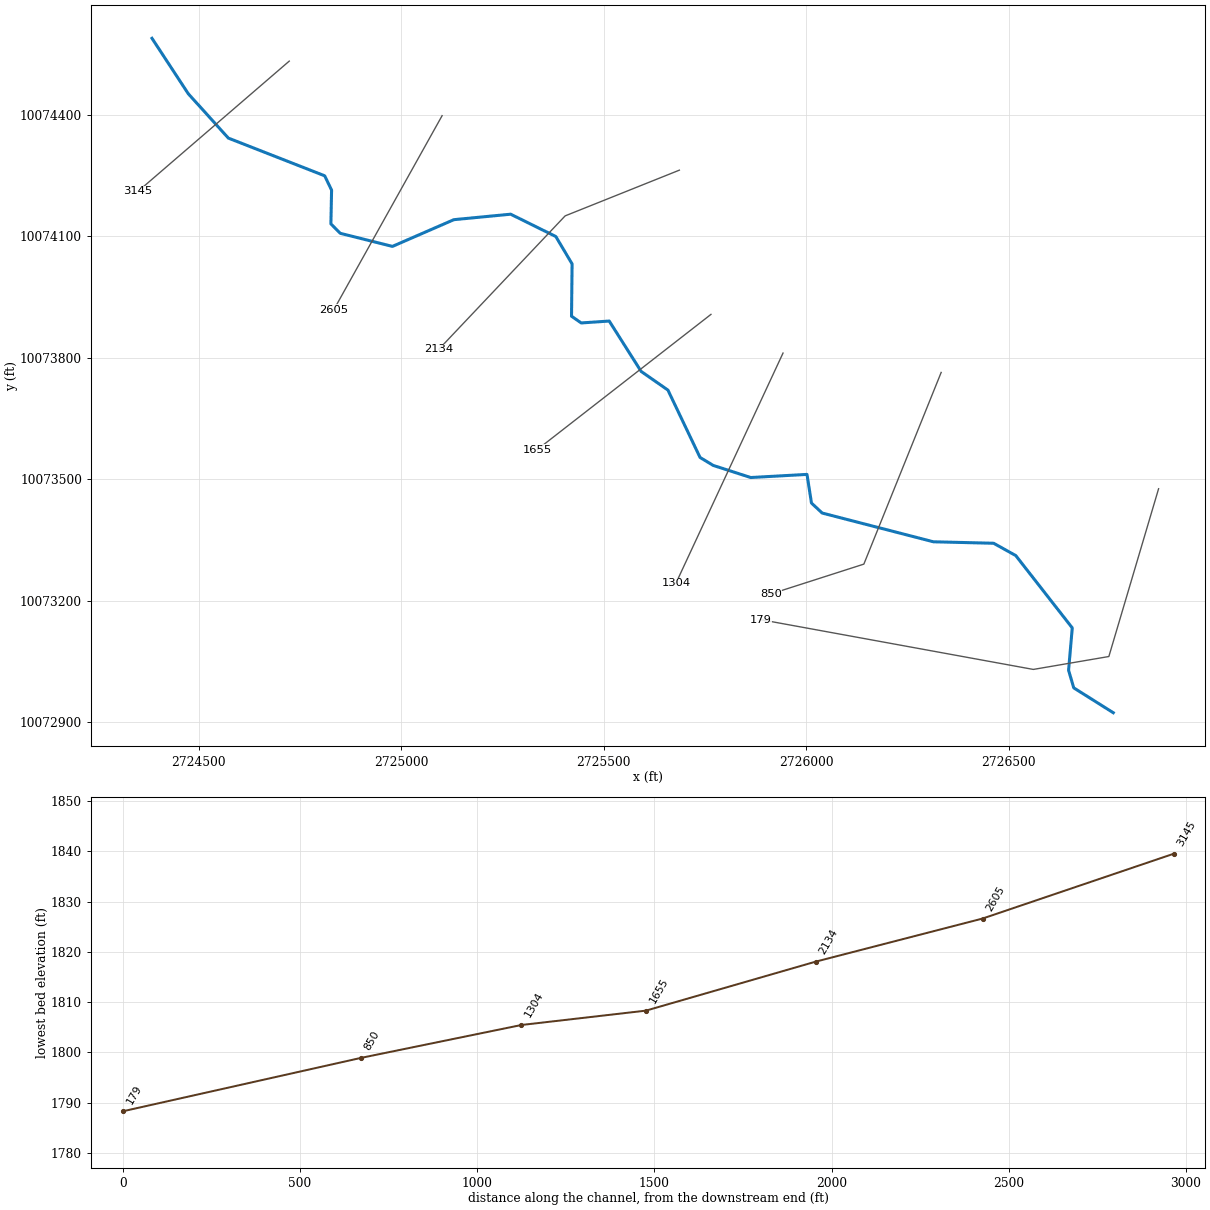
--- UNT 0038 IN HEWA.prj (project) ---

Proj Title=UNT 0038 IN HEWA Base Level Engineering
Current Plan=p01
Default Exp/Contr=0.3,0.1
English Units
Geom File=g01
Flow File=f01
Plan File=p01
BEGIN DESCRIPTION:
UNT 0038 IN HEWA
END DESCRIPTION:

--- UNT 0038 IN HEWA.p01 (plan) ---

Plan Title=Multiple Run
Short Identifier=Multiple
Geom File=g01
Flow File=f01
Subcritical Flow
K Sum by GR= 0
Std Step Tol= 0.01
Critical Tol= 0.01
Num of Std Step Trials= 20
Max Error Tol= 0.3
Flow Tol Ratio= 0.001
Split Flow NTrial= 30
Split Flow Tol= 0.02
Split Flow Ratio= 0.02
Log Output Level= 0
Friction Slope Method= 1
Unsteady Friction Slope Method= 2
Unsteady Bridges Friction Slope Method= 1
Parabolic Critical Depth
Global Vel Dist=  1 , 1 , 1
Global Log Level= 0
CheckData=True
Encroach Param= -1, 0, 0, 0
BEGIN DESCRIPTION:
Multiple Run
END DESCRIPTION:

--- UNT 0038 IN HEWA.f01 (steady flow) ---

Flow Title=Multiple
Number of Profiles=7
Profile Names=10-year,25-year,50-year,1pct_min,100-year,1pct_plu,500-year
River Rch & RM= UNT 0038 IN HEWA,Reach-1,3145
     558     794     995     915    1237    1673    1919
Boundary for River Rch & Prof#=UNT 0038 IN HEWA,Reach-1,1
Up Type=0
Dn Type=3
Dn Slope=0.005
Boundary for River Rch & Prof#=UNT 0038 IN HEWA,Reach-1,2
Up Type=0
Dn Type=3
Dn Slope=0.005
Boundary for River Rch & Prof#=UNT 0038 IN HEWA,Reach-1,3
Up Type=0
Dn Type=3
Dn Slope=0.005
Boundary for River Rch & Prof#=UNT 0038 IN HEWA,Reach-1,4
Up Type=0
Dn Type=3
Dn Slope=0.005
Boundary for River Rch & Prof#=UNT 0038 IN HEWA,Reach-1,5
Up Type=0
Dn Type=3
Dn Slope=0.005
Boundary for River Rch & Prof#=UNT 0038 IN HEWA,Reach-1,6
Up Type=0
Dn Type=3
Dn Slope=0.005
Boundary for River Rch & Prof#=UNT 0038 IN HEWA,Reach-1,7
Up Type=0
Dn Type=3
Dn Slope=0.005

--- UNT 0038 IN HEWA.g01 (geometry) ---

Geom Title=Existing Conditions

River Reach=UNT 0038 IN HEWA,Reach-1
Reach XY= 30
      2724384.07     10074588.13      2724473.69     10074451.38
      2724572.71     10074341.86      2724810.60     10074248.83
      2724827.68     10074213.49      2724825.97     10074130.16
      2724849.23     10074106.85      2724977.94     10074074.58
      2725129.78     10074140.55      2725269.95     10074154.07
      2725381.52     10074099.00      2725421.70     10074031.43
      2725420.30     10073902.31      2725444.19     10073885.67
      2725513.40     10073890.40      2725592.24     10073766.09
      2725658.42     10073720.00      2725737.76     10073553.76
      2725770.29     10073534.10      2725862.95     10073504.20
      2726001.91     10073511.92      2726012.99     10073441.17
      2726039.44     10073416.57      2726314.10     10073345.63
      2726462.93     10073342.00      2726517.59     10073311.61
      2726657.11     10073133.11      2726648.00     10073028.59
      2726660.77     10072985.15      2726758.47     10072923.73

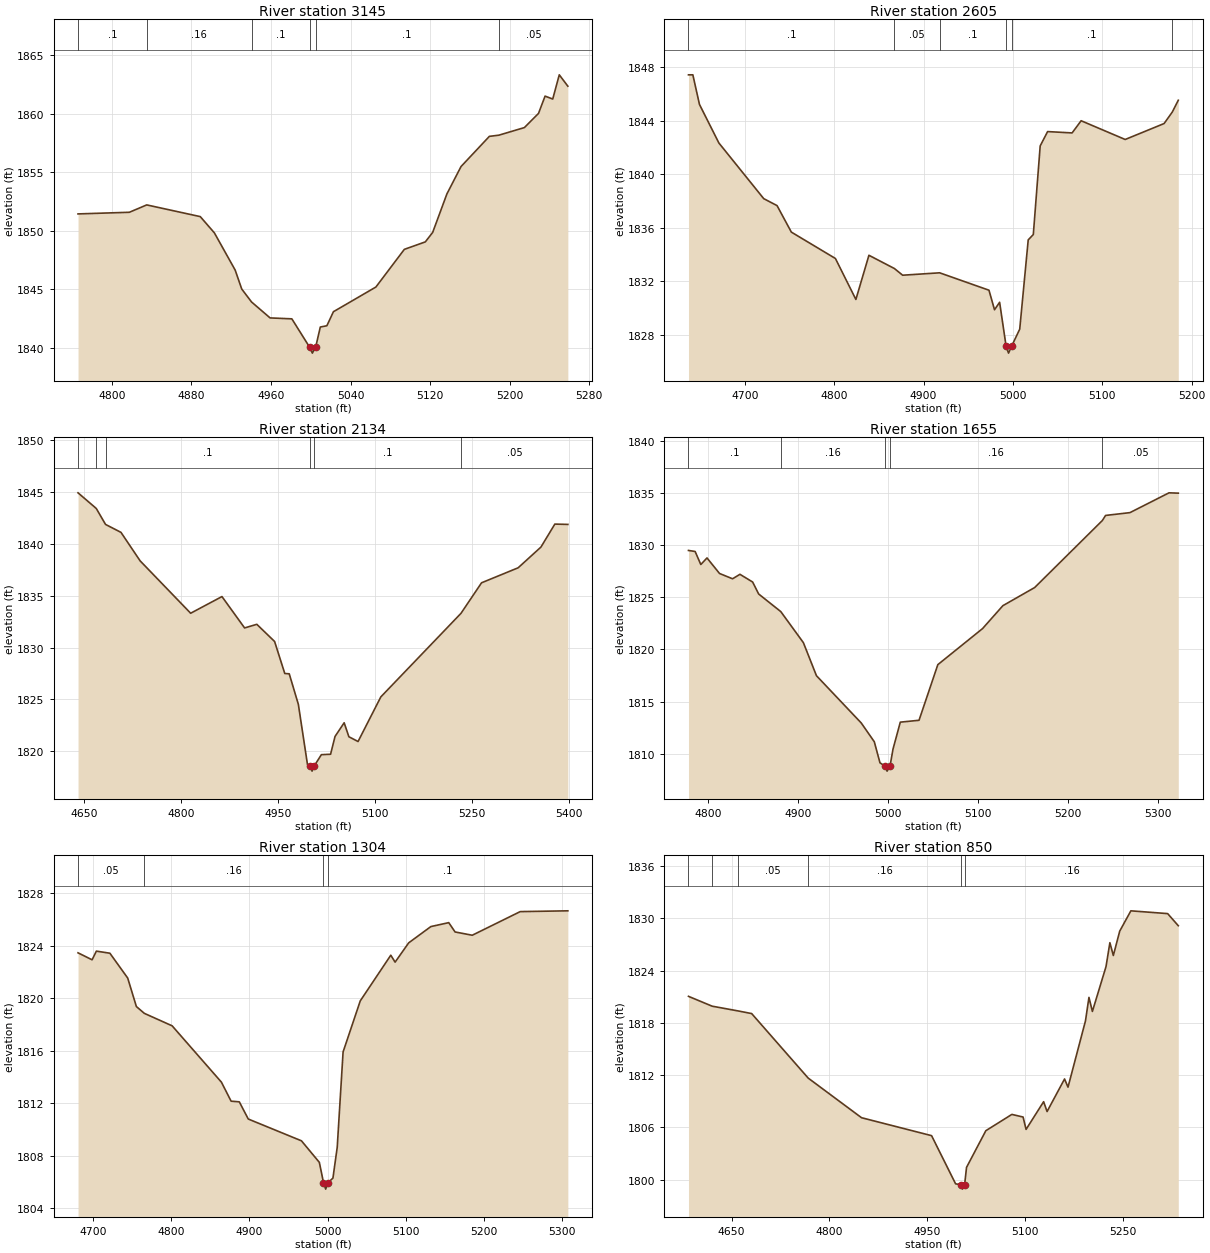
Type RM Length L Ch R = 1,3145,540,540,540
BEGIN DESCRIPTION:
UNT 0038 IN HEWA 5.0
END DESCRIPTION:
XS GIS Cut Line= 2
      2724723.13     10074531.86      2724349.81     10074210.64
#Sta/Elev= 30
  4766.0 1851.43  4817.6 1851.57  4835.1 1852.20  4888.9 1851.20  4903.1 1849.81
  4924.0 1846.63  4930.6 1845.01  4940.5 1843.90  4959.1 1842.54  4981.0 1842.46
  4998.9 1840.03  5001.6 1839.53  5004.9 1840.03  5009.6 1841.76  5016.2 1841.87
  5022.8 1843.07  5065.5 1845.18  5094.1 1848.40  5115.2 1849.04  5122.6 1849.85
  5136.9 1853.14  5151.1 1855.48  5179.6 1858.06  5189.1 1858.16  5214.8 1858.81
  5229.0 1860.02  5235.6 1861.50  5243.3 1861.25  5249.9 1863.32  5258.5 1862.35
#Mann=6,-1,0
  4766.0     0.1       0  4835.1    0.16       0  4940.5     0.1       0
  4998.9    0.07       0  5004.9     0.1       0  5189.1    0.05       0
Bank Sta=4998.9,5004.9
Exp/Cntr=0.3,0.1

Type RM Length L Ch R = 1,2605,471,471,471
BEGIN DESCRIPTION:
UNT 0038 IN HEWA 4.0
END DESCRIPTION:
XS GIS Cut Line= 2
      2725100.68     10074397.25      2724833.45     10073918.82
#Sta/Elev= 30
  4637.0 1847.42  4641.9 1847.42  4649.3 1845.21  4671.0 1842.33  4721.2 1838.17
  4736.1 1837.65  4752.1 1835.67  4801.4 1833.70  4824.3 1830.64  4838.9 1833.94
  4867.4 1832.95  4876.6 1832.45  4918.0 1832.63  4973.2 1831.33  4979.4 1829.87
  4985.1 1830.43  4992.4 1827.13  4995.1 1826.63  4998.4 1827.13  5007.6 1828.42
  5017.1 1835.09  5022.8 1835.49  5030.5 1842.11  5038.8 1843.18  5066.2 1843.08
  5076.3 1843.99  5125.6 1842.59  5169.1 1843.78  5178.3 1844.64  5185.0 1845.52
#Mann=6,-1,0
  4637.0     0.1       0  4867.4    0.05       0  4918.0     0.1       0
  4992.4    0.07       0  4998.4     0.1       0  5178.3    0.05       0
Bank Sta=4992.4,4998.4
Exp/Cntr=0.3,0.1

Type RM Length L Ch R = 1,2134,479,479,479
BEGIN DESCRIPTION:
UNT 0038 IN HEWA 3.0
END DESCRIPTION:
XS GIS Cut Line= 3
      2725686.66     10074262.75      2725404.52     10074149.89
      2725092.74     10073820.80
#Sta/Elev= 30
  4641.2 1844.94  4669.4 1843.43  4683.7 1841.89  4707.6 1841.12  4737.2 1838.37
  4815.3 1833.31  4863.7 1834.92  4898.7 1831.89  4917.6 1832.24  4945.1 1830.58
  4960.8 1827.49  4967.7 1827.46  4981.8 1824.51  4996.0 1818.66  5000.3 1818.56
  5003.0 1818.06  5006.3 1818.56  5017.4 1819.65  5031.6 1819.69  5038.5 1821.41
  5052.6 1822.73  5059.9 1821.38  5074.1 1820.92  5109.3 1825.23  5233.2 1833.30
  5265.0 1836.25  5321.6 1837.70  5356.8 1839.70  5378.3 1841.92  5398.4 1841.89
#Mann=6,-1,0
  4641.2     0.1       0  4669.4    0.16       0  4683.7     0.1       0
  5000.3    0.07       0  5006.3     0.1       0  5233.2    0.05       0
Bank Sta=5000.3,5006.3
Exp/Cntr=0.3,0.1

Type RM Length L Ch R = 1,1655,351,351,351
BEGIN DESCRIPTION:
Mapping XS c9d9dfc5
END DESCRIPTION:
XS GIS Cut Line= 2
      2725764.74     10073906.82      2725335.10     10073572.65
#Sta/Elev= 30
  4778.5 1829.50  4785.9 1829.40  4792.2 1828.15  4799.1 1828.78  4813.0 1827.29
  4827.5 1826.78  4835.7 1827.21  4849.8 1826.47  4856.5 1825.32  4881.1 1823.63
  4906.2 1820.65  4920.7 1817.48  4970.5 1812.94  4985.0 1811.14  4991.3 1809.12
  4996.5 1808.82  4999.2 1808.32  5002.5 1808.82  5005.8 1810.44  5013.9 1813.02
  5034.7 1813.20  5055.6 1818.54  5105.3 1822.00  5127.9 1824.20  5163.2 1825.94
  5238.4 1832.37  5242.0 1832.86  5269.1 1833.13  5312.5 1835.03  5322.8 1835.00
#Mann=5,-1,0
  4778.5     0.1       0  4881.1    0.16       0  4996.5    0.07       0
  5002.5    0.16       0  5238.4    0.05       0
Bank Sta=4996.5,5002.5
Exp/Cntr=0.3,0.1

Type RM Length L Ch R = 1,1304,454,454,454
BEGIN DESCRIPTION:
Mapping XS ed12d980
END DESCRIPTION:
XS GIS Cut Line= 2
      2725942.73     10073811.39      2725677.97     10073242.81
#Sta/Elev= 30
  4680.5 1823.47  4698.5 1822.94  4704.0 1823.60  4721.3 1823.44  4744.1 1821.55
  4755.2 1819.38  4765.4 1818.86  4801.0 1817.91  4864.1 1813.62  4876.5 1812.17
  4887.0 1812.12  4898.5 1810.81  4966.6 1809.15  4989.5 1807.51  4994.8 1805.97
  4997.6 1805.47  5000.8 1805.97  5006.9 1806.31  5012.4 1808.66  5019.9 1815.92
  5041.9 1819.81  5081.0 1823.29  5086.5 1822.76  5103.9 1824.23  5132.3 1825.47
  5155.2 1825.77  5163.3 1825.06  5185.3 1824.81  5246.7 1826.61  5307.7 1826.67
#Mann=4,-1,0
  4680.5    0.05       0  4765.4    0.16       0  4994.8    0.07       0
  5000.8     0.1       0
Bank Sta=4994.8,5000.8
Exp/Cntr=0.3,0.1

Type RM Length L Ch R = 1,850,671,671,671
BEGIN DESCRIPTION:
UNT 0038 IN HEWA 2.0
END DESCRIPTION:
XS GIS Cut Line= 3
      2726333.32     10073763.57      2726142.36     10073290.52
      2725912.92     10073216.92
#Sta/Elev= 30
  4583.8 1821.05  4620.1 1819.92  4659.5 1819.38  4680.7 1819.07  4767.4 1811.66
  4849.2 1807.11  4956.6 1805.05  4993.4 1799.52  5001.2 1799.41  5004.0 1798.91
  5007.2 1799.41  5010.2 1801.41  5039.8 1805.62  5079.7 1807.49  5096.9 1807.19
  5101.5 1805.77  5128.4 1808.95  5133.7 1807.82  5160.5 1811.56  5165.8 1810.62
  5192.6 1818.24  5197.9 1820.93  5203.2 1819.32  5224.1 1824.47  5230.0 1827.21
  5235.3 1825.74  5245.1 1828.54  5262.2 1830.87  5318.6 1830.55  5334.9 1829.16
#Mann=6,-1,0
  4583.8    0.05       0  4620.1     0.1       0  4659.5    0.05       0
  4767.4    0.16       0  5001.2    0.07       0  5007.2    0.16       0
Bank Sta=5001.2,5007.2
Exp/Cntr=0.3,0.1

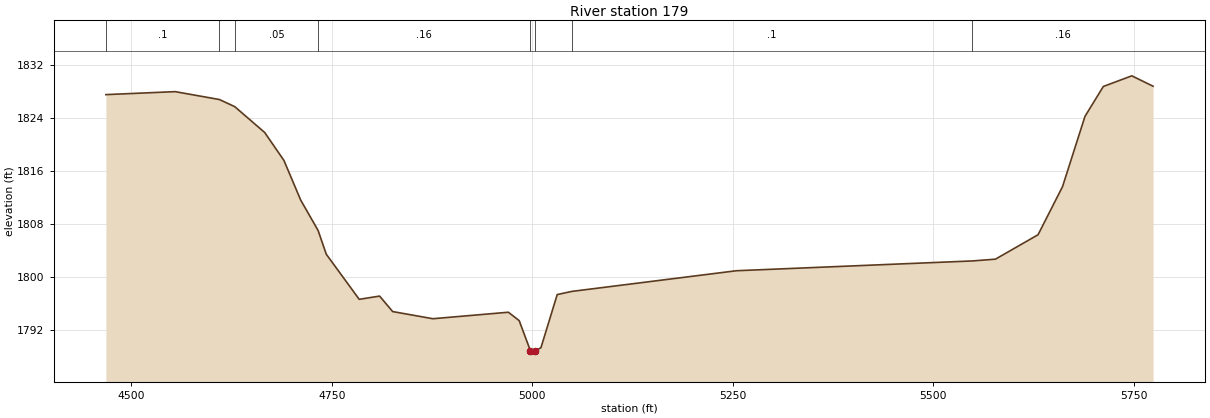
Type RM Length L Ch R = 1,179,0,0,0
BEGIN DESCRIPTION:
UNT 0038 IN HEWA 1.0
END DESCRIPTION:
XS GIS Cut Line= 4
      2726870.35     10073476.57      2726747.49     10073062.49
      2726560.92     10073030.64      2725887.43     10073153.51
#Sta/Elev= 30
  4468.3 1827.52  4554.7 1827.97  4609.8 1826.78  4628.9 1825.71  4666.3 1821.80
  4690.3 1817.58  4711.2 1811.59  4732.9 1807.00  4743.1 1803.41  4784.2 1796.59
  4809.6 1797.08  4825.9 1794.74  4876.0 1793.66  4970.2 1794.64  4983.7 1793.37
  4997.7 1788.81  5000.4 1788.31  5003.7 1788.81  5010.8 1789.28  5031.1 1797.31
  5049.5 1797.79  5254.6 1800.91  5548.8 1802.39  5577.6 1802.66  5630.7 1806.35
  5661.2 1813.61  5689.2 1824.23  5712.1 1828.75  5747.6 1830.36  5774.1 1828.79
#Mann=8,-1,0
  4468.3     0.1       0  4609.8    0.16       0  4628.9    0.05       0
  4732.9    0.16       0  4997.7    0.07       0  5003.7    0.16       0
  5049.5     0.1       0  5548.8    0.16       0
Bank Sta=4997.7,5003.7
Exp/Cntr=0.3,0.1

Chan Stop Cuts=-1