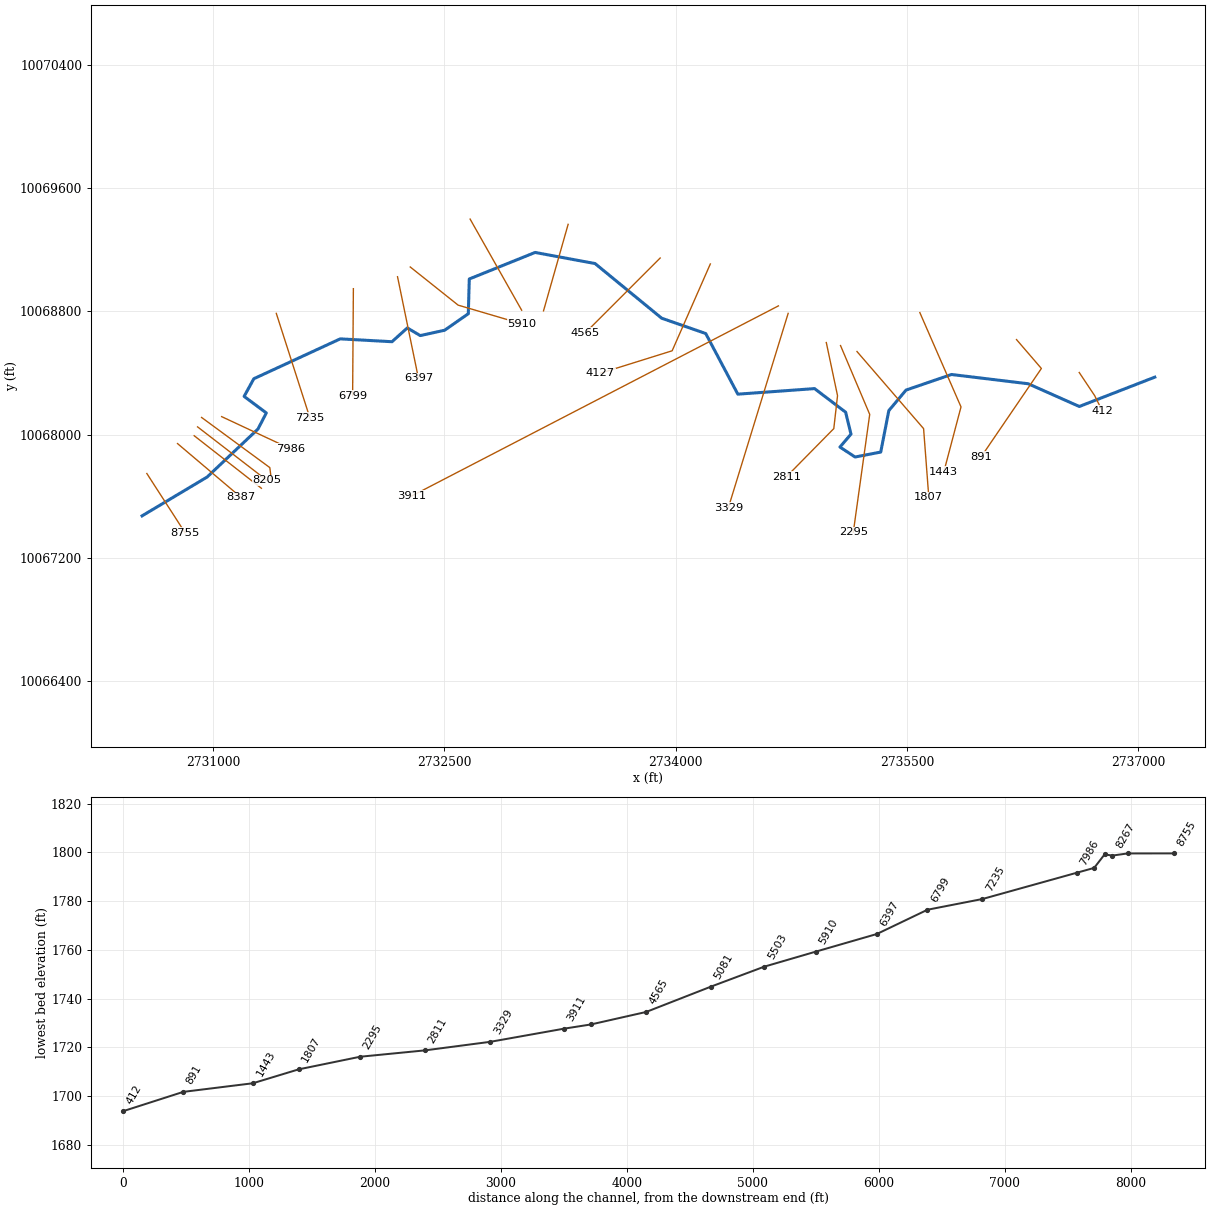
--- UNT 0039 IN HEWA.prj (project) ---

Proj Title=UNT 0039 IN HEWA Base Level Engineering
Current Plan=p01
Default Exp/Contr=0.3,0.1
English Units
Geom File=g01
Flow File=f01
Plan File=p01
BEGIN DESCRIPTION:
UNT 0039 IN HEWA
END DESCRIPTION:

--- UNT 0039 IN HEWA.p01 (plan) ---

Plan Title=Multiple Run
Short Identifier=Multiple
Geom File=g01
Flow File=f01
Subcritical Flow
K Sum by GR= 0
Std Step Tol= 0.01
Critical Tol= 0.01
Num of Std Step Trials= 20
Max Error Tol= 0.3
Flow Tol Ratio= 0.001
Split Flow NTrial= 30
Split Flow Tol= 0.02
Split Flow Ratio= 0.02
Log Output Level= 0
Friction Slope Method= 1
Unsteady Friction Slope Method= 2
Unsteady Bridges Friction Slope Method= 1
Parabolic Critical Depth
Global Vel Dist=  1 , 1 , 1
Global Log Level= 0
CheckData=True
Encroach Param= -1, 0, 0, 0
BEGIN DESCRIPTION:
Multiple Run
END DESCRIPTION:

--- UNT 0039 IN HEWA.f01 (steady flow) ---

Flow Title=Multiple
Number of Profiles=7
Profile Names=10-year,25-year,50-year,1pct_min,100-year,1pct_plu,500-year
River Rch & RM= UNT 0039 IN HEWA,Reach-1,8755
     795    1156    1471    1370    1853    2506    2954
River Rch & RM= UNT 0039 IN HEWA,Reach-1,2811
     910    1331    1700    1588    2148    2904    3445
Boundary for River Rch & Prof#=UNT 0039 IN HEWA,Reach-1,1
Up Type=0
Dn Type=3
Dn Slope=0.005
Boundary for River Rch & Prof#=UNT 0039 IN HEWA,Reach-1,2
Up Type=0
Dn Type=3
Dn Slope=0.005
Boundary for River Rch & Prof#=UNT 0039 IN HEWA,Reach-1,3
Up Type=0
Dn Type=3
Dn Slope=0.005
Boundary for River Rch & Prof#=UNT 0039 IN HEWA,Reach-1,4
Up Type=0
Dn Type=3
Dn Slope=0.005
Boundary for River Rch & Prof#=UNT 0039 IN HEWA,Reach-1,5
Up Type=0
Dn Type=3
Dn Slope=0.005
Boundary for River Rch & Prof#=UNT 0039 IN HEWA,Reach-1,6
Up Type=0
Dn Type=3
Dn Slope=0.005
Boundary for River Rch & Prof#=UNT 0039 IN HEWA,Reach-1,7
Up Type=0
Dn Type=3
Dn Slope=0.005

--- UNT 0039 IN HEWA.g01 (geometry) ---

Geom Title=Existing Conditions

River Reach=UNT 0039 IN HEWA,Reach-1
Reach XY= 30
      2730538.47     10067473.73      2730960.54     10067725.65
      2731290.58     10068037.26      2731344.57     10068141.47
      2731200.57     10068249.01      2731263.70     10068363.54
      2731824.25     10068622.12      2732159.95     10068603.60
      2732259.33     10068693.00      2732343.32     10068643.35
      2732501.39     10068678.06      2732655.07     10068785.27
      2732661.40     10069010.57      2733088.38     10069182.73
      2733477.17     10069110.71      2733909.47     10068756.15
      2734195.22     10068656.70      2734403.56     10068263.35
      2734901.26     10068299.39      2735102.84     10068146.30
      2735137.62     10068004.16      2735066.00     10067920.31
      2735164.09     10067855.65      2735330.59     10067887.69
      2735383.07     10068156.54      2735494.72     10068289.80
      2735789.68     10068390.97      2736287.28     10068330.86
      2736618.71     10068183.40      2737108.47     10068373.73

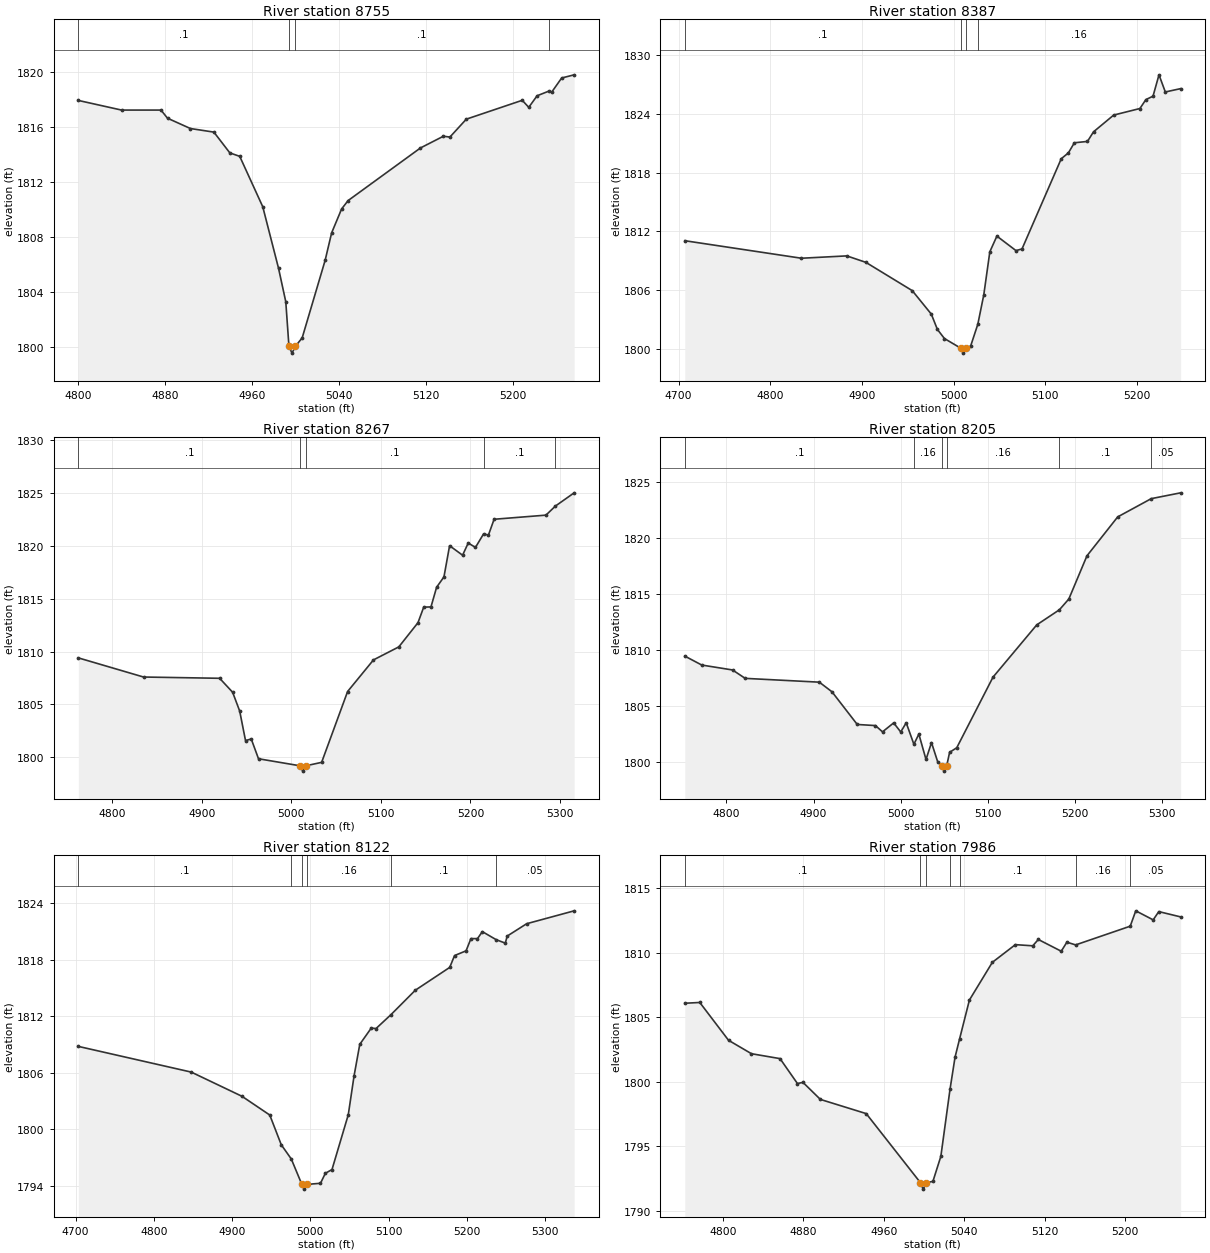
Type RM Length L Ch R = 1,8755,368,368,368
BEGIN DESCRIPTION:
UNT 0039 IN HEWA 19.0
END DESCRIPTION:
XS GIS Cut Line= 2
      2730569.53     10067748.60      2730817.12     10067365.07
#Sta/Elev= 30
  4799.9 1817.93  4839.7 1817.23  4876.0 1817.23  4882.0 1816.64  4903.1 1815.89
  4924.7 1815.63  4939.4 1814.12  4948.5 1813.87  4969.7 1810.21  4984.2 1805.75
  4990.9 1803.31  4993.8 1800.08  4996.6 1799.58  4999.8 1800.08  5006.0 1800.69
  5027.1 1806.31  5033.1 1808.31  5042.3 1810.05  5048.3 1810.66  5114.9 1814.48
  5136.0 1815.33  5142.0 1815.27  5157.1 1816.57  5208.6 1817.94  5214.6 1817.43
  5222.3 1818.27  5232.9 1818.60  5235.7 1818.53  5244.9 1819.56  5256.4 1819.79
#Mann=4,-1,0
  4799.9     0.1       0  4993.8    0.07       0  4999.8     0.1       0
  5232.9    0.16       0
Bank Sta=4993.8,4999.8
Exp/Cntr=0.3,0.1

Type RM Length L Ch R = 1,8387,120,120,120
BEGIN DESCRIPTION:
UNT 0039 IN HEWA 18.0
END DESCRIPTION:
XS GIS Cut Line= 2
      2730768.54     10067942.81      2731181.20     10067593.27
#Sta/Elev= 30
  4706.7 1811.05  4833.9 1809.26  4883.4 1809.50  4904.2 1808.84  4954.8 1805.95
  4975.6 1803.55  4982.2 1801.99  4989.9 1801.06  5007.8 1800.07  5010.5 1799.57
  5013.8 1800.07  5018.5 1800.30  5026.3 1802.52  5032.8 1805.52  5039.4 1809.92
  5047.1 1811.52  5067.9 1810.04  5074.5 1810.21  5117.3 1819.42  5125.1 1820.02
  5131.6 1821.05  5145.9 1821.19  5152.5 1822.17  5174.5 1823.88  5203.1 1824.55
  5209.6 1825.46  5217.4 1825.81  5223.9 1827.99  5230.8 1826.24  5247.5 1826.58
#Mann=4,-1,0
  4706.7     0.1       0  5007.8    0.07       0  5013.8     0.1       0
  5026.3    0.16       0
Bank Sta=5007.8,5013.8
Exp/Cntr=0.3,0.1

Type RM Length L Ch R = 1,8267,62,62,62
BEGIN DESCRIPTION:
Mapping XS f6722799
END DESCRIPTION:
XS GIS Cut Line= 2
      2730876.53     10067993.88      2731312.69     10067652.77
#Sta/Elev= 30
  4762.1 1809.40  4834.9 1807.59  4919.9 1807.47  4934.4 1806.15  4942.3 1804.37
  4948.8 1801.58  4955.2 1801.73  4963.3 1799.86  5010.0 1799.19  5012.8 1798.69
  5016.0 1799.19  5033.8 1799.52  5062.8 1806.22  5091.7 1809.21  5120.0 1810.44
  5141.4 1812.73  5147.8 1814.20  5155.9 1814.22  5162.2 1816.08  5170.4 1817.06
  5176.7 1820.01  5191.2 1819.11  5197.5 1820.26  5205.6 1819.85  5214.6 1821.12
  5220.1 1821.02  5226.4 1822.51  5284.3 1822.90  5294.9 1823.76  5315.8 1825.01
#Mann=5,-1,0
  4762.1     0.1       0  5010.0    0.07       0  5016.0     0.1       0
  5214.6     0.1       0  5294.9    0.05       0
Bank Sta=5010,5016
Exp/Cntr=0.3,0.1

Type RM Length L Ch R = 1,8205,83,83,83
BEGIN DESCRIPTION:
Mapping XS d41a846a
END DESCRIPTION:
XS GIS Cut Line= 2
      2730898.69     10068051.15      2731349.16     10067703.53
#Sta/Elev= 30
  4752.2 1809.45  4771.7 1808.65  4807.0 1808.21  4821.5 1807.46  4906.6 1807.12
  4921.1 1806.26  4950.1 1803.34  4971.0 1803.24  4979.1 1802.68  4991.9 1803.48
  5000.0 1802.67  5006.3 1803.49  5015.1 1801.57  5020.8 1802.48  5029.0 1800.21
  5035.3 1801.72  5042.4 1800.01  5046.8 1799.67  5049.5 1799.17  5052.8 1799.67
  5056.1 1800.85  5064.3 1801.26  5105.9 1807.57  5156.1 1812.24  5182.1 1813.59
  5192.9 1814.55  5213.7 1818.41  5249.0 1821.89  5287.5 1823.52  5321.2 1824.04
#Mann=6,-1,0
  4752.2     0.1       0  5015.1    0.16       0  5046.8    0.07       0
  5052.8    0.16       0  5182.1     0.1       0  5287.5    0.05       0
Bank Sta=5046.8,5052.8
Exp/Cntr=0.3,0.1

Type RM Length L Ch R = 1,8122,136,136,136
BEGIN DESCRIPTION:
Mapping XS d6586219
END DESCRIPTION:
XS GIS Cut Line= 3
      2730924.67     10068112.40      2731367.41     10067786.86
      2731377.82     10067703.54
#Sta/Elev= 30
  4703.6 1808.79  4847.9 1806.06  4912.7 1803.49  4948.2 1801.50  4962.9 1798.34
  4975.7 1796.83  4989.2 1794.13  4991.9 1793.63  4995.2 1794.13  5013.0 1794.25
  5019.2 1795.31  5027.7 1795.71  5048.5 1801.53  5055.9 1805.66  5063.2 1809.01
  5077.8 1810.73  5084.0 1810.69  5102.9 1812.15  5134.2 1814.76  5178.1 1817.18
  5184.3 1818.44  5199.0 1818.94  5205.2 1820.24  5213.6 1820.24  5219.8 1820.98
  5237.6 1820.12  5249.1 1819.76  5251.6 1820.51  5276.4 1821.82  5337.1 1823.19
#Mann=6,-1,0
  4703.6     0.1       0  4975.7    0.16       0  4989.2    0.07       0
  4995.2    0.16       0  5102.9     0.1       0  5237.6    0.05       0
Bank Sta=4989.2,4995.2
Exp/Cntr=0.3,0.1

Type RM Length L Ch R = 1,7986,751,751,751
BEGIN DESCRIPTION:
UNT 0039 IN HEWA 17.0
END DESCRIPTION:
XS GIS Cut Line= 2
      2731055.01     10068117.56      2731501.63     10067908.81
#Sta/Elev= 30
  4762.0 1806.07  4776.9 1806.13  4805.5 1803.20  4828.3 1802.16  4856.7 1801.78
  4874.0 1799.85  4879.5 1799.94  4896.8 1798.62  4942.4 1797.52  4996.3 1792.17
  4999.0 1791.67  5002.3 1792.17  5008.7 1792.27  5016.6 1794.21  5025.7 1799.40
  5030.7 1801.89  5035.2 1803.30  5045.0 1806.32  5067.8 1809.24  5090.7 1810.61
  5108.0 1810.52  5113.5 1811.01  5136.3 1810.10  5141.9 1810.80  5150.6 1810.59
  5204.9 1812.04  5210.4 1813.23  5227.7 1812.53  5233.3 1813.17  5255.0 1812.76
#Mann=7,-1,0
  4762.0     0.1       0  4996.3    0.07       0  5002.3     0.1       0
  5025.7    0.16       0  5035.2     0.1       0  5150.6    0.16       0
  5204.9    0.05       0
Bank Sta=4996.3,5002.3
Exp/Cntr=0.3,0.1

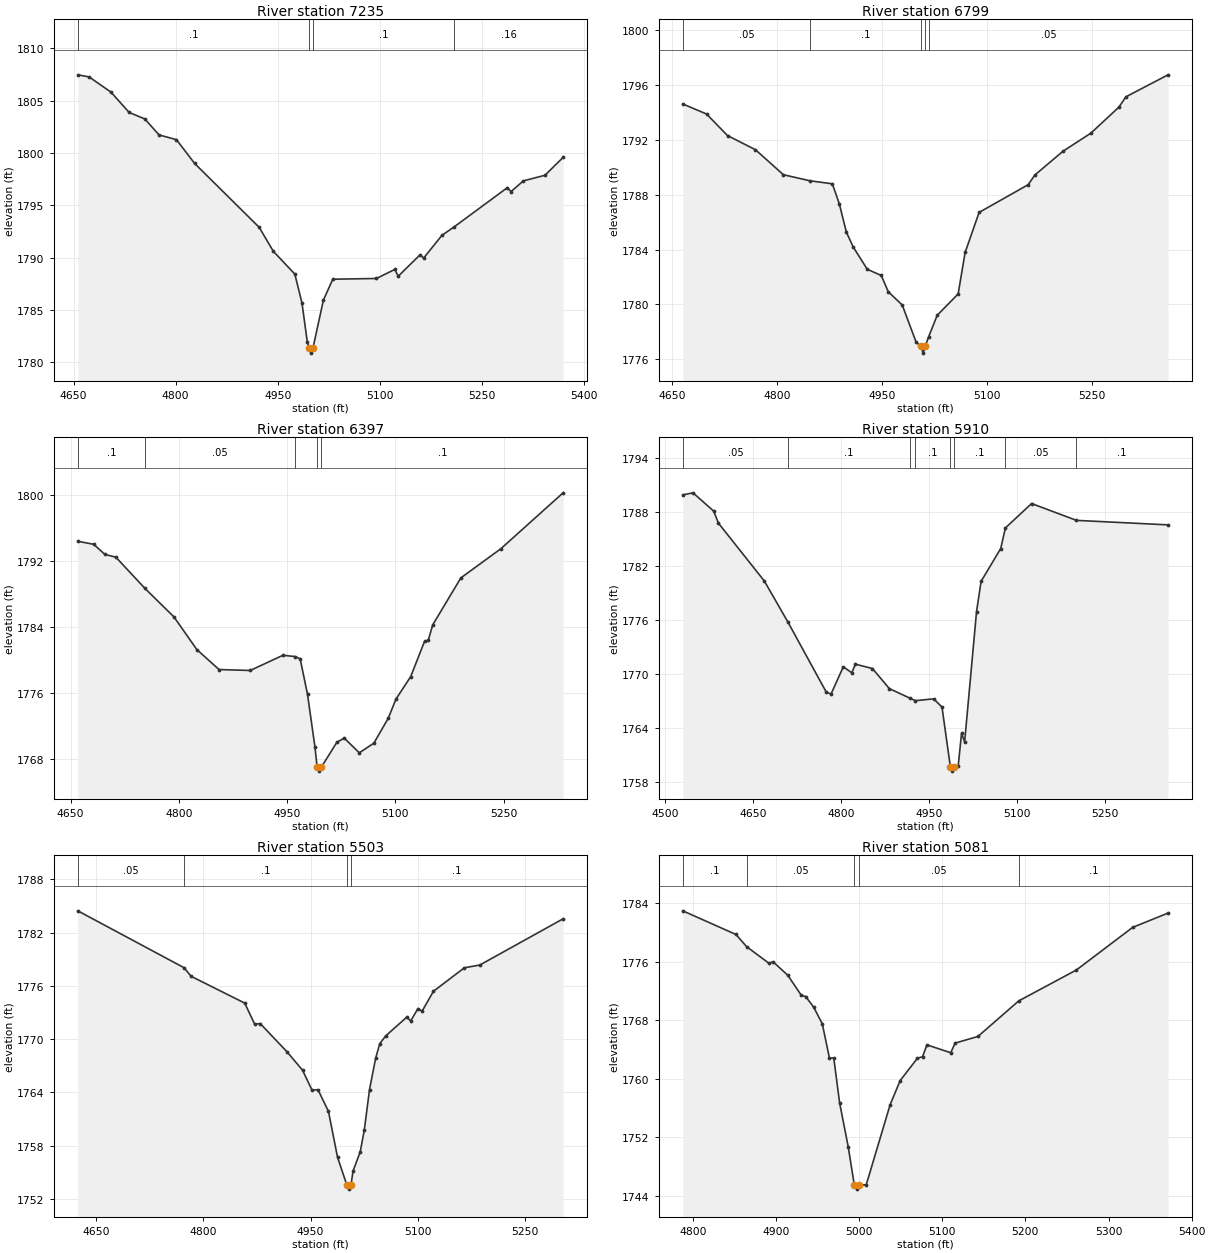
Type RM Length L Ch R = 1,7235,436,436,436
BEGIN DESCRIPTION:
UNT 0039 IN HEWA 16.0
END DESCRIPTION:
XS GIS Cut Line= 2
      2731409.36     10068787.55      2731627.70     10068108.27
#Sta/Elev= 30
  4656.2 1807.48  4672.8 1807.28  4704.9 1805.83  4731.7 1803.88  4754.7 1803.26
  4775.7 1801.73  4801.2 1801.28  4828.0 1799.00  4922.8 1792.90  4943.8 1790.59
  4975.3 1788.42  4985.8 1785.65  4993.7 1781.90  4996.0 1781.36  4998.7 1780.86
  5002.0 1781.36  5017.3 1785.93  5031.1 1787.93  5095.3 1788.00  5122.1 1788.86
  5127.4 1788.22  5159.5 1790.27  5164.7 1789.95  5191.6 1792.13  5209.0 1792.91
  5287.8 1796.69  5293.1 1796.31  5311.4 1797.34  5343.0 1797.87  5369.7 1799.58
#Mann=4,-1,0
  4656.2     0.1       0  4996.0    0.07       0  5002.0     0.1       0
  5209.0    0.16       0
Bank Sta=4996,5002
Exp/Cntr=0.3,0.1

Type RM Length L Ch R = 1,6799,402,402,402
BEGIN DESCRIPTION:
UNT 0039 IN HEWA 15.0
END DESCRIPTION:
XS GIS Cut Line= 2
      2731909.40     10068947.74      2731904.55     10068253.46
#Sta/Elev= 30
  4665.2 1794.59  4699.2 1793.86  4729.2 1792.29  4769.2 1791.26  4809.2 1789.44
  4847.2 1789.00  4879.2 1788.78  4889.2 1787.32  4899.2 1785.27  4909.2 1784.17
  4929.2 1782.56  4949.2 1782.11  4959.2 1780.93  4979.2 1779.96  4999.2 1777.24
  5006.2 1776.96  5009.0 1776.46  5012.2 1776.96  5016.9 1777.64  5029.2 1779.21
  5059.2 1780.77  5069.2 1783.79  5089.2 1786.70  5159.2 1788.71  5169.2 1789.43
  5209.2 1791.15  5249.2 1792.47  5289.2 1794.36  5299.2 1795.11  5359.5 1796.71
#Mann=5,-1,0
  4665.2    0.05       0  4847.2     0.1       0  5006.2    0.07       0
  5012.2     0.1       0  5016.9    0.05       0
Bank Sta=5006.2,5012.2
Exp/Cntr=0.3,0.1

Type RM Length L Ch R = 1,6397,487,487,487
BEGIN DESCRIPTION:
UNT 0039 IN HEWA 14.0
END DESCRIPTION:
XS GIS Cut Line= 2
      2732195.83     10069025.37      2732331.38     10068366.98
#Sta/Elev= 30
  4660.1 1794.36  4682.2 1793.99  4697.7 1792.76  4712.8 1792.43  4753.2 1788.64
  4793.3 1785.19  4825.1 1781.22  4855.8 1778.81  4899.0 1778.70  4944.2 1780.54
  4961.5 1780.38  4968.1 1780.11  4978.3 1775.80  4988.5 1769.48  4991.6 1767.00
  4994.3 1766.50  4997.6 1767.00  5019.1 1770.02  5029.3 1770.49  5050.0 1768.72
  5070.2 1769.89  5090.1 1772.90  5100.8 1775.23  5121.2 1777.95  5140.4 1782.23
  5145.5 1782.35  5151.8 1784.24  5190.7 1789.92  5246.2 1793.46  5332.3 1800.23
#Mann=5,-1,0
  4660.1     0.1       0  4753.2    0.05       0  4961.5     0.1       0
  4991.6    0.07       0  4997.6     0.1       0
Bank Sta=4991.6,4997.6
Exp/Cntr=0.3,0.1

Type RM Length L Ch R = 1,5910,407,407,407
BEGIN DESCRIPTION:
UNT 0039 IN HEWA 13.0
END DESCRIPTION:
XS GIS Cut Line= 3
      2732278.36     10069088.48      2732589.05     10068840.91
      2733001.71     10068719.54
#Sta/Elev= 30
  4530.7 1789.92  4548.2 1790.15  4583.4 1788.12  4591.4 1786.79  4669.9 1780.34
  4709.9 1775.80  4775.6 1767.98  4783.6 1767.81  4804.4 1770.82  4818.8 1770.16
  4825.2 1771.11  4854.1 1770.63  4882.9 1768.40  4918.5 1767.32  4927.5 1767.06
  4958.6 1767.26  4972.7 1766.34  4986.9 1759.73  4989.6 1759.23  4992.9 1759.73
  5000.3 1759.80  5006.0 1763.42  5011.3 1762.49  5031.6 1776.96  5039.4 1780.32
  5072.8 1783.96  5080.8 1786.25  5125.4 1788.96  5201.9 1787.09  5358.1 1786.59
#Mann=8,-1,0
  4530.7    0.05       0  4709.9     0.1       0  4918.5    0.05       0
  4927.5     0.1       0  4986.9    0.07       0  4992.9     0.1       0
  5080.8    0.05       0  5201.9     0.1       0
Bank Sta=4986.9,4992.9
Exp/Cntr=0.3,0.1

Type RM Length L Ch R = 1,5503,422,422,422
BEGIN DESCRIPTION:
UNT 0039 IN HEWA 12.0
END DESCRIPTION:
XS GIS Cut Line= 2
      2732666.72     10069399.19      2733001.19     10068807.82
#Sta/Elev= 30
  4624.1 1784.46  4773.0 1778.04  4782.7 1777.08  4857.8 1774.06  4871.6 1771.70
  4879.5 1771.75  4917.0 1768.57  4938.7 1766.50  4952.1 1764.24  4960.3 1764.30
  4975.0 1761.86  4987.7 1756.69  5000.6 1753.59  5003.3 1753.09  5006.6 1753.59
  5009.5 1755.14  5019.5 1757.30  5025.2 1759.75  5032.5 1764.31  5041.1 1767.85
  5046.9 1769.50  5055.4 1770.38  5084.4 1772.46  5090.2 1772.06  5100.3 1773.44
  5106.1 1773.15  5122.0 1775.39  5165.3 1778.04  5186.9 1778.35  5303.5 1783.56
#Mann=4,-1,0
  4624.1    0.05       0  4773.0     0.1       0  5000.6    0.07       0
  5006.6     0.1       0
Bank Sta=5000.6,5006.6
Exp/Cntr=0.3,0.1

Type RM Length L Ch R = 1,5081,516,516,516
BEGIN DESCRIPTION:
UNT 0039 IN HEWA 11.0
END DESCRIPTION:
XS GIS Cut Line= 2
      2733302.67     10069365.17      2733142.98     10068803.84
#Sta/Elev= 30
  4788.0 1782.98  4851.9 1779.75  4864.8 1778.08  4891.5 1775.82  4896.7 1776.00
  4914.3 1774.17  4930.6 1771.42  4935.8 1771.26  4945.4 1769.81  4955.8 1767.53
  4964.4 1762.83  4969.6 1762.85  4976.6 1756.74  4987.0 1750.69  4994.4 1745.42
  4997.2 1744.92  5000.4 1745.42  5008.7 1745.54  5037.4 1756.47  5049.4 1759.76
  5070.2 1762.82  5076.4 1763.03  5081.6 1764.65  5110.3 1763.57  5115.5 1764.89
  5143.0 1765.80  5192.0 1770.66  5261.4 1774.89  5329.1 1780.72  5371.6 1782.67
#Mann=5,-1,0
  4788.0     0.1       0  4864.8    0.05       0  4994.4   0.035       0
  5000.4    0.05       0  5192.0     0.1       0
Bank Sta=4994.4,5000.4
Exp/Cntr=0.3,0.1

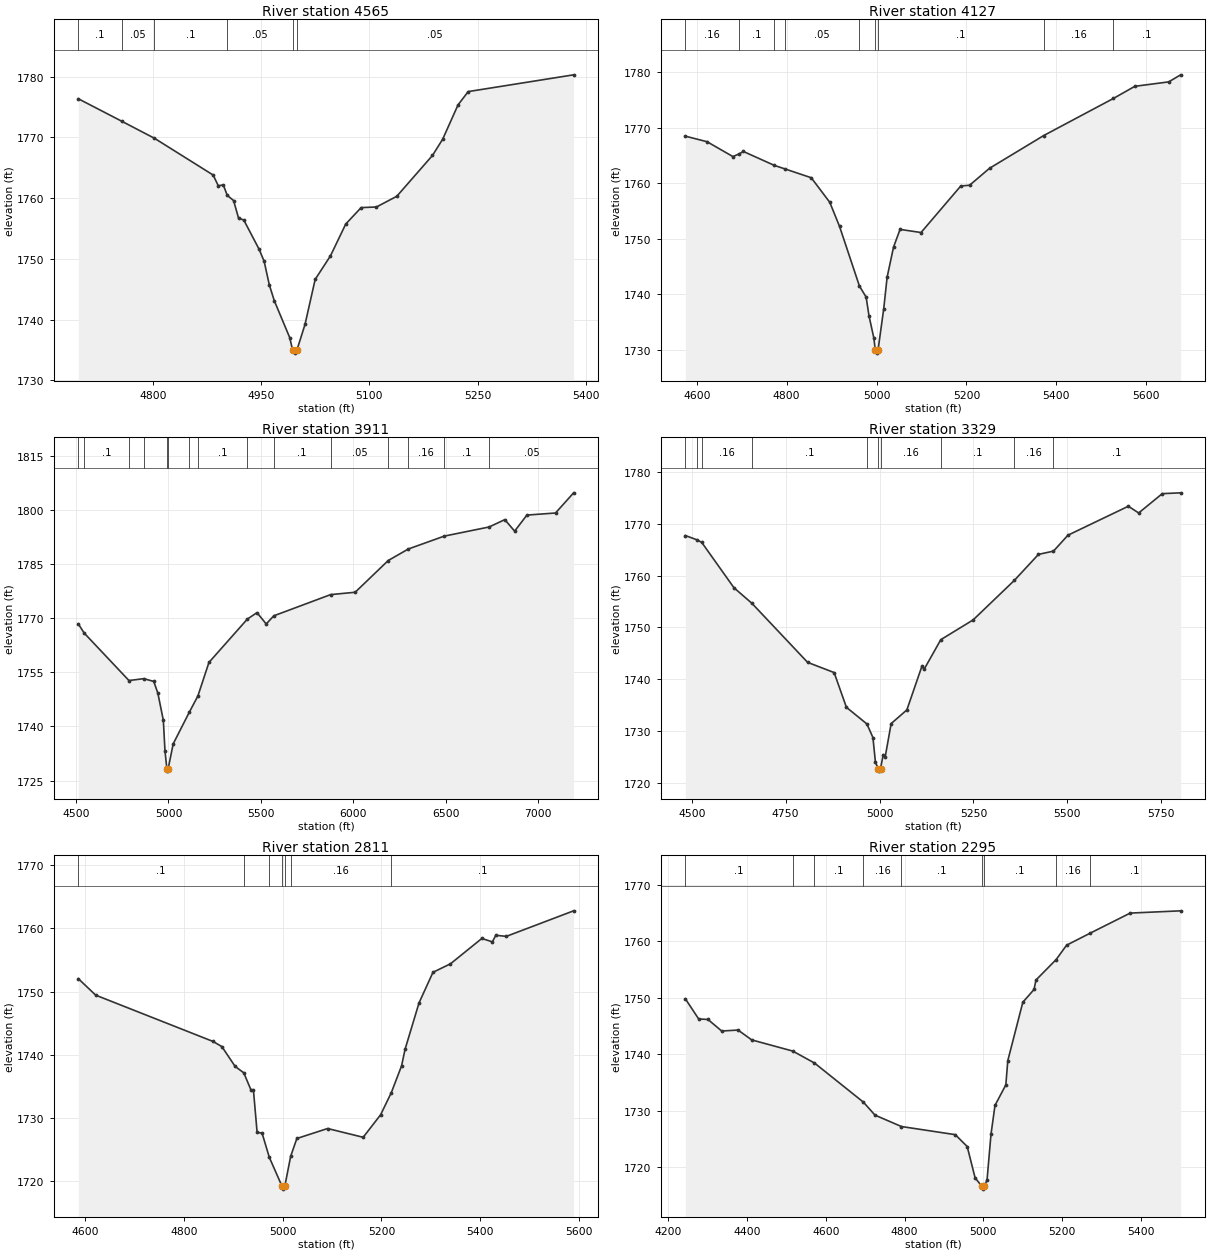
Type RM Length L Ch R = 1,4565,438,438,438
BEGIN DESCRIPTION:
UNT 0039 IN HEWA 10.0
END DESCRIPTION:
XS GIS Cut Line= 2
      2733899.78     10069146.72      2733414.35     10068661.29
#Sta/Elev= 30
  4696.7 1776.37  4757.4 1772.64  4802.3 1769.86  4883.6 1763.81  4890.7 1762.05
  4897.7 1762.18  4903.1 1760.47  4911.9 1759.61  4918.9 1756.68  4926.0 1756.42
  4947.2 1751.61  4954.3 1749.60  4961.4 1745.74  4968.4 1743.10  4989.7 1737.05
  4993.7 1734.99  4996.5 1734.49  4999.7 1734.99  5010.9 1739.21  5025.0 1746.63
  5046.2 1750.51  5067.4 1755.75  5088.7 1758.45  5109.9 1758.55  5138.1 1760.31
  5187.6 1767.04  5201.8 1769.73  5223.0 1775.36  5237.1 1777.55  5383.2 1780.31
#Mann=6,-1,0
  4696.7     0.1       0  4757.4    0.05       0  4802.3     0.1       0
  4903.1    0.05       0  4993.7   0.035       0  4999.7    0.05       0
Bank Sta=4993.7,4999.7
Exp/Cntr=0.3,0.1

Type RM Length L Ch R = 1,4127,216,216,216
BEGIN DESCRIPTION:
UNT 0039 IN HEWA 9.0
END DESCRIPTION:
XS GIS Cut Line= 3
      2734225.08     10069107.94      2733977.48     10068544.77
      2733512.45     10068399.45
#Sta/Elev= 30
  4574.5 1768.46  4622.8 1767.46  4680.4 1764.78  4693.7 1765.25  4703.7 1765.70
  4772.7 1763.19  4796.5 1762.55  4854.7 1760.97  4895.9 1756.55  4917.7 1752.20
  4961.9 1741.47  4976.9 1739.46  4983.3 1736.07  4994.2 1732.04  4997.3 1729.87
  5000.0 1729.37  5003.3 1729.87  5016.1 1737.40  5023.6 1743.05  5037.9 1748.48
  5052.4 1751.66  5099.1 1751.10  5187.5 1759.48  5207.2 1759.62  5251.5 1762.67
  5372.1 1768.57  5527.4 1775.26  5574.9 1777.44  5650.3 1778.24  5676.9 1779.51
#Mann=9,-1,0
  4574.5    0.16       0  4693.7     0.1       0  4772.7    0.16       0
  4796.5    0.05       0  4961.9     0.1       0  4997.3    0.07       0
  5003.3     0.1       0  5372.1    0.16       0  5527.4     0.1       0
Bank Sta=4997.3,5003.3
Exp/Cntr=0.3,0.1

Type RM Length L Ch R = 1,3911,582,582,582
BEGIN DESCRIPTION:
UNT 0039 IN HEWA 8.0
END DESCRIPTION:
XS GIS Cut Line= 2
      2734666.84     10068836.05      2732288.04     10067602.96
#Sta/Elev= 30
  4512.4 1768.43  4544.2 1765.89  4786.4 1752.73  4866.5 1753.25  4920.6 1752.48
  4942.7 1749.23  4972.4 1741.70  4981.3 1733.21  4991.9 1728.12  4994.7 1727.62
  4997.9 1728.12  5025.6 1735.17  5112.7 1743.94  5159.2 1748.44  5219.1 1757.75
  5426.8 1769.76  5479.0 1771.55  5528.9 1768.41  5570.0 1770.67  5877.5 1776.55
  6010.1 1777.20  6189.0 1786.00  6297.7 1789.19  6492.1 1792.76  6734.6 1795.29
  6819.6 1797.33  6872.7 1794.14  6939.1 1798.59  7094.0 1799.17  7191.8 1804.76
#Mann=15,-1,0
  4512.4    0.16       0  4544.2     0.1       0  4786.4    0.16       0
  4866.5     0.1       0  4991.9    0.07       0  4997.9     0.1       0
  5112.7    0.16       0  5159.2     0.1       0  5426.8    0.16       0
  5570.0     0.1       0  5877.5    0.05       0  6189.0     0.1       0
  6297.7    0.16       0  6492.1     0.1       0  6734.6    0.05       0
Bank Sta=4991.9,4997.9
Exp/Cntr=0.3,0.1

Type RM Length L Ch R = 1,3329,518,518,518
BEGIN DESCRIPTION:
UNT 0039 IN HEWA 7.0
END DESCRIPTION:
XS GIS Cut Line= 2
      2734729.96     10068787.55      2734342.09     10067526.97
#Sta/Elev= 30
  4482.9 1767.76  4514.0 1766.93  4526.5 1766.44  4612.4 1757.67  4660.0 1754.68
  4808.5 1743.26  4879.1 1741.29  4911.8 1734.58  4966.4 1731.36  4982.4 1728.74
  4989.1 1723.95  4996.6 1722.75  4999.3 1722.25  5002.6 1722.75  5009.9 1725.45
  5015.1 1725.01  5030.9 1731.43  5072.8 1734.08  5113.2 1742.59  5118.5 1741.90
  5163.1 1747.64  5249.2 1751.46  5358.9 1759.09  5423.2 1764.12  5463.2 1764.75
  5501.8 1767.83  5662.5 1773.42  5690.0 1772.12  5752.9 1775.85  5801.8 1776.01
#Mann=10,-1,0
  4482.9    0.16       0  4514.0     0.1       0  4526.5    0.16       0
  4660.0     0.1       0  4966.4    0.16       0  4996.6    0.07       0
  5002.6    0.16       0  5163.1     0.1       0  5358.9    0.16       0
  5463.2     0.1       0
Bank Sta=4996.6,5002.6
Exp/Cntr=0.3,0.1

Type RM Length L Ch R = 1,2811,516,516,516
BEGIN DESCRIPTION:
UNT 0039 IN HEWA 6.0
END DESCRIPTION:
XS GIS Cut Line= 4
      2734977.52     10068598.22      2735050.35     10068253.49
      2735026.08     10068039.89      2734720.23     10067729.18
#Sta/Elev= 30
  4585.9 1752.04  4621.1 1749.43  4858.9 1742.10  4876.7 1741.29  4903.6 1738.15
  4921.1 1737.14  4935.6 1734.44  4940.6 1734.44  4948.1 1727.72  4958.1 1727.61
  4972.8 1723.77  4998.3 1719.24  5001.1 1718.74  5004.3 1719.24  5016.1 1723.95
  5028.6 1726.75  5090.9 1728.33  5162.9 1726.94  5198.3 1730.51  5220.0 1734.02
  5240.7 1738.24  5247.8 1740.87  5276.1 1748.21  5304.3 1753.04  5339.8 1754.39
  5403.3 1758.40  5424.6 1757.86  5431.6 1758.90  5452.9 1758.73  5589.2 1762.77
#Mann=7,-1,0
  4585.9     0.1       0  4921.1    0.16       0  4972.8     0.1       0
  4998.3    0.07       0  5004.3     0.1       0  5016.1    0.16       0
  5220.0     0.1       0
Bank Sta=4998.3,5004.3
Exp/Cntr=0.3,0.1

Type RM Length L Ch R = 1,2295,488,488,488
BEGIN DESCRIPTION:
UNT 0039 IN HEWA 5.0
END DESCRIPTION:
XS GIS Cut Line= 3
      2735069.79     10068578.71      2735259.10     10068132.13
      2735152.55     10067366.87
#Sta/Elev= 30
  4243.1 1749.81  4276.9 1746.24  4300.6 1746.14  4335.4 1744.10  4377.0 1744.27
  4411.6 1742.53  4515.8 1740.55  4571.0 1738.44  4695.3 1731.51  4724.6 1729.22
  4791.7 1727.20  4928.5 1725.76  4958.8 1723.66  4978.9 1718.11  4996.1 1716.62
  4998.9 1716.12  5002.1 1716.62  5009.2 1717.75  5019.3 1725.87  5029.4 1730.94
  5056.9 1734.57  5061.9 1738.86  5100.1 1749.20  5128.5 1751.45  5133.5 1753.13
  5184.6 1756.74  5211.2 1759.29  5269.7 1761.37  5372.7 1764.97  5500.8 1765.37
#Mann=9,-1,0
  4243.1     0.1       0  4515.8    0.16       0  4571.0     0.1       0
  4695.3    0.16       0  4791.7     0.1       0  4996.1    0.07       0
  5002.1     0.1       0  5184.6    0.16       0  5269.7     0.1       0
Bank Sta=4996.1,5002.1
Exp/Cntr=0.3,0.1

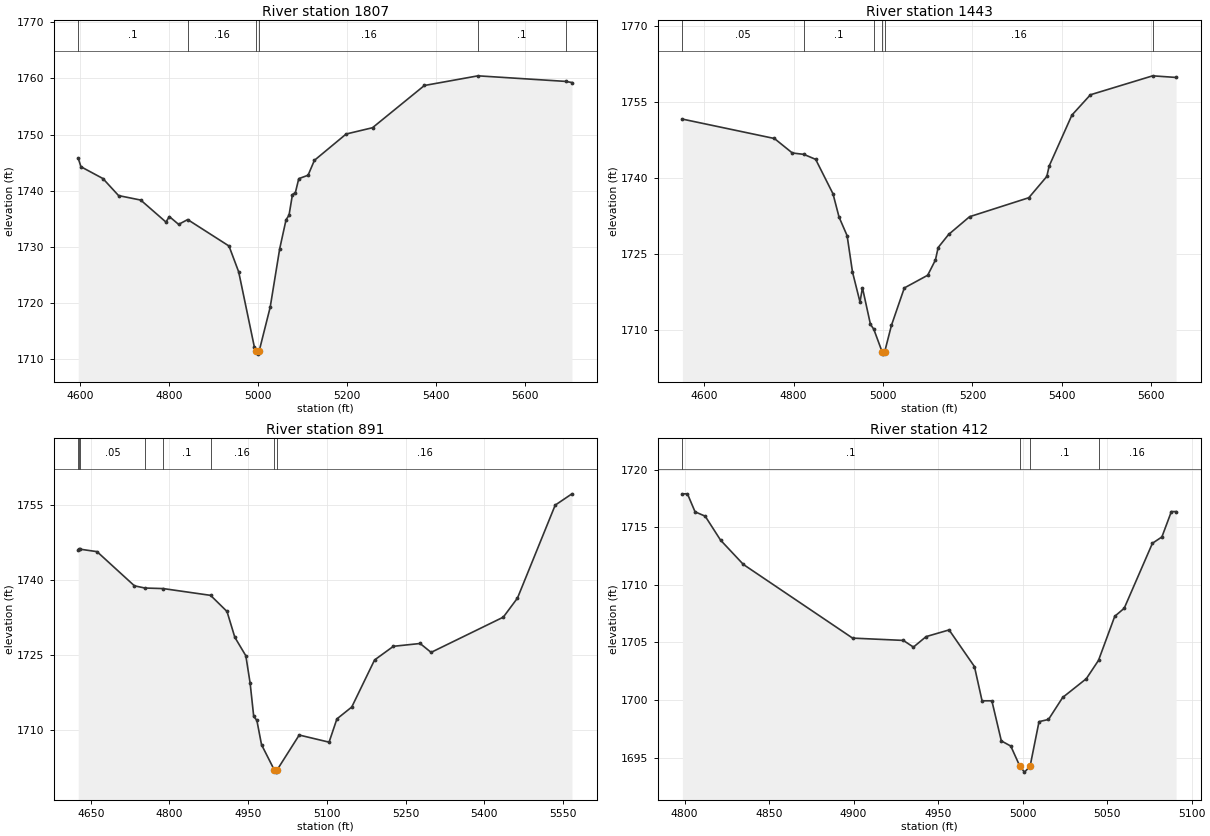
Type RM Length L Ch R = 1,1807,364,364,364
BEGIN DESCRIPTION:
UNT 0039 IN HEWA 4.0
END DESCRIPTION:
XS GIS Cut Line= 3
      2735176.55     10068539.95      2735608.64     10068039.89
      2735642.62     10067593.25
#Sta/Elev= 30
  4596.6 1745.78  4602.7 1744.27  4652.1 1742.17  4687.2 1739.14  4737.0 1738.34
  4793.6 1734.43  4801.2 1735.41  4822.1 1734.02  4842.4 1734.87  4935.2 1730.17
  4957.0 1725.56  4992.1 1712.23  4996.8 1711.44  4999.5 1710.94  5002.8 1711.44
  5027.7 1719.28  5049.1 1729.70  5063.4 1734.86  5070.0 1735.64  5077.7 1739.32
  5084.3 1739.68  5091.9 1742.15  5112.8 1742.76  5127.0 1745.41  5198.3 1750.09
  5257.5 1751.21  5374.0 1758.72  5494.4 1760.44  5691.0 1759.45  5705.4 1759.25
#Mann=6,-1,0
  4596.6     0.1       0  4842.4    0.16       0  4996.8    0.07       0
  5002.8    0.16       0  5494.4     0.1       0  5691.0    0.05       0
Bank Sta=4996.8,5002.8
Exp/Cntr=0.3,0.1

Type RM Length L Ch R = 1,1443,552,552,552
BEGIN DESCRIPTION:
UNT 0039 IN HEWA 3.0
END DESCRIPTION:
XS GIS Cut Line= 3
      2735584.36     10068792.37      2735851.37     10068180.68
      2735739.76     10067758.51
#Sta/Elev= 30
  4551.3 1751.62  4757.1 1747.79  4797.2 1744.93  4822.9 1744.66  4849.4 1743.67
  4888.1 1736.88  4901.7 1732.27  4919.7 1728.61  4931.7 1721.45  4948.5 1715.52
  4954.0 1718.33  4971.9 1711.10  4979.3 1710.16  4997.8 1705.73  5000.6 1705.23
  5003.8 1705.73  5018.8 1710.90  5047.6 1718.29  5099.9 1720.80  5117.2 1723.81
  5123.3 1726.27  5146.7 1728.85  5193.5 1732.35  5326.0 1736.10  5366.3 1740.30
  5371.5 1742.35  5422.4 1752.41  5463.8 1756.42  5603.0 1760.16  5655.4 1759.84
#Mann=6,-1,0
  4551.3    0.05       0  4822.9     0.1       0  4979.3    0.16       0
  4997.8    0.07       0  5003.8    0.16       0  5603.0     0.1       0
Bank Sta=4997.8,5003.8
Exp/Cntr=0.3,0.1

Type RM Length L Ch R = 1,891,479,479,479
BEGIN DESCRIPTION:
UNT 0039 IN HEWA 2.0
END DESCRIPTION:
XS GIS Cut Line= 3
      2736211.44     10068617.45      2736372.87     10068429.98
      2735982.25     10067857.07
#Sta/Elev= 30
  4626.1 1746.03  4628.1 1746.10  4629.0 1746.13  4661.9 1745.63  4733.2 1738.82
  4753.3 1738.38  4788.2 1738.27  4878.3 1736.92  4909.6 1733.71  4924.5 1728.57
  4945.5 1724.88  4953.7 1719.40  4960.5 1712.80  4966.5 1712.01  4975.4 1707.16
  4999.4 1702.20  5002.2 1701.70  5005.4 1702.20  5047.2 1709.09  5104.1 1707.67
  5119.0 1712.30  5147.3 1714.67  5190.8 1724.05  5226.7 1726.77  5277.6 1727.33
  5298.5 1725.56  5436.1 1732.58  5463.1 1736.38  5535.0 1754.90  5566.9 1757.15
#Mann=8,-1,0
  4626.1    0.08       0  4628.1    0.16       0  4629.0    0.05       0
  4753.3    0.16       0  4788.2     0.1       0  4878.3    0.16       0
  4999.4    0.07       0  5005.4    0.16       0
Bank Sta=4999.4,5005.4
Exp/Cntr=0.3,0.1

Type RM Length L Ch R = 1,412,0,0,0
BEGIN DESCRIPTION:
UNT 0039 IN HEWA 1.0
END DESCRIPTION:
XS GIS Cut Line= 3
      2736618.45     10068403.75      2736718.47     10068253.73
      2736768.47     10068153.73
#Sta/Elev= 30
  4798.7 1717.90  4801.7 1717.90  4806.2 1716.34  4812.2 1715.96  4821.3 1713.88
  4834.8 1711.77  4899.4 1705.38  4929.4 1705.18  4935.4 1704.60  4942.9 1705.51
  4956.5 1706.09  4971.5 1702.91  4976.0 1699.94  4981.8 1699.94  4987.4 1696.46
  4993.0 1696.01  4998.4 1694.25  5001.1 1693.75  5004.4 1694.25  5009.7 1698.13
  5015.3 1698.32  5023.7 1700.23  5037.7 1701.86  5044.9 1703.45  5054.5 1707.27
  5060.1 1707.97  5076.8 1713.61  5082.4 1714.16  5088.0 1716.36  5090.8 1716.36
#Mann=4,-1,0
  4798.7     0.1       0  4998.4    0.07       0  5004.4     0.1       0
  5044.9    0.16       0
Bank Sta=4998.4,5004.4
Exp/Cntr=0.3,0.1

Chan Stop Cuts=-1