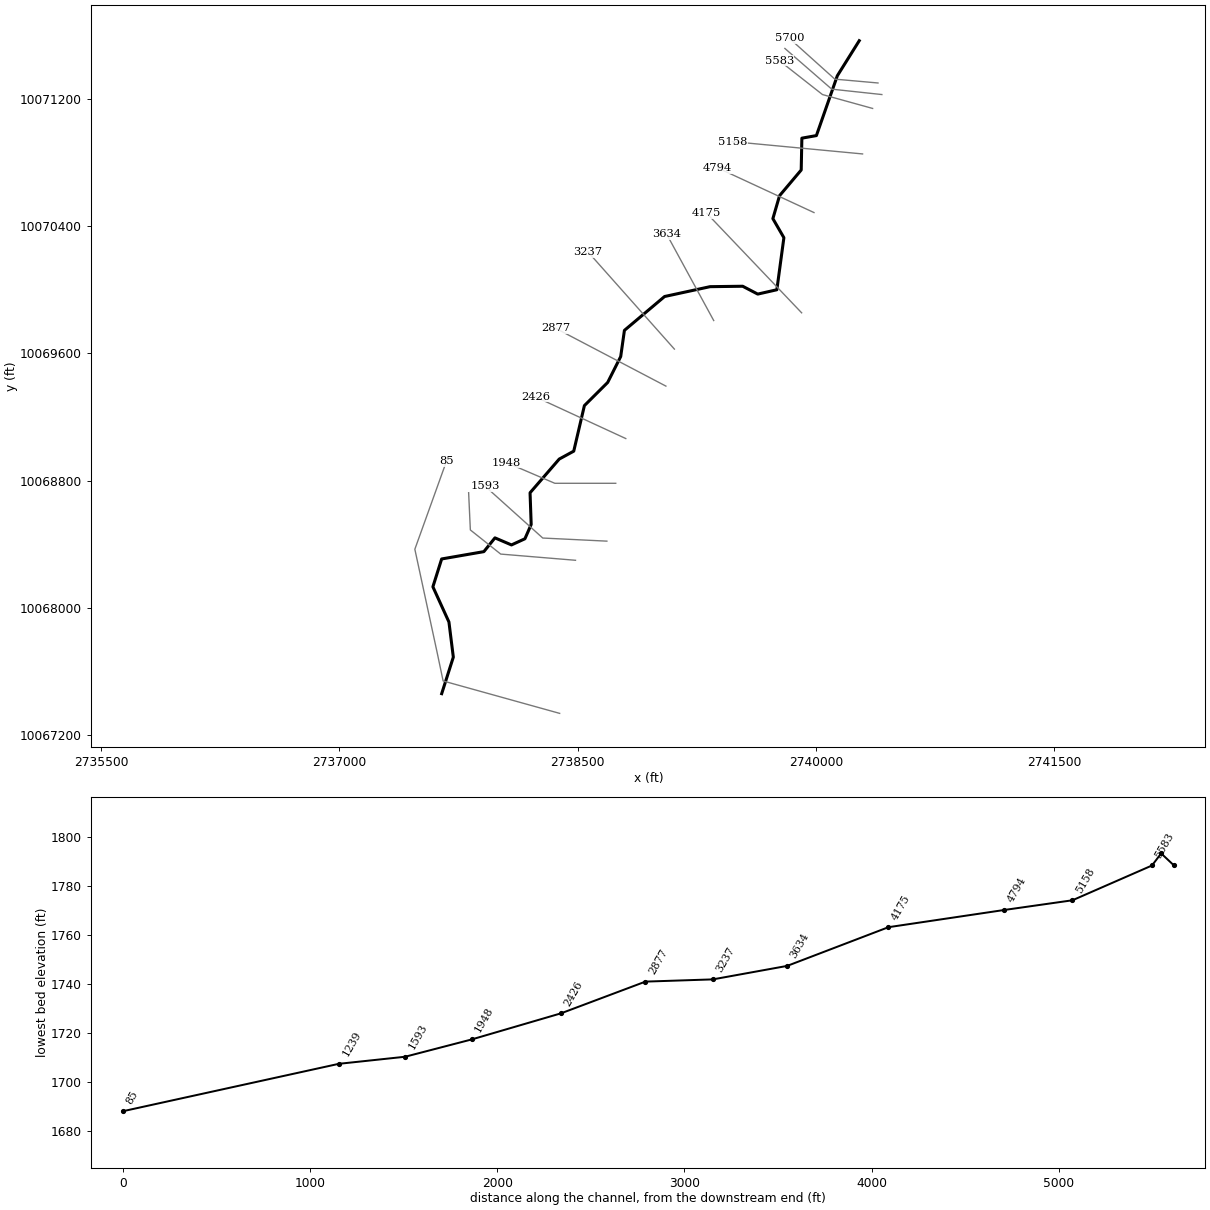
--- UNT 0040 IN HEWA.prj (project) ---

Proj Title=UNT 0040 IN HEWA Base Level Engineering
Current Plan=p01
Default Exp/Contr=0.3,0.1
English Units
Geom File=g01
Flow File=f01
Plan File=p01
Y Axis Title=Elevation
X Axis Title(PF)=Main Channel Distance
X Axis Title(XS)=Station
BEGIN DESCRIPTION:
UNT 0040 IN HEWA
END DESCRIPTION:
DSS Export Rating Curves= 0
DSS Export Rating Curve Sorted= 0
DSS Export Volume Flow Curves= 0
DXF OffsetX= 0
DXF OffsetY= 0
DXF ScaleX= 1
DXF ScaleY= 10

--- UNT 0040 IN HEWA.p01 (plan) ---

Plan Title=Multiple Run
Short Identifier=Multiple
Geom File=g01
Flow File=f01
Subcritical Flow
K Sum by GR= 0
Std Step Tol= 0.01
Critical Tol= 0.01
Num of Std Step Trials= 20
Max Error Tol= 0.3
Flow Tol Ratio= 0.001
Split Flow NTrial= 30
Split Flow Tol= 0.02
Split Flow Ratio= 0.02
Log Output Level= 0
Friction Slope Method= 1
Unsteady Friction Slope Method= 2
Unsteady Bridges Friction Slope Method= 1
Parabolic Critical Depth
Global Vel Dist=  1 , 1 , 1
Global Log Level= 0
CheckData=True
Encroach Param= -1, 0, 0, 0
BEGIN DESCRIPTION:
Multiple Run
END DESCRIPTION:

--- UNT 0040 IN HEWA.f01 (steady flow) ---

Flow Title=Multiple
Number of Profiles=7
Profile Names=10-year,25-year,50-year,1pct_min,100-year,1pct_plu,500-year
River Rch & RM= UNT 0040 IN HEWA,Reach-1,5700
     551     787     988     910    1231    1664    1917
Boundary for River Rch & Prof#=UNT 0040 IN HEWA,Reach-1,1
Up Type=0
Dn Type=3
Dn Slope=0.005
Boundary for River Rch & Prof#=UNT 0040 IN HEWA,Reach-1,2
Up Type=0
Dn Type=3
Dn Slope=0.005
Boundary for River Rch & Prof#=UNT 0040 IN HEWA,Reach-1,3
Up Type=0
Dn Type=3
Dn Slope=0.005
Boundary for River Rch & Prof#=UNT 0040 IN HEWA,Reach-1,4
Up Type=0
Dn Type=3
Dn Slope=0.005
Boundary for River Rch & Prof#=UNT 0040 IN HEWA,Reach-1,5
Up Type=0
Dn Type=3
Dn Slope=0.005
Boundary for River Rch & Prof#=UNT 0040 IN HEWA,Reach-1,6
Up Type=0
Dn Type=3
Dn Slope=0.005
Boundary for River Rch & Prof#=UNT 0040 IN HEWA,Reach-1,7
Up Type=0
Dn Type=3
Dn Slope=0.005

--- UNT 0040 IN HEWA.g01 (geometry) ---

Geom Title=Existing Conditions

River Reach=UNT 0040 IN HEWA,Reach-1
Reach XY= 30
      2740272.41     10071568.24      2740134.36     10071347.50
      2740002.68     10070971.09      2739911.27     10070954.93
      2739907.10     10070754.56      2739770.77     10070592.81
      2739728.79     10070448.39      2739798.08     10070328.49
      2739753.81     10070000.80      2739633.44     10069973.46
      2739538.82     10070022.87      2739333.35     10070020.21
      2739047.16     10069958.22      2738794.37     10069745.16
      2738771.02     10069580.36      2738688.84     10069417.15
      2738542.46     10069271.51      2738475.44     10068984.99
      2738383.94     10068935.02      2738200.48     10068722.98
      2738207.56     10068523.45      2738168.14     10068433.48
      2738083.52     10068394.70      2737979.48     10068439.13
      2737909.80     10068352.50      2737644.10     10068306.42
      2737588.91     10068131.11      2737689.84     10067909.74
      2737717.50     10067688.54      2737644.29     10067458.60

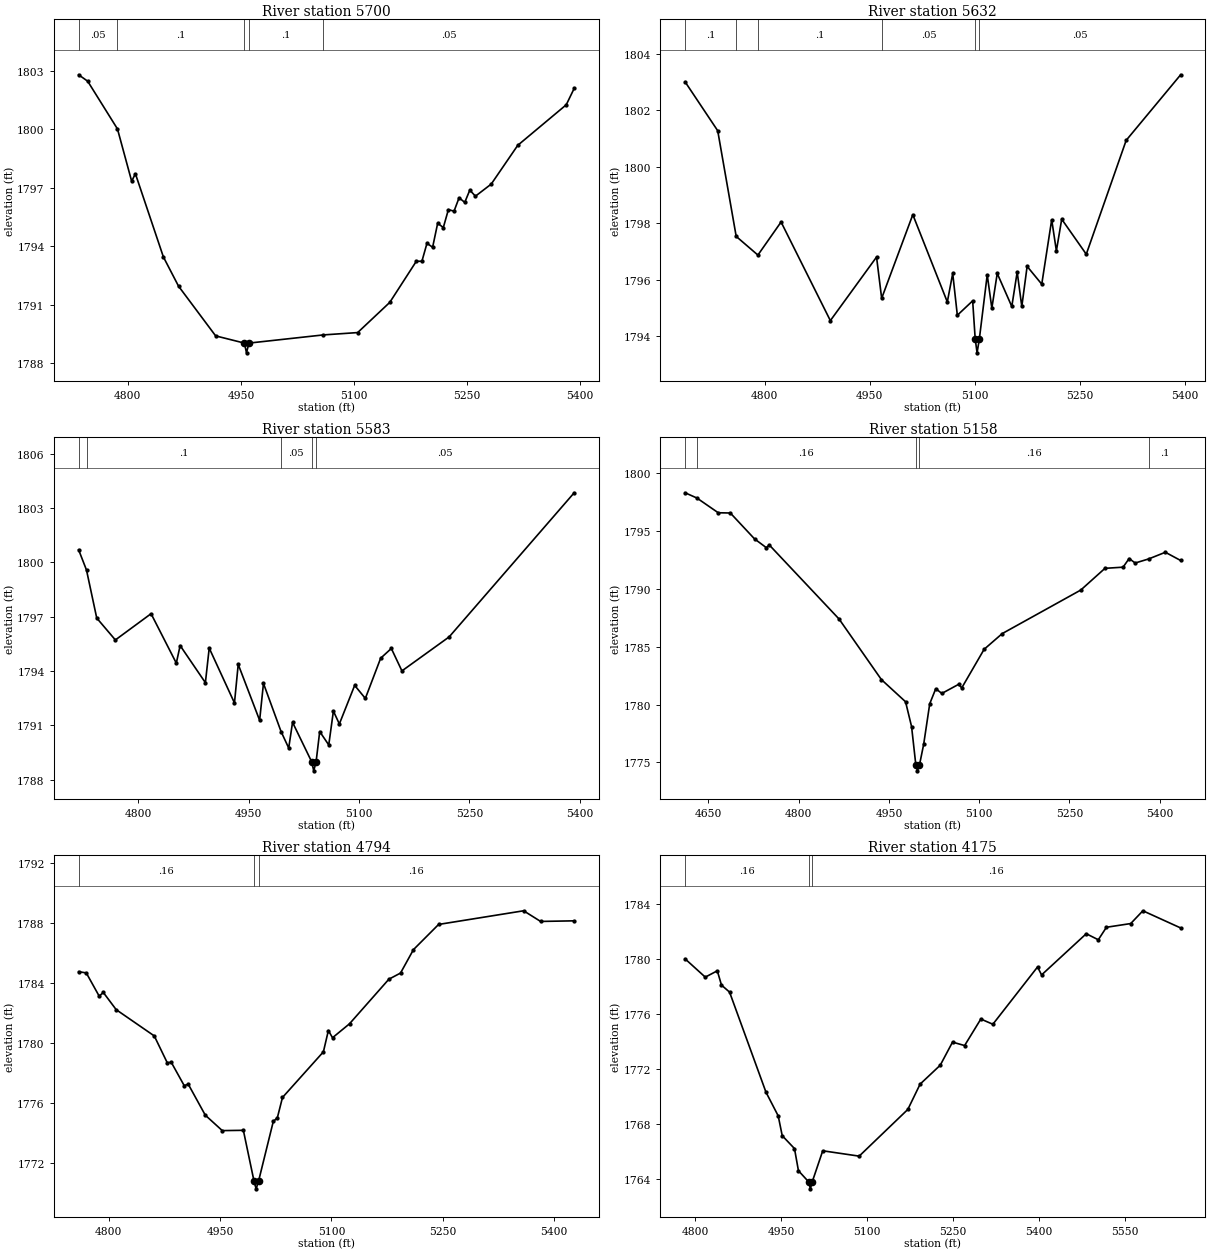
Type RM Length L Ch R = 1,5700,68,68,68
BEGIN DESCRIPTION:
UNT 0040 IN HEWA 12.0
END DESCRIPTION:
XS GIS Cut Line= 3
      2740390.42     10071302.21      2740118.59     10071326.48
      2739832.79     10071583.22
#Sta/Elev= 30
  4734.8 1802.80  4746.8 1802.47  4786.3 1800.02  4805.1 1797.34  4810.1 1797.72
  4847.2 1793.45  4867.3 1791.95  4916.5 1789.40  4954.6 1789.03  4957.4 1788.53
  4960.6 1789.03  5059.4 1789.45  5104.8 1789.57  5147.4 1791.12  5182.6 1793.23
  5190.0 1793.23  5196.7 1794.15  5204.2 1793.95  5210.9 1795.18  5218.4 1794.96
  5225.1 1795.88  5232.6 1795.80  5239.3 1796.49  5246.8 1796.25  5253.5 1796.88
  5261.0 1796.57  5281.9 1797.19  5317.1 1799.18  5381.4 1801.26  5391.9 1802.10
#Mann=5,-1,0
  4734.8    0.05       0  4786.3     0.1       0  4954.6    0.07       0
  4960.6     0.1       0  5059.4    0.05       0
Bank Sta=4954.6,4960.6
Exp/Cntr=0.3,0.1

Type RM Length L Ch R = 1,5632,49,49,49
BEGIN DESCRIPTION:
Mapping XS 8a543be7
END DESCRIPTION:
XS GIS Cut Line= 3
      2740414.75     10071229.39      2740099.18     10071263.37
      2739804.40     10071519.49
#Sta/Elev= 30
  4686.3 1803.01  4732.9 1801.28  4759.3 1797.54  4790.3 1796.88  4823.4 1798.05
  4893.8 1794.56  4959.8 1796.81  4967.1 1795.35  5011.6 1798.31  5060.9 1795.22
  5068.6 1796.23  5075.2 1794.75  5097.1 1795.26  5100.7 1793.92  5103.4 1793.42
  5106.7 1793.92  5117.9 1796.18  5124.5 1795.00  5132.2 1796.23  5153.0 1795.06
  5160.7 1796.28  5167.3 1795.06  5174.9 1796.48  5195.8 1795.85  5210.0 1798.13
  5216.7 1797.03  5224.3 1798.15  5259.4 1796.91  5316.4 1800.94  5394.2 1803.26
#Mann=6,-1,0
  4686.3     0.1       0  4759.3    0.05       0  4790.3     0.1       0
  4967.1    0.05       0  5100.7   0.035       0  5106.7    0.05       0
Bank Sta=5100.7,5106.7
Exp/Cntr=0.3,0.1

Type RM Length L Ch R = 1,5583,425,425,425
BEGIN DESCRIPTION:
UNT 0040 IN HEWA 11.0
END DESCRIPTION:
XS GIS Cut Line= 3
      2740356.52     10071141.99      2740040.92     10071229.39
      2739769.07     10071442.98
#Sta/Elev= 30
  4719.0 1800.69  4729.7 1799.57  4743.6 1796.92  4768.9 1795.71  4817.4 1797.16
  4851.7 1794.43  4856.9 1795.40  4891.2 1793.35  4896.4 1795.26  4930.7 1792.23
  4935.8 1794.36  4964.9 1791.27  4970.1 1793.31  4994.0 1790.65  5004.4 1789.74
  5009.6 1791.16  5035.6 1788.98  5038.4 1788.48  5041.6 1788.98  5046.5 1790.65
  5058.8 1789.91  5065.1 1791.78  5073.2 1791.07  5094.0 1793.20  5108.5 1792.48
  5129.3 1794.70  5143.8 1795.24  5158.2 1794.00  5222.4 1795.88  5392.2 1803.84
#Mann=5,-1,0
  4719.0    0.05       0  4729.7     0.1       0  4994.0    0.05       0
  5035.6   0.035       0  5041.6    0.05       0
Bank Sta=5035.6,5041.6
Exp/Cntr=0.3,0.1

Type RM Length L Ch R = 1,5158,364,364,364
BEGIN DESCRIPTION:
UNT 0040 IN HEWA 10.0
END DESCRIPTION:
XS GIS Cut Line= 2
      2740293.33     10070855.58      2739473.20     10070933.23
#Sta/Elev= 30
  4611.2 1798.33  4630.7 1797.88  4666.3 1796.60  4686.4 1796.58  4726.6 1794.34
  4746.2 1793.58  4751.2 1793.81  4867.2 1787.40  4937.5 1782.16  4977.7 1780.24
  4987.7 1778.09  4994.8 1774.76  4997.5 1774.26  5000.8 1774.76  5007.8 1776.55
  5017.9 1780.07  5027.9 1781.37  5038.0 1780.96  5066.0 1781.75  5071.1 1781.44
  5108.3 1784.78  5138.4 1786.14  5269.0 1789.91  5309.2 1791.79  5339.3 1791.89
  5349.4 1792.64  5359.4 1792.25  5381.7 1792.60  5409.6 1793.18  5435.0 1792.47
#Mann=5,-1,0
  4611.2     0.1       0  4630.7    0.16       0  4994.8    0.07       0
  5000.8    0.16       0  5381.7     0.1       0
Bank Sta=4994.8,5000.8
Exp/Cntr=0.3,0.1

Type RM Length L Ch R = 1,4794,619,619,619
BEGIN DESCRIPTION:
UNT 0040 IN HEWA 9.0
END DESCRIPTION:
XS GIS Cut Line= 2
      2739987.56     10070486.61      2739382.07     10070767.56
#Sta/Elev= 30
  4759.4 1784.77  4769.7 1784.69  4787.1 1783.14  4792.6 1783.39  4810.0 1782.24
  4861.3 1780.49  4878.7 1778.71  4884.2 1778.73  4901.6 1777.18  4907.1 1777.27
  4930.0 1775.21  4952.9 1774.18  4981.3 1774.20  4995.7 1770.80  4998.5 1770.30
  5001.7 1770.80  5021.6 1774.79  5027.1 1775.04  5034.0 1776.39  5089.1 1779.43
  5095.8 1780.85  5101.4 1780.37  5124.3 1781.30  5177.3 1784.27  5193.0 1784.68
  5210.4 1786.24  5244.3 1787.92  5358.8 1788.83  5381.7 1788.12  5426.9 1788.16
#Mann=3,-1,0
  4759.4    0.16       0  4995.7    0.07       0  5001.7    0.16       0
Bank Sta=4995.7,5001.7
Exp/Cntr=0.3,0.1

Type RM Length L Ch R = 1,4175,541,541,541
BEGIN DESCRIPTION:
UNT 0040 IN HEWA 8.0
END DESCRIPTION:
XS GIS Cut Line= 2
      2739909.86     10069855.51      2739313.08     10070481.40
#Sta/Elev= 30
  4782.6 1780.00  4817.8 1778.67  4838.8 1779.13  4846.1 1778.09  4860.2 1777.58
  4923.7 1770.30  4945.1 1768.57  4952.1 1767.13  4973.5 1766.19  4980.4 1764.58
  4998.4 1763.76  5001.2 1763.26  5004.4 1763.76  5022.8 1766.03  5086.4 1765.64
  5171.3 1769.04  5192.7 1770.88  5227.9 1772.26  5249.3 1773.94  5270.4 1773.69
  5298.7 1775.62  5319.7 1775.24  5397.7 1779.41  5404.7 1778.83  5482.7 1781.83
  5503.7 1781.39  5517.9 1782.30  5560.3 1782.57  5581.5 1783.50  5647.4 1782.25
#Mann=3,-1,0
  4782.6    0.16       0  4998.4    0.07       0  5004.4    0.16       0
Bank Sta=4998.4,5004.4
Exp/Cntr=0.3,0.1

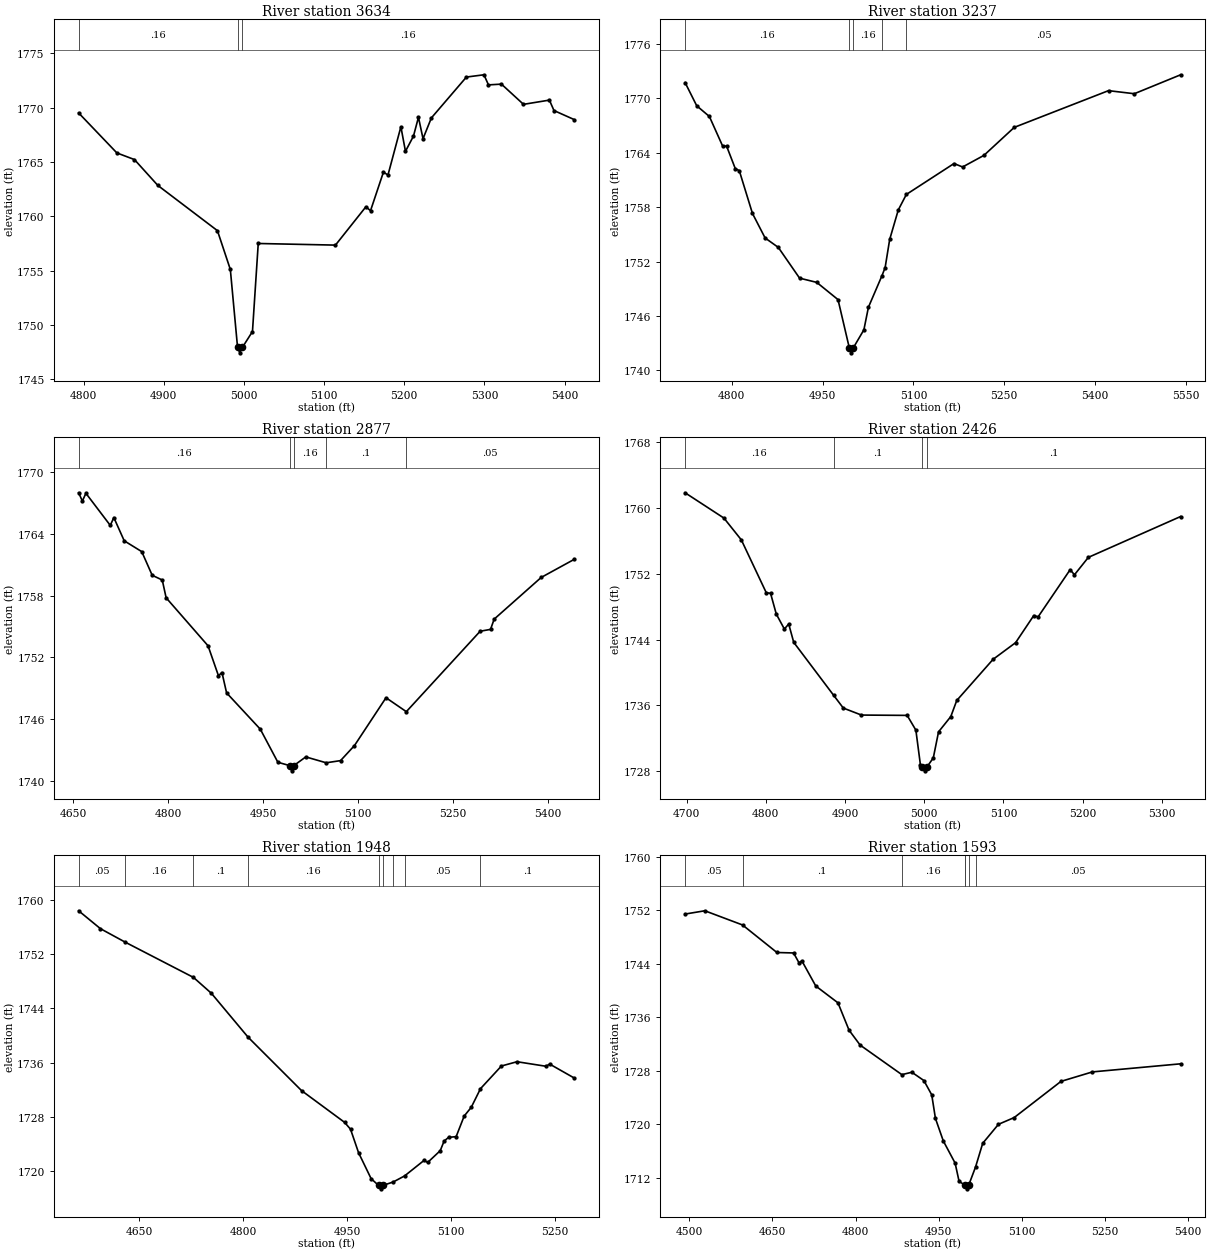
Type RM Length L Ch R = 1,3634,397,397,397
BEGIN DESCRIPTION:
UNT 0040 IN HEWA 7.0
END DESCRIPTION:
XS GIS Cut Line= 2
      2739356.40     10069807.00      2739060.81     10070349.73
#Sta/Elev= 30
  4793.9 1769.51  4841.6 1765.83  4863.5 1765.22  4892.7 1762.84  4967.0 1758.68
  4983.1 1755.11  4992.1 1747.94  4994.9 1747.44  4998.1 1747.94  5010.7 1749.40
  5017.9 1757.50  5114.2 1757.35  5152.2 1760.88  5157.9 1760.51  5174.0 1764.06
  5179.7 1763.80  5195.8 1768.24  5201.5 1765.98  5211.5 1767.38  5217.7 1769.11
  5223.4 1767.14  5233.8 1769.05  5277.5 1772.81  5299.4 1773.02  5305.0 1772.09
  5321.2 1772.16  5348.7 1770.30  5381.0 1770.69  5386.7 1769.73  5411.9 1768.90
#Mann=3,-1,0
  4793.9    0.16       0  4992.1    0.07       0  4998.1    0.16       0
Bank Sta=4992.1,4998.1
Exp/Cntr=0.3,0.1

Type RM Length L Ch R = 1,3237,360,360,360
BEGIN DESCRIPTION:
UNT 0040 IN HEWA 6.0
END DESCRIPTION:
XS GIS Cut Line= 2
      2739108.86     10069627.32      2738565.28     10070238.85
#Sta/Elev= 30
  4723.0 1771.74  4742.2 1769.18  4763.1 1768.00  4784.9 1764.75  4791.6 1764.72
  4805.8 1762.26  4812.5 1762.02  4834.2 1757.31  4855.1 1754.60  4876.9 1753.56
  4912.0 1750.17  4940.4 1749.70  4975.5 1747.80  4994.3 1742.43  4997.0 1741.93
  5000.3 1742.43  5018.2 1744.47  5025.7 1746.96  5048.2 1750.46  5053.3 1751.34
  5060.8 1754.44  5075.0 1757.69  5088.3 1759.40  5167.0 1762.81  5181.2 1762.43
  5216.4 1763.71  5266.5 1766.80  5422.1 1770.85  5464.7 1770.51  5541.2 1772.60
#Mann=5,-1,0
  4723.0    0.16       0  4994.3    0.07       0  5000.3    0.16       0
  5048.2     0.1       0  5088.3    0.05       0
Bank Sta=4994.3,5000.3
Exp/Cntr=0.3,0.1

Type RM Length L Ch R = 1,2877,451,451,451
BEGIN DESCRIPTION:
UNT 0040 IN HEWA 5.0
END DESCRIPTION:
XS GIS Cut Line= 2
      2739055.45     10069394.32      2738362.30     10069757.86
#Sta/Elev= 30
  4658.4 1767.95  4664.3 1767.15  4669.9 1767.90  4708.4 1764.79  4714.0 1765.55
  4730.4 1763.30  4758.1 1762.25  4774.6 1759.96  4790.5 1759.50  4796.6 1757.78
  4862.8 1753.13  4879.2 1750.24  4884.8 1750.54  4892.1 1748.57  4945.4 1745.05
  4973.1 1741.85  4992.1 1741.52  4994.9 1741.02  4998.1 1741.52  5017.2 1742.37
  5049.4 1741.80  5072.1 1742.01  5094.1 1743.47  5143.9 1748.10  5176.0 1746.75
  5292.6 1754.54  5309.0 1754.72  5314.7 1755.71  5389.0 1759.75  5441.1 1761.50
#Mann=5,-1,0
  4658.4    0.16       0  4992.1    0.07       0  4998.1    0.16       0
  5049.4     0.1       0  5176.0    0.05       0
Bank Sta=4992.1,4998.1
Exp/Cntr=0.3,0.1

Type RM Length L Ch R = 1,2426,478,478,478
BEGIN DESCRIPTION:
UNT 0040 IN HEWA 4.0
END DESCRIPTION:
XS GIS Cut Line= 2
      2738802.97     10069064.23      2738235.04     10069326.35
#Sta/Elev= 30
  4698.1 1761.81  4747.1 1758.74  4769.1 1756.09  4800.5 1749.69  4806.0 1749.60
  4813.2 1747.09  4823.4 1745.27  4828.9 1745.88  4835.2 1743.66  4885.5 1737.24
  4897.8 1735.68  4920.7 1734.83  4978.4 1734.79  4989.4 1733.00  4995.1 1728.81
  4997.6 1728.56  5000.3 1728.06  5003.6 1728.56  5011.4 1729.63  5018.0 1732.79
  5033.5 1734.65  5041.0 1736.60  5086.8 1741.59  5115.3 1743.62  5138.2 1746.91
  5143.7 1746.75  5184.1 1752.47  5189.6 1751.86  5207.1 1753.97  5323.6 1758.93
#Mann=4,-1,0
  4698.1    0.16       0  4885.5     0.1       0  4997.6    0.07       0
  5003.6     0.1       0
Bank Sta=4997.6,5003.6
Exp/Cntr=0.3,0.1

Type RM Length L Ch R = 1,1948,355,355,355
BEGIN DESCRIPTION:
UNT 0040 IN HEWA 3.0
END DESCRIPTION:
XS GIS Cut Line= 3
      2738739.87     10068782.65      2738356.36     10068782.65
      2738052.04     10068913.07
#Sta/Elev= 30
  4562.9 1758.43  4594.3 1755.79  4629.8 1753.81  4728.5 1748.59  4754.3 1746.25
  4807.2 1739.77  4884.3 1731.88  4946.4 1727.19  4955.0 1726.17  4966.6 1722.70
  4984.7 1718.87  4995.5 1717.87  4998.3 1717.37  5001.5 1717.87  5016.5 1718.38
  5033.0 1719.28  5060.9 1721.56  5066.3 1721.27  5084.4 1723.01  5089.9 1724.42
  5096.4 1724.97  5107.3 1725.08  5118.9 1728.12  5129.1 1729.41  5142.4 1732.16
  5172.6 1735.51  5195.1 1736.14  5236.8 1735.47  5242.2 1735.79  5277.5 1733.74
#Mann=9,-1,0
  4562.9    0.05       0  4629.8    0.16       0  4728.5     0.1       0
  4807.2    0.16       0  4995.5    0.07       0  5001.5    0.16       0
  5016.5     0.1       0  5033.0    0.05       0  5142.4     0.1       0
Bank Sta=4995.5,5001.5
Exp/Cntr=0.3,0.1

Type RM Length L Ch R = 1,1593,354,354,354
BEGIN DESCRIPTION:
Mapping XS e020ef0e
END DESCRIPTION:
XS GIS Cut Line= 3
      2738684.00     10068418.55      2738280.39     10068438.08
      2737915.80     10068765.77
#Sta/Elev= 30
  4492.4 1751.41  4528.0 1751.90  4596.0 1749.78  4658.1 1745.66  4688.2 1745.59
  4698.1 1744.10  4703.1 1744.42  4728.2 1740.65  4768.3 1738.13  4788.3 1734.04
  4808.3 1731.81  4883.6 1727.39  4901.6 1727.75  4923.3 1726.51  4937.5 1724.37
  4944.2 1720.84  4958.4 1717.47  4979.7 1714.16  4986.8 1711.45  4997.5 1710.84
  4998.0 1710.81  5000.8 1710.31  5004.0 1710.81  5016.6 1713.58  5029.5 1717.12
  5057.9 1719.96  5086.3 1720.97  5170.7 1726.38  5227.5 1727.80  5386.7 1729.01
#Mann=7,-1,0
  4492.4    0.05       0  4596.0     0.1       0  4883.6    0.16       0
  4997.5     0.1       0  4998.0    0.07       0  5004.0     0.1       0
  5016.6    0.05       0
Bank Sta=4998,5004
Exp/Cntr=0.3,0.1

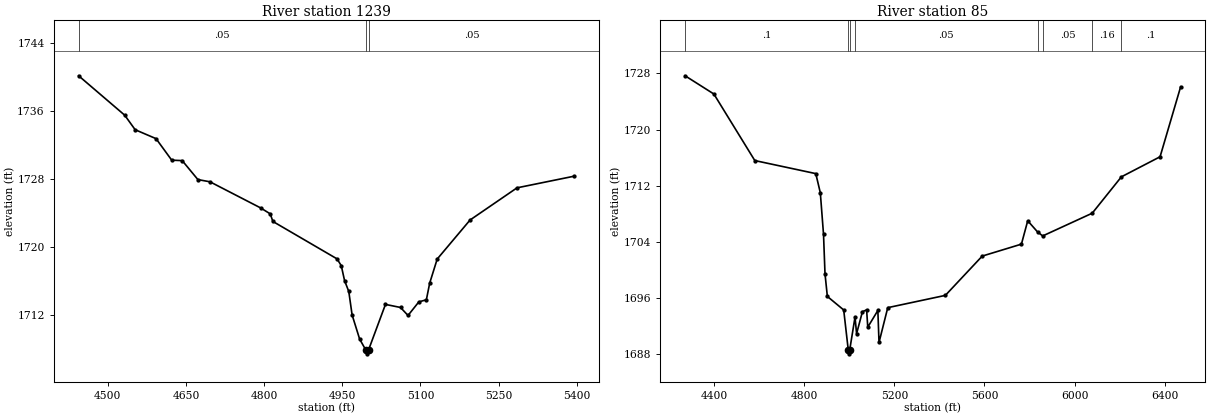
Type RM Length L Ch R = 1,1239,1154,1154,1154
BEGIN DESCRIPTION:
Mapping XS 502dce00
END DESCRIPTION:
XS GIS Cut Line= 4
      2738486.55     10068298.05      2738015.67     10068337.11
      2737824.70     10068489.02      2737813.85     10068723.35
#Sta/Elev= 30
  4444.0 1740.10  4532.4 1735.47  4552.5 1733.76  4592.6 1732.71  4622.7 1730.18
  4642.8 1730.13  4672.9 1727.90  4696.1 1727.64  4793.3 1724.57  4811.8 1723.87
  4816.8 1722.98  4940.0 1718.58  4948.1 1717.78  4954.4 1716.03  4962.5 1714.75
  4968.9 1711.99  4983.3 1709.16  4994.7 1707.92  4997.5 1707.42  5000.7 1707.92
  5032.9 1713.23  5061.8 1712.87  5076.2 1711.93  5097.0 1713.53  5111.4 1713.77
  5117.8 1715.73  5132.2 1718.56  5195.3 1723.15  5285.4 1726.93  5395.1 1728.30
#Mann=3,-1,0
  4444.0    0.05       0  4994.7    0.04       0  5000.7    0.05       0
Bank Sta=4994.7,5000.7
Exp/Cntr=0.3,0.1

Type RM Length L Ch R = 1,85,0,0,0
BEGIN DESCRIPTION:
UNT 0040 IN HEWA 2.0
END DESCRIPTION:
XS GIS Cut Line= 5
      2738386.75     10067334.51      2737653.26     10067538.50
      2737616.37     10067714.28      2737475.31     10068367.49
      2737674.95     10068923.00
#Sta/Elev= 30
  4271.3 1727.66  4399.1 1725.06  4580.7 1715.58  4851.4 1713.72  4871.5 1710.99
  4885.7 1705.06  4892.3 1699.44  4902.7 1696.22  4975.3 1694.29  4995.7 1688.54
  4998.5 1688.04  5001.7 1688.54  5025.5 1693.28  5032.5 1690.92  5058.4 1694.05
  5077.0 1694.30  5082.1 1691.84  5126.9 1694.22  5132.0 1689.66  5170.8 1694.62
  5426.5 1696.37  5590.2 1701.97  5764.1 1703.67  5792.1 1707.00  5835.7 1705.41
  5858.6 1704.84  6078.4 1708.08  6207.8 1713.26  6379.5 1716.12  6470.8 1726.09
#Mann=8,-1,0
  4271.3     0.1       0  4995.7    0.07       0  5001.7     0.1       0
  5025.5    0.05       0  5835.7     0.1       0  5858.6    0.05       0
  6078.4    0.16       0  6207.8     0.1       0
Bank Sta=4995.7,5001.7
Exp/Cntr=0.3,0.1

Chan Stop Cuts=-1