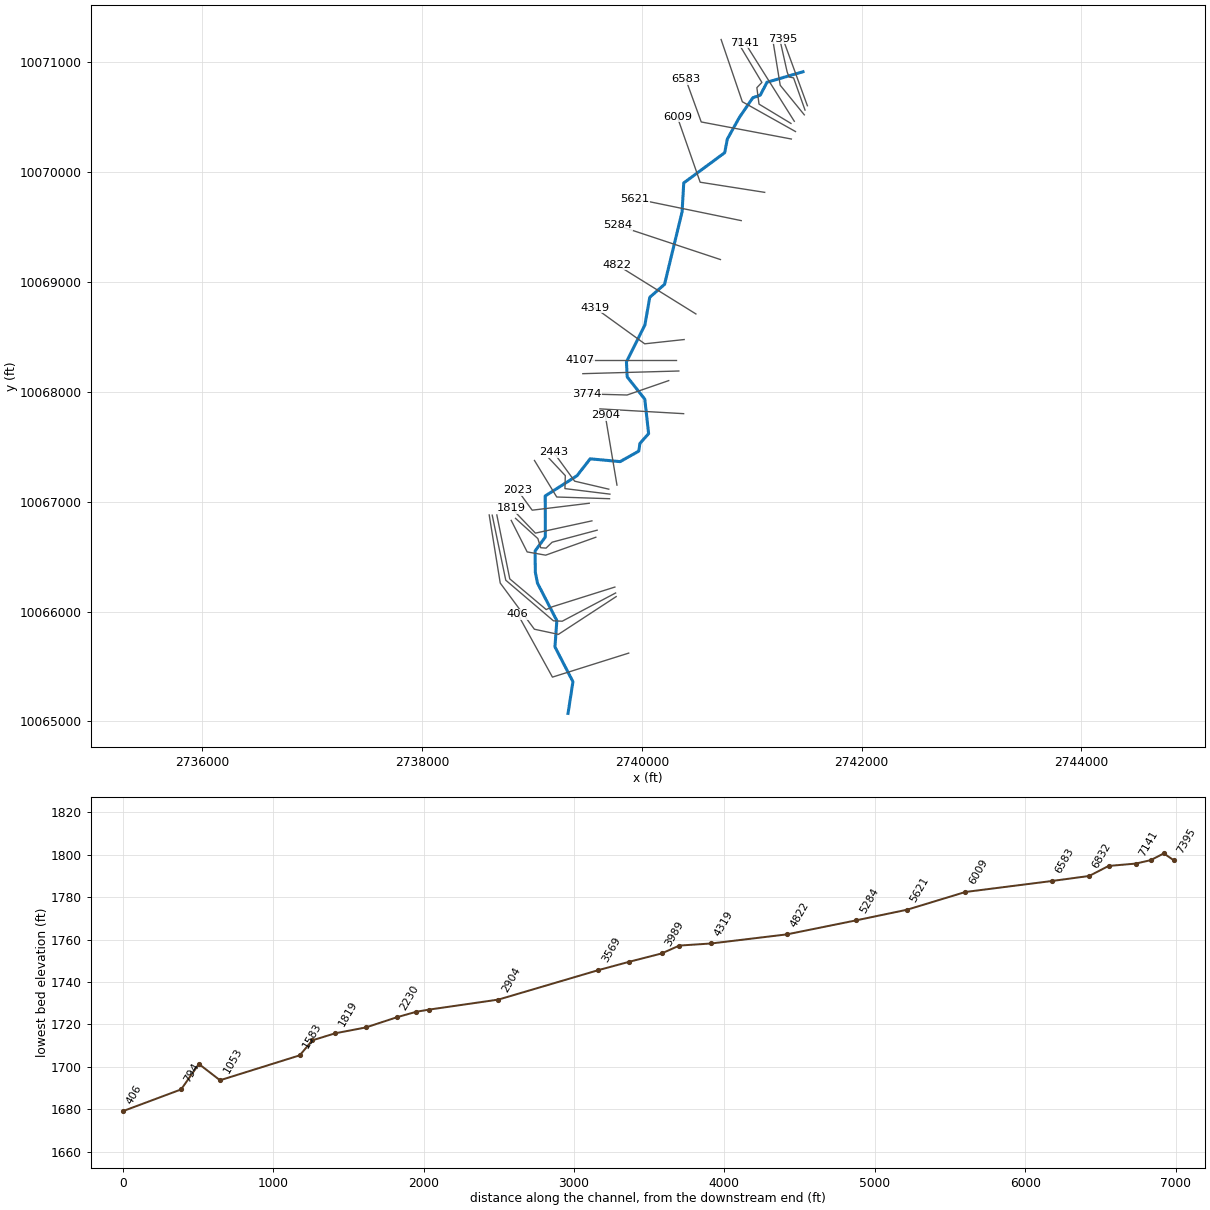
--- UNT 0041 IN HEWA.prj (project) ---

Proj Title=UNT 0041 IN HEWA Base Level Engineering
Current Plan=p01
Default Exp/Contr=0.3,0.1
English Units
Geom File=g01
Flow File=f01
Plan File=p01
Y Axis Title=Elevation
X Axis Title(PF)=Main Channel Distance
X Axis Title(XS)=Station
BEGIN DESCRIPTION:
UNT 0041 IN HEWA
END DESCRIPTION:
DSS Export Rating Curves= 0
DSS Export Rating Curve Sorted= 0
DSS Export Volume Flow Curves= 0
DXF OffsetX= 0
DXF OffsetY= 0
DXF ScaleX= 1
DXF ScaleY= 10

--- UNT 0041 IN HEWA.p01 (plan) ---

Plan Title=Multiple Run
Short Identifier=Multiple
Geom File=g01
Flow File=f01
Subcritical Flow
K Sum by GR= 0
Std Step Tol= 0.01
Critical Tol= 0.01
Num of Std Step Trials= 20
Max Error Tol= 0.3
Flow Tol Ratio= 0.001
Split Flow NTrial= 30
Split Flow Tol= 0.02
Split Flow Ratio= 0.02
Log Output Level= 0
Friction Slope Method= 1
Unsteady Friction Slope Method= 2
Unsteady Bridges Friction Slope Method= 1
Parabolic Critical Depth
Global Vel Dist=  1 , 1 , 1
Global Log Level= 0
CheckData=True
Encroach Param= -1, 0, 0, 0
BEGIN DESCRIPTION:
Multiple Run
END DESCRIPTION:

--- UNT 0041 IN HEWA.f01 (steady flow) ---

Flow Title=Multiple
Program Version=4.10
Number of Profiles= 7
Profile Names=10-year,25-year,50-year,1pct_min,100-year,1pct_plu,500-year
River Rch & RM=UNT 0041 IN HEWA,Reach-1         ,7395
     402     561     695     633     855    1157    1298
River Rch & RM=UNT 0041 IN HEWA,Reach-1         ,3989
     520     737     922     846    1144    1547    1768
Boundary for River Rch & Prof#=UNT 0041 IN HEWA,Reach-1         , 1
Up Type= 0
Dn Type= 3
Dn Slope=0.022
Boundary for River Rch & Prof#=UNT 0041 IN HEWA,Reach-1         , 2
Up Type= 0
Dn Type= 3
Dn Slope=0.022
Boundary for River Rch & Prof#=UNT 0041 IN HEWA,Reach-1         , 3
Up Type= 0
Dn Type= 3
Dn Slope=0.022
Boundary for River Rch & Prof#=UNT 0041 IN HEWA,Reach-1         , 4
Up Type= 0
Dn Type= 3
Dn Slope=0.022
Boundary for River Rch & Prof#=UNT 0041 IN HEWA,Reach-1         , 5
Up Type= 0
Dn Type= 3
Dn Slope=0.022
Boundary for River Rch & Prof#=UNT 0041 IN HEWA,Reach-1         , 6
Up Type= 0
Dn Type= 3
Dn Slope=0.022
Boundary for River Rch & Prof#=UNT 0041 IN HEWA,Reach-1         , 7
Up Type= 0
Dn Type= 3
Dn Slope=0.022
DSS Import GetInterval= 0
DSS Import GetPeak= 0
DSS Import FillOption= 0

--- UNT 0041 IN HEWA.g01 (geometry) ---

Geom Title=Existing Conditions
Program Version=4.10

River Reach=UNT 0041 IN HEWA,Reach-1
Reach XY= 30
      2741467.17     10070914.48      2741139.19     10070818.76
       2741078.6     10070700.89      2741010.85      10070678.3
      2740888.57     10070499.28      2740778.86     10070302.66
      2740754.38     10070177.38      2740381.83      10069902.4
      2740366.57     10069639.25      2740207.04     10068979.18
      2740072.44      10068861.3      2740028.14      10068609.6
      2739860.17     10068273.33       2739866.9      10068136.8
      2740027.18     10067933.82      2740062.08     10067620.02
      2739982.64     10067531.43      2739972.83     10067461.29
      2739802.88     10067365.54      2739529.83     10067390.89
      2739410.24     10067237.27      2739120.89     10067052.88
      2739121.63     10066678.99       2739028.7     10066552.34
      2739030.64     10066359.46      2739050.16     10066259.44
      2739226.55     10065918.26      2739209.36      10065679.1
      2739373.04     10065361.85      2739328.47     10065073.73

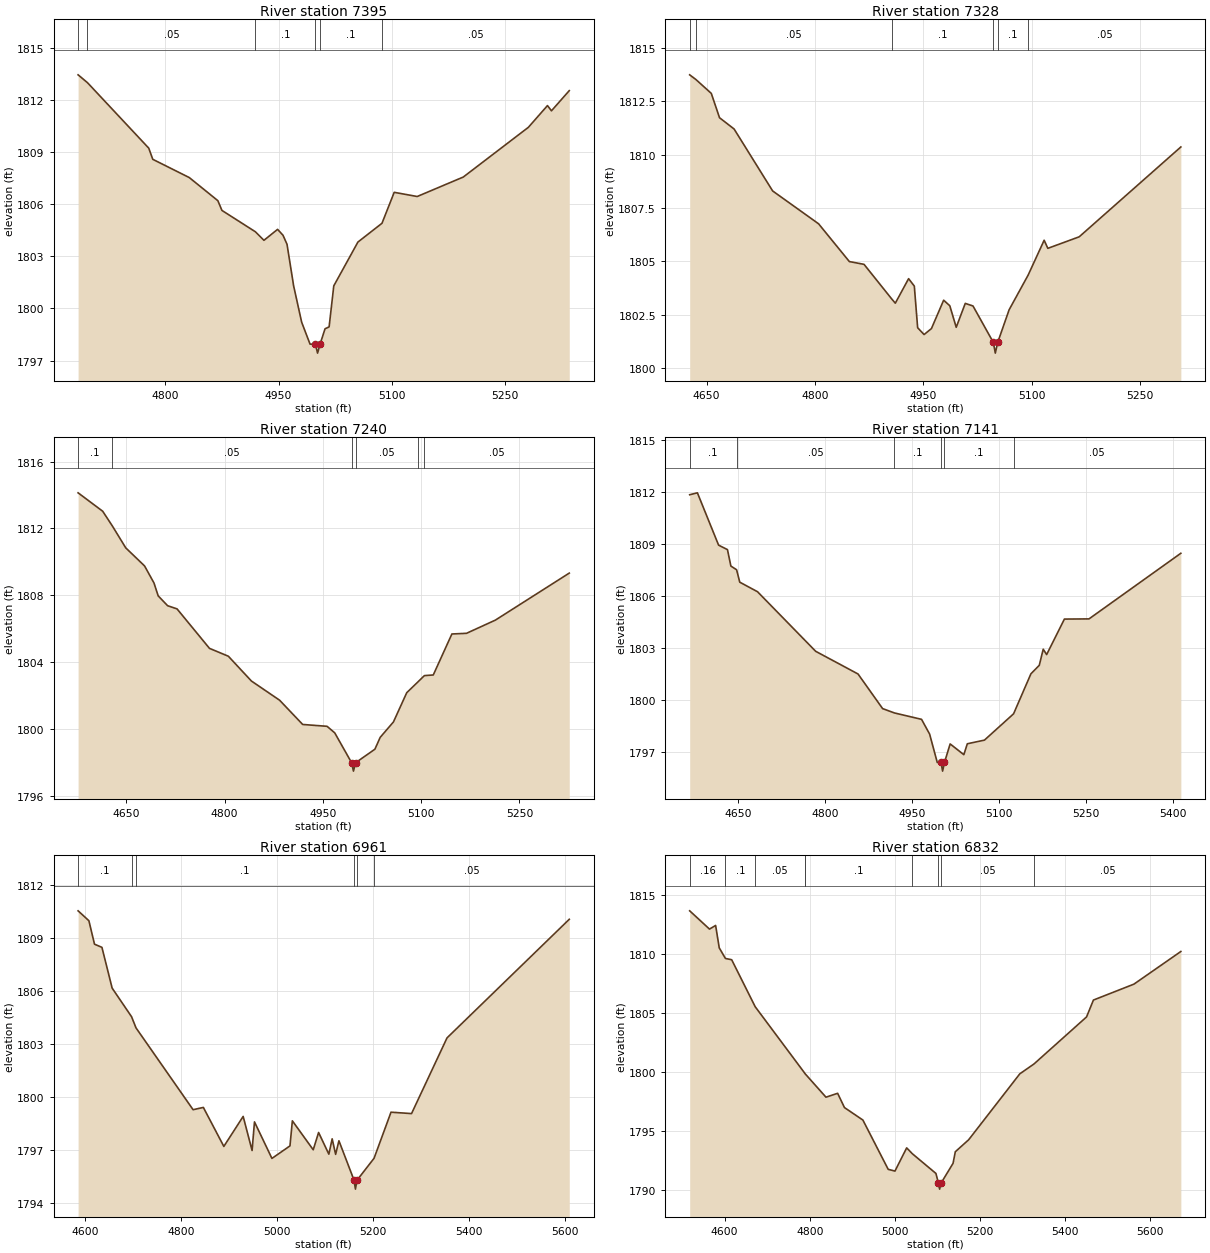
Type RM Length L Ch R = 1 ,7395    ,67,67,67
BEGIN DESCRIPTION:
UNT 0041 IN HEWA 16.0
END DESCRIPTION:
XS GIS Cut Line= 2
      2741507.26     10070605.27      2741283.94     10071216.98
#Sta/Elev= 30
  4684.3 1813.44  4696.7 1812.99    4778 1809.22  4783.3 1808.58  4831.7 1807.53
  4869.6  1806.2    4875 1805.64  4919.4 1804.41  4930.7 1803.92  4948.8 1804.55
    4956 1804.21  4961.3 1803.69  4970.1 1801.29  4980.7 1799.21  4991.8 1797.95
    4999 1797.93  5001.8 1797.43    5005 1797.93  5011.7 1798.83  5017.1 1798.94
  5023.3  1801.3  5055.3 1803.82  5087.2  1804.9  5103.4 1806.68  5133.9 1806.44
    5195 1807.56  5281.3 1810.42  5306.6 1811.67  5311.9 1811.37  5335.5 1812.53
#Mann= 6 ,-1 , 0
  4684.3      .1       0  4696.7     .05       0  4919.4      .1       0
    4999     .07       0    5005      .1       0  5087.2     .05       0
Bank Sta=4999,5005
XS Rating Curve= 0 ,0
Exp/Cntr=0.3,0.1

Type RM Length L Ch R = 1 ,7328    ,88,88,88
BEGIN DESCRIPTION:
Mapping XS b2b354dc
END DESCRIPTION:
XS GIS Cut Line= 5
      2741485.79      10070565.6      2741381.62     10070858.57
      2741340.39     10070867.25      2741323.03     10070912.83
      2741262.27     10071184.06
#Sta/Elev= 30
  4626.6 1813.74  4635.2 1813.52  4656.5 1812.87  4667.9 1811.73  4688.1  1811.2
  4741.4  1808.3    4805 1806.76  4847.6 1804.99  4867.9 1804.86  4906.9 1803.21
  4911.2 1803.04  4929.6 1804.19  4937.5 1803.84  4942.1 1801.89    4951 1801.57
  4961.2 1801.85  4978.1 1803.18  4986.6 1802.92  4995.5 1801.91    5008 1803.03
  5018.7 1802.91  5046.9  1801.2  5049.6  1800.7  5052.9  1801.2  5068.7 1802.73
  5095.1 1804.36  5117.2 1805.99  5122.3 1805.61  5165.7 1806.15  5306.4 1810.36
#Mann= 6 ,-1 , 0
  4626.6      .1       0  4635.2     .05       0  4906.9      .1       0
  5046.9     .07       0  5052.9      .1       0  5095.1     .05       0
Bank Sta=5046.9,5052.9
XS Rating Curve= 0 ,0
Exp/Cntr=0.3,0.1

Type RM Length L Ch R = 1 ,7240    ,99,99,99
BEGIN DESCRIPTION:
Mapping XS 04f34741
END DESCRIPTION:
XS GIS Cut Line= 3
      2741479.26     10070522.22      2741260.09      10070791.3
      2741194.99     10071188.46
#Sta/Elev= 30
  4576.5 1814.13    4614 1813.03  4628.6 1812.16  4649.2 1810.84  4677.9 1809.76
  4692.3 1808.74  4698.7 1807.97  4713.1 1807.38  4727.5 1807.19    4777 1804.83
  4805.8 1804.36  4840.9 1802.88    4884 1801.73  4919.2 1800.28  4956.4 1800.17
  4968.1 1799.78  4993.9 1797.99  4996.7 1797.49  4999.9 1797.99  5029.4  1798.8
  5037.5 1799.51  5057.7 1800.43    5078 1802.18  5094.7 1802.81  5104.9  1803.2
  5118.5 1803.24  5146.9 1805.69  5169.2 1805.73  5213.3 1806.52    5326 1809.33
#Mann= 6 ,-1 , 0
  4576.5      .1       0  4628.6     .05       0  4993.9    .035       0
  4999.9     .05       0  5094.7      .1       0  5104.9     .05       0
Bank Sta=4993.9,4999.9
XS Rating Curve= 0 ,0
Exp/Cntr=0.3,0.1

Type RM Length L Ch R = 1 ,7141    ,180,180,180
BEGIN DESCRIPTION:
Mapping XS ed9fed89
END DESCRIPTION:
XS GIS Cut Line= 2
      2741388.12     10070463.62      2740937.73     10071180.36
#Sta/Elev= 30
  4566.4 1811.86  4579.7 1811.97  4616.2 1808.95  4631.5 1808.69  4637.4 1807.74
  4647.2 1807.53  4652.7 1806.81  4683.3 1806.26  4783.5 1802.82  4856.5 1801.51
  4898.9 1799.51  4919.2 1799.26    4966 1798.89  4979.9 1798.04  4993.1  1796.4
  4999.5  1796.4  5002.3  1795.9  5005.5  1796.4  5015.3 1797.47  5038.9 1796.85
  5044.9 1797.48  5074.4 1797.69  5124.6 1799.21  5154.5 1801.52  5168.9 1802.01
  5175.7 1802.94  5181.6 1802.63  5212.2 1804.68  5254.6 1804.69  5412.9 1808.48
#Mann= 6 ,-1 , 0
  4566.4      .1       0  4647.2     .05       0  4919.2      .1       0
  4999.5     .07       0  5005.5      .1       0  5124.6     .05       0
Bank Sta=4999.5,5005.5
XS Rating Curve= 0 ,0
Exp/Cntr=0.3,0.1

Type RM Length L Ch R = 1 ,6961    ,129,129,129
BEGIN DESCRIPTION:
Mapping XS 8cf72442
END DESCRIPTION:
XS GIS Cut Line= 5
      2741357.72     10070444.09      2741066.95     10070619.86
      2741047.42      10070769.6      2741092.99     10070817.34
      2740853.46     10071218.72
#Sta/Elev= 30
  4584.9 1810.55  4607.4 1809.99  4619.1 1808.66  4634.6 1808.48  4655.9 1806.17
  4696.4 1804.55  4705.6 1803.92  4824.7 1799.28  4846.1 1799.41  4888.8  1797.2
  4929.1  1798.9  4947.7 1796.97  4952.7 1798.59  4989.1 1796.52  5026.7 1797.23
  5031.7 1798.65  5075.2 1797.01  5086.4 1797.99  5107.8 1796.76  5114.7 1797.63
  5121.9 1796.75  5128.8 1797.52  5160.4 1795.28  5163.2 1794.78  5166.4 1795.28
  5202.1 1796.53  5237.4 1799.14  5280.2 1799.06  5354.2 1803.35  5609.1 1810.07
#Mann= 6 ,-1 , 0
  4584.9      .1       0  4696.4     .05       0  4705.6      .1       0
  5160.4     .07       0  5166.4      .1       0  5202.1     .05       0
Bank Sta=5160.4,5166.4
XS Rating Curve= 0 ,0
Exp/Cntr=0.3,0.1

Type RM Length L Ch R = 1 ,6832    ,249,249,249
BEGIN DESCRIPTION:
UNT 0041 IN HEWA 15.0
END DESCRIPTION:
XS GIS Cut Line= 3
      2741399.02     10070370.27      2740915.04     10070641.56
      2740721.88     10071208.01
#Sta/Elev= 30
  4518.2 1813.67  4564.7 1812.12  4579.1 1812.43  4587.6 1810.53  4602.1 1809.63
  4616.8 1809.52  4672.1 1805.53  4788.1 1799.91  4788.7 1799.87  4838.2 1797.86
  4865.6 1798.19  4881.6 1796.98  4924.9 1795.92  4984.3 1791.74  5000.2 1791.59
  5027.7 1793.56  5041.1 1793.06  5096.4 1791.39  5102.3 1790.56  5105.1 1790.06
  5108.3 1790.56  5136.6 1792.25  5141.9 1793.23  5173.3 1794.25  5293.3 1799.84
  5326.7 1800.68  5450.1 1804.67  5466.2  1806.1  5561.3 1807.45  5671.5 1810.22
#Mann= 9 ,-1 , 0
  4518.2     .16       0  4602.1      .1       0  4672.1     .05       0
  4788.1     .16       0  4788.7      .1       0  5041.1     .05       0
  5102.3     .07       0  5108.3     .05       0  5326.7     .05       0
Bank Sta=5102.3,5108.3
XS Rating Curve= 0 ,0
Exp/Cntr=0.3,0.1

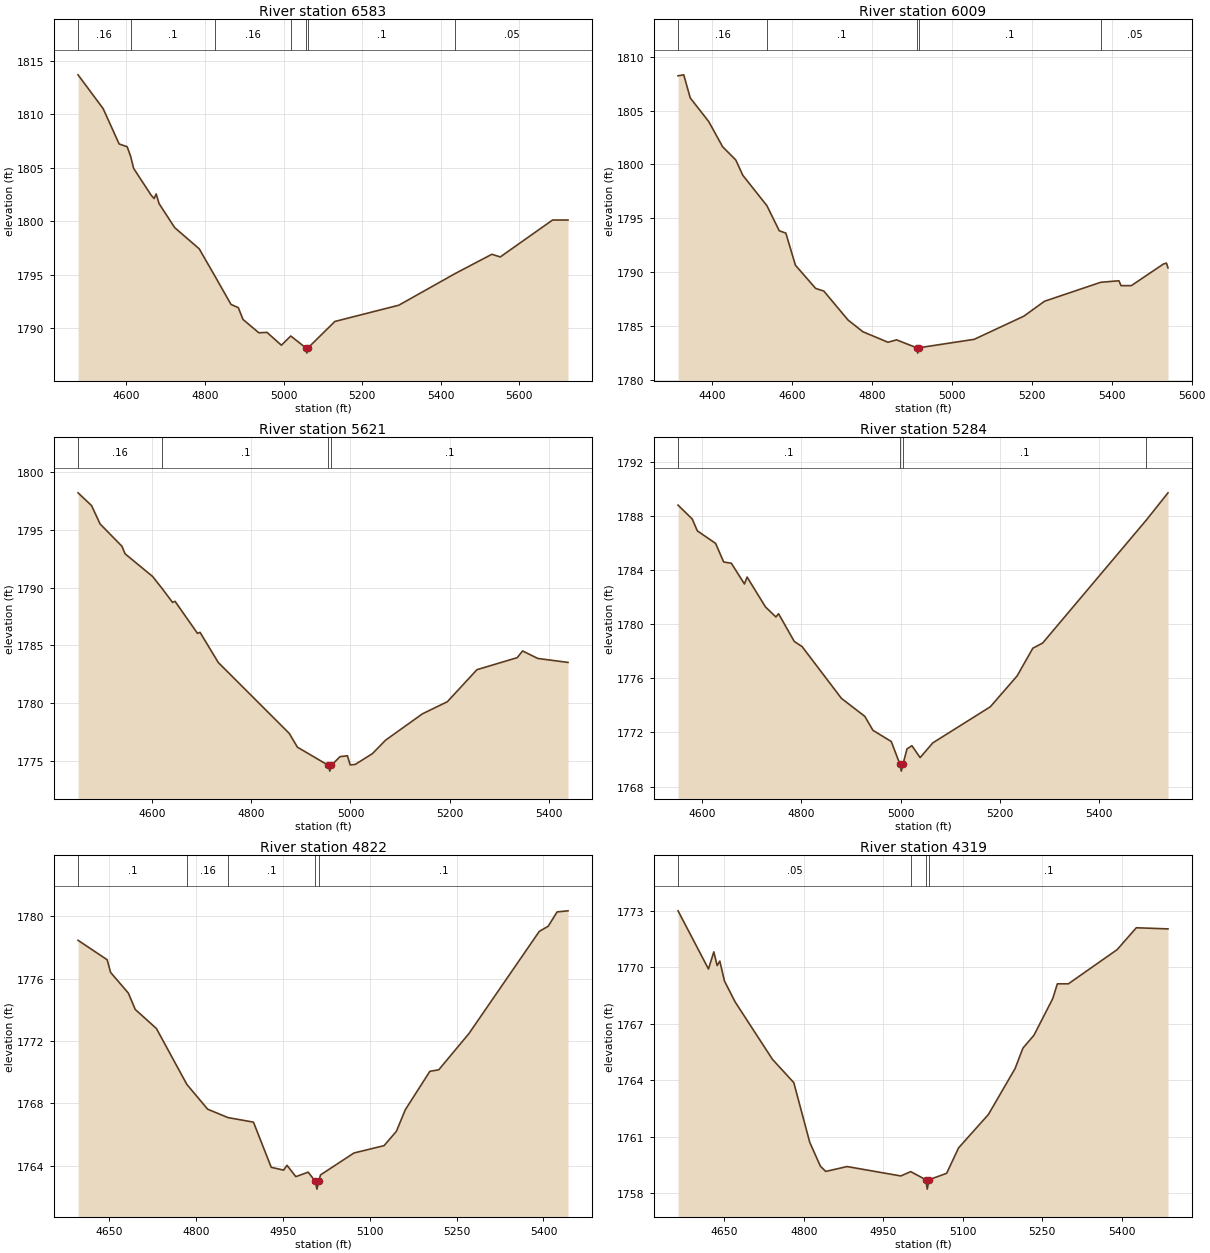
Type RM Length L Ch R = 1 ,6583    ,574,574,574
BEGIN DESCRIPTION:
UNT 0041 IN HEWA 14.0
END DESCRIPTION:
XS GIS Cut Line= 3
      2741361.36     10070302.16      2740540.95      10070457.5
      2740400.16     10070845.88
#Sta/Elev= 30
  4476.6 1813.68  4540.6 1810.52  4581.3 1807.22  4601.7 1806.96  4610.6 1806.07
  4618.2 1804.94  4662.7 1802.44  4670.5 1802.12  4675.6 1802.55  4683.1 1801.64
  4722.8  1799.4  4785.3 1797.42  4826.7 1794.78  4866.3 1792.22  4884.9 1791.92
  4896.8 1790.82  4937.2 1789.57  4957.9 1789.61  4994.6 1788.41  5018.5 1789.27
  5056.7 1788.17  5059.4 1787.67  5062.7 1788.17  5130.9 1790.63  5293.8 1792.15
  5436.9  1795.1  5530.9 1796.91  5552.2 1796.66  5685.4 1800.11  5724.7 1800.11
#Mann= 7 ,-1 , 0
  4476.6     .16       0  4610.6      .1       0  4826.7     .16       0
  5018.5      .1       0  5056.7     .07       0  5062.7      .1       0
  5436.9     .05       0
Bank Sta=5056.7,5062.7
XS Rating Curve= 0 ,0
Exp/Cntr=0.3,0.1

Type RM Length L Ch R = 1 ,6009    ,388,388,388
BEGIN DESCRIPTION:
UNT 0041 IN HEWA 13.0
END DESCRIPTION:
XS GIS Cut Line= 3
      2741118.64     10069816.69      2740531.24     10069908.93
      2740322.97     10070504.67
#Sta/Elev= 30
  4315.1 1808.22  4329.4 1808.31  4345.6 1806.17    4392 1803.97  4426.6 1801.64
  4459.6 1800.41  4477.2 1798.99  4537.5 1796.17  4568.3 1793.85  4584.8 1793.63
  4608.8 1790.65  4659.4  1788.5  4679.7 1788.26  4740.4 1785.57  4777.7 1784.48
  4840.3 1783.51  4861.9 1783.73  4911.9    1783  4914.6  1782.5  4917.9    1783
  5056.1 1783.78  5180.3 1785.93  5231.8 1787.31  5372.6 1789.07    5418 1789.21
  5423.3 1788.76  5449.1 1788.76  5529.2 1790.76  5536.9 1790.85  5540.8 1790.41
#Mann= 5 ,-1 , 0
  4315.1     .16       0  4537.5      .1       0  4911.9     .07       0
  4917.9      .1       0  5372.6     .05       0
Bank Sta=4911.9,4917.9
XS Rating Curve= 0 ,0
Exp/Cntr=0.3,0.1

Type RM Length L Ch R = 1 ,5621    ,337,337,337
BEGIN DESCRIPTION:
UNT 0041 IN HEWA 12.0
END DESCRIPTION:
XS GIS Cut Line= 2
      2740905.06     10069559.39      2739938.96     10069758.44
#Sta/Elev= 30
  4451.5 1798.19  4478.7 1797.09  4495.9  1795.5  4539.9 1793.57  4546.2 1792.92
  4601.6 1790.96  4621.3 1789.89  4641.7 1788.72  4646.8 1788.81    4692 1786.04
  4697.1 1786.13  4733.9 1783.52  4876.8 1777.39  4893.2  1776.2  4955.5 1774.63
  4958.3 1774.13  4961.5 1774.63  4978.9 1775.38  4993.8 1775.46  4999.4 1774.67
  5009.6 1774.71  5044.1 1775.64  5070.8 1776.81  5144.7 1779.08    5195 1780.13
  5254.6  1782.9  5335.7 1783.94  5346.5 1784.52  5377.1 1783.87  5437.9 1783.53
#Mann= 4 ,-1 , 0
  4451.5     .16       0  4621.3      .1       0  4955.5     .07       0
  4961.5      .1       0
Bank Sta=4955.5,4961.5
XS Rating Curve= 0 ,0
Exp/Cntr=0.3,0.1

Type RM Length L Ch R = 1 ,5284    ,462,462,462
BEGIN DESCRIPTION:
UNT 0041 IN HEWA 11.0
END DESCRIPTION:
XS GIS Cut Line= 2
      2740715.68     10069205.02      2739778.75     10069515.71
#Sta/Elev= 30
  4551.6 1788.81  4580.3 1787.78  4590.4 1786.91  4627.3 1785.98  4643.5 1784.61
    4659 1784.51  4685.4 1782.98  4690.7 1783.49  4727.8 1781.28  4748.8 1780.54
  4754.1 1780.78  4785.8 1778.73  4801.5 1778.35  4880.8 1774.52  4927.9 1773.19
  4944.2 1772.16  4981.2 1771.33  4998.7 1769.64  5001.4 1769.14  5004.7 1769.64
  5012.8 1770.78  5022.8 1771.02  5039.3 1770.14  5064.9 1771.23  5180.8  1773.9
  5234.7 1776.18  5266.4 1778.23  5286.1 1778.61  5494.9  1787.7  5538.7 1789.72
#Mann= 4 ,-1 , 0
  4551.6      .1       0  4998.7     .07       0  5004.7      .1       0
  5494.9     .16       0
Bank Sta=4998.7,5004.7
XS Rating Curve= 0 ,0
Exp/Cntr=0.3,0.1

Type RM Length L Ch R = 1 ,4822    ,503,503,503
BEGIN DESCRIPTION:
UNT 0041 IN HEWA 10.0
END DESCRIPTION:
XS GIS Cut Line= 2
       2740492.4     10068709.83       2739773.9     10069156.47
#Sta/Elev= 30
  4596.4 1778.47  4646.7 1777.22  4652.6 1776.41  4683.3 1775.08  4695.2 1774.03
  4731.7 1772.81  4784.3 1769.22  4820.2 1767.63  4855.4 1767.09  4899.3  1766.8
    4930  1763.9  4951.3 1763.72  4957.2 1764.03  4972.5  1763.3  4993.8 1763.59
  5006.1    1763  5008.9  1762.5  5012.1    1763    5015 1763.41  5072.9 1764.82
  5124.8 1765.29  5146.1 1766.21  5161.4 1767.59  5203.9 1770.06  5219.3 1770.16
  5271.3 1772.48  5392.8 1779.04  5408.2 1779.37  5423.6 1780.29  5442.4 1780.36
#Mann= 5 ,-1 , 0
  4596.4      .1       0  4784.3     .16       0  4855.4      .1       0
  5006.1     .07       0  5012.1      .1       0
Bank Sta=5006.1,5012.1
XS Rating Curve= 0 ,0
Exp/Cntr=0.3,0.1

Type RM Length L Ch R = 1 ,4319    ,212,212,212
BEGIN DESCRIPTION:
UNT 0041 IN HEWA 9.0
END DESCRIPTION:
XS GIS Cut Line= 3
      2740385.56      10068476.8      2740026.36     10068437.97
      2739570.03     10068768.08
#Sta/Elev= 30
  4562.6    1773    4620 1769.91  4630.1 1770.82  4636.4 1770.09  4641.4 1770.33
  4650.2 1769.27  4670.3 1768.16  4740.7 1765.11    4781 1763.87  4811.1  1760.7
  4831.2 1759.43  4841.3 1759.15  4881.5 1759.41    4983 1758.91  5001.6 1759.14
  5030.1 1758.71  5032.8 1758.21  5036.1 1758.71  5069.4 1759.05  5091.9  1760.4
  5148.3 1762.18  5198.6 1764.62  5213.3  1765.7  5234.2 1766.39  5269.7 1768.34
  5278.3 1769.12  5299.1 1769.12  5391.2 1770.94  5427.3  1772.1  5487.1 1772.04
#Mann= 4 ,-1 , 0
  4562.6     .05       0  5001.6      .1       0  5030.1     .04       0
  5036.1      .1       0
Bank Sta=5030.1,5036.1
XS Rating Curve= 0 ,0
Exp/Cntr=0.3,0.1

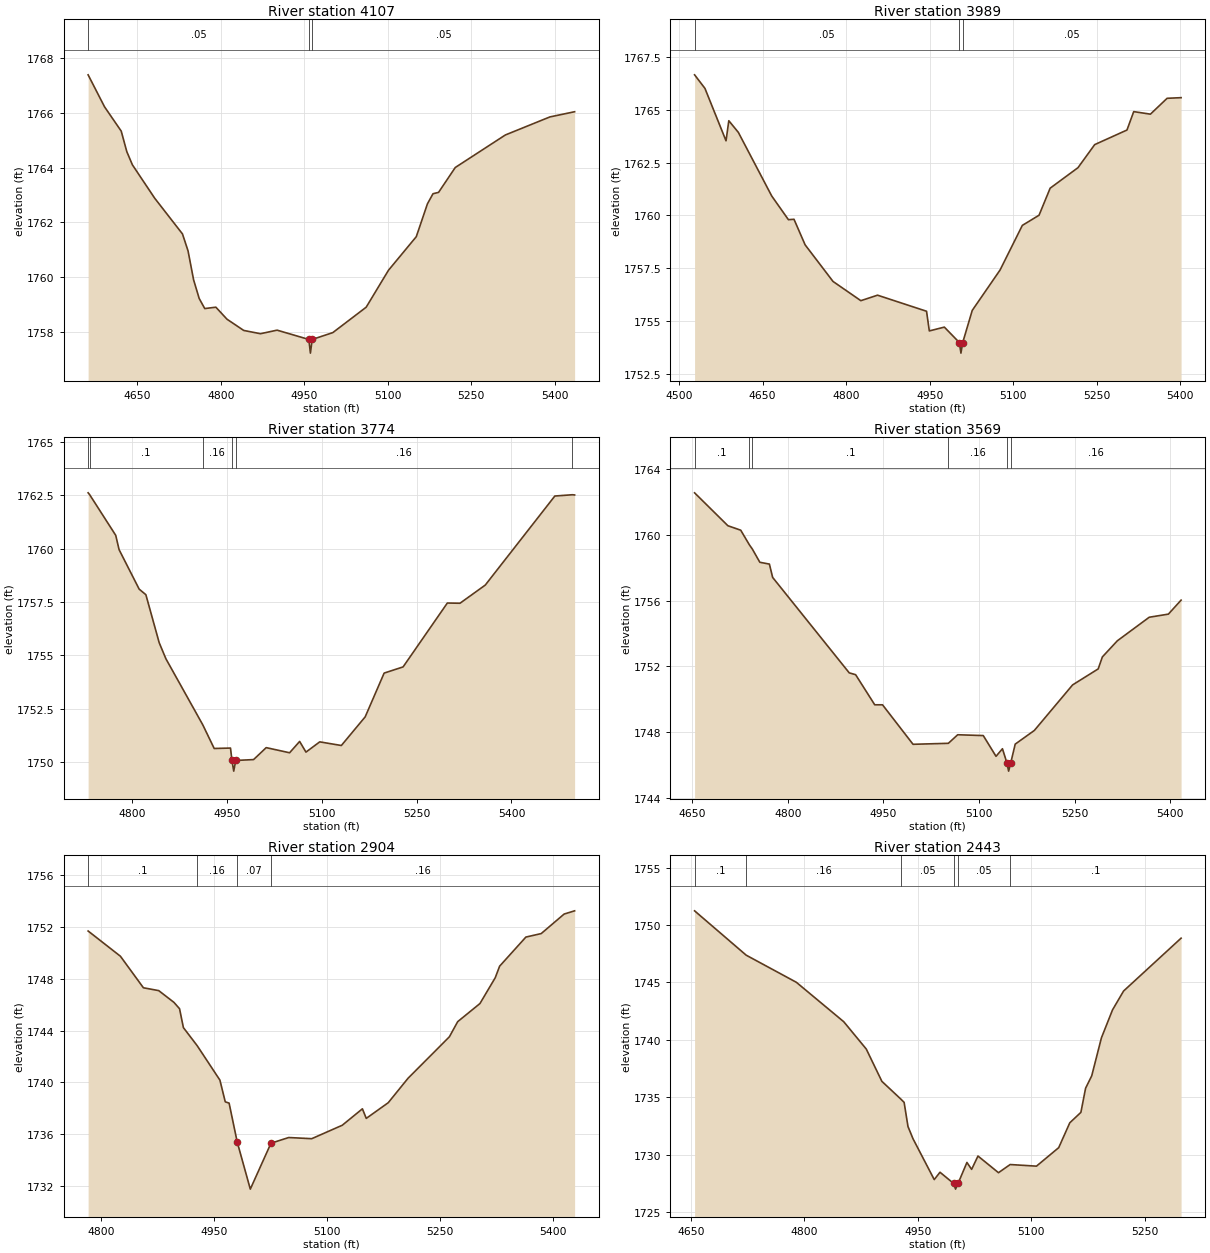
Type RM Length L Ch R = 1 ,4107    ,118,118,118
BEGIN DESCRIPTION:
Mapping XS 1a6f847b
END DESCRIPTION:
XS GIS Cut Line= 2
      2740307.97     10068292.33      2739434.07     10068292.33
#Sta/Elev= 30
  4561.7  1767.4  4591.2 1766.23  4621.2 1765.34  4631.2 1764.59  4641.2 1764.11
  4681.2 1762.89  4731.2 1761.58  4741.2 1760.96  4751.2  1759.9  4761.2 1759.22
  4771.2 1758.85  4791.2  1758.9  4811.2 1758.46  4841.2 1758.05  4871.2 1757.93
  4901.2 1758.06  4958.2 1757.72    4961 1757.22  4964.2 1757.72  5001.2 1757.97
  5061.2  1758.9  5101.2 1760.25  5151.2 1761.48  5171.2 1762.68  5181.2 1763.05
  5191.2  1763.1  5221.2 1764.01  5311.2  1765.2  5391.2 1765.86  5435.6 1766.05
#Mann= 3 ,-1 , 0
  4561.7     .05       0  4958.2     .04       0  4964.2     .05       0
Bank Sta=4958.2,4964.2
XS Rating Curve= 0 ,0
Exp/Cntr=0.3,0.1

Type RM Length L Ch R = 1 ,3989    ,215,215,215
BEGIN DESCRIPTION:
Mapping XS 8ddb2433
END DESCRIPTION:
XS GIS Cut Line= 2
      2740337.03     10068190.38      2739463.36     10068166.12
#Sta/Elev= 30
  4527.7 1766.65  4546.3 1766.01  4584.2 1763.53  4589.2 1764.48  4606.3 1763.93
  4666.3 1760.92  4696.3  1759.8  4706.3 1759.82  4726.3 1758.61  4776.4 1756.88
  4826.4 1755.97  4856.4 1756.23  4944.4 1755.47  4949.4 1754.54  4976.4 1754.72
  5003.4 1753.99  5006.2 1753.49  5009.4 1753.99  5026.5 1755.51  5076.5 1757.42
  5116.5 1759.53  5146.5 1760.01  5166.5 1761.29  5216.5 1762.26  5246.5 1763.35
  5304.5 1764.04  5316.6 1764.91  5346.6 1764.79  5376.6 1765.54  5401.7 1765.57
#Mann= 3 ,-1 , 0
  4527.7     .05       0  5003.4     .04       0  5009.4     .05       0
Bank Sta=5003.4,5009.4
XS Rating Curve= 0 ,0
Exp/Cntr=0.3,0.1

Type RM Length L Ch R = 1 ,3774    ,205,205,205
BEGIN DESCRIPTION:
UNT 0041 IN HEWA 8.0
END DESCRIPTION:
XS GIS Cut Line= 3
      2740244.79     10068102.99      2739866.15     10067971.93
      2739497.16     10067981.64
#Sta/Elev= 30
  4730.1 1762.61  4732.4 1762.53  4773.8 1760.62  4779.1 1759.95  4810.9  1758.1
  4821.5 1757.84  4842.6 1755.59  4853.2 1754.84  4911.5 1751.75  4929.6 1750.64
  4955.4 1750.66  4957.7 1750.08  4960.5 1749.58  4963.7 1750.08  4991.9 1750.12
  5011.9 1750.68  5048.9 1750.44  5064.8 1750.97  5074.8 1750.47  5096.6 1750.95
  5130.8 1750.78  5168.5 1752.12  5198.5 1754.17  5228.5 1754.46  5298.5 1757.45
  5318.5 1757.44  5358.5 1758.29  5468.6 1762.46  5496.2 1762.52  5499.9 1762.51
#Mann= 6 ,-1 , 0
  4730.1     .05       0  4732.4      .1       0  4911.5     .16       0
  4957.7     .07       0  4963.7     .16       0  5496.2     .05       0
Bank Sta=4957.7,4963.7
XS Rating Curve= 0 ,0
Exp/Cntr=0.3,0.1

Type RM Length L Ch R = 1 ,3569    ,665,665,665
BEGIN DESCRIPTION:
UNT 0041 IN HEWA 7.0
END DESCRIPTION:
XS GIS Cut Line= 2
      2740380.73     10067802.01      2739618.58      10067845.7
#Sta/Elev= 30
  4653.7 1762.55    4706 1760.55  4726.1 1760.28  4739.7 1759.39  4744.4 1759.13
  4756.1 1758.33  4771.1 1758.22  4776.2 1757.41  4896.4 1751.61  4906.4  1751.5
  4936.4 1749.67  4948.6 1749.67  4996.5 1747.27  5051.9 1747.33  5066.6 1747.85
  5106.7  1747.8  5126.7 1746.54  5136.8    1747  5143.8 1746.14  5146.5 1745.64
  5149.8 1746.14  5156.8 1747.28  5186.8 1748.11  5246.9 1750.88    5287 1751.85
  5293.6 1752.58  5317.1 1753.56  5367.1 1754.99  5397.2 1755.18  5417.1 1756.03
#Mann= 6 ,-1 , 0
  4653.7      .1       0  4739.7     .16       0  4744.4      .1       0
  5051.9     .16       0  5143.8     .07       0  5149.8     .16       0
Bank Sta=5143.8,5149.8
XS Rating Curve= 0 ,0
Exp/Cntr=0.3,0.1

Type RM Length L Ch R = 1 ,2904    ,461,461,461
BEGIN DESCRIPTION:
UNT 0041 IN HEWA 6.0
END DESCRIPTION:
XS GIS Cut Line= 2
      2739773.92     10067151.47      2739667.11     10067787.47
#Sta/Elev= 30
  4783.3  1751.7  4826.1 1749.75  4856.6 1747.31  4876.9 1747.09  4897.1 1746.18
  4904.5 1745.69  4909.6 1744.23  4927.9 1742.83    4958 1740.17  4965.1 1738.49
  4970.2 1738.39 4980.92 1735.39  4998.3 1731.74  5025.7 1735.29  5049.2 1735.73
  5079.7 1735.64  5120.2 1736.68  5146.9 1737.95    5152 1737.21  5181.1 1738.42
  5207.5 1740.32  5262.2 1743.52  5273.2 1744.69  5302.7 1746.09    5323 1748.09
  5328.8 1748.98  5363.6 1751.23  5383.9  1751.5  5414.3 1753.01  5428.2 1753.26
#Mann= 4 ,-1 , 0
  4783.3      .1       0  4927.9     .16       0 4980.92     .07       0
  5025.7     .16       0
Bank Sta=4980.92,5025.7
XS Rating Curve= 0 ,0
Exp/Cntr=0.3,0.1

Type RM Length L Ch R = 1 ,2443    ,85,85,85
BEGIN DESCRIPTION:
Mapping XS 60b46908
END DESCRIPTION:
XS GIS Cut Line= 3
      2739699.41     10067114.65      2739388.69     10067187.56
      2739198.07     10067449.22
#Sta/Elev= 30
  4654.9 1751.23  4723.1 1747.37  4789.4 1745.01    4852 1741.58  4881.8  1739.2
  4902.4 1736.39  4927.9 1734.82  4931.8 1734.56  4936.9 1732.46  4943.5  1731.4
  4971.6 1727.84  4979.2 1728.48  4997.1 1727.51  4999.8 1727.01  5003.1 1727.51
  5014.8 1729.33    5021 1728.73  5029.4 1729.89  5056.5 1728.44  5071.9 1729.15
  5106.7 1729.01  5136.1 1730.62  5150.7 1732.78  5165.4 1733.69  5171.6 1735.79
  5179.7 1736.87  5192.5 1740.17  5207.2 1742.61  5221.8 1744.25  5297.8 1748.85
#Mann= 6 ,-1 , 0
  4654.9      .1       0  4723.1     .16       0  4927.9     .05       0
  4997.1     .04       0  5003.1     .05       0  5071.9      .1       0
Bank Sta=4997.1,5003.1
XS Rating Curve= 0 ,0
Exp/Cntr=0.3,0.1

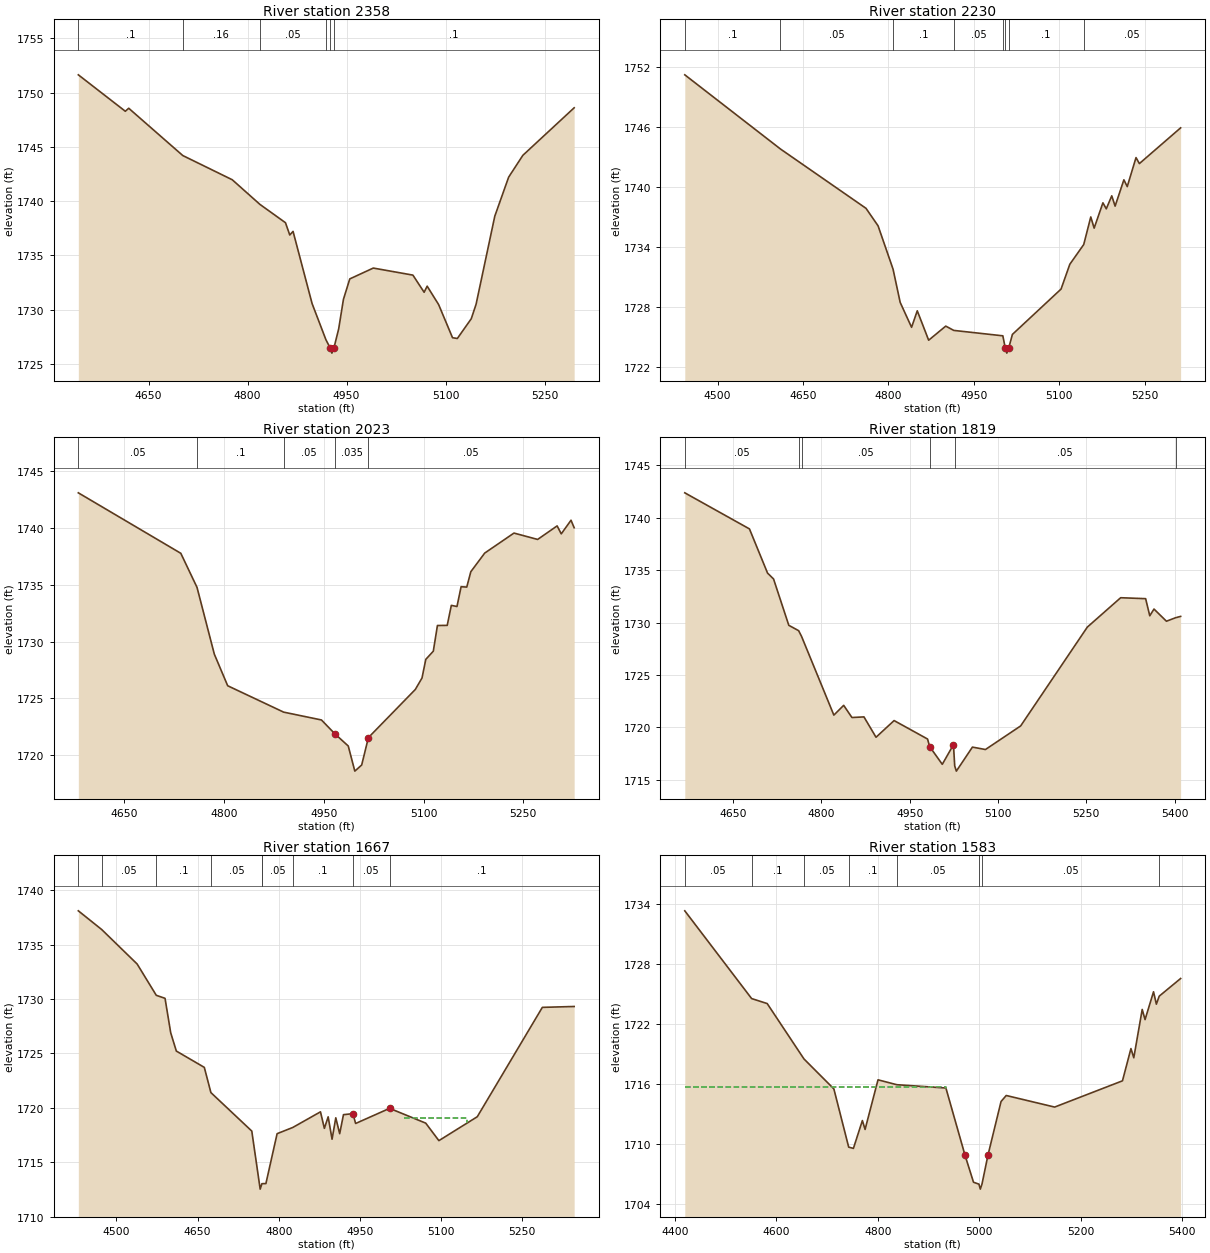
Type RM Length L Ch R = 1 ,2358    ,128,128,128
BEGIN DESCRIPTION:
UNT 0041 IN HEWA 5.0
END DESCRIPTION:
XS GIS Cut Line= 4
      2739709.82     10067069.51      2739300.14     10067119.85
      2739303.62     10067237.91      2739153.24     10067398.53
#Sta/Elev= 30
  4543.7 1751.64  4614.9 1748.28    4620 1748.56  4701.9  1744.2  4776.8 1741.97
  4818.7  1739.7  4857.4 1738.01  4863.9 1736.88  4868.9 1737.21  4897.7 1730.56
  4918.7 1727.22  4924.9 1726.49  4927.7 1725.99  4930.9 1726.49    4938 1728.23
  4945.2 1730.95  4954.8 1732.83  4990.4 1733.83  5050.4 1733.18  5067.4  1731.6
    5072 1732.16  5089.4 1730.46  5110.4 1727.41  5117.7 1727.34  5138.8 1729.16
  5146.1  1730.5  5174.4 1738.61  5195.4 1742.21  5216.9 1744.22  5294.6  1748.6
#Mann= 6 ,-1 , 0
  4543.7      .1       0  4701.9     .16       0  4818.7     .05       0
  4918.7      .1       0  4924.9     .07       0  4930.9      .1       0
Bank Sta=4924.9,4930.9
XS Rating Curve= 0 ,0
Exp/Cntr=0.3,0.1

Type RM Length L Ch R = 1 ,2230    ,207,207,207
BEGIN DESCRIPTION:
Mapping XS 000371b9
END DESCRIPTION:
XS GIS Cut Line= 3
      2739706.37     10067027.84      2739225.49     10067043.46
      2739022.93     10067375.87
#Sta/Elev= 30
  4442.5 1751.24  4610.4 1743.83  4760.6  1737.9  4781.8 1736.15  4808.1 1731.82
  4820.6  1728.5  4840.6 1726.01  4850.6 1727.66  4870.6 1724.72  4900.6 1726.13
  4914.7  1725.7  5000.8 1725.16  5005.1 1723.93  5007.8 1723.43  5011.1 1723.93
  5017.6  1725.3    5103 1729.83  5118.4 1732.31  5142.8 1734.28  5155.2 1737.04
  5161.1 1735.92  5176.5 1738.45  5182.4 1737.85    5192 1739.15  5197.9 1738.12
  5213.3 1740.75  5219.2 1740.07  5234.6 1742.97  5240.5 1742.37  5312.9 1745.94
#Mann= 8 ,-1 , 0
  4442.5      .1       0  4610.4     .05       0  4808.1      .1       0
  4914.7     .05       0  5000.8      .1       0  5005.1    .035       0
  5011.1      .1       0  5142.8     .05       0
Bank Sta=5005.1,5011.1
XS Rating Curve= 0 ,0
Exp/Cntr=0.3,0.1

Type RM Length L Ch R = 1 ,2023    ,204,204,204
BEGIN DESCRIPTION:
UNT 0041 IN HEWA 4.0
END DESCRIPTION:
XS GIS Cut Line= 3
      2739521.45     10066986.43      2739002.03     10066923.32
      2738870.95     10067102.95
#Sta/Elev= 30
  4580.8 1743.08  4734.9 1737.76  4759.3 1734.76  4785.3 1728.89  4805.4 1726.11
  4889.5 1723.79  4946.4  1723.1  4966.6 1721.88  4986.7 1720.81  4996.6  1718.6
  5006.9 1719.14    5017 1721.55  5087.5 1725.78  5097.6 1726.79  5103.3 1728.43
  5114.6 1729.15  5120.8 1731.41  5135.5 1731.42  5141.7 1733.18  5150.2 1733.08
  5156.4 1734.82  5164.9 1734.79    5171 1736.14  5191.9 1737.78  5235.9 1739.54
  5271.5 1738.98  5300.8 1740.17    5307 1739.47  5321.7 1740.67  5326.4 1740.01
#Mann= 5 ,-1 , 0
  4580.8     .05       0  4759.3      .1       0  4889.5     .05       0
  4966.6    .035       0    5017     .05       0
Bank Sta=4966.6,5017
XS Rating Curve= 0 ,0
Exp/Cntr=0.3,0.1

Type RM Length L Ch R = 1 ,1819    ,152,152,152
BEGIN DESCRIPTION:
UNT 0041 IN HEWA 3.0
END DESCRIPTION:
XS GIS Cut Line= 3
      2739545.77     10066826.24      2739031.16     10066714.57
       2738813.1     10066942.32
#Sta/Elev= 30
  4568.2 1742.37    4678 1738.93  4708.7 1734.72  4718.9 1734.16  4744.8 1729.74
  4761.5 1729.23  4766.4 1728.69  4821.3 1721.18    4838 1722.11    4852 1720.95
  4872.4 1721.01  4892.9 1719.07  4923.6 1720.66  4980.4  1718.9 4983.96 1718.18
  5005.4 1716.49  5024.4 1718.36  5026.5 1716.34  5029.3 1715.84  5056.6 1718.13
  5078.7  1717.9  5138.5 1720.15  5251.7 1729.57  5308.3 1732.37  5350.7 1732.28
  5357.7 1730.65  5364.9 1731.29    5386 1730.13  5401.4 1730.46  5410.1 1730.59
#Mann= 6 ,-1 , 0
  4568.2     .05       0  4761.5      .1       0  4766.4     .05       0
 4983.96    .035       0  5026.5     .05       0  5401.4      .1       0
Bank Sta=4983.96,5024.4
XS Rating Curve= 0 ,0
Exp/Cntr=0.3,0.1

Type RM Length L Ch R = 1 ,1667    ,84,84,84
BEGIN DESCRIPTION:
Mapping XS 84b57b92
END DESCRIPTION:
XS GIS Cut Line= 6
      2739593.51     10066741.37      2739183.82       10066632.
      2739128.27     10066578.18      2739079.66     10066581.66
      2739053.62     10066664.99      2738850.61     10066848.91
#Sta/Elev= 30
  4429.5 1738.12  4472.7  1736.4  4538.2 1733.23  4573.6 1730.35  4589.8 1730.07
  4600.3  1726.9  4610.7 1725.22  4662.4 1723.72  4674.6  1721.4  4750.2 1717.86
  4765.7 1712.52  4768.9 1713.02  4776.3 1713.03    4797 1717.62  4825.9 1718.19
  4877.2 1719.63  4884.4 1718.11  4891.4 1719.17  4898.6 1717.11  4905.5 1719.08
  4912.7 1717.62  4919.7 1719.37  4937.1 1719.46  4942.2 1718.56    5005 1719.95
  5071.8 1718.59  5096.1 1716.98  5167.1 1719.18  5287.4 1729.24  5346.2 1729.32
#Mann= 9 ,-1 , 0
  4429.5      .1       0  4472.7     .05       0  4573.6      .1       0
  4674.6     .05       0  4768.9    .035       0  4768.9     .05       0
  4825.9      .1       0  4937.1     .05       0    5005      .1       0
#XS Ineff= 2 ,-1
 4730.11  4926.7 1718.75 5032.39  5148.3 1719.05
Permanent Ineff=
       T       T
Bank Sta=4937.1,5005
XS Rating Curve= 0 ,0
Exp/Cntr=0.3,0.1

Type RM Length L Ch R = 1 ,1583    ,530,530,530
BEGIN DESCRIPTION:
Mapping XS 71dfb3d9
END DESCRIPTION:
XS GIS Cut Line= 4
      2739581.39     10066677.14       2739124.8     10066513.95
      2738956.39     10066543.46       2738811.3     10066830.19
#Sta/Elev= 30
  4419.6 1733.32  4551.3 1724.53    4582 1724.03  4654.5 1718.48  4713.4 1715.48
  4742.6 1709.65  4751.9 1709.52  4769.6 1712.31  4774.9 1711.42  4800.4 1716.39
  4837.5  1715.9  4934.2 1715.57  4971.8 1708.85  4988.6 1706.13  4999.3 1705.94
    5002 1705.44  5005.3 1705.94 5017.05 1708.83  5042.9 1714.22  5053.1 1714.82
  5148.5 1713.66  5282.2 1716.29  5298.9 1719.52  5304.5  1718.6  5321.1 1723.44
  5326.7 1722.42  5343.4 1725.21    5349 1723.97  5354.6 1724.77  5396.8 1726.54
#Mann= 8 ,-1 , 0
  4419.6     .05       0  4551.3      .1       0  4654.5     .05       0
  4742.6      .1       0  4837.5     .05       0  4999.3    .035       0
  5005.3     .05       0  5354.6      .1       0
#XS Ineff= 2 , 0
         4934.66 1715.63
Permanent Ineff=
       T       T
Bank Sta=4971.8,5017.05
XS Rating Curve= 0 ,0
Exp/Cntr=0.3,0.1

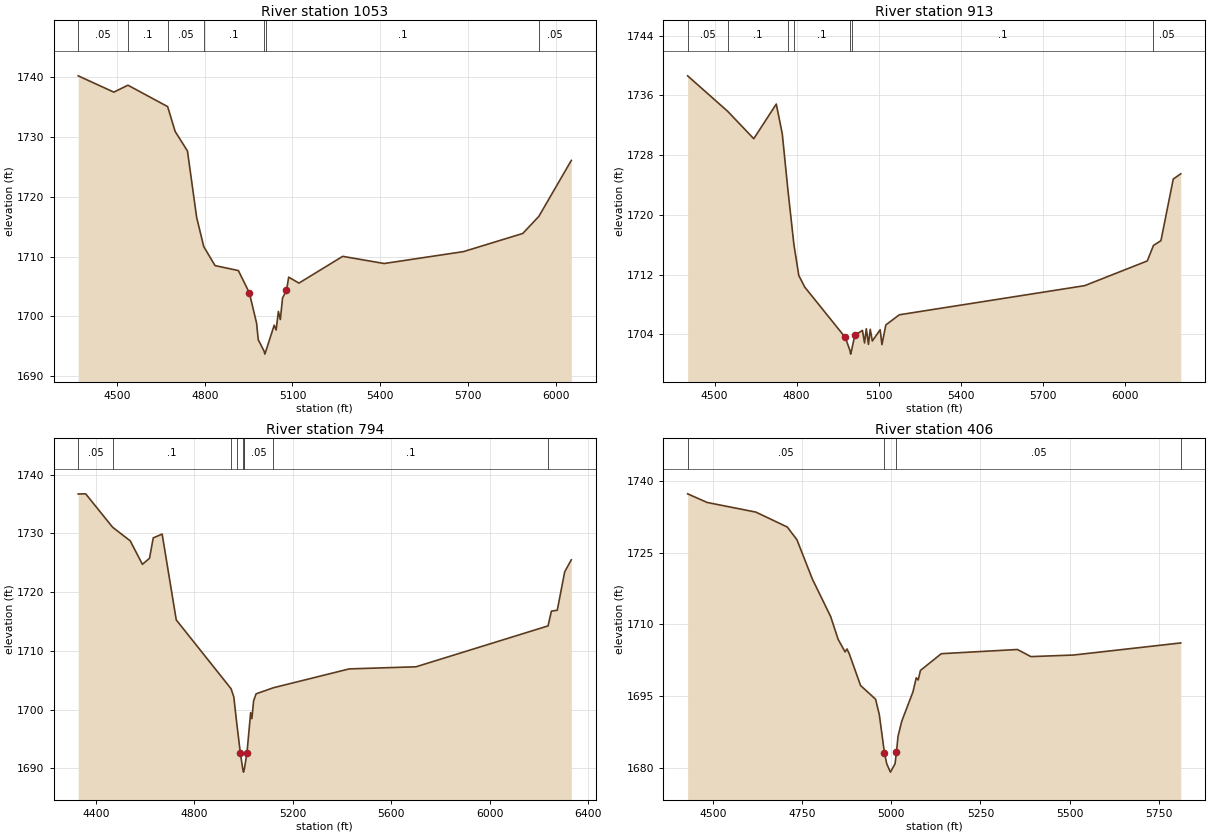
Type RM Length L Ch R = 1 ,1053    ,140,140,140
BEGIN DESCRIPTION:
UNT 0041 IN HEWA 2.0
END DESCRIPTION:
XS GIS Cut Line= 5
      2739754.67     10066223.51      2739186.94     10066044.68
      2739129.65     10066018.64      2738798.05     10066298.16
      2738680.28     10066880.11
#Sta/Elev= 30
  4367.6 1740.27  4489.4 1737.54  4537.6  1738.7  4673.3 1735.12  4699.1 1730.95
  4741.1 1727.69  4772.5 1716.57  4796.8 1711.68  4835.4  1708.5  4915.1 1707.67
  4952.7 1703.94  4977.4 1698.85  4983.1 1696.09    5003 1694.18  5005.7 1693.68
    5009 1694.18  5037.6 1698.53  5044.2 1697.72  5051.9 1700.83  5058.5 1699.47
  5066.2 1703.09  5079.6 1704.35  5087.1 1706.57  5122.2 1705.57  5271.7 1710.05
  5413.5 1708.85  5684.4 1710.84  5887.2 1713.88  5942.2 1716.74  6053.2 1726.11
#Mann= 7 ,-1 , 0
  4367.6     .05       0  4537.6      .1       0  4673.3     .05       0
  4796.8      .1       0    5003     .07       0    5009      .1       0
  5942.2     .05       0
Bank Sta=4952.7,5079.6
XS Rating Curve= 0 ,0
Exp/Cntr=0.3,0.1

Type RM Length L Ch R = 1 ,913     ,119,119,119
BEGIN DESCRIPTION:
Mapping XS aaa94f8a
END DESCRIPTION:
XS GIS Cut Line= 5
      2739761.56     10066169.67      2739275.48     10065912.74
      2739195.62     10065916.21      2738761.59       10066286.
      2738638.34     10066877.97
#Sta/Elev= 30
  4401.2 1738.62  4547.7 1733.87  4643.2  1730.2  4725.6 1734.84  4747.6 1730.85
  4767.5 1723.58    4790 1716.06    4808 1711.88    4830 1710.32    4978 1703.59
  4995.1 1701.85  4997.8 1701.35  5001.1 1701.85 5012.78 1703.85  5040.9 1704.53
  5048.6 1702.85  5055.1 1704.75  5062.9 1702.66  5069.4 1704.67  5077.1 1703.11
  5105.7 1704.61  5112.3 1702.63  5126.5 1705.26  5175.9 1706.62  5854.2 1710.52
  6083.3 1713.83  6105.9  1715.9  6133.3 1716.55  6178.3 1724.79  6205.8  1725.5
#Mann= 7 ,-1 , 0
  4401.2     .05       0  4547.7      .1       0  4767.5     .05       0
    4790      .1       0  4995.1     .07       0  5001.1      .1       0
  6105.9     .05       0
Bank Sta=4978,5012.78
XS Rating Curve= 0 ,0
Exp/Cntr=0.3,0.1

Type RM Length L Ch R = 1 ,794     ,388,388,388
BEGIN DESCRIPTION:
Mapping XS 1a4ba489
END DESCRIPTION:
XS GIS Cut Line= 5
      2739766.77     10066136.68      2739240.76     10065792.95
      2739022.01     10065839.82      2738711.25     10066259.96
      2738610.77     10066880.12
#Sta/Elev= 30
  4328.7 1736.69    4359 1736.72  4468.4 1731.04    4540 1728.72  4589.5 1724.72
  4618.4 1725.75  4633.5 1729.22  4669.7 1729.87    4727 1715.26  4949.7 1703.54
  4960.8 1702.15  4971.9 1697.96 4987.22 1692.62  4997.3 1689.85  5000.1 1689.35
  5003.3 1689.85  5003.6 1689.89  5014.2 1692.62  5029.1 1699.47  5034.2 1698.45
  5041.2 1701.49  5051.4 1702.68  5121.4 1703.71  5429.4 1706.92  5700.7 1707.28
  6237.1 1714.24  6250.7 1716.75  6274.5 1716.91  6304.9 1723.47  6331.6 1725.49
#Mann= 9 ,-1 , 0
  4328.7     .05       0  4468.4      .1       0  4949.7     .05       0
  4971.9      .1       0  4997.3     .07       0  5003.3      .1       0
  5003.6     .05       0  5121.4      .1       0  6237.1     .05       0
Bank Sta=4987.22,5014.2
XS Rating Curve= 0 ,0
Exp/Cntr=0.3,0.1

Type RM Length L Ch R = 1 ,406     ,0,0,0
BEGIN DESCRIPTION:
UNT 0041 IN HEWA 1.0
END DESCRIPTION:
XS GIS Cut Line= 3
      2739880.76      10065622.3       2739186.5     10065403.82
      2738870.97     10065976.64
#Sta/Elev= 30
  4429.5  1737.3  4484.3 1735.49  4620.6 1733.48  4708.8 1730.35  4735.9 1727.68
  4778.8  1719.5  4830.3 1711.62  4851.2 1706.86  4870.7 1704.23    4876 1704.84
  4882.7 1703.78  4914.1 1697.19  4956.1 1694.33  4966.6 1691.12 4980.91 1683.14
  4987.5  1680.8  4997.8 1679.07  5010.7 1680.82 5014.55 1683.23    5019 1686.53
  5029.5 1689.73  5060.9 1695.86  5070.2 1698.81  5075.5 1698.35  5081.9 1700.35
  5140.3 1703.85  5353.6 1704.73  5391.4 1703.24  5510.7 1703.57  5811.3  1706.1
#Mann= 4 ,-1 , 0
  4429.5     .05       0 4980.91    .035       0 5014.55     .05       0
  5811.3      .1       0
Bank Sta=4980.91,5014.55
XS Rating Curve= 0 ,0
Exp/Cntr=0.3,0.1

Chan Stop Cuts=-1
Use User Specified Reach Order=0
Composite Channel Slope=5