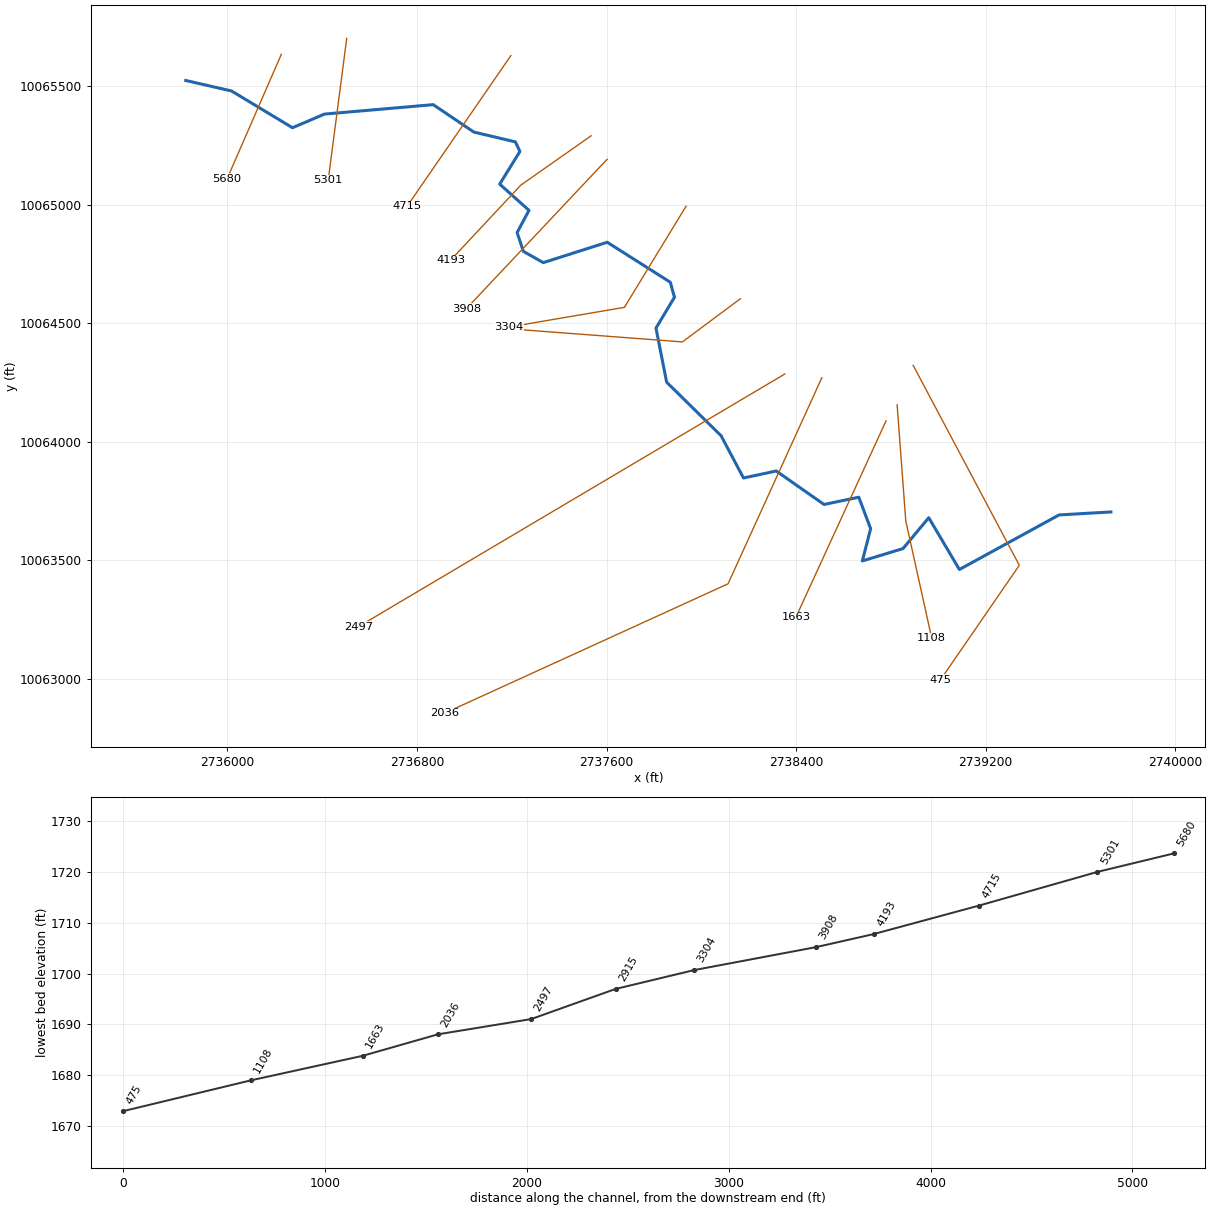
--- UNT 0042 IN HEWA.prj (project) ---

Proj Title=UNT 0042 IN HEWA Base Level Engineering
Current Plan=p01
Default Exp/Contr=0.3,0.1
English Units
Geom File=g01
Flow File=f01
Plan File=p01
BEGIN DESCRIPTION:
UNT 0042 IN HEWA
END DESCRIPTION:

--- UNT 0042 IN HEWA.p01 (plan) ---

Plan Title=Multiple Run
Short Identifier=Multiple
Geom File=g01
Flow File=f01
Subcritical Flow
K Sum by GR= 0
Std Step Tol= 0.01
Critical Tol= 0.01
Num of Std Step Trials= 20
Max Error Tol= 0.3
Flow Tol Ratio= 0.001
Split Flow NTrial= 30
Split Flow Tol= 0.02
Split Flow Ratio= 0.02
Log Output Level= 0
Friction Slope Method= 1
Unsteady Friction Slope Method= 2
Unsteady Bridges Friction Slope Method= 1
Parabolic Critical Depth
Global Vel Dist=  1 , 1 , 1
Global Log Level= 0
CheckData=True
Encroach Param= -1, 0, 0, 0
BEGIN DESCRIPTION:
Multiple Run
END DESCRIPTION:

--- UNT 0042 IN HEWA.f01 (steady flow) ---

Flow Title=Multiple
Number of Profiles=7
Profile Names=10-year,25-year,50-year,1pct_min,100-year,1pct_plu,500-year
River Rch & RM= UNT 0042 IN HEWA,Reach-1,5680
     709    1026    1300    1207    1632    2207    2583
Boundary for River Rch & Prof#=UNT 0042 IN HEWA,Reach-1,1
Up Type=0
Dn Type=3
Dn Slope=0.005
Boundary for River Rch & Prof#=UNT 0042 IN HEWA,Reach-1,2
Up Type=0
Dn Type=3
Dn Slope=0.005
Boundary for River Rch & Prof#=UNT 0042 IN HEWA,Reach-1,3
Up Type=0
Dn Type=3
Dn Slope=0.005
Boundary for River Rch & Prof#=UNT 0042 IN HEWA,Reach-1,4
Up Type=0
Dn Type=3
Dn Slope=0.005
Boundary for River Rch & Prof#=UNT 0042 IN HEWA,Reach-1,5
Up Type=0
Dn Type=3
Dn Slope=0.005
Boundary for River Rch & Prof#=UNT 0042 IN HEWA,Reach-1,6
Up Type=0
Dn Type=3
Dn Slope=0.005
Boundary for River Rch & Prof#=UNT 0042 IN HEWA,Reach-1,7
Up Type=0
Dn Type=3
Dn Slope=0.005

--- UNT 0042 IN HEWA.g01 (geometry) ---

Geom Title=Existing Conditions

River Reach=UNT 0042 IN HEWA,Reach-1
Reach XY= 30
      2735824.01     10065524.67      2736017.11     10065480.45
      2736274.31     10065325.31      2736409.02     10065382.82
      2736868.24     10065422.71      2737039.82     10065307.01
      2737215.07     10065265.62      2737234.18     10065225.12
      2737148.84     10065087.25      2737272.52     10064976.60
      2737222.40     10064882.94      2737248.63     10064803.60
      2737332.82     10064756.02      2737602.58     10064841.96
      2737868.85     10064673.27      2737886.54     10064609.93
      2737808.42     10064479.60      2737853.49     10064251.30
      2738083.15     10064025.35      2738177.74     10063847.12
      2738315.90     10063876.61      2738517.77     10063735.26
      2738664.32     10063765.99      2738714.35     10063633.07
      2738679.39     10063497.00      2738851.02     10063549.20
      2738959.56     10063679.49      2739088.98     10063460.94
      2739509.53     10063691.17      2739728.47     10063703.73

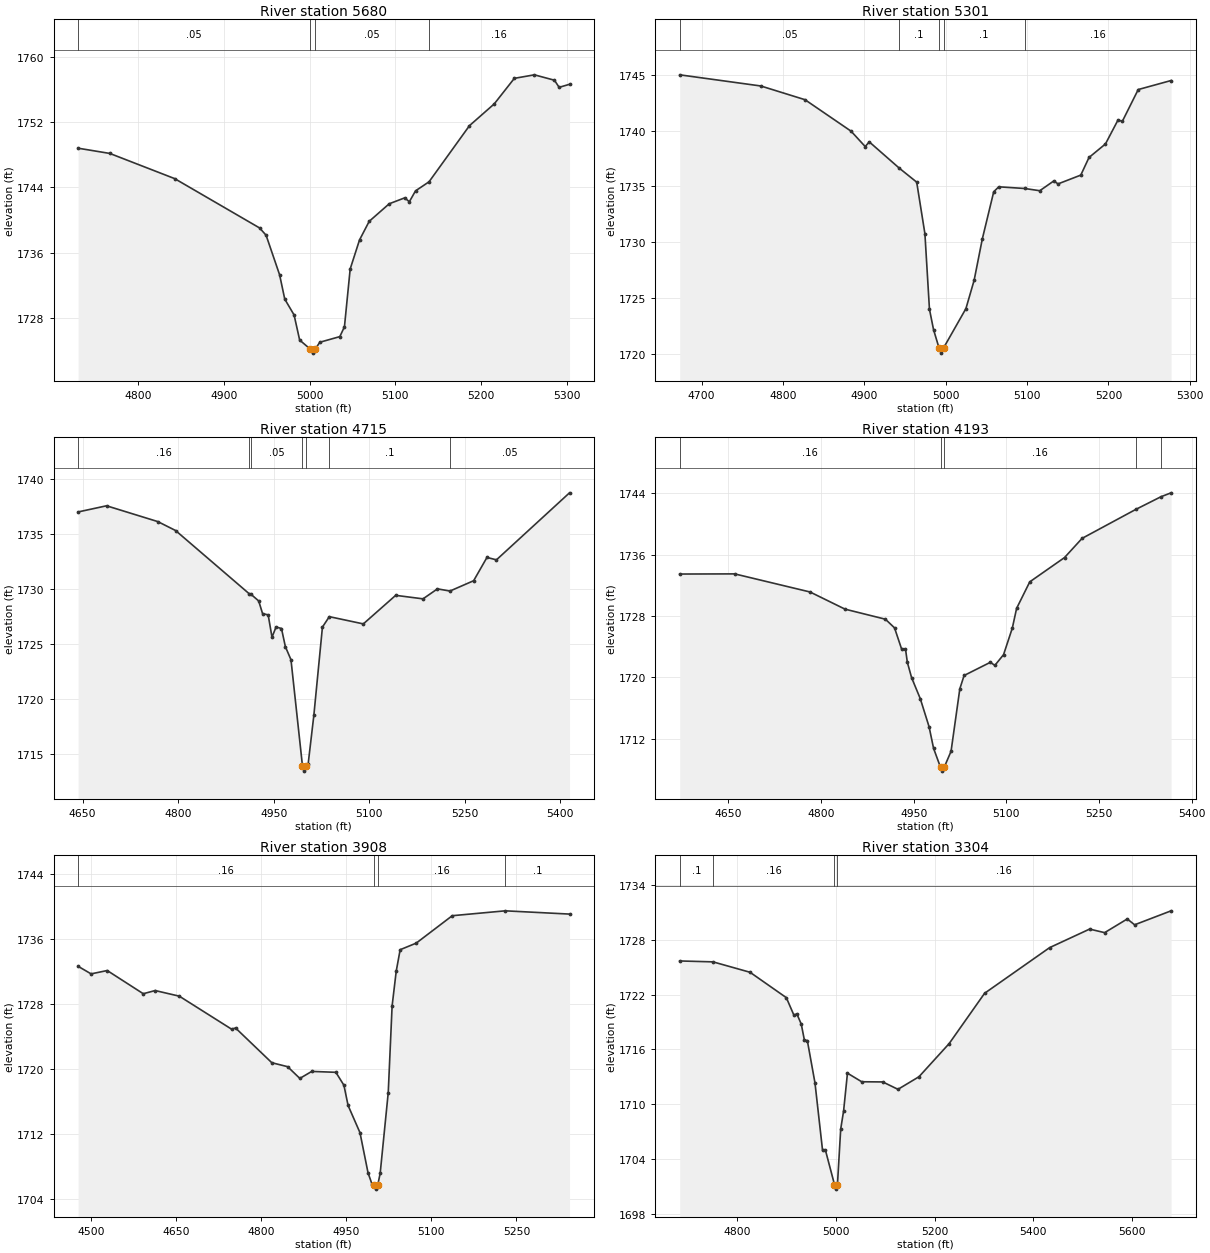
Type RM Length L Ch R = 1,5680,379,379,379
BEGIN DESCRIPTION:
UNT 0042 IN HEWA 12.0
END DESCRIPTION:
XS GIS Cut Line= 2
      2736227.22     10065634.96      2735998.05     10065108.91
#Sta/Elev= 30
  4729.6 1748.78  4766.6 1748.14  4842.3 1745.06  4941.5 1739.02  4949.1 1738.13
  4964.9 1733.28  4970.9 1730.31  4981.8 1728.37  4988.3 1725.30  5000.6 1724.20
  5003.4 1723.70  5006.6 1724.20  5011.8 1725.03  5035.2 1725.72  5040.6 1726.92
  5047.3 1734.00  5058.2 1737.55  5069.5 1739.83  5092.9 1741.98  5110.9 1742.70
  5116.4 1742.23  5123.6 1743.56  5139.4 1744.67  5186.6 1751.54  5215.5 1754.20
  5239.0 1757.33  5262.4 1757.76  5285.8 1757.10  5291.3 1756.23  5303.4 1756.60
#Mann=4,-1,0
  4729.6    0.05       0  5000.6    0.04       0  5006.6    0.05       0
  5139.4    0.16       0
Bank Sta=5000.6,5006.6
Exp/Cntr=0.3,0.1

Type RM Length L Ch R = 1,5301,586,586,586
BEGIN DESCRIPTION:
UNT 0042 IN HEWA 11.0
END DESCRIPTION:
XS GIS Cut Line= 2
      2736503.24     10065702.59      2736425.12     10065103.66
#Sta/Elev= 30
  4673.0 1745.00  4772.7 1744.00  4827.0 1742.77  4883.6 1739.95  4901.0 1738.57
  4906.0 1738.99  4943.1 1736.62  4964.3 1735.38  4974.4 1730.76  4980.0 1723.98
  4985.0 1722.16  4991.6 1720.55  4994.3 1720.05  4997.6 1720.55  5024.8 1724.04
  5034.9 1726.58  5045.0 1730.30  5059.0 1734.52  5065.2 1734.96  5097.0 1734.81
  5115.6 1734.61  5132.9 1735.49  5138.0 1735.22  5166.0 1736.01  5176.1 1737.59
  5196.3 1738.80  5211.9 1740.97  5217.0 1740.82  5236.6 1743.68  5277.0 1744.49
#Mann=5,-1,0
  4673.0    0.05       0  4943.1     0.1       0  4991.6    0.07       0
  4997.6     0.1       0  5097.0    0.16       0
Bank Sta=4991.6,4997.6
Exp/Cntr=0.3,0.1

Type RM Length L Ch R = 1,4715,522,522,522
BEGIN DESCRIPTION:
UNT 0042 IN HEWA 10.0
END DESCRIPTION:
XS GIS Cut Line= 2
      2737195.96     10065629.71      2736758.44     10064994.27
#Sta/Elev= 30
  4643.0 1737.00  4687.7 1737.56  4768.2 1736.12  4796.0 1735.31  4911.3 1729.57
  4914.3 1729.51  4926.5 1728.90  4932.6 1727.75  4941.4 1727.63  4947.4 1725.60
  4953.8 1726.53  4962.3 1726.39  4968.4 1724.74  4977.2 1723.55  4995.2 1713.91
  4997.9 1713.41  5001.2 1713.91  5004.2 1714.07  5013.1 1718.48  5026.6 1726.52
  5037.4 1727.47  5090.8 1726.81  5141.6 1729.41  5184.5 1729.09  5207.2 1730.00
  5226.8 1729.80  5264.0 1730.74  5284.9 1732.86  5299.8 1732.64  5414.5 1738.74
#Mann=7,-1,0
  4643.0    0.16       0  4911.3     0.1       0  4914.3    0.05       0
  4995.2   0.035       0  5001.2    0.05       0  5037.4     0.1       0
  5226.8    0.05       0
Bank Sta=4995.2,5001.2
Exp/Cntr=0.3,0.1

Type RM Length L Ch R = 1,4193,285,285,285
BEGIN DESCRIPTION:
UNT 0042 IN HEWA 9.0
END DESCRIPTION:
XS GIS Cut Line= 3
      2737534.48     10065291.15      2737237.62     10065082.83
      2736942.10     10064766.57
#Sta/Elev= 30
  4571.2 1733.49  4660.2 1733.51  4782.2 1731.15  4838.9 1728.91  4904.2 1727.60
  4919.0 1726.47  4930.3 1723.74  4936.7 1723.74  4939.7 1721.99  4946.6 1719.98
  4960.7 1717.23  4974.9 1713.58  4982.2 1710.76  4993.4 1708.29  4996.1 1707.79
  4999.4 1708.29  5010.5 1710.38  5024.7 1718.53  5031.6 1720.26  5074.1 1721.98
  5081.4 1721.58  5095.5 1722.98  5109.7 1726.45  5116.6 1729.01  5137.9 1732.47
  5194.2 1735.64  5222.6 1738.14  5309.4 1741.91  5350.3 1743.57  5366.7 1744.08
#Mann=5,-1,0
  4571.2    0.16       0  4993.4    0.07       0  4999.4    0.16       0
  5309.4     0.1       0  5350.3    0.05       0
Bank Sta=4993.4,4999.4
Exp/Cntr=0.3,0.1

Type RM Length L Ch R = 1,3908,604,604,604
BEGIN DESCRIPTION:
UNT 0042 IN HEWA 8.0
END DESCRIPTION:
XS GIS Cut Line= 2
      2737602.21     10065192.22      2737008.43     10064561.97
#Sta/Elev= 30
  4477.5 1732.61  4500.4 1731.68  4528.8 1732.09  4592.3 1729.24  4613.3 1729.63
  4655.8 1728.94  4748.0 1724.88  4754.9 1725.03  4818.8 1720.76  4846.7 1720.27
  4868.2 1718.83  4889.2 1719.69  4931.7 1719.58  4945.9 1717.99  4953.2 1715.51
  4974.2 1712.16  4988.4 1707.22  4995.6 1705.79  4999.5 1705.72  5002.3 1705.22
  5005.5 1705.72  5009.8 1707.17  5024.0 1717.09  5030.8 1727.73  5038.1 1732.03
  5045.0 1734.65  5073.3 1735.46  5136.8 1738.83  5230.1 1739.43  5343.4 1739.03
#Mann=4,-1,0
  4477.5    0.16       0  4999.5    0.07       0  5005.5    0.16       0
  5230.1     0.1       0
Bank Sta=4999.5,5005.5
Exp/Cntr=0.3,0.1

Type RM Length L Ch R = 1,3304,389,389,389
BEGIN DESCRIPTION:
UNT 0042 IN HEWA 7.0
END DESCRIPTION:
XS GIS Cut Line= 3
      2737935.52     10064994.27      2737675.12     10064567.21
      2737185.55     10064483.88
#Sta/Elev= 30
  4682.9 1725.68  4750.5 1725.58  4825.6 1724.44  4899.2 1721.66  4914.6 1719.74
  4920.5 1719.89  4929.5 1718.76  4935.9 1717.00  4941.8 1716.96  4957.3 1712.33
  4972.7 1704.93  4978.6 1704.94  4996.9 1701.19  4999.6 1700.69  5002.9 1701.19
  5009.5 1707.27  5015.4 1709.26  5023.2 1713.39  5052.1 1712.45  5094.8 1712.43
  5125.7 1711.62  5168.3 1713.00  5229.5 1716.63  5301.4 1722.14  5433.3 1727.14
  5514.4 1729.17  5544.9 1728.78  5590.8 1730.28  5605.7 1729.64  5679.7 1731.17
#Mann=4,-1,0
  4682.9     0.1       0  4750.5    0.16       0  4996.9    0.07       0
  5002.9    0.16       0
Bank Sta=4996.9,5002.9
Exp/Cntr=0.3,0.1

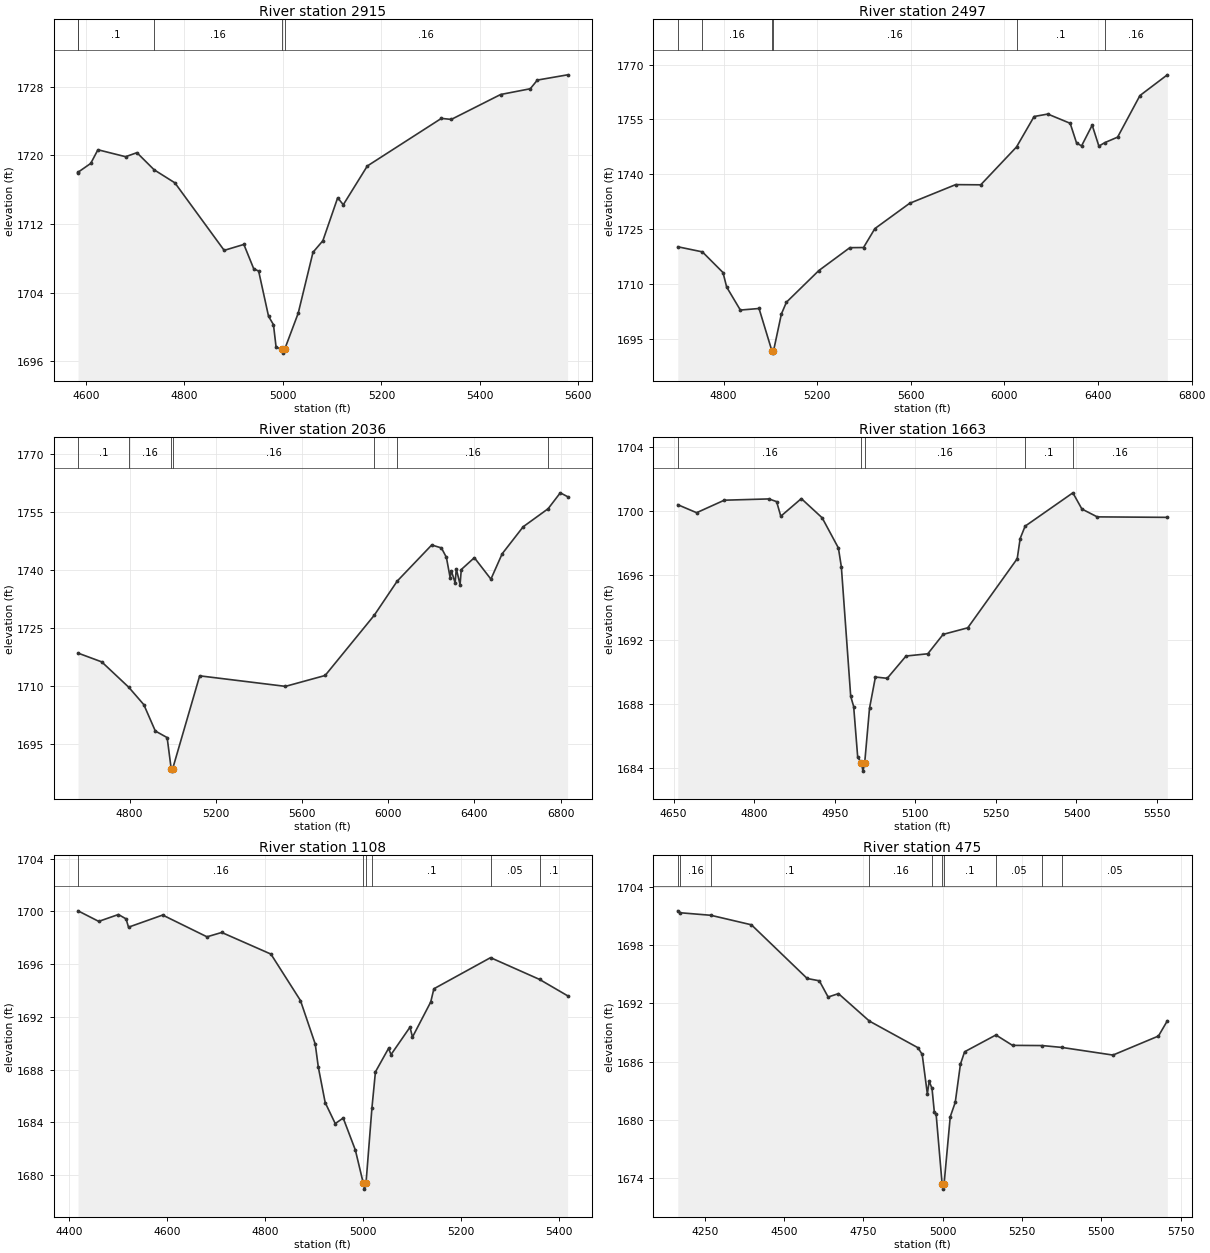
Type RM Length L Ch R = 1,2915,418,418,418
BEGIN DESCRIPTION:
UNT 0042 IN HEWA 6.0
END DESCRIPTION:
XS GIS Cut Line= 3
      2738164.71     10064603.67      2737919.91     10064421.37
      2737232.90     10064473.42
#Sta/Elev= 30
  4583.8 1717.99  4584.3 1718.04  4609.6 1719.05  4624.2 1720.64  4680.4 1719.83
  4703.4 1720.30  4738.3 1718.31  4780.5 1716.79  4880.6 1708.93  4920.6 1709.62
  4940.6 1706.79  4950.6 1706.52  4970.7 1701.26  4980.7 1700.28  4986.1 1697.63
  4997.8 1697.47  5000.5 1696.97  5003.8 1697.47  5030.9 1701.61  5061.0 1708.71
  5081.0 1710.05  5111.1 1715.05  5122.5 1714.24  5171.3 1718.75  5321.7 1724.29
  5341.8 1724.17  5442.0 1727.07  5502.2 1727.74  5516.6 1728.75  5578.0 1729.36
#Mann=5,-1,0
  4583.8    0.05       0  4584.3     0.1       0  4738.3    0.16       0
  4997.8    0.07       0  5003.8    0.16       0
Bank Sta=4997.8,5003.8
Exp/Cntr=0.3,0.1

Type RM Length L Ch R = 1,2497,461,461,461
BEGIN DESCRIPTION:
UNT 0042 IN HEWA 5.0
END DESCRIPTION:
XS GIS Cut Line= 2
      2738352.16     10064285.93      2736552.18     10063219.46
#Sta/Elev= 30
  4603.8 1720.15  4709.0 1718.75  4797.2 1713.09  4812.8 1709.12  4871.3 1702.82
  4951.2 1703.25  5006.7 1691.53  5009.4 1691.03  5012.7 1691.53  5046.7 1701.75
  5068.2 1704.97  5206.6 1713.63  5339.2 1719.90  5397.7 1719.94  5446.3 1725.13
  5594.6 1732.04  5791.4 1737.16  5898.6 1737.11  6051.5 1747.47  6126.7 1755.81
  6185.2 1756.48  6280.8 1753.95  6308.0 1748.58  6329.4 1747.76  6374.9 1753.44
  6403.5 1747.70  6429.2 1748.67  6483.5 1750.16  6579.0 1761.55  6696.0 1767.22
#Mann=6,-1,0
  4603.8     0.1       0  4709.0    0.16       0  5006.7    0.07       0
  5012.7    0.16       0  6051.5     0.1       0  6429.2    0.16       0
Bank Sta=5006.7,5012.7
Exp/Cntr=0.3,0.1

Type RM Length L Ch R = 1,2036,373,373,373
BEGIN DESCRIPTION:
UNT 0042 IN HEWA 4.0
END DESCRIPTION:
XS GIS Cut Line= 3
      2738508.44     10064270.29      2738112.62     10063400.54
      2736914.73     10062853.68
#Sta/Elev= 30
  4560.3 1718.51  4670.4 1716.24  4795.8 1709.69  4865.8 1705.19  4919.1 1698.39
  4974.0 1696.69  4993.0 1688.53  4995.7 1688.03  4999.0 1688.53  5125.0 1712.64
  5523.1 1709.92  5707.3 1712.73  5935.4 1728.29  6041.8 1737.10  6202.0 1746.43
  6247.0 1745.67  6270.1 1743.24  6287.6 1737.97  6293.1 1739.76  6310.6 1736.67
  6316.1 1740.29  6333.7 1736.20  6339.2 1740.09  6399.9 1743.15  6476.8 1737.61
  6528.9 1744.15  6626.6 1751.14  6742.2 1755.79  6798.8 1759.90  6832.7 1758.91
#Mann=7,-1,0
  4560.3     0.1       0  4795.8    0.16       0  4993.0    0.07       0
  4999.0    0.16       0  5935.4     0.1       0  6041.8    0.16       0
  6742.2     0.1       0
Bank Sta=4993,4999
Exp/Cntr=0.3,0.1

Type RM Length L Ch R = 1,1663,555,555,555
BEGIN DESCRIPTION:
UNT 0042 IN HEWA 3.0
END DESCRIPTION:
XS GIS Cut Line= 2
      2738779.29     10064088.05      2738399.10     10063259.95
#Sta/Elev= 30
  4657.9 1700.41  4693.0 1699.91  4744.5 1700.69  4827.7 1700.77  4841.9 1700.60
  4849.7 1699.69  4887.9 1700.79  4926.7 1699.59  4956.9 1697.71  4962.4 1696.53
  4979.8 1688.46  4985.3 1687.82  4992.8 1684.67  4999.8 1684.29  5002.6 1683.79
  5005.8 1684.29  5014.8 1687.71  5025.8 1689.66  5047.8 1689.58  5082.8 1690.97
  5123.3 1691.11  5151.8 1692.32  5197.7 1692.73  5289.7 1697.04  5295.2 1698.30
  5304.4 1699.07  5393.3 1701.15  5410.1 1700.14  5438.6 1699.65  5569.1 1699.62
#Mann=5,-1,0
  4657.9    0.16       0  4999.8    0.07       0  5005.8    0.16       0
  5304.4     0.1       0  5393.3    0.16       0
Bank Sta=4999.8,5005.8
Exp/Cntr=0.3,0.1

Type RM Length L Ch R = 1,1108,633,633,633
BEGIN DESCRIPTION:
UNT 0042 IN HEWA 2.0
END DESCRIPTION:
XS GIS Cut Line= 3
      2738826.16     10064155.79      2738862.62     10063666.16
      2738971.99     10063171.39
#Sta/Elev= 30
  4419.0 1700.04  4461.2 1699.24  4501.3 1699.76  4516.9 1699.43  4521.9 1698.80
  4591.5 1699.72  4681.8 1698.07  4711.9 1698.40  4812.1 1696.76  4872.3 1693.24
  4902.4 1689.94  4908.7 1688.19  4922.7 1685.50  4943.2 1683.91  4959.4 1684.33
  4984.2 1681.90  5000.0 1679.44  5002.8 1678.94  5006.0 1679.44  5018.0 1685.11
  5025.1 1687.83  5051.8 1689.61  5056.9 1689.14  5095.5 1691.22  5100.6 1690.47
  5137.8 1693.13  5144.2 1694.13  5259.7 1696.49  5359.5 1694.84  5416.7 1693.60
#Mann=6,-1,0
  4419.0    0.16       0  5000.0    0.07       0  5006.0    0.16       0
  5018.0     0.1       0  5259.7    0.05       0  5359.5     0.1       0
Bank Sta=5000,5006
Exp/Cntr=0.3,0.1

Type RM Length L Ch R = 1,475,0,0,0
BEGIN DESCRIPTION:
UNT 0042 IN HEWA 1.0
END DESCRIPTION:
XS GIS Cut Line= 3
      2738893.88     10064322.40      2739341.79     10063478.66
      2739008.48     10062994.33
#Sta/Elev= 30
  4164.8 1701.53  4173.1 1701.33  4269.3 1701.07  4397.0 1700.09  4572.8 1694.56
  4611.1 1694.32  4638.8 1692.65  4671.4 1693.00  4768.9 1690.17  4921.8 1687.43
  4935.3 1686.74  4951.6 1682.66  4957.2 1683.98  4966.3 1683.23  4973.6 1680.79
  4979.2 1680.59  4998.2 1673.36  5001.0 1672.86  5004.2 1673.36  5023.7 1680.31
  5039.5 1681.80  5055.9 1685.74  5069.0 1687.01  5167.7 1688.74  5220.0 1687.67
  5313.3 1687.65  5375.1 1687.46  5536.6 1686.67  5680.0 1688.63  5708.0 1690.20
#Mann=10,-1,0
  4164.8     0.1       0  4173.1    0.16       0  4269.3     0.1       0
  4768.9    0.16       0  4966.3     0.1       0  4998.2    0.07       0
  5004.2     0.1       0  5167.7    0.05       0  5313.3    0.16       0
  5375.1    0.05       0
Bank Sta=4998.2,5004.2
Exp/Cntr=0.3,0.1

Chan Stop Cuts=-1