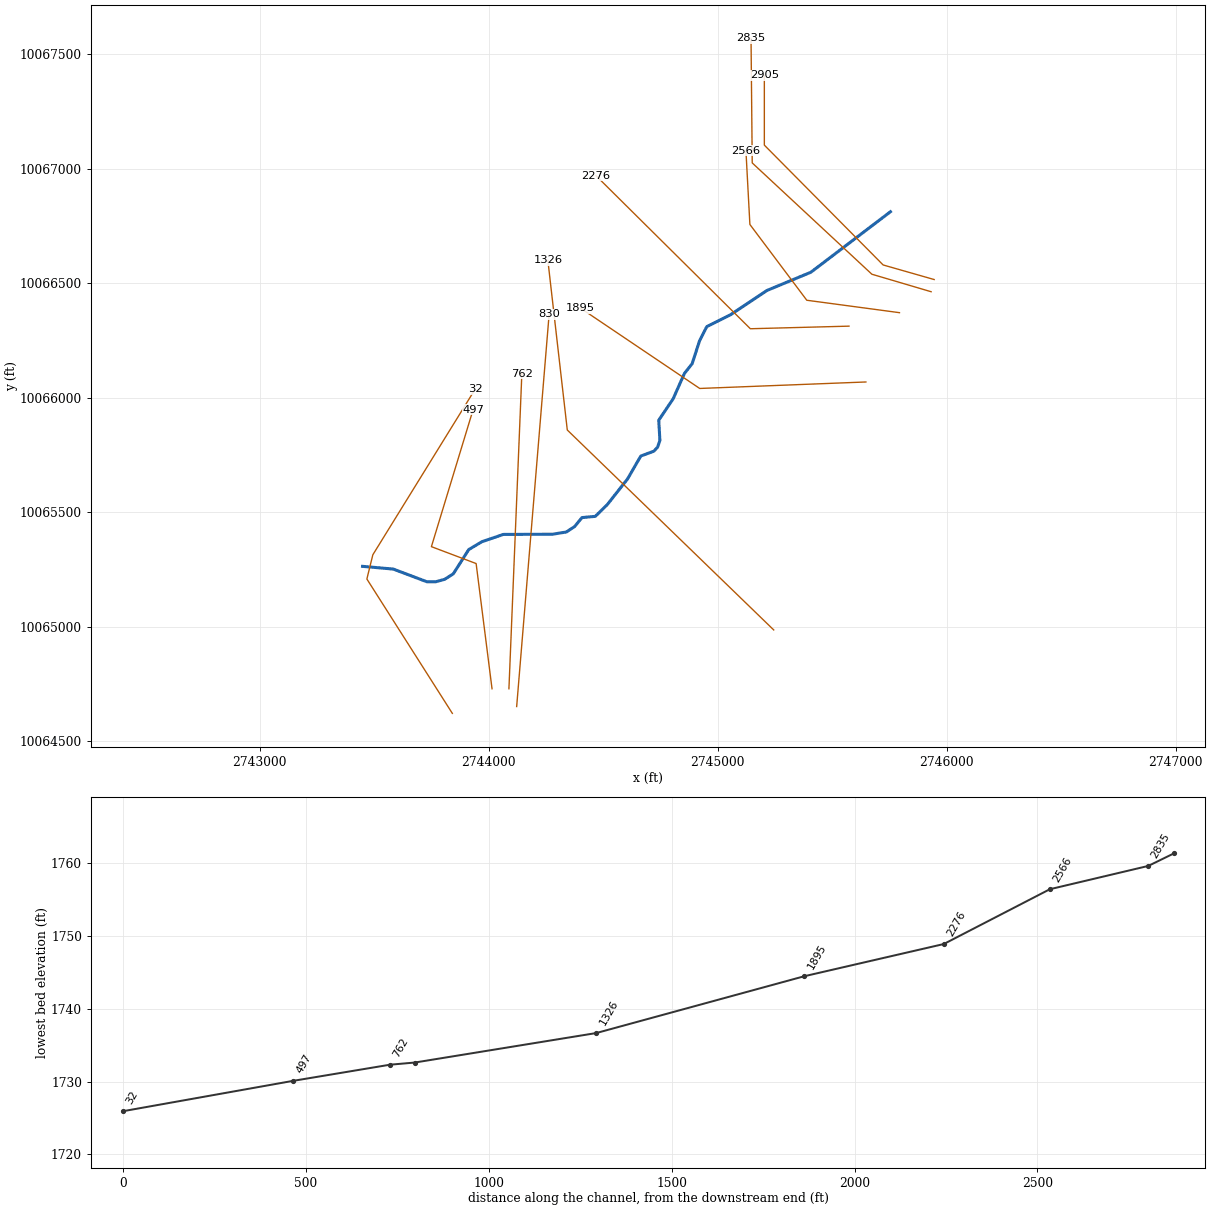
--- UNT 0043 IN HEWA.prj (project) ---

Proj Title=UNT 0043 IN HEWA Base Level Engineering
Current Plan=p01
Default Exp/Contr=0.3,0.1
English Units
Geom File=g01
Flow File=f01
Plan File=p01
Y Axis Title=Elevation
X Axis Title(PF)=Main Channel Distance
X Axis Title(XS)=Station
BEGIN DESCRIPTION:
UNT 0043 IN HEWA
END DESCRIPTION:
DSS Export Rating Curves= 0
DSS Export Rating Curve Sorted= 0
DSS Export Volume Flow Curves= 0
DXF OffsetX= 0
DXF OffsetY= 0
DXF ScaleX= 1
DXF ScaleY= 10

--- UNT 0043 IN HEWA.p01 (plan) ---

Plan Title=Multiple Run
Short Identifier=Multiple
Geom File=g01
Flow File=f01
Subcritical Flow
K Sum by GR= 0
Std Step Tol= 0.01
Critical Tol= 0.01
Num of Std Step Trials= 20
Max Error Tol= 0.3
Flow Tol Ratio= 0.001
Split Flow NTrial= 30
Split Flow Tol= 0.02
Split Flow Ratio= 0.02
Log Output Level= 0
Friction Slope Method= 1
Unsteady Friction Slope Method= 2
Unsteady Bridges Friction Slope Method= 1
Parabolic Critical Depth
Global Vel Dist=  1 , 1 , 1
Global Log Level= 0
CheckData=True
Encroach Param= -1, 0, 0, 0
BEGIN DESCRIPTION:
Multiple Run
END DESCRIPTION:

--- UNT 0043 IN HEWA.f01 (steady flow) ---

Flow Title=Multiple
Program Version=4.10
Number of Profiles= 7
Profile Names=10-year,25-year,50-year,1pct_min,100-year,1pct_plu,500-year
River Rch & RM=UNT 0043 IN HEWA,Reach-1         ,2905
     507     720     901     828    1120    1514    1734
Boundary for River Rch & Prof#=UNT 0043 IN HEWA,Reach-1         , 1
Up Type= 0
Dn Type= 3
Dn Slope=0.0089
Boundary for River Rch & Prof#=UNT 0043 IN HEWA,Reach-1         , 2
Up Type= 0
Dn Type= 3
Dn Slope=0.0089
Boundary for River Rch & Prof#=UNT 0043 IN HEWA,Reach-1         , 3
Up Type= 0
Dn Type= 3
Dn Slope=0.0089
Boundary for River Rch & Prof#=UNT 0043 IN HEWA,Reach-1         , 4
Up Type= 0
Dn Type= 3
Dn Slope=0.0089
Boundary for River Rch & Prof#=UNT 0043 IN HEWA,Reach-1         , 5
Up Type= 0
Dn Type= 3
Dn Slope=0.0089
Boundary for River Rch & Prof#=UNT 0043 IN HEWA,Reach-1         , 6
Up Type= 0
Dn Type= 3
Dn Slope=0.0089
Boundary for River Rch & Prof#=UNT 0043 IN HEWA,Reach-1         , 7
Up Type= 0
Dn Type= 3
Dn Slope=0.0089
DSS Import GetInterval= 0
DSS Import GetPeak= 0
DSS Import FillOption= 0

--- UNT 0043 IN HEWA.g01 (geometry) ---

Geom Title=Existing Conditions
Program Version=4.10

River Reach=UNT 0043 IN HEWA,Reach-1
Reach XY= 30
      2745754.03     10066812.43      2745406.37      10066548.1
      2745214.97     10066468.68       2745056.3     10066362.93
      2744951.89     10066310.49      2744920.36     10066249.03
      2744888.05     10066148.91      2744854.25     10066106.05
      2744804.86     10065995.23      2744742.12     10065902.11
      2744747.13     10065813.68      2744737.07     10065784.41
      2744721.06     10065766.81      2744663.78     10065745.51
      2744605.82     10065645.45       2744517.4     10065533.34
      2744464.86     10065481.97      2744406.82     10065476.69
      2744374.82     10065437.65      2744338.47     10065413.73
      2744278.75       10065404.      2744063.42     10065403.14
      2743969.47     10065371.15       2743912.2     10065336.91
      2743844.92     10065231.11       2743807.1     10065206.99
      2743767.28     10065196.13      2743729.73     10065196.31
      2743582.68     10065251.84      2743448.47     10065263.73

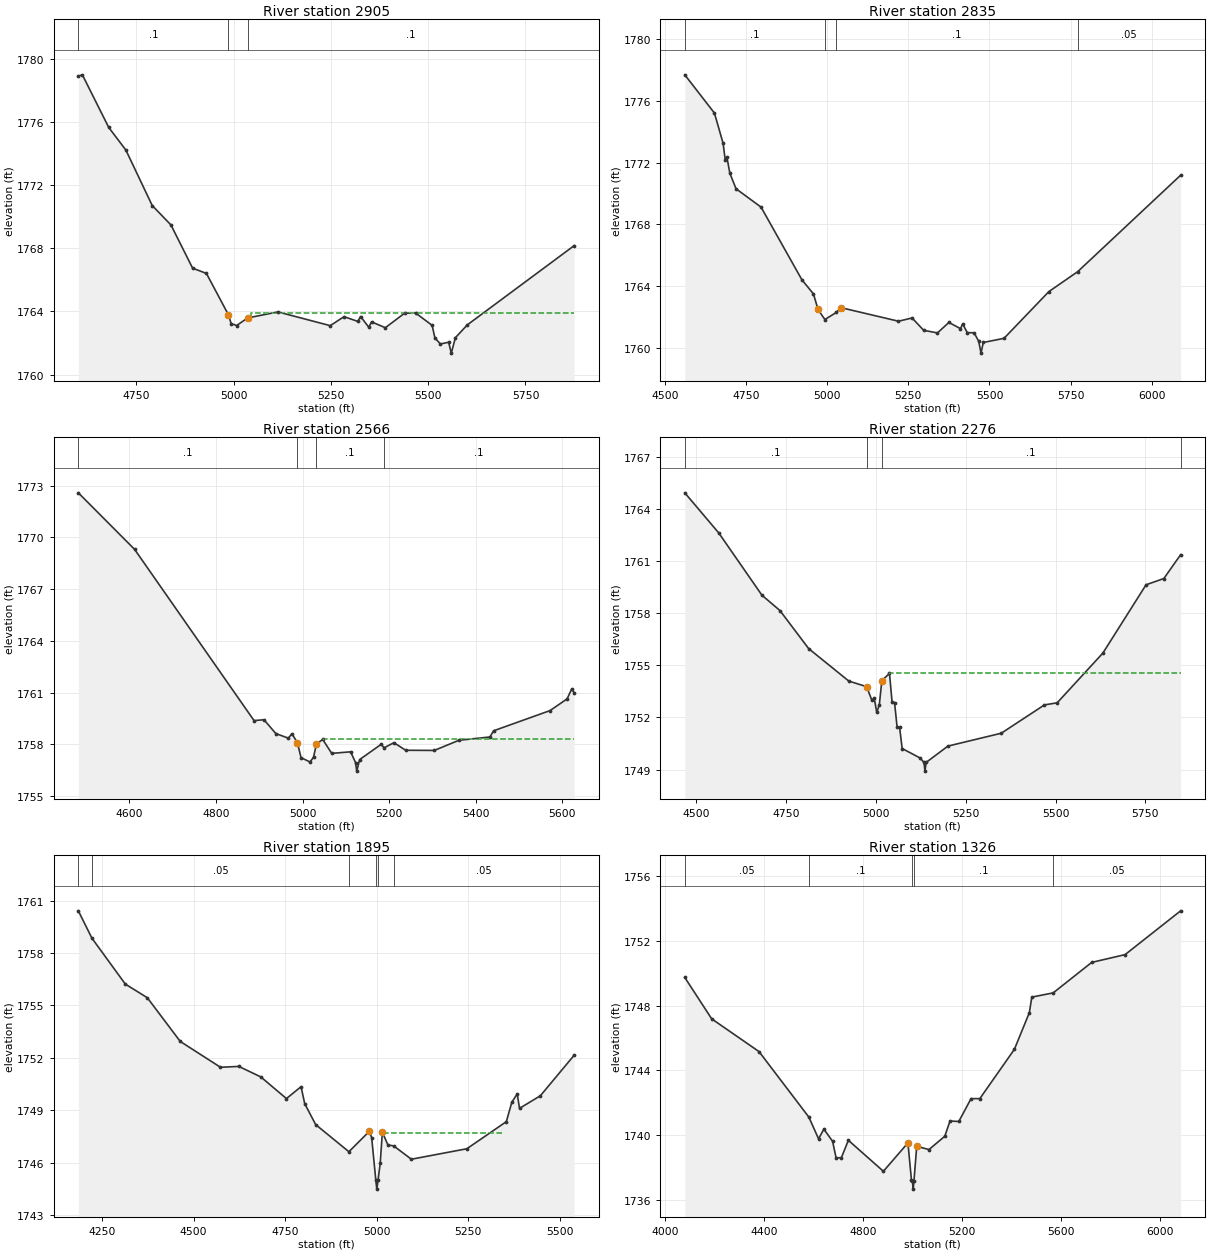
Type RM Length L Ch R = 1 ,2905    ,70,70,70
BEGIN DESCRIPTION:
UNT 0043 IN HEWA 6.0
END DESCRIPTION:
XS GIS Cut Line= 4
      2745944.96     10066516.28      2745722.03     10066579.98
      2745203.28     10067103.28      2745203.28     10067408.18
#Sta/Elev= 30
  4601.4 1778.91  4611.8 1778.99  4679.4 1775.66  4723.6 1774.22  4791.2 1770.71
  4839.3 1769.48    4895 1766.74  4930.4 1766.41  4986.9 1763.79    4994 1763.23
  5008.1 1763.11  5036.4 1763.59  5114.2 1763.97  5248.5  1763.1  5283.9 1763.67
  5319.2 1763.37  5326.3 1763.68  5347.5    1763  5354.6 1763.34    5390 1762.97
  5439.5 1763.89  5467.8  1763.9  5510.2 1763.12  5517.2 1762.33  5531.4 1761.94
  5552.6 1762.05  5559.4 1761.36    5570 1762.34  5600.6 1763.15    5875 1768.17
#Mann= 3 , 0 , 0
  4601.4      .1       0  4986.9     .07       0  5036.4      .1       0
#XS Ineff= 2 , 0
                         5043.86         1763.93
Permanent Ineff=
       T       T
Bank Sta=4986.9,5036.4
XS Rating Curve= 0 ,0
Exp/Cntr=0.3,0.1

Type RM Length L Ch R = 1 ,2835    ,269,269,269
BEGIN DESCRIPTION:
Mapping XS 3114e577
END DESCRIPTION:
XS GIS Cut Line= 4
      2745931.63     10066463.07      2745672.92     10066539.47
      2745150.35     10067025.58      2745145.15     10067569.68
#Sta/Elev= 30
  4561.4 1777.69  4652.7 1775.21  4679.4 1773.25    4686 1772.16  4691.2 1772.34
  4700.3  1771.3  4719.3  1770.3  4796.3 1769.11  4922.1  1764.4  4957.8 1763.48
  4971.9 1762.47  4992.9 1761.82  5028.4 1762.28  5042.3 1762.59  5219.7 1761.71
  5261.7 1761.92  5297.3 1761.12  5339.9 1760.95    5375 1761.63  5410.7 1761.23
  5417.5 1761.53  5431.7 1760.97  5452.7 1760.96  5466.9 1760.41    5474 1759.64
    5481 1760.33  5544.9  1760.6    5683 1763.63  5771.7 1764.92    6089 1771.18
#Mann= 4 ,-1 , 0
  4561.4      .1       0  4992.9     .07       0  5028.4      .1       0
  5771.7     .05       0
#XS Ineff= 2 , 0
                         5044.96         1762.57
Permanent Ineff=
       T       T
Bank Sta=4971.9,5042.3
XS Rating Curve= 0 ,0
Exp/Cntr=0.3,0.1

Type RM Length L Ch R = 1 ,2566    ,290,290,290
BEGIN DESCRIPTION:
Mapping XS b61b92e7
END DESCRIPTION:
XS GIS Cut Line= 4
      2745793.36     10066371.59      2745388.63     10066425.84
      2745140.15     10066756.79      2745122.83     10067079.43
#Sta/Elev= 30
  4482.1 1772.58  4612.1  1769.3    4888 1759.37  4911.1 1759.42  4938.2 1758.62
  4967.4 1758.35  4975.3 1758.61  4988.2 1758.09  4996.5 1757.22  5017.4 1756.97
  5025.4 1757.25    5032    1758  5046.5 1758.28  5067.4 1757.47  5111.1 1757.56
  5122.4 1756.94  5125.2 1756.44  5131.9 1757.11  5181.9    1758  5188.2 1757.79
  5211.1 1758.09  5238.2 1757.65  5304.3 1757.64  5361.3 1758.23  5432.7 1758.42
  5441.4 1758.78  5571.6 1759.95  5611.1 1760.63  5621.7  1761.2  5627.4 1760.99
#Mann= 4 ,-1 , 0
  4482.1      .1       0  4988.2     .07       0    5032      .1       0
  5188.2      .1       0
#XS Ineff= 2 , 0
                          5047.5         1758.28
Permanent Ineff=
       T       T
Bank Sta=4988.2,5032
XS Rating Curve= 0 ,0
Exp/Cntr=0.3,0.1

Type RM Length L Ch R = 1 ,2276    ,381,381,381
BEGIN DESCRIPTION:
UNT 0043 IN HEWA 5.0
END DESCRIPTION:
XS GIS Cut Line= 3
      2745573.05     10066312.74      2745142.18      10066301.4
      2744468.33     10066969.58
#Sta/Elev= 30
  4468.1 1764.92  4562.7 1762.61  4682.8 1759.03  4732.8 1758.15  4812.8 1755.96
  4924.6 1754.09  4974.1 1753.77  4988.3 1753.01  4995.3  1753.1  5002.4 1752.29
  5009.5 1752.73  5016.6 1754.12  5037.8 1754.53  5044.9 1752.91  5051.9 1752.85
    5059 1751.44    5066 1751.42  5073.1 1750.21  5122.6 1749.67  5133.8 1749.41
  5136.5 1748.91  5139.8 1749.41  5200.4 1750.35  5348.9 1751.09  5469.1 1752.72
  5504.5 1752.84  5631.7  1755.7  5751.9 1759.63  5801.4 1759.99  5848.1 1761.36
#Mann= 4 ,-1 , 0
  4468.1      .1       0  4974.1     .07       0  5016.6      .1       0
  5848.1     .05       0
#XS Ineff= 2 , 0
                         5037.27         1754.58
Permanent Ineff=
       T       T
Bank Sta=4974.1,5016.6
XS Rating Curve= 0 ,0
Exp/Cntr=0.3,0.1

Type RM Length L Ch R = 1 ,1895    ,569,569,569
BEGIN DESCRIPTION:
UNT 0043 IN HEWA 4.0
END DESCRIPTION:
XS GIS Cut Line= 3
      2745646.79     10066068.93      2744921.05     10066040.58
      2744399.43      10066392.1
#Sta/Elev= 30
  4184.7 1760.41    4222 1758.84  4313.1 1756.22  4373.2 1755.44  4463.2 1752.94
  4573.3 1751.46  4623.4 1751.51  4683.4 1750.91  4753.5 1749.67  4793.5 1750.35
  4803.5 1749.38  4833.5 1748.18  4924.3 1746.63  4979.8 1747.79  4986.5 1747.44
  4997.9 1744.99  5000.6 1744.49  5003.9 1744.99  5009.8 1745.96  5015.8 1747.75
  5030.8 1747.02  5046.9 1746.96    5095  1746.2  5246.7  1746.8  5354.6 1748.35
  5369.6 1749.46  5384.4 1749.94  5390.6 1749.11  5447.6 1749.83    5540 1752.15
#Mann= 6 ,-1 , 0
  4184.7      .1       0    4222     .05       0  4924.3      .1       0
  4997.9     .07       0  5003.9      .1       0  5046.9     .05       0
#XS Ineff= 2 ,-1
 4843.63 4978.25 1747.68 5017.38 5341.91 1747.68
Permanent Ineff=
       T       T
Bank Sta=4979.8,5015.8
XS Rating Curve= 0 ,0
Exp/Cntr=0.3,0.1

Type RM Length L Ch R = 1 ,1326    ,496,496,496
BEGIN DESCRIPTION:
UNT 0043 IN HEWA 3.0
END DESCRIPTION:
XS GIS Cut Line= 3
       2745244.2       10064986.      2744342.72     10065859.14
      2744257.85     10066600.29
#Sta/Elev= 30
  4081.1 1749.73  4189.6 1747.18  4380.7 1745.16  4581.8 1741.12    4621 1739.78
  4642.3 1740.38  4677.5 1739.63  4691.7 1738.61    4713 1738.62  4741.3 1739.69
  4882.6 1737.78  4981.6 1739.53  4995.8 1737.24  4999.9 1737.18  5002.7 1736.68
  5005.9 1737.18  5017.1 1739.32  5066.5 1739.12  5130.3 1739.94  5151.4 1740.88
  5186.9 1740.85  5236.3 1742.26  5271.7 1742.26  5411.2  1745.3  5471.6 1747.56
  5481.6 1748.52  5567.8 1748.78  5723.2 1750.66    5858 1751.14  6082.1 1753.84
#Mann= 5 ,-1 , 0
  4081.1     .05       0  4581.8      .1       0  4999.9     .07       0
  5005.9      .1       0  5567.8     .05       0
Bank Sta=4981.6,5017.1
XS Rating Curve= 0 ,0
Exp/Cntr=0.3,0.1

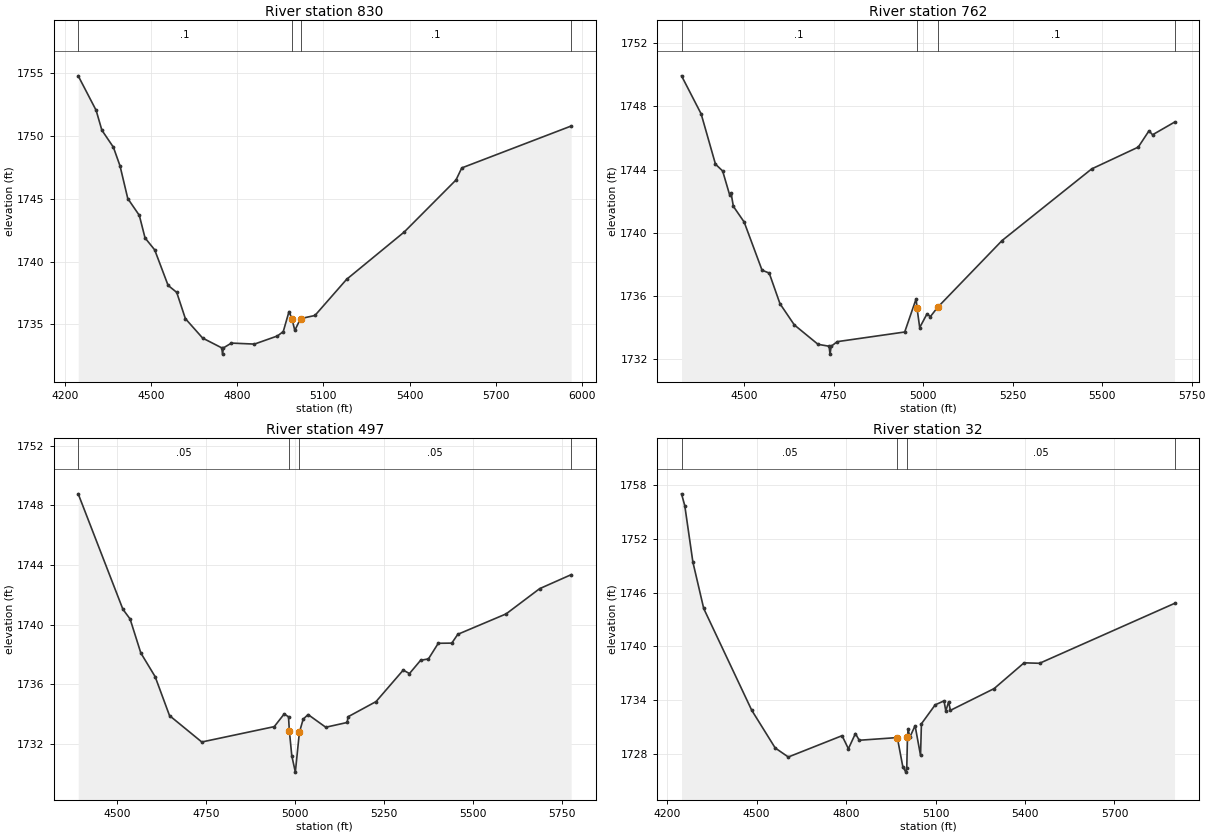
Type RM Length L Ch R = 1 ,830     ,68,68,68
BEGIN DESCRIPTION:
UNT 0043 IN HEWA 2.0
END DESCRIPTION:
XS GIS Cut Line= 2
      2744121.59     10064651.49      2744263.33     10066363.74
#Sta/Elev= 30
  4245.3 1754.81  4307.8 1752.06  4327.8 1750.48    4368 1749.12  4391.1 1747.63
  4418.1 1745.03  4458.3 1743.69  4478.3 1741.89  4511.9 1740.94  4558.6 1738.11
  4588.7 1737.55  4618.8 1735.46    4679 1733.91  4745.6 1733.13  4748.3 1732.63
  4751.6 1733.13  4779.4 1733.51  4859.6 1733.43  4939.9 1734.08    4960 1734.43
    4980 1736.02  4990.1 1735.46  5000.2 1734.52  5020.2 1735.46  5070.4 1735.71
  5180.7 1738.59  5381.4 1742.36    5562 1746.51  5582.1 1747.47  5963.4 1750.81
#Mann= 4 ,-1 , 0
  4245.3      .1       0  4990.1     .05       0  5020.2      .1       0
  5963.4     .05       0
Bank Sta=4990.1,5020.2
XS Rating Curve= 0 ,0
Exp/Cntr=0.3,0.1

Type RM Length L Ch R = 1 ,762     ,265,265,265
BEGIN DESCRIPTION:
Mapping XS a1cdc1ba
END DESCRIPTION:
XS GIS Cut Line= 2
      2744087.79     10064729.01      2744144.22     10066104.95
#Sta/Elev= 30
  4325.1 1749.94  4379.9 1747.53  4419.9 1744.35  4439.9 1743.92  4459.3 1742.42
  4463.6  1742.5  4469.9 1741.68    4500 1740.69    4550 1737.64    4570 1737.46
  4600.1 1735.52  4640.1 1734.18  4706.4 1732.95  4737.2 1732.83  4739.9 1732.33
  4743.2 1732.83  4760.2 1733.12  4948.5 1733.73  4980.4 1735.83 4982.73 1735.28
  4990.4 1734.01  5010.4 1734.86  5020.4 1734.71  5040.4 1735.29  5220.6 1739.52
  5470.8 1744.05  5600.9 1745.43  5630.9 1746.46  5640.9 1746.21  5702.2 1747.01
#Mann= 4 ,-1 , 0
  4325.1      .1       0 4982.73     .05       0  5040.4      .1       0
  5702.2     .05       0
Bank Sta=4982.73,5040.4
XS Rating Curve= 0 ,0
Exp/Cntr=0.3,0.1

Type RM Length L Ch R = 1 ,497     ,465,465,465
BEGIN DESCRIPTION:
Mapping XS fd856001
END DESCRIPTION:
XS GIS Cut Line= 4
      2744014.01     10064729.02      2743944.56     10065275.93
      2743749.25     10065349.71      2743931.55      10065948.7
#Sta/Elev= 30
  4390.8 1748.77  4516.5 1741.03  4536.7 1740.38  4566.9  1738.1  4607.2 1736.51
  4647.6  1733.9  4738.3 1732.13  4942.1 1733.16    4970 1734.01  4982.2 1733.82
 4984.55 1732.88  4991.4 1731.21  5001.4 1730.11  5012.8 1732.78  5023.4 1733.66
  5037.2 1733.97  5086.9 1733.12  5147.2 1733.44  5149.5 1733.82  5228.3 1734.84
  5304.7 1736.95  5322.3 1736.72  5353.7 1737.61  5375.6  1737.7  5403.3 1738.75
  5441.3 1738.76  5458.2 1739.35  5594.1 1740.72  5688.2 1742.41    5777 1743.35
#Mann= 4 ,-1 , 0
  4390.8     .05       0 4984.55    .035       0  5012.8     .05       0
    5777     .16       0
Bank Sta=4984.55,5012.8
XS Rating Curve= 0 ,0
Exp/Cntr=0.3,0.1

Type RM Length L Ch R = 1 ,32      ,0,0,0
BEGIN DESCRIPTION:
UNT 0043 IN HEWA 1.0
END DESCRIPTION:
XS GIS Cut Line= 4
      2743840.67     10064621.61      2743467.43     10065208.38
      2743493.47     10065314.28      2743939.65      10066036.5
#Sta/Elev= 30
  4248.1 1757.03    4259  1755.7  4286.2  1749.4  4322.5 1744.22  4483.4 1732.86
  4562.2 1728.64  4606.2 1727.63  4786.5 1730.01  4807.7 1728.55  4831.3 1730.25
  4844.1  1729.5  4971.8  1729.8  4990.2 1726.55  5000.3 1725.94  5003.5 1726.44
 5005.91 1729.91  5008.2 1730.79  5013.3 1729.81  5031.4 1731.13  5049.7  1727.8
  5052.6 1731.34  5098.9 1733.46  5128.5  1733.9  5134.4 1732.77  5143.9  1733.8
  5149.8 1732.84  5296.4 1735.27  5396.9 1738.15  5448.9  1738.1  5901.5 1744.79
#Mann= 4 ,-1 , 0
  4248.1     .05       0  4971.8    .035       0  5003.5     .05       0
  5901.5      .1       0
Bank Sta=4971.8,5005.91
XS Rating Curve= 0 ,0
Exp/Cntr=0.3,0.1

Chan Stop Cuts=-1
Use User Specified Reach Order=0
Composite Channel Slope=5