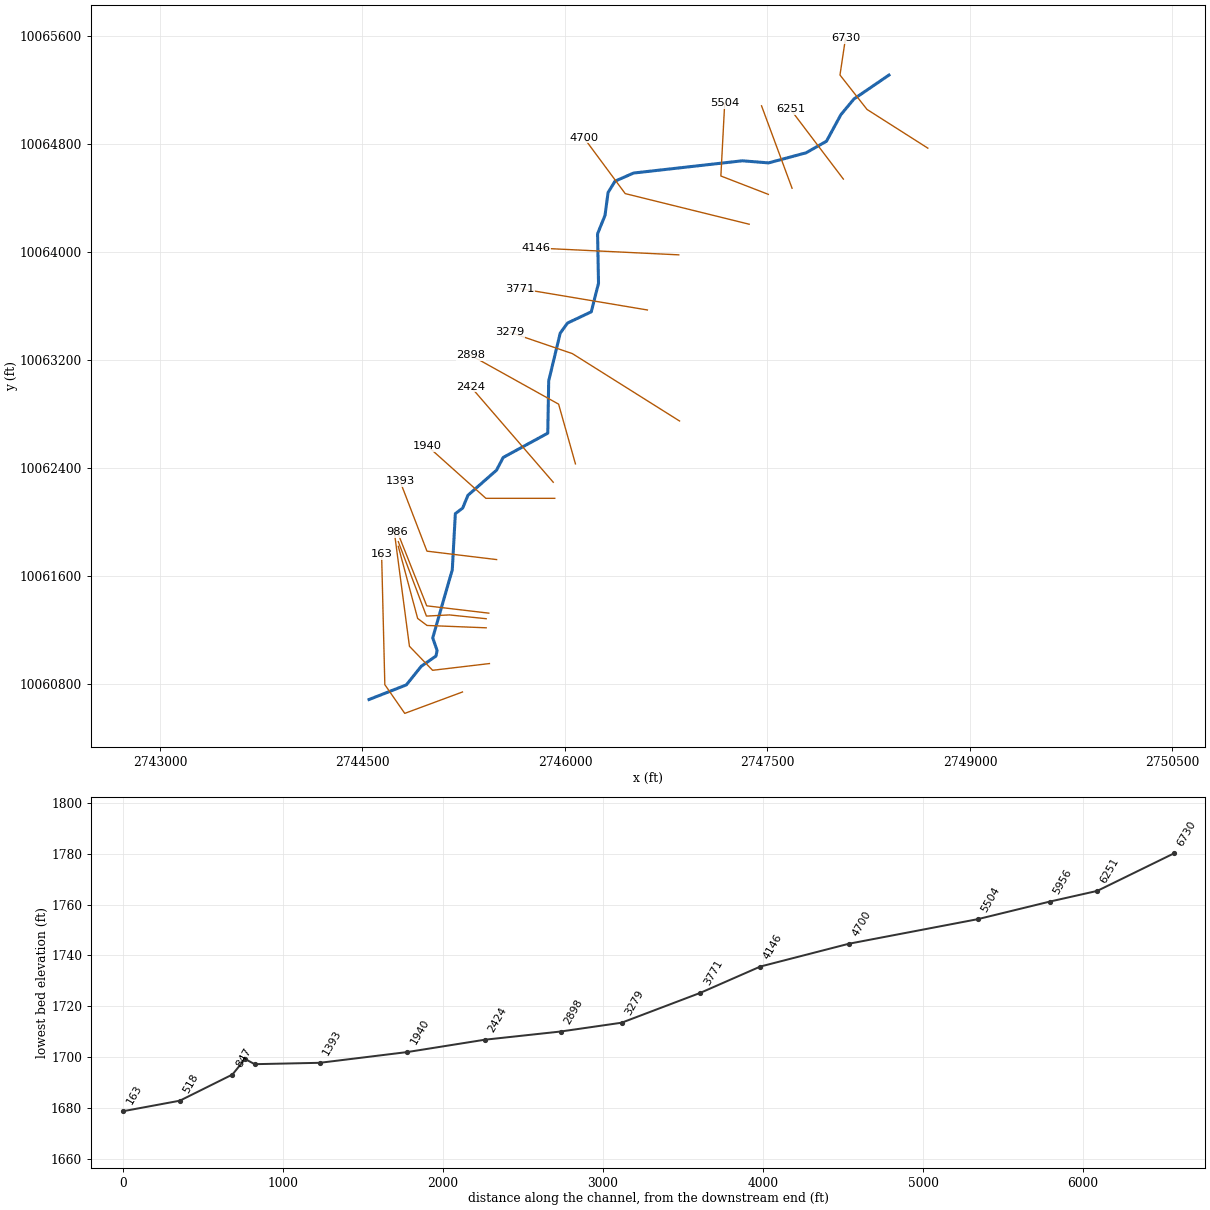
--- UNT 0045 IN HEWA.prj (project) ---

Proj Title=UNT 0045 IN HEWA Base Level Engineering
Current Plan=p01
Default Exp/Contr=0.3,0.1
English Units
Geom File=g01
Flow File=f01
Plan File=p01
Y Axis Title=Elevation
X Axis Title(PF)=Main Channel Distance
X Axis Title(XS)=Station
BEGIN DESCRIPTION:
UNT 0045 IN HEWA
END DESCRIPTION:
DSS Export Rating Curves= 0
DSS Export Rating Curve Sorted= 0
DSS Export Volume Flow Curves= 0
DXF OffsetX= 0
DXF OffsetY= 0
DXF ScaleX= 1
DXF ScaleY= 10

--- UNT 0045 IN HEWA.p01 (plan) ---

Plan Title=Multiple Run
Short Identifier=Multiple
Geom File=g01
Flow File=f01
Subcritical Flow
K Sum by GR= 0
Std Step Tol= 0.01
Critical Tol= 0.01
Num of Std Step Trials= 20
Max Error Tol= 0.3
Flow Tol Ratio= 0.001
Split Flow NTrial= 30
Split Flow Tol= 0.02
Split Flow Ratio= 0.02
Log Output Level= 0
Friction Slope Method= 1
Unsteady Friction Slope Method= 2
Unsteady Bridges Friction Slope Method= 1
Parabolic Critical Depth
Global Vel Dist=  1 , 1 , 1
Global Log Level= 0
CheckData=True
Encroach Param= -1, 0, 0, 0
BEGIN DESCRIPTION:
Multiple Run
END DESCRIPTION:

--- UNT 0045 IN HEWA.f01 (steady flow) ---

Flow Title=Multiple
Number of Profiles=7
Profile Names=10-year,25-year,50-year,1pct_min,100-year,1pct_plu,500-year
River Rch & RM= UNT 0045 IN HEWA,Reach-1,6730
     377     521     641     579     783    1059    1170
Boundary for River Rch & Prof#=UNT 0045 IN HEWA,Reach-1,1
Up Type=0
Dn Type=3
Dn Slope=0.005
Boundary for River Rch & Prof#=UNT 0045 IN HEWA,Reach-1,2
Up Type=0
Dn Type=3
Dn Slope=0.005
Boundary for River Rch & Prof#=UNT 0045 IN HEWA,Reach-1,3
Up Type=0
Dn Type=3
Dn Slope=0.005
Boundary for River Rch & Prof#=UNT 0045 IN HEWA,Reach-1,4
Up Type=0
Dn Type=3
Dn Slope=0.005
Boundary for River Rch & Prof#=UNT 0045 IN HEWA,Reach-1,5
Up Type=0
Dn Type=3
Dn Slope=0.005
Boundary for River Rch & Prof#=UNT 0045 IN HEWA,Reach-1,6
Up Type=0
Dn Type=3
Dn Slope=0.005
Boundary for River Rch & Prof#=UNT 0045 IN HEWA,Reach-1,7
Up Type=0
Dn Type=3
Dn Slope=0.005

--- UNT 0045 IN HEWA.g01 (geometry) ---

Geom Title=Existing Conditions
Program Version=4.10

River Reach=UNT 0045 IN HEWA,Reach-1
Reach XY= 30
      2748400.01     10065307.94      2748140.54     10065130.84
      2748044.19     10065014.95      2747937.42     10064818.34
      2747786.38      10064732.4       2747508.6     10064657.75
      2747313.79     10064673.23       2746508.4     10064582.47
      2746370.93      10064522.3      2746319.47     10064438.32
      2746296.75     10064268.84      2746241.65     10064132.78
      2746248.68     10063766.43      2746194.87     10063554.94
      2746019.15     10063471.62      2745965.09     10063397.46
      2745879.64     10063043.25      2745872.76     10062656.12
      2745542.36     10062476.08      2745493.13     10062382.07
      2745281.45      10062196.2      2745242.42     10062101.61
      2745188.07     10062060.02      2745165.46      10061644.6
       2745020.5     10061139.98      2745052.79     10061047.31
      2745044.92      10061005.9      2744935.41     10060930.02
      2744825.01     10060791.99      2744548.47     10060683.73

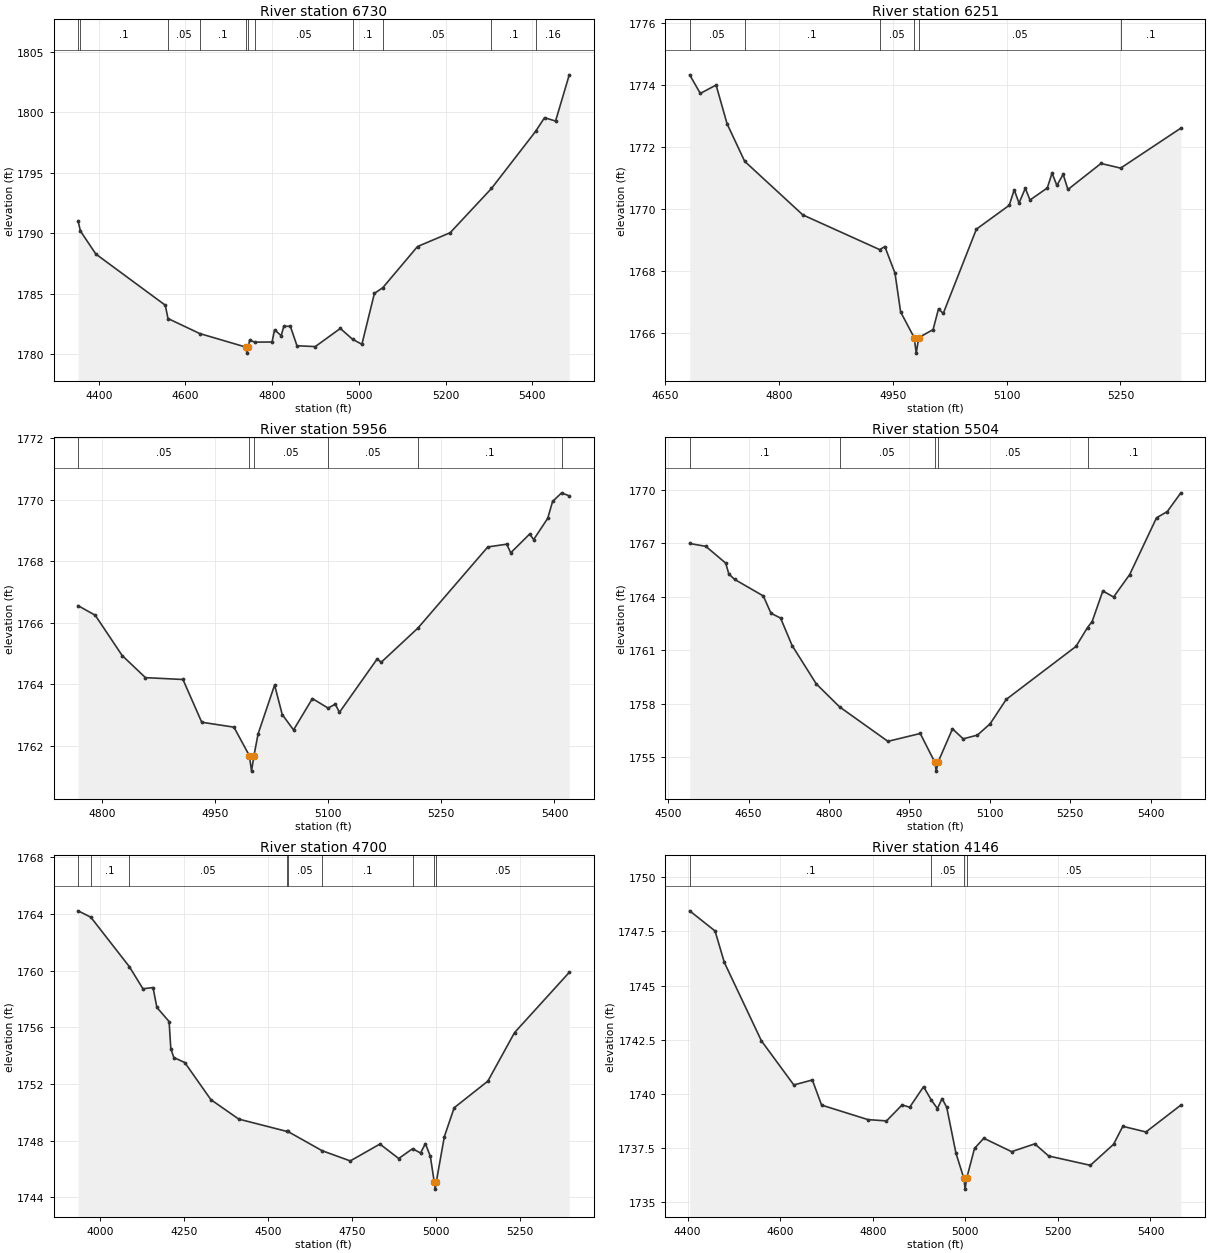
Type RM Length L Ch R = 1 ,6730    ,479,479,479
BEGIN DESCRIPTION:
UNT 0045 IN HEWA 14.0
END DESCRIPTION:
XS GIS Cut Line= 4
      2748688.12     10064766.89       2748237.6     10065053.58
      2748037.38     10065308.41      2748078.13     10065580.09
#Sta/Elev= 30
  4352.5 1791.01  4357.9 1790.19  4393.4 1788.29  4553.6 1784.06  4559.8 1782.96
  4632.9 1781.72  4739.2  1780.6  4741.9  1780.1  4745.2  1780.6  4748.1 1781.18
  4759.8 1781.01  4799.8 1781.02  4805.7 1782.03  4820.9 1781.54  4826.9 1782.32
  4842.1 1782.32  4857.3 1780.71  4899.5 1780.64  4957.3 1782.14  4985.4 1781.25
    5007 1780.83  5035.9 1785.04  5055.3 1785.51  5135.3 1788.91  5210.6 1790.05
  5305.9 1793.71  5407.5 1798.42  5428.3 1799.56  5453.7 1799.28  5485.3  1803.1
#Mann= 11 ,-1 , 0
  4352.5     .05       0  4357.9      .1       0  4559.8     .05       0
  4632.9      .1       0  4739.2     .07       0  4745.2      .1       0
  4759.8     .05       0  4985.4      .1       0  5055.3     .05       0
  5305.9      .1       0  5407.5     .16       0
Bank Sta=4739.2,4745.2
XS Rating Curve= 0 ,0
Exp/Cntr=0.3,0.1

Type RM Length L Ch R = 1 ,6251    ,295,295,295
BEGIN DESCRIPTION:
UNT 0045 IN HEWA 13.0
END DESCRIPTION:
XS GIS Cut Line= 2
      2748062.21     10064538.02      2747670.94     10065054.05
#Sta/Elev= 30
    4682 1774.33    4696 1773.73  4716.8    1774  4731.3 1772.75  4754.5 1771.54
  4831.2 1769.81  4932.5 1768.69  4939.3 1768.79  4952.7 1767.93  4960.1 1766.68
    4978 1765.85  4980.7 1765.35    4984 1765.85  5002.9 1766.11  5010.1 1766.78
  5016.3 1766.63    5060 1769.35  5103.3 1770.12  5109.9 1770.62  5116.2 1770.19
  5124.5 1770.67  5130.7 1770.29  5153.5 1770.68  5159.8 1771.16  5166.1 1770.76
  5174.4 1771.12  5180.7 1770.63  5224.3 1771.47  5250.2 1771.32  5329.6 1772.61
#Mann= 6 ,-1 , 0
    4682     .05       0  4754.5      .1       0  4932.5     .05       0
    4978    .035       0    4984     .05       0  5250.2      .1       0
Bank Sta=4978,4984
XS Rating Curve= 0 ,0
Exp/Cntr=0.3,0.1

Type RM Length L Ch R = 1 ,5956    ,452,452,452
BEGIN DESCRIPTION:
UNT 0045 IN HEWA 12.0
END DESCRIPTION:
XS GIS Cut Line= 2
      2747682.31       10064470.      2747456.17     10065080.57
#Sta/Elev= 30
  4768.5 1766.55  4791.2 1766.24  4826.9 1764.93  4857.8 1764.21  4907.5 1764.15
  4932.4 1762.76  4975.1  1762.6  4995.6 1761.67  4998.4 1761.17  5001.6 1761.67
  5007.1 1762.38    5029 1763.97  5039.1 1763.01  5054.1 1762.51  5079.1 1763.53
  5099.9 1763.22  5109.5 1763.35  5114.9 1763.08    5165 1764.82  5170.3 1764.71
  5218.9 1765.82  5311.6 1768.46  5336.7 1768.55    5342 1768.27  5367.1 1768.88
  5372.4  1768.7    5391 1769.39  5397.5 1769.94  5409.5 1770.22  5419.6 1770.12
#Mann= 6 ,-1 , 0
  4768.5     .05       0  4995.6     .07       0  5001.6     .05       0
  5099.9     .05       0  5218.9      .1       0  5409.5     .05       0
Bank Sta=4995.6,5001.6
XS Rating Curve= 0 ,0
Exp/Cntr=0.3,0.1

Type RM Length L Ch R = 1 ,5504    ,804,804,804
BEGIN DESCRIPTION:
UNT 0045 IN HEWA 11.0
END DESCRIPTION:
XS GIS Cut Line= 3
      2747506.54     10064424.65        2747155.     10064560.73
      2747183.33     10065099.03
#Sta/Elev= 30
  4540.1 1766.99  4570.2 1766.83  4607.3 1765.89  4613.1 1765.28  4623.8 1764.98
  4677.4 1764.05  4691.7 1763.08  4709.6 1762.81  4731.1 1761.27  4776.2 1759.12
  4819.7 1757.83  4909.8  1755.9  4970.1 1756.34  4997.2 1754.73  4999.9 1754.23
  5003.2 1754.73  5030.2  1756.6  5050.2 1756.04  5076.7 1756.25  5100.3 1756.88
  5130.4 1758.25  5260.5 1761.22    5282 1762.28  5290.6 1762.61  5310.6 1764.33
  5330.6 1763.99  5360.7 1765.25  5410.7 1768.43  5430.8 1768.78  5456.1 1769.83
#Mann= 5 ,-1 , 0
  4540.1      .1       0  4819.7     .05       0  4997.2    .035       0
  5003.2     .05       0    5282      .1       0
Bank Sta=4997.2,5003.2
XS Rating Curve= 0 ,0
Exp/Cntr=0.3,0.1

Type RM Length L Ch R = 1 ,4700    ,554,554,554
BEGIN DESCRIPTION:
UNT 0045 IN HEWA 10.0
END DESCRIPTION:
XS GIS Cut Line= 3
      2747364.84     10064203.51      2746446.26     10064430.32
      2746140.09     10064844.22
#Sta/Elev= 30
  3934.9 1764.21  3972.8 1763.76  4087.4 1760.27  4127.8 1758.71  4157.8  1758.8
  4169.2  1757.4  4205.6  1756.4  4210.7 1754.49  4219.6 1753.86  4252.2 1753.51
  4329.9 1750.89  4412.8 1749.52  4556.1 1748.65  4557.9 1748.66  4660.7 1747.29
  4744.5 1746.57  4832.6 1747.76  4888.6 1746.74  4929.7 1747.43  4953.4 1747.13
    4968 1747.79  4982.6  1746.9  4994.3 1745.08    4997 1744.58  5000.3 1745.08
  5024.3 1748.28  5053.6 1750.32  5153.8  1752.2  5233.1 1755.62  5395.9 1759.87
#Mann= 9 ,-1 , 0
  3934.9     .05       0  3972.8      .1       0  4087.4     .05       0
  4556.1      .1       0  4557.9     .05       0  4660.7      .1       0
  4929.7     .05       0  4994.3    .035       0  5000.3     .05       0
Bank Sta=4994.3,5000.3
XS Rating Curve= 0 ,0
Exp/Cntr=0.3,0.1

Type RM Length L Ch R = 1 ,4146    ,375,375,375
BEGIN DESCRIPTION:
UNT 0045 IN HEWA 9.0
END DESCRIPTION:
XS GIS Cut Line= 2
      2746843.17     10063976.72       2745783.2     10064027.74
#Sta/Elev= 30
  4404.5 1748.45  4459.3 1747.52  4479.3 1746.07  4559.4 1742.45  4629.5 1740.41
  4669.5 1740.64  4689.5 1739.48  4789.7 1738.81  4829.7 1738.75  4863.5 1739.49
  4879.8 1739.38  4909.8 1740.33  4926.6 1739.71  4939.8 1739.32  4949.8 1739.78
  4959.8 1739.38  4979.9 1737.25  4996.9  1736.1  4999.6  1735.6  5002.9  1736.1
  5019.9 1737.48  5039.9 1737.95    5100 1737.33  5150.1 1737.69  5180.1 1737.13
  5270.2  1736.7  5320.3 1737.67  5340.3  1738.5  5390.3 1738.24  5465.7 1739.48
#Mann= 4 ,-1 , 0
  4404.5      .1       0  4926.6     .05       0  4996.9    .035       0
  5002.9     .05       0
Bank Sta=4996.9,5002.9
XS Rating Curve= 0 ,0
Exp/Cntr=0.3,0.1

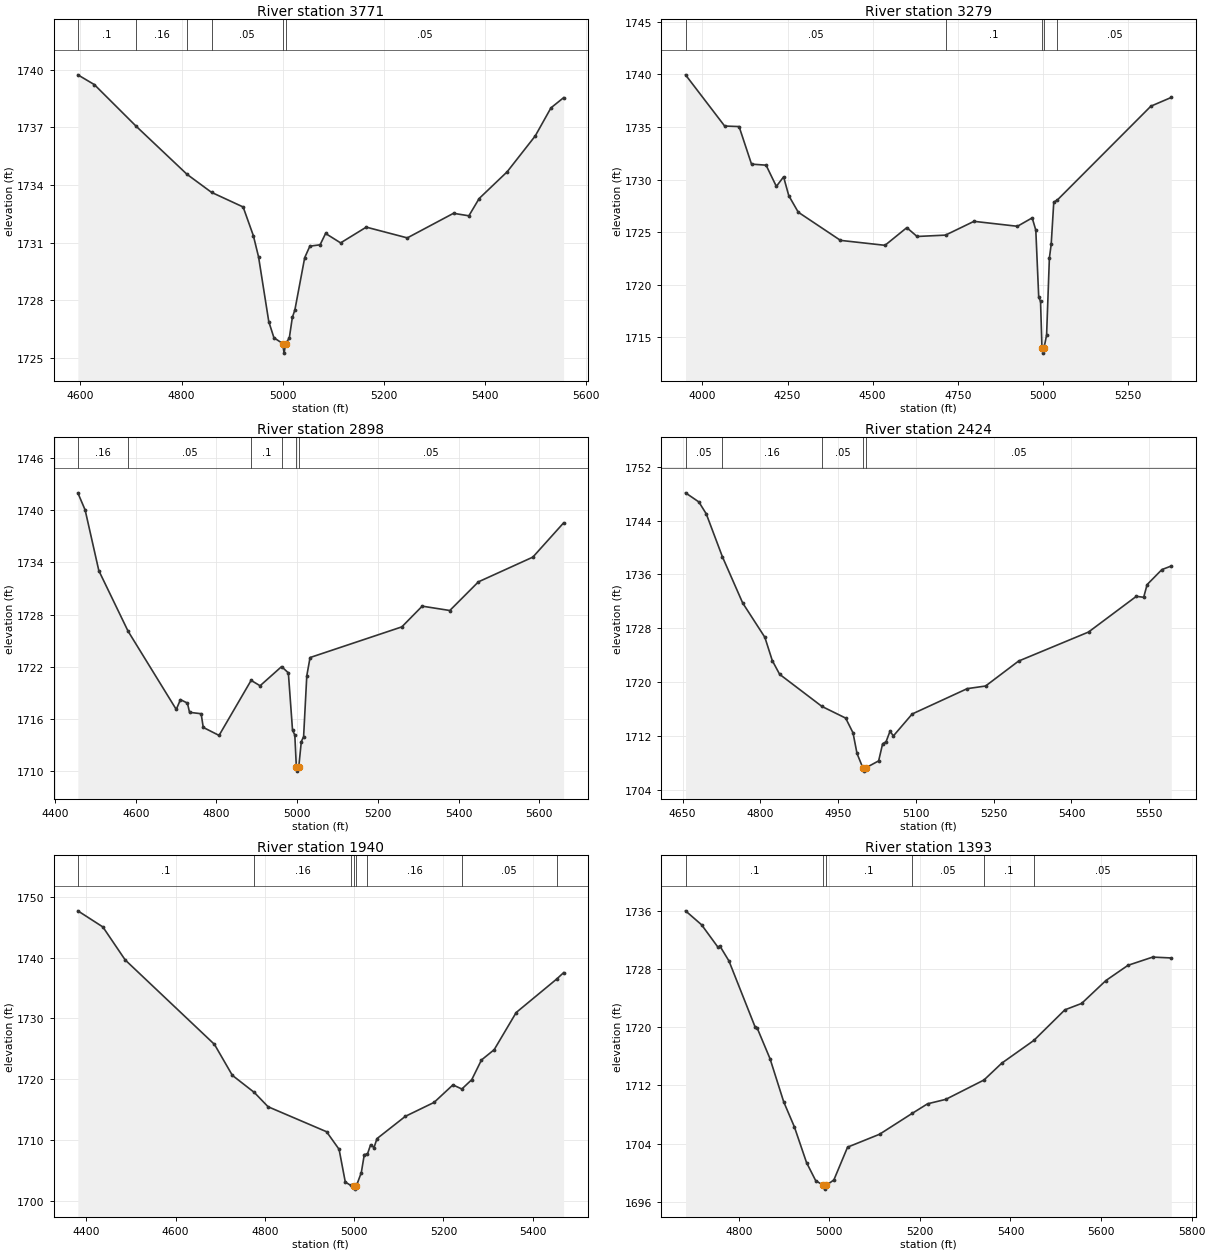
Type RM Length L Ch R = 1 ,3771    ,492,492,492
BEGIN DESCRIPTION:
UNT 0045 IN HEWA 8.0
END DESCRIPTION:
XS GIS Cut Line= 2
      2746610.72     10063568.48      2745663.84     10063727.24
#Sta/Elev= 30
  4594.8 1739.74  4627.5 1739.23  4709.8 1737.07  4810.6 1734.56  4859.1 1733.62
  4921.5 1732.86  4941.8 1731.36    4952 1730.26  4972.2 1726.89  4982.4 1726.05
  4999.7 1725.75  5002.4 1725.25  5005.7 1725.75  5012.8 1726.04  5018.8 1727.11
  5023.8  1727.5  5043.2 1730.22  5053.4 1730.82  5073.6 1730.89  5084.5 1731.48
  5114.2 1730.99  5164.9 1731.81    5246 1731.25  5337.3 1732.53  5367.7  1732.4
    5388  1733.3  5443.3 1734.69  5498.9 1736.56  5529.9 1738.02  5554.9 1738.55
#Mann= 6 ,-1 , 0
  4594.8      .1       0  4709.8     .16       0  4810.6      .1       0
  4859.1     .05       0  4999.7    .035       0  5005.7     .05       0
Bank Sta=4999.7,5005.7
XS Rating Curve= 0 ,0
Exp/Cntr=0.3,0.1

Type RM Length L Ch R = 1 ,3279    ,381,381,381
BEGIN DESCRIPTION:
UNT 0045 IN HEWA 7.0
END DESCRIPTION:
XS GIS Cut Line= 3
      2746848.85     10062746.33      2746055.04      10063245.3
       2745591.8     10063403.48
#Sta/Elev= 30
  3950.2 1739.96  4065.2 1735.09  4107.6 1735.04  4144.1 1731.47  4186.9 1731.37
  4217.1 1729.35  4238.3 1730.26  4253.6 1728.47  4281.4  1726.9  4405.5 1724.22
  4536.3 1723.75  4600.3 1725.43  4630.5 1724.59    4714 1724.72  4797.7 1726.03
  4925.3 1725.56  4968.7 1726.36  4979.3 1725.19  4987.9  1718.8  4993.2 1718.43
  4997.4    1714  5000.2  1713.5  5003.4    1714    5011 1715.21  5019.2 1722.54
  5024.5 1723.84  5032.1 1727.86  5042.6 1728.06  5317.4 1736.98  5377.3 1737.81
#Mann= 5 ,-1 , 0
  3950.2     .05       0    4714      .1       0  4997.4     .07       0
  5003.4      .1       0  5042.6     .05       0
Bank Sta=4997.4,5003.4
XS Rating Curve= 0 ,0
Exp/Cntr=0.3,0.1

Type RM Length L Ch R = 1 ,2898    ,474,474,474
BEGIN DESCRIPTION:
UNT 0045 IN HEWA 6.0
END DESCRIPTION:
XS GIS Cut Line= 3
       2746077.7     10062428.88      2745952.98     10062871.09
      2745302.23     10063233.24
#Sta/Elev= 30
  4456.3 1741.99  4474.4 1740.02  4508.4 1733.05  4580.8 1726.11  4700.3 1717.12
  4710.7 1718.25    4728 1717.85  4733.2 1716.79    4762 1716.63  4767.2 1715.06
  4806.4 1714.14  4885.9 1720.46  4908.1 1719.84  4961.4 1722.04  4978.2 1721.32
  4988.5 1714.75  4994.2 1714.18    4998 1710.54  5000.8 1710.04    5004 1710.54
  5010.3 1713.43    5016    1714  5023.9 1720.99    5032 1723.08  5259.5  1726.6
    5310 1728.98  5378.4 1728.48  5449.3 1731.77  5584.3 1734.61  5660.5 1738.54
#Mann= 6 ,-1 , 0
  4456.3     .16       0  4580.8     .05       0  4885.9      .1       0
  4961.4     .05       0    4998    .035       0    5004     .05       0
Bank Sta=4998,5004
XS Rating Curve= 0 ,0
Exp/Cntr=0.3,0.1

Type RM Length L Ch R = 1 ,2424    ,484,484,484
BEGIN DESCRIPTION:
UNT 0045 IN HEWA 5.0
END DESCRIPTION:
XS GIS Cut Line= 2
       2745913.3     10062292.73      2745300.91     10063001.52
#Sta/Elev= 30
  4655.8 1748.11  4681.5 1746.76  4695.8 1744.99  4726.9 1738.63    4766 1731.77
  4808.8 1726.67  4823.1 1723.22  4837.3 1721.18  4918.9 1716.41  4964.6 1714.68
  4978.8 1712.49  4986.5 1709.43  4997.7 1707.31  5000.5 1706.81  5003.7 1707.31
  5028.2 1708.33  5035.9 1710.87  5042.5 1711.17  5050.1 1712.72  5056.7 1712.04
  5092.9 1715.29    5199 1719.05  5234.4 1719.44    5298 1723.14  5432.9 1727.45
  5525.1 1732.75  5539.3 1732.61  5545.9 1734.49  5574.4 1736.72  5592.5 1737.25
#Mann= 5 ,-1 , 0
  4655.8     .05       0  4726.9     .16       0  4918.9     .05       0
  4997.7    .035       0  5003.7     .05       0
Bank Sta=4997.7,5003.7
XS Rating Curve= 0 ,0
Exp/Cntr=0.3,0.1

Type RM Length L Ch R = 1 ,1940    ,547,547,547
BEGIN DESCRIPTION:
UNT 0045 IN HEWA 4.0
END DESCRIPTION:
XS GIS Cut Line= 3
      2745924.58     10062173.68      2745414.33     10062173.68
      2744983.69     10062558.99
#Sta/Elev= 30
    4381 1747.69  4437.1 1745.04  4487.1 1739.62  4687.1 1725.74  4727.1 1720.66
  4776.4 1717.84  4807.1  1715.5  4938.2 1711.39  4966.2  1708.5  4980.1 1703.13
  4991.9 1702.59  4998.8 1702.46  5001.5 1701.96  5004.8 1702.46    5016 1704.68
  5022.7 1707.65  5029.8 1707.74  5036.9 1709.27  5044.4 1708.78  5051.1 1710.26
  5114.6 1713.92    5179 1716.21  5221.2 1719.09  5241.2 1718.41  5263.4 1719.95
  5285.1 1723.18  5313.6 1724.87  5362.9 1730.98  5453.6 1736.48  5469.1 1737.53
#Mann= 8 ,-1 , 0
    4381      .1       0  4776.4     .16       0  4991.9     .05       0
  4998.8    .035       0  5004.8     .05       0  5029.8     .16       0
  5241.2     .05       0  5453.6     .16       0
Bank Sta=4998.8,5004.8
XS Rating Curve= 0 ,0
Exp/Cntr=0.3,0.1

Type RM Length L Ch R = 1 ,1393    ,407,407,407
BEGIN DESCRIPTION:
UNT 0045 IN HEWA 3.0
END DESCRIPTION:
XS GIS Cut Line= 3
       2745493.7     10061720.09      2744977.75     10061782.46
      2744779.31     10062298.41
#Sta/Elev= 30
  4682.5 1735.99    4718 1734.07  4753.9 1731.01  4758.9  1731.1  4778.4  1729.1
  4835.8 1720.08  4840.9 1719.85  4869.1 1715.66  4899.3 1709.73  4922.8  1706.3
  4949.7 1701.38  4969.8 1698.91    4987 1698.23  4989.7 1697.73    4993 1698.23
  5010.1    1699  5040.3  1703.5  5110.8 1705.27  5182.6 1708.13  5216.9 1709.46
  5257.1 1710.07  5341.4 1712.73  5380.8 1715.05  5451.5 1718.17  5520.1 1722.38
  5557.1 1723.26  5610.7 1726.41  5659.4  1728.5    5714 1729.63    5755 1729.51
#Mann= 6 ,-1 , 0
  4682.5      .1       0    4987     .07       0    4993      .1       0
  5182.6     .05       0  5341.4      .1       0  5451.5     .05       0
Bank Sta=4987,4993
XS Rating Curve= 0 ,0
Exp/Cntr=0.3,0.1

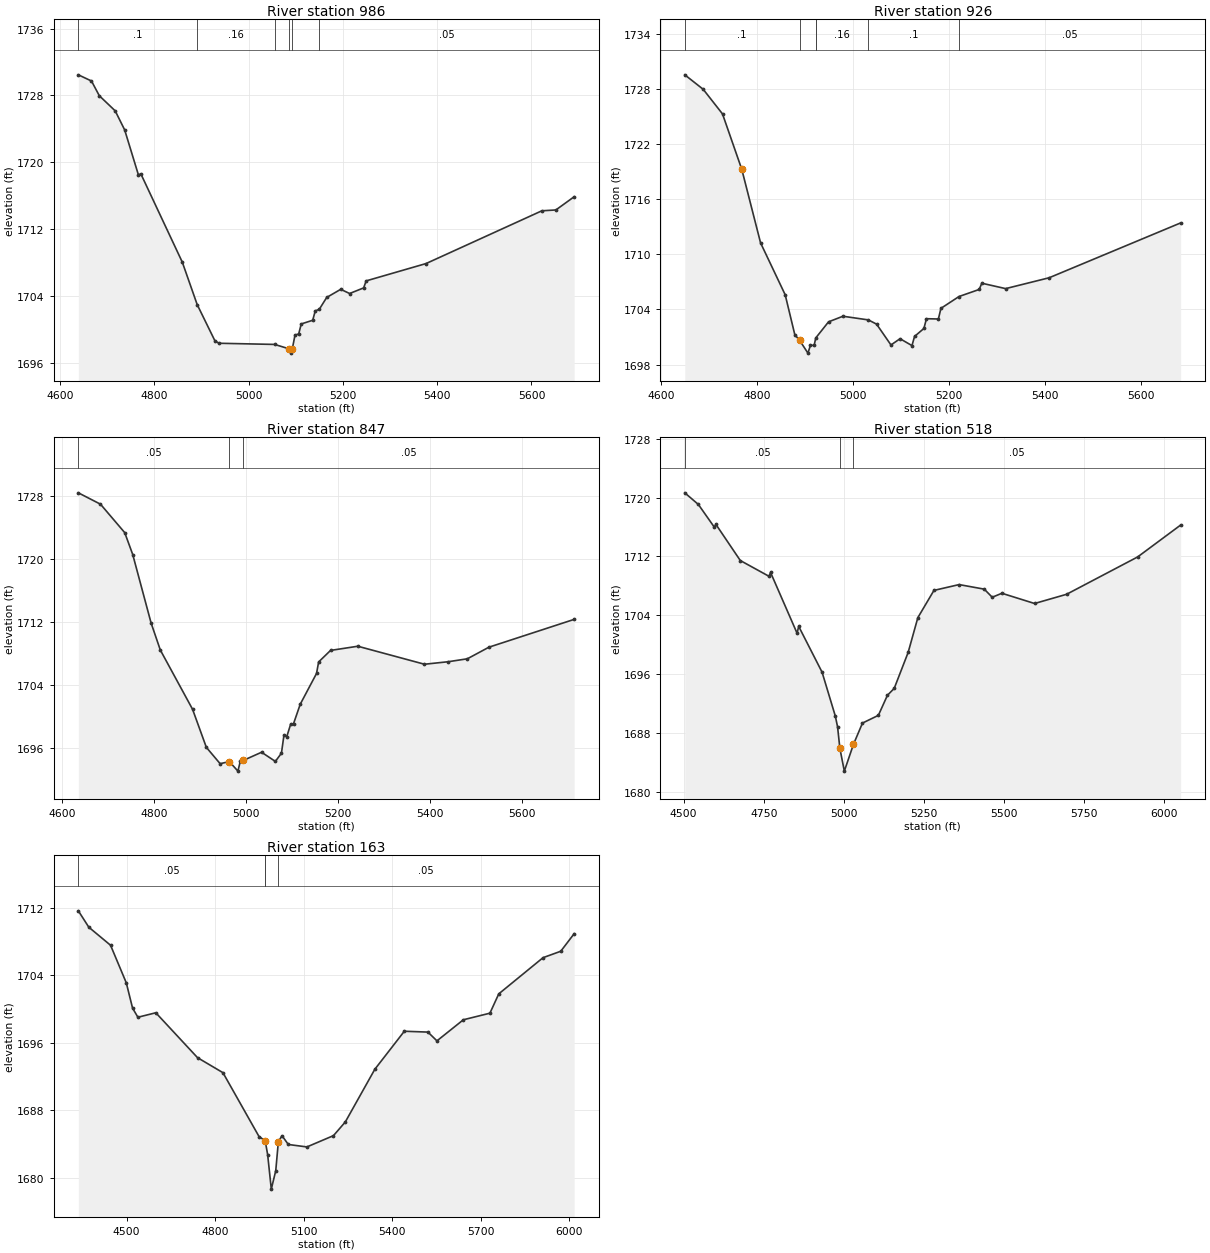
Type RM Length L Ch R = 1 ,986     ,60,60,60
BEGIN DESCRIPTION:
Mapping XS 49b1da75
END DESCRIPTION:
XS GIS Cut Line= 3
      2745436.13     10061323.34      2744976.06      10061377.6
      2744759.05     10061924.46
#Sta/Elev= 30
    4639 1730.47  4666.9 1729.73  4683.5 1727.97  4717.2 1726.16  4737.3 1723.88
  4766.5 1718.49  4771.5 1718.64  4859.5 1708.07  4891.1 1702.99  4928.7 1698.66
  4937.4 1698.37  5055.4 1698.23  5086.8 1697.69  5089.5 1697.19  5092.8 1697.69
  5098.5 1699.34  5106.4 1699.49  5111.8 1700.68  5136.1 1701.12  5141.5 1702.24
    5150 1702.43  5165.8 1703.85  5195.5 1704.82  5214.4 1704.32  5244.1 1704.99
  5249.5 1705.83  5376.4  1707.9  5622.1 1714.21  5651.8 1714.31  5690.6 1715.89
#Mann= 6 ,-1 , 0
    4639      .1       0  4891.1     .16       0  5055.4      .1       0
  5086.8     .07       0  5092.8      .1       0    5150     .05       0
Bank Sta=5086.8,5092.8
XS Rating Curve= 0 ,0
Exp/Cntr=0.3,0.1

Type RM Length L Ch R = 1 ,926     ,79,79,79
BEGIN DESCRIPTION:
Mapping XS fa212a8a
END DESCRIPTION:
XS GIS Cut Line= 4
      2745416.64     10061282.11      2745143.16     10061310.32
      2744973.89     10061301.64      2744765.55     10061852.86
#Sta/Elev= 30
  4649.6 1729.57    4688 1727.99  4728.2 1725.31  4768.4 1719.27  4807.6 1711.25
  4858.9  1705.6    4879 1701.24    4889 1700.63  4906.3 1699.24  4911.6  1700.1
  4919.2 1700.08  4922.7  1700.9  4949.3 1702.65  4979.3 1703.26  5032.3 1702.86
  5049.4  1702.4  5079.4 1700.13  5098.4 1700.81  5123.2 1700.06  5128.6 1701.06
  5148.1 1701.93  5153.4 1702.99  5178.3 1702.96  5183.6 1704.12  5221.3 1705.41
  5263.4 1706.18  5268.8 1706.86  5318.5 1706.27    5409 1707.45  5683.3 1713.43
#Mann= 6 ,-1 , 0
  4649.6      .1       0    4889     .05       0  4922.7      .1       0
  4922.7     .16       0  5032.3      .1       0  5221.3     .05       0
Bank Sta=4768.4,4889
XS Rating Curve= 0 ,0
Exp/Cntr=0.3,0.1

Type RM Length L Ch R = 1 ,847     ,329,329,329
BEGIN DESCRIPTION:
Mapping XS 24878a63
END DESCRIPTION:
XS GIS Cut Line= 4
      2745416.64     10061214.84      2744978.23      10061232.2
      2744908.78     10061284.28      2744765.55     10061818.14
#Sta/Elev= 30
  4635.9 1728.34  4684.1  1726.9  4736.8  1723.3  4754.2 1720.53  4794.2 1711.85
  4814.2 1708.44  4884.3 1700.94  4914.3 1696.12  4944.3 1694.05  4964.3 1694.32
    4983 1693.11  4988.2 1694.38  4994.4 1694.46  5034.4  1695.5  5064.4 1694.34
  5077.6 1695.38  5083.1 1697.67  5089.3 1697.49  5097.7 1699.06  5103.9 1699.11
  5118.5 1701.58  5153.9 1705.47  5158.5 1706.93  5184.4 1708.39  5243.7 1708.92
  5388.7 1706.64  5440.4 1706.96  5481.9 1707.33  5528.9  1708.8  5714.2 1712.32
#Mann= 3 , 0 , 0
  4635.9     .05       0  4964.3    .035       0  4994.4     .05       0
Bank Sta=4964.3,4994.4
XS Rating Curve= 0 ,0
Exp/Cntr=0.3,0.1

Type RM Length L Ch R = 1 ,518     ,355,355,355
BEGIN DESCRIPTION:
UNT 0045 IN HEWA 2.0
END DESCRIPTION:
XS GIS Cut Line= 4
      2745440.49     10060950.08      2745019.46     10060900.17
      2744848.02     10061078.12      2744733.23     10061946.59
#Sta/Elev= 30
  4503.7 1720.64    4546 1719.06  4595.7 1715.98  4600.8 1716.35  4676.9 1711.44
  4766.3  1709.3  4771.3 1709.82    4854 1701.56  4859.1 1702.49    4932 1696.27
  4973.4  1690.3  4980.4 1688.83  4987.6 1685.91  5001.5 1682.82  5029.8 1686.44
  5058.1 1689.35  5107.7  1690.4    5136 1693.13  5157.1 1694.06  5200.6 1698.95
  5230.9 1703.68  5281.1 1707.38  5359.6 1708.17  5438.1 1707.55  5462.9 1706.45
  5493.1 1706.99  5595.1  1705.6  5694.9 1706.85  5916.8 1711.93  6050.8 1716.26
#Mann= 3 , 0 , 0
  4503.7     .05       0  4987.6    .035       0  5029.8     .05       0
Bank Sta=4987.6,5029.8
XS Rating Curve= 0 ,0
Exp/Cntr=0.3,0.1

Type RM Length L Ch R = 1 ,163     ,0,0,0
BEGIN DESCRIPTION:
UNT 0045 IN HEWA 1.0
END DESCRIPTION:
XS GIS Cut Line= 4
      2745240.83     10060739.58       2744813.3     10060581.16
      2744665.73     10060793.83      2744641.87     10061759.14
#Sta/Elev= 30
  4336.4 1711.66  4371.9 1709.72  4445.6 1707.58  4498.9 1703.13  4520.2 1700.13
  4538.3 1699.05    4599 1699.58  4740.3 1694.26  4826.5 1692.48  4948.8 1684.91
  4969.7 1684.41    4978 1682.77  4990.4 1678.68  5005.5 1680.87  5014.3  1684.3
  5026.7 1685.01  5048.1 1683.97  5111.1 1683.68  5201.1 1685.02  5241.2 1686.64
  5341.2 1692.88  5441.2 1697.39  5521.2 1697.29  5551.8 1696.25  5641.3 1698.75
  5731.3 1699.53  5761.3 1701.82  5911.4 1706.11  5971.4 1706.87  6016.8 1708.95
#Mann= 4 ,-1 , 0
  4336.4     .05       0  4969.7     .16       0  4969.7    .035       0
  5014.3     .05       0
Bank Sta=4969.7,5014.3
XS Rating Curve= 0 ,0
Exp/Cntr=0.3,0.1

Chan Stop Cuts=-1
Use User Specified Reach Order=0
Composite Channel Slope=5