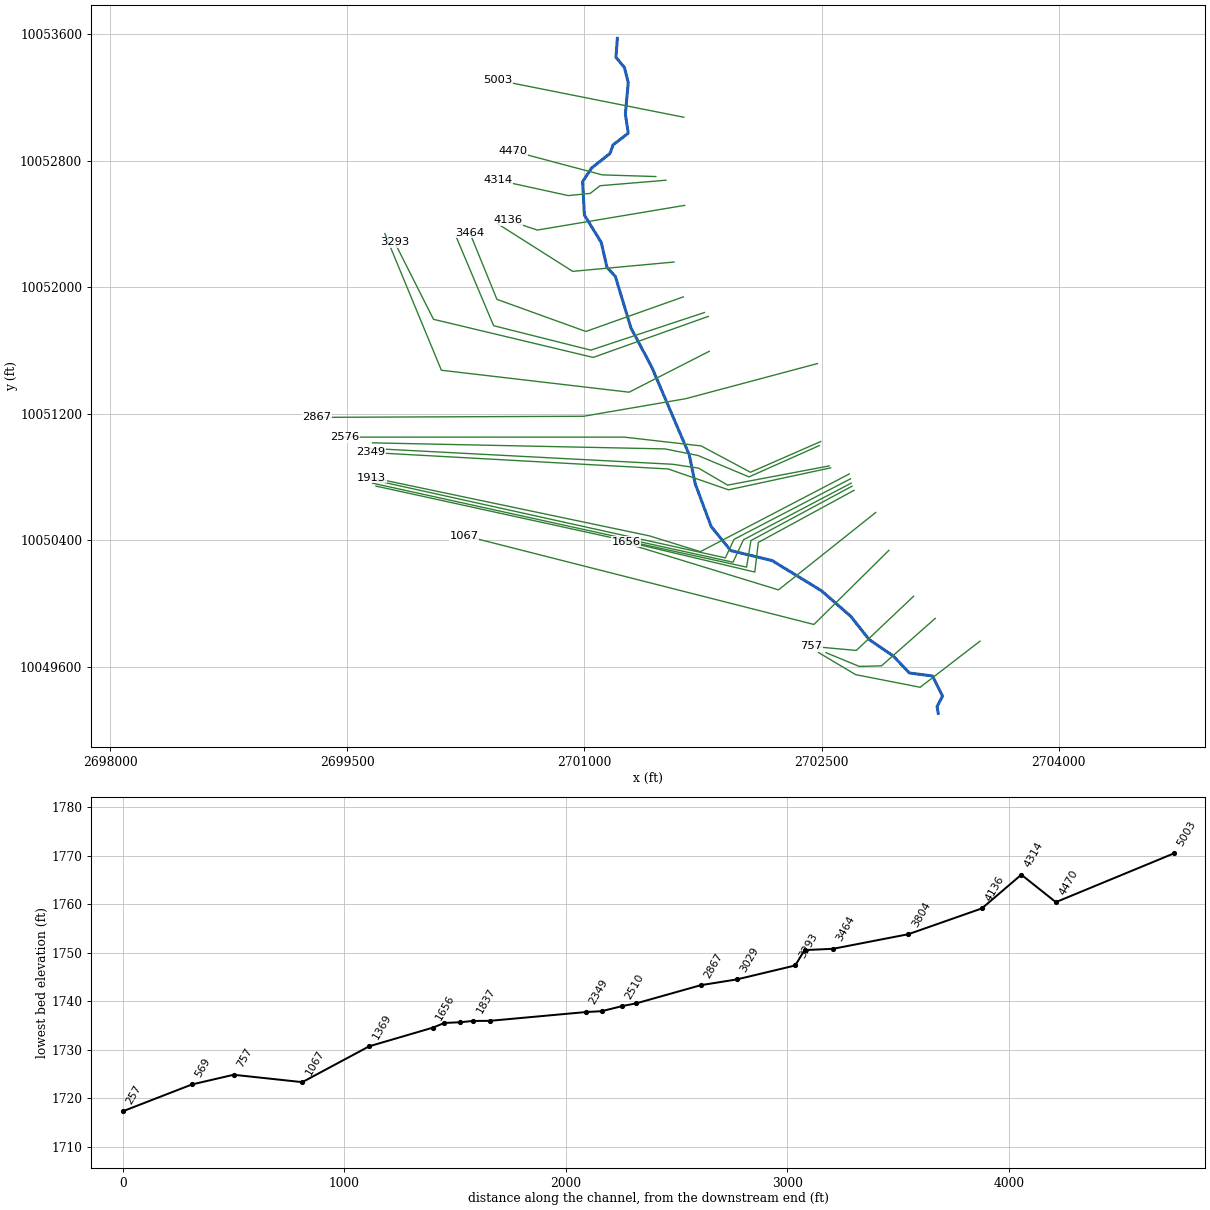
--- UNT 0046 IN HEWA.prj (project) ---

Proj Title=UNT 0046 IN HEWA Base Level Engineering
Current Plan=p01
Default Exp/Contr=0.3,0.1
English Units
Geom File=g01
Flow File=f01
Plan File=p01
Y Axis Title=Elevation
X Axis Title(PF)=Main Channel Distance
X Axis Title(XS)=Station
BEGIN DESCRIPTION:
UNT 0046 IN HEWA
END DESCRIPTION:
DSS Export Rating Curves= 0
DSS Export Rating Curve Sorted= 0
DSS Export Volume Flow Curves= 0
DXF OffsetX= 0
DXF OffsetY= 0
DXF ScaleX= 1
DXF ScaleY= 10

--- UNT 0046 IN HEWA.p01 (plan) ---

Plan Title=Multiple Run
Short Identifier=Multiple
Geom File=g01
Flow File=f01
Subcritical Flow
K Sum by GR= 0
Std Step Tol= 0.01
Critical Tol= 0.01
Num of Std Step Trials= 20
Max Error Tol= 0.3
Flow Tol Ratio= 0.001
Split Flow NTrial= 30
Split Flow Tol= 0.02
Split Flow Ratio= 0.02
Log Output Level= 0
Friction Slope Method= 1
Unsteady Friction Slope Method= 2
Unsteady Bridges Friction Slope Method= 1
Parabolic Critical Depth
Global Vel Dist=  1 , 1 , 1
Global Log Level= 0
CheckData=True
Encroach Param= -1, 0, 0, 0
BEGIN DESCRIPTION:
Multiple Run
END DESCRIPTION:

--- UNT 0046 IN HEWA.f01 (steady flow) ---

Flow Title=Multiple
Number of Profiles=7
Profile Names=10-year,25-year,50-year,1pct_min,100-year,1pct_plu,500-year
River Rch & RM= UNT 0046 IN HEWA,Reach-1,5003
    1390    2061    2652    2488    3365    4551    5416
Boundary for River Rch & Prof#=UNT 0046 IN HEWA,Reach-1,1
Up Type=0
Dn Type=3
Dn Slope=0.005
Boundary for River Rch & Prof#=UNT 0046 IN HEWA,Reach-1,2
Up Type=0
Dn Type=3
Dn Slope=0.005
Boundary for River Rch & Prof#=UNT 0046 IN HEWA,Reach-1,3
Up Type=0
Dn Type=3
Dn Slope=0.005
Boundary for River Rch & Prof#=UNT 0046 IN HEWA,Reach-1,4
Up Type=0
Dn Type=3
Dn Slope=0.005
Boundary for River Rch & Prof#=UNT 0046 IN HEWA,Reach-1,5
Up Type=0
Dn Type=3
Dn Slope=0.005
Boundary for River Rch & Prof#=UNT 0046 IN HEWA,Reach-1,6
Up Type=0
Dn Type=3
Dn Slope=0.005
Boundary for River Rch & Prof#=UNT 0046 IN HEWA,Reach-1,7
Up Type=0
Dn Type=3
Dn Slope=0.005

--- UNT 0046 IN HEWA.g01 (geometry) ---

Geom Title=Existing Conditions
Program Version=4.10

River Reach=UNT 0046 IN HEWA,Reach-1
Reach XY= 30
      2701208.47     10053573.73      2701199.66     10053453.38
      2701253.08     10053389.81      2701277.37     10053293.74
      2701259.27     10053093.75      2701277.34     10052973.87
      2701181.38     10052899.78      2701162.72     10052846.41
      2701044.25     10052752.04      2700989.02     10052667.34
      2700999.87     10052456.35      2701106.54     10052282.95
      2701142.88     10052125.11      2701195.99     10052067.37
      2701294.55     10051741.78      2701425.16     10051496.47
      2701663.19      10050939.9      2701701.39     10050754.94
      2701802.19     10050485.26      2701926.02     10050333.29
       2702187.1     10050270.44      2702500.74     10050078.72
       2702684.4     10049917.92      2702800.89     10049771.24
      2702955.03     10049665.78      2703055.89     10049558.95
      2703202.12     10049540.39      2703265.65     10049412.64
      2703230.81     10049347.87      2703238.47     10049303.73

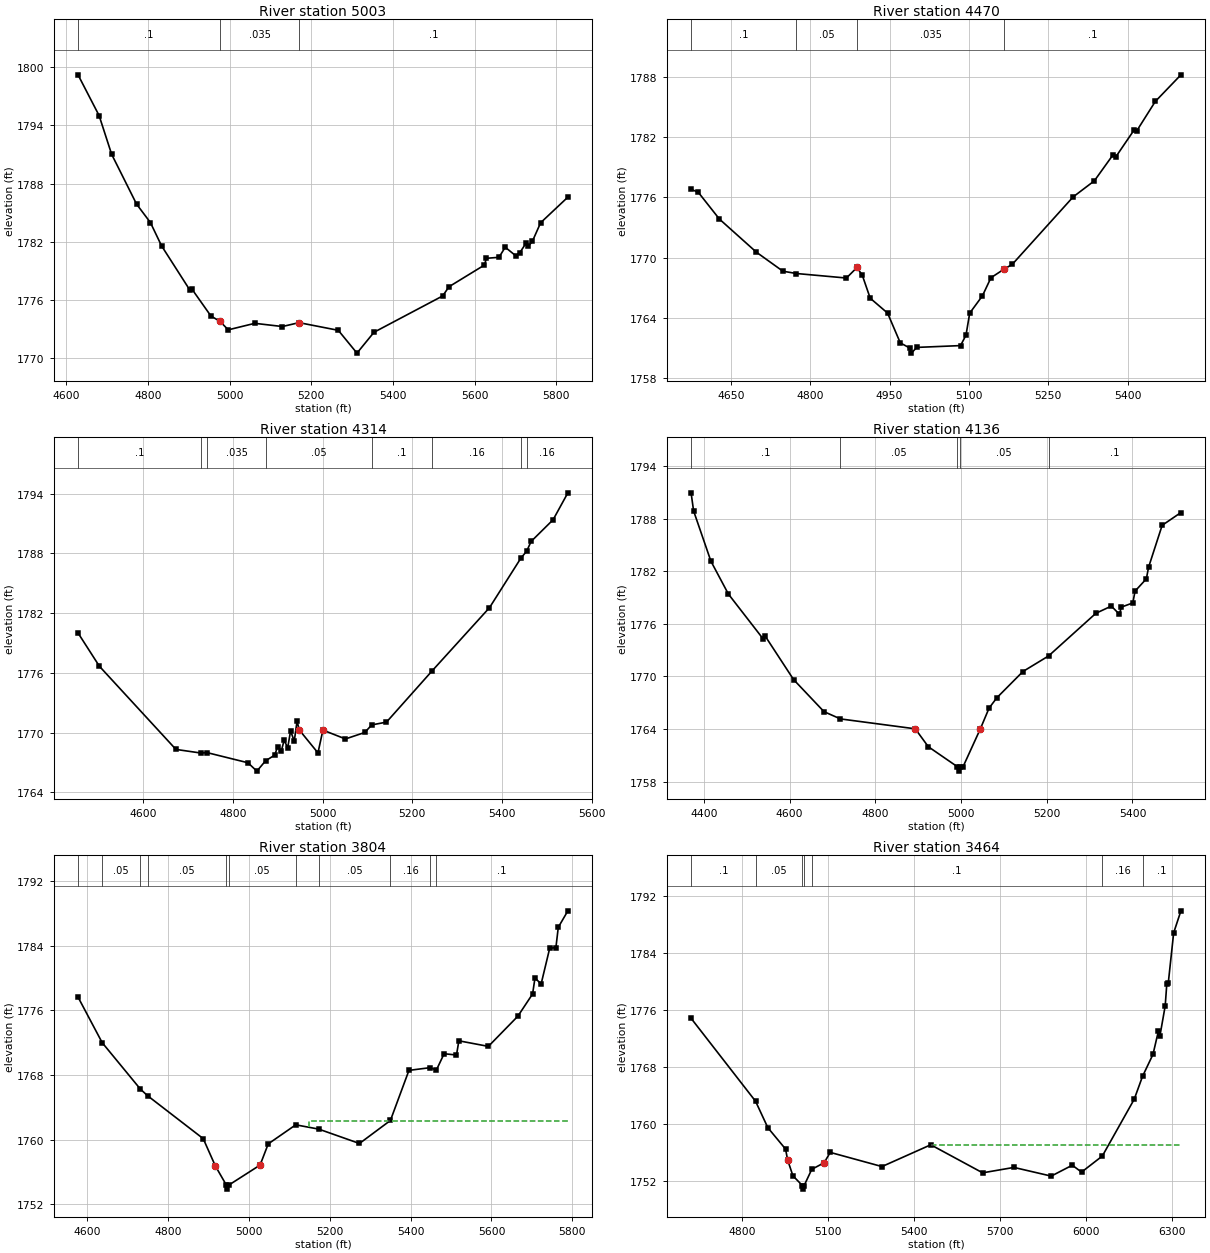
Type RM Length L Ch R = 1 ,5003    ,533,533,533
BEGIN DESCRIPTION:
UNT 0046 IN HEWA 11.0
END DESCRIPTION:
XS GIS Cut Line= 2
      2701629.05     10053074.48      2700453.04     10053308.64
#Sta/Elev= 30
  4629.2  1799.2  4680.8    1795  4711.4 1791.02  4772.5 1785.88  4806.4 1783.98
  4833.7 1781.58  4903.5 1776.99  4908.6 1777.09  4954.6 1774.35  4976.5 1773.81
  4996.9 1772.93  5061.9  1773.6  5129.4 1773.27  5170.2 1773.67  5266.3 1772.88
    5312 1770.53  5353.7 1772.68  5521.8 1776.42  5537.3 1777.37  5623.9  1779.6
    5629  1780.3  5659.6  1780.4    5675 1781.44  5700.4 1780.57  5710.6 1780.87
  5726.1 1781.88  5731.2 1781.52  5741.2 1782.03  5761.6 1783.96  5828.3  1786.6
#Mann= 3 , 0 , 0
  4629.2      .1       0  4976.5    .035       0  5170.2      .1       0
Bank Sta=4976.5,5170.2
XS Rating Curve= 0 ,0
Exp/Cntr=0.3,0.1

Type RM Length L Ch R = 1 ,4470    ,156,156,156
BEGIN DESCRIPTION:
UNT 0046 IN HEWA 10.0
END DESCRIPTION:
XS GIS Cut Line= 3
      2701452.03     10052699.47      2701113.46     10052709.88
      2700545.74     10052860.93
#Sta/Elev= 30
  4574.8  1776.8  4588.4  1776.5  4628.4 1773.83  4698.4 1770.53  4748.4 1768.64
    4774 1768.41  4868.5 1767.96  4888.5 1769.01  4898.5 1768.24  4913.5 1765.95
  4946.3 1764.47  4970.4  1761.5  4988.6 1760.98  4991.3 1760.48  5001.5 1761.05
  5084.3 1761.23  5094.6 1762.27  5101.6 1764.46  5125.7 1766.19  5141.8 1767.99
    5167 1768.86  5181.9 1769.31  5297.2 1776.04  5337.3 1777.64  5372.3 1780.21
  5377.5    1780  5412.4  1782.7  5417.6 1782.63  5452.6 1785.55    5501  1788.2
#Mann= 4 ,-1 , 0
  4574.8      .1       0    4774     .05       0  4888.5    .035       0
    5167      .1       0
Bank Sta=4888.5,5167
XS Rating Curve= 0 ,0
Exp/Cntr=0.3,0.1

Type RM Length L Ch R = 1 ,4314    ,178,178,178
BEGIN DESCRIPTION:
Mapping XS b08d026a
END DESCRIPTION:
XS GIS Cut Line= 5
      2701515.89      10052676.2      2701099.24     10052641.48
      2701036.74     10052592.87      2700897.86     10052578.98
      2700453.41     10052676.21
#Sta/Elev= 30
  4454.9 1780.01  4502.5 1776.67  4673.1 1768.32  4728.1 1767.96  4743.3 1767.99
  4833.6 1766.98  4853.5 1766.14    4873 1767.18  4893.4 1767.75  4899.7  1768.6
  4907.8 1768.13  4914.2 1769.23  4922.3  1768.5  4928.7 1770.19  4936.8 1769.14
  4943.1 1771.16  4947.9 1770.28  4989.7 1767.97  5000.7 1770.26  5050.9 1769.37
    5094 1770.02  5109.5 1770.78  5142.4 1771.06  5244.4 1776.22    5372 1782.55
  5442.2 1787.54  5454.7 1788.21  5464.8  1789.2  5513.8 1791.38  5546.7 1794.08
#Mann= 8 ,-1 , 0
  4454.9      .1       0  4728.1     .05       0  4743.3    .035       0
    4873     .05       0  5109.5      .1       0  5244.4     .16       0
  5442.2      .1       0  5454.7     .16       0
Bank Sta=4947.9,5000.7
XS Rating Curve= 0 ,0
Exp/Cntr=0.3,0.1

Type RM Length L Ch R = 1 ,4136    ,332,332,332
BEGIN DESCRIPTION:
UNT 0046 IN HEWA 9.0
END DESCRIPTION:
XS GIS Cut Line= 3
      2701634.33     10052517.18        2700702.     10052360.93
      2700514.48     10052423.44
#Sta/Elev= 30
  4370.1 1790.96    4376 1788.89  4416.4 1783.15  4457.2  1779.4  4537.7 1774.32
  4542.8 1774.62  4609.3 1769.64  4680.2 1765.98  4718.6 1765.15  4893.2 1764.02
  4923.6 1761.98  4991.6 1759.69  4994.3 1759.19  4997.6 1759.69  5004.7 1759.69
  5045.2 1764.03  5065.5 1766.39  5083.7 1767.57  5144.4 1770.56  5204.3 1772.34
  5314.7 1777.21  5350.8 1778.03  5369.2 1777.11  5374.4 1777.92  5400.8 1778.39
  5406.1 1779.74  5432.4 1781.14  5437.7 1782.48  5469.3 1787.25  5513.1 1788.71
#Mann= 5 ,-1 , 0
  4370.1      .1       0  4718.6     .05       0  4991.6    .035       0
  4997.6     .05       0  5204.3      .1       0
Bank Sta=4893.2,5045.2
XS Rating Curve= 0 ,0
Exp/Cntr=0.3,0.1

Type RM Length L Ch R = 1 ,3804    ,340,340,340
BEGIN DESCRIPTION:
UNT 0046 IN HEWA 8.0
END DESCRIPTION:
XS GIS Cut Line= 3
      2701566.55     10052158.73      2700925.93     10052099.71
      2700446.76     10052403.53
#Sta/Elev= 30
  4578.1 1777.64  4637.8    1772  4731.9 1766.27  4749.8 1765.44  4887.5 1760.12
  4917.6 1756.73  4944.7 1754.37  4947.5 1753.87  4950.7 1754.37  5028.1 1756.85
  5048.2 1759.47  5116.2 1761.83    5173  1761.3  5273.7 1759.52  5350.2 1762.37
    5396 1768.57    5449 1768.91  5463.6 1768.59  5482.9 1770.63  5513.5 1770.47
  5519.4 1772.23  5592.3 1771.54  5665.1 1775.27  5701.6 1778.03  5707.5    1780
  5722.7 1779.27  5743.9 1783.69  5759.2 1783.76  5765.1 1786.28  5788.8 1788.32
#Mann= 11 ,-1 , 0
  4578.1      .1       0  4637.8     .05       0  4731.9      .1       0
  4749.8     .05       0  4944.7    .035       0  4950.7     .05       0
  5116.2      .1       0    5173     .05       0  5350.2     .16       0
    5449     .05       0  5463.6      .1       0
#XS Ineff= 2 , 0
                         5147.73         1762.27
Permanent Ineff=
       T       T
Bank Sta=4917.6,5028.1
XS Rating Curve= 0 ,0
Exp/Cntr=0.3,0.1

Type RM Length L Ch R = 1 ,3464    ,129,129,129
BEGIN DESCRIPTION:
Mapping XS 1377b7f5
END DESCRIPTION:
XS GIS Cut Line= 4
      2701625.61     10051938.26      2701009.26      10051719.5
      2700446.76     10051922.62      2700274.89     10052344.49
#Sta/Elev= 30
  4622.3 1774.86    4847 1763.21  4889.9 1759.49  4951.6 1756.49  4958.8 1754.97
  4977.2 1752.74  5010.4 1751.36  5013.1 1750.86  5016.4 1751.36    5043 1753.64
  5086.2 1754.57  5107.4 1756.02  5287.8 1754.03  5457.9 1757.09  5638.7 1753.15
  5747.7 1753.91  5877.7 1752.69  5951.2 1754.22  5983.5 1753.25  6055.9 1755.51
  6167.1 1763.49  6196.1 1766.71  6232.5 1769.79  6251.1 1773.01  6256.5 1772.34
  6275.1 1776.61  6280.6 1779.67    6286 1779.89  6304.6 1786.87  6329.9 1789.96
#Mann= 7 ,-1 , 0
  4622.3      .1       0    4847     .05       0  5010.4    .035       0
  5016.4     .05       0    5043      .1       0  6055.9     .16       0
  6196.1      .1       0
#XS Ineff= 2 , 0
                         5457.96         1757.11
Permanent Ineff=
       T       T
Bank Sta=4958.8,5086.2
XS Rating Curve= 0 ,0
Exp/Cntr=0.3,0.1

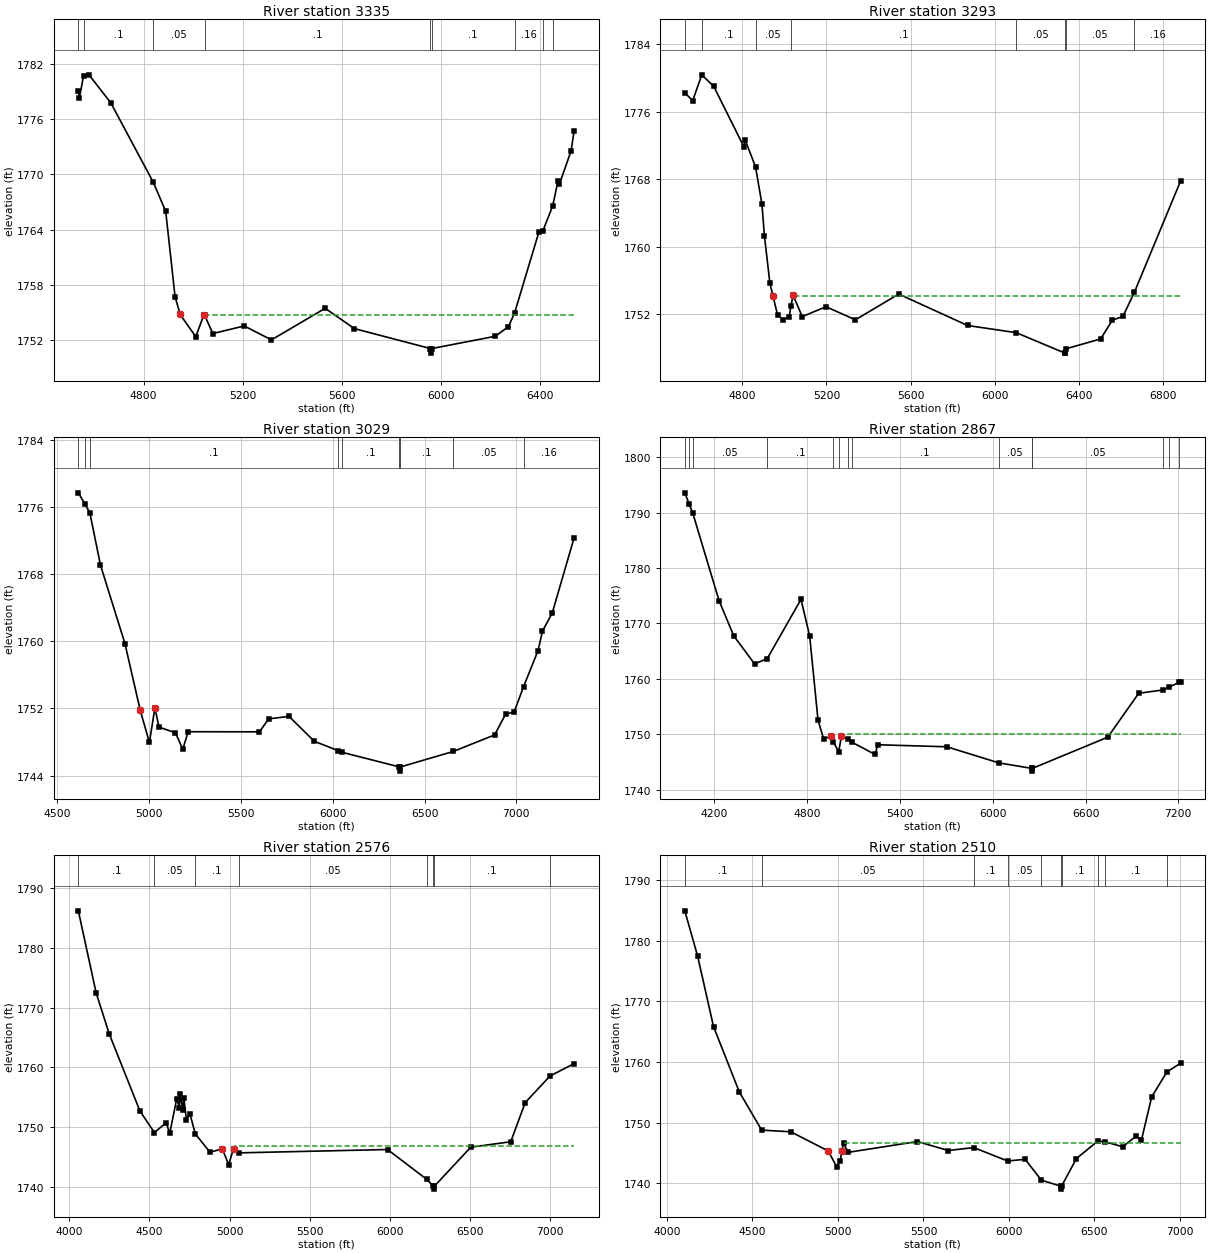
Type RM Length L Ch R = 1 ,3335    ,42,42,42
BEGIN DESCRIPTION:
Mapping XS a29f9156
END DESCRIPTION:
XS GIS Cut Line= 4
      2701759.29      10051839.3      2701040.51     10051601.44
      2700425.93     10051755.96      2700188.41     10052319.42
#Sta/Elev= 30
  4536.1 1779.06  4540.1 1778.27  4557.3 1780.73  4579.1 1780.82  4666.9 1777.79
  4839.2 1769.13  4888.9 1765.99  4926.7 1756.73  4947.1 1754.79  5010.5 1752.37
  5042.2 1754.69  5045.8 1754.73  5079.2 1752.72  5206.1 1753.54  5315.9 1752.03
  5532.9 1755.46  5651.1 1753.25  5957.7 1751.09  5960.5 1750.59  5963.7 1751.09
  6219.7 1752.42  6272.6 1753.46  6297.5 1754.93  6396.6  1763.8  6411.3 1763.81
  6451.8 1766.59  6473.2  1769.3  6478.6 1768.92  6526.1 1772.57  6538.4 1774.77
#Mann= 9 ,-1 , 0
  4536.1     .05       0  4557.3      .1       0  4839.2     .05       0
  5045.8      .1       0  5957.7    .035       0  5963.7      .1       0
  6297.5     .16       0  6411.3      .1       0  6451.8     .16       0
#XS Ineff= 2 , 0
                            5048         1754.75
Permanent Ineff=
       T       T
Bank Sta=4947.1,5042.2
XS Rating Curve= 0 ,0
Exp/Cntr=0.3,0.1

Type RM Length L Ch R = 1 ,3293    ,264,264,264
BEGIN DESCRIPTION:
UNT 0046 IN HEWA 7.0
END DESCRIPTION:
XS GIS Cut Line= 4
      2701783.65     10051814.67      2701055.62     10051555.31
      2700045.42     10051796.48      2699799.71     10052283.36
#Sta/Elev= 30
  4526.8 1778.23  4564.2 1777.27  4607.5 1780.34  4664.3 1778.98  4807.8 1771.82
  4813.1 1772.67    4863 1769.46  4893.2 1765.09  4905.6 1761.23  4931.1 1755.72
  4946.3 1754.13  4967.5 1751.97  4992.8 1751.35  5023.6 1751.73  5031.2 1753.03
  5041.9 1754.24  5085.2 1751.74  5197.9 1752.91  5337.8 1751.36  5543.5 1754.41
  5870.8 1750.69  6102.2 1749.84  6333.9 1747.42  6334.4 1747.42  6337.1 1747.92
  6503.4  1749.1  6559.1 1751.32  6609.3 1751.76  6663.5  1754.6  6883.6 1767.79
#Mann= 8 ,-1 , 0
  4526.8     .05       0  4607.5      .1       0    4863     .05       0
  5031.2      .1       0  6102.2     .05       0  6334.4    .035       0
  6337.1     .05       0  6663.5     .16       0
#XS Ineff= 2 , 0
                         5043.58         1754.22
Permanent Ineff=
       T       T
Bank Sta=4946.3,5041.9
XS Rating Curve= 0 ,0
Exp/Cntr=0.3,0.1

Type RM Length L Ch R = 1 ,3029    ,162,162,162
BEGIN DESCRIPTION:
Mapping XS a05e51b5
END DESCRIPTION:
XS GIS Cut Line= 4
      2701789.75     10051594.02      2701282.84     10051335.35
      2700095.34     10051474.24      2699737.71      10052338.8
#Sta/Elev= 30
  4614.5 1777.67  4650.6 1776.34  4677.3 1775.28    4735 1769.07  4868.3 1759.73
  4951.6 1751.78  5001.7 1747.95  5031.3 1752.06  5053.8 1749.78  5143.6  1749.1
  5183.2 1747.15  5212.9 1749.23  5600.8 1749.22  5651.1 1750.76  5761.9 1751.06
  5899.6 1748.09  6028.4 1746.99  6049.1 1746.79    6363 1745.04  6365.7 1744.54
    6369 1745.04  6656.3 1746.88  6881.5 1748.85  6941.4 1751.32  6987.9 1751.58
  7039.5 1754.61  7118.3  1758.9  7142.2 1761.21  7195.4 1763.36  7314.8 1772.34
#Mann= 9 ,-1 , 0
  4614.5      .1       0  4650.6     .05       0  4677.3      .1       0
  6028.4     .05       0  6049.1      .1       0    6363     .07       0
    6369      .1       0  6656.3     .05       0  7039.5     .16       0
#XS Ineff= 2 , 0
                         5031.86         1751.98
Permanent Ineff=
       T       T
Bank Sta=4951.6,5031.3
XS Rating Curve= 0 ,0
Exp/Cntr=0.3,0.1

Type RM Length L Ch R = 1 ,2867    ,291,291,291
BEGIN DESCRIPTION:
UNT 0046 IN HEWA 6.0
END DESCRIPTION:
XS GIS Cut Line= 4
      2702474.27     10051516.49      2701640.91     10051294.26
      2700995.08     10051183.15      2699307.59     10051176.21
#Sta/Elev= 30
  4009.6 1793.57  4037.5 1791.57  4060.6 1789.96  4230.8 1774.14  4326.1 1767.76
  4460.6 1762.71  4542.7 1763.66  4760.8 1774.35  4816.8 1767.74  4870.8 1752.54
  4907.4 1749.16  4955.7 1749.66  4969.3 1748.63  5004.8  1746.9  5022.2 1749.68
    5064 1749.15  5087.9 1748.61  5239.8 1746.36  5256.8 1748.12    5704 1747.75
    6038 1744.86    6251 1743.86  6253.8 1743.36    6257 1743.86    6744 1749.49
    6944 1757.41  7102.1 1758.01    7140 1758.52  7204.7 1759.36  7214.9 1759.49
#Mann= 14 ,-1 , 0
  4009.6     .05       0  4037.5      .1       0  4060.6     .05       0
  4542.7      .1       0  4969.3     .05       0  5004.8      .1       0
    5064     .05       0  5087.9      .1       0    6038     .05       0
    6251    .035       0    6257     .05       0  7102.1      .1       0
    7140     .05       0  7204.7      .1       0
#XS Ineff= 2 , 0
                         5028.03            1750
Permanent Ineff=
       T       T
Bank Sta=4955.7,5022.2
XS Rating Curve= 0 ,0
Exp/Cntr=0.3,0.1

Type RM Length L Ch R = 1 ,2576    ,66,66,66
BEGIN DESCRIPTION:
Mapping XS b1859af8
END DESCRIPTION:
XS GIS Cut Line= 5
      2702495.05     10051023.42      2702050.63     10050828.98
      2701738.13     10050995.65      2701252.02     10051051.21
      2699482.35     10051051.21
#Sta/Elev= 30
  4055.4  1786.2  4166.6 1772.48  4248.1 1765.63  4440.2  1752.7  4530.6 1749.09
  4604.5 1750.75  4626.4 1748.96  4670.4 1754.77  4686.7 1753.25  4692.3 1755.56
  4708.6 1752.82  4714.3 1754.93  4730.6 1751.27  4752.5 1752.24  4786.3 1748.87
  4878.6 1745.78  4954.7 1746.38    4995 1743.71  5025.2 1746.42  5058.2 1745.69
  5987.5 1746.25    6231 1741.28  6274.5 1740.12  6277.2 1739.62  6280.5 1740.12
  6507.5 1746.64  6757.5 1747.55  6847.5  1754.1  7002.9 1758.56  7153.6 1760.63
#Mann= 8 ,-1 , 0
  4055.4      .1       0  4530.6     .05       0  4786.3      .1       0
  5058.2     .05       0    6231      .1       0  6274.5     .07       0
  6280.5      .1       0  7002.9     .05       0
#XS Ineff= 2 , 0
                          5034.7         1746.86
Permanent Ineff=
       T       T
Bank Sta=4954.7,5025.2
XS Rating Curve= 0 ,0
Exp/Cntr=0.3,0.1

Type RM Length L Ch R = 1 ,2510    ,91,91,91
BEGIN DESCRIPTION:
Mapping XS 04a693d4
END DESCRIPTION:
XS GIS Cut Line= 5
      2702485.75     10050997.53      2702041.27      10050799.6
      2701718.36     10050935.02      2701510.02     10050976.68
       2699659.3     10051014.88
#Sta/Elev= 30
    4104 1784.93    4179 1777.46  4271.9 1765.85  4422.3  1755.1  4553.5 1748.76
  4723.7 1748.49  4943.2 1745.32  4991.6 1742.74  5013.9 1743.72  5022.2 1745.35
  5032.4 1746.57  5059.8  1745.1  5464.8 1746.88  5644.8  1745.4  5794.6 1745.88
  5992.1 1743.67  6094.9 1743.95  6189.7 1740.51    6302 1739.53  6304.7 1739.03
    6308 1739.53    6395 1744.08  6518.6 1746.93  6559.4 1746.86  6665.1 1746.02
  6745.1 1747.79  6775.1 1747.11  6835.1 1754.26  6924.4 1758.36  7004.3 1759.81
#Mann= 10 ,-1 , 0
    4104      .1       0  4553.5     .05       0  5794.6      .1       0
  5992.1     .05       0  6189.7      .1       0    6302     .04       0
    6308      .1       0  6518.6     .05       0  6559.4      .1       0
  6924.4     .05       0
#XS Ineff= 2 , 0
                         5032.51         1746.62
Permanent Ineff=
       T       T
Bank Sta=4943.2,5022.2
XS Rating Curve= 0 ,0
Exp/Cntr=0.3,0.1

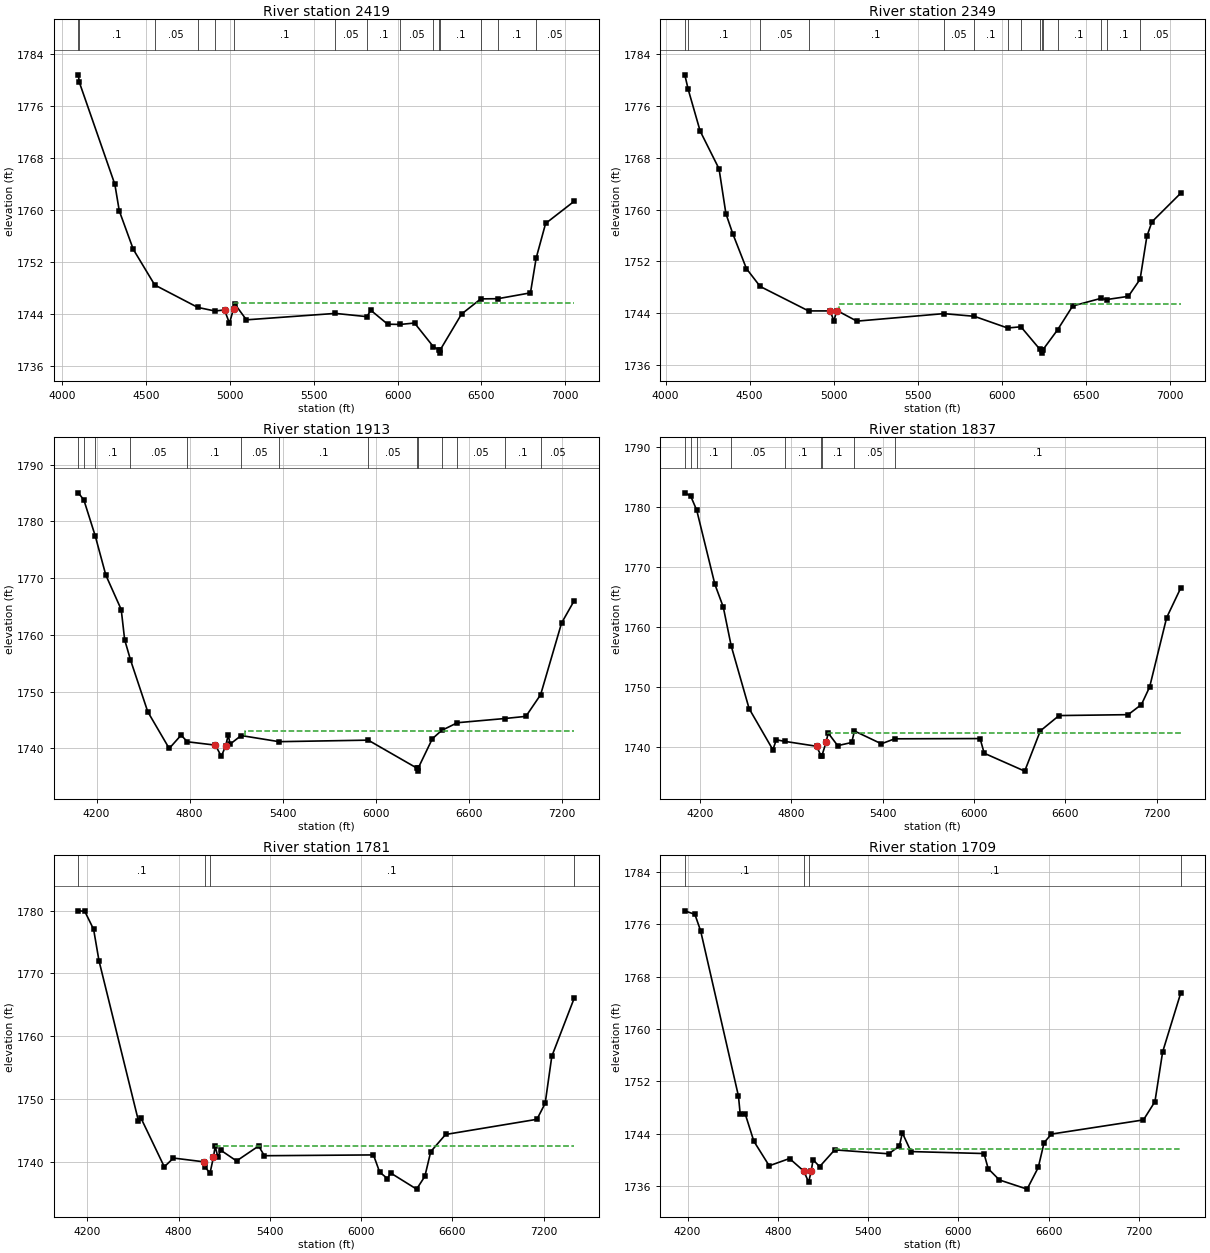
Type RM Length L Ch R = 1 ,2419    ,70,70,70
BEGIN DESCRIPTION:
Mapping XS 7c59ff2e
END DESCRIPTION:
XS GIS Cut Line= 5
      2702548.26     10050869.05      2701905.86     10050747.52
      2701721.83     10050855.16      2701558.63     10050879.46
      2699638.46     10050980.16
#Sta/Elev= 30
  4097.8 1780.79  4103.2 1779.69  4315.5 1763.94  4341.8 1759.87  4425.3 1753.95
  4553.2 1748.47  4809.7 1745.02  4911.6 1744.47    4969 1744.63  4998.5 1742.57
  5022.9 1744.85  5028.9 1745.59  5099.6 1743.11  5629.7  1744.1  5817.3  1743.6
  5840.9 1744.58  5941.1 1742.44  6015.4  1742.4  6101.3 1742.62  6213.5 1738.98
  6248.5 1738.49  6251.2 1737.99  6254.5 1738.49  6381.7    1744  6496.1 1746.33
  6597.9 1746.36  6792.2 1747.26  6826.1  1752.6  6882.4 1757.93  7052.6 1761.34
#Mann= 15 ,-1 , 0
  4097.8     .05       0  4103.2      .1       0  4553.2     .05       0
  4809.7      .1       0  4911.6     .05       0  5022.9      .1       0
  5629.7     .05       0  5817.3      .1       0  6015.4     .05       0
  6213.5      .1       0  6248.5     .04       0  6254.5      .1       0
  6496.1     .05       0  6597.9      .1       0  6826.1     .05       0
#XS Ineff= 2 , 0
                         5028.22         1745.63
Permanent Ineff=
       T       T
Bank Sta=4969,5022.9
XS Rating Curve= 0 ,0
Exp/Cntr=0.3,0.1

Type RM Length L Ch R = 1 ,2349    ,436,436,436
BEGIN DESCRIPTION:
UNT 0046 IN HEWA 5.0
END DESCRIPTION:
XS GIS Cut Line= 4
      2702557.61     10050856.77      2701911.74     10050717.87
       2701529.8     10050849.82       2699647.9     10050953.98
#Sta/Elev= 30
  4114.3 1780.81  4134.1  1778.6  4205.5 1772.13    4318 1766.29  4358.9 1759.36
  4399.8 1756.26    4481 1750.87  4562.6 1748.12  4850.4 1744.34  4979.4 1744.34
  5000.6 1742.82  5019.5  1744.4  5138.1 1742.76  5654.8 1743.92  5836.5 1743.51
  6034.7  1741.7  6113.7 1741.89  6225.9 1738.43    6238 1738.32  6240.8 1737.82
    6244 1738.32  6331.8 1741.42  6421.6  1745.1    6588 1746.27  6624.8  1746.1
  6752.8 1746.59  6822.8 1749.24  6862.9 1755.84    6893  1758.1  7063.8 1762.51
#Mann= 15 ,-1 , 0
  4114.3     .05       0  4134.1      .1       0  4562.6     .05       0
  4850.4      .1       0  5654.8     .05       0  5836.5      .1       0
  6034.7     .05       0  6113.7      .1       0  6225.9     .05       0
    6238     .07       0    6244     .05       0  6331.8      .1       0
    6588     .05       0  6624.8      .1       0  6822.8     .05       0
#XS Ineff= 2 , 0
                         5031.48         1745.37
Permanent Ineff=
       T       T
Bank Sta=4979.4,5019.5
XS Rating Curve= 0 ,0
Exp/Cntr=0.3,0.1

Type RM Length L Ch R = 1 ,1913    ,76,76,76
BEGIN DESCRIPTION:
UNT 0046 IN HEWA 4.0
END DESCRIPTION:
XS GIS Cut Line= 4
      2702675.59     10050818.14      2701733.64     10050326.69
      2701410.56      10050426.8      2699654.09     10050795.38
#Sta/Elev= 30
  4082.8 1785.04  4118.6 1783.77  4191.7 1777.45  4260.1 1770.53  4359.2 1764.47
  4381.3 1759.16  4418.9  1755.6  4530.3 1746.46  4668.5 1739.99    4745 1742.34
  4785.6 1741.17  4966.4 1740.58  5004.4 1738.59  5032.7  1740.5  5049.1 1742.38
  5060.8 1740.75  5132.1 1742.27  5376.5 1741.19    5951 1741.46  6266.6  1736.5
  6269.4    1736  6272.6  1736.5  6364.3 1741.71  6423.8 1743.16  6525.6 1744.53
  6830.8 1745.27  6967.2 1745.65    7062 1749.46  7197.1  1762.1  7278.2 1766.02
#Mann= 14 ,-1 , 0
  4082.8      .1       0  4118.6     .05       0  4191.7      .1       0
  4418.9     .05       0  4785.6      .1       0  5132.1     .05       0
  5376.5      .1       0    5951     .05       0  6266.6     .07       0
  6272.6     .05       0  6423.8      .1       0  6525.6     .05       0
  6830.8      .1       0    7062     .05       0
#XS Ineff= 2 , 0
                         5154.54         1743.14
Permanent Ineff=
       T       T
Bank Sta=4966.4,5032.7
XS Rating Curve= 0 ,0
Exp/Cntr=0.3,0.1

Type RM Length L Ch R = 1 ,1837    ,56,56,56
BEGIN DESCRIPTION:
Mapping XS 7c1365cc
END DESCRIPTION:
XS GIS Cut Line= 4
       2702683.5     10050787.43      2701946.53     10050404.62
      2701891.84     10050287.43      2699648.62      10050783.5
#Sta/Elev= 30
  4099.7 1782.31  4138.1 1781.79    4178 1779.42  4297.3 1767.08  4352.4  1763.3
  4404.5 1756.83  4522.3 1746.38  4678.5 1739.53  4700.6  1741.2  4755.1 1740.94
  4965.4 1740.12  4994.4 1738.55  5000.4 1738.55  5028.5 1740.84  5041.5 1742.33
    5104 1740.22  5196.2 1740.75  5214.2 1742.66    5391 1740.53  5478.4 1741.36
  6039.5  1741.4  6066.6 1738.96  6332.6 1735.98  6435.3 1742.68  6558.2 1745.23
  7012.3 1745.38  7099.6 1747.07  7153.5    1750  7264.9 1761.52  7356.9 1766.43
#Mann= 9 ,-1 , 0
  4099.7      .1       0  4138.1     .05       0    4178      .1       0
  4404.5     .05       0  4755.1      .1       0  4994.4     .07       0
  5000.4      .1       0  5214.2     .05       0  5478.4      .1       0
#XS Ineff= 2 , 0
                         5040.11         1742.39
Permanent Ineff=
       T       T
Bank Sta=4965.4,5028.5
XS Rating Curve= 0 ,0
Exp/Cntr=0.3,0.1

Type RM Length L Ch R = 1 ,1781    ,72,72,72
BEGIN DESCRIPTION:
Mapping XS 95bc2793
END DESCRIPTION:
XS GIS Cut Line= 4
      2702687.38     10050760.07      2702006.43     10050402.02
      2701940.02     10050260.09      2699659.12     10050760.04
#Sta/Elev= 30
  4140.1 1779.96  4182.2 1779.89  4240.6 1777.02    4276 1772.02  4534.9 1746.62
  4551.2 1747.05  4705.5 1739.26    4766 1740.65    4966 1740.05  4973.8 1739.22
  5006.1 1738.24    5029 1740.82    5040 1742.52  5057.3 1740.89    5078 1741.88
  5180.7 1740.19  5326.1 1742.57  5363.4 1741.02  6081.2 1741.15  6122.2  1738.4
  6173.4 1737.39  6193.9 1738.28  6364.9 1735.71  6419.2 1737.74  6457.9 1741.67
  6555.8  1744.4  7156.2 1746.81  7210.4 1749.34  7254.2 1756.83  7401.2 1766.05
#Mann= 4 ,-1 , 0
  4140.1      .1       0  4973.8     .05       0  5006.1      .1       0
  7401.2      .1       0
#XS Ineff= 2 , 0
                         5040.11         1742.64
Permanent Ineff=
       T       T
Bank Sta=4966,5029
XS Rating Curve= 0 ,0
Exp/Cntr=0.3,0.1

Type RM Length L Ch R = 1 ,1709    ,53,53,53
BEGIN DESCRIPTION:
Mapping XS af58c92b
END DESCRIPTION:
XS GIS Cut Line= 4
      2702692.64     10050740.57       2702053.3     10050396.81
      2702025.96     10050228.84      2699681.72     10050741.43
#Sta/Elev= 30
    4182 1778.03  4249.2 1777.49  4287.4 1774.96  4538.7 1749.76  4550.3    1747
  4582.8  1747.1  4640.9 1742.88  4743.1 1739.13  4878.2 1740.24    4973 1738.32
  5005.2 1736.63  5022.5 1738.36  5034.5 1740.06  5078.1    1739  5178.2 1741.56
  5537.8 1740.96  5607.8 1742.14  5628.3 1744.14  5685.4  1741.3  6170.8    1741
  6198.7 1738.69  6273.1 1736.97  6457.2 1735.57  6531.5 1738.88    6570 1742.66
  6619.2 1743.97  7230.6 1746.13    7307 1748.92  7358.2 1756.51  7477.7 1765.43
#Mann= 4 ,-1 , 0
    4182      .1       0    4973     .05       0  5005.2      .1       0
  7477.7      .1       0
#XS Ineff= 2 , 0
                         5178.41         1741.64
Permanent Ineff=
       T       T
Bank Sta=4973,5022.5
XS Rating Curve= 0 ,0
Exp/Cntr=0.3,0.1

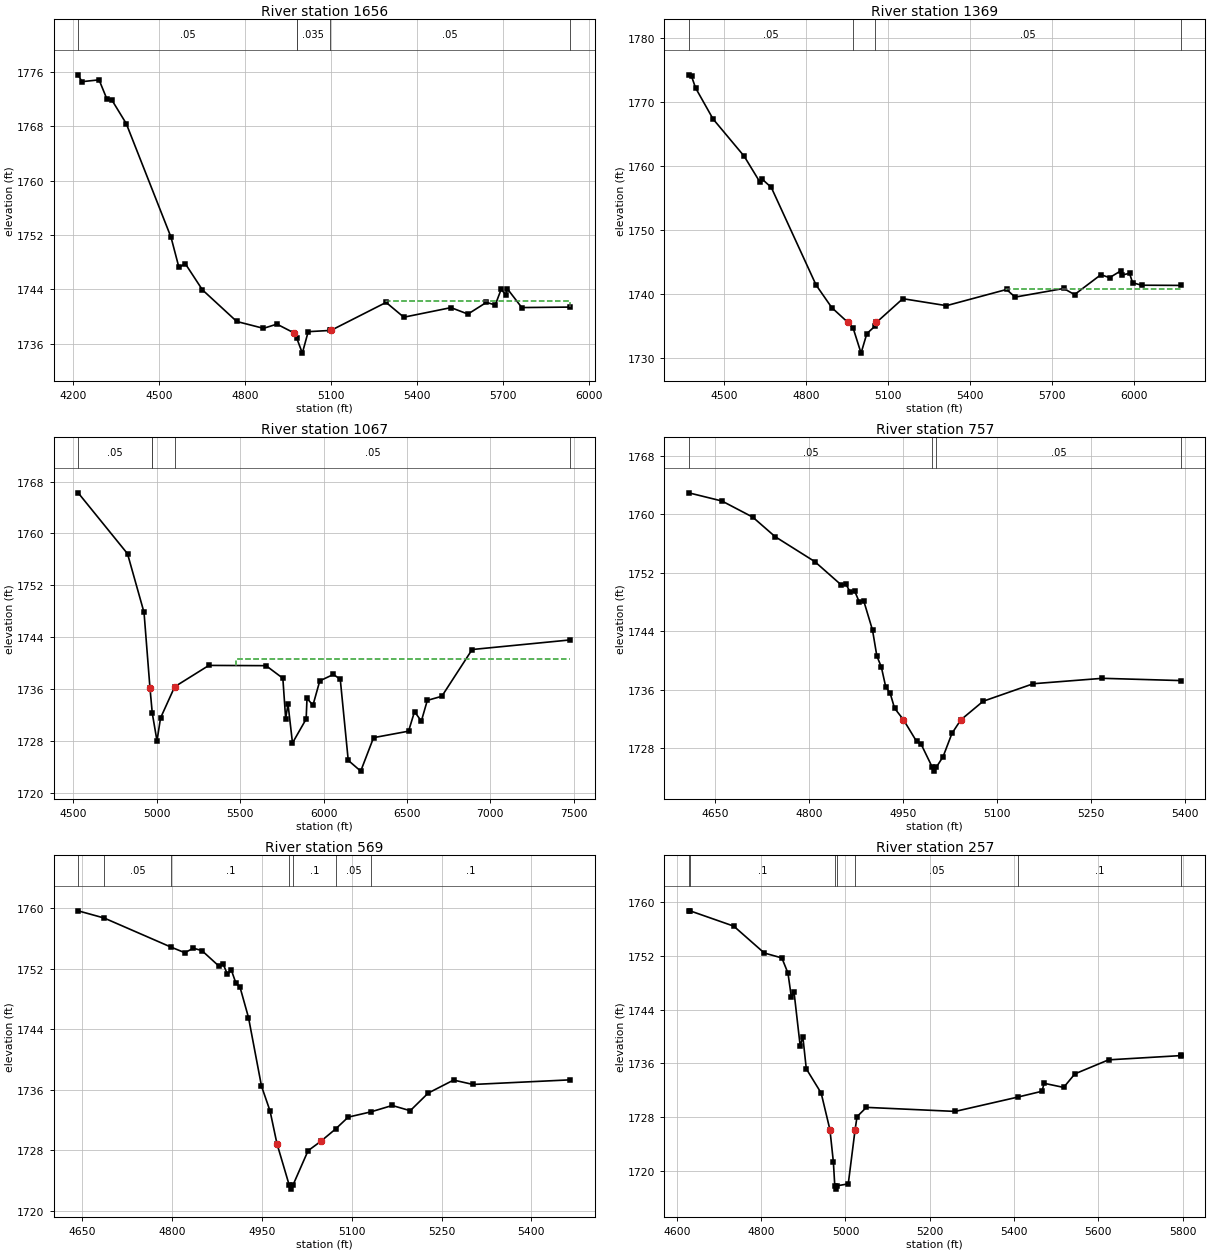
Type RM Length L Ch R = 1 ,1656    ,287,287,287
BEGIN DESCRIPTION:
Mapping XS ccbcad99
END DESCRIPTION:
XS GIS Cut Line= 4
      2702705.68     10050714.54      2702100.18     10050385.09
      2702078.04     10050197.59      2701264.27     10050390.29
#Sta/Elev= 30
  4219.1 1775.57  4232.1 1774.56    4292 1774.83  4319.5 1771.98  4335.7 1771.92
  4386.7 1768.39  4542.7 1751.65  4570.3  1747.2  4592.1 1747.78    4652 1743.91
  4771.7 1739.25  4864.8 1738.24  4911.6 1738.86  4970.5 1737.58  4980.3 1736.84
  5000.2 1734.59  5020.6 1737.75  5096.7 1737.93  5099.6 1737.93    5292 1742.06
  5353.7 1739.88  5518.1 1741.29  5577.1 1740.34  5641.4 1742.06  5672.3 1741.68
  5692.8 1743.98    5709 1743.17  5714.1 1744.08  5764.8  1741.3  5933.5 1741.37
#Mann= 5 ,-1 , 0
  4219.1     .05       0  4980.3      .1       0  4980.3    .035       0
  5096.7     .05       0  5933.5      .1       0
#XS Ineff= 2 , 0
                         5292.27         1742.27
Permanent Ineff=
       T       T
Bank Sta=4970.5,5099.6
XS Rating Curve= 0 ,0
Exp/Cntr=0.3,0.1

Type RM Length L Ch R = 1 ,1369    ,302,302,302
BEGIN DESCRIPTION:
UNT 0046 IN HEWA 3.0
END DESCRIPTION:
XS GIS Cut Line= 3
      2702842.64     10050574.47      2702228.05     10050084.88
      2701259.28     10050381.77
#Sta/Elev= 30
    4371 1774.31  4381.5 1774.05  4395.9 1772.27  4459.9  1767.4  4573.7 1761.57
  4631.3 1757.52  4637.7 1758.05  4672.9 1756.68  4836.6 1741.41    4894 1737.87
  4951.6 1735.61  4972.4 1734.62    5001 1730.75  5022.1  1733.8  5050.9 1734.93
  5057.3 1735.56  5153.7 1739.27  5313.2 1738.18  5532.8 1740.71  5564.2 1739.52
    5742 1740.87  5781.4 1739.91    5878 1743.03  5909.4 1742.56  5950.4 1743.62
  5955.7 1742.97  5982.6 1743.25  5993.6 1741.77  6026.4 1741.38    6170 1741.35
#Mann= 4 ,-1 , 0
    4371     .05       0  4972.4    .035       0  5050.9     .05       0
    6170      .1       0
#XS Ineff= 2 , 0
                         5532.67         1740.76
Permanent Ineff=
       T       T
Bank Sta=4951.6,5057.3
XS Rating Curve= 0 ,0
Exp/Cntr=0.3,0.1

Type RM Length L Ch R = 1 ,1067    ,310,310,310
BEGIN DESCRIPTION:
UNT 0046 IN HEWA 2.0
END DESCRIPTION:
XS GIS Cut Line= 3
      2702925.97     10050334.89        2702452.     10049866.13
      2700238.47     10050428.63
#Sta/Elev= 30
  4528.4 1766.27  4824.4 1756.88  4923.4 1747.83  4958.8 1736.25    4973 1732.27
  5001.2 1728.02  5022.4 1731.55  5107.3 1736.37  5312.2 1739.66    5655 1739.62
  5755.8 1737.68  5772.6 1731.47  5786.8 1733.69  5813.6  1727.7  5895.5 1731.39
  5900.6 1734.57  5936.4 1733.53  5977.3 1737.28  6059.2 1738.27  6100.1 1737.51
  6147.9 1725.02  6222.7 1723.36  6299.7 1728.52  6509.5 1729.52  6545.3 1732.53
  6586.2 1731.07    6622 1734.27    6709  1734.9  6890.8 1742.11  7478.9 1743.59
#Mann= 5 ,-1 , 0
  4528.4     .05       0    4973      .1       0    4973    .035       0
  5107.3     .05       0  7478.9     .05       0
#XS Ineff= 2 , 0
                            5475         1740.59
Permanent Ineff=
       T       T
Bank Sta=4958.8,5107.3
XS Rating Curve= 0 ,0
Exp/Cntr=0.3,0.1

Type RM Length L Ch R = 1 ,757     ,188,188,188
BEGIN DESCRIPTION:
Mapping XS a3f08a86
END DESCRIPTION:
XS GIS Cut Line= 3
      2703082.56      10050044.7      2702720.14     10049701.81
      2702433.64     10049727.86
#Sta/Elev= 30
  4607.4 1762.96  4660.5 1761.84  4709.8 1759.63  4745.4 1756.97  4808.9 1753.55
  4851.4 1750.34  4858.7 1750.45  4865.6 1749.37  4872.9 1749.47  4879.7 1748.08
    4887 1748.22  4901.2 1744.17  4908.1 1740.64  4915.3 1739.12  4922.2 1736.45
  4929.5 1735.51  4936.4 1733.49  4950.5 1731.93  4971.6 1728.95  4978.8 1728.58
  4996.9 1725.38  4999.6 1724.88  5002.9 1725.38    5014 1726.86  5028.2 1730.05
  5042.4  1731.9    5078 1734.44  5158.2 1736.84  5268.7 1737.58    5394 1737.27
#Mann= 4 ,-1 , 0
  4607.4     .05       0  4996.9    .035       0  5002.9     .05       0
    5394      .1       0
Bank Sta=4950.5,5042.4
XS Rating Curve= 0 ,0
Exp/Cntr=0.3,0.1

Type RM Length L Ch R = 1 ,569     ,312,312,312
BEGIN DESCRIPTION:
Mapping XS d8afa85a
END DESCRIPTION:
XS GIS Cut Line= 4
       2703219.4     10049904.62      2702879.13     10049604.28
      2702738.51     10049600.81      2702528.46      10049687.6
#Sta/Elev= 30
    4643 1759.69  4686.4 1758.74  4798.8 1754.87  4821.2 1754.15  4835.4 1754.75
  4849.7 1754.43  4878.1 1752.38  4884.8  1752.7  4892.3 1751.32    4899 1751.82
  4906.6  1750.1  4913.2 1749.63  4927.5 1745.58  4949.2 1736.51  4963.5 1733.22
    4975 1728.91  4995.6 1723.39  4998.3 1722.89  5001.6 1723.39    5027 1727.97
  5047.9 1729.19  5073.2 1730.86    5094 1732.41  5132.1 1733.11  5167.5 1733.95
  5197.6 1733.26  5227.6 1735.59    5270 1737.31  5302.5 1736.73  5464.8 1737.34
#Mann= 7 ,-1 , 0
    4643      .1       0  4686.4     .05       0  4798.8      .1       0
  4995.6     .07       0  5001.6      .1       0  5073.2     .05       0
  5132.1      .1       0
Bank Sta=4975,5047.9
XS Rating Curve= 0 ,0
Exp/Cntr=0.3,0.1

Type RM Length L Ch R = 1 ,257     ,0,0,0
BEGIN DESCRIPTION:
UNT 0046 IN HEWA 1.0
END DESCRIPTION:
XS GIS Cut Line= 4
      2703502.43     10049760.56      2703123.92     10049468.86
      2702715.94     10049548.72      2702480.35     10049689.04
#Sta/Elev= 30
    4628 1758.62    4631 1758.65  4734.8 1756.38  4807.3 1752.39    4849 1751.66
  4863.5 1749.41  4871.6 1745.83    4878 1746.54  4892.5  1738.6  4898.8 1739.97
    4907 1735.21  4942.3 1731.61  4963.1 1726.17  4971.3 1721.37  4974.6 1717.86
  4977.4 1717.36  4980.6 1717.86  5006.6 1718.14  5022.7 1726.12  5027.4 1728.11
  5049.6 1729.49  5260.3 1728.89  5409.3 1731.02  5466.3 1731.88  5471.4 1733.06
  5517.8 1732.45  5544.4 1734.46  5624.3 1736.54  5795.6 1737.17  5795.8 1737.21
#Mann= 7 ,-1 , 0
    4628     .05       0    4631      .1       0  4974.6     .07       0
  4980.6      .1       0  5022.7     .05       0  5409.3      .1       0
  5795.6     .16       0
Bank Sta=4963.1,5022.7
XS Rating Curve= 0 ,0
Exp/Cntr=0.3,0.1

Chan Stop Cuts=-1
Use User Specified Reach Order=0
Composite Channel Slope=5