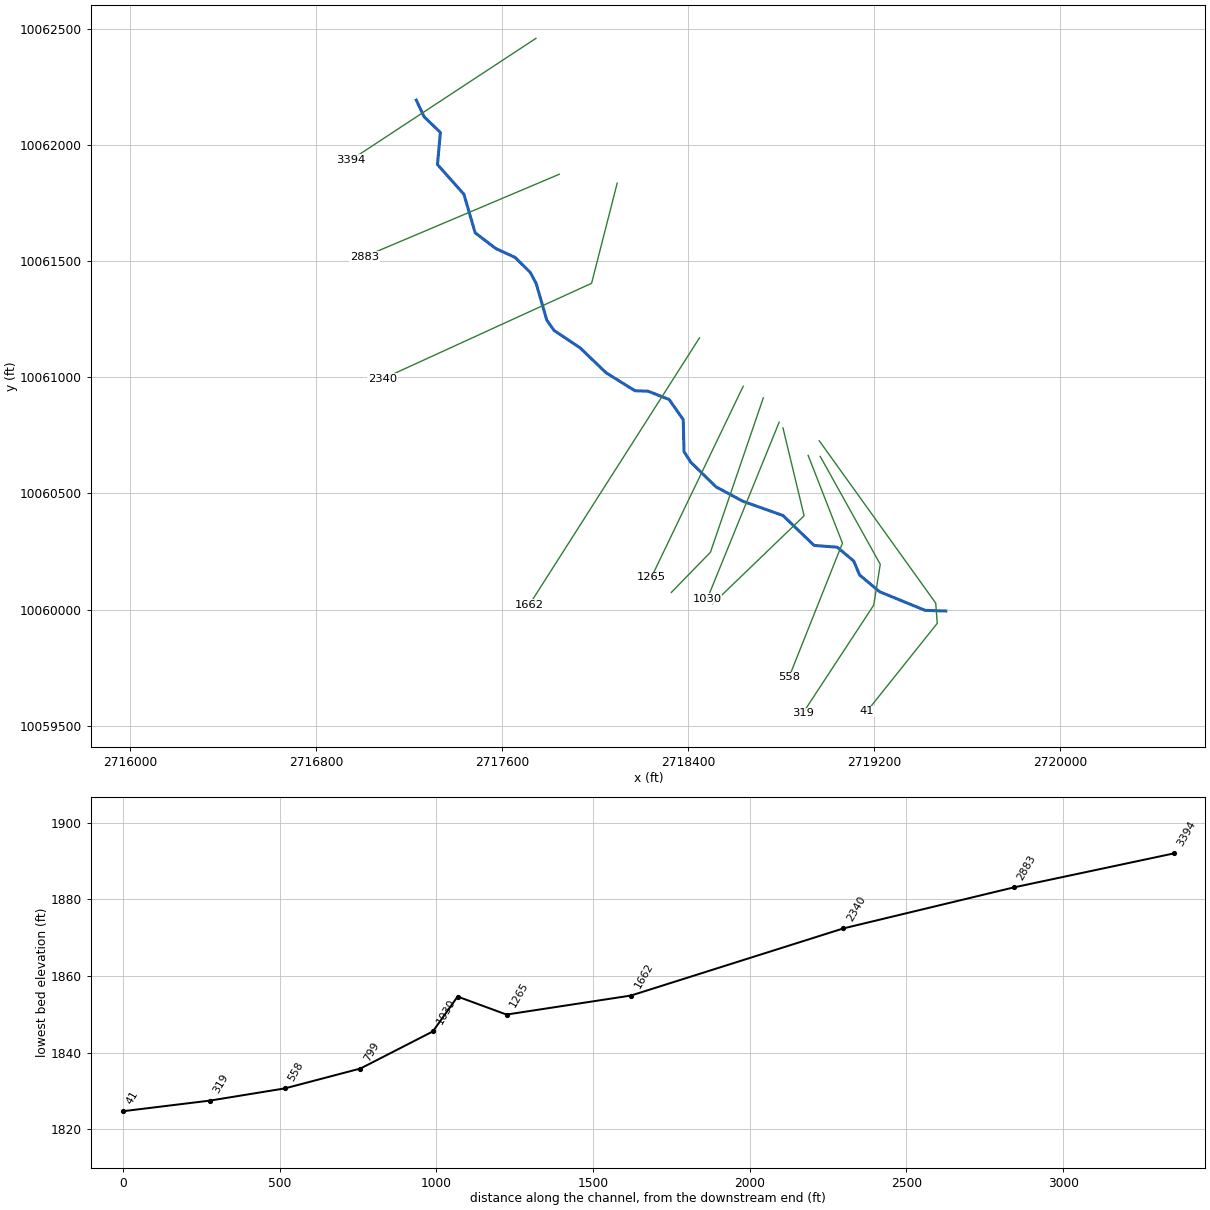
--- UNT 0048 IN HEWA.prj (project) ---

Proj Title=UNT 0048 IN HEWA Base Level Engineering
Current Plan=p01
Default Exp/Contr=0.3,0.1
English Units
Geom File=g01
Flow File=f01
Plan File=p01
Y Axis Title=Elevation
X Axis Title(PF)=Main Channel Distance
X Axis Title(XS)=Station
BEGIN DESCRIPTION:
UNT 0048 IN HEWA
END DESCRIPTION:
DSS Export Rating Curves= 0
DSS Export Rating Curve Sorted= 0
DSS Export Volume Flow Curves= 0
DXF OffsetX= 0
DXF OffsetY= 0
DXF ScaleX= 1
DXF ScaleY= 10

--- UNT 0048 IN HEWA.p01 (plan) ---

Plan Title=Multiple Run
Short Identifier=Multiple
Geom File=g01
Flow File=f01
Subcritical Flow
K Sum by GR= 0
Std Step Tol= 0.01
Critical Tol= 0.01
Num of Std Step Trials= 20
Max Error Tol= 0.3
Flow Tol Ratio= 0.001
Split Flow NTrial= 30
Split Flow Tol= 0.02
Split Flow Ratio= 0.02
Log Output Level= 0
Friction Slope Method= 1
Unsteady Friction Slope Method= 2
Unsteady Bridges Friction Slope Method= 1
Parabolic Critical Depth
Global Vel Dist=  1 , 1 , 1
Global Log Level= 0
CheckData=True
Encroach Param= -1, 0, 0, 0
BEGIN DESCRIPTION:
Multiple Run
END DESCRIPTION:

--- UNT 0048 IN HEWA.f01 (steady flow) ---

Flow Title=Multiple
Number of Profiles=7
Profile Names=10-year,25-year,50-year,1pct_min,100-year,1pct_plu,500-year
River Rch & RM= UNT 0048 IN HEWA,Reach-1,3394
    1122    1652    2116    1980    2677    3621    4288
Boundary for River Rch & Prof#=UNT 0048 IN HEWA,Reach-1,1
Up Type=0
Dn Type=3
Dn Slope=0.005
Boundary for River Rch & Prof#=UNT 0048 IN HEWA,Reach-1,2
Up Type=0
Dn Type=3
Dn Slope=0.005
Boundary for River Rch & Prof#=UNT 0048 IN HEWA,Reach-1,3
Up Type=0
Dn Type=3
Dn Slope=0.005
Boundary for River Rch & Prof#=UNT 0048 IN HEWA,Reach-1,4
Up Type=0
Dn Type=3
Dn Slope=0.005
Boundary for River Rch & Prof#=UNT 0048 IN HEWA,Reach-1,5
Up Type=0
Dn Type=3
Dn Slope=0.005
Boundary for River Rch & Prof#=UNT 0048 IN HEWA,Reach-1,6
Up Type=0
Dn Type=3
Dn Slope=0.005
Boundary for River Rch & Prof#=UNT 0048 IN HEWA,Reach-1,7
Up Type=0
Dn Type=3
Dn Slope=0.005

--- UNT 0048 IN HEWA.g01 (geometry) ---

Geom Title=Existing Conditions
Program Version=4.10

River Reach=UNT 0048 IN HEWA,Reach-1
Reach XY= 30
      2717229.84     10062192.36      2717263.13     10062120.88
      2717333.53     10062053.02        2717321.     10061914.92
      2717434.84     10061787.02      2717483.29     10061621.12
      2717571.89     10061553.43      2717654.87      10061515.5
      2717720.68     10061450.38      2717745.88     10061402.66
      2717791.56     10061244.92      2717822.38     10061201.44
      2717934.96     10061125.86      2718046.77     10061018.74
      2718170.84     10060941.54      2718227.63     10060939.57
      2718318.02     10060903.77      2718378.53     10060817.19
      2718381.92     10060679.63      2718410.67      10060634.4
      2718520.03     10060527.64       2718635.8     10060465.65
      2718807.54     10060404.78      2718941.89     10060275.89
       2719041.2     10060268.31      2719112.07     10060208.87
      2719137.53     10060148.84       2719223.9     10060076.52
      2719419.52     10059996.52      2719508.47     10059993.73

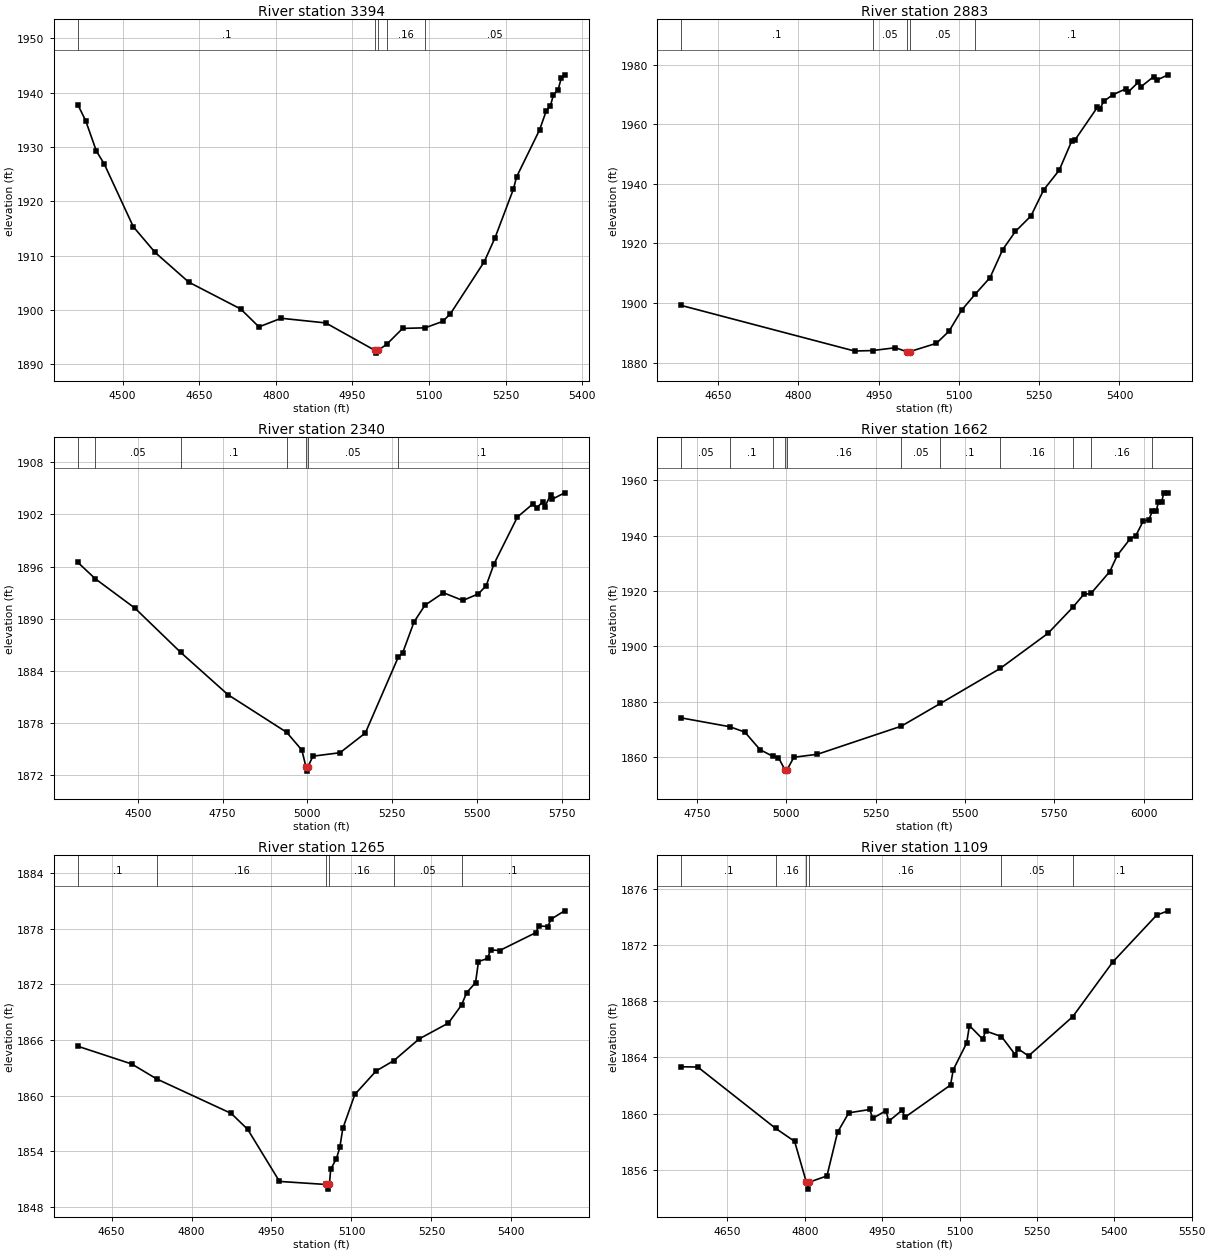
Type RM Length L Ch R = 1 ,3394    ,511,511,511
BEGIN DESCRIPTION:
UNT 0048 IN HEWA 6.0
END DESCRIPTION:
XS GIS Cut Line= 2
      2717744.83     10062458.02      2716948.49      10061934.7
#Sta/Elev= 30
  4412.6 1937.76  4427.9 1934.83  4448.9 1929.22    4464 1926.91  4521.2  1915.3
  4563.8 1910.58  4629.7 1905.11  4731.3 1900.17  4767.2 1896.87  4810.5 1898.46
  4897.9  1897.6  4994.3 1892.54    4997 1892.04  5000.3 1892.54  5017.2 1893.66
  5048.5 1896.59  5092.6  1896.7  5126.8 1897.88  5141.9 1899.27  5208.2 1908.86
  5229.3 1913.27  5265.5 1922.28  5271.4 1924.46  5316.7 1933.17  5329.6 1936.64
  5337.8 1937.59  5343.8 1939.62  5352.9 1940.55  5358.9 1942.63  5365.5 1943.28
#Mann= 5 ,-1 , 0
  4412.6      .1       0  4994.3     .07       0  5000.3      .1       0
  5017.2     .16       0  5092.6     .05       0
Bank Sta=4994.3,5000.3
XS Rating Curve= 0 ,0
Exp/Cntr=0.3,0.1

Type RM Length L Ch R = 1 ,2883    ,543,543,543
BEGIN DESCRIPTION:
UNT 0048 IN HEWA 5.0
END DESCRIPTION:
XS GIS Cut Line= 2
      2717845.43      10061873.2      2717007.56      10061518.9
#Sta/Elev= 30
  4581.1 1899.16  4904.8 1883.86  4938.6 1884.01  4981.3 1884.97    5002 1883.65
  5004.8 1883.15    5008 1883.65  5057.8 1886.44  5081.5 1890.53  5105.2 1897.63
  5130.3 1902.93  5158.1 1908.51  5181.8 1917.93  5205.5 1924.02  5234.6 1929.22
  5258.3 1937.96  5287.4 1944.59  5311.1 1954.52  5316.5 1954.65  5358.5 1965.65
  5363.9  1965.3  5370.4  1967.7  5387.6 1969.92  5411.3 1971.86  5416.7  1970.9
    5435  1974.1  5440.4 1972.62  5464.1 1976.03  5469.5 1974.81  5490.8 1976.61
#Mann= 5 ,-1 , 0
  4581.1      .1       0  4938.6     .05       0    5002    .035       0
    5008     .05       0  5130.3      .1       0
Bank Sta=5002,5008
XS Rating Curve= 0 ,0
Exp/Cntr=0.3,0.1

Type RM Length L Ch R = 1 ,2340    ,678,678,678
BEGIN DESCRIPTION:
UNT 0048 IN HEWA 4.0
END DESCRIPTION:
XS GIS Cut Line= 3
      2718094.38      10061834.9      2717984.26       10061404.
      2717084.21     10060992.27
#Sta/Elev= 30
  4323.6 1896.47  4374.9 1894.59    4492  1891.2  4626.8 1886.11  4765.9 1881.25
  4938.9 1876.92  4983.7 1874.88  4995.8 1872.95  4998.5 1872.45  5001.8 1872.95
  5016.3 1874.17  5096.3 1874.57  5170.9 1876.84  5267.8 1885.56  5280.5 1886.02
  5314.5 1889.63  5346.5 1891.54    5401 1892.98  5458.1 1892.09  5504.1 1892.85
  5527.1  1893.8  5550.1  1896.3  5619.2  1901.7  5665.2 1903.22  5676.4 1902.75
  5693.7 1903.45  5699.2 1902.82  5716.7 1904.22  5722.2 1903.75  5758.1 1904.48
#Mann= 7 ,-1 , 0
  4323.6      .1       0  4374.9     .05       0  4626.8      .1       0
  4938.9     .05       0  4995.8    .035       0  5001.8     .05       0
  5267.8      .1       0
Bank Sta=4995.8,5001.8
XS Rating Curve= 0 ,0
Exp/Cntr=0.3,0.1

Type RM Length L Ch R = 1 ,1662    ,397,397,397
BEGIN DESCRIPTION:
UNT 0048 IN HEWA 3.0
END DESCRIPTION:
XS GIS Cut Line= 2
      2718448.69     10061169.43      2717716.16     10060020.36
#Sta/Elev= 30
  4705.9 1874.14  4841.9 1870.94  4883.8    1869  4926.1 1862.67  4961.8 1860.27
  4977.8 1859.79  4995.9  1855.4  4998.7  1854.9  5001.9  1855.4    5021 1859.92
  5086.9 1860.99  5321.7 1871.15    5431 1879.35  5598.5 1892.01  5732.5 1904.72
  5801.6 1914.06  5832.6 1918.77  5852.9 1919.15  5905.3    1927  5926.5 1932.91
  5962.9 1938.96  5978.1 1939.95  5999.3 1945.37  6014.5 1945.73  6024.7 1948.82
  6035.7 1949.06  6041.6 1952.15  6050.9 1952.37  6056.8 1955.51  6068.6 1955.38
#Mann= 11 ,-1 , 0
  4705.9     .05       0  4841.9      .1       0  4961.8     .16       0
  4995.9     .07       0  5001.9     .16       0  5321.7     .05       0
    5431      .1       0  5598.5     .16       0  5801.6      .1       0
  5852.9     .16       0  6024.7      .1       0
Bank Sta=4995.9,5001.9
XS Rating Curve= 0 ,0
Exp/Cntr=0.3,0.1

Type RM Length L Ch R = 1 ,1265    ,156,156,156
BEGIN DESCRIPTION:
Mapping XS e00dde78
END DESCRIPTION:
XS GIS Cut Line= 2
       2718636.7     10060960.91      2718241.17     10060138.03
#Sta/Elev= 30
  4586.8 1865.33  4687.8 1863.42  4734.6 1861.81  4874.5 1858.09  4905.4 1856.37
    4965 1850.76  5052.6 1850.43  5055.3 1849.93  5058.6 1850.43  5061.1 1852.08
  5071.9 1853.23  5078.2 1854.44  5083.8 1856.47  5106.4 1860.14  5146.1 1862.66
  5179.7 1863.79  5227.2 1866.13  5281.9 1867.83  5306.6 1869.78    5316  1871.1
  5332.8 1872.19  5338.3 1874.46  5355.4  1874.8  5360.9 1875.72    5378 1875.65
  5445.9 1877.58  5451.5  1878.3  5468.6 1878.24  5474.1 1879.02  5499.8 1879.93
#Mann= 6 ,-1 , 0
  4586.8      .1       0  4734.6     .16       0  5052.6     .07       0
  5058.6     .16       0  5179.7     .05       0  5306.6      .1       0
Bank Sta=5052.6,5058.6
XS Rating Curve= 0 ,0
Exp/Cntr=0.3,0.1

Type RM Length L Ch R = 1 ,1109    ,79,79,79
BEGIN DESCRIPTION:
Mapping XS c599d686
END DESCRIPTION:
XS GIS Cut Line= 3
      2718723.14     10060910.81      2718495.63     10060246.48
      2718327.23     10060073.53
#Sta/Elev= 30
  4560.6 1863.34  4592.5 1863.32  4743.2 1858.96  4780.2 1858.03  4802.9 1855.13
  4805.7 1854.63  4808.9 1855.13  4842.9 1855.57  4863.5 1858.68  4885.2 1860.06
  4926.1  1860.3  4931.4 1859.66  4957.4 1860.22  4962.7 1859.46  4988.7 1860.25
  4993.9 1859.74  5082.5 1862.04  5087.8 1863.13  5113.8 1865.03  5119.1 1866.27
  5145.1  1865.3  5150.4 1865.89  5181.3 1865.49  5207.7 1864.21    5213 1864.63
  5233.7 1864.11  5319.5 1866.91  5397.1  1870.8    5482 1874.13  5504.2 1874.44
#Mann= 6 ,-1 , 0
  4560.6      .1       0  4743.2     .16       0  4802.9     .07       0
  4808.9     .16       0  5181.3     .05       0  5319.5      .1       0
Bank Sta=4802.9,4808.9
XS Rating Curve= 0 ,0
Exp/Cntr=0.3,0.1

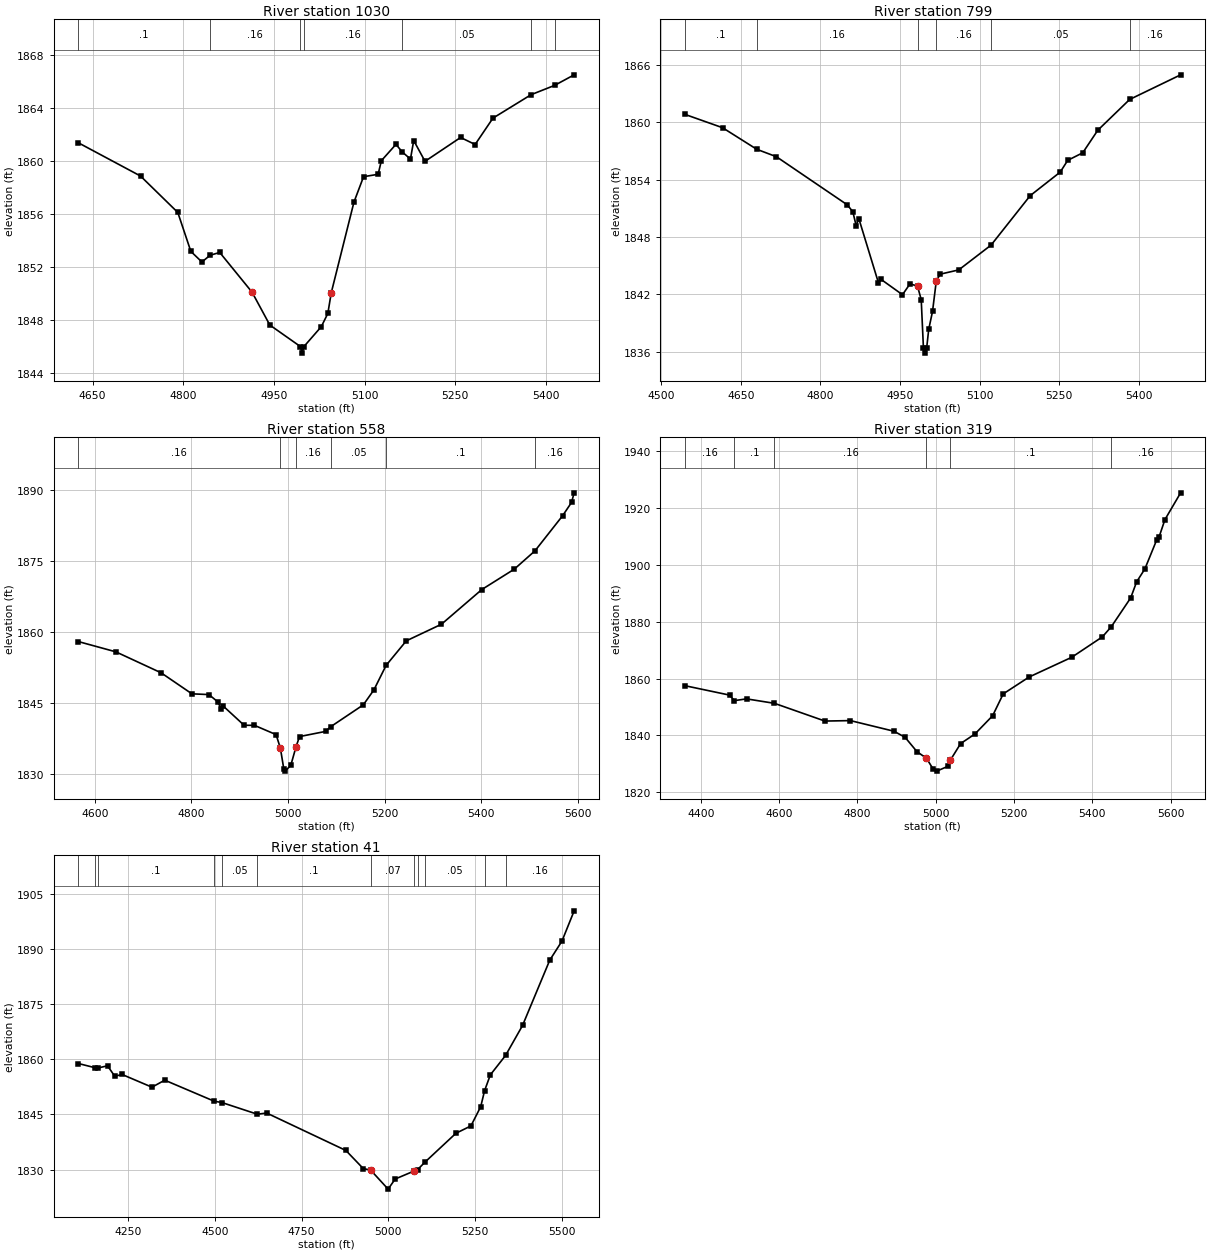
Type RM Length L Ch R = 1 ,1030    ,231,231,231
BEGIN DESCRIPTION:
Mapping XS 61bf11b1
END DESCRIPTION:
XS GIS Cut Line= 2
      2718791.39     10060806.15      2718481.97     10060046.23
#Sta/Elev= 30
  4626.3  1861.4  4729.2 1858.89  4790.9 1856.14  4812.5  1853.2  4830.8  1852.4
  4844.4 1852.91  4860.3 1853.12  4913.8 1850.12  4943.2 1847.64  4993.7 1846.02
  4996.5 1845.52  4999.7 1846.02  5028.4 1847.52  5039.2 1848.52  5044.8 1850.07
  5082.4 1856.92  5098.3 1858.84  5122.4 1859.02  5127.8 1860.05  5151.9 1861.28
  5162.5  1860.7  5175.9 1860.17  5181.3 1861.57    5200    1860  5258.9  1861.8
  5282.9 1861.27  5312.4 1863.26  5375.5 1865.03  5414.3 1865.73  5446.8 1866.53
#Mann= 7 ,-1 , 0
  4626.3      .1       0  4844.4     .16       0  4993.7     .07       0
  4999.7     .16       0  5162.5     .05       0  5375.5      .1       0
  5414.3     .16       0
Bank Sta=4913.8,5044.8
XS Rating Curve= 0 ,0
Exp/Cntr=0.3,0.1

Type RM Length L Ch R = 1 ,799     ,241,241,241
BEGIN DESCRIPTION:
UNT 0048 IN HEWA 2.0
END DESCRIPTION:
XS GIS Cut Line= 3
      2718807.76     10060781.57      2718898.72     10060403.36
      2718506.16     10060025.16
#Sta/Elev= 30
  4544.6 1860.85  4615.7 1859.45  4680.1 1857.19  4717.2 1856.41  4850.9 1851.36
  4861.2 1850.64  4867.4 1849.19  4872.5 1849.92  4909.3 1843.22  4914.5 1843.55
  4954.7 1841.95  4968.9 1843.09    4983 1842.85    4990 1841.43  4994.2 1836.33
  4996.9 1835.83  5000.2 1836.33  5004.1 1838.31  5011.3  1840.2  5018.3 1843.35
  5025.5  1844.1  5060.7 1844.55  5121.6 1847.15  5195.3 1852.33  5251.9  1854.8
    5266 1856.03  5294.3 1856.82  5322.6 1859.18  5382.7 1862.41  5478.7 1864.99
#Mann= 6 ,-1 , 0
  4544.6      .1       0  4680.1     .16       0    4983     .07       0
  5018.3     .16       0  5121.6     .05       0  5382.7     .16       0
Bank Sta=4983,5018.3
XS Rating Curve= 0 ,0
Exp/Cntr=0.3,0.1

Type RM Length L Ch R = 1 ,558     ,239,239,239
BEGIN DESCRIPTION:
Mapping XS 15f6c1fe
END DESCRIPTION:
XS GIS Cut Line= 3
      2718916.09     10060663.38      2719063.67     10060285.77
      2718833.68     10059708.63
#Sta/Elev= 30
  4565.8 1858.01  4643.5 1855.84  4737.2 1851.41    4801 1846.97  4836.3 1846.81
  4855.3 1845.21  4860.7 1843.83  4866.1 1844.36    4909 1840.33  4930.5 1840.31
  4975.3 1838.35  4984.2 1835.48  4991.2 1831.14  4993.9 1830.64  5005.7 1831.85
  5016.5 1835.75  5023.8 1837.94  5077.8 1839.03  5088.2 1840.01  5155.9 1844.64
  5177.9 1847.81  5203.1 1852.98  5244.9 1858.16  5317.7 1861.67  5401.3    1869
  5468.6 1873.31  5511.4 1877.18  5568.5 1884.58    5587 1887.39  5592.5 1889.43
#Mann= 6 ,-1 , 0
  4565.8     .16       0  4984.2     .07       0  5016.5     .16       0
  5088.2     .05       0  5203.1      .1       0  5511.4     .16       0
Bank Sta=4984.2,5016.5
XS Rating Curve= 0 ,0
Exp/Cntr=0.3,0.1

Type RM Length L Ch R = 1 ,319     ,278,278,278
BEGIN DESCRIPTION:
Mapping XS b861e5cd
END DESCRIPTION:
XS GIS Cut Line= 4
       2718968.2     10060658.99      2719226.43     10060194.62
      2719198.22     10060018.84      2718892.85     10059553.21
#Sta/Elev= 30
  4359.3 1857.49  4473.5 1854.18  4485.9 1852.23    4517 1852.85  4588.3 1851.28
  4717.1 1845.05  4782.3 1845.21  4893.6 1841.47  4921.9 1839.33  4952.3 1834.28
  4976.4 1831.99  4992.8 1828.33  5002.7 1827.45  5031.9 1829.19    5037  1831.2
  5063.7 1837.14  5100.1 1840.49  5145.4 1846.92  5172.5 1854.61  5238.8 1860.55
  5347.3 1867.46  5425.7 1874.65  5448.6 1878.24    5498 1888.35  5513.1 1893.98
  5534.2 1898.53  5564.4 1908.73  5570.4 1909.74  5585.5 1915.89  5625.5 1925.28
#Mann= 6 ,-1 , 0
  4359.3     .16       0  4485.9      .1       0  4588.3     .16       0
  4976.4     .07       0    5037      .1       0  5448.6     .16       0
Bank Sta=4976.4,5037
XS Rating Curve= 0 ,0
Exp/Cntr=0.3,0.1

Type RM Length L Ch R = 1 ,41      ,0,0,0
BEGIN DESCRIPTION:
UNT 0048 IN HEWA 1.0
END DESCRIPTION:
XS GIS Cut Line= 4
      2718963.83     10060726.32      2719465.14     10060027.52
      2719471.65     10059940.72      2719169.98     10059563.09
#Sta/Elev= 30
  4105.9 1858.89  4153.7 1857.75  4162.9 1857.67  4190.1 1858.27    4211 1855.42
  4232.2  1855.9  4318.3 1852.44  4355.2 1854.35  4497.6 1848.63  4520.3 1848.25
  4622.5 1845.07  4649.3  1845.4  4877.8  1835.2  4928.1 1830.25    4949 1829.88
  4999.6 1824.67  5019.9 1827.42  5074.7 1829.61  5084.7 1829.99  5106.1 1832.04
  5195.3 1839.89  5238.5 1841.89  5266.7 1847.12  5277.8 1851.46  5294.5  1855.8
  5338.4 1861.08  5387.4 1869.25  5465.9 1887.04  5501.1 1892.23  5536.3 1900.48
#Mann= 12 ,-1 , 0
  4105.9      .1       0  4153.7     .16       0  4162.9      .1       0
  4497.6     .16       0  4520.3     .05       0  4622.5      .1       0
    4949     .07       0  5074.7      .1       0  5084.7     .16       0
  5106.1     .05       0  5277.8      .1       0  5338.4     .16       0
Bank Sta=4949,5074.7
XS Rating Curve= 0 ,0
Exp/Cntr=0.3,0.1

Chan Stop Cuts=-1
Use User Specified Reach Order=0
Composite Channel Slope=5