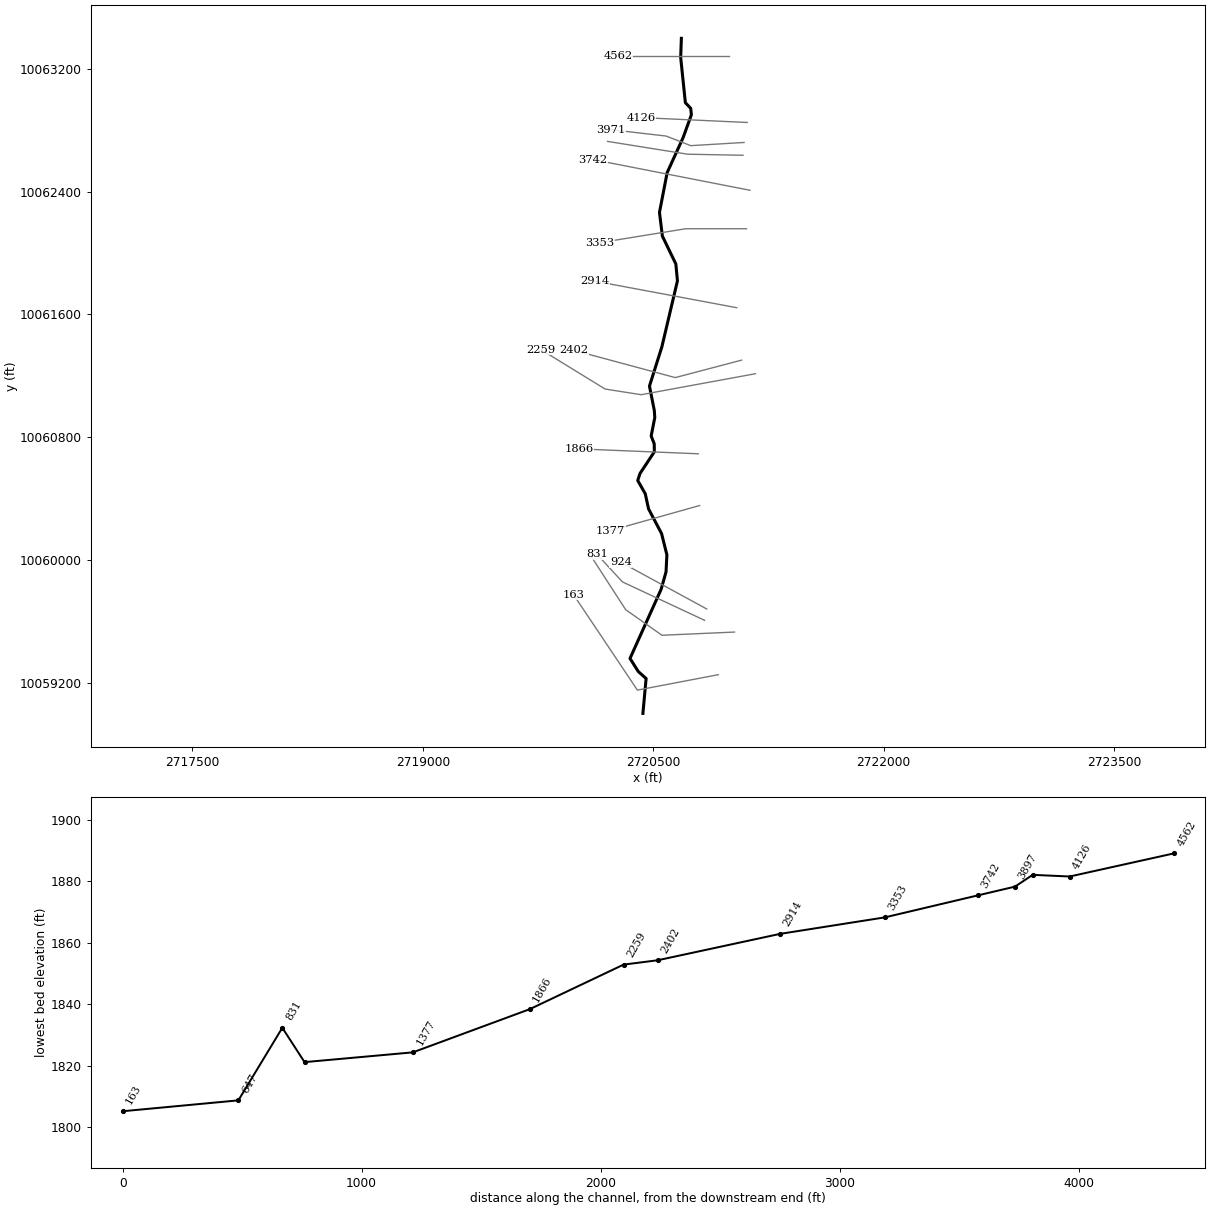
--- UNT 0049 IN HEWA.prj (project) ---

Proj Title=UNT 0049 IN HEWA Base Level Engineering
Current Plan=p01
Default Exp/Contr=0.3,0.1
English Units
Geom File=g01
Flow File=f01
Plan File=p01
BEGIN DESCRIPTION:
UNT 0049 IN HEWA
END DESCRIPTION:

--- UNT 0049 IN HEWA.p01 (plan) ---

Plan Title=Multiple Run
Short Identifier=Multiple
Geom File=g01
Flow File=f01
Subcritical Flow
K Sum by GR= 0
Std Step Tol= 0.01
Critical Tol= 0.01
Num of Std Step Trials= 20
Max Error Tol= 0.3
Flow Tol Ratio= 0.001
Split Flow NTrial= 30
Split Flow Tol= 0.02
Split Flow Ratio= 0.02
Log Output Level= 0
Friction Slope Method= 1
Unsteady Friction Slope Method= 2
Unsteady Bridges Friction Slope Method= 1
Parabolic Critical Depth
Global Vel Dist=  1 , 1 , 1
Global Log Level= 0
CheckData=True
Encroach Param= -1, 0, 0, 0
BEGIN DESCRIPTION:
Multiple Run
END DESCRIPTION:

--- UNT 0049 IN HEWA.f01 (steady flow) ---

Flow Title=Multiple
Number of Profiles=7
Profile Names=10-year,25-year,50-year,1pct_min,100-year,1pct_plu,500-year
River Rch & RM= UNT 0049 IN HEWA,Reach-1,4562
     579     826    1037     955    1292    1747    2010
Boundary for River Rch & Prof#=UNT 0049 IN HEWA,Reach-1,1
Up Type=0
Dn Type=3
Dn Slope=0.005
Boundary for River Rch & Prof#=UNT 0049 IN HEWA,Reach-1,2
Up Type=0
Dn Type=3
Dn Slope=0.005
Boundary for River Rch & Prof#=UNT 0049 IN HEWA,Reach-1,3
Up Type=0
Dn Type=3
Dn Slope=0.005
Boundary for River Rch & Prof#=UNT 0049 IN HEWA,Reach-1,4
Up Type=0
Dn Type=3
Dn Slope=0.005
Boundary for River Rch & Prof#=UNT 0049 IN HEWA,Reach-1,5
Up Type=0
Dn Type=3
Dn Slope=0.005
Boundary for River Rch & Prof#=UNT 0049 IN HEWA,Reach-1,6
Up Type=0
Dn Type=3
Dn Slope=0.005
Boundary for River Rch & Prof#=UNT 0049 IN HEWA,Reach-1,7
Up Type=0
Dn Type=3
Dn Slope=0.005

--- UNT 0049 IN HEWA.g01 (geometry) ---

Geom Title=Existing Conditions

River Reach=UNT 0049 IN HEWA,Reach-1
Reach XY= 30
      2720683.41     10063397.19      2720678.94     10063273.16
      2720709.44     10062978.28      2720744.43     10062940.98
      2720748.55     10062899.18      2720695.22     10062751.95
      2720590.91     10062522.73      2720540.88     10062263.70
      2720559.94     10062109.34      2720647.44     10061928.32
      2720657.86     10061818.34      2720556.70     10061389.46
      2720475.80     10061133.19      2720507.20     10060974.62
      2720510.36     10060928.31      2720486.80     10060808.38
      2720506.67     10060757.83      2720507.49     10060705.22
      2720414.03     10060563.94      2720399.38     10060518.62
      2720448.45     10060431.97      2720469.74     10060333.70
      2720554.57     10060172.81      2720589.22     10060034.33
      2720583.60     10059923.58      2720551.73     10059810.37
      2720349.03     10059359.98      2720403.01     10059274.69
      2720453.90     10059229.29      2720433.05     10059002.35

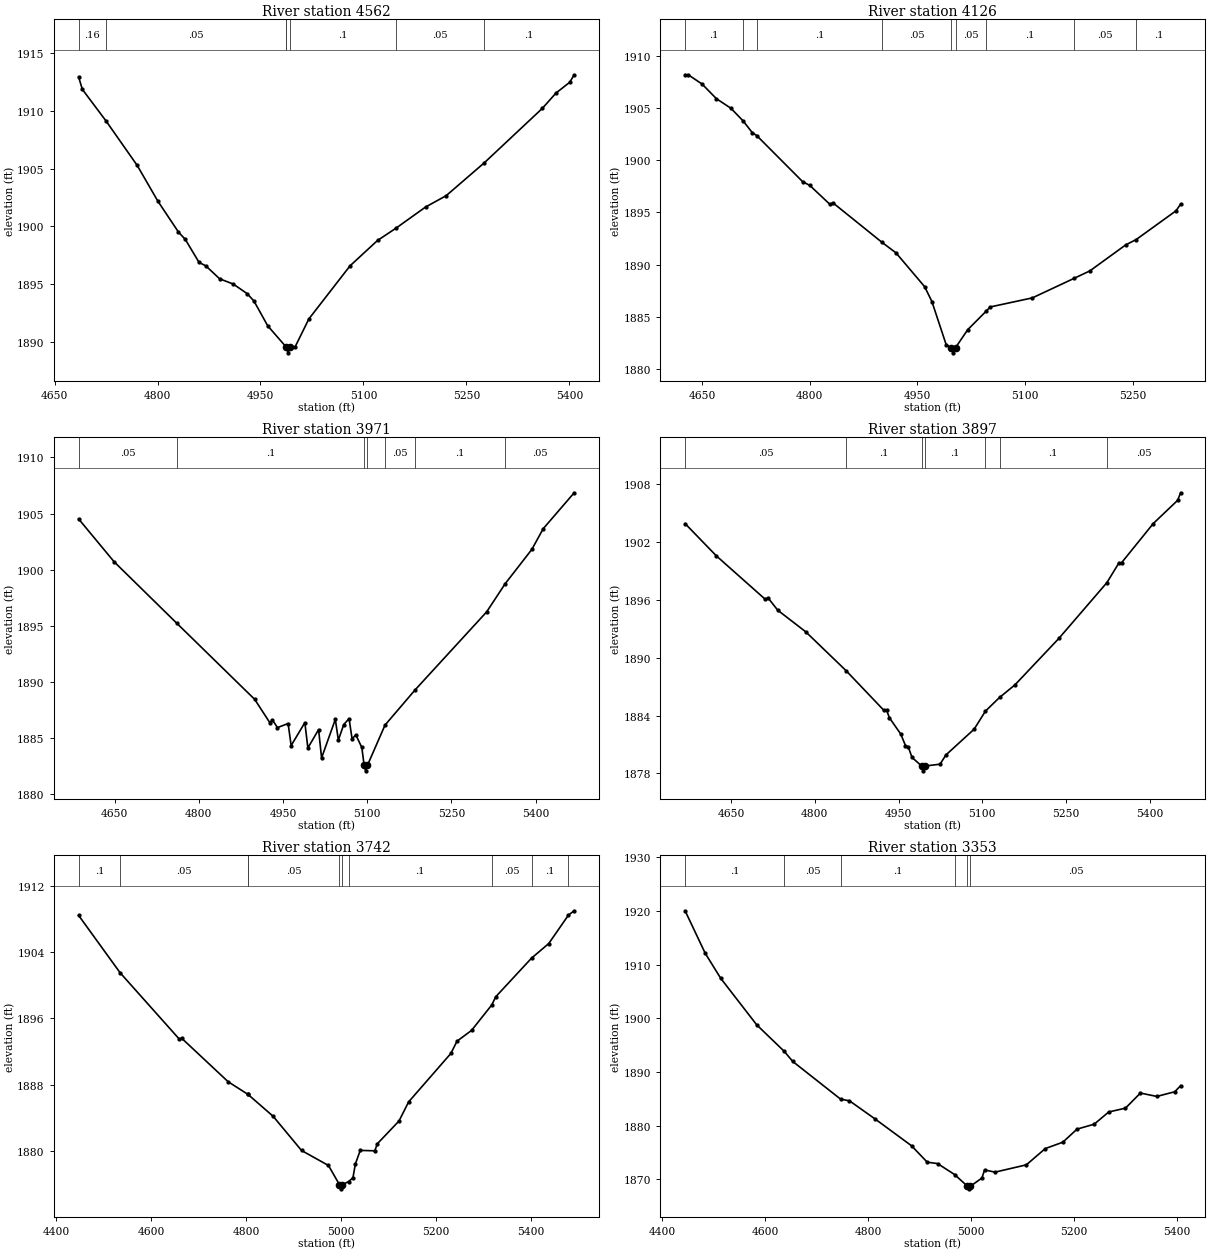
Type RM Length L Ch R = 1,4562,436,436,436
BEGIN DESCRIPTION:
UNT 0049 IN HEWA 10.0
END DESCRIPTION:
XS GIS Cut Line= 2
      2720993.83     10063281.63      2720271.93     10063281.63
#Sta/Elev= 30
  4685.1 1912.91  4690.5 1911.85  4725.0 1909.12  4770.5 1905.27  4800.5 1902.19
  4830.5 1899.52  4840.5 1898.88  4860.5 1896.90  4870.5 1896.59  4890.5 1895.48
  4910.5 1895.02  4930.5 1894.20  4940.5 1893.56  4960.5 1891.42  4987.3 1889.59
  4987.5 1889.58  4990.2 1889.08  4993.5 1889.58  5000.5 1889.60  5020.5 1892.01
  5080.5 1896.60  5120.5 1898.79  5147.1 1899.84  5190.5 1901.68  5220.5 1902.66
  5276.2 1905.51  5360.5 1910.20  5380.5 1911.53  5400.5 1912.46  5407.0 1913.11
#Mann=7,-1,0
  4685.1    0.16       0  4725.0    0.05       0  4987.3     0.1       0
  4987.5    0.07       0  4993.5     0.1       0  5147.1    0.05       0
  5276.2     0.1       0
Bank Sta=4987.5,4993.5
Exp/Cntr=0.3,0.1

Type RM Length L Ch R = 1,4126,155,155,155
BEGIN DESCRIPTION:
UNT 0049 IN HEWA 9.0
END DESCRIPTION:
XS GIS Cut Line= 2
      2721112.16     10062849.34      2720421.99     10062881.12
#Sta/Elev= 30
  4626.1 1908.17  4630.5 1908.17  4649.8 1907.28  4669.8 1905.88  4689.9 1904.97
  4707.2 1903.74  4719.9 1902.62  4726.0 1902.35  4790.0 1897.94  4800.0 1897.58
  4827.7 1895.79  4832.7 1895.89  4900.7 1892.13  4920.1 1891.13  4960.1 1887.89
  4970.2 1886.47  4990.2 1882.32  4997.2 1882.06  4999.9 1881.56  5003.2 1882.06
  5020.2 1883.78  5045.9 1885.55  5051.5 1885.95  5110.3 1886.82  5168.8 1888.70
  5190.4 1889.40  5240.4 1891.89  5255.0 1892.40  5310.5 1895.15  5317.0 1895.79
#Mann=9,-1,0
  4626.1     0.1       0  4707.2    0.16       0  4726.0     0.1       0
  4900.7    0.05       0  4997.2   0.035       0  5003.2    0.05       0
  5045.9     0.1       0  5168.8    0.05       0  5255.0     0.1       0
Bank Sta=4997.2,5003.2
Exp/Cntr=0.3,0.1

Type RM Length L Ch R = 1,3971,74,74,74
BEGIN DESCRIPTION:
Mapping XS fcc0e0ed
END DESCRIPTION:
XS GIS Cut Line= 4
      2721091.58     10062719.26      2720744.38     10062698.43
      2720584.66     10062760.93      2720223.59     10062802.59
#Sta/Elev= 30
  4585.8 1904.52  4649.0 1900.71  4760.4 1895.25  4899.5 1888.46  4926.5 1886.38
  4931.1 1886.63  4940.0 1885.95  4959.0 1886.31  4964.4 1884.35  4988.8 1886.39
  4994.2 1884.14  5013.3 1885.77  5018.6 1883.25  5043.1 1886.68  5048.5 1884.84
  5058.1 1886.22  5067.6 1886.75  5072.9 1884.95  5079.6 1885.30  5090.3 1884.18
  5094.4 1882.60  5097.1 1882.10  5100.4 1882.60  5131.6 1886.17  5185.3 1889.31
  5312.7 1896.25  5345.6 1898.75  5393.2 1901.81  5413.4 1903.65  5468.6 1906.85
#Mann=7,-1,0
  4585.8    0.05       0  4760.4     0.1       0  5094.4    0.07       0
  5100.4     0.1       0  5131.6    0.05       0  5185.3     0.1       0
  5345.6    0.05       0
Bank Sta=5094.4,5100.4
Exp/Cntr=0.3,0.1

Type RM Length L Ch R = 1,3897,155,155,155
BEGIN DESCRIPTION:
Mapping XS c4a8bf79
END DESCRIPTION:
XS GIS Cut Line= 3
      2721084.67     10062635.93      2720723.55     10062642.87
      2720203.06     10062726.15
#Sta/Elev= 30
  4567.4 1903.93  4623.6 1900.57  4710.9 1896.08  4715.9 1896.23  4733.6 1894.93
  4783.6 1892.70  4855.8 1888.67  4923.6 1884.55  4928.6 1884.55  4933.7 1883.76
  4954.0 1882.08  4962.4 1880.89  4967.4 1880.74  4974.2 1879.65  4991.5 1878.76
  4994.3 1878.26  4997.5 1878.76  5024.4 1878.95  5035.0 1879.91  5085.6 1882.59
  5105.8 1884.46  5131.1 1885.88  5158.6 1887.18  5237.6 1892.02  5323.5 1897.80
  5344.7 1899.81  5349.7 1899.86  5406.7 1903.94  5450.2 1906.34  5455.7 1907.13
#Mann=7,-1,0
  4567.4    0.05       0  4855.8     0.1       0  4991.5    0.07       0
  4997.5     0.1       0  5105.8    0.05       0  5131.1     0.1       0
  5323.5    0.05       0
Bank Sta=4991.5,4997.5
Exp/Cntr=0.3,0.1

Type RM Length L Ch R = 1,3742,389,389,389
BEGIN DESCRIPTION:
UNT 0049 IN HEWA 8.0
END DESCRIPTION:
XS GIS Cut Line= 2
      2721130.38     10062407.94      2720106.47     10062608.17
#Sta/Elev= 30
  4447.6 1908.43  4534.9 1901.51  4659.3 1893.51  4664.4 1893.61  4762.4 1888.35
  4803.7 1886.84  4803.8 1886.84  4857.1 1884.18  4916.9 1880.05  4973.6 1878.24
  4996.8 1875.92  4999.5 1875.42  5002.8 1875.92  5016.0 1876.30  5025.1 1876.75
  5030.3 1878.43  5040.5 1880.06  5071.1 1880.01  5076.6 1880.87  5122.1 1883.61
  5142.4 1885.92  5231.2 1891.76  5244.3 1893.25  5274.9 1894.55  5317.5 1897.63
  5325.8 1898.61  5401.1 1903.27  5437.3 1905.03  5478.9 1908.47  5490.9 1908.99
#Mann=10,-1,0
  4447.6     0.1       0  4534.9    0.05       0  4803.7     0.1       0
  4803.8    0.05       0  4996.8   0.035       0  5002.8    0.05       0
  5016.0     0.1       0  5317.5    0.05       0  5401.1     0.1       0
  5478.9    0.05       0
Bank Sta=4996.8,5002.8
Exp/Cntr=0.3,0.1

Type RM Length L Ch R = 1,3353,439,439,439
BEGIN DESCRIPTION:
UNT 0049 IN HEWA 7.0
END DESCRIPTION:
XS GIS Cut Line= 3
      2721107.58     10062157.67      2720711.70     10062157.67
      2720152.72     10062066.78
#Sta/Elev= 30
  4445.0 1920.05  4484.1 1912.13  4514.1 1907.48  4584.1 1898.80  4637.5 1893.87
  4654.1 1891.98  4747.0 1884.96  4764.1 1884.66  4814.1 1881.26  4884.7 1876.28
  4915.1 1873.23  4935.3 1872.96  4968.5 1870.91  4993.1 1868.76  4995.9 1868.26
  4999.1 1868.76  5021.3 1870.27  5026.5 1871.78  5046.8 1871.37  5107.6 1872.73
  5144.4 1875.76  5178.5 1876.95  5206.0 1879.38  5239.3 1880.30  5267.5 1882.57
  5300.1 1883.29  5329.1 1886.10  5360.9 1885.47  5395.7 1886.34  5407.2 1887.47
#Mann=6,-1,0
  4445.0     0.1       0  4637.5    0.05       0  4747.0     0.1       0
  4968.5    0.05       0  4993.1   0.035       0  4999.1    0.05       0
Bank Sta=4993.1,4999.1
Exp/Cntr=0.3,0.1

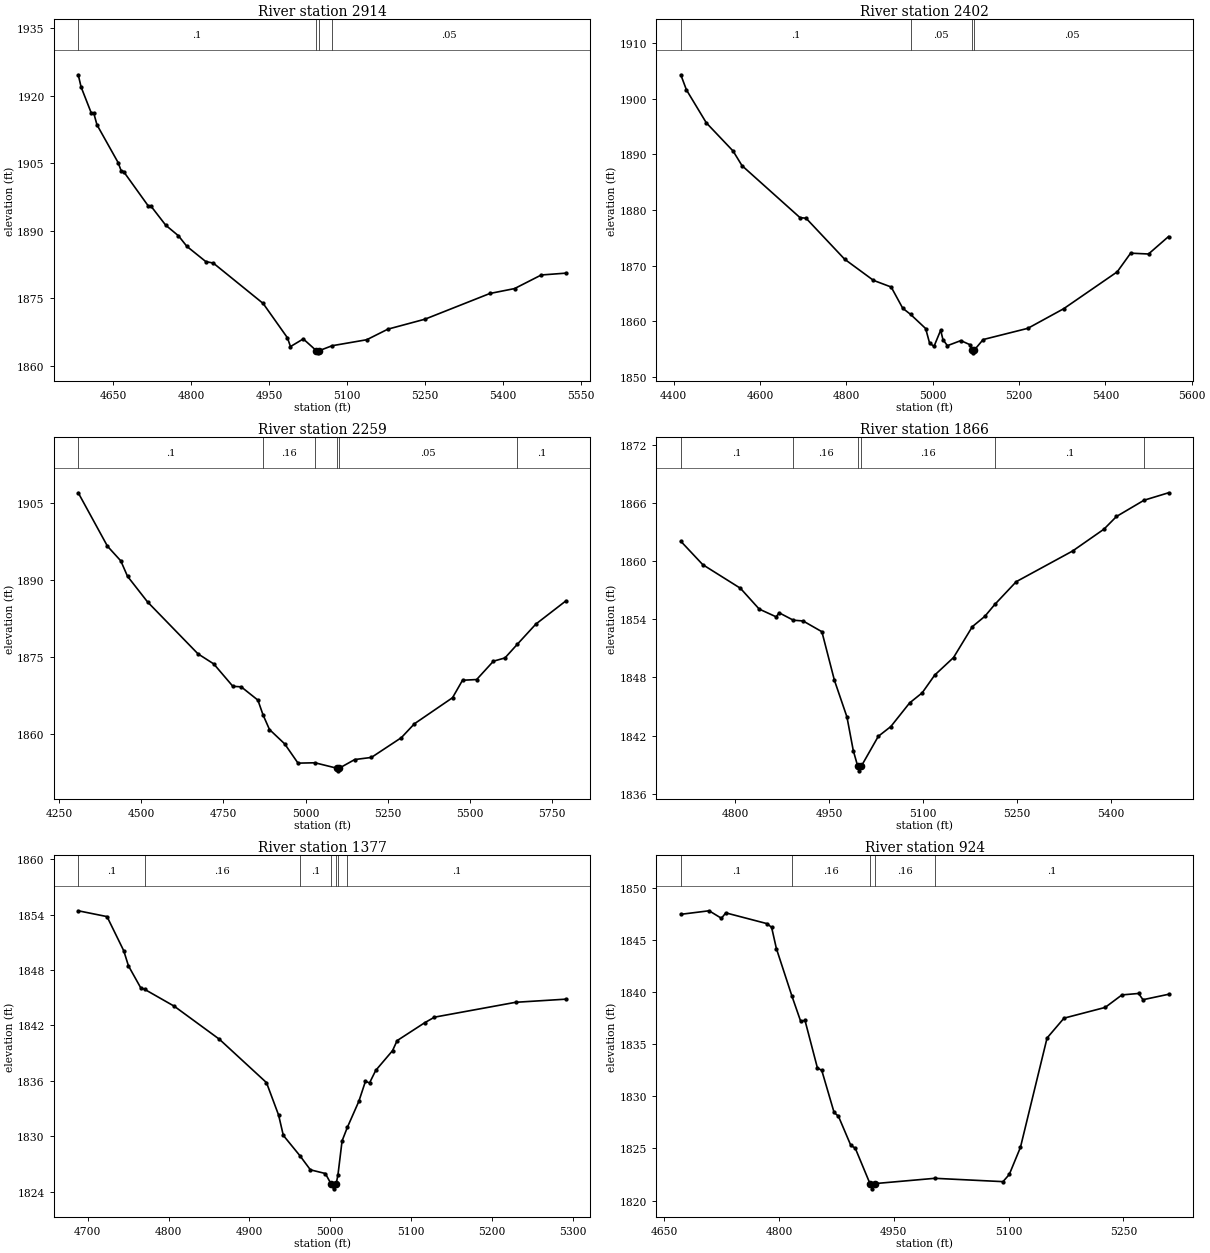
Type RM Length L Ch R = 1,2914,512,512,512
BEGIN DESCRIPTION:
UNT 0049 IN HEWA 6.0
END DESCRIPTION:
XS GIS Cut Line= 2
      2721043.86     10061643.47      2720121.77     10061816.08
#Sta/Elev= 30
  4582.5 1924.63  4588.0 1921.91  4607.2 1916.25  4612.3 1916.14  4618.5 1913.52
  4659.2 1905.13  4664.9 1903.36  4669.9 1903.11  4717.5 1895.45  4722.6 1895.43
  4750.8 1891.22  4775.2 1888.88  4791.5 1886.52  4827.8 1883.15  4842.3 1882.81
  4938.1 1873.85  4984.8 1866.23  4990.7 1864.27  5015.3 1865.97  5040.3 1863.38
  5043.0 1862.88  5046.3 1863.38  5070.8 1864.46  5137.4 1865.79  5178.1 1868.14
  5249.3 1870.35  5374.2 1876.06  5421.7 1877.15  5473.1 1880.17  5520.6 1880.58
#Mann=4,-1,0
  4582.5     0.1       0  5040.3    0.07       0  5046.3     0.1       0
  5070.8    0.05       0
Bank Sta=5040.3,5046.3
Exp/Cntr=0.3,0.1

Type RM Length L Ch R = 1,2402,143,143,143
BEGIN DESCRIPTION:
UNT 0049 IN HEWA 5.0
END DESCRIPTION:
XS GIS Cut Line= 3
      2721075.70     10061302.17      2720643.44     10061188.42
      2719983.66     10061365.88
#Sta/Elev= 30
  4416.2 1904.31  4429.3 1901.59  4475.4 1895.66  4537.4 1890.59  4558.1 1887.96
  4692.5 1878.61  4706.4 1878.51  4795.9 1871.13  4862.6 1867.33  4903.7 1866.13
  4930.5 1862.31  4948.6 1861.21  4983.6 1858.66  4992.6 1856.07  5002.9 1855.44
  5018.4 1858.36  5023.7 1856.66  5034.0 1855.58  5065.1 1856.49  5085.8 1855.77
  5090.2 1854.79  5092.9 1854.29  5096.2 1854.79  5116.9 1856.68  5220.4 1858.70
  5303.3 1862.22  5427.5 1868.86  5458.6 1872.22  5500.0 1872.07  5546.4 1875.21
#Mann=4,-1,0
  4416.2     0.1       0  4948.6    0.05       0  5090.2   0.035       0
  5096.2    0.05       0
Bank Sta=5090.2,5096.2
Exp/Cntr=0.3,0.1

Type RM Length L Ch R = 1,2259,393,393,393
BEGIN DESCRIPTION:
Mapping XS 0add4b7a
END DESCRIPTION:
XS GIS Cut Line= 4
      2721165.77     10061213.72      2720421.42     10061077.00
      2720187.04     10061113.89      2719770.40     10061369.95
#Sta/Elev= 30
  4308.5 1907.02  4397.3 1896.62  4437.9 1893.76  4458.3 1890.76  4519.3 1885.76
  4672.5 1875.66  4720.6 1873.69  4778.7 1869.33  4804.0 1869.23  4854.8 1866.64
  4870.4 1863.77  4890.0 1860.92  4936.1 1858.13  4976.8 1854.37  5028.3 1854.44
  5095.7 1853.37  5098.4 1852.87  5101.7 1853.37  5149.3 1855.07  5199.9 1855.48
  5291.0 1859.33  5330.6 1862.03  5446.6 1867.11  5477.0 1870.51  5520.0 1870.65
  5570.9 1874.22  5606.1 1874.86  5643.8 1877.53  5700.0 1881.45  5791.6 1885.98
#Mann=6,-1,0
  4308.5     0.1       0  4870.4    0.16       0  5028.3    0.05       0
  5095.7    0.07       0  5101.7    0.05       0  5643.8     0.1       0
Bank Sta=5095.7,5101.7
Exp/Cntr=0.3,0.1

Type RM Length L Ch R = 1,1866,489,489,489
BEGIN DESCRIPTION:
UNT 0049 IN HEWA 4.0
END DESCRIPTION:
XS GIS Cut Line= 2
      2720793.59     10060692.42      2720015.44     10060724.28
#Sta/Elev= 30
  4713.2 1862.08  4748.3 1859.66  4808.4 1857.22  4838.4 1855.07  4865.4 1854.27
  4870.4 1854.68  4892.9 1853.92  4908.5 1853.84  4938.5 1852.73  4958.5 1847.71
  4978.5 1843.92  4988.6 1840.45  4995.6 1838.85  4998.3 1838.35  5001.6 1838.85
  5028.6 1841.92  5048.6 1842.93  5078.6 1845.37  5098.6 1846.41  5118.7 1848.25
  5148.7 1850.06  5178.7 1853.25  5198.7 1854.32  5214.6 1855.55  5248.8 1857.90
  5338.8 1861.07  5388.9 1863.33  5408.9 1864.64  5452.9 1866.32  5492.0 1867.09
#Mann=6,-1,0
  4713.2     0.1       0  4892.9    0.16       0  4995.6    0.07       0
  5001.6    0.16       0  5214.6     0.1       0  5452.9    0.05       0
Bank Sta=4995.6,5001.6
Exp/Cntr=0.3,0.1

Type RM Length L Ch R = 1,1377,453,453,453
BEGIN DESCRIPTION:
UNT 0049 IN HEWA 3.0
END DESCRIPTION:
XS GIS Cut Line= 2
      2720802.70     10060355.69      2720221.84     10060192.32
#Sta/Elev= 30
  4688.3 1854.41  4723.9 1853.78  4744.6 1850.08  4750.4 1848.45  4765.4 1846.10
  4770.7 1845.89  4807.0 1844.08  4862.9 1840.50  4921.2 1835.80  4936.2 1832.28
  4942.0 1830.09  4962.6 1827.88  4975.5 1826.36  4994.0 1825.96  5001.3 1824.80
  5004.1 1824.30  5007.3 1824.80  5009.6 1825.81  5014.7 1829.49  5021.2 1830.95
  5035.5 1833.79  5043.6 1835.94  5048.7 1835.77  5056.3 1837.12  5077.1 1839.26
  5082.8 1840.35  5116.8 1842.28  5129.0 1842.89  5229.4 1844.50  5291.7 1844.84
#Mann=7,-1,0
  4688.3     0.1       0  4770.7    0.16       0  4962.6     0.1       0
  5001.3    0.07       0  5007.3     0.1       0  5009.6    0.16       0
  5021.2     0.1       0
Bank Sta=5001.3,5007.3
Exp/Cntr=0.3,0.1

Type RM Length L Ch R = 1,924,93,93,93
BEGIN DESCRIPTION:
UNT 0049 IN HEWA 2.0
END DESCRIPTION:
XS GIS Cut Line= 2
      2720848.18     10059682.24      2720288.52     10059987.10
#Sta/Elev= 30
  4671.7 1847.45  4708.7 1847.79  4724.8 1847.07  4730.5 1847.59  4784.7 1846.55
  4790.4 1846.19  4796.6 1844.17  4817.0 1839.59  4828.3 1837.20  4834.0 1837.27
  4850.2 1832.72  4855.9 1832.48  4872.0 1828.45  4877.7 1828.08  4893.9 1825.28
  4899.6 1825.03  4918.9 1821.62  4921.6 1821.12  4924.9 1821.62  5003.6 1822.13
  5092.7 1821.81  5100.9 1822.50  5115.5 1825.10  5150.3 1835.59  5172.4 1837.49
  5226.2 1838.52  5248.1 1839.72  5269.9 1839.86  5275.6 1839.26  5309.0 1839.78
#Mann=5,-1,0
  4671.7     0.1       0  4817.0    0.16       0  4918.9    0.07       0
  4924.9    0.16       0  5003.6     0.1       0
Bank Sta=4918.9,4924.9
Exp/Cntr=0.3,0.1

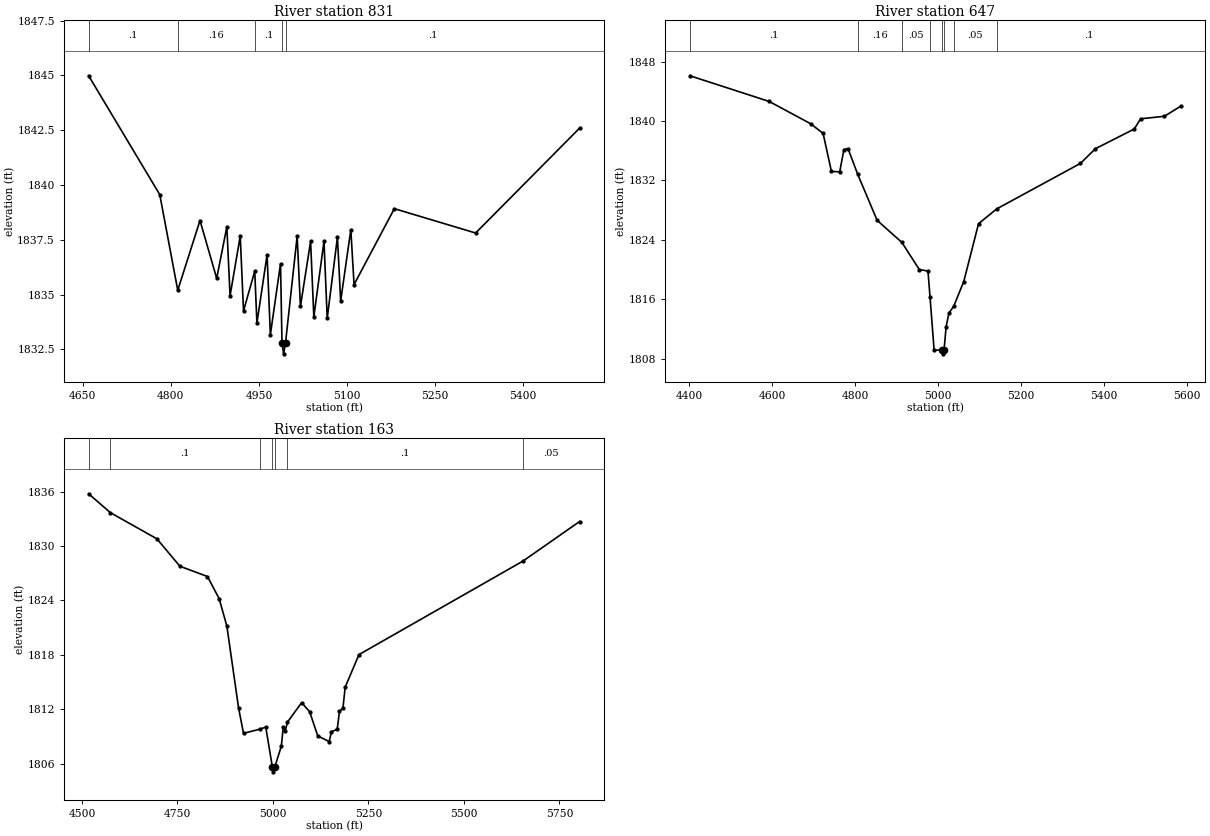
Type RM Length L Ch R = 1,831,184,184,184
BEGIN DESCRIPTION:
Mapping XS eb793d2b
END DESCRIPTION:
XS GIS Cut Line= 3
      2720834.65     10059608.16      2720299.94     10059858.15
      2720133.40     10060038.57
#Sta/Elev= 30
  4660.1 1844.98  4781.2 1839.56  4811.8 1835.20  4849.7 1838.38  4878.1 1835.74
  4895.4 1838.09  4900.9 1834.95  4918.2 1837.67  4923.8 1834.26  4942.9 1836.07
  4946.6 1833.70  4963.9 1836.81  4969.5 1833.17  4986.8 1836.41  4989.3 1832.80
  4992.0 1832.30  4995.3 1832.80  5015.1 1837.66  5020.7 1834.46  5038.0 1837.43
  5043.5 1833.99  5060.8 1837.43  5066.3 1833.92  5083.7 1837.62  5089.2 1834.71
  5106.5 1837.96  5112.0 1835.46  5180.6 1838.92  5319.0 1837.81  5495.9 1842.59
#Mann=5,-1,0
  4660.1     0.1       0  4811.8    0.16       0  4942.9     0.1       0
  4989.3    0.07       0  4995.3     0.1       0
Bank Sta=4989.3,4995.3
Exp/Cntr=0.3,0.1

Type RM Length L Ch R = 1,647,484,484,484
BEGIN DESCRIPTION:
Mapping XS 47d6ac42
END DESCRIPTION:
XS GIS Cut Line= 4
      2721029.10     10059531.76      2720556.88     10059510.93
      2720320.77     10059677.60      2720091.62     10060031.74
#Sta/Elev= 30
  4401.8 1846.08  4592.6 1842.63  4692.6 1839.63  4722.7 1838.33  4742.8 1833.21
  4762.8 1833.16  4772.8 1836.13  4782.8 1836.28  4806.3 1832.81  4852.9 1826.64
  4912.8 1823.65  4954.7 1820.01  4975.6 1819.81  4980.6 1816.25  4990.4 1809.17
  5008.3 1809.17  5011.1 1808.67  5014.3 1809.17  5019.4 1812.33  5026.1 1814.16
  5037.5 1815.05  5061.8 1818.39  5097.5 1826.18  5141.3 1828.17  5343.1 1834.29
  5379.3 1836.27  5473.0 1838.92  5488.1 1840.29  5545.5 1840.63  5585.3 1842.00
#Mann=8,-1,0
  4401.8     0.1       0  4806.3    0.16       0  4912.8    0.05       0
  4980.6    0.16       0  5008.3    0.07       0  5014.3    0.16       0
  5037.5    0.05       0  5141.3     0.1       0
Bank Sta=5008.3,5014.3
Exp/Cntr=0.3,0.1

Type RM Length L Ch R = 1,163,0,0,0
BEGIN DESCRIPTION:
UNT 0049 IN HEWA 1.0
END DESCRIPTION:
XS GIS Cut Line= 3
      2720923.96     10059254.31      2720397.28     10059153.77
      2719980.75     10059776.16
#Sta/Elev= 30
  4517.6 1835.75  4574.5 1833.67  4696.3 1830.79  4756.5 1827.77  4828.6 1826.64
  4859.2 1824.21  4879.5 1821.17  4910.1 1812.16  4923.0 1809.37  4964.9 1809.82
  4981.3 1810.05  4998.7 1805.63  5001.4 1805.13  5004.7 1805.63  5022.0 1807.95
  5027.2 1810.10  5032.3 1809.60  5038.0 1810.60  5075.2 1812.75  5096.2 1811.75
  5117.3 1809.09  5147.3 1808.46  5153.3 1809.55  5168.3 1809.81  5174.3 1811.78
  5183.3 1812.16  5189.3 1814.47  5225.3 1818.04  5654.3 1828.33  5802.7 1832.69
#Mann=7,-1,0
  4517.6    0.05       0  4574.5     0.1       0  4964.9    0.05       0
  4998.7   0.033       0  5004.7    0.05       0  5038.0     0.1       0
  5654.3    0.05       0
Bank Sta=4998.7,5004.7
Exp/Cntr=0.3,0.1

Chan Stop Cuts=-1