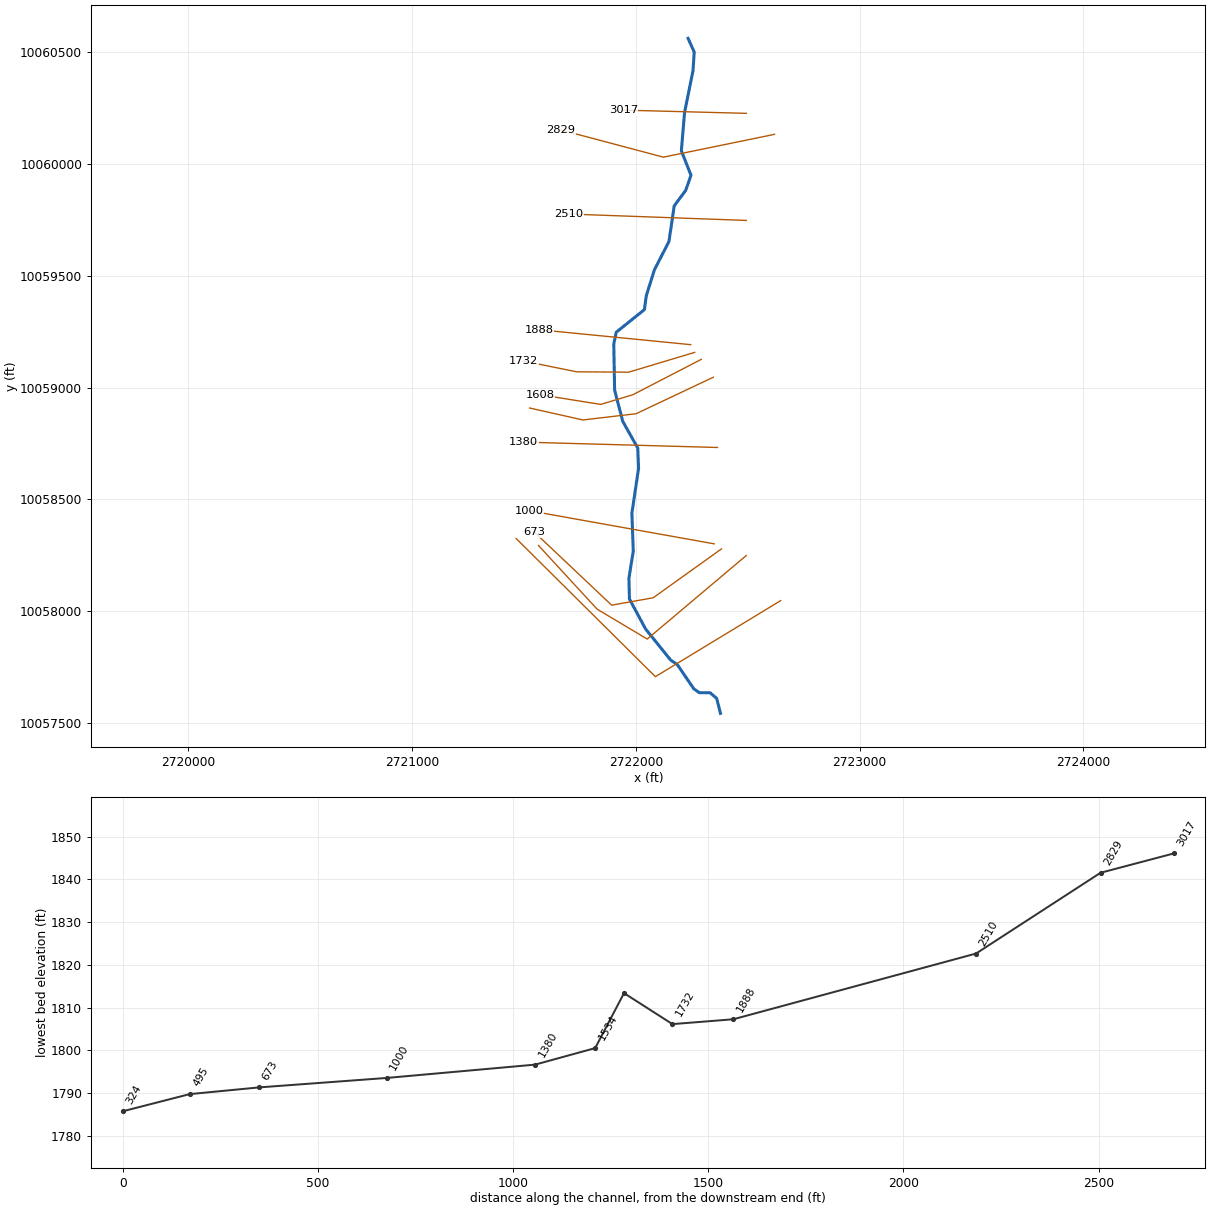
--- UNT 0050 IN HEWA.prj (project) ---

Proj Title=UNT 0050 IN HEWA Base Level Engineering
Current Plan=p01
Default Exp/Contr=0.3,0.1
English Units
Geom File=g01
Flow File=f01
Plan File=p01
Y Axis Title=Elevation
X Axis Title(PF)=Main Channel Distance
X Axis Title(XS)=Station
BEGIN DESCRIPTION:
UNT 0050 IN HEWA
END DESCRIPTION:
DSS Export Rating Curves= 0
DSS Export Rating Curve Sorted= 0
DSS Export Volume Flow Curves= 0
DXF OffsetX= 0
DXF OffsetY= 0
DXF ScaleX= 1
DXF ScaleY= 10

--- UNT 0050 IN HEWA.p01 (plan) ---

Plan Title=Multiple Run
Short Identifier=Multiple
Geom File=g01
Flow File=f01
Subcritical Flow
K Sum by GR= 0
Std Step Tol= 0.01
Critical Tol= 0.01
Num of Std Step Trials= 20
Max Error Tol= 0.3
Flow Tol Ratio= 0.001
Split Flow NTrial= 30
Split Flow Tol= 0.02
Split Flow Ratio= 0.02
Log Output Level= 0
Friction Slope Method= 1
Unsteady Friction Slope Method= 2
Unsteady Bridges Friction Slope Method= 1
Parabolic Critical Depth
Global Vel Dist=  1 , 1 , 1
Global Log Level= 0
CheckData=True
Encroach Param= -1, 0, 0, 0
BEGIN DESCRIPTION:
Multiple Run
END DESCRIPTION:

--- UNT 0050 IN HEWA.f01 (steady flow) ---

Flow Title=Multiple
Number of Profiles=7
Profile Names=10-year,25-year,50-year,1pct_min,100-year,1pct_plu,500-year
River Rch & RM= UNT 0050 IN HEWA,Reach-1,3017
     307     422     518     467     631     854     940
Boundary for River Rch & Prof#=UNT 0050 IN HEWA,Reach-1,1
Up Type=0
Dn Type=3
Dn Slope=0.005
Boundary for River Rch & Prof#=UNT 0050 IN HEWA,Reach-1,2
Up Type=0
Dn Type=3
Dn Slope=0.005
Boundary for River Rch & Prof#=UNT 0050 IN HEWA,Reach-1,3
Up Type=0
Dn Type=3
Dn Slope=0.005
Boundary for River Rch & Prof#=UNT 0050 IN HEWA,Reach-1,4
Up Type=0
Dn Type=3
Dn Slope=0.005
Boundary for River Rch & Prof#=UNT 0050 IN HEWA,Reach-1,5
Up Type=0
Dn Type=3
Dn Slope=0.005
Boundary for River Rch & Prof#=UNT 0050 IN HEWA,Reach-1,6
Up Type=0
Dn Type=3
Dn Slope=0.005
Boundary for River Rch & Prof#=UNT 0050 IN HEWA,Reach-1,7
Up Type=0
Dn Type=3
Dn Slope=0.005

--- UNT 0050 IN HEWA.g01 (geometry) ---

Geom Title=Existing Conditions
Program Version=4.10

River Reach=UNT 0050 IN HEWA,Reach-1
Reach XY= 30
      2722233.52     10060561.53      2722260.86     10060500.33
      2722255.66       10060417.      2722217.89      10060230.8
      2722203.47     10060058.73      2722246.62     10059949.51
      2722222.69     10059881.45      2722171.49     10059812.47
      2722148.12     10059653.68      2722083.06     10059526.54
      2722046.61     10059410.69       2722038.4     10059348.76
      2721912.43     10059247.73      2721901.36     10059194.82
      2721905.12     10058989.36      2721941.53     10058849.17
      2722008.51     10058729.99      2722012.23     10058639.91
      2721982.41     10058438.79      2721988.52      10058268.7
      2721969.14     10058148.43      2721971.43     10058054.98
      2722043.68      10057920.9      2722154.97     10057783.01
      2722185.49      10057761.7      2722259.06     10057653.66
      2722283.87     10057636.22      2722331.84     10057635.98
      2722361.18     10057610.83      2722378.47     10057543.73

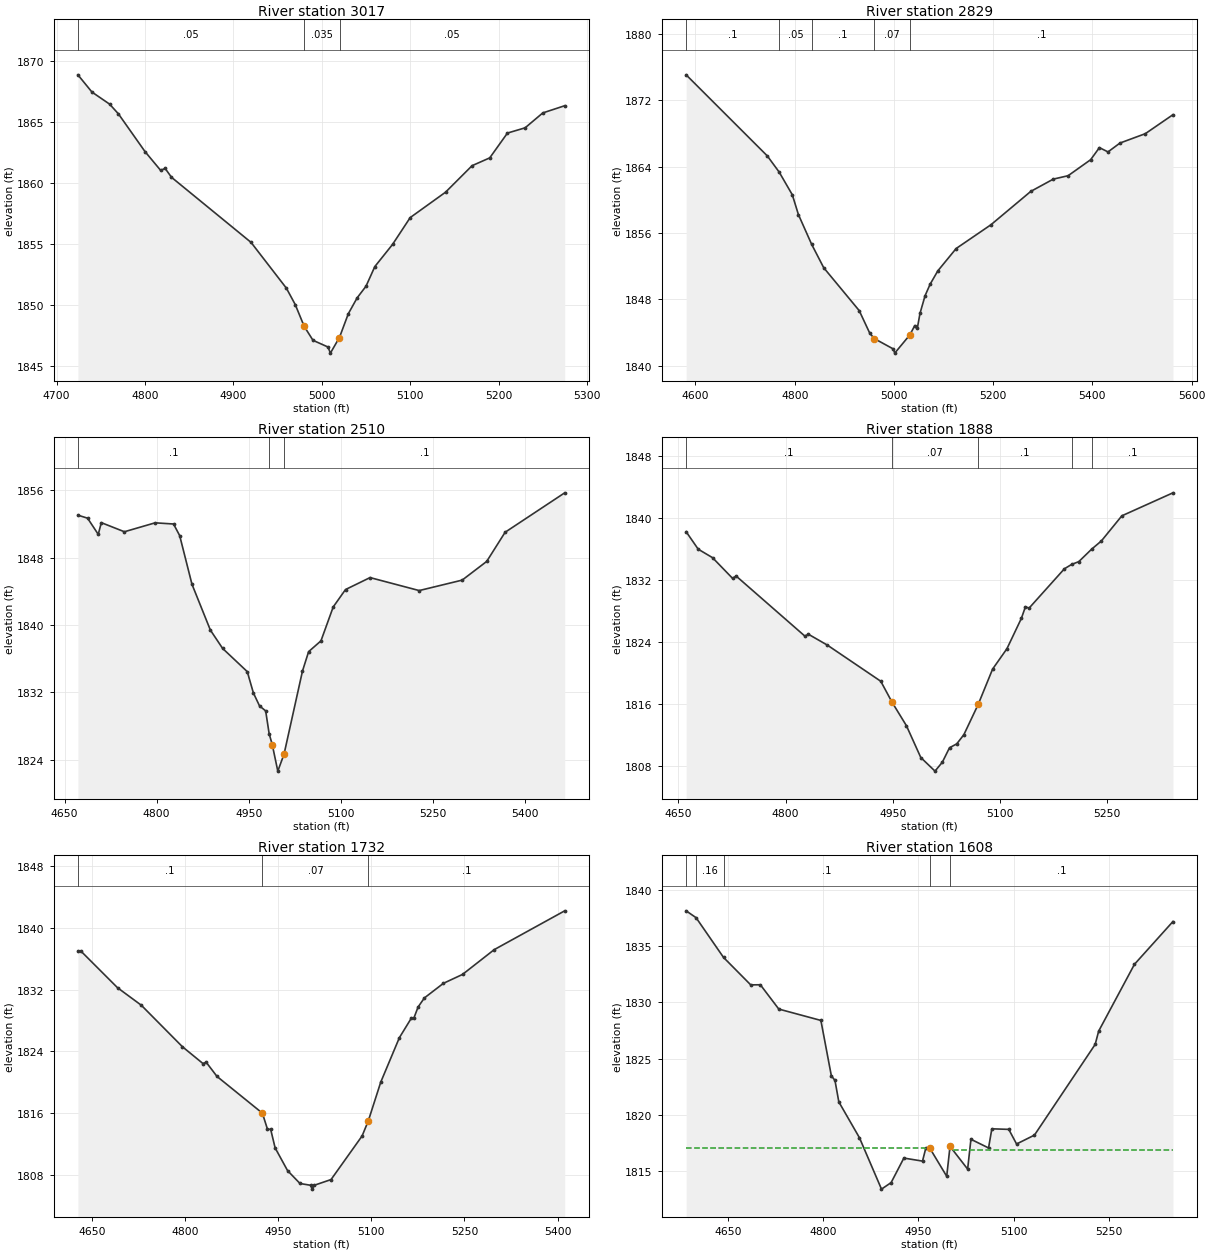
Type RM Length L Ch R = 1 ,3017    ,188,188,188
BEGIN DESCRIPTION:
UNT 0050 IN HEWA 6.0
END DESCRIPTION:
XS GIS Cut Line= 2
      2722494.33     10060226.22      2721943.72     10060240.58
#Sta/Elev= 30
    4724 1868.84  4739.9 1867.43  4759.9 1866.44  4769.9 1865.64  4799.9 1862.56
  4817.7 1861.01  4822.7 1861.18  4829.9 1860.45  4919.9 1855.12  4959.9 1851.37
  4969.9 1850.03    4980 1848.25    4990  1847.1    5007 1846.55  5009.7 1846.05
  5019.8 1847.32    5020 1847.34    5030 1849.28    5040 1850.58    5050 1851.53
    5060 1853.14    5080 1854.95    5100 1857.15    5140 1859.23    5170  1861.4
    5190 1862.04    5210 1864.07    5230  1864.5    5250 1865.72  5274.8 1866.31
#Mann= 3 ,-1 , 0
    4724     .05       0    4980    .035       0    5020     .05       0
Bank Sta=4980,5019.8
XS Rating Curve= 0 ,0
Exp/Cntr=0.3,0.1

Type RM Length L Ch R = 1 ,2829    ,319,319,319
BEGIN DESCRIPTION:
Mapping XS c54d39b2
END DESCRIPTION:
XS GIS Cut Line= 3
      2722620.15     10060132.34      2722123.18     10060030.34
      2721665.26     10060151.88
#Sta/Elev= 30
  4581.2 1875.09  4744.8 1865.31  4768.7 1863.36  4795.2 1860.62  4807.5 1858.23
  4834.2 1854.64  4858.5 1851.82    4930 1846.65  4951.4 1843.91  4960.6 1843.27
  4998.8 1842.02  5001.6 1841.52  5032.1 1843.72    5042 1844.85  5047.1 1844.51
  5052.5 1846.31  5062.7 1848.44  5072.9 1849.83  5088.4 1851.44  5125.4 1854.14
  5195.4    1857  5275.8 1861.03  5321.2 1862.51    5351 1862.92  5396.4 1864.85
  5414.1 1866.31  5431.4 1865.79  5455.5 1866.86  5506.6 1867.99  5562.3 1870.28
#Mann= 5 ,-1 , 0
  4581.2      .1       0  4768.7     .05       0  4834.2      .1       0
  4960.6     .07       0  5032.1      .1       0
Bank Sta=4960.6,5032.1
XS Rating Curve= 0 ,0
Exp/Cntr=0.3,0.1

Type RM Length L Ch R = 1 ,2510    ,622,622,622
BEGIN DESCRIPTION:
UNT 0050 IN HEWA 5.0
END DESCRIPTION:
XS GIS Cut Line= 2
      2722494.26     10059747.45      2721701.48      10059776.1
#Sta/Elev= 30
  4671.7 1853.03  4687.5 1852.67  4704.9 1850.75  4709.9 1852.14  4747.5 1851.06
  4797.6 1852.12  4827.6 1851.98  4837.6  1850.6  4857.6 1844.83  4887.6 1839.39
  4907.6 1837.21  4947.7 1834.46  4957.7 1831.93  4967.7 1830.39  4977.7  1829.8
  4983.4 1827.08  4988.4 1825.81  4997.5 1822.65  5007.7 1824.68  5037.7 1834.53
  5047.7 1836.83  5067.8 1838.11  5087.8 1842.14  5107.8  1844.2  5147.8 1845.62
  5227.9 1844.08  5297.9 1845.32  5337.9 1847.54  5367.9    1851    5465 1855.68
#Mann= 3 ,-1 , 0
  4671.7      .1       0  4983.4     .07       0  5007.7      .1       0
Bank Sta=4988.4,5007.7
XS Rating Curve= 0 ,0
Exp/Cntr=0.3,0.1

Type RM Length L Ch R = 1 ,1888    ,156,156,156
BEGIN DESCRIPTION:
UNT 0050 IN HEWA 4.0
END DESCRIPTION:
XS GIS Cut Line= 2
      2722245.31     10059192.07       2721567.3     10059258.92
#Sta/Elev= 30
  4660.8 1838.22  4677.7 1835.96  4697.8 1834.86  4725.8 1832.19  4730.8 1832.49
    4827 1824.73    4832 1824.97  4858.6 1823.56  4933.2  1818.9    4949 1816.19
  4969.1 1813.16  4989.2 1809.05  5009.1 1807.29  5019.4 1808.45  5029.4 1810.31
  5039.5 1810.81  5049.5    1812  5069.6 1815.92  5089.7 1820.47  5109.8 1823.11
  5129.9 1827.01  5135.7 1828.53  5140.7 1828.34  5190.2 1833.43  5200.3 1833.99
  5210.3 1834.35  5228.4 1835.97  5241.9 1837.02  5270.6 1840.27  5342.1 1843.24
#Mann= 5 ,-1 , 0
  4660.8      .1       0    4949     .07       0  5069.6      .1       0
  5200.3     .05       0  5228.4      .1       0
Bank Sta=4949,5069.6
XS Rating Curve= 0 ,0
Exp/Cntr=0.3,0.1

Type RM Length L Ch R = 1 ,1732    ,124,124,124
BEGIN DESCRIPTION:
Mapping XS 2a4539a5
END DESCRIPTION:
XS GIS Cut Line= 4
      2722262.96     10059157.56      2721967.86     10059069.03
      2721735.22     10059070.77      2721497.21     10059119.06
#Sta/Elev= 30
  4627.7 1836.99  4632.6 1836.99  4691.5 1832.25  4729.8 1829.98  4795.9 1824.61
    4829 1822.43  4834.2  1822.6  4851.6 1820.76  4924.7    1816  4932.9 1813.91
    4938 1813.91  4945.2  1811.5  4965.2 1808.56  4985.2 1806.89  5002.2 1806.66
  5004.9 1806.16  5008.2 1806.66  5035.2  1807.4  5085.2 1813.05  5095.2 1815.01
  5115.2 1820.02  5145.2 1825.78  5164.3 1828.29  5168.4 1828.29  5175.3 1829.75
  5185.5 1830.93  5216.1 1832.82  5246.8 1833.97  5297.8 1837.18  5411.3 1842.21
#Mann= 3 , 0 , 0
  4627.7      .1       0  4924.7     .07       0  5095.2      .1       0
Bank Sta=4924.7,5095.2
XS Rating Curve= 0 ,0
Exp/Cntr=0.3,0.1

Type RM Length L Ch R = 1 ,1608    ,74,74,74
BEGIN DESCRIPTION:
Mapping XS 9883cbf3
END DESCRIPTION:
XS GIS Cut Line= 4
      2722292.49     10059126.31      2721986.96     10058968.34
      2721842.86     10058924.93      2721572.76     10058968.22
#Sta/Elev= 30
  4583.5 1838.13  4599.2 1837.52  4642.5 1833.99  4685.4 1831.55  4700.6 1831.56
  4729.7  1829.4  4796.1 1828.39  4812.6 1823.47  4818.3 1823.06  4824.4 1821.15
  4856.9 1817.97  4891.7  1813.4  4906.9 1813.98    4927 1816.16  4956.4 1815.89
  4961.6 1817.04  4967.7 1817.06  4994.6 1814.54  4999.8  1817.2  5027.6 1815.18
  5032.8 1817.83  5060.6 1817.06  5065.8 1818.76  5092.5 1818.71  5104.8 1817.41
    5133  1818.2  5228.8 1826.26  5234.3 1827.44  5290.8 1833.38  5351.5 1837.18
#Mann= 5 ,-1 , 0
  4583.5      .1       0  4599.2     .16       0  4642.5      .1       0
  4967.7     .07       0  4999.8      .1       0
#XS Ineff= 2 , 0
         4960.32 1817.05 5005.38         1816.84
Permanent Ineff=
       T       T
Bank Sta=4967.7,4999.8
XS Rating Curve= 0 ,0
Exp/Cntr=0.3,0.1

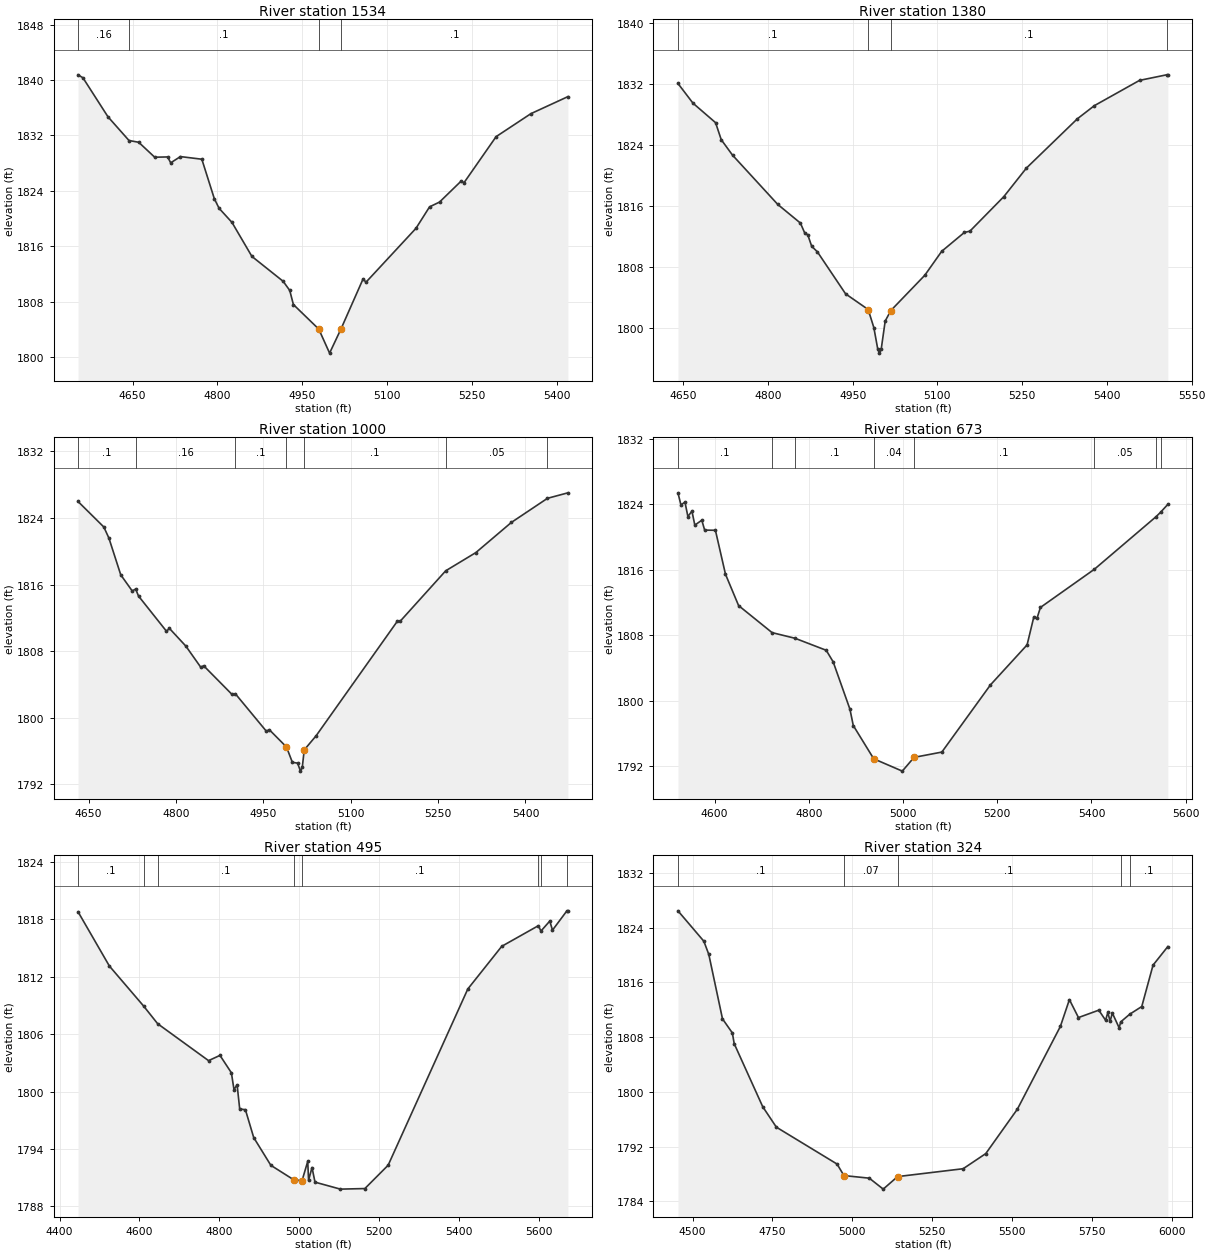
Type RM Length L Ch R = 1 ,1534    ,154,154,154
BEGIN DESCRIPTION:
Mapping XS 51bb1189
END DESCRIPTION:
XS GIS Cut Line= 4
      2722346.32     10059046.46      2722000.84     10058883.27
        2721763.     10058855.49      2721524.68     10058909.02
#Sta/Elev= 30
  4553.7 1840.75  4562.4 1840.32  4606.6 1834.69  4643.8 1831.26  4660.9 1831.01
  4689.2 1828.85    4712 1828.89  4717.5 1828.04  4734.7 1828.94  4772.5 1828.56
  4794.6 1822.85    4803 1821.47  4825.8 1819.43    4861 1814.52  4916.3 1810.92
  4927.9  1809.6  4934.3 1807.57  4979.2 1804.02  4998.3 1800.55  5018.7 1804.09
  5057.5 1811.27  5062.6 1810.79    5151 1818.58    5175 1821.68  5192.6 1822.37
  5230.8  1825.4    5236 1825.18  5292.6 1831.82  5354.1 1835.14  5419.5  1837.6
#Mann= 4 ,-1 , 0
  4553.7     .16       0  4643.8      .1       0  4979.2     .07       0
  5018.7      .1       0
Bank Sta=4979.2,5018.7
XS Rating Curve= 0 ,0
Exp/Cntr=0.3,0.1

Type RM Length L Ch R = 1 ,1380    ,380,380,380
BEGIN DESCRIPTION:
UNT 0050 IN HEWA 3.0
END DESCRIPTION:
XS GIS Cut Line= 2
      2722365.08     10058732.45      2721498.41     10058756.39
#Sta/Elev= 30
  4640.8 1832.08  4667.4 1829.49  4707.4 1826.93  4717.4  1824.7  4737.4 1822.67
  4817.5  1816.2  4857.5 1813.76  4865.5  1812.4  4870.5 1812.23  4877.5 1810.71
  4887.5 1809.99  4937.5 1804.47  4977.5 1802.41  4987.5 1800.04  4994.5 1797.19
  4997.3 1796.69  5000.5 1797.19  5007.6  1800.9  5017.6 1802.28  5077.6  1806.9
  5107.6 1810.05  5147.6 1812.52  5157.6  1812.7  5217.6 1817.23  5257.6 1820.98
  5347.7 1827.44  5377.7 1829.16  5457.7 1832.48  5505.6 1833.21  5507.8 1833.21
#Mann= 4 ,-1 , 0
  4640.8      .1       0  4977.5     .07       0  5017.6      .1       0
  5505.6     .05       0
Bank Sta=4977.5,5017.6
XS Rating Curve= 0 ,0
Exp/Cntr=0.3,0.1

Type RM Length L Ch R = 1 ,1000    ,327,327,327
BEGIN DESCRIPTION:
UNT 0050 IN HEWA 2.0
END DESCRIPTION:
XS GIS Cut Line= 2
      2722350.63     10058301.56      2721522.91     10058449.88
#Sta/Elev= 30
  4631.9 1825.98  4676.2 1822.91  4684.9 1821.58  4705.2 1817.17  4724.9 1815.23
  4730.8 1815.46  4735.7 1814.62  4783.7 1810.39  4788.8 1810.73    4817  1808.6
  4842.5 1806.07  4847.6 1806.24  4896.3 1802.79  4901.9 1802.88  4955.1 1798.38
  4960.2 1798.56  4989.7 1796.48  4999.8 1794.64  5008.8 1794.54  5013.7 1793.58
  5016.9 1794.08  5020.2 1796.13  5040.5 1797.82  5180.2 1811.61  5185.3 1811.62
    5263 1817.65  5314.8 1819.84  5375.7 1823.46  5437.7 1826.36  5472.8 1827.02
#Mann= 7 ,-1 , 0
  4631.9      .1       0  4730.8     .16       0  4901.9      .1       0
  4989.7     .07       0  5020.2      .1       0    5263     .05       0
  5437.7      .1       0
Bank Sta=4989.7,5020.2
XS Rating Curve= 0 ,0
Exp/Cntr=0.3,0.1

Type RM Length L Ch R = 1 ,673     ,178,178,178
BEGIN DESCRIPTION:
Mapping XS b37dd6a0
END DESCRIPTION:
XS GIS Cut Line= 4
       2722383.1     10058279.22      2722077.58     10058060.49
      2721891.82     10058027.51      2721546.33      10058353.9
#Sta/Elev= 30
  4522.4 1825.41  4528.7 1823.94  4537.3 1824.27  4543.5 1822.51  4552.1 1823.17
  4558.2 1821.46    4573 1822.06  4579.1 1820.85  4601.9 1820.83  4623.3 1815.45
  4651.1 1811.62  4722.2 1808.31  4770.9 1807.62  4837.1 1806.15  4851.8 1804.74
  4887.4 1798.95  4894.5 1796.95  4937.9 1792.88  4998.6 1791.37  5023.4 1793.05
  5082.5  1793.7  5185.7 1801.92  5263.4 1806.81  5277.5 1810.18  5284.4 1810.05
  5291.7 1811.39  5406.2 1816.06  5537.1 1822.49  5546.7 1823.03  5562.1    1824
#Mann= 8 ,-1 , 0
  4522.4      .1       0  4722.2     .16       0  4770.9      .1       0
  4937.9     .04       0  5023.4      .1       0  5406.2     .05       0
  5537.1      .1       0  5546.7     .05       0
Bank Sta=4937.9,5023.4
XS Rating Curve= 0 ,0
Exp/Cntr=0.3,0.1

Type RM Length L Ch R = 1 ,495     ,171,171,171
BEGIN DESCRIPTION:
Mapping XS ad2b8461
END DESCRIPTION:
XS GIS Cut Line= 4
      2722493.55     10058249.29      2722050.83     10057876.01
      2721826.87     10058009.69      2721564.74     10058294.39
#Sta/Elev= 30
  4446.2 1818.79  4524.7 1813.12  4610.2 1808.95  4645.6 1807.09  4773.1 1803.23
  4801.7 1803.78  4830.3 1801.96  4836.8  1800.2  4844.6 1800.71  4851.1 1798.18
  4865.4  1798.1  4886.2 1795.19  4929.1 1792.29  4986.3 1790.78  5007.2 1790.68
  5021.5  1792.7  5023.6 1790.73  5032.2 1792.06  5039.7 1790.53  5103.2  1789.8
  5164.6 1789.86  5222.9  1792.3  5422.4 1810.72  5507.4 1815.18  5599.3 1817.34
  5605.5 1816.77  5627.7 1817.82  5634.5 1816.87  5670.6 1818.89  5673.1 1818.89
#Mann= 8 ,-1 , 0
  4446.2      .1       0  4610.2     .16       0  4645.6      .1       0
  4986.3     .07       0  5007.2      .1       0  5599.3      .1       0
  5605.5     .05       0  5670.6      .1       0
#XS Ineff= 2 , 0
                         5020.64         1792.56
Permanent Ineff=
       T       T
Bank Sta=4986.3,5007.2
XS Rating Curve= 0 ,0
Exp/Cntr=0.3,0.1

Type RM Length L Ch R = 1 ,324     ,0,0,0
BEGIN DESCRIPTION:
UNT 0050 IN HEWA 1.0
END DESCRIPTION:
XS GIS Cut Line= 3
      2722647.53     10058047.81      2722087.35     10057707.87
      2721464.94     10058325.49
#Sta/Elev= 30
  4454.4 1826.45  4535.4 1822.01  4550.9 1820.08  4593.7 1810.67  4624.5 1808.62
  4630.4 1807.04  4719.5 1797.84  4762.2 1794.85  4952.1 1789.46  4973.5 1787.78
  5052.9  1787.4  5096.4  1785.8  5141.3 1787.63  5346.4 1788.78  5417.1 1790.99
  5516.1 1797.49  5650.4 1809.56  5678.7 1813.48    5707 1810.86  5770.6 1811.94
  5791.8 1810.47  5798.9  1811.6    5806 1810.32    5813 1811.52  5834.3 1809.36
  5839.2 1810.23    5868 1811.37    5905 1812.47  5940.3 1818.52  5986.5 1821.23
#Mann= 5 ,-1 , 0
  4454.4      .1       0  4973.5     .07       0  5141.3      .1       0
  5839.2     .05       0    5868      .1       0
Bank Sta=4973.5,5141.3
XS Rating Curve= 0 ,0
Exp/Cntr=0.3,0.1

Chan Stop Cuts=-1
Use User Specified Reach Order=0
Composite Channel Slope=5