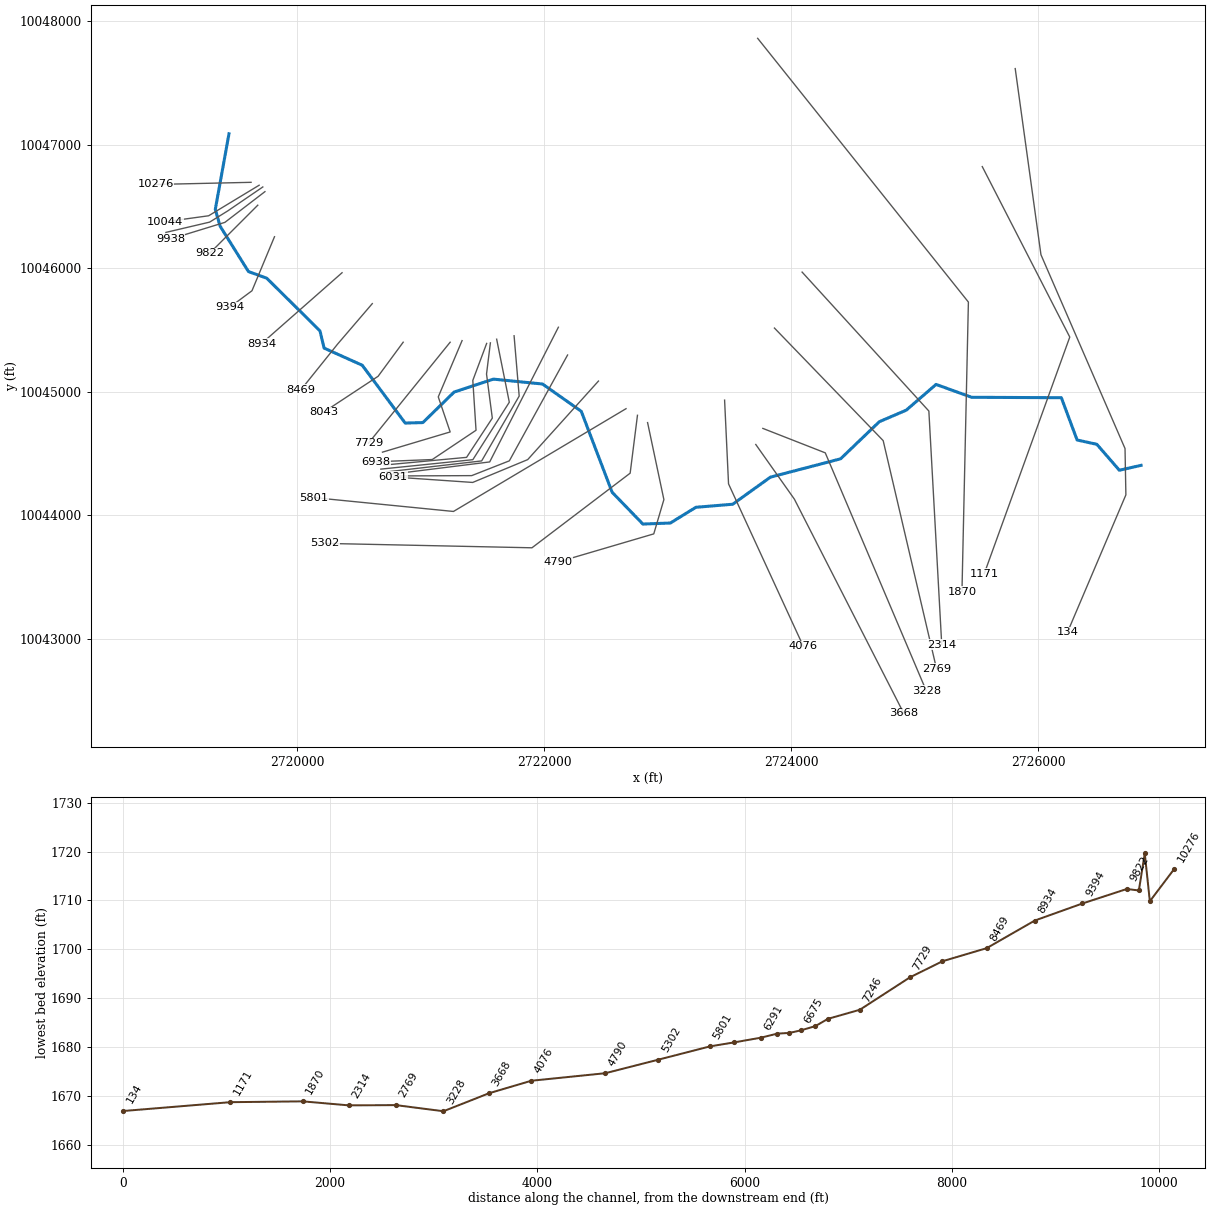
--- UNT 0051 IN HEWA.prj (project) ---

Proj Title=UNT 0051 IN HEWA Base Level Engineering
Current Plan=p01
Default Exp/Contr=0.3,0.1
English Units
Geom File=g01
Flow File=f01
Plan File=p01
Y Axis Title=Elevation
X Axis Title(PF)=Main Channel Distance
X Axis Title(XS)=Station
BEGIN DESCRIPTION:
UNT 0051 IN HEWA
END DESCRIPTION:
DSS Export Rating Curves= 0
DSS Export Rating Curve Sorted= 0
DSS Export Volume Flow Curves= 0
DXF OffsetX= 0
DXF OffsetY= 0
DXF ScaleX= 1
DXF ScaleY= 10

--- UNT 0051 IN HEWA.p01 (plan) ---

Plan Title=Multiple Run
Short Identifier=Multiple
Geom File=g01
Flow File=f01
Subcritical Flow
K Sum by GR= 0
Std Step Tol= 0.01
Critical Tol= 0.01
Num of Std Step Trials= 20
Max Error Tol= 0.3
Flow Tol Ratio= 0.001
Split Flow NTrial= 30
Split Flow Tol= 0.02
Split Flow Ratio= 0.02
Log Output Level= 0
Friction Slope Method= 1
Unsteady Friction Slope Method= 2
Unsteady Bridges Friction Slope Method= 1
Parabolic Critical Depth
Global Vel Dist=  1 , 1 , 1
Global Log Level= 0
CheckData=True
Encroach Param= -1, 0, 0, 0
BEGIN DESCRIPTION:
Multiple Run
END DESCRIPTION:

--- UNT 0051 IN HEWA.f01 (steady flow) ---

Flow Title=Multiple
Number of Profiles=7
Profile Names=10-year,25-year,50-year,1pct_min,100-year,1pct_plu,500-year
River Rch & RM= UNT 0051 IN HEWA,Reach-1,10276
     768    1108    1401    1296    1753    2370    2754
River Rch & RM= UNT 0051 IN HEWA,Reach-1,4076
     999    1462    1866    1741    2355    3185    3768
River Rch & RM= UNT 0051 IN HEWA,Reach-1,1870
    1290    1912    2460    2313    3127    4229    5080
Boundary for River Rch & Prof#=UNT 0051 IN HEWA,Reach-1,1
Up Type=0
Dn Type=3
Dn Slope=0.005
Boundary for River Rch & Prof#=UNT 0051 IN HEWA,Reach-1,2
Up Type=0
Dn Type=3
Dn Slope=0.005
Boundary for River Rch & Prof#=UNT 0051 IN HEWA,Reach-1,3
Up Type=0
Dn Type=3
Dn Slope=0.005
Boundary for River Rch & Prof#=UNT 0051 IN HEWA,Reach-1,4
Up Type=0
Dn Type=3
Dn Slope=0.005
Boundary for River Rch & Prof#=UNT 0051 IN HEWA,Reach-1,5
Up Type=0
Dn Type=3
Dn Slope=0.005
Boundary for River Rch & Prof#=UNT 0051 IN HEWA,Reach-1,6
Up Type=0
Dn Type=3
Dn Slope=0.005
Boundary for River Rch & Prof#=UNT 0051 IN HEWA,Reach-1,7
Up Type=0
Dn Type=3
Dn Slope=0.005

--- UNT 0051 IN HEWA.g01 (geometry) ---

Geom Title=Existing Conditions
Program Version=4.10

River Reach=UNT 0051 IN HEWA,Reach-1
Reach XY= 30
      2719449.61     10047087.73      2719338.77     10046475.21
      2719377.38     10046339.73      2719607.14     10045971.79
      2719754.85     10045918.19      2720186.04     10045491.56
      2720219.48     10045351.85      2720527.93     10045213.35
      2720875.76     10044745.09      2721018.95     10044748.89
      2721272.18     10044996.16      2721589.71     10045100.73
      2721987.47     10045061.32      2722301.29     10044840.17
      2722550.95     10044184.76      2722799.92     10043927.25
      2723022.61     10043935.81      2723229.01     10044063.06
      2723527.08     10044087.82      2723832.24     10044307.15
      2724400.42     10044455.55       2724713.5     10044755.85
      2724931.84     10044849.45       2725173.1     10045057.91
      2725461.18     10044953.72       2726187.3     10044950.26
      2726314.72       10044608.      2726474.69      10044572.9
      2726656.93     10044362.93      2726832.55     10044402.72

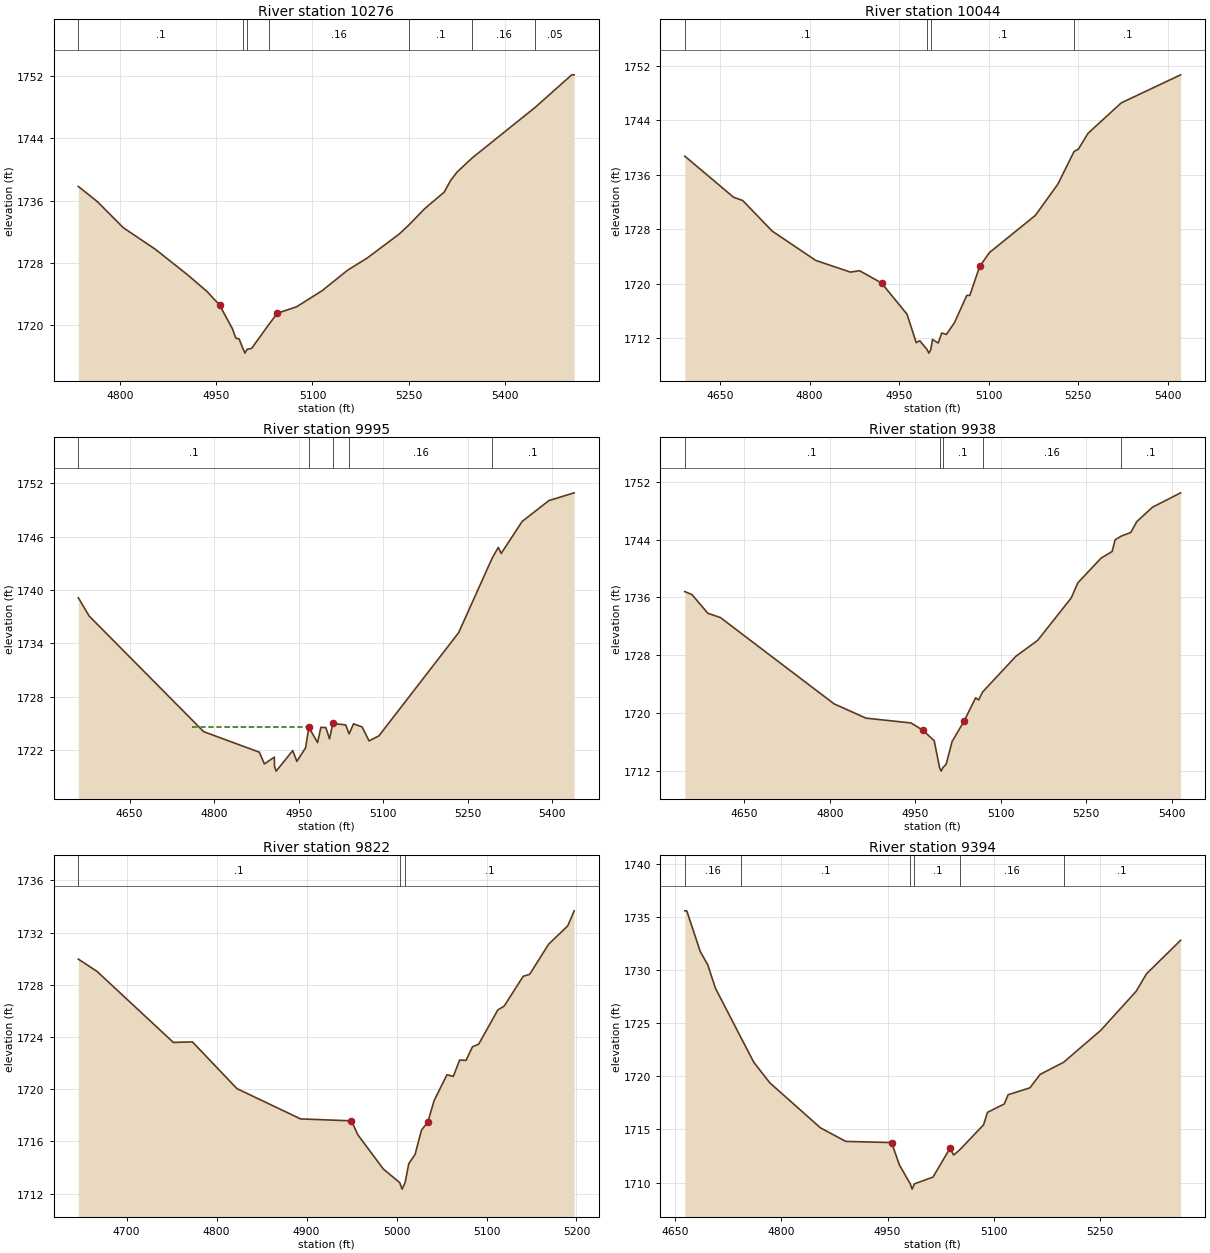
Type RM Length L Ch R = 1 ,10276   ,232,232,232
BEGIN DESCRIPTION:
UNT 0051 IN HEWA 18.0
END DESCRIPTION:
XS GIS Cut Line= 2
      2719628.38     10046694.26      2718855.87      10046676.9
#Sta/Elev= 30
  4735.1 1737.81    4765 1735.84    4805 1732.51    4855 1729.73  4905.1 1726.45
  4935.1 1724.33  4955.1 1722.55  4975.1 1719.51  4980.6 1718.28  4985.6 1718.19
  4992.1 1716.85  4994.8 1716.35  4998.1 1716.85  5005.1 1716.95  5031.5 1719.98
  5045.1 1721.48  5075.1 1722.31  5115.1 1724.39  5155.1 1727.05  5185.1 1728.58
  5235.1 1731.68  5250.3 1732.85  5275.1 1734.97  5305.2 1737.07  5315.2 1738.57
  5325.2 1739.65  5348.9 1741.48  5447.5 1748.02    5504 1752.18  5507.8 1752.18
#Mann= 7 ,-1 , 0
  4735.1      .1       0  4992.1     .07       0  4998.1      .1       0
  5031.5     .16       0  5250.3      .1       0  5348.9     .16       0
  5447.5     .05       0
Bank Sta=4955.1,5045.1
XS Rating Curve= 0 ,0
Exp/Cntr=0.3,0.1

Type RM Length L Ch R = 1 ,10044   ,49,49,49
BEGIN DESCRIPTION:
Mapping XS 3a0e65d5
END DESCRIPTION:
XS GIS Cut Line= 3
      2719693.71     10046670.78      2719284.85     10046423.38
      2718934.63     10046375.21
#Sta/Elev= 30
  4590.6 1738.72  4672.3  1732.7  4687.8 1732.21    4737 1727.74    4810 1723.44
  4868.2 1721.72  4883.7 1721.92  4920.5 1720.12  4963.2 1715.55  4978.7 1711.37
  4984.6 1711.66  4997.1 1710.34  4999.8 1709.84  5003.1 1710.34  5005.9 1711.84
  5015.6 1711.33  5021.4 1712.79  5029.2 1712.58  5042.8  1714.3  5063.4  1718.3
  5068.5  1718.3    5085 1722.54  5101.4 1724.58  5178.4 1730.03  5216.2 1734.62
  5243.4 1739.41  5250.5 1739.74  5266.7 1742.06  5322.5 1746.53    5422 1750.64
#Mann= 4 ,-1 , 0
  4590.6      .1       0  4997.1     .07       0  5003.1      .1       0
  5243.4      .1       0
Bank Sta=4920.5,5085
XS Rating Curve= 0 ,0
Exp/Cntr=0.3,0.1

Type RM Length L Ch R = 1 ,9995    ,57,57,57
BEGIN DESCRIPTION:
Mapping XS 726f9804
END DESCRIPTION:
XS GIS Cut Line= 4
      2719723.52     10046656.74      2719438.83     10046462.32
      2719292.99     10046372.04      2718938.92     10046288.73
#Sta/Elev= 30
  4558.9 1739.13  4578.1 1737.07  4781.4 1724.06  4880.2 1721.75  4889.1 1720.43
  4906.8  1721.2  4907.2 1720.12    4910 1719.62  4939.4 1721.93  4946.8 1720.72
  4962.2 1722.24  4968.1 1724.54  4983.5 1722.83  4989.4 1724.55  4998.2 1724.52
  5004.7 1723.25  5010.6 1724.99  5033.4 1724.82  5039.5 1723.81  5047.3 1724.94
  5062.6 1724.59  5074.9 1723.02  5092.4 1723.59  5233.9  1735.2  5293.2 1743.56
  5304.3 1744.79  5309.4 1744.11  5346.7 1747.72  5394.2 1750.06  5438.9 1750.93
#Mann= 5 ,-1 , 0
  4558.9      .1       0  4968.1     .07       0  5010.6      .1       0
  5039.5     .16       0  5293.2      .1       0
#XS Ineff= 2 ,-1
 4760.13 4966.91 1724.58 5011.93 5111.13 1724.93
Permanent Ineff=
       T       T
Bank Sta=4968.1,5010.6
XS Rating Curve= 0 ,0
Exp/Cntr=0.3,0.1

Type RM Length L Ch R = 1 ,9938    ,116,116,116
BEGIN DESCRIPTION:
Mapping XS 30db4c2f
END DESCRIPTION:
XS GIS Cut Line= 3
      2719740.57     10046618.69      2719416.36     10046369.99
      2718974.97     10046234.58
#Sta/Elev= 30
  4545.6 1736.82  4558.3 1736.39  4586.1 1733.82  4608.1 1733.23  4807.5 1721.33
  4863.7 1719.35  4942.6 1718.69  4963.1  1717.7  4983.4 1716.24  4992.8 1712.54
  4995.6 1712.04  4998.8 1712.54  5004.3 1712.97  5014.8 1716.13  5035.7 1718.93
  5056.1 1722.16  5061.3 1721.86  5068.2 1722.95  5126.8 1727.89  5164.8 1730.07
    5224 1735.95  5235.5 1738.02  5276.3 1741.43  5295.7 1742.35  5300.9 1743.95
  5311.2 1744.45  5328.4 1744.97    5339 1746.47  5366.4 1748.45  5415.9 1750.44
#Mann= 5 ,-1 , 0
  4545.6      .1       0  4992.8     .07       0  4998.8      .1       0
  5068.2     .16       0  5311.2      .1       0
Bank Sta=4963.1,5035.7
XS Rating Curve= 0 ,0
Exp/Cntr=0.3,0.1

Type RM Length L Ch R = 1 ,9822    ,428,428,428
BEGIN DESCRIPTION:
UNT 0051 IN HEWA 17.0
END DESCRIPTION:
XS GIS Cut Line= 2
      2719682.56     10046509.02      2719292.87     10046119.33
#Sta/Elev= 30
  4646.3 1729.97  4667.1 1729.03  4751.9 1723.59  4773.1 1723.63  4822.6 1720.05
  4893.3 1717.73  4949.9 1717.58    4957 1716.51  4985.3 1713.89  5003.5 1712.85
  5006.2 1712.35  5009.5 1712.85  5013.6  1714.3  5020.6 1715.01  5027.7 1716.87
  5034.8  1717.5  5041.8 1719.14    5056 1721.11  5063.1 1720.99  5070.1 1722.24
  5077.2 1722.21  5084.3 1723.25  5091.3 1723.46  5112.6 1726.08  5119.6 1726.37
  5140.8 1728.66  5147.9  1728.8  5169.1 1731.12  5190.3 1732.52  5197.4 1733.67
#Mann= 3 ,-1 , 0
  4646.3      .1       0  5003.5     .07       0  5009.5      .1       0
Bank Sta=4949.9,5034.8
XS Rating Curve= 0 ,0
Exp/Cntr=0.3,0.1

Type RM Length L Ch R = 1 ,9394    ,460,460,460
BEGIN DESCRIPTION:
UNT 0051 IN HEWA 16.0
END DESCRIPTION:
XS GIS Cut Line= 3
      2719817.98     10046253.81      2719635.68     10045816.31
      2719453.43     10045680.92
#Sta/Elev= 30
  4663.3 1735.57  4666.1 1735.57  4685.1 1731.75  4695.7  1730.5  4706.7 1728.28
  4742.9 1723.62  4760.9 1721.32  4783.5 1719.39    4855 1715.16  4890.9 1713.88
  4955.7 1713.77  4966.7 1711.67    4982 1709.89  4984.7 1709.39    4988 1709.89
  5014.2 1710.52  5038.1 1713.22  5043.5  1712.6  5052.5 1713.12  5085.7 1715.44
  5091.2 1716.61    5115  1717.4  5120.4 1718.27  5151.2 1718.92  5165.8 1720.19
  5198.8 1721.32  5251.4 1724.33  5301.4    1728    5316 1729.64  5364.3  1732.8
#Mann= 6 ,-1 , 0
  4663.3     .16       0  4742.9      .1       0    4982     .07       0
    4988      .1       0  5052.5     .16       0  5198.8      .1       0
Bank Sta=4955.7,5038.1
XS Rating Curve= 0 ,0
Exp/Cntr=0.3,0.1

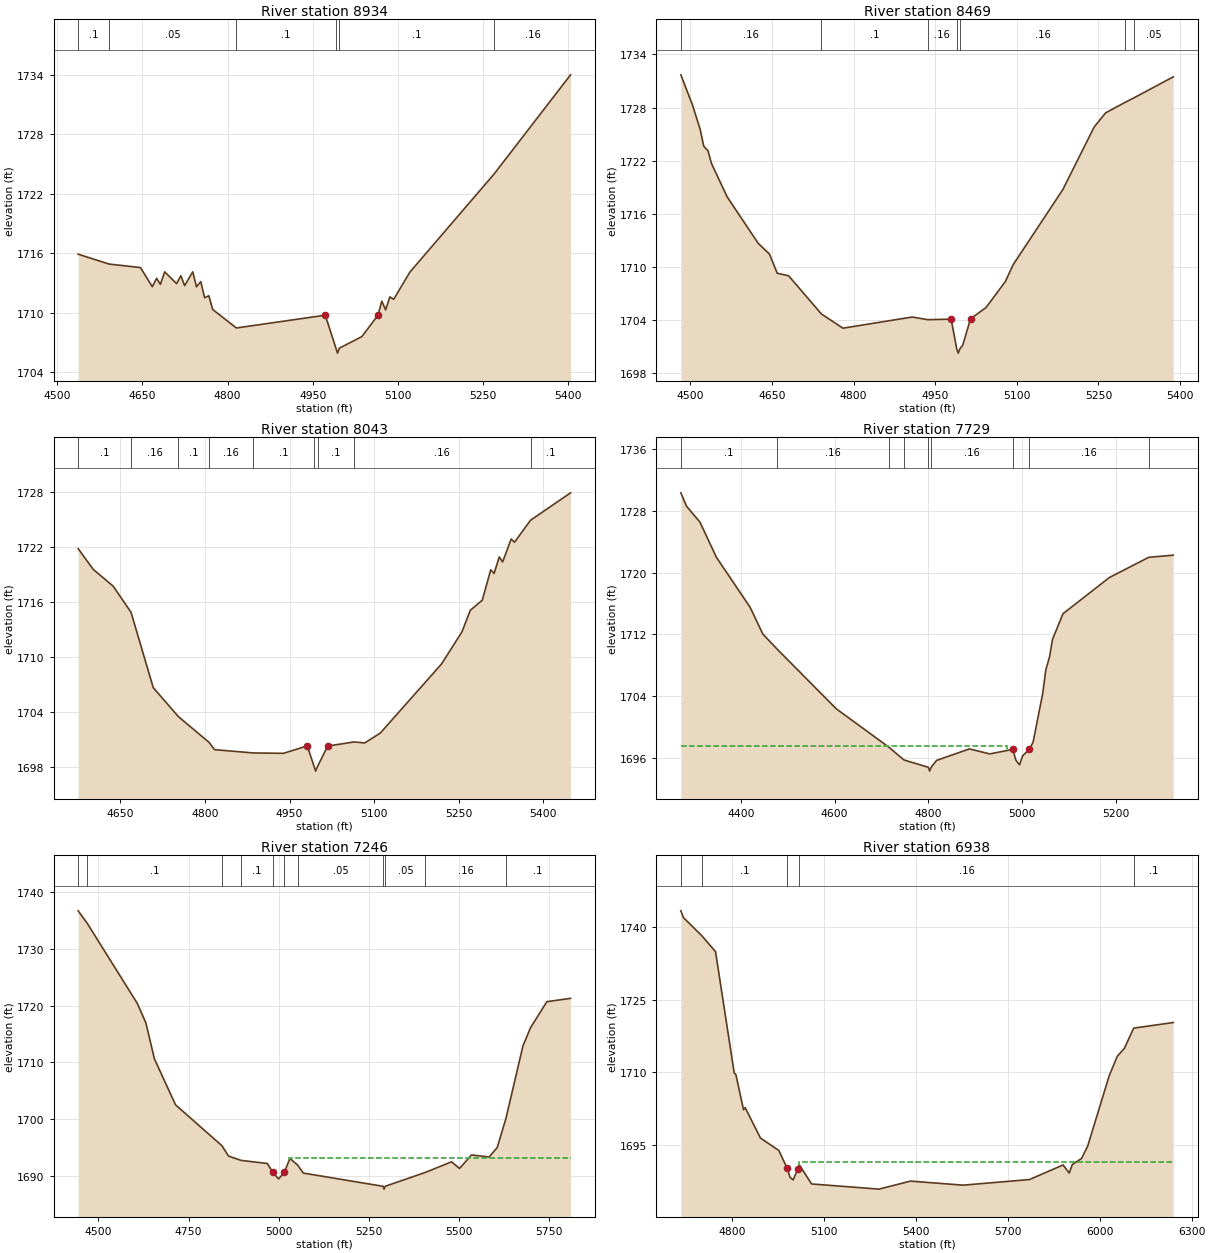
Type RM Length L Ch R = 1 ,8934    ,465,465,465
BEGIN DESCRIPTION:
UNT 0051 IN HEWA 15.0
END DESCRIPTION:
XS GIS Cut Line= 2
      2720364.82     10045962.12       2719713.8     10045389.22
#Sta/Elev= 30
  4536.8 1715.89  4591.5 1714.89  4646.5 1714.54  4667.4 1712.61    4675 1713.45
  4681.6 1712.85  4689.2 1714.11  4710.1 1712.92  4717.7 1713.71  4724.3 1712.71
  4738.6 1714.11  4745.2  1712.6  4752.8 1713.12  4759.5 1711.49    4767 1711.69
  4773.7 1710.31  4815.4 1708.44    4972 1709.73  4990.8  1706.4  4993.5  1705.9
  4996.8  1706.4  5036.5 1707.57  5064.8 1709.73  5071.6 1711.15  5078.2 1710.27
  5085.8 1711.58  5092.5 1711.33  5120.9 1714.07  5269.7 1724.01    5404    1734
#Mann= 6 ,-1 , 0
  4536.8      .1       0  4591.5     .05       0  4815.4      .1       0
  4990.8     .07       0  4996.8      .1       0  5269.7     .16       0
Bank Sta=4972,5064.8
XS Rating Curve= 0 ,0
Exp/Cntr=0.3,0.1

Type RM Length L Ch R = 1 ,8469    ,426,426,426
BEGIN DESCRIPTION:
UNT 0051 IN HEWA 14.0
END DESCRIPTION:
XS GIS Cut Line= 3
      2720609.65     10045712.15      2720328.39     10045384.02
      2720032.51     10045015.47
#Sta/Elev= 30
  4482.6  1731.7  4503.9 1728.31  4518.1 1725.54  4524.7 1723.63  4532.4 1723.13
    4539 1721.67  4567.5 1717.93  4624.6 1712.67  4645.5 1711.44  4659.7 1709.28
  4680.6 1708.99    4741 1704.67  4780.5 1703.07  4907.8 1704.33  4936.2 1704.03
  4979.3 1704.09  4989.5 1700.75  4992.3 1700.25  4995.5 1700.75  5000.5 1701.13
  5014.9 1704.13  5043.4  1705.4  5078.9 1708.34  5093.3 1710.25  5184.5 1718.73
  5242.1  1725.8  5262.9 1727.39  5298.7 1728.58  5315.3  1729.1  5387.4 1731.47
#Mann= 7 ,-1 , 0
  4482.6     .16       0    4741      .1       0  4936.2     .16       0
  4989.5     .07       0  4995.5     .16       0  5298.7      .1       0
  5315.3     .05       0
Bank Sta=4979.3,5014.9
XS Rating Curve= 0 ,0
Exp/Cntr=0.3,0.1

Type RM Length L Ch R = 1 ,8043    ,314,314,314
BEGIN DESCRIPTION:
UNT 0051 IN HEWA 13.0
END DESCRIPTION:
XS GIS Cut Line= 3
      2720859.65     10045399.65      2720656.52      10045123.6
       2720213.8     10044831.93
#Sta/Elev= 30
  4575.2 1721.82  4601.8 1719.57  4637.3 1717.73  4668.9 1714.89  4708.3 1706.68
    4753 1703.51  4807.2 1700.72    4817 1699.92  4885.6 1699.56  4939.3 1699.52
  4981.4 1700.33  4993.5 1698.08  4996.2 1697.58  4999.5 1698.08  5017.5 1700.31
  5064.3 1700.76  5083.3 1700.65  5110.9 1701.73  5219.3 1709.25  5255.4 1712.73
  5270.5 1715.11  5291.6  1716.2  5306.6 1719.51  5312.6 1719.12  5321.7 1720.91
  5327.7 1720.37  5342.8 1722.87  5348.8 1722.52  5377.1 1724.91  5448.1  1727.9
#Mann= 9 ,-1 , 0
  4575.2      .1       0  4668.9     .16       0    4753      .1       0
  4807.2     .16       0  4885.6      .1       0  4993.5     .07       0
  4999.5      .1       0  5064.3     .16       0  5377.1      .1       0
Bank Sta=4981.4,5017.5
XS Rating Curve= 0 ,0
Exp/Cntr=0.3,0.1

Type RM Length L Ch R = 1 ,7729    ,483,483,483
BEGIN DESCRIPTION:
UNT 0051 IN HEWA 12.0
END DESCRIPTION:
XS GIS Cut Line= 2
      2721239.82     10045399.61       2720578.4     10044581.94
#Sta/Elev= 30
  4271.6 1730.32  4283.7 1728.59  4312.4 1726.53  4347.6 1721.97  4419.5 1715.51
  4446.8 1712.03    4478 1710.04  4603.4 1702.37  4715.9 1697.39  4748.3 1695.73
  4800.3 1694.79    4803 1694.29  4806.3 1694.79  4817.6 1695.67    4888 1697.17
  4931.2 1696.52  4980.7  1697.1  4987.2 1695.71  4995.1  1695.1  5001.6 1696.27
  5015.9 1697.12  5023.9 1698.02  5044.7  1704.4  5051.1  1707.4  5059.1 1709.08
  5065.5 1711.36  5087.8 1714.67    5187 1719.36  5270.9 1721.97  5323.3 1722.25
#Mann= 9 ,-1 , 0
  4271.6      .1       0    4478     .16       0  4715.9      .1       0
  4748.3     .16       0  4800.3     .07       0  4806.3     .16       0
  4980.7     .07       0  5015.9     .16       0  5270.9      .1       0
#XS Ineff= 2 , 0
         4969.13  1697.5
Permanent Ineff=
       T       T
Bank Sta=4980.7,5015.9
XS Rating Curve= 0 ,0
Exp/Cntr=0.3,0.1

Type RM Length L Ch R = 1 ,7246    ,308,308,308
BEGIN DESCRIPTION:
Mapping XS 37d546a9
END DESCRIPTION:
XS GIS Cut Line= 4
      2721336.35     10045412.66      2721143.65     10044956.95
        2721240.      10044673.1      2720691.95     10044509.46
#Sta/Elev= 30
  4443.6 1736.74  4468.7 1734.55  4607.9  1720.4  4631.6 1716.97  4655.3 1710.63
  4713.9 1702.53  4842.2 1695.35  4861.1 1693.49  4895.7 1692.74  4968.5 1692.19
    4984 1690.63  4999.9 1689.47  5015.7 1690.61  5031.3 1693.07  5052.7 1691.92
  5068.5  1690.5  5289.7 1688.17  5292.5 1687.67  5295.7 1688.17  5407.4 1690.62
  5479.8 1692.49    5502 1691.31  5535.1 1693.69  5584.1 1693.34  5606.6    1695
  5630.8 1700.14  5678.1 1712.94  5698.9 1716.11  5744.3 1720.72  5810.1 1721.31
#Mann= 11 ,-1 , 0
  4443.6     .16       0  4468.7      .1       0  4842.2     .16       0
  4895.7      .1       0    4984     .07       0  5015.7      .1       0
  5052.7     .05       0  5289.7     .07       0  5295.7     .05       0
  5407.4     .16       0  5630.8      .1       0
#XS Ineff= 2 , 0
                            5030         1693.12
Permanent Ineff=
       T       T
Bank Sta=4984,5015.7
XS Rating Curve= 0 ,0
Exp/Cntr=0.3,0.1

Type RM Length L Ch R = 1 ,6938    ,122,122,122
BEGIN DESCRIPTION:
Mapping XS f955df6d
END DESCRIPTION:
XS GIS Cut Line= 5
      2721535.25      10045389.8      2721423.28     10045090.33
      2721449.32     10044686.69      2721095.16     10044449.71
      2720639.46     10044431.48
#Sta/Elev= 30
  4633.5 1743.39    4642 1741.99  4701.1  1738.3  4746.7 1734.94  4807.7 1709.81
    4813 1709.53    4838 1702.23  4843.3 1702.68  4893.2 1696.38    4953 1693.82
  4979.9 1690.18  4989.9 1688.26  4999.9 1687.71  5015.4 1689.99    5020 1690.84
    5060 1686.88  5280.2 1685.81  5382.8 1687.47  5554.5 1686.63  5770.7 1687.79
  5880.6 1690.81  5900.6 1689.13  5910.6 1690.89  5940.7 1692.14  5960.7 1694.69
  6030.7 1709.21  6057.1 1713.27  6080.8 1714.97  6110.8 1719.12  6239.9 1720.28
#Mann= 5 ,-1 , 0
  4633.5     .16       0  4701.1      .1       0  4979.9     .07       0
    5020     .16       0  6110.8      .1       0
#XS Ineff= 2 , 0
                         5017.82         1691.34
Permanent Ineff=
       T       T
Bank Sta=4979.9,5015.4
XS Rating Curve= 0 ,0
Exp/Cntr=0.3,0.1

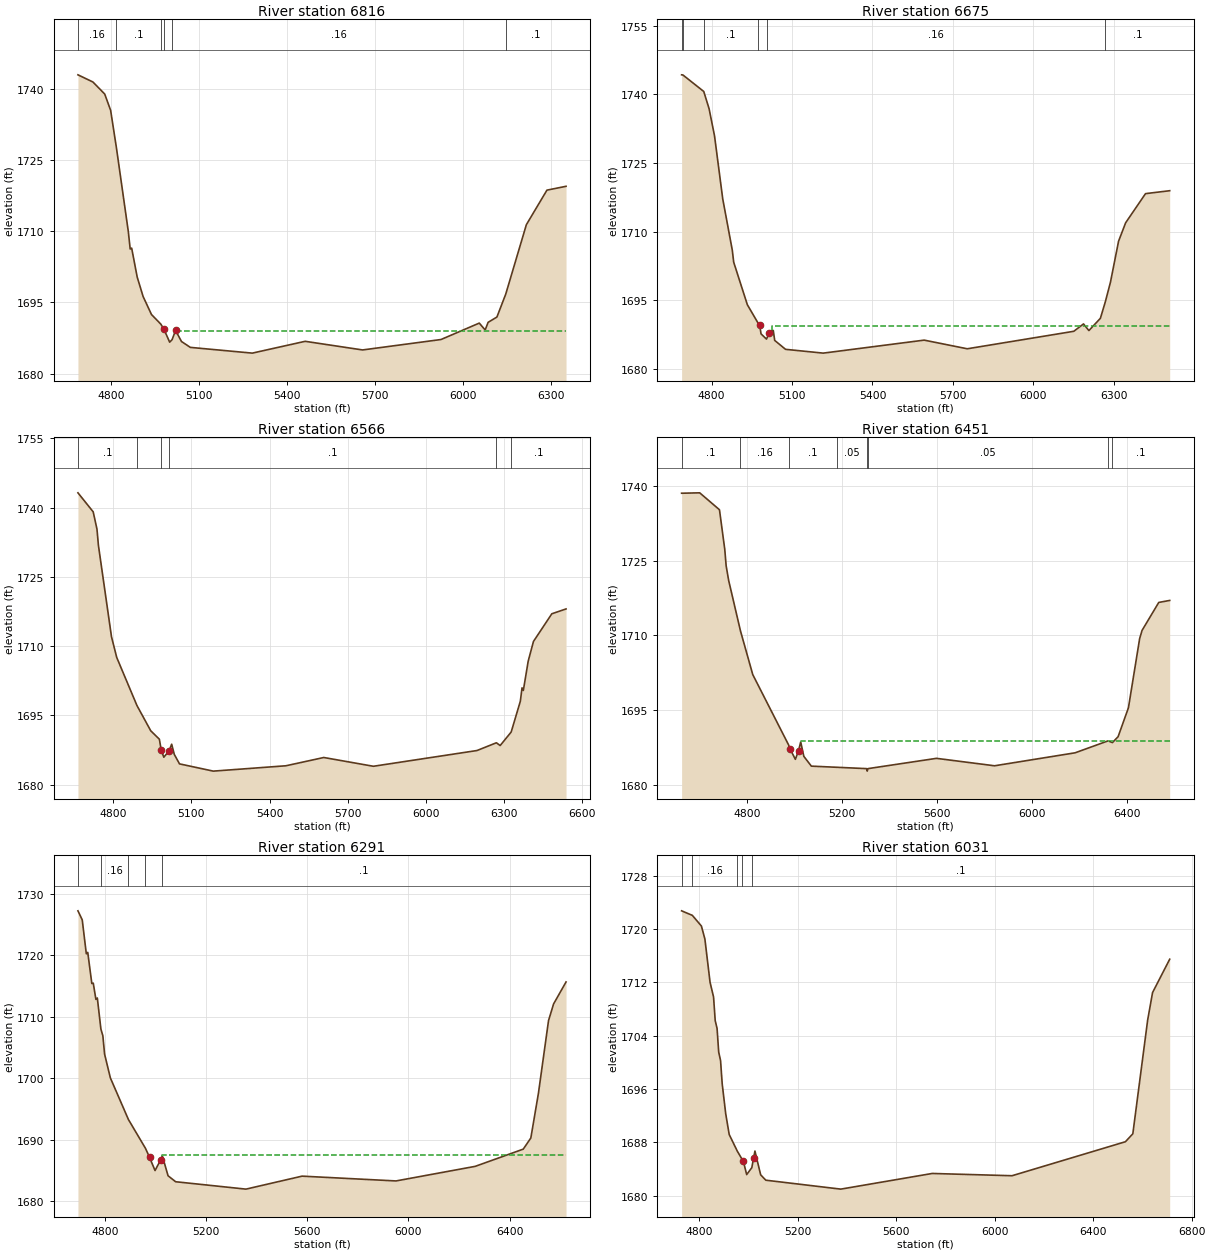
Type RM Length L Ch R = 1 ,6816    ,141,141,141
BEGIN DESCRIPTION:
Mapping XS f085123d
END DESCRIPTION:
XS GIS Cut Line= 5
      2721565.53     10045394.46      2721534.27     10045141.85
      2721581.15     10044785.08      2721372.82     10044467.37
      2720703.53     10044404.87
#Sta/Elev= 30
  4686.5 1742.99  4737.6 1741.48  4777.9 1738.94  4798.1 1735.51  4817.7 1727.69
  4858.5 1709.94  4864.9 1706.26  4869.9 1706.46  4888.8 1700.36  4908.9 1696.27
  4937.6 1692.46  4969.4 1690.44  4979.5 1689.43  4999.7 1686.63  5008.1 1687.17
  5019.8 1689.12    5040 1686.77  5070.3 1685.53  5281.8 1684.32  5462.3 1686.81
  5658.3 1684.99  5926.2 1687.19  6056.8 1690.65  6076.9  1689.2  6086.9 1690.81
    6117 1691.93  6147.2 1696.77  6217.5 1711.39  6287.8 1718.68    6353 1719.49
#Mann= 6 ,-1 , 0
  4686.5     .16       0  4817.7      .1       0  4969.4     .05       0
  4979.5     .07       0  5008.1     .16       0  6147.2      .1       0
#XS Ineff= 2 , 0
                         5020.96         1689.07
Permanent Ineff=
       T       T
Bank Sta=4979.5,5019.8
XS Rating Curve= 0 ,0
Exp/Cntr=0.3,0.1

Type RM Length L Ch R = 1 ,6675    ,109,109,109
BEGIN DESCRIPTION:
Mapping XS cf25cd52
END DESCRIPTION:
XS GIS Cut Line= 4
      2721616.27     10045424.16       2721718.7     10044913.78
      2721423.56      10044448.5      2720678.72     10044372.11
#Sta/Elev= 30
  4688.1 1744.28  4692.9 1744.25  4770.7 1740.64  4790.5 1736.89  4810.9 1730.93
  4841.5 1717.16  4877.2 1705.93  4882.3 1703.34  4933.3 1694.03  4973.9 1689.95
    4979 1689.67  4984.3 1687.66  5004.7 1686.51  5014.9  1687.9  5029.9 1688.41
  5035.3 1686.23  5075.7 1684.28  5216.3 1683.45  5592.7 1686.29  5753.5  1684.4
  6150.6 1688.22    6187 1689.83  6207.1 1688.38  6249.9 1691.06  6268.5  1694.7
  6287.5 1698.96  6317.7 1707.91  6344.1 1711.94  6418.2 1718.31  6508.4 1718.95
#Mann= 6 ,-1 , 0
  4688.1      .1       0  4692.9     .16       0  4770.7      .1       0
  4973.9     .07       0  5004.7     .16       0  6268.5      .1       0
#XS Ineff= 2 , 0
                         5025.91         1689.38
Permanent Ineff=
       T       T
Bank Sta=4979,5014.9
XS Rating Curve= 0 ,0
Exp/Cntr=0.3,0.1

Type RM Length L Ch R = 1 ,6566    ,115,115,115
BEGIN DESCRIPTION:
Mapping XS a3253ff9
END DESCRIPTION:
XS GIS Cut Line= 4
      2721757.36     10045451.98       2721798.6     10044963.68
      2721494.78     10044438.51      2720724.36     10044349.53
#Sta/Elev= 30
    4665 1743.19  4723.5 1739.07    4738 1735.33  4743.5 1731.83  4793.7 1712.03
  4813.8 1707.54  4891.5 1697.12  4944.2 1691.67  4977.3 1689.84  4984.4 1687.53
  4994.4 1685.94  5014.5 1687.32  5024.5 1688.76  5034.6 1686.55  5054.6  1684.5
  5184.3 1682.93    5463 1684.09    5608 1685.88  5798.3 1683.98  6195.8 1687.39
  6270.1 1689.07  6284.6 1688.47  6326.9  1691.4    6362 1698.06  6368.5 1700.96
  6373.5  1700.4  6392.2 1706.76  6412.4 1711.01  6482.8    1717  6537.3 1718.05
#Mann= 6 ,-1 , 0
    4665      .1       0  4891.5     .16       0  4984.4     .07       0
  5014.5      .1       0  6270.1     .16       0  6326.9      .1       0
#XS Ineff= 2 , 0
                         5024.42         1688.74
Permanent Ineff=
       T       T
Bank Sta=4984.4,5014.5
XS Rating Curve= 0 ,0
Exp/Cntr=0.3,0.1

Type RM Length L Ch R = 1 ,6451    ,160,160,160
BEGIN DESCRIPTION:
Mapping XS 7d10464b
END DESCRIPTION:
XS GIS Cut Line= 3
      2722115.94     10045521.02      2721559.79     10044430.28
      2720732.77      10044326.9
#Sta/Elev= 30
  4522.3 1738.48  4598.6 1738.56  4681.9 1735.17  4704.2 1727.26  4710.1 1723.92
  4720.8 1720.98  4770.3 1710.93  4822.3 1702.14  4973.6 1688.03  4979.5 1687.25
  5001.9 1685.16  5015.4 1686.91  5024.4 1688.65  5037.6 1685.76  5069.3  1683.8
  5176.5 1683.57    5302  1683.3  5304.8  1682.8    5308  1683.3  5596.8 1685.36
  5841.7 1683.87  6181.3 1686.47  6320.1 1688.86  6338.7 1688.52  6362.7 1689.71
  6406.1 1695.49  6453.4 1709.35  6463.5 1710.99    6534  1716.6  6580.1    1717
#Mann= 8 ,-1 , 0
  4522.3      .1       0  4770.3     .16       0  4973.6      .1       0
  5176.5     .05       0    5302     .07       0    5308     .05       0
  6320.1     .16       0  6338.7      .1       0
#XS Ineff= 2 , 0
                         5024.39         1688.83
Permanent Ineff=
       T       T
Bank Sta=4979.5,5015.4
XS Rating Curve= 0 ,0
Exp/Cntr=0.3,0.1

Type RM Length L Ch R = 1 ,6291    ,260,260,260
BEGIN DESCRIPTION:
Mapping XS 5c6a58cc
END DESCRIPTION:
XS GIS Cut Line= 4
      2722190.37     10045296.04      2721719.01     10044439.25
      2721414.32     10044319.46      2720789.31     10044316.85
#Sta/Elev= 30
  4692.8 1727.19  4709.8 1725.72  4725.9 1720.21  4731.6 1720.43  4747.7 1715.37
  4753.4 1715.44  4763.8  1712.8  4769.5 1713.02  4783.6 1707.97  4791.3 1706.89
  4798.2  1703.9    4821 1700.04  4892.6 1693.26  4959.9 1688.59  4975.9 1687.13
  4997.7 1684.98  5019.5 1686.68  5026.4 1687.38  5049.2 1684.13  5079.2 1683.16
  5357.2 1681.96  5579.2 1684.07  5950.7 1683.29  6263.9 1685.66  6453.9 1688.46
  6483.9 1690.27  6513.9 1697.53  6553.9 1709.36  6573.9 1712.06  6623.1 1715.63
#Mann= 5 ,-1 , 0
  4692.8      .1       0  4783.6     .16       0  4892.6      .1       0
  4959.9     .07       0  5026.4      .1       0
#XS Ineff= 2 , 0
                         5026.89         1687.45
Permanent Ineff=
       T       T
Bank Sta=4975.9,5019.5
XS Rating Curve= 0 ,0
Exp/Cntr=0.3,0.1

Type RM Length L Ch R = 1 ,6031    ,230,230,230
BEGIN DESCRIPTION:
Mapping XS 6a54ac52
END DESCRIPTION:
XS GIS Cut Line= 4
      2722440.36     10045085.08      2721867.61     10044449.14
       2721422.3     10044264.24      2720779.03     10044308.52
#Sta/Elev= 30
    4728 1722.74  4771.6 1722.06  4808.4 1720.46  4822.6 1718.51  4843.6 1712.01
  4857.8 1709.81  4864.5 1706.26    4872 1705.11  4878.7 1701.54  4886.2 1700.29
  4892.9 1696.78  4907.1 1692.32  4921.3 1689.19  4954.5 1686.67  4971.4 1685.61
  4978.1 1685.28  4992.3 1683.17  5013.2 1684.21  5020.7 1685.72 5025.91  1686.7
  5049.1 1683.14    5070 1682.33  5374.7 1680.99  5746.1 1683.34  6070.4    1683
  6530.9  1688.1    6561 1689.29  6621.2 1706.34  6641.2 1710.48  6710.8 1715.48
#Mann= 5 ,-1 , 0
    4728      .1       0  4771.6     .16       0  4954.5      .1       0
  4971.4     .07       0  5013.2      .1       0
#XS Ineff= 2 , 0
                         5025.58          1686.5
Permanent Ineff=
       T       T
Bank Sta=4978.1,5020.7
XS Rating Curve= 0 ,0
Exp/Cntr=0.3,0.1

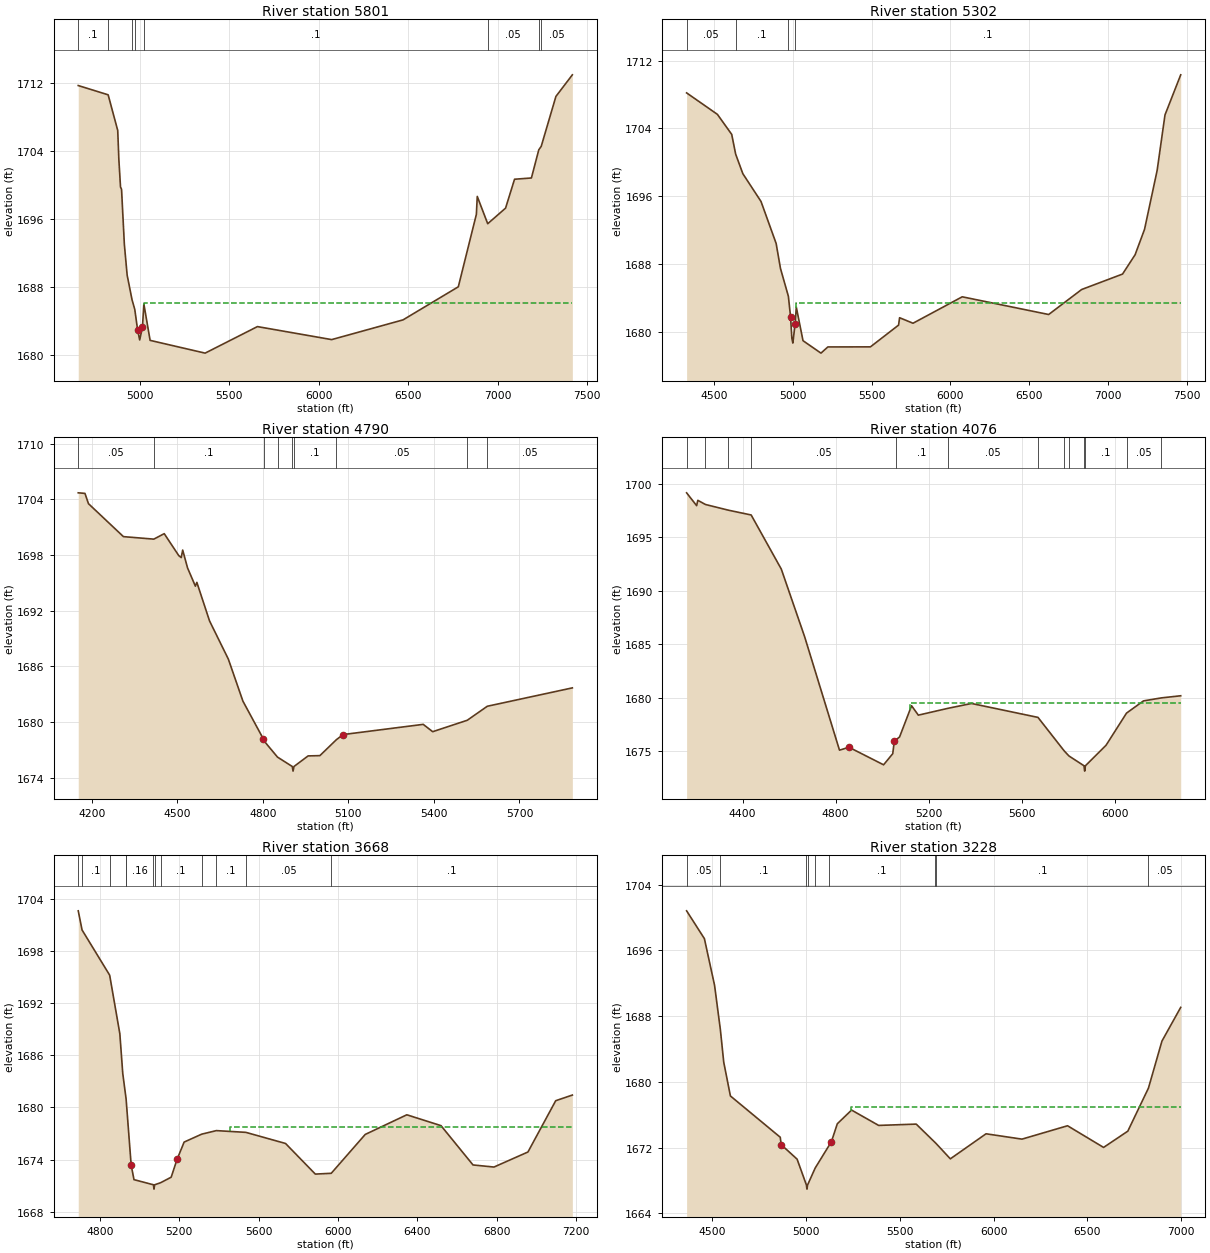
Type RM Length L Ch R = 1 ,5801    ,499,499,499
BEGIN DESCRIPTION:
UNT 0051 IN HEWA 11.0
END DESCRIPTION:
XS GIS Cut Line= 3
       2722663.4     10044861.37      2721266.63     10044029.34
      2720137.09     10044141.43
#Sta/Elev= 30
  4656.8 1711.66  4823.9 1710.57  4877.4 1706.38  4883.7 1702.98    4893 1699.73
  4898.8 1699.45  4914.4    1693    4930 1689.37  4957.5 1686.46  4972.8 1685.32
  4988.4 1682.94  5000.1 1681.74  5015.6 1683.24  5023.4 1685.97  5058.4 1681.69
  5365.8 1680.19  5658.1 1683.31  6072.8 1681.78  6471.7  1684.1  6780.5 1687.99
  6881.4 1696.51  6886.4 1698.62  6944.8 1695.41  7044.5 1697.24  7094.7 1700.64
    7189 1700.79  7230.3 1704.11  7243.6  1704.5  7325.9 1710.38  7417.7 1712.92
#Mann= 8 ,-1 , 0
  4656.8      .1       0  4823.9     .16       0  4957.5      .1       0
  4972.8     .07       0  5023.4      .1       0  6944.8     .05       0
  7230.3      .1       0  7243.6     .05       0
#XS Ineff= 2 , 0
                         5022.95         1686.04
Permanent Ineff=
       T       T
Bank Sta=4988.4,5015.6
XS Rating Curve= 0 ,0
Exp/Cntr=0.3,0.1

Type RM Length L Ch R = 1 ,5302    ,512,512,512
BEGIN DESCRIPTION:
UNT 0051 IN HEWA 10.0
END DESCRIPTION:
XS GIS Cut Line= 4
      2722756.08     10044807.99      2722696.92     10044339.25
      2721901.99     10043735.11     2720225.797    10043770.823
#Sta/Elev= 30
  4324.4  1708.2  4520.2 1705.66  4610.9  1703.3  4635.9 1700.97  4681.5 1698.66
  4796.9 1695.38    4893 1690.42  4920.5 1687.47  4970.8 1684.18  4984.6 1681.76
  4992.8 1679.22  4999.1 1678.66  5013.6 1680.92    5021 1682.91  5063.6 1678.94
  5177.7 1677.47  5221.5  1678.2  5491.9 1678.21  5670.7 1680.78    5677 1681.65
  5762.3    16816074.808 1684.126623.8411682.0316833.4731684.9847093.0161686.807
7172.8751689.091 7232.771692.0967312.629 1699.047362.5411705.5957462.3651710.332
#Mann= 4 ,-1 , 0
  4324.4     .05       0  4635.9      .1       0  4970.8     .07       0
  5013.6      .1       0
#XS Ineff= 2 , 0
                         5020.73          1683.4
Permanent Ineff=
       T       T
Bank Sta=4984.6,5013.6
XS Rating Curve= 0 ,0
Exp/Cntr=0.3,0.1

Type RM Length L Ch R = 1 ,4790    ,714,714,714
BEGIN DESCRIPTION:
UNT 0051 IN HEWA 9.0
END DESCRIPTION:
XS GIS Cut Line= 4
      2722837.97     10044748.82      2722969.94     10044125.38
      2722888.03      10043847.8      2722114.47     10043620.28
#Sta/Elev= 30
  4152.5 1704.69    4176 1704.63  4188.4 1703.52    4311 1699.97  4417.6  1699.7
  4454.1 1700.29  4505.2 1697.92  4513.7 1697.71  4518.8 1698.52  4535.9  1696.6
  4563.4 1694.63  4568.5 1695.04  4613.1 1690.88    4679 1686.77  4730.1 1682.24
  4801.9 1678.16  4805.1 1677.92  4851.4 1676.21  4903.2  1675.2  4905.9  1674.7
  4909.2  1675.2  4958.7 1676.34    5000 1676.37    5058 1678.09  5081.5 1678.64
  5362.4 1679.74  5395.7 1678.95  5516.8 1680.18  5587.2 1681.69  5885.5 1683.67
#Mann= 9 ,-1 , 0
  4152.5     .05       0  4417.6      .1       0  4805.1     .16       0
  4851.4      .1       0  4903.2     .07       0  4909.2      .1       0
    5058     .05       0  5516.8      .1       0  5587.2     .05       0
Bank Sta=4801.9,5081.5
XS Rating Curve= 0 ,0
Exp/Cntr=0.3,0.1

Type RM Length L Ch R = 1 ,4076    ,408,408,408
BEGIN DESCRIPTION:
UNT 0051 IN HEWA 8.0
END DESCRIPTION:
XS GIS Cut Line= 3
      2723461.39      10044930.8      2723493.24     10044252.79
      2724098.24     10042938.18
#Sta/Elev= 30
  4158.9 1699.16  4202.1 1697.96  4207.1 1698.46  4240.1 1698.07  4338.4 1697.54
  4436.7 1697.09  4566.4 1692.03  4666.5 1685.73  4816.7 1675.12  4857.6 1675.39
  5006.4 1673.75  5045.8 1674.79  5052.4 1675.94  5057.9 1676.04  5075.3 1676.36
  5126.8 1679.27  5155.9 1678.39    5284 1679.03  5384.9 1679.48  5670.7 1678.18
  5782.8 1675.07  5803.7 1674.58  5868.8 1673.66  5871.6 1673.16  5874.8 1673.66
  5963.7 1675.58  6051.7 1678.58  6124.5 1679.72    6201    1680  6284.8  1680.2
#Mann= 13 ,-1 , 0
  4158.9      .1       0  4240.1     .05       0  4338.4      .1       0
  4436.7     .05       0  5057.9      .1       0    5284     .05       0
  5670.7      .1       0  5782.8     .05       0  5803.7      .1       0
  5868.8     .07       0  5874.8      .1       0  6051.7     .05       0
    6201      .1       0
#XS Ineff= 2 , 0
                         5119.17         1679.53
Permanent Ineff=
       T       T
Bank Sta=4857.6,5052.4
XS Rating Curve= 0 ,0
Exp/Cntr=0.3,0.1

Type RM Length L Ch R = 1 ,3668    ,440,440,440
BEGIN DESCRIPTION:
UNT 0051 IN HEWA 7.0
END DESCRIPTION:
XS GIS Cut Line= 3
       2723713.8     10044571.53      2724026.31     10044128.81
      2724911.72     10042394.45
#Sta/Elev= 30
  4691.3 1702.62  4710.5 1700.42  4849.6 1695.22  4900.8 1688.49  4915.6 1683.91
  4929.7 1681.45  4932.2 1681.03  4957.9 1673.38  4972.2  1671.7  5070.2 1671.11
  5072.9 1670.61  5076.2 1671.11  5106.6 1671.35  5159.4 1671.98    5189 1674.02
  5224.7 1676.02  5312.9 1676.93    5387 1677.34  5535.6 1677.14  5735.7 1675.86
  5885.6 1672.34  5965.9 1672.43  6137.1  1676.9  6346.7 1679.16  6518.9 1677.91
  6680.1 1673.39  6785.6 1673.15  6956.8 1674.88  7096.7 1680.78  7180.5 1681.43
#Mann= 12 ,-1 , 0
  4691.3     .05       0  4710.5      .1       0  4849.6     .16       0
  4929.7      .1       0  4932.2     .16       0  5070.2     .07       0
  5076.2     .16       0  5106.6      .1       0  5312.9     .05       0
    5387      .1       0  5535.6     .05       0  5965.9      .1       0
#XS Ineff= 2 , 0
                         5457.51         1677.74
Permanent Ineff=
       T       T
Bank Sta=4957.9,5189
XS Rating Curve= 0 ,0
Exp/Cntr=0.3,0.1

Type RM Length L Ch R = 1 ,3228    ,459,459,459
BEGIN DESCRIPTION:
UNT 0051 IN HEWA 6.0
END DESCRIPTION:
XS GIS Cut Line= 3
      2723771.08     10044701.74      2724276.31     10044503.81
      2725093.31     10042578.39
#Sta/Elev= 30
  4363.8 1700.83  4458.7 1697.44  4512.9 1691.75  4543.8 1686.36  4561.8 1682.39
  4597.3 1678.28    4863 1673.25  4868.3 1672.34  4952.9 1670.58  5002.6 1667.43
  5005.4 1666.93  5008.6 1667.43  5049.3  1669.5  5122.3 1672.21  5134.8 1672.64
  5167.2 1674.89  5243.3 1676.56  5387.7 1674.69  5587.9 1674.85  5687.6 1672.63
  5695.5 1672.45  5769.8 1670.62  5960.2 1673.67  6151.9 1673.02  6394.7 1674.65
  6586.8 1672.01    6716 1673.99  6826.1 1679.24  6897.9 1684.96    6998 1689.07
#Mann= 9 ,-1 , 0
  4363.8     .05       0  4543.8      .1       0  5002.6     .07       0
  5008.6      .1       0  5049.3     .16       0  5122.3      .1       0
  5687.6     .05       0  5695.5      .1       0  6826.1     .05       0
#XS Ineff= 2 , 0
                         5240.41         1676.96
Permanent Ineff=
       T       T
Bank Sta=4868.3,5134.8
XS Rating Curve= 0 ,0
Exp/Cntr=0.3,0.1

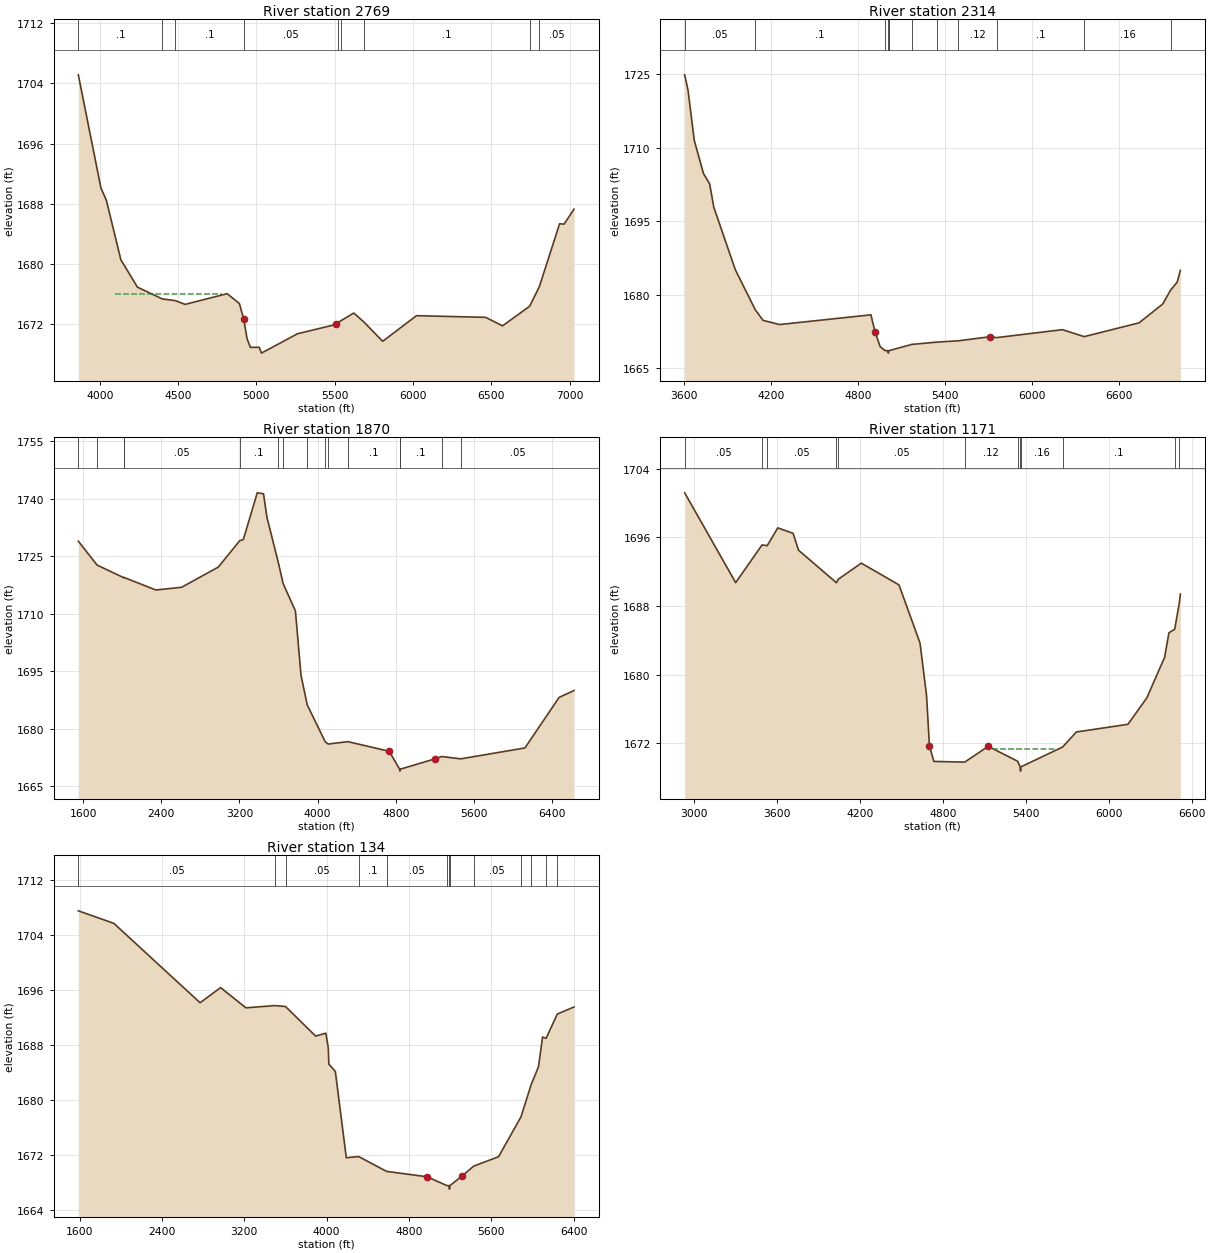
Type RM Length L Ch R = 1 ,2769    ,455,455,455
BEGIN DESCRIPTION:
UNT 0051 IN HEWA 5.0
END DESCRIPTION:
XS GIS Cut Line= 3
      2723864.85     10045514.23      2724745.06     10044602.77
      2725177.35     10042753.83
#Sta/Elev= 30
  3862.5 1705.12  4006.8 1690.11  4042.3 1688.42  4134.2 1680.57  4240.1 1676.94
  4399.1 1675.37  4482.2 1675.15  4544.4 1674.65    4813 1676.07    4891 1674.77
  4919.3 1672.66  4940.4 1670.06  4961.5 1668.95  5018.1 1668.95    5032 1668.18
  5262.1 1670.75  5508.6 1671.99    5519 1672.21  5537.3 1672.45  5621.6  1673.5
  5685.9 1672.32  5806.4 1669.75  6022.1 1673.15  6463.7 1672.93  6571.8  1671.8
  6744.8  1674.4  6806.6 1676.99  6936.1 1685.35  6964.6  1685.3  7028.4 1687.29
#Mann= 9 ,-1 , 0
  3862.5      .1       0  4399.1     .05       0  4482.2      .1       0
  4919.3     .05       0    5519      .1       0  5537.3     .05       0
  5685.9      .1       0  6744.8     .16       0  6806.6     .05       0
#XS Ineff= 2 ,-1
 4096.89 4776.68 1676.07 5622.28 6045.08 1672.71
Permanent Ineff=
       T       T
Bank Sta=4919.3,5508.6
XS Rating Curve= 0 ,0
Exp/Cntr=0.3,0.1

Type RM Length L Ch R = 1 ,2314    ,444,444,444
BEGIN DESCRIPTION:
UNT 0051 IN HEWA 4.0
END DESCRIPTION:
XS GIS Cut Line= 3
      2724088.81     10045967.35      2725114.85     10044842.35
      2725219.02     10042951.74
#Sta/Elev= 30
  3607.6  1724.8  3631.1 1721.61  3673.6 1711.47  3737.2  1704.7  3779.7  1702.6
  3808.1 1697.87  3956.7  1685.1  4094.6 1676.94  4147.9  1674.8  4261.4 1673.95
  4891.1 1675.93  4919.5 1672.48  4954.6 1669.46  4987.9 1668.65  5008.4 1668.63
  5011.1 1668.13  5014.4 1668.63  5017.4 1668.65  5172.6  1669.9    5348 1670.38
  5491.4 1670.63  5709.7 1671.46  5758.8 1671.29  6210.5 1672.91  6360.9 1671.49
  6738.6 1674.29  6901.5 1678.12    6956 1680.95  7001.7 1682.58  7023.7 1684.99
#Mann= 12 ,-1 , 0
  3607.6     .05       0  4094.6      .1       0  4987.9     .16       0
  5008.4     .07       0  5014.4     .16       0  5017.4      .1       0
  5172.6     .16       0    5348      .1       0  5491.4     .12       0
  5758.8      .1       0  6360.9     .16       0    6956     .05       0
#XS Ineff= 2 , 0
         4838.86  1675.7
Permanent Ineff=
       T       T
Bank Sta=4919.5,5709.7
XS Rating Curve= 0 ,0
Exp/Cntr=0.3,0.1

Type RM Length L Ch R = 1 ,1870    ,699,699,699
BEGIN DESCRIPTION:
UNT 0051 IN HEWA 3.0
END DESCRIPTION:
XS GIS Cut Line= 3
       2723729.1     10047860.06      2725434.83     10045724.64
      2725382.75     10043380.86
#Sta/Elev= 30
  1549.2 1728.88  1741.1 1722.66  2014.3 1719.36    2016 1719.44  2342.9 1716.16
  2606.8 1716.86  2983.3 1722.13  3202.3    1729  3239.4  1729.3  3381.9 1741.48
    3446 1741.24  3481.2 1735.09  3594.5 1723.63  3647.3  1717.8  3772.6 1710.73
  3830.2 1693.92    3894 1686.21  4077.2 1676.64  4107.8 1676.01    4310 1676.63
  4733.3 1674.13  4840.3 1669.45    4843 1668.95  4846.3 1669.45  5203.4 1672.16
  5269.2 1672.75  5466.5 1672.15  6123.6 1674.99  6473.7 1688.16  6626.6 1689.96
#Mann= 15 ,-1 , 0
  1549.2      .1       0  1741.1     .05       0  2014.3      .1       0
    2016     .05       0  3202.3      .1       0  3594.5     .05       0
  3647.3      .1       0    3894     .05       0  4077.2      .1       0
  4107.8     .05       0    4310      .1       0  4840.3     .07       0
  4846.3      .1       0  5269.2     .16       0  5466.5     .05       0
Bank Sta=4733.3,5203.4
XS Rating Curve= 0 ,0
Exp/Cntr=0.3,0.1

Type RM Length L Ch R = 1 ,1171    ,1037,1037,1037
BEGIN DESCRIPTION:
UNT 0051 IN HEWA 2.0
END DESCRIPTION:
XS GIS Cut Line= 3
      2725547.14     10046821.52      2726255.48     10045441.31
      2725563.13     10043525.64
#Sta/Elev= 30
  2930.3 1701.19  3299.5 1690.73  3490.4 1695.12    3528 1695.04  3604.5 1697.11
  3715.5 1696.47  3754.2 1694.51    4029 1690.72  4042.8 1691.13    4209    1693
  4481.7 1690.47    4634 1683.69  4681.1  1677.6  4702.4 1671.66  4734.3 1669.91
  4957.7 1669.83  5127.7 1671.67  5340.7 1669.93  5358.6 1669.28  5361.4 1668.78
  5364.6 1669.28  5666.5 1671.59  5765.7 1673.34  6139.1 1674.23  6276.1 1677.32
  6404.5 1682.04  6435.6 1684.89  6477.5  1685.3  6511.7 1688.46  6518.6 1689.39
#Mann= 12 ,-1 , 0
  2930.3     .05       0  3490.4      .1       0    3528     .05       0
    4029      .1       0  4042.8     .05       0  4957.7     .12       0
  5340.7     .16       0  5358.6     .07       0  5364.6     .16       0
  5666.5      .1       0  6477.5     .05       0  6511.7      .1       0
#XS Ineff= 1 ,-1
 5153.37 5619.69 1671.36
Permanent Ineff=
       T
Bank Sta=4702.4,5127.7
XS Rating Curve= 0 ,0
Exp/Cntr=0.3,0.1

Type RM Length L Ch R = 1 ,134     ,0,0,0
BEGIN DESCRIPTION:
UNT 0051 IN HEWA 1.0
END DESCRIPTION:
XS GIS Cut Line= 5
      2725813.82     10047615.13      2726022.16     10046108.15
      2726702.72     10044538.71      2726709.66     10044163.71
      2726237.45     10043052.62
#Sta/Elev= 30
    1588 1707.49  1932.6 1705.67  2770.5 1694.11  2970.1 1696.31  3215.4 1693.37
  3494.9 1693.69  3600.2 1693.56  3892.6 1689.25    3992 1689.68  4015.4 1687.55
  4020.9 1685.18  4084.2  1684.1  4190.6 1671.54  4310.3 1671.71  4582.3 1669.55
    4975 1668.77  5164.9  1667.5  5189.5 1667.47  5192.3 1666.97  5195.5 1667.47
  5316.5  1668.9  5426.7 1670.31  5669.4 1671.69    5887 1677.49  5987.1 1682.24
  6056.7 1684.77  6096.8 1689.12  6130.8 1688.92  6239.7 1692.46  6402.3 1693.49
#Mann= 13 ,-1 , 0
    1588     .05       0  3494.9      .1       0  3600.2     .05       0
  4310.3      .1       0  4582.3     .05       0  5164.9      .1       0
  5189.5     .04       0  5195.5      .1       0  5426.7     .05       0
    5887      .1       0  5987.1     .05       0  6130.8      .1       0
  6239.7     .05       0
Bank Sta=4975,5316.5
XS Rating Curve= 0 ,0
Exp/Cntr=0.3,0.1

Chan Stop Cuts=-1
Use User Specified Reach Order=0
Composite Channel Slope=5