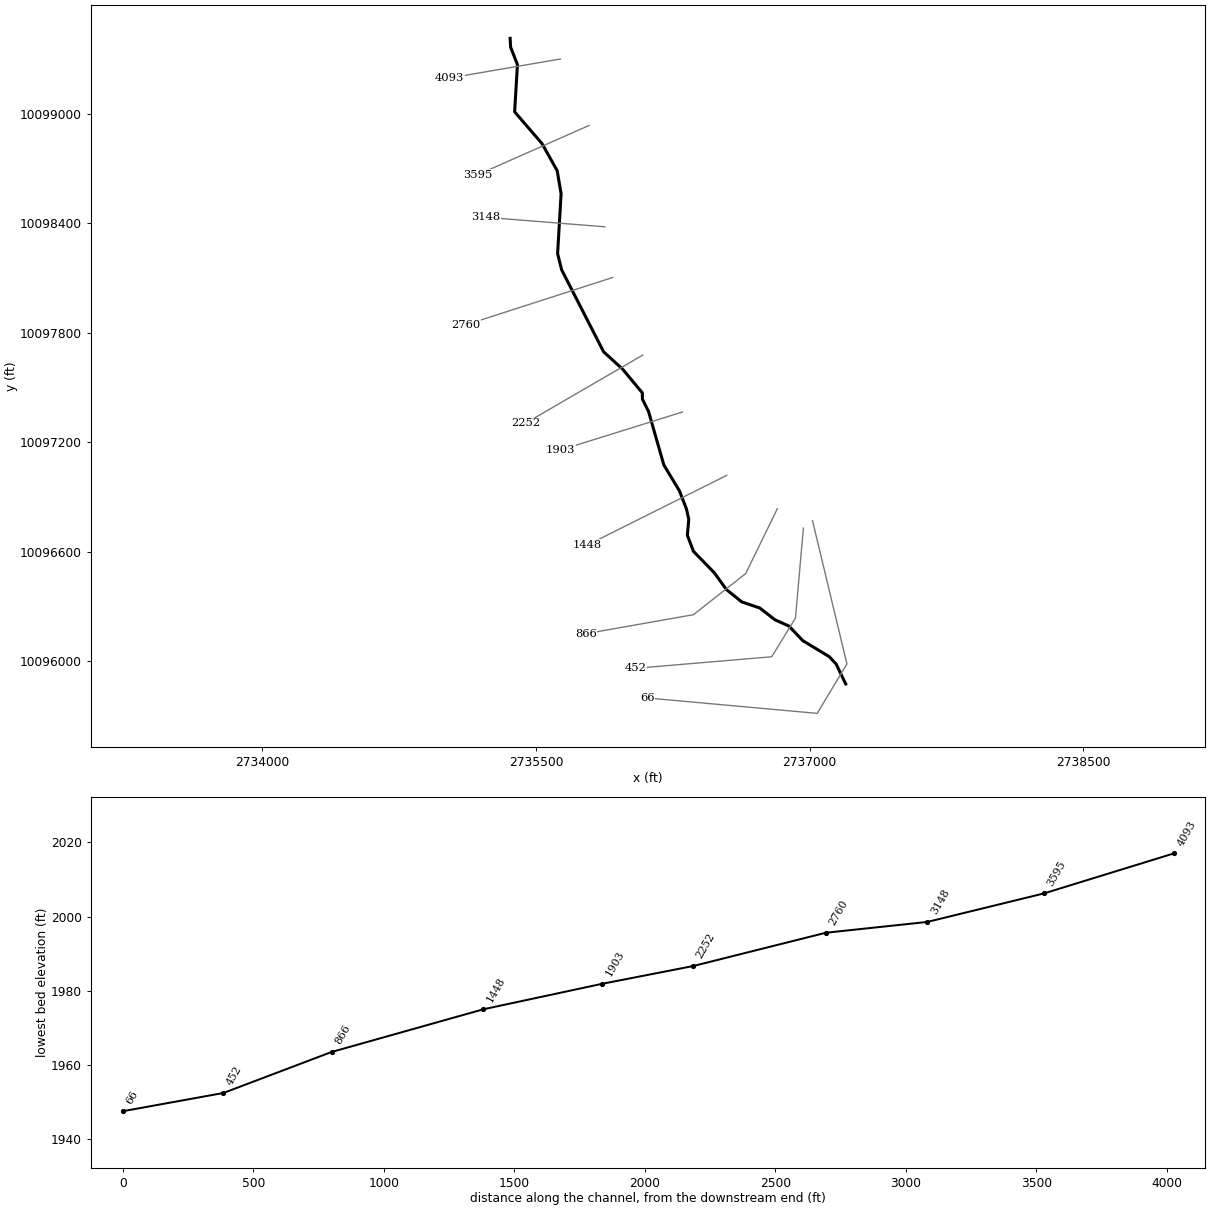
--- UNT 0053 IN HEWA.prj (project) ---

Proj Title=UNT 0053 IN HEWA Base Level Engineering
Current Plan=p01
Default Exp/Contr=0.3,0.1
English Units
Geom File=g01
Flow File=f01
Plan File=p01
Y Axis Title=Elevation
X Axis Title(PF)=Main Channel Distance
X Axis Title(XS)=Station
BEGIN DESCRIPTION:
UNT 0053 IN HEWA
END DESCRIPTION:
DSS Export Rating Curves= 0
DSS Export Rating Curve Sorted= 0
DSS Export Volume Flow Curves= 0
DXF OffsetX= 0
DXF OffsetY= 0
DXF ScaleX= 1
DXF ScaleY= 10

--- UNT 0053 IN HEWA.p01 (plan) ---

Plan Title=Multiple Run
Short Identifier=Multiple
Geom File=g01
Flow File=f01
Subcritical Flow
K Sum by GR= 0
Std Step Tol= 0.01
Critical Tol= 0.01
Num of Std Step Trials= 20
Max Error Tol= 0.3
Flow Tol Ratio= 0.001
Split Flow NTrial= 30
Split Flow Tol= 0.02
Split Flow Ratio= 0.02
Log Output Level= 0
Friction Slope Method= 1
Unsteady Friction Slope Method= 2
Unsteady Bridges Friction Slope Method= 1
Parabolic Critical Depth
Global Vel Dist=  1 , 1 , 1
Global Log Level= 0
CheckData=True
Encroach Param= -1, 0, 0, 0
BEGIN DESCRIPTION:
Multiple Run
END DESCRIPTION:

--- UNT 0053 IN HEWA.f01 (steady flow) ---

Flow Title=Multiple
Number of Profiles=7
Profile Names=10-year,25-year,50-year,1pct_min,100-year,1pct_plu,500-year
River Rch & RM= UNT 0053 IN HEWA,Reach-1,4093
     815    1178    1491    1383    1870    2529    2951
Boundary for River Rch & Prof#=UNT 0053 IN HEWA,Reach-1,1
Up Type=0
Dn Type=3
Dn Slope=0.005
Boundary for River Rch & Prof#=UNT 0053 IN HEWA,Reach-1,2
Up Type=0
Dn Type=3
Dn Slope=0.005
Boundary for River Rch & Prof#=UNT 0053 IN HEWA,Reach-1,3
Up Type=0
Dn Type=3
Dn Slope=0.005
Boundary for River Rch & Prof#=UNT 0053 IN HEWA,Reach-1,4
Up Type=0
Dn Type=3
Dn Slope=0.005
Boundary for River Rch & Prof#=UNT 0053 IN HEWA,Reach-1,5
Up Type=0
Dn Type=3
Dn Slope=0.005
Boundary for River Rch & Prof#=UNT 0053 IN HEWA,Reach-1,6
Up Type=0
Dn Type=3
Dn Slope=0.005
Boundary for River Rch & Prof#=UNT 0053 IN HEWA,Reach-1,7
Up Type=0
Dn Type=3
Dn Slope=0.005

--- UNT 0053 IN HEWA.g01 (geometry) ---

Geom Title=Existing Conditions
Program Version=4.10

River Reach=UNT 0053 IN HEWA,Reach-1
Reach XY= 30
      2735358.47     10099413.73      2735361.22     10099364.87
      2735398.57     10099269.78      2735383.16     10099010.83
      2735533.25     10098836.57      2735616.53     10098687.86
      2735637.91      10098561.5      2735618.76     10098233.37
      2735640.83     10098144.71      2735871.06     10097694.89
      2735975.04     10097600.27       2736083.3      10097469.9
      2736083.89     10097434.96      2736117.25     10097368.28
      2736201.16     10097074.85      2736286.56     10096932.94
      2736325.47     10096832.45      2736338.04     10096775.38
      2736330.12     10096689.52      2736363.66     10096601.15
      2736477.88     10096483.56      2736543.78     10096392.04
      2736628.47     10096323.73       2736727.1     10096290.44
      2736809.54     10096226.32      2736887.47     10096191.19
      2736962.41     10096111.85      2737108.42     10096023.25
       2737146.1     10095982.83      2737198.47     10095873.73

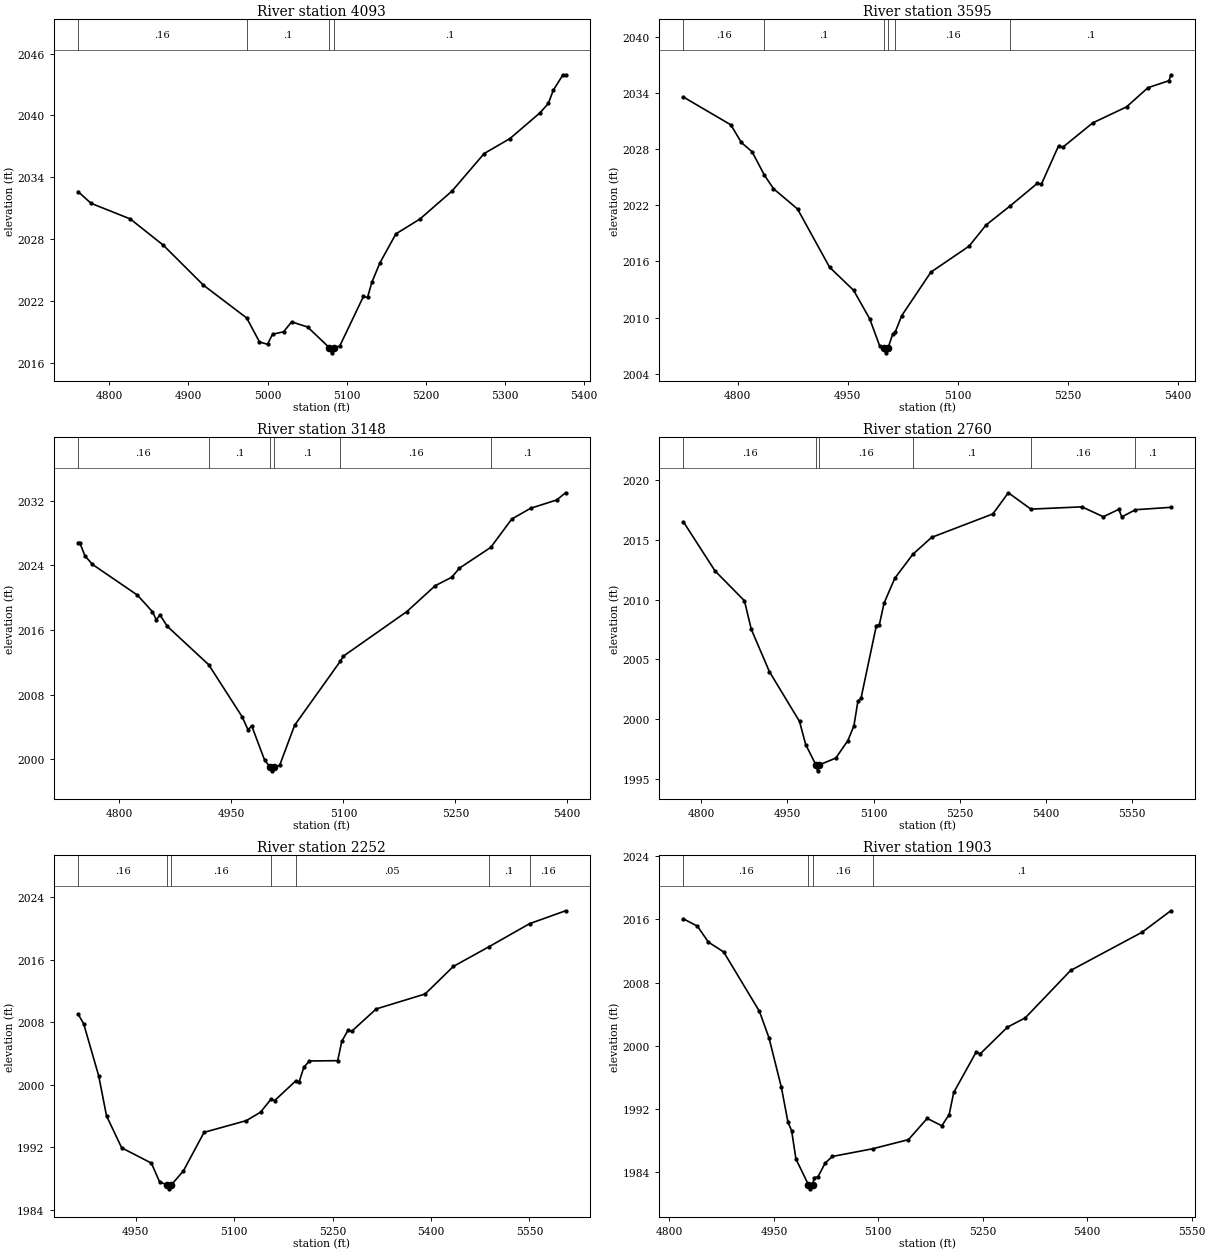
Type RM Length L Ch R = 1 ,4093    ,498,498,498
BEGIN DESCRIPTION:
UNT 0053 IN HEWA 9.0
END DESCRIPTION:
XS GIS Cut Line= 2
      2735634.58     10099300.51      2735026.95     10099196.34
#Sta/Elev= 30
  4760.4 2032.62  4776.8 2031.49  4826.3 2029.98  4868.1 2027.44  4918.8 2023.57
  4973.7 2020.38  4989.8 2018.06    5000 2017.84  5006.3 2018.81  5020.3 2019.05
  5030.4 2020.01  5050.7 2019.51  5078.1 2017.51  5080.9 2017.01  5084.1 2017.51
  5091.3 2017.67  5121.3 2022.48  5126.4 2022.37  5131.9 2023.84    5142 2025.71
  5162.3 2028.53  5192.7 2029.97  5233.3 2032.68  5273.9 2036.31  5306.5 2037.76
  5344.9 2040.28  5355.1 2041.17  5361.4 2042.45  5373.6 2043.94  5376.9 2043.94
#Mann= 4 ,-1 , 0
  4760.4     .16       0  4973.7      .1       0  5078.1     .07       0
  5084.1      .1       0
Bank Sta=5078.1,5084.1
XS Rating Curve= 0 ,0
Exp/Cntr=0.3,0.1

Type RM Length L Ch R = 1 ,3595    ,447,447,447
BEGIN DESCRIPTION:
UNT 0053 IN HEWA 8.0
END DESCRIPTION:
XS GIS Cut Line= 2
       2735790.8     10098935.92      2735183.31     10098666.89
#Sta/Elev= 30
    4726 2033.55  4790.9 2030.57  4805.1 2028.69  4819.7 2027.71  4836.5 2025.21
  4848.9 2023.76  4881.7 2021.59  4925.4 2015.37  4958.2  2012.9  4980.1 2009.86
  4993.6 2006.98    4999 2006.73  5001.7 2006.23    5005 2006.73  5011.4 2008.24
  5014.9 2008.46  5023.8 2010.21  5063.5 2014.85  5115.5 2017.62  5138.8 2019.89
  5171.4 2021.91  5208.6 2024.33  5214.1 2024.24  5237.4 2028.32  5242.9 2028.16
    5284 2030.78  5330.1 2032.49  5359.3 2034.54    5388 2035.29  5390.4 2035.92
#Mann= 6 ,-1 , 0
    4726     .16       0  4836.5      .1       0    4999     .07       0
    5005      .1       0  5014.9     .16       0  5171.4      .1       0
Bank Sta=4999,5005
XS Rating Curve= 0 ,0
Exp/Cntr=0.3,0.1

Type RM Length L Ch R = 1 ,3148    ,388,388,388
BEGIN DESCRIPTION:
UNT 0053 IN HEWA 7.0
END DESCRIPTION:
XS GIS Cut Line= 2
      2735877.61     10098380.36      2735226.59     10098432.44
#Sta/Elev= 30
  4744.6 2026.83  4746.7 2026.83  4753.8 2025.18  4763.8 2024.12    4824 2020.32
  4844.1 2018.27  4849.3 2017.26  4854.3 2017.86  4864.1 2016.45  4919.6 2011.69
  4964.4 2005.24  4972.2 2003.64  4977.2 2004.12  4994.5 1999.87  5001.6 1999.05
  5004.3 1998.55  5007.6 1999.05  5014.6 1999.22  5034.7  2004.2    5096 2012.14
  5100.1 2012.76  5185.1 2018.28    5223 2021.48  5245.3 2022.53  5255.4 2023.65
  5297.5 2026.23  5325.6 2029.74  5350.9 2031.07  5385.8  2032.1  5397.7 2032.99
#Mann= 6 ,-1 , 0
  4744.6     .16       0  4919.6      .1       0  5001.6     .07       0
  5007.6      .1       0    5096     .16       0  5297.5      .1       0
Bank Sta=5001.6,5007.6
XS Rating Curve= 0 ,0
Exp/Cntr=0.3,0.1

Type RM Length L Ch R = 1 ,2760    ,508,508,508
BEGIN DESCRIPTION:
UNT 0053 IN HEWA 6.0
END DESCRIPTION:
XS GIS Cut Line= 2
      2735921.01     10098102.59      2735113.67     10097842.16
#Sta/Elev= 30
    4769 2016.54  4824.2 2012.41  4875.4 2009.91  4887.3 2007.52  4918.8 2003.97
  4971.3 1999.79    4982 1997.85  4999.8 1996.15  5002.6 1995.65  5005.8 1996.15
  5034.4 1996.72  5055.4 1998.19  5065.9 1999.42  5072.9  2001.5  5078.2 2001.72
    5105 2007.83  5110.2 2007.91  5118.4 2009.71    5137 2011.79  5168.4  2013.8
  5201.1 2015.22  5307.8 2017.19  5334.6 2018.96  5373.9 2017.59  5462.7 2017.78
    5500 2016.95  5526.8 2017.57  5532.1 2016.94  5555.9 2017.54  5617.3 2017.74
#Mann= 6 ,-1 , 0
    4769     .16       0  4999.8     .07       0  5005.8     .16       0
  5168.4      .1       0  5373.9     .16       0  5555.9      .1       0
Bank Sta=4999.8,5005.8
XS Rating Curve= 0 ,0
Exp/Cntr=0.3,0.1

Type RM Length L Ch R = 1 ,2252    ,349,349,349
BEGIN DESCRIPTION:
UNT 0053 IN HEWA 5.0
END DESCRIPTION:
XS GIS Cut Line= 2
      2736085.91     10097677.23      2735443.58     10097303.98
#Sta/Elev= 30
  4862.2 2009.06  4870.8 2007.78  4893.6 2001.14  4905.5 1996.03  4928.6 1991.94
  4973.9 1989.98  4986.5 1987.56  4998.2 1987.19  5000.9 1986.69  5004.2 1987.19
  5022.7 1988.99  5054.2 1993.92  5118.7 1995.42  5140.2  1996.5  5155.9 1998.13
  5161.8 1997.99  5193.6 2000.48    5199 2000.36  5206.2 2002.25  5214.7 2003.05
  5257.8 2003.09    5264 2005.56  5273.5 2006.97  5279.3 2006.86  5316.5 2009.71
    5391 2011.62  5434.1 2015.15  5488.4 2017.67  5550.2 2020.62  5605.1 2022.27
#Mann= 7 ,-1 , 0
  4862.2     .16       0  4998.2     .07       0  5004.2     .16       0
  5155.9      .1       0  5193.6     .05       0  5488.4      .1       0
  5550.2     .16       0
Bank Sta=4998.2,5004.2
XS Rating Curve= 0 ,0
Exp/Cntr=0.3,0.1

Type RM Length L Ch R = 1 ,1903    ,455,455,455
BEGIN DESCRIPTION:
UNT 0053 IN HEWA 4.0
END DESCRIPTION:
XS GIS Cut Line= 2
      2736302.94     10097364.74      2735634.56     10097156.41
#Sta/Elev= 30
  4819.9 2016.09  4840.2 2015.15    4856 2013.13  4877.9 2011.89  4929.3 2004.36
    4943 2001.01  4960.8 1994.73  4970.2 1990.35  4975.5 1989.25  4981.7 1985.68
  4999.7  1982.4  5002.4  1981.9  5005.7  1982.4    5008 1983.33  5013.2  1983.4
  5023.6 1985.16  5034.1    1986  5091.7 1986.97  5143.3 1988.13  5170.2 1990.82
  5191.2 1989.88  5201.7  1991.3  5208.3  1994.1  5240.8 1999.26  5246.1 1998.97
  5285.5 2002.37  5311.1 2003.55  5376.1 2009.54  5478.9 2014.39    5520  2017.1
#Mann= 4 ,-1 , 0
  4819.9     .16       0  4999.7     .07       0  5005.7     .16       0
  5091.7      .1       0
Bank Sta=4999.7,5005.7
XS Rating Curve= 0 ,0
Exp/Cntr=0.3,0.1

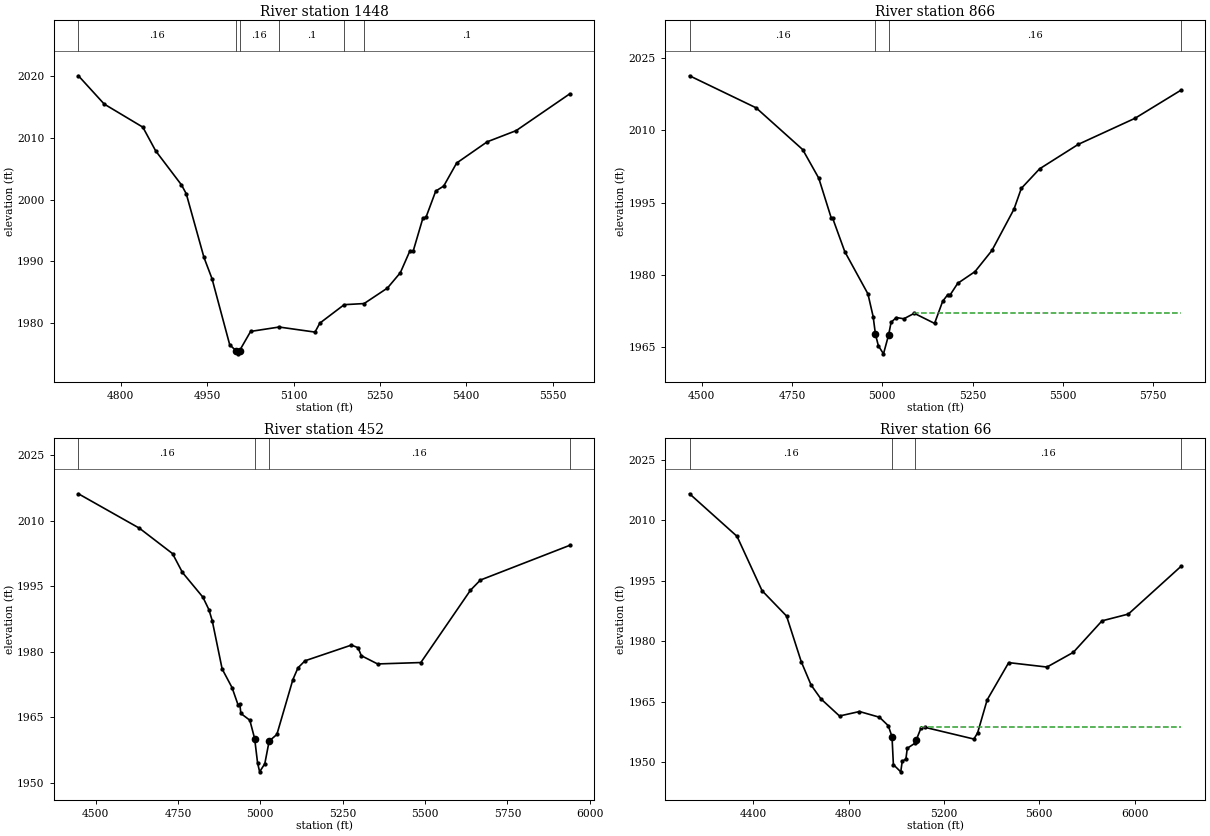
Type RM Length L Ch R = 1 ,1448    ,582,582,582
BEGIN DESCRIPTION:
UNT 0053 IN HEWA 3.0
END DESCRIPTION:
XS GIS Cut Line= 2
      2736546.01     10097017.52      2735782.79     10096635.91
#Sta/Elev= 30
  4726.3 2020.06  4771.1 2015.48  4838.2 2011.74  4860.5  2007.9  4905.3 2002.39
  4913.6 2000.96  4944.4 1990.64  4958.3 1987.22  4989.1  1976.5  5000.1 1975.54
  5002.8 1975.04  5006.1 1975.54  5025.4 1978.67  5074.9 1979.38  5137.2 1978.56
  5145.6 1980.01  5187.9    1983  5222.5 1983.18    5263 1985.69  5285.4 1988.17
  5302.2 1991.74  5307.7 1991.66  5324.5 1996.98  5330.1 1997.18  5346.9 2001.39
  5360.8 2002.21  5383.2 2005.93  5436.3 2009.37  5486.6 2011.18  5579.6 2017.13
#Mann= 6 ,-1 , 0
  4726.3     .16       0  5000.1     .07       0  5006.1     .16       0
  5074.9      .1       0  5187.9     .05       0  5222.5      .1       0
Bank Sta=5000.1,5006.1
XS Rating Curve= 0 ,0
Exp/Cntr=0.3,0.1

Type RM Length L Ch R = 1 ,866     ,414,414,414
BEGIN DESCRIPTION:
UNT 0053 IN HEWA 2.0
END DESCRIPTION:
XS GIS Cut Line= 4
       2736823.8     10096835.27      2736650.17     10096479.32
      2736363.71     10096253.63      2735773.45     10096149.46
#Sta/Elev= 30
  4466.5 2021.36  4650.8 2014.69  4779.7 2006.01  4824.2 2000.06  4858.8 1991.77
  4862.5 1991.77  4896.2 1984.79  4960.3    1976  4974.8 1971.26  4981.1  1967.6
  4989.2  1965.2  5003.4 1963.53  5017.5 1967.45  5024.5  1970.1  5038.9 1971.08
  5059.7 1970.82  5088.6 1971.96  5144.8 1969.86  5167.2 1974.46  5181.6 1975.87
    5188  1975.8  5208.8 1978.19  5256.7 1980.63  5303.6 1985.03  5364.6 1993.61
  5384.9 1997.94  5435.6 2002.01  5542.7  2007.1  5699.7 2012.52  5826.6 2018.35
#Mann= 4 ,-1 , 0
  4466.5     .16       0  4981.1     .07       0  5017.5     .16       0
  5826.6      .1       0
#XS Ineff= 2 , 0
                         5087.27            1972
Permanent Ineff=
       T       T
Bank Sta=4981.1,5017.5
XS Rating Curve= 0 ,0
Exp/Cntr=0.3,0.1

Type RM Length L Ch R = 1 ,452     ,386,386,386
BEGIN DESCRIPTION:
Mapping XS 14876524
END DESCRIPTION:
XS GIS Cut Line= 4
      2736966.33     10096728.26      2736922.92     10096235.59
      2736792.72     10096022.92      2736048.32     10095959.98
#Sta/Elev= 30
  4447.8 2016.18    4633 2008.29  4733.4 2002.48  4763.5 1998.16  4825.5 1992.51
  4843.9 1989.63  4853.9 1987.11    4884 1976.06  4914.1 1971.78  4932.7 1967.75
  4937.7 1967.98  4940.8 1965.87    4968 1964.32  4982.6 1960.12  4991.5 1954.55
  4997.8  1952.5  5013.5 1954.37  5026.6 1959.53  5050.1 1961.07  5098.7 1973.63
  5114.1 1976.31  5135.4 1977.93  5276.3 1981.53  5296.4 1980.93  5306.4  1979.1
  5355.8 1977.21    5487 1977.53  5637.6 1994.09  5667.7 1996.42  5938.8 2004.37
#Mann= 4 ,-1 , 0
  4447.8     .16       0  4982.6     .07       0  5026.6     .16       0
  5938.8     .16       0
Bank Sta=4982.6,5026.6
XS Rating Curve= 0 ,0
Exp/Cntr=0.3,0.1

Type RM Length L Ch R = 1 ,66      ,0,0,0
BEGIN DESCRIPTION:
UNT 0053 IN HEWA 1.0
END DESCRIPTION:
XS GIS Cut Line= 4
      2737016.24     10096769.44      2737205.04     10095983.86
      2737042.28     10095712.59      2736109.11     10095797.22
#Sta/Elev= 30
  4132.7  2016.6  4331.8 2006.04  4436.8 1992.55  4539.7 1986.25  4601.4  1974.9
  4642.5 1969.14  4683.7  1965.7  4761.8 1961.44  4845.7 1962.55  4929.6 1961.13
  4966.5 1959.03  4982.1  1956.3  4987.9 1949.37  5018.8 1947.58  5024.9 1950.17
  5040.4 1950.78  5046.2 1953.43  5077.3 1954.64  5083.2 1955.39  5104.5 1958.58
  5120.1 1958.63  5325.6 1955.72  5341.2 1957.24  5381.3 1965.44  5471.7 1974.69
  5632.3 1973.59  5742.8 1977.24  5863.3 1985.06  5973.7 1986.74    6194 1998.55
#Mann= 4 ,-1 , 0
  4132.7     .16       0  4982.1     .07       0  5077.3     .16       0
    6194     .16       0
#XS Ineff= 2 , 0
                         5105.11         1958.62
Permanent Ineff=
       T       T
Bank Sta=4982.1,5083.2
XS Rating Curve= 0 ,0
Exp/Cntr=0.3,0.1

Chan Stop Cuts=-1
Use User Specified Reach Order=0
Composite Channel Slope=5