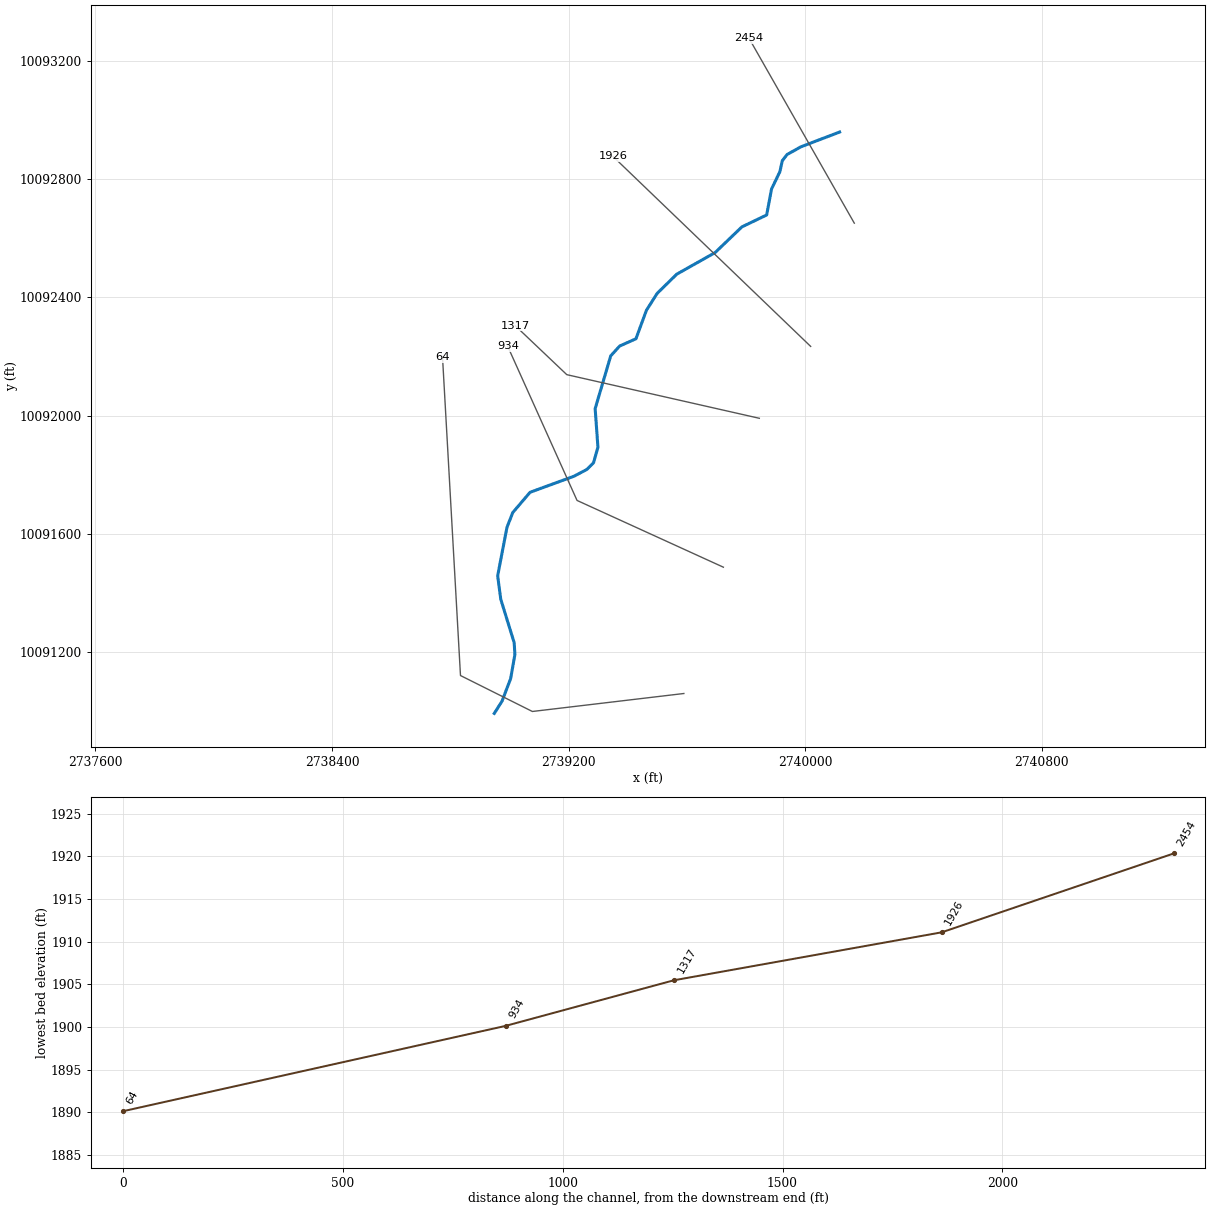
--- UNT 0054 IN HEWA.prj (project) ---

Proj Title=UNT 0054 IN HEWA Base Level Engineering
Current Plan=p01
Default Exp/Contr=0.3,0.1
English Units
Geom File=g01
Flow File=f01
Plan File=p01
Y Axis Title=Elevation
X Axis Title(PF)=Main Channel Distance
X Axis Title(XS)=Station
BEGIN DESCRIPTION:
UNT 0054 IN HEWA
END DESCRIPTION:
DSS Export Rating Curves= 0
DSS Export Rating Curve Sorted= 0
DSS Export Volume Flow Curves= 0
DXF OffsetX= 0
DXF OffsetY= 0
DXF ScaleX= 1
DXF ScaleY= 10

--- UNT 0054 IN HEWA.p01 (plan) ---

Plan Title=Multiple Run
Short Identifier=Multiple
Geom File=g01
Flow File=f01
Subcritical Flow
K Sum by GR= 0
Std Step Tol= 0.01
Critical Tol= 0.01
Num of Std Step Trials= 20
Max Error Tol= 0.3
Flow Tol Ratio= 0.001
Split Flow NTrial= 30
Split Flow Tol= 0.02
Split Flow Ratio= 0.02
Log Output Level= 0
Friction Slope Method= 1
Unsteady Friction Slope Method= 2
Unsteady Bridges Friction Slope Method= 1
Parabolic Critical Depth
Global Vel Dist=  1 , 1 , 1
Global Log Level= 0
CheckData=True
Encroach Param= -1, 0, 0, 0
BEGIN DESCRIPTION:
Multiple Run
END DESCRIPTION:

--- UNT 0054 IN HEWA.f01 (steady flow) ---

Flow Title=Multiple
Program Version=4.10
Number of Profiles= 7
Profile Names=10-year,25-year,50-year,1pct_min,100-year,1pct_plu,500-year
River Rch & RM=UNT 0054 IN HEWA,Reach-1         ,2454
     776    1120    1417    1313    1776    2402    2801
Boundary for River Rch & Prof#=UNT 0054 IN HEWA,Reach-1         , 1
Up Type= 0
Dn Type= 3
Dn Slope=0.011
Boundary for River Rch & Prof#=UNT 0054 IN HEWA,Reach-1         , 2
Up Type= 0
Dn Type= 3
Dn Slope=0.011
Boundary for River Rch & Prof#=UNT 0054 IN HEWA,Reach-1         , 3
Up Type= 0
Dn Type= 3
Dn Slope=0.011
Boundary for River Rch & Prof#=UNT 0054 IN HEWA,Reach-1         , 4
Up Type= 0
Dn Type= 3
Dn Slope=0.011
Boundary for River Rch & Prof#=UNT 0054 IN HEWA,Reach-1         , 5
Up Type= 0
Dn Type= 3
Dn Slope=0.011
Boundary for River Rch & Prof#=UNT 0054 IN HEWA,Reach-1         , 6
Up Type= 0
Dn Type= 3
Dn Slope=0.011
Boundary for River Rch & Prof#=UNT 0054 IN HEWA,Reach-1         , 7
Up Type= 0
Dn Type= 3
Dn Slope=0.011
DSS Import GetInterval= 0
DSS Import GetPeak= 0
DSS Import FillOption= 0

--- UNT 0054 IN HEWA.g01 (geometry) ---

Geom Title=Existing Conditions
Program Version=4.10

River Reach=UNT 0054 IN HEWA,Reach-1
Reach XY= 30
      2740116.02     10092959.33      2739985.42     10092909.46
      2739938.47     10092883.33      2739922.22     10092862.36
      2739914.22     10092825.49      2739886.01     10092766.97
      2739869.37     10092678.88      2739785.74     10092638.68
      2739694.96     10092551.61      2739565.56     10092478.82
      2739499.34     10092414.02      2739462.88      10092356.6
      2739427.52     10092260.46      2739372.24      10092235.6
      2739342.14     10092202.43      2739289.56      10092024.1
       2739298.9     10091893.57      2739283.92     10091840.73
      2739261.52     10091818.49       2739217.8      10091795.5
      2739069.52     10091741.27      2739010.93     10091672.76
       2738991.3     10091622.56      2738959.87     10091458.75
      2738970.38     10091379.56      2739015.75     10091232.42
      2739018.11     10091192.42      2739003.73     10091111.03
      2738974.78     10091035.28      2738948.47     10090993.73

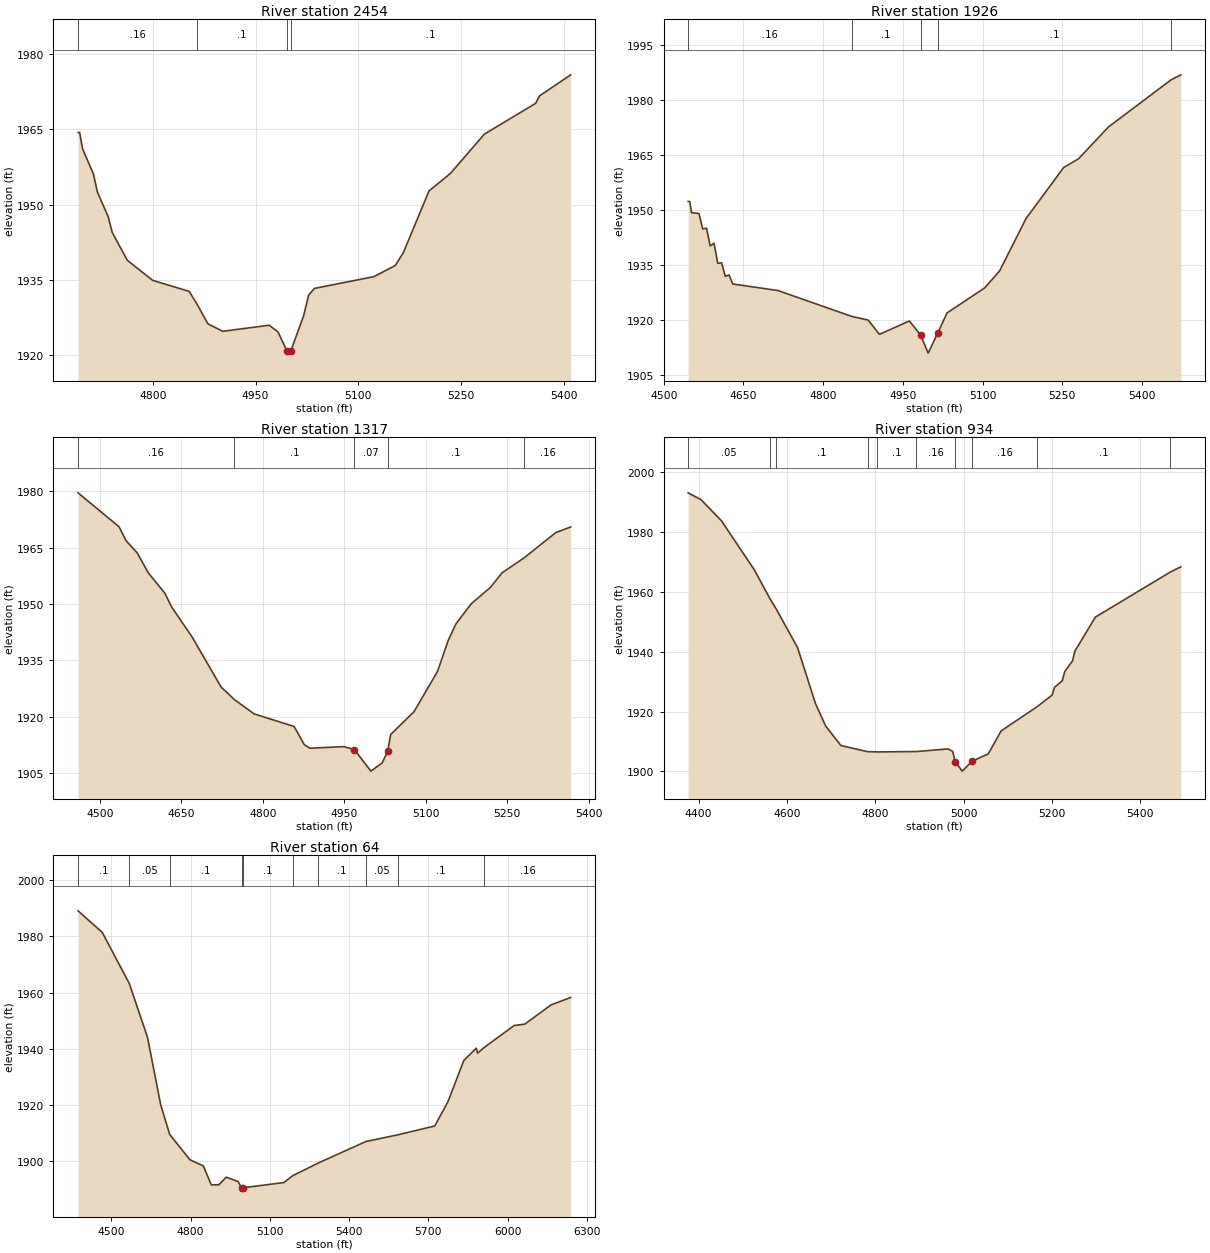
Type RM Length L Ch R = 1 ,2454    ,528,528,528
BEGIN DESCRIPTION:
UNT 0054 IN HEWA 5.0
END DESCRIPTION:
XS GIS Cut Line= 2
      2740165.78     10092651.22      2739809.89     10093276.19
#Sta/Elev= 30
  4690.8 1964.39  4693.1 1964.39  4697.5 1961.08  4713.3 1956.06  4719.1 1952.47
  4734.9 1947.54  4740.7 1944.43  4762.7 1938.86  4799.8 1934.86  4853.1 1932.65
  4864.3 1930.15  4880.5 1926.17  4902.1 1924.69  4969.9  1925.9  4982.8 1924.55
  4995.6 1920.83  4998.4 1920.33  5001.6 1920.83  5020.2 1927.81  5027.4 1931.91
  5036.1 1933.26  5122.5 1935.59    5154 1937.82  5165.8 1940.42  5203.2 1952.71
  5234.6 1956.22  5283.9 1964.04  5358.9  1970.2  5364.6 1971.69    5410 1975.89
#Mann= 4 ,-1 , 0
  4690.8     .16       0  4864.3      .1       0  4995.6     .07       0
  5001.6      .1       0
Bank Sta=4995.6,5001.6
XS Rating Curve= 0 ,0
Exp/Cntr=0.3,0.1

Type RM Length L Ch R = 1 ,1926    ,609,609,609
BEGIN DESCRIPTION:
UNT 0054 IN HEWA 4.0
END DESCRIPTION:
XS GIS Cut Line= 2
      2740018.19     10092234.56      2739349.81      10092876.9
#Sta/Elev= 30
    4546 1952.34    4549 1952.34  4552.3 1949.32  4566.4 1949.05  4573.4 1944.87
  4580.6 1945.09  4587.5 1940.25  4594.7 1940.99  4601.7 1935.52  4608.9 1935.68
  4615.8    1932    4623 1932.35    4630 1929.89  4714.9 1928.12  4853.8 1921.07
  4884.7 1920.07    4906 1916.19  4962.4 1919.83  4983.7 1915.94  4997.6 1911.08
 5016.04 1916.64  5033.1 1922.01  5103.9 1928.81  5132.2 1933.48  5181.8  1947.7
  5252.6 1961.59  5280.7 1963.98  5337.2 1972.66  5454.7 1985.44    5473 1986.81
#Mann= 5 ,-1 , 0
    4546     .16       0  4853.8      .1       0  4983.7     .07       0
 5016.04      .1       0  5454.7     .16       0
Bank Sta=4983.7,5016.04
XS Rating Curve= 0 ,0
Exp/Cntr=0.3,0.1

Type RM Length L Ch R = 1 ,1317    ,383,383,383
BEGIN DESCRIPTION:
UNT 0054 IN HEWA 3.0
END DESCRIPTION:
XS GIS Cut Line= 3
      2739844.59     10091991.48      2739193.57     10092139.04
      2739019.96     10092303.97
#Sta/Elev= 30
  4459.6 1979.58  4535.1 1970.54  4547.9 1966.86  4568.4 1963.62  4588.9 1958.28
  4619.7 1952.79  4631.6 1949.24  4669.6 1941.19    4723 1927.86  4747.4 1924.52
  4783.7 1920.71  4857.5 1917.35    4876 1912.54  4886.3 1911.55  4948.9 1911.99
  4968.3  1911.2  4998.8 1905.46  5019.6 1907.66  5029.8 1910.79  5035.1  1915.2
  5078.2  1921.3  5121.4    1932  5141.1 1940.25  5155.3 1944.67  5183.6 1950.05
  5218.8 1954.39  5240.2 1958.26  5280.9 1962.27  5339.3 1969.01  5366.6 1970.48
#Mann= 5 ,-1 , 0
  4459.6     .16       0  4747.4      .1       0  4968.3     .07       0
  5029.8      .1       0  5280.9     .16       0
Bank Sta=4968.3,5029.8
XS Rating Curve= 0 ,0
Exp/Cntr=0.3,0.1

Type RM Length L Ch R = 1 ,934     ,870,870,870
BEGIN DESCRIPTION:
UNT 0054 IN HEWA 2.0
END DESCRIPTION:
XS GIS Cut Line= 3
      2739723.12     10091487.98      2739228.29     10091713.69
      2738993.92     10092234.51
#Sta/Elev= 30
  4376.4  1993.1  4405.7  1990.8  4451.7 1983.78  4526.3 1967.34  4561.2 1957.82
  4576.3 1954.13    4624 1941.39  4664.6 1922.69  4687.6  1915.2  4722.2 1908.66
  4782.5 1906.62  4804.3 1906.53  4893.2 1906.65  4964.2 1907.53  4975.2 1906.72
  4980.7 1903.27  4996.8 1900.11    5019 1903.43  5055.6 1905.86  5084.8 1913.55
  5165.3 1921.53    5200  1925.5  5205.5 1928.07  5223.2  1930.3  5228.7 1933.38
  5246.3 1936.92  5251.8 1940.22  5298.1 1951.57  5466.7 1966.54  5491.4 1968.37
#Mann= 10 ,-1 , 0
  4376.4     .05       0  4561.2     .16       0  4576.3      .1       0
  4782.5     .05       0  4804.3      .1       0  4893.2     .16       0
  4980.7     .07       0    5019     .16       0  5165.3      .1       0
  5466.7     .16       0
Bank Sta=4980.7,5019
XS Rating Curve= 0 ,0
Exp/Cntr=0.3,0.1

Type RM Length L Ch R = 1 ,64      ,0,0,0
BEGIN DESCRIPTION:
UNT 0054 IN HEWA 1.0
END DESCRIPTION:
XS GIS Cut Line= 4
      2739589.44     10091060.92      2739077.25     10091000.15
      2738834.19     10091121.68      2738773.45     10092197.74
#Sta/Elev= 30
  4373.8 1989.04  4465.4 1981.39  4567.7 1963.24  4636.6 1944.16    4687 1919.97
    4721 1909.53  4797.7 1900.52  4848.1 1898.38  4878.3 1891.64  4906.9 1891.63
  4934.8 1894.37  4979.6  1892.8  4993.3 1890.61  4996.1 1890.11  4999.3 1890.61
  5152.9 1892.44  5186.2 1894.86  5282.7 1899.36  5463.9 1907.04  5584.8 1909.42
  5724.3 1912.55  5774.4 1921.16  5834.5 1935.86  5881.7 1940.22  5886.7 1938.44
  5911.8 1940.48  6024.8 1948.25  6065.6 1948.79    6165 1955.61  6239.1 1958.25
#Mann= 10 ,-1 , 0
  4373.8      .1       0  4567.7     .05       0    4721      .1       0
  4993.3     .07       0  4999.3      .1       0  5186.2     .05       0
  5282.7      .1       0  5463.9     .05       0  5584.8      .1       0
  5911.8     .16       0
Bank Sta=4993.3,4999.3
XS Rating Curve= 0 ,0
Exp/Cntr=0.3,0.1

Chan Stop Cuts=-1
Use User Specified Reach Order=0
Composite Channel Slope=5