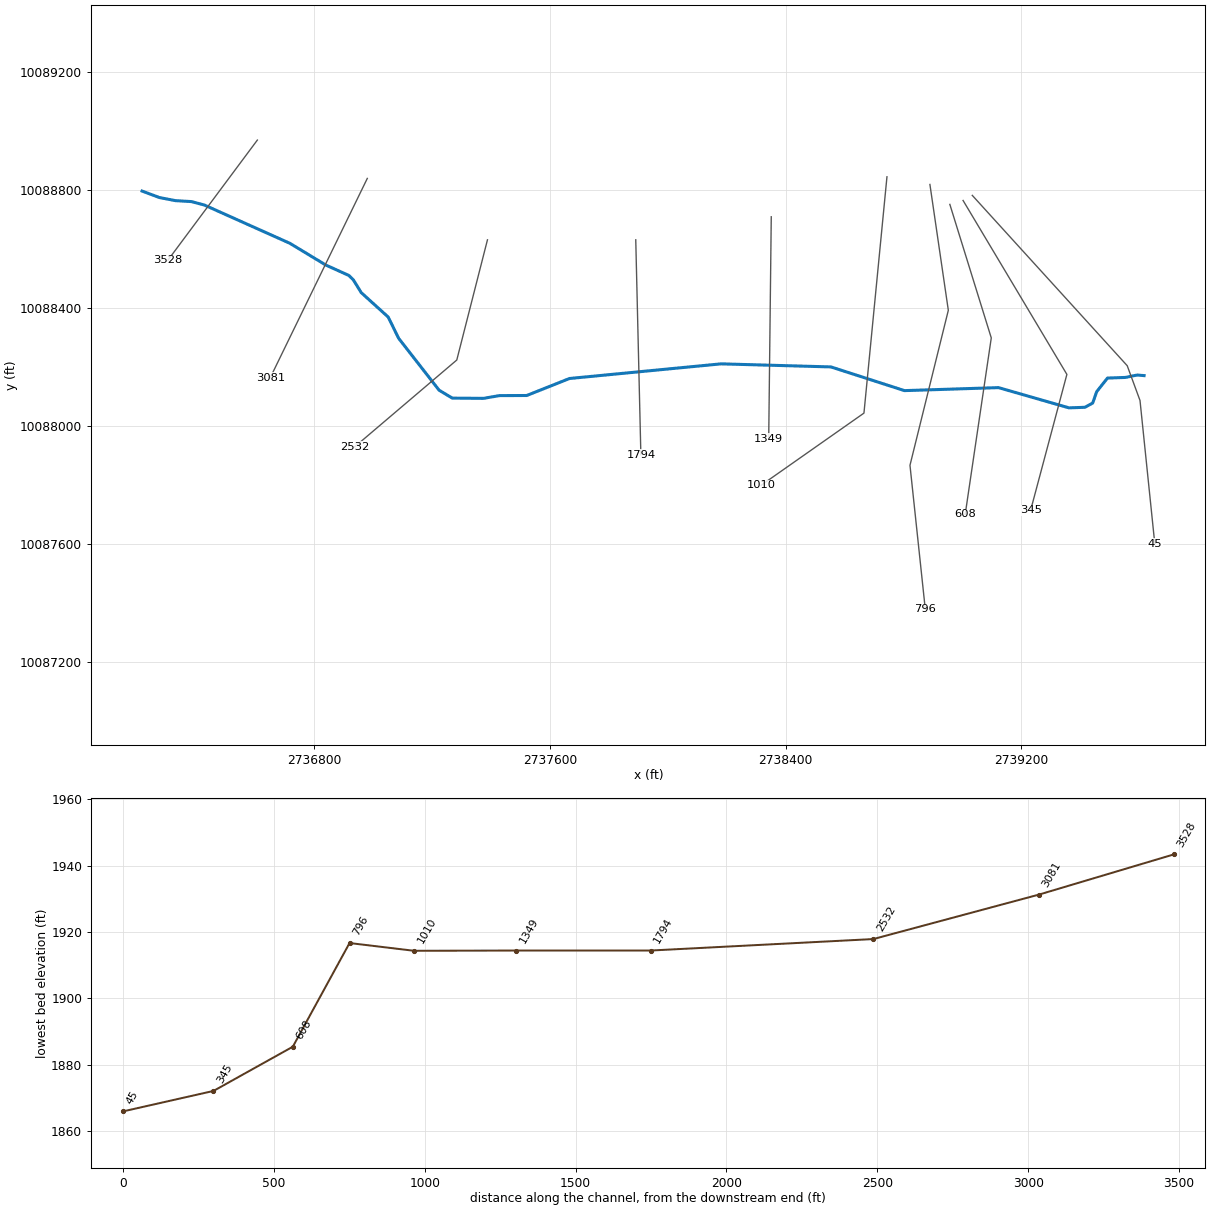
--- UNT 0055 IN HEWA.prj (project) ---

Proj Title=UNT 0055 IN HEWA Base Level Engineering
Current Plan=p01
Default Exp/Contr=0.3,0.1
English Units
Geom File=g01
Flow File=f01
Plan File=p01
BEGIN DESCRIPTION:
UNT 0055 IN HEWA
END DESCRIPTION:

--- UNT 0055 IN HEWA.p01 (plan) ---

Plan Title=Multiple Run
Short Identifier=Multiple
Geom File=g01
Flow File=f01
Subcritical Flow
K Sum by GR= 0
Std Step Tol= 0.01
Critical Tol= 0.01
Num of Std Step Trials= 20
Max Error Tol= 0.3
Flow Tol Ratio= 0.001
Split Flow NTrial= 30
Split Flow Tol= 0.02
Split Flow Ratio= 0.02
Log Output Level= 0
Friction Slope Method= 1
Unsteady Friction Slope Method= 2
Unsteady Bridges Friction Slope Method= 1
Parabolic Critical Depth
Global Vel Dist=  1 , 1 , 1
Global Log Level= 0
CheckData=True
Encroach Param= -1, 0, 0, 0
BEGIN DESCRIPTION:
Multiple Run
END DESCRIPTION:

--- UNT 0055 IN HEWA.f01 (steady flow) ---

Flow Title=Multiple
Number of Profiles=7
Profile Names=10-year,25-year,50-year,1pct_min,100-year,1pct_plu,500-year
River Rch & RM= UNT 0055 IN HEWA,Reach-1,3528
     671     961    1210    1117    1510    2042    2359
Boundary for River Rch & Prof#=UNT 0055 IN HEWA,Reach-1,1
Up Type=0
Dn Type=3
Dn Slope=0.005
Boundary for River Rch & Prof#=UNT 0055 IN HEWA,Reach-1,2
Up Type=0
Dn Type=3
Dn Slope=0.005
Boundary for River Rch & Prof#=UNT 0055 IN HEWA,Reach-1,3
Up Type=0
Dn Type=3
Dn Slope=0.005
Boundary for River Rch & Prof#=UNT 0055 IN HEWA,Reach-1,4
Up Type=0
Dn Type=3
Dn Slope=0.005
Boundary for River Rch & Prof#=UNT 0055 IN HEWA,Reach-1,5
Up Type=0
Dn Type=3
Dn Slope=0.005
Boundary for River Rch & Prof#=UNT 0055 IN HEWA,Reach-1,6
Up Type=0
Dn Type=3
Dn Slope=0.005
Boundary for River Rch & Prof#=UNT 0055 IN HEWA,Reach-1,7
Up Type=0
Dn Type=3
Dn Slope=0.005

--- UNT 0055 IN HEWA.g01 (geometry) ---

Geom Title=Existing Conditions

River Reach=UNT 0055 IN HEWA,Reach-1
Reach XY= 30
      2736215.28     10088797.58      2736274.21     10088775.53
      2736329.01     10088765.04      2736382.71     10088761.85
      2736427.03     10088750.08      2736717.04     10088620.29
      2736839.53     10088546.26      2736917.35     10088511.16
      2736932.73     10088496.08      2736959.50     10088452.78
      2737050.87     10088370.09      2737086.54     10088297.66
      2737223.71     10088121.76      2737268.50     10088094.83
      2737374.21     10088093.94      2737428.65     10088103.29
      2737521.28     10088103.66      2737666.47     10088161.37
      2738181.11     10088211.08      2738554.21     10088200.68
      2738803.80     10088120.24      2739122.96     10088130.44
      2739362.42     10088061.73      2739416.48     10088063.65
      2739442.87     10088078.03      2739456.46     10088116.73
      2739493.10     10088162.85      2739553.83     10088164.98
      2739593.82     10088173.10      2739617.33     10088171.22

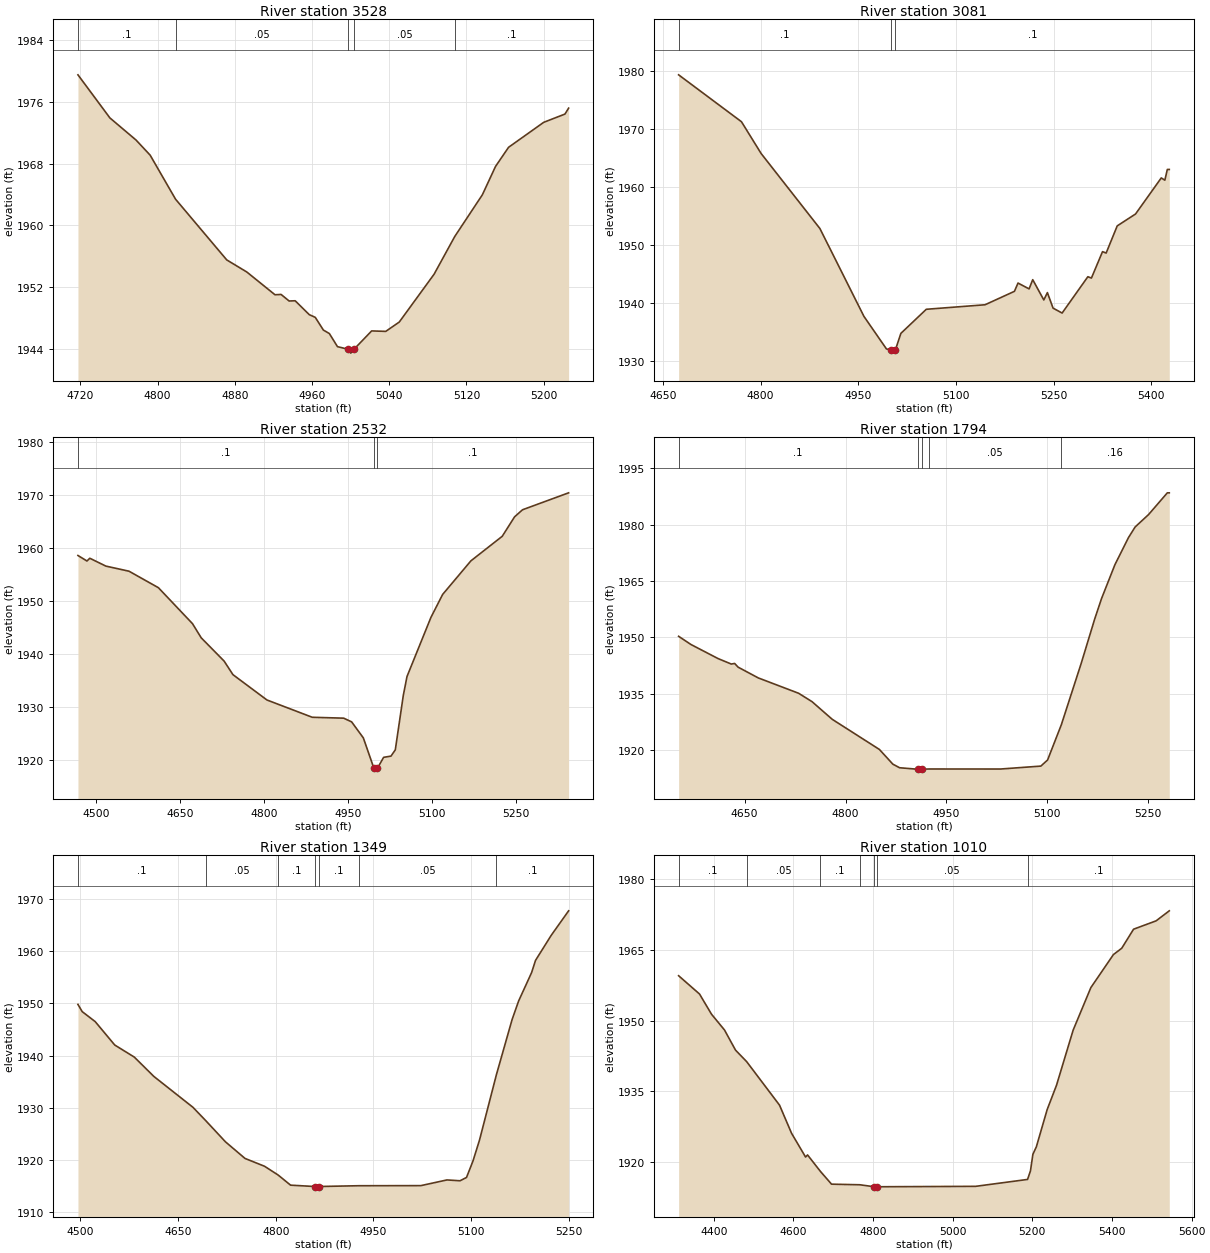
Type RM Length L Ch R = 1,3528,447,447,447
BEGIN DESCRIPTION:
UNT 0055 IN HEWA 8.0
END DESCRIPTION:
XS GIS Cut Line= 2
      2736606.75     10088970.62      2736303.22     10088563.02
#Sta/Elev= 30
  4717.6 1979.50  4750.7 1973.91  4777.8 1971.04  4792.4 1969.08  4818.7 1963.37
  4871.7 1955.50  4892.5 1953.93  4921.7 1950.98  4928.0 1951.02  4936.3 1950.17
  4942.6 1950.20  4957.2 1948.40  4963.4 1948.05  4971.8 1946.40  4978.0 1945.95
  4986.4 1944.25  4997.5 1943.91  5000.2 1943.41  5003.5 1943.91  5021.8 1946.29
  5036.4 1946.23  5050.4 1947.44  5086.5 1953.65  5107.9 1958.54  5136.5 1963.95
  5150.1 1967.62  5163.6 1970.10  5200.0 1973.34  5222.0 1974.41  5225.8 1975.18
#Mann=5,-1,0
  4717.6     0.1       0  4818.7    0.05       0  4997.5   0.035       0
  5003.5    0.05       0  5107.9     0.1       0
Bank Sta=4997.5,5003.5
Exp/Cntr=0.3,0.1

Type RM Length L Ch R = 1,3081,549,549,549
BEGIN DESCRIPTION:
UNT 0055 IN HEWA 7.0
END DESCRIPTION:
XS GIS Cut Line= 2
      2736980.04     10088840.47      2736650.17     10088163.35
#Sta/Elev= 30
  4674.2 1979.34  4770.7 1971.24  4800.9 1965.75  4891.1 1952.80  4958.7 1937.63
  4993.2 1932.02  5000.8 1931.79  5003.5 1931.29  5006.8 1931.79  5015.4 1934.70
  5054.4 1938.86  5144.6 1939.64  5189.7 1941.96  5195.2 1943.39  5212.2 1942.38
  5217.8 1943.97  5234.8 1940.47  5240.3 1941.74  5249.0 1939.06  5262.9 1938.21
  5302.4 1944.48  5307.9 1944.25  5324.9 1948.81  5330.5 1948.57  5347.5 1953.26
  5375.6 1955.31  5415.1 1961.54  5420.6 1961.15  5424.4 1963.00  5427.4 1963.00
#Mann=3,-1,0
  4674.2     0.1       0  5000.8    0.07       0  5006.8     0.1       0
Bank Sta=5000.8,5006.8
Exp/Cntr=0.3,0.1

Type RM Length L Ch R = 1,2532,738,738,738
BEGIN DESCRIPTION:
UNT 0055 IN HEWA 5.0
END DESCRIPTION:
XS GIS Cut Line= 3
      2737388.01     10088632.08      2737283.85     10088224.11
      2736936.59     10087928.95
#Sta/Elev= 30
  4467.6 1958.52  4483.7 1957.48  4488.8 1958.00  4517.5 1956.52  4558.8 1955.56
  4611.4 1952.45  4672.3 1945.67  4687.9 1943.00  4728.8 1938.62  4744.6 1936.06
  4805.3 1931.29  4886.3 1928.03  4942.5 1927.86  4956.7 1927.16  4977.6 1924.14
  4996.6 1918.38  4999.3 1917.88  5002.6 1918.38  5013.8 1920.48  5027.0 1920.71
  5034.7 1921.89  5049.0 1932.15  5055.6 1935.71  5098.4 1946.86  5119.3 1951.18
  5169.8 1957.51  5225.8 1962.14  5247.8 1965.80  5262.1 1967.14  5344.4 1970.33
#Mann=3,-1,0
  4467.6     0.1       0  4996.6    0.07       0  5002.6     0.1       0
Bank Sta=4996.6,5002.6
Exp/Cntr=0.3,0.1

Type RM Length L Ch R = 1,1794,445,445,445
BEGIN DESCRIPTION:
UNT 0055 IN HEWA 4.0
END DESCRIPTION:
XS GIS Cut Line= 2
      2737891.48     10088632.11      2737908.85     10087902.91
#Sta/Elev= 30
  4551.9 1950.32  4570.3 1948.13  4610.3 1944.41  4630.2 1942.93  4635.2 1943.09
  4640.3 1942.11  4670.3 1939.24  4730.3 1935.15  4750.3 1932.91  4780.3 1928.21
  4850.4 1920.19  4870.4 1916.27  4880.4 1915.32  4907.4 1914.92  4910.1 1914.42
  4913.4 1914.92  4924.2 1914.99  5030.4 1914.98  5090.4 1915.76  5100.4 1917.39
  5120.8 1926.75  5150.4 1943.13  5170.5 1954.97  5180.5 1960.32  5200.5 1969.40
  5220.5 1976.56  5230.5 1979.42  5250.5 1982.73  5278.4 1988.52  5281.3 1988.52
#Mann=5,-1,0
  4551.9     0.1       0  4907.4   0.033       0  4913.4     0.1       0
  4924.2    0.05       0  5120.8    0.16       0
Bank Sta=4907.4,4913.4
Exp/Cntr=0.3,0.1

Type RM Length L Ch R = 1,1349,339,339,339
BEGIN DESCRIPTION:
UNT 0055 IN HEWA 3.0
END DESCRIPTION:
XS GIS Cut Line= 2
      2738351.55     10088710.26      2738342.90     10087956.91
#Sta/Elev= 30
  4496.2 1949.80  4502.7 1948.42  4522.7 1946.50  4552.7 1942.02  4582.7 1939.71
  4612.7 1936.01  4672.7 1930.10  4692.7 1927.50  4722.7 1923.48  4752.7 1920.30
  4782.7 1918.80  4803.6 1917.12  4822.7 1915.18  4859.8 1914.92  4862.5 1914.42
  4865.8 1914.92  4927.3 1915.07  5022.8 1915.09  5062.8 1916.18  5082.8 1916.02
  5092.8 1916.65  5102.8 1919.82  5112.8 1923.82  5138.8 1936.37  5162.8 1946.89
  5172.8 1950.44  5192.8 1955.90  5198.8 1958.23  5222.8 1963.01  5249.6 1967.72
#Mann=7,-1,0
  4496.2     0.1       0  4692.7    0.05       0  4803.6     0.1       0
  4859.8   0.033       0  4865.8     0.1       0  4927.3    0.05       0
  5138.8     0.1       0
Bank Sta=4859.8,4865.8
Exp/Cntr=0.3,0.1

Type RM Length L Ch R = 1,1010,214,214,214
BEGIN DESCRIPTION:
Mapping XS b39e6a3b
END DESCRIPTION:
XS GIS Cut Line= 3
      2738744.38     10088845.96      2738666.26     10088043.91
      2738317.30     10087799.12
#Sta/Elev= 30
  4311.7 1959.49  4364.2 1955.62  4394.3 1951.35  4426.9 1948.01  4454.6 1943.75
  4482.4 1941.33  4565.1 1932.11  4595.3 1926.16  4630.5 1921.13  4635.5 1921.57
  4667.7 1918.10  4695.7 1915.39  4766.9 1915.26  4803.3 1914.84  4806.0 1914.34
  4809.3 1914.84  5057.4 1914.93  5187.9 1916.39  5195.2 1918.20  5201.3 1921.71
  5210.0 1923.29  5237.1 1931.15  5260.6 1936.31  5302.4 1947.98  5346.9 1956.98
  5403.5 1963.96  5424.5 1965.31  5454.1 1969.33  5510.7 1971.10  5543.8 1973.22
#Mann=7,-1,0
  4311.7     0.1       0  4482.4    0.05       0  4667.7     0.1       0
  4766.9    0.05       0  4803.3   0.033       0  4809.3    0.05       0
  5187.9     0.1       0
Bank Sta=4803.3,4809.3
Exp/Cntr=0.3,0.1

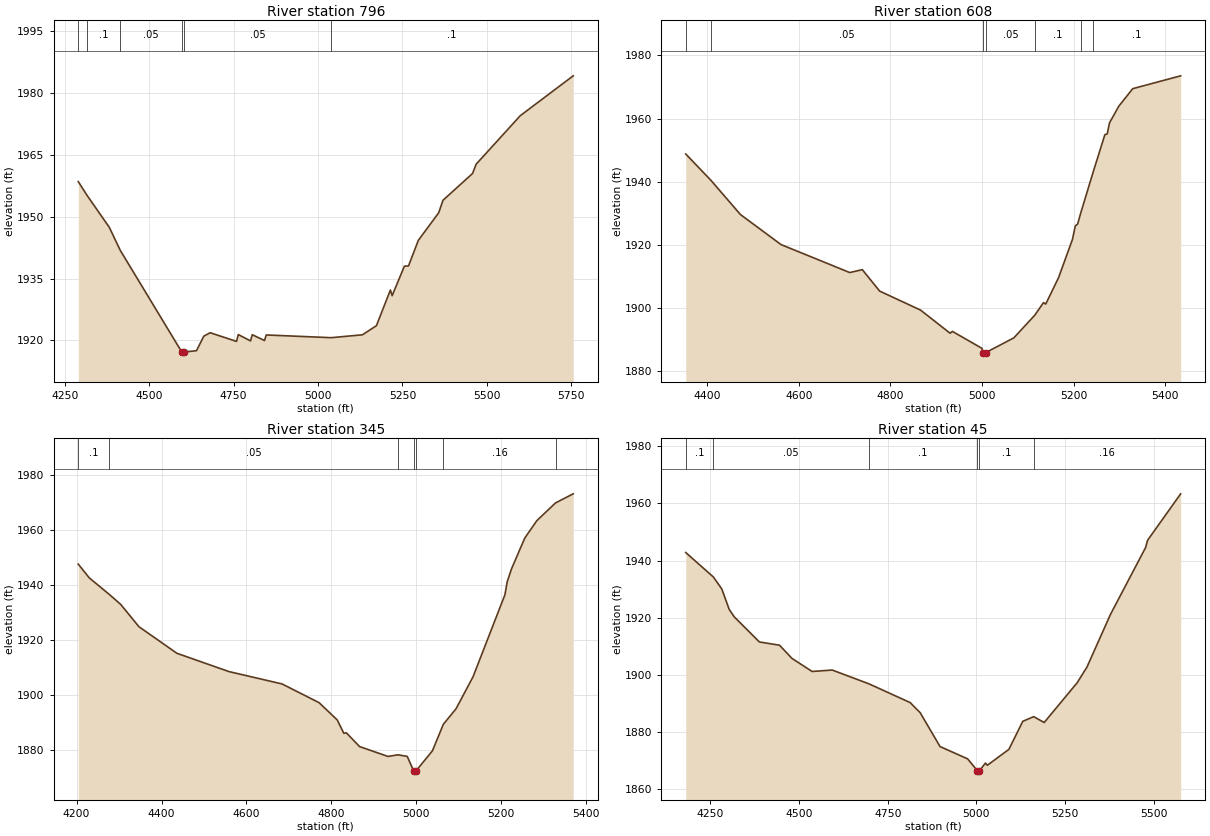
Type RM Length L Ch R = 1,796,188,188,188
BEGIN DESCRIPTION:
Mapping XS aa8d5ade
END DESCRIPTION:
XS GIS Cut Line= 4
      2738890.22     10088819.97      2738952.72     10088392.87
      2738822.51     10087866.83      2738874.52     10087377.95
#Sta/Elev= 30
  4290.2 1958.54  4315.8 1955.25  4382.1 1947.44  4414.5 1941.86  4596.7 1917.18
  4599.4 1916.68  4602.7 1917.18  4640.1 1917.51  4661.7 1921.03  4680.5 1921.87
  4758.7 1919.77  4763.8 1921.43  4800.1 1919.89  4805.2 1921.39  4841.5 1919.98
  4846.7 1921.33  5039.0 1920.67  5131.4 1921.37  5172.8 1923.58  5214.2 1932.24
  5219.4 1930.87  5255.6 1938.02  5267.8 1938.08  5297.0 1944.30  5357.4 1951.01
  5369.9 1954.02  5457.4 1960.51  5468.0 1962.76  5598.7 1974.54  5755.4 1984.21
#Mann=6,-1,0
  4290.2    0.05       0  4315.8     0.1       0  4414.5    0.05       0
  4596.7   0.033       0  4602.7    0.05       0  5039.0     0.1       0
Bank Sta=4596.7,4602.7
Exp/Cntr=0.3,0.1

Type RM Length L Ch R = 1,608,263,263,263
BEGIN DESCRIPTION:
UNT 0055 IN HEWA 2.0
END DESCRIPTION:
XS GIS Cut Line= 3
      2738957.92     10088752.28      2739098.55     10088299.12
      2739010.02     10087700.21
#Sta/Elev= 30
  4353.4 1948.80  4408.4 1940.45  4472.8 1929.62  4561.3 1920.11  4711.3 1911.25
  4738.7 1912.17  4776.5 1905.38  4865.7 1899.37  4930.2 1892.04  4935.2 1892.62
  4999.8 1887.25  5002.2 1885.92  5004.9 1885.42  5008.2 1885.92  5069.3 1890.57
  5115.1 1897.77  5133.9 1901.71  5138.9 1901.28  5166.9 1909.64  5197.2 1921.76
  5203.4 1926.01  5208.5 1926.61  5215.2 1930.08  5242.3 1943.05  5267.9 1954.92
  5273.0 1955.14  5278.1 1958.67  5298.3 1963.93  5328.7 1969.48  5433.3 1973.55
#Mann=7,-1,0
  4353.4     0.1       0  4408.4    0.05       0  5002.2   0.035       0
  5008.2    0.05       0  5115.1     0.1       0  5215.2    0.16       0
  5242.3     0.1       0
Bank Sta=5002.2,5008.2
Exp/Cntr=0.3,0.1

Type RM Length L Ch R = 1,345,300,300,300
BEGIN DESCRIPTION:
Mapping XS bbe376e3
END DESCRIPTION:
XS GIS Cut Line= 3
      2739002.80     10088765.60      2739355.25     10088175.28
      2739231.99     10087713.48
#Sta/Elev= 30
  4204.0 1947.63  4230.0 1942.63  4277.3 1936.60  4304.0 1932.99  4346.8 1924.91
  4436.3 1915.24  4558.9 1908.60  4683.7 1904.12  4771.0 1897.32  4813.8 1891.04
  4829.4 1886.16  4835.2 1886.37  4866.4 1881.36  4933.3 1877.78  4956.7 1878.37
  4978.6 1877.80  4993.6 1872.58  4996.4 1872.08  4999.6 1872.58  5038.0 1879.83
  5063.7 1889.46  5093.6 1895.10  5133.7 1906.74  5208.7 1936.51  5214.0 1941.20
  5224.3 1945.94  5255.4 1957.09  5283.7 1963.41  5327.9 1969.87  5369.5 1973.17
#Mann=7,-1,0
  4204.0     0.1       0  4277.3    0.05       0  4956.7     0.1       0
  4993.6    0.07       0  4999.6     0.1       0  5063.7    0.16       0
  5327.9     0.1       0
Bank Sta=4993.6,4999.6
Exp/Cntr=0.3,0.1

Type RM Length L Ch R = 1,45,0,0,0
BEGIN DESCRIPTION:
UNT 0055 IN HEWA 1.0
END DESCRIPTION:
XS GIS Cut Line= 4
      2739034.10     10088782.89      2739560.11     10088204.79
      2739603.52     10088086.74      2739653.67     10087600.79
#Sta/Elev= 30
  4180.2 1942.82  4258.3 1934.23  4281.9 1930.06  4302.8 1922.90  4317.0 1920.30
  4388.0 1911.50  4444.7 1910.36  4479.8 1905.74  4536.6 1901.16  4593.4 1901.66
  4697.0 1896.83  4813.0 1890.28  4841.3 1886.75  4897.4 1874.87  4975.2 1870.56
  5002.7 1866.41  5005.4 1865.91  5008.7 1866.41  5025.5 1869.09  5030.8 1868.31
  5091.6 1873.88  5130.8 1883.71  5161.8 1885.34  5191.1 1883.28  5284.3 1897.23
  5311.8 1902.71  5378.2 1921.17  5477.2 1944.56  5482.7 1947.09  5576.1 1963.38
#Mann=6,-1,0
  4180.2     0.1       0  4258.3    0.05       0  4697.0     0.1       0
  5002.7    0.07       0  5008.7     0.1       0  5161.8    0.16       0
Bank Sta=5002.7,5008.7
Exp/Cntr=0.3,0.1

Chan Stop Cuts=-1