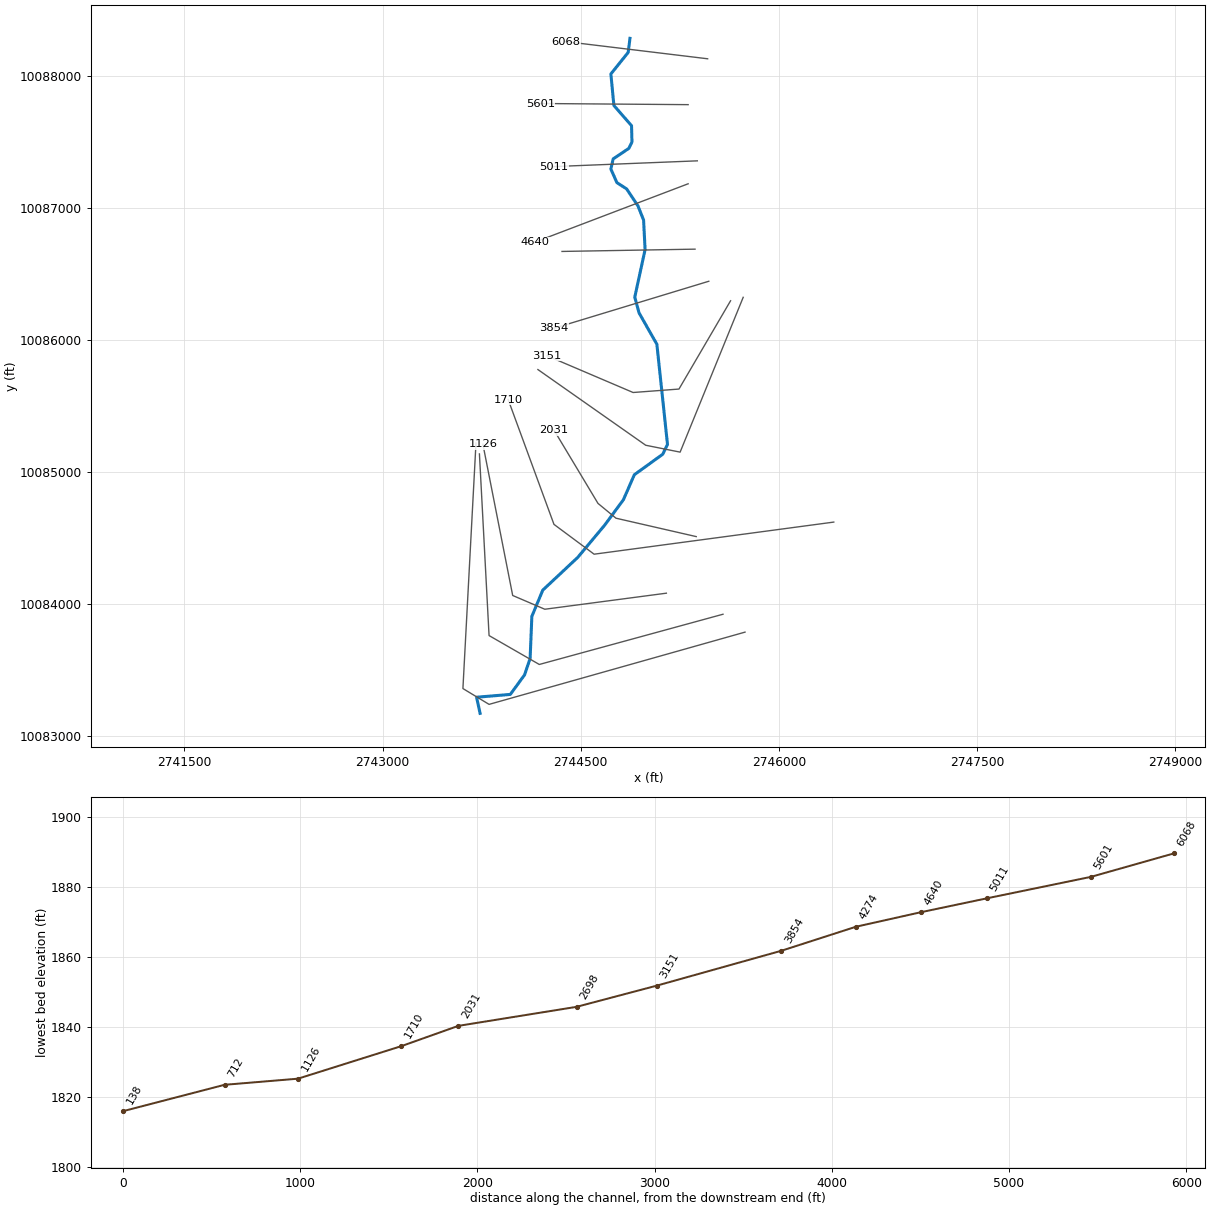
--- UNT 0056 IN HEWA.prj (project) ---

Proj Title=UNT 0056 IN HEWA Base Level Engineering
Current Plan=p01
Default Exp/Contr=0.3,0.1
English Units
Geom File=g01
Flow File=f01
Plan File=p01
BEGIN DESCRIPTION:
UNT 0056 IN HEWA
END DESCRIPTION:

--- UNT 0056 IN HEWA.p01 (plan) ---

Plan Title=Multiple Run
Short Identifier=Multiple
Geom File=g01
Flow File=f01
Subcritical Flow
K Sum by GR= 0
Std Step Tol= 0.01
Critical Tol= 0.01
Num of Std Step Trials= 20
Max Error Tol= 0.3
Flow Tol Ratio= 0.001
Split Flow NTrial= 30
Split Flow Tol= 0.02
Split Flow Ratio= 0.02
Log Output Level= 0
Friction Slope Method= 1
Unsteady Friction Slope Method= 2
Unsteady Bridges Friction Slope Method= 1
Parabolic Critical Depth
Global Vel Dist=  1 , 1 , 1
Global Log Level= 0
CheckData=True
Encroach Param= -1, 0, 0, 0
BEGIN DESCRIPTION:
Multiple Run
END DESCRIPTION:

--- UNT 0056 IN HEWA.f01 (steady flow) ---

Flow Title=Multiple
Number of Profiles=7
Profile Names=10-year,25-year,50-year,1pct_min,100-year,1pct_plu,500-year
River Rch & RM= UNT 0056 IN HEWA,Reach-1,6068
     795    1148    1454    1349    1824    2466    2880
River Rch & RM= UNT 0056 IN HEWA,Reach-1,2031
    1182    1746    2244    2108    2851    3856    4625
Boundary for River Rch & Prof#=UNT 0056 IN HEWA,Reach-1,1
Up Type=0
Dn Type=3
Dn Slope=0.005
Boundary for River Rch & Prof#=UNT 0056 IN HEWA,Reach-1,2
Up Type=0
Dn Type=3
Dn Slope=0.005
Boundary for River Rch & Prof#=UNT 0056 IN HEWA,Reach-1,3
Up Type=0
Dn Type=3
Dn Slope=0.005
Boundary for River Rch & Prof#=UNT 0056 IN HEWA,Reach-1,4
Up Type=0
Dn Type=3
Dn Slope=0.005
Boundary for River Rch & Prof#=UNT 0056 IN HEWA,Reach-1,5
Up Type=0
Dn Type=3
Dn Slope=0.005
Boundary for River Rch & Prof#=UNT 0056 IN HEWA,Reach-1,6
Up Type=0
Dn Type=3
Dn Slope=0.005
Boundary for River Rch & Prof#=UNT 0056 IN HEWA,Reach-1,7
Up Type=0
Dn Type=3
Dn Slope=0.005

--- UNT 0056 IN HEWA.g01 (geometry) ---

Geom Title=Existing Conditions

River Reach=UNT 0056 IN HEWA,Reach-1
Reach XY= 30
      2744873.08     10088283.38      2744859.43     10088176.80
      2744728.39     10088013.80      2744751.40     10087774.94
      2744884.90     10087622.24      2744888.06     10087498.36
      2744864.48     10087450.72      2744745.67     10087370.36
      2744728.32     10087293.96      2744774.00     10087191.36
      2744847.91     10087143.53      2744932.89     10087016.14
      2744976.07     10086907.74      2744987.38     10086683.82
      2744909.35     10086324.31      2744941.66     10086205.06
      2745076.53     10085968.15      2745157.02     10085209.44
      2745120.87     10085135.03      2744906.22     10084980.28
      2744823.46     10084791.09      2744680.70     10084597.52
      2744477.77     10084354.55      2744213.07     10084106.61
      2744130.31     10083907.97      2744117.19     10083589.46
      2744075.09     10083465.14      2743967.30     10083317.26
      2743712.07     10083295.95      2743738.47     10083173.73

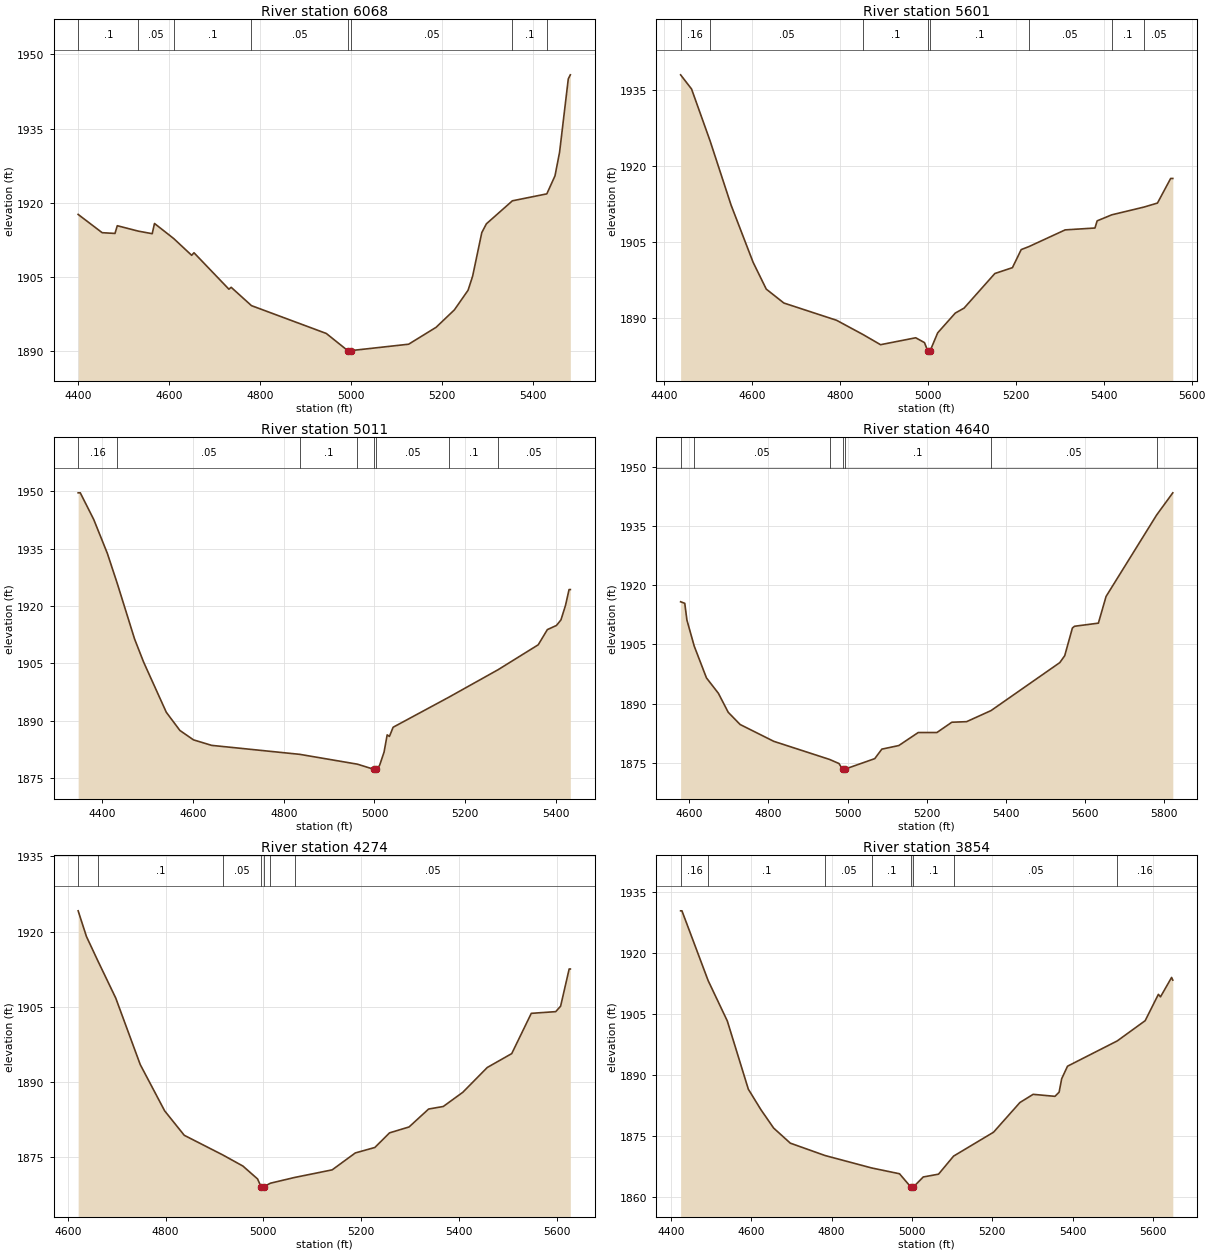
Type RM Length L Ch R = 1,6068,467,467,467
BEGIN DESCRIPTION:
UNT 0056 IN HEWA 13.0
END DESCRIPTION:
XS GIS Cut Line= 2
      2745460.98     10088128.62      2744384.92     10088258.79
#Sta/Elev= 30
  4399.4 1917.68  4452.3 1913.99  4480.5 1913.84  4485.6 1915.40  4532.1 1914.30
  4562.5 1913.79  4567.5 1915.85  4609.7 1912.82  4649.4 1909.42  4654.5 1909.94
  4731.4 1902.58  4736.4 1902.96  4781.1 1899.26  4945.9 1893.64  4993.2 1890.17
  4996.0 1889.67  4999.2 1890.17  5127.2 1891.47  5187.6 1894.88  5227.9 1898.40
  5258.1 1902.37  5268.2 1905.24  5288.3 1914.01  5298.4 1915.78  5355.7 1920.43
  5431.5 1921.83  5449.5 1925.47  5459.6 1930.23  5478.8 1945.05  5483.3 1945.87
#Mann=8,-1,0
  4399.4     0.1       0  4532.1    0.05       0  4609.7     0.1       0
  4781.1    0.05       0  4993.2   0.035       0  4999.2    0.05       0
  5355.7     0.1       0  5431.5    0.05       0
Bank Sta=4993.2,4999.2
Exp/Cntr=0.3,0.1

Type RM Length L Ch R = 1,5601,590,590,590
BEGIN DESCRIPTION:
UNT 0056 IN HEWA 12.0
END DESCRIPTION:
XS GIS Cut Line= 2
      2745313.38     10087781.40      2744193.61     10087790.08
#Sta/Elev= 30
  4437.3 1938.07  4462.2 1935.26  4504.4 1924.98  4552.2 1912.26  4602.2 1900.96
  4632.2 1895.64  4672.2 1892.89  4792.2 1889.47  4852.7 1886.63  4892.2 1884.64
  4972.2 1886.01  4992.2 1885.05  4999.2 1883.47  5002.0 1882.97  5005.2 1883.47
  5022.2 1886.99  5062.2 1890.90  5082.2 1891.88  5152.2 1898.73  5192.2 1899.89
  5212.2 1903.47  5229.2 1904.04  5312.2 1907.37  5380.0 1907.74  5385.0 1909.16
  5418.2 1910.35  5491.6 1911.89  5522.2 1912.68  5552.2 1917.55  5557.1 1917.55
#Mann=8,-1,0
  4437.3    0.16       0  4504.4    0.05       0  4852.7     0.1       0
  4999.2    0.07       0  5005.2     0.1       0  5229.2    0.05       0
  5418.2     0.1       0  5491.6    0.05       0
Bank Sta=4999.2,5005.2
Exp/Cntr=0.3,0.1

Type RM Length L Ch R = 1,5011,371,371,371
BEGIN DESCRIPTION:
UNT 0056 IN HEWA 11.0
END DESCRIPTION:
XS GIS Cut Line= 2
      2745382.80     10087356.06      2744297.77     10087312.65
#Sta/Elev= 30
  4346.3 1949.62  4351.0 1949.62  4380.7 1942.64  4410.7 1933.79  4432.9 1925.80
  4470.7 1911.41  4490.8 1905.31  4540.8 1892.20  4570.8 1887.44  4600.8 1884.98
  4640.9 1883.54  4835.3 1881.19  4962.4 1878.62  4998.2 1877.30  5000.9 1876.80
  5004.2 1877.30  5011.2 1878.26  5021.2 1881.76  5028.1 1886.29  5033.1 1885.89
  5041.2 1888.28  5164.0 1896.13  5273.0 1903.35  5361.4 1909.86  5381.5 1913.83
  5401.5 1914.91  5411.5 1916.37  5421.5 1920.15  5429.4 1924.31  5432.2 1924.31
#Mann=8,-1,0
  4346.3    0.16       0  4432.9    0.05       0  4835.3     0.1       0
  4962.4    0.05       0  4998.2   0.035       0  5004.2    0.05       0
  5164.0     0.1       0  5273.0    0.05       0
Bank Sta=4998.2,5004.2
Exp/Cntr=0.3,0.1

Type RM Length L Ch R = 1,4640,366,366,366
BEGIN DESCRIPTION:
UNT 0056 IN HEWA 10.0
END DESCRIPTION:
XS GIS Cut Line= 2
      2745313.32     10087182.43      2744151.81     10086740.36
#Sta/Elev= 30
  4578.5 1915.82  4589.0 1915.42  4594.4 1911.18  4612.8 1904.58  4643.8 1896.49
  4673.9 1892.59  4698.7 1887.77  4728.8 1884.67  4813.8 1880.40  4954.5 1875.81
  4978.4 1874.77  4987.3 1873.34  4990.0 1872.84  4993.3 1873.34  5068.7 1876.01
  5086.6 1878.42  5129.4 1879.33  5178.4 1882.63  5225.7 1882.64  5263.4 1885.25
  5300.6 1885.39  5362.3 1888.20  5536.0 1900.38  5548.4 1902.14  5567.8 1909.16
  5573.1 1909.60  5633.4 1910.39  5652.8 1917.17  5780.5 1937.84  5821.3 1943.46
#Mann=7,-1,0
  4578.5    0.16       0  4612.8    0.05       0  4954.5     0.1       0
  4987.3    0.07       0  4993.3     0.1       0  5362.3    0.05       0
  5780.5     0.1       0
Bank Sta=4987.3,4993.3
Exp/Cntr=0.3,0.1

Type RM Length L Ch R = 1,4274,420,420,420
BEGIN DESCRIPTION:
UNT 0056 IN HEWA 9.0
END DESCRIPTION:
XS GIS Cut Line= 2
      2745365.49     10086687.65      2744358.54     10086670.29
#Sta/Elev= 30
  4621.0 1924.15  4638.0 1919.03  4661.0 1914.25  4698.0 1906.75  4748.0 1893.52
  4798.0 1884.29  4838.1 1879.42  4917.2 1875.49  4958.1 1873.29  4988.1 1870.72
  4995.1 1869.19  4997.8 1868.69  5001.1 1869.19  5014.4 1869.87  5063.7 1871.01
  5140.8 1872.53  5188.1 1875.90  5228.1 1876.99  5258.1 1879.90  5298.1 1881.08
  5338.1 1884.65  5368.1 1885.16  5408.1 1887.99  5458.1 1892.93  5508.2 1895.70
  5548.2 1903.72  5598.2 1904.06  5608.2 1905.15  5625.7 1912.56  5628.1 1912.56
#Mann=7,-1,0
  4621.0    0.16       0  4661.0     0.1       0  4917.2    0.05       0
  4995.1   0.035       0  5001.1    0.05       0  5014.4     0.1       0
  5063.7    0.05       0
Bank Sta=4995.1,5001.1
Exp/Cntr=0.3,0.1

Type RM Length L Ch R = 1,3854,703,703,703
BEGIN DESCRIPTION:
UNT 0056 IN HEWA 8.0
END DESCRIPTION:
XS GIS Cut Line= 2
      2745469.65     10086444.61      2744297.80     10086088.71
#Sta/Elev= 30
  4424.3 1930.30  4427.6 1930.30  4492.8 1913.14  4540.5 1903.20  4592.8 1886.42
  4624.1 1881.38  4655.8 1876.85  4697.3 1873.14  4783.6 1870.10  4899.6 1867.04
  4969.0 1865.61  4997.3 1862.33  5000.1 1861.83  5003.3 1862.33  5028.0 1864.82
  5066.1 1865.51  5103.5 1869.95  5202.9 1875.83  5268.6 1883.14  5301.5 1885.15
  5355.7 1884.66  5366.1 1885.68  5372.5 1888.99  5387.0 1892.07  5510.7 1898.29
  5580.2 1903.27  5613.1 1909.75  5618.4 1909.14  5646.0 1913.91  5649.0 1913.25
#Mann=8,-1,0
  4424.3    0.16       0  4492.8     0.1       0  4783.6    0.05       0
  4899.6     0.1       0  4997.3    0.07       0  5003.3     0.1       0
  5103.5    0.05       0  5510.7    0.16       0
Bank Sta=4997.3,5003.3
Exp/Cntr=0.3,0.1

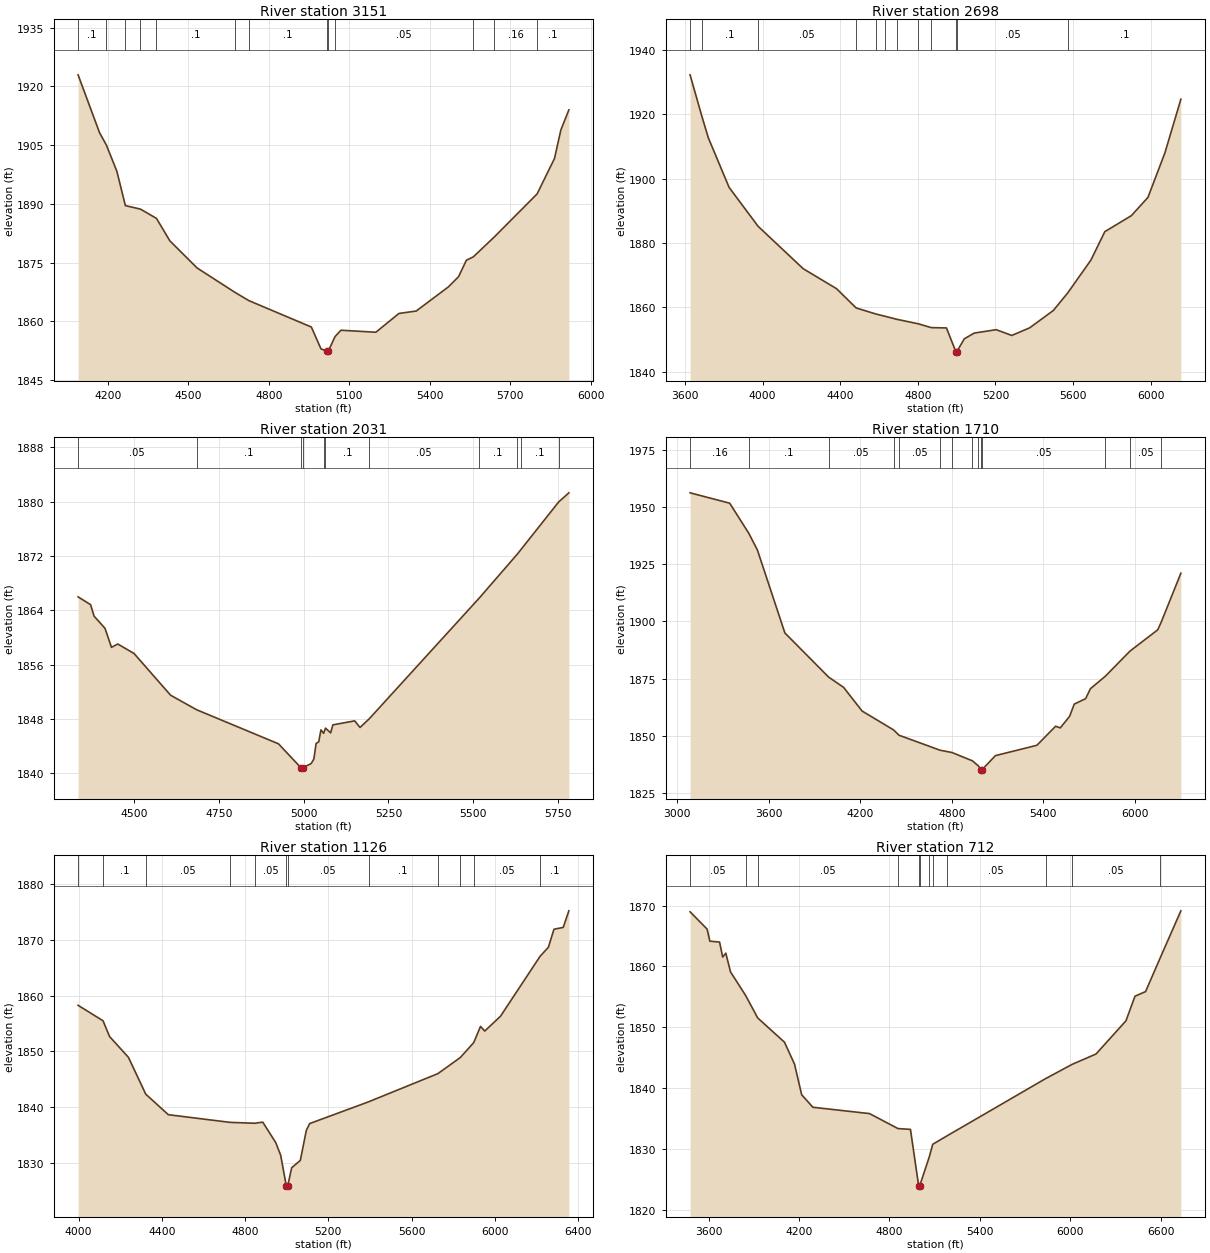
Type RM Length L Ch R = 1,3151,453,453,453
BEGIN DESCRIPTION:
UNT 0056 IN HEWA 7.0
END DESCRIPTION:
XS GIS Cut Line= 4
      2745634.53     10086297.00      2745243.92     10085628.63
      2744896.69     10085602.58      2744245.62     10085880.37
#Sta/Elev= 30
  4088.3 1922.97  4168.5 1908.16  4193.8 1905.03  4233.0 1898.31  4264.7 1889.55
  4321.0 1888.65  4380.7 1886.28  4430.5 1880.55  4532.2 1873.61  4674.2 1867.34
  4725.4 1865.26  4958.2 1858.52  4994.0 1852.95  5015.3 1852.35  5018.1 1851.85
  5021.3 1852.35  5046.6 1856.08  5068.5 1857.70  5198.8 1857.19  5284.8 1861.99
  5349.2 1862.61  5469.7 1868.80  5507.2 1871.40  5536.2 1875.58  5562.4 1876.47
  5640.4 1881.54  5800.1 1892.54  5864.9 1901.60  5888.5 1908.85  5918.5 1914.02
#Mann=13,-1,0
  4088.3     0.1       0  4193.8    0.16       0  4264.7     0.1       0
  4321.0    0.16       0  4380.7     0.1       0  4674.2    0.05       0
  4725.4     0.1       0  5015.3    0.07       0  5021.3     0.1       0
  5046.6    0.05       0  5562.4     0.1       0  5640.4    0.16       0
  5800.1     0.1       0
Bank Sta=5015.3,5021.3
Exp/Cntr=0.3,0.1

Type RM Length L Ch R = 1,2698,667,667,667
BEGIN DESCRIPTION:
UNT 0056 IN HEWA 5.0
END DESCRIPTION:
XS GIS Cut Line= 4
      2745730.01     10086323.03      2745252.60     10085151.19
      2744992.18     10085203.28      2744176.24     10085776.17
#Sta/Elev= 30
  3627.0 1932.20  3687.8 1919.32  3720.9 1912.66  3827.9 1897.26  3977.1 1885.18
  4209.3 1872.01  4381.6 1865.78  4482.2 1859.82  4584.0 1857.93  4633.0 1857.19
  4692.1 1856.28  4800.2 1854.92  4869.3 1853.70  4947.6 1853.60  4995.5 1846.28
  4998.3 1845.78  5001.5 1846.28  5039.3 1850.22  5090.3 1852.00  5203.7 1853.06
  5283.9 1851.27  5376.3 1853.64  5498.3 1859.04  5572.4 1864.50  5691.7 1874.69
  5763.2 1883.50  5900.0 1888.47  5985.3 1894.14  6072.6 1907.95  6154.9 1924.63
#Mann=12,-1,0
  3627.0    0.16       0  3687.8     0.1       0  3977.1    0.05       0
  4482.2     0.1       0  4584.0    0.05       0  4633.0     0.1       0
  4692.1    0.05       0  4800.2     0.1       0  4869.3    0.05       0
  4995.5    0.04       0  5001.5    0.05       0  5572.4     0.1       0
Bank Sta=4995.5,5001.5
Exp/Cntr=0.3,0.1

Type RM Length L Ch R = 1,2031,321,321,321
BEGIN DESCRIPTION:
Mapping XS 3a5757ae
END DESCRIPTION:
XS GIS Cut Line= 4
      2745374.47     10084511.84      2744767.07     10084651.10
      2744630.95     10084763.04      2744297.50     10085318.54
#Sta/Elev= 30
  4334.9 1865.99  4371.8 1864.84  4382.1 1863.15  4414.3 1861.36  4433.4 1858.56
  4452.0 1859.05  4500.0 1857.65  4607.8 1851.51  4684.2 1849.38  4925.9 1844.36
  4992.1 1840.84  4994.8 1840.34  4998.1 1840.84  5022.4 1841.46  5030.3 1842.13
  5036.7 1844.40  5044.6 1844.66  5051.1 1846.41  5059.0 1845.90  5064.5 1846.67
  5079.8 1845.97  5086.2 1847.15  5150.7 1847.74  5166.3 1846.77  5193.1 1848.02
  5518.4 1865.84  5629.0 1872.21  5640.2 1872.91  5752.0 1879.95  5782.2 1881.30
#Mann=11,-1,0
  4334.9    0.05       0  4684.2     0.1       0  4992.1    0.07       0
  4998.1     0.1       0  5059.0    0.05       0  5064.5     0.1       0
  5193.1    0.05       0  5518.4     0.1       0  5629.0    0.05       0
  5640.2     0.1       0  5752.0    0.05       0
Bank Sta=4992.1,4998.1
Exp/Cntr=0.3,0.1

Type RM Length L Ch R = 1,1710,584,584,584
BEGIN DESCRIPTION:
UNT 0056 IN HEWA 3.0
END DESCRIPTION:
XS GIS Cut Line= 4
      2746415.78     10084621.68      2744601.55     10084378.63
      2744297.73     10084604.32      2743950.85     10085549.57
#Sta/Elev= 30
  3085.7 1956.20  3345.3 1951.67  3470.2 1938.54  3526.9 1931.20  3706.9 1894.95
  3993.3 1875.67  4091.9 1871.14  4213.0 1860.81  4418.8 1852.58  4454.4 1850.25
  4724.2 1843.68  4801.4 1842.69  4935.7 1839.05  4975.2 1836.80  4991.3 1835.05
  4994.1 1834.55  4997.3 1835.05  5086.1 1841.32  5357.9 1845.84  5480.8 1854.17
  5511.3 1853.45  5572.3 1858.48  5602.9 1863.85  5677.5 1866.24  5708.7 1870.57
  5806.1 1876.00  5967.7 1887.00  6150.1 1896.33  6174.2 1899.91  6301.5 1921.06
#Mann=14,-1,0
  3085.7    0.16       0  3470.2     0.1       0  3993.3    0.05       0
  4418.8     0.1       0  4454.4    0.05       0  4724.2     0.1       0
  4801.4    0.05       0  4935.7     0.1       0  4975.2    0.05       0
  4991.3   0.035       0  4997.3    0.05       0  5806.1     0.1       0
  5967.7    0.05       0  6174.2     0.1       0
Bank Sta=4991.3,4997.3
Exp/Cntr=0.3,0.1

Type RM Length L Ch R = 1,1126,414,414,414
BEGIN DESCRIPTION:
UNT 0056 IN HEWA 2.0
END DESCRIPTION:
XS GIS Cut Line= 4
      2745148.43     10084083.49      2744228.29     10083961.96
      2743985.23     10084066.13      2743759.85     10085210.37
#Sta/Elev= 30
  3997.4 1858.27  4117.3 1855.49  4148.7 1852.66  4239.4 1848.92  4322.7 1842.30
  4431.1 1838.61  4727.4 1837.23  4845.9 1837.07  4885.0 1837.27  4947.6 1833.58
  4971.2 1831.31  4998.5 1825.73  5001.2 1825.23  5004.5 1825.73  5023.8 1829.06
  5065.5 1830.40  5094.5 1835.80  5110.3 1837.01  5393.4 1840.92  5726.8 1845.99
  5834.4 1848.88  5898.8 1851.56  5931.6 1854.48  5951.9 1853.64  6027.7 1856.31
  6218.5 1867.11  6257.7 1868.69  6284.5 1871.94  6329.0 1872.27  6356.2 1875.25
#Mann=12,-1,0
  3997.4    0.05       0  4117.3     0.1       0  4322.7    0.05       0
  4727.4     0.1       0  4845.9    0.05       0  4998.5   0.035       0
  5004.5    0.05       0  5393.4     0.1       0  5726.8    0.05       0
  5834.4     0.1       0  5898.8    0.05       0  6218.5     0.1       0
Bank Sta=4998.5,5004.5
Exp/Cntr=0.3,0.1

Type RM Length L Ch R = 1,712,574,574,574
BEGIN DESCRIPTION:
Mapping XS 0426cea3
END DESCRIPTION:
XS GIS Cut Line= 4
      2745577.23     10083924.17      2744186.62     10083543.96
      2743806.41     10083762.71      2743733.49     10085137.68
#Sta/Elev= 30
  3477.3 1868.97  3590.1 1866.14  3608.6 1864.15  3673.0 1864.01  3693.7 1861.55
  3714.5 1862.19  3745.6 1859.12  3846.4 1855.23  3926.1 1851.56  4103.9 1847.58
  4170.6 1843.97  4217.8 1838.97  4292.0 1836.91  4668.2 1835.87  4857.4 1833.41
  4939.9 1833.28  4994.6 1823.98  4997.3 1823.48  5000.6 1823.98  5064.5 1828.75
  5087.8 1830.84  5181.4 1832.20  5837.0 1841.61  6013.3 1843.95  6171.6 1845.65
  6370.0 1851.09  6430.1 1855.13  6500.2 1855.88  6598.4 1861.47  6734.5 1869.13
#Mann=12,-1,0
  3477.3    0.05       0  3846.4     0.1       0  3926.1    0.05       0
  4857.4     0.1       0  4994.6    0.07       0  5000.6     0.1       0
  5064.5    0.05       0  5087.8     0.1       0  5181.4    0.05       0
  5837.0     0.1       0  6013.3    0.05       0  6598.4     0.1       0
Bank Sta=4994.6,5000.6
Exp/Cntr=0.3,0.1

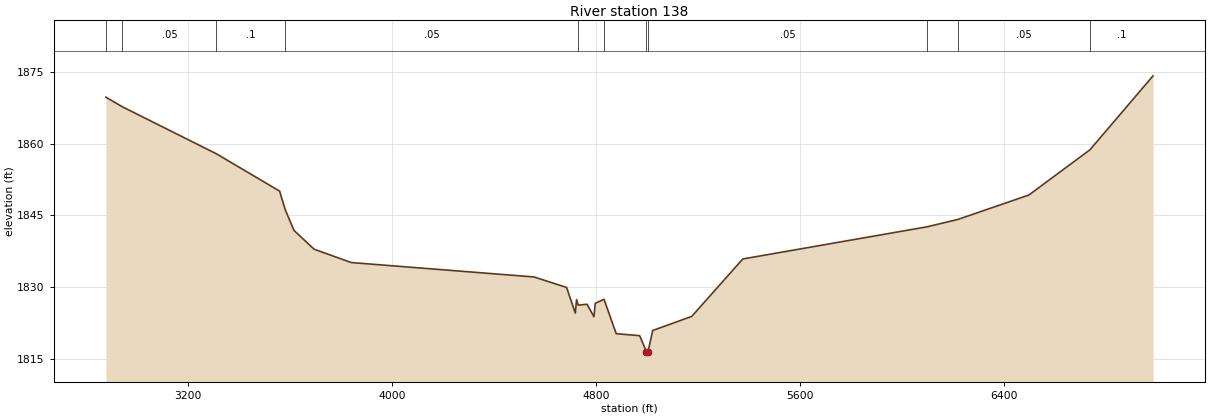
Type RM Length L Ch R = 1,138,0,0,0
BEGIN DESCRIPTION:
UNT 0056 IN HEWA 1.0
END DESCRIPTION:
XS GIS Cut Line= 4
      2745743.94     10083788.76      2743806.41     10083241.88
      2743608.49     10083361.67      2743707.39     10085219.87
#Sta/Elev= 30
  2879.5 1869.77  2943.4 1867.77  3313.1 1857.89  3560.6 1850.08  3582.4 1846.20
  3616.8 1841.85  3695.7 1837.91  3841.5 1835.11  4558.1 1832.09  4685.7 1829.89
  4719.7 1824.53  4724.9 1827.35  4731.2 1826.19  4765.9 1826.37  4792.9 1823.75
  4798.1 1826.58  4832.5 1827.40  4880.2 1820.21  4972.1 1819.78  4998.9 1816.42
  5001.7 1815.92  5004.9 1816.42  5023.3 1820.87  5176.2 1823.82  5376.5 1835.86
  6097.9 1842.59  6220.1 1844.15  6498.1 1849.26  6737.3 1858.73  6984.9 1874.24
#Mann=11,-1,0
  2879.5     0.1       0  2943.4    0.05       0  3313.1     0.1       0
  3582.4    0.05       0  4731.2    0.16       0  4832.5    0.05       0
  4998.9   0.035       0  5004.9    0.05       0  6097.9     0.1       0
  6220.1    0.05       0  6737.3     0.1       0
Bank Sta=4998.9,5004.9
Exp/Cntr=0.3,0.1

Chan Stop Cuts=-1