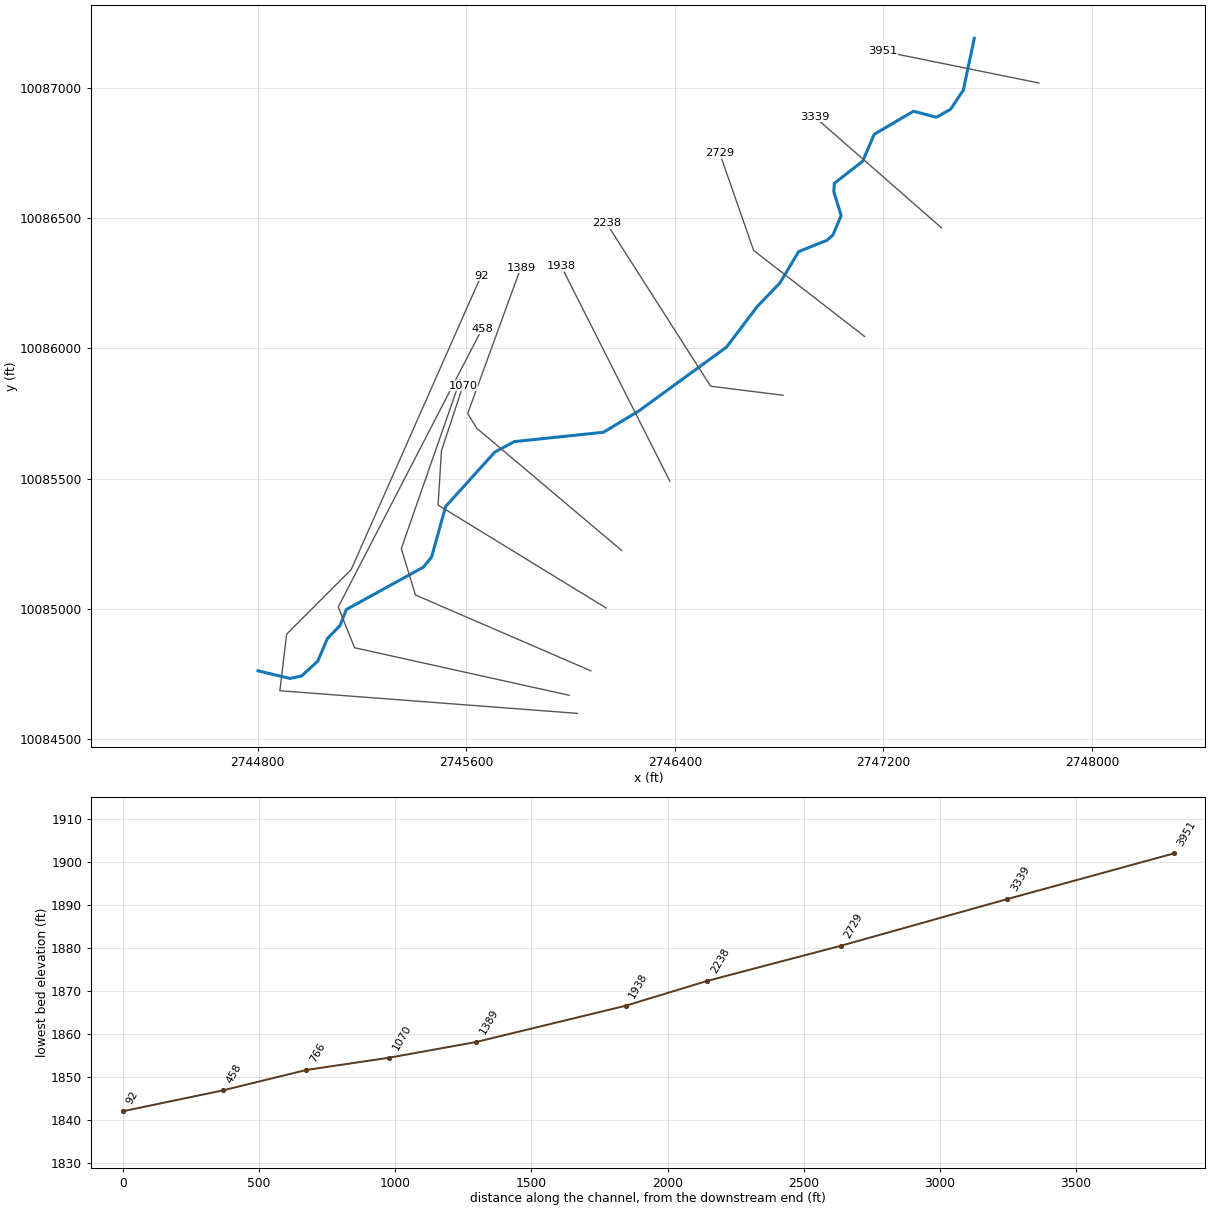
--- UNT 0057 IN HEWA.prj (project) ---

Proj Title=UNT 0057 IN HEWA Base Level Engineering
Current Plan=p01
Default Exp/Contr=0.3,0.1
English Units
Geom File=g01
Flow File=f01
Plan File=p01
BEGIN DESCRIPTION:
UNT 0057 IN HEWA
END DESCRIPTION:

--- UNT 0057 IN HEWA.p01 (plan) ---

Plan Title=Multiple Run
Short Identifier=Multiple
Geom File=g01
Flow File=f01
Subcritical Flow
K Sum by GR= 0
Std Step Tol= 0.01
Critical Tol= 0.01
Num of Std Step Trials= 20
Max Error Tol= 0.3
Flow Tol Ratio= 0.001
Split Flow NTrial= 30
Split Flow Tol= 0.02
Split Flow Ratio= 0.02
Log Output Level= 0
Friction Slope Method= 1
Unsteady Friction Slope Method= 2
Unsteady Bridges Friction Slope Method= 1
Parabolic Critical Depth
Global Vel Dist=  1 , 1 , 1
Global Log Level= 0
CheckData=True
Encroach Param= -1, 0, 0, 0
BEGIN DESCRIPTION:
Multiple Run
END DESCRIPTION:

--- UNT 0057 IN HEWA.f01 (steady flow) ---

Flow Title=Multiple
Number of Profiles=7
Profile Names=10-year,25-year,50-year,1pct_min,100-year,1pct_plu,500-year
River Rch & RM= UNT 0057 IN HEWA,Reach-1,3951
     566     803    1004     920    1244    1683    1919
Boundary for River Rch & Prof#=UNT 0057 IN HEWA,Reach-1,1
Up Type=0
Dn Type=3
Dn Slope=0.005
Boundary for River Rch & Prof#=UNT 0057 IN HEWA,Reach-1,2
Up Type=0
Dn Type=3
Dn Slope=0.005
Boundary for River Rch & Prof#=UNT 0057 IN HEWA,Reach-1,3
Up Type=0
Dn Type=3
Dn Slope=0.005
Boundary for River Rch & Prof#=UNT 0057 IN HEWA,Reach-1,4
Up Type=0
Dn Type=3
Dn Slope=0.005
Boundary for River Rch & Prof#=UNT 0057 IN HEWA,Reach-1,5
Up Type=0
Dn Type=3
Dn Slope=0.005
Boundary for River Rch & Prof#=UNT 0057 IN HEWA,Reach-1,6
Up Type=0
Dn Type=3
Dn Slope=0.005
Boundary for River Rch & Prof#=UNT 0057 IN HEWA,Reach-1,7
Up Type=0
Dn Type=3
Dn Slope=0.005

--- UNT 0057 IN HEWA.g01 (geometry) ---

Geom Title=Existing Conditions

River Reach=UNT 0057 IN HEWA,Reach-1
Reach XY= 30
      2747548.69     10087188.66      2747506.46     10086989.56
      2747457.38     10086916.20      2747403.00     10086885.92
      2747315.63     10086909.13      2747164.96     10086820.58
      2747120.80     10086717.76      2747011.71     10086632.28
      2747009.96     10086599.82      2747038.04     10086508.88
      2747006.48     10086434.38      2746983.54     10086413.91
      2746875.08     10086370.66      2746803.55     10086250.89
      2746716.41     10086160.20      2746598.34     10086004.32
      2746261.08     10085758.79      2746126.16     10085677.68
      2745784.25     10085641.84      2745709.38     10085601.52
      2745520.84     10085392.75      2745467.09     10085199.21
      2745435.45     10085160.29      2745139.87     10084997.65
      2745116.12     10084936.68      2745067.25     10084886.36
      2745030.53     10084799.72      2744968.45     10084742.98
      2744924.04     10084733.33      2744801.40     10084762.52

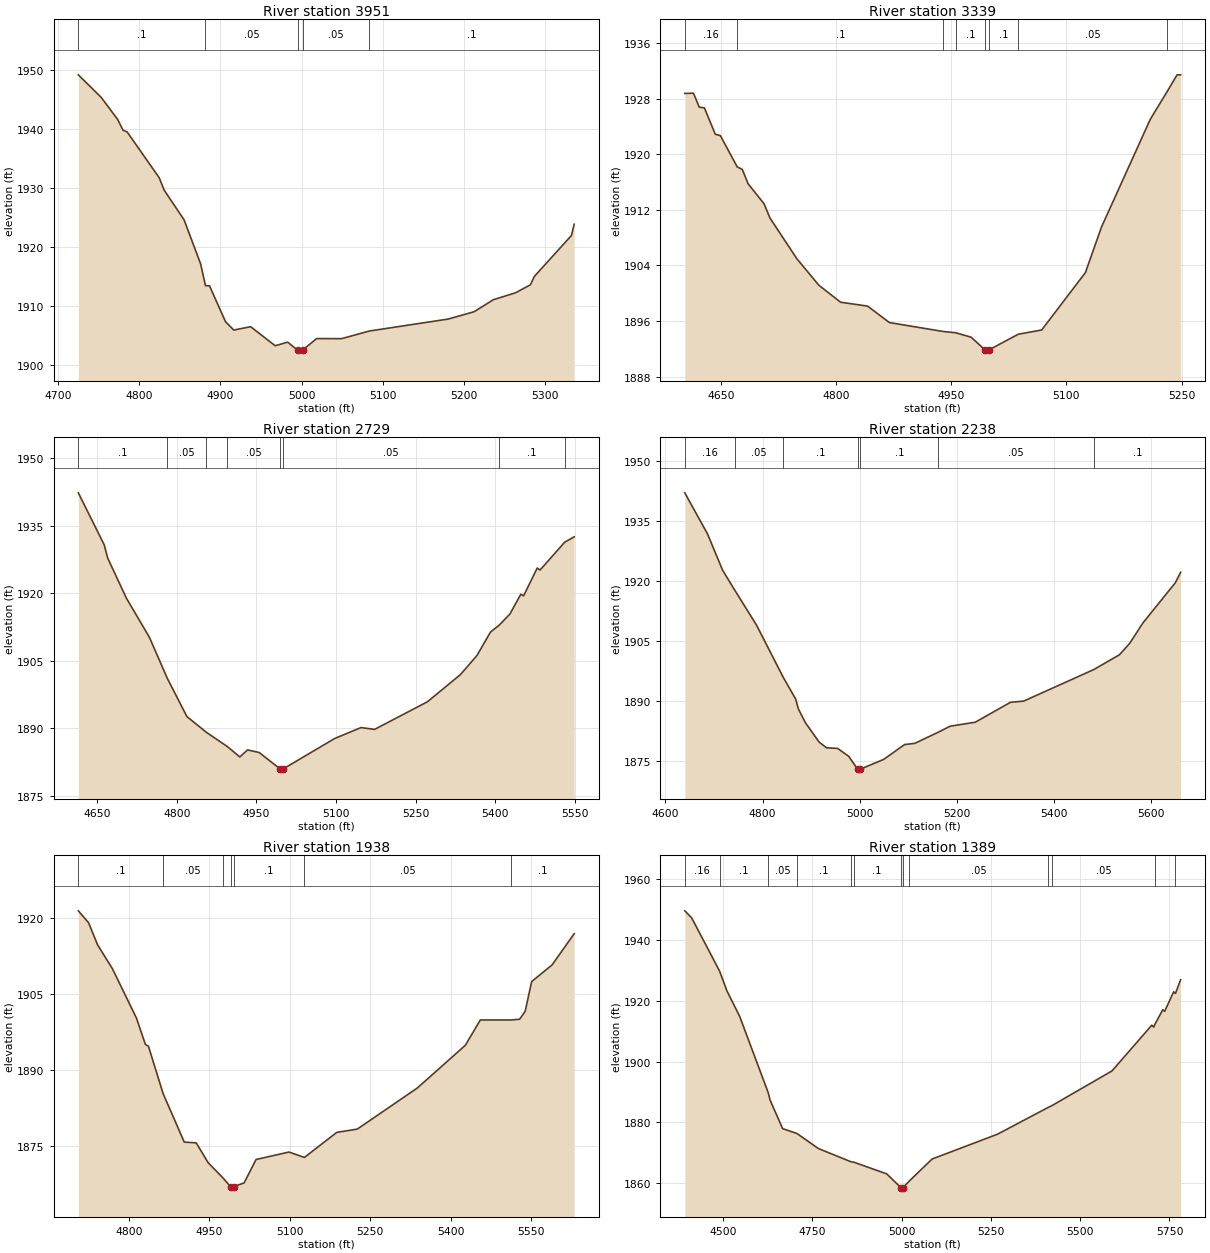
Type RM Length L Ch R = 1,3951,612,612,612
BEGIN DESCRIPTION:
UNT 0057 IN HEWA 7.0
END DESCRIPTION:
XS GIS Cut Line= 2
      2747796.03     10087017.51      2747197.82     10087138.88
#Sta/Elev= 30
  4725.0 1949.18  4753.1 1945.37  4773.5 1941.60  4780.0 1939.80  4785.1 1939.50
  4824.6 1931.73  4830.7 1929.63  4855.2 1924.60  4875.6 1917.12  4881.5 1913.45
  4886.5 1913.42  4906.2 1907.33  4916.4 1905.92  4937.1 1906.49  4967.4 1903.26
  4982.7 1903.87  4995.0 1902.51  4997.8 1902.01  5001.0 1902.51  5018.4 1904.48
  5049.0 1904.46  5083.4 1905.76  5180.2 1907.78  5212.3 1909.03  5235.9 1911.06
  5263.3 1912.24  5281.5 1913.59  5286.6 1915.04  5332.1 1921.96  5335.4 1923.86
#Mann=5,-1,0
  4725.0     0.1       0  4881.5    0.05       0  4995.0   0.035       0
  5001.0    0.05       0  5083.4     0.1       0
Bank Sta=4995,5001
Exp/Cntr=0.3,0.1

Type RM Length L Ch R = 1,3339,610,610,610
BEGIN DESCRIPTION:
UNT 0057 IN HEWA 6.0
END DESCRIPTION:
XS GIS Cut Line= 2
      2747422.71     10086461.98      2746936.62     10086887.31
#Sta/Elev= 30
  4602.9 1928.77  4614.2 1928.81  4621.8 1926.79  4628.4 1926.70  4642.6 1922.90
  4649.3 1922.69  4671.2 1918.19  4677.8 1917.83  4685.4 1915.76  4706.2 1912.88
  4713.8 1910.84  4748.9 1904.97  4777.4 1901.17  4805.9 1898.71  4841.0 1898.15
  4869.5 1895.78  4939.8 1894.49  4955.8 1894.31  4975.8 1893.68  4993.7 1891.88
  4996.4 1891.38  4999.7 1891.88  5037.3 1894.10  5067.8 1894.71  5124.8 1902.98
  5145.7 1909.53  5209.3 1925.05  5230.5 1928.90  5244.2 1931.45  5248.8 1931.45
#Mann=8,-1,0
  4602.9    0.16       0  4671.2     0.1       0  4939.8    0.05       0
  4955.8     0.1       0  4993.7    0.07       0  4999.7     0.1       0
  5037.3    0.05       0  5230.5     0.1       0
Bank Sta=4993.7,4999.7
Exp/Cntr=0.3,0.1

Type RM Length L Ch R = 1,2729,491,491,491
BEGIN DESCRIPTION:
UNT 0057 IN HEWA 5.0
END DESCRIPTION:
XS GIS Cut Line= 3
      2747127.57     10086045.31      2746702.25     10086375.15
      2746572.02     10086748.46
#Sta/Elev= 30
  4614.8 1942.33  4663.6 1930.77  4670.0 1927.87  4705.3 1918.94  4748.7 1910.23
  4782.4 1901.12  4819.3 1892.64  4856.0 1889.14  4894.9 1886.03  4918.9 1883.68
  4933.4 1885.24  4955.3 1884.67  4994.7 1881.03  4997.4 1880.53  5000.7 1881.03
  5097.2 1887.76  5147.0 1890.20  5172.7 1889.80  5272.0 1895.92  5334.2 1901.96
  5365.3 1906.19  5391.0 1911.43  5407.1 1912.93  5427.4 1915.41  5447.9 1919.80
  5453.2 1919.46  5478.9 1925.63  5484.2 1925.19  5530.6 1931.37  5548.4 1932.56
#Mann=8,-1,0
  4614.8     0.1       0  4782.4    0.05       0  4856.0     0.1       0
  4894.9    0.05       0  4994.7   0.035       0  5000.7    0.05       0
  5407.1     0.1       0  5530.6    0.16       0
Bank Sta=4994.7,5000.7
Exp/Cntr=0.3,0.1

Type RM Length L Ch R = 1,2238,300,300,300
BEGIN DESCRIPTION:
UNT 0057 IN HEWA 4.0
END DESCRIPTION:
XS GIS Cut Line= 3
      2746815.05     10085819.60      2746537.32     10085854.32
      2746138.21     10086479.02
#Sta/Elev= 30
  4639.8 1942.02  4686.7 1931.71  4717.7 1922.64  4742.8 1917.64  4787.5 1908.91
  4842.8 1895.78  4868.1 1890.41  4873.9 1887.88  4888.3 1884.46  4916.6 1879.60
  4931.8 1878.19  4954.6 1878.04  4977.5 1876.05  4995.6 1872.85  4998.4 1872.35
  5001.6 1872.85  5049.5 1875.29  5092.5 1879.00  5113.7 1879.31  5161.9 1882.10
  5186.4 1883.60  5238.0 1884.59  5310.6 1889.58  5337.9 1889.88  5482.4 1897.79
  5535.0 1901.48  5556.1 1904.34  5583.5 1909.47  5650.0 1919.49  5661.0 1922.12
#Mann=7,-1,0
  4639.8    0.16       0  4742.8    0.05       0  4842.8     0.1       0
  4995.6    0.07       0  5001.6     0.1       0  5161.9    0.05       0
  5482.4     0.1       0
Bank Sta=4995.6,5001.6
Exp/Cntr=0.3,0.1

Type RM Length L Ch R = 1,1938,549,549,549
BEGIN DESCRIPTION:
UNT 0057 IN HEWA 3.0
END DESCRIPTION:
XS GIS Cut Line= 2
      2746381.09     10085489.70      2745964.39     10086314.41
#Sta/Elev= 30
  4705.9 1921.35  4725.0 1919.01  4741.7 1914.67  4769.6 1909.92  4814.2 1900.24
  4830.9 1895.04  4836.5 1894.71  4863.9 1885.37  4903.3 1875.82  4925.6 1875.67
  4947.9 1871.75  4975.6 1868.75  4989.5 1867.06  4992.3 1866.56  4995.5 1867.06
  5014.8 1867.78  5037.1 1872.39  5098.4 1873.86  5127.2 1872.80  5187.5 1877.73
  5225.8 1878.38  5337.8 1886.48  5427.1 1894.88  5455.0 1899.86  5511.6 1899.86
  5528.3 1900.01  5538.6 1901.56  5550.7 1907.42  5588.8 1910.71  5629.9 1916.84
#Mann=7,-1,0
  4705.9     0.1       0  4863.9    0.05       0  4975.6     0.1       0
  4989.5    0.07       0  4995.5     0.1       0  5127.2    0.05       0
  5511.6     0.1       0
Bank Sta=4989.5,4995.5
Exp/Cntr=0.3,0.1

Type RM Length L Ch R = 1,1389,319,319,319
BEGIN DESCRIPTION:
UNT 0057 IN HEWA 2.0
END DESCRIPTION:
XS GIS Cut Line= 4
      2746195.80     10085224.43      2745640.26     10085693.16
      2745605.54     10085749.59      2745809.40     10086309.10
#Sta/Elev= 30
  4392.6 1949.50  4411.8 1947.20  4490.0 1929.72  4510.6 1923.22  4546.1 1914.90
  4626.2 1889.81  4631.5 1887.35  4666.6 1877.98  4706.7 1876.39  4766.7 1871.45
  4857.9 1867.11  4865.3 1866.99  4957.9 1863.14  4997.8 1858.62  5000.5 1858.12
  5003.8 1858.62  5021.4 1860.79  5085.3 1868.01  5268.6 1876.17  5411.0 1884.99
  5421.4 1885.58  5588.9 1896.92  5700.6 1911.97  5705.9 1911.32  5709.3 1912.26
  5731.1 1917.01  5736.5 1916.50  5761.7 1922.91  5766.8 1922.38  5781.2 1926.88
#Mann=13,-1,0
  4392.6    0.16       0  4490.0     0.1       0  4626.2    0.05       0
  4706.7     0.1       0  4857.9    0.05       0  4865.3     0.1       0
  4997.8    0.07       0  5003.8     0.1       0  5021.4    0.05       0
  5411.0     0.1       0  5421.4    0.05       0  5709.3    0.16       0
  5766.8    0.05       0
Bank Sta=4997.8,5003.8
Exp/Cntr=0.3,0.1

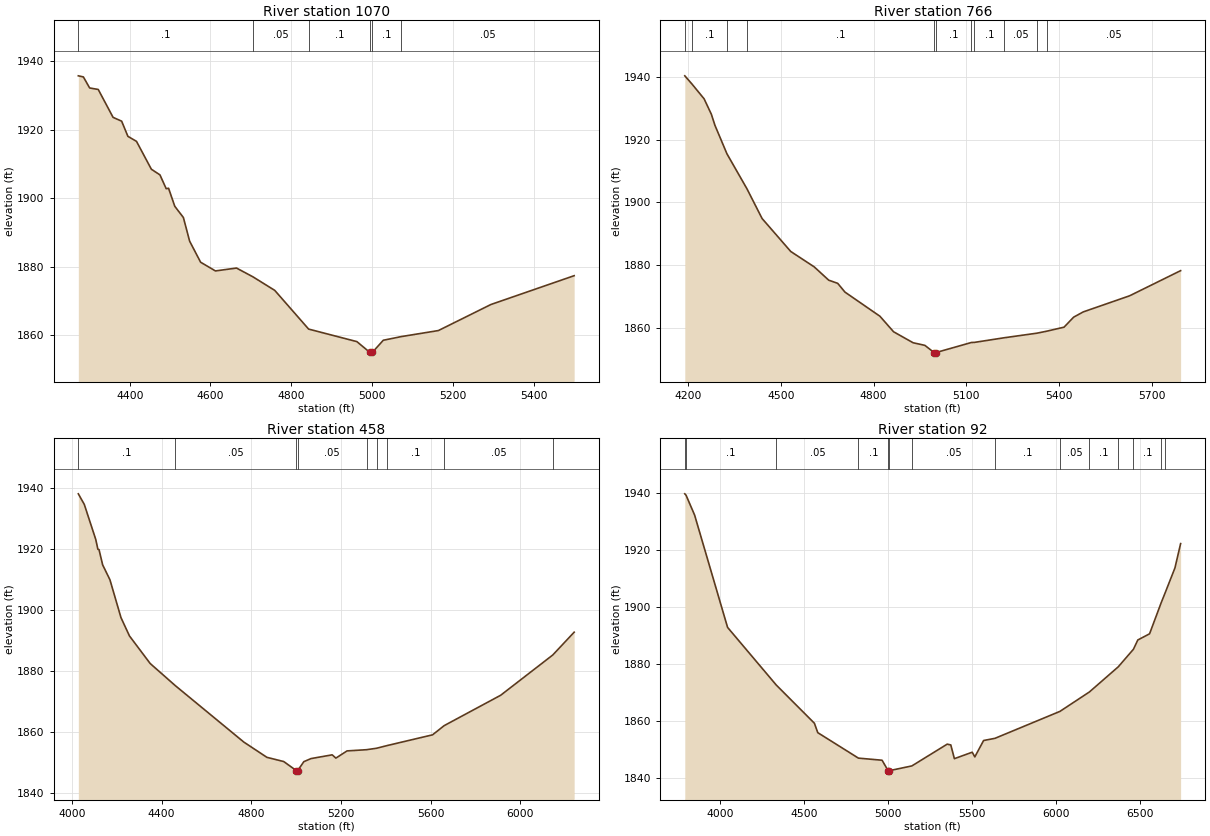
Type RM Length L Ch R = 1,1070,304,304,304
BEGIN DESCRIPTION:
Mapping XS 14059e87
END DESCRIPTION:
XS GIS Cut Line= 4
      2746136.47     10085003.60      2745491.94     10085398.56
      2745504.96     10085606.90      2745587.43     10085856.46
#Sta/Elev= 30
  4272.8 1935.69  4285.3 1935.37  4300.8 1932.15  4322.1 1931.71  4358.8 1923.57
  4380.1 1922.45  4395.5 1918.03  4416.8 1916.56  4453.6 1908.43  4474.9 1906.78
  4490.3 1902.75  4496.2 1902.88  4511.6 1897.61  4532.9 1894.34  4548.3 1887.45
  4575.5 1881.30  4612.2 1878.75  4664.4 1879.59  4704.9 1877.04  4759.1 1873.07
  4842.9 1861.78  4962.4 1858.12  4994.6 1854.97  4997.4 1854.47  5000.6 1854.97
  5027.8 1858.52  5072.5 1859.59  5164.2 1861.35  5294.2 1868.95  5500.3 1877.36
#Mann=6,-1,0
  4272.8     0.1       0  4704.9    0.05       0  4842.9     0.1       0
  4994.6    0.07       0  5000.6     0.1       0  5072.5    0.05       0
Bank Sta=4994.6,5000.6
Exp/Cntr=0.3,0.1

Type RM Length L Ch R = 1,766,308,308,308
BEGIN DESCRIPTION:
Mapping XS 91cf8303
END DESCRIPTION:
XS GIS Cut Line= 4
      2746077.90     10084762.70      2745405.14     10085053.51
      2745350.88     10085231.46      2745576.57     10085878.15
#Sta/Elev= 30
  4189.4 1940.41  4212.3 1937.83  4251.9 1933.07  4275.3 1928.16  4286.8 1924.65
  4325.7 1915.54  4390.8 1904.31  4439.4 1894.89  4532.1 1884.37  4608.0 1879.46
  4655.0 1875.21  4684.0 1874.21  4707.5 1871.41  4820.6 1863.71  4864.8 1858.75
  4927.9 1855.25  4966.0 1854.42  4995.8 1852.12  4998.5 1851.62  5001.8 1852.12
  5116.8 1855.34  5125.9 1855.36  5222.6 1856.84  5328.3 1858.30  5360.8 1858.95
  5416.2 1860.22  5447.2 1863.41  5478.3 1865.09  5628.3 1870.23  5793.3 1878.25
#Mann=11,-1,0
  4189.4    0.16       0  4212.3     0.1       0  4325.7    0.16       0
  4390.8     0.1       0  4995.8    0.07       0  5001.8     0.1       0
  5116.8    0.05       0  5125.9     0.1       0  5222.6    0.05       0
  5328.3     0.1       0  5360.8    0.05       0
Bank Sta=4995.8,5001.8
Exp/Cntr=0.3,0.1

Type RM Length L Ch R = 1,458,366,366,366
BEGIN DESCRIPTION:
Mapping XS 68b91ac4
END DESCRIPTION:
XS GIS Cut Line= 4
      2745994.39     10084668.91      2745171.47     10084851.21
      2745108.97     10085007.46      2745661.07     10086075.20
#Sta/Elev= 30
  4028.0 1937.96  4054.6 1934.50  4105.8 1923.02  4115.3 1919.81  4120.4 1919.70
  4136.5 1914.72  4169.1 1909.82  4218.4 1897.43  4256.3 1891.43  4348.6 1882.42
  4461.3 1875.14  4766.7 1856.69  4869.8 1851.69  4944.9 1850.31  5001.2 1847.35
  5003.9 1846.85  5007.2 1847.35  5034.5 1850.27  5066.9 1851.29  5161.1 1852.51
  5177.6 1851.44  5227.6 1853.80  5314.6 1854.19  5359.4 1854.67  5407.3 1855.56
  5609.1 1859.06  5661.2 1862.08  5913.1 1872.01  6145.6 1885.19  6241.2 1892.66
#Mann=9,-1,0
  4028.0     0.1       0  4461.3    0.05       0  5001.2    0.04       0
  5007.2    0.05       0  5314.6     0.1       0  5359.4    0.05       0
  5407.3     0.1       0  5661.2    0.05       0  6145.6     0.1       0
Bank Sta=5001.2,5007.2
Exp/Cntr=0.3,0.1

Type RM Length L Ch R = 1,92,0,0,0
BEGIN DESCRIPTION:
UNT 0057 IN HEWA 1.0
END DESCRIPTION:
XS GIS Cut Line= 5
      2746026.55     10084599.41      2744885.06     10084686.22
      2744911.10     10084903.23      2745158.49     10085150.63
      2745657.56     10086278.95
#Sta/Elev= 30
  3792.6 1939.83  3800.2 1939.33  3850.9 1932.37  4046.9 1892.88  4336.3 1872.62
  4562.9 1859.19  4583.0 1855.88  4824.6 1846.93  4965.1 1846.19  5001.2 1842.51
  5003.9 1842.01  5007.2 1842.51  5142.2 1844.19  5352.4 1851.85  5373.7 1851.56
  5394.9 1846.74  5500.9 1849.01  5516.4 1847.37  5568.5 1853.12  5636.2 1853.89
  6022.0 1863.35  6197.5 1870.19  6369.2 1879.04  6459.3 1885.21  6485.1 1888.46
  6555.0 1890.63  6624.2 1901.57  6645.5 1904.71  6705.7 1913.76  6739.6 1922.34
#Mann=14,-1,0
  3792.6    0.16       0  3800.2     0.1       0  4336.3    0.05       0
  4824.6     0.1       0  5001.2    0.07       0  5007.2     0.1       0
  5142.2    0.05       0  5636.2     0.1       0  6022.0    0.05       0
  6197.5     0.1       0  6369.2    0.05       0  6459.3     0.1       0
  6624.2    0.16       0  6645.5     0.1       0
Bank Sta=5001.2,5007.2
Exp/Cntr=0.3,0.1

Chan Stop Cuts=-1