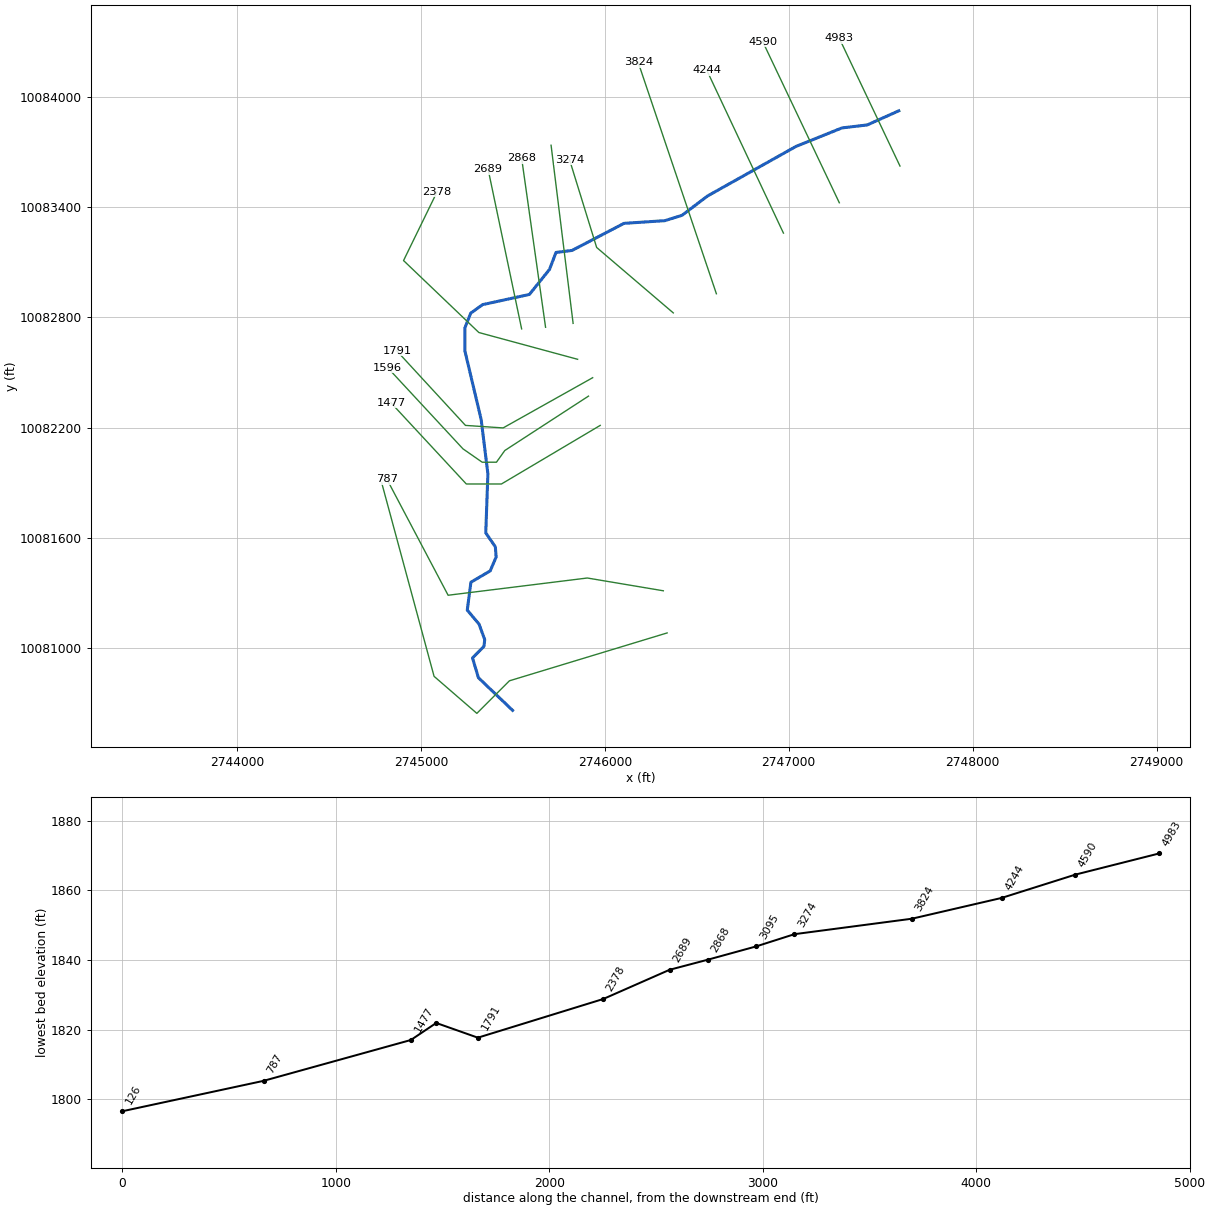
--- UNT 0058 IN HEWA.prj (project) ---

Proj Title=UNT 0058 IN HEWA Base Level Engineering
Current Plan=p01
Default Exp/Contr=0.3,0.1
English Units
Geom File=g01
Flow File=f01
Plan File=p01
BEGIN DESCRIPTION:
UNT 0058 IN HEWA
END DESCRIPTION:

--- UNT 0058 IN HEWA.p01 (plan) ---

Plan Title=Multiple Run
Short Identifier=Multiple
Geom File=g01
Flow File=f01
Subcritical Flow
K Sum by GR= 0
Std Step Tol= 0.01
Critical Tol= 0.01
Num of Std Step Trials= 20
Max Error Tol= 0.3
Flow Tol Ratio= 0.001
Split Flow NTrial= 30
Split Flow Tol= 0.02
Split Flow Ratio= 0.02
Log Output Level= 0
Friction Slope Method= 1
Unsteady Friction Slope Method= 2
Unsteady Bridges Friction Slope Method= 1
Parabolic Critical Depth
Global Vel Dist=  1 , 1 , 1
Global Log Level= 0
CheckData=True
Encroach Param= -1, 0, 0, 0
BEGIN DESCRIPTION:
Multiple Run
END DESCRIPTION:

--- UNT 0058 IN HEWA.f01 (steady flow) ---

Flow Title=Multiple
Number of Profiles=7
Profile Names=10-year,25-year,50-year,1pct_min,100-year,1pct_plu,500-year
River Rch & RM= UNT 0058 IN HEWA,Reach-1,4983
     765    1103    1394    1291    1746    2362    2750
Boundary for River Rch & Prof#=UNT 0058 IN HEWA,Reach-1,1
Up Type=0
Dn Type=3
Dn Slope=0.005
Boundary for River Rch & Prof#=UNT 0058 IN HEWA,Reach-1,2
Up Type=0
Dn Type=3
Dn Slope=0.005
Boundary for River Rch & Prof#=UNT 0058 IN HEWA,Reach-1,3
Up Type=0
Dn Type=3
Dn Slope=0.005
Boundary for River Rch & Prof#=UNT 0058 IN HEWA,Reach-1,4
Up Type=0
Dn Type=3
Dn Slope=0.005
Boundary for River Rch & Prof#=UNT 0058 IN HEWA,Reach-1,5
Up Type=0
Dn Type=3
Dn Slope=0.005
Boundary for River Rch & Prof#=UNT 0058 IN HEWA,Reach-1,6
Up Type=0
Dn Type=3
Dn Slope=0.005
Boundary for River Rch & Prof#=UNT 0058 IN HEWA,Reach-1,7
Up Type=0
Dn Type=3
Dn Slope=0.005

--- UNT 0058 IN HEWA.g01 (geometry) ---

Geom Title=Existing Conditions

River Reach=UNT 0058 IN HEWA,Reach-1
Reach XY= 30
      2747598.47     10083923.73      2747427.15     10083846.91
      2747289.71     10083830.73      2747039.93     10083730.21
      2746559.56     10083461.08      2746419.52     10083355.28
      2746326.55     10083326.38      2746104.50     10083311.75
      2745821.98     10083164.50      2745734.44     10083153.46
      2745699.52     10083061.46      2745590.05     10082925.16
      2745335.36     10082869.70      2745270.71     10082823.04
      2745239.47     10082743.64      2745239.23     10082618.57
      2745327.73     10082245.07      2745364.36     10081949.69
      2745352.73     10081628.81      2745405.01     10081552.26
      2745409.12     10081496.93      2745376.88     10081421.79
      2745271.96     10081360.23      2745252.18     10081208.54
      2745316.05     10081132.79      2745347.16     10081048.22
      2745342.97     10081011.58      2745280.67     10080948.44
      2745312.91     10080840.80      2745498.47     10080663.73

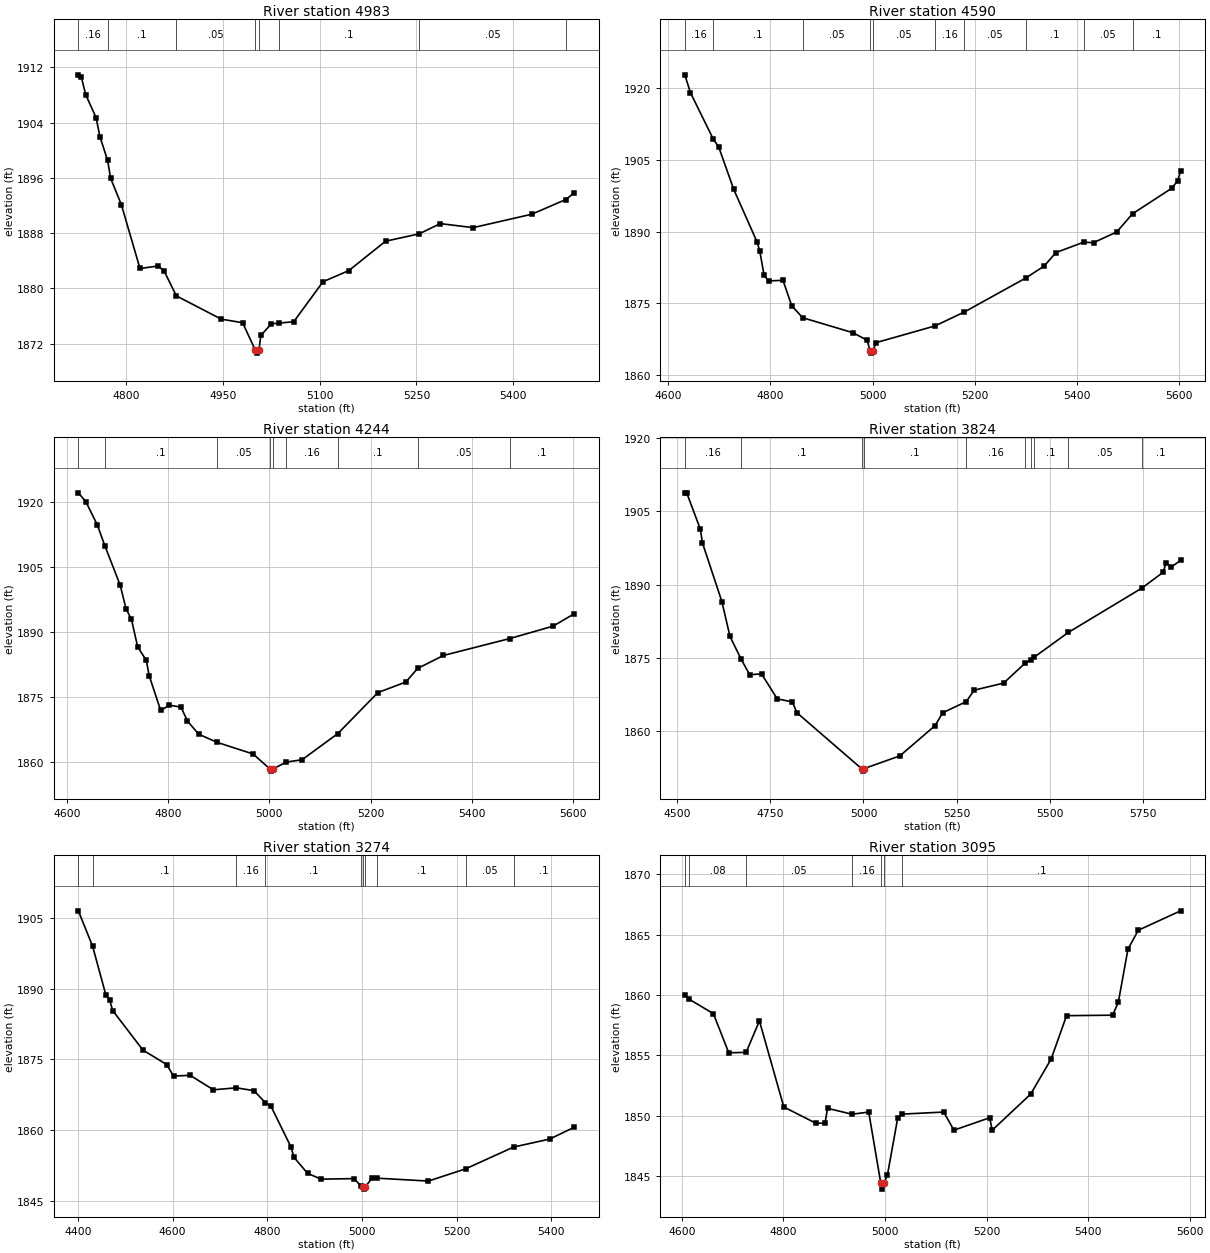
Type RM Length L Ch R = 1,4983,393,393,393
BEGIN DESCRIPTION:
UNT 0058 IN HEWA 7.0
END DESCRIPTION:
XS GIS Cut Line= 2
      2747605.02     10083623.43      2747275.16     10084317.87
#Sta/Elev= 30
  4725.8 1910.90  4730.5 1910.57  4737.2 1908.03  4753.3 1904.72  4759.3 1901.94
  4771.1 1898.56  4776.0 1895.91  4792.6 1892.10  4821.4 1882.89  4849.7 1883.25
  4859.0 1882.49  4877.8 1878.93  4947.5 1875.56  4980.5 1875.05  4999.9 1871.15
  5002.7 1870.65  5005.9 1871.15  5008.8 1873.20  5025.0 1874.89  5036.5 1874.99
  5059.8 1875.19  5105.2 1880.98  5145.1 1882.58  5202.2 1886.84  5254.3 1887.90
  5287.0 1889.38  5338.0 1888.80  5428.9 1890.74  5481.5 1892.86  5494.6 1893.82
#Mann=8,-1,0
  4725.8    0.16       0  4771.1     0.1       0  4877.8    0.05       0
  4999.9   0.035       0  5005.9    0.05       0  5036.5     0.1       0
  5254.3    0.05       0  5481.5     0.1       0
Bank Sta=4999.9,5005.9
Exp/Cntr=0.3,0.1

Type RM Length L Ch R = 1,4590,346,346,346
BEGIN DESCRIPTION:
UNT 0058 IN HEWA 6.0
END DESCRIPTION:
XS GIS Cut Line= 2
      2747275.17     10083423.76      2746858.93     10084299.58
#Sta/Elev= 30
  4632.8 1922.86  4643.8 1919.13  4688.4 1909.41  4699.2 1907.72  4728.4 1898.89
  4773.9 1887.90  4779.4 1885.98  4787.8 1880.92  4796.6 1879.69  4824.8 1879.81
  4842.0 1874.48  4863.2 1871.98  4961.2 1868.85  4989.4 1867.27  4995.1 1865.06
  4997.9 1864.56  5001.1 1865.06  5006.6 1866.75  5121.9 1870.25  5179.4 1873.17
  5299.9 1880.31  5335.8 1882.81  5358.5 1885.62  5412.6 1887.79  5432.2 1887.70
  5477.6 1889.95  5508.5 1893.76  5584.9 1899.08  5596.7 1900.66  5602.5 1902.74
#Mann=10,-1,0
  4632.8    0.16       0  4688.4     0.1       0  4863.2    0.05       0
  4995.1   0.035       0  5001.1    0.05       0  5121.9    0.16       0
  5179.4    0.05       0  5299.9     0.1       0  5412.6    0.05       0
  5508.5     0.1       0
Bank Sta=4995.1,5001.1
Exp/Cntr=0.3,0.1

Type RM Length L Ch R = 1,4244,420,420,420
BEGIN DESCRIPTION:
UNT 0058 IN HEWA 5.0
END DESCRIPTION:
XS GIS Cut Line= 2
      2746971.35     10083258.83      2746554.66     10084144.29
#Sta/Elev= 30
  4622.9 1922.13  4637.6 1920.10  4660.4 1914.71  4675.3 1909.89  4705.7 1900.73
  4717.1 1895.32  4727.8 1892.89  4739.9 1886.59  4757.1 1883.41  4762.7 1879.91
  4785.4 1871.87  4802.7 1873.08  4825.5 1872.64  4838.3 1869.41  4860.4 1866.38
  4897.4 1864.47  4967.8 1861.81  5001.1 1858.35  5003.8 1857.85  5007.1 1858.35
  5033.3 1859.94  5064.5 1860.48  5135.2 1866.54  5214.1 1875.99  5269.3 1878.43
  5292.4 1881.56  5343.6 1884.57  5474.4 1888.47  5559.8 1891.33  5601.5 1894.19
#Mann=9,-1,0
  4622.9    0.16       0  4675.3     0.1       0  4897.4    0.05       0
  5001.1   0.035       0  5007.1    0.05       0  5033.3    0.16       0
  5135.2     0.1       0  5292.4    0.05       0  5474.4     0.1       0
Bank Sta=5001.1,5007.1
Exp/Cntr=0.3,0.1

Type RM Length L Ch R = 1,3824,550,550,550
BEGIN DESCRIPTION:
UNT 0058 IN HEWA 4.0
END DESCRIPTION:
XS GIS Cut Line= 2
      2746606.75     10082929.00      2746181.41     10084187.67
#Sta/Elev= 30
  4521.3 1908.73  4526.4 1908.73  4563.0 1901.29  4568.5 1898.53  4620.6 1886.53
  4642.4 1879.39  4672.3 1874.74  4695.2 1871.58  4726.9 1871.74  4769.1 1866.64
  4809.4 1866.02  4821.9 1863.80  4995.1 1852.38  4997.8 1851.88  5001.1 1852.38
  5097.7 1855.00  5192.0 1861.18  5212.4 1863.81  5275.1 1866.06  5296.9 1868.42
  5375.5 1869.86  5432.7 1873.90  5448.0 1874.61  5456.9 1875.12  5549.1 1880.22
  5745.7 1889.25  5803.5 1892.52  5810.5 1894.43  5824.6 1893.57  5849.9 1894.93
#Mann=10,-1,0
  4521.3    0.16       0  4672.3     0.1       0  4995.1    0.07       0
  5001.1     0.1       0  5275.1    0.16       0  5432.7     0.1       0
  5448.0    0.05       0  5456.9     0.1       0  5549.1    0.05       0
  5745.7     0.1       0
Bank Sta=4995.1,5001.1
Exp/Cntr=0.3,0.1

Type RM Length L Ch R = 1,3274,179,179,179
BEGIN DESCRIPTION:
UNT 0058 IN HEWA 3.0
END DESCRIPTION:
XS GIS Cut Line= 3
      2746372.42     10082824.78      2745955.72     10083180.71
      2745808.16     10083658.11
#Sta/Elev= 30
  4400.7 1906.54  4430.8 1899.04  4459.0 1888.63  4466.7 1887.67  4473.3 1885.36
  4537.4 1876.95  4587.5 1873.90  4601.8 1871.45  4636.9 1871.61  4686.3 1868.53
  4734.3 1868.96  4771.9 1868.35  4795.8 1865.80  4807.1 1865.17  4849.9 1856.42
  4856.5 1854.17  4885.0 1850.80  4913.6 1849.56  4983.3 1849.67  4998.4 1848.05
  5001.2 1847.94  5004.0 1847.44  5007.2 1847.94  5022.0 1849.87  5031.6 1849.77
  5140.3 1849.15  5219.1 1851.75  5320.3 1856.37  5396.6 1858.07  5448.4 1860.57
#Mann=10,-1,0
  4400.7    0.16       0  4430.8     0.1       0  4734.3    0.16       0
  4795.8     0.1       0  4998.4    0.16       0  5001.2    0.07       0
  5007.2    0.16       0  5031.6     0.1       0  5219.1    0.05       0
  5320.3     0.1       0
Bank Sta=5001.2,5007.2
Exp/Cntr=0.3,0.1

Type RM Length L Ch R = 1,3095,227,227,227
BEGIN DESCRIPTION:
Mapping XS 2b6d3dc6
END DESCRIPTION:
XS GIS Cut Line= 2
      2745827.71     10082767.90      2745707.93     10083736.62
#Sta/Elev= 30
  4605.8 1860.02  4614.4 1859.65  4662.1 1858.46  4692.3 1855.22  4726.5 1855.25
  4752.7 1857.86  4800.7 1850.73  4863.6 1849.39  4881.8 1849.38  4886.8 1850.62
  4935.1 1850.13  4967.9 1850.31  4991.6 1844.43  4994.3 1843.93  4997.6 1844.43
  5004.6 1845.08  5024.8 1849.78  5033.6 1850.14  5115.5 1850.31  5135.6 1848.81
  5206.0 1849.84  5211.0 1848.81  5286.8 1851.80  5327.1 1854.71  5357.3 1858.29
  5448.0 1858.33  5459.2 1859.39  5478.2 1863.79  5498.4 1865.36  5581.9 1866.97
#Mann=7,-1,0
  4605.8    0.05       0  4614.4    0.08       0  4726.5    0.05       0
  4935.1    0.16       0  4991.6    0.07       0  4997.6    0.16       0
  5033.6     0.1       0
Bank Sta=4991.6,4997.6
Exp/Cntr=0.3,0.1

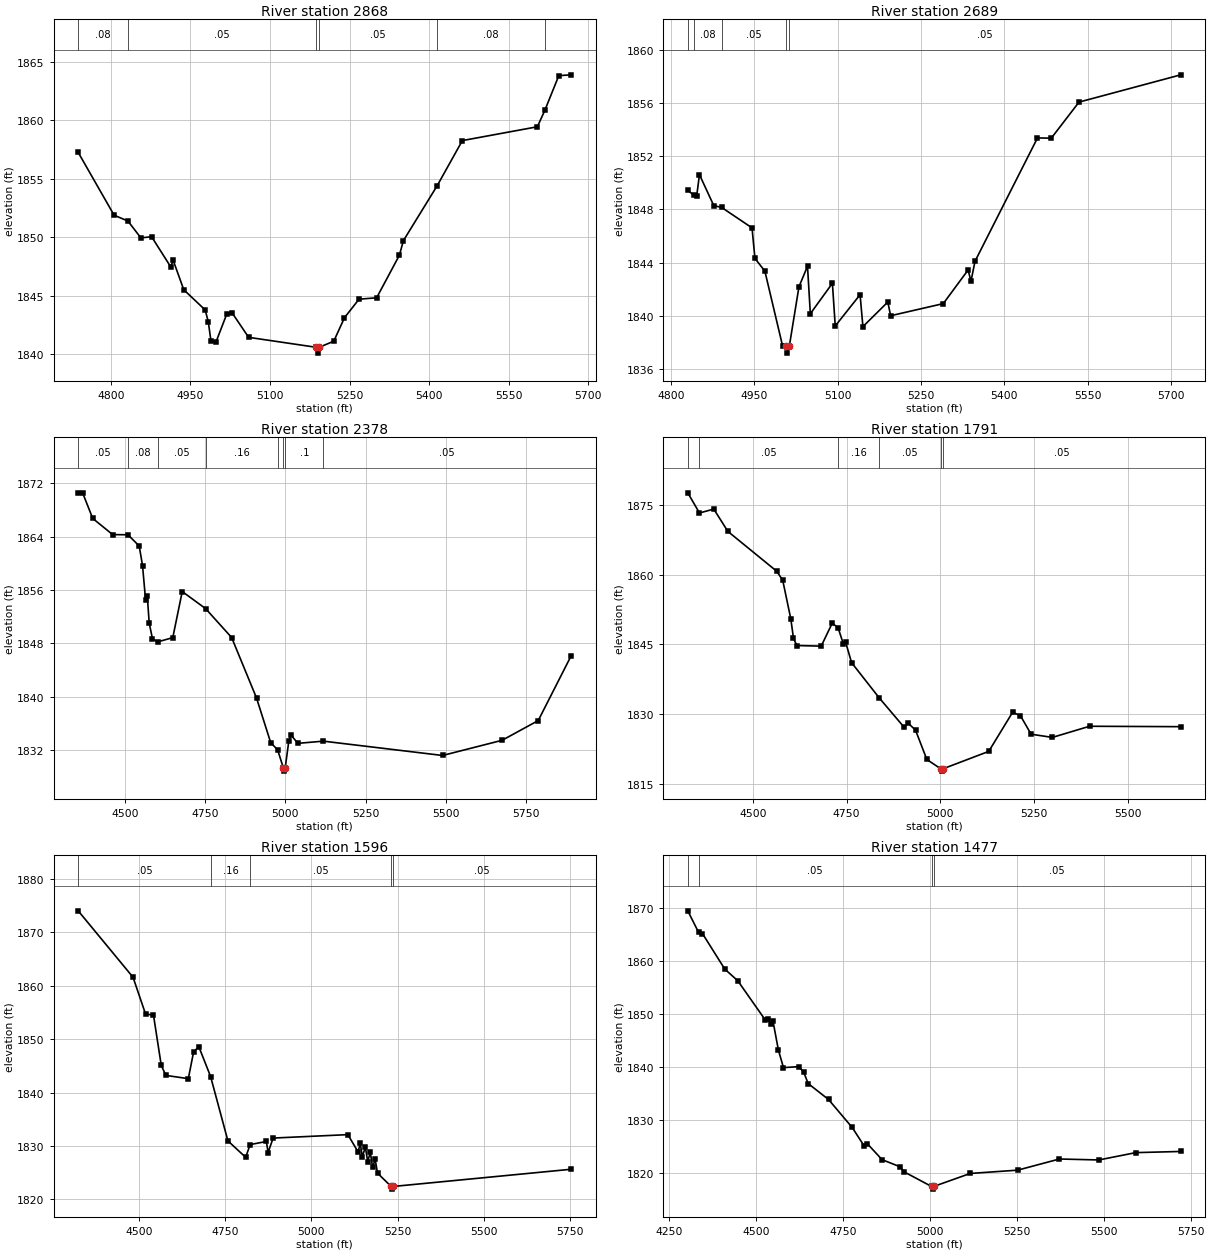
Type RM Length L Ch R = 1,2868,179,179,179
BEGIN DESCRIPTION:
Mapping XS 64fe91c0
END DESCRIPTION:
XS GIS Cut Line= 2
      2745677.94     10082746.71      2745547.73     10083666.85
#Sta/Elev= 30
  4738.4 1857.26  4806.1 1851.89  4832.2 1851.39  4856.6 1849.95  4876.8 1850.05
  4912.6 1847.49  4917.6 1848.02  4937.4 1845.52  4977.8 1843.79  4983.6 1842.79
  4988.7 1841.13  4998.0 1841.03  5018.2 1843.41  5028.3 1843.56  5059.7 1841.45
  5186.9 1840.60  5189.6 1840.10  5192.9 1840.60  5220.2 1841.12  5240.4 1843.13
  5267.8 1844.71  5301.0 1844.83  5343.9 1848.47  5351.5 1849.72  5415.1 1854.41
  5462.6 1858.27  5604.0 1859.45  5618.1 1860.86  5644.4 1863.82  5667.7 1863.89
#Mann=6,-1,0
  4738.4    0.08       0  4832.2    0.05       0  5186.9    0.04       0
  5192.9    0.05       0  5415.1    0.08       0  5618.1    0.05       0
Bank Sta=5186.9,5192.9
Exp/Cntr=0.3,0.1

Type RM Length L Ch R = 1,2689,311,311,311
BEGIN DESCRIPTION:
Mapping XS 8a0243a3
END DESCRIPTION:
XS GIS Cut Line= 2
      2745547.74     10082737.97      2745365.45     10083606.03
#Sta/Elev= 30
  4830.6 1849.43  4841.7 1849.06  4846.5 1848.97  4851.6 1850.61  4877.4 1848.28
  4891.4 1848.15  4946.2 1846.61  4951.4 1844.32  4969.3 1843.36  5001.2 1837.73
  5007.2 1837.70  5009.9 1837.20  5013.2 1837.70  5030.6 1842.18  5046.0 1843.73
  5051.1 1840.16  5090.8 1842.45  5095.9 1839.24  5140.6 1841.59  5145.7 1839.19
  5190.5 1841.04  5195.6 1840.01  5290.3 1840.92  5335.0 1843.45  5340.1 1842.60
  5347.4 1844.10  5459.8 1853.37  5484.6 1853.35  5534.5 1856.06  5717.6 1858.11
#Mann=5,-1,0
  4830.6    0.05       0  4841.7    0.08       0  4891.4    0.05       0
  5007.2    0.04       0  5013.2    0.05       0
Bank Sta=5007.2,5013.2
Exp/Cntr=0.3,0.1

Type RM Length L Ch R = 1,2378,587,587,587
BEGIN DESCRIPTION:
UNT 0058 IN HEWA 2.0
END DESCRIPTION:
XS GIS Cut Line= 4
      2745852.20     10082572.53      2745315.26     10082718.14
      2744905.72     10083109.48      2745087.76     10083482.66
#Sta/Elev= 30
  4353.6 1870.58  4367.8 1870.53  4398.9 1866.74  4461.1 1864.31  4509.1 1864.28
  4544.0 1862.59  4554.3 1859.66  4563.9 1854.49  4569.1 1855.15  4575.1 1851.04
  4585.4 1848.65  4602.1 1848.21  4648.7 1848.84  4678.2 1855.76  4751.0 1853.20
  4832.3 1848.86  4909.9 1839.79  4954.1 1833.09  4976.0 1831.98  4993.5 1829.30
  4996.3 1828.80  4999.5 1829.30  5010.7 1833.32  5017.6 1834.21  5039.0 1832.97
  5118.4 1833.30  5490.4 1831.15  5676.2 1833.43  5788.8 1836.39  5891.6 1846.12
#Mann=8,-1,0
  4353.6    0.05       0  4509.1    0.08       0  4602.1    0.05       0
  4751.0    0.16       0  4976.0     0.1       0  4993.5    0.07       0
  4999.5     0.1       0  5118.4    0.05       0
Bank Sta=4993.5,4999.5
Exp/Cntr=0.3,0.1

Type RM Length L Ch R = 1,1791,195,195,195
BEGIN DESCRIPTION:
Mapping XS 0481a142
END DESCRIPTION:
XS GIS Cut Line= 4
      2745934.16     10082472.44      2745447.22     10082199.39
      2745242.45     10082213.04      2744869.30     10082618.06
#Sta/Elev= 30
  4326.7 1877.61  4357.8 1873.27  4396.0 1874.11  4433.6 1869.30  4563.7 1860.73
  4579.7 1858.81  4601.4 1850.44  4608.4 1846.32  4617.3 1844.73  4682.4 1844.60
  4711.6 1849.53  4727.3 1848.58  4741.7 1845.01  4747.4 1845.47  4763.4 1841.04
  4837.7 1833.39  4903.8 1827.10  4913.8 1828.04  4933.8 1826.52  4963.9 1820.21
  5001.0 1818.19  5003.7 1817.69  5007.0 1818.19  5129.0 1821.94  5192.6 1830.36
  5213.5 1829.62  5241.9 1825.64  5298.6 1824.95  5397.8 1827.35  5640.9 1827.26
#Mann=6,-1,0
  4326.7     0.1       0  4357.8    0.05       0  4727.3    0.16       0
  4837.7    0.05       0  5001.0   0.035       0  5007.0    0.05       0
Bank Sta=5001,5007
Exp/Cntr=0.3,0.1

Type RM Length L Ch R = 1,1596,119,119,119
BEGIN DESCRIPTION:
Mapping XS 39203164
END DESCRIPTION:
XS GIS Cut Line= 6
      2745911.37     10082372.31      2745456.32     10082076.53
      2745410.82     10082012.82      2745333.46     10082012.82
      2745228.80     10082085.63      2744819.25     10082527.04
#Sta/Elev= 30
  4324.7 1874.02  4483.6 1861.58  4519.8 1854.70  4542.8 1854.50  4565.3 1845.10
  4578.6 1843.21  4643.7 1842.60  4658.8 1847.55  4674.0 1848.61  4708.3 1842.99
  4758.4 1830.95  4809.8 1827.88  4822.8 1830.26  4869.9 1830.84  4874.7 1828.77
  4889.4 1831.48  5105.9 1832.12  5135.6 1828.87  5141.7 1830.51  5147.7 1828.01
  5156.6 1829.76  5163.4 1827.07  5170.8 1828.82  5177.6 1826.01  5184.9 1827.52
  5191.8 1824.91  5231.3 1822.42  5234.0 1821.92  5237.3 1822.42  5752.7 1825.64
#Mann=5,-1,0
  4324.7    0.05       0  4708.3    0.16       0  4822.8    0.05       0
  5231.3   0.035       0  5237.3    0.05       0
Bank Sta=5231.3,5237.3
Exp/Cntr=0.3,0.1

Type RM Length L Ch R = 1,1477,690,690,690
BEGIN DESCRIPTION:
Mapping XS a8856732
END DESCRIPTION:
XS GIS Cut Line= 4
      2745975.10     10082213.06      2745438.12     10081894.51
      2745247.00     10081894.51      2744837.46     10082335.91
#Sta/Elev= 30
  4303.5 1869.40  4334.5 1865.35  4345.7 1865.12  4410.0 1858.42  4447.1 1856.25
  4526.9 1848.80  4532.8 1849.11  4542.6 1848.03  4548.4 1848.67  4564.0 1843.21
  4578.6 1839.89  4622.5 1840.07  4636.8 1839.04  4649.7 1836.89  4708.2 1833.89
  4776.3 1828.62  4811.2 1825.09  4819.3 1825.60  4862.1 1822.57  4914.8 1821.20
  4924.7 1820.30  5004.5 1817.52  5007.3 1817.02  5010.5 1817.52  5115.7 1819.97
  5252.0 1820.59  5372.2 1822.69  5485.6 1822.51  5591.6 1823.89  5721.1 1824.11
#Mann=4,-1,0
  4303.5     0.1       0  4334.5    0.05       0  5004.5   0.035       0
  5010.5    0.05       0
Bank Sta=5004.5,5010.5
Exp/Cntr=0.3,0.1

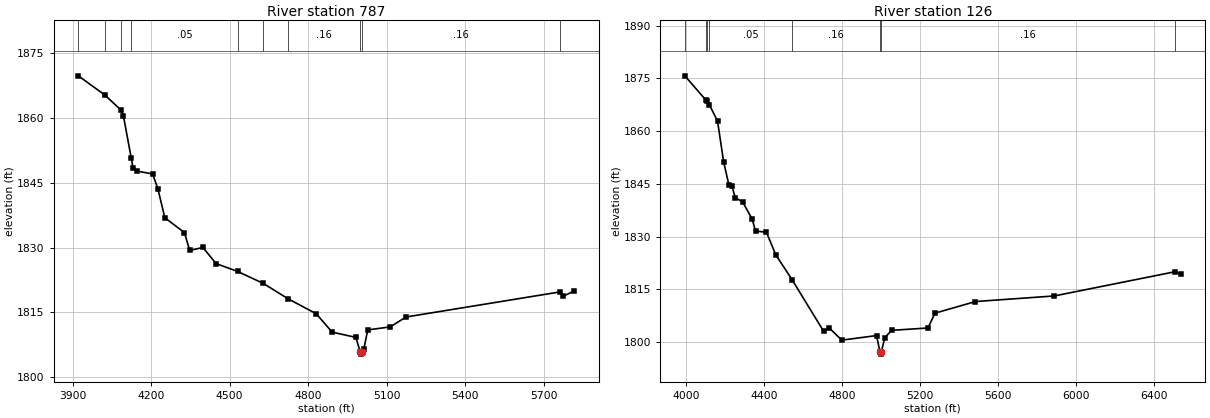
Type RM Length L Ch R = 1,787,661,661,661
BEGIN DESCRIPTION:
Mapping XS 791e1d7b
END DESCRIPTION:
XS GIS Cut Line= 4
      2746318.20     10081313.76      2745905.02     10081383.20
      2745148.08     10081289.45      2744815.43     10081920.10
#Sta/Elev= 30
  3921.7 1869.82  4023.2 1865.36  4083.7 1861.94  4093.8 1860.59  4124.0 1850.71
  4131.0 1848.37  4144.5 1847.74  4205.4 1847.07  4225.6 1843.65  4252.2 1836.91
  4327.0 1833.47  4347.3 1829.34  4397.7 1830.01  4448.0 1826.28  4530.2 1824.46
  4628.8 1821.67  4721.5 1818.17  4830.9 1814.64  4891.4 1810.39  4982.1 1809.16
  4999.2 1805.78  5002.0 1805.28  5005.2 1805.78  5012.3 1806.39  5027.7 1810.89
  5113.6 1811.60  5174.0 1813.89  5760.7 1819.69  5773.7 1818.69  5816.4 1819.90
#Mann=10,-1,0
  3921.7    0.16       0  4023.2     0.1       0  4083.7    0.16       0
  4124.0    0.05       0  4530.2    0.16       0  4628.8     0.1       0
  4721.5    0.16       0  4999.2    0.07       0  5005.2    0.16       0
  5760.7    0.05       0
Bank Sta=4999.2,5005.2
Exp/Cntr=0.3,0.1

Type RM Length L Ch R = 1,126,0,0,0
BEGIN DESCRIPTION:
UNT 0058 IN HEWA 1.0
END DESCRIPTION:
XS GIS Cut Line= 5
      2746339.03     10081084.58      2745481.41     10080824.17
      2745304.33     10080647.09      2745071.69     10080848.48
      2744787.21     10081899.65
#Sta/Elev= 30
  3995.2 1875.73  4102.5 1868.88  4108.9 1868.51  4120.4 1867.56  4163.0 1862.90
  4194.4 1851.27  4221.2 1844.71  4236.2 1844.45  4254.1 1841.11  4292.2 1839.81
  4340.7 1834.99  4357.9 1831.56  4413.8 1831.24  4461.8 1824.81  4545.3 1817.75
  4707.7 1803.02  4735.3 1804.04  4800.5 1800.53  4978.7 1801.83  4996.9 1797.05
  4999.7 1796.55  5002.9 1797.05  5021.2 1801.27  5056.5 1803.32  5242.5 1803.99
  5278.6 1808.21  5486.2 1811.51  5890.2 1813.10  6509.5 1819.99  6538.6 1819.36
#Mann=8,-1,0
  3995.2     0.1       0  4102.5    0.16       0  4108.9     0.1       0
  4120.4    0.05       0  4545.3    0.16       0  4996.9    0.07       0
  5002.9    0.16       0  6509.5     0.1       0
Bank Sta=4996.9,5002.9
Exp/Cntr=0.3,0.1

Chan Stop Cuts=-1