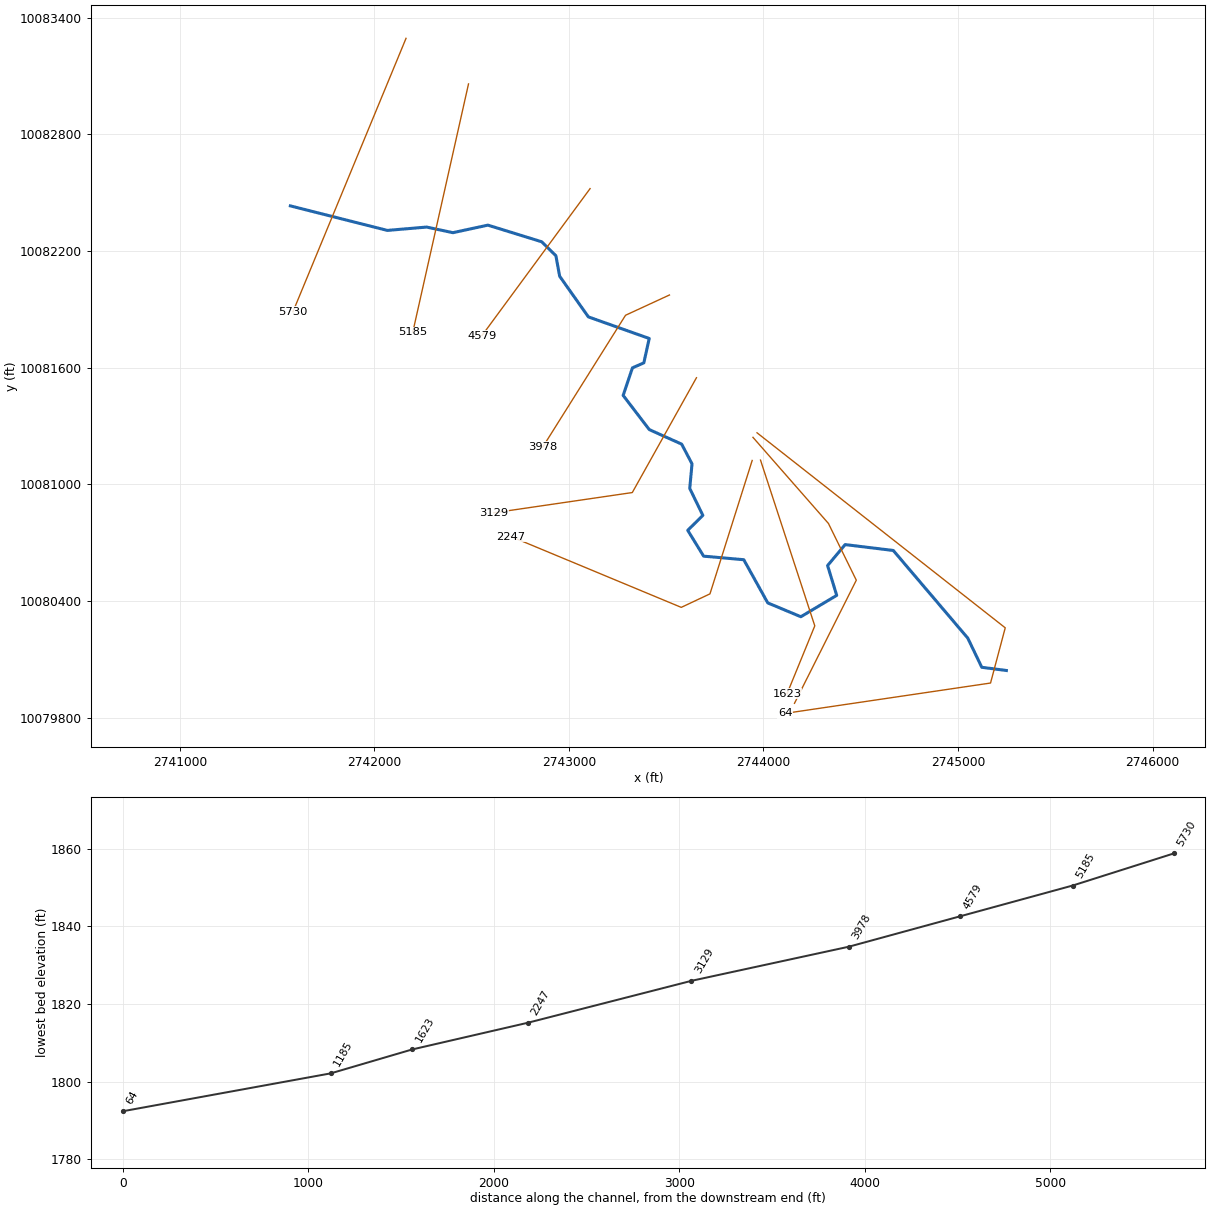
--- UNT 0059 IN HEWA.prj (project) ---

Proj Title=UNT 0059 IN HEWA Base Level Engineering
Current Plan=p01
Default Exp/Contr=0.3,0.1
English Units
Geom File=g01
Flow File=f01
Plan File=p01
BEGIN DESCRIPTION:
UNT 0059 IN HEWA
END DESCRIPTION:

--- UNT 0059 IN HEWA.p01 (plan) ---

Plan Title=Multiple Run
Short Identifier=Multiple
Geom File=g01
Flow File=f01
Subcritical Flow
K Sum by GR= 0
Std Step Tol= 0.01
Critical Tol= 0.01
Num of Std Step Trials= 20
Max Error Tol= 0.3
Flow Tol Ratio= 0.001
Split Flow NTrial= 30
Split Flow Tol= 0.02
Split Flow Ratio= 0.02
Log Output Level= 0
Friction Slope Method= 1
Unsteady Friction Slope Method= 2
Unsteady Bridges Friction Slope Method= 1
Parabolic Critical Depth
Global Vel Dist=  1 , 1 , 1
Global Log Level= 0
CheckData=True
Encroach Param= -1, 0, 0, 0
BEGIN DESCRIPTION:
Multiple Run
END DESCRIPTION:

--- UNT 0059 IN HEWA.f01 (steady flow) ---

Flow Title=Multiple
Number of Profiles=7
Profile Names=10-year,25-year,50-year,1pct_min,100-year,1pct_plu,500-year
River Rch & RM= UNT 0059 IN HEWA,Reach-1,5730
     632     899    1127    1036    1401    1894    2170
River Rch & RM= UNT 0059 IN HEWA,Reach-1,1623
     845    1223    1551    1439    1946    2631    3076
Boundary for River Rch & Prof#=UNT 0059 IN HEWA,Reach-1,1
Up Type=0
Dn Type=3
Dn Slope=0.005
Boundary for River Rch & Prof#=UNT 0059 IN HEWA,Reach-1,2
Up Type=0
Dn Type=3
Dn Slope=0.005
Boundary for River Rch & Prof#=UNT 0059 IN HEWA,Reach-1,3
Up Type=0
Dn Type=3
Dn Slope=0.005
Boundary for River Rch & Prof#=UNT 0059 IN HEWA,Reach-1,4
Up Type=0
Dn Type=3
Dn Slope=0.005
Boundary for River Rch & Prof#=UNT 0059 IN HEWA,Reach-1,5
Up Type=0
Dn Type=3
Dn Slope=0.005
Boundary for River Rch & Prof#=UNT 0059 IN HEWA,Reach-1,6
Up Type=0
Dn Type=3
Dn Slope=0.005
Boundary for River Rch & Prof#=UNT 0059 IN HEWA,Reach-1,7
Up Type=0
Dn Type=3
Dn Slope=0.005

--- UNT 0059 IN HEWA.g01 (geometry) ---

Geom Title=Existing Conditions

River Reach=UNT 0059 IN HEWA,Reach-1
Reach XY= 30
      2741567.68     10082432.22      2742066.26     10082306.13
      2742268.30     10082323.30      2742403.24     10082294.44
      2742583.13     10082333.26      2742859.76     10082247.70
      2742932.77     10082175.91      2742952.11     10082070.49
      2743099.80     10081861.56      2743412.57     10081750.53
      2743384.82     10081625.31      2743326.38     10081599.58
      2743278.50     10081457.94      2743412.85     10081282.15
      2743579.36     10081207.38      2743632.55     10081106.10
      2743620.86     10080979.61      2743688.31     10080841.12
      2743610.55     10080764.24      2743692.17     10080631.53
      2743898.60     10080613.21      2744021.90     10080391.17
      2744192.07     10080320.08      2744376.38     10080429.90
      2744329.48     10080583.25      2744419.74     10080690.93
      2744667.23     10080660.72      2745050.36     10080209.88
      2745122.13     10080060.18      2745248.47     10080043.73

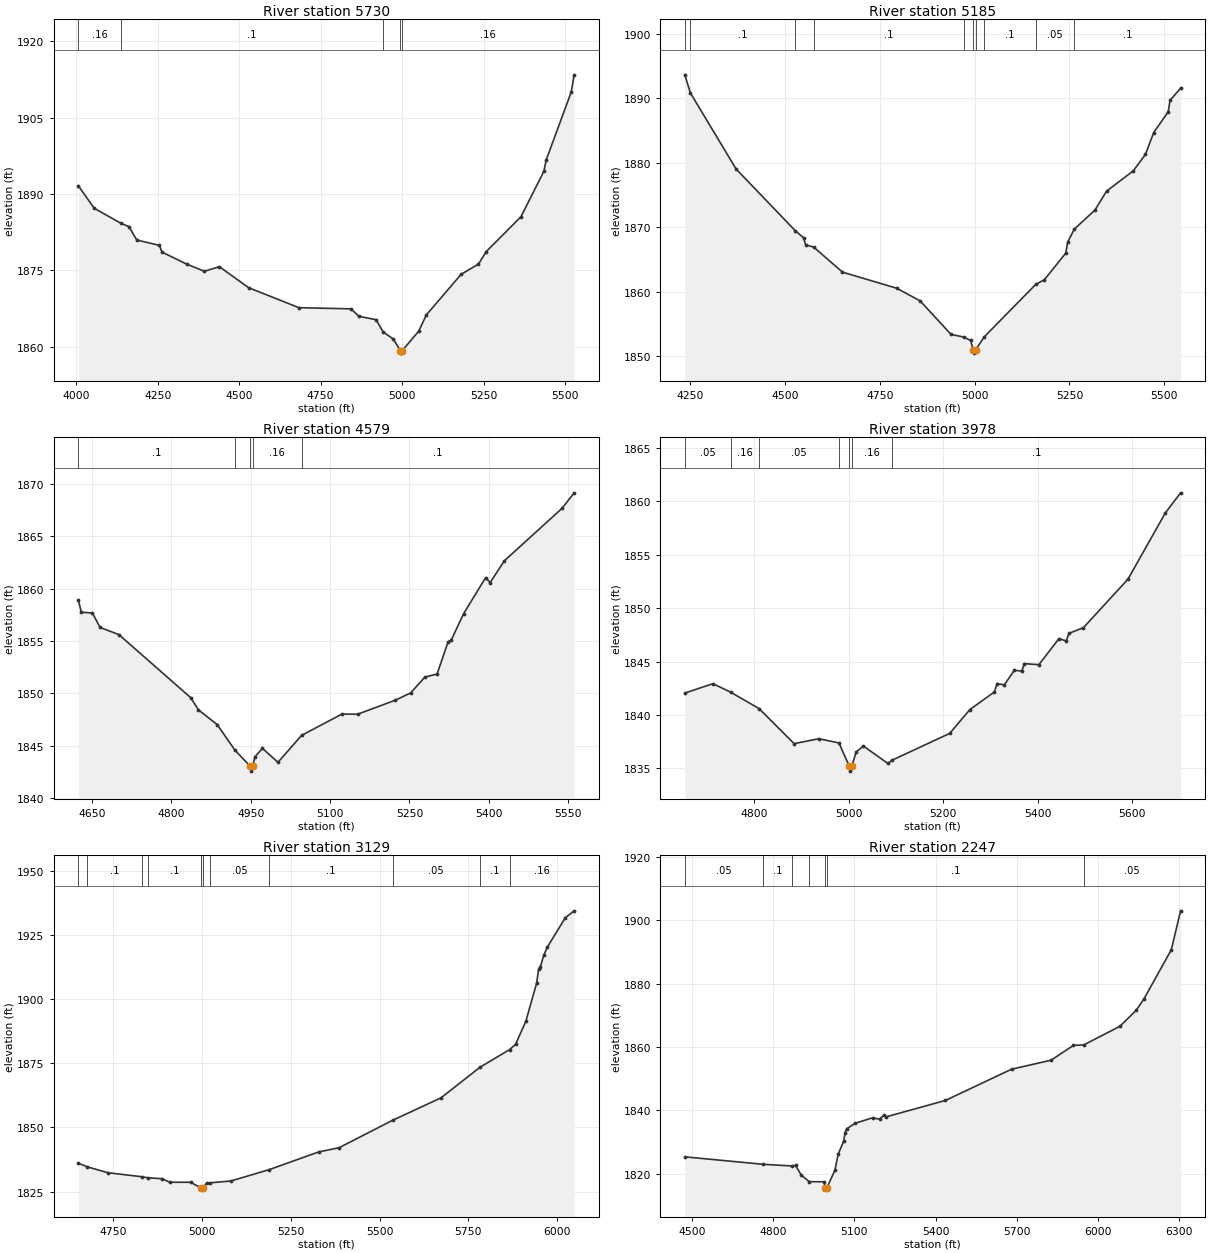
Type RM Length L Ch R = 1,5730,545,545,545
BEGIN DESCRIPTION:
UNT 0059 IN HEWA 6.0
END DESCRIPTION:
XS GIS Cut Line= 2
      2742162.32     10083293.56      2741581.02     10081888.02
#Sta/Elev= 30
  4006.6 1891.61  4055.5 1887.18  4138.0 1884.22  4162.0 1883.58  4185.9 1880.96
  4255.3 1879.91  4263.0 1878.60  4340.1 1876.19  4393.3 1874.83  4439.3 1875.72
  4529.1 1871.60  4683.3 1867.68  4843.0 1867.45  4866.9 1865.99  4920.1 1865.32
  4941.8 1862.91  4973.3 1861.50  4994.2 1859.26  4997.0 1858.76  5000.2 1859.26
  5050.5 1863.05  5074.4 1866.28  5180.8 1874.22  5234.0 1876.23  5257.9 1878.69
  5364.4 1885.53  5434.8 1894.45  5441.5 1896.61  5518.6 1910.00  5527.6 1913.38
#Mann=5,-1,0
  4006.6    0.16       0  4138.0     0.1       0  4941.8    0.16       0
  4994.2    0.07       0  5000.2    0.16       0
Bank Sta=4994.2,5000.2
Exp/Cntr=0.3,0.1

Type RM Length L Ch R = 1,5185,606,606,606
BEGIN DESCRIPTION:
Mapping XS 79cda47b
END DESCRIPTION:
XS GIS Cut Line= 2
      2742483.50     10083059.19      2742197.04     10081783.15
#Sta/Elev= 30
  4235.6 1893.65  4250.5 1890.83  4371.0 1879.04  4527.5 1869.45  4548.7 1868.39
  4554.6 1867.28  4575.5 1866.94  4651.5 1863.06  4794.6 1860.56  4856.1 1858.61
  4938.1 1853.39  4971.2 1853.00  4989.4 1852.46  4996.6 1851.00  4999.4 1850.50
  5002.6 1851.00  5025.5 1853.03  5161.3 1861.16  5184.1 1861.89  5240.3 1865.99
  5245.6 1867.73  5263.1 1869.74  5317.3 1872.67  5348.1 1875.62  5418.7 1878.77
  5450.6 1881.31  5472.3 1884.69  5510.5 1887.91  5515.6 1889.70  5543.4 1891.59
#Mann=10,-1,0
  4235.6    0.16       0  4250.5     0.1       0  4527.5    0.16       0
  4575.5     0.1       0  4971.2    0.16       0  4996.6    0.07       0
  5002.6    0.16       0  5025.5     0.1       0  5161.3    0.05       0
  5263.1     0.1       0
Bank Sta=4996.6,5002.6
Exp/Cntr=0.3,0.1

Type RM Length L Ch R = 1,4579,601,601,601
BEGIN DESCRIPTION:
UNT 0059 IN HEWA 5.0
END DESCRIPTION:
XS GIS Cut Line= 2
      2743108.53     10082521.02      2742552.94     10081765.77
#Sta/Elev= 30
  4623.9 1858.92  4629.6 1857.75  4650.4 1857.69  4665.1 1856.30  4700.6 1855.62
  4836.4 1849.60  4851.0 1848.44  4886.5 1847.03  4919.9 1844.60  4948.3 1843.09
  4951.0 1842.59  4954.3 1843.09  4957.5 1843.94  4972.1 1844.76  5001.4 1843.43
  5046.0 1846.00  5122.6 1848.04  5151.9 1848.02  5222.9 1849.35  5252.2 1850.05
  5279.2 1851.56  5302.3 1851.86  5323.1 1854.93  5329.4 1855.13  5352.4 1857.61
  5394.1 1861.06  5402.6 1860.58  5429.6 1862.67  5538.4 1867.66  5561.5 1869.15
#Mann=5,-1,0
  4623.9     0.1       0  4919.9    0.16       0  4948.3    0.07       0
  4954.3    0.16       0  5046.0     0.1       0
Bank Sta=4948.3,4954.3
Exp/Cntr=0.3,0.1

Type RM Length L Ch R = 1,3978,849,849,849
BEGIN DESCRIPTION:
UNT 0059 IN HEWA 4.0
END DESCRIPTION:
XS GIS Cut Line= 3
      2743516.49     10081974.11      2743290.79     10081869.94
      2742865.43     10081192.85
#Sta/Elev= 30
  4653.7 1842.05  4713.2 1842.93  4750.4 1842.14  4810.7 1840.60  4884.8 1837.32
  4937.0 1837.78  4979.5 1837.39  5001.1 1835.25  5003.8 1834.75  5007.1 1835.25
  5015.9 1836.53  5031.2 1837.10  5083.0 1835.47  5092.7 1835.79  5213.8 1838.28
  5256.2 1840.50  5308.0 1842.15  5313.9 1842.94  5329.2 1842.82  5350.4 1844.19
  5365.8 1844.10  5371.7 1844.80  5402.3 1844.71  5444.7 1847.14  5460.0 1846.93
  5465.9 1847.64  5496.5 1848.17  5590.7 1852.71  5669.7 1858.91  5701.9 1860.78
#Mann=7,-1,0
  4653.7    0.05       0  4750.4    0.16       0  4810.7    0.05       0
  4979.5    0.16       0  5001.1    0.07       0  5007.1    0.16       0
  5092.7     0.1       0
Bank Sta=5001.1,5007.1
Exp/Cntr=0.3,0.1

Type RM Length L Ch R = 1,3129,882,882,882
BEGIN DESCRIPTION:
UNT 0059 IN HEWA 3.0
END DESCRIPTION:
XS GIS Cut Line= 3
      2743655.35     10081548.72      2743325.51     10080958.49
      2742613.74     10080854.32
#Sta/Elev= 30
  4652.2 1836.08  4676.1 1834.71  4735.2 1832.36  4831.0 1830.79  4848.4 1830.38
  4887.2 1830.02  4909.9 1828.65  4968.2 1828.63  4997.2 1826.46  5000.0 1825.96
  5003.2 1826.46  5013.0 1828.29  5023.9 1828.43  5081.3 1829.13  5188.4 1833.52
  5328.2 1840.44  5386.0 1842.11  5536.5 1852.78  5673.0 1861.56  5782.1 1873.43
  5865.8 1880.35  5882.7 1882.42  5911.5 1891.33  5941.9 1906.18  5947.6 1911.65
  5952.6 1912.64  5962.1 1917.13  5972.2 1920.34  6022.7 1931.77  6047.7 1934.48
#Mann=11,-1,0
  4652.2    0.05       0  4676.1     0.1       0  4831.0    0.05       0
  4848.4     0.1       0  4997.2    0.07       0  5003.2     0.1       0
  5023.9    0.05       0  5188.4     0.1       0  5536.5    0.05       0
  5782.1     0.1       0  5865.8    0.16       0
Bank Sta=4997.2,5003.2
Exp/Cntr=0.3,0.1

Type RM Length L Ch R = 1,2247,624,624,624
BEGIN DESCRIPTION:
UNT 0059 IN HEWA 2.0
END DESCRIPTION:
XS GIS Cut Line= 4
      2743941.84     10081123.45      2743724.82     10080437.65
      2743577.25     10080368.21      2742702.02     10080732.17
#Sta/Elev= 30
  4474.1 1825.36  4763.7 1823.00  4868.3 1822.49  4882.9 1822.64  4904.3 1819.56
  4933.7 1817.53  4987.8 1817.49  4993.0 1815.67  4995.8 1815.17  4999.0 1815.67
  5028.3 1821.12  5040.2 1826.18  5060.6 1830.31  5065.9 1833.04  5071.7 1834.22
  5103.4 1835.96  5168.0 1837.71  5192.9 1837.24  5210.2 1838.59  5215.7 1837.94
  5436.2 1843.16  5680.1 1853.01  5826.5 1855.87  5908.9 1860.55  5946.9 1860.68
  6080.8 1866.59  6139.8 1871.56  6169.1 1875.21  6269.9 1890.69  6304.4 1903.00
#Mann=7,-1,0
  4474.1    0.05       0  4763.7     0.1       0  4868.3    0.16       0
  4933.7     0.1       0  4993.0    0.07       0  4999.0     0.1       0
  5946.9    0.05       0
Bank Sta=4993,4999
Exp/Cntr=0.3,0.1

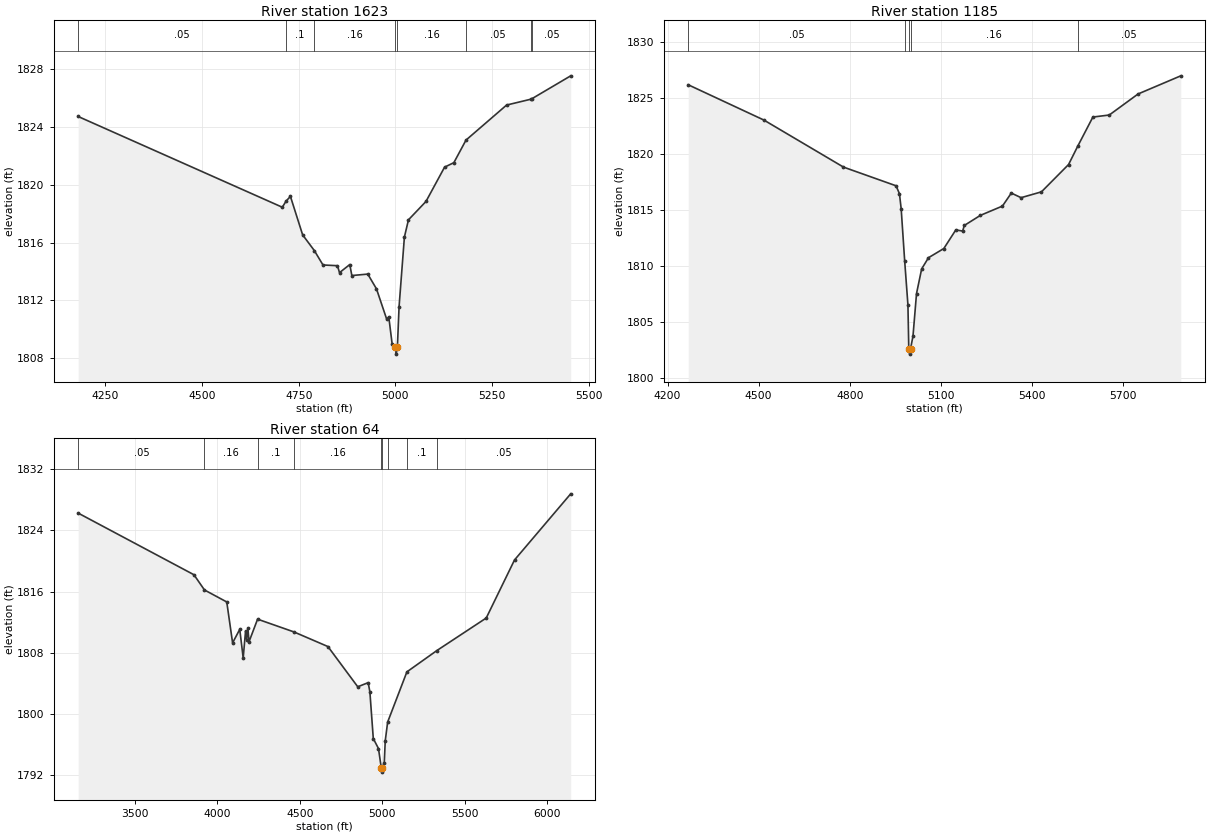
Type RM Length L Ch R = 1,1623,438,438,438
BEGIN DESCRIPTION:
Mapping XS 0ce1e04e
END DESCRIPTION:
XS GIS Cut Line= 3
      2743984.66     10081125.32      2744263.67     10080273.14
      2744121.11     10079924.33
#Sta/Elev= 30
  4179.7 1824.71  4707.5 1818.44  4717.2 1818.86  4728.5 1819.19  4760.1 1816.53
  4790.2 1815.45  4812.7 1814.45  4850.2 1814.40  4855.4 1813.92  4882.0 1814.48
  4887.3 1813.72  4928.5 1813.82  4951.0 1812.80  4977.6 1810.69  4982.8 1810.87
  4991.6 1808.97  4999.1 1808.79  5001.9 1808.29  5005.1 1808.79  5009.4 1811.56
  5023.2 1816.38  5033.7 1817.57  5079.0 1818.84  5127.1 1821.21  5151.1 1821.52
  5182.5 1823.08  5287.4 1825.50  5349.5 1825.90  5353.0 1825.94  5453.2 1827.52
#Mann=8,-1,0
  4179.7    0.05       0  4717.2     0.1       0  4790.2    0.16       0
  4999.1    0.07       0  5005.1    0.16       0  5182.5    0.05       0
  5349.5     0.1       0  5353.0    0.05       0
Bank Sta=4999.1,5005.1
Exp/Cntr=0.3,0.1

Type RM Length L Ch R = 1,1185,1121,1121,1121
BEGIN DESCRIPTION:
Mapping XS 187d7fc2
END DESCRIPTION:
XS GIS Cut Line= 4
      2743945.89     10081242.26      2744333.90     10080799.56
      2744477.12     10080507.90      2744159.41     10079875.08
#Sta/Elev= 30
  4268.1 1826.20  4517.2 1823.05  4779.2 1818.85  4952.4 1817.18  4963.5 1816.47
  4969.2 1815.12  4980.6 1810.51  4991.4 1806.55  4994.2 1802.65  4997.0 1802.15
  5000.2 1802.65  5008.1 1803.77  5019.7 1807.56  5036.6 1809.76  5059.1 1810.76
  5109.6 1811.58  5149.0 1813.24  5171.5 1813.14  5177.1 1813.64  5230.0 1814.54
  5302.6 1815.37  5331.8 1816.53  5364.0 1816.12  5431.0 1816.64  5520.3 1819.08
  5550.0 1820.69  5600.4 1823.32  5654.3 1823.50  5749.2 1825.38  5889.8 1827.00
#Mann=5,-1,0
  4268.1    0.05       0  4980.6    0.16       0  4994.2    0.07       0
  5000.2    0.16       0  5550.0    0.05       0
Bank Sta=4994.2,5000.2
Exp/Cntr=0.3,0.1

Type RM Length L Ch R = 1,64,0,0,0
BEGIN DESCRIPTION:
UNT 0059 IN HEWA 1.0
END DESCRIPTION:
XS GIS Cut Line= 4
      2743966.73     10081265.69      2745242.75     10080263.11
      2745167.23     10079979.25      2744111.70     10079823.26
#Sta/Elev= 30
  3157.7 1826.27  3859.0 1818.21  3922.7 1816.22  4057.8 1814.65  4093.1 1809.30
  4136.5 1811.07  4157.3 1807.33  4171.7 1810.86  4178.1 1809.74  4186.2 1811.19
  4192.5 1809.44  4244.5 1812.40  4463.8 1810.74  4670.6 1808.82  4851.3 1803.56
  4914.4 1804.10  4924.7 1802.90  4945.4 1796.79  4976.9 1795.48  4994.1 1792.90
  4996.9 1792.40  5000.1 1792.90  5011.9 1793.62  5017.8 1796.50  5032.4 1798.95
  5149.0 1805.51  5330.7 1808.30  5629.5 1812.55  5800.8 1820.14  6141.2 1828.79
#Mann=9,-1,0
  3157.7    0.05       0  3922.7    0.16       0  4244.5     0.1       0
  4463.8    0.16       0  4994.1    0.07       0  5000.1    0.16       0
  5032.4    0.05       0  5149.0     0.1       0  5330.7    0.05       0
Bank Sta=4994.1,5000.1
Exp/Cntr=0.3,0.1

Chan Stop Cuts=-1