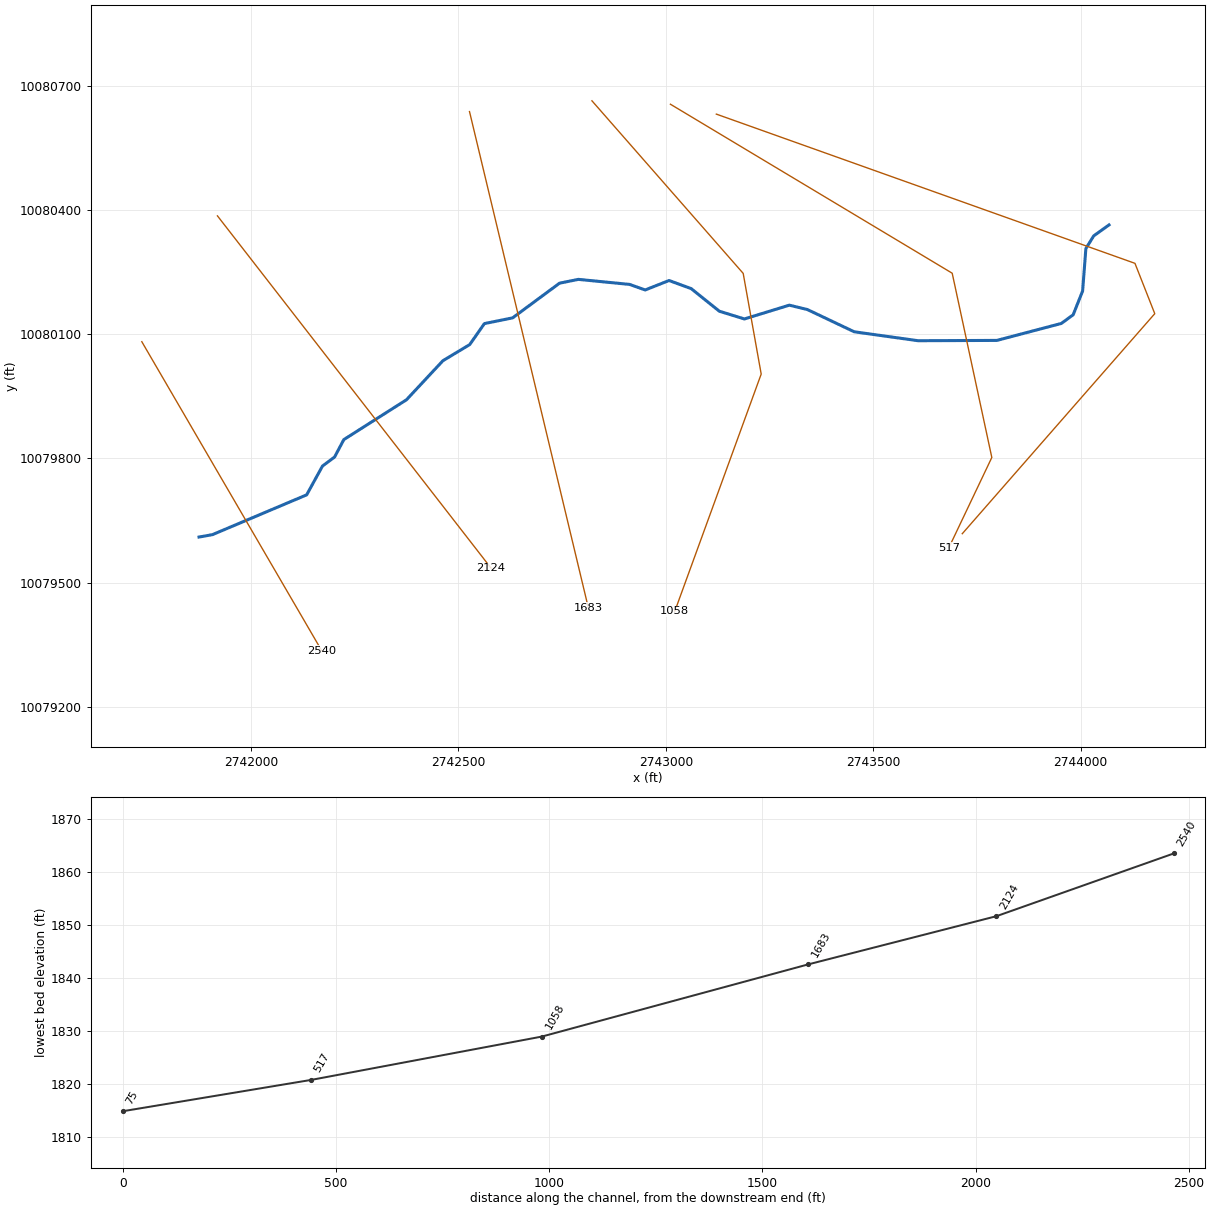
--- UNT 0060 IN HEWA.prj (project) ---

Proj Title=UNT 0060 IN HEWA Base Level Engineering
Current Plan=p01
Default Exp/Contr=0.3,0.1
English Units
Geom File=g01
Flow File=f01
Plan File=p01
Y Axis Title=Elevation
X Axis Title(PF)=Main Channel Distance
X Axis Title(XS)=Station
BEGIN DESCRIPTION:
UNT 0060 IN HEWA
END DESCRIPTION:
DSS Export Rating Curves= 0
DSS Export Rating Curve Sorted= 0
DSS Export Volume Flow Curves= 0
DXF OffsetX= 0
DXF OffsetY= 0
DXF ScaleX= 1
DXF ScaleY= 10

--- UNT 0060 IN HEWA.p01 (plan) ---

Plan Title=Multiple Run
Short Identifier=Multiple
Geom File=g01
Flow File=f01
Subcritical Flow
K Sum by GR= 0
Std Step Tol= 0.01
Critical Tol= 0.01
Num of Std Step Trials= 20
Max Error Tol= 0.3
Flow Tol Ratio= 0.001
Split Flow NTrial= 30
Split Flow Tol= 0.02
Split Flow Ratio= 0.02
Log Output Level= 0
Friction Slope Method= 1
Unsteady Friction Slope Method= 2
Unsteady Bridges Friction Slope Method= 1
Parabolic Critical Depth
Global Vel Dist=  1 , 1 , 1
Global Log Level= 0
CheckData=True
Encroach Param= -1, 0, 0, 0
BEGIN DESCRIPTION:
Multiple Run
END DESCRIPTION:

--- UNT 0060 IN HEWA.f01 (steady flow) ---

Flow Title=Multiple
Program Version=4.10
Number of Profiles= 7
Profile Names=10-year,25-year,50-year,1pct_min,100-year,1pct_plu,500-year
River Rch & RM=UNT 0060 IN HEWA,Reach-1         ,2540
     374     517     635     574     776    1049    1160
Boundary for River Rch & Prof#=UNT 0060 IN HEWA,Reach-1         , 1
Up Type= 0
Dn Type= 3
Dn Slope=0.013
Boundary for River Rch & Prof#=UNT 0060 IN HEWA,Reach-1         , 2
Up Type= 0
Dn Type= 3
Dn Slope=0.013
Boundary for River Rch & Prof#=UNT 0060 IN HEWA,Reach-1         , 3
Up Type= 0
Dn Type= 3
Dn Slope=0.013
Boundary for River Rch & Prof#=UNT 0060 IN HEWA,Reach-1         , 4
Up Type= 0
Dn Type= 3
Dn Slope=0.013
Boundary for River Rch & Prof#=UNT 0060 IN HEWA,Reach-1         , 5
Up Type= 0
Dn Type= 3
Dn Slope=0.013
Boundary for River Rch & Prof#=UNT 0060 IN HEWA,Reach-1         , 6
Up Type= 0
Dn Type= 3
Dn Slope=0.013
Boundary for River Rch & Prof#=UNT 0060 IN HEWA,Reach-1         , 7
Up Type= 0
Dn Type= 3
Dn Slope=0.013
DSS Import GetInterval= 0
DSS Import GetPeak= 0
DSS Import FillOption= 0

--- UNT 0060 IN HEWA.g01 (geometry) ---

Geom Title=Existing Conditions
Program Version=4.10

River Reach=UNT 0060 IN HEWA,Reach-1
Reach XY= 30
      2741874.84      10079610.1      2741907.29     10079615.94
      2742134.36     10079711.99       2742172.5     10079781.61
      2742201.61      10079803.2      2742223.95     10079845.41
      2742375.06     10079941.61      2742462.73      10080035.8
      2742527.42     10080074.82      2742562.77     10080125.46
      2742630.84     10080139.29      2742743.88     10080223.02
      2742789.34     10080232.23      2742912.82     10080220.05
      2742950.37     10080206.63      2743007.91     10080229.49
      2743061.13     10080209.97      2743129.14     10080155.35
      2743189.52     10080136.65      2743297.75     10080169.94
      2743341.23     10080159.42      2743454.28      10080105.7
      2743608.18     10080084.11      2743798.22     10080084.87
      2743953.57     10080125.82      2743982.07     10080146.76
      2744004.86      10080204.2      2744012.64     10080306.54
      2744031.54     10080337.18      2744068.47     10080363.73

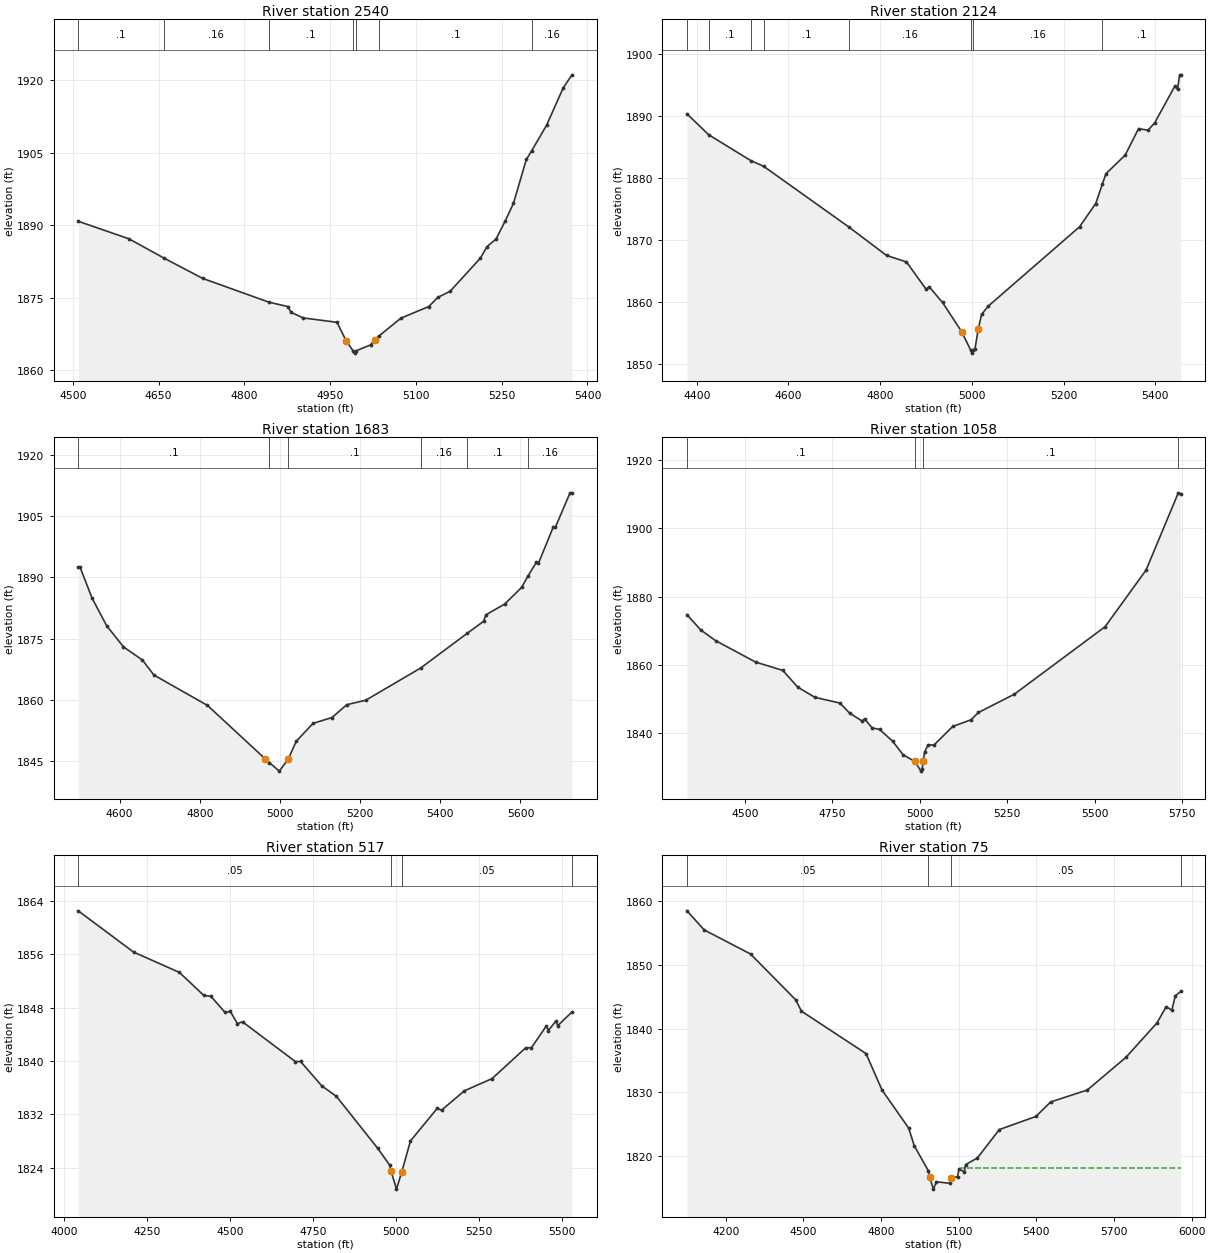
Type RM Length L Ch R = 1 ,2540    ,416,416,416
BEGIN DESCRIPTION:
UNT 0060 IN HEWA 5.0
END DESCRIPTION:
XS GIS Cut Line= 2
      2741736.98     10080081.74      2742170.99     10079335.24
#Sta/Elev= 30
  4509.4 1890.86  4597.9 1887.24  4658.7 1883.28    4727 1879.04  4842.5 1874.13
    4876 1873.21  4881.7    1872  4903.2 1870.85    4962 1869.95  4977.7 1866.17
  4989.9 1864.07  4992.7 1863.57  4995.9 1864.07  5020.8 1865.28  5027.6 1866.37
  5035.5 1867.14  5073.8 1870.81  5122.6 1873.22  5138.3 1875.11  5159.8 1876.37
  5212.7 1883.22  5224.4 1885.62  5240.1 1887.18  5255.8 1890.83  5270.5 1894.54
  5293.1 1903.65  5302.6 1905.49  5328.4 1910.71  5357.6 1918.47  5372.9 1921.17
#Mann= 7 ,-1 , 0
  4509.4      .1       0  4658.7     .16       0  4842.5      .1       0
  4989.9     .07       0  4995.9      .1       0  5035.5      .1       0
  5302.6     .16       0
Bank Sta=4977.7,5027.6
XS Rating Curve= 0 ,0
Exp/Cntr=0.3,0.1

Type RM Length L Ch R = 1 ,2124    ,441,441,441
BEGIN DESCRIPTION:
UNT 0060 IN HEWA 4.0
END DESCRIPTION:
XS GIS Cut Line= 2
      2741919.27     10080385.57      2742578.97     10079534.89
#Sta/Elev= 30
  4378.8 1890.31  4426.1 1886.94  4518.1 1882.76  4545.8 1881.86  4732.4 1872.02
  4813.8 1867.47  4857.3 1866.42    4900 1862.03  4907.1 1862.39    4936 1859.88
  4977.7 1855.17  4997.3 1852.21  5000.1 1851.71  5003.3 1852.21  5006.6 1852.35
  5013.9 1855.63  5021.1 1857.95  5035.6 1859.29  5234.7 1872.09    5270 1875.85
  5284.6 1879.02  5292.3 1880.66  5334.3 1883.67  5363.3 1887.92  5384.1 1887.68
  5398.6 1888.87  5442.1 1894.74  5448.4 1894.29  5452.9 1896.61  5455.3 1896.61
#Mann= 8 ,-1 , 0
  4378.8     .16       0  4426.1      .1       0  4518.1     .16       0
  4545.8      .1       0  4732.4     .16       0  4997.3     .07       0
  5003.3     .16       0  5284.6      .1       0
Bank Sta=4977.7,5013.9
XS Rating Curve= 0 ,0
Exp/Cntr=0.3,0.1

Type RM Length L Ch R = 1 ,1683    ,625,625,625
BEGIN DESCRIPTION:
UNT 0060 IN HEWA 3.0
END DESCRIPTION:
XS GIS Cut Line= 2
       2742526.9     10080637.32      2742813.36     10079439.39
#Sta/Elev= 30
  4496.7 1892.54  4501.1 1892.54  4531.2 1884.94  4567.6 1878.19  4609.6 1873.01
  4656.8  1869.8  4685.5 1866.12  4819.1 1858.69  4963.1 1845.62  4973.4 1844.72
  4998.2 1842.61 5020.45 1845.51  5040.5 1849.91  5082.6  1854.3  5129.8 1855.72
  5166.7 1858.87  5213.9 1859.95    5351 1867.84  5466.5 1876.29    5508 1879.27
  5513.5 1880.84  5560.7  1883.5  5602.8 1887.55  5618.7 1890.35  5639.7 1893.72
  5644.8 1893.45  5681.8 1902.35  5686.9 1902.24  5723.6  1910.7  5728.4  1910.7
#Mann= 6 ,-1 , 0
  4496.7      .1       0  4973.4     .07       0 5020.45      .1       0
    5351     .16       0  5466.5      .1       0  5618.7     .16       0
Bank Sta=4963.1,5020.45
XS Rating Curve= 0 ,0
Exp/Cntr=0.3,0.1

Type RM Length L Ch R = 1 ,1058    ,541,541,541
BEGIN DESCRIPTION:
UNT 0060 IN HEWA 2.0
END DESCRIPTION:
XS GIS Cut Line= 4
      2742822.05     10080663.34      2743186.62     10080246.68
      2743230.03     10080003.63      2743021.68     10079430.68
#Sta/Elev= 30
    4335 1874.75  4374.3 1870.27    4417 1867.13  4530.9 1860.88  4608.7 1858.44
  4651.4 1853.53  4700.8 1850.54  4771.9 1848.88  4799.5 1845.93  4835.5 1843.61
  4842.2 1844.25    4864  1841.6  4884.9 1841.18  4922.1 1837.74  4952.6  1833.7
  4986.3 1831.79  5003.1 1828.96  5006.4 1829.46    5010 1832.02  5013.5 1834.52
  5023.7 1836.68  5040.1 1836.57    5094 1842.03  5146.1 1843.98  5167.4 1846.12
  5270.1 1851.48  5529.1 1871.22  5646.2  1887.8  5738.3 1910.41  5745.2 1910.13
#Mann= 4 ,-1 , 0
    4335      .1       0  4986.3     .05       0    5010      .1       0
  5738.3     .16       0
Bank Sta=4986.3,5010
XS Rating Curve= 0 ,0
Exp/Cntr=0.3,0.1

Type RM Length L Ch R = 1 ,517     ,442,442,442
BEGIN DESCRIPTION:
Mapping XS 416df51e
END DESCRIPTION:
XS GIS Cut Line= 4
      2743011.18     10080655.08      2743690.47     10080247.08
      2743785.95      10079802.2      2743682.64     10079584.81
#Sta/Elev= 30
  4041.4 1862.54  4208.2 1856.35  4346.2  1853.3    4420 1849.84  4441.4 1849.71
  4484.2 1847.28  4499.7 1847.45  4521.1 1845.62  4536.6 1845.88    4696 1839.91
  4711.5 1839.93  4775.6 1836.26  4819.8 1834.68    4944  1826.9  4980.4 1824.35
 4984.55 1823.44  5000.6 1820.77 5016.36 1823.32  5042.8 1828.01  5123.6  1832.9
  5136.5 1832.62  5205.4 1835.53  5288.8 1837.36    5390 1841.98  5407.2 1841.99
  5452.7 1845.29  5458.2 1844.57  5480.9 1845.99  5486.5  1845.3  5529.5 1847.36
#Mann= 4 ,-1 , 0
  4041.4     .05       0 4984.55    .035       0 5016.36     .05       0
  5529.5     .16       0
Bank Sta=4984.55,5016.36
XS Rating Curve= 0 ,0
Exp/Cntr=0.3,0.1

Type RM Length L Ch R = 1 ,75      ,0,0,0
BEGIN DESCRIPTION:
UNT 0060 IN HEWA 1.0
END DESCRIPTION:
XS GIS Cut Line= 4
      2743121.87      10080631.2        2744131.     10080270.95
      2744178.75     10080149.42      2743714.75      10079618.2
#Sta/Elev= 30
  4050.6 1858.46  4116.7 1855.48  4296.2 1851.69  4470.4 1844.52  4492.9 1842.73
  4742.2 1836.09  4803.8  1830.4    4907 1824.41  4928.3 1821.67  4983.3  1817.7
  4987.5 1816.82  5002.4 1814.85  5014.1    1816  5065.1 1815.77  5070.4 1816.63
  5095.9 1816.79  5101.2    1818  5122.1 1817.56  5126.7 1818.68  5172.8 1819.75
  5257.1 1824.18  5398.6 1826.24  5455.5 1828.51    5597 1830.38    5746 1835.49
  5866.6 1840.91  5901.7 1843.44  5923.5 1842.89  5937.4 1845.16    5958 1845.83
#Mann= 4 ,-1 , 0
  4050.6     .05       0  4983.3    .035       0  5070.4     .05       0
    5958     .16       0
#XS Ineff= 2 , 0
                         5108.71         1818.09
Permanent Ineff=
       T       T
Bank Sta=4987.5,5070.4
XS Rating Curve= 0 ,0
Exp/Cntr=0.3,0.1

Chan Stop Cuts=-1
Use User Specified Reach Order=0
Composite Channel Slope=5