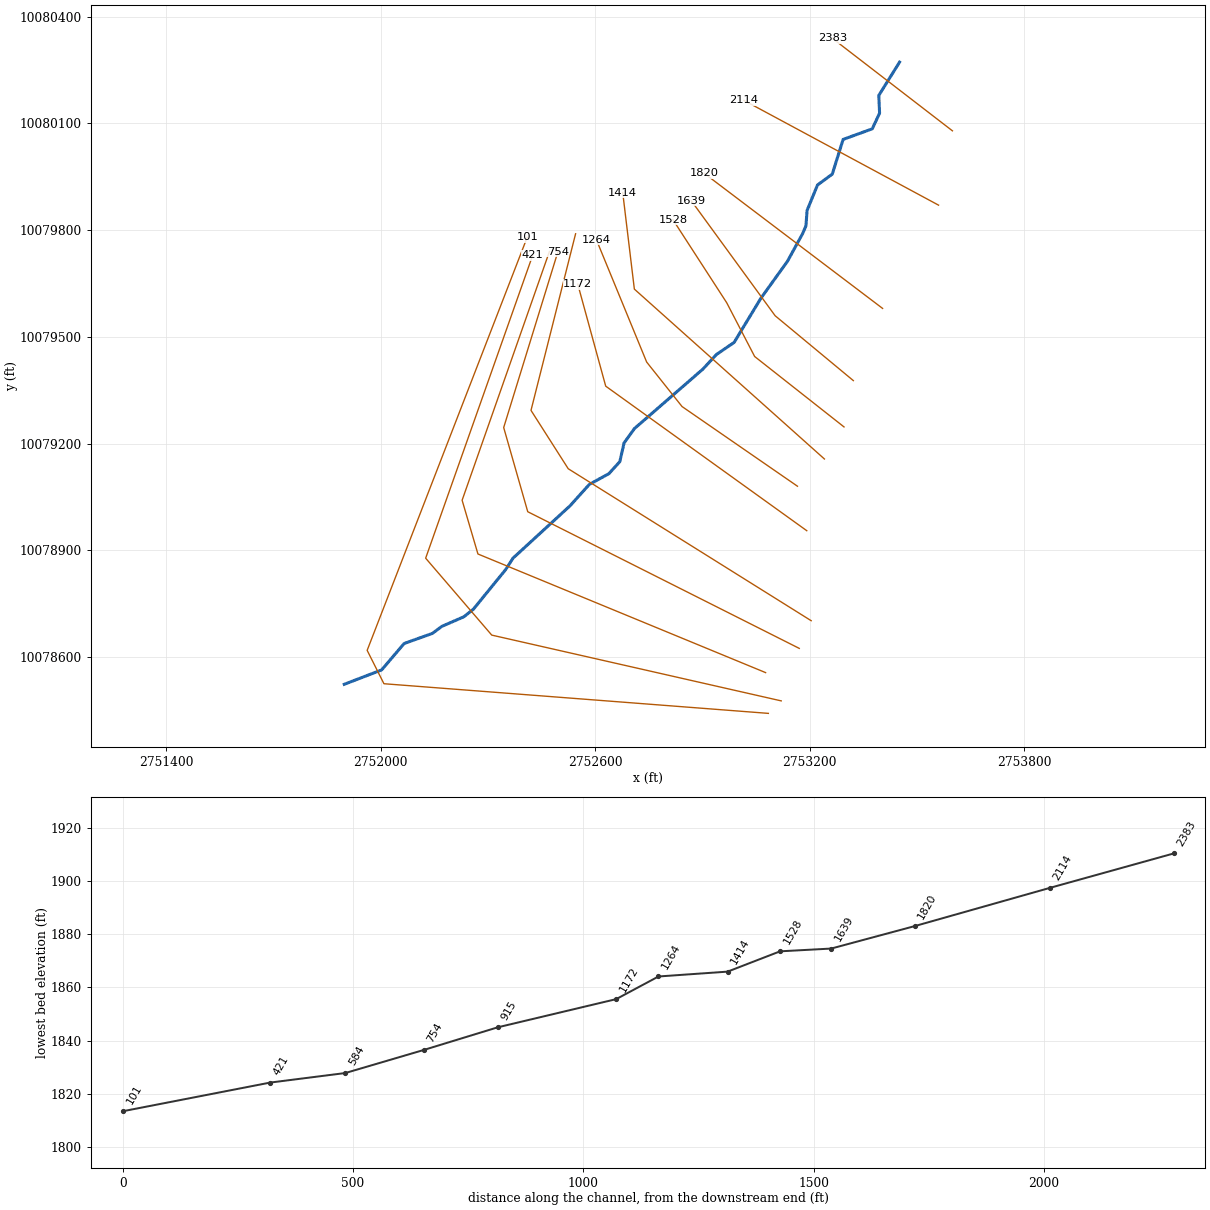
--- UNT 0062 IN HEWA.prj (project) ---

Proj Title=UNT 0062 IN HEWA Base Level Engineering
Current Plan=p01
Default Exp/Contr=0.3,0.1
English Units
Geom File=g01
Flow File=f01
Plan File=p01
Y Axis Title=Elevation
X Axis Title(PF)=Main Channel Distance
X Axis Title(XS)=Station
BEGIN DESCRIPTION:
UNT 0062 IN HEWA
END DESCRIPTION:
DSS Export Rating Curves= 0
DSS Export Rating Curve Sorted= 0
DSS Export Volume Flow Curves= 0
DXF OffsetX= 0
DXF OffsetY= 0
DXF ScaleX= 1
DXF ScaleY= 10

--- UNT 0062 IN HEWA.p01 (plan) ---

Plan Title=Multiple Run
Short Identifier=Multiple
Geom File=g01
Flow File=f01
Subcritical Flow
K Sum by GR= 0
Std Step Tol= 0.01
Critical Tol= 0.01
Num of Std Step Trials= 20
Max Error Tol= 0.3
Flow Tol Ratio= 0.001
Split Flow NTrial= 30
Split Flow Tol= 0.02
Split Flow Ratio= 0.02
Log Output Level= 0
Friction Slope Method= 1
Unsteady Friction Slope Method= 2
Unsteady Bridges Friction Slope Method= 1
Parabolic Critical Depth
Global Vel Dist=  1 , 1 , 1
Global Log Level= 0
CheckData=True
Encroach Param= -1, 0, 0, 0
BEGIN DESCRIPTION:
Multiple Run
END DESCRIPTION:

--- UNT 0062 IN HEWA.f01 (steady flow) ---

Flow Title=Multiple
Program Version=4.10
Number of Profiles= 7
Profile Names=10-year,25-year,50-year,1pct_min,100-year,1pct_plu,500-year
River Rch & RM=UNT 0062 IN HEWA,Reach-1         ,2383
     157     204     241     210     285     385     395
Boundary for River Rch & Prof#=UNT 0062 IN HEWA,Reach-1         , 1
Up Type= 0
Dn Type= 3
Dn Slope=0.036
Boundary for River Rch & Prof#=UNT 0062 IN HEWA,Reach-1         , 2
Up Type= 0
Dn Type= 3
Dn Slope=0.036
Boundary for River Rch & Prof#=UNT 0062 IN HEWA,Reach-1         , 3
Up Type= 0
Dn Type= 3
Dn Slope=0.036
Boundary for River Rch & Prof#=UNT 0062 IN HEWA,Reach-1         , 4
Up Type= 0
Dn Type= 3
Dn Slope=0.036
Boundary for River Rch & Prof#=UNT 0062 IN HEWA,Reach-1         , 5
Up Type= 0
Dn Type= 3
Dn Slope=0.036
Boundary for River Rch & Prof#=UNT 0062 IN HEWA,Reach-1         , 6
Up Type= 0
Dn Type= 3
Dn Slope=0.036
Boundary for River Rch & Prof#=UNT 0062 IN HEWA,Reach-1         , 7
Up Type= 0
Dn Type= 3
Dn Slope=0.036
DSS Import GetInterval= 0
DSS Import GetPeak= 0
DSS Import FillOption= 0

--- UNT 0062 IN HEWA.g01 (geometry) ---

Geom Title=Existing Conditions
Program Version=4.10

River Reach=UNT 0062 IN HEWA,Reach-1
Reach XY= 30
      2753451.86     10080272.33      2753393.77     10080178.76
      2753395.94     10080128.85      2753375.47     10080084.83
      2753293.95     10080055.06      2753263.57     10079957.41
      2753222.33     10079927.02      2753193.17     10079855.66
      2753189.94     10079812.07      2753180.65     10079790.25
      2753138.19     10079712.48      2753063.91     10079608.72
      2752989.02     10079484.56      2752939.51     10079450.54
      2752901.38     10079409.28      2752710.24     10079242.48
      2752681.21      10079202.2      2752669.26     10079149.54
      2752638.85     10079115.75      2752584.09     10079085.58
      2752530.12     10079025.46      2752370.44     10078878.14
      2752349.99     10078846.21      2752259.75     10078734.88
      2752232.66     10078713.29       2752171.5      10078686.6
      2752144.99     10078666.74      2752065.88     10078638.34
      2752003.04     10078564.15      2751898.47     10078523.73

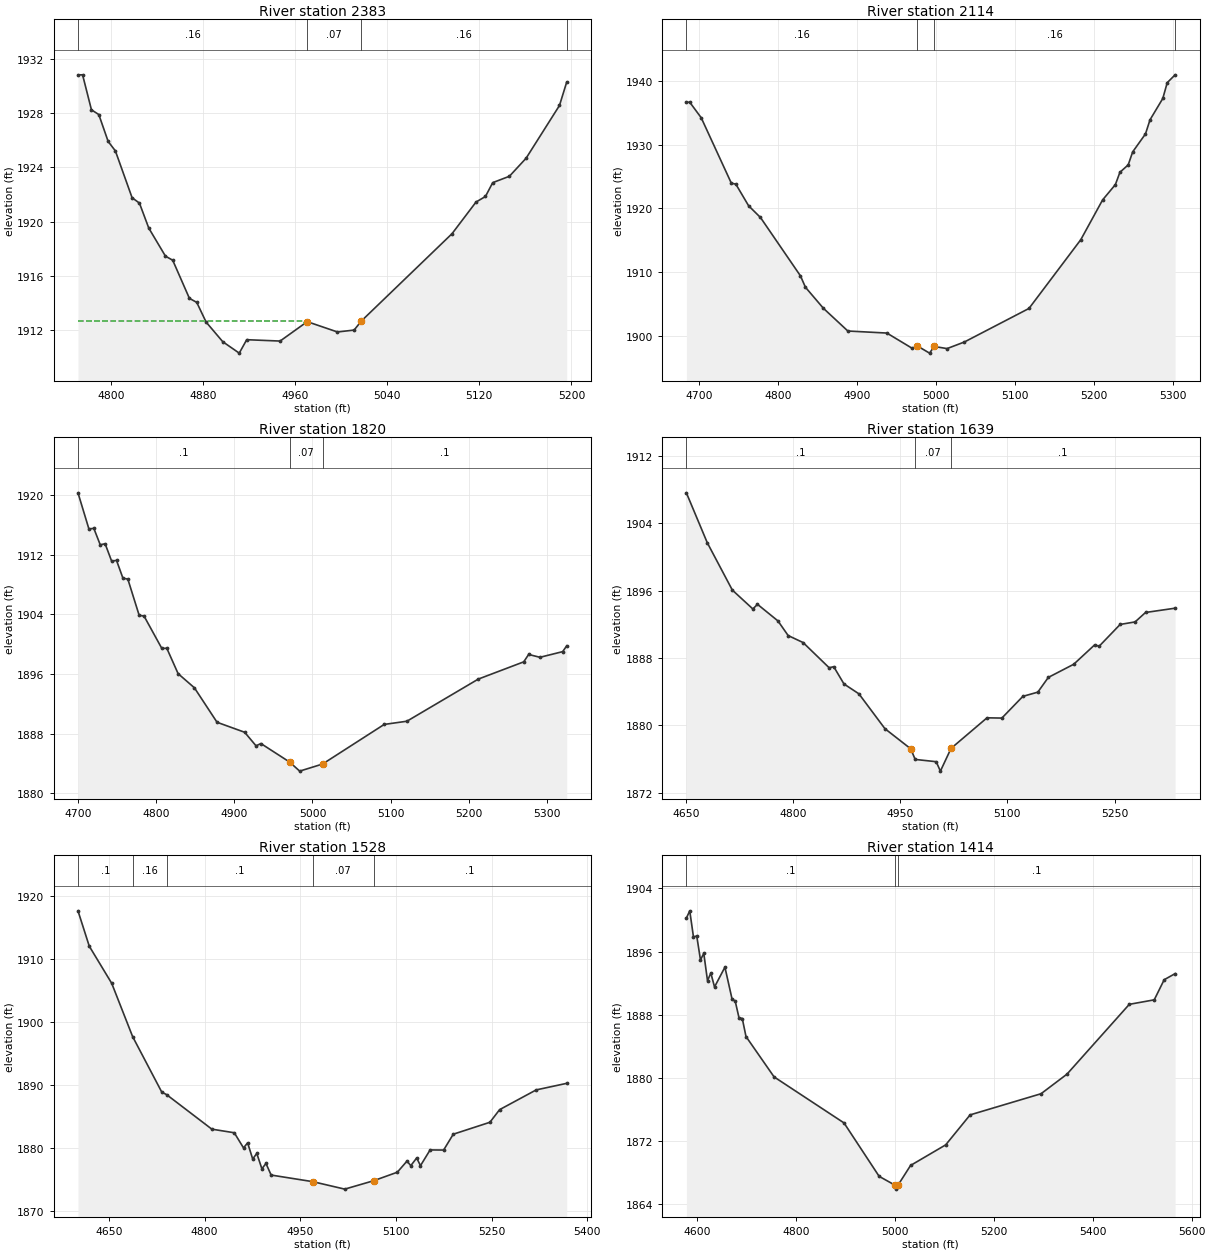
Type RM Length L Ch R = 1 ,2383    ,269,269,269
BEGIN DESCRIPTION:
UNT 0062 IN HEWA 5.0
END DESCRIPTION:
XS GIS Cut Line= 2
      2753599.73     10080079.22      2753263.99     10080339.15
#Sta/Elev= 30
  4771.3 1930.83  4775.3 1930.83    4783 1928.25  4789.4  1927.9  4797.5 1925.92
  4803.8 1925.22  4818.3 1921.77  4824.7 1921.37  4832.8 1919.53  4847.3 1917.46
  4853.6 1917.16  4868.1 1914.35  4874.5 1914.05  4882.6  1912.6  4897.1 1911.15
  4911.4 1910.31  4917.9  1911.3  4946.9  1911.2 4970.45 1912.63  4996.7 1911.87
  5011.2 1912.01  5017.5 1912.68  5096.3 1919.12  5117.1 1921.45  5125.3 1921.86
  5131.6 1922.88  5146.1 1923.35  5160.6 1924.68  5189.6 1928.57  5195.9  1930.3
#Mann= 4 ,-1 , 0
  4771.3     .16       0 4970.45     .07       0  5017.5     .16       0
  5195.9      .1       0
#XS Ineff= 2 , 0
         4967.33 1912.66
Permanent Ineff=
       T       T
Bank Sta=4970.45,5017.5
XS Rating Curve= 0 ,0
Exp/Cntr=0.3,0.1

Type RM Length L Ch R = 1 ,2114    ,294,294,294
BEGIN DESCRIPTION:
Mapping XS d4da1f80
END DESCRIPTION:
XS GIS Cut Line= 2
      2753560.99     10079870.31      2753016.75     10080164.57
#Sta/Elev= 30
  4684.2 1936.62  4688.5 1936.62    4703 1934.19  4741.1 1923.96  4746.8 1923.81
    4763 1920.42    4778 1918.59  4828.6 1909.46  4834.9 1907.68  4857.6 1904.39
  4888.6 1900.83    4938 1900.51  4970.4  1898.1  4976.1 1898.53    4992 1897.37
    4998 1898.41  5014.2 1898.08  5036.1 1899.11  5117.9 1904.36  5183.5 1915.12
  5211.1 1921.34  5227.3 1923.74    5233 1925.66  5243.5 1926.82  5249.2 1928.86
  5265.4 1931.67  5271.1 1933.87  5287.3 1937.21  5292.9 1939.68  5302.9 1940.91
#Mann= 4 ,-1 , 0
  4684.2     .16       0  4976.1     .07       0    4998     .16       0
  5302.9      .1       0
Bank Sta=4976.1,4998
XS Rating Curve= 0 ,0
Exp/Cntr=0.3,0.1

Type RM Length L Ch R = 1 ,1820    ,181,181,181
BEGIN DESCRIPTION:
UNT 0062 IN HEWA 4.0
END DESCRIPTION:
XS GIS Cut Line= 2
      2753404.41      10079580.1      2752905.98     10079959.34
#Sta/Elev= 30
  4699.5 1920.29  4713.5 1915.45  4719.8 1915.53    4728 1913.33  4734.3 1913.46
  4742.6 1911.14  4748.9 1911.23  4757.1 1908.85  4763.4 1908.72  4777.9 1903.87
  4784.2 1903.76    4807 1899.42  4813.3 1899.46  4827.8 1896.05  4848.7 1894.15
  4877.7 1889.53  4913.1 1888.19  4927.7 1886.37  4933.9 1886.68  4970.8 1884.19
  4983.6 1882.98  5012.9 1883.93  5091.9 1889.24    5121 1889.67  5212.5 1895.32
  5270.7 1897.63    5277 1898.62  5291.5 1898.24  5320.6    1899  5325.8 1899.78
#Mann= 3 , 0 , 0
  4699.5      .1       0  4970.8     .07       0  5012.9      .1       0
Bank Sta=4970.8,5012.9
XS Rating Curve= 0 ,0
Exp/Cntr=0.3,0.1

Type RM Length L Ch R = 1 ,1639    ,111,111,111
BEGIN DESCRIPTION:
Mapping XS 29b0bd3a
END DESCRIPTION:
XS GIS Cut Line= 3
      2753322.53     10079377.23      2753103.76     10079559.54
      2752869.37     10079882.47
#Sta/Elev= 30
  4650.9 1907.61  4680.1 1901.69  4715.2 1896.06  4743.9 1893.82  4750.4 1894.37
    4779  1892.4  4793.3 1890.66  4814.2 1889.83  4850.6 1886.84  4857.1 1886.96
  4871.4 1884.91  4892.3 1883.74  4928.7  1879.6  4964.8 1877.21    4971 1875.95
  5000.4 1875.68  5006.3 1874.56  5021.2 1877.26  5071.5 1880.89  5092.3 1880.86
  5121.7 1883.44  5142.6 1883.94  5157.3 1885.69  5192.8 1887.25  5222.2 1889.56
  5228.4 1889.39  5257.8 1891.98  5278.7 1892.28  5293.3  1893.4  5334.7 1893.91
#Mann= 3 ,-1 , 0
  4650.9      .1       0    4971     .07       0  5021.2      .1       0
Bank Sta=4964.8,5021.2
XS Rating Curve= 0 ,0
Exp/Cntr=0.3,0.1

Type RM Length L Ch R = 1 ,1528    ,114,114,114
BEGIN DESCRIPTION:
Mapping XS 4228bd67
END DESCRIPTION:
XS GIS Cut Line= 4
      2753296.45     10079247.06      2753046.47     10079444.96
      2752968.34       10079596.      2752817.85     10079829.52
#Sta/Elev= 30
  4601.3 1917.61    4619 1912.01  4654.2 1906.13    4687 1897.69  4732.8 1888.88
  4740.2  1888.5  4811.3 1883.02  4846.5 1882.45    4861 1880.05  4867.4 1880.85
  4875.4 1878.29  4881.8 1879.18  4889.8 1876.74  4896.2 1877.59  4904.3 1875.75
  4969.8  1874.7  5019.8 1873.52  5065.1 1874.85  5102.3  1876.2  5117.4 1877.96
  5123.4 1877.24  5132.6 1878.45  5138.6 1877.24  5153.7 1879.73  5174.9 1879.71
    5190 1882.22  5247.5 1884.11  5262.7 1886.11  5320.1 1889.24    5368 1890.28
#Mann= 5 ,-1 , 0
  4601.3      .1       0    4687     .16       0  4740.2      .1       0
  4969.8     .07       0  5065.1      .1       0
Bank Sta=4969.8,5065.1
XS Rating Curve= 0 ,0
Exp/Cntr=0.3,0.1

Type RM Length L Ch R = 1 ,1414    ,150,150,150
BEGIN DESCRIPTION:
UNT 0062 IN HEWA 3.0
END DESCRIPTION:
XS GIS Cut Line= 3
      2753241.64     10079156.93      2752709.94     10079634.37
      2752677.39     10079905.63
#Sta/Elev= 30
  4578.8 1900.24  4585.6 1901.16  4593.1 1897.87  4599.8 1897.96  4607.3 1894.94
    4614 1895.77  4621.5  1892.3  4628.2 1893.28  4635.7 1891.51  4656.7 1894.02
  4670.9 1890.04  4677.6 1889.69  4685.1 1887.62  4691.8 1887.51  4699.3 1885.23
  4756.1 1880.11  4897.4 1874.28  4968.4 1867.51  5000.5 1866.39  5003.2 1865.89
  5006.5 1866.39  5031.9 1868.89  5102.9  1871.5  5152.3  1875.3  5295.6 1877.98
    5348 1880.46    5474 1889.31  5524.4 1889.88  5544.5 1892.43  5566.6  1893.2
#Mann= 3 ,-1 , 0
  4578.8      .1       0  5000.5     .07       0  5006.5      .1       0
Bank Sta=5000.5,5006.5
XS Rating Curve= 0 ,0
Exp/Cntr=0.3,0.1

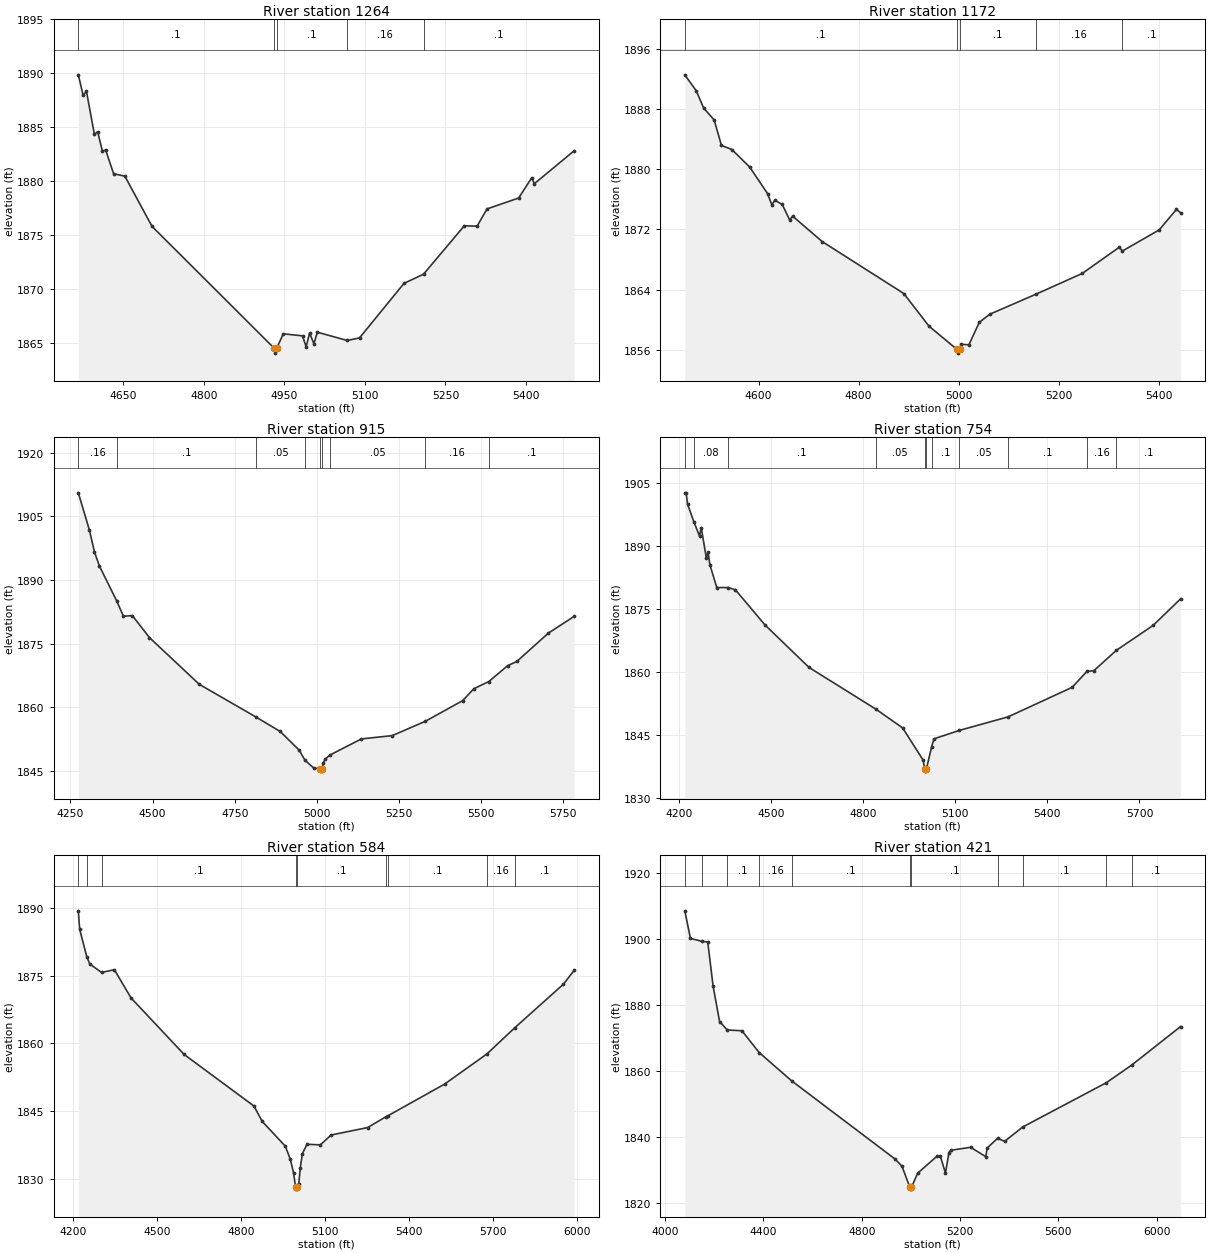
Type RM Length L Ch R = 1 ,1264    ,92,92,92
BEGIN DESCRIPTION:
Mapping XS d654c033
END DESCRIPTION:
XS GIS Cut Line= 4
      2753166.23      10079080.4      2752843.34     10079304.33
      2752744.38     10079429.33      2752603.75     10079773.11
#Sta/Elev= 30
  4566.1 1889.85  4575.1 1887.94  4581.2 1888.33    4596 1884.34  4602.1 1884.58
  4610.9 1882.78    4617 1882.89  4631.8 1880.69  4652.8 1880.46  4703.4 1875.81
  4930.1 1864.57  4932.9 1864.07  4936.1 1864.57    4948 1865.86  4983.8 1865.67
  4990.6 1864.65    4997 1865.93    5005 1864.94  5011.4 1866.01  5067.1 1865.24
    5090 1865.48  5172.8 1870.53  5209.2 1871.38  5285.3 1875.87    5309 1875.83
  5327.6 1877.43  5386.5 1878.44  5410.5 1880.29  5415.9 1879.77  5489.9 1882.82
#Mann= 5 ,-1 , 0
  4566.1      .1       0  4930.1     .07       0  4936.1      .1       0
  5067.1     .16       0  5209.2      .1       0
Bank Sta=4930.1,4936.1
XS Rating Curve= 0 ,0
Exp/Cntr=0.3,0.1

Type RM Length L Ch R = 1 ,1172    ,257,257,257
BEGIN DESCRIPTION:
Mapping XS 51232d2e
END DESCRIPTION:
XS GIS Cut Line= 3
      2753192.28     10078955.39       2752629.8     10079361.62
      2752551.67     10079648.12
#Sta/Elev= 30
  4452.6 1892.54  4475.6 1890.41  4490.3 1888.12  4511.2 1886.55  4525.9 1883.15
  4546.8 1882.61  4582.4 1880.27  4617.9 1876.76  4626.5 1875.27  4632.6 1875.87
  4647.3 1875.31  4662.1 1873.27  4668.2 1873.75  4727.1 1870.38  4890.3 1863.47
  4940.6 1859.13  4996.4 1856.05  4999.1 1855.55  5002.4 1856.05  5005.5 1856.72
  5020.3 1856.66  5041.1 1859.64    5062 1860.72  5153.9 1863.37  5246.8 1866.14
  5321.1 1869.64  5326.8 1869.11  5400.6 1871.93  5435.1 1874.66  5443.4  1874.2
#Mann= 5 ,-1 , 0
  4452.6      .1       0  4996.4     .07       0  5002.4      .1       0
  5153.9     .16       0  5326.8      .1       0
Bank Sta=4996.4,5002.4
XS Rating Curve= 0 ,0
Exp/Cntr=0.3,0.1

Type RM Length L Ch R = 1 ,915     ,161,161,161
BEGIN DESCRIPTION:
UNT 0062 IN HEWA 2.0
END DESCRIPTION:
XS GIS Cut Line= 4
      2753204.64     10078702.43      2752524.98      10079129.5
      2752420.81     10079293.56      2752545.55     10079789.89
#Sta/Elev= 30
  4273.9 1910.56  4307.6 1901.77  4322.9 1896.64  4338.2 1893.29  4390.5 1885.11
  4411.1 1881.47  4438.4 1881.63  4490.2 1876.45  4642.1 1865.42  4814.9  1857.7
  4888.3 1854.31    4946 1849.91  4963.7 1847.52  4989.8 1845.74  5010.1 1845.47
  5012.9 1844.97  5016.1 1845.47  5019.1  1846.9  5025.2 1847.79  5039.1 1848.75
  5135.2 1852.56  5229.2 1853.34  5329.7 1856.71  5443.6 1861.59  5477.3 1864.39
    5523 1866.08  5580.4 1869.83  5608.1 1870.81  5704.2 1877.49  5782.7 1881.45
#Mann= 9 ,-1 , 0
  4273.9     .16       0  4390.5      .1       0  4814.9     .05       0
  4963.7      .1       0  5010.1     .07       0  5016.1      .1       0
  5039.1     .05       0  5329.7     .16       0    5523      .1       0
Bank Sta=5010.1,5016.1
XS Rating Curve= 0 ,0
Exp/Cntr=0.3,0.1

Type RM Length L Ch R = 1 ,754     ,170,170,170
BEGIN DESCRIPTION:
Mapping XS 205d4e83
END DESCRIPTION:
XS GIS Cut Line= 4
      2753171.27     10078624.63      2752411.68     10079008.76
      2752344.41     10079245.31      2752496.11     10079739.43
#Sta/Elev= 30
    4220 1902.56  4224.4 1902.56  4228.9 1899.89  4250.2 1895.54  4267.9 1892.31
  4273.5 1894.31  4290.2 1887.02  4295.8 1888.52  4301.6  1885.5    4324 1880.06
  4361.7 1880.05  4384.9 1879.51  4480.9 1871.18  4624.5 1861.07  4842.3 1851.15
  4929.1 1846.71  4996.4 1838.99  5000.3 1836.94  5003.1 1836.44  5006.3 1836.94
  5023.4 1842.18  5031.2 1844.12  5113.5 1846.11  5272.3 1849.33  5480.9 1856.35
  5528.8 1860.12  5551.6 1860.31  5624.6 1865.13  5744.4 1871.06    5834 1877.38
#Mann= 11 ,-1 , 0
    4220      .1       0  4250.2     .08       0  4361.7      .1       0
  4842.3     .05       0  5000.3    .035       0  5006.3     .05       0
  5023.4      .1       0  5113.5     .05       0  5272.3      .1       0
  5528.8     .16       0  5624.6      .1       0
Bank Sta=5000.3,5006.3
XS Rating Curve= 0 ,0
Exp/Cntr=0.3,0.1

Type RM Length L Ch R = 1 ,584     ,163,163,163
BEGIN DESCRIPTION:
Mapping XS 7324ae08
END DESCRIPTION:
XS GIS Cut Line= 4
       2753077.1     10078556.57      2752272.38     10078889.92
      2752228.11     10079040.96      2752472.41     10079740.07
#Sta/Elev= 30
  4219.3 1889.34  4224.1 1885.27  4250.1 1879.03  4261.1 1877.52  4302.3 1875.71
  4347.7 1876.32  4407.6 1870.06  4596.7 1857.58  4845.6 1846.18  4875.4 1842.77
  4957.9 1837.28  4975.5 1834.39  4987.2 1831.38  4994.2 1828.29  4996.9 1827.79
  5000.2 1828.29  5005.7 1828.88  5011.1 1832.49  5018.8 1835.63    5035 1837.71
  5082.8 1837.58  5121.2 1839.76  5251.8 1841.41    5316 1843.78  5324.5 1844.04
  5526.1 1851.02  5676.9 1857.68  5776.4 1863.48  5949.8  1873.1  5988.3 1876.17
#Mann= 9 ,-1 , 0
  4219.3      .1       0  4250.1     .08       0  4302.3      .1       0
  4994.2     .07       0  5000.2      .1       0    5316     .05       0
  5324.5      .1       0  5676.9     .16       0  5776.4      .1       0
Bank Sta=4994.2,5000.2
XS Rating Curve= 0 ,0
Exp/Cntr=0.3,0.1

Type RM Length L Ch R = 1 ,421     ,320,320,320
BEGIN DESCRIPTION:
Mapping XS db822ab8
END DESCRIPTION:
XS GIS Cut Line= 4
      2753120.86     10078477.09      2752311.01     10078661.97
      2752126.11     10078878.12      2752425.42      10079729.2
#Sta/Elev= 30
  4080.3 1908.51  4103.3 1900.17  4150.9 1899.24  4173.7 1899.08  4195.6 1885.63
  4221.8 1874.98  4253.2 1872.42  4312.9 1872.18  4382.9 1865.57  4515.4 1856.99
  4935.5 1833.34    4964 1831.15  4996.2 1824.71  4998.9 1824.21  5002.2 1824.71
  5027.7 1829.03  5105.7 1834.14  5119.9 1834.24  5140.8 1829.06    5155  1835.3
  5162.7 1835.98  5243.1 1836.88    5305 1834.04  5310.3 1836.66  5353.2 1839.62
  5381.6 1838.68  5455.1 1843.03  5795.5 1856.45  5898.2 1861.77  6097.6 1873.47
#Mann= 11 ,-1 , 0
  4080.3      .1       0  4150.9     .08       0  4253.2      .1       0
  4382.9     .16       0  4515.4      .1       0  4996.2     .07       0
  5002.2      .1       0  5353.2     .05       0  5455.1      .1       0
  5795.5     .16       0  5898.2      .1       0
Bank Sta=4996.2,5002.2
XS Rating Curve= 0 ,0
Exp/Cntr=0.3,0.1

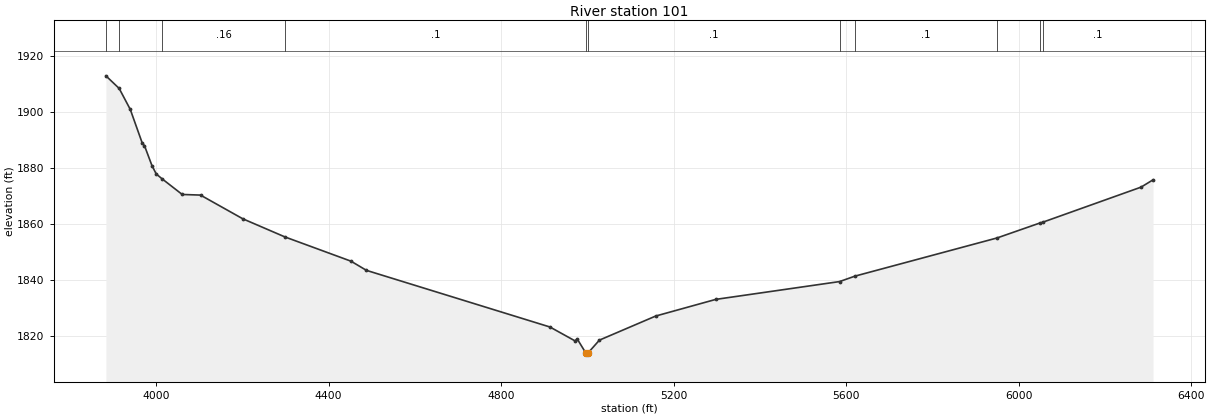
Type RM Length L Ch R = 1 ,101     ,0,0,0
BEGIN DESCRIPTION:
UNT 0062 IN HEWA 1.0
END DESCRIPTION:
XS GIS Cut Line= 4
      2753084.84       10078442.      2752009.36     10078525.33
      2751962.48     10078619.08      2752410.05     10079779.65
#Sta/Elev= 30
  3883.6 1912.78  3914.4 1908.27  3940.1 1900.79    3968 1888.71    3973 1887.86
  3990.3 1880.76  4000.3 1877.75  4013.8 1876.02  4060.5 1870.43  4102.9 1870.21
  4200.9 1861.75    4299 1855.25  4451.7 1846.62  4487.6 1843.34    4913 1823.12
  4970.8 1818.19  4976.4  1818.8  4995.7 1813.94  4998.5 1813.44  5001.7 1813.94
  5027.6 1818.44  5158.2 1827.04  5297.4 1832.98  5584.3 1839.34    5620 1841.28
  5949.4 1854.91  6049.2 1860.27  6056.3 1860.58  6283.2 1873.05    6311 1875.66
#Mann= 11 ,-1 , 0
  3883.6      .1       0  3914.4     .08       0  4013.8     .16       0
    4299      .1       0  4995.7     .07       0  5001.7      .1       0
  5584.3     .05       0    5620      .1       0  5949.4     .05       0
  6049.2     .16       0  6056.3      .1       0
Bank Sta=4995.7,5001.7
XS Rating Curve= 0 ,0
Exp/Cntr=0.3,0.1

Chan Stop Cuts=-1
Use User Specified Reach Order=0
Composite Channel Slope=5