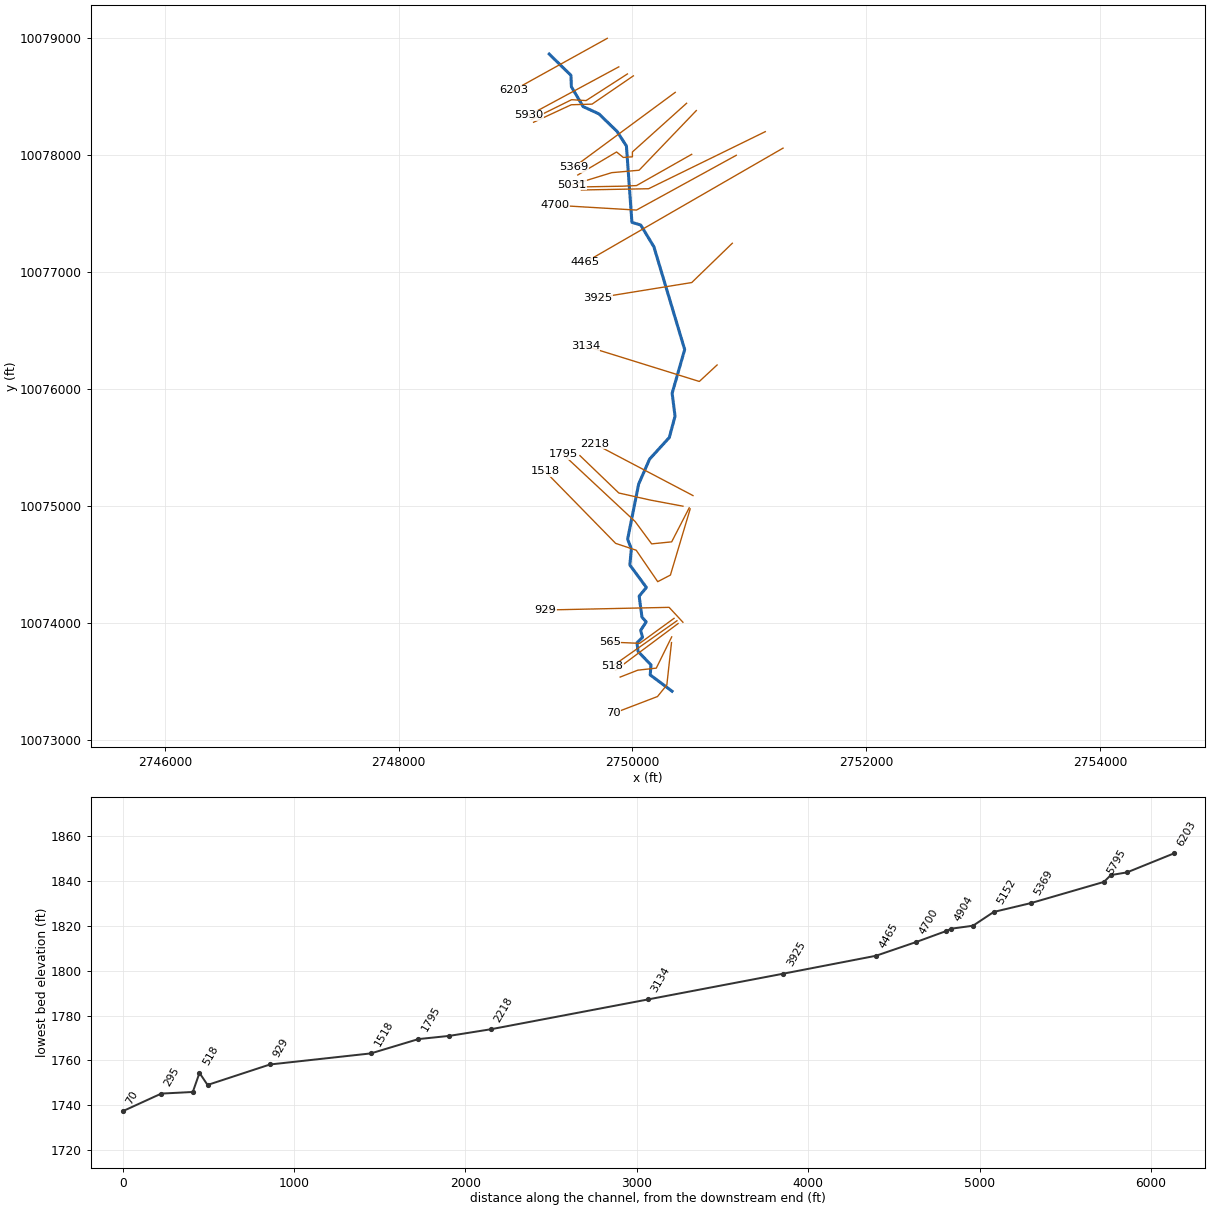
--- UNT 0063 IN HEWA.prj (project) ---

Proj Title=UNT 0063 IN HEWA Base Level Engineering
Current Plan=p01
Default Exp/Contr=0.3,0.1
English Units
Geom File=g01
Flow File=f01
Plan File=p01
Y Axis Title=Elevation
X Axis Title(PF)=Main Channel Distance
X Axis Title(XS)=Station
BEGIN DESCRIPTION:
UNT 0063 IN HEWA
END DESCRIPTION:
DSS Export Rating Curves= 0
DSS Export Rating Curve Sorted= 0
DSS Export Volume Flow Curves= 0
DXF OffsetX= 0
DXF OffsetY= 0
DXF ScaleX= 1
DXF ScaleY= 10

--- UNT 0063 IN HEWA.p01 (plan) ---

Plan Title=Multiple Run
Short Identifier=Multiple
Geom File=g01
Flow File=f01
Subcritical Flow
K Sum by GR= 0
Std Step Tol= 0.01
Critical Tol= 0.01
Num of Std Step Trials= 20
Max Error Tol= 0.3
Flow Tol Ratio= 0.001
Split Flow NTrial= 30
Split Flow Tol= 0.02
Split Flow Ratio= 0.02
Log Output Level= 0
Friction Slope Method= 1
Unsteady Friction Slope Method= 2
Unsteady Bridges Friction Slope Method= 1
Parabolic Critical Depth
Global Vel Dist=  1 , 1 , 1
Global Log Level= 0
CheckData=True
Encroach Param= -1, 0, 0, 0
BEGIN DESCRIPTION:
Multiple Run
END DESCRIPTION:

--- UNT 0063 IN HEWA.f01 (steady flow) ---

Flow Title=Multiple
Program Version=4.10
Number of Profiles= 7
Profile Names=10-year,25-year,50-year,1pct_min,100-year,1pct_plu,500-year
River Rch & RM=UNT 0063 IN HEWA,Reach-1         ,6203
     384     532     655     593     802    1084    1203
Boundary for River Rch & Prof#=UNT 0063 IN HEWA,Reach-1         , 1
Up Type= 0
Dn Type= 3
Dn Slope=0.021
Boundary for River Rch & Prof#=UNT 0063 IN HEWA,Reach-1         , 2
Up Type= 0
Dn Type= 3
Dn Slope=0.021
Boundary for River Rch & Prof#=UNT 0063 IN HEWA,Reach-1         , 3
Up Type= 0
Dn Type= 3
Dn Slope=0.021
Boundary for River Rch & Prof#=UNT 0063 IN HEWA,Reach-1         , 4
Up Type= 0
Dn Type= 3
Dn Slope=0.021
Boundary for River Rch & Prof#=UNT 0063 IN HEWA,Reach-1         , 5
Up Type= 0
Dn Type= 3
Dn Slope=0.021
Boundary for River Rch & Prof#=UNT 0063 IN HEWA,Reach-1         , 6
Up Type= 0
Dn Type= 3
Dn Slope=0.021
Boundary for River Rch & Prof#=UNT 0063 IN HEWA,Reach-1         , 7
Up Type= 0
Dn Type= 3
Dn Slope=0.021
DSS Import GetInterval= 0
DSS Import GetPeak= 0
DSS Import FillOption= 0

--- UNT 0063 IN HEWA.g01 (geometry) ---

Geom Title=Existing Conditions
Program Version=4.10

River Reach=UNT 0063 IN HEWA,Reach-1
Reach XY= 30
      2749287.74     10078866.08      2749473.78     10078683.97
      2749477.25     10078586.75      2749577.95     10078416.61
      2749713.36     10078354.11      2749868.47     10078203.73
      2749948.33     10078079.22      2749995.42     10077426.31
      2750071.09     10077402.82      2750183.67     10077216.51
      2750446.91      10076337.9      2750339.63     10075963.65
      2750364.41     10075767.29      2750315.39     10075584.92
       2750146.6     10075399.81      2750053.11     10075186.52
       2749958.5      10074714.5      2749990.75      10074631.2
      2749977.57     10074493.54      2750119.37     10074301.84
      2750057.42     10074227.13      2750081.35     10074047.51
      2750117.71     10074007.02      2750069.97     10073934.57
       2750086.3     10073875.73       2750038.6     10073828.63
      2750048.18     10073754.09       2750158.6     10073638.75
      2750151.99     10073553.25      2750338.55     10073414.06

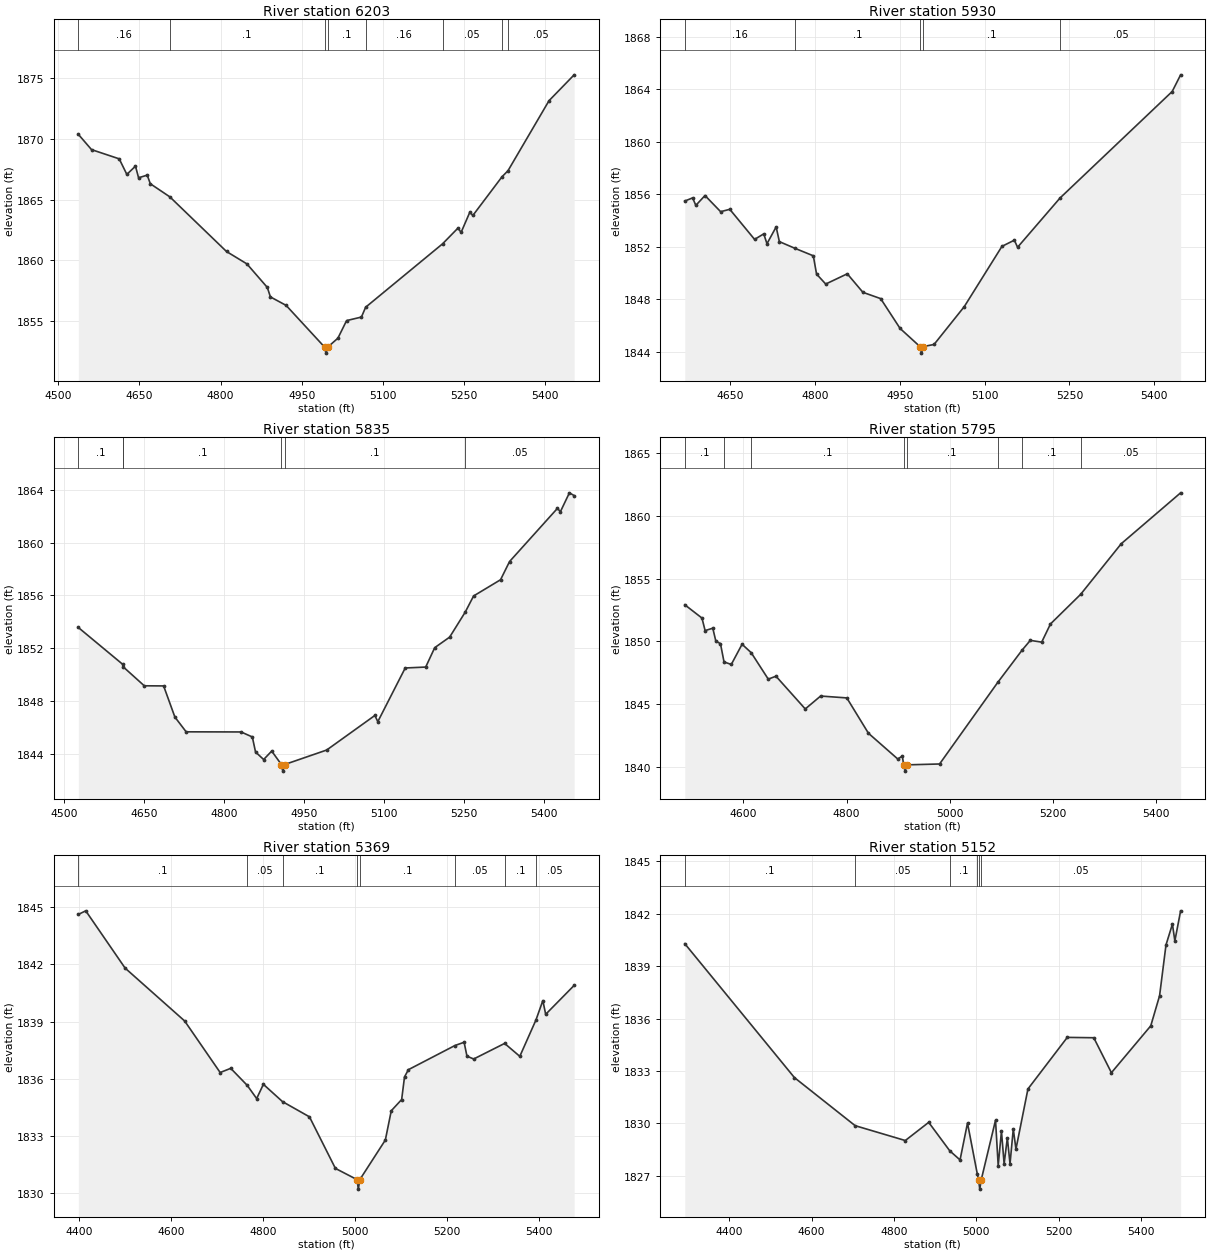
Type RM Length L Ch R = 1 ,6203    ,273,273,273
BEGIN DESCRIPTION:
UNT 0063 IN HEWA 9.0
END DESCRIPTION:
XS GIS Cut Line= 2
      2749784.59     10079000.68      2748982.56     10078556.32
#Sta/Elev= 30
  4536.9 1870.37  4561.3 1869.11  4612.5 1868.35  4626.6 1867.07  4642.6 1867.75
  4648.3 1866.79  4664.3 1867.01    4670  1866.3  4706.1 1865.22  4810.9 1860.72
  4848.6  1859.7  4886.4 1857.76  4892.1 1856.98  4921.2 1856.28  4992.2 1852.85
  4994.9 1852.35  4998.2 1852.85  5016.9 1853.58    5033 1855.03  5060.4 1855.32
  5068.2 1856.13  5210.4 1861.35    5239 1862.65  5244.7 1862.29  5260.8 1863.95
  5266.5 1863.69  5320.5 1866.88  5331.4 1867.37  5407.3 1873.14  5453.8 1875.27
#Mann= 8 ,-1 , 0
  4536.9     .16       0  4706.1      .1       0  4992.2     .07       0
  4998.2      .1       0  5068.2     .16       0  5210.4     .05       0
  5320.5      .1       0  5331.4     .05       0
Bank Sta=4992.2,4998.2
XS Rating Curve= 0 ,0
Exp/Cntr=0.3,0.1

Type RM Length L Ch R = 1 ,5930    ,95,95,95
BEGIN DESCRIPTION:
Mapping XS bd33e2ab
END DESCRIPTION:
XS GIS Cut Line= 2
      2749883.12     10078756.67      2749112.02     10078340.79
#Sta/Elev= 30
  4570.3 1855.48  4584.1 1855.72  4589.8 1855.15    4606  1855.9  4633.6 1854.67
  4649.8 1854.85  4693.6 1852.56  4709.8 1852.98  4715.5 1852.23  4731.7 1853.51
  4737.4 1852.39  4764.4 1851.89  4797.4 1851.31  4803.1 1849.92  4819.3 1849.16
  4857.4 1849.94    4885 1848.53  4916.4 1848.05  4950.7 1845.78  4985.8  1844.4
  4988.5  1843.9  4991.8  1844.4  5010.7 1844.56  5064.1 1847.44  5130.7 1852.03
  5152.6  1852.5  5158.3 1851.96  5233.3 1855.71  5431.5 1863.82  5446.4 1865.09
#Mann= 5 ,-1 , 0
  4570.3     .16       0  4764.4      .1       0  4985.8     .07       0
  4991.8      .1       0  5233.3     .05       0
Bank Sta=4985.8,4991.8
XS Rating Curve= 0 ,0
Exp/Cntr=0.3,0.1

Type RM Length L Ch R = 1 ,5835    ,40,40,40
BEGIN DESCRIPTION:
Mapping XS 83544c93
END DESCRIPTION:
XS GIS Cut Line= 4
      2749956.93     10078695.91      2749603.22     10078468.06
      2749479.52     10078475.66      2749134.46      10078305.3
#Sta/Elev= 30
  4527.4 1853.56  4610.2 1850.78  4611.7 1850.57    4651 1849.14  4687.3 1849.13
  4708.4 1846.77  4729.5 1845.65  4832.5 1845.64  4853.6 1845.26  4859.6 1844.12
  4874.8 1843.55  4889.9 1844.19  4908.1 1843.17  4910.8 1842.67  4914.1 1843.17
    4993 1844.27  5083.3 1846.89  5088.8 1846.42  5140.2 1850.49  5178.6 1850.56
  5195.5 1852.03  5223.5 1852.83  5252.6 1854.72  5268.4 1855.95  5318.9 1857.18
  5335.8 1858.56  5425.5 1862.59  5431.1 1862.34    5448 1863.77  5456.9 1863.56
#Mann= 6 ,-1 , 0
  4527.4      .1       0  4610.2     .16       0  4611.7      .1       0
  4908.1     .07       0  4914.1      .1       0  5252.6     .05       0
Bank Sta=4908.1,4914.1
XS Rating Curve= 0 ,0
Exp/Cntr=0.3,0.1

Type RM Length L Ch R = 1 ,5795    ,426,426,426
BEGIN DESCRIPTION:
Mapping XS 08a652e5
END DESCRIPTION:
XS GIS Cut Line= 4
      2750007.91     10078679.63      2749654.21     10078437.68
      2749476.26     10078432.25      2749154.02     10078282.52
#Sta/Elev= 30
  4486.2 1852.91  4519.5 1851.85  4525.6 1850.85  4540.5 1851.04  4546.5    1850
  4555.4 1849.81  4562.3 1848.35  4576.4 1848.15  4597.3 1849.76    4615 1849.09
  4648.1 1846.98  4663.1 1847.21  4719.9  1844.6  4749.7 1845.63  4800.5 1845.48
  4842.5 1842.66  4899.3 1840.61  4908.2 1840.84  4910.8 1840.14  4913.6 1839.64
  4916.8 1840.14  4980.5 1840.21  5093.2 1846.71  5140.7  1849.3  5156.5 1850.07
  5178.6 1849.93  5195.6 1851.38  5254.1 1853.74  5332.9 1857.78  5448.1 1861.84
#Mann= 8 ,-1 , 0
  4486.2      .1       0  4562.3     .16       0    4615      .1       0
  4910.8     .07       0  4916.8      .1       0  5093.2     .05       0
  5140.7      .1       0  5254.1     .05       0
Bank Sta=4910.8,4916.8
XS Rating Curve= 0 ,0
Exp/Cntr=0.3,0.1

Type RM Length L Ch R = 1 ,5369    ,217,217,217
BEGIN DESCRIPTION:
UNT 0063 IN HEWA 8.0
END DESCRIPTION:
XS GIS Cut Line= 2
      2750366.16     10078538.43      2749498.42     10077898.47
#Sta/Elev= 30
  4399.1 1844.63  4415.2 1844.82  4500.8 1841.81  4630.3 1839.03  4707.5 1836.32
  4730.5 1836.54  4766.2 1835.65  4786.9 1834.95  4801.5  1835.7  4843.1 1834.79
  4901.7 1833.99  4958.1 1831.28  5005.2 1830.69    5008 1830.19  5011.2 1830.69
  5066.7 1832.77  5079.6 1834.31  5102.2  1834.9  5108.4 1836.09  5116.9 1836.47
  5218.1 1837.74    5238 1837.91  5244.2 1837.18  5258.8 1837.03  5326.1 1837.85
  5359.1 1837.17  5394.2 1839.08  5409.2  1840.1  5415.4 1839.38  5477.3  1840.9
#Mann= 8 ,-1 , 0
  4399.1      .1       0  4766.2     .05       0  4843.1      .1       0
  5005.2     .07       0  5011.2      .1       0  5218.1     .05       0
  5326.1      .1       0  5394.2     .05       0
Bank Sta=5005.2,5011.2
XS Rating Curve= 0 ,0
Exp/Cntr=0.3,0.1

Type RM Length L Ch R = 1 ,5152    ,121,121,121
BEGIN DESCRIPTION:
Mapping XS cad12dc3
END DESCRIPTION:
XS GIS Cut Line= 6
      2750463.16     10078444.98      2749999.59     10078028.29
      2749999.59     10077986.62      2749921.47     10077981.41
      2749864.18     10078028.29      2749532.11     10077831.13
#Sta/Elev= 30
  4292.2 1840.28  4558.3 1832.62  4705.7 1829.87  4827.4 1829.02  4884.2 1830.06
  4935.4 1828.43  4960.3 1827.91  4978.4 1830.02  5002.3 1827.09  5005.4 1826.74
  5008.2 1826.24  5011.4 1826.74  5046.4 1830.18  5052.9 1827.59  5060.8 1829.55
  5067.3 1827.69  5075.1 1829.17  5081.6 1827.69  5089.5 1829.68    5096 1828.53
  5125.1 1831.97  5220.6 1834.92  5284.9  1834.9  5327.7  1832.9  5423.2 1835.58
  5444.6  1837.3  5460.2 1840.21  5475.8  1841.4  5481.7 1840.44  5495.7 1842.16
#Mann= 6 ,-1 , 0
  4292.2      .1       0  4705.7     .05       0  4935.4      .1       0
  5002.3     .05       0  5005.4     .07       0  5011.4     .05       0
Bank Sta=5005.4,5011.4
XS Rating Curve= 0 ,0
Exp/Cntr=0.3,0.1

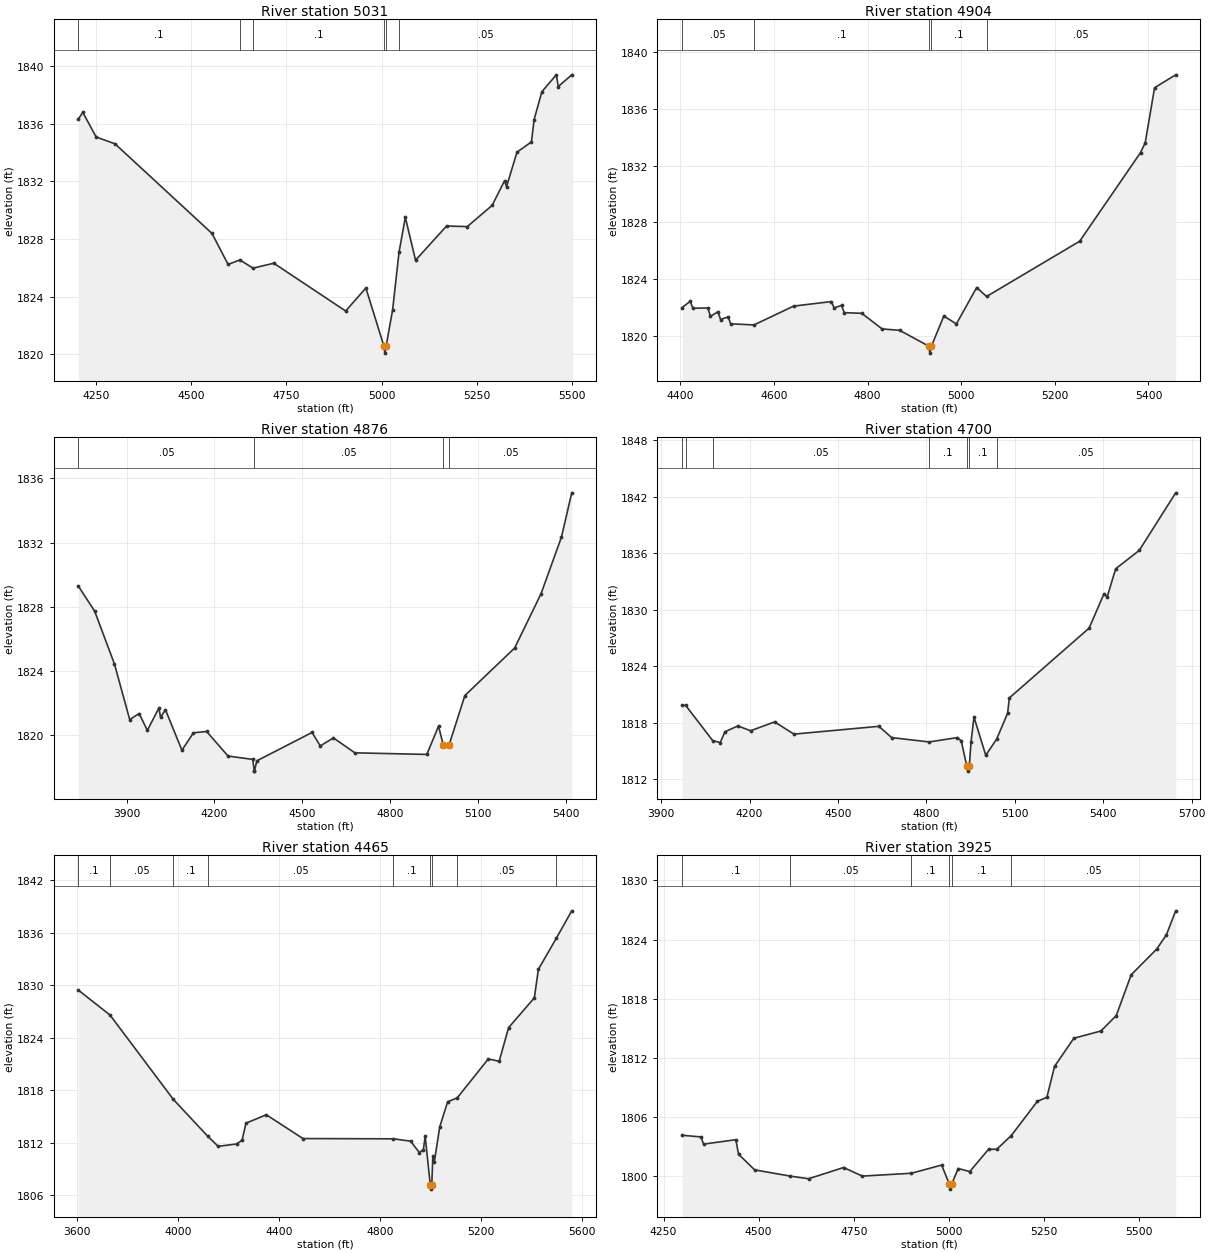
Type RM Length L Ch R = 1 ,5031    ,127,127,127
BEGIN DESCRIPTION:
Mapping XS a0e320c7
END DESCRIPTION:
XS GIS Cut Line= 4
       2750546.5     10078382.49      2750056.88     10077872.04
      2749822.51     10077851.21      2749483.97     10077747.04
#Sta/Elev= 30
    4203  1836.3    4215 1836.78  4250.2 1835.07  4299.6  1834.6  4554.4 1828.39
  4596.8 1826.24  4627.8 1826.55  4662.2 1825.98  4716.9 1826.32  4905.7 1823.01
  4958.9  1824.6  5006.1 1820.59  5008.9 1820.09  5012.1 1820.59  5029.2  1823.1
    5046 1827.09  5062.5  1829.5  5089.4 1826.53  5170.8  1828.9  5225.2 1828.86
  5290.6 1830.33  5323.3 1832.04  5328.5 1831.63  5355.9 1834.02  5393.9 1834.73
  5400.9 1836.28  5421.3 1838.21  5459.3 1839.38  5464.5 1838.57  5499.8 1839.38
#Mann= 6 ,-1 , 0
    4203      .1       0  4627.8     .05       0  4662.2      .1       0
  5006.1     .07       0  5012.1      .1       0    5046     .05       0
Bank Sta=5006.1,5012.1
XS Rating Curve= 0 ,0
Exp/Cntr=0.3,0.1

Type RM Length L Ch R = 1 ,4904    ,28,28,28
BEGIN DESCRIPTION:
Mapping XS c2438f18
END DESCRIPTION:
XS GIS Cut Line= 4
       2750506.9     10078008.05      2750034.65     10077740.68
      2749914.86     10077735.47      2749523.42     10077728.52
#Sta/Elev= 30
  4404.1 1821.99  4421.3 1822.43    4427 1821.94  4458.8 1821.96  4464.6 1821.37
  4480.5 1821.69  4486.2 1821.14  4502.1 1821.33  4507.8 1820.84  4557.4 1820.76
  4642.1 1822.09  4722.9 1822.41  4728.6 1821.96  4744.5 1822.14  4750.3 1821.63
  4787.8 1821.58  4831.1 1820.48  4868.6 1820.38  4930.6 1819.27  4933.3 1818.77
  4936.6 1819.27    4963 1821.39  4989.8 1820.83  5033.1  1823.4  5054.4 1822.77
  5253.1 1826.67  5383.1 1832.93  5393.1 1833.62  5413.1 1837.51  5458.2 1838.42
#Mann= 5 ,-1 , 0
  4404.1     .05       0  4557.4      .1       0  4930.6     .07       0
  4936.6      .1       0  5054.4     .05       0
Bank Sta=4930.6,4936.6
XS Rating Curve= 0 ,0
Exp/Cntr=0.3,0.1

Type RM Length L Ch R = 1 ,4876    ,176,176,176
BEGIN DESCRIPTION:
UNT 0063 IN HEWA 7.0
END DESCRIPTION:
XS GIS Cut Line= 3
       2751136.6     10078202.08      2750138.33      10077713.8
      2749563.32     10077702.95
#Sta/Elev= 30
  3734.9  1829.3    3791 1827.73  3858.6 1824.44  3910.9 1820.97  3943.1 1821.35
  3971.1  1820.3  4010.6 1821.69  4016.2 1821.12  4033.1 1821.58  4089.3 1819.06
  4128.7 1820.15  4173.7 1820.23  4246.8  1818.7  4331.3 1818.49  4336.6 1817.76
  4337.1 1817.76  4345.1  1818.4  4533.9 1820.17    4562 1819.33    4607 1819.83
  4680.1  1818.9  4926.1  1818.8  4966.1 1820.56 4982.27 1819.39 5002.55 1819.41
  5056.1 1822.47  5226.1 1825.43  5316.1  1828.8  5386.1 1832.34  5421.3  1835.1
#Mann= 4 ,-1 , 0
  3734.9     .05       0  4337.1     .05       0 4982.27     .07       0
 5002.55     .05       0
Bank Sta=4982.27,5002.55
XS Rating Curve= 0 ,0
Exp/Cntr=0.3,0.1

Type RM Length L Ch R = 1 ,4700    ,235,235,235
BEGIN DESCRIPTION:
Mapping XS 40f79840
END DESCRIPTION:
XS GIS Cut Line= 3
      2750888.54     10077999.83      2750034.35     10077531.07
      2749335.15     10077572.74
#Sta/Elev= 30
  3971.1 1819.85  3983.1 1819.82  4074.5 1816.09  4100.2 1815.87  4116.3 1817.02
  4159.9 1817.64  4203.5 1817.13    4285 1818.07  4350.4 1816.77  4638.5  1817.6
  4682.1  1816.4  4809.2 1815.94  4904.8  1816.4    4918 1816.07  4937.3 1813.34
    4940 1812.84  4943.3 1813.34  4945.5 1813.34  4951.4 1815.93  4961.4 1818.58
  5001.4 1814.52  5038.6 1816.26  5075.4 1818.98  5081.6 1820.62  5352.1 1828.03
  5402.2 1831.65  5413.8 1831.38  5442.2 1834.33  5522.4 1836.29  5645.9  1842.4
#Mann= 7 ,-1 , 0
  3971.1     .05       0  3983.1      .1       0  4074.5     .05       0
  4809.2      .1       0  4937.3     .07       0  4943.3      .1       0
  5038.6     .05       0
Bank Sta=4937.3,4943.3
XS Rating Curve= 0 ,0
Exp/Cntr=0.3,0.1

Type RM Length L Ch R = 1 ,4465    ,540,540,540
BEGIN DESCRIPTION:
UNT 0063 IN HEWA 6.0
END DESCRIPTION:
XS GIS Cut Line= 2
       2751288.5     10078061.02       2749595.8     10077084.46
#Sta/Elev= 30
  3604.3 1829.45  3730.1 1826.59  3981.1 1816.94  4116.7 1812.75  4158.5 1811.58
  4231.4 1811.85  4252.9 1812.27  4268.7 1814.23  4349.1 1815.19  4494.2 1812.47
  4852.7 1812.44  4920.5 1812.17  4955.2 1810.86    4971 1811.21  4978.2 1812.73
  4998.3 1807.19    5001 1806.69  5004.3 1807.19  5008.3 1810.43  5014.1 1809.76
  5035.9 1813.82  5067.2 1816.68  5104.9 1817.12  5228.1 1821.57  5271.2 1821.31
  5308.5 1825.15  5410.5 1828.56  5426.3 1831.81  5498.1  1835.4  5558.5  1838.5
#Mann= 9 ,-1 , 0
  3604.3      .1       0  3730.1     .05       0  3981.1      .1       0
  4116.7     .05       0  4852.7      .1       0  4998.3     .07       0
  5004.3      .1       0  5104.9     .05       0  5498.1     .08       0
Bank Sta=4998.3,5004.3
XS Rating Curve= 0 ,0
Exp/Cntr=0.3,0.1

Type RM Length L Ch R = 1 ,3925    ,791,791,791
BEGIN DESCRIPTION:
UNT 0063 IN HEWA 5.0
END DESCRIPTION:
XS GIS Cut Line= 3
      2750854.49     10077247.23      2750507.25     10076910.85
       2749704.3     10076780.64
#Sta/Elev= 30
  4298.9 1804.17  4348.2    1804  4355.1 1803.27    4440 1803.72    4447 1802.25
  4489.4 1800.66  4581.6 1800.04  4630.9 1799.76    4723  1800.9  4772.4 1800.03
  4901.5 1800.32  4980.8 1801.15    5001 1799.21  5003.7 1798.71    5007 1799.21
  5024.3  1800.8  5054.7 1800.49  5104.1 1802.75  5125.6 1802.75  5163.8 1804.14
  5232.4 1807.61  5257.3 1808.01  5277.5 1811.15  5328.2    1814  5399.1 1814.73
  5439.6 1816.29  5478.9 1820.43  5545.6 1823.02  5571.3 1824.47  5595.8 1826.91
#Mann= 6 ,-1 , 0
  4298.9      .1       0  4581.6     .05       0  4901.5      .1       0
    5001     .07       0    5007      .1       0  5163.8     .05       0
Bank Sta=5001,5007
XS Rating Curve= 0 ,0
Exp/Cntr=0.3,0.1

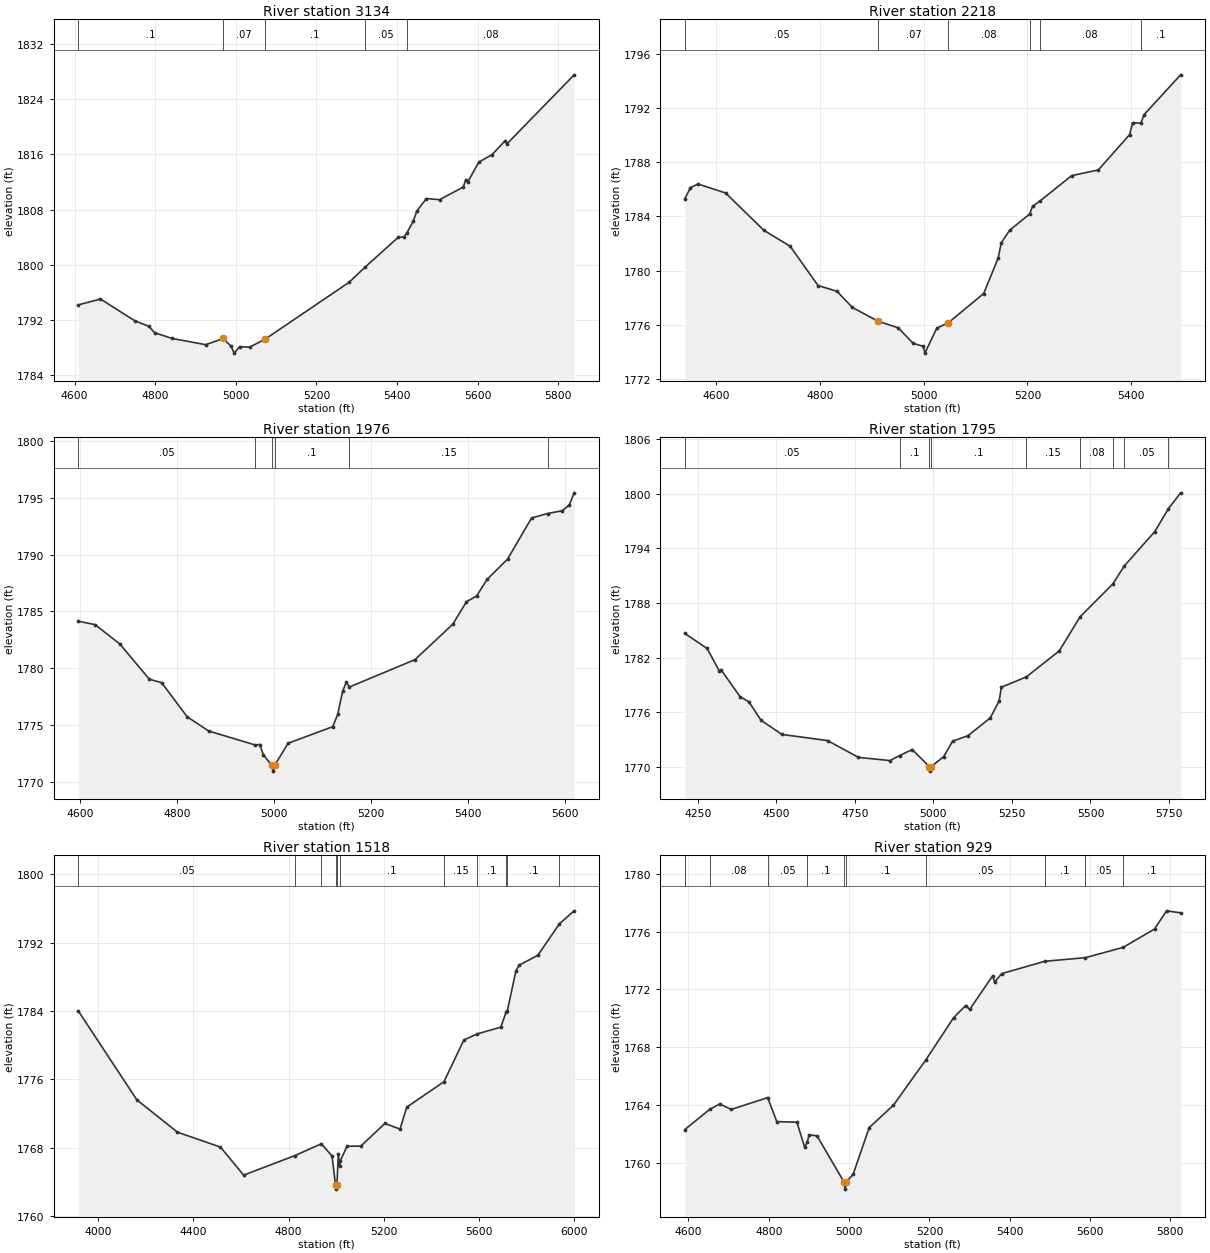
Type RM Length L Ch R = 1 ,3134    ,916,916,916
BEGIN DESCRIPTION:
UNT 0063 IN HEWA 4.0
END DESCRIPTION:
XS GIS Cut Line= 3
       2750724.3     10076205.58      2750572.36     10076064.49
      2749595.77     10076368.32
#Sta/Elev= 30
  4609.4 1794.19  4664.3 1795.04  4749.4 1791.89  4784.5 1791.08  4798.7 1790.16
  4841.8 1789.33  4925.5 1788.42  4969.2 1789.33  4988.4 1788.18  4996.2  1787.2
  5009.3 1788.13  5034.3 1788.07  5072.2  1789.2  5281.6 1797.48  5319.8 1799.61
  5402.7 1803.96  5417.8 1804.05  5424.5 1804.62  5440.4 1806.32  5449.2 1807.79
    5473  1809.6  5505.5 1809.43  5564.4 1811.26  5570.6 1812.34  5575.8 1812.03
  5603.2 1814.88  5635.7 1815.96  5668.2 1817.97  5673.5 1817.56  5839.5 1827.52
#Mann= 5 ,-1 , 0
  4609.4      .1       0  4969.2     .07       0  5072.2      .1       0
  5319.8     .05       0  5424.5     .08       0
Bank Sta=4969.2,5072.2
XS Rating Curve= 0 ,0
Exp/Cntr=0.3,0.1

Type RM Length L Ch R = 1 ,2218    ,242,242,242
BEGIN DESCRIPTION:
UNT 0063 IN HEWA 3.0
END DESCRIPTION:
XS GIS Cut Line= 2
      2750518.07     10075087.95      2749672.65     10075532.33
#Sta/Elev= 30
  4540.1 1785.29    4551 1786.13  4565.6 1786.39  4618.7 1785.73  4692.2 1782.98
    4743  1781.8  4796.8  1778.9  4833.4 1778.47  4862.9 1777.28  4912.6 1776.26
  4951.1 1775.78  4980.2 1774.63  4999.8 1774.41  5002.6 1773.91  5025.4 1775.75
    5048 1776.16  5115.8 1778.31  5143.8 1780.93  5149.7 1782.05  5165.9 1782.98
  5204.2 1784.17    5210 1784.74  5223.4 1785.11  5285.3 1787.01  5336.6 1787.43
    5397 1790.04  5402.7 1790.91  5418.7 1790.89  5424.7 1791.51  5495.2 1794.45
#Mann= 6 ,-1 , 0
  4540.1     .05       0  4912.6     .07       0    5048     .08       0
  5204.2     .15       0  5223.4     .08       0  5418.7      .1       0
Bank Sta=4912.6,5048
XS Rating Curve= 0 ,0
Exp/Cntr=0.3,0.1

Type RM Length L Ch R = 1 ,1976    ,181,181,181
BEGIN DESCRIPTION:
Mapping XS b7a5d004
END DESCRIPTION:
XS GIS Cut Line= 4
      2750432.49      10074997.1      2750154.72     10075049.18
      2749883.45     10075109.94      2749550.49     10075429.93
#Sta/Elev= 30
  4596.5 1784.14  4631.1 1783.84    4682 1782.14    4743 1779.04  4768.3 1778.74
  4820.9 1775.74  4865.1 1774.49  4961.2 1773.26  4970.6  1773.3  4977.8 1772.42
  4995.2 1771.46    4998 1770.96  5001.2 1771.46    5029 1773.41  5121.2 1774.87
  5131.5 1775.97  5141.7 1778.03  5149.2 1778.76  5155.6 1778.36  5290.5 1780.76
  5368.5 1783.87  5396.8 1785.85  5417.9 1786.37  5439.2 1787.81  5481.7 1789.61
  5531.1 1793.22    5564 1793.61  5594.6 1793.86  5608.8 1794.36  5618.9 1795.43
#Mann= 6 ,-1 , 0
  4596.5     .05       0  4961.2      .1       0  4995.2     .07       0
  5001.2      .1       0  5155.6     .15       0    5564     .05       0
Bank Sta=4995.2,5001.2
XS Rating Curve= 0 ,0
Exp/Cntr=0.3,0.1

Type RM Length L Ch R = 1 ,1795    ,277,277,277
BEGIN DESCRIPTION:
Mapping XS db2d4028
END DESCRIPTION:
XS GIS Cut Line= 5
      2750485.44     10074982.81      2750335.68     10074691.98
      2750164.24     10074674.62      2750023.18     10074865.59
       2749407.9     10075439.71
#Sta/Elev= 30
  4208.6 1784.65  4279.6    1783  4318.3 1780.53  4323.9 1780.67  4384.8 1777.69
  4412.6 1777.14  4451.3 1775.11  4517.8 1773.55  4662.9 1772.88  4761.4 1771.03
  4861.6 1770.68  4892.4 1771.23  4932.5 1771.89  4987.1 1770.02  4989.8 1769.52
  4993.1 1770.02  5032.6 1771.11  5060.9  1772.8  5110.3 1773.42  5181.1 1775.37
  5209.4 1777.25  5216.3 1778.74  5295.7 1779.87  5400.4 1782.72    5467 1786.48
  5571.2 1790.09  5607.7 1792.07  5704.3 1795.82  5748.4 1798.37    5787  1800.1
#Mann= 9 ,-1 , 0
  4208.6     .05       0  4892.4      .1       0  4987.1     .07       0
  4993.1      .1       0  5295.7     .15       0    5467     .08       0
  5571.2     .15       0  5607.7     .05       0  5748.4      .1       0
Bank Sta=4987.1,4993.1
XS Rating Curve= 0 ,0
Exp/Cntr=0.3,0.1

Type RM Length L Ch R = 1 ,1518    ,589,589,589
BEGIN DESCRIPTION:
Mapping XS 7ffdf0d4
END DESCRIPTION:
XS GIS Cut Line= 6
      2750494.09     10074974.07      2750324.83     10074407.69
      2750216.32     10074351.27      2750031.86     10074620.36
      2749856.08     10074678.96      2749253.15      10075294.9
#Sta/Elev= 30
  3915.4    1784  4161.5  1773.6  4332.3 1769.81  4513.7 1768.06  4611.1 1764.78
  4826.4 1767.06  4938.5 1768.45  4983.3 1767.01  4997.8 1763.64  5000.6 1763.14
  5003.8 1763.64  5009.6 1767.26  5014.9 1765.79  5017.7 1766.45  5046.5 1768.16
  5104.5 1768.18  5205.7 1770.83  5269.4 1770.17  5297.7 1772.74  5454.2 1775.71
  5538.1  1780.6  5594.4 1781.31  5693.6  1782.1  5716.8 1783.93  5720.8 1783.98
  5757.3 1788.71  5771.4 1789.37  5849.2 1790.51  5940.6 1794.21  6002.3 1795.72
#Mann= 11 ,-1 , 0
  3915.4     .05       0  4826.4     .15       0  4938.5     .05       0
  4997.8     .04       0  5003.8     .05       0  5017.7      .1       0
  5454.2     .15       0  5594.4      .1       0  5716.8     .08       0
  5720.8      .1       0  5940.6     .08       0
Bank Sta=4997.8,5003.8
XS Rating Curve= 0 ,0
Exp/Cntr=0.3,0.1

Type RM Length L Ch R = 1 ,929     ,364,364,364
BEGIN DESCRIPTION:
UNT 0063 IN HEWA 2.0
END DESCRIPTION:
XS GIS Cut Line= 3
      2750431.98     10074004.09      2750313.69     10074131.48
      2749253.48     10074108.73
#Sta/Elev= 30
  4591.1 1762.31  4653.3 1763.71  4678.2 1764.08  4706.6  1763.7  4797.3 1764.52
  4820.2 1762.86  4870.2 1762.82  4889.2 1761.11  4895.9 1761.42  4900.2 1761.94
  4920.2 1761.88  4987.2 1758.69    4990 1758.19  4993.2 1758.69  5010.2 1759.22
  5050.2 1762.45  5110.3 1763.99  5191.7 1767.15  5260.3 1770.05  5290.3 1770.89
  5300.3 1770.62  5357.3 1772.94  5362.3 1772.52  5380.3  1773.1  5487.5 1773.95
    5588  1774.2  5682.1 1774.91  5760.4 1776.18  5790.4 1777.44  5825.4  1777.3
#Mann= 10 ,-1 , 0
  4591.1     .05       0  4653.3     .08       0  4797.3     .05       0
  4895.9      .1       0  4987.2     .07       0  4993.2      .1       0
  5191.7     .05       0  5487.5      .1       0    5588     .05       0
  5682.1      .1       0
Bank Sta=4987.2,4993.2
XS Rating Curve= 0 ,0
Exp/Cntr=0.3,0.1

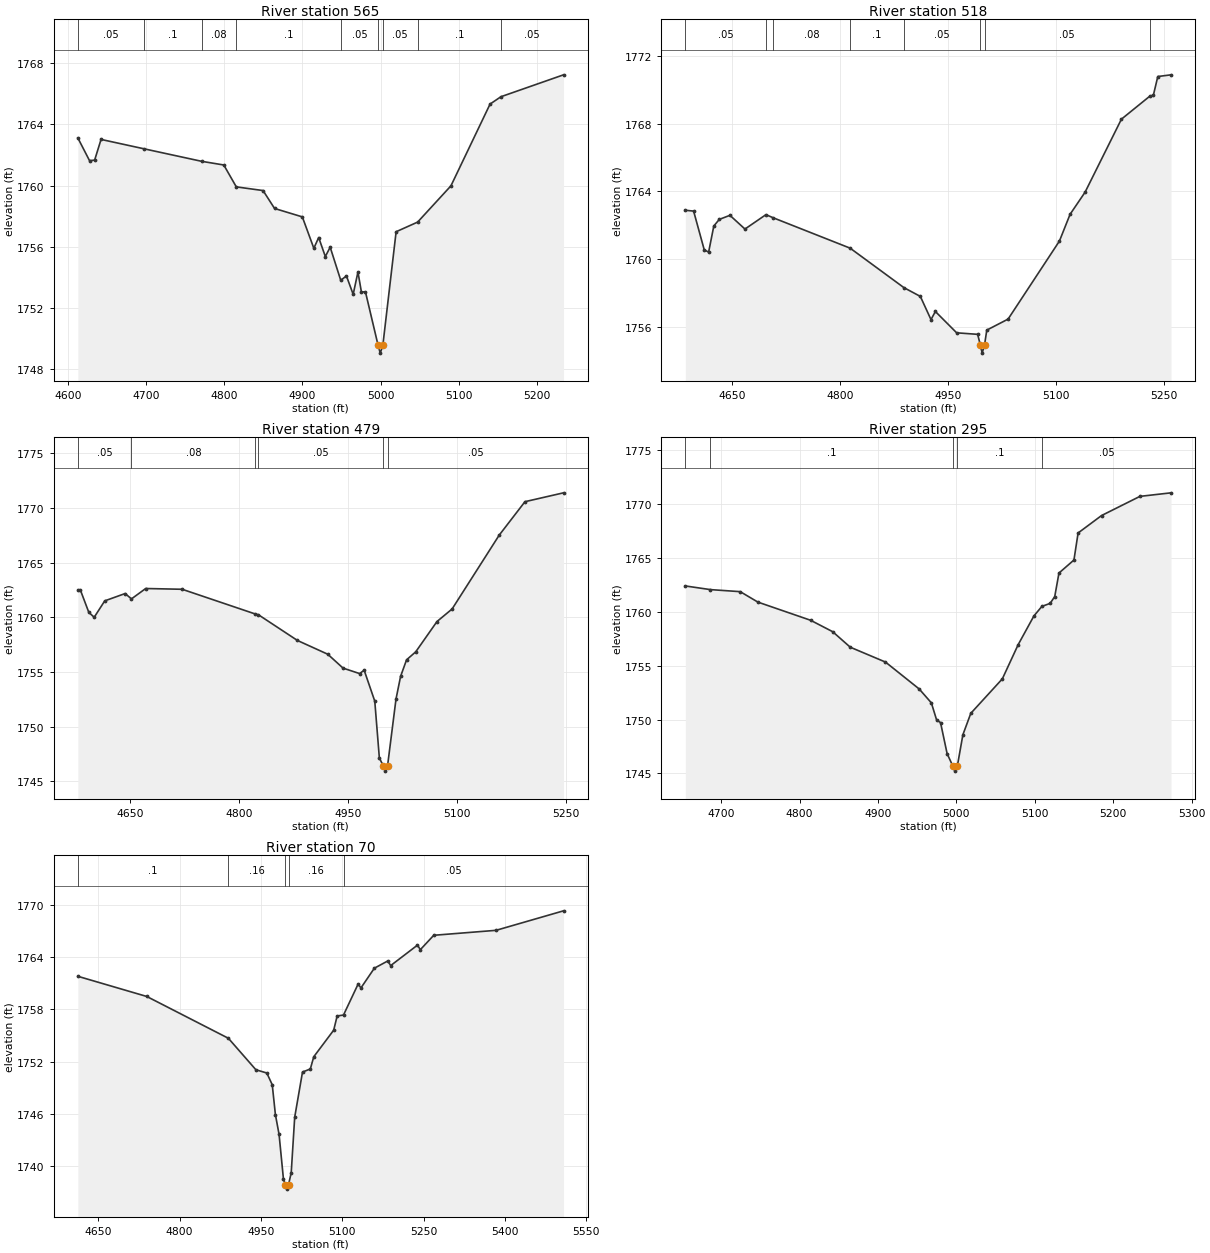
Type RM Length L Ch R = 1 ,565     ,47,47,47
BEGIN DESCRIPTION:
Mapping XS 1d8c4e84
END DESCRIPTION:
XS GIS Cut Line= 3
      2750355.85     10074037.35       2750061.8     10073823.59
      2749804.66     10073834.44
#Sta/Elev= 30
  4612.9 1763.12  4627.9 1761.63  4634.4 1761.67  4642.6 1763.02  4697.3 1762.41
  4771.2 1761.59  4799.5 1761.35  4815.5 1759.92  4849.7 1759.68  4864.4 1758.51
  4899.9 1757.96  4914.6 1755.91  4920.8 1756.61  4929.3 1755.37  4935.5 1755.98
    4949 1753.82  4956.3  1754.1  4964.9  1752.9    4971 1754.36  4975.4 1753.06
  4980.6 1753.06  4996.8 1749.56  4999.5 1749.06  5002.8 1749.56  5019.8 1756.99
  5047.3 1757.62  5089.9 1759.99  5139.9 1765.33  5153.8 1765.81  5233.8 1767.24
#Mann= 9 ,-1 , 0
  4612.9     .05       0  4697.3      .1       0  4771.2     .08       0
  4815.5      .1       0    4949     .05       0  4996.8     .04       0
  5002.8     .05       0  5047.3      .1       0  5153.8     .05       0
Bank Sta=4996.8,5002.8
XS Rating Curve= 0 ,0
Exp/Cntr=0.3,0.1

Type RM Length L Ch R = 1 ,518     ,39,39,39
BEGIN DESCRIPTION:
Mapping XS 45e7913b
END DESCRIPTION:
XS GIS Cut Line= 2
      2750380.85     10074016.76      2749828.56     10073627.99
#Sta/Elev= 30
  4584.8 1762.89  4596.3 1762.84  4611.1 1760.55  4617.2 1760.42  4624.4 1761.96
    4632 1762.35  4646.8 1762.59  4667.7 1761.78  4696.9 1762.63  4706.7 1762.45
    4814 1760.65  4888.7 1758.32  4911.6  1757.8  4926.4 1756.43  4932.5 1756.91
  4962.1 1755.65  4991.3 1755.56  4994.9 1754.95  4997.6 1754.45  5000.9 1754.95
    5004 1755.81  5033.6 1756.46    5105 1761.07  5119.8 1762.65  5140.7 1763.96
  5191.2 1768.27    5231 1769.64  5235.6 1769.68  5241.8 1770.79  5260.2 1770.89
#Mann= 8 ,-1 , 0
  4584.8     .05       0  4696.9      .1       0  4706.7     .08       0
    4814      .1       0  4888.7     .05       0  4994.9     .04       0
  5000.9     .05       0    5231      .1       0
Bank Sta=4994.9,5000.9
XS Rating Curve= 0 ,0
Exp/Cntr=0.3,0.1

Type RM Length L Ch R = 1 ,479     ,184,184,184
BEGIN DESCRIPTION:
Mapping XS a451db68
END DESCRIPTION:
XS GIS Cut Line= 2
      2750390.55     10073992.84      2749855.64     10073593.56
#Sta/Elev= 30
  4578.6 1762.51    4582 1762.51  4593.7 1760.45  4601.1    1760  4615.6  1761.5
  4643.6 1762.17  4652.3 1761.68  4671.9 1762.63    4722 1762.56  4822.5  1760.3
  4826.8 1760.23  4880.4 1757.88  4922.1 1756.62  4943.1 1755.35  4965.9 1754.85
  4972.1 1755.16  4986.7 1752.33    4993 1747.13  4998.3 1746.43  5001.1 1745.93
  5004.3 1746.43  5015.9 1752.53  5022.2  1754.6  5030.4 1756.11    5043 1756.84
  5072.2 1759.61    5093 1760.76  5157.7 1767.51  5193.1 1770.57  5246.1 1771.38
#Mann= 6 ,-1 , 0
  4578.6     .05       0  4652.3     .08       0  4822.5      .1       0
  4826.8     .05       0  4998.3     .04       0  5004.3     .05       0
Bank Sta=4998.3,5004.3
XS Rating Curve= 0 ,0
Exp/Cntr=0.3,0.1

Type RM Length L Ch R = 1 ,295     ,225,225,225
BEGIN DESCRIPTION:
Mapping XS 95b75f96
END DESCRIPTION:
XS GIS Cut Line= 4
      2750335.86     10073878.71      2750203.91     10073611.34
      2750045.92     10073593.98      2749894.85     10073534.94
#Sta/Elev= 30
  4654.4 1762.41  4686.4 1762.07  4724.4 1761.88  4746.9 1760.91  4814.2 1759.22
  4842.3 1758.16  4864.7 1756.72  4909.6 1755.34  4952.6 1752.84  4968.1 1751.55
  4974.8 1749.96  4979.8 1749.72  4988.2 1746.83  4995.3 1745.71    4998 1745.21
  5001.3 1745.71  5008.3 1748.59  5018.4 1750.58  5058.6 1753.78  5078.8 1756.96
  5098.9 1759.63    5109 1760.51  5119.5 1760.79  5125.4 1761.42  5130.8 1763.61
  5149.9 1764.82  5155.2 1767.33  5185.1 1768.95    5234 1770.73  5273.7 1771.06
#Mann= 5 ,-1 , 0
  4654.4     .08       0  4686.4      .1       0  4995.3     .07       0
  5001.3      .1       0    5109     .05       0
Bank Sta=4995.3,5001.3
XS Rating Curve= 0 ,0
Exp/Cntr=0.3,0.1

Type RM Length L Ch R = 1 ,70      ,0,0,0
BEGIN DESCRIPTION:
UNT 0063 IN HEWA 1.0
END DESCRIPTION:
XS GIS Cut Line= 4
      2750334.12     10073830.12      2750294.18     10073467.24
      2750214.32     10073368.28      2749837.57     10073224.18
#Sta/Elev= 30
  4612.5 1761.79  4739.7 1759.47  4890.1 1754.67  4940.9 1751.05    4961 1750.68
    4971 1749.33  4976.8 1745.91  4983.6 1743.62  4991.6 1738.53    4995 1737.84
  4997.7 1737.34    5001 1737.84    5006 1739.23  5012.4  1745.6  5026.8 1750.79
  5041.2 1751.14  5047.6 1752.55  5084.3  1755.6  5090.7 1757.23  5102.4 1757.34
  5129.3 1760.89  5134.6 1760.46  5159.3 1762.72    5184 1763.55  5189.4 1763.02
  5238.8 1765.37  5244.1 1764.85  5268.8  1766.5  5383.7 1767.07  5508.1 1769.31
#Mann= 5 ,-1 , 0
  4612.5      .1       0  4890.1     .16       0    4995     .07       0
    5001     .16       0  5102.4     .05       0
Bank Sta=4995,5001
XS Rating Curve= 0 ,0
Exp/Cntr=0.3,0.1

Chan Stop Cuts=-1
Use User Specified Reach Order=0
Composite Channel Slope=5