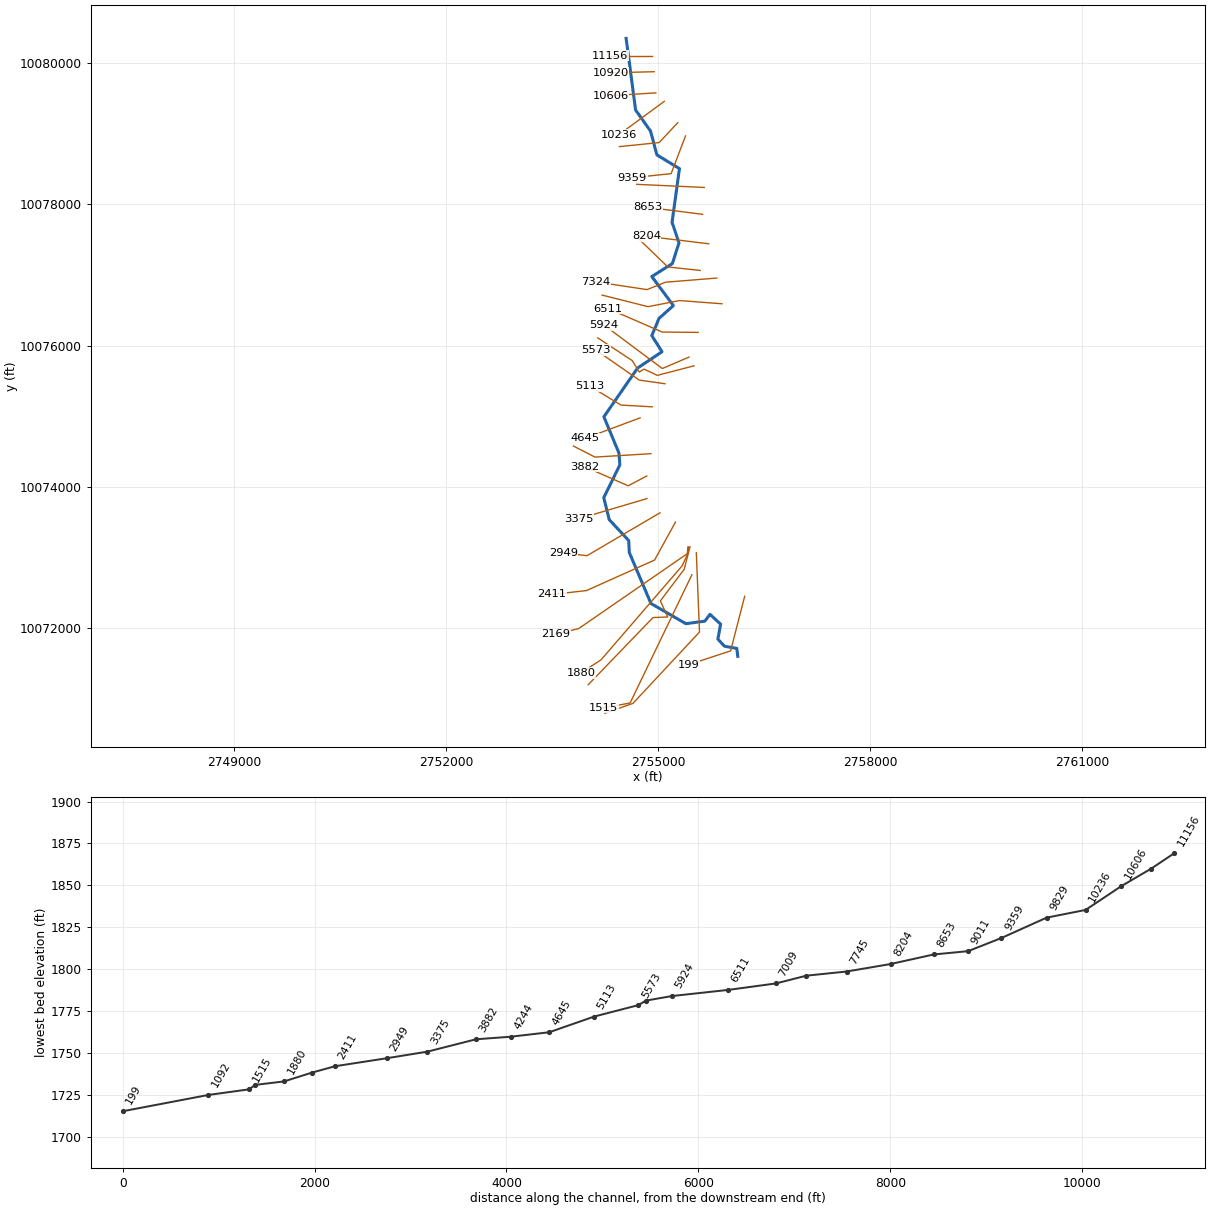
--- UNT 0064 IN HEWA.prj (project) ---

Proj Title=UNT 0064 IN HEWA Base Level Engineering
Current Plan=p01
Default Exp/Contr=0.3,0.1
English Units
Geom File=g01
Geom File=g02
Flow File=f01
Plan File=p01
Y Axis Title=Elevation
X Axis Title(PF)=Main Channel Distance
X Axis Title(XS)=Station
BEGIN DESCRIPTION:
UNT 0064 IN HEWA
END DESCRIPTION:
DSS Export Rating Curves= 0
DSS Export Rating Curve Sorted= 0
DSS Export Volume Flow Curves= 0
DXF OffsetX= 0
DXF OffsetY= 0
DXF ScaleX= 1
DXF ScaleY= 10

--- UNT 0064 IN HEWA.p01 (plan) ---

Plan Title=Multiple Run
Short Identifier=Multiple
Geom File=g01
Flow File=f01
Subcritical Flow
K Sum by GR= 0
Std Step Tol= 0.01
Critical Tol= 0.01
Num of Std Step Trials= 20
Max Error Tol= 0.3
Flow Tol Ratio= 0.001
Split Flow NTrial= 30
Split Flow Tol= 0.02
Split Flow Ratio= 0.02
Log Output Level= 0
Friction Slope Method= 1
Unsteady Friction Slope Method= 2
Unsteady Bridges Friction Slope Method= 1
Parabolic Critical Depth
Global Vel Dist=  1 , 1 , 1
Global Log Level= 0
CheckData=True
Encroach Param= -1, 0, 0, 0
BEGIN DESCRIPTION:
Multiple Run
END DESCRIPTION:

--- UNT 0064 IN HEWA.f01 (steady flow) ---

Flow Title=Multiple
Program Version=4.10
Number of Profiles= 7
Profile Names=10-year,25-year,50-year,1pct_min,100-year,1pct_plu,500-year
River Rch & RM=UNT 0064 IN HEWA,Reach-1         ,11156
     297     407     498     449     607     821     902
River Rch & RM=UNT 0064 IN HEWA,Reach-1         ,9011
     854    1243    1582    1475    1994    2697    3182
Boundary for River Rch & Prof#=UNT 0064 IN HEWA,Reach-1         , 1
Up Type= 0
Dn Type= 3
Dn Slope=0.011
Boundary for River Rch & Prof#=UNT 0064 IN HEWA,Reach-1         , 2
Up Type= 0
Dn Type= 3
Dn Slope=0.011
Boundary for River Rch & Prof#=UNT 0064 IN HEWA,Reach-1         , 3
Up Type= 0
Dn Type= 3
Dn Slope=0.011
Boundary for River Rch & Prof#=UNT 0064 IN HEWA,Reach-1         , 4
Up Type= 0
Dn Type= 3
Dn Slope=0.011
Boundary for River Rch & Prof#=UNT 0064 IN HEWA,Reach-1         , 5
Up Type= 0
Dn Type= 3
Dn Slope=0.011
Boundary for River Rch & Prof#=UNT 0064 IN HEWA,Reach-1         , 6
Up Type= 0
Dn Type= 3
Dn Slope=0.011
Boundary for River Rch & Prof#=UNT 0064 IN HEWA,Reach-1         , 7
Up Type= 0
Dn Type= 3
Dn Slope=0.011
DSS Import GetInterval= 0
DSS Import GetPeak= 0
DSS Import FillOption= 0

--- UNT 0064 IN HEWA.g01 (geometry) ---

Geom Title=Existing Conditions
Program Version=4.10

River Reach=UNT 0064 IN HEWA,Reach-1
Reach XY= 30
       2754547.8     10080350.38      2754682.27     10079335.27
      2754894.03     10079036.61      2754983.26      10078700.9
      2755302.97     10078506.26      2755198.02     10077746.08
      2755296.11     10077454.84       2755202.6     10077162.46
      2754911.67     10076978.89      2755217.13     10076567.73
      2755013.37     10076386.46      2754911.35     10076142.57
      2755055.99     10075915.27      2754711.68     10075685.96
      2754233.04     10074994.04      2754447.34     10074478.26
      2754458.69     10074312.56      2754231.62     10073849.47
      2754308.56     10073539.01      2754584.97     10073242.36
      2754592.22     10073075.28      2754899.36     10072351.88
      2755394.09     10072065.82      2755661.94     10072102.11
        2755735.      10072198.3      2755885.36     10072059.12
      2755847.04     10071847.85      2755939.67     10071746.89
      2756114.93     10071716.51      2756128.47     10071603.73

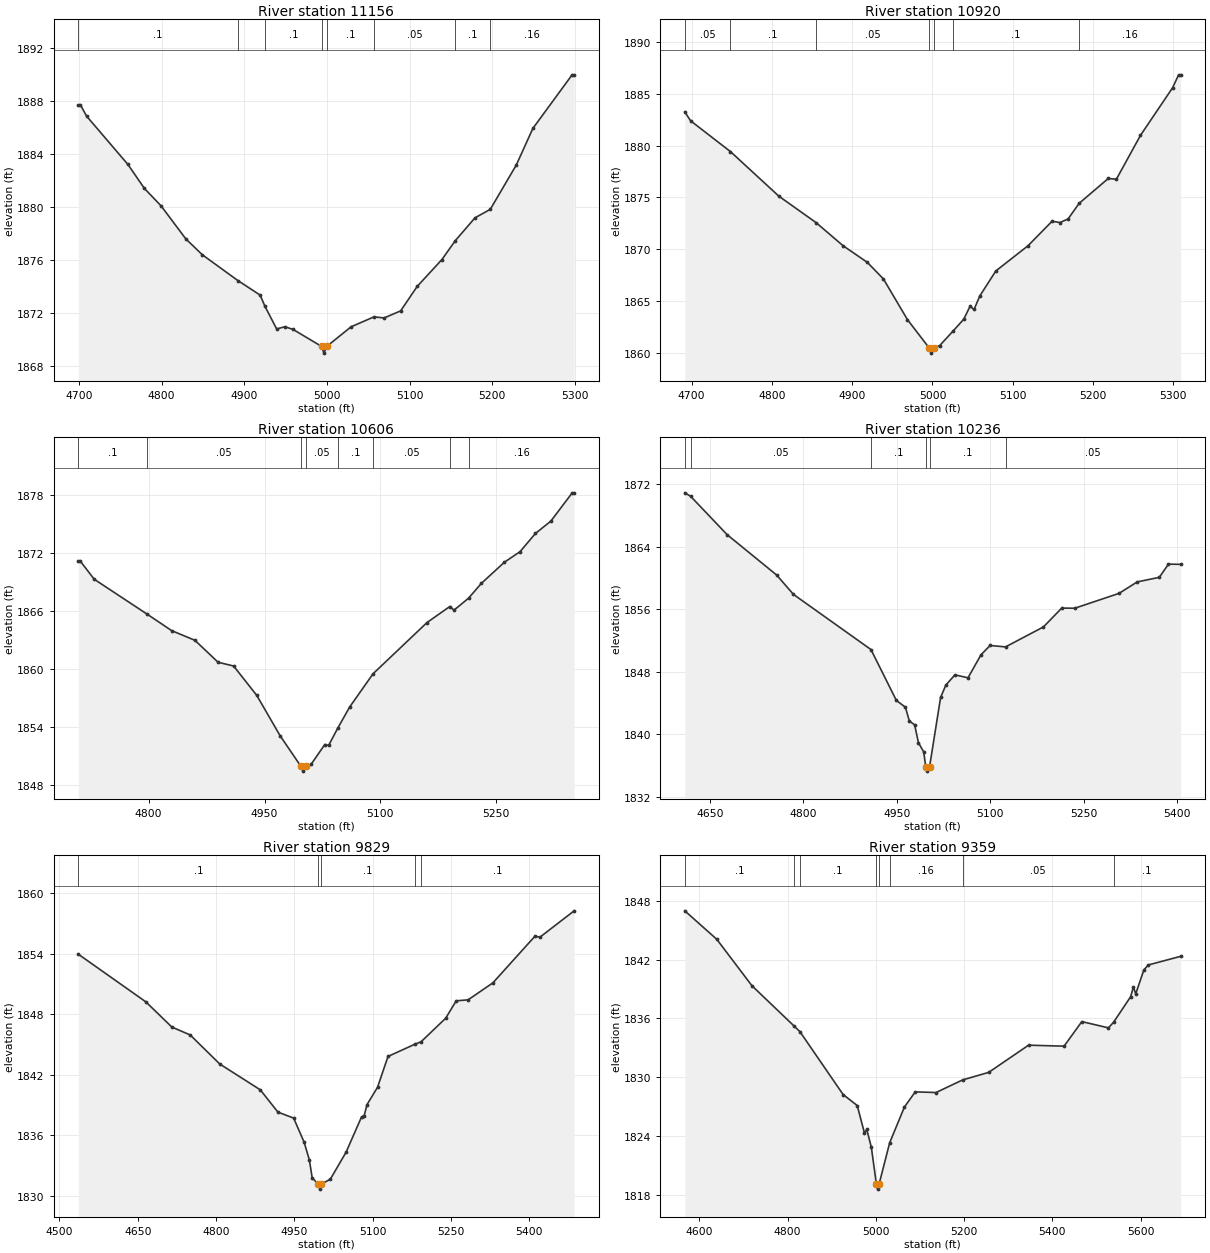
Type RM Length L Ch R = 1 ,11156   ,236,236,236
BEGIN DESCRIPTION:
UNT 0064 IN HEWA 23.0
END DESCRIPTION:
XS GIS Cut Line= 3
      2754918.46     10080103.73      2754618.47     10080103.73
      2754318.46     10080103.73
#Sta/Elev= 30
  4699.2 1887.69  4701.7 1887.69  4709.2 1886.84  4759.2  1883.2  4779.2 1881.39
  4799.2 1880.09  4829.2  1877.6  4849.2  1876.4  4892.4 1874.45  4919.2 1873.36
    4925 1872.52  4939.2 1870.81  4949.2 1870.98  4959.2 1870.77  4993.7 1869.49
  4996.4 1868.99  4999.7 1869.49  5029.2 1870.97  5056.9 1871.72  5069.2 1871.64
  5089.2 1872.17  5109.2 1874.01  5139.2 1876.04  5155.5 1877.47  5179.2 1879.18
  5197.7 1879.82  5229.2 1883.16  5249.2 1885.91  5296.7 1889.95  5299.2 1889.95
#Mann= 8 ,-1 , 0
  4699.2      .1       0  4892.4     .05       0    4925      .1       0
  4993.7     .07       0  4999.7      .1       0  5056.9     .05       0
  5155.5      .1       0  5197.7     .16       0
Bank Sta=4993.7,4999.7
XS Rating Curve= 0 ,0
Exp/Cntr=0.3,0.1

Type RM Length L Ch R = 1 ,10920   ,314,314,314
BEGIN DESCRIPTION:
Mapping XS c141775e
END DESCRIPTION:
XS GIS Cut Line= 2
      2754945.65      10079877.8      2754328.45     10079862.17
#Sta/Elev= 30
  4691.6 1883.26  4698.8  1882.4  4748.5 1879.42  4808.8 1875.11  4854.9 1872.57
  4888.8 1870.32  4918.9 1868.72  4938.9 1867.12  4968.9 1863.18  4995.9 1860.45
  4998.6 1859.95  5001.9 1860.45  5008.9 1860.67  5025.6 1862.08  5038.9 1863.22
  5046.8 1864.47  5051.8 1864.17  5058.9 1865.47  5078.9 1867.89  5118.9 1870.32
  5148.9 1872.69  5158.9 1872.57  5168.9 1872.92  5182.7 1874.43    5219 1876.83
    5229 1876.75    5259 1880.99    5299 1885.59  5306.5 1886.84    5309 1886.84
#Mann= 7 ,-1 , 0
  4691.6     .05       0  4748.5      .1       0  4854.9     .05       0
  4995.9    .035       0  5001.9     .05       0  5025.6      .1       0
  5182.7     .16       0
Bank Sta=4995.9,5001.9
XS Rating Curve= 0 ,0
Exp/Cntr=0.3,0.1

Type RM Length L Ch R = 1 ,10606   ,370,370,370
BEGIN DESCRIPTION:
UNT 0064 IN HEWA 22.0
END DESCRIPTION:
XS GIS Cut Line= 2
      2754969.07     10079578.32      2754328.46     10079539.25
#Sta/Elev= 30
    4709 1871.12  4711.8 1871.12  4729.6 1869.27  4798.3 1865.65  4829.8 1863.96
  4859.9 1862.96  4889.9 1860.69    4910  1860.3    4940 1857.26  4970.1  1853.1
  4997.1 1849.93  4999.9 1849.43  5003.1 1849.93  5010.2 1850.12    5028 1852.18
    5033 1852.09  5045.1 1853.92  5060.3 1856.07  5090.5  1859.5  5160.4  1864.8
  5189.8 1866.45  5195.3 1866.08  5214.2 1867.32  5230.6 1868.84  5260.6 1871.04
  5280.7 1872.12  5300.7 1874.01  5320.7 1875.29  5348.3 1878.21  5350.8 1878.21
#Mann= 8 ,-1 , 0
    4709      .1       0  4798.3     .05       0  4997.1    .035       0
  5003.1     .05       0  5045.1      .1       0  5090.5     .05       0
  5189.8      .1       0  5214.2     .16       0
Bank Sta=4997.1,5003.1
XS Rating Curve= 0 ,0
Exp/Cntr=0.3,0.1

Type RM Length L Ch R = 1 ,10236   ,407,407,407
BEGIN DESCRIPTION:
UNT 0064 IN HEWA 21.0
END DESCRIPTION:
XS GIS Cut Line= 2
      2755088.83     10079458.52      2754446.68     10078987.96
#Sta/Elev= 30
  4609.8 1870.93  4619.1 1870.49  4677.8 1865.57  4757.3  1860.4  4784.3 1857.92
  4908.7 1850.86  4949.5 1844.34  4964.1 1843.47  4970.3 1841.71  4978.8 1841.22
    4985 1838.92  4993.5 1837.74  4996.7 1835.79  4999.4 1835.29  5002.7 1835.79
  5020.5 1844.72    5029 1846.32  5043.6 1847.62  5064.5 1847.24  5085.3 1850.18
    5100 1851.38  5124.8  1851.2  5185.7 1853.76    5215 1856.17  5235.9 1856.15
  5306.9 1858.05  5336.2 1859.52  5371.7 1860.11  5386.4  1861.8  5405.9 1861.77
#Mann= 6 ,-1 , 0
  4609.8      .1       0  4619.1     .05       0  4908.7      .1       0
  4996.7     .07       0  5002.7      .1       0  5124.8     .05       0
Bank Sta=4996.7,5002.7
XS Rating Curve= 0 ,0
Exp/Cntr=0.3,0.1

Type RM Length L Ch R = 1 ,9829    ,470,470,470
BEGIN DESCRIPTION:
UNT 0064 IN HEWA 20.0
END DESCRIPTION:
XS GIS Cut Line= 3
      2755278.93     10079156.43      2755015.92     10078875.19
      2754453.49     10078817.91
#Sta/Elev= 30
  4536.1 1853.96  4665.5 1849.24  4715.4 1846.74  4750.5 1845.96  4807.2 1843.08
  4884.9 1840.52  4918.7 1838.31  4948.8 1837.72  4968.9 1835.33  4978.9 1833.58
  4984.4 1831.79    4996 1831.18  4998.8 1830.68    5002 1831.18  5019.1 1831.66
  5049.3 1834.34    5079 1837.84    5084 1837.96  5089.5 1839.06  5109.6 1840.77
  5129.7 1843.83  5181.2 1845.04    5193 1845.28  5240.3 1847.62  5260.4 1849.34
  5283.2 1849.44  5330.7 1851.12  5411.1 1855.73  5421.2 1855.66  5486.5 1858.26
#Mann= 5 ,-1 , 0
  4536.1      .1       0    4996     .07       0    5002      .1       0
  5181.2     .05       0    5193      .1       0
Bank Sta=4996,5002
XS Rating Curve= 0 ,0
Exp/Cntr=0.3,0.1

Type RM Length L Ch R = 1 ,9359    ,348,348,348
BEGIN DESCRIPTION:
UNT 0064 IN HEWA 19.0
END DESCRIPTION:
XS GIS Cut Line= 3
      2755388.32     10078968.94      2755185.19     10078435.09
      2754635.76      10078377.8
#Sta/Elev= 30
  4567.2 1846.99  4639.7 1844.08  4719.3 1839.34  4815.5 1835.19    4828 1834.65
  4925.9 1828.22    4958 1827.09  4974.3 1824.28  4979.6 1824.65    4990 1822.81
  5001.4 1819.05  5004.1 1818.55  5007.4 1819.05  5031.5 1823.29  5064.9 1826.94
  5089.4 1828.49  5136.4 1828.42  5196.8 1829.71  5255.8 1830.48  5346.2 1833.26
  5426.7 1833.16  5466.9 1835.67  5527.2 1835.03  5538.8  1835.6  5577.5 1838.21
  5583.9 1839.22    5589  1838.5  5607.6 1840.96  5617.7 1841.46  5690.8 1842.34
#Mann= 8 ,-1 , 0
  4567.2      .1       0  4815.5     .05       0    4828      .1       0
  5001.4     .07       0  5007.4      .1       0  5031.5     .16       0
  5196.8     .05       0  5538.8      .1       0
Bank Sta=5001.4,5007.4
XS Rating Curve= 0 ,0
Exp/Cntr=0.3,0.1

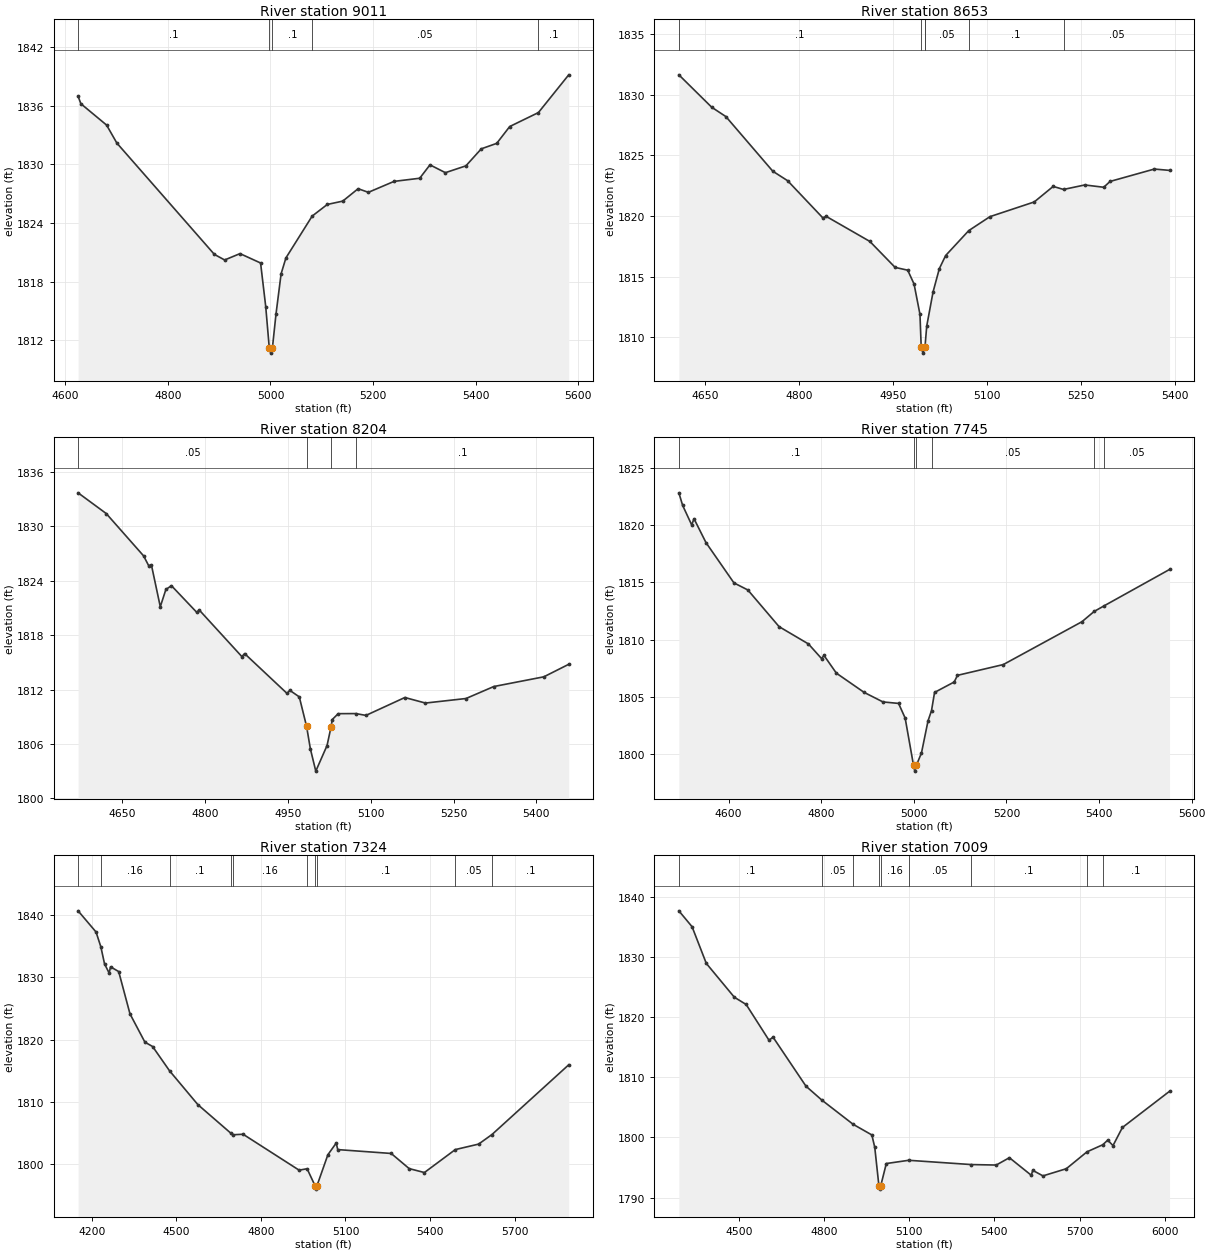
Type RM Length L Ch R = 1 ,9011    ,358,358,358
BEGIN DESCRIPTION:
UNT 0064 IN HEWA 18.0
END DESCRIPTION:
XS GIS Cut Line= 2
      2755653.97     10078239.77      2754698.19     10078284.05
#Sta/Elev= 30
  4624.8 1836.96  4630.3 1836.19  4680.4 1834.01  4700.4 1832.17  4890.6 1820.78
  4910.6 1820.21  4940.6 1820.86  4980.7  1819.9  4990.7 1815.45  4997.7 1811.18
  5000.5 1810.68  5003.7 1811.18  5010.7 1814.65  5020.7 1818.79  5030.1 1820.42
  5081.3  1824.7  5110.8 1825.89  5140.9 1826.23  5170.9  1827.5  5190.9 1827.13
    5241 1828.25    5291 1828.57    5311 1829.94  5341.1 1829.14  5381.1 1829.84
  5411.1 1831.58  5441.2 1832.14  5466.5 1833.86  5522.5 1835.29  5581.6 1839.15
#Mann= 5 ,-1 , 0
  4624.8      .1       0  4997.7     .07       0  5003.7      .1       0
  5081.3     .05       0  5522.5      .1       0
Bank Sta=4997.7,5003.7
XS Rating Curve= 0 ,0
Exp/Cntr=0.3,0.1

Type RM Length L Ch R = 1 ,8653    ,449,449,449
BEGIN DESCRIPTION:
UNT 0064 IN HEWA 17.0
END DESCRIPTION:
XS GIS Cut Line= 2
      2755630.47     10077859.57      2754854.46     10077958.52
#Sta/Elev= 30
  4608.4 1831.63  4660.8 1828.96  4683.4 1828.19  4758.2 1823.69  4781.8 1822.91
  4838.1 1819.84  4843.1 1819.98  4912.9 1817.91  4953.2 1815.77  4973.3 1815.54
  4983.4  1814.4  4992.8 1811.91  4994.8 1809.21  4997.6 1808.71  5000.8 1809.21
    5001 1809.33  5003.6 1810.94  5013.7 1813.75  5023.7 1815.67  5033.8 1816.75
  5070.6  1818.8  5104.4 1819.95    5175 1821.16  5205.2 1822.44  5221.7 1822.19
  5255.6 1822.56  5285.8 1822.37  5295.9 1822.85  5366.5 1823.87  5390.7 1823.76
#Mann= 6 ,-1 , 0
  4608.4      .1       0  4994.8     .07       0  5000.8      .1       0
    5001     .05       0  5070.6      .1       0  5221.7     .05       0
Bank Sta=4994.8,5000.8
XS Rating Curve= 0 ,0
Exp/Cntr=0.3,0.1

Type RM Length L Ch R = 1 ,8204    ,459,459,459
BEGIN DESCRIPTION:
UNT 0064 IN HEWA 16.0
END DESCRIPTION:
XS GIS Cut Line= 2
      2755716.42      10077442.9      2754833.65     10077549.67
#Sta/Elev= 30
  4569.5 1833.67  4620.5 1831.39  4688.3 1826.72  4697.4 1825.65  4702.4 1825.73
  4718.5 1821.12  4728.6 1823.02  4738.7 1823.44  4784.3 1820.52  4789.4 1820.74
  4866.3 1815.63  4871.3 1815.96  4948.2 1811.57  4953.2 1811.91  4970.4 1811.19
 4983.64 1807.93  4990.5 1805.46  5000.3 1803.01  5020.7 1805.83 5027.95 1807.88
  5030.1 1808.69  5040.9 1809.34  5072.8 1809.35  5091.2 1809.15  5161.7 1811.12
    5199 1810.51  5272.5 1811.01  5322.9 1812.33  5413.6  1813.4  5458.7 1814.78
#Mann= 4 ,-1 , 0
  4569.5     .05       0 4983.64     .07       0 5027.95     .05       0
  5072.8      .1       0
Bank Sta=4983.64,5027.95
XS Rating Curve= 0 ,0
Exp/Cntr=0.3,0.1

Type RM Length L Ch R = 1 ,7745    ,421,421,421
BEGIN DESCRIPTION:
UNT 0064 IN HEWA 15.0
END DESCRIPTION:
XS GIS Cut Line= 3
      2755596.64      10077065.3      2755138.32     10077114.77
      2754707.46     10077530.06
#Sta/Elev= 30
  4492.8 1822.82    4501 1821.72  4520.5 1820.02  4525.5 1820.56  4551.3 1818.48
  4611.7 1814.96  4641.8 1814.34  4709.2 1811.14  4772.6 1809.63    4801 1808.35
  4806.1 1808.63  4832.9 1807.08  4892.9  1805.4  4933.5 1804.57  4967.2 1804.44
  4981.4 1803.16  4999.5 1799.03  5002.2 1798.53  5005.5 1799.03  5016.6 1800.11
  5030.8 1802.92  5038.3 1803.81  5044.9  1805.4  5087.3 1806.31  5094.3 1806.89
  5193.3 1807.83  5363.1 1811.57  5389.6 1812.47  5411.1 1812.96  5552.2 1816.13
#Mann= 6 ,-1 , 0
  4492.8      .1       0  4999.5     .07       0  5005.5      .1       0
  5038.3     .05       0  5389.6      .1       0  5411.1     .05       0
Bank Sta=4999.5,5005.5
XS Rating Curve= 0 ,0
Exp/Cntr=0.3,0.1

Type RM Length L Ch R = 1 ,7324    ,315,315,315
BEGIN DESCRIPTION:
UNT 0064 IN HEWA 14.0
END DESCRIPTION:
XS GIS Cut Line= 4
      2755832.05     10076957.75      2755103.97      10076898.6
       2754844.6     10076793.94      2754122.25     10076902.97
#Sta/Elev= 30
  4151.4 1840.67  4215.2 1837.27  4232.3 1834.88  4245.3 1832.16  4261.6 1830.69
  4266.6 1831.69  4295.5 1830.93  4335.6 1824.14  4388.5 1819.61  4415.8 1818.91
    4476 1815.01  4576.4 1809.59  4693.6    1805  4701.1 1804.76  4736.9 1804.84
  4935.6 1799.08  4963.9 1799.31  4992.6 1796.54  4995.4 1796.04  4998.6 1796.54
  5037.6 1801.55  5067.2 1803.43  5072.6 1802.38  5262.3 1801.76  5326.1 1799.33
  5380.1  1798.7  5489.6 1802.38  5572.3 1803.26  5619.6 1804.79  5892.1 1815.98
#Mann= 10 ,-1 , 0
  4151.4      .1       0  4232.3     .16       0    4476      .1       0
  4693.6     .05       0  4701.1     .16       0  4963.9      .1       0
  4992.6     .07       0  4998.6      .1       0  5489.6     .05       0
  5619.6      .1       0
Bank Sta=4992.6,4998.6
XS Rating Curve= 0 ,0
Exp/Cntr=0.3,0.1

Type RM Length L Ch R = 1 ,7009    ,498,498,498
BEGIN DESCRIPTION:
UNT 0064 IN HEWA 13.0
END DESCRIPTION:
XS GIS Cut Line= 4
      2755904.82     10076593.72      2755304.19     10076639.22
      2754858.25     10076552.76      2754207.55     10076716.58
#Sta/Elev= 30
  4289.2 1837.65  4335.7 1835.01  4385.8 1828.92  4484.5  1823.3  4526.2 1822.09
  4606.5 1816.16  4620.9 1816.66  4736.8 1808.52  4792.9  1806.2  4902.8 1802.19
  4968.7 1800.42  4978.9 1798.38  4993.7 1791.92  4996.4 1791.42  4999.7 1791.92
  5019.6 1795.67  5098.4 1796.21  5318.7  1795.5  5406.7 1795.42    5453 1796.64
  5530.1 1793.72  5535.2 1794.54  5571.2 1793.62  5653.4 1794.81  5726.3 1797.62
  5781.7 1798.79  5799.3 1799.56  5817.8 1798.65  5850.9 1801.66  6016.8 1807.67
#Mann= 9 ,-1 , 0
  4289.2      .1       0  4792.9     .05       0  4902.8     .16       0
  4993.7     .07       0  4999.7     .16       0  5098.4     .05       0
  5318.7      .1       0  5726.3     .05       0  5781.7      .1       0
Bank Sta=4993.7,4999.7
XS Rating Curve= 0 ,0
Exp/Cntr=0.3,0.1

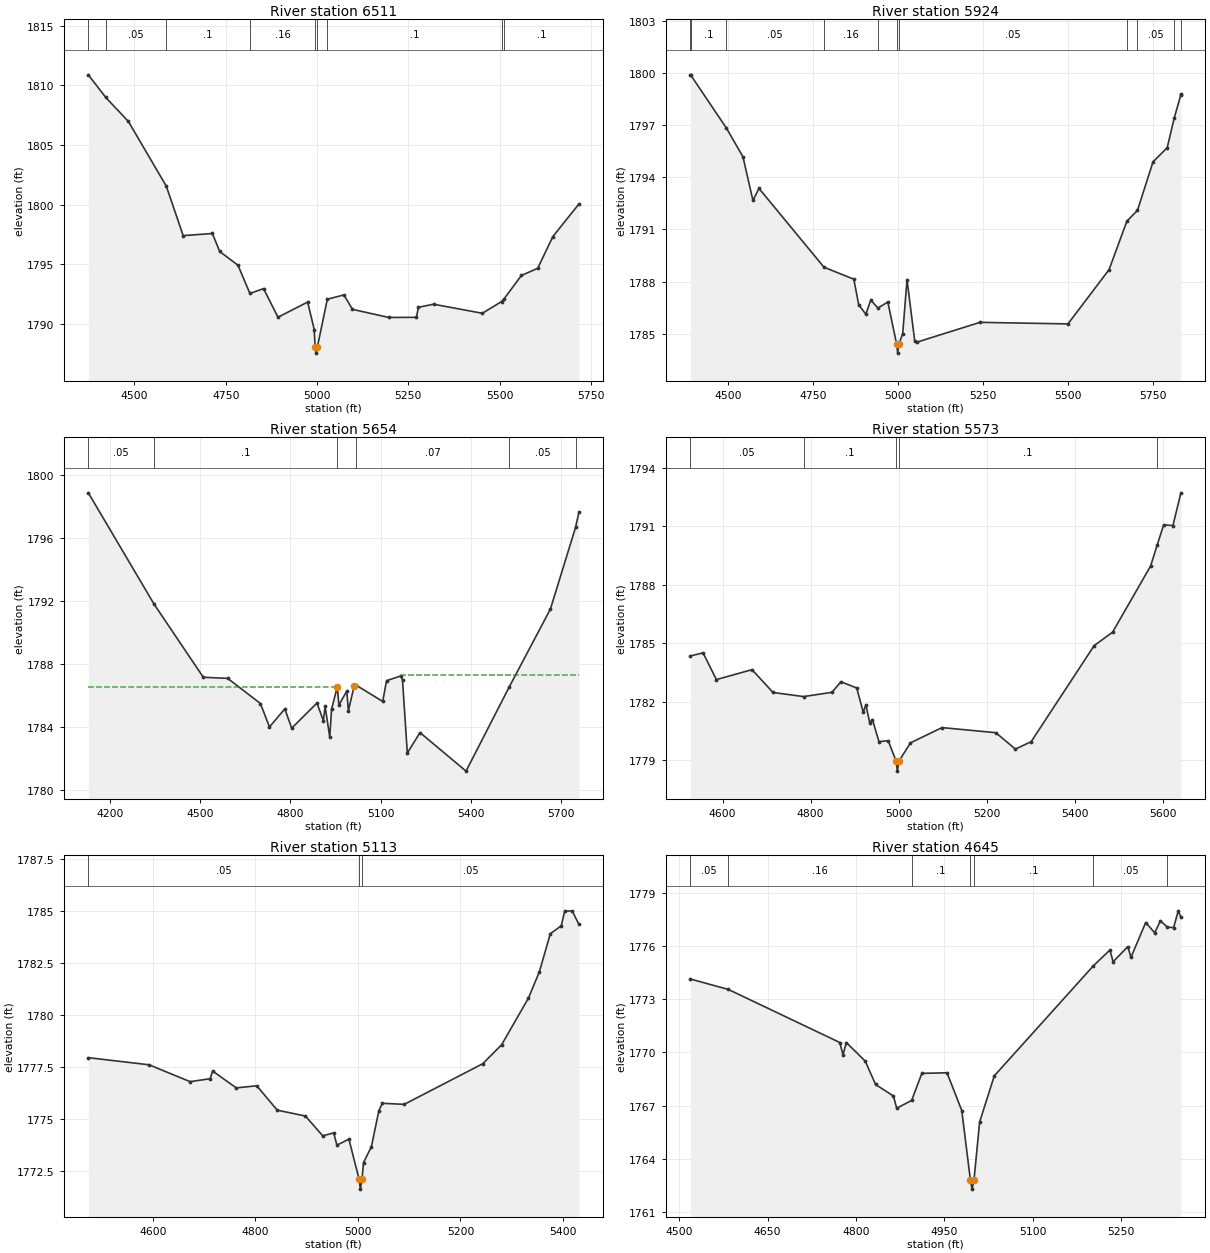
Type RM Length L Ch R = 1 ,6511    ,587,587,587
BEGIN DESCRIPTION:
UNT 0064 IN HEWA 12.0
END DESCRIPTION:
XS GIS Cut Line= 3
      2755568.15     10076188.73      2755058.47     10076193.28
      2754294.02     10076525.45
#Sta/Elev= 30
  4373.9 1810.88  4421.5 1808.99  4483.6 1806.97  4587.4 1801.55  4633.6  1797.4
  4713.6 1797.58  4733.6 1796.07  4783.6 1794.92  4816.4 1792.55  4853.6 1792.96
  4893.2 1790.56  4974.4 1791.83  4992.4 1789.53  4994.9 1788.05  4997.6 1787.55
  5000.9 1788.05  5028.3 1792.07  5073.7 1792.43  5097.1 1791.22  5196.4 1790.54
  5272.2 1790.55  5277.6 1791.39  5319.1 1791.65  5452.7 1790.89  5505.2 1791.87
  5512.2  1792.1  5559.6 1794.06  5604.3 1794.66  5645.7 1797.32  5717.1 1800.05
#Mann= 9 ,-1 , 0
  4373.9     .16       0  4421.5     .05       0  4587.4      .1       0
  4816.4     .16       0  4994.9     .07       0  5000.9     .16       0
  5028.3      .1       0  5505.2     .05       0  5512.2      .1       0
Bank Sta=4994.9,5000.9
XS Rating Curve= 0 ,0
Exp/Cntr=0.3,0.1

Type RM Length L Ch R = 1 ,5924    ,270,270,270
BEGIN DESCRIPTION:
UNT 0064 IN HEWA 11.0
END DESCRIPTION:
XS GIS Cut Line= 3
      2755437.81     10075838.74      2755060.19     10075677.27
      2754232.79     10076293.92
#Sta/Elev= 30
  4389.2 1799.89    4390 1799.89  4495.3 1796.83    4544 1795.18  4573.4 1792.67
  4591.2 1793.36  4782.3 1788.83    4870 1788.14  4884.6 1786.66  4905.4 1786.13
    4920 1786.94    4941 1786.48    4970 1786.83  4996.2 1784.39    4999 1783.89
  5002.2 1784.39  5013.8 1785.01  5026.5 1788.12  5049.3 1784.56  5055.5 1784.52
  5241.1 1785.66  5499.7 1785.57  5620.6 1788.69  5673.1 1791.48  5704.2  1792.1
  5749.9 1794.89  5791.6  1795.7    5812 1797.39  5831.4 1798.73  5831.8 1798.77
#Mann= 11 ,-1 , 0
  4389.2     .05       0    4390      .1       0  4495.3     .05       0
  4782.3     .16       0    4941     .05       0  4996.2    .035       0
  5002.2     .05       0  5673.1      .1       0  5704.2     .05       0
    5812      .1       0  5831.4     .05       0
Bank Sta=4996.2,5002.2
XS Rating Curve= 0 ,0
Exp/Cntr=0.3,0.1

Type RM Length L Ch R = 1 ,5654    ,81,81,81
BEGIN DESCRIPTION:
Mapping XS 047d83b7
END DESCRIPTION:
XS GIS Cut Line= 6
        2755510.     10075715.79      2754989.18     10075580.37
      2754801.68     10075668.91      2754733.97     10075627.25
      2754635.01     10075788.71      2754145.46      10076111.6
#Sta/Elev= 30
    4128 1798.88  4346.6  1791.8  4510.2 1787.15  4591.3 1787.08  4700.1 1785.48
  4730.2 1783.99  4781.2 1785.14    4804 1783.91    4888 1785.51  4909.3 1784.39
  4915.2  1785.3  4930.6 1783.33  4936.5 1785.12  4955.6 1786.53  4960.9 1785.38
  4987.2 1786.27  4992.5 1785.02  5011.5 1786.58  5017.2 1786.66  5106.6 1785.61
  5119.3 1786.93  5167.3 1787.24  5172.4 1786.97  5188.4 1782.33  5230.5 1783.63
  5383.6 1781.18  5527.6 1786.55  5664.1 1791.49  5747.6 1796.68  5758.8 1797.64
#Mann= 6 ,-1 , 0
    4128     .05       0  4346.6      .1       0  4955.6     .05       0
  5017.2     .07       0  5527.6     .05       0  5747.6      .1       0
#XS Ineff= 2 , 0
         4951.68  1786.5 5167.67         1787.27
Permanent Ineff=
       T       T
Bank Sta=4955.6,5011.5
XS Rating Curve= 0 ,0
Exp/Cntr=0.3,0.1

Type RM Length L Ch R = 1 ,5573    ,460,460,460
BEGIN DESCRIPTION:
UNT 0064 IN HEWA 10.0
END DESCRIPTION:
XS GIS Cut Line= 3
      2755097.22     10075461.82      2754732.62     10075513.91
      2754119.68     10075939.84
#Sta/Elev= 30
  4526.7 1784.35  4555.7 1784.51    4586 1783.14  4666.9 1783.65  4714.7 1782.48
  4784.3 1782.27  4848.7 1782.49  4868.9 1783.03  4904.8 1782.71  4919.7 1781.47
  4925.7 1781.84  4934.5 1780.92  4940.6 1781.09  4955.4 1779.96  4976.4 1780.01
  4994.5 1778.95  4997.2 1778.45  5000.5 1778.95    5027  1779.9  5098.6 1780.68
  5220.8 1780.42  5265.4 1779.58  5301.2 1779.96  5444.3 1784.88  5486.2 1785.57
  5572.6 1788.96  5587.5 1790.03  5602.3 1791.07  5623.3 1791.03  5641.4 1792.71
#Mann= 5 ,-1 , 0
  4526.7     .05       0  4784.3      .1       0  4994.5     .07       0
  5000.5      .1       0  5587.5     .05       0
Bank Sta=4994.5,5000.5
XS Rating Curve= 0 ,0
Exp/Cntr=0.3,0.1

Type RM Length L Ch R = 1 ,5113    ,468,468,468
BEGIN DESCRIPTION:
Mapping XS 119bb9bc
END DESCRIPTION:
XS GIS Cut Line= 3
      2754916.64     10075135.43      2754475.67     10075159.74
      2754034.72     10075427.09
#Sta/Elev= 30
  4473.8 1777.95  4592.2 1777.61  4672.3  1776.8  4711.4 1776.94  4716.4 1777.31
  4762.4  1776.5  4802.5  1776.6  4842.5 1775.43  4897.4 1775.15  4931.2  1774.2
  4952.6 1774.34  4958.9 1773.75  4982.3 1774.04  5001.9 1772.14  5004.7 1771.64
  5007.9 1772.14  5010.8 1772.91  5026.2 1773.68  5040.8 1775.41  5047.6 1775.76
  5090.3 1775.71  5243.4 1777.66  5280.3 1778.57  5332.6 1780.81  5353.9 1782.07
  5375.3  1783.9  5396.6 1784.28  5403.3 1784.98  5417.9    1785  5431.1 1784.35
#Mann= 3 ,-1 , 0
  4473.8     .05       0  5001.9     .04       0  5007.9     .05       0
Bank Sta=5001.9,5007.9
XS Rating Curve= 0 ,0
Exp/Cntr=0.3,0.1

Type RM Length L Ch R = 1 ,4645    ,401,401,401
BEGIN DESCRIPTION:
UNT 0064 IN HEWA 9.0
END DESCRIPTION:
XS GIS Cut Line= 2
      2754746.48     10074979.17      2753966.84     10074688.11
#Sta/Elev= 30
  4518.9 1774.15  4583.4 1773.56  4772.6 1770.56  4777.9 1769.86  4783.6 1770.56
  4815.7 1769.51  4833.2 1768.19  4863.5 1767.54    4869 1766.85  4894.4 1767.29
  4911.7 1768.82  4954.4 1768.85  4979.4 1766.72  4994.1 1762.78  4996.9 1762.28
  5000.1 1762.78  5009.7 1766.07  5034.6 1768.68  5202.8  1774.9  5230.8 1775.79
  5236.1 1775.12  5261.1 1775.98  5266.4 1775.37  5291.4 1777.34  5306.7 1776.76
  5316.4 1777.44  5328.1 1777.08  5338.7 1777.05  5346.7    1778  5351.1 1777.64
#Mann= 7 ,-1 , 0
  4518.9     .05       0  4583.4     .16       0  4894.4      .1       0
  4994.1     .07       0  5000.1      .1       0  5202.8     .05       0
  5328.1      .1       0
Bank Sta=4994.1,5000.1
XS Rating Curve= 0 ,0
Exp/Cntr=0.3,0.1

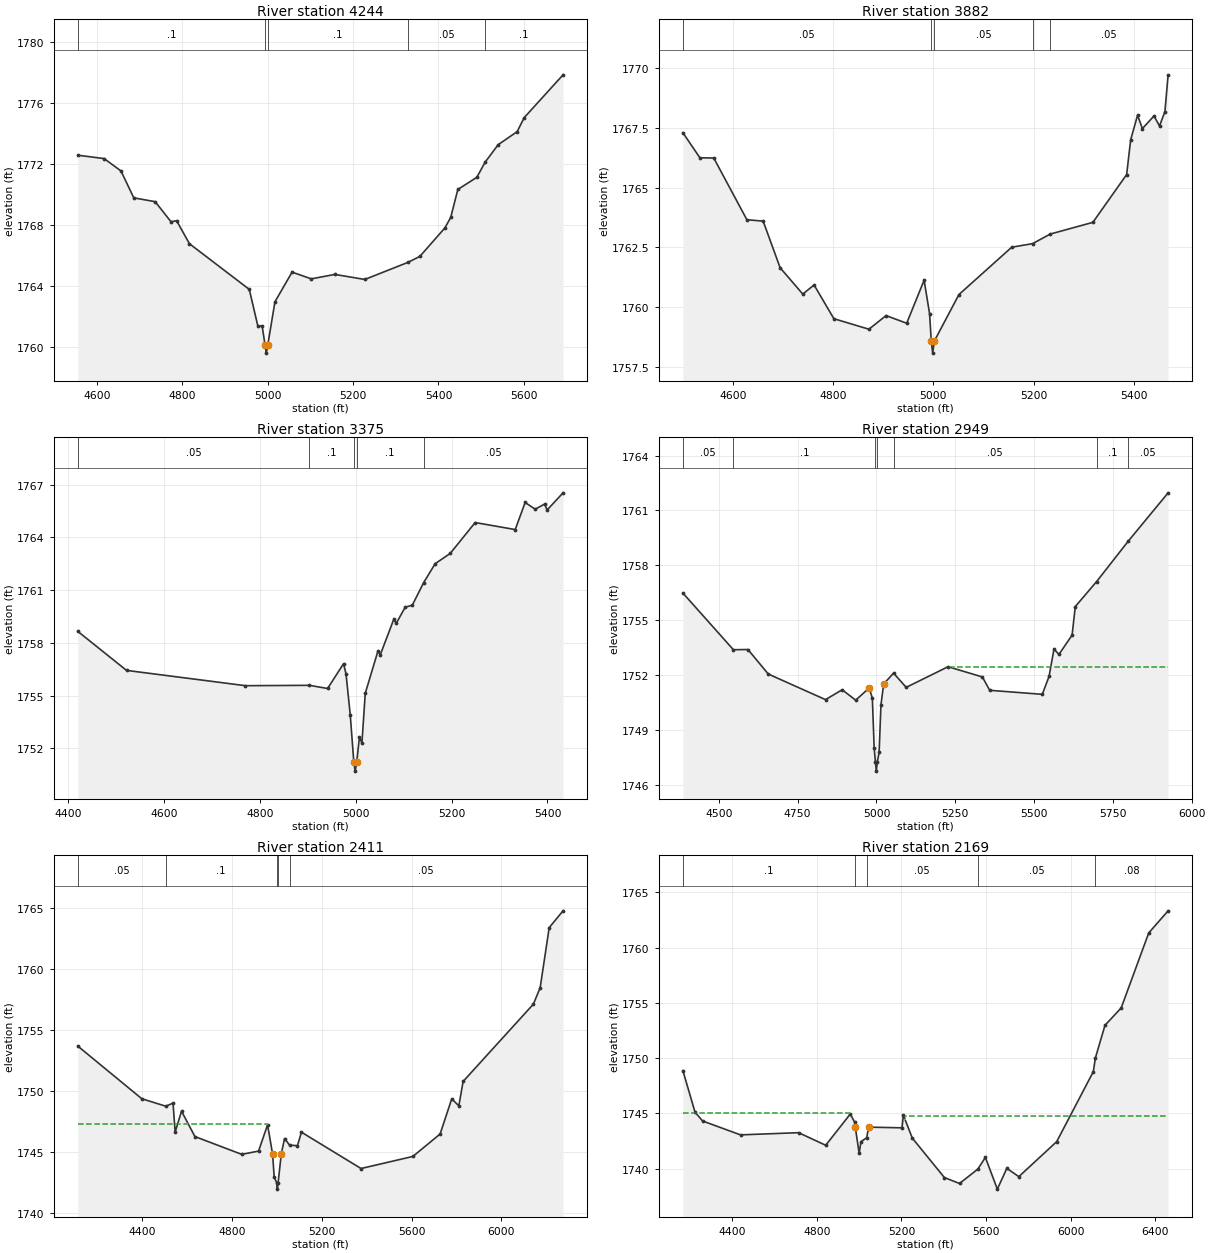
Type RM Length L Ch R = 1 ,4244    ,362,362,362
BEGIN DESCRIPTION:
UNT 0064 IN HEWA 8.0
END DESCRIPTION:
XS GIS Cut Line= 3
      2754899.33     10074472.24      2754107.62     10074423.63
      2753802.05     10074579.88
#Sta/Elev= 30
  4555.4 1772.56    4617 1772.34  4656.5 1771.53  4686.5 1769.77  4736.6 1769.52
  4773.8  1768.2  4786.7 1768.28  4816.8 1766.77    4957 1763.78  4977.1 1761.38
  4987.1 1761.39  4994.1 1760.11  4996.8 1759.61  5000.1 1760.11  5017.1 1762.97
  5057.2 1764.91  5102.2 1764.47  5157.4 1764.76  5227.5 1764.43  5328.7 1765.55
  5356.5 1765.94    5415  1767.8  5428.8 1768.49  5445.4 1770.32  5489.8 1771.11
  5509.5 1772.11  5539.9 1773.25  5584.3  1774.1  5600.9 1775.02  5691.8 1777.82
#Mann= 5 ,-1 , 0
  4555.4      .1       0  4994.1     .07       0  5000.1      .1       0
  5328.7     .05       0  5509.5      .1       0
Bank Sta=4994.1,5000.1
XS Rating Curve= 0 ,0
Exp/Cntr=0.3,0.1

Type RM Length L Ch R = 1 ,3882    ,507,507,507
BEGIN DESCRIPTION:
UNT 0064 IN HEWA 7.0
END DESCRIPTION:
XS GIS Cut Line= 3
      2754840.28     10074156.28      2754576.37     10074017.38
      2753962.65     10074287.83
#Sta/Elev= 30
  4499.7  1767.3  4533.7 1766.25  4561.4 1766.24  4627.5 1763.66    4660  1763.6
  4693.9 1761.65  4739.1 1760.55  4761.7 1760.93  4801.2 1759.52  4871.2 1759.08
  4905.4 1759.65  4946.6 1759.33  4981.4 1761.13  4992.3 1759.73  4995.7 1758.58
  4998.5 1758.08  5001.7 1758.58  5050.9 1760.53  5156.3 1762.51  5198.1 1762.66
  5233.2 1763.06  5318.4 1763.55  5385.8 1765.55  5393.8    1767  5407.6 1768.03
  5417.2 1767.47  5440.4    1768  5451.4 1767.58  5462.2 1768.18  5468.6 1769.72
#Mann= 5 ,-1 , 0
  4499.7     .05       0  4995.7     .04       0  5001.7     .05       0
  5198.1      .1       0  5233.2     .05       0
Bank Sta=4995.7,5001.7
XS Rating Curve= 0 ,0
Exp/Cntr=0.3,0.1

Type RM Length L Ch R = 1 ,3375    ,426,426,426
BEGIN DESCRIPTION:
UNT 0064 IN HEWA 6.0
END DESCRIPTION:
XS GIS Cut Line= 2
      2754843.75     10073836.83      2753872.62     10073548.96
#Sta/Elev= 30
  4419.6 1758.65  4521.3 1756.43  4769.6 1755.56  4903.2 1755.58    4941  1755.4
  4974.3 1756.81  4979.5 1756.23  4988.3  1753.9  4995.8  1751.2  4998.5  1750.7
  5001.8  1751.2  5007.5 1752.64  5012.7  1752.3  5019.6 1755.12    5046 1757.52
  5051.2 1757.33  5079.2 1759.34  5084.4 1759.11  5103.1 1760.03  5117.7 1760.13
  5141.5 1761.42  5165.6  1762.5  5196.9 1763.08  5249.1 1764.84  5332.7 1764.44
  5353.4 1765.98  5374.3  1765.6    5394 1765.89  5399.2 1765.55  5432.5 1766.53
#Mann= 5 ,-1 , 0
  4419.6     .05       0  4903.2      .1       0  4995.8     .07       0
  5001.8      .1       0  5141.5     .05       0
Bank Sta=4995.8,5001.8
XS Rating Curve= 0 ,0
Exp/Cntr=0.3,0.1

Type RM Length L Ch R = 1 ,2949    ,538,538,538
BEGIN DESCRIPTION:
UNT 0064 IN HEWA 5.0
END DESCRIPTION:
XS GIS Cut Line= 3
       2755027.8     10073635.46      2753993.03     10073027.79
       2753656.2     10073069.46
#Sta/Elev= 30
  4385.9 1756.48  4546.1 1753.38  4592.4 1753.39  4656.8 1752.05  4838.4 1750.65
  4891.2 1751.19  4934.2 1750.62  4977.1 1751.29    4987 1750.73  4992.8 1747.99
  4996.8 1747.24  4999.5 1746.74  5002.8 1747.24  5008.5 1747.78  5014.3 1750.37
    5023 1751.51  5054.4  1752.1  5094.3 1751.32  5227.2 1752.45  5336.1 1751.89
  5359.3 1751.16  5526.1 1750.94  5547.6 1751.92  5563.3 1753.42  5578.9 1753.12
  5620.7 1754.18  5630.8 1755.74  5698.6 1757.11  5798.5 1759.31  5925.3 1761.96
#Mann= 7 ,-1 , 0
  4385.9     .05       0  4546.1      .1       0  4996.8     .07       0
  5002.8      .1       0  5054.4     .05       0  5698.6      .1       0
  5798.5     .05       0
#XS Ineff= 2 , 0
                         5228.86         1752.45
Permanent Ineff=
       T       T
Bank Sta=4977.1,5023
XS Rating Curve= 0 ,0
Exp/Cntr=0.3,0.1

Type RM Length L Ch R = 1 ,2411    ,242,242,242
BEGIN DESCRIPTION:
UNT 0064 IN HEWA 4.0
END DESCRIPTION:
XS GIS Cut Line= 4
      2755246.42     10073503.61      2754950.65     10072966.68
      2753985.99      10072534.4      2753497.17     10072479.44
#Sta/Elev= 30
  4112.9 1753.71  4398.2 1749.39  4504.7 1748.78  4537.2 1749.03  4546.6 1746.66
  4575.1 1748.37  4634.7 1746.29  4843.3 1744.83  4918.3  1745.1  4958.4 1747.25
  4980.8 1744.85  4987.8 1742.99  4999.3 1742.48    5002 1741.98  5005.3 1742.48
 5019.66 1744.89  5034.2 1746.13  5056.3 1745.59  5091.5 1745.54  5109.3 1746.65
  5374.8 1743.67  5605.8 1744.66  5727.2  1746.5  5778.9 1749.38  5810.7 1748.81
  5829.7 1750.81  6142.8 1757.15    6173  1758.5  6213.2 1763.42  6274.9  1764.8
#Mann= 5 ,-1 , 0
  4112.9     .05       0  4504.7      .1       0  4999.3     .07       0
  5005.3      .1       0  5056.3     .05       0
#XS Ineff= 2 , 0
         4958.76 1747.32 5139.32         1745.89
Permanent Ineff=
       T       T
Bank Sta=4980.8,5019.66
XS Rating Curve= 0 ,0
Exp/Cntr=0.3,0.1

Type RM Length L Ch R = 1 ,2169    ,289,289,289
BEGIN DESCRIPTION:
UNT 0064 IN HEWA 3.0
END DESCRIPTION:
XS GIS Cut Line= 4
      2755421.73     10073151.01       2755414.8     10073057.69
      2753877.39     10071997.47      2753553.03     10071917.02
#Sta/Elev= 30
  4166.2 1748.87  4223.6 1745.11  4259.3 1744.31  4438.8 1743.05  4713.4 1743.25
  4841.8 1742.11  4958.2 1744.94  4979.1 1744.18 4981.53 1743.78  5000.1 1741.37
  5008.5 1742.43  5035.9  1742.8  5044.7 1743.75  5202.8 1743.69    5209 1744.84
  5251.4 1742.76  5403.1 1739.19  5474.7 1738.65  5561.3 1739.95  5597.1 1741.01
  5653.7 1738.14  5698.6 1740.02  5755.3 1739.27  5934.5 1742.44  6107.6 1748.77
  6117.6 1750.02  6162.9 1752.97  6239.5 1754.54  6369.8 1761.33  6461.5 1763.33
#Mann= 5 ,-1 , 0
  4166.2      .1       0  4979.1     .07       0  5035.9     .05       0
  5561.3     .05       0  6117.6     .08       0
#XS Ineff= 2 , 0
         4955.96    1745 5217.33          1744.8
Permanent Ineff=
       T       T
Bank Sta=4981.53,5044.7
XS Rating Curve= 0 ,0
Exp/Cntr=0.3,0.1

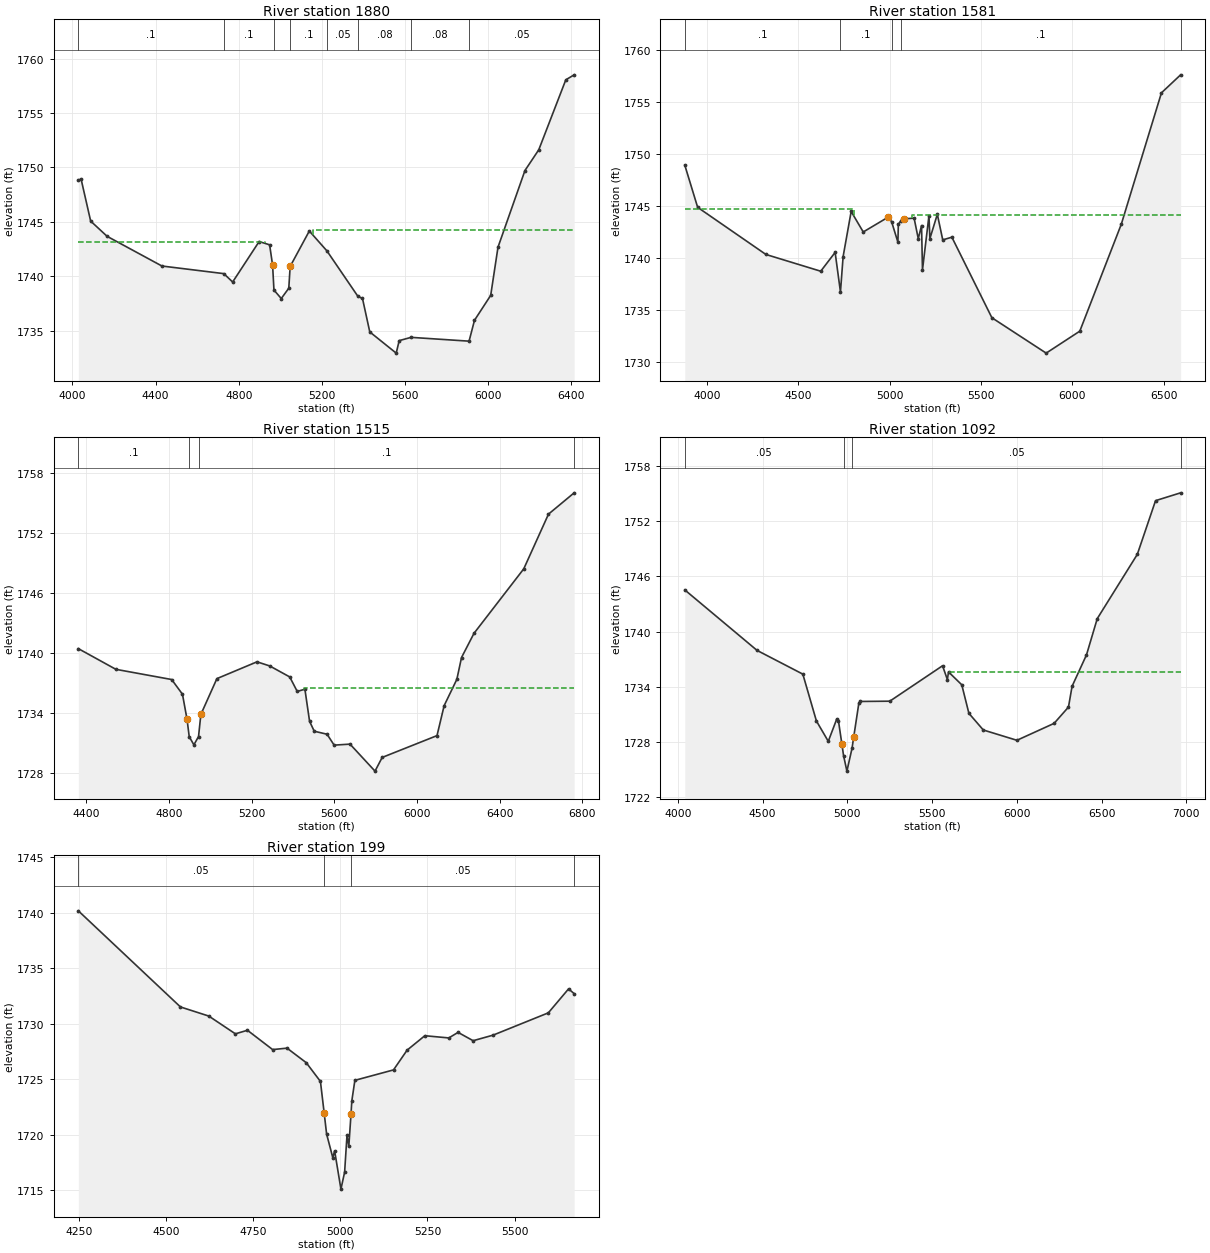
Type RM Length L Ch R = 1 ,1880    ,299,299,299
BEGIN DESCRIPTION:
Mapping XS 56a75d6c
END DESCRIPTION:
XS GIS Cut Line= 5
      2755435.83     10073152.04      2755416.31     10073044.65
      2755337.44     10072880.22       2754192.1     10071553.42
      2753907.13      10071368.5
#Sta/Elev= 30
  4028.9 1748.84  4042.3 1748.91  4088.2 1745.06  4167.3 1743.66  4430.8 1740.93
  4728.2 1740.23  4770.9 1739.46  4898.2 1743.18  4948.6 1742.88  4962.9 1741.02
  4969.5 1738.72  5004.6 1737.94  5040.8 1738.89  5047.4 1740.89  5139.5 1744.15
  5224.2 1742.32  5373.2 1738.14  5395.1 1737.95  5430.2 1734.87  5557.3 1732.92
  5571.7 1734.07  5628.8 1734.37  5907.6 1734.02  5933.7 1735.94  6011.6 1738.23
  6046.7 1742.66  6176.3 1749.71  6242.8 1751.62  6372.7 1758.05  6412.9 1758.51
#Mann= 8 ,-1 , 0
  4028.9      .1       0  4728.2      .1       0  4969.5     .07       0
  5047.4      .1       0  5224.2     .05       0  5373.2     .08       0
  5628.8     .08       0  5907.6     .05       0
#XS Ineff= 2 , 0
         4927.46 1743.17 5157.67         1744.21
Permanent Ineff=
       T       T
Bank Sta=4962.9,5047.4
XS Rating Curve= 0 ,0
Exp/Cntr=0.3,0.1

Type RM Length L Ch R = 1 ,1581    ,66,66,66
BEGIN DESCRIPTION:
Mapping XS 244a5a4a
END DESCRIPTION:
XS GIS Cut Line= 6
      2755452.11     10073153.15      2755369.29     10072834.72
      2755032.56     10072388.77      2755137.22     10072161.25
       2754927.9     10072152.15      2754012.24     10071202.64
#Sta/Elev= 30
  3879.6 1748.91  3949.9 1744.86  4323.4 1740.33  4623.4 1738.72  4702.2 1740.53
  4731.3 1736.73  4745.9 1740.13  4789.9 1744.46    4856 1742.49  4990.9  1743.9
  5010.9 1743.49  5045.7 1741.51    5048 1743.22    5063 1743.59    5078 1743.75
  5134.3 1743.82    5157 1741.85    5175 1743.11  5180.1 1738.85  5215.6 1744.06
  5220.8 1741.86 5261.36 1744.19    5291 1741.73 5340.91 1741.99  5559.9 1734.25
  5856.9 1730.85  6040.9 1732.96  6267.9 1743.23  6487.7 1755.86  6592.6 1757.59
#Mann= 5 ,-1 , 0
  3879.6      .1       0  4731.3      .1       0  5010.9     .05       0
    5063      .1       0  6592.6     .05       0
#XS Ineff= 2 , 0
         4803.11 1744.67 5124.35         1744.09
Permanent Ineff=
       T       T
Bank Sta=4990.9,5078
XS Rating Curve= 0 ,0
Exp/Cntr=0.3,0.1

Type RM Length L Ch R = 1 ,1515    ,423,423,423
BEGIN DESCRIPTION:
Mapping XS 10031f0b
END DESCRIPTION:
XS GIS Cut Line= 3
      2755478.49     10072757.33      2754603.87     10070942.94
      2754226.28     10070875.26
#Sta/Elev= 30
  4362.1 1740.44  4543.7 1738.37  4813.5 1737.35  4865.7 1735.88  4887.9 1733.36
  4898.4 1731.63    4921 1730.82  4943.4 1731.65  4954.7 1733.86  5032.2 1737.44
  5226.1 1739.12  5287.5 1738.71  5384.4 1737.61  5420.7 1736.16  5457.8 1736.38
  5480.4 1733.17    5503 1732.18    5565 1731.88  5599.1 1730.79    5676 1730.89
  5796.8 1728.19  5831.5 1729.56  6096.6 1731.74  6131.2 1734.74  6192.6 1737.37
  6215.2 1739.55  6275.5 1741.97  6516.2 1748.42  6635.8 1753.89  6759.9 1756.02
#Mann= 4 ,-1 , 0
  4362.1      .1       0  4898.4     .05       0  4943.4      .1       0
  6759.9     .05       0
#XS Ineff= 2 , 0
                          5451.7         1736.47
Permanent Ineff=
       T       T
Bank Sta=4887.9,4954.7
XS Rating Curve= 0 ,0
Exp/Cntr=0.3,0.1

Type RM Length L Ch R = 1 ,1092    ,893,893,893
BEGIN DESCRIPTION:
UNT 0064 IN HEWA 2.0
END DESCRIPTION:
XS GIS Cut Line= 4
      2755541.65     10073069.46      2755586.78     10071947.93
      2754644.63       10070938.       2754247.1     10070798.87
#Sta/Elev= 30
  4041.5 1744.54  4467.6 1737.97  4737.8 1735.39  4817.9  1730.3  4887.9 1728.09
    4938 1730.52    4948 1730.31    4968 1727.81    4978 1726.54  4997.8 1724.85
    5028 1727.33    5038 1728.56  5068.1 1732.22  5077.2 1732.42  5250.8 1732.45
    5562  1736.3  5590.4  1734.8  5597.2 1735.63  5675.4 1734.23  5717.4 1731.13
  5802.4 1729.32  6000.7  1728.2  6220.1 1730.04  6304.8 1731.81  6326.1 1734.07
  6411.1 1737.48  6474.6 1741.42  6710.8  1748.4  6818.5 1754.24  6966.4 1755.09
#Mann= 4 ,-1 , 0
  4041.5     .05       0    4978    .035       0    5028     .05       0
  6966.4     .05       0
#XS Ineff= 2 ,-1
 4790.91  4937.5 1730.46 5597.16  6966.4 1735.64
Permanent Ineff=
       T       T
Bank Sta=4968,5038
XS Rating Curve= 0 ,0
Exp/Cntr=0.3,0.1

Type RM Length L Ch R = 1 ,199     ,0,0,0
BEGIN DESCRIPTION:
UNT 0064 IN HEWA 1.0
END DESCRIPTION:
XS GIS Cut Line= 3
      2756226.31     10072453.71      2756027.34     10071681.72
      2755433.24     10071485.45
#Sta/Elev= 30
  4248.3 1740.19  4541.4 1731.53  4622.7 1730.71    4699 1729.11  4733.6 1729.43
  4805.9 1727.69  4847.2 1727.82  4902.4 1726.51  4943.1 1724.82 4953.64 1722.02
  4960.8 1720.08  4978.6 1717.95  4983.8 1718.57  5001.9 1715.12  5012.5 1716.65
  5019.3 1719.97  5024.5 1718.98 5030.91 1721.91  5033.1 1723.06  5041.9 1724.92
  5152.8 1725.86  5191.8 1727.64  5242.7 1728.94  5311.5 1728.74    5338 1729.24
  5381.3 1728.49  5438.4 1728.99  5597.1    1731  5655.2 1733.16  5671.2 1732.73
#Mann= 4 ,-1 , 0
  4248.3     .05       0 4953.64    .035       0 5030.91     .05       0
  5671.2     .05       0
Bank Sta=4953.64,5030.91
XS Rating Curve= 0 ,0
Exp/Cntr=0.3,0.1

Chan Stop Cuts=-1
Use User Specified Reach Order=0
Composite Channel Slope=5

--- UNT 0064 IN HEWA.g02 (geometry) ---

Geom Title=Delete
Program Version=4.10

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
River Reach=UNT 0064 IN HEWA,Reach-1