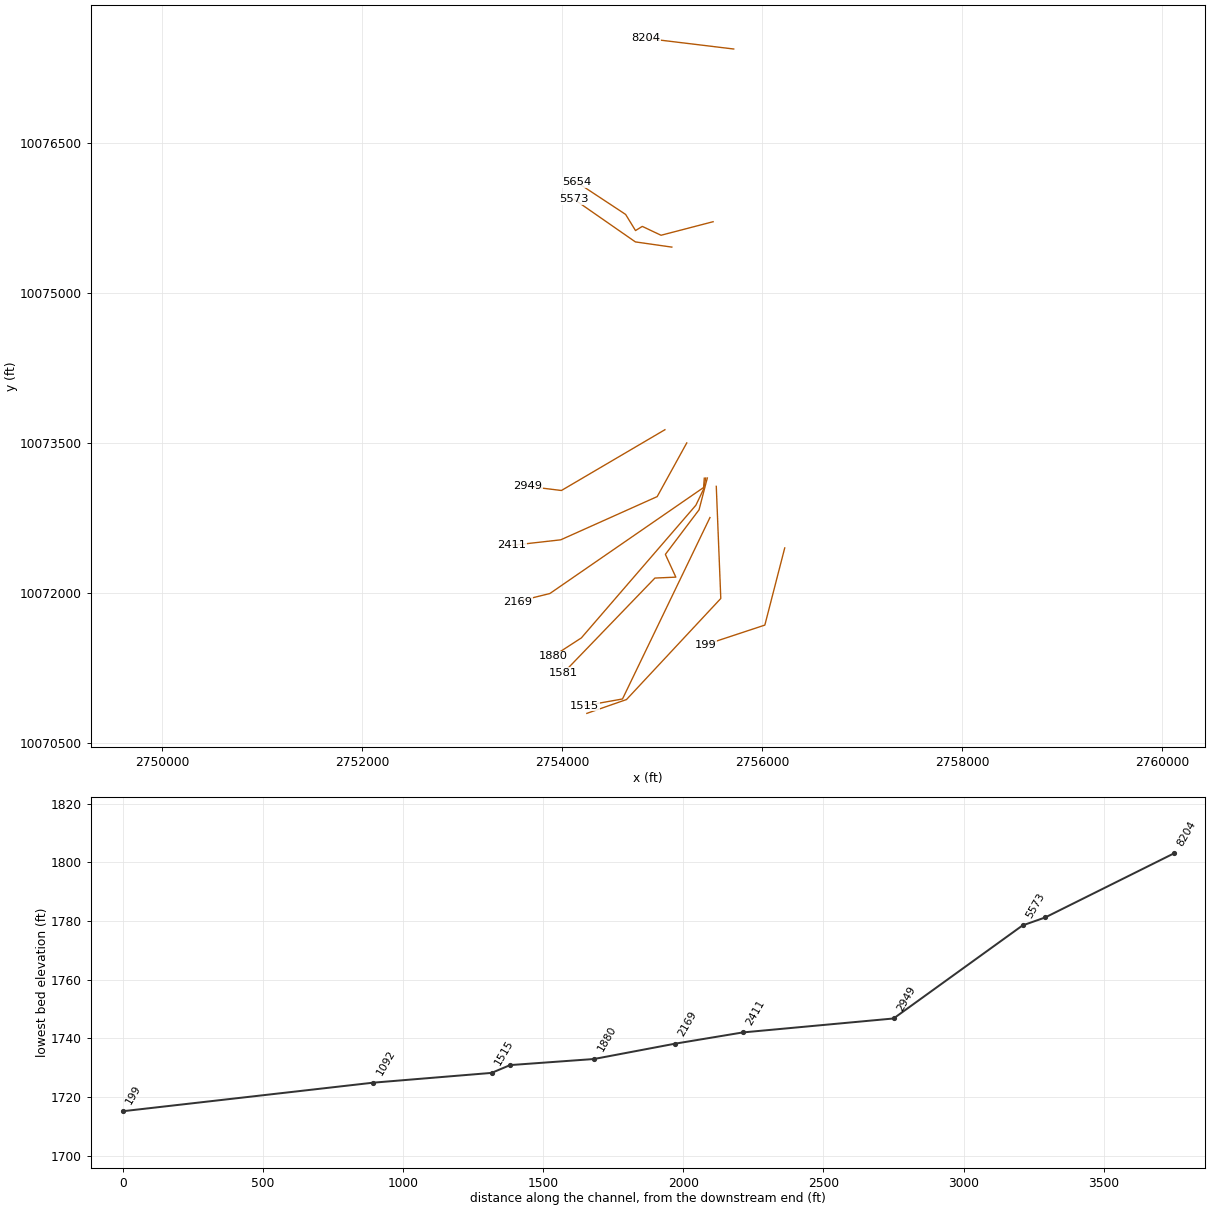
HEC-RAS study UNT 0064 IN HEWA.prj: UNT 0064 IN HEWA Base Level Engineering

--- UNT 0064 IN HEWA.g02 (geometry) --- (continued)

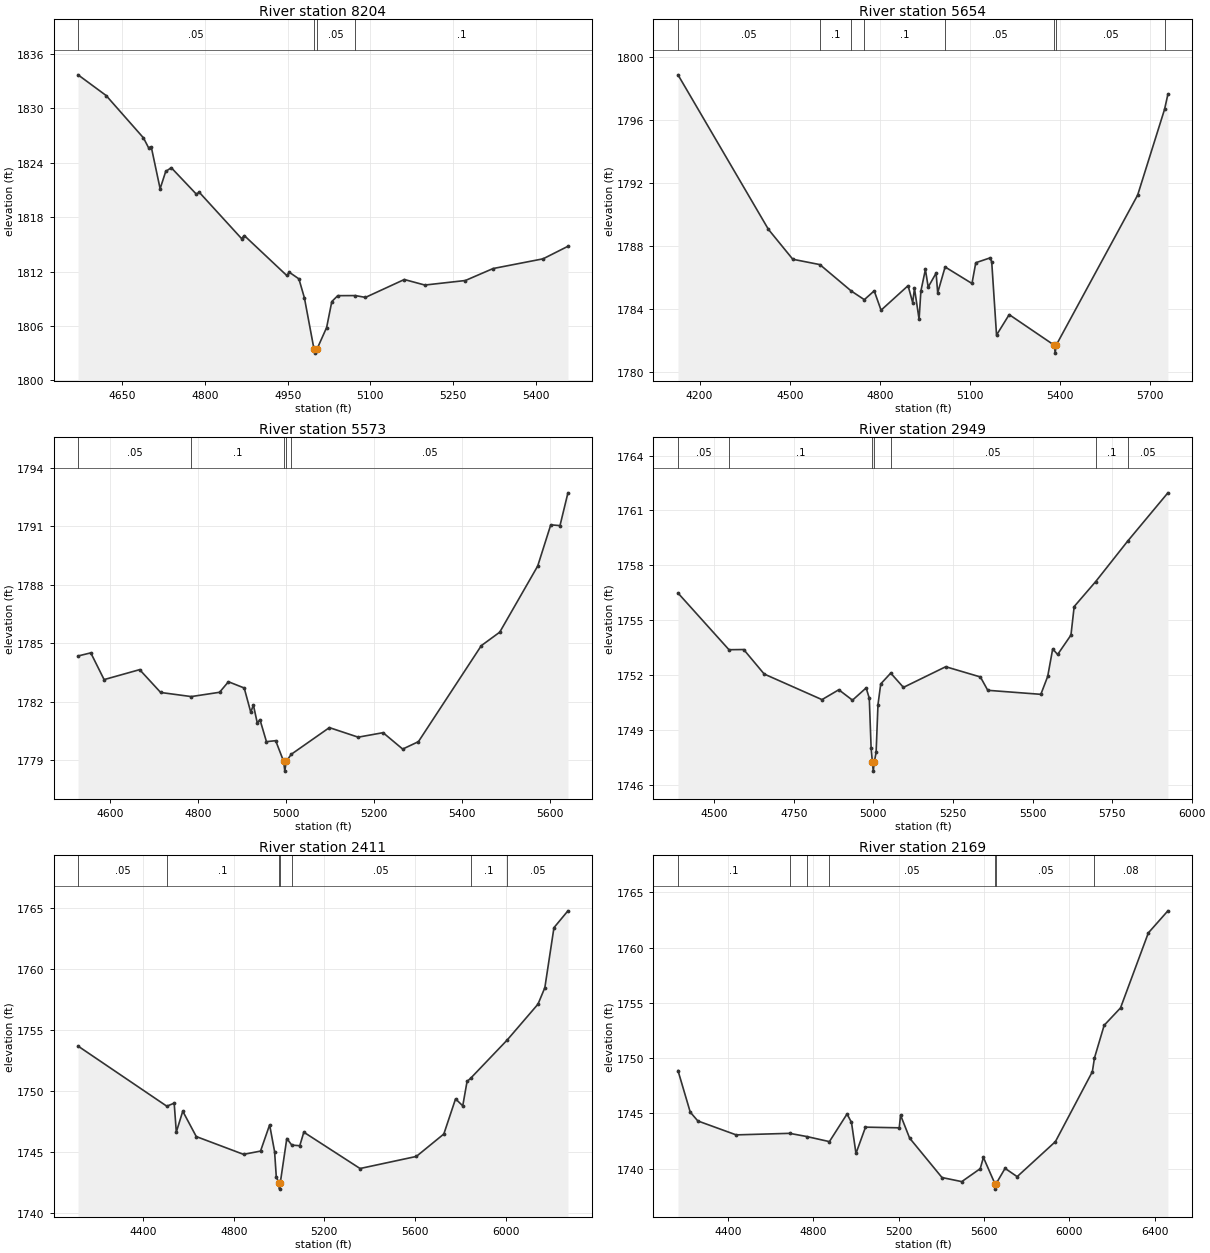
Type RM Length L Ch R = 1 ,8204    ,459,459,459
BEGIN DESCRIPTION:
UNT 0064 IN HEWA 16.0
END DESCRIPTION:
XS GIS Cut Line= 2
      2755716.42      10077442.9      2754833.65     10077549.67
#Sta/Elev= 30
  4569.5 1833.67  4620.5 1831.39  4688.3 1826.72  4697.4 1825.65  4702.4 1825.73
  4718.5 1821.12  4728.6 1823.02  4738.7 1823.44  4784.3 1820.52  4789.4 1820.74
  4866.3 1815.63  4871.3 1815.96  4948.2 1811.57  4953.2 1811.91  4970.4 1811.19
  4980.4 1809.09  4997.6 1803.51  5000.3 1803.01  5003.6 1803.51  5020.7 1805.83
  5030.1 1808.69  5040.9 1809.34  5072.8 1809.35  5091.2 1809.15  5161.7 1811.12
    5199 1810.51  5272.5 1811.01  5322.9 1812.33  5413.6  1813.4  5458.7 1814.78
#Mann= 4 ,-1 , 0
  4569.5     .05       0  4997.6    .035       0  5003.6     .05       0
  5072.8      .1       0
Bank Sta=4997.6,5003.6
XS Rating Curve= 0 ,0
Exp/Cntr=0.3,0.1

Type RM Length L Ch R = 1 ,5654    ,81,81,81
BEGIN DESCRIPTION:
Mapping XS 047d83b7
END DESCRIPTION:
XS GIS Cut Line= 6
        2755510.     10075715.79      2754989.18     10075580.37
      2754801.68     10075668.91      2754733.97     10075627.25
      2754635.01     10075788.71      2754145.46      10076111.6
#Sta/Elev= 30
    4128 1798.88  4429.1 1789.05  4510.2 1787.15  4600.3 1786.81  4704.8 1785.13
  4748.3 1784.58  4781.2 1785.14    4804 1783.91  4893.9 1785.47  4909.3 1784.39
  4915.2  1785.3  4930.6 1783.33  4936.5 1785.12  4951.6  1786.5  4960.9 1785.38
  4987.2 1786.27  4992.5 1785.02  5017.2 1786.66  5106.6 1785.61  5119.3 1786.93
  5167.3 1787.24  5172.4 1786.97  5188.4 1782.33  5230.5 1783.63  5380.8 1781.68
  5383.6 1781.18  5386.8 1781.68  5658.1 1791.23  5747.6 1796.68  5758.8 1797.64
#Mann= 8 ,-1 , 0
    4128     .05       0  4600.3      .1       0  4704.8     .16       0
  4748.3      .1       0  5017.2     .05       0  5380.8     .07       0
  5386.8     .05       0  5747.6      .1       0
Bank Sta=5380.8,5386.8
XS Rating Curve= 0 ,0
Exp/Cntr=0.3,0.1

Type RM Length L Ch R = 1 ,5573    ,460,460,460
BEGIN DESCRIPTION:
UNT 0064 IN HEWA 10.0
END DESCRIPTION:
XS GIS Cut Line= 3
      2755097.22     10075461.82      2754732.62     10075513.91
      2754119.68     10075939.84
#Sta/Elev= 30
  4526.7 1784.35  4555.7 1784.51    4586 1783.14  4666.9 1783.65  4714.7 1782.48
  4784.3 1782.27  4848.7 1782.49  4868.9 1783.03  4904.8 1782.71  4919.7 1781.47
  4925.7 1781.84  4934.5 1780.92  4940.6 1781.09  4955.4 1779.96  4976.4 1780.01
  4994.5 1778.95  4997.2 1778.45  5000.5 1778.95  5011.7 1779.31  5098.6 1780.68
  5164.1 1780.19  5220.8 1780.42  5265.4 1779.58  5301.2 1779.96  5444.3 1784.88
  5486.2 1785.57  5572.6 1788.96  5602.3 1791.07  5623.3 1791.03  5641.4 1792.71
#Mann= 5 ,-1 , 0
  4526.7     .05       0  4784.3      .1       0  4994.5     .07       0
  5000.5      .1       0  5011.7     .05       0
Bank Sta=4994.5,5000.5
XS Rating Curve= 0 ,0
Exp/Cntr=0.3,0.1

Type RM Length L Ch R = 1 ,2949    ,538,538,538
BEGIN DESCRIPTION:
UNT 0064 IN HEWA 5.0
END DESCRIPTION:
XS GIS Cut Line= 3
       2755027.8     10073635.46      2753993.03     10073027.79
       2753656.2     10073069.46
#Sta/Elev= 30
  4385.9 1756.48  4546.1 1753.38  4592.4 1753.39  4656.8 1752.05  4838.4 1750.65
  4891.2 1751.19  4934.2 1750.62  4977.1 1751.29    4987 1750.73  4992.8 1747.99
  4996.8 1747.24  4999.5 1746.74  5002.8 1747.24  5008.5 1747.78  5014.3 1750.37
    5023 1751.51  5054.4  1752.1  5094.3 1751.32  5227.2 1752.45  5336.1 1751.89
  5359.3 1751.16  5526.1 1750.94  5547.6 1751.92  5563.3 1753.42  5578.9 1753.12
  5620.7 1754.18  5630.8 1755.74  5698.6 1757.11  5798.5 1759.31  5925.3 1761.96
#Mann= 7 ,-1 , 0
  4385.9     .05       0  4546.1      .1       0  4996.8     .07       0
  5002.8      .1       0  5054.4     .05       0  5698.6      .1       0
  5798.5     .05       0
Bank Sta=4996.8,5002.8
XS Rating Curve= 0 ,0
Exp/Cntr=0.3,0.1

Type RM Length L Ch R = 1 ,2411    ,242,242,242
BEGIN DESCRIPTION:
UNT 0064 IN HEWA 4.0
END DESCRIPTION:
XS GIS Cut Line= 4
      2755246.42     10073503.61      2754950.65     10072966.68
      2753985.96     10072534.39      2753497.17     10072479.44
#Sta/Elev= 30
  4112.9 1753.71  4504.7 1748.78  4537.2 1749.03  4546.6 1746.66  4575.1 1748.37
  4634.7 1746.29  4843.3 1744.83  4918.3  1745.1  4958.4 1747.25  4980.3 1745.06
  4987.8 1742.99  4999.3 1742.48    5002 1741.98  5005.3 1742.48  5034.2 1746.13
  5056.3 1745.59  5091.5 1745.54  5109.3 1746.65  5357.5 1743.67  5605.8 1744.66
  5727.2  1746.5  5778.9 1749.38  5810.7 1748.81  5829.7 1750.81  5845.5 1751.07
  6006.9 1754.21  6142.8 1757.15    6173  1758.5  6213.2 1763.42  6274.9  1764.8
#Mann= 7 ,-1 , 0
  4112.9     .05       0  4504.7      .1       0  4999.3     .07       0
  5005.3      .1       0  5056.3     .05       0  5845.5      .1       0
  6006.9     .05       0
Bank Sta=4999.3,5005.3
XS Rating Curve= 0 ,0
Exp/Cntr=0.3,0.1

Type RM Length L Ch R = 1 ,2169    ,289,289,289
BEGIN DESCRIPTION:
UNT 0064 IN HEWA 3.0
END DESCRIPTION:
XS GIS Cut Line= 4
      2755421.73     10073151.01       2755414.8     10073057.69
      2753877.39     10071997.47      2753553.03     10071917.02
#Sta/Elev= 30
  4166.2 1748.87  4223.6 1745.11  4259.3 1744.31  4438.8 1743.05  4689.1 1743.19
  4769.7  1742.9  4875.6 1742.44  4958.2 1744.94  4979.1 1744.18  5000.1 1741.37
  5044.7 1743.75  5202.8 1743.69    5209 1744.84  5251.4 1742.76  5403.1 1739.19
  5495.7 1738.82  5582.2 1739.99  5597.1 1741.01  5650.9 1738.64  5653.7 1738.14
  5656.9 1738.64  5698.6 1740.02  5755.3 1739.27  5934.5 1742.44  6107.6 1748.77
  6117.6 1750.02  6162.9 1752.97  6239.5 1754.54  6369.8 1761.33  6461.5 1763.33
#Mann= 7 ,-1 , 0
  4166.2      .1       0  4689.1     .05       0  4769.7      .1       0
  4875.6     .05       0  5650.9    .035       0  5656.9     .05       0
  6117.6     .08       0
Bank Sta=5650.9,5656.9
XS Rating Curve= 0 ,0
Exp/Cntr=0.3,0.1

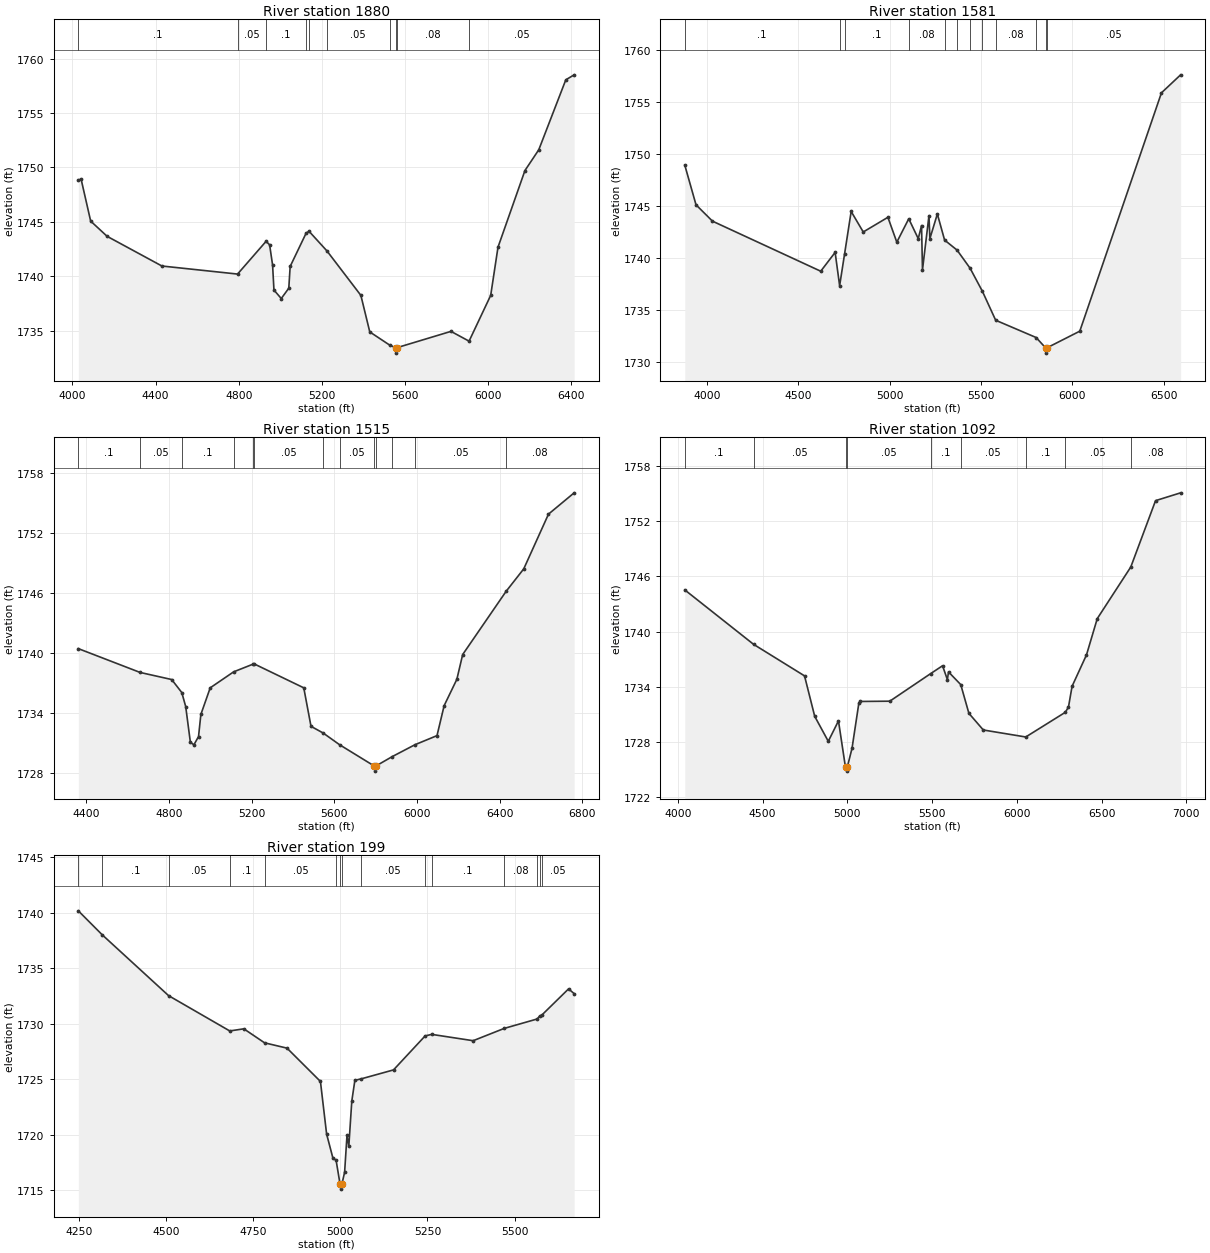
Type RM Length L Ch R = 1 ,1880    ,299,299,299
BEGIN DESCRIPTION:
Mapping XS 56a75d6c
END DESCRIPTION:
XS GIS Cut Line= 5
      2755435.83     10073152.04      2755416.31     10073044.65
      2755337.44     10072880.22       2754192.1     10071553.42
      2753907.13      10071368.5
#Sta/Elev= 30
  4028.9 1748.84  4042.3 1748.91  4088.2 1745.06  4167.3 1743.66  4430.8 1740.93
  4794.5 1740.19  4931.6  1743.2  4948.6 1742.88  4962.9 1741.02  4969.5 1738.72
  5004.6 1737.94  5040.8 1738.89  5047.4 1740.89  5123.6 1743.93  5137.9 1744.13
  5224.2 1742.32  5387.4 1738.23  5430.2 1734.87  5525.8 1733.66  5554.6 1733.42
  5557.3 1732.92  5560.6 1733.42  5820.7 1734.92  5907.6 1734.02  6011.6 1738.23
  6046.7 1742.66  6176.3 1749.71  6242.8 1751.62  6372.7 1758.05  6412.9 1758.51
#Mann= 10 ,-1 , 0
  4028.9      .1       0  4794.5     .05       0  4931.6      .1       0
  5123.6     .08       0  5137.9      .1       0  5224.2     .05       0
  5525.8     .08       0  5554.6     .07       0  5560.6     .08       0
  5907.6     .05       0
Bank Sta=5554.6,5560.6
XS Rating Curve= 0 ,0
Exp/Cntr=0.3,0.1

Type RM Length L Ch R = 1 ,1581    ,66,66,66
BEGIN DESCRIPTION:
Mapping XS 244a5a4a
END DESCRIPTION:
XS GIS Cut Line= 6
      2755452.11     10073153.15      2755369.29     10072834.72
      2755032.56     10072388.77      2755137.22     10072161.25
       2754927.9     10072152.15      2754012.24     10071202.64
#Sta/Elev= 30
  3879.6 1748.91    3941  1745.1    4031 1743.53  4623.4 1738.72  4702.2 1740.53
  4726.8 1737.33  4754.2 1740.42  4789.9 1744.46    4856 1742.49  4990.9  1743.9
  5039.7 1741.51    5105 1743.76    5157 1741.85    5175 1743.11  5180.1 1738.85
  5215.6 1744.06  5220.8 1741.86  5261.5 1744.22  5301.2 1741.71  5369.3 1740.75
  5440.9    1739    5508 1736.79  5580.6 1734.01  5801.9 1732.35  5854.1 1731.35
  5856.9 1730.85  5860.1 1731.35  6040.9 1732.96  6487.7 1755.86  6592.6 1757.59
#Mann= 12 ,-1 , 0
  3879.6      .1       0  4726.8     .05       0  4754.2      .1       0
    5105     .08       0  5301.2      .1       0  5369.3     .05       0
  5440.9      .1       0    5508     .05       0  5580.6     .08       0
  5801.9     .05       0  5854.1     .07       0  5860.1     .05       0
Bank Sta=5854.1,5860.1
XS Rating Curve= 0 ,0
Exp/Cntr=0.3,0.1

Type RM Length L Ch R = 1 ,1515    ,423,423,423
BEGIN DESCRIPTION:
Mapping XS 10031f0b
END DESCRIPTION:
XS GIS Cut Line= 3
      2755478.49     10072757.33      2754603.88     10070942.96
      2754226.28     10070875.26
#Sta/Elev= 30
  4362.1 1740.44  4660.6 1738.06  4813.5 1737.35  4862.4 1736.05  4881.3 1734.65
  4903.9 1731.08    4921 1730.82  4943.4 1731.65  4954.7 1733.86  4999.9 1736.52
  5113.3 1738.12  5208.6  1738.9  5211.7 1738.92  5452.3 1736.52  5487.3 1732.67
  5546.2    1732  5625.5 1730.83  5794.1 1728.69  5796.8 1728.19  5800.1 1728.69
  5880.7 1729.65    5990 1730.83  6096.6 1731.74  6131.2 1734.74  6192.6 1737.37
  6220.8 1739.85  6430.5 1746.16  6516.2 1748.42  6635.8 1753.89  6759.9 1756.02
#Mann= 13 ,-1 , 0
  4362.1      .1       0  4660.6     .05       0  4862.4      .1       0
  5113.3     .05       0  5208.6     .08       0  5211.7     .05       0
  5546.2     .08       0  5625.5     .05       0  5794.1     .07       0
  5800.1     .05       0  5880.7      .1       0    5990     .05       0
  6430.5     .08       0
Bank Sta=5794.1,5800.1
XS Rating Curve= 0 ,0
Exp/Cntr=0.3,0.1

Type RM Length L Ch R = 1 ,1092    ,893,893,893
BEGIN DESCRIPTION:
UNT 0064 IN HEWA 2.0
END DESCRIPTION:
XS GIS Cut Line= 4
      2755541.65     10073069.46      2755586.78     10071947.93
      2754643.92     10070937.24       2754247.1     10070798.87
#Sta/Elev= 30
  4041.5 1744.54  4447.1 1738.63  4747.8  1735.2  4807.8 1730.81  4887.9 1728.09
    4948 1730.31    4988 1725.43    4995 1725.35  4997.8 1724.85    5001 1725.35
    5028 1727.33  5068.1 1732.22  5077.2 1732.42  5250.8 1732.45  5492.1 1735.45
    5562  1736.3  5590.4  1734.8  5597.2 1735.63  5669.4 1734.25  5717.4 1731.13
  5802.4 1729.32  6052.8 1728.56    6286 1731.24  6304.8 1731.81  6326.1 1734.07
  6411.1 1737.48  6474.6 1741.42  6672.4 1747.03  6818.5 1754.24  6966.4 1755.09
#Mann= 9 ,-1 , 0
  4041.5      .1       0  4447.1     .05       0    4995    .035       0
    5001     .05       0  5492.1      .1       0  5669.4     .05       0
  6052.8      .1       0    6286     .05       0  6672.4     .08       0
Bank Sta=4995,5001
XS Rating Curve= 0 ,0
Exp/Cntr=0.3,0.1

Type RM Length L Ch R = 1 ,199     ,0,0,0
BEGIN DESCRIPTION:
UNT 0064 IN HEWA 1.0
END DESCRIPTION:
XS GIS Cut Line= 3
      2756226.31     10072453.71      2756027.34     10071681.72
      2755433.24     10071485.45
#Sta/Elev= 30
  4248.3 1740.19  4316.5 1738.04  4507.3 1732.55  4682.8 1729.37  4723.3 1729.56
  4782.7  1728.3  4847.2 1727.82  4943.1 1724.82  4960.8 1720.08  4978.6 1717.95
  4988.1 1717.71  4999.1 1715.62  5001.9 1715.12  5005.1 1715.62  5012.5 1716.65
  5019.3 1719.97  5024.5 1718.98  5033.1 1723.06  5041.9 1724.92  5060.8 1725.06
  5152.8 1725.86  5243.5 1728.92  5262.4 1729.06  5381.3 1728.49  5470.6  1729.6
  5565.4 1730.45  5572.1 1730.71  5578.1 1730.79  5655.2 1733.16  5671.2 1732.73
#Mann= 15 ,-1 , 0
  4248.3     .05       0  4316.5      .1       0  4507.3     .05       0
  4682.8      .1       0  4782.7     .05       0  4988.1     .16       0
  4999.1     .07       0  5005.1     .16       0  5060.8     .05       0
  5243.5     .08       0  5262.4      .1       0  5470.6     .08       0
  5565.4      .1       0  5572.1     .08       0  5578.1     .05       0
Bank Sta=4999.1,5005.1
XS Rating Curve= 0 ,0
Exp/Cntr=0.3,0.1