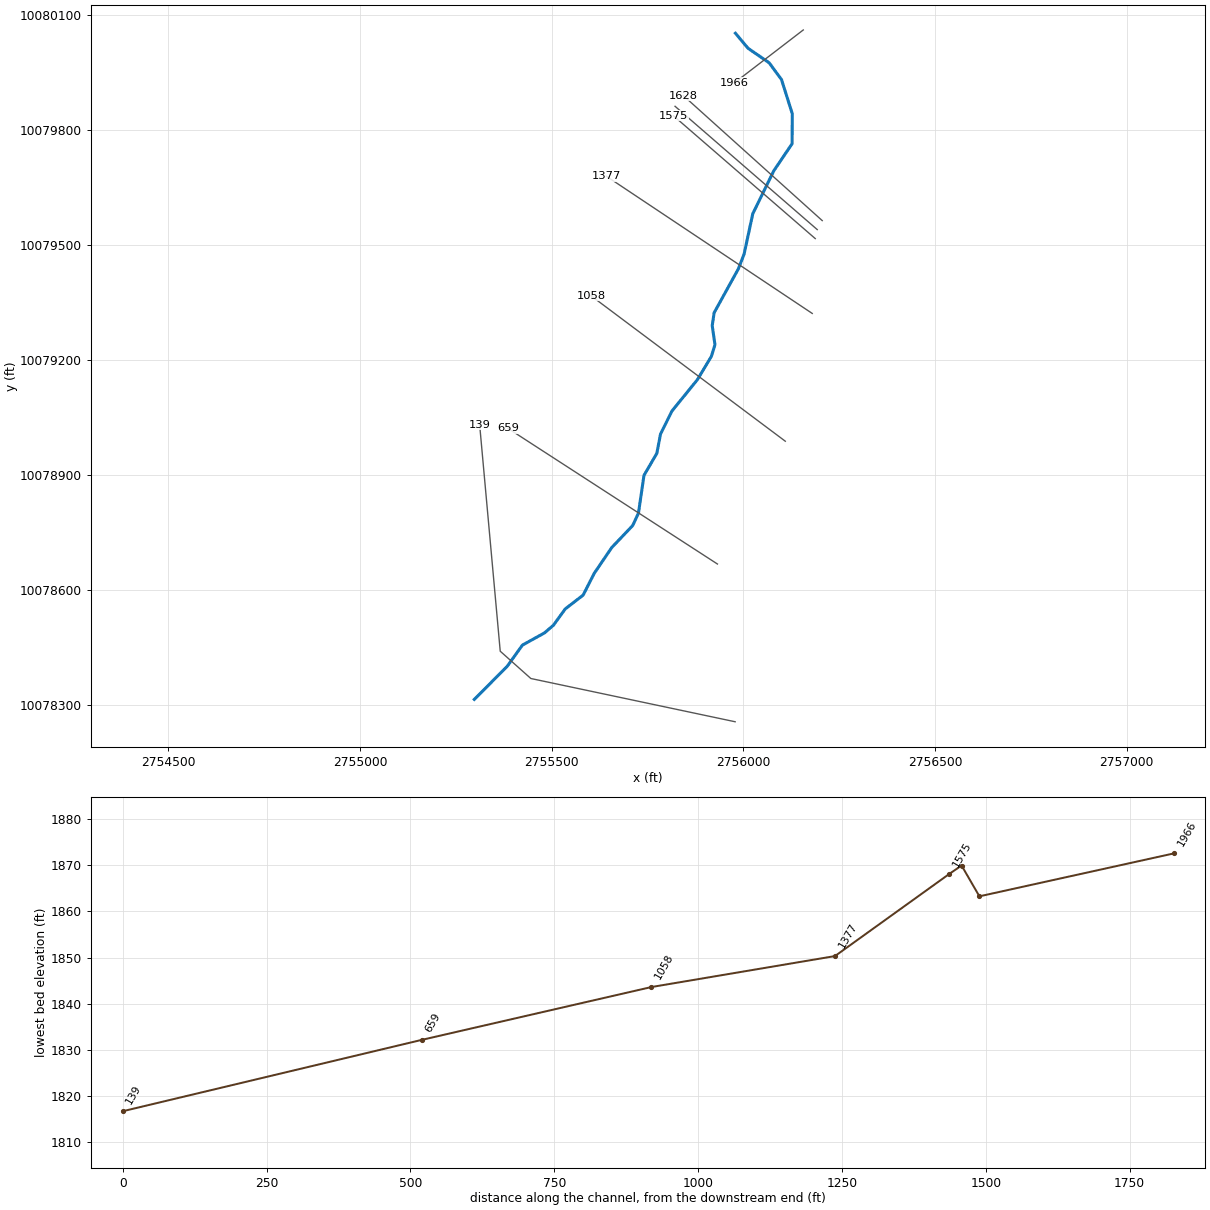
--- UNT 0065 IN HEWA.prj (project) ---

Proj Title=UNT 0065 IN HEWA Base Level Engineering
Current Plan=p01
Default Exp/Contr=0.3,0.1
English Units
Geom File=g01
Flow File=f01
Plan File=p01
BEGIN DESCRIPTION:
UNT 0065 IN HEWA
END DESCRIPTION:

--- UNT 0065 IN HEWA.p01 (plan) ---

Plan Title=Multiple Run
Short Identifier=Multiple
Geom File=g01
Flow File=f01
Subcritical Flow
K Sum by GR= 0
Std Step Tol= 0.01
Critical Tol= 0.01
Num of Std Step Trials= 20
Max Error Tol= 0.3
Flow Tol Ratio= 0.001
Split Flow NTrial= 30
Split Flow Tol= 0.02
Split Flow Ratio= 0.02
Log Output Level= 0
Friction Slope Method= 1
Unsteady Friction Slope Method= 2
Unsteady Bridges Friction Slope Method= 1
Parabolic Critical Depth
Global Vel Dist=  1 , 1 , 1
Global Log Level= 0
CheckData=True
Encroach Param= -1, 0, 0, 0
BEGIN DESCRIPTION:
Multiple Run
END DESCRIPTION:

--- UNT 0065 IN HEWA.f01 (steady flow) ---

Flow Title=Multiple
Number of Profiles=7
Profile Names=10-year,25-year,50-year,1pct_min,100-year,1pct_plu,500-year
River Rch & RM= UNT 0065 IN HEWA,Reach-1,1966
     246     332     403     360     487     659     712
Boundary for River Rch & Prof#=UNT 0065 IN HEWA,Reach-1,1
Up Type=0
Dn Type=3
Dn Slope=0.005
Boundary for River Rch & Prof#=UNT 0065 IN HEWA,Reach-1,2
Up Type=0
Dn Type=3
Dn Slope=0.005
Boundary for River Rch & Prof#=UNT 0065 IN HEWA,Reach-1,3
Up Type=0
Dn Type=3
Dn Slope=0.005
Boundary for River Rch & Prof#=UNT 0065 IN HEWA,Reach-1,4
Up Type=0
Dn Type=3
Dn Slope=0.005
Boundary for River Rch & Prof#=UNT 0065 IN HEWA,Reach-1,5
Up Type=0
Dn Type=3
Dn Slope=0.005
Boundary for River Rch & Prof#=UNT 0065 IN HEWA,Reach-1,6
Up Type=0
Dn Type=3
Dn Slope=0.005
Boundary for River Rch & Prof#=UNT 0065 IN HEWA,Reach-1,7
Up Type=0
Dn Type=3
Dn Slope=0.005

--- UNT 0065 IN HEWA.g01 (geometry) ---

Geom Title=Existing Conditions

River Reach=UNT 0065 IN HEWA,Reach-1
Reach XY= 30
      2755979.58     10080051.51      2756012.34     10080012.32
      2756067.49     10079974.44      2756099.79     10079930.55
      2756127.95     10079841.31      2756127.32     10079763.18
      2756079.73     10079692.81      2756024.83     10079580.69
      2756002.14     10079475.20      2755986.98     10079436.48
      2755924.04     10079322.41      2755918.99     10079288.61
      2755926.15     10079239.10      2755916.82     10079208.53
      2755880.31     10079147.69      2755814.05     10079066.13
      2755784.21     10079006.07      2755774.44     10078955.39
      2755740.99     10078898.07      2755726.58     10078799.55
      2755711.50     10078767.16      2755656.79     10078709.70
      2755611.21     10078642.52      2755582.17     10078585.61
      2755535.66     10078549.78      2755504.79     10078507.19
      2755481.72     10078487.28      2755423.89     10078455.34
      2755384.28     10078400.10      2755298.47     10078313.73

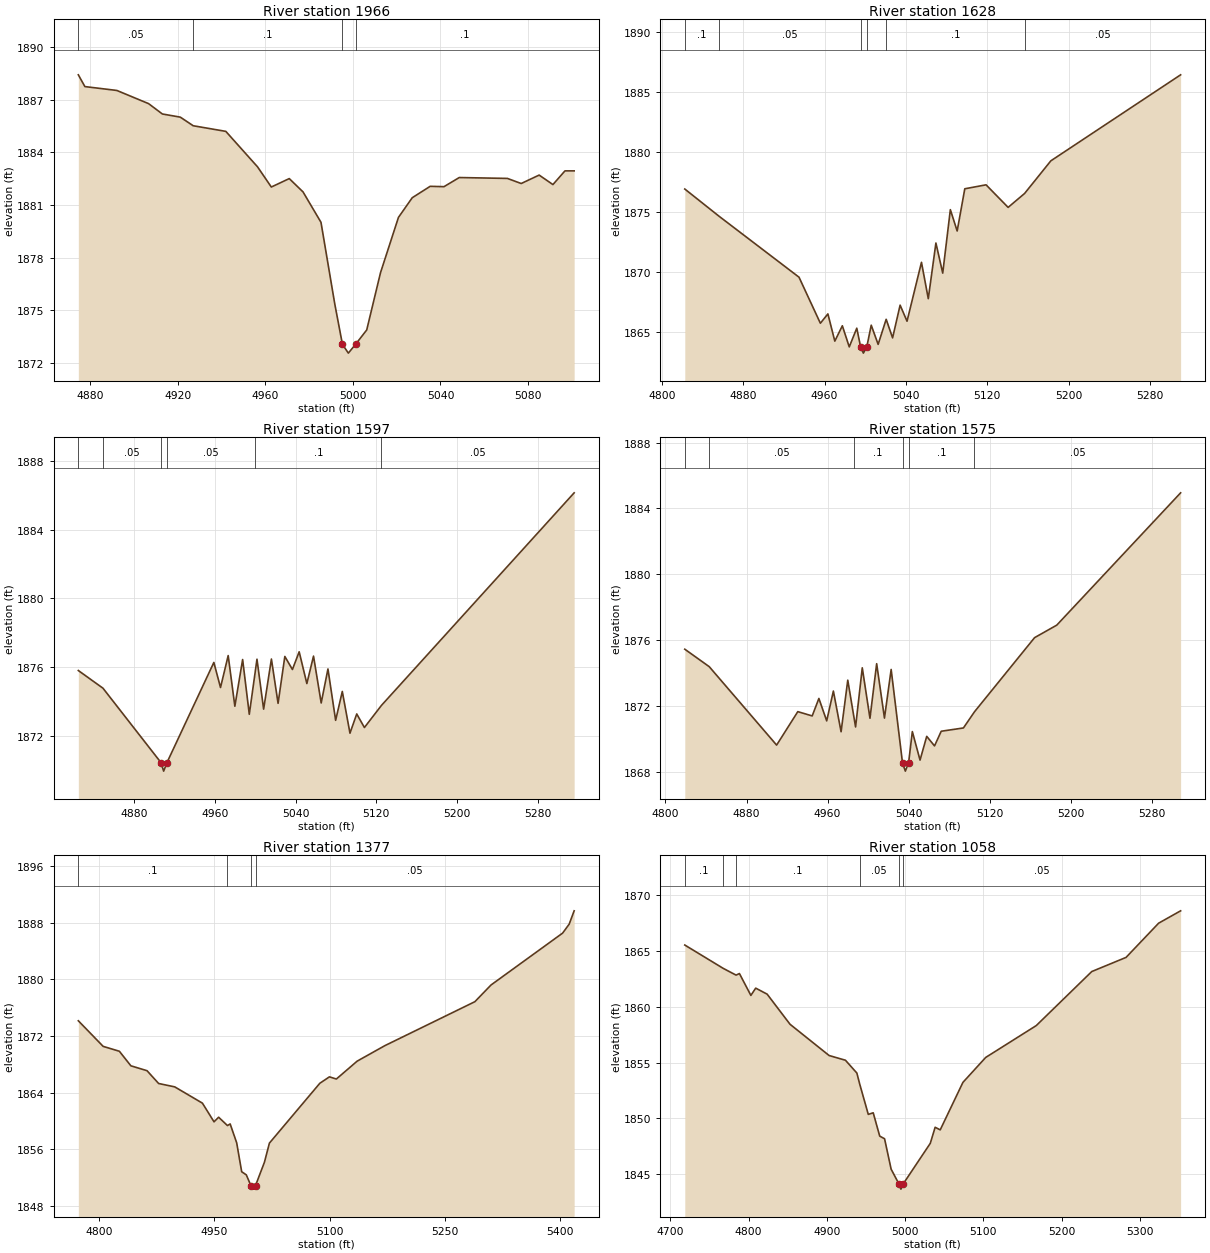
Type RM Length L Ch R = 1,1966,338,338,338
BEGIN DESCRIPTION:
UNT 0065 IN HEWA 4.0
END DESCRIPTION:
XS GIS Cut Line= 2
      2756156.53     10080060.08      2755976.83     10079922.04
#Sta/Elev= 30
  4874.5 1888.41  4877.5 1887.74  4892.1 1887.52  4906.6 1886.77  4912.9 1886.18
  4921.1 1886.00  4927.0 1885.51  4941.9 1885.19  4956.4 1883.17  4962.7 1882.02
  4970.9 1882.50  4977.2 1881.74  4985.4 1880.01  4991.7 1875.36  4995.2 1873.06
  4997.9 1872.56  5001.2 1873.06  5006.3 1873.88  5012.6 1877.14  5020.8 1880.29
  5027.1 1881.41  5035.3 1882.06  5041.6 1882.04  5048.6 1882.56  5070.6 1882.51
  5076.9 1882.22  5085.1 1882.70  5091.4 1882.16  5096.9 1882.94  5101.1 1882.94
#Mann=4,-1,0
  4874.5    0.05       0  4927.0     0.1       0  4995.2    0.07       0
  5001.2     0.1       0
Bank Sta=4995.2,5001.2
Exp/Cntr=0.3,0.1

Type RM Length L Ch R = 1,1628,31,31,31
BEGIN DESCRIPTION:
Mapping XS 9b241356
END DESCRIPTION:
XS GIS Cut Line= 2
      2756206.00     10079562.71      2755843.65     10079888.83
#Sta/Elev= 30
  4822.6 1876.95  4856.3 1874.68  4934.9 1869.60  4955.9 1865.76  4963.3 1866.54
  4970.1 1864.27  4977.5 1865.55  4984.3 1863.79  4991.7 1865.35  4995.5 1863.77
  4998.2 1863.27  5001.5 1863.77  5005.9 1865.60  5012.7 1864.00  5020.6 1866.09
  5026.9 1864.54  5034.3 1867.27  5041.1 1865.93  5055.3 1870.84  5062.0 1867.81
  5069.5 1872.45  5076.2 1869.94  5083.7 1875.23  5090.4 1873.45  5097.9 1876.97
  5118.8 1877.30  5140.5 1875.42  5156.7 1876.58  5182.5 1879.30  5310.1 1886.47
#Mann=6,-1,0
  4822.6     0.1       0  4856.3    0.05       0  4995.5   0.035       0
  5001.5    0.05       0  5020.6     0.1       0  5156.7    0.05       0
Bank Sta=4995.5,5001.5
Exp/Cntr=0.3,0.1

Type RM Length L Ch R = 1,1597,22,22,22
BEGIN DESCRIPTION:
Mapping XS bd596aed
END DESCRIPTION:
XS GIS Cut Line= 2
      2756193.00     10079539.25      2755822.05     10079860.92
#Sta/Elev= 30
  4824.9 1875.80  4849.3 1874.77  4906.7 1870.44  4909.4 1869.94  4912.7 1870.44
  4959.1 1876.27  4965.7 1874.81  4973.3 1876.67  4979.9 1873.72  4987.6 1876.44
  4994.2 1873.25  5000.2 1875.78  5001.8 1876.46  5008.4 1873.55  5016.1 1876.47
  5022.7 1873.89  5029.4 1876.62  5036.9 1875.86  5043.6 1876.89  5051.2 1875.04
  5057.8 1876.64  5065.4 1873.91  5072.1 1875.89  5079.7 1872.90  5086.3 1874.58
  5093.9 1872.15  5100.6 1873.27  5108.2 1872.48  5125.1 1873.77  5315.9 1886.15
#Mann=6,-1,0
  4824.9     0.1       0  4849.3    0.05       0  4906.7   0.035       0
  4912.7    0.05       0  5000.2     0.1       0  5125.1    0.05       0
Bank Sta=4906.7,4912.7
Exp/Cntr=0.3,0.1

Type RM Length L Ch R = 1,1575,198,198,198
BEGIN DESCRIPTION:
Mapping XS 617cf9d5
END DESCRIPTION:
XS GIS Cut Line= 2
      2756187.80     10079515.81      2755818.03     10079836.11
#Sta/Elev= 30
  4819.1 1875.46  4843.2 1874.40  4909.7 1869.64  4930.6 1871.67  4944.8 1871.41
  4951.4 1872.47  4959.1 1871.11  4965.7 1872.92  4973.3 1870.45  4979.9 1873.58
  4985.7 1871.44  4987.6 1870.74  4994.2 1874.33  5001.8 1871.27  5008.4 1874.58
  5016.1 1871.28  5022.7 1874.23  5033.9 1868.56  5036.7 1868.06  5039.9 1868.56
  5043.6 1870.46  5051.2 1868.73  5057.8 1870.17  5065.5 1869.59  5072.1 1870.48
  5094.0 1870.68  5104.9 1871.66  5164.2 1876.16  5186.1 1876.92  5308.3 1884.95
#Mann=6,-1,0
  4819.1     0.1       0  4843.2    0.05       0  4985.7     0.1       0
  5033.9    0.07       0  5039.9     0.1       0  5104.9    0.05       0
Bank Sta=5033.9,5039.9
Exp/Cntr=0.3,0.1

Type RM Length L Ch R = 1,1377,319,319,319
BEGIN DESCRIPTION:
UNT 0065 IN HEWA 3.0
END DESCRIPTION:
XS GIS Cut Line= 2
      2756179.97     10079320.52      2755643.04     10079678.46
#Sta/Elev= 30
  4772.8 1874.15  4805.1 1870.53  4826.2 1869.84  4841.2 1867.78  4862.2 1867.09
  4877.3 1865.28  4898.3 1864.80  4934.3 1862.50  4949.4 1859.86  4955.4 1860.51
  4966.9 1859.33  4970.4 1859.56  4978.9 1856.89  4985.4 1852.80  4991.4 1852.36
  4997.4 1850.84  5000.2 1850.34  5003.4 1850.84  5015.0 1854.14  5021.5 1856.85
  5087.1 1865.31  5099.6 1866.22  5108.6 1865.91  5135.7 1868.44  5171.7 1870.63
  5288.9 1876.85  5309.9 1879.21  5403.1 1886.55  5411.6 1887.81  5418.1 1889.70
#Mann=4,-1,0
  4772.8     0.1       0  4966.9    0.05       0  4997.4   0.035       0
  5003.4    0.05       0
Bank Sta=4997.4,5003.4
Exp/Cntr=0.3,0.1

Type RM Length L Ch R = 1,1058,399,399,399
BEGIN DESCRIPTION:
UNT 0065 IN HEWA 2.0
END DESCRIPTION:
XS GIS Cut Line= 2
      2756109.68     10078987.17      2755602.64     10079366.79
#Sta/Elev= 30
  4718.6 1865.55  4767.8 1863.45  4784.1 1862.85  4788.4 1862.99  4803.0 1861.03
  4809.2 1861.68  4823.8 1861.14  4853.0 1858.44  4903.0 1855.63  4923.8 1855.21
  4938.4 1854.06  4942.2 1853.03  4953.0 1850.35  4959.3 1850.49  4967.6 1848.40
  4973.8 1848.16  4982.2 1845.43  4991.9 1844.14  4994.7 1843.64  4997.9 1844.14
  5032.2 1847.75  5038.4 1849.19  5044.9 1848.96  5073.9 1853.22  5103.0 1855.46
  5167.6 1858.32  5238.5 1863.17  5282.3 1864.44  5323.9 1867.51  5352.0 1868.62
#Mann=6,-1,0
  4718.6     0.1       0  4767.8    0.05       0  4784.1     0.1       0
  4942.2    0.05       0  4991.9   0.035       0  4997.9    0.05       0
Bank Sta=4991.9,4997.9
Exp/Cntr=0.3,0.1

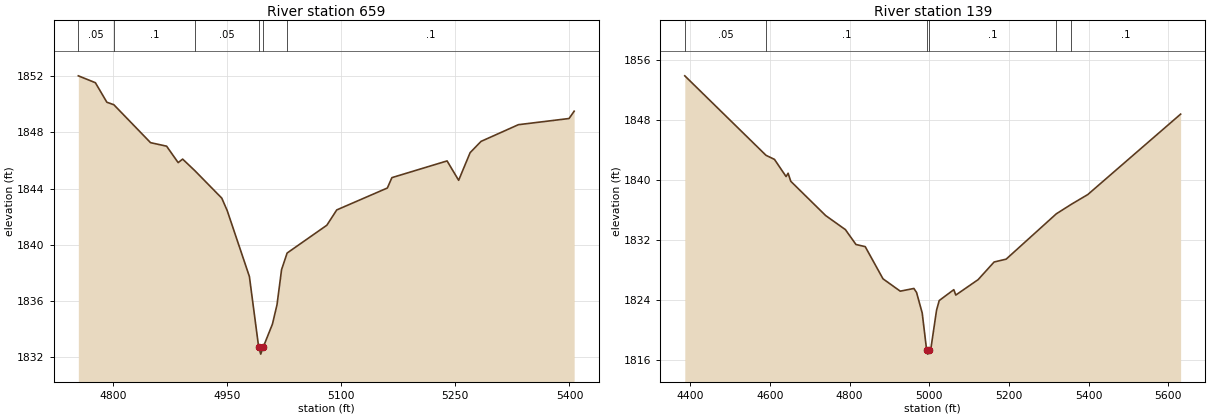
Type RM Length L Ch R = 1,659,520,520,520
BEGIN DESCRIPTION:
Mapping XS 466273b0
END DESCRIPTION:
XS GIS Cut Line= 2
      2755932.62     10078666.84      2755385.70     10079021.04
#Sta/Elev= 30
  4754.6 1852.03  4777.0 1851.54  4792.1 1850.15  4801.3 1849.97  4849.5 1847.27
  4870.6 1847.02  4885.8 1845.85  4891.7 1846.10  4908.0 1845.26  4943.1 1843.32
  4950.2 1842.44  4979.4 1837.74  4991.6 1832.71  4994.3 1832.21  4997.6 1832.71
  5009.7 1834.35  5015.7 1835.73  5021.7 1838.23  5029.0 1839.41  5081.2 1841.39
  5094.2 1842.48  5160.7 1844.04  5166.7 1844.78  5239.2 1845.97  5254.4 1844.59
  5269.5 1846.56  5283.8 1847.36  5332.9 1848.55  5399.5 1848.99  5406.2 1849.51
#Mann=6,-1,0
  4754.6    0.05       0  4801.3     0.1       0  4908.0    0.05       0
  4991.6   0.035       0  4997.6    0.05       0  5029.0     0.1       0
Bank Sta=4991.6,4997.6
Exp/Cntr=0.3,0.1

Type RM Length L Ch R = 1,139,0,0,0
BEGIN DESCRIPTION:
UNT 0065 IN HEWA 1.0
END DESCRIPTION:
XS GIS Cut Line= 4
      2755978.82     10078255.35      2755445.85     10078368.19
      2755365.99     10078439.37      2755312.29     10079030.08
#Sta/Elev= 30
  4386.2 1853.89  4590.0 1843.29  4611.4 1842.74  4640.5 1840.45  4645.6 1840.89
  4652.3 1839.82  4739.8 1835.25  4789.5 1833.37  4815.9 1831.39  4839.2 1831.10
  4883.8 1826.81  4927.1 1825.16  4961.4 1825.52  4968.1 1824.99  4982.3 1822.24
  4993.5 1817.26  4996.3 1816.76  4999.5 1817.26  5004.0 1817.47  5018.3 1822.62
  5025.0 1823.91  5061.6 1825.36  5066.6 1824.64  5122.7 1826.70  5162.8 1829.05
  5193.0 1829.43  5319.0 1835.48  5357.0 1836.76  5398.0 1838.05  5631.1 1848.78
#Mann=6,-1,0
  4386.2    0.05       0  4590.0     0.1       0  4993.5    0.07       0
  4999.5     0.1       0  5319.0    0.05       0  5357.0     0.1       0
Bank Sta=4993.5,4999.5
Exp/Cntr=0.3,0.1

Chan Stop Cuts=-1