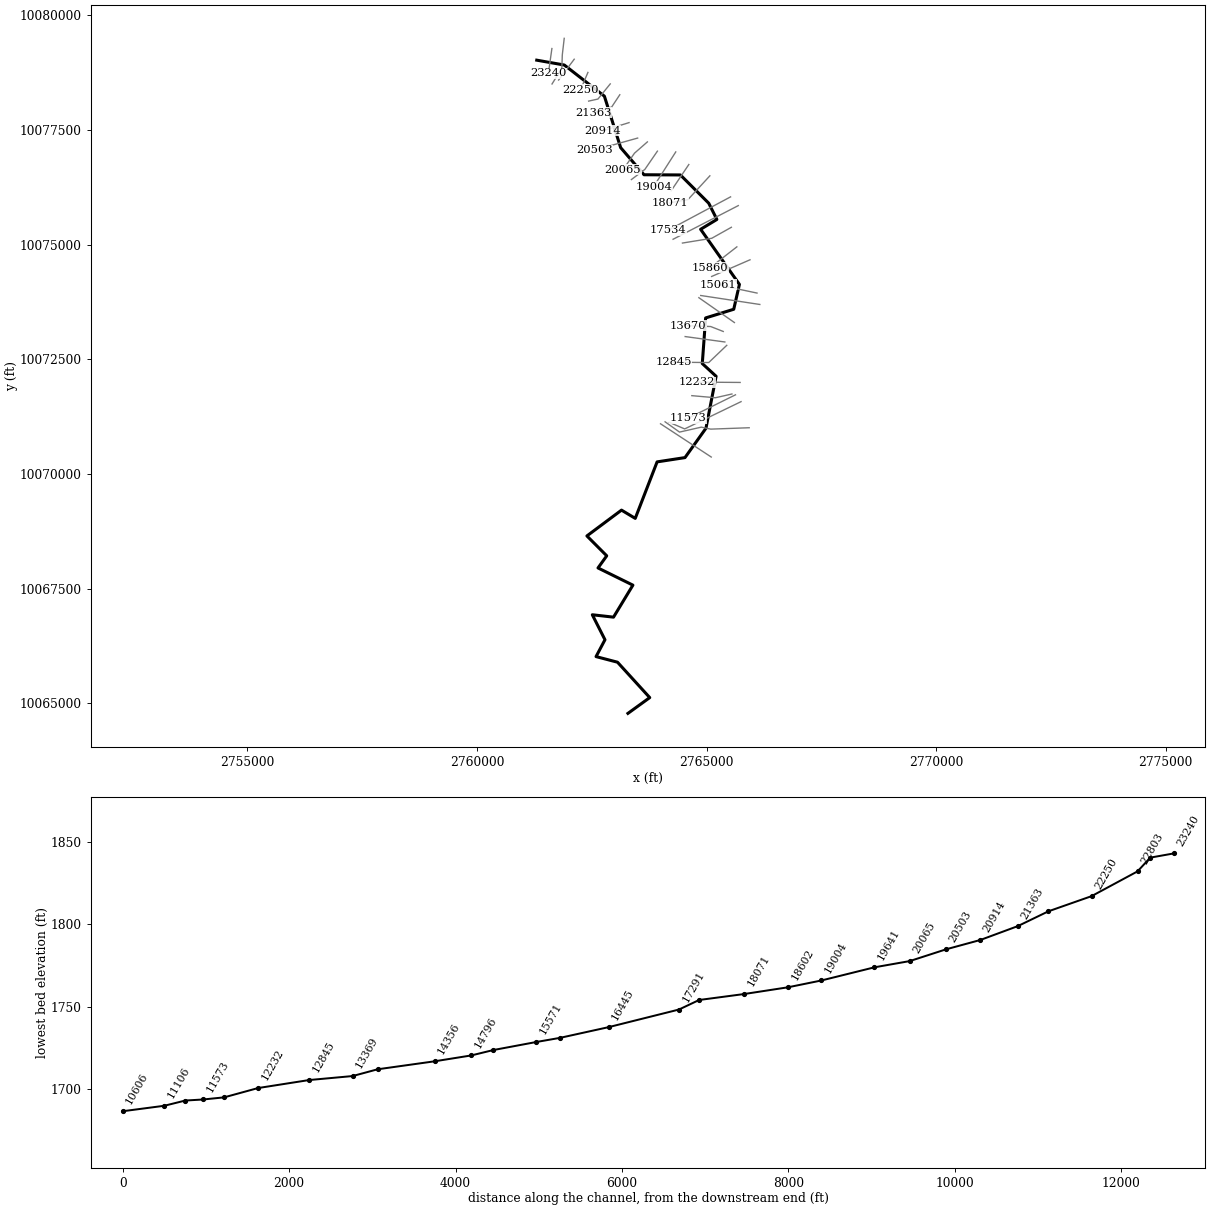
--- UNT 0067 IN HEWA.prj (project) ---

Proj Title=UNT 0067 IN HEWA Base Level Engineering
Current Plan=p01
Default Exp/Contr=0.3,0.1
English Units
Geom File=g01
Flow File=f01
Plan File=p01
Y Axis Title=Elevation
X Axis Title(PF)=Main Channel Distance
X Axis Title(XS)=Station
BEGIN DESCRIPTION:
UNT 0067 IN HEWA
END DESCRIPTION:
DSS Export Rating Curves= 0
DSS Export Rating Curve Sorted= 0
DSS Export Volume Flow Curves= 0
DXF OffsetX= 0
DXF OffsetY= 0
DXF ScaleX= 1
DXF ScaleY= 10

--- UNT 0067 IN HEWA.p01 (plan) ---

Plan Title=Multiple Run
Short Identifier=Multiple
Geom File=g01
Flow File=f01
Subcritical Flow
K Sum by GR= 0
Std Step Tol= 0.01
Critical Tol= 0.01
Num of Std Step Trials= 20
Max Error Tol= 0.3
Flow Tol Ratio= 0.001
Split Flow NTrial= 30
Split Flow Tol= 0.02
Split Flow Ratio= 0.02
Log Output Level= 0
Friction Slope Method= 1
Unsteady Friction Slope Method= 2
Unsteady Bridges Friction Slope Method= 1
Parabolic Critical Depth
Global Vel Dist=  1 , 1 , 1
Global Log Level= 0
CheckData=True
Encroach Param= -1, 0, 0, 0
BEGIN DESCRIPTION:
Multiple Run
END DESCRIPTION:

--- UNT 0067 IN HEWA.f01 (steady flow) ---

Flow Title=Multiple
Number of Profiles=7
Profile Names=10-year,25-year,50-year,1pct_min,100-year,1pct_plu,500-year
River Rch & RM= UNT 0067 IN HEWA,Reach-1,23240
     801    1160    1472    1368    1850    2502    2934
River Rch & RM= UNT 0067 IN HEWA,Reach-1,17291
    1097    1610    2060    1927    2606    3525    4191
River Rch & RM= UNT 0067 IN HEWA,Reach-1,11358
    1375    2038    2624    2469    3340    4516    5434
River Rch & RM= UNT 0067 IN HEWA,Reach-1,7253
    1665    2484    3213    3033    4102    5547    6719
River Rch & RM= UNT 0067 IN HEWA,Reach-1,3476
    1779    2661    3447    3258    4406    5959    7238
Boundary for River Rch & Prof#=UNT 0067 IN HEWA,Reach-1,1
Up Type=0
Dn Type=3
Dn Slope=0.005
Boundary for River Rch & Prof#=UNT 0067 IN HEWA,Reach-1,2
Up Type=0
Dn Type=3
Dn Slope=0.005
Boundary for River Rch & Prof#=UNT 0067 IN HEWA,Reach-1,3
Up Type=0
Dn Type=3
Dn Slope=0.005
Boundary for River Rch & Prof#=UNT 0067 IN HEWA,Reach-1,4
Up Type=0
Dn Type=3
Dn Slope=0.005
Boundary for River Rch & Prof#=UNT 0067 IN HEWA,Reach-1,5
Up Type=0
Dn Type=3
Dn Slope=0.005
Boundary for River Rch & Prof#=UNT 0067 IN HEWA,Reach-1,6
Up Type=0
Dn Type=3
Dn Slope=0.005
Boundary for River Rch & Prof#=UNT 0067 IN HEWA,Reach-1,7
Up Type=0
Dn Type=3
Dn Slope=0.005

--- UNT 0067 IN HEWA.g01 (geometry) ---

Geom Title=Existing Conditions
Program Version=4.10

River Reach=UNT 0067 IN HEWA,Reach-1
Reach XY= 30
      2761302.24     10079021.21      2761902.92     10078915.13
      2762775.34     10078237.11      2763130.08     10077114.41
      2763638.96     10076523.59      2764431.42     10076519.47
      2765048.47     10075903.73      2765226.07     10075549.48
      2764871.99     10075335.12      2765717.13     10074133.86
      2765593.34     10073591.95      2764980.95     10073402.75
      2764908.16      10072408.6        2765209.     10072131.52
      2764988.32     10070998.77      2764531.19     10070358.58
      2763923.93     10070265.45      2763447.66     10069033.83
       2763148.5      10069213.9      2762394.95     10068651.32
      2762826.64       10068218.      2762636.64     10067953.39
      2763396.82     10067578.52      2762974.52     10066881.09
      2762512.43     10066933.16      2762788.39      10066388.5
      2762593.92     10066021.28      2763061.24     10065899.04
      2763763.34     10065127.64      2763288.47     10064783.73

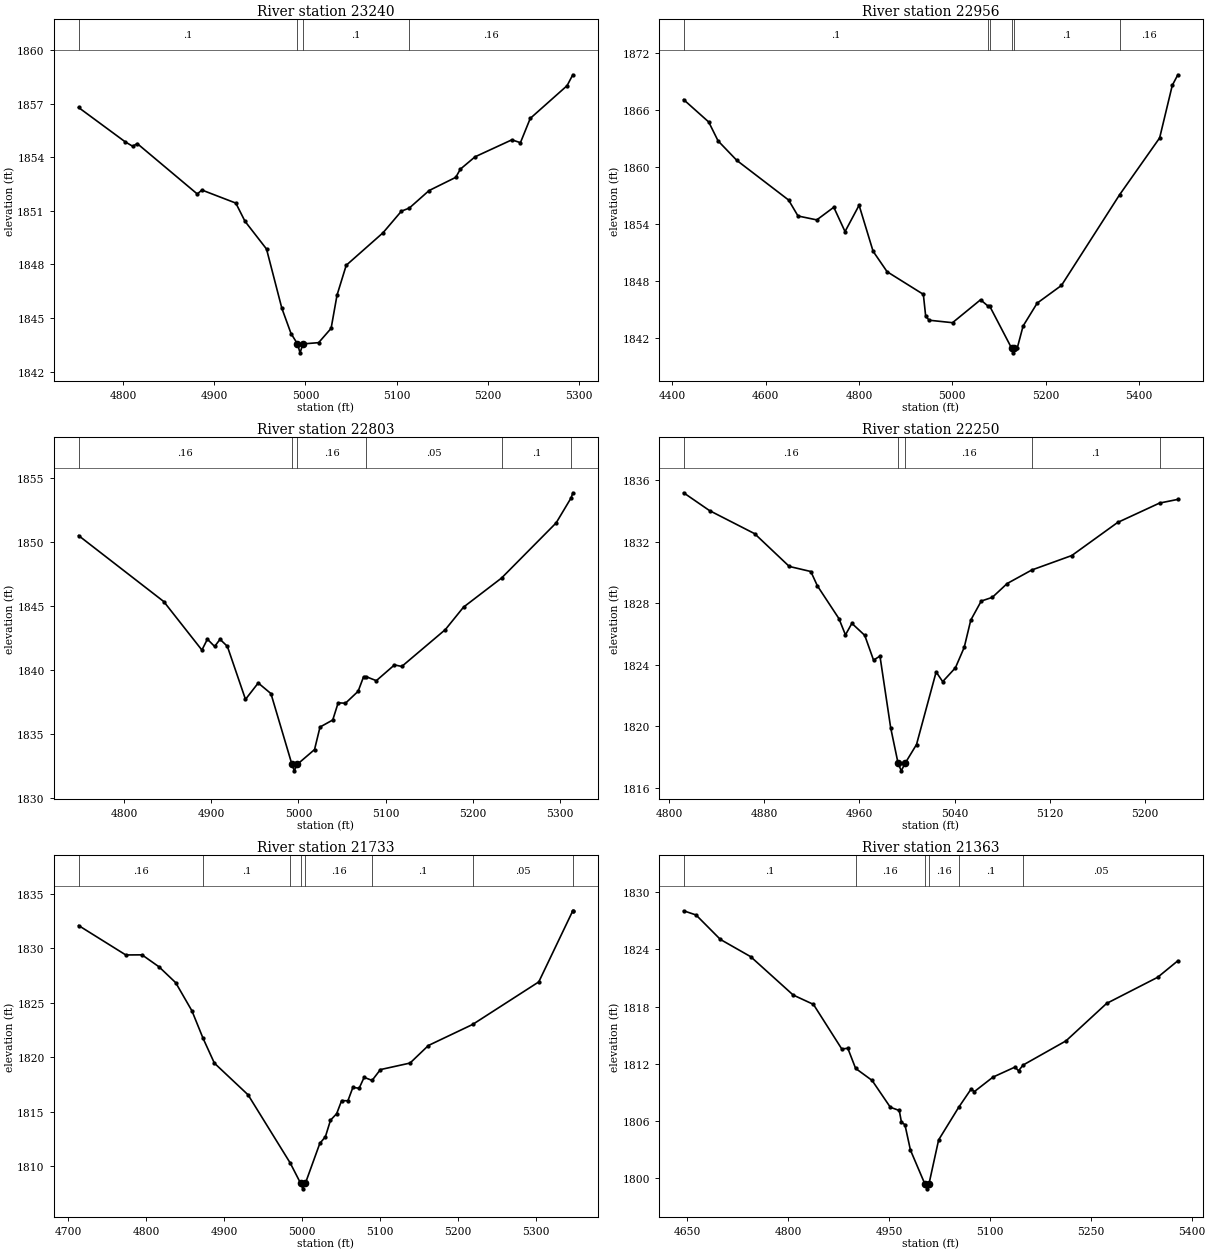
Type RM Length L Ch R = 1 ,23240   ,284,284,284
BEGIN DESCRIPTION:
UNT 0067 IN HEWA 48.0
END DESCRIPTION:
XS GIS Cut Line= 2
      2761632.22     10079274.65      2761555.98     10078737.53
#Sta/Elev= 30
    4751 1856.78  4802.4 1854.85  4810.4 1854.61  4815.4 1854.76  4881.3 1851.94
  4886.4 1852.16  4923.6 1851.43  4933.7 1850.41  4957.3 1848.86  4974.1 1845.55
  4984.2 1844.13  4991.3 1843.55  4994.1 1843.05  4997.3 1843.55  5014.5 1843.62
  5028.2 1844.42  5034.7 1846.28  5044.8 1847.95  5085.2 1849.77  5105.4 1850.98
    5114 1851.15  5135.7 1852.13    5165 1852.87  5170.1 1853.33  5186.2 1854.02
  5226.6 1854.97    5236 1854.81  5246.8 1856.17  5287.2    1858  5293.5 1858.61
#Mann= 4 ,-1 , 0
    4751      .1       0  4991.3     .07       0  4997.3      .1       0
    5114     .16       0
Bank Sta=4991.3,4997.3
XS Rating Curve= 0 ,0
Exp/Cntr=0.3,0.1

Type RM Length L Ch R = 1 ,22956   ,153,153,153
BEGIN DESCRIPTION:
Mapping XS bee19691
END DESCRIPTION:
XS GIS Cut Line= 4
      2761900.64     10079497.08      2761858.97     10079137.66
      2761848.55       10078846.      2761634.99     10078502.21
#Sta/Elev= 30
  4424.6 1867.12  4478.3 1864.77  4498.4 1862.78  4538.7 1860.72  4649.4 1856.56
  4669.6 1854.88  4709.8 1854.47  4746.2  1855.8  4770.3 1853.24  4800.4 1856.01
  4830.4 1851.17  4860.4 1849.02    4938 1846.64    4943 1844.34  4950.5 1843.92
  5000.5 1843.66  5060.5 1846.07  5076.9 1845.39  5080.2 1845.39  5126.9 1840.99
  5129.6 1840.49  5132.9 1840.99  5139.3 1841.03  5151.6 1843.31  5181.8 1845.72
  5233.8 1847.58  5358.2 1857.11    5444 1863.09  5471.1 1868.62    5483 1869.73
#Mann= 6 ,-1 , 0
  4424.6      .1       0  5076.9     .16       0  5080.2      .1       0
  5126.9     .07       0  5132.9      .1       0  5358.2     .16       0
Bank Sta=5126.9,5132.9
XS Rating Curve= 0 ,0
Exp/Cntr=0.3,0.1

Type RM Length L Ch R = 1 ,22803   ,553,553,553
BEGIN DESCRIPTION:
UNT 0067 IN HEWA 47.0
END DESCRIPTION:
XS GIS Cut Line= 2
      2762118.31     10079041.95      2761778.66     10078587.93
#Sta/Elev= 30
  4747.7 1850.51  4845.4 1845.36  4889.2 1841.57  4895.5 1842.42  4903.8 1841.85
    4910 1842.41  4918.4 1841.86  4939.2 1837.72  4953.8    1839  4968.4 1838.17
  4992.5 1832.64  4995.2 1832.14  4998.5 1832.64  5018.4  1833.8  5024.7 1835.56
  5039.3 1836.11  5045.5 1837.45  5053.9 1837.42  5068.4 1838.35  5074.7 1839.49
  5077.7 1839.49  5089.3 1839.18  5110.1 1840.41  5118.5 1840.29  5168.5 1843.17
  5189.3 1844.92  5232.9 1847.19  5295.6  1851.5  5312.9 1853.47  5314.7 1853.85
#Mann= 6 ,-1 , 0
  4747.7     .16       0  4992.5     .07       0  4998.5     .16       0
  5077.7     .05       0  5232.9      .1       0  5312.9     .16       0
Bank Sta=4992.5,4998.5
XS Rating Curve= 0 ,0
Exp/Cntr=0.3,0.1

Type RM Length L Ch R = 1 ,22250   ,517,517,517
BEGIN DESCRIPTION:
UNT 0067 IN HEWA 46.0
END DESCRIPTION:
XS GIS Cut Line= 2
      2762416.92     10078753.73      2762253.74     10078371.83
#Sta/Elev= 30
  4812.2 1835.18    4834 1834.02  4871.9 1832.52    4901 1830.39  4919.1 1830.06
  4924.6 1829.13  4942.7    1827  4948.2 1825.94  4953.6 1826.69  4964.4 1825.91
  4971.8  1824.3  4977.2 1824.56  4986.2  1819.9  4992.4  1817.6  4995.1  1817.1
  4998.4  1817.6  5007.9 1818.81  5024.4 1823.53  5029.9  1822.9  5040.6  1823.8
    5048 1825.13  5053.5  1826.9  5062.3 1828.14  5071.6 1828.38  5084.1 1829.28
  5104.8 1830.16  5138.4  1831.1  5176.9 1833.25  5212.1 1834.51  5227.5 1834.75
#Mann= 5 ,-1 , 0
  4812.2     .16       0  4992.4     .07       0  4998.4     .16       0
  5104.8      .1       0  5212.1     .05       0
Bank Sta=4992.4,4998.4
XS Rating Curve= 0 ,0
Exp/Cntr=0.3,0.1

Type RM Length L Ch R = 1 ,21733   ,370,370,370
BEGIN DESCRIPTION:
UNT 0067 IN HEWA 45.0
END DESCRIPTION:
XS GIS Cut Line= 3
      2762903.07      10078503.8      2762635.69     10078173.92
      2762432.11     10078129.06
#Sta/Elev= 30
  4713.6 1832.07  4774.1 1829.37  4794.9 1829.38  4816.7 1828.28    4838 1826.83
  4858.8 1824.25    4873 1821.74  4887.6 1819.45  4930.7 1816.55  4984.7  1810.3
  4998.1 1808.43  5000.8 1807.93  5004.1 1808.43  5022.6 1812.09  5029.8 1812.71
  5036.3 1814.22  5044.2 1814.82  5050.6 1816.02  5058.6    1816    5065 1817.23
    5073 1817.15  5079.4 1818.15  5089.6 1817.87  5100.2 1818.86  5138.2 1819.46
  5161.7 1821.07  5218.4    1823  5303.1  1826.9  5346.5 1833.39  5346.7 1833.42
#Mann= 8 ,-1 , 0
  4713.6     .16       0    4873      .1       0  4984.7     .16       0
  4998.1     .07       0  5004.1     .16       0  5089.6      .1       0
  5218.4     .05       0  5346.5      .1       0
Bank Sta=4998.1,5004.1
XS Rating Curve= 0 ,0
Exp/Cntr=0.3,0.1

Type RM Length L Ch R = 1 ,21363   ,449,449,449
BEGIN DESCRIPTION:
UNT 0067 IN HEWA 44.0
END DESCRIPTION:
XS GIS Cut Line= 3
      2763111.36     10078267.63       2762934.3     10078000.31
      2762538.48     10077878.78
#Sta/Elev= 30
  4644.7 1828.04  4663.2  1827.6  4699.3 1825.04  4744.4 1823.23  4807.6 1819.21
  4837.7 1818.23  4879.8 1813.56  4888.8 1813.63  4900.4 1811.52  4924.9 1810.26
    4952 1807.45  4965.3 1807.11  4968.5 1805.89  4973.7 1805.62  4981.9 1802.96
  5003.4  1799.4  5006.2  1798.9  5009.4  1799.4  5023.8 1804.03  5053.5 1807.43
  5071.9 1809.34  5077.1  1809.1  5104.6 1810.61  5137.3 1811.66  5142.6 1811.27
  5149.3 1811.87  5213.2 1814.41  5273.5 1818.33  5349.4 1821.07  5379.4  1822.8
#Mann= 6 ,-1 , 0
  4644.7      .1       0  4900.4     .16       0  5003.4     .07       0
  5009.4     .16       0  5053.5      .1       0  5149.3     .05       0
Bank Sta=5003.4,5009.4
XS Rating Curve= 0 ,0
Exp/Cntr=0.3,0.1

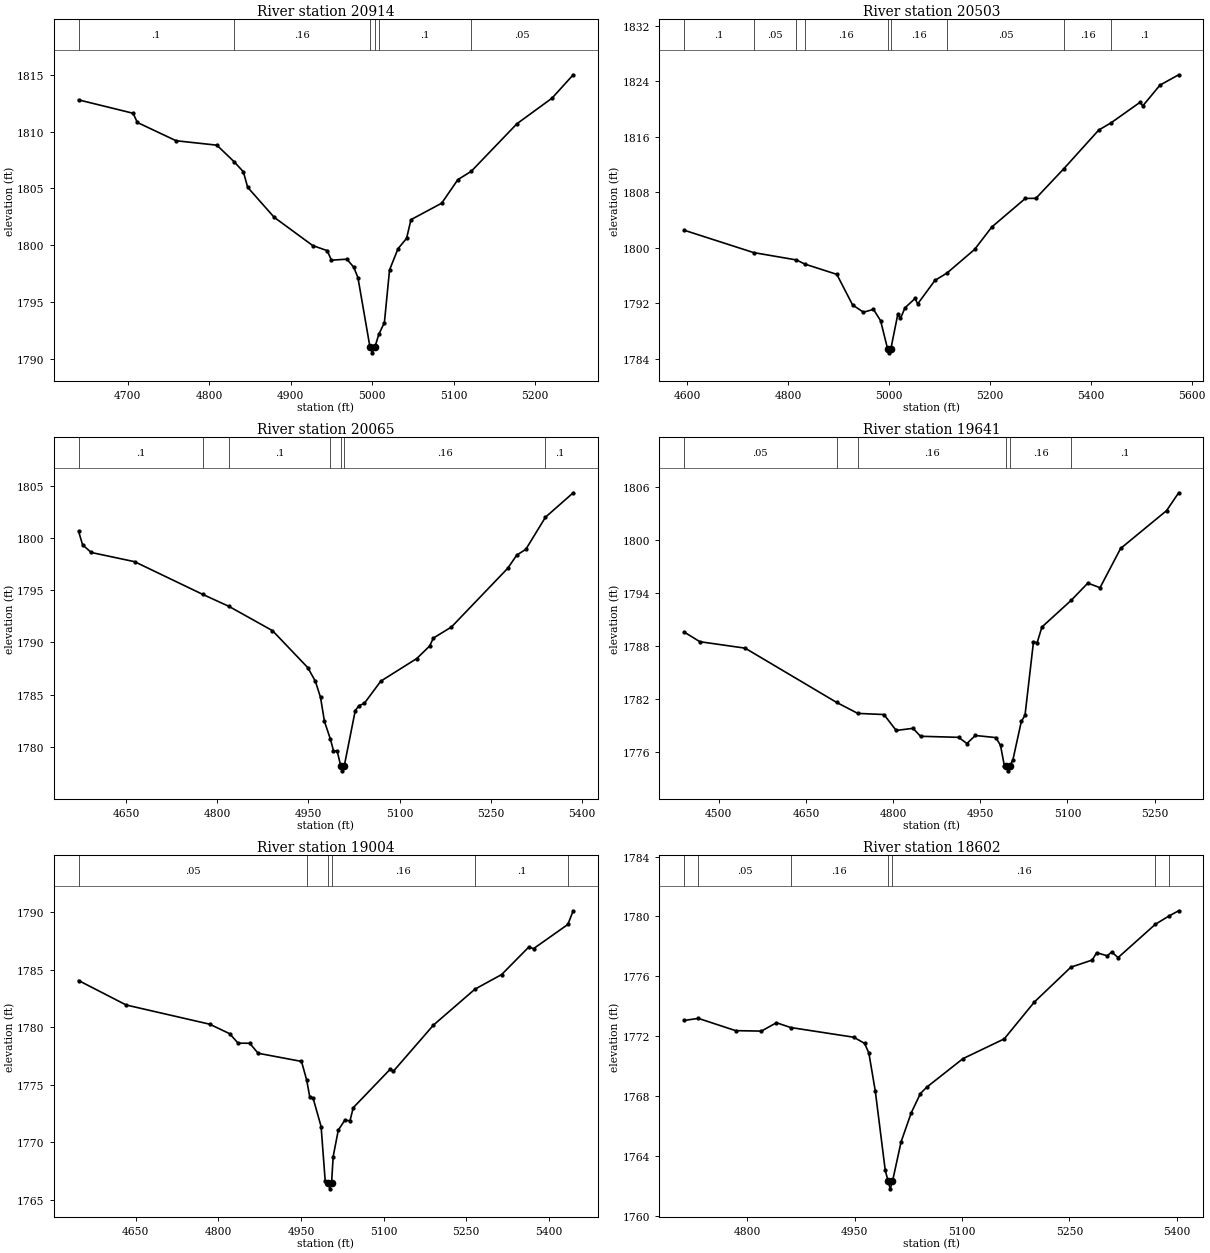
Type RM Length L Ch R = 1 ,20914   ,411,411,411
BEGIN DESCRIPTION:
UNT 0067 IN HEWA 43.0
END DESCRIPTION:
XS GIS Cut Line= 2
      2763312.78     10077660.03      2762733.22     10077479.57
#Sta/Elev= 30
  4639.8 1812.79  4706.7 1811.61  4711.9  1810.8  4759.5 1809.19  4809.5  1808.8
  4830.4 1807.36    4842 1806.46  4847.3 1805.09  4879.8 1802.45  4927.1 1799.96
  4944.9 1799.51  4950.1 1798.67    4969 1798.76  4977.4 1798.06  4982.6 1797.14
  4997.4 1791.01  5000.2 1790.51  5003.4 1791.01  5008.2 1792.13  5015.1 1793.18
  5021.4 1797.81  5031.8 1799.68  5042.3 1800.59  5047.7 1802.24  5085.4 1803.69
  5105.2 1805.76  5121.7  1806.5  5177.8 1810.69  5220.8 1812.94  5246.8    1815
#Mann= 6 ,-1 , 0
  4639.8      .1       0  4830.4     .16       0  4997.4     .07       0
  5003.4     .16       0  5008.2      .1       0  5121.7     .05       0
Bank Sta=4997.4,5003.4
XS Rating Curve= 0 ,0
Exp/Cntr=0.3,0.1

Type RM Length L Ch R = 1 ,20503   ,438,438,438
BEGIN DESCRIPTION:
UNT 0067 IN HEWA 42.0
END DESCRIPTION:
XS GIS Cut Line= 2
      2763500.23     10077323.21       2762555.8     10077059.33
#Sta/Elev= 30
  4593.7 1802.54  4731.7 1799.31  4816.5 1798.25    4833 1797.66  4896.6 1796.17
  4927.8 1791.77  4949.3 1790.72  4969.3 1791.12  4983.4 1789.49  4997.5 1785.36
  5000.2 1784.86  5003.5 1785.36  5017.6 1790.46  5022.8 1789.81  5031.6 1791.34
  5051.7  1792.7  5056.9 1791.91  5091.1  1795.3    5115 1796.36  5169.8 1799.77
  5203.9    1803  5270.4 1807.12  5291.2 1807.13  5346.9 1811.42  5415.8 1816.97
  5440.4 1818.02  5497.9 1820.98  5503.1 1820.45  5537.3 1823.45  5574.3 1824.94
#Mann= 9 ,-1 , 0
  4593.7      .1       0  4731.7     .05       0  4816.5      .1       0
    4833     .16       0  4997.5     .07       0  5003.5     .16       0
    5115     .05       0  5346.9     .16       0  5440.4      .1       0
Bank Sta=4997.5,5003.5
XS Rating Curve= 0 ,0
Exp/Cntr=0.3,0.1

Type RM Length L Ch R = 1 ,20065   ,424,424,424
BEGIN DESCRIPTION:
UNT 0067 IN HEWA 41.0
END DESCRIPTION:
XS GIS Cut Line= 3
      2763712.05     10077239.87      2763430.82     10076993.36
      2763180.81     10076632.23
#Sta/Elev= 30
  4572.1 1800.65  4578.7 1799.35  4592.9 1798.62  4664.1 1797.74    4776 1794.61
  4819.2 1793.46  4890.9 1791.13  4948.9 1787.59  4961.4 1786.28  4969.9 1784.73
  4976.3 1782.44  4986.2 1780.72  4991.2 1779.63  4997.2  1779.6    5003  1778.2
  5005.8  1777.7    5009  1778.2    5027 1783.48  5033.1 1783.94  5041.8 1784.16
  5068.9 1786.29  5128.1 1788.46  5149.3 1789.66  5155.4 1790.42  5185.1 1791.48
  5277.7 1797.11  5292.5 1798.37  5307.4 1798.92  5339.7    1802  5385.3 1804.34
#Mann= 7 ,-1 , 0
  4572.1      .1       0    4776     .05       0  4819.2      .1       0
  4986.2     .16       0    5003     .07       0    5009     .16       0
  5339.7      .1       0
Bank Sta=5003,5009
XS Rating Curve= 0 ,0
Exp/Cntr=0.3,0.1

Type RM Length L Ch R = 1 ,19641   ,637,637,637
BEGIN DESCRIPTION:
UNT 0067 IN HEWA 40.0
END DESCRIPTION:
XS GIS Cut Line= 3
      2763930.83      10077038.5      2763656.52     10076639.19
      2763363.61     10076418.65
#Sta/Elev= 30
  4440.3 1789.63  4467.6 1788.53  4545.4  1787.8  4702.9 1781.66  4739.2 1780.42
  4784.3 1780.29  4805.3 1778.49  4834.3 1778.73  4847.2 1777.83  4912.8 1777.71
    4927 1777.01  4941.6 1777.92    4977 1777.68  4984.9 1776.79  4991.6 1774.45
  4994.8 1774.42  4997.6 1773.92  5000.8 1774.42  5006.2 1775.17  5020.7 1779.52
    5027  1780.2  5041.6 1788.53  5047.8  1788.4  5056.1 1790.19  5106.9 1793.24
  5135.1 1795.16  5156.1 1794.64  5191.5 1799.08  5270.6 1803.36  5291.4 1805.38
#Mann= 6 ,-1 , 0
  4440.3     .05       0  4702.9      .1       0  4739.2     .16       0
  4994.8     .07       0  5000.8     .16       0  5106.9      .1       0
Bank Sta=4994.8,5000.8
XS Rating Curve= 0 ,0
Exp/Cntr=0.3,0.1

Type RM Length L Ch R = 1 ,19004   ,402,402,402
BEGIN DESCRIPTION:
UNT 0067 IN HEWA 39.0
END DESCRIPTION:
XS GIS Cut Line= 2
      2764330.15     10077021.18      2763847.47     10076264.17
#Sta/Elev= 30
  4546.4 1784.07  4632.8 1781.94  4784.3 1780.27  4820.7 1779.44  4835.9 1778.62
    4857 1778.61  4872.3 1777.74    4951 1777.03  4960.4 1775.41  4966.2 1773.89
  4972.1 1773.83  4986.6 1771.36    4994 1766.65  4999.6 1766.44  5002.4 1765.94
  5005.6 1766.44  5008.5 1768.75  5017.8 1771.05  5029.7 1771.92    5039 1771.86
  5044.9    1773  5111.8 1776.34  5117.7 1776.17  5190.5 1780.19  5265.9 1783.32
  5314.3 1784.59  5363.1 1786.96  5372.4 1786.85  5434.5 1788.95  5444.2 1790.14
#Mann= 6 ,-1 , 0
  4546.4     .05       0  4960.4     .16       0  4999.6     .07       0
  5005.6     .16       0  5265.9      .1       0  5434.5     .16       0
Bank Sta=4999.6,5005.6
XS Rating Curve= 0 ,0
Exp/Cntr=0.3,0.1

Type RM Length L Ch R = 1 ,18602   ,531,531,531
BEGIN DESCRIPTION:
UNT 0067 IN HEWA 38.0
END DESCRIPTION:
XS GIS Cut Line= 2
      2764614.83      10076746.8      2764229.41     10076173.88
#Sta/Elev= 30
  4711.9 1773.05  4731.9 1773.19  4783.9 1772.37  4819.9 1772.34  4840.9  1772.9
  4860.7 1772.58  4948.9 1771.93  4963.9 1771.52  4969.9 1770.88  4978.9 1768.33
  4992.8 1763.03  4996.9  1762.3  4999.7  1761.8  5002.9  1762.3  5014.9 1764.94
    5029 1766.87  5041.9 1768.17  5050.9  1768.6  5101.3  1770.5  5158.9 1771.82
  5200.9 1774.28  5251.9 1776.61  5281.8 1777.09  5287.9 1777.58  5302.8 1777.37
  5308.9 1777.63  5317.8 1777.25  5369.9 1779.48  5389.2 1780.04  5402.4 1780.38
#Mann= 7 ,-1 , 0
  4711.9      .1       0  4731.9     .05       0  4860.7     .16       0
  4996.9     .07       0  5002.9     .16       0  5369.9     .05       0
  5389.2     .16       0
Bank Sta=4996.9,5002.9
XS Rating Curve= 0 ,0
Exp/Cntr=0.3,0.1

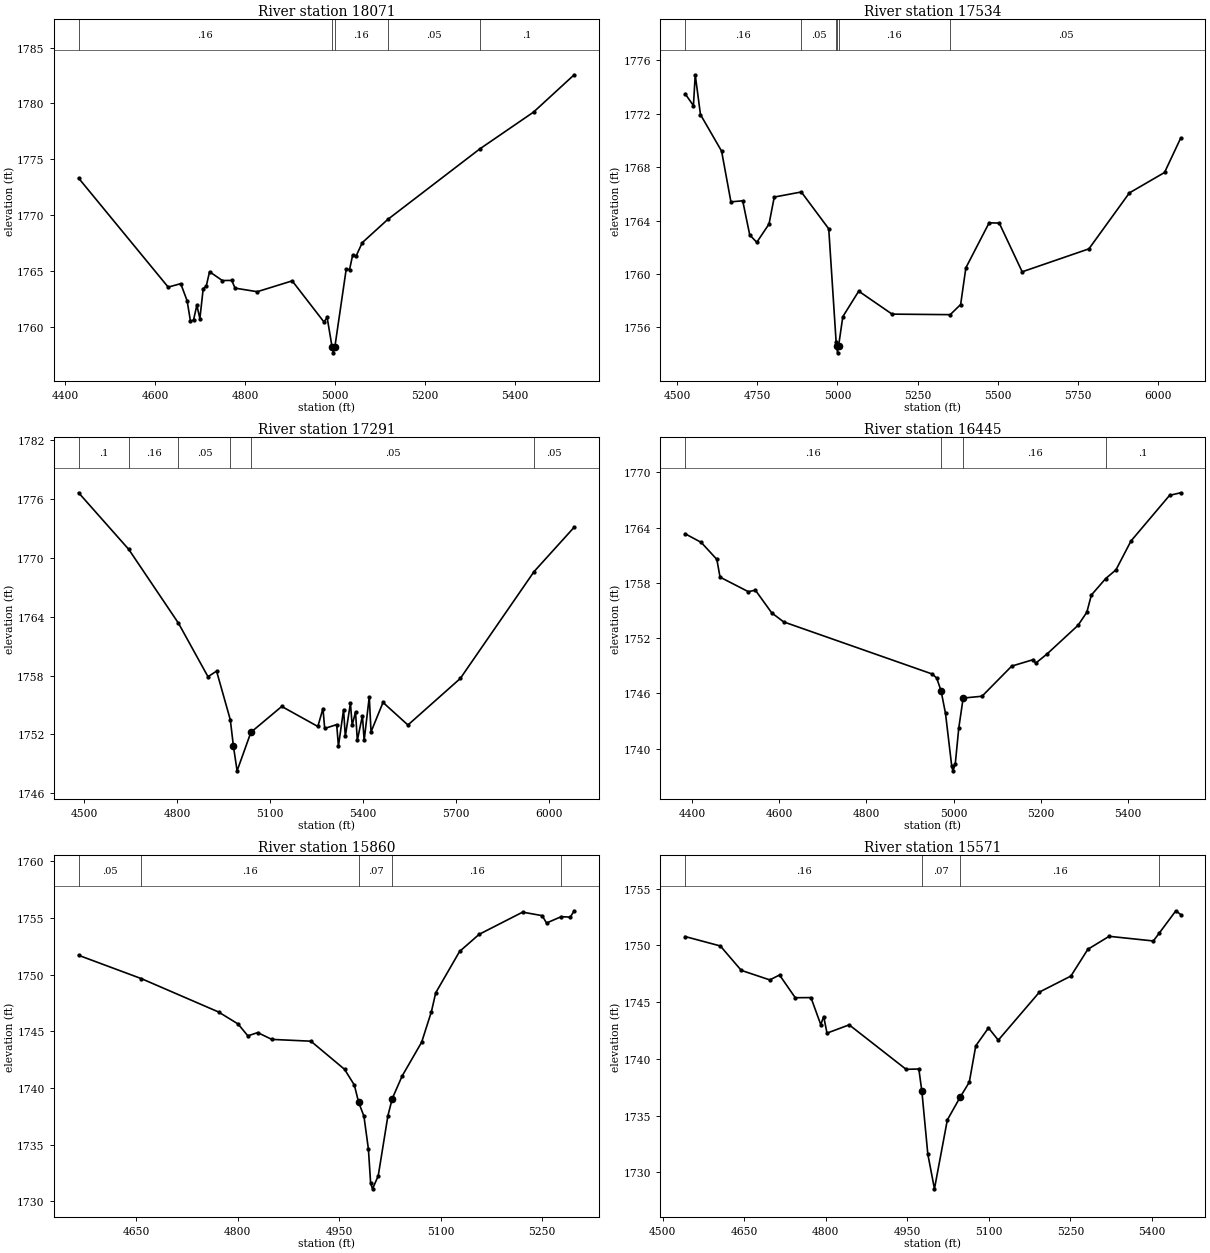
Type RM Length L Ch R = 1 ,18071   ,537,537,537
BEGIN DESCRIPTION:
UNT 0067 IN HEWA 37.0
END DESCRIPTION:
XS GIS Cut Line= 3
      2765073.18      10076500.3      2764594.02     10075979.47
      2764205.09     10075913.49
#Sta/Elev= 30
  4429.7 1773.31  4628.9 1763.56  4656.8 1763.87    4671 1762.34  4678.4 1760.52
  4685.2 1760.61  4692.6 1761.93  4699.4 1760.75  4706.8 1763.43  4713.5 1763.64
  4720.9 1764.94  4749.3 1764.15  4770.3 1764.16  4777.6 1763.47    4827 1763.15
  4904.7 1764.12  4975.6 1760.43  4982.4 1760.86  4993.5 1758.18  4996.3 1757.68
  4999.5 1758.18  5024.9 1765.18  5032.3 1765.13  5039.1 1766.41  5046.5 1766.31
  5060.6 1767.54  5117.4 1769.62  5321.8 1775.92  5441.5 1779.22  5531.9 1782.56
#Mann= 5 ,-1 , 0
  4429.7     .16       0  4993.5     .07       0  4999.5     .16       0
  5117.4     .05       0  5321.8      .1       0
Bank Sta=4993.5,4999.5
XS Rating Curve= 0 ,0
Exp/Cntr=0.3,0.1

Type RM Length L Ch R = 1 ,17534   ,243,243,243
BEGIN DESCRIPTION:
UNT 0067 IN HEWA 36.0
END DESCRIPTION:
XS GIS Cut Line= 2
      2765524.54     10076041.95       2764161.7     10075313.72
#Sta/Elev= 30
  4524.9  1773.5  4550.9 1772.61  4556.5 1774.92  4572.8 1771.94  4638.7  1769.2
  4667.8  1765.4  4704.5 1765.48  4726.5 1762.92  4748.4 1762.37  4786.6 1763.74
  4802.9 1765.76  4887.3 1766.14  4972.8 1763.38  4995.9 1754.88  4997.4 1754.59
  5000.2 1754.09  5003.4 1754.59  5016.7  1756.8  5066.3 1758.71  5170.3 1756.99
  5351.6 1756.95  5384.1 1757.71  5400.4 1760.46  5472.9 1763.83  5504.5 1763.81
    5576 1760.16  5784.1 1761.88  5910.2 1766.07  6019.9  1767.6  6070.1 1770.17
#Mann= 6 ,-1 , 0
  4524.9     .16       0  4887.3     .05       0  4995.9     .16       0
  4997.4     .07       0  5003.4     .16       0  5351.6     .05       0
Bank Sta=4997.4,5003.4
XS Rating Curve= 0 ,0
Exp/Cntr=0.3,0.1

Type RM Length L Ch R = 1 ,17291   ,846,846,846
BEGIN DESCRIPTION:
Mapping XS 872b4eeb
END DESCRIPTION:
XS GIS Cut Line= 2
      2765692.29      10075851.2      2764271.94     10075117.61
#Sta/Elev= 30
    4483 1776.62  4644.8 1770.85  4805.1 1763.33  4900.3 1757.88    4928 1758.45
  4972.3 1753.49  4982.5 1750.77  4994.2 1748.29  5038.8 1752.22  5138.3 1754.85
  5254.7 1752.81  5271.2 1754.64  5276.8 1752.61  5315.5    1753  5321.1  1750.8
  5337.7 1754.53  5343.3 1751.79  5359.8 1755.19  5365.4 1752.94  5376.3 1754.29
    5382  1751.4  5398.5  1753.9  5404.1 1751.39  5420.6 1755.83  5426.3 1752.26
  5464.9 1755.26  5545.3 1752.96  5714.2  1757.7  5952.2 1768.59  6081.6 1773.11
#Mann= 6 ,-1 , 0
    4483      .1       0  4644.8     .16       0  4805.1     .05       0
  4972.3    .035       0  5038.8     .05       0  5952.2     .05       0
Bank Sta=4982.5,5038.8
XS Rating Curve= 0 ,0
Exp/Cntr=0.3,0.1

Type RM Length L Ch R = 1 ,16445   ,585,585,585
BEGIN DESCRIPTION:
UNT 0067 IN HEWA 35.0
END DESCRIPTION:
XS GIS Cut Line= 3
      2765541.92     10075378.77      2765114.85     10075139.19
      2764475.96     10075035.03
#Sta/Elev= 30
  4384.1 1763.34  4420.9 1762.41  4456.9 1760.56  4464.3 1758.63  4529.3 1757.05
  4545.3 1757.22  4582.9 1754.75  4610.3 1753.77  4951.2 1748.11  4961.3 1747.68
  4971.4 1746.29  4981.6 1743.83  4995.9  1738.1  4998.6  1737.6  5003.9  1738.3
    5012 1742.23  5022.1  1745.5  5065.4  1745.7  5133.5 1748.97  5183.3 1749.68
  5188.3 1749.28  5214.6 1750.29  5285.5 1753.39  5305.8 1754.81  5316.3 1756.69
  5349.2 1758.48  5372.7 1759.42  5407.1 1762.55  5495.7 1767.51  5521.1 1767.79
#Mann= 4 ,-1 , 0
  4384.1     .16       0  4971.4     .07       0  5022.1     .16       0
  5349.2      .1       0
Bank Sta=4971.4,5022.1
XS Rating Curve= 0 ,0
Exp/Cntr=0.3,0.1

Type RM Length L Ch R = 1 ,15860   ,289,289,289
BEGIN DESCRIPTION:
UNT 0067 IN HEWA 34.0
END DESCRIPTION:
XS GIS Cut Line= 2
      2765661.17     10074952.24      2765083.38     10074501.84
#Sta/Elev= 30
  4564.7  1751.7  4657.5 1749.64  4771.5  1746.7  4800.4 1745.64  4814.9 1744.59
  4829.4 1744.88  4850.2 1744.28  4908.1 1744.12  4957.8 1741.64  4972.3 1740.25
  4978.6 1738.74  4986.5 1737.49  4993.1  1734.6  4996.4 1731.59  4999.2 1731.09
  5007.6 1732.23    5022 1737.56  5028.4 1739.06  5042.9 1741.04  5071.8 1744.03
  5086.3 1746.74  5092.6 1748.39  5127.9 1752.04  5156.8 1753.55  5221.1 1755.51
    5250  1755.2  5256.4 1754.55  5278.2 1755.11  5291.6 1755.07  5297.3 1755.63
#Mann= 5 ,-1 , 0
  4564.7     .05       0  4657.5     .16       0  4978.6     .07       0
  5028.4     .16       0  5278.2     .05       0
Bank Sta=4978.6,5028.4
XS Rating Curve= 0 ,0
Exp/Cntr=0.3,0.1

Type RM Length L Ch R = 1 ,15571   ,510,510,510
BEGIN DESCRIPTION:
UNT 0067 IN HEWA 33.0
END DESCRIPTION:
XS GIS Cut Line= 2
      2765947.85      10074670.1      2765112.03      10074306.7
#Sta/Elev= 30
  4541.2 1750.77    4606 1749.94  4644.5 1747.79  4696.9 1746.95  4714.9 1747.38
  4743.8 1745.38  4772.7 1745.39  4790.7 1743.01  4796.1 1743.72  4802.2 1742.26
    4843 1742.99  4947.7 1739.07  4971.1  1739.1  4976.7 1737.12  4987.6  1731.6
  4999.8 1728.54  5023.5 1734.61  5046.9  1736.6  5063.9 1737.94  5075.8 1741.14
  5099.2 1742.72  5117.2 1741.64    5193 1745.88  5250.8 1747.29    5282 1749.65
  5321.1 1750.79  5402.4 1750.38  5412.9 1751.05  5443.8 1753.04  5452.6 1752.71
#Mann= 4 ,-1 , 0
  4541.2     .16       0  4976.7     .07       0  5046.9     .16       0
  5412.9     .05       0
Bank Sta=4976.7,5046.9
XS Rating Curve= 0 ,0
Exp/Cntr=0.3,0.1

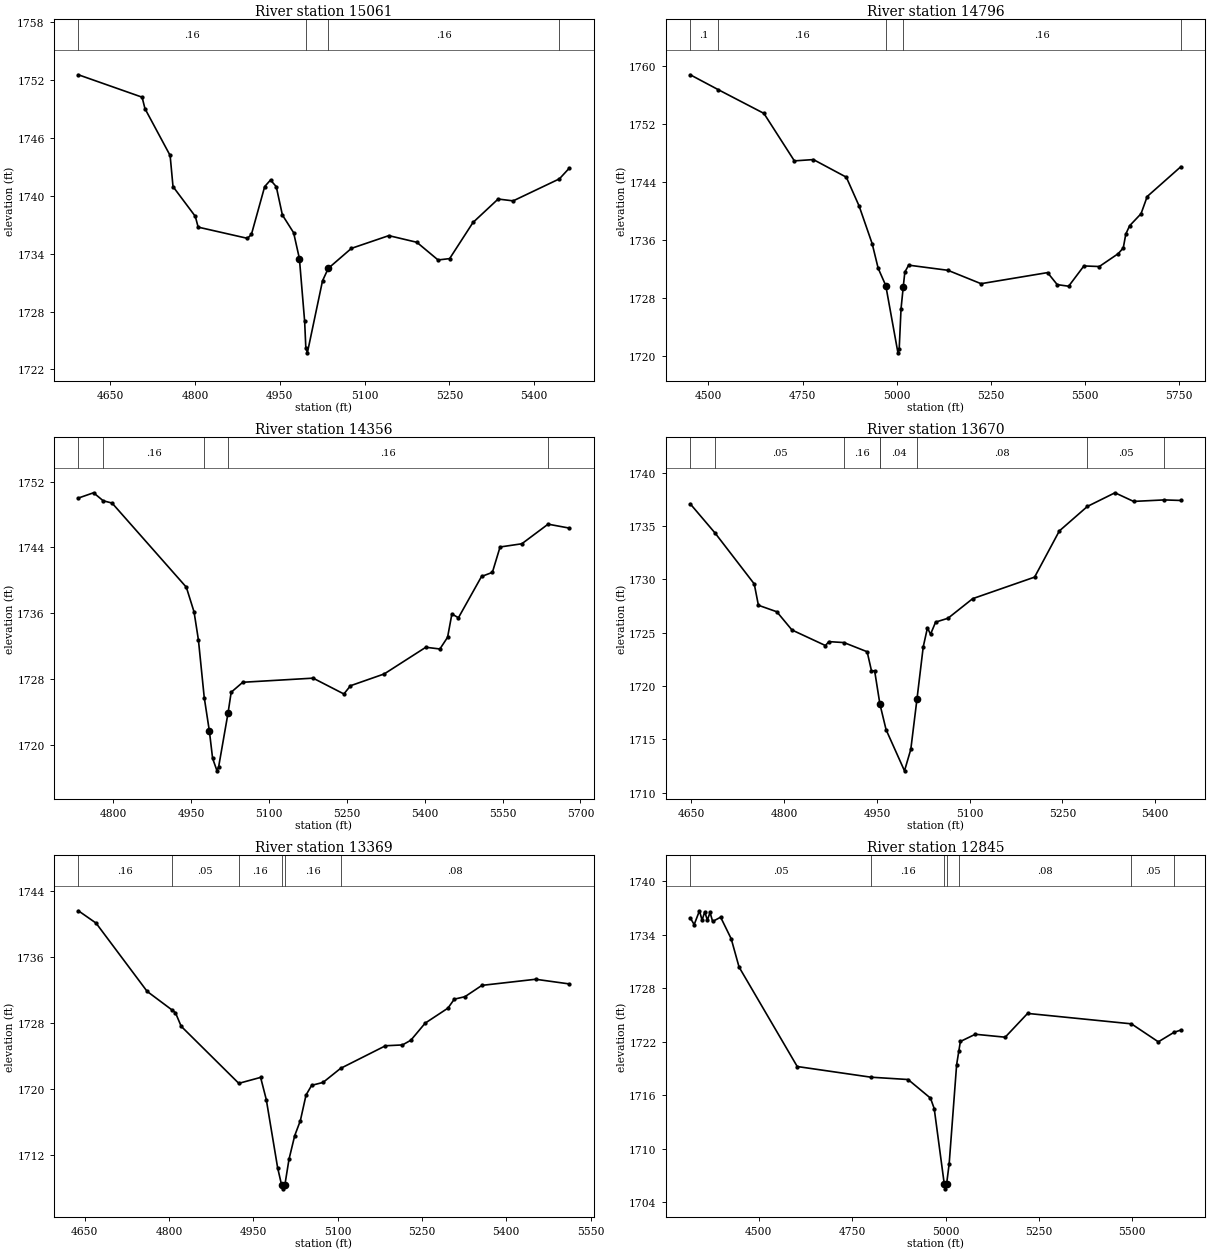
Type RM Length L Ch R = 1 ,15061   ,265,265,265
BEGIN DESCRIPTION:
UNT 0067 IN HEWA 32.0
END DESCRIPTION:
XS GIS Cut Line= 2
      2766100.93     10073944.76      2765251.84     10074124.97
#Sta/Elev= 30
  4593.7 1752.52  4706.4  1750.2  4711.5 1749.01    4756 1744.16  4761.1 1740.94
  4800.5 1737.86  4805.6 1736.74  4892.7 1735.58  4899.8 1735.98  4923.3 1740.94
  4933.6 1741.62  4943.8 1740.93  4954.6    1738  4974.5 1736.16  4984.7 1733.49
    4994 1726.97  4996.1 1724.22  4998.8 1723.72  5025.6 1731.18  5035.8 1732.47
  5076.7 1734.54  5142.9 1735.86  5192.5 1735.17    5230 1733.34  5250.5 1733.48
  5291.8 1737.22  5336.3 1739.65  5362.9 1739.46  5444.7 1741.74  5461.7 1742.82
#Mann= 4 ,-1 , 0
  4593.7     .16       0  4996.1     .07       0  5035.8     .16       0
  5444.7     .05       0
Bank Sta=4984.7,5035.8
XS Rating Curve= 0 ,0
Exp/Cntr=0.3,0.1

Type RM Length L Ch R = 1 ,14796   ,440,440,440
BEGIN DESCRIPTION:
UNT 0067 IN HEWA 31.0
END DESCRIPTION:
XS GIS Cut Line= 2
       2766161.7     10073696.29      2764873.88     10073891.97
#Sta/Elev= 30
    4452 1758.85  4526.1  1756.8  4647.5 1753.52  4728.4 1746.96  4778.9 1747.14
  4866.3 1744.71  4900.3 1740.73    4935 1735.52  4950.9 1732.13  4971.1 1729.74
  5003.4 1720.45  5006.7 1720.95  5011.6 1726.53 5017.59 1729.61  5021.7  1731.6
  5031.8 1732.56    5136 1731.85    5224    1730  5400.6 1731.53  5426.3 1729.87
  5456.6 1729.65  5497.1 1732.45    5538 1732.37  5588.1 1734.14  5601.6 1734.93
  5608.4 1736.86  5618.5    1738  5648.8 1739.66  5665.2 1742.04  5754.6 1746.16
#Mann= 5 ,-1 , 0
    4452      .1       0  4526.1     .16       0  4971.1     .07       0
 5017.59     .16       0  5754.6     .05       0
Bank Sta=4971.1,5017.59
XS Rating Curve= 0 ,0
Exp/Cntr=0.3,0.1

Type RM Length L Ch R = 1 ,14356   ,686,686,686
BEGIN DESCRIPTION:
UNT 0067 IN HEWA 30.0
END DESCRIPTION:
XS GIS Cut Line= 2
      2765607.91     10073302.38      2764833.58     10073844.07
#Sta/Elev= 30
  4733.1    1750  4762.3 1750.64  4780.9 1749.67    4798 1749.39    4941 1739.18
  4955.9 1736.18  4964.3 1732.78  4975.5 1725.79  4985.5 1721.67  4991.6 1718.41
  5000.1 1716.89  5003.3 1717.39  5021.3 1723.89  5027.4 1726.43  5049.7 1727.64
  5185.2 1728.14  5244.5 1726.22  5257.2 1727.22  5322.1 1728.65  5402.3 1731.89
  5429.4 1731.68  5444.2  1733.1  5452.5 1735.93  5465.1 1735.47  5509.6 1740.48
  5530.5 1740.98  5545.3 1744.06  5587.2 1744.45  5637.8 1746.83  5678.1 1746.36
#Mann= 5 ,-1 , 0
  4733.1     .05       0  4780.9     .16       0  4975.5     .07       0
  5021.3     .16       0  5637.8     .05       0
Bank Sta=4985.5,5021.3
XS Rating Curve= 0 ,0
Exp/Cntr=0.3,0.1

Type RM Length L Ch R = 1 ,13670   ,301,301,301
BEGIN DESCRIPTION:
UNT 0067 IN HEWA 29.0
END DESCRIPTION:
XS GIS Cut Line= 3
      2765364.81     10073107.96      2765090.55     10073215.58
      2764591.97      10073232.9
#Sta/Elev= 30
    4648 1737.08  4688.2 1734.34  4751.5 1729.57  4758.2 1727.57    4788 1726.96
  4812.5 1725.25  4866.7 1723.79  4872.1 1724.16  4896.6 1724.07  4934.1 1723.21
  4941.1 1721.42  4946.2 1721.42  4954.7 1718.31  4964.7  1715.9  4994.5 1712.04
  5004.7 1714.06  5014.7 1718.78  5024.8 1723.67  5031.6 1725.45  5036.6 1724.85
  5044.8 1725.99  5064.8 1726.35  5104.8 1728.19  5204.9 1730.21  5244.9 1734.54
  5290.3 1736.84  5334.9 1738.12    5365 1737.31  5414.1 1737.45  5441.5  1737.4
#Mann= 8 ,-1 , 0
    4648     .16       0  4688.2     .05       0  4896.6     .16       0
  4954.7     .05       0  4954.7     .04       0  5014.7     .08       0
  5290.3     .05       0  5414.1     .08       0
Bank Sta=4954.7,5014.7
XS Rating Curve= 0 ,0
Exp/Cntr=0.3,0.1

Type RM Length L Ch R = 1 ,13369   ,524,524,524
BEGIN DESCRIPTION:
UNT 0067 IN HEWA 28.0
END DESCRIPTION:
XS GIS Cut Line= 2
       2765399.6     10072878.77      2764535.02     10072996.83
#Sta/Elev= 30
    4639 1741.59  4670.4  1740.1  4761.3 1731.83  4804.8 1729.62  4811.7 1729.24
  4821.8 1727.61  4924.3  1720.7  4963.1 1721.42  4973.2 1718.73  4993.4 1710.47
  5000.3 1708.43  5003.1 1707.93  5006.3 1708.43  5013.6 1711.51  5023.7 1714.36
  5033.8 1716.19  5043.9 1719.29  5053.9 1720.46  5074.1 1720.81  5105.3 1722.51
  5185.2 1725.25  5215.4 1725.35  5230.3 1725.92  5255.8 1727.99  5296.2  1729.8
  5307.6 1730.89  5326.5 1731.19  5356.7 1732.56  5452.2  1733.3  5511.6 1732.74
#Mann= 6 ,-1 , 0
    4639     .16       0  4804.8     .05       0  4924.3     .16       0
  5000.3     .07       0  5006.3     .16       0  5105.3     .08       0
Bank Sta=5000.3,5006.3
XS Rating Curve= 0 ,0
Exp/Cntr=0.3,0.1

Type RM Length L Ch R = 1 ,12845   ,613,613,613
BEGIN DESCRIPTION:
UNT 0067 IN HEWA 27.0
END DESCRIPTION:
XS GIS Cut Line= 3
      2765441.25     10072805.87      2765048.88     10072430.86
      2764278.06     10072437.81
#Sta/Elev= 30
  4316.6 1735.91  4327.1 1735.16  4341.3 1736.71  4348.2 1735.66  4355.4 1736.58
  4362.4 1735.67  4369.6 1736.52  4376.5 1735.51  4397.9 1735.99  4426.2 1733.57
  4447.3 1730.39    4603 1719.23  4800.5 1718.03  4899.8 1717.77  4959.8 1715.68
  4969.8  1714.5  4996.8    1706  4999.5  1705.5  5002.8    1706  5009.8 1708.31
  5029.8 1719.44  5035.5 1720.92  5039.8 1722.04  5079.8 1722.85  5159.8 1722.52
  5219.8 1725.19  5497.7 1724.02  5569.8    1722  5611.9 1723.07  5630.2 1723.32
#Mann= 7 ,-1 , 0
  4316.6     .05       0  4800.5     .16       0  4996.8     .07       0
  5002.8     .16       0  5035.5     .08       0  5497.7     .05       0
  5611.9     .08       0
Bank Sta=4996.8,5002.8
XS Rating Curve= 0 ,0
Exp/Cntr=0.3,0.1

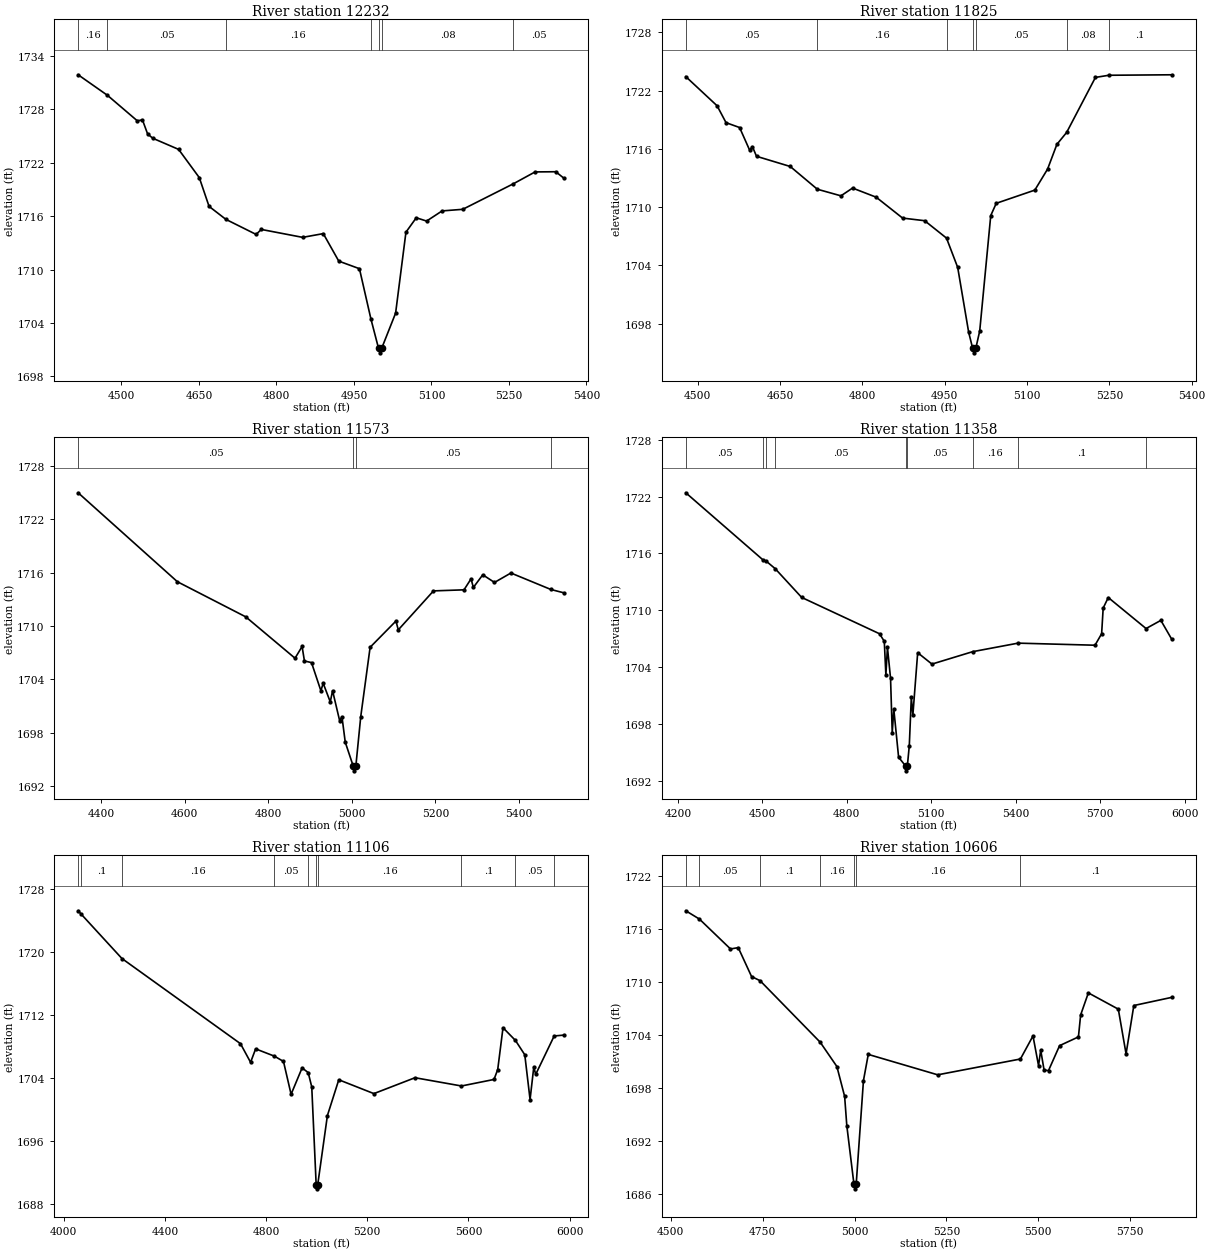
Type RM Length L Ch R = 1 ,12232   ,407,407,407
BEGIN DESCRIPTION:
UNT 0067 IN HEWA 26.0
END DESCRIPTION:
XS GIS Cut Line= 2
      2765732.95     10071996.83      2764792.68     10072003.77
#Sta/Elev= 30
  4416.1 1731.87  4472.9 1729.56  4530.6  1726.7  4540.6  1726.8  4550.6 1725.22
  4560.6 1724.74  4610.6 1723.49  4650.6 1720.32  4669.5 1717.09  4702.1 1715.63
  4760.6 1713.94  4770.6  1714.5  4850.6 1713.61  4890.6 1714.03  4920.6 1710.94
  4960.6 1710.09  4982.9 1704.42  4997.6 1701.14  5000.4 1700.64  5003.6 1701.14
  5030.6  1705.1  5050.6 1714.19  5070.6 1715.81  5090.6 1715.44  5120.6 1716.58
  5160.6 1716.76  5258.6 1719.63  5300.6 1720.96  5340.6 1720.98  5356.4 1720.25
#Mann= 7 ,-1 , 0
  4416.1     .16       0  4472.9     .05       0  4702.1     .16       0
  4982.9     .08       0  4997.6     .07       0  5003.6     .08       0
  5258.6     .05       0
Bank Sta=4997.6,5003.6
XS Rating Curve= 0 ,0
Exp/Cntr=0.3,0.1

Type RM Length L Ch R = 1 ,11825   ,252,252,252
BEGIN DESCRIPTION:
UNT 0067 IN HEWA 25.0
END DESCRIPTION:
XS GIS Cut Line= 3
      2765554.02     10071745.22      2765194.55     10071663.32
      2764680.35     10071708.82
#Sta/Elev= 30
  4478.4 1723.43  4535.4 1720.43  4551.7 1718.69  4576.4 1718.19  4594.7 1715.86
  4599.8 1716.22  4607.2 1715.23  4668.7 1714.18    4718 1711.84    4761 1711.16
  4782.2 1711.96  4825.2 1711.02  4873.3 1708.87  4913.5  1708.6  4953.3 1706.81
  4973.7 1703.79  4993.7 1697.11  5000.8  1695.5  5003.5    1695  5006.8  1695.5
  5013.8 1697.25  5033.9 1709.13  5043.9 1710.39  5114.2 1711.75  5137.4 1713.91
  5154.4 1716.46  5172.2 1717.69  5224.6 1723.35    5249 1723.57  5363.3 1723.62
#Mann= 7 ,-1 , 0
  4478.4     .05       0    4718     .16       0  4953.3     .05       0
  5000.8     .04       0  5006.8     .05       0  5172.2     .08       0
    5249      .1       0
Bank Sta=5000.8,5006.8
XS Rating Curve= 0 ,0
Exp/Cntr=0.3,0.1

Type RM Length L Ch R = 1 ,11573   ,215,215,215
BEGIN DESCRIPTION:
Mapping XS aae382b9
END DESCRIPTION:
XS GIS Cut Line= 2
      2765631.39     10071727.02      2764589.35     10071212.82
#Sta/Elev= 30
  4345.4 1724.97  4582.8 1714.97  4746.4 1711.02  4864.2 1706.37  4881.1 1707.69
  4886.7 1706.06  4903.6 1705.88    4926 1702.72  4931.6 1703.55  4948.5 1701.46
    4954 1702.72  4970.9 1699.35  4976.5 1699.78  4984.3 1696.94  5003.6 1694.21
  5006.3 1693.71  5009.6 1694.21  5021.4 1699.81  5043.8  1707.6  5105.6 1710.55
  5111.2 1709.56  5195.4 1713.94  5268.4 1714.06  5285.2 1715.29  5290.8 1714.33
  5313.3 1715.75  5341.3 1714.89  5380.6 1715.95  5476.1  1714.1  5507.4 1713.72
#Mann= 4 ,-1 , 0
  4345.4     .05       0  5003.6     .04       0  5009.6     .05       0
  5476.1      .1       0
Bank Sta=5003.6,5009.6
XS Rating Curve= 0 ,0
Exp/Cntr=0.3,0.1

Type RM Length L Ch R = 1 ,11358   ,252,252,252
BEGIN DESCRIPTION:
UNT 0067 IN HEWA 24.0
END DESCRIPTION:
XS GIS Cut Line= 3
      2765753.14     10071578.57      2764524.45     10070983.63
      2764192.96     10071125.69
#Sta/Elev= 30
  4228.1  1722.4  4503.9 1715.28  4512.4 1715.22  4545.5  1714.4  4639.8 1711.36
  4916.3 1707.53  4933.3 1706.73  4938.9 1703.19  4944.5 1706.08  4955.5 1702.84
  4961.5  1697.1  4967.1 1699.56  4984.1 1694.51  5009.2 1693.57    5012 1693.07
  5015.2 1693.57  5022.1 1695.72  5029.3 1700.81  5034.8 1698.96  5051.9 1705.53
  5102.6 1704.33  5247.3 1705.64  5408.6 1706.54  5681.9 1706.32  5705.4 1707.53
  5710.9 1710.24    5729 1711.35  5863.2 1708.08  5915.8 1708.94  5953.9 1706.98
#Mann= 9 ,-1 , 0
  4228.1     .05       0  4503.9      .1       0  4512.4     .16       0
  4545.5     .05       0  5009.2     .04       0  5015.2     .05       0
  5247.3     .16       0  5408.6      .1       0  5863.2     .05       0
Bank Sta=5009.2,5015.2
XS Rating Curve= 0 ,0
Exp/Cntr=0.3,0.1

Type RM Length L Ch R = 1 ,11106   ,500,500,500
BEGIN DESCRIPTION:
UNT 0067 IN HEWA 23.0
END DESCRIPTION:
XS GIS Cut Line= 5
      2765929.94      10071009.5      2765093.52     10070979.32
      2764886.59     10071022.43      2764412.36     10070914.65
      2764097.69     10071138.79
#Sta/Elev= 30
  4056.7 1725.26  4069.9 1724.79  4229.8 1719.19  4698.6 1708.36  4738.6 1705.99
  4758.6  1707.7  4832.9 1706.77  4868.7  1706.1  4898.8 1701.92  4942.3 1705.28
  4966.5 1704.68  4980.5 1702.86    4998  1690.4  5000.7  1689.9    5004  1690.4
  5042.4 1699.22  5087.4 1703.77  5226.2 1702.01  5388.8 1704.03  5572.6 1702.98
  5701.2 1703.81  5715.9 1705.07  5736.8 1710.39    5786 1708.77  5822.9 1706.95
  5843.8 1701.26  5858.5 1705.38  5866.2 1704.46  5939.2 1709.34  5977.7 1709.45
#Mann= 10 ,-1 , 0
  4056.7     .05       0  4069.9      .1       0  4229.8     .16       0
  4832.9     .05       0  4966.5     .16       0    4998     .07       0
    5004     .16       0  5572.6      .1       0    5786     .05       0
  5939.2      .1       0
Bank Sta=4998,5004
XS Rating Curve= 0 ,0
Exp/Cntr=0.3,0.1

Type RM Length L Ch R = 1 ,10606   ,503,503,503
BEGIN DESCRIPTION:
UNT 0067 IN HEWA 22.0
END DESCRIPTION:
XS GIS Cut Line= 2
      2765103.55     10070370.98       2763998.5     10071095.71
#Sta/Elev= 30
    4541 1718.04  4578.1  1717.1  4662.6 1713.72  4683.7 1713.87  4719.9  1710.6
  4743.1 1710.13  4906.6 1703.17    4952 1700.42  4973.1 1697.04    4979 1693.73
  4998.5 1687.08  5001.3 1686.58  5004.5 1687.08  5024.3 1698.83  5037.4 1701.79
  5226.3 1699.48  5451.3 1701.27  5485.5 1703.88  5500.6 1700.52  5506.5 1702.27
  5515.7 1700.01  5527.7 1699.96  5557.8 1702.78  5609.1 1703.77  5615.1 1706.25
  5636.1 1708.75  5717.6 1706.91  5738.7 1701.85  5759.8 1707.32  5862.5 1708.24
#Mann= 7 ,-1 , 0
    4541     .16       0  4578.1     .05       0  4743.1      .1       0
  4906.6     .16       0  4998.5     .07       0  5004.5     .16       0
  5451.3      .1       0
Bank Sta=4998.5,5004.5
XS Rating Curve= 0 ,0
Exp/Cntr=0.3,0.1