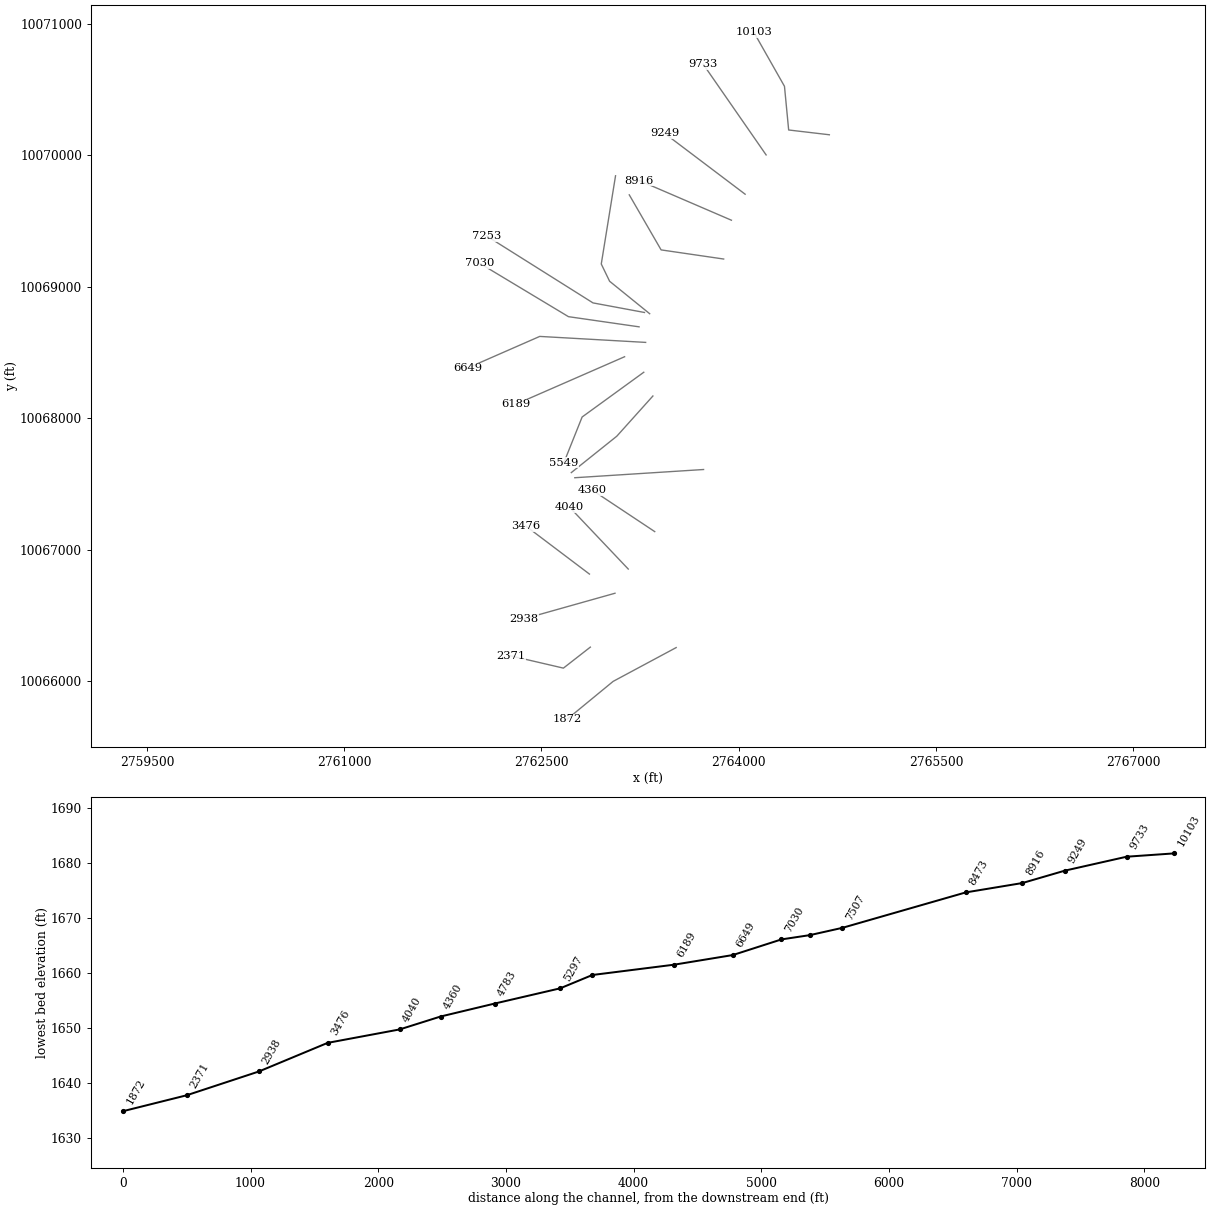
HEC-RAS study UNT 0067 IN HEWA.prj: UNT 0067 IN HEWA Base Level Engineering

--- UNT 0067 IN HEWA.g01 (geometry) --- (continued)

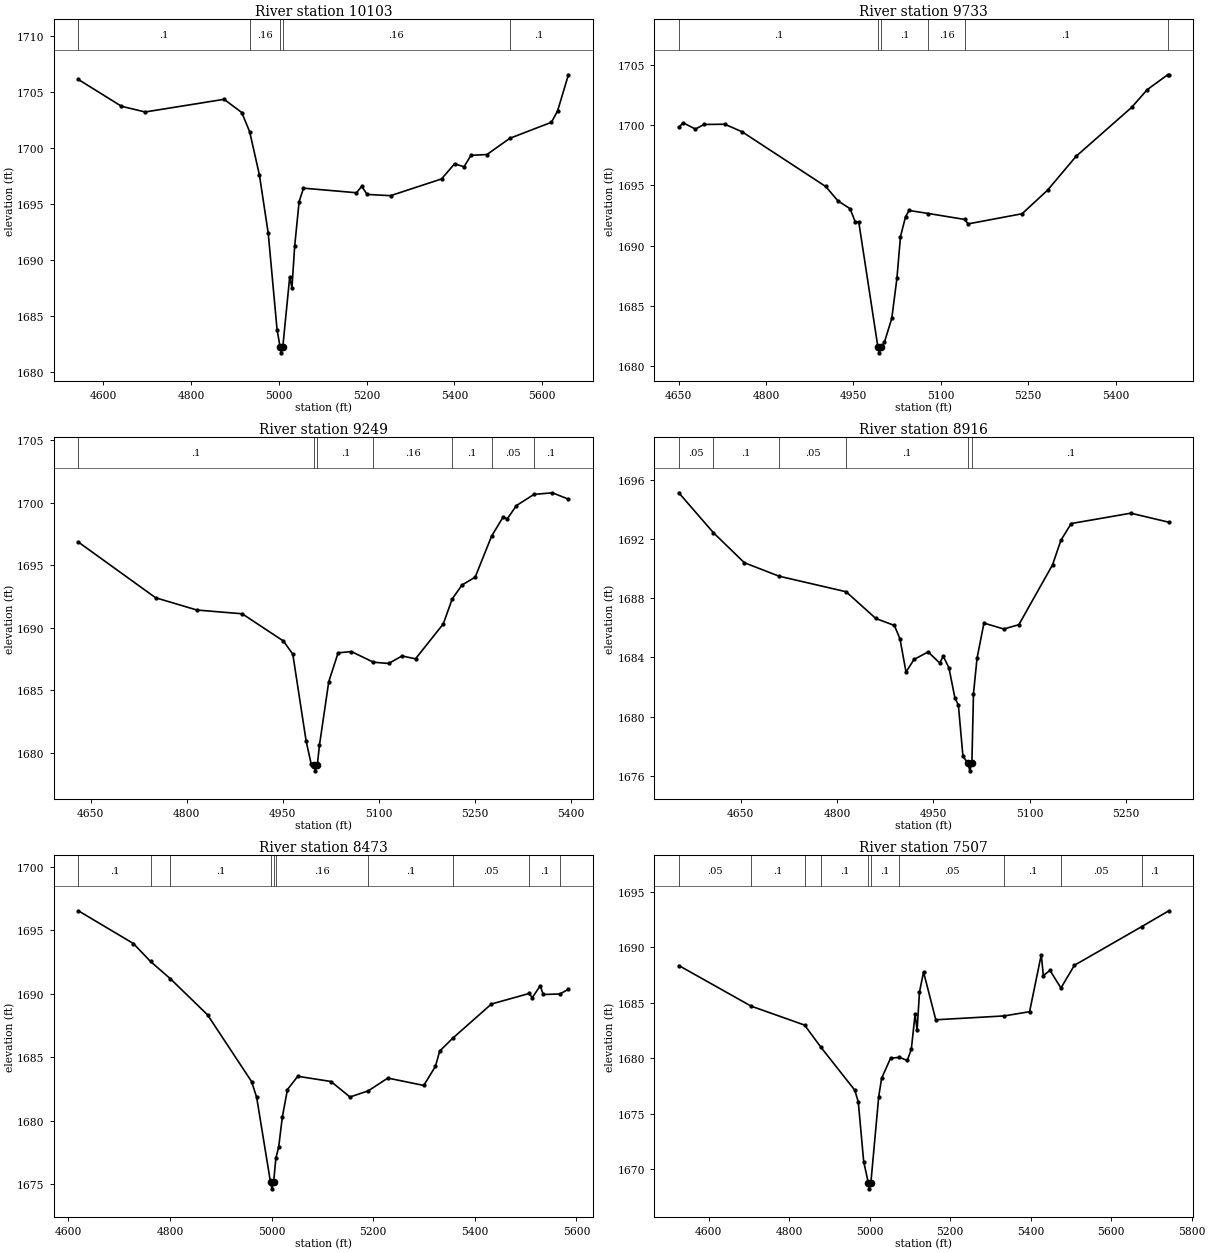
Type RM Length L Ch R = 1 ,10103   ,370,370,370
BEGIN DESCRIPTION:
UNT 0067 IN HEWA 21.0
END DESCRIPTION:
XS GIS Cut Line= 4
       2764689.5     10070157.11      2764380.02     10070193.52
      2764348.17      10070525.7      2764116.12     10070935.21
#Sta/Elev= 30
  4543.7 1706.11  4641.8 1703.72  4695.8 1703.21  4875.6 1704.34  4915.8 1703.16
  4933.8 1701.45    4956 1697.59  4976.1 1692.38  4996.2 1683.79  5003.2 1682.21
    5006 1681.71  5009.2 1682.21    5025 1688.48  5030.1 1687.52  5036.3 1691.22
  5046.4  1695.2  5056.4 1696.41    5177    1696    5189 1696.57  5201.3 1695.85
  5254.7 1695.74  5370.7 1697.23  5400.4 1698.58    5422 1698.32  5437.9 1699.34
  5474.1 1699.41  5526.3 1700.86  5621.1 1702.29    5635  1703.3  5659.7 1706.53
#Mann= 5 ,-1 , 0
  4543.7      .1       0  4933.8     .16       0  5003.2     .07       0
  5009.2     .16       0  5526.3      .1       0
Bank Sta=5003.2,5009.2
XS Rating Curve= 0 ,0
Exp/Cntr=0.3,0.1

Type RM Length L Ch R = 1 ,9733    ,484,484,484
BEGIN DESCRIPTION:
UNT 0067 IN HEWA 20.0
END DESCRIPTION:
XS GIS Cut Line= 2
       2764208.6     10070003.78      2763729.41     10070694.78
#Sta/Elev= 30
  4650.4  1699.8  4657.9 1700.18  4678.9 1699.66  4693.7 1700.04  4729.5 1700.06
  4759.2 1699.43  4902.5  1694.9  4923.4 1693.71  4944.3 1693.06  4953.1 1691.98
  4959.2 1691.96    4992 1681.61  4994.7 1681.11    4998 1681.61  5003.3    1682
  5015.9 1683.97  5024.7 1687.29  5030.8 1690.74  5039.6 1692.41  5045.7 1692.91
  5078.8 1692.66  5140.8 1692.17    5147  1691.8  5239.5 1692.64  5283.1 1694.59
  5332.1  1697.4  5427.3 1701.45  5454.3 1702.93  5489.3 1704.16  5491.3 1704.16
#Mann= 6 ,-1 , 0
  4650.4      .1       0    4992     .07       0    4998      .1       0
  5078.8     .16       0  5140.8      .1       0  5489.3     .05       0
Bank Sta=4992,4998
XS Rating Curve= 0 ,0
Exp/Cntr=0.3,0.1

Type RM Length L Ch R = 1 ,9249    ,333,333,333
BEGIN DESCRIPTION:
UNT 0067 IN HEWA 19.0
END DESCRIPTION:
XS GIS Cut Line= 2
       2764048.9     10069705.15      2763437.77     10070166.97
#Sta/Elev= 30
  4630.6 1696.86  4751.4 1692.41  4815.9 1691.43  4886.7 1691.13  4951.2 1688.95
  4965.8  1687.9  4986.6 1680.97  4994.6 1679.11  4998.2 1679.08  5000.9 1678.58
  5004.2 1679.08  5007.4 1680.61    5022  1685.7  5036.6 1688.01  5057.4 1688.11
  5091.8 1687.26  5115.6 1687.16  5136.5 1687.76  5157.6 1687.53    5201 1690.32
  5214.9 1692.31  5230.1 1693.42  5250.9 1694.06  5276.5 1697.33  5294.6 1698.87
  5300.9 1698.71  5315.4 1699.78  5342.8 1700.67  5371.6  1700.8  5396.6 1700.29
#Mann= 7 ,-1 , 0
  4630.6      .1       0  4998.2     .07       0  5004.2      .1       0
  5091.8     .16       0  5214.9      .1       0  5276.5     .05       0
  5342.8      .1       0
Bank Sta=4998.2,5004.2
XS Rating Curve= 0 ,0
Exp/Cntr=0.3,0.1

Type RM Length L Ch R = 1 ,8916    ,443,443,443
BEGIN DESCRIPTION:
UNT 0067 IN HEWA 18.0
END DESCRIPTION:
XS GIS Cut Line= 2
       2763944.7     10069507.25      2763244.12     10069808.99
#Sta/Elev= 30
  4553.9 1695.13  4607.8 1692.43    4656  1690.4    4710 1689.49  4814.3 1688.44
  4860.6 1686.63  4889.5 1686.16  4898.2 1685.25  4907.6 1683.01    4920 1683.86
    4942 1684.37  4960.1 1683.62  4965.6 1684.08  4974.4 1683.29  4983.6 1681.28
  4989.1 1680.77  4996.2 1677.32  5004.1 1676.83  5006.9 1676.33  5010.1 1676.83
  5012.6 1681.54  5018.1 1683.93  5028.9 1686.32  5059.7 1685.92  5083.2 1686.21
  5135.7 1690.26  5148.6 1691.91  5164.7 1693.05  5257.5 1693.75  5316.7 1693.14
#Mann= 6 ,-1 , 0
  4553.9     .05       0  4607.8      .1       0    4710     .05       0
  4814.3      .1       0  5004.1     .07       0  5010.1      .1       0
Bank Sta=5004.1,5010.1
XS Rating Curve= 0 ,0
Exp/Cntr=0.3,0.1

Type RM Length L Ch R = 1 ,8473    ,966,966,966
BEGIN DESCRIPTION:
UNT 0067 IN HEWA 17.0
END DESCRIPTION:
XS GIS Cut Line= 3
       2763885.7     10069212.11      2763409.99     10069281.56
       2763167.8      10069700.2
#Sta/Elev= 30
  4619.8 1696.52  4728.2 1693.94  4761.8 1692.53  4801.1 1691.16    4874 1688.33
  4960.6 1683.08  4970.7 1681.83    4998 1675.13  5000.8 1674.63    5004 1675.13
  5008.5 1677.05    5014 1677.91  5021.2 1680.28  5031.3 1682.45  5051.6 1683.49
    5117 1683.08  5154.3 1681.86  5190.1 1682.34  5228.9 1683.35  5299.5 1682.77
  5322.6 1684.28  5330.8 1685.47  5356.6 1686.49  5432.7 1689.18    5507 1690.01
  5513.1 1689.68  5528.8 1690.62  5534.6 1689.93  5567.4 1689.97  5584.2 1690.34
#Mann= 10 ,-1 , 0
  4619.8      .1       0  4761.8     .05       0  4801.1      .1       0
    4998     .07       0    5004      .1       0  5008.5     .16       0
  5190.1      .1       0  5356.6     .05       0    5507      .1       0
  5567.4     .05       0
Bank Sta=4998,5004
XS Rating Curve= 0 ,0
Exp/Cntr=0.3,0.1

Type RM Length L Ch R = 1 ,7507    ,254,254,254
BEGIN DESCRIPTION:
UNT 0067 IN HEWA 16.0
END DESCRIPTION:
XS GIS Cut Line= 4
      2763322.92     10068796.28      2763018.34     10069043.05
      2762954.89     10069174.18      2763063.45     10069845.28
#Sta/Elev= 30
  4525.8 1688.36  4705.7 1684.69  4838.4 1682.98  4878.3 1681.01    4963 1677.11
  4971.7 1676.06  4985.2 1670.65  4996.9  1668.7  4999.6  1668.2  5002.9  1668.7
  5022.5 1676.52  5029.7 1678.18  5051.9 1679.99  5073.9 1680.07  5093.4 1679.79
  5103.5 1680.81  5112.9 1683.96  5117.9 1682.51  5123.8 1685.97  5133.9 1687.77
  5164.3 1683.46  5334.5 1683.81  5397.3 1684.19  5426.4 1689.34  5431.5 1687.45
    5448 1687.92  5475.2 1686.33  5508.7 1688.38  5675.9 1691.87  5743.3  1693.3
#Mann= 10 ,-1 , 0
  4525.8     .05       0  4705.7      .1       0  4838.4     .16       0
  4878.3      .1       0  4996.9     .07       0  5002.9      .1       0
  5073.9     .05       0  5334.5      .1       0  5475.2     .05       0
  5675.9      .1       0
Bank Sta=4996.9,5002.9
XS Rating Curve= 0 ,0
Exp/Cntr=0.3,0.1

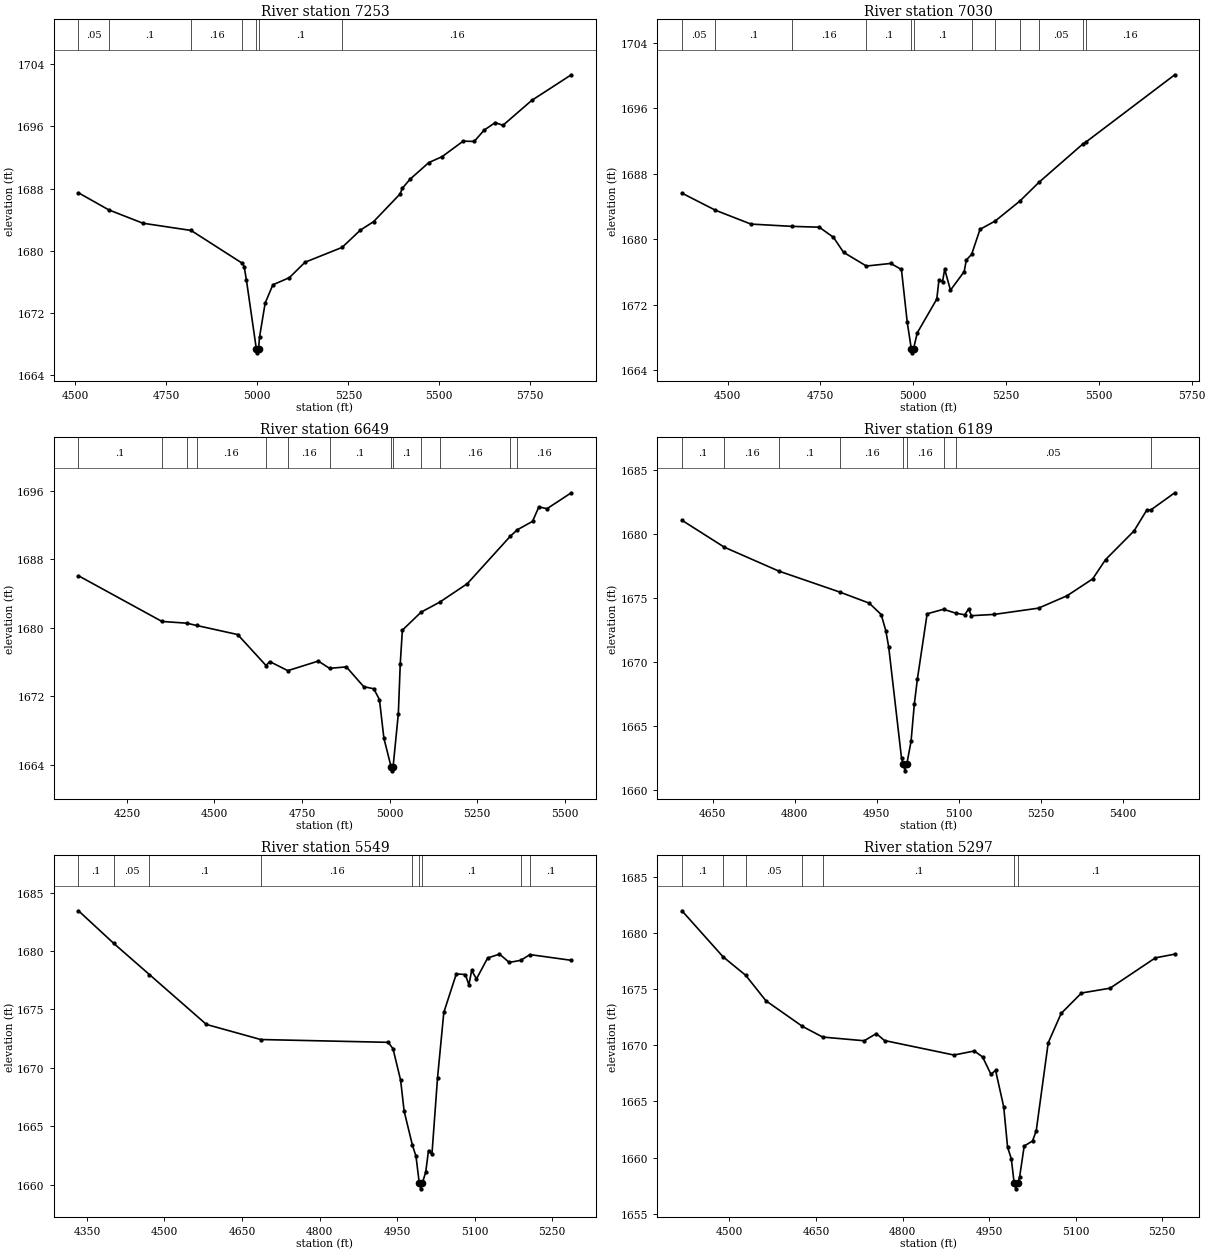
Type RM Length L Ch R = 1 ,7253    ,223,223,223
BEGIN DESCRIPTION:
UNT 0067 IN HEWA 15.0
END DESCRIPTION:
XS GIS Cut Line= 3
      2763283.39     10068805.63      2762892.03     10068878.44
      2762082.77     10069387.63
#Sta/Elev= 30
  4508.5 1687.46  4591.5 1685.27  4685.4 1683.55  4817.9 1682.62  4958.9 1678.39
  4963.7 1677.98  4969.9 1676.26  4997.2 1667.38    5000 1666.88  5003.2 1667.38
  5006.1 1668.94  5021.4 1673.27  5042.6 1675.63    5088 1676.55  5130.9 1678.53
  5232.9 1680.44  5282.8 1682.65  5319.3 1683.75  5392.3 1687.32  5398.2 1688.03
  5419.4  1689.2  5471.2 1691.35  5507.7 1692.11  5565.4  1694.1    5596 1694.07
  5623.1 1695.52  5653.7 1696.49  5674.9 1696.14  5753.8 1699.34  5862.7 1702.64
#Mann= 7 ,-1 , 0
  4508.5     .05       0  4591.5      .1       0  4817.9     .16       0
  4958.9      .1       0  4997.2     .07       0  5003.2      .1       0
  5232.9     .16       0
Bank Sta=4997.2,5003.2
XS Rating Curve= 0 ,0
Exp/Cntr=0.3,0.1

Type RM Length L Ch R = 1 ,7030    ,381,381,381
BEGIN DESCRIPTION:
UNT 0067 IN HEWA 14.0
END DESCRIPTION:
XS GIS Cut Line= 3
       2763242.4     10068696.42      2762705.46     10068773.78
       2762032.8     10069178.28
#Sta/Elev= 30
  4377.1 1685.62  4467.4 1683.53  4562.9 1681.84  4673.2 1681.56  4746.9 1681.46
  4785.2 1680.22  4812.3 1678.39  4873.9 1676.71  4939.4 1677.03  4968.3 1676.29
  4983.8 1669.88  4994.8  1666.6  4997.5  1666.1  5000.8  1666.6    5011 1668.55
  5063.5 1672.67  5069.3    1675    5079 1674.81  5084.8 1676.31  5100.4 1673.76
  5137.3 1676.03  5143.1 1677.46  5157.3 1678.13    5180  1681.2  5220.4  1682.2
  5287.2 1684.65  5338.6 1686.94  5456.9 1691.63  5465.3 1691.87  5704.5 1700.09
#Mann= 12 ,-1 , 0
  4377.1     .05       0  4467.4      .1       0  4673.2     .16       0
  4873.9      .1       0  4994.8     .07       0  5000.8      .1       0
  5157.3     .16       0  5220.4     .05       0  5287.2     .16       0
  5338.6     .05       0  5456.9      .1       0  5465.3     .16       0
Bank Sta=4994.8,5000.8
XS Rating Curve= 0 ,0
Exp/Cntr=0.3,0.1

Type RM Length L Ch R = 1 ,6649    ,460,460,460
BEGIN DESCRIPTION:
UNT 0067 IN HEWA 13.0
END DESCRIPTION:
XS GIS Cut Line= 3
      2763292.44     10068578.11      2762487.04     10068623.62
      2761936.43     10068382.44
#Sta/Elev= 30
  4111.5 1686.06  4349.9 1680.72  4420.3 1680.52    4449 1680.25  4566.2 1679.19
  4647.2 1675.57  4657.8 1676.03  4709.4 1674.97  4796.6 1676.09  4828.7 1675.24
  4876.7 1675.41  4926.2  1673.1  4955.1 1672.85  4971.2 1671.59  4983.9 1667.08
  5004.3 1663.76    5007 1663.26  5010.3 1663.76  5025.2 1669.94  5030.7 1675.79
  5036.7  1679.7  5090.3 1681.81  5143.2 1682.97  5222.3 1685.14  5344.8 1690.67
  5364.9 1691.43  5408.6 1692.42  5426.6 1694.11  5449.9  1693.9  5519.3 1695.76
#Mann= 13 ,-1 , 0
  4111.5      .1       0  4349.9     .16       0  4420.3      .1       0
    4449     .16       0  4647.2      .1       0  4709.4     .16       0
  4828.7      .1       0  5004.3     .07       0  5010.3      .1       0
  5090.3     .05       0  5143.2     .16       0  5344.8     .05       0
  5364.9     .16       0
Bank Sta=5004.3,5010.3
XS Rating Curve= 0 ,0
Exp/Cntr=0.3,0.1

Type RM Length L Ch R = 1 ,6189    ,640,640,640
BEGIN DESCRIPTION:
UNT 0067 IN HEWA 12.0
END DESCRIPTION:
XS GIS Cut Line= 2
      2763132.24     10068469.07      2762306.71     10068108.33
#Sta/Elev= 30
  4593.9  1681.1  4671.6 1678.99  4770.8 1677.13  4882.9 1675.48  4936.3 1674.62
  4958.1 1673.73  4966.5 1672.48  4971.9 1671.18  4995.3  1662.5  4998.8 1662.01
  5001.5 1661.51  5004.8 1662.01  5012.7 1663.81  5018.7 1666.73  5024.2 1668.66
  5042.1 1673.79  5072.1 1674.14  5094.3 1673.84  5110.9 1673.71  5117.8 1674.16
  5123.2 1673.64  5164.6 1673.74  5245.7 1674.23    5298  1675.2  5344.8 1676.52
  5368.2 1678.02  5420.4 1680.27  5443.8 1681.91  5451.1 1681.91  5494.8 1683.25
#Mann= 9 ,-1 , 0
  4593.9      .1       0  4671.6     .16       0  4770.8      .1       0
  4882.9     .16       0  4998.8     .07       0  5004.8     .16       0
  5072.1      .1       0  5094.3     .05       0  5451.1     .16       0
Bank Sta=4998.8,5004.8
XS Rating Curve= 0 ,0
Exp/Cntr=0.3,0.1

Type RM Length L Ch R = 1 ,5549    ,252,252,252
BEGIN DESCRIPTION:
UNT 0067 IN HEWA 11.0
END DESCRIPTION:
XS GIS Cut Line= 3
      2763278.03     10068350.99       2762809.3     10068010.72
       2762670.4     10067663.49
#Sta/Elev= 30
  4333.7 1683.44  4402.1 1680.64  4470.9 1677.98  4581.2 1673.71  4686.2 1672.42
  4932.6 1672.18    4942 1671.64  4956.8 1668.93  4963.5  1666.3  4979.6 1663.37
  4986.5 1662.43  4992.8 1660.14  4995.6 1659.64  4998.8 1660.14  5005.3 1661.07
  5010.7 1662.92  5017.4 1662.63  5028.1 1669.11  5040.3 1674.74  5064.5 1678.04
    5082 1677.98  5088.8  1677.1  5094.2 1678.33  5103.5 1677.61  5125.1  1679.4
    5148 1679.73  5166.9 1679.02  5189.2  1679.2  5206.9 1679.69  5286.9  1679.2
#Mann= 9 ,-1 , 0
  4333.7      .1       0  4402.1     .05       0  4470.9      .1       0
  4686.2     .16       0  4979.6      .1       0  4992.8     .07       0
  4998.8      .1       0  5189.2     .16       0  5206.9      .1       0
Bank Sta=4992.8,4998.8
XS Rating Curve= 0 ,0
Exp/Cntr=0.3,0.1

Type RM Length L Ch R = 1 ,5297    ,514,514,514
BEGIN DESCRIPTION:
UNT 0067 IN HEWA 10.0
END DESCRIPTION:
XS GIS Cut Line= 3
      2763347.51     10068170.46      2763073.19     10067864.89
      2762726.98     10067587.92
#Sta/Elev= 30
  4417.7 1681.97    4489 1677.87  4528.3 1676.22  4563.2 1673.96  4626.5 1671.68
  4661.5 1670.73  4733.6  1670.4  4754.5 1671.04  4768.7 1670.42  4889.1 1669.13
  4924.3 1669.49  4938.7 1668.96  4953.1 1667.42  4961.2 1667.76  4975.3 1664.51
    4982 1660.92  4988.4 1659.91  4993.4 1657.72  4996.1 1657.22  4999.4 1657.72
  5002.8 1658.26  5010.8 1661.03  5025.2 1661.48  5031.6 1662.38  5052.4 1670.22
  5074.8 1672.83    5110 1674.65  5159.6 1675.08  5238.1 1677.78  5271.7 1678.11
#Mann= 7 ,-1 , 0
  4417.7      .1       0    4489     .16       0  4528.3     .05       0
  4626.5     .16       0  4661.5      .1       0  4993.4     .07       0
  4999.4      .1       0
Bank Sta=4993.4,4999.4
XS Rating Curve= 0 ,0
Exp/Cntr=0.3,0.1

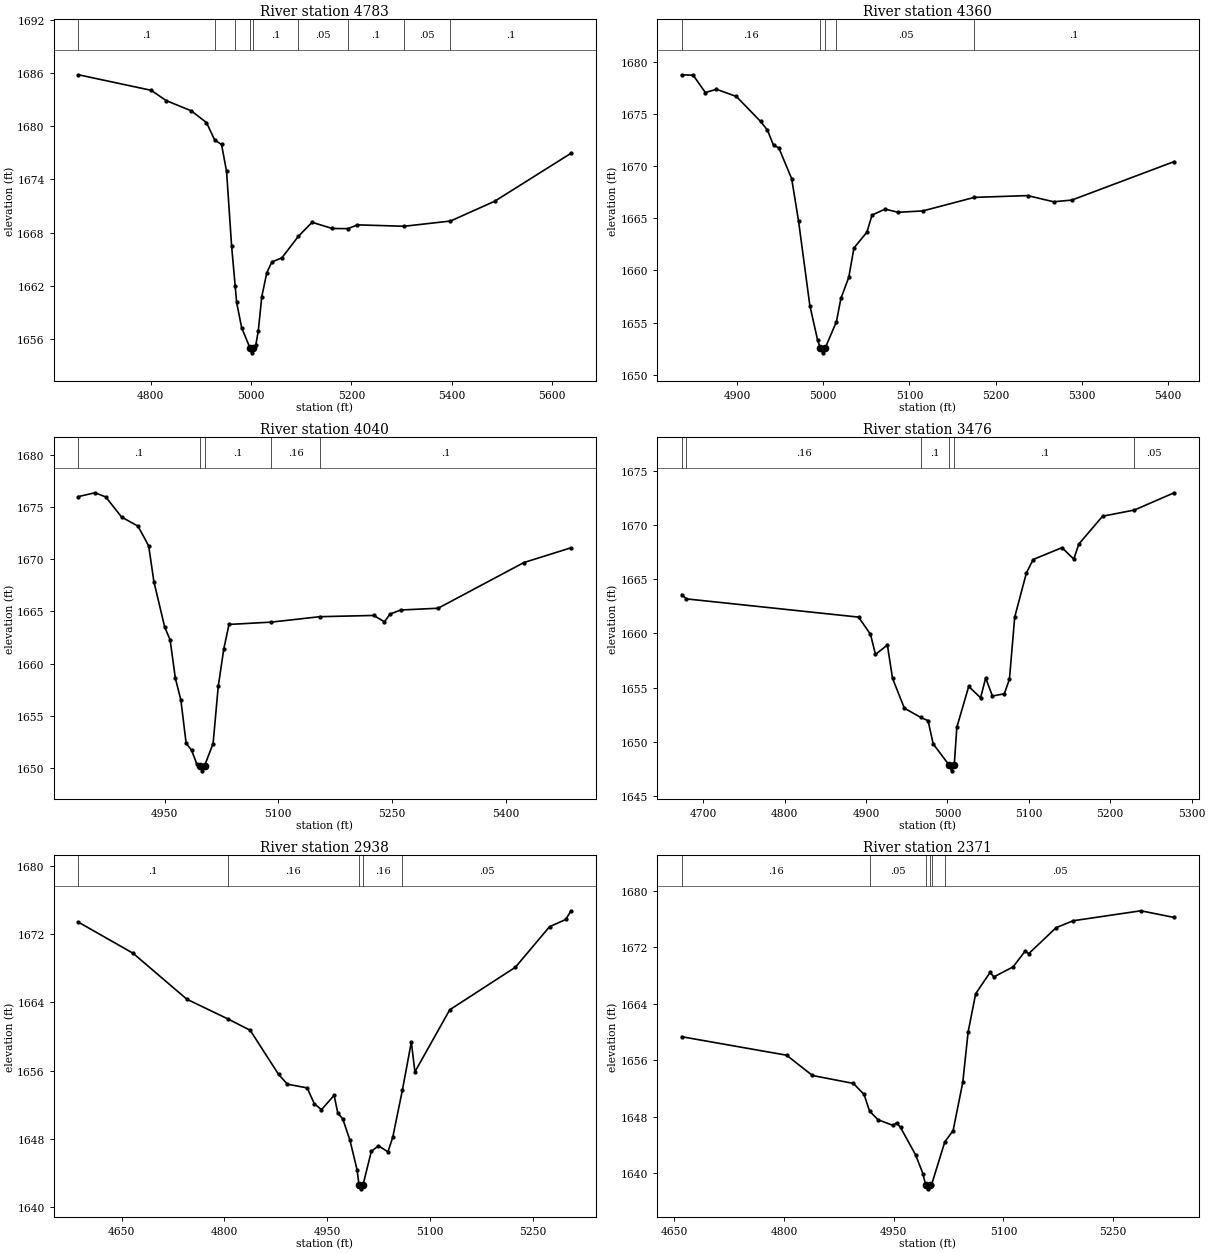
Type RM Length L Ch R = 1 ,4783    ,423,423,423
BEGIN DESCRIPTION:
UNT 0067 IN HEWA 9.0
END DESCRIPTION:
XS GIS Cut Line= 2
      2763732.91     10067611.42       2762753.7     10067548.91
#Sta/Elev= 30
  4656.1  1685.8  4800.8 1684.05  4830.9 1682.89    4881 1681.73  4911.1 1680.41
  4927.6 1678.43  4941.1 1677.94  4951.1 1674.91  4961.2 1666.46  4968.2 1662.03
  4971.2 1660.13  4981.2 1657.27  4998.2 1654.95    5001 1654.45  5004.2 1654.95
  5009.2 1655.28  5014.3 1656.91  5021.3  1660.8  5031.3 1663.48  5041.3 1664.69
  5061.4 1665.17  5094.4  1667.6  5121.5 1669.17  5161.6 1668.47    5193 1668.45
  5211.7 1668.88  5304.6 1668.72  5397.2 1669.31  5485.2 1671.54  5637.3 1676.95
#Mann= 9 ,-1 , 0
  4656.1      .1       0  4927.6     .16       0  4968.2      .1       0
  4998.2     .07       0  5004.2      .1       0  5094.4     .05       0
    5193      .1       0  5304.6     .05       0  5397.2      .1       0
Bank Sta=4998.2,5004.2
XS Rating Curve= 0 ,0
Exp/Cntr=0.3,0.1

Type RM Length L Ch R = 1 ,4360    ,320,320,320
BEGIN DESCRIPTION:
UNT 0067 IN HEWA 8.0
END DESCRIPTION:
XS GIS Cut Line= 2
      2763361.39     10067139.19      2762885.67     10067455.18
#Sta/Elev= 30
  4835.8 1678.75  4849.2 1678.71  4863.3 1677.05  4876.2 1677.36  4899.3 1676.67
  4927.3 1674.28  4935.3 1673.45  4942.4 1671.98  4948.4 1671.76  4963.4 1668.79
  4971.4 1664.72  4984.5 1656.62  4993.5 1653.31  4996.5  1652.6  4999.3  1652.1
  5002.5  1652.6  5015.3 1655.09  5020.5 1657.32  5029.6 1659.33  5035.6 1662.15
  5050.6 1663.66  5056.6  1665.3  5071.7 1665.88  5086.7 1665.57  5115.4  1665.7
  5175.2    1667    5237 1667.17  5267.1 1666.58  5288.2 1666.74  5406.9 1670.43
#Mann= 5 ,-1 , 0
  4835.8     .16       0  4996.5     .07       0  5002.5     .16       0
  5015.3     .05       0  5175.2      .1       0
Bank Sta=4996.5,5002.5
XS Rating Curve= 0 ,0
Exp/Cntr=0.3,0.1

Type RM Length L Ch R = 1 ,4040    ,564,564,564
BEGIN DESCRIPTION:
UNT 0067 IN HEWA 7.0
END DESCRIPTION:
XS GIS Cut Line= 2
      2763159.99     10066854.48       2762712.8     10067325.93
#Sta/Elev= 30
  4836.5 1675.99  4858.3 1676.35  4872.5 1675.95  4893.5 1674.02    4915 1673.16
  4929.1 1671.28    4936 1667.85  4950.2 1663.52  4957.4 1662.28  4964.3 1658.62
  4971.6 1656.52  4978.5 1652.41  4985.7 1651.73  4992.6 1650.42  4996.9 1650.26
  4999.6 1649.76  5002.9 1650.26  5014.1 1652.36  5020.9 1657.84  5028.2 1661.42
  5035.1 1663.76  5090.7 1663.98  5154.8  1664.5    5226 1664.62  5240.2 1664.01
  5247.5 1664.75  5261.6 1665.14    5311 1665.31  5424.2 1669.68  5486.3 1671.09
#Mann= 5 ,-1 , 0
  4836.5      .1       0  4996.9     .07       0  5002.9      .1       0
  5090.7     .16       0  5154.8      .1       0
Bank Sta=4996.9,5002.9
XS Rating Curve= 0 ,0
Exp/Cntr=0.3,0.1

Type RM Length L Ch R = 1 ,3476    ,538,538,538
BEGIN DESCRIPTION:
UNT 0067 IN HEWA 6.0
END DESCRIPTION:
XS GIS Cut Line= 2
      2762864.89     10066816.25      2762382.22     10067180.86
#Sta/Elev= 30
  4673.6 1663.56  4679.5 1663.17  4890.9 1661.49  4905.5 1659.91  4911.7 1658.05
  4926.3 1658.92  4932.6 1655.85  4947.1  1653.1  4967.4 1652.24  4976.3 1651.94
  4982.5 1649.81  5002.4 1647.82  5005.1 1647.32  5008.4 1647.82  5011.6 1651.34
  5026.2  1655.1  5040.8 1654.05    5047 1655.88  5055.3 1654.22  5069.9 1654.42
  5076.2 1655.77  5082.7  1661.5    5097 1665.55  5105.3  1666.8  5140.7 1667.89
  5155.2 1666.84  5161.5 1668.23  5190.6 1670.79  5229.7 1671.36  5278.5 1672.95
#Mann= 6 ,-1 , 0
  4673.6      .1       0  4679.5     .16       0  4967.4      .1       0
  5002.4     .07       0  5008.4      .1       0  5229.7     .05       0
Bank Sta=5002.4,5008.4
XS Rating Curve= 0 ,0
Exp/Cntr=0.3,0.1

Type RM Length L Ch R = 1 ,2938    ,567,567,567
BEGIN DESCRIPTION:
UNT 0067 IN HEWA 5.0
END DESCRIPTION:
XS GIS Cut Line= 2
      2763059.31     10066670.45      2762368.34     10066476.01
#Sta/Elev= 30
  4587.2  1673.4  4666.7 1669.76  4745.1 1664.37  4804.6 1662.07  4837.4 1660.73
  4878.9 1655.54  4891.7  1654.4  4920.5 1653.97  4930.9 1652.11  4941.3 1651.41
  4959.8  1653.1    4965 1651.06  4972.4 1650.32  4982.8 1647.84  4993.2 1644.36
    4996 1642.63  4998.8 1642.13    5002 1642.63    5014 1646.53  5024.4 1647.18
  5038.2 1646.47  5045.2 1648.17  5059.2 1653.68  5072.3 1659.35  5077.5 1655.85
  5128.3 1663.13    5224 1668.12  5273.7 1672.87  5297.3 1673.72    5305 1674.74
#Mann= 5 ,-1 , 0
  4587.2      .1       0  4804.6     .16       0    4996     .07       0
    5002     .16       0  5059.2     .05       0
Bank Sta=4996,5002
XS Rating Curve= 0 ,0
Exp/Cntr=0.3,0.1

Type RM Length L Ch R = 1 ,2371    ,499,499,499
BEGIN DESCRIPTION:
UNT 0067 IN HEWA 4.0
END DESCRIPTION:
XS GIS Cut Line= 3
      2762871.83     10066260.75      2762666.94       10066101.
      2762264.11     10066194.76
#Sta/Elev= 30
    4660 1659.35  4803.5 1656.73  4838.8 1653.86  4894.9 1652.73  4909.4 1651.17
    4917 1648.81  4928.5 1647.59  4948.9 1646.79    4954 1647.16  4959.3 1646.49
  4979.8 1642.63  4990.1  1639.9  4993.6  1638.3  4996.4  1637.8  4999.6  1638.3
  5001.7 1638.38  5019.8 1644.44  5031.2 1646.06  5044.4 1652.89  5051.7 1660.01
    5062 1665.43  5081.8 1668.47  5086.9 1667.82  5113.3 1669.25  5129.5 1671.46
  5134.7 1671.13  5172.1  1674.8  5195.5 1675.78  5287.9 1677.19  5333.4 1676.24
#Mann= 6 ,-1 , 0
    4660     .16       0    4917     .05       0  4993.6    .035       0
  4999.6     .05       0  5001.7     .16       0  5019.8     .05       0
Bank Sta=4993.6,4999.6
XS Rating Curve= 0 ,0
Exp/Cntr=0.3,0.1

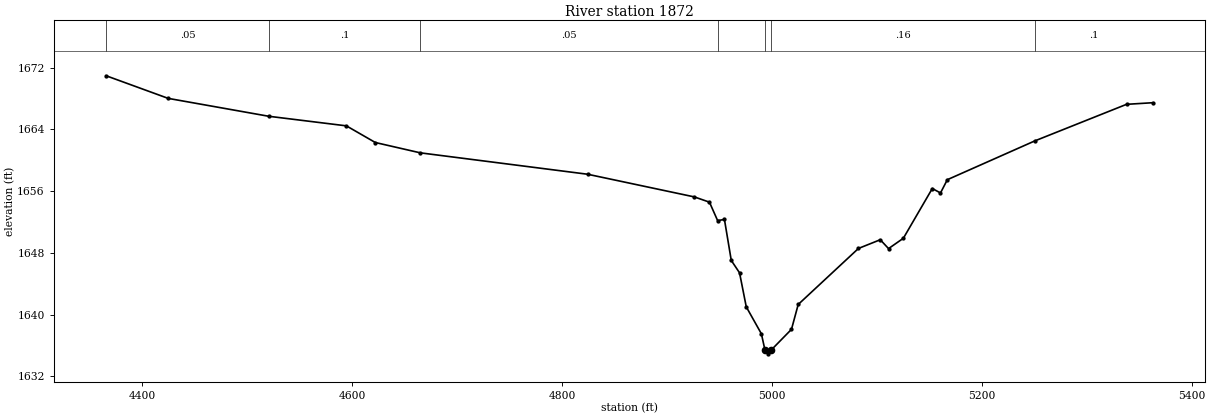
Type RM Length L Ch R = 1 ,1872    ,328,328,328
BEGIN DESCRIPTION:
UNT 0067 IN HEWA 3.0
END DESCRIPTION:
XS GIS Cut Line= 3
      2763524.54     10066257.23      2763045.41     10066000.31
       2762694.7      10065712.1
#Sta/Elev= 30
  4365.5 1670.95  4424.6 1668.02  4520.5  1665.7  4594.4 1664.46    4622  1662.3
  4664.9 1660.96  4824.2 1658.19    4926 1655.25  4940.4 1654.57  4948.2 1652.18
  4954.7 1652.33  4961.2 1647.02  4969.1 1645.41  4975.5    1641  4989.9 1637.51
  4993.3 1635.41  4996.1 1634.91  4999.3 1635.41  5018.6 1638.09    5025 1641.31
  5082.4 1648.57  5103.2  1649.7  5111.1 1648.55  5125.2 1649.89  5152.8 1656.34
  5160.6 1655.76  5167.1 1657.48  5250.5 1662.51  5337.9 1667.25  5363.1 1667.46
#Mann= 7 ,-1 , 0
  4365.5     .05       0  4520.5      .1       0  4664.9     .05       0
  4948.2     .16       0  4993.3     .07       0  4999.3     .16       0
  5250.5      .1       0
Bank Sta=4993.3,4999.3
XS Rating Curve= 0 ,0
Exp/Cntr=0.3,0.1