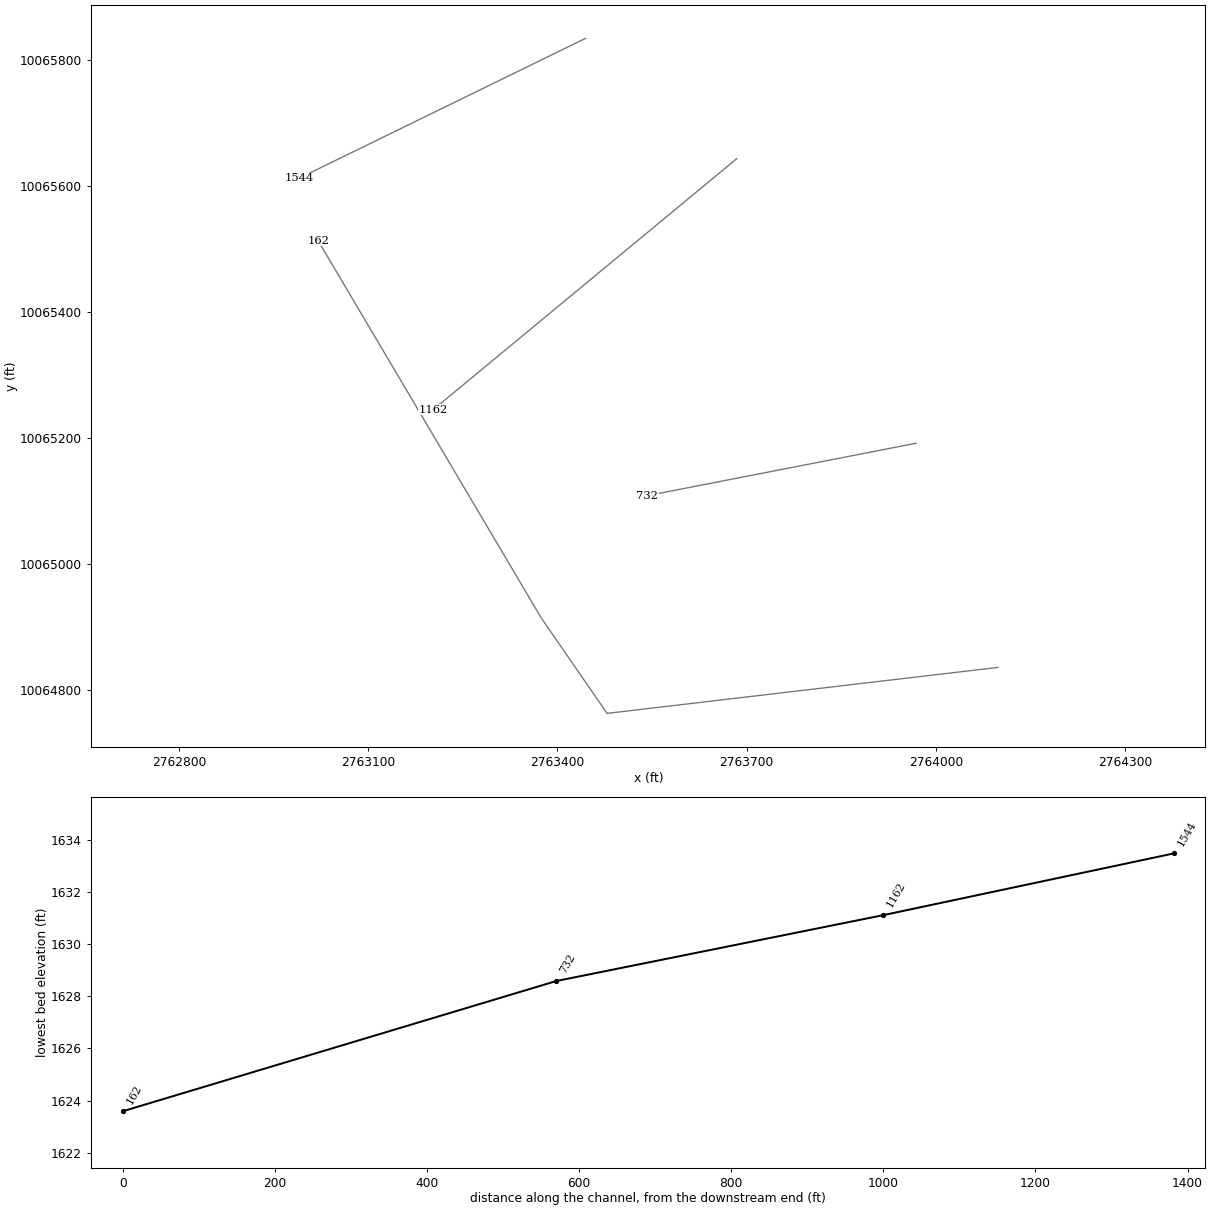
HEC-RAS study UNT 0067 IN HEWA.prj: UNT 0067 IN HEWA Base Level Engineering

--- UNT 0067 IN HEWA.g01 (geometry) --- (continued)

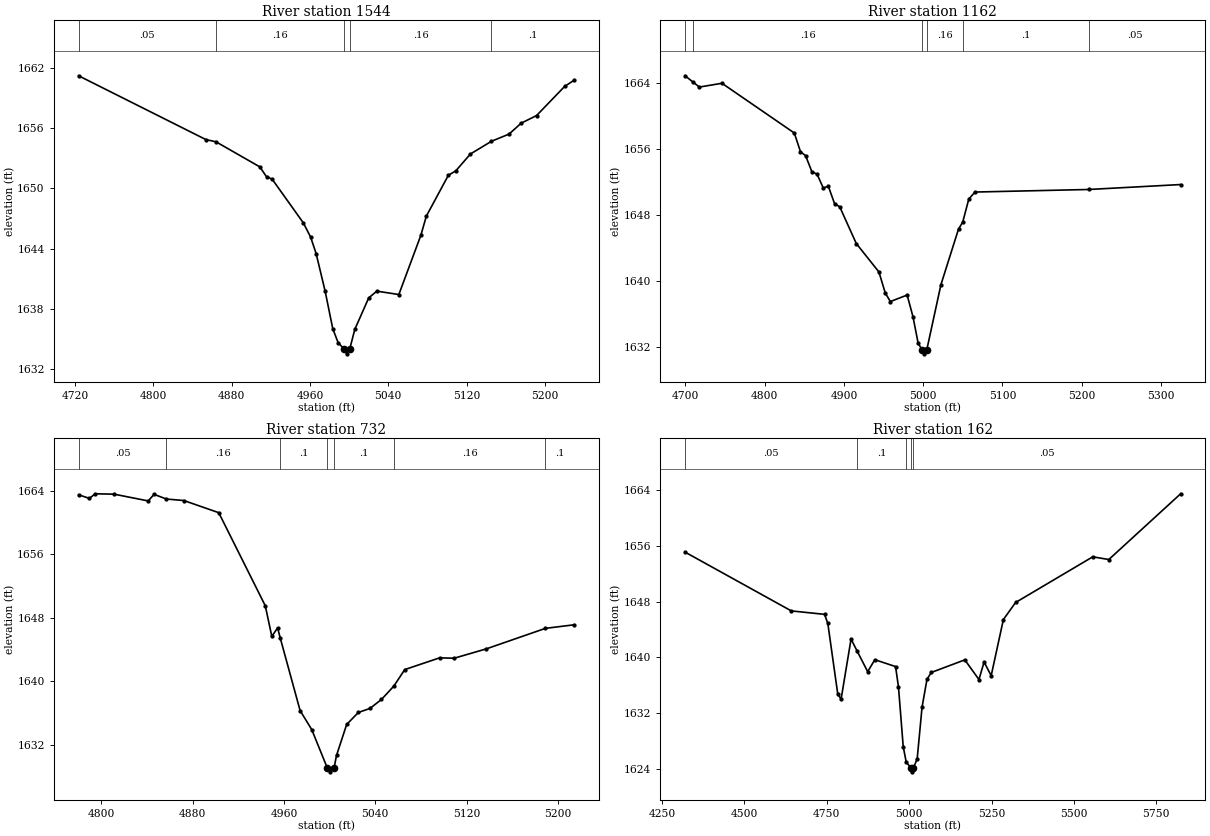
Type RM Length L Ch R = 1 ,1544    ,382,382,382
BEGIN DESCRIPTION:
UNT 0067 IN HEWA 2.0
END DESCRIPTION:
XS GIS Cut Line= 2
       2763444.7     10065833.63      2762989.88     10065611.43
#Sta/Elev= 30
  4723.7 1661.25  4853.7 1654.88    4864 1654.66  4908.7 1652.16  4915.7 1651.16
  4921.3 1650.94  4953.2 1646.57  4960.7 1645.14  4966.3  1643.5  4975.5 1639.75
  4983.3    1636  4988.8  1634.6  4994.7 1633.99  4997.5 1633.49  5000.7 1633.99
  5005.8 1635.93    5020 1639.07  5028.3 1639.75  5050.8 1639.41  5073.3 1645.33
  5078.9 1647.24  5101.4 1651.32    5109 1651.76  5123.9 1653.44  5145.4 1654.71
  5163.4 1655.43  5175.8 1656.52  5191.5 1657.28  5220.3  1660.2  5229.9 1660.81
#Mann= 5 ,-1 , 0
  4723.7     .05       0    4864     .16       0  4994.7     .07       0
  5000.7     .16       0  5145.4      .1       0
Bank Sta=4994.7,5000.7
XS Rating Curve= 0 ,0
Exp/Cntr=0.3,0.1

Type RM Length L Ch R = 1 ,1162    ,430,430,430
BEGIN DESCRIPTION:
Mapping XS 279fd901
END DESCRIPTION:
XS GIS Cut Line= 2
      2763684.33     10065642.69      2763202.54     10065244.09
#Sta/Elev= 30
  4699.6 1664.89  4710.1 1664.09  4717.6 1663.52  4746.1 1663.98  4837.4 1657.94
  4845.2 1655.67  4851.7 1655.18  4859.6 1653.23  4866.1 1652.95  4873.9 1651.27
  4880.4 1651.46  4888.2 1649.36  4894.7 1648.98  4915.6 1644.52  4944.2 1641.06
  4952.1 1638.53  4958.6 1637.47  4979.8 1638.26  4987.2 1635.61  4993.7  1632.4
  4998.6 1631.62  5001.3 1631.12  5004.6 1631.62  5022.4 1639.51  5044.6 1646.27
  5049.9 1647.11  5057.6 1649.92  5065.4 1650.77  5208.7 1651.08  5324.9 1651.68
#Mann= 6 ,-1 , 0
  4699.6     .05       0  4710.1     .16       0  4998.6     .07       0
  5004.6     .16       0  5049.9      .1       0  5208.7     .05       0
Bank Sta=4998.6,5004.6
XS Rating Curve= 0 ,0
Exp/Cntr=0.3,0.1

Type RM Length L Ch R = 1 ,732     ,570,570,570
BEGIN DESCRIPTION:
Mapping XS c48e58cb
END DESCRIPTION:
XS GIS Cut Line= 2
        2763969.     10065191.27      2763542.73      10065108.1
#Sta/Elev= 30
    4780 1663.46  4789.5 1663.01  4794.5 1663.59  4811.1 1663.54    4841 1662.69
  4846.1 1663.52  4856.9 1662.93  4872.2 1662.74  4902.8 1661.21  4943.6 1649.49
  4949.3 1645.64  4954.4 1646.71  4956.6 1645.49  4974.1  1636.3  4984.3 1633.91
  4997.9 1629.09  5000.6 1628.59  5003.9 1629.09    5006 1630.65  5014.9 1634.55
  5025.1 1636.06  5035.3 1636.57  5045.4  1637.7  5056.3 1639.39  5065.8 1641.46
  5096.4 1642.94  5109.1 1642.89  5137.1 1644.06  5189.1 1646.65  5214.3  1647.1
#Mann= 7 ,-1 , 0
    4780     .05       0  4856.9     .16       0  4956.6      .1       0
  4997.9     .07       0  5003.9      .1       0  5056.3     .16       0
  5189.1      .1       0
Bank Sta=4997.9,5003.9
XS Rating Curve= 0 ,0
Exp/Cntr=0.3,0.1

Type RM Length L Ch R = 1 ,162     ,0,0,0
BEGIN DESCRIPTION:
UNT 0067 IN HEWA 1.0
END DESCRIPTION:
XS GIS Cut Line= 4
      2764098.53     10064835.58      2763478.76     10064762.66
      2763374.59     10064913.71       2763020.4     10065512.71
#Sta/Elev= 30
  4320.4  1655.1  4642.7 1646.67  4743.4 1646.18  4753.4 1644.88  4783.6 1634.73
  4793.7 1634.02  4823.9 1642.64  4842.4  1640.9  4874.3 1637.96    4896 1639.67
  4958.9 1638.69  4967.7 1635.79  4982.2 1627.18  4991.2    1625  5006.6 1624.09
  5009.3 1623.59  5012.6 1624.09  5024.5 1625.45  5039.3 1632.87  5054.2 1636.85
  5067.2 1637.84    5169 1639.65  5211.9 1636.83  5227.5 1639.34    5249 1637.38
    5286 1645.43  5323.1 1647.88  5557.2 1654.43  5605.9 1654.04  5823.8 1663.47
#Mann= 5 ,-1 , 0
  4320.4     .05       0  4842.4      .1       0  4991.2     .05       0
  5006.6     .04       0  5012.6     .05       0
Bank Sta=5006.6,5012.6
XS Rating Curve= 0 ,0
Exp/Cntr=0.3,0.1

Chan Stop Cuts=-1
Use User Specified Reach Order=0
Composite Channel Slope=5