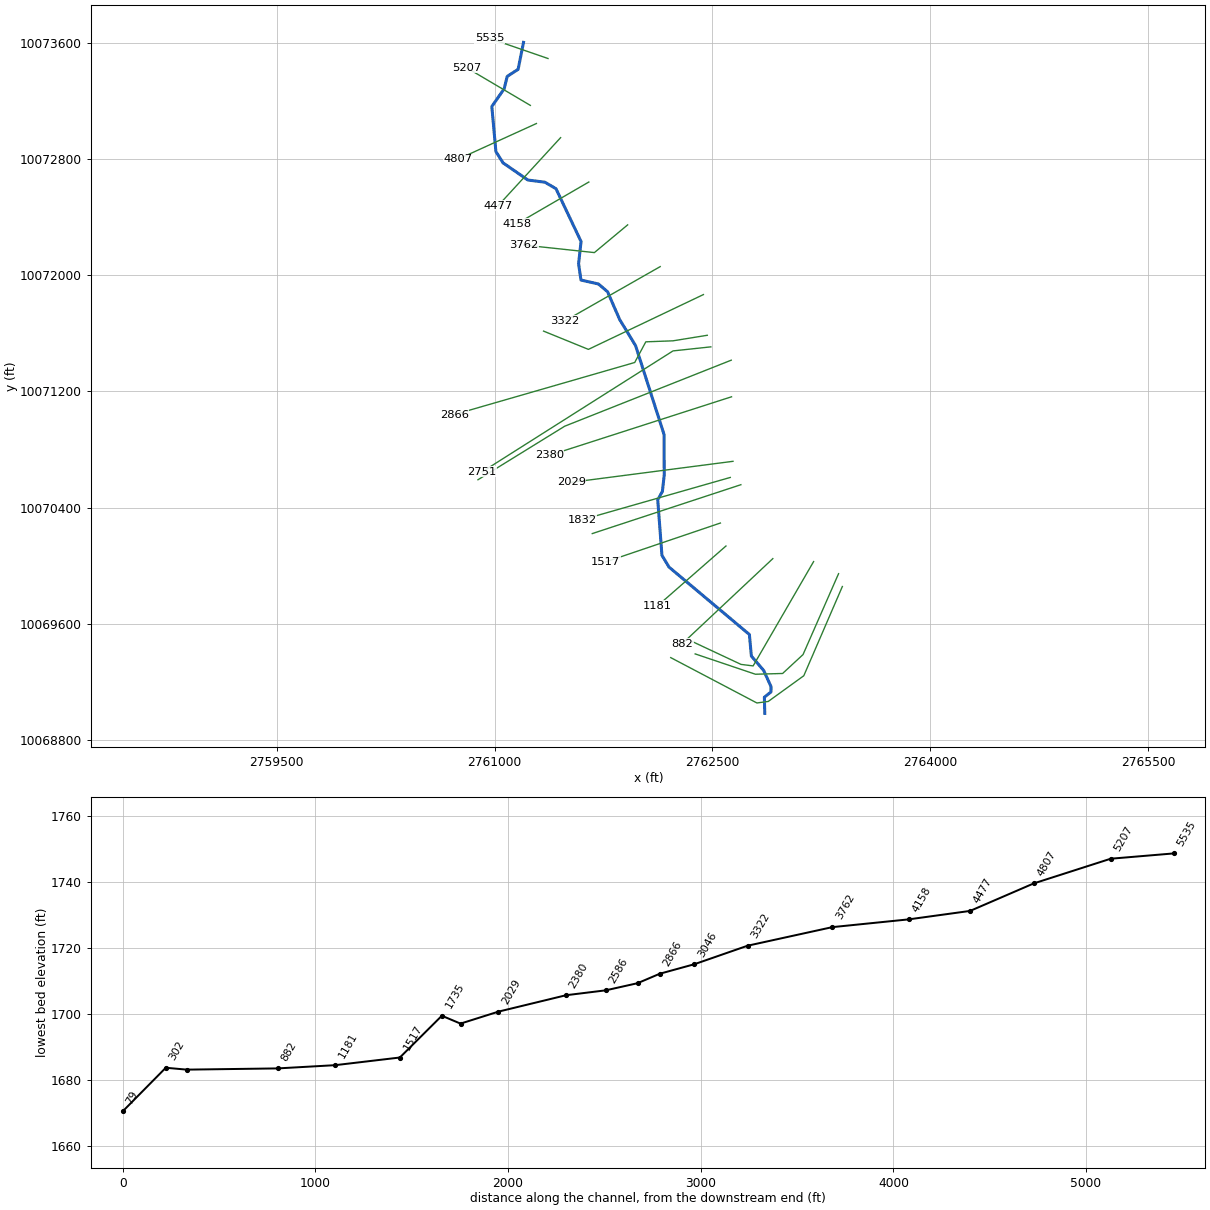
--- UNT 0068 IN HEWA.prj (project) ---

Proj Title=UNT 0068 IN HEWA Base Level Engineering
Current Plan=p01
Default Exp/Contr=0.3,0.1
English Units
Geom File=g01
Flow File=f01
Plan File=p01
BEGIN DESCRIPTION:
UNT 0068 IN HEWA
END DESCRIPTION:

--- UNT 0068 IN HEWA.p01 (plan) ---

Plan Title=Multiple Run
Short Identifier=Multiple
Geom File=g01
Flow File=f01
Subcritical Flow
K Sum by GR= 0
Std Step Tol= 0.01
Critical Tol= 0.01
Num of Std Step Trials= 20
Max Error Tol= 0.3
Flow Tol Ratio= 0.001
Split Flow NTrial= 30
Split Flow Tol= 0.02
Split Flow Ratio= 0.02
Log Output Level= 0
Friction Slope Method= 1
Unsteady Friction Slope Method= 2
Unsteady Bridges Friction Slope Method= 1
Parabolic Critical Depth
Global Vel Dist=  1 , 1 , 1
Global Log Level= 0
CheckData=True
Encroach Param= -1, 0, 0, 0
BEGIN DESCRIPTION:
Multiple Run
END DESCRIPTION:

--- UNT 0068 IN HEWA.f01 (steady flow) ---

Flow Title=Multiple
Number of Profiles=7
Profile Names=10-year,25-year,50-year,1pct_min,100-year,1pct_plu,500-year
River Rch & RM= UNT 0068 IN HEWA,Reach-1,5535
     675     972    1228    1138    1540    2082    2427
River Rch & RM= UNT 0068 IN HEWA,Reach-1,79
    1665    2484    3213    3033    4102    5547    6719
Boundary for River Rch & Prof#=UNT 0068 IN HEWA,Reach-1,1
Up Type=0
Dn Type=3
Dn Slope=0.005
Boundary for River Rch & Prof#=UNT 0068 IN HEWA,Reach-1,2
Up Type=0
Dn Type=3
Dn Slope=0.005
Boundary for River Rch & Prof#=UNT 0068 IN HEWA,Reach-1,3
Up Type=0
Dn Type=3
Dn Slope=0.005
Boundary for River Rch & Prof#=UNT 0068 IN HEWA,Reach-1,4
Up Type=0
Dn Type=3
Dn Slope=0.005
Boundary for River Rch & Prof#=UNT 0068 IN HEWA,Reach-1,5
Up Type=0
Dn Type=3
Dn Slope=0.005
Boundary for River Rch & Prof#=UNT 0068 IN HEWA,Reach-1,6
Up Type=0
Dn Type=3
Dn Slope=0.005
Boundary for River Rch & Prof#=UNT 0068 IN HEWA,Reach-1,7
Up Type=0
Dn Type=3
Dn Slope=0.005

--- UNT 0068 IN HEWA.g01 (geometry) ---

Geom Title=Existing Conditions

River Reach=UNT 0068 IN HEWA,Reach-1
Reach XY= 30
      2761199.45     10073604.33      2761162.23     10073418.52
      2761087.03     10073369.70      2761066.19     10073284.54
      2760981.08     10073162.69      2761009.22     10072852.28
      2761058.44     10072774.23      2761229.54     10072656.05
      2761347.21     10072640.84      2761423.06     10072596.22
      2761595.73     10072232.59      2761578.73     10072079.06
      2761595.01     10071967.10      2761715.65     10071940.08
      2761778.28     10071886.66      2761861.49     10071695.30
      2761970.94     10071516.06      2762167.38     10070903.39
      2762168.48     10070623.63      2762155.83     10070511.31
      2762123.89     10070453.29      2762152.78     10070071.29
      2762201.53     10069990.31      2762755.13     10069525.97
      2762768.72     10069377.51      2762853.96     10069277.50
      2762903.90     10069167.33      2762903.71     10069130.17
      2762858.31     10069093.86      2762861.05     10068982.66

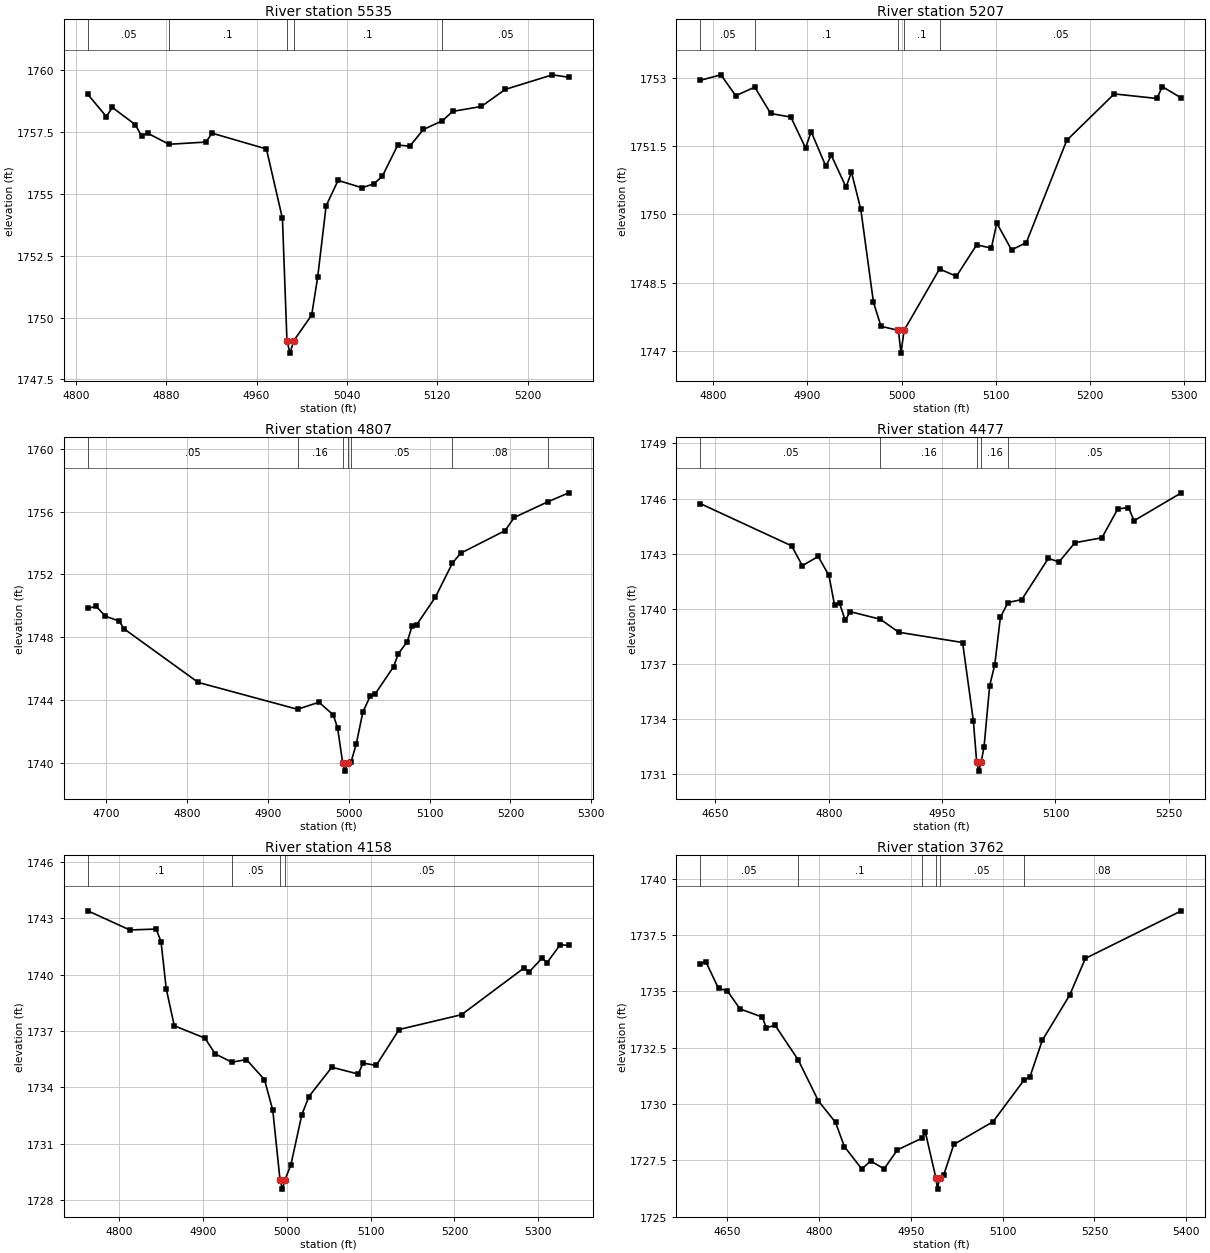
Type RM Length L Ch R = 1,5535,328,328,328
BEGIN DESCRIPTION:
UNT 0068 IN HEWA 12.0
END DESCRIPTION:
XS GIS Cut Line= 2
      2761368.06     10073493.06      2760965.23     10073631.97
#Sta/Elev= 30
  4810.5 1759.03  4826.9 1758.13  4832.2 1758.50  4852.4 1757.81  4858.1 1757.35
  4863.4 1757.46  4882.4 1757.01  4915.2 1757.10  4920.5 1757.46  4968.7 1756.82
  4982.9 1754.01  4986.9 1749.06  4989.6 1748.56  4992.9 1749.06  5008.8 1750.10
  5014.1 1751.63  5021.6 1754.52  5032.2 1755.55  5053.4 1755.25  5063.9 1755.41
  5071.3 1755.71  5085.1 1756.98  5095.7 1756.93  5107.8 1757.61  5124.6 1757.96
  5133.7 1758.34  5159.1 1758.54  5180.3 1759.23  5222.0 1759.82  5236.6 1759.72
#Mann=5,-1,0
  4810.5    0.05       0  4882.4     0.1       0  4986.9    0.07       0
  4992.9     0.1       0  5124.6    0.05       0
Bank Sta=4986.9,4992.9
Exp/Cntr=0.3,0.1

Type RM Length L Ch R = 1,5207,400,400,400
BEGIN DESCRIPTION:
UNT 0068 IN HEWA 11.0
END DESCRIPTION:
XS GIS Cut Line= 2
      2761246.53     10073170.14      2760807.13     10073429.63
#Sta/Elev= 30
  4786.5 1752.95  4808.3 1753.07  4824.0 1752.61  4844.2 1752.80  4861.1 1752.22
  4882.5 1752.14  4898.1 1751.46  4904.0 1751.82  4919.6 1751.06  4925.4 1751.30
  4941.0 1750.60  4946.8 1750.93  4956.7 1750.11  4970.1 1748.07  4978.1 1747.54
  4996.6 1747.45  4999.3 1746.95  5002.6 1747.45  5040.2 1748.80  5058.1 1748.64
  5079.6 1749.33  5095.2 1749.26  5101.0 1749.81  5116.6 1749.22  5132.3 1749.38
  5175.2 1751.63  5225.6 1752.65  5270.8 1752.55  5276.6 1752.81  5296.8 1752.56
#Mann=5,-1,0
  4786.5    0.05       0  4844.2     0.1       0  4996.6    0.07       0
  5002.6     0.1       0  5040.2    0.05       0
Bank Sta=4996.6,5002.6
Exp/Cntr=0.3,0.1

Type RM Length L Ch R = 1,4807,330,330,330
BEGIN DESCRIPTION:
Mapping XS a7af278a
END DESCRIPTION:
XS GIS Cut Line= 2
      2761288.17     10073045.16      2760746.63     10072798.68
#Sta/Elev= 30
  4677.2 1749.83  4687.5 1749.96  4698.9 1749.33  4716.1 1749.02  4721.6 1748.54
  4813.8 1745.11  4936.6 1743.40  4963.1 1743.85  4980.7 1743.05  4986.2 1742.21
  4992.5 1739.96  4995.3 1739.46  4998.5 1739.96  5002.8 1740.04  5009.3 1741.20
  5017.5 1743.24  5026.8 1744.26  5032.3 1744.35  5055.4 1746.11  5061.4 1746.95
  5072.4 1747.71  5078.4 1748.72  5083.9 1748.78  5107.0 1750.53  5128.2 1752.71
  5138.3 1753.34  5193.3 1754.78  5204.7 1755.62  5246.7 1756.63  5272.2 1757.19
#Mann=7,-1,0
  4677.2    0.05       0  4936.6    0.16       0  4992.5    0.07       0
  4998.5    0.16       0  5002.8    0.05       0  5128.2    0.08       0
  5246.7    0.05       0
Bank Sta=4992.5,4998.5
Exp/Cntr=0.3,0.1

Type RM Length L Ch R = 1,4477,319,319,319
BEGIN DESCRIPTION:
UNT 0068 IN HEWA 10.0
END DESCRIPTION:
XS GIS Cut Line= 2
      2761454.86     10072947.95      2761024.29     10072479.19
#Sta/Elev= 30
  4630.1 1745.72  4750.8 1743.42  4765.0 1742.34  4786.0 1742.84  4800.2 1741.81
  4807.6 1740.20  4814.3 1740.28  4821.7 1739.37  4828.5 1739.83  4868.2 1739.42
  4892.6 1738.71  4977.1 1738.15  4991.3 1733.89  4995.7 1731.64  4998.4 1731.14
  5001.7 1731.64  5005.5 1732.47  5012.9 1735.79  5019.7 1736.95  5027.1 1739.53
  5037.2 1740.33  5055.4 1740.49  5090.6 1742.74  5104.7 1742.54  5125.7 1743.59
  5161.5 1743.86  5182.4 1745.43  5196.6 1745.51  5204.0 1744.79  5266.6 1746.31
#Mann=5,-1,0
  4630.1    0.05       0  4868.2    0.16       0  4995.7    0.07       0
  5001.7    0.16       0  5037.2    0.05       0
Bank Sta=4995.7,5001.7
Exp/Cntr=0.3,0.1

Type RM Length L Ch R = 1,4158,396,396,396
BEGIN DESCRIPTION:
UNT 0068 IN HEWA 9.0
END DESCRIPTION:
XS GIS Cut Line= 2
      2761649.30     10072642.39      2761153.13     10072354.40
#Sta/Elev= 30
  4762.7 1743.40  4812.8 1742.38  4844.2 1742.43  4850.0 1741.76  4856.2 1739.25
  4865.8 1737.28  4902.4 1736.62  4914.6 1735.78  4934.6 1735.34  4951.9 1735.48
  4973.4 1734.41  4983.3 1732.78  4991.9 1729.08  4994.7 1728.58  4997.9 1729.08
  5004.9 1729.88  5018.0 1732.55  5026.4 1733.51  5053.7 1735.07  5085.2 1734.71
  5091.0 1735.29  5106.7 1735.17  5134.0 1737.08  5208.5 1737.87  5283.1 1740.36
  5288.8 1740.13  5304.6 1740.89  5310.4 1740.64  5326.1 1741.59  5336.4 1741.56
#Mann=4,-1,0
  4762.7     0.1       0  4934.6    0.05       0  4991.9    0.04       0
  4997.9    0.05       0
Bank Sta=4991.9,4997.9
Exp/Cntr=0.3,0.1

Type RM Length L Ch R = 1,3762,440,440,440
BEGIN DESCRIPTION:
UNT 0068 IN HEWA 8.0
END DESCRIPTION:
XS GIS Cut Line= 3
      2761916.68     10072347.27      2761687.48     10072156.27
      2761202.41     10072208.24
#Sta/Elev= 30
  4605.8 1736.22  4614.6 1736.32  4635.4 1735.13  4649.7 1735.03  4670.5 1734.22
  4707.0 1733.86  4713.5 1733.38  4727.8 1733.50  4765.7 1731.96  4798.7 1730.14
  4826.7 1729.19  4841.1 1728.12  4869.7 1727.12  4884.0 1727.48  4906.2 1727.13
  4927.8 1727.97  4968.1 1728.49  4973.6 1728.75  4990.7 1726.73  4993.4 1726.23
  4996.7 1726.73  5003.7 1726.87  5020.0 1728.21  5084.2 1729.22  5134.4 1731.05
  5144.5 1731.21  5164.7 1732.83  5209.4 1734.83  5235.1 1736.46  5392.0 1738.57
#Mann=6,-1,0
  4605.8    0.05       0  4765.7     0.1       0  4968.1    0.05       0
  4990.7    0.04       0  4996.7    0.05       0  5134.4    0.08       0
Bank Sta=4990.7,4996.7
Exp/Cntr=0.3,0.1

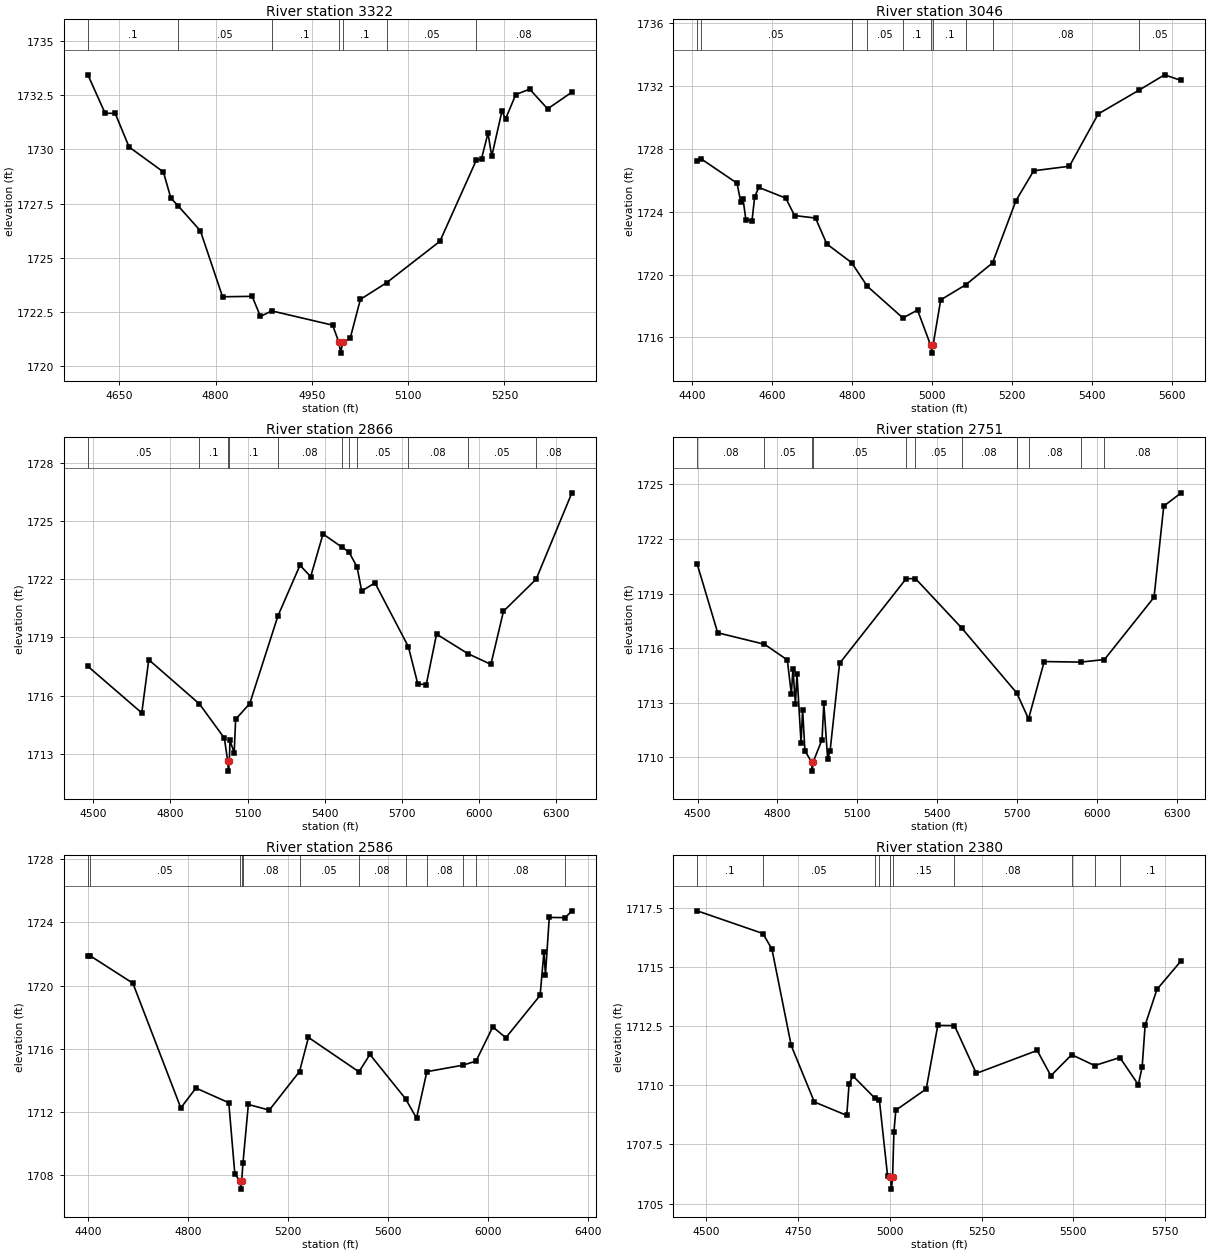
Type RM Length L Ch R = 1,3322,276,276,276
BEGIN DESCRIPTION:
UNT 0068 IN HEWA 7.0
END DESCRIPTION:
XS GIS Cut Line= 2
      2762140.82     10072059.66      2761485.60     10071686.55
#Sta/Elev= 30
  4601.1 1733.44  4627.9 1731.67  4643.7 1731.66  4665.3 1730.11  4718.7 1728.96
  4730.4 1727.75  4741.9 1727.39  4776.4 1726.24  4810.9 1723.20  4857.0 1723.22
  4870.0 1722.29  4887.3 1722.55  4982.4 1721.89  4992.1 1721.10  4994.8 1720.60
  4998.1 1721.10  5009.7 1721.28  5025.6 1723.08  5066.5 1723.85  5149.5 1725.76
  5206.0 1729.49  5214.3 1729.57  5224.4 1730.75  5230.2 1729.68  5246.1 1731.76
  5251.8 1731.41  5267.7 1732.53  5289.3 1732.78  5317.3 1731.87  5355.1 1732.64
#Mann=7,-1,0
  4601.1     0.1       0  4741.9    0.05       0  4887.3     0.1       0
  4992.1    0.07       0  4998.1     0.1       0  5066.5    0.05       0
  5206.0    0.08       0
Bank Sta=4992.1,4998.1
Exp/Cntr=0.3,0.1

Type RM Length L Ch R = 1,3046,180,180,180
BEGIN DESCRIPTION:
Mapping XS f6cc8d95
END DESCRIPTION:
XS GIS Cut Line= 3
      2762438.49     10071867.18      2761646.33     10071489.68
      2761337.49     10071615.51
#Sta/Elev= 30
  4412.6 1727.22  4421.9 1727.38  4512.3 1725.82  4521.5 1724.64  4527.1 1724.84
  4534.5 1723.49  4549.8 1723.44  4556.6 1724.97  4566.9 1725.55  4634.2 1724.87
  4656.3 1723.76  4708.7 1723.60  4736.9 1721.95  4799.0 1720.76  4838.1 1719.26
  4927.2 1717.24  4963.9 1717.74  4996.7 1715.50  4999.5 1715.00  5002.7 1715.50
  5021.9 1718.39  5084.9 1719.36  5151.5 1720.74  5210.2 1724.71  5254.5 1726.61
  5343.9 1726.90  5416.0 1730.23  5517.1 1731.73  5581.9 1732.72  5623.6 1732.36
#Mann=10,-1,0
  4412.6     0.1       0  4421.9    0.05       0  4799.0     0.1       0
  4838.1    0.05       0  4927.2     0.1       0  4996.7    0.07       0
  5002.7     0.1       0  5084.9    0.05       0  5151.5    0.08       0
  5517.1    0.05       0
Bank Sta=4996.7,5002.7
Exp/Cntr=0.3,0.1

Type RM Length L Ch R = 1,2866,115,115,115
BEGIN DESCRIPTION:
Mapping XS 2073106a
END DESCRIPTION:
XS GIS Cut Line= 5
      2762465.25     10071586.82      2762229.15     10071548.63
      2762041.65     10071541.68      2761965.26     10071399.32
      2760723.02     10071040.80
#Sta/Elev= 30
  4479.5 1717.51  4689.0 1715.11  4716.2 1717.85  4913.3 1715.57  5010.0 1713.81
  5023.2 1712.61  5026.0 1712.11  5029.2 1712.61  5031.9 1713.69  5048.2 1713.05
  5053.8 1714.78  5108.7 1715.59  5218.3 1720.11  5303.9 1722.72  5345.5 1722.13
  5393.5 1724.33  5466.9 1723.65  5493.8 1723.41  5525.8 1722.63  5543.7 1721.39
  5595.3 1721.81  5724.9 1718.53  5761.9 1716.60  5794.8 1716.57  5834.7 1719.17
  5955.7 1718.17  6045.9 1717.61  6094.9 1720.35  6221.8 1722.00  6360.8 1726.45
#Mann=11,-1,0
  4479.5    0.05       0  4913.3     0.1       0  5023.2    0.07       0
  5029.2     0.1       0  5218.3    0.08       0  5466.9    0.05       0
  5493.8    0.08       0  5525.8    0.05       0  5724.9    0.08       0
  5955.7    0.05       0  6221.8    0.08       0
Bank Sta=5023.2,5029.2
Exp/Cntr=0.3,0.1

Type RM Length L Ch R = 1,2751,165,165,165
BEGIN DESCRIPTION:
Mapping XS f689eecb
END DESCRIPTION:
XS GIS Cut Line= 3
      2762489.60     10071506.96      2762229.15     10071479.18
      2760914.21     10070646.02
#Sta/Elev= 30
  4498.7 1720.63  4575.8 1716.85  4751.6 1716.22  4837.3 1715.36  4852.6 1713.48
  4858.5 1714.88  4867.8 1712.94  4873.7 1714.58  4889.0 1710.80  4894.9 1712.63
  4903.5 1710.37  4928.4 1709.75  4931.1 1709.25  4934.4 1709.75  4967.8 1710.98
  4974.5 1712.97  4989.0 1709.90  4998.2 1710.38  5033.7 1715.17  5283.7 1719.82
  5318.7 1719.83  5492.1 1717.12  5699.5 1713.54  5743.7 1712.12  5802.5 1715.27
  5940.2 1715.24  6028.8 1715.38  6215.2 1718.80  6251.7 1723.81  6317.3 1724.54
#Mann=11,-1,0
  4498.7    0.08       0  4751.6    0.05       0  4928.4    0.04       0
  4934.4    0.05       0  5283.7    0.08       0  5318.7    0.05       0
  5492.1    0.08       0  5699.5     0.1       0  5743.7    0.08       0
  5940.2    0.05       0  6028.8    0.08       0
Bank Sta=4928.4,4934.4
Exp/Cntr=0.3,0.1

Type RM Length L Ch R = 1,2586,206,206,206
BEGIN DESCRIPTION:
UNT 0068 IN HEWA 6.0
END DESCRIPTION:
XS GIS Cut Line= 3
      2762630.19     10071415.34      2761483.32     10070960.60
      2760885.63     10070591.69
#Sta/Elev= 30
  4399.9 1721.85  4407.9 1721.90  4579.9 1720.15  4771.7 1712.24  4832.0 1713.50
  4963.5 1712.57  4987.8 1708.04  5009.1 1707.59  5011.9 1707.09  5015.1 1707.59
  5020.3 1708.75  5041.8 1712.46  5125.5 1712.10  5246.5 1714.55  5282.2 1716.71
  5484.2 1714.53  5528.0 1715.63  5670.6 1712.82  5714.5 1711.59  5755.9 1714.54
  5900.0 1714.95  5952.4 1715.21  6019.6 1717.38  6071.7 1716.69  6208.8 1719.38
  6224.2 1722.14  6230.1 1720.69  6245.5 1724.32  6309.4 1724.31  6336.0 1724.74
#Mann=12,-1,0
  4399.9     0.1       0  4407.9    0.05       0  5009.1    0.04       0
  5015.1    0.05       0  5020.3    0.08       0  5246.5    0.05       0
  5484.2    0.08       0  5670.6     0.1       0  5755.9    0.08       0
  5900.0    0.05       0  5952.4    0.08       0  6309.4    0.05       0
Bank Sta=5009.1,5015.1
Exp/Cntr=0.3,0.1

Type RM Length L Ch R = 1,2380,351,351,351
BEGIN DESCRIPTION:
UNT 0068 IN HEWA 5.0
END DESCRIPTION:
XS GIS Cut Line= 2
      2762632.25     10071163.21      2761377.31     10070759.45
#Sta/Elev= 30
  4475.5 1717.39  4654.4 1716.43  4679.1 1715.77  4731.6 1711.69  4794.6 1709.30
  4882.9 1708.73  4889.2 1710.06  4899.7 1710.40  4960.2 1709.45  4971.8 1709.37
  4994.2 1706.15  5001.7 1706.11  5004.5 1705.61  5007.7 1706.11  5011.3 1708.02
  5016.5 1708.95  5099.3 1709.85  5130.8 1712.54  5176.3 1712.53  5235.8 1710.51
  5401.5 1711.48  5438.8 1710.41  5495.5 1711.30  5558.0 1710.84  5626.7 1711.18
  5677.0 1710.03  5687.5 1710.79  5695.5 1712.55  5727.6 1714.06  5793.8 1715.28
#Mann=10,-1,0
  4475.5     0.1       0  4654.4    0.05       0  4960.2    0.08       0
  4971.8    0.15       0  5001.7    0.07       0  5007.7    0.15       0
  5176.3    0.08       0  5495.5    0.05       0  5558.0    0.08       0
  5626.7     0.1       0
Bank Sta=5001.7,5007.7
Exp/Cntr=0.3,0.1

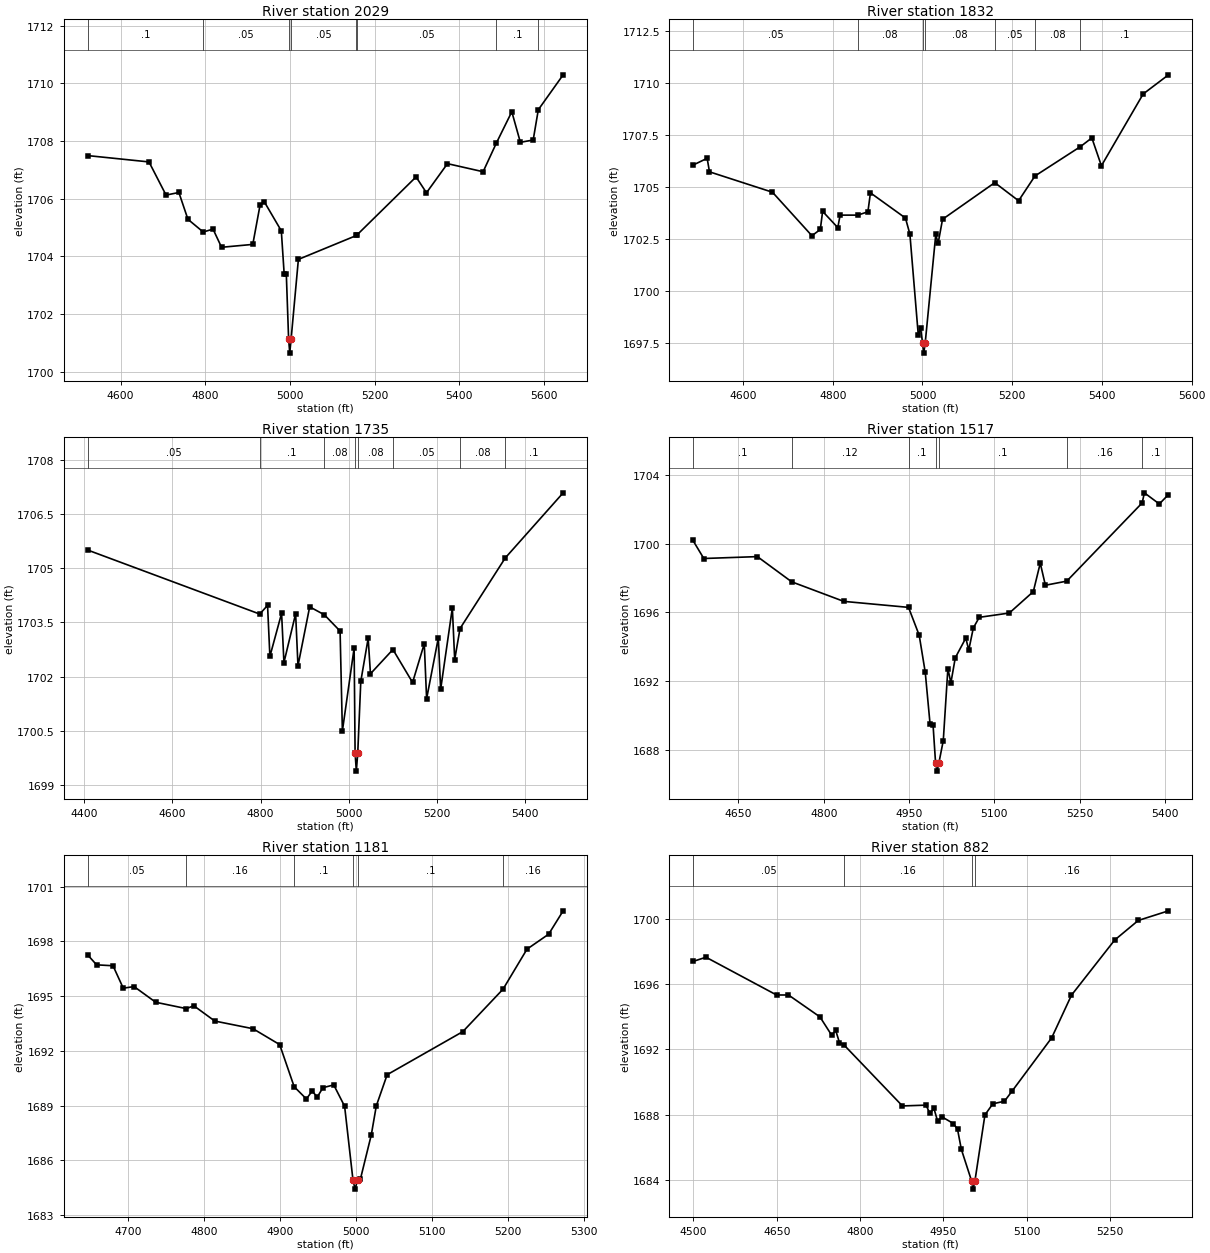
Type RM Length L Ch R = 1,2029,197,197,197
BEGIN DESCRIPTION:
UNT 0068 IN HEWA 4.0
END DESCRIPTION:
XS GIS Cut Line= 2
      2762642.37     10070718.77      2761528.22     10070574.07
#Sta/Elev= 30
  4522.0 1707.49  4667.1 1707.27  4707.4 1706.12  4737.7 1706.21  4759.1 1705.28
  4795.2 1704.84  4818.4 1704.94  4838.5 1704.31  4912.3 1704.41  4929.3 1705.76
  4939.4 1705.89  4979.7 1704.88  4986.5 1703.37  4991.5 1703.38  4996.9 1701.14
  4999.6 1700.64  5002.9 1701.14  5020.0 1703.89  5157.3 1704.72  5157.9 1704.73
  5298.0 1706.75  5322.6 1706.20  5372.2 1707.21  5456.4 1706.93  5487.9 1707.93
  5524.2 1709.01  5544.4 1707.95  5574.7 1708.03  5586.8 1709.08  5645.5 1710.29
#Mann=8,-1,0
  4522.0     0.1       0  4795.2    0.05       0  4996.9    0.04       0
  5002.9    0.05       0  5157.3    0.08       0  5157.9    0.05       0
  5487.9     0.1       0  5586.8    0.08       0
Bank Sta=4996.9,5002.9
Exp/Cntr=0.3,0.1

Type RM Length L Ch R = 1,1832,97,97,97
BEGIN DESCRIPTION:
Mapping XS aff8552c
END DESCRIPTION:
XS GIS Cut Line= 2
      2762623.55     10070607.61      2761604.24     10070316.38
#Sta/Elev= 30
  4488.2 1706.04  4520.0 1706.37  4525.2 1705.72  4665.6 1704.74  4753.5 1702.65
  4772.2 1702.95  4777.4 1703.82  4811.2 1703.04  4816.4 1703.64  4855.8 1703.64
  4878.3 1703.80  4884.0 1704.71  4962.0 1703.50  4971.9 1702.73  4990.6 1697.88
  4995.8 1698.20  5000.1 1697.51  5002.8 1697.01  5006.1 1697.51  5029.6 1702.71
  5034.8 1702.28  5044.7 1703.44  5161.1 1705.20  5214.2 1704.33  5250.7 1705.52
  5352.0 1706.93  5377.5 1707.35  5398.8 1706.01  5491.9 1709.46  5548.3 1710.38
#Mann=7,-1,0
  4488.2    0.05       0  4855.8    0.08       0  5000.1    0.07       0
  5006.1    0.08       0  5161.1    0.05       0  5250.7    0.08       0
  5352.0     0.1       0
Bank Sta=5000.1,5006.1
Exp/Cntr=0.3,0.1

Type RM Length L Ch R = 1,1735,218,218,218
BEGIN DESCRIPTION:
Mapping XS 81eea382
END DESCRIPTION:
XS GIS Cut Line= 2
      2762696.40     10070557.57      2761673.02     10070220.99
#Sta/Elev= 30
  4408.2 1705.50  4798.2 1703.73  4815.9 1703.97  4821.2 1702.56  4847.7 1703.75
  4853.0 1702.39  4879.5 1703.74  4884.8 1702.30  4911.3 1703.93  4944.6 1703.71
  4980.2 1703.26  4985.4 1700.50  5012.0 1702.79  5014.2 1699.89  5017.0 1699.39
  5020.2 1699.89  5027.1 1701.87  5043.8 1703.06  5049.0 1702.08  5099.9 1702.75
  5144.4 1701.84  5170.9 1702.91  5176.2 1701.39  5202.7 1703.07  5208.0 1701.65
  5234.5 1703.90  5239.8 1702.47  5251.9 1703.33  5354.3 1705.28  5485.5 1707.08
#Mann=8,-1,0
  4408.2    0.05       0  4798.2     0.1       0  4944.6    0.08       0
  5014.2    0.07       0  5020.2    0.08       0  5099.9    0.05       0
  5251.9    0.08       0  5354.3     0.1       0
Bank Sta=5014.2,5020.2
Exp/Cntr=0.3,0.1

Type RM Length L Ch R = 1,1517,336,336,336
BEGIN DESCRIPTION:
Mapping XS 771d4642
END DESCRIPTION:
XS GIS Cut Line= 2
      2762555.31     10070293.64      2761763.49     10070025.15
#Sta/Elev= 30
  4569.9 1700.20  4589.1 1699.14  4683.3 1699.25  4743.6 1697.78  4835.1 1696.64
  4949.0 1696.29  4967.8 1694.66  4978.4 1692.50  4986.8 1689.51  4992.1 1689.45
  4996.5 1687.24  4999.2 1686.74  5002.5 1687.24  5010.1 1688.52  5018.2 1692.72
  5023.5 1691.89  5031.2 1693.35  5049.7 1694.50  5054.9 1693.80  5062.9 1695.09
  5073.4 1695.71  5126.2 1695.96  5168.4 1697.21  5180.6 1698.87  5189.6 1697.58
  5227.2 1697.82  5359.7 1702.38  5363.7 1702.97  5389.9 1702.32  5406.0 1702.87
#Mann=7,-1,0
  4569.9     0.1       0  4743.6    0.12       0  4949.0     0.1       0
  4996.5    0.07       0  5002.5     0.1       0  5227.2    0.16       0
  5359.7     0.1       0
Bank Sta=4996.5,5002.5
Exp/Cntr=0.3,0.1

Type RM Length L Ch R = 1,1181,299,299,299
BEGIN DESCRIPTION:
UNT 0068 IN HEWA 3.0
END DESCRIPTION:
XS GIS Cut Line= 2
      2762593.70     10070135.40      2762122.51     10069723.11
#Sta/Elev= 30
  4646.4 1697.26  4658.3 1696.71  4679.9 1696.66  4693.4 1695.43  4707.6 1695.52
  4736.1 1694.66  4776.6 1694.31  4786.2 1694.47  4813.9 1693.63  4864.2 1693.21
  4899.3 1692.34  4918.4 1690.03  4934.5 1689.36  4942.1 1689.80  4948.7 1689.46
  4956.3 1689.98  4970.5 1690.13  4984.8 1688.96  4995.8 1684.92  4998.6 1684.42
  5001.8 1684.92  5005.6 1684.97  5019.9 1687.39  5026.5 1688.98  5040.8 1690.69
  5140.4 1693.05  5193.4 1695.38  5224.9 1697.57  5253.4 1698.39  5272.5 1699.67
#Mann=6,-1,0
  4646.4    0.05       0  4776.6    0.16       0  4918.4     0.1       0
  4995.8    0.07       0  5001.8     0.1       0  5193.4    0.16       0
Bank Sta=4995.8,5001.8
Exp/Cntr=0.3,0.1

Type RM Length L Ch R = 1,882,471,471,471
BEGIN DESCRIPTION:
UNT 0068 IN HEWA 2.0
END DESCRIPTION:
XS GIS Cut Line= 2
      2762916.66     10070048.64      2762292.54     10069462.66
#Sta/Elev= 30
  4499.1 1697.37  4522.7 1697.63  4649.7 1695.32  4671.2 1695.32  4727.8 1693.98
  4748.9 1692.86  4756.2 1693.15  4763.0 1692.40  4770.9 1692.27  4876.3 1688.53
  4918.8 1688.58  4925.7 1688.07  4933.0 1688.38  4939.8 1687.58  4947.1 1687.87
  4968.2 1687.45  4975.5 1687.10  4982.3 1685.88  5000.8 1683.94  5003.5 1683.44
  5006.8 1683.94  5024.8 1687.98  5039.0 1688.66  5060.0 1688.82  5074.2 1689.46
  5145.0 1692.70  5180.6 1695.31  5258.3 1698.68  5300.8 1699.88  5355.2 1700.47
#Mann=4,-1,0
  4499.1    0.05       0  4770.9    0.16       0  5000.8    0.07       0
  5006.8    0.16       0
Bank Sta=5000.8,5006.8
Exp/Cntr=0.3,0.1

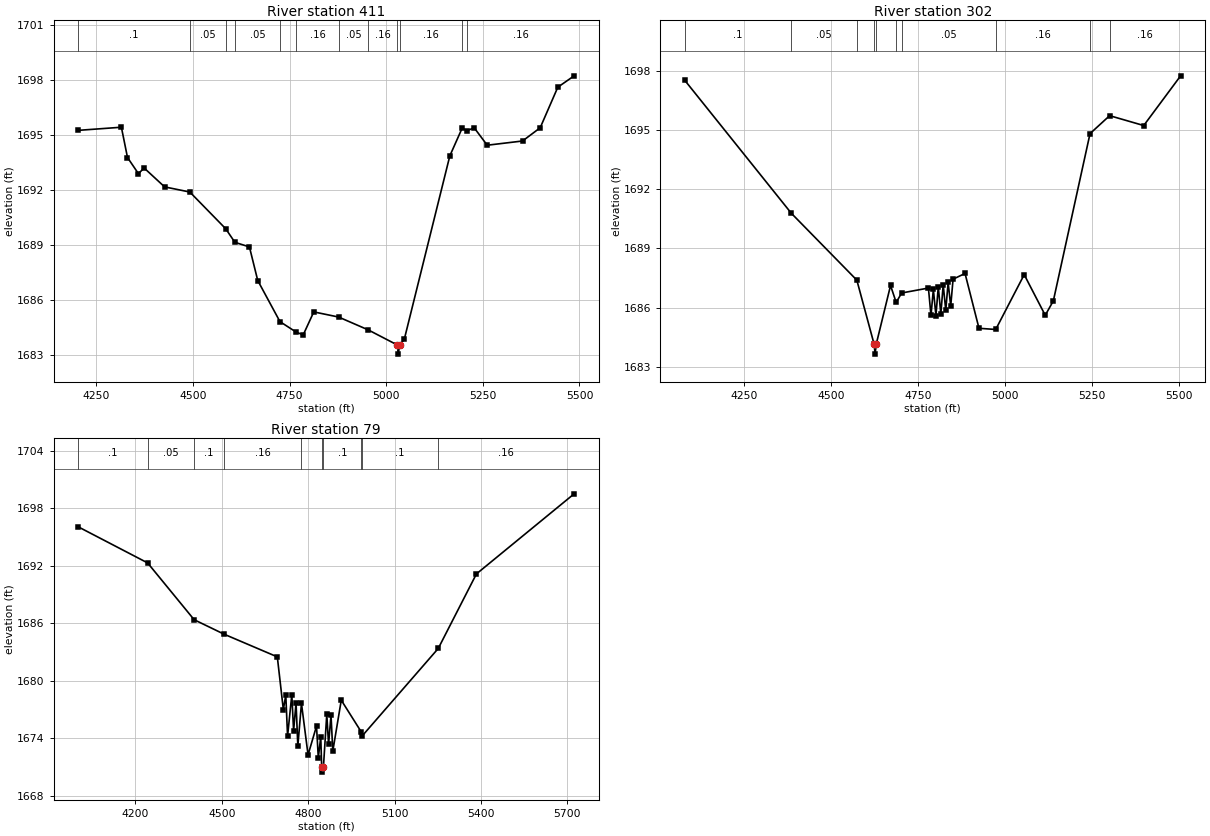
Type RM Length L Ch R = 1,411,109,109,109
BEGIN DESCRIPTION:
Mapping XS 05475a16
END DESCRIPTION:
XS GIS Cut Line= 4
      2763197.51     10070028.29      2762780.84     10069309.54
      2762697.51     10069319.96      2762364.18     10069476.20
#Sta/Elev= 30
  4203.4 1695.26  4314.8 1695.43  4330.6 1693.78  4358.9 1692.90  4373.6 1693.21
  4426.6 1692.18  4491.9 1691.90  4584.7 1689.90  4608.5 1689.16  4646.1 1688.91
  4667.6 1687.08  4725.1 1684.84  4767.7 1684.26  4785.3 1684.12  4812.6 1685.37
  4876.9 1685.09  4953.5 1684.39  5028.6 1683.57  5031.3 1683.07  5034.6 1683.57
  5046.7 1683.87  5164.6 1693.87  5196.5 1695.38  5209.0 1695.24  5227.6 1695.40
  5261.4 1694.45  5352.7 1694.68  5398.4 1695.40  5444.0 1697.61  5486.3 1698.23
#Mann=12,-1,0
  4203.4     0.1       0  4491.9    0.05       0  4584.7     0.1       0
  4608.5    0.05       0  4725.1     0.1       0  4767.7    0.16       0
  4876.9    0.05       0  4953.5    0.16       0  5028.6    0.07       0
  5034.6    0.16       0  5196.5     0.1       0  5209.0    0.16       0
Bank Sta=5028.6,5034.6
Exp/Cntr=0.3,0.1

Type RM Length L Ch R = 1,302,223,223,223
BEGIN DESCRIPTION:
Mapping XS 75dccca7
END DESCRIPTION:
XS GIS Cut Line= 5
      2763369.38     10069944.96      2763124.59     10069387.66
      2762983.97     10069257.46      2762796.47     10069252.25
      2762381.66     10069392.25
#Sta/Elev= 30
  4080.2 1697.52  4386.6 1690.78  4574.9 1687.39  4624.6 1684.14  4627.4 1683.64
  4630.6 1684.14  4671.8 1687.12  4688.0 1686.26  4703.7 1686.74  4780.7 1686.99
  4788.1 1685.60  4794.9 1686.92  4802.3 1685.59  4809.1 1687.06  4816.4 1685.67
  4823.2 1687.16  4830.6 1685.86  4837.4 1687.28  4844.8 1686.07  4851.6 1687.44
  4886.0 1687.73  4926.1 1684.95  4974.2 1684.89  5056.1 1687.67  5116.6 1685.61
  5139.9 1686.34  5245.4 1694.82  5301.8 1695.73  5399.8 1695.23  5505.9 1697.75
#Mann=10,-1,0
  4080.2     0.1       0  4386.6    0.05       0  4574.9     0.1       0
  4624.6    0.07       0  4630.6     0.1       0  4688.0    0.16       0
  4703.7    0.05       0  4974.2    0.16       0  5245.4     0.1       0
  5301.8    0.16       0
Bank Sta=4624.6,4630.6
Exp/Cntr=0.3,0.1

Type RM Length L Ch R = 1,79,0,0,0
BEGIN DESCRIPTION:
UNT 0068 IN HEWA 1.0
END DESCRIPTION:
XS GIS Cut Line= 5
      2763395.43     10069856.43      2763129.80     10069241.83
      2762885.01     10069064.75      2762806.88     10069054.33
      2762213.28     10069366.76
#Sta/Elev= 30
  4002.2 1696.07  4242.7 1692.31  4404.2 1686.38  4508.8 1684.86  4693.0 1682.50
  4713.9 1677.00  4722.4 1678.51  4728.6 1674.23  4743.3 1678.55  4749.5 1674.79
  4758.0 1677.70  4764.2 1673.19  4776.8 1677.64  4799.7 1672.27  4829.1 1675.28
  4835.3 1671.96  4843.8 1674.16  4847.0 1670.97  4849.8 1670.47  4853.0 1670.97
  4864.7 1676.52  4870.9 1673.36  4879.4 1676.43  4885.6 1672.66  4915.0 1677.98
  4984.8 1674.65  4986.5 1674.21  5251.7 1683.38  5384.2 1691.16  5723.5 1699.52
#Mann=10,-1,0
  4002.2     0.1       0  4242.7    0.05       0  4404.2     0.1       0
  4508.8    0.16       0  4776.8     0.1       0  4847.0    0.07       0
  4853.0     0.1       0  4984.8    0.16       0  4986.5     0.1       0
  5251.7    0.16       0
Bank Sta=4847,4853
Exp/Cntr=0.3,0.1

Chan Stop Cuts=-1