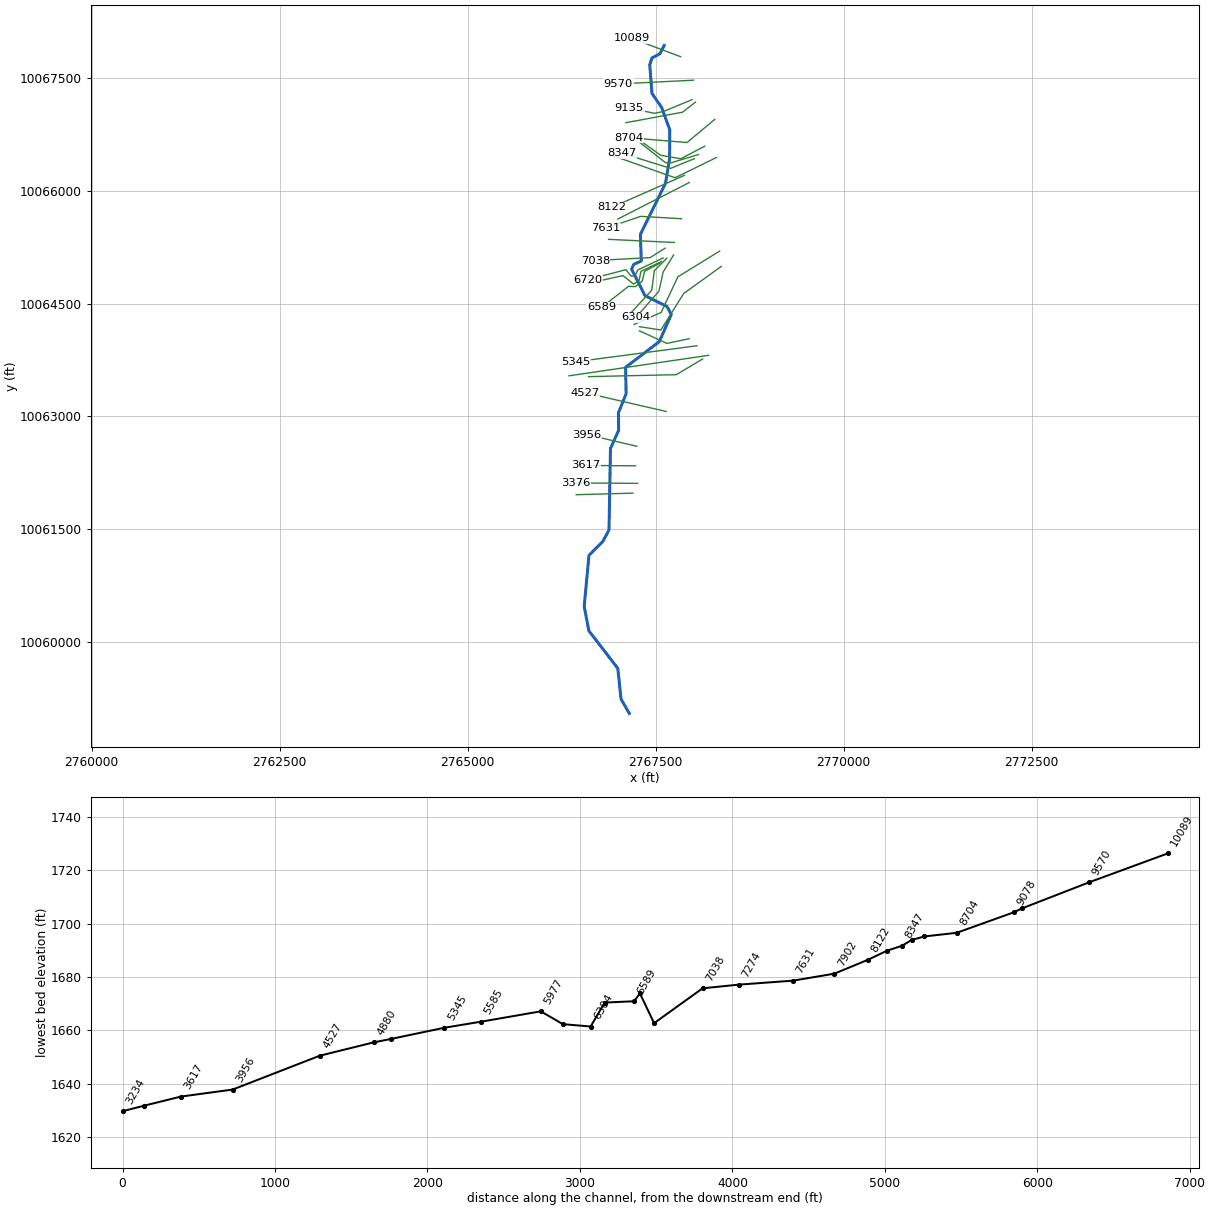
--- UNT 0069 IN HEWA.prj (project) ---

Proj Title=UNT 0069 IN HEWA Base Level Engineering
Current Plan=p01
Default Exp/Contr=0.3,0.1
English Units
Geom File=g01
Flow File=f01
Plan File=p01
Y Axis Title=Elevation
X Axis Title(PF)=Main Channel Distance
X Axis Title(XS)=Station
BEGIN DESCRIPTION:
UNT 0069 IN HEWA
END DESCRIPTION:
DSS Export Rating Curves= 0
DSS Export Rating Curve Sorted= 0
DSS Export Volume Flow Curves= 0
DXF OffsetX= 0
DXF OffsetY= 0
DXF ScaleX= 1
DXF ScaleY= 10

--- UNT 0069 IN HEWA.p01 (plan) ---

Plan Title=Multiple Run
Short Identifier=Multiple
Geom File=g01
Flow File=f01
Subcritical Flow
K Sum by GR= 0
Std Step Tol= 0.01
Critical Tol= 0.01
Num of Std Step Trials= 20
Max Error Tol= 0.3
Flow Tol Ratio= 0.001
Split Flow NTrial= 30
Split Flow Tol= 0.02
Split Flow Ratio= 0.02
Log Output Level= 0
Friction Slope Method= 1
Unsteady Friction Slope Method= 2
Unsteady Bridges Friction Slope Method= 1
Parabolic Critical Depth
Global Vel Dist=  1 , 1 , 1
Global Log Level= 0
CheckData=True
Encroach Param= -1, 0, 0, 0
BEGIN DESCRIPTION:
Multiple Run
END DESCRIPTION:

--- UNT 0069 IN HEWA.f01 (steady flow) ---

Flow Title=Multiple
Program Version=4.10
Number of Profiles= 7
Profile Names=10-year,25-year,50-year,1pct_min,100-year,1pct_plu,500-year
River Rch & RM=UNT 0069 IN HEWA,Reach-1         ,10089
     242     326     394     352     476     644     693
River Rch & RM=UNT 0069 IN HEWA,Reach-1         ,8493
     743    1072    1357    1258    1702    2301    2687
River Rch & RM=UNT 0069 IN HEWA,Reach-1         ,8122
     743    1072    1357    1258    1702    2301    2687
River Rch & RM=UNT 0069 IN HEWA,Reach-1         ,1133
    1169    1731    2230    2101    2841    3842    4632
Boundary for River Rch & Prof#=UNT 0069 IN HEWA,Reach-1         , 1
Up Type= 0
Dn Type= 3
Dn Slope=0.0056
Boundary for River Rch & Prof#=UNT 0069 IN HEWA,Reach-1         , 2
Up Type= 0
Dn Type= 3
Dn Slope=0.0056
Boundary for River Rch & Prof#=UNT 0069 IN HEWA,Reach-1         , 3
Up Type= 0
Dn Type= 3
Dn Slope=0.0056
Boundary for River Rch & Prof#=UNT 0069 IN HEWA,Reach-1         , 4
Up Type= 0
Dn Type= 3
Dn Slope=0.0056
Boundary for River Rch & Prof#=UNT 0069 IN HEWA,Reach-1         , 5
Up Type= 0
Dn Type= 3
Dn Slope=0.0056
Boundary for River Rch & Prof#=UNT 0069 IN HEWA,Reach-1         , 6
Up Type= 0
Dn Type= 3
Dn Slope=0.0056
Boundary for River Rch & Prof#=UNT 0069 IN HEWA,Reach-1         , 7
Up Type= 0
Dn Type= 3
Dn Slope=0.0056
DSS Import GetInterval= 0
DSS Import GetPeak= 0
DSS Import FillOption= 0

--- UNT 0069 IN HEWA.g01 (geometry) ---

Geom Title=Existing Conditions
Program Version=4.10

River Reach=UNT 0069 IN HEWA,Reach-1
Reach XY= 30
      2767614.16     10067937.99      2767556.65     10067827.21
      2767449.88     10067770.78       2767420.8     10067680.51
      2767450.32     10067299.89      2767581.12     10067107.36
      2767687.19     10066813.74      2767684.46     10066423.74
      2767630.32      10066101.6      2767296.91     10065423.51
      2767308.14     10065067.73      2767207.99     10065021.82
      2767179.68     10064958.11      2767357.11     10064606.96
      2767649.67     10064462.04      2767707.18     10064355.52
      2767547.61     10063993.64      2767099.35     10063651.43
      2767106.54     10063299.08      2767004.59     10063047.61
      2767006.72     10062811.38      2766898.61     10062570.69
      2766878.91     10061485.91      2766797.66     10061333.92
      2766612.47     10061148.08      2766549.25      10060468.9
       2766610.6     10060144.62      2766996.09     10059642.75
      2767038.81     10059235.76      2767148.47     10059043.73

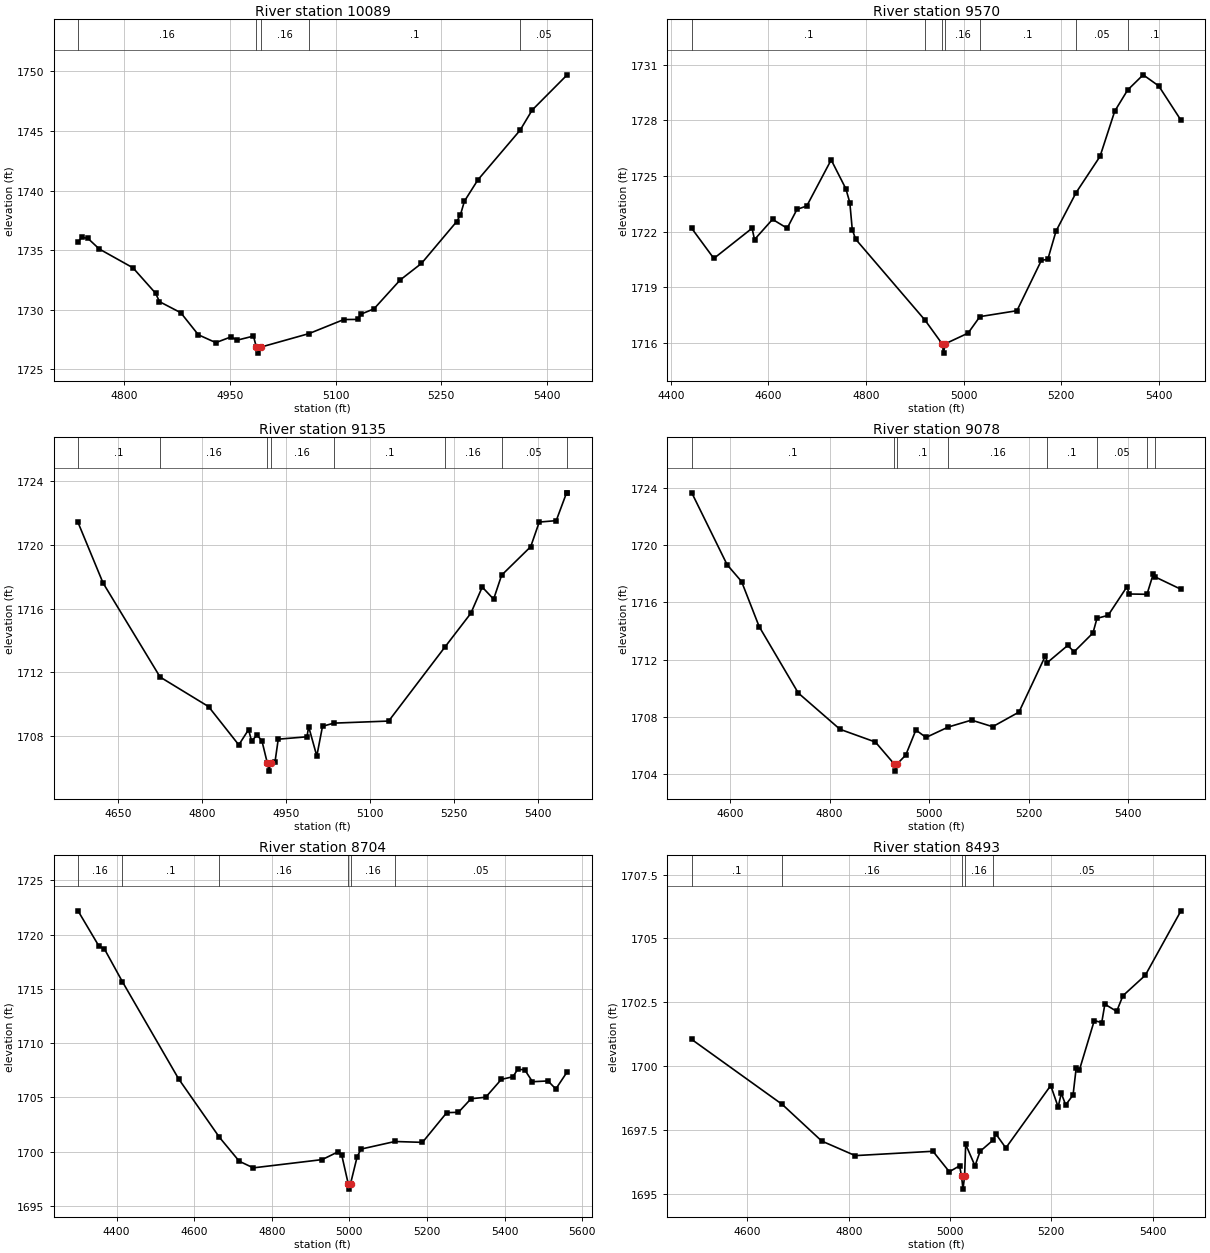
Type RM Length L Ch R = 1 ,10089   ,519,519,519
BEGIN DESCRIPTION:
UNT 0069 IN HEWA 21.0
END DESCRIPTION:
XS GIS Cut Line= 2
      2767831.47     10067788.01      2767181.97     10068032.22
#Sta/Elev= 30
  4734.7 1735.69    4740 1736.06  4748.6 1735.99  4764.9 1735.09  4812.7 1733.51
  4844.7 1731.38  4850.3 1730.67  4880.5 1729.74  4905.4 1727.89  4930.2 1727.23
  4951.6 1727.71  4960.5 1727.44  4983.6 1727.78  4987.7 1726.85  4990.5 1726.35
  4993.7 1726.85  5062.4 1727.99  5111.8 1729.17  5131.2 1729.18  5136.5 1729.63
  5154.6 1730.07  5191.7 1732.49  5221.9 1733.88  5271.7 1737.38    5277 1737.92
  5282.8  1739.1  5301.9 1740.89  5361.8 1745.06  5378.9 1746.75  5428.6 1749.71
#Mann= 5 ,-1 , 0
  4734.7     .16       0  4987.7     .07       0  4993.7     .16       0
  5062.4      .1       0  5361.8     .05       0
Bank Sta=4987.7,4993.7
XS Rating Curve= 0 ,0
Exp/Cntr=0.3,0.1

Type RM Length L Ch R = 1 ,9570    ,435,435,435
BEGIN DESCRIPTION:
UNT 0069 IN HEWA 20.0
END DESCRIPTION:
XS GIS Cut Line= 2
      2768003.66     10067475.06      2767003.01     10067425.02
#Sta/Elev= 30
  4443.1 1722.17  4488.3 1720.55  4566.6 1722.18  4571.6 1721.57  4608.5 1722.66
  4638.5 1722.18  4658.6  1723.2  4678.6 1723.38  4728.6 1725.87  4758.7 1724.31
  4766.8 1723.56  4771.8 1722.11  4778.7 1721.59  4920.8 1717.22  4955.9 1715.94
  4958.7 1715.44  4961.9 1715.94    5009 1716.52  5033.2 1717.41  5109.1 1717.73
  5159.2 1720.45  5172.3  1720.5  5189.2 1722.03  5230.2  1724.1  5279.3 1726.06
  5309.4  1728.5  5335.8 1729.64  5367.6 1730.46  5399.5 1729.86    5445 1728.01
#Mann= 7 ,-1 , 0
  4443.1      .1       0  4920.8     .16       0  4955.9     .07       0
  4961.9     .16       0  5033.2      .1       0  5230.2     .05       0
  5335.8      .1       0
Bank Sta=4955.9,4961.9
XS Rating Curve= 0 ,0
Exp/Cntr=0.3,0.1

Type RM Length L Ch R = 1 ,9135    ,57,57,57
BEGIN DESCRIPTION:
Mapping XS d83c8da7
END DESCRIPTION:
XS GIS Cut Line= 4
      2767984.14     10067216.24      2767607.83     10067059.98
      2767485.43     10067033.94      2767149.49     10067101.65
#Sta/Elev= 30
  4577.6 1721.42  4622.4 1717.61  4724.5 1711.69  4811.2 1709.83  4865.3 1707.42
  4882.8 1708.38  4888.2 1707.66  4897.8 1708.04  4906.6 1707.69  4916.4 1706.27
  4919.2 1705.77  4922.4 1706.27  4930.2 1706.37  4935.9 1707.78  4987.3 1707.93
  4990.3 1708.57  5004.9 1706.72  5015.1 1708.59  5035.5 1708.79  5133.5 1708.92
    5234 1713.57  5280.5  1715.7  5300.9 1717.35  5321.3 1716.59  5335.6  1718.1
  5387.6 1719.89  5402.9 1721.44  5433.3 1721.53  5451.8 1723.28  5452.9 1723.28
#Mann= 8 ,-1 , 0
  4577.6      .1       0  4724.5     .16       0  4916.4     .07       0
  4922.4     .16       0  5035.5      .1       0    5234     .16       0
  5335.6     .05       0  5451.8      .1       0
Bank Sta=4916.4,4922.4
XS Rating Curve= 0 ,0
Exp/Cntr=0.3,0.1

Type RM Length L Ch R = 1 ,9078    ,374,374,374
BEGIN DESCRIPTION:
UNT 0069 IN HEWA 19.0
END DESCRIPTION:
XS GIS Cut Line= 3
      2768029.05     10067182.74      2767855.43     10067048.19
      2767104.52     10066909.29
#Sta/Elev= 30
  4522.9 1723.65    4594 1718.63    4623 1717.46  4658.3 1714.32    4737 1709.68
  4820.8 1707.15    4892 1706.26  4929.7 1704.73  4932.4 1704.23  4935.7 1704.73
    4953 1705.35  4973.4  1707.1  4993.7 1706.58  5038.7 1707.31  5085.2 1707.79
  5127.7 1707.33  5180.6 1708.35  5233.5 1712.26  5237.8 1711.81  5278.5    1713
  5291.5 1712.56  5329.3 1713.87  5337.4 1714.89  5359.8  1715.1  5397.4 1717.08
  5402.5 1716.59  5437.9 1716.57  5450.3 1717.96  5453.8 1717.79  5506.2 1716.92
#Mann= 8 ,-1 , 0
  4522.9      .1       0  4929.7     .07       0  4935.7      .1       0
  5038.7     .16       0  5237.8      .1       0  5337.4     .05       0
  5437.9      .1       0  5453.8     .05       0
Bank Sta=4929.7,4935.7
XS Rating Curve= 0 ,0
Exp/Cntr=0.3,0.1

Type RM Length L Ch R = 1 ,8704    ,211,211,211
BEGIN DESCRIPTION:
UNT 0069 IN HEWA 18.0
END DESCRIPTION:
XS GIS Cut Line= 3
      2768285.15     10066952.73      2767916.19     10066644.54
      2767139.25     10066709.65
#Sta/Elev= 30
  4300.8  1722.2  4354.5 1718.96  4368.8 1718.69    4415 1715.68  4560.1 1706.71
  4665.3 1701.32  4716.3 1699.12  4752.5 1698.51  4929.8 1699.27  4969.9 1699.97
    4980 1699.74    4997 1697.05  4999.8 1696.55    5003 1697.05  5020.1 1699.54
  5030.1 1700.24  5117.4 1700.94  5188.3 1700.86  5250.9  1703.6    5281 1703.63
  5313.4 1704.88  5351.3 1705.02  5391.4 1706.66  5421.5 1706.91  5433.5 1707.58
  5451.6 1707.56  5471.7 1706.45  5511.8 1706.52  5531.9 1705.78  5561.2 1707.36
#Mann= 6 ,-1 , 0
  4300.8     .16       0    4415      .1       0  4665.3     .16       0
    4997     .07       0    5003     .16       0  5117.4     .05       0
Bank Sta=4997,5003
XS Rating Curve= 0 ,0
Exp/Cntr=0.3,0.1

Type RM Length L Ch R = 1 ,8493    ,84,84,84
BEGIN DESCRIPTION:
Mapping XS 6856adec
END DESCRIPTION:
XS GIS Cut Line= 4
      2768153.15     10066596.65      2767833.03     10066428.45
       2767566.1     10066475.11      2767295.26     10066669.03
#Sta/Elev= 30
  4490.2 1701.05  4668.9 1698.51  4746.7 1697.08  4812.8 1696.51  4966.3 1696.68
  4998.6 1695.88  5018.9 1696.11  5022.8  1695.7  5025.6  1695.2  5028.8  1695.7
  5030.9 1696.95  5049.3 1696.11  5059.5 1696.68  5085.8 1697.13  5090.4 1697.36
  5110.2 1696.81  5198.8 1699.25  5213.5 1698.41  5219.7 1698.95  5228.3 1698.49
  5242.9 1698.88  5249.1 1699.94  5255.3 1699.85  5284.8 1701.79  5299.5 1701.71
  5305.7 1702.43    5329 1702.15  5341.3 1702.76  5385.5 1703.56  5455.9 1706.08
#Mann= 5 ,-1 , 0
  4490.2      .1       0  4668.9     .16       0  5022.8     .07       0
  5028.8     .16       0  5085.8     .05       0
Bank Sta=5022.8,5028.8
XS Rating Curve= 0 ,0
Exp/Cntr=0.3,0.1

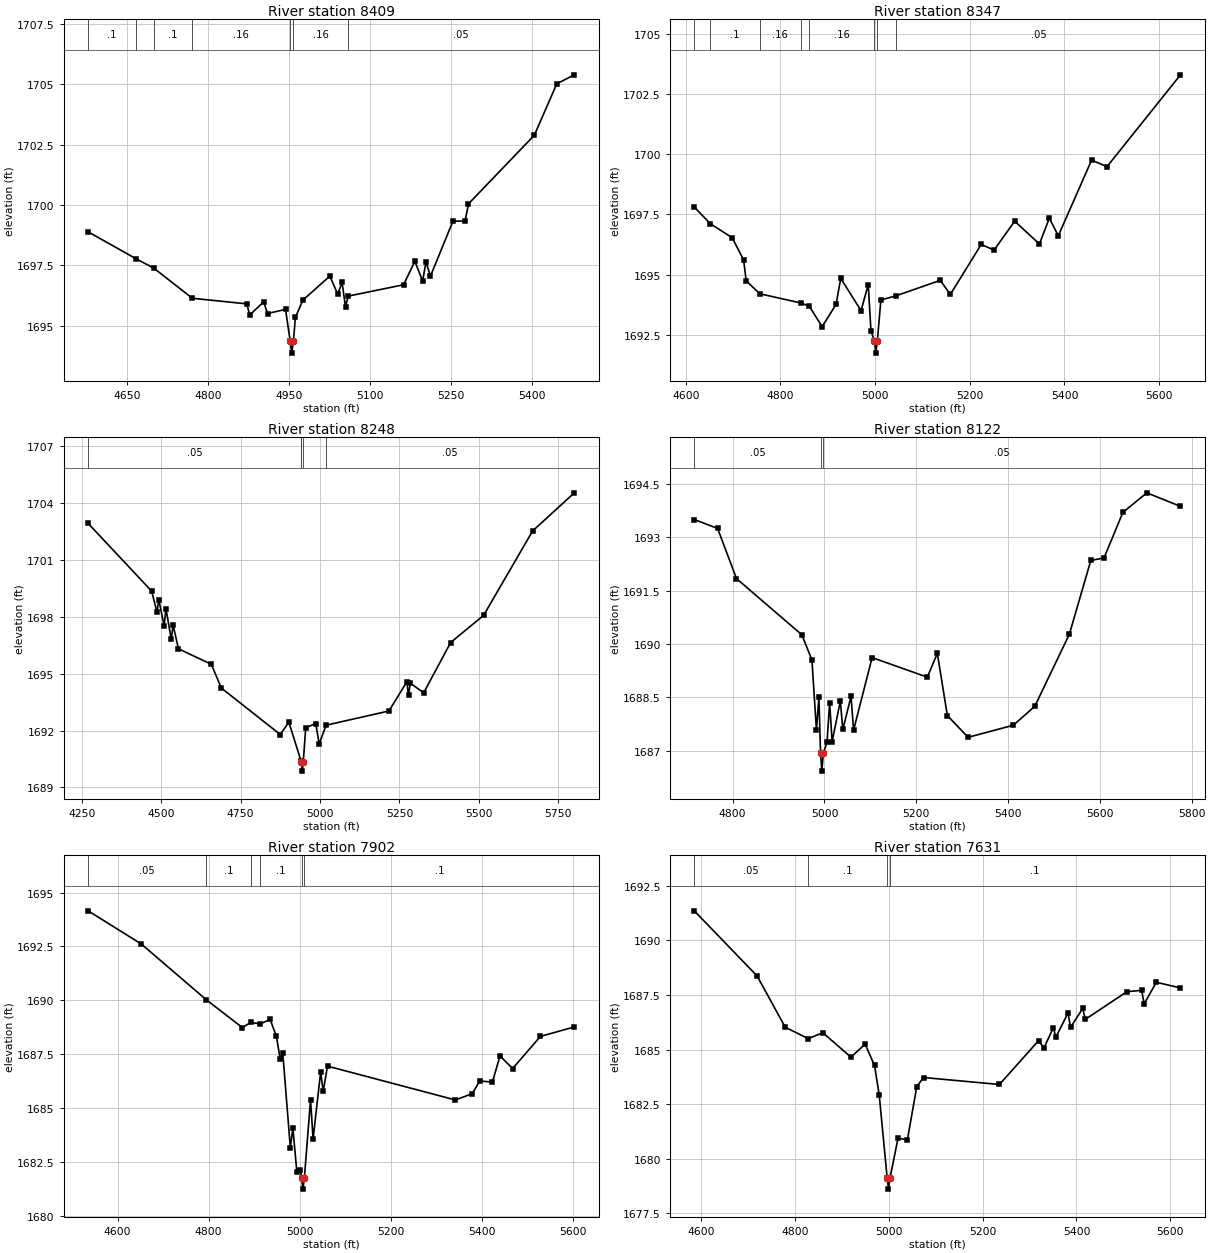
Type RM Length L Ch R = 1 ,8409    ,62,62,62
BEGIN DESCRIPTION:
Mapping XS 78412ff2
END DESCRIPTION:
XS GIS Cut Line= 4
      2768069.61     10066484.88      2767700.65     10066374.19
      2767632.29     10066375.28      2767282.09     10066651.98
#Sta/Elev= 30
  4578.2 1698.89  4667.5 1697.77  4699.6 1697.39  4771.2 1696.14  4871.7 1695.91
  4877.5 1695.45    4903 1695.99  4910.5 1695.51  4943.6 1695.68  4952.2 1694.37
    4955 1693.87  4958.2 1694.37  4961.9 1695.35  4975.6 1696.06  5025.6 1697.06
  5040.2 1696.31  5048.2  1696.8  5054.6 1695.78  5059.6 1696.23  5162.1  1696.7
  5182.9 1697.67  5197.3 1696.86  5203.7 1697.65  5211.7 1697.05  5253.4 1699.33
  5275.9 1699.34  5282.2 1700.05  5404.1 1702.89  5445.7 1705.02  5478.1 1705.39
#Mann= 7 ,-1 , 0
  4578.2      .1       0  4667.5     .16       0  4699.6      .1       0
  4771.2     .16       0  4952.2     .07       0  4958.2     .16       0
  5059.6     .05       0
Bank Sta=4952.2,4958.2
XS Rating Curve= 0 ,0
Exp/Cntr=0.3,0.1

Type RM Length L Ch R = 1 ,8347    ,99,99,99
BEGIN DESCRIPTION:
Mapping XS 1d62b692
END DESCRIPTION:
XS GIS Cut Line= 3
      2768015.12     10066430.07      2767698.75     10066301.17
      2767043.85     10066504.29
#Sta/Elev= 30
  4617.8 1697.81  4651.5 1697.12    4698 1696.53  4722.1 1695.61  4727.5 1694.74
  4756.2  1694.2  4842.4 1693.82  4860.9 1693.68    4888 1692.83  4917.4 1693.76
  4927.3 1694.84  4970.2  1693.5  4985.4 1694.58  4991.1 1692.67  4998.6 1692.23
  5001.3 1691.73  5004.6 1692.23  5012.1 1693.94  5044.8 1694.12  5137.7 1694.76
  5158.8 1694.17    5224 1696.25  5251.3 1696.02  5294.8 1697.22  5347.1 1696.27
    5368 1697.35  5386.9 1696.61  5457.3 1699.76  5489.9 1699.49  5645.1 1703.31
#Mann= 8 ,-1 , 0
  4617.8     .05       0  4651.5      .1       0  4756.2     .16       0
  4842.4      .1       0  4860.9     .16       0  4998.6     .07       0
  5004.6     .16       0  5044.8     .05       0
Bank Sta=4998.6,5004.6
XS Rating Curve= 0 ,0
Exp/Cntr=0.3,0.1

Type RM Length L Ch R = 1 ,8248    ,126,126,126
BEGIN DESCRIPTION:
UNT 0069 IN HEWA 17.0
END DESCRIPTION:
XS GIS Cut Line= 3
       2768306.8     10066444.88      2767757.77     10066175.79
      2766891.56      10066483.3
#Sta/Elev= 30
  4269.8 1702.92  4469.8 1699.35  4486.7 1698.24  4492.3  1698.9  4509.2 1697.51
  4514.8 1698.43  4531.7  1696.8  4537.2 1697.57  4554.2 1696.31  4657.7 1695.49
  4689.2 1694.24  4874.7 1691.79  4901.7 1692.44  4940.6 1690.37  4941.2 1690.36
  4943.9 1689.86  4947.2 1690.36  4954.9 1692.15  4986.6 1692.37  4997.2 1691.29
  5018.9 1692.28  5216.8 1693.03  5273.1 1694.57  5278.5 1693.85  5283.8  1694.5
  5326.2 1693.99  5411.1 1696.64  5514.8 1698.07  5669.1 1702.52  5800.4 1704.53
#Mann= 5 ,-1 , 0
  4269.8     .05       0  4940.6     .16       0  4941.2     .07       0
  4947.2     .16       0  5018.9     .05       0
Bank Sta=4941.2,4947.2
XS Rating Curve= 0 ,0
Exp/Cntr=0.3,0.1

Type RM Length L Ch R = 1 ,8122    ,220,220,220
BEGIN DESCRIPTION:
UNT 0069 IN HEWA 16.0
END DESCRIPTION:
XS GIS Cut Line= 2
        2767883.     10066207.96      2766913.79     10065780.23
#Sta/Elev= 30
  4716.3  1693.5  4767.2 1693.25  4808.3 1691.84  4950.8 1690.26  4972.7 1689.55
  4982.5 1687.59  4987.9  1688.5  4991.5 1686.93  4994.3 1686.43  4997.5 1686.93
  5005.5 1687.24  5011.3 1688.35  5016.7 1687.26  5034.6  1688.4    5040  1687.6
  5057.9 1688.53  5063.4 1687.58  5103.8 1689.62  5224.1 1689.07  5245.9 1689.74
  5267.8 1687.99  5312.9 1687.38  5411.6 1687.72  5458.2 1688.25  5533.7 1690.28
  5580.3 1692.35  5609.1 1692.42  5650.2  1693.7  5702.3 1694.25  5775.7 1693.87
#Mann= 3 ,-1 , 0
  4716.3     .05       0  4991.5     .04       0  4997.5     .05       0
Bank Sta=4991.5,4997.5
XS Rating Curve= 0 ,0
Exp/Cntr=0.3,0.1

Type RM Length L Ch R = 1 ,7902    ,271,271,271
BEGIN DESCRIPTION:
Mapping XS 8582d0fa
END DESCRIPTION:
XS GIS Cut Line= 2
      2767946.76     10066112.43      2766995.66      10065625.5
#Sta/Elev= 30
  4535.1 1694.15    4652 1692.61  4794.9 1690.02  4874.1 1688.73  4892.6 1688.97
  4913.7  1688.9  4935.1 1689.11  4948.9 1688.32  4957.3 1687.26  4962.9 1687.55
  4979.5 1683.15  4985.1 1684.06  4993.8 1682.04  5001.7 1682.13  5004.3 1681.73
  5007.1 1681.23  5010.3 1681.73  5023.9 1685.38  5029.5 1683.56  5046.1 1686.66
  5051.7 1685.77  5061.2 1686.94  5342.1 1685.37  5379.2 1685.66  5395.8 1686.25
  5423.6  1686.2  5440.2 1687.41  5468.1 1686.83  5529.1 1688.32  5603.6 1688.76
#Mann= 6 ,-1 , 0
  4535.1     .05       0  4794.9      .1       0  4892.6     .05       0
  4913.7      .1       0  5004.3     .07       0  5010.3      .1       0
Bank Sta=5004.3,5010.3
XS Rating Curve= 0 ,0
Exp/Cntr=0.3,0.1

Type RM Length L Ch R = 1 ,7631    ,357,357,357
BEGIN DESCRIPTION:
Mapping XS ec3cbb5d
END DESCRIPTION:
XS GIS Cut Line= 3
       2767842.1     10065630.07      2767300.58     10065661.92
      2766832.71     10065502.94
#Sta/Elev= 30
  4585.2 1691.35  4719.1 1688.37  4779.2 1686.02  4828.3  1685.5  4859.3 1685.77
  4919.4 1684.65  4949.5 1685.25  4969.5 1684.27  4979.5 1682.93  4996.5 1679.11
  4999.3 1678.61  5002.5 1679.11  5019.6 1680.94  5039.6 1680.87  5059.6  1683.3
    5074 1683.72  5235.8  1683.4  5319.4 1685.41  5330.6 1685.07  5350.8    1686
    5356 1685.56  5382.1 1686.68  5387.4 1686.01  5413.5 1686.89  5418.8 1686.38
  5507.7 1687.65  5539.1 1687.71  5544.3 1687.09  5570.4 1688.08  5621.8 1687.82
#Mann= 4 ,-1 , 0
  4585.2     .05       0  4828.3      .1       0  4996.5     .07       0
  5002.5      .1       0
Bank Sta=4996.5,5002.5
XS Rating Curve= 0 ,0
Exp/Cntr=0.3,0.1

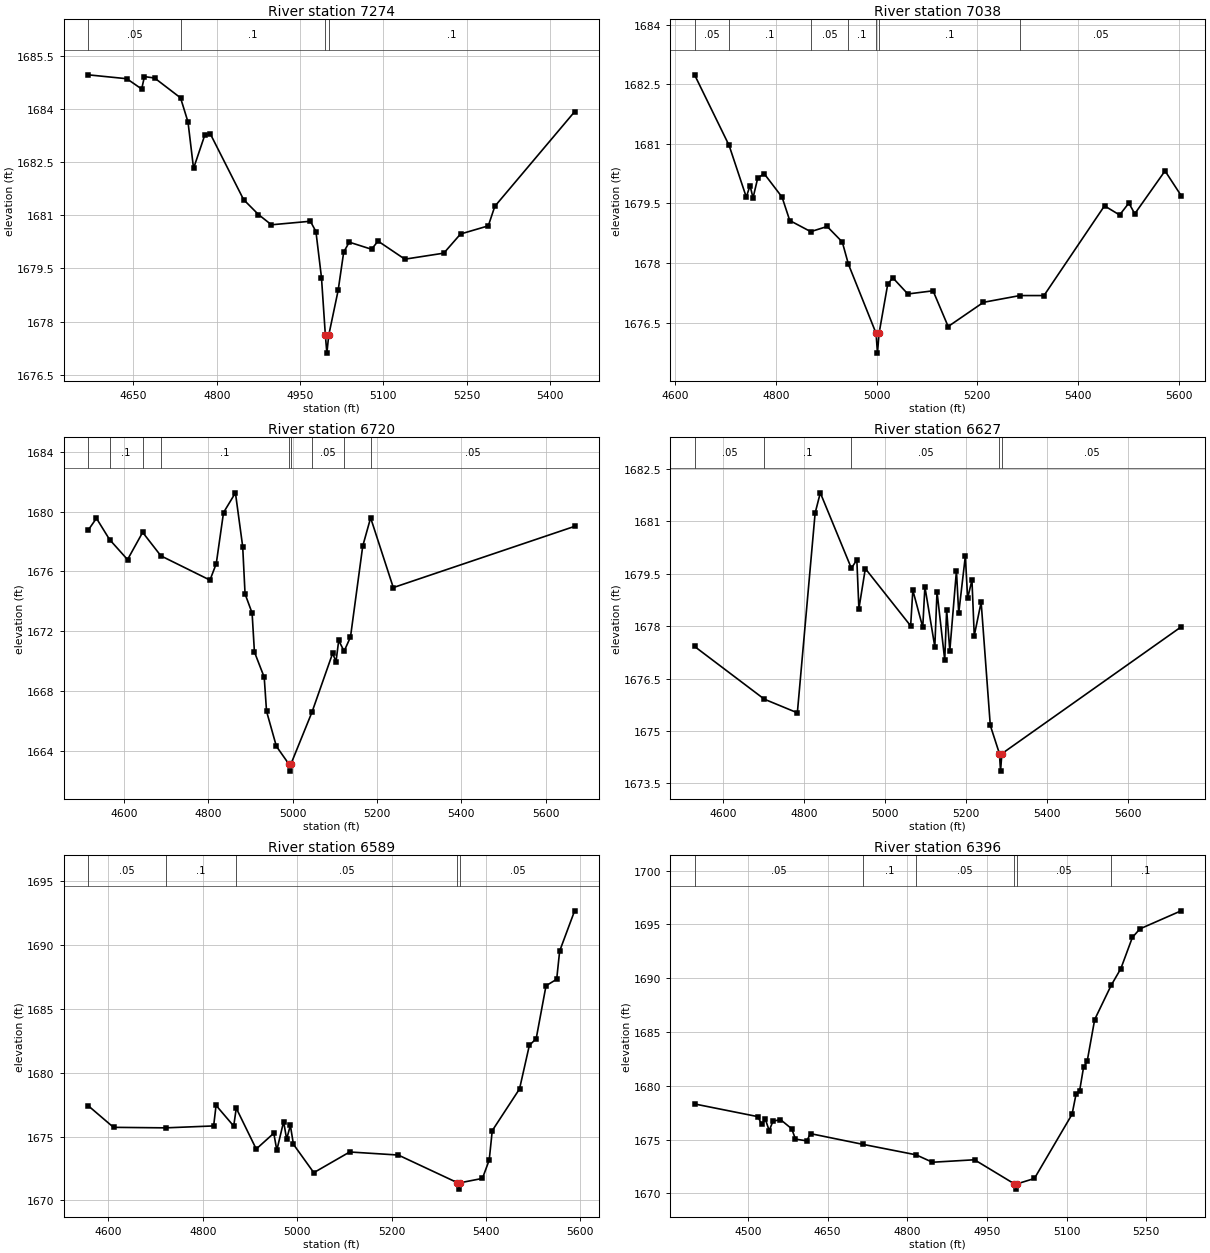
Type RM Length L Ch R = 1 ,7274    ,236,236,236
BEGIN DESCRIPTION:
UNT 0069 IN HEWA 15.0
END DESCRIPTION:
XS GIS Cut Line= 2
      2767748.06     10065314.07      2766873.26     10065355.72
#Sta/Elev= 30
  4568.4 1684.96  4638.1 1684.85  4664.8 1684.56  4669.8 1684.91  4688.1 1684.87
  4734.8 1684.31  4748.2 1683.63  4758.2 1682.32  4778.2 1683.25  4788.2  1683.3
  4848.3 1681.44    4875 1681.02  4898.4 1680.73  4968.5 1680.83  4978.5 1680.54
  4988.5 1679.24  4995.5 1677.61  4998.2 1677.11  5001.5 1677.61  5018.5 1678.88
  5028.5 1679.96  5038.5 1680.24  5078.6 1680.04  5090.3 1680.27  5138.6 1679.76
  5208.7 1679.93  5238.8 1680.47  5288.8  1680.7  5300.5 1681.25  5444.2 1683.92
#Mann= 4 ,-1 , 0
  4568.4     .05       0  4734.8      .1       0  4995.5     .07       0
  5001.5      .1       0
Bank Sta=4995.5,5001.5
XS Rating Curve= 0 ,0
Exp/Cntr=0.3,0.1

Type RM Length L Ch R = 1 ,7038    ,318,318,318
BEGIN DESCRIPTION:
Mapping XS b8a571e9
END DESCRIPTION:
XS GIS Cut Line= 3
      2767625.37     10065238.28      2767425.74     10065112.42
      2766696.57     10065073.36
#Sta/Elev= 30
  4638.5 1682.74  4707.1 1680.96  4741.2 1679.66  4748.6 1679.95  4754.6 1679.64
  4763.9 1680.14  4776.7 1680.25  4812.2 1679.66  4827.5 1679.07  4869.2 1678.79
  4901.8 1678.92  4931.8 1678.53    4944 1677.97  4998.9 1676.23  5001.7 1675.73
  5004.9 1676.23    5022 1677.46    5032 1677.63    5062 1677.22  5112.1  1677.3
  5142.1  1676.4  5212.2 1677.01  5284.5 1677.18  5332.4 1677.18  5452.6 1679.44
  5482.6 1679.21    5501 1679.51  5512.7 1679.24  5572.8 1680.32  5604.7  1679.7
#Mann= 7 ,-1 , 0
  4638.5     .05       0  4707.1      .1       0  4869.2     .05       0
    4944      .1       0  4998.9     .07       0  5004.9      .1       0
  5284.5     .05       0
Bank Sta=4998.9,5004.9
XS Rating Curve= 0 ,0
Exp/Cntr=0.3,0.1

Type RM Length L Ch R = 1 ,6720    ,93,93,93
BEGIN DESCRIPTION:
UNT 0069 IN HEWA 14.0
END DESCRIPTION:
XS GIS Cut Line= 6
      2767599.34     10065108.08      2767260.81     10064947.49
      2767226.09     10064869.37      2767174.01     10064865.03
      2767104.56     10064951.83      2766592.93     10064817.42
#Sta/Elev= 30
  4515.6 1678.75  4535.3 1679.55  4566.4 1678.13    4609 1676.79  4644.8 1678.61
    4688 1677.04  4804.3 1675.42  4819.2 1676.52  4836.4 1679.93  4864.6 1681.25
  4881.8 1677.66  4887.4  1674.5  4904.1 1673.22  4909.6 1670.62  4932.8 1668.93
  4938.3 1666.66  4961.6 1664.32  4990.5 1663.16  4993.2 1662.66  4996.5 1663.16
  5046.1 1666.61  5094.9 1670.53  5102.9 1669.97  5109.3 1671.39  5122.1 1670.67
  5137.2 1671.62  5166.2 1677.69  5184.9 1679.58  5238.6 1674.92  5668.2 1679.01
#Mann= 9 ,-1 , 0
  4515.6     .05       0  4566.4      .1       0  4644.8     .05       0
    4688      .1       0  4990.5     .07       0  4996.5      .1       0
  5046.1     .05       0  5122.1      .1       0  5184.9     .05       0
Bank Sta=4990.5,4996.5
XS Rating Curve= 0 ,0
Exp/Cntr=0.3,0.1

Type RM Length L Ch R = 1 ,6627    ,38,38,38
BEGIN DESCRIPTION:
Mapping XS e1c98145
END DESCRIPTION:
XS GIS Cut Line= 6
      2767577.63     10065060.33      2767304.21     10064930.13
      2767278.17     10064804.26      2767204.39     10064760.86
       2767065.5     10064873.71      2766583.73      10064765.2
#Sta/Elev= 30
    4529 1677.42  4701.3 1675.91  4782.8 1675.52  4826.7 1681.24  4839.5 1681.82
  4916.2 1679.66  4929.7  1679.9  4934.8  1678.5  4950.7 1679.65  5062.6 1678.01
    5068 1679.03  5092.5 1677.97  5097.8 1679.13  5122.3 1677.41  5127.7 1678.99
  5146.8 1677.03  5151.5 1678.47  5159.3  1677.3  5175.7 1679.59  5181.3 1678.37
  5197.7 1680.01  5203.3  1678.8    5214 1679.32  5219.7 1677.73  5236.7 1678.69
  5259.3 1675.16  5281.9 1674.35  5284.6 1673.85  5287.9 1674.35  5730.5 1677.98
#Mann= 5 ,-1 , 0
    4529     .05       0  4701.3      .1       0  4916.2     .05       0
  5281.9    .035       0  5287.9     .05       0
Bank Sta=5281.9,5287.9
XS Rating Curve= 0 ,0
Exp/Cntr=0.3,0.1

Type RM Length L Ch R = 1 ,6589    ,193,193,193
BEGIN DESCRIPTION:
Mapping XS 4b555a64
END DESCRIPTION:
XS GIS Cut Line= 6
      2767555.95     10065038.64      2767351.96     10064930.13
      2767321.57     10064799.92      2767230.43     10064726.14
      2767139.28     10064730.48      2766779.31     10064448.57
#Sta/Elev= 30
  4557.3 1677.42  4611.1 1675.72  4721.5 1675.68  4823.2 1675.83  4828.3 1677.44
  4865.7 1675.82  4871.1 1677.22  4913.4 1674.02  4950.6 1675.26    4957 1673.92
  4971.4 1676.17  4977.8  1674.8  4985.7 1675.87  4992.2 1674.39  5035.3 1672.17
  5111.4 1673.79  5214.3 1673.55  5339.7 1671.38  5342.5 1670.88  5345.7 1671.38
  5392.5 1671.72  5406.9 1673.16  5413.3 1675.46  5471.1 1678.73  5491.9 1682.14
  5506.4 1682.67  5527.2 1686.81  5549.8 1687.32  5556.1 1689.53  5587.8 1692.68
#Mann= 5 ,-1 , 0
  4557.3     .05       0  4721.5      .1       0  4871.1     .05       0
  5339.7    .035       0  5345.7     .05       0
Bank Sta=5339.7,5345.7
XS Rating Curve= 0 ,0
Exp/Cntr=0.3,0.1

Type RM Length L Ch R = 1 ,6396    ,92,92,92
BEGIN DESCRIPTION:
Mapping XS 64cb7f89
END DESCRIPTION:
XS GIS Cut Line= 4
       2767647.1     10065103.75      2767482.17     10064938.81
      2767447.44      10064678.4      2767163.56      10064368.7
#Sta/Elev= 30
  4399.6 1678.31  4518.9 1677.13  4525.9 1676.41    4533 1676.87  4540.1 1675.83
  4547.1  1676.7  4561.3 1676.86  4582.5    1676  4589.6 1675.04  4610.8 1674.88
  4617.9 1675.55  4716.9 1674.55  4816.7 1673.58  4847.4 1672.89  4926.7 1673.12
  5001.4 1670.89  5004.1 1670.39  5007.4 1670.89  5039.5 1671.38  5110.4 1677.35
  5117.8  1679.2  5124.6 1679.53    5132 1681.71  5138.8 1682.27    5153 1686.16
  5183.9 1689.33  5202.3  1690.9  5223.9 1693.79  5238.1 1694.59  5315.7 1696.27
#Mann= 6 ,-1 , 0
  4399.6     .05       0  4716.9      .1       0  4816.7     .05       0
  5001.4    .035       0  5007.4     .05       0  5183.9      .1       0
Bank Sta=5001.4,5007.4
XS Rating Curve= 0 ,0
Exp/Cntr=0.3,0.1

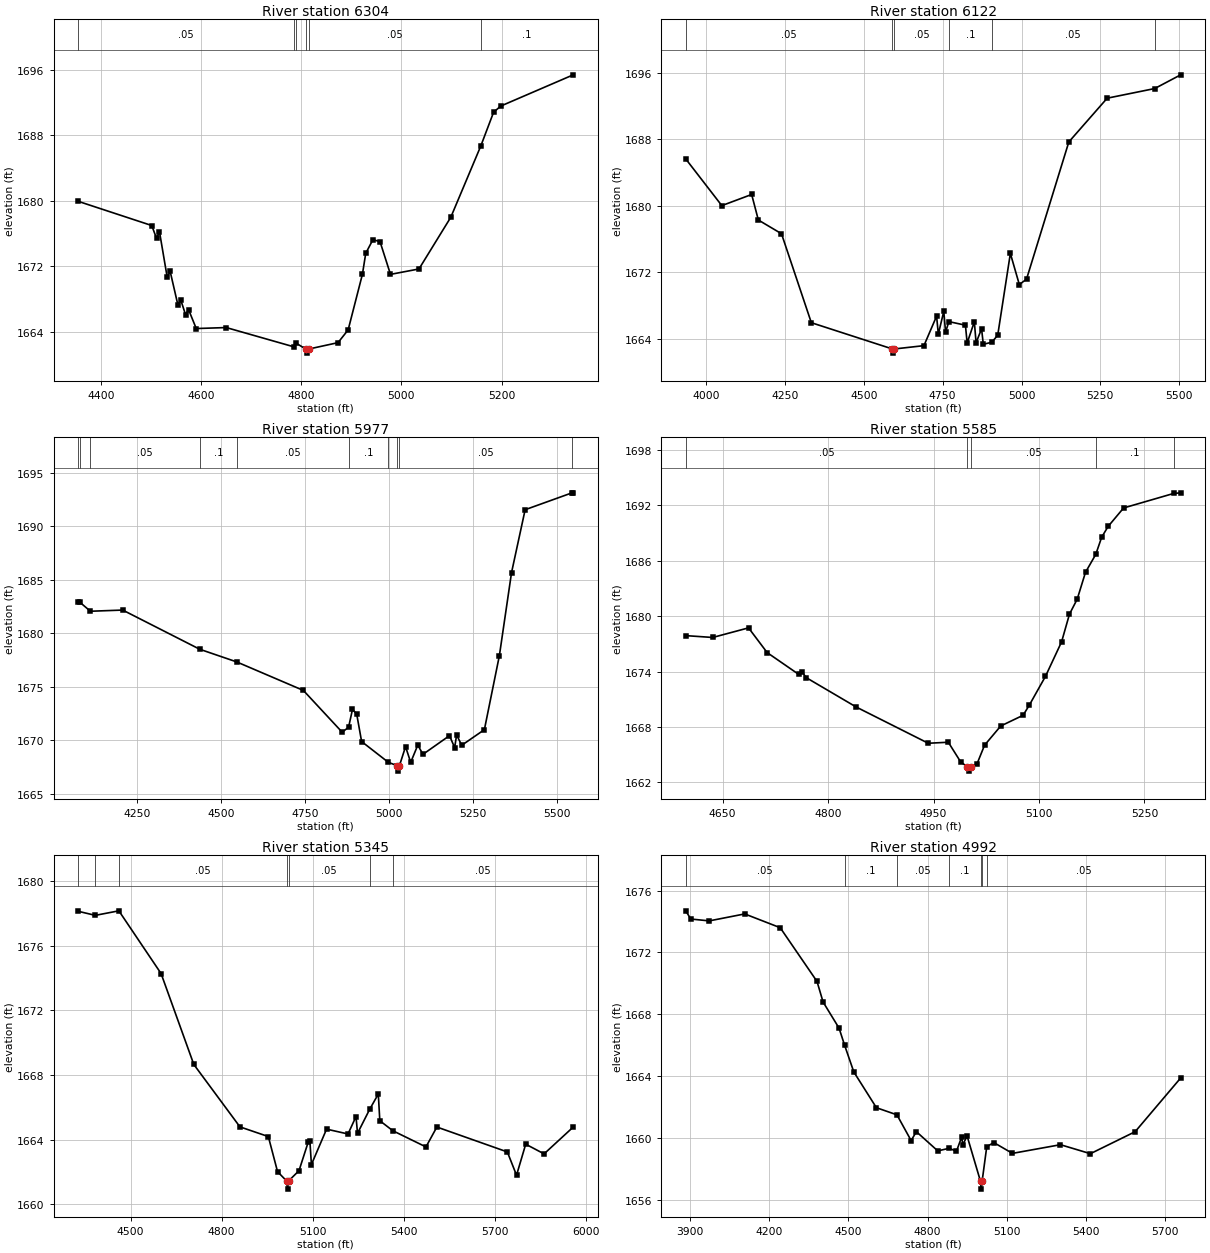
Type RM Length L Ch R = 1 ,6304    ,182,182,182
BEGIN DESCRIPTION:
Mapping XS 77c4a9b2
END DESCRIPTION:
XS GIS Cut Line= 4
      2767738.23     10065147.13      2767599.35     10064921.45
      2767542.93     10064665.38      2767239.36     10064318.44
#Sta/Elev= 30
  4354.9 1679.93  4501.6 1676.98  4511.1 1675.41    4517 1676.23  4532.4 1670.67
  4538.3 1671.39  4553.7 1667.31  4559.6 1667.87  4569.1  1666.1    4575 1666.73
  4590.4 1664.41  4650.3 1664.53  4784.7 1662.19  4789.9 1662.62  4809.1 1661.91
  4811.9 1661.41  4815.1 1661.91  4873.5 1662.69  4893.7 1664.25  4922.2 1671.04
  4928.8 1673.59  4943.1 1675.25  4957.3 1675.02  4978.2 1671.02  5035.1 1671.68
  5098.7    1678  5158.6  1686.7  5184.1 1690.81  5198.4 1691.56  5343.1 1695.37
#Mann= 6 ,-1 , 0
  4354.9     .05       0  4784.7      .1       0  4789.9     .05       0
  4809.1    .035       0  4815.1     .05       0  5158.6      .1       0
Bank Sta=4809.1,4815.1
XS Rating Curve= 0 ,0
Exp/Cntr=0.3,0.1

Type RM Length L Ch R = 1 ,6122    ,145,145,145
BEGIN DESCRIPTION:
UNT 0069 IN HEWA 13.0
END DESCRIPTION:
XS GIS Cut Line= 4
      2768350.23     10065199.24      2767794.67     10064856.35
      2767573.31     10064383.26      2767213.24     10064222.74
#Sta/Elev= 30
  3935.2 1685.65  4049.7 1680.03  4144.3 1681.37  4165.5  1678.3  4238.9 1676.65
  4333.5 1665.95  4590.7 1662.79  4593.4 1662.29  4596.7 1662.79  4690.6 1663.19
  4730.7 1666.74  4736.2 1664.57  4753.5 1667.32  4759.1 1664.81  4769.6 1666.08
  4822.1 1665.65  4827.6 1663.51  4850.4 1666.06  4855.9 1663.53  4873.3 1665.22
  4878.8 1663.35  4905.7  1663.6  4924.5 1664.44  4964.6 1674.28    4993 1670.54
  5015.8 1671.18    5150 1687.69  5271.6 1692.95  5422.3 1694.11  5504.6 1695.76
#Mann= 6 ,-1 , 0
  3935.2     .05       0  4590.7    .035       0  4596.7     .05       0
  4769.6      .1       0  4905.7     .05       0  5422.3      .1       0
Bank Sta=4590.7,4596.7
XS Rating Curve= 0 ,0
Exp/Cntr=0.3,0.1

Type RM Length L Ch R = 1 ,5977    ,392,392,392
BEGIN DESCRIPTION:
Mapping XS 6442f343
END DESCRIPTION:
XS GIS Cut Line= 4
      2768371.94     10064995.25      2767872.79     10064634.99
      2767568.97     10064148.88      2767286.81     10064192.29
#Sta/Elev= 30
  4074.1 1682.91  4078.5 1682.91  4110.2 1682.06  4206.4 1682.17  4436.1  1678.5
  4545.9 1677.32  4744.6 1674.65  4860.2 1670.74  4879.2 1671.21  4890.8 1672.87
  4903.4 1672.44    4918 1669.87  4997.4 1667.93  5024.6  1667.6  5027.4  1667.1
  5030.6  1667.6  5048.9 1669.39  5064.2 1667.92  5085.4 1669.54  5100.7 1668.67
  5179.8 1670.42  5195.1  1669.3    5201 1670.48  5216.3 1669.52  5283.7 1670.98
  5328.4 1677.91  5364.6 1685.68  5405.1 1691.56  5543.9 1693.13  5548.4 1693.14
#Mann= 10 ,-1 , 0
  4074.1     .05       0  4078.5      .1       0  4110.2     .05       0
  4436.1      .1       0  4545.9     .05       0  4879.2      .1       0
  4997.4     .05       0  5024.6    .035       0  5030.6     .05       0
  5543.9      .1       0
Bank Sta=5024.6,5030.6
XS Rating Curve= 0 ,0
Exp/Cntr=0.3,0.1

Type RM Length L Ch R = 1 ,5585    ,240,240,240
BEGIN DESCRIPTION:
UNT 0069 IN HEWA 11.0
END DESCRIPTION:
XS GIS Cut Line= 3
        2767946.     10064032.81      2767649.14     10063970.31
      2767284.59     10064136.97
#Sta/Elev= 30
  4597.4 1677.89  4635.8 1677.69  4686.8 1678.73  4713.3 1676.05    4758  1673.7
  4763.2 1673.95  4768.6 1673.35  4840.1 1670.15  4942.5 1666.23    4971 1666.34
  4988.6 1664.21  4997.5 1663.71  5000.2 1663.21  5003.5 1663.71  5011.5 1663.93
  5022.6 1666.02  5045.6  1668.1  5077.4 1669.26  5086.2 1670.35  5109.2 1673.47
  5132.2 1677.22  5143.4 1680.22  5154.4 1681.84  5166.2 1684.75  5180.8 1686.69
  5189.2 1688.55  5198.4 1689.72  5220.4 1691.72  5291.5 1693.29  5301.6 1693.36
#Mann= 5 ,-1 , 0
  4597.4     .05       0  4997.5     .04       0  5003.5     .05       0
  5180.8      .1       0  5291.5     .05       0
Bank Sta=4997.5,5003.5
XS Rating Curve= 0 ,0
Exp/Cntr=0.3,0.1

Type RM Length L Ch R = 1 ,5345    ,353,353,353
BEGIN DESCRIPTION:
Mapping XS f7b4b15e
END DESCRIPTION:
XS GIS Cut Line= 2
      2768048.75     10063938.88      2766433.34     10063725.01
#Sta/Elev= 30
  4328.1 1678.13  4384.1 1677.88  4461.7 1678.16  4600.7 1674.28  4708.4 1668.66
  4860.3  1664.8  4953.8  1664.2  4984.1 1662.03  5014.2 1661.45  5016.9 1660.95
  5020.2 1661.45  5054.7 1662.09  5084.9 1663.85  5090.6 1663.91  5095.6 1662.47
  5145.5 1664.66  5216.1 1664.36  5242.4 1665.44  5247.4  1664.4  5287.5 1665.89
  5315.8 1666.83  5320.8 1665.18  5363.7 1664.56  5472.7 1663.56  5508.6 1664.79
  5740.6 1663.25  5770.9 1661.81  5801.1 1663.73  5861.6 1663.13  5957.6 1664.79
#Mann= 7 ,-1 , 0
  4328.1     .05       0  4384.1      .1       0  4461.7     .05       0
  5014.2     .04       0  5020.2     .05       0  5287.5      .1       0
  5363.7     .05       0
Bank Sta=5014.2,5020.2
XS Rating Curve= 0 ,0
Exp/Cntr=0.3,0.1

Type RM Length L Ch R = 1 ,4992    ,112,112,112
BEGIN DESCRIPTION:
Mapping XS 24e20c38
END DESCRIPTION:
XS GIS Cut Line= 2
      2768203.38     10063811.46      2766347.84     10063538.58
#Sta/Elev= 30
  3883.4 1674.69  3902.8 1674.16  3972.6 1674.04    4107 1674.49  4241.4  1673.6
  4380.9 1670.13  4403.9  1668.8  4464.5 1667.11  4485.6    1666  4520.4 1664.28
    4606 1661.97  4683.8 1661.51  4737.4 1659.85  4757.6 1660.42  4838.5 1659.18
    4882 1659.35  4909.2 1659.15  4928.7 1660.06  4933.8 1659.59  4949.7 1660.14
  5000.5 1657.21  5003.3 1656.71  5006.5 1657.21  5024.1 1659.45  5050.7 1659.72
  5121.5 1659.02  5303.4 1659.58  5416.9    1659  5586.4 1660.42  5758.9 1663.89
#Mann= 7 ,-1 , 0
  3883.4     .05       0  4485.6      .1       0  4683.8     .05       0
    4882      .1       0  5000.5     .07       0  5006.5      .1       0
  5024.1     .05       0
Bank Sta=5000.5,5006.5
XS Rating Curve= 0 ,0
Exp/Cntr=0.3,0.1

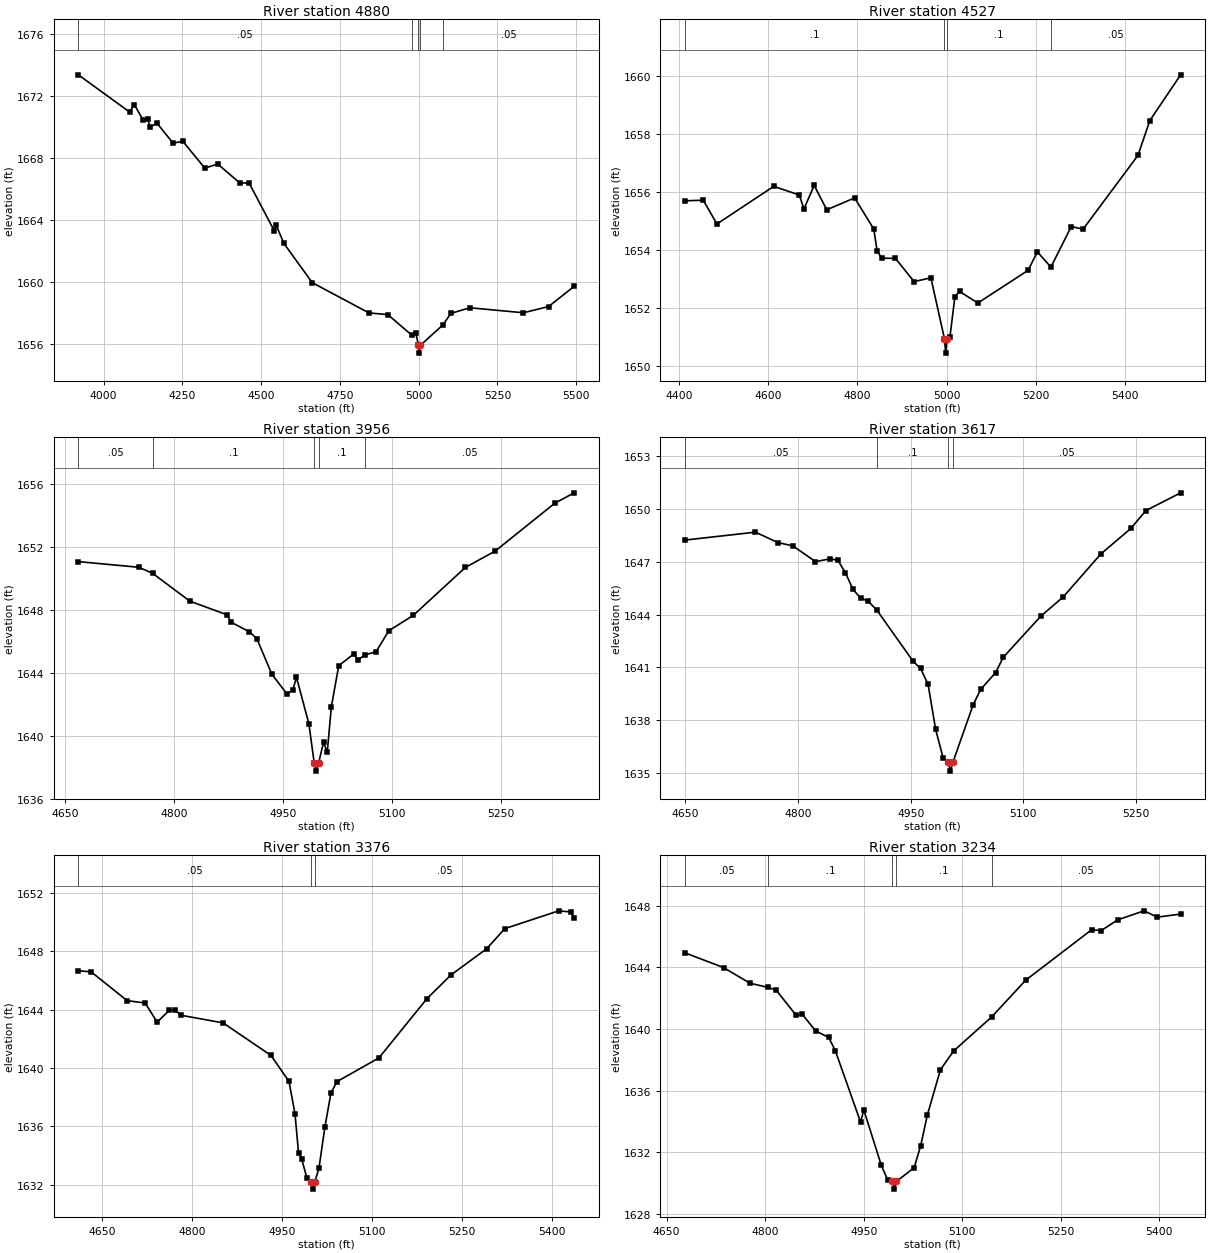
Type RM Length L Ch R = 1 ,4880    ,353,353,353
BEGIN DESCRIPTION:
UNT 0069 IN HEWA 10.0
END DESCRIPTION:
XS GIS Cut Line= 3
      2768123.06     10063761.96      2767774.14     10063553.65
       2766607.5     10063527.61
#Sta/Elev= 30
  3920.1 1673.36  4082.6 1670.97  4098.1 1671.44  4125.4 1670.45  4140.9 1670.53
  4146.8    1670    4170 1670.24  4220.7 1668.96  4251.6 1669.08  4321.5 1667.35
  4362.2 1667.62  4432.2  1666.4  4462.2 1666.39    4542 1663.31    4547 1663.72
  4572.2 1662.51  4662.2 1659.98  4842.3 1658.03  4902.3 1657.92  4978.5 1656.59
  4991.1 1656.74  4999.3 1655.94  5002.1 1655.44  5005.3 1655.94  5077.1 1657.26
  5102.3    1658  5162.4 1658.36  5332.4 1658.04  5412.4 1658.44  5493.4 1659.74
#Mann= 5 ,-1 , 0
  3920.1     .05       0  4978.5      .1       0  4999.3     .07       0
  5005.3      .1       0  5077.1     .05       0
Bank Sta=4999.3,5005.3
XS Rating Curve= 0 ,0
Exp/Cntr=0.3,0.1

Type RM Length L Ch R = 1 ,4527    ,571,571,571
BEGIN DESCRIPTION:
UNT 0069 IN HEWA 9.0
END DESCRIPTION:
XS GIS Cut Line= 2
      2767638.69     10063064.07      2766555.36     10063314.07
#Sta/Elev= 30
  4412.9  1655.7  4454.2 1655.72    4485  1654.9  4612.4  1656.2  4669.7  1655.9
    4680 1655.42    4703 1656.23  4731.3 1655.39  4793.7  1655.8  4836.5 1654.73
  4844.2 1653.97  4854.4 1653.72  4885.2 1653.71  4927.1 1652.91  4964.7 1653.04
  4995.1 1650.94  4997.9 1650.44  5001.1 1650.94  5007.5 1651.01  5018.6 1652.39
  5028.9 1652.57  5069.9 1652.17  5182.8  1653.3  5203.4 1653.94  5233.8 1653.41
  5279.5 1654.81    5306 1654.72  5429.1 1657.27  5455.6 1658.47  5524.7 1660.05
#Mann= 4 ,-1 , 0
  4412.9      .1       0  4995.1     .07       0  5001.1      .1       0
  5233.8     .05       0
Bank Sta=4995.1,5001.1
XS Rating Curve= 0 ,0
Exp/Cntr=0.3,0.1

Type RM Length L Ch R = 1 ,3956    ,339,339,339
BEGIN DESCRIPTION:
UNT 0069 IN HEWA 8.0
END DESCRIPTION:
XS GIS Cut Line= 2
      2767248.11     10062600.52      2766582.45     10062756.53
#Sta/Elev= 30
  4667.8 1651.06  4751.2  1650.7  4770.1 1650.32  4821.5 1648.55  4872.9 1647.68
  4878.5 1647.21  4903.7  1646.6  4913.9 1646.17  4934.5 1643.92    4955 1642.68
  4963.4 1642.88  4968.6 1643.71  4985.8 1640.74  4993.1 1638.25  4995.9 1637.75
  4999.1 1638.25  5005.9 1639.59    5011 1638.94  5016.7 1641.84  5026.9 1644.45
  5047.5 1645.19  5053.5 1644.82  5063.3 1645.14  5078.3 1645.33  5095.9 1646.67
  5129.6 1647.64  5201.5 1650.69  5242.6 1651.73  5324.8 1654.77  5351.5 1655.43
#Mann= 5 ,-1 , 0
  4667.8     .05       0  4770.1      .1       0  4993.1     .07       0
  4999.1      .1       0  5063.3     .05       0
Bank Sta=4993.1,4999.1
XS Rating Curve= 0 ,0
Exp/Cntr=0.3,0.1

Type RM Length L Ch R = 1 ,3617    ,241,241,241
BEGIN DESCRIPTION:
UNT 0069 IN HEWA 7.0
END DESCRIPTION:
XS GIS Cut Line= 2
      2767232.49     10062340.11      2766572.21     10062345.31
#Sta/Elev= 30
  4649.2 1648.22  4743.2 1648.67  4773.2 1648.08  4793.2 1647.89  4823.2    1647
  4843.2 1647.16  4853.2 1647.07  4863.2 1646.36  4873.2 1645.42  4883.2 1644.94
  4893.2 1644.76  4904.8 1644.26  4953.2 1641.35  4963.2 1640.94  4973.2 1640.04
  4983.2 1637.49  4993.2 1635.87  5000.2 1635.62    5003 1635.12  5006.2 1635.62
  5033.2 1638.88  5043.2 1639.75  5063.2 1640.71  5073.2 1641.57  5123.2  1643.9
  5153.2    1645  5203.2 1647.43  5243.2 1648.88  5263.2 1649.89  5309.5  1650.9
#Mann= 4 ,-1 , 0
  4649.2     .05       0  4904.8      .1       0  5000.2     .07       0
  5006.2     .05       0
Bank Sta=5000.2,5006.2
XS Rating Curve= 0 ,0
Exp/Cntr=0.3,0.1

Type RM Length L Ch R = 1 ,3376    ,142,142,142
BEGIN DESCRIPTION:
Mapping XS 89f8dc7e
END DESCRIPTION:
XS GIS Cut Line= 2
      2767259.97     10062106.42      2766432.69     10062111.62
#Sta/Elev= 30
  4609.8 1646.66  4631.3 1646.58  4691.3 1644.61  4721.3 1644.45  4741.3 1643.14
  4761.3 1643.94  4771.3 1643.96  4781.3 1643.61  4851.3 1643.09  4931.3 1640.86
  4961.3 1639.08  4971.3 1636.87  4977.3 1634.16  4982.3  1633.8  4991.3 1632.45
  4998.3 1632.21  5001.1 1631.71  5004.3 1632.21  5011.3 1633.14  5021.3 1635.99
  5031.3 1638.29  5041.3 1639.07  5111.3 1640.69  5191.3 1644.74  5231.3 1646.36
  5291.3 1648.17  5321.3 1649.54  5411.3 1650.76  5431.3 1650.68  5437.1 1650.28
#Mann= 3 ,-1 , 0
  4609.8     .05       0  4998.3     .04       0  5004.3     .05       0
Bank Sta=4998.3,5004.3
XS Rating Curve= 0 ,0
Exp/Cntr=0.3,0.1

Type RM Length L Ch R = 1 ,3234    ,78,78,78
BEGIN DESCRIPTION:
Mapping XS 997d57e2
END DESCRIPTION:
XS GIS Cut Line= 2
      2767197.52     10061976.21       2766442.9     10061955.39
#Sta/Elev= 30
  4677.6 1644.94  4736.7 1643.98  4776.7 1642.97  4804.9 1642.69  4816.7 1642.52
  4846.7 1640.91  4856.7 1640.94  4876.7 1639.88  4896.7 1639.45  4906.7  1638.6
  4945.2 1633.97  4950.2 1634.75  4976.8 1631.16  4986.8 1630.19  4993.8 1630.12
  4996.5 1629.62  4999.8 1630.12  5026.8 1631.01  5036.8 1632.44  5046.8 1634.41
  5066.8 1637.36  5086.8 1638.57    5145 1640.79  5196.8 1643.17  5296.9 1646.43
  5311.6 1646.38  5336.9 1647.08  5376.9 1647.66  5396.9 1647.25  5432.5 1647.45
#Mann= 5 ,-1 , 0
  4677.6     .05       0  4804.9      .1       0  4993.8     .07       0
  4999.8      .1       0    5145     .05       0
Bank Sta=4993.8,4999.8
XS Rating Curve= 0 ,0
Exp/Cntr=0.3,0.1