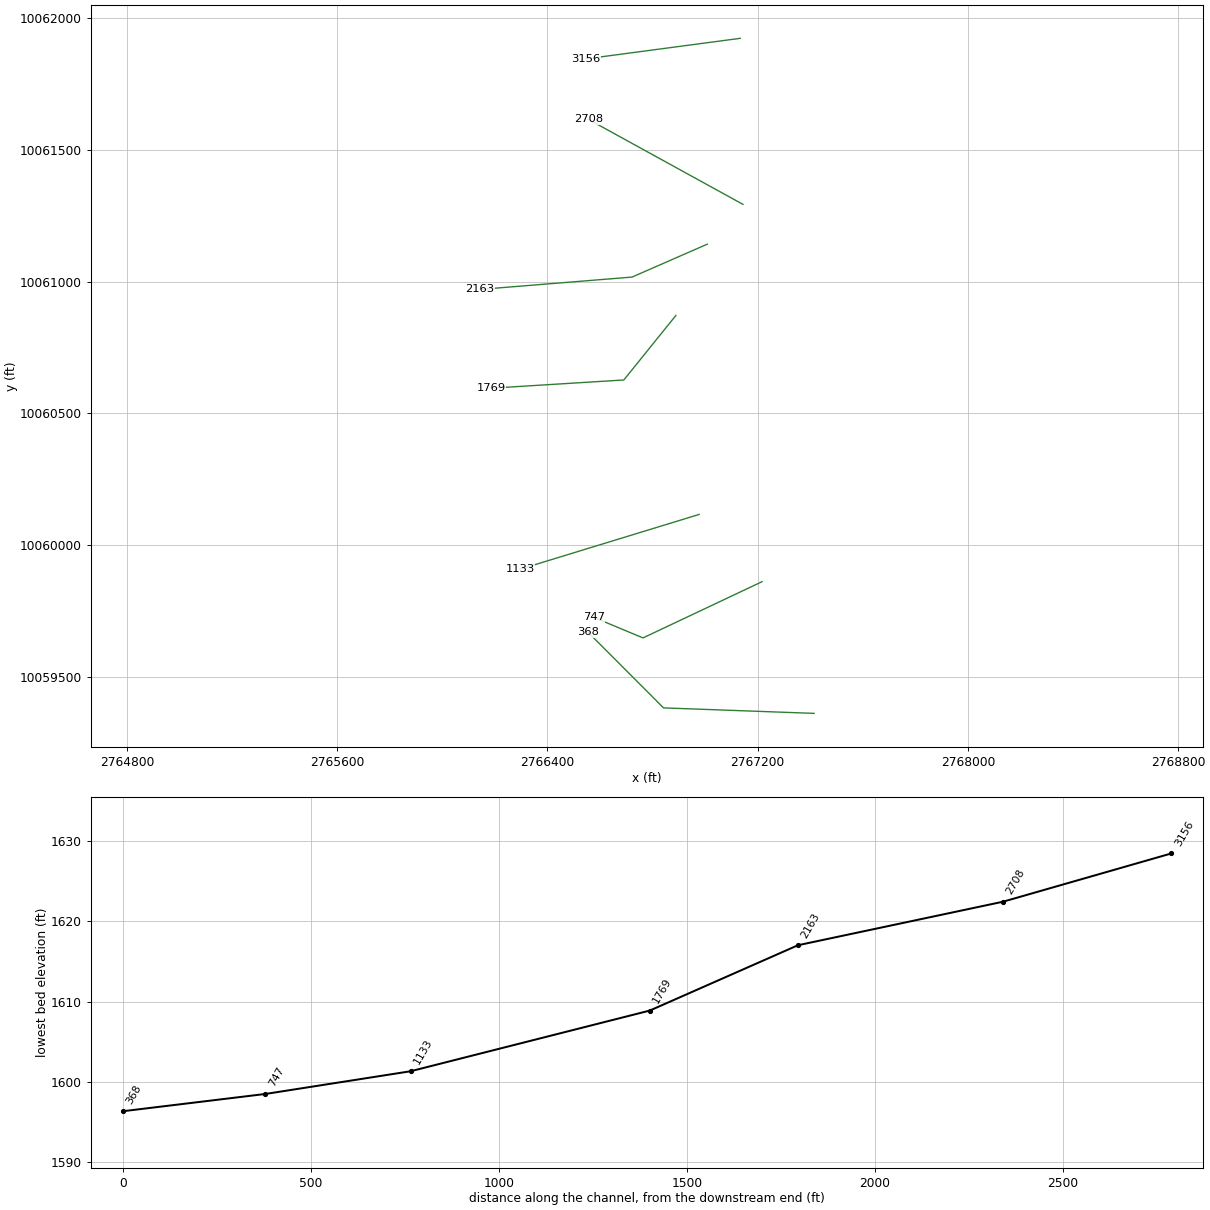
HEC-RAS study UNT 0069 IN HEWA.prj: UNT 0069 IN HEWA Base Level Engineering

--- UNT 0069 IN HEWA.g01 (geometry) --- (continued)

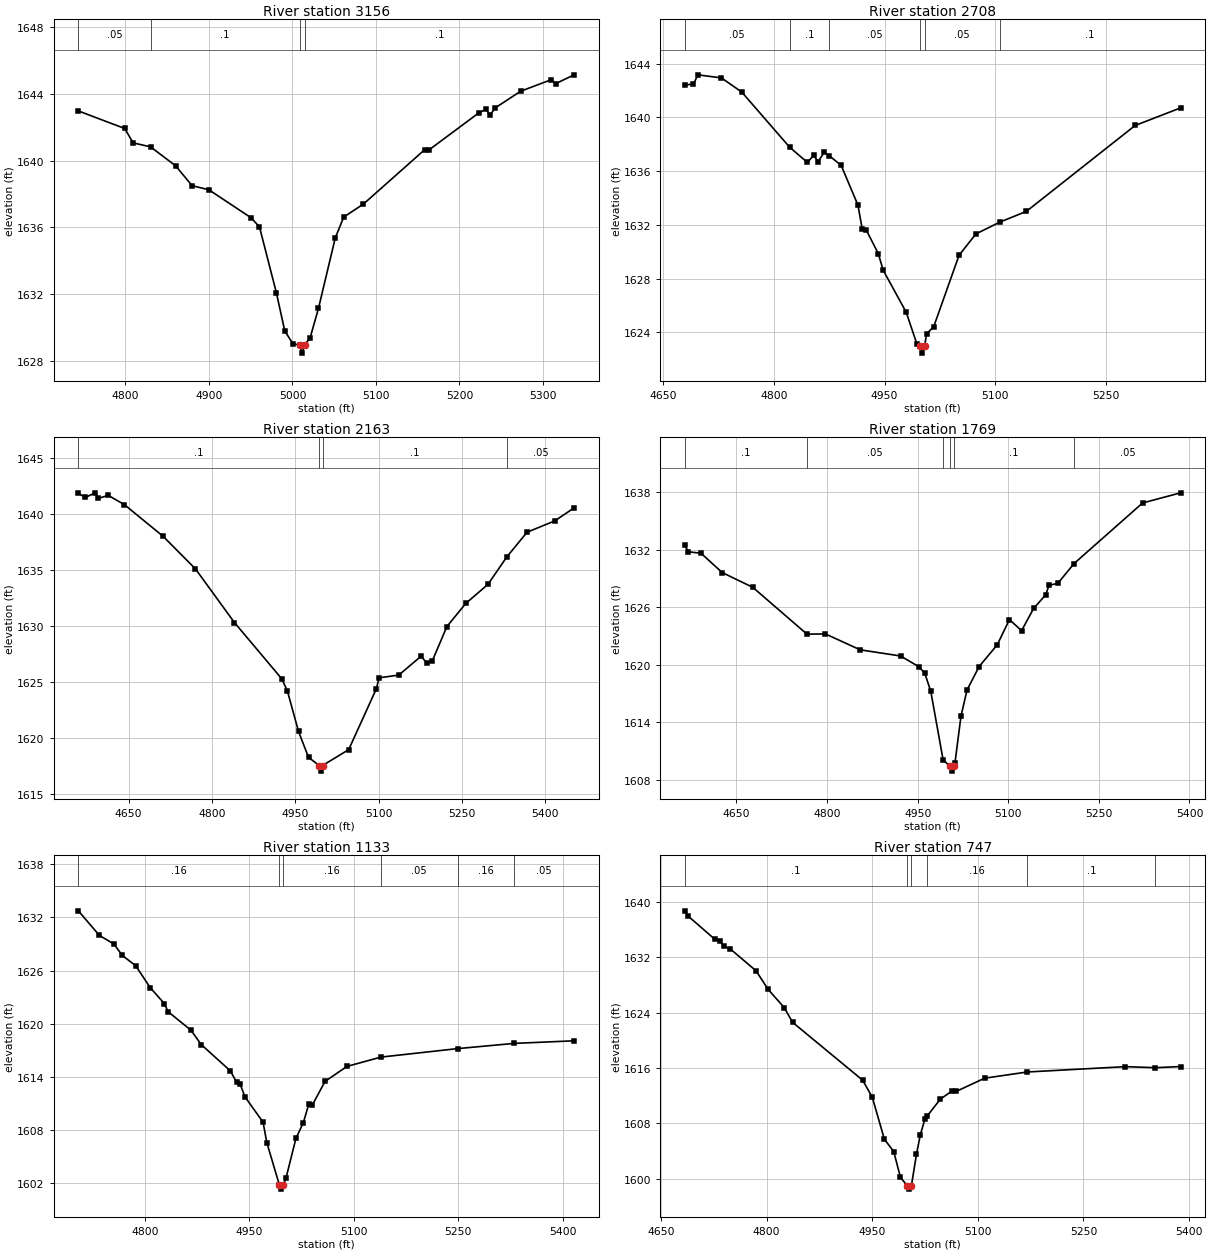
Type RM Length L Ch R = 1 ,3156    ,448,448,448
BEGIN DESCRIPTION:
UNT 0069 IN HEWA 6.0
END DESCRIPTION:
XS GIS Cut Line= 2
      2767133.52     10061923.44      2766544.98     10061845.32
#Sta/Elev= 30
  4743.6 1642.97  4799.1 1641.92  4809.2 1641.06  4830.1 1640.82    4860 1639.69
  4879.8  1638.5    4900 1638.25  4950.4 1636.58  4960.5 1636.03  4980.7  1632.1
  4990.8  1629.8  5000.9 1629.02  5008.7 1628.98  5011.4 1628.48  5014.7 1628.98
  5021.1 1629.39  5031.1 1631.15  5051.3 1635.38  5061.4 1636.62    5085  1637.4
  5158.3 1640.65  5163.3 1640.63  5222.8 1642.84  5231.6 1643.07  5236.6 1642.73
    5243 1643.16  5273.3 1644.15  5309.9 1644.84    5315  1644.6  5337.3 1645.13
#Mann= 4 ,-1 , 0
  4743.6     .05       0  4830.1      .1       0  5008.7     .07       0
  5014.7      .1       0
Bank Sta=5008.7,5014.7
XS Rating Curve= 0 ,0
Exp/Cntr=0.3,0.1

Type RM Length L Ch R = 1 ,2708    ,545,545,545
BEGIN DESCRIPTION:
UNT 0069 IN HEWA 5.0
END DESCRIPTION:
XS GIS Cut Line= 2
      2767143.97     10061293.21      2766555.43     10061616.12
#Sta/Elev= 30
  4679.6 1642.43  4691.3 1642.47  4697.3 1643.17  4729.2 1642.94  4756.7 1641.89
  4821.6 1637.78  4845.6 1636.65  4854.3 1637.19    4860 1636.69  4868.4 1637.42
  4875.5 1637.13  4891.2 1636.44    4914 1633.48  4919.7 1631.73  4925.4 1631.61
  4941.5 1629.87  4948.2 1628.63  4979.4  1625.5  4993.8 1623.14  4998.2 1622.96
    5001 1622.46  5004.2 1622.96  5006.9 1623.88  5016.7 1624.44  5050.9 1629.74
  5073.7 1631.33  5105.8  1632.2  5142.1 1633.01  5289.3  1639.4  5350.9 1640.71
#Mann= 6 ,-1 , 0
  4679.6     .05       0  4821.6      .1       0  4875.5     .05       0
  4998.2    .035       0  5004.2     .05       0  5105.8      .1       0
Bank Sta=4998.2,5004.2
XS Rating Curve= 0 ,0
Exp/Cntr=0.3,0.1

Type RM Length L Ch R = 1 ,2163    ,394,394,394
BEGIN DESCRIPTION:
UNT 0069 IN HEWA 4.0
END DESCRIPTION:
XS GIS Cut Line= 3
      2767008.53      10061142.2      2766722.06     10061017.19
      2766143.92     10060970.31
#Sta/Elev= 30
  4559.4 1641.84    4572 1641.48  4589.9 1641.89  4595.4  1641.4  4613.3 1641.66
  4642.2 1640.84  4712.2    1638  4770.2  1635.1  4840.4 1630.31  4925.7 1625.28
  4935.8 1624.19  4955.8 1620.58  4973.8 1618.27    4993 1617.54  4995.7 1617.04
    4999 1617.54  5046.1 1618.96  5095.8 1624.38  5100.8 1625.37  5136.4 1625.62
  5176.6 1627.31  5186.6 1626.68  5196.6 1626.88  5222.9 1629.95  5256.8 1632.01
  5296.9 1633.72  5330.6 1636.16  5367.2 1638.37  5417.3 1639.39    5452 1640.55
#Mann= 4 ,-1 , 0
  4559.4      .1       0    4993     .07       0    4999      .1       0
  5330.6     .05       0
Bank Sta=4993,4999
XS Rating Curve= 0 ,0
Exp/Cntr=0.3,0.1

Type RM Length L Ch R = 1 ,1769    ,636,636,636
BEGIN DESCRIPTION:
UNT 0069 IN HEWA 3.0
END DESCRIPTION:
XS GIS Cut Line= 3
      2766888.71     10060871.34      2766690.81     10060626.56
      2766185.55     10060595.31
#Sta/Elev= 30
  4564.4 1632.46  4570.3 1631.79  4591.1 1631.65  4626.3 1629.63  4677.1 1628.08
  4766.6  1623.2  4797.3 1623.22  4854.9 1621.56  4921.6 1620.92  4951.7 1619.81
  4961.7 1619.13  4971.7 1617.23  4992.1 1610.08  5003.4  1609.4  5006.2  1608.9
  5009.4  1609.4  5011.8 1609.79  5021.8 1614.67  5031.8 1617.38  5051.8 1619.82
  5081.9  1622.1  5101.9 1624.72    5122 1623.56    5142 1625.88  5162.1 1627.31
  5167.5  1628.3  5182.1  1628.5    5209 1630.57  5322.4 1636.89  5385.4 1637.95
#Mann= 6 ,-1 , 0
  4564.4      .1       0  4766.6     .05       0  4992.1      .1       0
  5003.4     .07       0  5009.4      .1       0    5209     .05       0
Bank Sta=5003.4,5009.4
XS Rating Curve= 0 ,0
Exp/Cntr=0.3,0.1

Type RM Length L Ch R = 1 ,1133    ,386,386,386
BEGIN DESCRIPTION:
Mapping XS 540e2fb3
END DESCRIPTION:
XS GIS Cut Line= 2
      2766977.25     10060116.14      2766296.48     10059908.27
#Sta/Elev= 30
  4704.7 1632.75    4735 1629.97  4755.7 1629.01  4767.9 1627.71  4787.1 1626.55
    4808 1624.07  4828.2 1622.28  4833.5 1621.37  4866.3 1619.28  4881.2 1617.65
    4923 1614.68  4931.9  1613.4  4937.1 1613.16  4943.9 1611.76  4969.9 1608.89
  4975.3 1606.59  4993.2 1601.84  4995.9 1601.34  4999.2 1601.84  5002.7 1602.55
  5017.1 1607.07  5027.6 1608.82  5035.5 1610.92  5040.8 1610.86  5058.9  1613.5
  5090.3 1615.19  5139.1 1616.24  5249.3  1617.2  5330.7 1617.79  5416.5 1618.08
#Mann= 6 ,-1 , 0
  4704.7     .16       0  4993.2     .07       0  4999.2     .16       0
  5139.1     .05       0  5249.3     .16       0  5330.7     .05       0
Bank Sta=4993.2,4999.2
XS Rating Curve= 0 ,0
Exp/Cntr=0.3,0.1

Type RM Length L Ch R = 1 ,747     ,379,379,379
BEGIN DESCRIPTION:
UNT 0069 IN HEWA 2.0
END DESCRIPTION:
XS GIS Cut Line= 3
      2767216.89     10059860.96      2766763.72      10059647.4
      2766576.22     10059725.52
#Sta/Elev= 30
  4683.9 1638.73  4688.4 1637.99  4726.4 1634.63    4734 1634.36  4739.5 1633.58
  4748.5 1633.22  4785.1 1630.06  4802.3 1627.37  4825.1 1624.74  4836.9 1622.62
  4936.4 1614.26  4950.1  1611.8  4967.3 1605.72  4980.6 1603.94  4990.1 1600.22
  4999.7 1599.01  5002.5 1598.51  5005.7 1599.01  5012.9 1603.56  5018.4 1606.38
  5024.9 1608.64  5027.8 1609.04    5047 1611.54    5064 1612.73  5069.5 1612.64
  5109.6 1614.54  5170.3 1615.44  5309.7 1616.21  5352.3 1616.06    5388 1616.23
#Mann= 6 ,-1 , 0
  4683.9      .1       0  4999.7     .07       0  5005.7      .1       0
  5027.8     .16       0  5170.3      .1       0  5352.3     .16       0
Bank Sta=4999.7,5005.7
XS Rating Curve= 0 ,0
Exp/Cntr=0.3,0.1

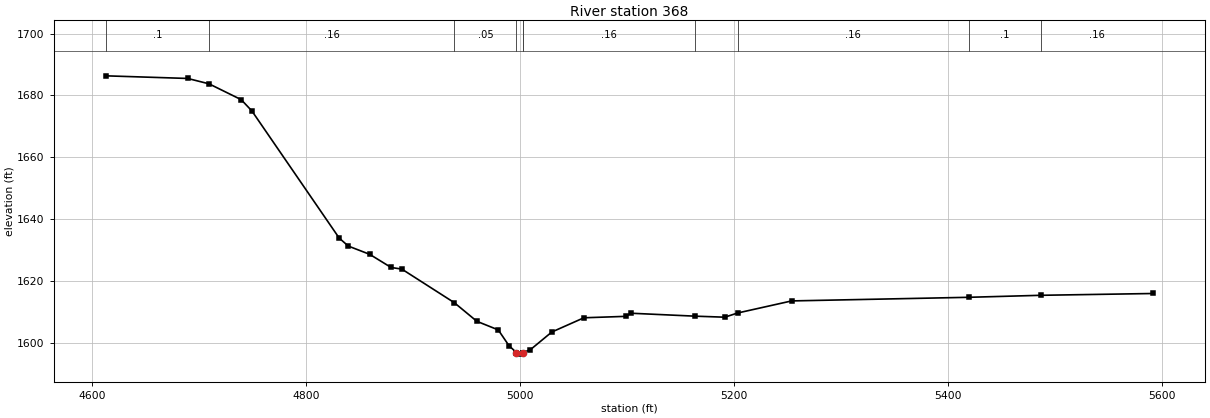
Type RM Length L Ch R = 1 ,368     ,0,0,0
BEGIN DESCRIPTION:
UNT 0069 IN HEWA 1.0
END DESCRIPTION:
XS GIS Cut Line= 3
      2767414.79     10059360.94      2766841.85     10059381.77
      2766555.41     10059668.21
#Sta/Elev= 30
  4612.9 1686.33  4689.3 1685.48  4709.2 1683.75  4739.3 1678.63  4749.3 1674.98
  4830.9 1633.87  4839.4 1631.29  4859.4 1628.62  4879.4 1624.37  4889.4 1623.85
  4938.4    1613  4959.5 1606.97  4979.5 1604.19  4989.5  1599.1  4996.5 1596.86
  4999.2 1596.36  5002.5 1596.86  5002.6 1596.87  5009.5 1597.79  5029.5  1603.5
  5059.5 1608.11  5098.5 1608.57  5103.5 1609.58  5163.5 1608.63  5191.1  1608.3
  5203.2 1609.66  5253.6 1613.56    5419 1614.73  5486.8 1615.38  5591.3 1615.96
#Mann= 10 ,-1 , 0
  4612.9      .1       0  4709.2     .16       0  4938.4     .05       0
  4996.5    .035       0  5002.5     .05       0  5002.6     .16       0
  5163.5     .05       0  5203.2     .16       0    5419      .1       0
  5486.8     .16       0
Bank Sta=4996.5,5002.5
XS Rating Curve= 0 ,0
Exp/Cntr=0.3,0.1

Chan Stop Cuts=-1
Use User Specified Reach Order=0
Composite Channel Slope=5