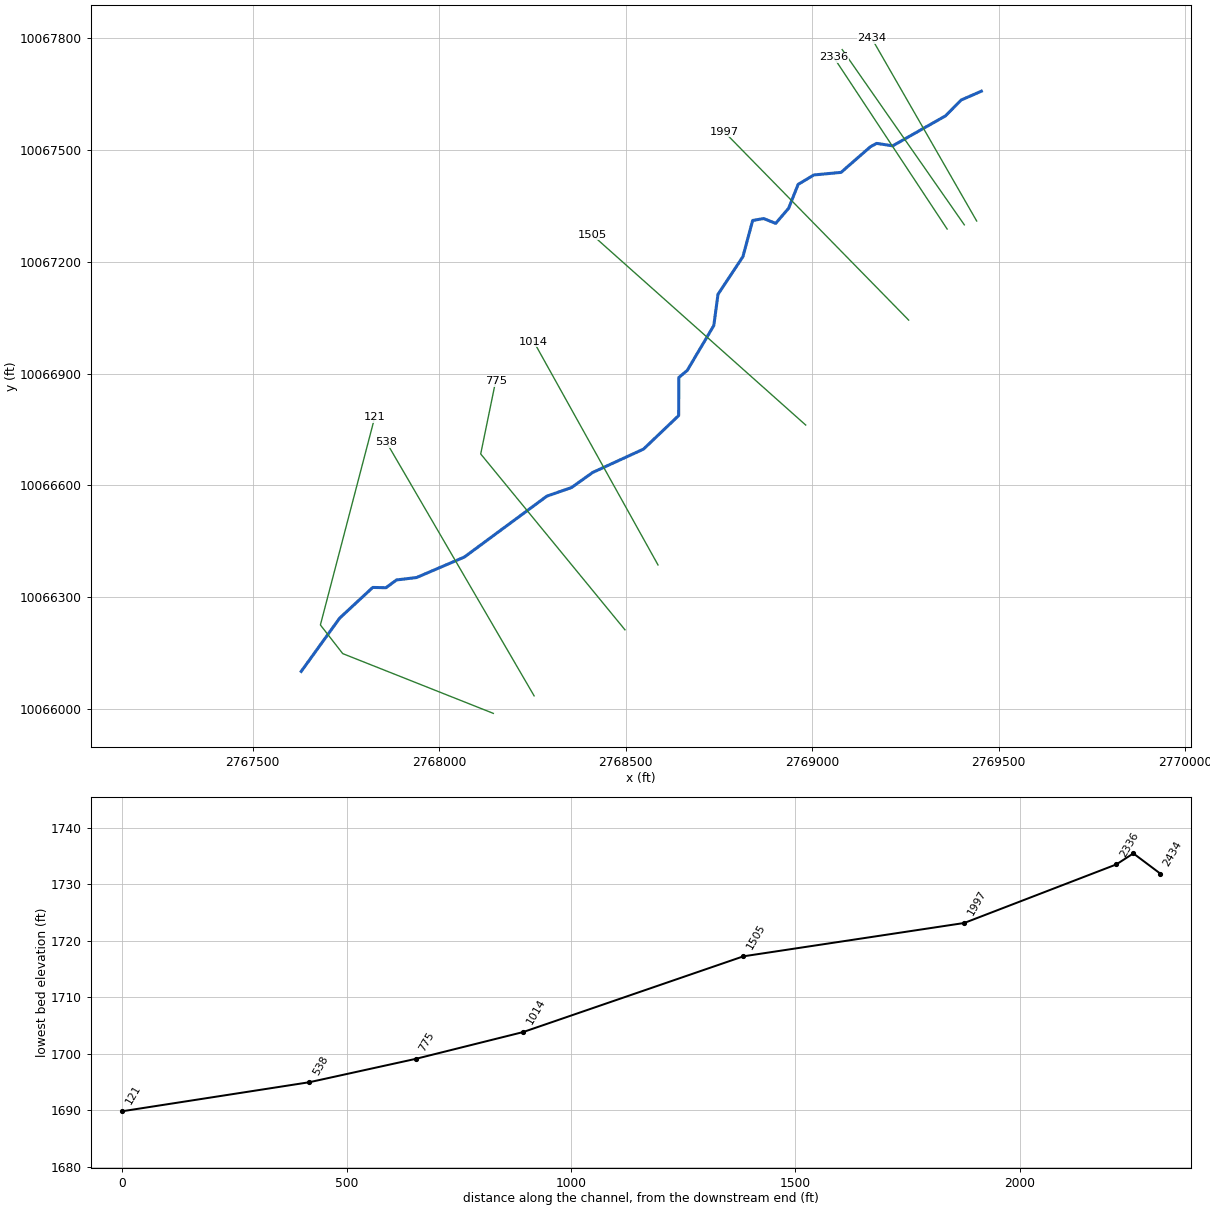
--- UNT 0070 IN HEWA.prj (project) ---

Proj Title=UNT 0070 IN HEWA Base Level Engineering
Current Plan=p01
Default Exp/Contr=0.3,0.1
English Units
Geom File=g01
Flow File=f01
Plan File=p01
Y Axis Title=Elevation
X Axis Title(PF)=Main Channel Distance
X Axis Title(XS)=Station
BEGIN DESCRIPTION:
UNT 0070 IN HEWA
END DESCRIPTION:
DSS Export Rating Curves= 0
DSS Export Rating Curve Sorted= 0
DSS Export Volume Flow Curves= 0
DXF OffsetX= 0
DXF OffsetY= 0
DXF ScaleX= 1
DXF ScaleY= 10

--- UNT 0070 IN HEWA.p01 (plan) ---

Plan Title=Multiple Run
Short Identifier=Multiple
Geom File=g01
Flow File=f01
Subcritical Flow
K Sum by GR= 0
Std Step Tol= 0.01
Critical Tol= 0.01
Num of Std Step Trials= 20
Max Error Tol= 0.3
Flow Tol Ratio= 0.001
Split Flow NTrial= 30
Split Flow Tol= 0.02
Split Flow Ratio= 0.02
Log Output Level= 0
Friction Slope Method= 1
Unsteady Friction Slope Method= 2
Unsteady Bridges Friction Slope Method= 1
Parabolic Critical Depth
Global Vel Dist=  1 , 1 , 1
Global Log Level= 0
CheckData=True
Encroach Param= -1, 0, 0, 0
BEGIN DESCRIPTION:
Multiple Run
END DESCRIPTION:

--- UNT 0070 IN HEWA.f01 (steady flow) ---

Flow Title=Multiple
Program Version=4.10
Number of Profiles= 7
Profile Names=10-year,25-year,50-year,1pct_min,100-year,1pct_plu,500-year
River Rch & RM=UNT 0070 IN HEWA,Reach-1         ,2434
     171     224     267     234     316     427     443
Boundary for River Rch & Prof#=UNT 0070 IN HEWA,Reach-1         , 1
Up Type= 0
Dn Type= 3
Dn Slope=0.012
Boundary for River Rch & Prof#=UNT 0070 IN HEWA,Reach-1         , 2
Up Type= 0
Dn Type= 3
Dn Slope=0.012
Boundary for River Rch & Prof#=UNT 0070 IN HEWA,Reach-1         , 3
Up Type= 0
Dn Type= 3
Dn Slope=0.012
Boundary for River Rch & Prof#=UNT 0070 IN HEWA,Reach-1         , 4
Up Type= 0
Dn Type= 3
Dn Slope=0.012
Boundary for River Rch & Prof#=UNT 0070 IN HEWA,Reach-1         , 5
Up Type= 0
Dn Type= 3
Dn Slope=0.012
Boundary for River Rch & Prof#=UNT 0070 IN HEWA,Reach-1         , 6
Up Type= 0
Dn Type= 3
Dn Slope=0.012
Boundary for River Rch & Prof#=UNT 0070 IN HEWA,Reach-1         , 7
Up Type= 0
Dn Type= 3
Dn Slope=0.012
DSS Import GetInterval= 0
DSS Import GetPeak= 0
DSS Import FillOption= 0

--- UNT 0070 IN HEWA.g01 (geometry) ---

Geom Title=Existing Conditions
Program Version=4.10

River Reach=UNT 0070 IN HEWA,Reach-1
Reach XY= 30
      2769453.37     10067656.75      2769399.34     10067633.18
      2769357.24     10067590.64      2769215.79     10067510.37
      2769172.38     10067516.88      2769155.89     10067507.77
      2769077.33     10067439.19      2769004.42     10067432.25
      2768962.31     10067407.07      2768936.71     10067342.84
      2768901.98     10067302.47      2768869.87     10067315.49
      2768840.35     10067310.28      2768814.31      10067213.5
      2768747.47     10067112.37      2768736.19      10067028.6
      2768665.01     10066908.37      2768642.44     10066889.28
        2768642.     10066787.28      2768547.82     10066697.44
      2768411.73     10066634.92      2768354.88     10066594.41
      2768288.79     10066571.37      2768067.66      10066408.1
      2767939.41     10066353.17      2767885.75     10066346.71
      2767857.47     10066325.86      2767822.06     10066326.67
      2767733.25     10066244.27      2767630.32      10066101.6

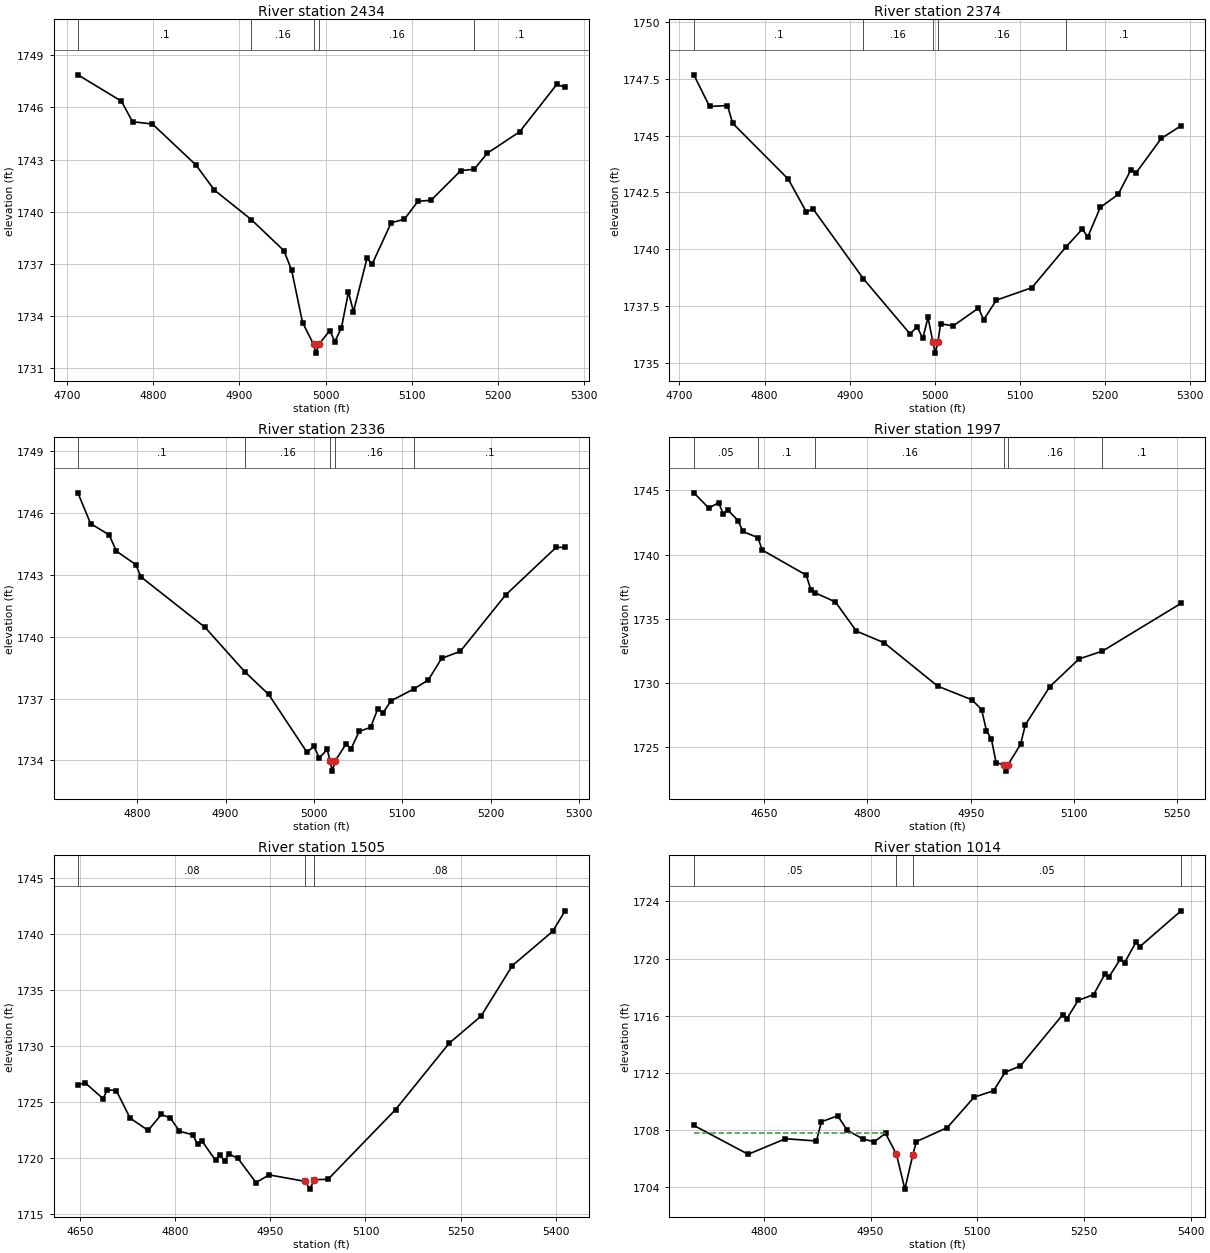
Type RM Length L Ch R = 1 ,2434    ,60,60,60
BEGIN DESCRIPTION:
UNT 0070 IN HEWA 5.0
END DESCRIPTION:
XS GIS Cut Line= 2
      2769440.83     10067308.82      2769159.54     10067798.48
#Sta/Elev= 30
  4712.9 1747.88  4763.4 1746.36  4776.2 1745.18  4799.3 1745.05  4849.7 1742.69
  4871.2 1741.24  4913.8 1739.55  4951.7 1737.76  4960.7 1736.62  4973.3 1733.62
  4986.1 1732.36  4988.9 1731.86  4992.1 1732.36  5004.9 1733.16  5010.7 1732.52
  5018.4 1733.33  5026.5 1735.37  5032.3 1734.25  5048.1 1737.34  5053.8 1736.97
  5076.1 1739.37  5091.2 1739.56    5107  1740.6  5122.2 1740.66  5156.8 1742.37
  5172.1 1742.44  5187.5 1743.37  5224.9  1744.6    5268 1747.33  5277.6 1747.16
#Mann= 5 ,-1 , 0
  4712.9      .1       0  4913.8     .16       0  4986.1     .07       0
  4992.1     .16       0  5172.1      .1       0
Bank Sta=4986.1,4992.1
XS Rating Curve= 0 ,0
Exp/Cntr=0.3,0.1

Type RM Length L Ch R = 1 ,2374    ,38,38,38
BEGIN DESCRIPTION:
Mapping XS 8c301b20
END DESCRIPTION:
XS GIS Cut Line= 2
      2769407.65     10067298.63      2769080.39     10067768.25
#Sta/Elev= 30
  4716.9 1747.67  4735.3 1746.28  4756.4 1746.32  4762.5 1745.54  4827.9 1743.08
  4848.9 1741.65  4857.2 1741.76  4915.9 1738.71    4971 1736.27  4979.1 1736.59
  4985.9 1736.08    4992    1737  4997.7 1735.93  5000.5 1735.43  5003.7 1735.93
  5006.8 1736.72  5021.6 1736.63  5051.3 1737.41  5057.4  1736.9  5072.3 1737.76
  5114.1 1738.31  5153.6 1740.08  5173.5 1740.89  5179.6 1740.53  5194.4 1741.84
  5215.4 1742.41  5230.2 1743.48  5236.3 1743.35    5266 1744.87  5289.3 1745.43
#Mann= 5 ,-1 , 0
  4716.9      .1       0  4915.9     .16       0  4997.7     .07       0
  5003.7     .16       0  5153.6      .1       0
Bank Sta=4997.7,5003.7
XS Rating Curve= 0 ,0
Exp/Cntr=0.3,0.1

Type RM Length L Ch R = 1 ,2336    ,339,339,339
BEGIN DESCRIPTION:
Mapping XS 8d6038b6
END DESCRIPTION:
XS GIS Cut Line= 2
      2769361.66     10067287.33      2769057.86     10067747.37
#Sta/Elev= 30
  4732.9 1746.98  4747.2 1745.49  4768.2 1744.94  4776.5 1744.15  4798.4  1743.5
  4804.3  1742.9  4876.6 1740.46  4922.2 1738.28  4948.8  1737.2  4992.2 1734.39
    5000 1734.69    5006 1734.11  5015.1 1734.54  5018.1 1733.98  5020.8 1733.48
  5024.1 1733.98  5036.1 1734.78  5042.1 1734.57  5051.2 1735.41  5064.1  1735.6
  5072.3 1736.51  5078.3 1736.32  5087.3 1736.89  5113.6 1737.48  5129.4  1737.9
  5144.5 1738.95  5165.6 1739.29  5216.8 1742.02  5273.9 1744.33  5284.2 1744.34
#Mann= 5 ,-1 , 0
  4732.9      .1       0  4922.2     .16       0  5018.1     .07       0
  5024.1     .16       0  5113.6      .1       0
Bank Sta=5018.1,5024.1
XS Rating Curve= 0 ,0
Exp/Cntr=0.3,0.1

Type RM Length L Ch R = 1 ,1997    ,492,492,492
BEGIN DESCRIPTION:
UNT 0070 IN HEWA 4.0
END DESCRIPTION:
XS GIS Cut Line= 2
      2769258.53     10067043.21       2768763.7     10067548.46
#Sta/Elev= 30
  4548.2 1744.81  4569.8 1743.63    4584 1744.03    4591 1743.18  4598.1 1743.44
  4612.3 1742.65  4619.3  1741.8  4641.1 1741.32  4647.5 1740.35  4711.3  1738.4
  4718.3 1737.21  4724.2 1737.02  4753.7 1736.31  4784.1 1734.04  4824.4 1733.13
  4902.1 1729.75  4951.7 1728.69  4965.9 1727.93  4972.9 1726.28    4980 1725.65
    4987 1723.78  4998.2 1723.63  5000.9 1723.13  5004.2 1723.63  5022.4 1725.21
  5029.4 1726.74  5064.9 1729.71  5107.3 1731.87  5141.3 1732.48  5255.4  1736.2
#Mann= 6 ,-1 , 0
  4548.2     .05       0  4641.1      .1       0  4724.2     .16       0
  4998.2     .07       0  5004.2     .16       0  5141.3      .1       0
Bank Sta=4998.2,5004.2
XS Rating Curve= 0 ,0
Exp/Cntr=0.3,0.1

Type RM Length L Ch R = 1 ,1505    ,491,491,491
BEGIN DESCRIPTION:
UNT 0070 IN HEWA 3.0
END DESCRIPTION:
XS GIS Cut Line= 2
       2768982.5     10066761.96      2768409.58     10067272.37
#Sta/Elev= 30
  4647.1 1726.53  4658.2 1726.74  4686.7 1725.32  4693.4  1726.1  4707.6 1726.04
  4729.3 1723.58  4757.7 1722.48  4778.6 1723.91  4792.8 1723.58  4807.1 1722.41
    4828 1722.09  4835.5 1721.25  4842.2 1721.56  4863.9 1719.81  4870.6  1720.3
  4878.1 1719.77  4884.8 1720.36    4899    1720  4927.5 1717.83  4948.4 1718.51
  5005.2 1717.93  5012.5 1717.24  5019.4 1718.09  5040.9 1718.11  5147.4 1724.34
  5231.8 1730.26    5282 1732.68  5331.3 1737.19  5394.9 1740.25  5414.4 1742.08
#Mann= 3 , 0 , 0
  4647.1     .08       0  5005.2     .05       0  5019.4     .08       0
Bank Sta=5005.2,5019.4
XS Rating Curve= 0 ,0
Exp/Cntr=0.3,0.1

Type RM Length L Ch R = 1 ,1014    ,239,239,239
BEGIN DESCRIPTION:
UNT 0070 IN HEWA 2.0
END DESCRIPTION:
XS GIS Cut Line= 2
      2768586.66     10066386.94      2768253.41     10066985.76
#Sta/Elev= 30
  4701.4 1708.31  4777.8 1706.29  4830.3 1707.38  4873.8 1707.22  4880.8 1708.57
  4903.7 1708.98  4917.2 1707.97    4939 1707.37    4955 1707.16    4971 1707.76
 4986.36 1706.29  4998.2 1703.85 5009.43 1706.26  5014.4 1707.18  5057.9 1708.16
  5095.6 1710.29  5123.1 1710.74  5139.1 1712.03  5160.8 1712.48  5220.3 1716.07
    5226 1715.78    5242 1717.07  5263.7 1717.47  5279.7 1718.92  5285.4 1718.72
  5301.4 1719.96  5307.2  1719.7  5323.2 1721.14  5328.9 1720.84  5386.7 1723.34
#Mann= 4 ,-1 , 0
  4701.4     .05       0 4986.36    .035       0 5009.43     .05       0
  5386.7     .16       0
#XS Ineff= 2 , 0
       0 4970.45 1707.79               0
Permanent Ineff=
       T       T
Bank Sta=4986.36,5009.43
XS Rating Curve= 0 ,0
Exp/Cntr=0.3,0.1

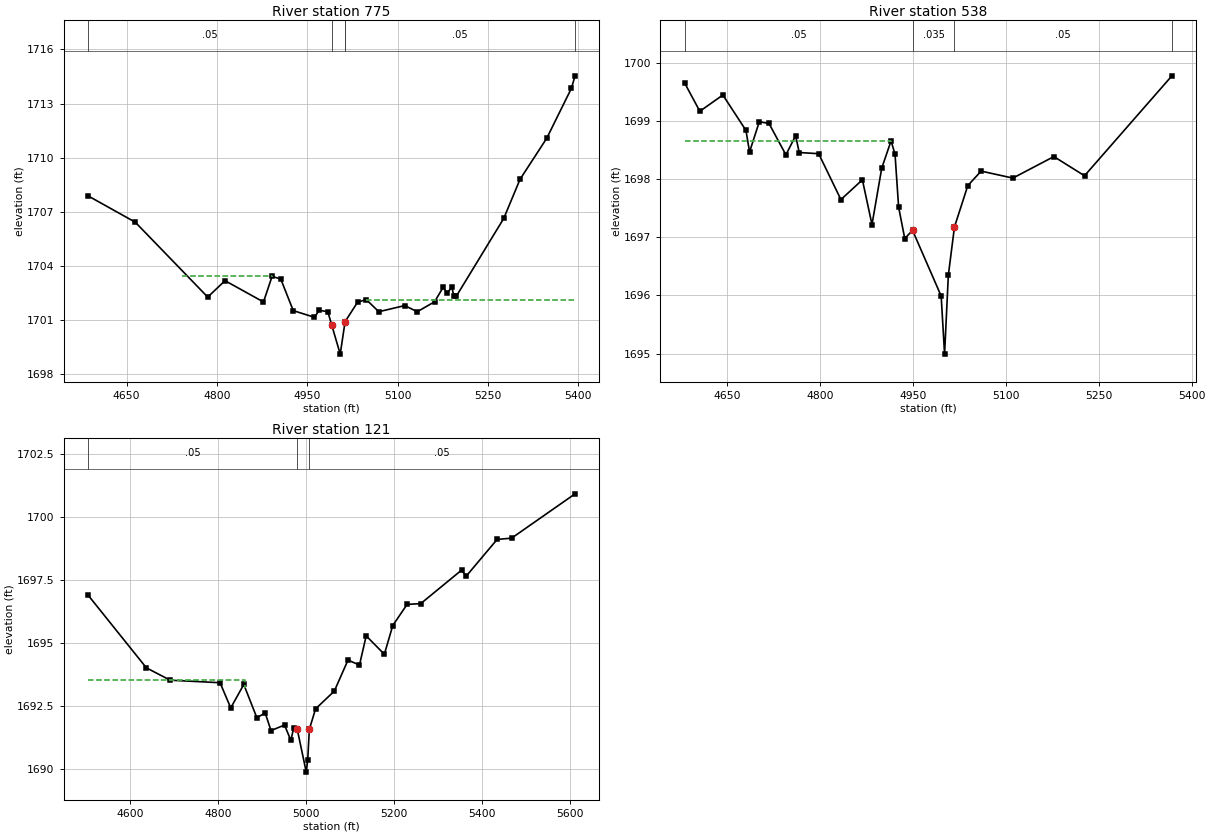
Type RM Length L Ch R = 1 ,775     ,237,237,237
BEGIN DESCRIPTION:
Mapping XS b765b9cf
END DESCRIPTION:
XS GIS Cut Line= 3
       2768498.1     10066213.06      2768111.39     10066684.41
      2768151.51     10066879.84
#Sta/Elev= 30
  4585.8 1707.89  4664.3 1706.43  4784.7 1702.28  4813.4 1703.19  4877.3 1702.01
  4891.6 1703.43    4906 1703.28  4926.8 1701.53    4962 1701.16  4969.9 1701.55
  4984.2 1701.47  4990.7 1700.73  5004.8 1699.12  5012.9 1700.92  5033.7    1702
  5048.1 1702.14  5068.9 1701.47    5112 1701.81  5132.8 1701.47  5161.5 1702.02
  5175.8 1702.82  5182.3 1702.51  5190.2 1702.82  5193.8 1702.33  5197.7 1702.33
  5276.5 1706.64  5303.6 1708.81  5347.9 1711.08  5388.8 1713.84    5395 1714.54
#Mann= 5 ,-1 , 0
  4585.8     .05       0  4990.7    .035       0  5012.9     .05       0
  5012.9     .05       0    5395      .1       0
#XS Ineff= 2 ,-1
 4741.48 4891.48 1703.45 5048.11    5395 1702.14
Permanent Ineff=
       T       T
Bank Sta=4990.7,5012.9
XS Rating Curve= 0 ,0
Exp/Cntr=0.3,0.1

Type RM Length L Ch R = 1 ,538     ,417,417,417
BEGIN DESCRIPTION:
Mapping XS 1cc33b78
END DESCRIPTION:
XS GIS Cut Line= 2
       2768254.6       10066036.      2767858.79     10066715.64
#Sta/Elev= 30
  4581.6 1699.65  4605.8 1699.17    4643 1699.45  4680.3 1698.84  4686.1 1698.47
  4701.8 1698.99  4717.5 1698.96  4744.8 1698.42  4760.5 1698.75  4766.3 1698.46
  4797.7 1698.44  4833.6 1697.65  4868.3 1697.99  4883.8 1697.22  4899.5 1698.19
  4914.6 1698.66    4921 1698.43  4926.8 1697.52  4936.7 1696.98  4949.3 1697.12
  4995.5 1695.99    5001 1694.99  5007.1 1696.35    5017 1697.18  5038.5 1697.89
    5060 1698.14  5111.3 1698.02  5177.5 1698.39    5227 1698.06  5368.1 1699.78
#Mann= 4 ,-1 , 0
  4581.6     .05       0  4949.3    .035       0    5017     .05       0
  5368.1     .16       0
#XS Ineff= 2 , 0
       0  4914.2 1698.66               0
Permanent Ineff=
       T       T
Bank Sta=4949.3,5017
XS Rating Curve= 0 ,0
Exp/Cntr=0.3,0.1

Type RM Length L Ch R = 1 ,121     ,0,0,0
BEGIN DESCRIPTION:
UNT 0070 IN HEWA 1.0
END DESCRIPTION:
XS GIS Cut Line= 4
      2768145.28     10065989.08      2767741.59     10066149.25
       2767681.7     10066226.07      2767827.54     10066783.39
#Sta/Elev= 30
  4504.6 1696.89  4637.4    1694  4691.5 1693.51  4804.9 1693.41  4829.2 1692.41
  4858.9 1693.34  4888.6 1692.02  4907.5 1692.21  4920.8 1691.51  4951.5 1691.73
    4966 1691.12  4972.3 1691.61  4980.5 1691.56    5001 1689.86  5004.3 1690.36
    5008 1691.56  5022.1 1692.37  5064.9 1693.08  5095.9 1694.31    5122 1694.11
  5137.3 1695.27  5178.6 1694.54  5197.7 1695.68  5230.3 1696.52  5261.3 1696.55
  5354.2 1697.88  5364.7 1697.64  5435.1  1699.1    5468 1699.15  5612.4 1700.91
#Mann= 3 , 0 , 0
  4504.6     .05       0  4980.5    .035       0    5008     .05       0
#XS Ineff= 2 , 0
       0 4861.89  1693.5               0
Permanent Ineff=
       T       T
Bank Sta=4980.5,5008
XS Rating Curve= 0 ,0
Exp/Cntr=0.3,0.1

Chan Stop Cuts=-1
Use User Specified Reach Order=0
Composite Channel Slope=5