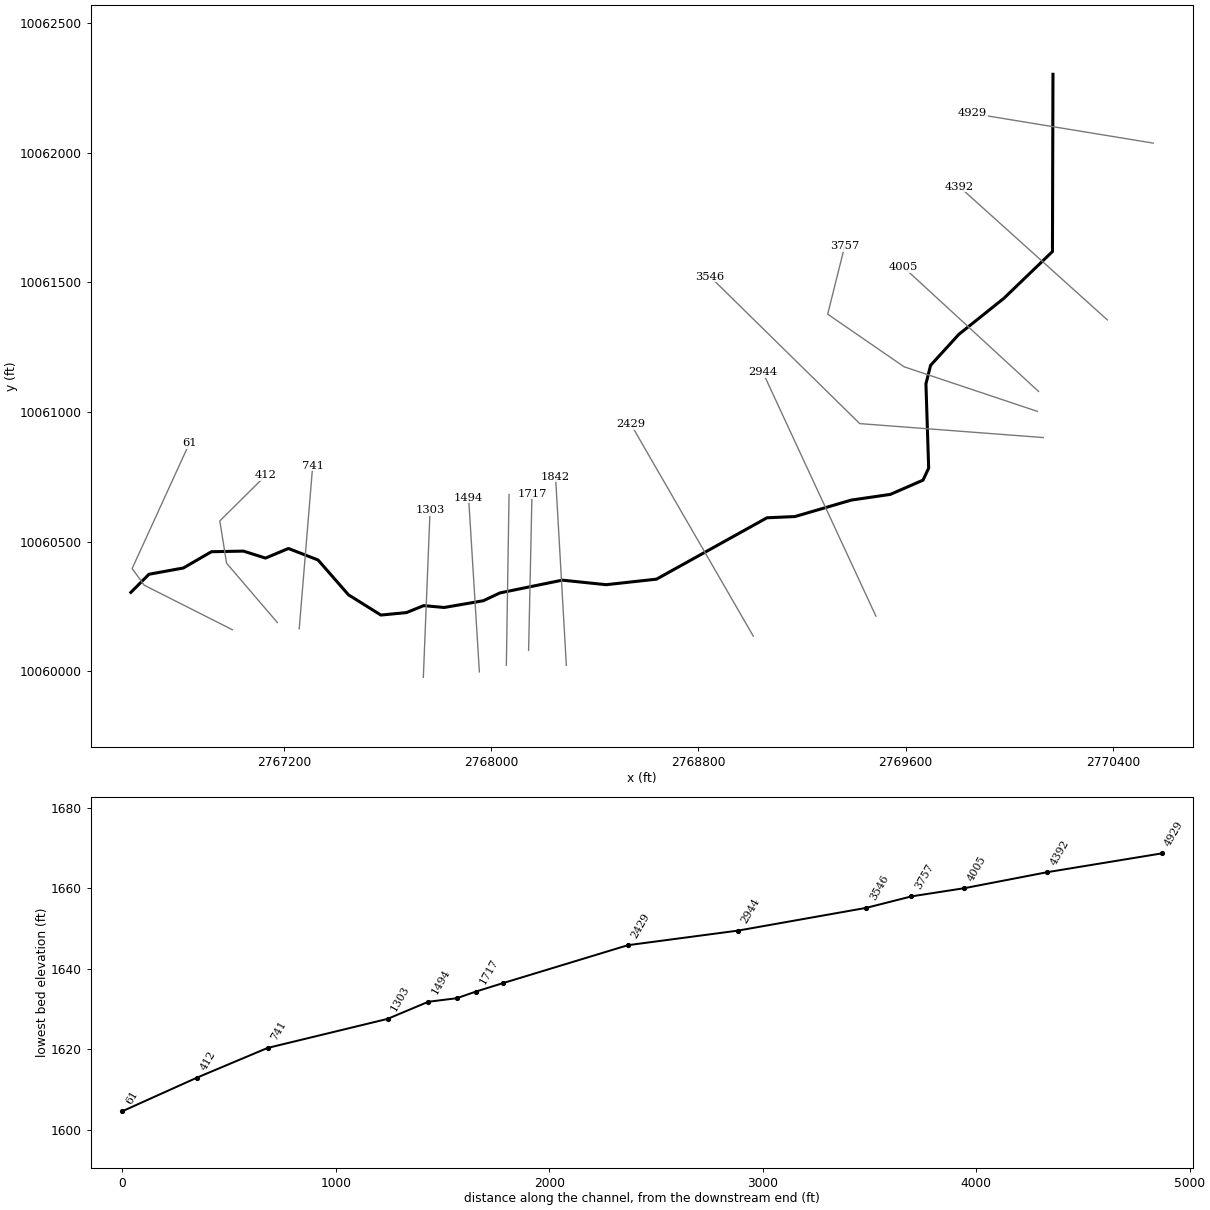
--- UNT 0071 IN HEWA.prj (project) ---

Proj Title=UNT 0071 IN HEWA Base Level Engineering
Current Plan=p01
Default Exp/Contr=0.3,0.1
English Units
Geom File=g01
Flow File=f01
Plan File=p01
Y Axis Title=Elevation
X Axis Title(PF)=Main Channel Distance
X Axis Title(XS)=Station
BEGIN DESCRIPTION:
UNT 0071 IN HEWA
END DESCRIPTION:
DSS Export Rating Curves= 0
DSS Export Rating Curve Sorted= 0
DSS Export Volume Flow Curves= 0
DXF OffsetX= 0
DXF OffsetY= 0
DXF ScaleX= 1
DXF ScaleY= 10

--- UNT 0071 IN HEWA.p01 (plan) ---

Plan Title=Multiple Run
Short Identifier=Multiple
Geom File=g01
Flow File=f01
Subcritical Flow
K Sum by GR= 0
Std Step Tol= 0.01
Critical Tol= 0.01
Num of Std Step Trials= 20
Max Error Tol= 0.3
Flow Tol Ratio= 0.001
Split Flow NTrial= 30
Split Flow Tol= 0.02
Split Flow Ratio= 0.02
Log Output Level= 0
Friction Slope Method= 1
Unsteady Friction Slope Method= 2
Unsteady Bridges Friction Slope Method= 1
Parabolic Critical Depth
Global Vel Dist=  1 , 1 , 1
Global Log Level= 0
CheckData=True
Encroach Param= -1, 0, 0, 0
BEGIN DESCRIPTION:
Multiple Run
END DESCRIPTION:

--- UNT 0071 IN HEWA.f01 (steady flow) ---

Flow Title=Multiple
Number of Profiles=7
Profile Names=10-year,25-year,50-year,1pct_min,100-year,1pct_plu,500-year
River Rch & RM= UNT 0071 IN HEWA,Reach-1,4929
     455     628     771     694     939    1269    1394
Boundary for River Rch & Prof#=UNT 0071 IN HEWA,Reach-1,1
Up Type=0
Dn Type=3
Dn Slope=0.005
Boundary for River Rch & Prof#=UNT 0071 IN HEWA,Reach-1,2
Up Type=0
Dn Type=3
Dn Slope=0.005
Boundary for River Rch & Prof#=UNT 0071 IN HEWA,Reach-1,3
Up Type=0
Dn Type=3
Dn Slope=0.005
Boundary for River Rch & Prof#=UNT 0071 IN HEWA,Reach-1,4
Up Type=0
Dn Type=3
Dn Slope=0.005
Boundary for River Rch & Prof#=UNT 0071 IN HEWA,Reach-1,5
Up Type=0
Dn Type=3
Dn Slope=0.005
Boundary for River Rch & Prof#=UNT 0071 IN HEWA,Reach-1,6
Up Type=0
Dn Type=3
Dn Slope=0.005
Boundary for River Rch & Prof#=UNT 0071 IN HEWA,Reach-1,7
Up Type=0
Dn Type=3
Dn Slope=0.005

--- UNT 0071 IN HEWA.g01 (geometry) ---

Geom Title=Existing Conditions
Program Version=4.10

River Reach=UNT 0071 IN HEWA,Reach-1
Reach XY= 30
      2770168.47     10062303.73      2770166.45     10061619.44
      2769979.51     10061439.43      2769805.15     10061299.89
      2769696.03     10061180.22      2769678.02     10061108.86
      2769688.59     10060783.48      2769666.79       10060737.
      2769540.66     10060682.06      2769389.62     10060660.05
      2769172.49      10060596.5      2769064.35     10060591.75
        2768638.     10060354.86      2768443.47     10060333.45
      2768274.28     10060350.98      2768033.56     10060301.74
      2767969.31     10060271.53      2767818.13     10060245.47
      2767739.02     10060252.67       2767672.6     10060225.77
      2767573.88     10060216.25      2767448.76     10060294.34
      2767331.37     10060428.74       2767216.8     10060473.22
      2767128.41     10060436.17      2767043.22     10060463.09
      2766919.68     10060460.75      2766811.36     10060397.98
      2766678.47     10060373.73      2766608.47     10060303.73

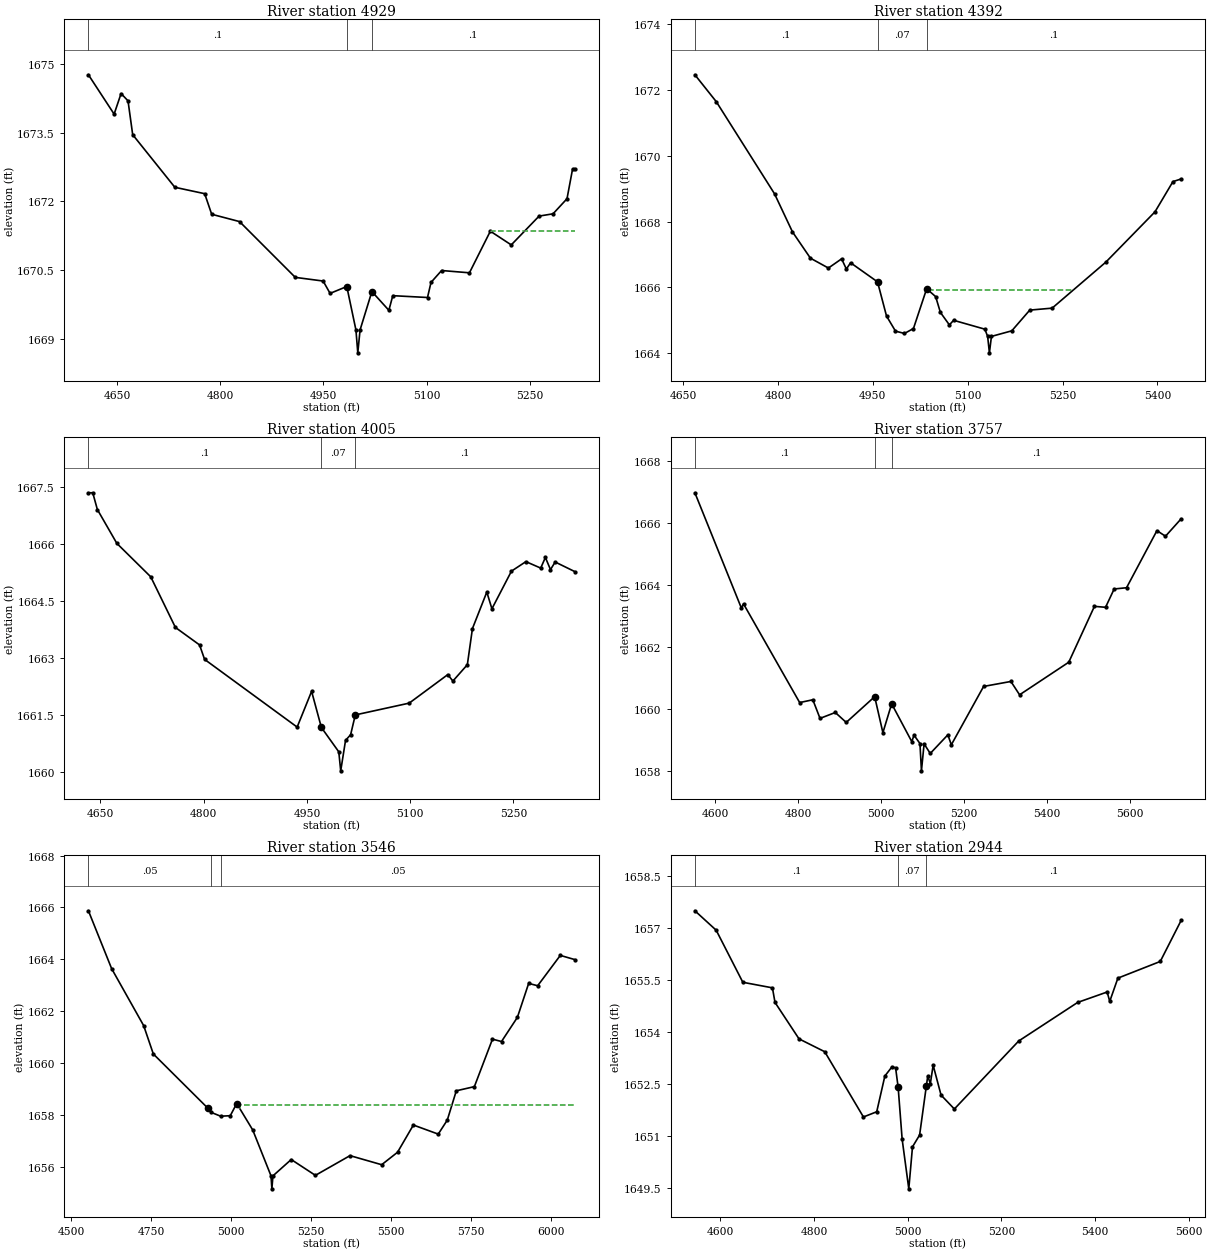
Type RM Length L Ch R = 1 ,4929    ,537,537,537
BEGIN DESCRIPTION:
UNT 0071 IN HEWA 10.0
END DESCRIPTION:
XS GIS Cut Line= 2
      2770555.35     10062038.03      2769857.49      10062152.6
#Sta/Elev= 30
  4608.1 1674.77  4645.5 1673.91  4655.6 1674.36  4665.7  1674.2  4672.5 1673.46
  4733.8 1672.31  4777.2 1672.17  4787.4 1671.72  4827.9 1671.56    4909 1670.34
  4949.5 1670.26  4959.6 1669.99  4983.9 1670.14  4997.2 1669.19  4999.9 1668.69
  5003.2 1669.19  5020.4 1670.03  5045.1 1669.62  5050.8 1669.94  5101.3  1669.9
  5106.4 1670.23  5121.8 1670.49  5162.3 1670.44  5192.7 1671.35  5223.1 1671.05
  5263.6 1671.68  5283.9 1671.73  5304.2 1672.06  5312.3 1672.71  5315.3 1672.71
#Mann= 3 , 0 , 0
  4608.1      .1       0  4983.9     .07       0  5020.4      .1       0
#XS Ineff= 2 , 0
                         5194.09         1671.36
Permanent Ineff=
       T       T
Bank Sta=4983.9,5020.4
XS Rating Curve= 0 ,0
Exp/Cntr=0.3,0.1

Type RM Length L Ch R = 1 ,4392    ,387,387,387
BEGIN DESCRIPTION:
UNT 0071 IN HEWA 9.0
END DESCRIPTION:
XS GIS Cut Line= 2
      2770378.33     10061355.71      2769806.89     10061870.01
#Sta/Elev= 30
  4668.6 1672.47  4702.5 1671.65  4794.5 1668.85  4822.9 1667.69  4851.3 1666.89
  4879.7 1666.59  4900.6 1666.87  4908.1 1666.56  4914.8 1666.75  4957.4 1666.17
  4971.6 1665.13  4985.8 1664.67    5000  1664.6  5014.2 1664.75  5035.1 1665.96
  5049.3 1665.72  5056.8 1665.24    5071 1664.86  5077.7    1665  5127.1 1664.73
  5131.5 1664.51  5134.3 1664.01  5137.5 1664.51  5169.7 1664.68  5198.1 1665.31
  5233.5 1665.37  5318.4 1666.77  5396.1  1668.3  5424.5 1669.22  5437.4  1669.3
#Mann= 3 , 0 , 0
  4668.6      .1       0  4957.4     .07       0  5035.1      .1       0
#XS Ineff= 1 ,-1
 5036.93 5267.61 1665.93
Permanent Ineff=
       T
Bank Sta=4957.4,5035.1
XS Rating Curve= 0 ,0
Exp/Cntr=0.3,0.1

Type RM Length L Ch R = 1 ,4005    ,248,248,248
BEGIN DESCRIPTION:
UNT 0071 IN HEWA 8.0
END DESCRIPTION:
XS GIS Cut Line= 2
       2770112.7     10061079.68      2769592.76     10061558.02
#Sta/Elev= 30
  4632.5 1667.35  4638.8 1667.35  4645.5 1666.91  4673.8 1666.02  4723.1 1665.14
  4758.9 1663.81    4794 1663.35  4801.3 1662.97  4935.8 1661.19  4956.8 1662.13
    4971 1661.18  4996.3 1660.54  4999.1 1660.04  5006.1 1660.84  5013.5 1660.99
  5020.3 1661.51  5098.6 1661.82  5154.7 1662.57  5162.1  1662.4  5183.1 1662.83
  5190.5 1663.78  5211.4 1664.74  5218.8  1664.3  5247.2 1665.29  5268.2 1665.54
  5289.7 1665.37  5296.5 1665.65  5303.9 1665.33  5310.7 1665.53    5339 1665.28
#Mann= 3 , 0 , 0
  4632.5      .1       0    4971     .07       0  5020.3      .1       0
Bank Sta=4971,5020.3
XS Rating Curve= 0 ,0
Exp/Cntr=0.3,0.1

Type RM Length L Ch R = 1 ,3757    ,211,211,211
BEGIN DESCRIPTION:
Mapping XS 82e8afe3
END DESCRIPTION:
XS GIS Cut Line= 4
      2770107.77     10061002.71      2769593.86     10061174.59
      2769298.72     10061377.72      2769364.33     10061640.16
#Sta/Elev= 30
  4551.8 1666.96  4663.6 1663.25  4668.9 1663.38  4804.1  1660.2  4835.8 1660.29
  4853.1 1659.69  4889.9 1659.88  4916.2 1659.56  4984.7 1660.39  5004.5 1659.23
  5025.6 1660.16  5074.1 1658.94  5079.4 1659.15  5093.7 1658.88  5097.3    1658
  5103.7 1658.87  5118.5 1658.56  5160.9 1659.16  5169.3 1658.84    5247 1660.72
  5312.7 1660.88  5333.6 1660.45    5452  1661.5  5513.8  1663.3  5540.6 1663.27
  5561.3 1663.86  5591.1  1663.9  5664.3 1665.74  5684.9 1665.56  5722.5 1666.12
#Mann= 3 , 0 , 0
  4551.8      .1       0  4984.7     .07       0  5025.6      .1       0
#XS Ineff= 1 ,-1
 5026.12 5234.72 1660.14
Permanent Ineff=
       T
Bank Sta=4984.7,5025.6
XS Rating Curve= 0 ,0
Exp/Cntr=0.3,0.1

Type RM Length L Ch R = 1 ,3546    ,602,602,602
BEGIN DESCRIPTION:
UNT 0071 IN HEWA 7.0
END DESCRIPTION:
XS GIS Cut Line= 3
       2770130.9     10060901.45      2769422.52     10060955.27
      2768844.38       10061523.
#Sta/Elev= 30
  4553.7 1665.87  4626.3 1663.64  4726.6 1661.44  4756.7 1660.35  4927.2 1658.26
  4937.2  1658.1  4967.3 1657.95  4997.4 1657.97  5017.5 1658.44  5067.6 1657.42
  5124.8 1655.65  5127.5 1655.15  5130.8 1655.65    5188 1656.28  5263.6 1655.67
  5371.9 1656.43  5470.9 1656.08  5520.5 1656.56    5570 1657.61  5647.8 1657.26
  5676.1  1657.8  5704.3 1658.93  5760.8 1659.09  5817.4 1660.92  5845.7 1660.83
  5895.3 1661.76  5930.6 1663.07  5958.8 1662.98  6029.6 1664.15  6074.4 1663.99
#Mann= 3 ,-1 , 0
  4553.7     .05       0  4937.2     .04       0  4967.3     .05       0
#XS Ineff= 2 , 0
                         5027.72         1658.37
Permanent Ineff=
       T       T
Bank Sta=4927.2,5017.5
XS Rating Curve= 0 ,0
Exp/Cntr=0.3,0.1

Type RM Length L Ch R = 1 ,2944    ,515,515,515
BEGIN DESCRIPTION:
UNT 0071 IN HEWA 6.0
END DESCRIPTION:
XS GIS Cut Line= 2
      2769484.83     10060212.17      2769047.99     10061154.11
#Sta/Elev= 30
  4545.3 1657.49  4590.8 1656.93  4647.7 1655.43  4710.9 1655.27  4716.4 1654.85
  4767.7  1653.8  4822.6 1653.43  4905.2 1651.55  4933.6  1651.7    4951 1652.73
  4965.9 1652.99  4973.9 1652.97  4979.4  1652.4  4987.9 1650.91  5002.1 1649.48
    5010 1650.69  5025.2 1651.03 5039.55 1652.44  5042.6 1652.73  5048.1 1652.51
  5054.1 1653.04    5071 1652.18  5099.4 1651.78  5236.9 1653.74  5362.7 1654.85
  5425.7 1655.15  5431.2 1654.88  5448.6 1655.55  5539.1 1656.03  5583.6 1657.21
#Mann= 3 , 0 , 0
  4545.3      .1       0  4979.4     .07       0 5039.55      .1       0
Bank Sta=4979.4,5039.55
XS Rating Curve= 0 ,0
Exp/Cntr=0.3,0.1

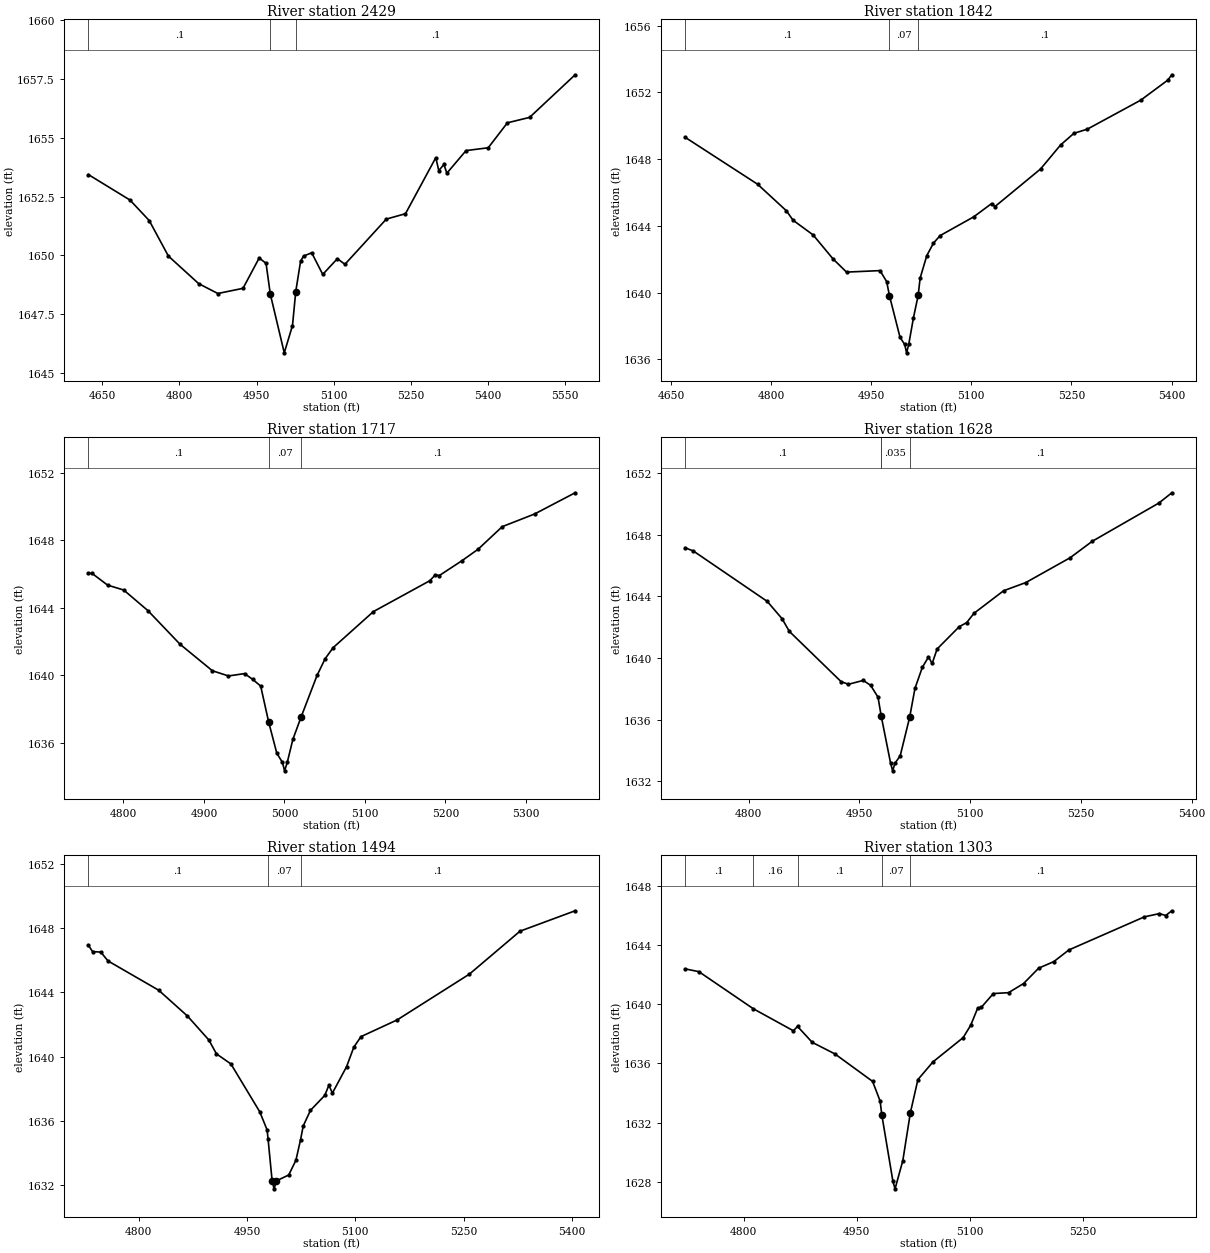
Type RM Length L Ch R = 1 ,2429    ,587,587,587
BEGIN DESCRIPTION:
UNT 0071 IN HEWA 5.0
END DESCRIPTION:
XS GIS Cut Line= 2
      2769011.57     10060134.85      2768538.35     10060953.87
#Sta/Elev= 30
  4623.2 1653.43  4703.9 1652.35  4741.3 1651.48  4778.6 1649.97  4837.4  1648.8
  4874.7 1648.38  4923.6  1648.6  4955.1 1649.89  4968.4 1649.66  4976.7 1648.35
  5003.8 1645.86  5019.8 1647.02  5026.1 1648.46  5035.5 1649.75  5041.3 1649.97
  5057.1 1650.11  5078.6 1649.19    5107 1649.86  5121.7 1649.62  5202.1 1651.54
  5239.4 1651.77  5298.3 1654.15  5304.1  1653.6  5314.1 1653.86  5319.8 1653.49
  5357.1 1654.45  5400.2 1654.57  5437.5 1655.63  5480.6 1655.86  5569.1 1657.67
#Mann= 3 , 0 , 0
  4623.2      .1       0  4976.7     .07       0  5026.1      .1       0
Bank Sta=4976.7,5026.1
XS Rating Curve= 0 ,0
Exp/Cntr=0.3,0.1

Type RM Length L Ch R = 1 ,1842    ,125,125,125
BEGIN DESCRIPTION:
UNT 0071 IN HEWA 4.0
END DESCRIPTION:
XS GIS Cut Line= 2
      2768289.76     10060022.44      2768248.18     10060750.15
#Sta/Elev= 30
  4671.4 1649.31  4779.8  1646.5  4822.9 1644.91    4833 1644.34    4863 1643.46
  4893.1 1642.01  4913.1 1641.23  4963.2 1641.32  4973.2 1640.66 4977.39 1639.81
  4993.2 1637.32  5000.2 1636.89    5003 1636.39  5006.2 1636.89  5013.3 1638.49
 5020.34 1639.83  5023.3 1640.87  5033.3 1642.22  5043.3 1642.97  5053.3 1643.42
  5103.4 1644.54  5130.4 1645.34  5135.4 1645.16  5203.6 1647.41  5233.6 1648.85
  5253.6 1649.55  5273.7  1649.8  5353.8 1651.54  5393.9 1652.73  5400.3 1653.06
#Mann= 3 , 0 , 0
  4671.4      .1       0 4977.39     .07       0 5020.34      .1       0
Bank Sta=4977.39,5020.34
XS Rating Curve= 0 ,0
Exp/Cntr=0.3,0.1

Type RM Length L Ch R = 1 ,1717    ,89,89,89
BEGIN DESCRIPTION:
Mapping XS 33041fc8
END DESCRIPTION:
XS GIS Cut Line= 2
      2768144.14     10060079.91      2768157.17     10060684.17
#Sta/Elev= 30
  4756.6 1646.04    4761 1646.04  4780.4 1645.34  4800.4 1645.05  4830.4 1643.83
  4870.4 1641.83  4910.5 1640.26  4930.5 1639.95  4950.5 1640.09  4960.5 1639.75
  4970.5 1639.35  4980.5  1637.2  4990.5 1635.37  4997.5 1634.82  5000.2 1634.32
  5003.5 1634.82  5010.5 1636.19  5020.5 1637.49  5040.5 1639.98  5050.5 1640.97
  5060.5 1641.63  5110.5 1643.77  5180.5  1645.6  5187.4 1645.95  5192.4 1645.91
  5220.5 1646.79  5240.5 1647.47  5270.5 1648.81  5310.6 1649.56    5361 1650.82
#Mann= 3 , 0 , 0
  4756.6      .1       0  4980.5     .07       0  5020.5      .1       0
Bank Sta=4980.5,5020.5
XS Rating Curve= 0 ,0
Exp/Cntr=0.3,0.1

Type RM Length L Ch R = 1 ,1628    ,134,134,134
BEGIN DESCRIPTION:
Mapping XS d8798ac1
END DESCRIPTION:
XS GIS Cut Line= 2
      2768058.21     10060022.66      2768068.62     10060681.48
#Sta/Elev= 30
  4714.2 1647.15  4725.3 1646.94  4825.3 1643.67  4845.3 1642.55  4855.3 1641.72
  4925.3 1638.46  4935.3 1638.29  4955.3 1638.54  4965.3 1638.22  4975.3 1637.45
  4979.6 1636.23  4992.3 1633.17  4995.1 1632.67  4998.3 1633.17  5005.3 1633.64
 5018.18 1636.16  5025.3 1638.02  5035.3 1639.39  5043.6 1640.06  5048.6 1639.64
  5055.3 1640.58  5085.3 1642.03  5095.3 1642.29  5105.3  1642.9  5145.3 1644.36
  5175.3 1644.89  5235.3  1646.5  5265.3 1647.57  5355.4 1650.05  5373.1 1650.72
#Mann= 4 ,-1 , 0
  4714.2      .1       0  4979.6     .05       0  4979.6    .035       0
 5018.18      .1       0
Bank Sta=4979.6,5018.18
XS Rating Curve= 0 ,0
Exp/Cntr=0.3,0.1

Type RM Length L Ch R = 1 ,1494    ,191,191,191
BEGIN DESCRIPTION:
Mapping XS 993a81dd
END DESCRIPTION:
XS GIS Cut Line= 2
      2767954.04     10059996.64      2767912.44     10060669.96
#Sta/Elev= 30
  4730.1 1646.93  4735.8 1646.54  4747.2 1646.51  4757.2 1645.96  4827.4 1644.14
  4867.4 1642.53    4897 1641.04  4907.5 1640.18  4927.6 1639.55  4967.6 1636.57
  4977.7 1635.45 4979.09 1634.88  4984.7 1632.28  4987.4 1631.78  4990.7 1632.28
  5007.7 1632.64  5017.7 1633.56 5024.09 1634.83  5027.8 1635.69  5037.8 1636.66
  5057.8  1637.6  5063.3 1638.22  5068.3 1637.74  5087.9 1639.38  5097.9 1640.59
  5107.9 1641.25    5158 1642.29  5258.2 1645.14  5328.3 1647.81  5404.7 1649.08
#Mann= 3 ,-1 , 0
  4730.1      .1       0 4979.09     .07       0 5024.09      .1       0
Bank Sta=4984.7,4990.7
XS Rating Curve= 0 ,0
Exp/Cntr=0.3,0.1

Type RM Length L Ch R = 1 ,1303    ,562,562,562
BEGIN DESCRIPTION:
UNT 0071 IN HEWA 3.0
END DESCRIPTION:
XS GIS Cut Line= 2
      2767737.68     10059975.51      2767763.67     10060620.09
#Sta/Elev= 30
  4722.5  1642.4  4740.7 1642.21  4812.9  1639.7    4866 1638.21  4871.4 1638.51
  4890.9 1637.43  4920.9 1636.65  4970.9 1634.79  4980.9 1633.46 4983.18 1632.51
  4997.9 1628.02  5000.7 1627.52    5011 1629.43    5021 1632.67    5031 1634.91
    5051 1636.11    5091 1637.75    5101 1638.59  5110.2 1639.74  5115.2 1639.81
    5131 1640.73  5151.1 1640.79  5171.1 1641.41  5191.1 1642.45  5211.1 1642.89
  5231.1 1643.68  5331.2 1645.92  5351.2 1646.14  5359.4 1646.01  5367.6 1646.33
#Mann= 5 ,-1 , 0
  4722.5      .1       0  4812.9     .16       0  4871.4      .1       0
 4983.18     .07       0    5021      .1       0
Bank Sta=4983.18,5021
XS Rating Curve= 0 ,0
Exp/Cntr=0.3,0.1

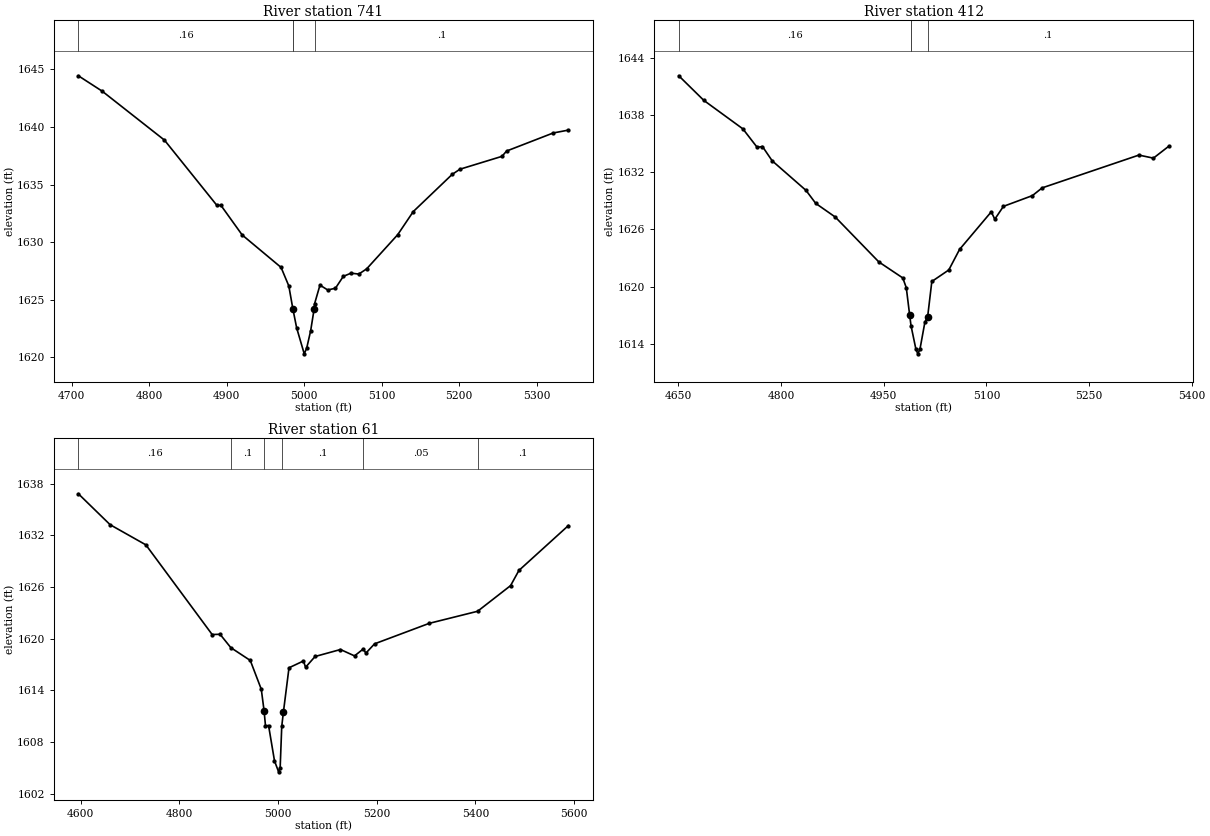
Type RM Length L Ch R = 1 ,741     ,329,329,329
BEGIN DESCRIPTION:
UNT 0071 IN HEWA 2.0
END DESCRIPTION:
XS GIS Cut Line= 2
      2767258.51     10060163.02       2767310.6     10060793.27
#Sta/Elev= 30
  4708.4 1644.45  4739.2 1643.11  4819.5 1638.86  4887.3 1633.18  4892.3  1633.2
  4919.8 1630.62    4970  1627.8    4980 1626.19 4985.17 1624.22  4990.1 1622.55
  4999.9 1620.29  5003.1 1620.79  5008.2  1622.3 5012.61 1624.16  5013.2 1624.63
  5020.2 1626.26  5030.2 1625.84  5040.2 1625.99  5050.3 1627.02  5060.3  1627.3
  5070.3 1627.22  5080.4 1627.67  5120.5 1630.64  5140.6 1632.65  5190.8 1635.88
  5200.8 1636.33  5255.1 1637.45    5261 1637.91  5321.2 1639.48  5340.8 1639.73
#Mann= 4 ,-1 , 0
  4708.4     .16       0 4985.17     .05       0 4985.17     .07       0
  5013.2      .1       0
Bank Sta=4985.17,5012.61
XS Rating Curve= 0 ,0
Exp/Cntr=0.3,0.1

Type RM Length L Ch R = 1 ,412     ,351,351,351
BEGIN DESCRIPTION:
Mapping XS 9122a710
END DESCRIPTION:
XS GIS Cut Line= 4
      2767174.22     10060187.32      2766978.04     10060416.48
        2766952.     10060579.67      2767129.06       10060755.
#Sta/Elev= 30
  4650.4 1642.11    4687 1639.53  4744.1 1636.54    4765  1634.6  4772.7 1634.69
  4786.9 1633.19  4836.3 1630.09  4850.6 1628.72  4879.1 1627.29  4942.8 1622.58
  4977.8  1620.9  4982.9 1619.87 4987.73 1617.05  4989.8 1615.89  4996.9 1613.44
  4999.7 1612.94  5002.9 1613.44    5010 1616.24 5014.09 1616.83  5020.2 1620.53
    5045 1621.74  5060.7 1623.89  5107.1 1627.84  5112.2 1627.06  5124.8 1628.41
  5167.2 1629.54  5181.4 1630.35  5322.8 1633.79    5344 1633.47  5366.5 1634.72
#Mann= 4 ,-1 , 0
  4650.4     .16       0  4989.8     .05       0  4989.8     .07       0
 5014.09      .1       0
Bank Sta=4987.73,5014.09
XS Rating Curve= 0 ,0
Exp/Cntr=0.3,0.1

Type RM Length L Ch R = 1 ,61      ,0,0,0
BEGIN DESCRIPTION:
UNT 0071 IN HEWA 1.0
END DESCRIPTION:
XS GIS Cut Line= 4
      2767000.59     10060159.54      2766660.33     10060331.41
      2766613.46     10060395.65      2766835.01     10060880.28
#Sta/Elev= 30
  4595.1 1636.83  4659.5 1633.24    4732  1630.9  4866.4 1620.49  4882.4 1620.52
  4904.2 1618.97  4943.7 1617.48    4966 1614.14  4971.6 1611.67  4974.5 1609.92
  4980.8 1609.92  4992.8 1605.82  5001.1 1604.55  5004.3 1605.05  5007.5 1609.84
 5010.91 1611.51  5022.2 1616.63  5051.5 1617.42  5055.8 1616.69  5075.1 1617.94
  5126.6 1618.75  5155.1 1618.01  5172.9 1618.82  5178.1 1618.33  5195.7 1619.41
  5306.6 1621.79  5404.6 1623.19  5471.5 1626.17  5488.4 1627.93  5588.7 1633.14
#Mann= 6 ,-1 , 0
  4595.1     .16       0  4904.2      .1       0  4971.6     .07       0
  5007.5      .1       0  5172.9     .05       0  5404.6      .1       0
Bank Sta=4971.6,5010.91
XS Rating Curve= 0 ,0
Exp/Cntr=0.3,0.1

Chan Stop Cuts=-1
Use User Specified Reach Order=0
Composite Channel Slope=5