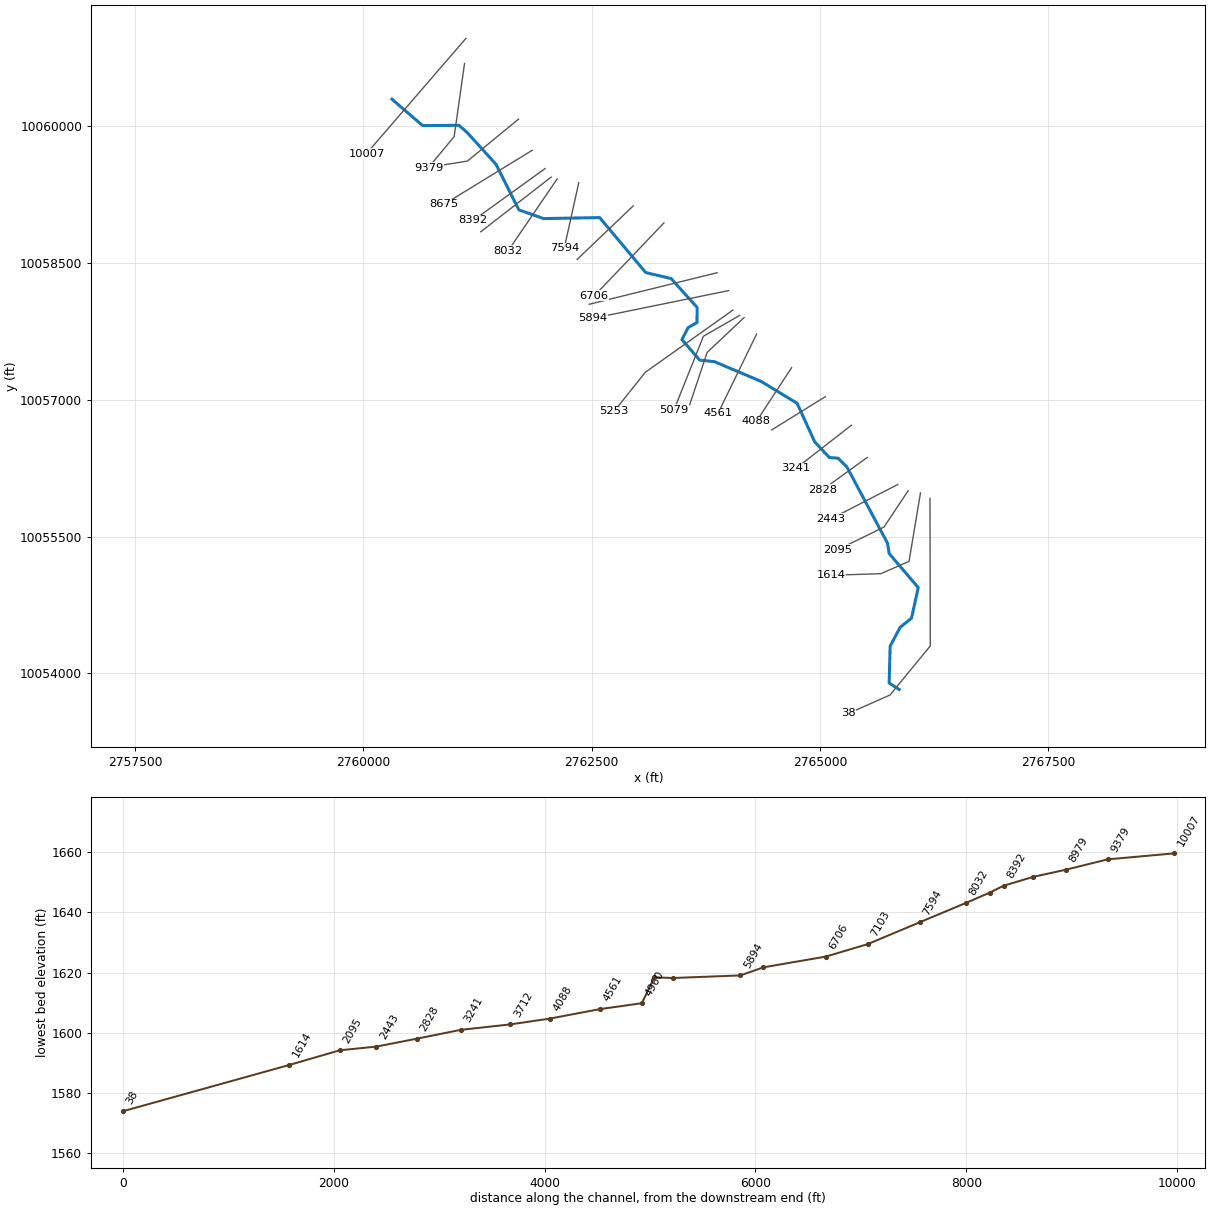
--- UNT 0072 IN HEWA.prj (project) ---

Proj Title=UNT 0072 IN HEWA Base Level Engineering
Current Plan=p01
Default Exp/Contr=0.3,0.1
English Units
Geom File=g01
Flow File=f01
Plan File=p01
Y Axis Title=Elevation
X Axis Title(PF)=Main Channel Distance
X Axis Title(XS)=Station
BEGIN DESCRIPTION:
UNT 0072 IN HEWA
END DESCRIPTION:
DSS File=dss
DSS Export Rating Curves= 0
DSS Export Rating Curve Sorted= 0
DSS Export Volume Flow Curves= 0
DXF OffsetX= 0
DXF OffsetY= 0
DXF ScaleX= 1
DXF ScaleY= 10

--- UNT 0072 IN HEWA.p01 (plan) ---

Plan Title=Multiple Run
Program Version=4.10
Short Identifier=Multiple Run
Geom File=g01
Flow File=f01
Subcritical Flow
K Sum by GR= 0
Std Step Tol= 0.01
Critical Tol= 0.01
Num of Std Step Trials= 20
Max Error Tol= 0.3
Flow Tol Ratio= 0.001
Split Flow NTrial= 30
Split Flow Tol= 0.02
Split Flow Ratio= 0.02
Log Output Level= 0
Friction Slope Method= 1
Unsteady Friction Slope Method= 2
Unsteady Bridges Friction Slope Method= 1
Parabolic Critical Depth
Global Vel Dist= 1 , 1 , 1
Global Log Level= 0
CheckData=True
Encroach Param=-1 ,0,0, 0
BEGIN DESCRIPTION:
Multiple Run
END DESCRIPTION:
Computation Interval=1HOUR
Output Interval=1HOUR
Run HTab= 0
Run UNet= 0
Run PostProcess= 0
Run WQNet= 0
UNET Theta= 1
UNET Theta Warmup= 1
UNET ZTol= 0.02
UNET ZSATol= 0.05
UNET MxIter= 20
UNET MaxInSteps= 0
UNET DtIC= 0
UNET DtMin= 0
UNET MaxCRTS= 20
UNET WFStab= 2
UNET SFStab= 1
UNET WFX= 1
UNET SFX= 1
UNET DSS MLevel= 4
UNET DZMax Abort= 100
UNET Convert EG Bridges= 0
UNET Use Existing IB Tables=-1
UNET Froude Reduction=False
UNET Froude Limit= 1
UNET Froude Power= 10
UNET Time Slicing=0,0, 5
UNET Junction Losses=0
Instantaneous Interval=1HOUR
DSS File=dss
Write IC File= 0
Write IC File at Sim End=0
Echo Input=False
Echo Parameters=False
Echo Output=False
Write Detailed= 0
WQ AD Non Conservative
WQ ULTIMATE=-1
WQ Max Comp Step=1HOUR
WQ Output Interval=15MIN
WQ Output Selected Increments= 0
WQ Output face flow=0
WQ Output face velocity=0
WQ Output face area=0
WQ Output face dispersion=0
WQ Output cell volume=0
WQ Output cell surface area=0
WQ Output cell continuity=0
WQ Output cumulative cell continuity=0
WQ Output face conc=0
WQ Output face dconc_dx=0
WQ Output face courant=0
WQ Output face peclet=0
WQ Output face adv mass=0
WQ Output face disp mass=0
WQ Output cell mass=0
WQ Output cell source sink temp=0
WQ Output cell source sink nsm=0
WQ Output MaxMinRange=-1
WQ Daily Max Min Mean=-1
WQ Daily Range=0
WQ Daily Time=0
WQ Create Restart=0
WQ Fixed Restart=0
WQ System Summary=0
WQ Use Fixed Temperature=0
Sorting and Armoring Iterations= 10
XS Update Threshold= 0.02
Hydraulics Update Threshold= 0.02
Energy Slope Method= 1
Volume Change Method= 0
XS Weighting Method= 0
Number of US Weighted Cross Sections= 1
Number of DS Weighted Cross Sections= 1
Upstream XS Weight=0.25
Main XS Weight=0.5
Downstream XS Weight=0.25
Number of DS XS's Weighted with US Boundary= 1
Upstream Boundary Weight= 1
Weight of XSs Associated with US Boundary= 0
Number of US XS's Weighted with DS Boundary= 1
Downstream Boundary Weight= 0.5
Weight of XSs Associated with DS Boundary= 0.5
Sediment Output Level= 4
Mass or Volume Output= 0
Output Increment Type= 1
Profile and TS Output Increment= 10
XS Output Flag= 0
XS Output Increment= 10
Disregard all LS=0
Disregard all Conn=0
Disregard all Breaches=0
Disregard all Pumps=0

--- UNT 0072 IN HEWA.f01 (steady flow) ---

Flow Title=Multiple
Program Version=4.10
Number of Profiles= 7
Profile Names=10-year,25-year,50-year,1pct_min,100-year,1pct_plu,500-year
River Rch & RM=UNT 0072 IN HEWA,Reach-1         ,10007
     759    1093    1381    1276    1726    2334    2709
River Rch & RM=UNT 0072 IN HEWA,Reach-1         ,4960
     918    1332    1690    1567    2120    2867    3353
Boundary for River Rch & Prof#=UNT 0072 IN HEWA,Reach-1         , 1
Up Type= 0
Dn Type= 3
Dn Slope=0.009
Boundary for River Rch & Prof#=UNT 0072 IN HEWA,Reach-1         , 2
Up Type= 0
Dn Type= 3
Dn Slope=0.009
Boundary for River Rch & Prof#=UNT 0072 IN HEWA,Reach-1         , 3
Up Type= 0
Dn Type= 3
Dn Slope=0.009
Boundary for River Rch & Prof#=UNT 0072 IN HEWA,Reach-1         , 4
Up Type= 0
Dn Type= 3
Dn Slope=0.009
Boundary for River Rch & Prof#=UNT 0072 IN HEWA,Reach-1         , 5
Up Type= 0
Dn Type= 3
Dn Slope=0.009
Boundary for River Rch & Prof#=UNT 0072 IN HEWA,Reach-1         , 6
Up Type= 0
Dn Type= 3
Dn Slope=0.009
Boundary for River Rch & Prof#=UNT 0072 IN HEWA,Reach-1         , 7
Up Type= 0
Dn Type= 3
Dn Slope=0.009
DSS Import GetInterval= 0
DSS Import GetPeak= 0
DSS Import FillOption= 0

--- UNT 0072 IN HEWA.g01 (geometry) ---

Geom Title=Existing Conditions
Program Version=4.10

River Reach=UNT 0072 IN HEWA,Reach-1
Reach XY= 30
      2760313.32     10060293.83      2760649.22     10060004.67
      2761046.45     10060007.59        2761137.     10059928.73
      2761452.45     10059581.14      2761704.23     10059080.44
      2761974.84     10058985.08      2762588.49     10058996.03
      2763092.65     10058393.74      2763370.89     10058327.35
      2763656.12     10058011.74      2763654.54     10057845.94
      2763557.93     10057789.99      2763489.11     10057658.91
      2763684.54      10057433.6      2763845.52     10057416.79
      2764357.07     10057200.33      2764751.09     10056960.38
      2764943.89      10056538.2      2765104.09     10056365.98
      2765200.54     10056357.98      2765296.91     10056262.61
      2765741.39     10055426.78      2765760.52     10055312.46
      2766078.28     10054939.47      2766004.65     10054605.71
      2765879.34     10054503.43      2765770.62      10054298.3
       2765759.3     10053893.35      2765868.47     10053823.73

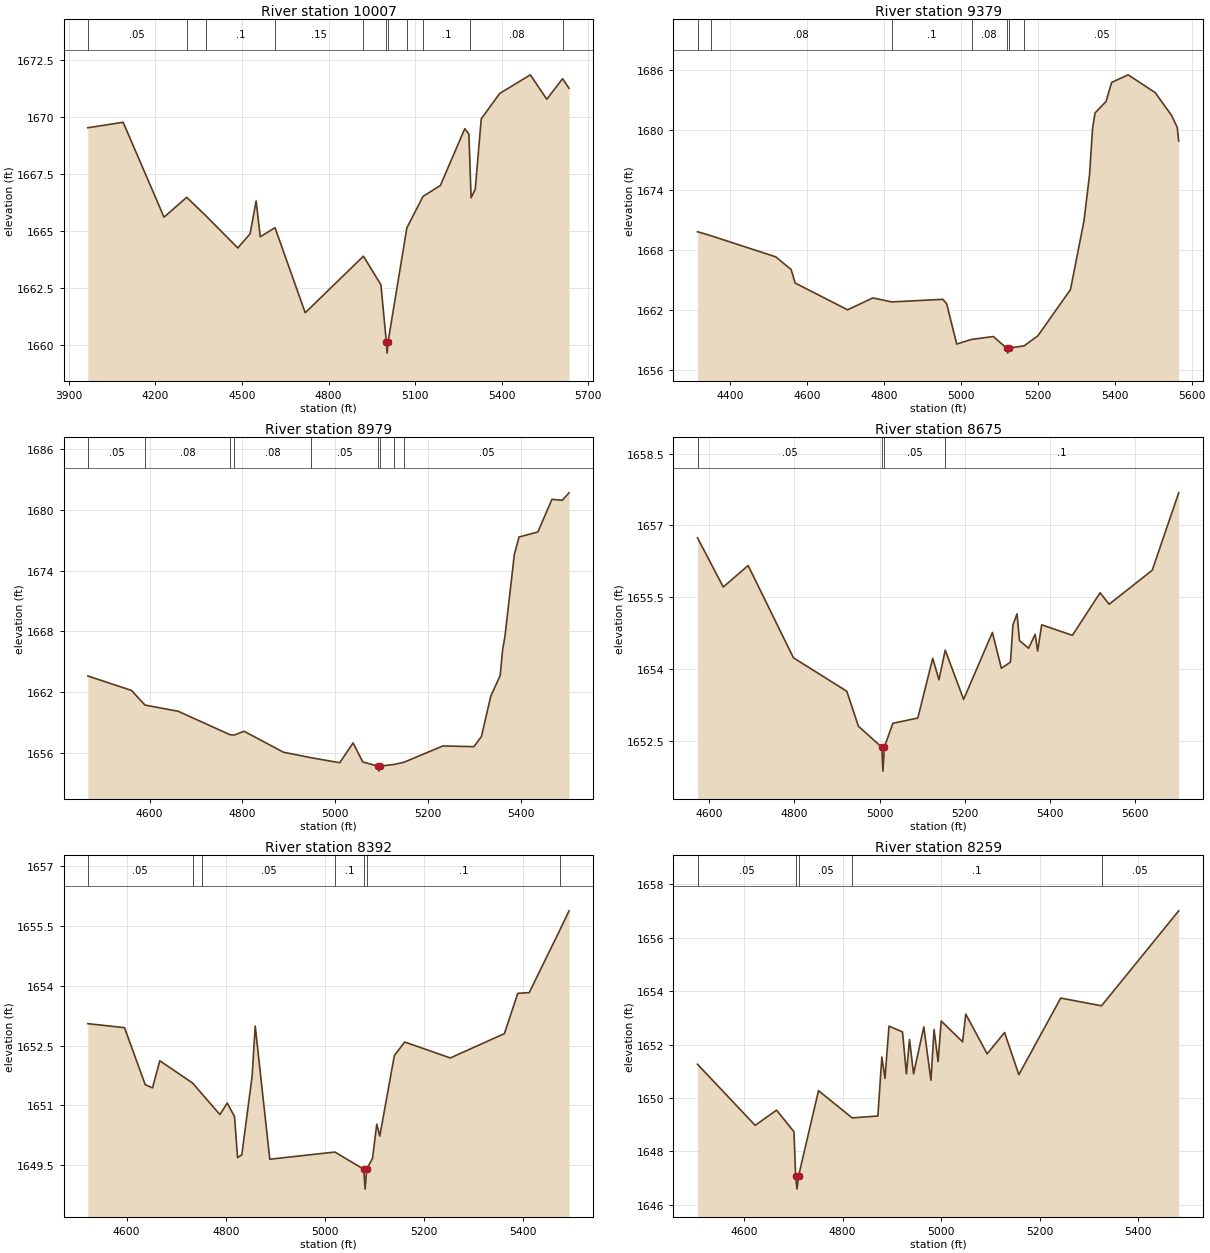
Type RM Length L Ch R = 1 ,10007   ,628,628,628
BEGIN DESCRIPTION:
UNT 0072 IN HEWA 19.0
END DESCRIPTION:
XS GIS Cut Line= 2
       2761123.7     10060960.97      2760034.91     10059698.13
#Sta/Elev= 30
  3965.7 1669.52    4088 1669.76  4229.6  1665.6  4308.2 1666.47  4376.4 1665.64
  4485.2 1664.25  4527.9 1664.87  4548.8 1666.31  4563.1 1664.74  4614.2 1665.14
  4718.9 1661.41  4920.6 1663.89  4981.1 1662.64    5000 1660.14  5002.7 1659.64
    5006 1660.14  5071.1 1665.13    5127 1666.51  5187.3 1666.99  5271.8 1669.48
    5286 1669.24  5291.5 1667.25  5293.7 1666.45    5308 1666.82  5328.8 1669.91
  5392.5 1671.02  5498.9 1671.84  5555.9 1670.77  5610.7 1671.67  5633.1 1671.25
#Mann= 11 ,-1 , 0
  3965.7     .05       0  4308.2     .08       0  4376.4      .1       0
  4614.2     .15       0  4920.6      .1       0    5000     .07       0
    5006      .1       0  5071.1     .05       0    5127      .1       0
  5291.5     .08       0  5610.7     .05       0
Bank Sta=5000,5006
XS Rating Curve= 0 ,0
Exp/Cntr=0.3,0.1

Type RM Length L Ch R = 1 ,9379    ,400,400,400
BEGIN DESCRIPTION:
UNT 0072 IN HEWA 18.0
END DESCRIPTION:
XS GIS Cut Line= 3
      2761108.35     10060685.03      2760994.59     10059884.16
      2760712.98      10059543.5
#Sta/Elev= 30
  4315.5  1669.8  4349.7 1669.41  4518.8 1667.29  4558.9 1666.02  4569.3 1664.67
  4705.7 1661.99  4771.3 1663.18  4820.5 1662.78  4953.1 1663.04  4963.2  1662.6
  4989.3 1658.57    5028 1659.03  5084.4 1659.32  5119.1 1658.16  5121.9 1657.66
  5125.1 1658.16  5164.6 1658.39  5200.5  1659.4  5285.1 1664.02  5320.3 1670.91
  5334.6 1675.49  5342.5 1680.14    5349 1681.68  5377.6 1682.83    5392 1684.73
    5435 1685.49  5505.3 1683.71  5548.3  1681.4  5562.6 1680.23  5566.4 1678.88
#Mann= 7 ,-1 , 0
  4315.5     .05       0  4349.7     .08       0  4820.5      .1       0
    5028     .08       0  5119.1     .07       0  5125.1     .08       0
  5164.6     .05       0
Bank Sta=5119.1,5125.1
XS Rating Curve= 0 ,0
Exp/Cntr=0.3,0.1

Type RM Length L Ch R = 1 ,8979    ,304,304,304
BEGIN DESCRIPTION:
UNT 0072 IN HEWA 17.0
END DESCRIPTION:
XS GIS Cut Line= 3
      2761699.93     10060075.29       2761140.2     10059615.68
      2760832.15     10059565.85
#Sta/Elev= 30
    4467  1663.6    4561 1662.17  4590.1 1660.72  4661.5 1660.11  4773.2 1657.79
  4782.4 1657.76  4803.5 1658.13  4888.2 1656.06  4947.4 1655.52  5009.5 1655.02
  5038.2 1656.98    5059  1655.1  5091.2 1654.69  5093.9 1654.19  5097.2 1654.69
  5126.5 1654.85  5147.8 1655.07  5231.6 1656.68  5298.4 1656.61  5314.6 1657.61
  5334.8 1661.62    5355 1663.64  5360.1 1666.15  5365.2  1667.5  5385.5 1675.62
  5395.6 1677.34  5436.1 1677.84  5466.5 1681.07  5488.5 1680.97  5503.3 1681.71
#Mann= 9 ,-1 , 0
    4467     .05       0  4590.1     .08       0  4773.2     .05       0
  4782.4     .08       0  4947.4     .05       0  5091.2    .035       0
  5097.2     .05       0  5126.5      .1       0  5147.8     .05       0
Bank Sta=5091.2,5097.2
XS Rating Curve= 0 ,0
Exp/Cntr=0.3,0.1

Type RM Length L Ch R = 1 ,8675    ,283,283,283
BEGIN DESCRIPTION:
UNT 0072 IN HEWA 16.0
END DESCRIPTION:
XS GIS Cut Line= 2
       2761850.1     10059734.01      2760885.34     10059142.41
#Sta/Elev= 30
  4571.9 1656.74  4632.5 1655.71    4691 1656.16  4797.5 1654.23  4923.1 1653.53
  4950.3  1652.8  5005.3 1652.36    5008 1651.86  5011.3 1652.36  5031.3 1652.86
    5090 1652.97  5125.1 1654.22  5139.7 1653.77  5154.5 1654.39  5197.8 1653.36
  5265.4 1654.76  5286.6 1654.01  5307.9 1654.14  5313.8 1654.92  5323.4 1655.15
  5329.2 1654.59  5350.5 1654.43    5366 1654.72  5371.8 1654.37  5381.4 1654.92
  5453.6  1654.7  5518.7 1655.59    5540 1655.35  5641.3 1656.06  5703.6 1657.68
#Mann= 4 ,-1 , 0
  4571.9     .05       0  5005.3    .035       0  5011.3     .05       0
  5154.5      .1       0
Bank Sta=5005.3,5011.3
XS Rating Curve= 0 ,0
Exp/Cntr=0.3,0.1

Type RM Length L Ch R = 1 ,8392    ,133,133,133
BEGIN DESCRIPTION:
Mapping XS 01d9fc4a
END DESCRIPTION:
XS GIS Cut Line= 2
      2761991.13     10059533.77      2761203.92     10058964.97
#Sta/Elev= 30
  4521.7 1653.05  4595.7 1652.95  4637.5 1651.52  4652.2 1651.44  4666.9 1652.12
  4733.2 1651.56  4751.9 1651.29  4788.3 1650.77    4803 1651.06  4817.7 1650.72
  4823.9 1649.69  4832.4 1649.76  4853.3 1651.74  4859.5 1652.99  4888.9 1649.65
  5020.3 1649.83  5078.5  1649.4  5081.3  1648.9  5084.5  1649.4  5096.2 1649.67
  5104.8 1650.53  5110.9 1650.23  5140.3 1652.25  5161.2 1652.59  5253.2 1652.19
  5362.4  1652.8  5389.4 1653.81  5412.6 1653.83  5475.6 1655.43  5492.9 1655.88
#Mann= 7 ,-1 , 0
  4521.7     .05       0  4733.2      .1       0  4751.9     .05       0
  5020.3      .1       0  5078.5    .035       0  5084.5      .1       0
  5475.6     .05       0
Bank Sta=5078.5,5084.5
XS Rating Curve= 0 ,0
Exp/Cntr=0.3,0.1

Type RM Length L Ch R = 1 ,8259    ,227,227,227
BEGIN DESCRIPTION:
Mapping XS 8e4a6424
END DESCRIPTION:
XS GIS Cut Line= 2
      2762056.87     10059439.74      2761286.02     10058840.77
#Sta/Elev= 30
  4505.8 1651.26  4622.8 1648.97  4666.2 1649.54  4701.5 1648.73  4704.9 1647.08
  4707.6 1646.58  4710.9 1647.08  4751.3 1650.27  4819.6 1649.25  4871.7 1649.32
  4879.8 1651.53  4886.2 1650.73  4894.3 1652.69  4921.7 1652.47  4929.6  1650.9
  4935.9 1652.19  4944.1  1650.9  4964.9 1652.66  4979.4 1650.66  4985.7 1652.56
  4993.9 1651.36  5000.2 1652.88  5043.6  1652.1    5050 1653.14  5093.4 1651.65
  5128.7 1652.45  5157.7 1650.87  5242.7 1653.74  5325.4 1653.45    5482 1657.01
#Mann= 5 ,-1 , 0
  4505.8     .05       0  4704.9     .07       0  4710.9     .05       0
  4819.6      .1       0  5325.4     .05       0
Bank Sta=4704.9,4710.9
XS Rating Curve= 0 ,0
Exp/Cntr=0.3,0.1

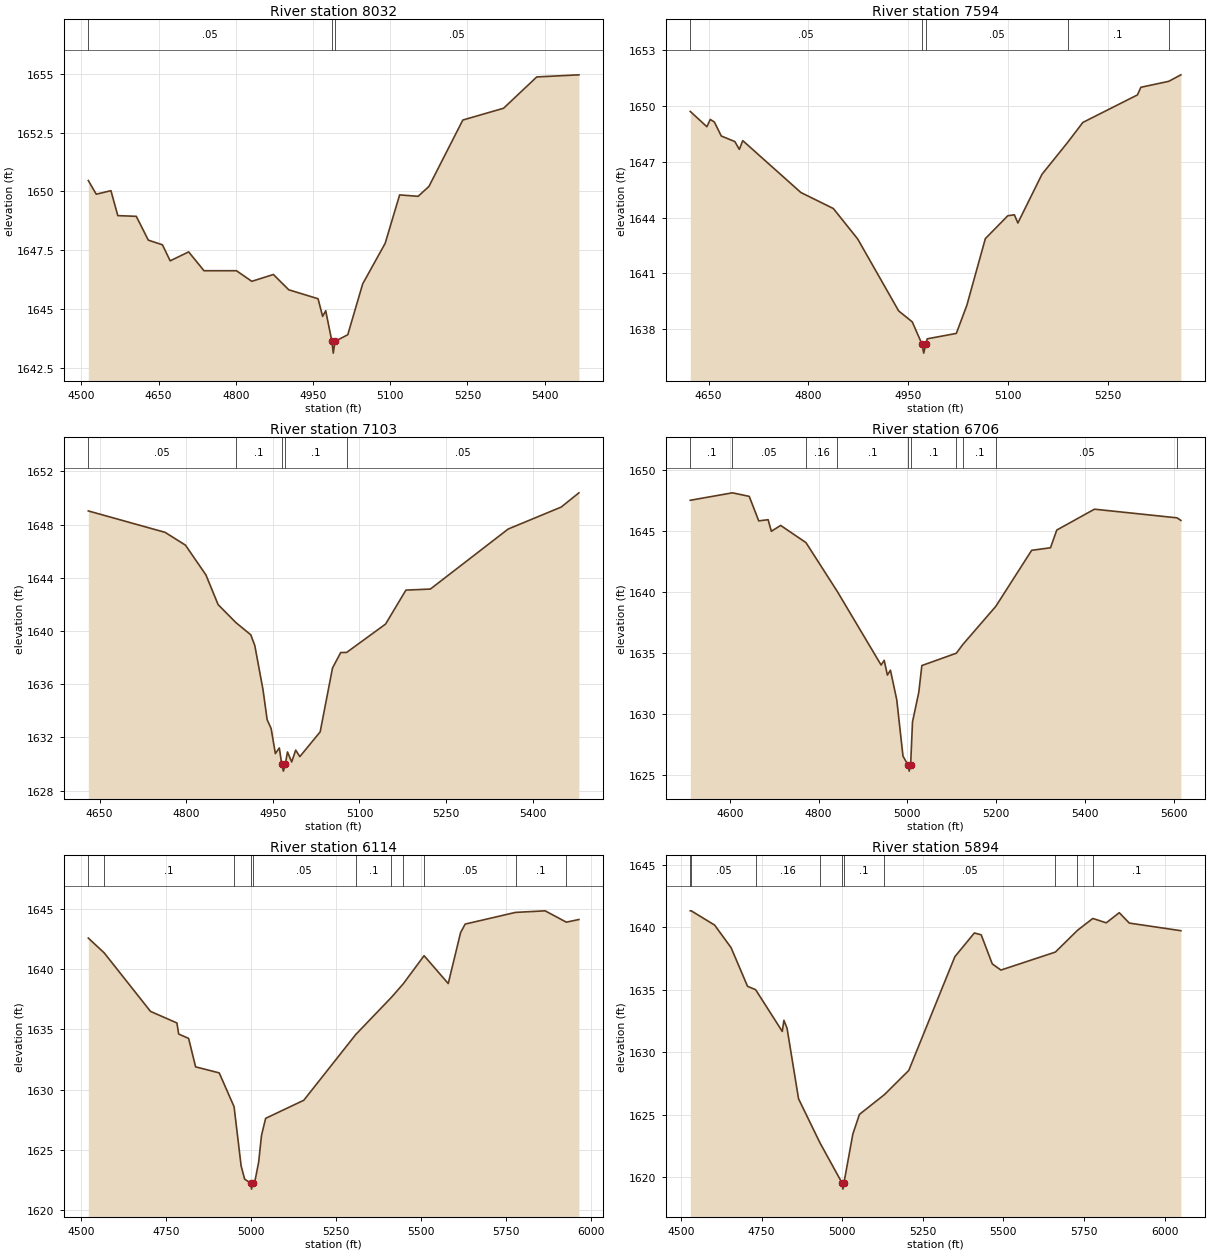
Type RM Length L Ch R = 1 ,8032    ,438,438,438
BEGIN DESCRIPTION:
UNT 0072 IN HEWA 15.0
END DESCRIPTION:
XS GIS Cut Line= 2
      2762123.09       10059420.      2761586.14     10058632.78
#Sta/Elev= 30
  4513.6 1650.46    4529 1649.88  4557.5 1650.03  4570.9 1648.97  4606.8 1648.94
  4630.1 1647.93  4657.6 1647.73  4672.6 1647.05  4708.5 1647.43  4738.3 1646.63
  4801.3 1646.63  4831.1 1646.18  4873.1 1646.47  4902.9 1645.82  4959.8 1645.44
  4968.7 1644.69  4974.7 1644.93  4986.7 1643.63  4989.4 1643.13  4992.7 1643.63
  5017.5 1643.91  5046.5 1646.07  5090.1 1647.79  5118.3 1649.85  5154.2 1649.79
  5175.2 1650.21    5241 1653.03  5320.1 1653.53  5384.6 1654.86  5466.5 1654.95
#Mann= 3 ,-1 , 0
  4513.6     .05       0  4986.7    .035       0  4992.7     .05       0
Bank Sta=4986.7,4992.7
XS Rating Curve= 0 ,0
Exp/Cntr=0.3,0.1

Type RM Length L Ch R = 1 ,7594    ,491,491,491
BEGIN DESCRIPTION:
UNT 0072 IN HEWA 14.0
END DESCRIPTION:
XS GIS Cut Line= 2
      2762359.73     10059379.09      2762200.46     10058660.12
#Sta/Elev= 30
  4622.6 1649.71  4647.5 1648.89  4652.6 1649.28  4658.8 1649.14  4669.1 1648.39
  4689.5 1648.09  4696.2 1647.67  4701.4 1648.14  4788.6 1645.35  4837.3 1644.49
  4873.9 1642.85  4935.4 1638.98  4955.8 1638.39  4970.2 1637.21    4973 1636.71
  4976.2 1637.21  4978.3 1637.48  5021.9 1637.77  5037.8 1639.29  5065.5 1642.87
  5099.2  1644.1  5109.1 1644.15  5114.3 1643.71  5150.5 1646.33  5188.9 1648.04
  5211.9 1649.12  5293.8  1650.6  5298.9 1651.01  5340.8 1651.33    5359 1651.68
#Mann= 5 ,-1 , 0
  4622.6     .05       0  4970.2    .035       0  4976.2     .05       0
  5188.9      .1       0  5340.8     .05       0
Bank Sta=4970.2,4976.2
XS Rating Curve= 0 ,0
Exp/Cntr=0.3,0.1

Type RM Length L Ch R = 1 ,7103    ,397,397,397
BEGIN DESCRIPTION:
UNT 0072 IN HEWA 13.0
END DESCRIPTION:
XS GIS Cut Line= 2
       2762955.8     10059124.21      2762341.55     10058537.25
#Sta/Elev= 30
  4630.4 1649.02  4763.4 1647.41  4798.6 1646.45  4834.1 1644.21  4855.2 1641.98
    4886 1640.63  4911.8 1639.71  4918.7 1638.91  4932.9 1635.59  4940.1 1633.33
    4947 1632.67  4954.3 1630.79  4961.2 1631.21  4965.4 1629.97  4968.2 1629.47
  4971.4 1629.97  4975.3 1630.91  4982.6 1630.16  4989.5 1631.05  4996.7 1630.56
  5031.9 1632.42  5053.3 1637.22  5067.5 1638.38  5077.8 1638.39  5145.2 1640.52
  5180.4 1643.07  5222.8 1643.15  5357.5 1647.66  5449.3 1649.31    5480 1650.38
#Mann= 5 ,-1 , 0
  4630.4     .05       0    4886      .1       0  4965.4     .07       0
  4971.4      .1       0  5077.8     .05       0
Bank Sta=4965.4,4971.4
XS Rating Curve= 0 ,0
Exp/Cntr=0.3,0.1

Type RM Length L Ch R = 1 ,6706    ,592,592,592
BEGIN DESCRIPTION:
UNT 0072 IN HEWA 12.0
END DESCRIPTION:
XS GIS Cut Line= 2
       2763292.6      10058937.7        2762529.     10058137.74
#Sta/Elev= 30
  4510.6 1647.52  4605.6 1648.13  4643.5 1647.84  4664.9 1645.83    4686 1645.93
  4693.3 1644.98  4714.3 1645.46  4771.4 1644.05    4842 1640.05  4940.8 1634.02
  4947.7 1634.41  4954.9  1633.2  4961.8  1633.6    4976 1631.18  4990.1 1626.56
  5001.3 1625.83  5004.1 1625.33  5007.3 1625.83  5011.5 1629.36  5025.7 1631.79
  5032.6 1633.98  5110.3 1634.99  5125.1 1635.71  5199.3 1638.83  5280.1 1643.42
  5322.6 1643.63  5336.7 1645.08  5421.7 1646.79  5607.9 1646.08  5616.5 1645.87
#Mann= 10 ,-1 , 0
  4510.6      .1       0  4605.6     .05       0  4771.4     .16       0
    4842      .1       0  5001.3     .07       0  5007.3      .1       0
  5110.3     .05       0  5125.1      .1       0  5199.3     .05       0
  5607.9      .1       0
Bank Sta=5001.3,5007.3
XS Rating Curve= 0 ,0
Exp/Cntr=0.3,0.1

Type RM Length L Ch R = 1 ,6114    ,220,220,220
BEGIN DESCRIPTION:
UNT 0072 IN HEWA 11.0
END DESCRIPTION:
XS GIS Cut Line= 2
      2763874.99      10058391.6      2762473.52     10058045.79
#Sta/Elev= 30
  4521.2 1642.57    4568 1641.34  4704.2 1636.49  4781.9 1635.53  4787.1 1634.61
  4816.3 1634.25  4836.9 1631.89  4906.4 1631.39  4950.1 1628.58  4970.8 1623.68
  4981.1 1622.58  4998.7 1622.25  5001.5 1621.75  5004.7 1622.25    5012  1622.5
  5022.3 1623.97  5030.8 1626.21  5042.9 1627.62  5155.2 1629.12    5308 1634.57
  5413.2 1637.66  5447.9 1638.78  5509.1 1641.11  5580.2  1638.8  5616.5 1643.02
    5630 1643.73  5778.2  1644.7  5865.3 1644.83  5927.7 1643.89  5964.7 1644.11
#Mann= 11 ,-1 , 0
  4521.2     .05       0    4568      .1       0  4950.1     .05       0
  4998.7     .04       0  5004.7     .05       0    5308      .1       0
  5413.2     .05       0  5447.9      .1       0  5509.1     .05       0
  5778.2      .1       0  5927.7     .05       0
Bank Sta=4998.7,5004.7
XS Rating Curve= 0 ,0
Exp/Cntr=0.3,0.1

Type RM Length L Ch R = 1 ,5894    ,641,641,641
BEGIN DESCRIPTION:
UNT 0072 IN HEWA 10.0
END DESCRIPTION:
XS GIS Cut Line= 2
      2764002.48     10058195.95      2762511.67     10057891.42
#Sta/Elev= 30
    4529 1641.33    4532 1641.33  4604.5 1640.19  4655.6 1638.38  4706.6 1635.29
  4731.7 1635.02  4814.3 1631.68  4819.4 1632.57  4829.1 1631.94  4864.8 1626.29
  4931.3 1622.76  4999.6 1619.56  5002.3 1619.06  5005.6 1619.56  5033.2 1623.47
  5053.6 1625.04    5131 1626.62  5206.7 1628.56  5349.6 1637.66  5410.1 1639.56
  5431.3 1639.41  5465.7 1637.08  5492.5 1636.59  5661.4 1638.03  5729.9 1639.77
  5777.5 1640.72  5819.2 1640.37  5859.5 1641.18  5890.6 1640.35  6050.6 1639.74
#Mann= 10 ,-1 , 0
    4529      .1       0    4532     .05       0  4731.7     .16       0
  4931.3      .1       0  4999.6     .07       0  5005.6      .1       0
    5131     .05       0  5661.4      .1       0  5729.9     .16       0
  5777.5      .1       0
Bank Sta=4999.6,5005.6
XS Rating Curve= 0 ,0
Exp/Cntr=0.3,0.1

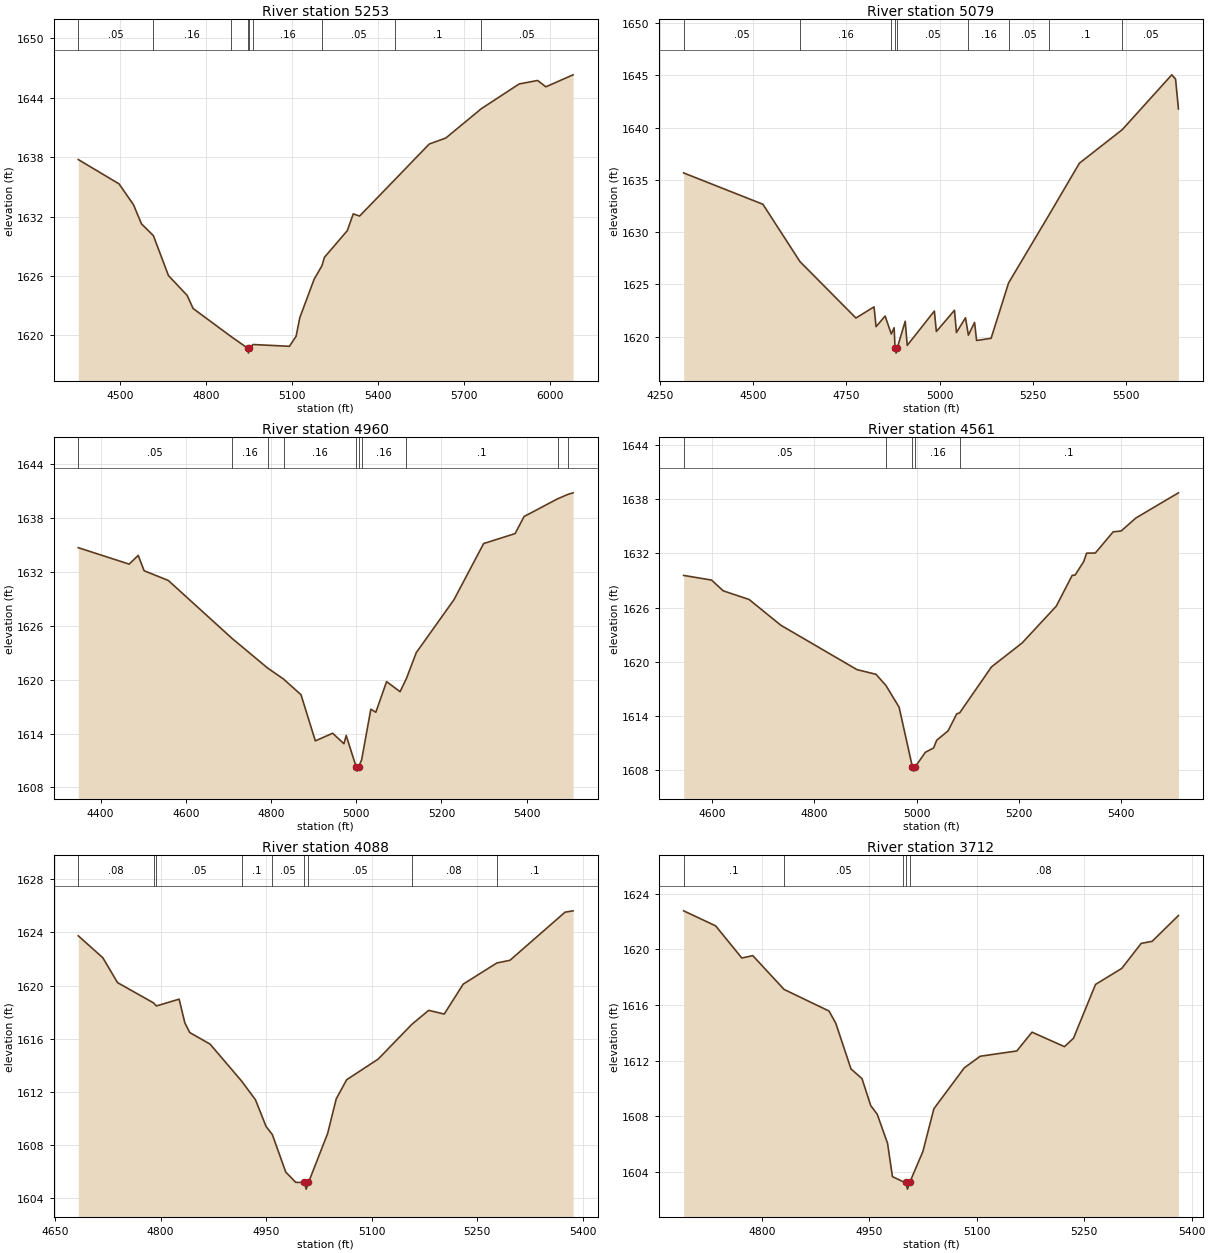
Type RM Length L Ch R = 1 ,5253    ,174,174,174
BEGIN DESCRIPTION:
UNT 0072 IN HEWA 8.0
END DESCRIPTION:
XS GIS Cut Line= 3
      2764047.97     10057982.09       2763087.8      10057299.5
       2762746.5     10056871.75
#Sta/Elev= 30
  4355.6 1637.76  4497.8  1635.3  4548.2 1633.19  4575.8 1631.27  4617.5 1630.07
    4670 1626.04  4735.2 1624.03    4756 1622.71  4889.2 1619.86  4946.1  1618.7
  4948.9  1618.2  4952.1  1618.7  4964.9 1619.07  5091.8 1618.89  5115.2 1619.91
    5128 1621.78  5177.9 1625.66  5205.5 1627.05  5213.8 1627.88  5293.5 1630.57
  5314.4 1632.27  5336.5 1632.05  5459.2 1635.72  5579.4 1639.33  5636.9 1639.93
  5761.5 1642.91  5893.1  1645.4  5957.2 1645.75    5986 1645.11  6080.9 1646.32
#Mann= 9 ,-1 , 0
  4355.6     .05       0  4617.5     .16       0  4889.2     .05       0
  4946.1     .07       0  4952.1     .05       0  4964.9     .16       0
  5205.5     .05       0  5459.2      .1       0  5761.5     .05       0
Bank Sta=4946.1,4952.1
XS Rating Curve= 0 ,0
Exp/Cntr=0.3,0.1

Type RM Length L Ch R = 1 ,5079    ,119,119,119
BEGIN DESCRIPTION:
Mapping XS 49026b7d
END DESCRIPTION:
XS GIS Cut Line= 3
      2764120.78     10057922.93      2763724.86     10057695.39
      2763402.44     10056887.07
#Sta/Elev= 30
  4313.7 1635.67  4526.3 1632.67  4625.9 1627.17  4775.8 1621.78  4824.3 1622.85
  4829.7 1620.95    4854 1621.97  4870.6 1620.25  4878.2 1620.85  4880.6 1618.92
  4883.4 1618.42  4886.6 1618.92  4907.9 1621.47  4913.3 1619.16  4986.1 1622.45
  4991.4 1620.49    5040 1622.52  5045.3 1620.39  5069.6 1621.81  5077.3 1620.14
  5093.9 1621.36  5099.3 1619.63  5138.2 1619.84  5185.1 1625.14  5292.9 1631.61
    5375  1636.6  5489.9 1639.81  5622.7 1645.06  5632.9 1644.65  5640.6  1641.8
#Mann= 9 ,-1 , 0
  4313.7     .05       0  4625.9     .16       0  4870.6     .05       0
  4880.6    .033       0  4886.6     .05       0  5077.3     .16       0
  5185.1     .05       0  5292.9      .1       0  5489.9     .05       0
Bank Sta=4880.6,4886.6
XS Rating Curve= 0 ,0
Exp/Cntr=0.3,0.1

Type RM Length L Ch R = 1 ,4960    ,399,399,399
BEGIN DESCRIPTION:
Mapping XS e700537a
END DESCRIPTION:
XS GIS Cut Line= 3
      2764170.78     10057900.14      2763765.81     10057517.92
       2763574.7      10056944.6
#Sta/Elev= 30
  4347.8  1634.7  4467.1 1632.87  4488.5 1633.84  4502.3 1632.13    4559 1631.05
  4708.8 1624.59  4792.5 1621.28  4829.4 1620.07  4870.5 1618.32  4904.1 1613.18
  4944.8 1614.03  4971.2 1612.86  4976.5 1613.78  4999.8 1610.31  5002.6 1609.81
  5005.8 1610.31  5012.7 1611.06  5034.4 1616.71  5046.1 1616.37  5071.3 1619.78
  5102.9 1618.66  5117.9 1620.13    5141 1623.01  5229.4  1628.9  5299.1 1635.16
  5372.9 1636.27    5394 1638.17  5472.5 1640.14  5497.6 1640.65    5509 1640.81
#Mann= 10 ,-1 , 0
  4347.8     .05       0  4708.8     .16       0  4792.5     .05       0
  4829.4     .16       0  4999.8     .07       0  5005.8     .16       0
  5012.7     .16       0  5117.9      .1       0  5472.5     .05       0
  5497.6      .1       0
Bank Sta=4999.8,5005.8
XS Rating Curve= 0 ,0
Exp/Cntr=0.3,0.1

Type RM Length L Ch R = 1 ,4561    ,473,473,473
BEGIN DESCRIPTION:
UNT 0072 IN HEWA 7.0
END DESCRIPTION:
XS GIS Cut Line= 2
      2764307.33     10057718.17      2763884.13     10056849.02
#Sta/Elev= 30
    4545 1629.56  4599.7 1629.04  4622.3 1627.85  4672.9 1626.89    4735 1624.03
  4883.6 1619.11  4920.9 1618.59  4940.1 1617.36    4966 1614.94  4991.8 1608.35
  4994.6 1607.85  4997.8 1608.35  5017.1 1609.93  5033.5 1610.43  5039.3 1611.27
  5061.7 1612.32  5078.7 1614.22  5084.1  1614.3  5146.4 1619.41  5206.2 1622.06
  5272.9 1626.14  5304.2 1629.57  5309.7 1629.59  5326.7  1631.1  5332.3 1632.03
  5349.3 1632.04  5384.1 1634.39  5399.9 1634.49  5428.6 1635.93  5511.7 1638.72
#Mann= 5 ,-1 , 0
    4545     .05       0  4940.1     .16       0  4991.8     .07       0
  4997.8     .16       0  5084.1      .1       0
Bank Sta=4991.8,4997.8
XS Rating Curve= 0 ,0
Exp/Cntr=0.3,0.1

Type RM Length L Ch R = 1 ,4088    ,376,376,376
BEGIN DESCRIPTION:
UNT 0072 IN HEWA 6.0
END DESCRIPTION:
XS GIS Cut Line= 2
      2764690.79      10057350.5      2764305.38     10056761.97
#Sta/Elev= 30
  4682.9 1623.74  4717.7  1622.1  4738.8 1620.22  4789.9  1618.7    4794 1618.47
  4826.3 1618.98  4834.4  1617.2  4841.4 1616.47  4870.3  1615.6    4915 1612.83
  4934.8 1611.42  4949.9 1609.41  4958.8  1608.8  4977.9 1605.98  4992.1 1605.21
  5004.2  1605.2  5006.9  1604.7  5010.2  1605.2  5037.4 1608.88  5049.6 1611.48
  5064.4 1612.92  5109.4 1614.48    5157 1617.08  5181.1 1618.14  5203.2 1617.86
  5230.2 1620.11    5278  1621.7  5296.6  1621.9    5375 1625.52  5386.4 1625.62
#Mann= 9 ,-1 , 0
  4682.9     .08       0  4789.9      .1       0    4794     .05       0
    4915      .1       0  4958.8     .05       0  5004.2    .035       0
  5010.2     .05       0    5157     .08       0    5278      .1       0
Bank Sta=5004.2,5010.2
XS Rating Curve= 0 ,0
Exp/Cntr=0.3,0.1

Type RM Length L Ch R = 1 ,3712    ,471,471,471
BEGIN DESCRIPTION:
UNT 0072 IN HEWA 5.0
END DESCRIPTION:
XS GIS Cut Line= 2
      2765060.56     10057032.79      2764473.14      10056668.9
#Sta/Elev= 30
  4690.6 1622.77  4735.3 1621.69  4771.9 1619.38  4787.2 1619.55  4830.9 1617.12
  4893.6 1615.57  4903.1 1614.69  4924.3 1611.41  4939.7 1610.71  4951.9 1608.77
  4960.9 1608.16  4975.4 1606.06  4982.2 1603.67  4996.8 1603.31  5000.5 1603.27
  5003.2 1602.77  5006.5 1603.27  5024.7 1605.47  5040.1 1608.55  5082.6 1611.49
  5104.8 1612.32  5155.9  1612.7  5177.1 1614.05  5222.4 1613.01    5235 1613.61
  5265.8 1617.48  5302.4 1618.63  5329.6 1620.43  5344.9 1620.58  5381.6 1622.43
#Mann= 5 ,-1 , 0
  4690.6      .1       0  4830.9     .05       0  4996.8     .08       0
  5000.5     .07       0  5006.5     .08       0
Bank Sta=5000.5,5006.5
XS Rating Curve= 0 ,0
Exp/Cntr=0.3,0.1

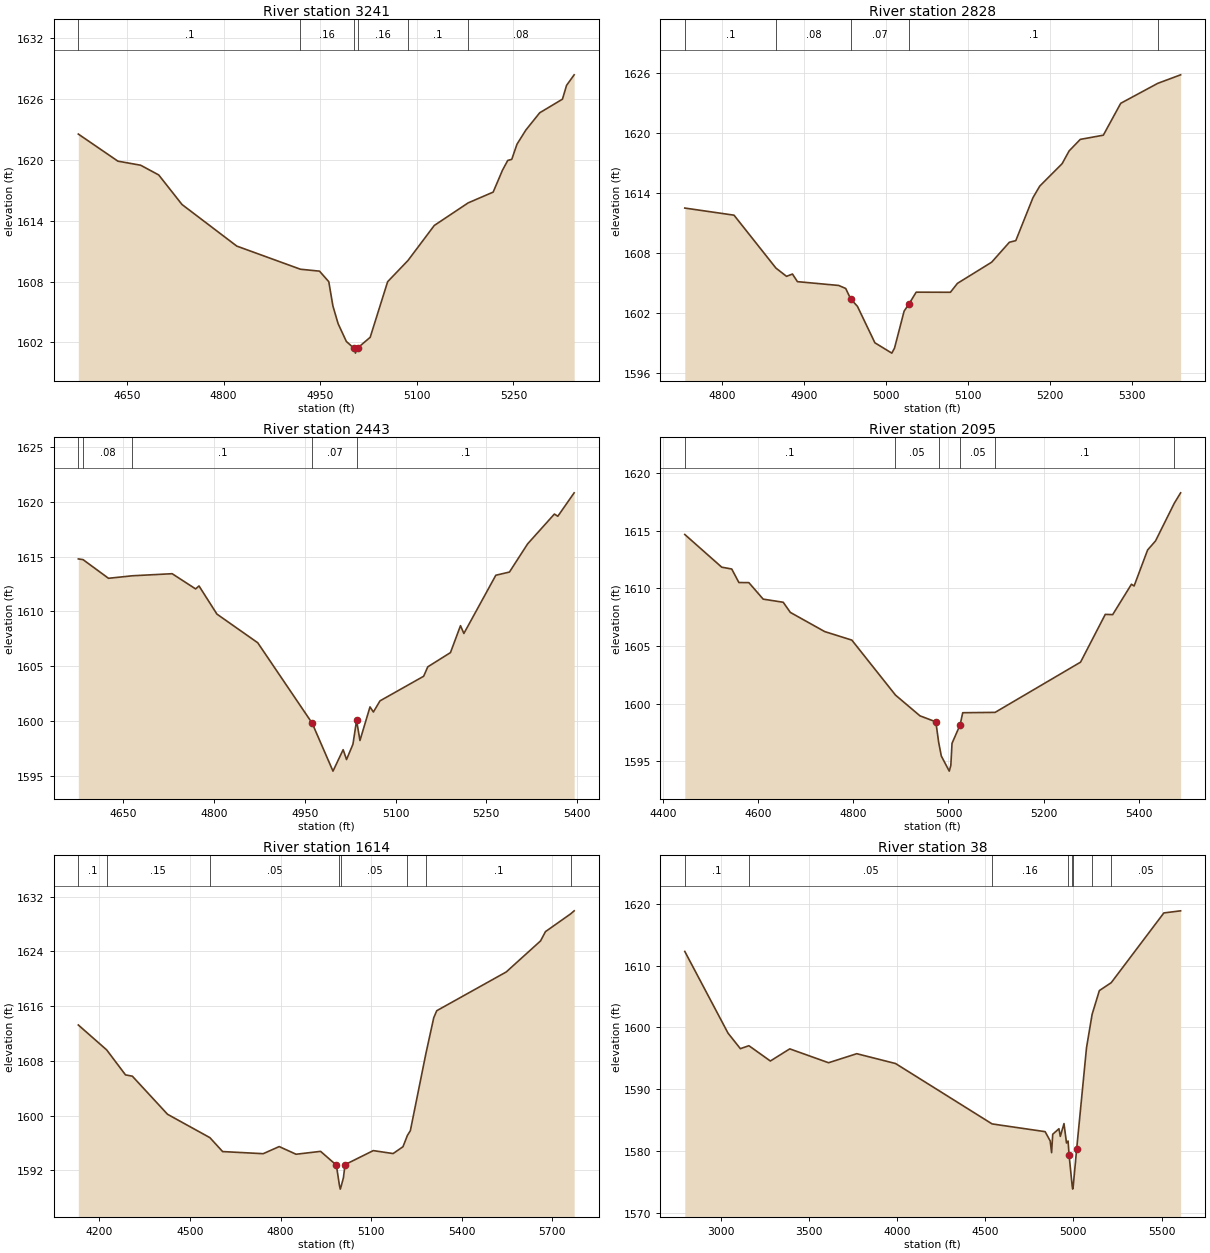
Type RM Length L Ch R = 1 ,3241    ,413,413,413
BEGIN DESCRIPTION:
UNT 0072 IN HEWA 4.0
END DESCRIPTION:
XS GIS Cut Line= 2
      2765347.05     10056720.31      2764739.17     10056247.52
#Sta/Elev= 30
  4574.3 1622.54  4635.8 1619.87  4671.1 1619.47  4699.2 1618.51  4735.3  1615.6
  4820.4  1611.5  4919.2 1609.22  4948.9 1609.03  4963.3 1607.99  4969.7  1605.6
  4977.8 1603.85  4990.6  1602.1    5002 1601.45  5004.7 1600.95    5008 1601.45
  5027.6 1602.51  5054.7 1607.99  5086.3 1610.08  5127.1 1613.53  5179.8 1615.76
  5218.6 1616.82    5233 1618.97  5241.2 1619.94  5247.5 1620.05  5255.6 1621.54
  5269.3 1622.93  5290.9 1624.64  5326.2 1625.98  5332.6 1627.34  5344.4 1628.38
#Mann= 6 ,-1 , 0
  4574.3      .1       0  4919.2     .16       0    5002     .07       0
    5008     .16       0  5086.3      .1       0  5179.8     .08       0
Bank Sta=5002,5008
XS Rating Curve= 0 ,0
Exp/Cntr=0.3,0.1

Type RM Length L Ch R = 1 ,2828    ,385,385,385
BEGIN DESCRIPTION:
UNT 0072 IN HEWA 3.0
END DESCRIPTION:
XS GIS Cut Line= 2
      2765518.95     10056366.16      2765029.34     10056011.97
#Sta/Elev= 30
    4755  1612.5    4815 1611.79  4866.1 1606.51    4879 1605.69  4886.2 1605.92
  4892.3 1605.16  4942.6 1604.78  4951.1 1604.48  4957.3 1603.42  4965.4  1602.7
  4986.7 1599.06  5007.3 1598.03  5010.6 1598.53  5022.3 1602.22  5028.5 1602.97
    5037 1604.11  5078.7  1604.1  5087.3 1604.99    5129  1607.1  5150.6 1609.09
  5158.4 1609.25  5179.3 1613.53  5187.6 1614.69  5214.9 1616.93  5223.4  1618.2
    5237 1619.35  5265.1 1619.77  5286.3 1622.95  5331.4 1624.94  5359.3 1625.79
#Mann= 5 ,-1 , 0
    4755      .1       0  4866.1     .08       0  4957.3     .07       0
  5028.5      .1       0  5331.4     .08       0
Bank Sta=4957.3,5028.5
XS Rating Curve= 0 ,0
Exp/Cntr=0.3,0.1

Type RM Length L Ch R = 1 ,2443    ,348,348,348
BEGIN DESCRIPTION:
UNT 0072 IN HEWA 2.0
END DESCRIPTION:
XS GIS Cut Line= 2
      2765852.24     10056069.26      2765123.29     10055694.37
#Sta/Elev= 30
  4575.5 1614.79  4583.2 1614.73  4625.4 1613.02  4664.9 1613.25  4730.6 1613.44
  4769.4 1612.05    4775 1612.32  4804.6 1609.75  4872.1 1607.13  4962.1 1599.78
  4996.5  1595.4  5013.3 1597.36  5018.9 1596.46  5029.5 1597.86  5035.5 1600.03
  5041.1  1598.2  5057.7 1601.27  5063.3  1600.8  5074.2 1601.82  5146.4 1604.07
  5153.2 1604.93  5190.7 1606.23  5207.3 1608.69  5212.9 1607.98  5265.7  1613.3
  5288.2 1613.59  5318.2 1616.16  5362.5 1618.89  5368.2 1618.69  5395.2 1620.83
#Mann= 5 ,-1 , 0
  4575.5      .1       0  4583.2     .08       0  4664.9      .1       0
  4962.1     .07       0  5035.5      .1       0
Bank Sta=4962.1,5035.5
XS Rating Curve= 0 ,0
Exp/Cntr=0.3,0.1

Type RM Length L Ch R = 1 ,2095    ,481,481,481
BEGIN DESCRIPTION:
Mapping XS 2353e9b7
END DESCRIPTION:
XS GIS Cut Line= 3
      2765967.53     10056001.71      2765702.79     10055603.19
      2765196.12     10055355.54
#Sta/Elev= 30
  4445.7 1614.66  4523.3 1611.83  4544.4 1611.67  4559.4  1610.5  4580.4 1610.49
  4610.5 1609.06  4652.6 1608.79  4667.6 1607.91  4739.8 1606.25  4796.9 1605.51
  4888.6 1600.75  4940.1 1598.95  4973.5 1598.43  4979.4 1596.66    4985 1595.47
  5001.7 1594.16    5005 1594.66  5007.5 1596.57  5024.5 1598.17    5030 1599.22
  5098.1 1599.25  5277.7  1603.6  5329.7 1607.74  5345.3 1607.72  5384.7 1610.35
  5390.3  1610.2  5418.7 1613.32  5435.3  1614.1  5474.8 1617.37  5488.1 1618.27
#Mann= 6 ,-1 , 0
  4445.7      .1       0  4888.6     .05       0  4979.4     .04       0
  5024.5     .05       0  5098.1      .1       0  5474.8     .05       0
Bank Sta=4973.5,5024.5
XS Rating Curve= 0 ,0
Exp/Cntr=0.3,0.1

Type RM Length L Ch R = 1 ,1614    ,1576,1576,1576
BEGIN DESCRIPTION:
Mapping XS 1e7035e7
END DESCRIPTION:
XS GIS Cut Line= 4
      2766102.46     10055977.88      2765977.47     10055227.92
      2765668.44      10055092.5      2765123.42     10055075.15
#Sta/Elev= 30
    4130 1613.25    4224 1609.61  4286.3 1605.96    4309 1605.77  4425.6  1600.2
  4566.1 1596.78  4608.1 1594.75  4742.5 1594.44  4795.6 1595.48  4851.4 1594.36
  4932.8 1594.78    4985 1592.77  4995.4 1589.76  4998.1 1589.26  5001.4 1589.76
  5008.4 1590.91  5013.8 1592.84  5107.3 1594.89  5173.1 1594.46  5205.8 1595.46
  5220.4 1597.11  5230.2  1597.8  5281.7 1609.07  5307.7 1614.31  5317.7 1615.34
  5547.8    1621  5661.6 1625.54  5677.9  1626.9  5761.5  1629.5    5773 1629.94
#Mann= 8 ,-1 , 0
    4130      .1       0    4224     .15       0  4566.1     .05       0
  4995.4    .035       0  5001.4     .05       0  5220.4     .16       0
  5281.7      .1       0  5761.5     .05       0
Bank Sta=4985,5013.8
XS Rating Curve= 0 ,0
Exp/Cntr=0.3,0.1

Type RM Length L Ch R = 1 ,38      ,0,0,0
BEGIN DESCRIPTION:
UNT 0072 IN HEWA 1.0
END DESCRIPTION:
XS GIS Cut Line= 4
      2766206.64     10055918.86      2766210.11     10054300.84
      2765769.14     10053762.64      2765314.23     10053561.23
#Sta/Elev= 30
  2796.8 1612.27  3041.9 1599.08  3111.9 1596.57  3160.3 1597.05  3281.9 1594.58
  3391.9 1596.54  3611.9  1594.3  3771.9 1595.76  3991.9 1594.17  4539.2 1584.42
  4839.9 1583.17  4868.6 1581.67  4876.5 1579.78  4882.9 1582.75  4918.1 1583.64
    4926 1582.41  4946.8 1584.47  4961.1 1581.34    4970 1581.66  4975.5 1579.45
  4993.3 1574.39  4996.1 1573.89  4999.3 1574.39  5018.6 1580.35  5074.5 1596.72
  5106.2 1602.11  5147.3 1605.95  5214.7 1607.23    5513 1618.49  5608.1 1618.83
#Mann= 8 ,-1 , 0
  2796.8      .1       0  3160.3     .05       0  4539.2     .16       0
    4970     .05       0  4993.3    .035       0  4999.3     .05       0
  5106.2      .1       0  5214.7     .05       0
Bank Sta=4975.5,5018.6
XS Rating Curve= 0 ,0
Exp/Cntr=0.3,0.1

Chan Stop Cuts=-1
Use User Specified Reach Order=0
Composite Channel Slope=5