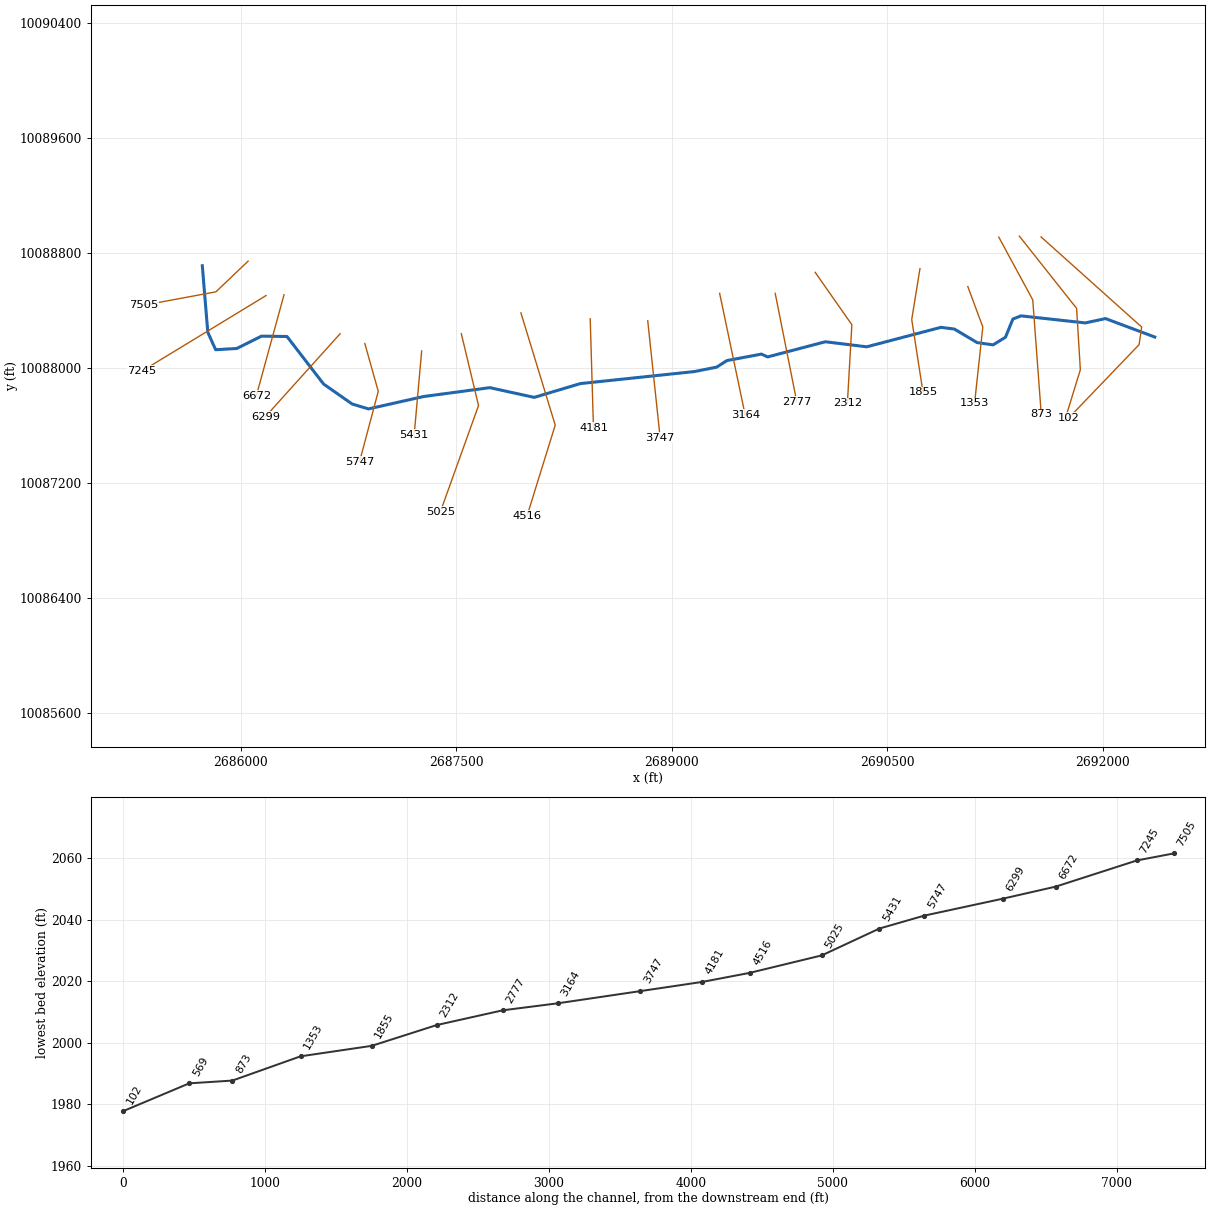
--- UNT 0074 IN HEWA.prj (project) ---

Proj Title=UNT 0074 IN HEWA Base Level Engineering
Current Plan=p01
Default Exp/Contr=0.3,0.1
English Units
Geom File=g01
Flow File=f01
Plan File=p01
BEGIN DESCRIPTION:
UNT 0074 IN HEWA
END DESCRIPTION:

--- UNT 0074 IN HEWA.p01 (plan) ---

Plan Title=Multiple Run
Short Identifier=Multiple
Geom File=g01
Flow File=f01
Subcritical Flow
K Sum by GR= 0
Std Step Tol= 0.01
Critical Tol= 0.01
Num of Std Step Trials= 20
Max Error Tol= 0.3
Flow Tol Ratio= 0.001
Split Flow NTrial= 30
Split Flow Tol= 0.02
Split Flow Ratio= 0.02
Log Output Level= 0
Friction Slope Method= 1
Unsteady Friction Slope Method= 2
Unsteady Bridges Friction Slope Method= 1
Parabolic Critical Depth
Global Vel Dist=  1 , 1 , 1
Global Log Level= 0
CheckData=True
Encroach Param= -1, 0, 0, 0
BEGIN DESCRIPTION:
Multiple Run
END DESCRIPTION:

--- UNT 0074 IN HEWA.f01 (steady flow) ---

Flow Title=Multiple
Number of Profiles=7
Profile Names=10-year,25-year,50-year,1pct_min,100-year,1pct_plu,500-year
River Rch & RM= UNT 0074 IN HEWA,Reach-1,7505
    1265    1858    2373    2209    2987    4040    4735
River Rch & RM= UNT 0074 IN HEWA,Reach-1,6672
    2027    3038    3935    3707    5013    6780    8143
Boundary for River Rch & Prof#=UNT 0074 IN HEWA,Reach-1,1
Up Type=0
Dn Type=3
Dn Slope=0.005
Boundary for River Rch & Prof#=UNT 0074 IN HEWA,Reach-1,2
Up Type=0
Dn Type=3
Dn Slope=0.005
Boundary for River Rch & Prof#=UNT 0074 IN HEWA,Reach-1,3
Up Type=0
Dn Type=3
Dn Slope=0.005
Boundary for River Rch & Prof#=UNT 0074 IN HEWA,Reach-1,4
Up Type=0
Dn Type=3
Dn Slope=0.005
Boundary for River Rch & Prof#=UNT 0074 IN HEWA,Reach-1,5
Up Type=0
Dn Type=3
Dn Slope=0.005
Boundary for River Rch & Prof#=UNT 0074 IN HEWA,Reach-1,6
Up Type=0
Dn Type=3
Dn Slope=0.005
Boundary for River Rch & Prof#=UNT 0074 IN HEWA,Reach-1,7
Up Type=0
Dn Type=3
Dn Slope=0.005

--- UNT 0074 IN HEWA.g01 (geometry) ---

Geom Title=Existing Conditions

River Reach=UNT 0074 IN HEWA,Reach-1
Reach XY= 30
      2685732.29     10088712.11      2685770.36     10088249.57
      2685824.76     10088127.40      2685972.61     10088136.05
      2686144.26     10088221.83      2686321.58     10088219.41
      2686576.34     10087888.72      2686775.95     10087749.04
      2686888.80     10087715.37      2687274.01     10087801.71
      2687733.74     10087863.30      2688042.70     10087795.55
      2688364.32     10087891.69      2689158.45     10087975.41
      2689312.82     10088006.13      2689384.25     10088051.82
      2689624.42     10088096.83      2689667.73     10088077.25
      2690069.13     10088182.71      2690357.85     10088147.66
      2690873.84     10088283.18      2690967.40     10088271.20
      2691126.17     10088176.74      2691237.59     10088161.13
      2691323.33     10088214.48      2691375.19     10088341.40
      2691431.60     10088362.94      2691878.70     10088314.00
      2692019.92     10088344.09      2692362.63     10088215.78

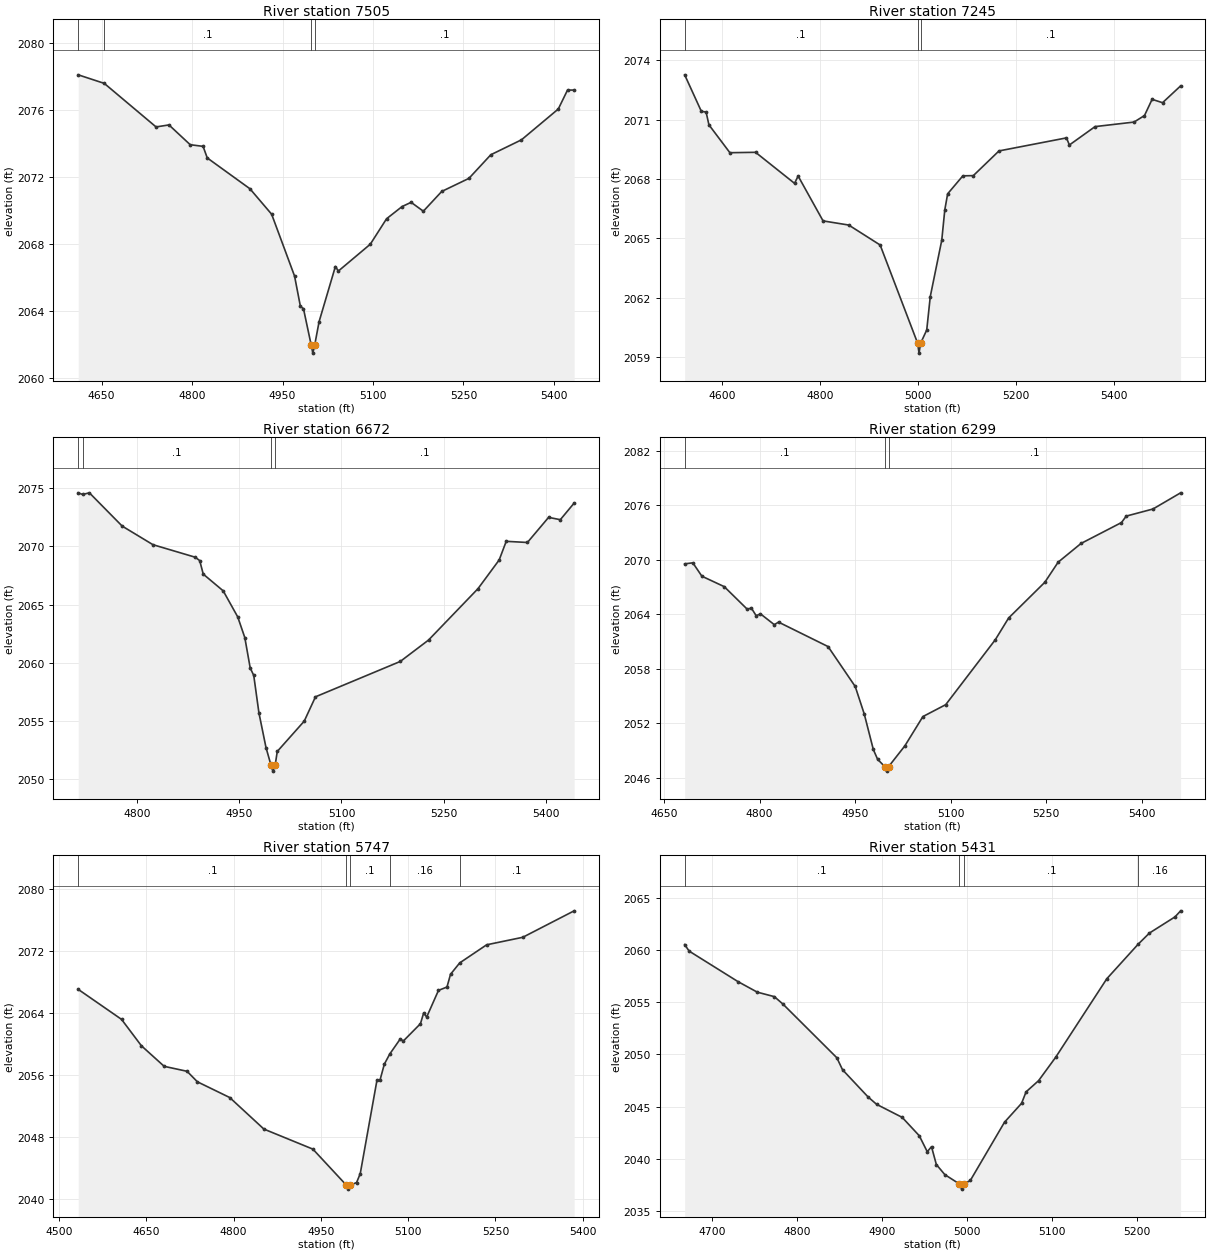
Type RM Length L Ch R = 1,7505,260,260,260
BEGIN DESCRIPTION:
UNT 0074 IN HEWA 17.0
END DESCRIPTION:
XS GIS Cut Line= 3
      2686050.96     10088743.93      2685826.96     10088530.35
      2685322.57     10088436.75
#Sta/Elev= 30
  4611.1 2078.08  4654.3 2077.57  4740.2 2074.97  4761.6 2075.09  4796.8 2073.91
  4818.2 2073.81  4825.1 2073.12  4895.9 2071.28  4931.9 2069.76  4969.9 2066.07
  4979.6 2064.26  4984.7 2064.12  4997.4 2061.97  5000.2 2061.47  5003.4 2061.97
  5010.6 2063.35  5037.6 2066.64  5042.6 2066.37  5095.5 2067.97  5122.5 2069.49
  5148.3 2070.22  5163.2 2070.47  5183.5 2069.94  5214.0 2071.12  5259.1 2071.90
  5295.4 2073.31  5346.2 2074.20  5407.3 2076.04  5422.6 2077.17  5433.6 2077.17
#Mann=4,-1,0
  4611.1    0.16       0  4654.3     0.1       0  4997.4    0.07       0
  5003.4     0.1       0
Bank Sta=4997.4,5003.4
Exp/Cntr=0.3,0.1

Type RM Length L Ch R = 1,7245,573,573,573
BEGIN DESCRIPTION:
UNT 0074 IN HEWA 16.0
END DESCRIPTION:
XS GIS Cut Line= 2
      2686175.90     10088504.30      2685312.81     10087979.16
#Sta/Elev= 30
  4524.6 2073.27  4558.6 2071.42  4568.2 2071.39  4574.0 2070.74  4616.7 2069.33
  4669.0 2069.35  4748.4 2067.78  4755.7 2068.15  4806.5 2065.88  4858.8 2065.67
  4922.8 2064.66  4999.2 2059.69  5002.0 2059.19  5005.2 2059.69  5017.7 2060.36
  5024.9 2062.05  5048.3 2064.90  5054.5 2066.44  5060.3 2067.25  5091.3 2068.16
  5112.6 2068.17  5164.9 2069.42  5302.4 2070.08  5308.3 2069.72  5360.6 2070.65
  5440.0 2070.88  5461.3 2071.21  5476.8 2072.03  5498.1 2071.86  5534.9 2072.71
#Mann=3,-1,0
  4524.6     0.1       0  4999.2    0.07       0  5005.2     0.1       0
Bank Sta=4999.2,5005.2
Exp/Cntr=0.3,0.1

Type RM Length L Ch R = 1,6672,373,373,373
BEGIN DESCRIPTION:
UNT 0074 IN HEWA 15.0
END DESCRIPTION:
XS GIS Cut Line= 2
      2686300.92     10088509.52      2686108.55     10087807.61
#Sta/Elev= 30
  4713.7 2074.61  4720.1 2074.47  4730.1 2074.61  4778.2 2071.75  4823.4 2070.15
  4885.6 2069.07  4892.0 2068.78  4897.2 2067.62  4926.5 2066.18  4947.8 2063.94
  4958.2 2062.16  4966.1 2059.55  4971.3 2058.91  4978.9 2055.69  4989.3 2052.70
  4996.7 2051.18  4999.4 2050.68  5002.7 2051.18  5005.8 2052.37  5045.4 2054.98
  5061.9 2057.07  5186.3 2060.11  5227.8 2061.95  5300.4 2066.37  5331.5 2068.84
  5341.8 2070.44  5372.9 2070.34  5404.0 2072.50  5421.2 2072.30  5441.5 2073.73
#Mann=4,-1,0
  4713.7    0.16       0  4720.1     0.1       0  4996.7    0.07       0
  5002.7     0.1       0
Bank Sta=4996.7,5002.7
Exp/Cntr=0.3,0.1

Type RM Length L Ch R = 1,6299,552,552,552
BEGIN DESCRIPTION:
UNT 0074 IN HEWA 14.0
END DESCRIPTION:
XS GIS Cut Line= 2
      2686691.58     10088238.72      2686170.70     10087660.55
#Sta/Elev= 30
  4682.5 2069.56  4695.3 2069.67  4709.5 2068.20  4744.6 2067.05  4780.5 2064.58
  4787.2 2064.69  4794.7 2063.85  4801.4 2064.06  4823.1 2062.87  4829.8 2063.15
  4907.5 2060.46  4950.1 2056.07  4964.3 2053.04  4978.5 2049.14  4985.3 2048.05
  4996.5 2047.26  4999.2 2046.76  5002.5 2047.26  5027.9 2049.53  5056.3 2052.76
  5092.1 2054.07  5169.9 2061.21  5190.8 2063.60  5247.6 2067.53  5268.5 2069.74
  5304.4 2071.80  5367.9 2074.10  5375.4 2074.81  5417.3 2075.59  5460.7 2077.37
#Mann=3,-1,0
  4682.5     0.1       0  4996.5    0.07       0  5002.5     0.1       0
Bank Sta=4996.5,5002.5
Exp/Cntr=0.3,0.1

Type RM Length L Ch R = 1,5747,316,316,316
BEGIN DESCRIPTION:
UNT 0074 IN HEWA 13.0
END DESCRIPTION:
XS GIS Cut Line= 3
      2686863.42     10088170.97      2686957.17     10087837.64
      2686827.06     10087348.41
#Sta/Elev= 30
  4532.8 2067.09  4607.3 2063.21  4641.4 2059.80  4680.6 2057.14  4719.9 2056.50
  4737.7 2055.14  4793.2 2053.11  4852.0 2049.03  4936.2 2046.44  4993.9 2041.77
  4996.7 2041.27  4999.9 2041.77  5011.3 2042.12  5017.6 2043.27  5046.3 2055.33
  5051.5 2055.34  5059.0 2057.42  5068.3 2058.73  5086.4 2060.68  5091.6 2060.41
  5121.1 2062.65  5126.6 2064.04  5131.8 2063.51  5152.1 2066.96  5166.7 2067.39
  5172.8 2069.04  5188.6 2070.51  5234.9 2072.85  5297.0 2073.82  5385.3 2077.24
#Mann=5,-1,0
  4532.8     0.1       0  4993.9    0.07       0  4999.9     0.1       0
  5068.3    0.16       0  5188.6     0.1       0
Bank Sta=4993.9,4999.9
Exp/Cntr=0.3,0.1

Type RM Length L Ch R = 1,5431,406,406,406
BEGIN DESCRIPTION:
UNT 0074 IN HEWA 12.0
END DESCRIPTION:
XS GIS Cut Line= 2
      2687259.26     10088118.93      2687207.31     10087537.14
#Sta/Elev= 30
  4667.6 2060.54  4672.8 2059.91  4730.4 2056.98  4753.1 2055.97  4773.2 2055.54
  4783.3 2054.83  4846.8 2049.68  4853.5 2048.53  4883.6 2045.92  4893.7 2045.21
  4923.8 2043.96  4943.9 2042.20  4953.3 2040.67  4958.3 2041.15  4964.0 2039.44
  4974.0 2038.47  4991.1 2037.58  4993.8 2037.08  4997.1 2037.58  5004.1 2037.92
  5044.3 2043.50  5064.4 2045.31  5069.7 2046.41  5084.4 2047.48  5104.5 2049.72
  5164.8 2057.26  5201.7 2060.57  5215.0 2061.64  5245.1 2063.19  5251.7 2063.77
#Mann=4,-1,0
  4667.6     0.1       0  4991.1    0.07       0  4997.1     0.1       0
  5201.7    0.16       0
Bank Sta=4991.1,4997.1
Exp/Cntr=0.3,0.1

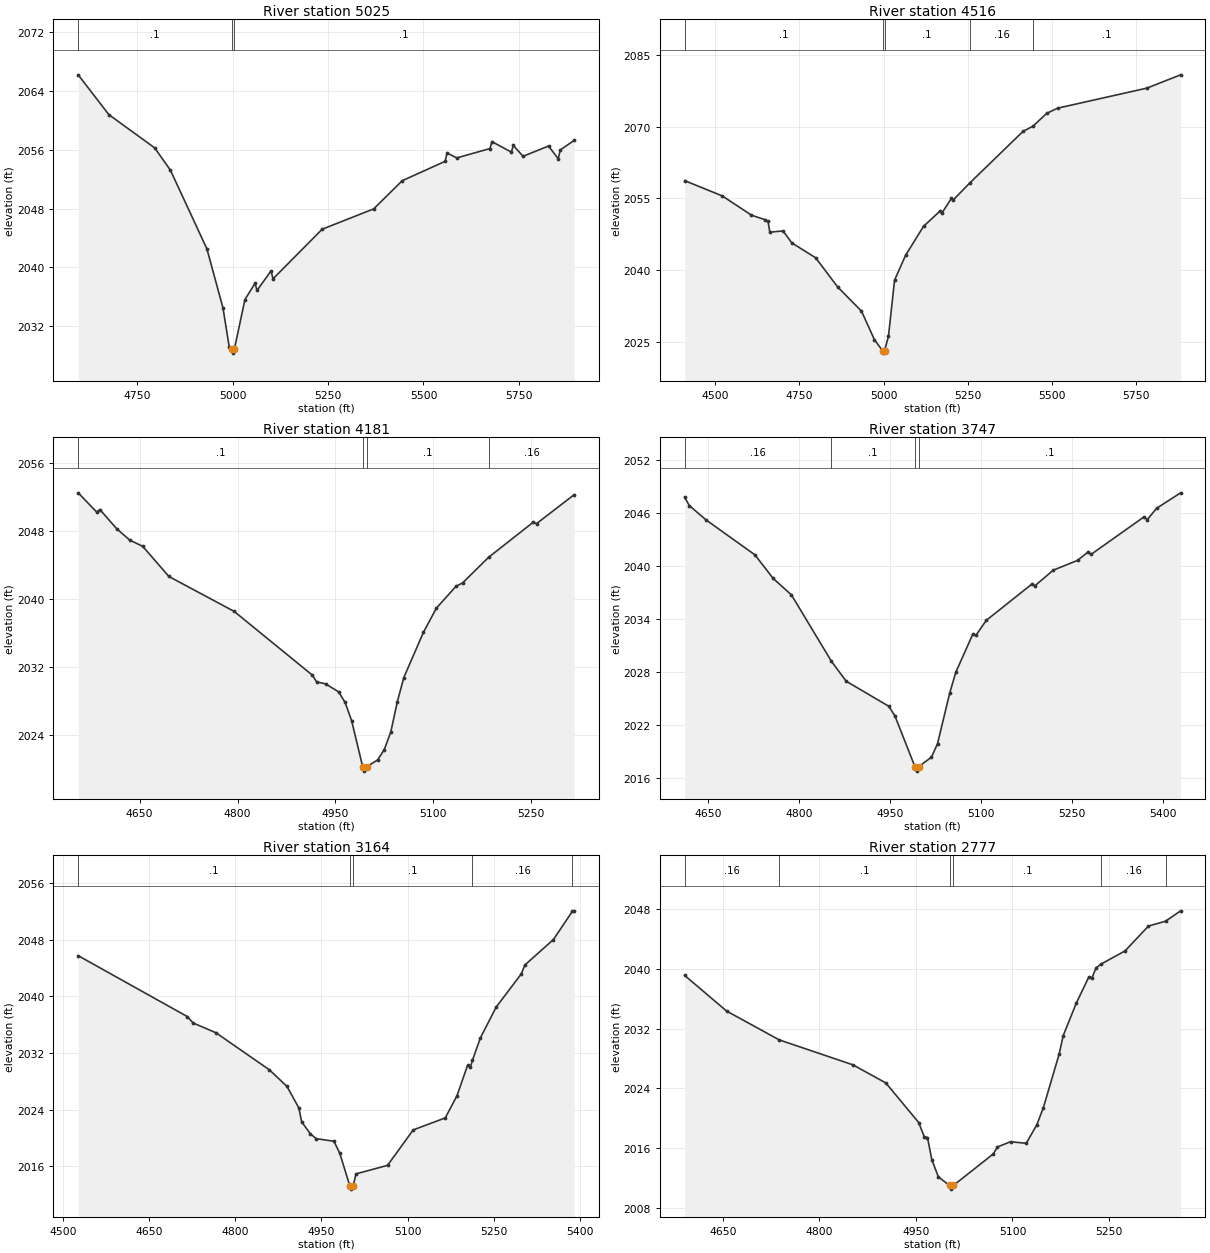
Type RM Length L Ch R = 1,5025,509,509,509
BEGIN DESCRIPTION:
UNT 0074 IN HEWA 11.0
END DESCRIPTION:
XS GIS Cut Line= 3
      2687535.29     10088238.72      2687655.09     10087738.68
      2687389.47     10086999.12
#Sta/Elev= 30
  4595.0 2066.18  4675.1 2060.78  4795.5 2056.25  4836.6 2053.23  4932.4 2042.52
  4974.5 2034.50  4990.9 2029.19  4998.2 2028.86  5000.9 2028.36  5004.2 2028.86
  5032.0 2035.64  5058.5 2037.85  5063.7 2036.88  5100.5 2039.53  5105.7 2038.46
  5234.5 2045.20  5369.5 2047.96  5444.3 2051.79  5556.6 2054.42  5561.9 2055.56
  5587.3 2054.89  5674.2 2056.16  5679.5 2057.10  5730.3 2055.68  5735.6 2056.58
  5761.1 2055.11  5827.8 2056.50  5853.3 2054.78  5858.6 2055.97  5895.0 2057.27
#Mann=3,-1,0
  4595.0     0.1       0  4998.2    0.07       0  5004.2     0.1       0
Bank Sta=4998.2,5004.2
Exp/Cntr=0.3,0.1

Type RM Length L Ch R = 1,4516,335,335,335
BEGIN DESCRIPTION:
UNT 0074 IN HEWA 10.0
END DESCRIPTION:
XS GIS Cut Line= 3
      2687950.23     10088383.64      2688188.94     10087602.40
      2687993.61     10086973.01
#Sta/Elev= 30
  4408.3 2058.70  4520.0 2055.52  4606.9 2051.50  4648.7 2050.51  4656.4 2050.18
  4661.7 2047.94  4701.0 2048.20  4727.2 2045.69  4798.1 2042.59  4863.7 2036.48
  4934.5 2031.44  4972.9 2025.49  4997.1 2023.17  4999.8 2022.67  5003.1 2023.17
  5014.7 2026.16  5032.9 2037.92  5065.7 2043.10  5119.2 2049.17  5169.3 2052.42
  5174.5 2052.01  5202.1 2055.00  5207.3 2054.65  5256.4 2058.19  5414.9 2068.98
  5445.4 2070.11  5485.6 2072.76  5517.9 2073.84  5783.7 2078.03  5884.2 2080.81
#Mann=5,-1,0
  4408.3     0.1       0  4997.1    0.07       0  5003.1     0.1       0
  5256.4    0.16       0  5445.4     0.1       0
Bank Sta=4997.1,5003.1
Exp/Cntr=0.3,0.1

Type RM Length L Ch R = 1,4181,434,434,434
BEGIN DESCRIPTION:
UNT 0074 IN HEWA 9.0
END DESCRIPTION:
XS GIS Cut Line= 2
      2688432.49     10088342.63      2688455.24     10087582.77
#Sta/Elev= 30
  4555.8 2052.50  4584.0 2050.24  4589.0 2050.53  4614.7 2048.28  4634.7 2046.94
  4654.7 2046.20  4694.8 2042.65  4794.8 2038.54  4914.9 2031.02  4921.2 2030.24
  4934.9 2030.01  4954.9 2029.07  4964.9 2027.82  4974.9 2025.67  4991.9 2020.23
  4994.6 2019.73  4997.9 2020.23  5014.9 2021.06  5024.9 2022.26  5034.9 2024.33
  5044.9 2027.88  5054.9 2030.75  5084.9 2036.06  5104.9 2038.93  5135.0 2041.50
  5145.0 2041.89  5184.9 2044.91  5253.3 2049.04  5258.3 2048.87  5316.0 2052.28
#Mann=4,-1,0
  4555.8     0.1       0  4991.9    0.07       0  4997.9     0.1       0
  5184.9    0.16       0
Bank Sta=4991.9,4997.9
Exp/Cntr=0.3,0.1

Type RM Length L Ch R = 1,3747,583,583,583
BEGIN DESCRIPTION:
UNT 0074 IN HEWA 8.0
END DESCRIPTION:
XS GIS Cut Line= 2
      2688832.93     10088329.05      2688919.39     10087514.52
#Sta/Elev= 30
  4610.7 2047.80  4618.4 2046.86  4646.2 2045.23  4726.7 2041.28  4756.8 2038.61
  4787.0 2036.74  4852.9 2029.23  4877.5 2026.95  4947.9 2024.11  4958.0 2023.01
  4991.0 2017.26  4993.7 2016.76  4997.0 2017.26  5018.3 2018.34  5028.3 2019.87
  5048.5 2025.63  5058.5 2027.97  5086.6 2032.29  5091.6 2032.14  5108.8 2033.85
  5184.2 2037.97  5189.3 2037.78  5219.4 2039.54  5259.6 2040.65  5276.9 2041.60
  5281.9 2041.33  5369.5 2045.59  5374.5 2045.26  5390.4 2046.57  5429.8 2048.31
#Mann=4,-1,0
  4610.7    0.16       0  4852.9     0.1       0  4991.0    0.07       0
  4997.0     0.1       0
Bank Sta=4991,4997
Exp/Cntr=0.3,0.1

Type RM Length L Ch R = 1,3164,387,387,387
BEGIN DESCRIPTION:
UNT 0074 IN HEWA 7.0
END DESCRIPTION:
XS GIS Cut Line= 2
      2689333.49     10088520.10      2689510.96     10087673.71
#Sta/Elev= 30
  4525.8 2045.74  4715.9 2037.15  4726.4 2036.23  4765.8 2034.87  4859.3 2029.62
  4889.9 2027.28  4910.4 2024.27  4915.5 2022.28  4930.8 2020.58  4941.0 2019.91
  4971.7 2019.55  4981.9 2017.85  4999.3 2013.29  5002.1 2012.79  5005.3 2013.29
  5010.2 2014.94  5065.2 2016.15  5110.0 2021.15  5165.8 2022.84  5186.2 2025.95
  5204.7 2030.25  5209.8 2030.04  5213.3 2030.98  5227.1 2034.14  5254.6 2038.48
  5298.6 2043.19  5304.6 2044.42  5354.5 2048.02  5387.6 2052.02  5390.6 2052.07
#Mann=5,-1,0
  4525.8     0.1       0  4999.3    0.07       0  5005.3     0.1       0
  5213.3    0.16       0  5387.6     0.1       0
Bank Sta=4999.3,5005.3
Exp/Cntr=0.3,0.1

Type RM Length L Ch R = 1,2777,465,465,465
BEGIN DESCRIPTION:
UNT 0074 IN HEWA 6.0
END DESCRIPTION:
XS GIS Cut Line= 2
      2689720.26     10088520.16      2689870.44     10087764.74
#Sta/Elev= 30
  4590.9 2039.10  4656.1 2034.33  4737.7 2030.48  4852.3 2027.14  4903.3 2024.72
  4954.3 2019.43  4962.9 2017.55  4968.0 2017.42  4974.7 2014.47  4984.9 2012.15
  5002.3 2011.02  5005.0 2010.52  5008.3 2011.02  5070.2 2015.23  5076.6 2016.16
  5097.0 2016.86  5121.4 2016.65  5137.8 2019.13  5148.0 2021.43  5172.5 2028.59
  5178.6 2031.01  5199.0 2035.38  5218.5 2038.88  5223.6 2038.81  5229.6 2040.08
  5237.6 2040.62  5274.8 2042.38  5311.1 2045.70  5337.9 2046.36  5361.1 2047.74
#Mann=6,-1,0
  4590.9    0.16       0  4737.7     0.1       0  5002.3    0.07       0
  5008.3     0.1       0  5237.6    0.16       0  5337.9     0.1       0
Bank Sta=5002.3,5008.3
Exp/Cntr=0.3,0.1

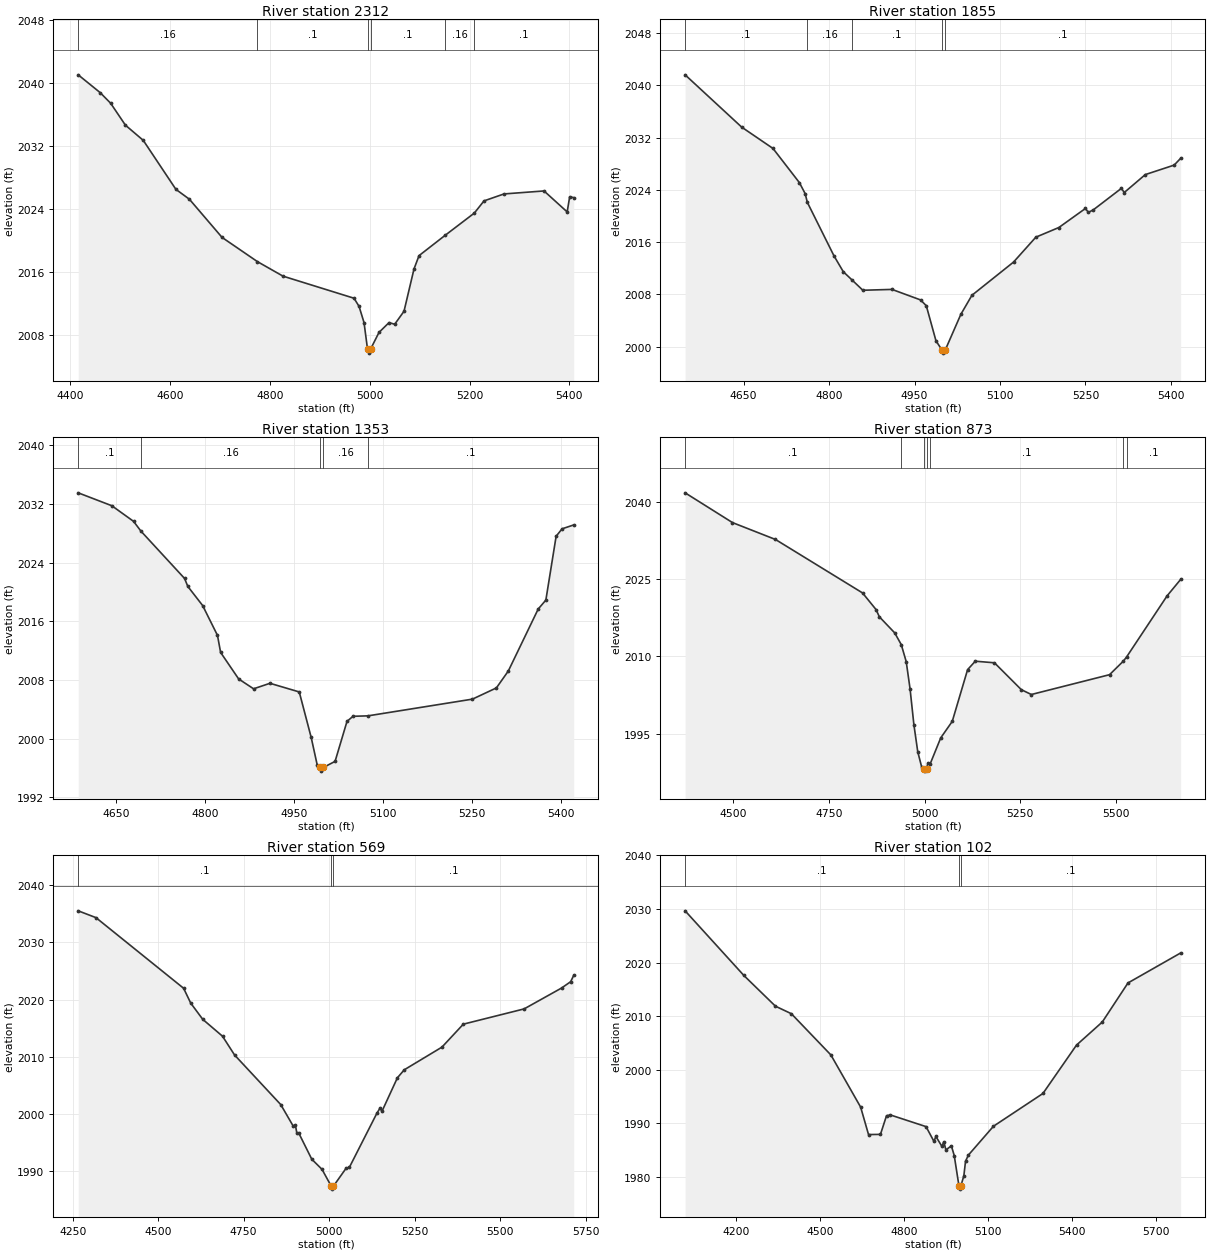
Type RM Length L Ch R = 1,2312,457,457,457
BEGIN DESCRIPTION:
UNT 0074 IN HEWA 5.0
END DESCRIPTION:
XS GIS Cut Line= 3
      2689998.85     10088665.75      2690254.05     10088301.18
      2690222.79     10087754.29
#Sta/Elev= 30
  4415.9 2041.01  4460.0 2038.75  4480.9 2037.41  4510.5 2034.63  4546.3 2032.70
  4611.7 2026.49  4638.7 2025.24  4704.1 2020.40  4775.0 2017.33  4826.2 2015.49
  4968.5 2012.69  4978.6 2011.66  4988.6 2009.60  4995.6 2006.23  4998.3 2005.73
  5001.6 2006.23  5018.6 2008.36  5038.7 2009.60  5050.0 2009.39  5068.7 2011.04
  5088.7 2016.40  5098.8 2018.09  5150.8 2020.65  5209.5 2023.48  5229.0 2025.03
  5269.0 2025.91  5349.2 2026.29  5395.6 2023.63  5400.6 2025.55  5408.7 2025.44
#Mann=6,-1,0
  4415.9    0.16       0  4775.0     0.1       0  4995.6    0.07       0
  5001.6     0.1       0  5150.8    0.16       0  5209.5     0.1       0
Bank Sta=4995.6,5001.6
Exp/Cntr=0.3,0.1

Type RM Length L Ch R = 1,1855,502,502,502
BEGIN DESCRIPTION:
UNT 0074 IN HEWA 4.0
END DESCRIPTION:
XS GIS Cut Line= 3
      2690728.00     10088691.77      2690670.71     10088337.64
      2690748.83     10087832.48
#Sta/Elev= 30
  4547.3 2041.62  4646.6 2033.61  4701.6 2030.34  4747.9 2025.11  4758.0 2023.43
  4761.9 2022.08  4808.7 2013.88  4825.0 2011.46  4840.4 2010.19  4859.3 2008.62
  4910.5 2008.75  4960.6 2007.14  4970.7 2006.25  4987.7 2000.87  4998.1 1999.49
  5000.8 1998.99  5004.1 1999.49  5031.4 2004.94  5050.8 2007.85  5123.9 2012.94
  5163.0 2016.75  5203.4 2018.23  5250.1 2021.15  5255.2 2020.55  5264.1 2020.95
  5313.2 2024.23  5318.2 2023.59  5355.2 2026.34  5405.8 2027.79  5417.2 2028.83
#Mann=5,-1,0
  4547.3     0.1       0  4761.9    0.16       0  4840.4     0.1       0
  4998.1    0.07       0  5004.1     0.1       0
Bank Sta=4998.1,5004.1
Exp/Cntr=0.3,0.1

Type RM Length L Ch R = 1,1353,480,480,480
BEGIN DESCRIPTION:
UNT 0074 IN HEWA 3.0
END DESCRIPTION:
XS GIS Cut Line= 3
      2691061.34     10088566.81      2691165.50     10088285.56
      2691108.21     10087754.26
#Sta/Elev= 30
  4586.8 2033.54  4643.4 2031.78  4680.0 2029.65  4692.5 2028.31  4765.9 2021.86
  4771.4 2020.77  4796.3 2018.17  4821.3 2014.10  4826.6 2011.77  4857.0 2008.15
  4882.1 2006.81  4909.7 2007.56  4959.0 2006.38  4979.1 2000.17  4989.1 1996.47
  4993.6 1996.08  4996.3 1995.58  4999.6 1996.08  5019.3 1996.91  5039.4 2002.37
  5049.5 2003.06  5074.7 2003.12  5250.6 2005.40  5290.9 2006.93  5311.0 2009.24
  5361.3 2017.69  5374.2 2018.91  5391.5 2027.62  5401.5 2028.63  5421.1 2029.16
#Mann=5,-1,0
  4586.8     0.1       0  4692.5    0.16       0  4993.6    0.07       0
  4999.6    0.16       0  5074.7     0.1       0
Bank Sta=4993.6,4999.6
Exp/Cntr=0.3,0.1

Type RM Length L Ch R = 1,873,304,304,304
BEGIN DESCRIPTION:
UNT 0074 IN HEWA 2.0
END DESCRIPTION:
XS GIS Cut Line= 3
      2691276.54     10088911.43      2691513.15     10088474.62
      2691572.29     10087678.49
#Sta/Elev= 30
  4374.3 2041.76  4498.1 2035.98  4610.5 2032.70  4838.0 2022.32  4873.2 2019.10
  4882.0 2017.68  4922.1 2014.56  4939.3 2012.27  4952.2 2008.97  4962.2 2003.71
  4972.2 1996.75  4982.3 1991.48  4992.3 1988.58  4999.3 1988.21  5002.1 1987.71
  5005.3 1988.21  5008.9 1989.23  5014.3 1989.03  5042.4 1994.17  5072.5 1997.37
  5112.6 2007.42  5132.7 2009.06  5182.8 2008.75  5253.0 2003.53  5279.2 2002.59
  5483.6 2006.44  5520.0 2009.10  5528.3 2009.90  5634.1 2021.76  5669.4 2024.94
#Mann=7,-1,0
  4374.3     0.1       0  4939.3    0.16       0  4999.3    0.07       0
  5005.3    0.16       0  5014.3     0.1       0  5520.0    0.16       0
  5528.3     0.1       0
Bank Sta=4999.3,5005.3
Exp/Cntr=0.3,0.1

Type RM Length L Ch R = 1,569,467,467,467
BEGIN DESCRIPTION:
Mapping XS bc34037f
END DESCRIPTION:
XS GIS Cut Line= 4
      2691420.01     10088917.86      2691818.45     10088415.24
      2691844.50     10087988.16      2691733.01     10087625.16
#Sta/Elev= 30
  4266.2 2035.53  4318.1 2034.34  4574.5 2021.97  4595.3 2019.37  4630.5 2016.53
  4688.2 2013.58  4723.5 2010.29  4858.5 2001.61  4895.0 1997.84  4901.4 1998.01
  4905.4 1996.66  4910.9 1996.66  4949.2 1992.05  4979.2 1990.27  5006.3 1987.31
  5009.0 1986.81  5012.3 1987.31  5049.4 1990.45  5059.4 1990.65  5139.5 2000.08
  5149.4 2001.05  5154.4 2000.42  5199.6 2006.30  5219.7 2007.70  5329.9 2011.67
  5392.4 2015.69  5570.2 2018.36  5679.8 2022.02  5706.2 2023.12  5715.2 2024.23
#Mann=3,-1,0
  4266.2     0.1       0  5006.3    0.07       0  5012.3     0.1       0
Bank Sta=5006.3,5012.3
Exp/Cntr=0.3,0.1

Type RM Length L Ch R = 1,102,0,0,0
BEGIN DESCRIPTION:
UNT 0074 IN HEWA 1.0
END DESCRIPTION:
XS GIS Cut Line= 4
      2691571.07     10088912.62      2692271.58     10088285.03
      2692253.35     10088162.64      2691763.78     10087652.24
#Sta/Elev= 30
  4016.6 2029.66  4226.7 2017.60  4339.6 2011.87  4396.4 2010.47  4537.7 2002.78
  4644.1 1993.05  4672.3 1987.93  4714.9 1987.96  4736.6 1991.44  4750.8 1991.58
  4877.9 1989.41  4906.3 1986.64  4913.0 1987.58  4934.7 1985.72  4941.4 1986.59
  4948.9 1985.07  4968.5 1985.82  4978.7 1984.02  4995.9 1978.25  4998.6 1977.75
  5001.9 1978.25  5013.1 1980.25  5019.1 1982.95  5029.2 1984.09  5119.0 1989.48
  5295.8 1995.59  5415.9 2004.62  5508.0 2008.92  5599.9 2016.21  5788.1 2021.80
#Mann=3,-1,0
  4016.6     0.1       0  4995.9    0.07       0  5001.9     0.1       0
Bank Sta=4995.9,5001.9
Exp/Cntr=0.3,0.1

Chan Stop Cuts=-1