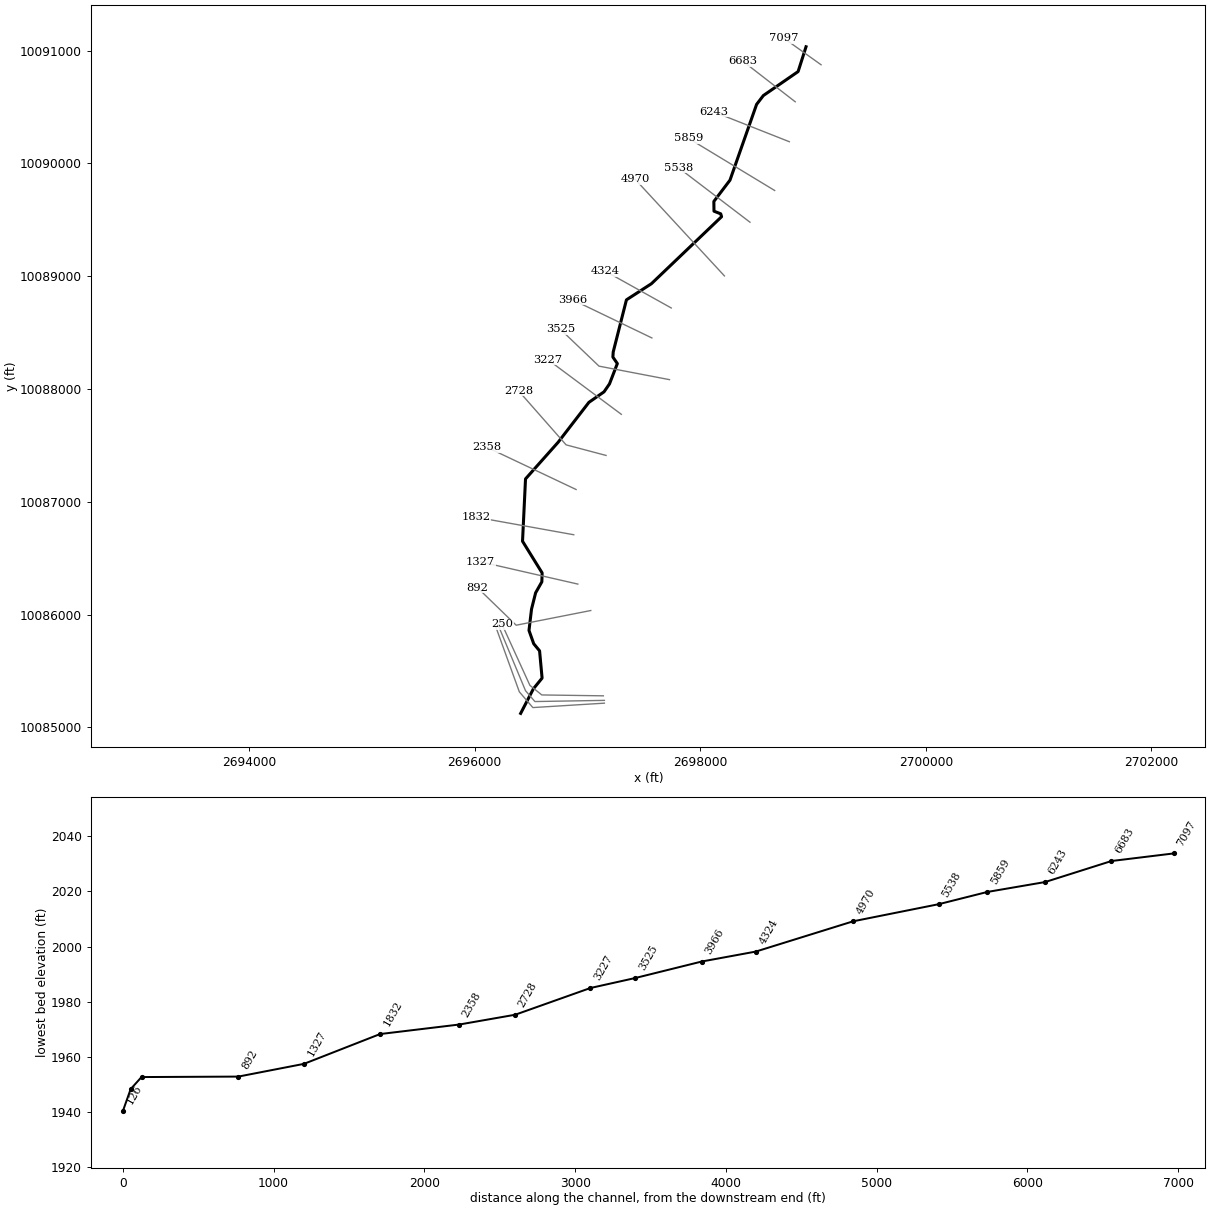
--- UNT 0075 IN HEWA.prj (project) ---

Proj Title=UNT 0075 IN HEWA Base Level Engineering
Current Plan=p01
Default Exp/Contr=0.3,0.1
English Units
Geom File=g01
Flow File=f01
Plan File=p01
BEGIN DESCRIPTION:
UNT 0075 IN HEWA
END DESCRIPTION:

--- UNT 0075 IN HEWA.p01 (plan) ---

Plan Title=Multiple Run
Short Identifier=Multiple
Geom File=g01
Flow File=f01
Subcritical Flow
K Sum by GR= 0
Std Step Tol= 0.01
Critical Tol= 0.01
Num of Std Step Trials= 20
Max Error Tol= 0.3
Flow Tol Ratio= 0.001
Split Flow NTrial= 30
Split Flow Tol= 0.02
Split Flow Ratio= 0.02
Log Output Level= 0
Friction Slope Method= 1
Unsteady Friction Slope Method= 2
Unsteady Bridges Friction Slope Method= 1
Parabolic Critical Depth
Global Vel Dist=  1 , 1 , 1
Global Log Level= 0
CheckData=True
Encroach Param= -1, 0, 0, 0
BEGIN DESCRIPTION:
Multiple Run
END DESCRIPTION:

--- UNT 0075 IN HEWA.f01 (steady flow) ---

Flow Title=Multiple
Number of Profiles=7
Profile Names=10-year,25-year,50-year,1pct_min,100-year,1pct_plu,500-year
River Rch & RM= UNT 0075 IN HEWA,Reach-1,7097
    1178    1725    2200    2047    2768    3744    4380
River Rch & RM= UNT 0075 IN HEWA,Reach-1,5859
    1602    2381    3067    2878    3892    5264    6269
Boundary for River Rch & Prof#=UNT 0075 IN HEWA,Reach-1,1
Up Type=0
Dn Type=3
Dn Slope=0.005
Boundary for River Rch & Prof#=UNT 0075 IN HEWA,Reach-1,2
Up Type=0
Dn Type=3
Dn Slope=0.005
Boundary for River Rch & Prof#=UNT 0075 IN HEWA,Reach-1,3
Up Type=0
Dn Type=3
Dn Slope=0.005
Boundary for River Rch & Prof#=UNT 0075 IN HEWA,Reach-1,4
Up Type=0
Dn Type=3
Dn Slope=0.005
Boundary for River Rch & Prof#=UNT 0075 IN HEWA,Reach-1,5
Up Type=0
Dn Type=3
Dn Slope=0.005
Boundary for River Rch & Prof#=UNT 0075 IN HEWA,Reach-1,6
Up Type=0
Dn Type=3
Dn Slope=0.005
Boundary for River Rch & Prof#=UNT 0075 IN HEWA,Reach-1,7
Up Type=0
Dn Type=3
Dn Slope=0.005

--- UNT 0075 IN HEWA.g01 (geometry) ---

Geom Title=Existing Conditions

River Reach=UNT 0075 IN HEWA,Reach-1
Reach XY= 30
      2698938.47     10091033.73      2698868.19     10090813.77
      2698560.07     10090601.15      2698500.22     10090523.03
      2698264.07     10089850.84      2698121.22     10089662.45
      2698122.45     10089576.06      2698182.24     10089552.58
      2698189.60     10089527.02      2697567.87     10088933.12
      2697346.22     10088790.01      2697229.02     10088328.04
      2697226.01     10088282.57      2697265.57     10088224.99
      2697195.92     10088044.72      2697147.55     10087974.43
      2697013.43     10087881.15      2696740.70     10087527.44
      2696451.55     10087202.45      2696424.96     10086649.92
      2696598.81     10086368.79      2696596.24     10086289.70
      2696541.08     10086192.64      2696504.80     10086048.05
      2696482.33     10085858.98      2696524.09     10085741.23
      2696576.18     10085678.03      2696598.41     10085436.38
      2696521.07     10085341.21      2696408.47     10085123.73

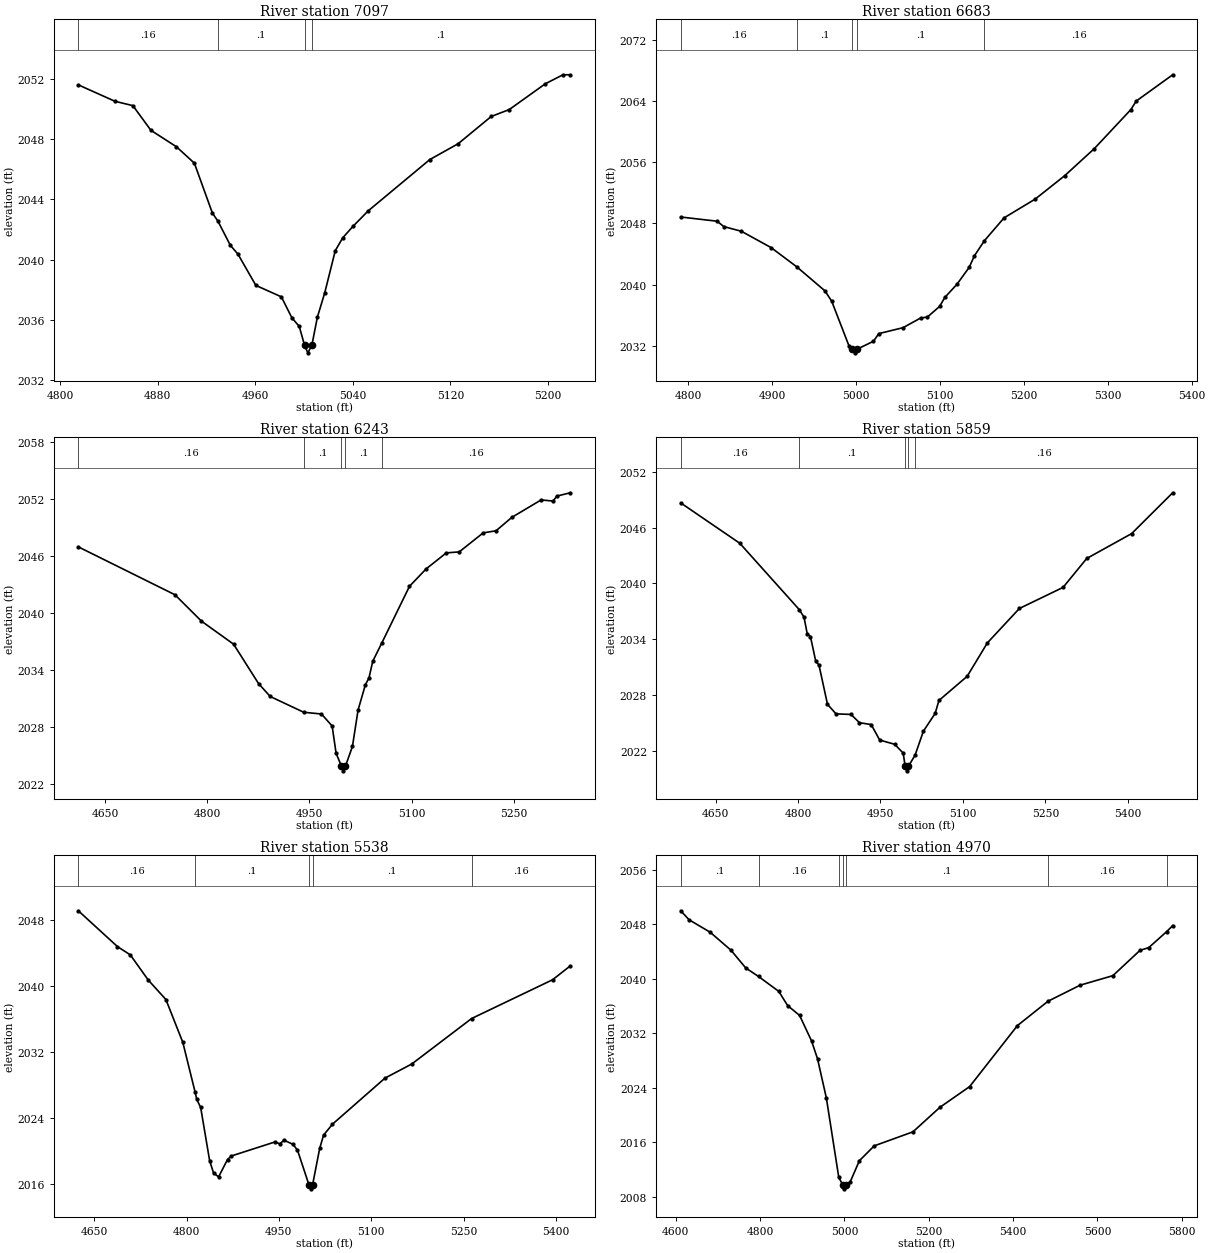
Type RM Length L Ch R = 1,7097,414,414,414
BEGIN DESCRIPTION:
UNT 0075 IN HEWA 16.0
END DESCRIPTION:
XS GIS Cut Line= 2
      2699071.77     10090874.09      2698743.67     10091108.45
#Sta/Elev= 30
  4815.0 2051.60  4845.0 2050.51  4859.7 2050.22  4874.5 2048.58  4895.4 2047.49
  4910.1 2046.40  4924.9 2043.08  4929.4 2042.55  4939.6 2040.94  4945.8 2040.36
  4960.5 2038.28  4981.4 2037.52  4990.0 2036.13  4996.1 2035.55  5000.4 2034.30
  5003.1 2033.80  5006.4 2034.30  5010.9 2036.16  5017.0 2037.80  5025.6 2040.59
  5031.8 2041.45  5040.3 2042.22  5052.7 2043.24  5103.1 2046.64  5126.3 2047.69
  5153.4 2049.50  5168.2 2049.96  5197.7 2051.67  5212.2 2052.27  5218.2 2052.27
#Mann=4,-1,0
  4815.0    0.16       0  4929.4     0.1       0  5000.4    0.07       0
  5006.4     0.1       0
Bank Sta=5000.4,5006.4
Exp/Cntr=0.3,0.1

Type RM Length L Ch R = 1,6683,440,440,440
BEGIN DESCRIPTION:
UNT 0075 IN HEWA 15.0
END DESCRIPTION:
XS GIS Cut Line= 2
      2698842.59     10090545.98      2698379.07     10090905.33
#Sta/Elev= 30
  4790.8 2048.85  4834.1 2048.30  4842.3 2047.59  4863.1 2046.98  4898.4 2044.85
  4928.9 2042.34  4962.7 2039.17  4970.8 2037.81  4991.6 2031.89  4995.5 2031.54
  4998.2 2031.04  5001.5 2031.54  5020.6 2032.56  5026.9 2033.56  5055.9 2034.34
  5076.7 2035.60  5084.9 2035.74  5099.4 2037.12  5105.7 2038.31  5120.2 2040.04
  5134.7 2042.25  5141.0 2043.78  5152.9 2045.75  5176.3 2048.74  5213.4 2051.20
  5248.7 2054.28  5284.0 2057.83  5327.5 2062.94  5333.8 2064.05  5377.3 2067.50
#Mann=5,-1,0
  4790.8    0.16       0  4928.9     0.1       0  4995.5    0.07       0
  5001.5     0.1       0  5152.9    0.16       0
Bank Sta=4995.5,5001.5
Exp/Cntr=0.3,0.1

Type RM Length L Ch R = 1,6243,384,384,384
BEGIN DESCRIPTION:
UNT 0075 IN HEWA 14.0
END DESCRIPTION:
XS GIS Cut Line= 2
      2698790.46     10090191.83      2698118.66     10090457.42
#Sta/Elev= 30
  4610.7 2046.94  4752.6 2041.91  4791.5 2039.14  4838.7 2036.72  4875.3 2032.59
  4892.4 2031.23  4941.7 2029.57  4967.7 2029.39  4983.4 2028.13  4989.2 2025.27
  4997.0 2023.92  4999.7 2023.42  5003.0 2023.92  5013.2 2025.98  5021.5 2029.81
  5032.2 2032.46  5037.5 2033.17  5043.0 2034.92  5056.5 2036.87  5097.0 2042.80
  5121.3 2044.62  5151.1 2046.31  5170.0 2046.41  5205.2 2048.41  5224.1 2048.63
  5247.3 2050.04  5290.3 2051.87  5307.9 2051.75  5313.3 2052.27  5333.1 2052.62
#Mann=5,-1,0
  4610.7    0.16       0  4941.7     0.1       0  4997.0    0.07       0
  5003.0     0.1       0  5056.5    0.16       0
Bank Sta=4997,5003
Exp/Cntr=0.3,0.1

Type RM Length L Ch R = 1,5859,321,321,321
BEGIN DESCRIPTION:
UNT 0075 IN HEWA 13.0
END DESCRIPTION:
XS GIS Cut Line= 2
      2698660.30     10089759.52      2697894.69     10090223.05
#Sta/Elev= 30
  4586.6 2048.65  4694.0 2044.31  4802.1 2037.18  4810.9 2036.35  4816.7 2034.58
  4822.6 2034.27  4832.2 2031.62  4838.1 2031.21  4853.6 2026.98  4869.1 2025.95
  4896.3 2025.89  4911.8 2025.00  4933.1 2024.80  4948.6 2023.13  4975.8 2022.68
  4991.3 2021.73  4994.9 2020.32  4997.6 2019.82  5000.9 2020.32  5012.9 2021.50
  5028.1 2024.09  5049.5 2026.00  5056.3 2027.39  5107.7 2029.99  5144.5 2033.59
  5202.7 2037.29  5282.2 2039.56  5325.2 2042.67  5407.0 2045.35  5481.6 2049.74
#Mann=5,-1,0
  4586.6    0.16       0  4802.1     0.1       0  4994.9    0.07       0
  5000.9     0.1       0  5012.9    0.16       0
Bank Sta=4994.9,5000.9
Exp/Cntr=0.3,0.1

Type RM Length L Ch R = 1,5538,568,568,568
BEGIN DESCRIPTION:
UNT 0075 IN HEWA 12.0
END DESCRIPTION:
XS GIS Cut Line= 2
      2698441.54     10089478.27      2697806.11     10089962.66
#Sta/Elev= 30
  4624.3 2049.15  4687.9 2044.80  4708.7 2043.80  4737.8 2040.75  4766.5 2038.38
  4794.0 2033.18  4813.9 2027.16  4816.7 2026.25  4823.0 2025.28  4837.6 2018.80
  4843.9 2017.33  4852.1 2016.85  4866.6 2018.96  4872.9 2019.39  4943.6 2021.09
  4951.9 2020.86  4958.2 2021.31  4972.7 2020.81  4980.2 2020.11  4998.8 2015.90
  5001.5 2015.40  5004.8 2015.90  5016.3 2020.31  5022.6 2021.92  5037.1 2023.25
  5122.4 2028.84  5166.0 2030.56  5263.0 2036.07  5394.6 2040.78  5423.3 2042.46
#Mann=5,-1,0
  4624.3    0.16       0  4813.9     0.1       0  4998.8    0.07       0
  5004.8     0.1       0  5263.0    0.16       0
Bank Sta=4998.8,5004.8
Exp/Cntr=0.3,0.1

Type RM Length L Ch R = 1,4970,646,646,646
BEGIN DESCRIPTION:
UNT 0075 IN HEWA 11.0
END DESCRIPTION:
XS GIS Cut Line= 2
      2698215.02     10089002.10      2697423.49     10089858.69
#Sta/Elev= 30
  4612.0 2049.96  4631.8 2048.64  4681.7 2046.82  4731.1 2044.18  4766.2 2041.57
  4796.4 2040.33  4844.5 2038.14  4865.4 2036.06  4893.8 2034.62  4922.1 2030.88
  4936.3 2028.26  4957.3 2022.50  4986.7 2010.87  4996.8 2009.69  4999.6 2009.19
  5002.8 2009.69  5014.0 2010.24  5035.5 2013.31  5070.7 2015.49  5162.6 2017.55
  5226.6 2021.15  5296.9 2024.18  5410.3 2033.13  5482.8 2036.70  5558.9 2039.05
  5636.6 2040.45  5700.7 2044.15  5721.6 2044.56  5763.8 2046.89  5778.3 2047.78
#Mann=7,-1,0
  4612.0     0.1       0  4796.4    0.16       0  4986.7     0.1       0
  4996.8    0.07       0  5002.8     0.1       0  5482.8    0.16       0
  5763.8     0.1       0
Bank Sta=4996.8,5002.8
Exp/Cntr=0.3,0.1

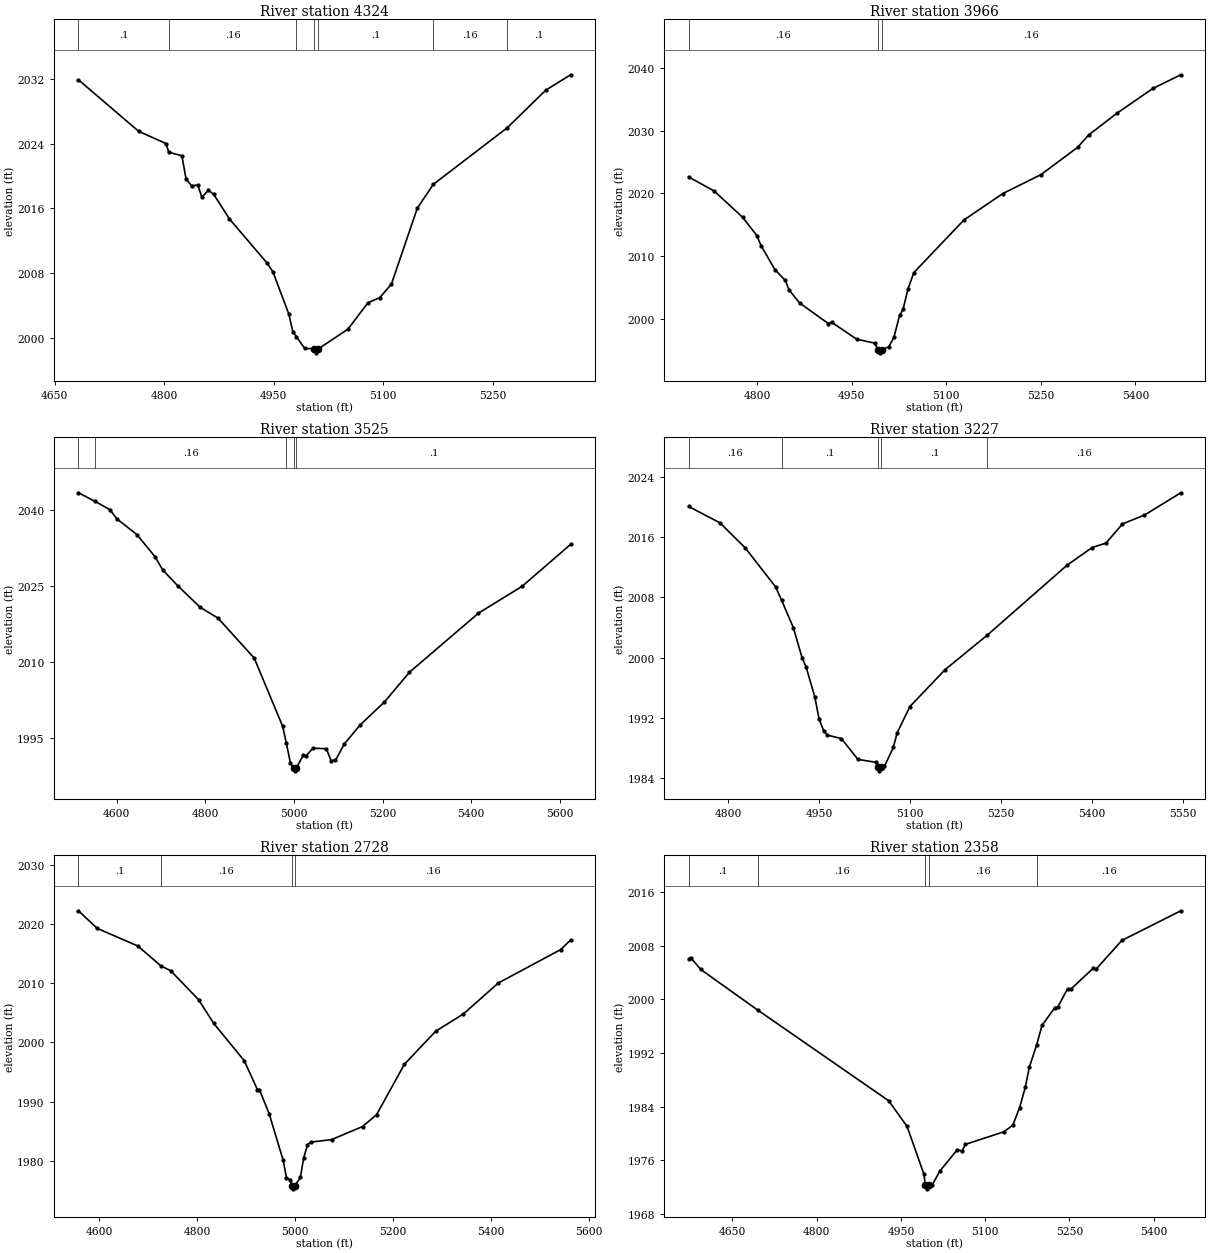
Type RM Length L Ch R = 1,4324,358,358,358
BEGIN DESCRIPTION:
UNT 0075 IN HEWA 10.0
END DESCRIPTION:
XS GIS Cut Line= 2
      2697743.64     10088717.85      2697155.12     10089045.96
#Sta/Elev= 30
  4682.7 2031.85  4764.9 2025.52  4802.6 2023.99  4806.3 2022.93  4824.3 2022.49
  4830.0 2019.65  4837.5 2018.78  4846.0 2018.90  4851.7 2017.37  4860.4 2018.24
  4867.7 2017.76  4889.4 2014.71  4940.5 2009.32  4948.9 2008.20  4970.6 2003.02
  4976.3 2000.80  4981.1 2000.21  4992.3 1998.76  5005.3 1998.71  5008.0 1998.21
  5011.3 1998.71  5051.7 2001.13  5079.2 2004.40  5095.2 2005.01  5111.1 2006.66
  5146.6 2016.03  5168.4 2018.96  5269.6 2025.93  5322.6 2030.58  5356.5 2032.47
#Mann=7,-1,0
  4682.7     0.1       0  4806.3    0.16       0  4981.1     0.1       0
  5005.3    0.07       0  5011.3     0.1       0  5168.4    0.16       0
  5269.6     0.1       0
Bank Sta=5005.3,5011.3
Exp/Cntr=0.3,0.1

Type RM Length L Ch R = 1,3966,441,441,441
BEGIN DESCRIPTION:
UNT 0075 IN HEWA 9.0
END DESCRIPTION:
XS GIS Cut Line= 2
      2697571.78     10088452.22      2696868.64     10088790.76
#Sta/Elev= 30
  4691.7 2022.62  4732.0 2020.39  4777.2 2016.21  4799.9 2013.27  4806.4 2011.69
  4828.6 2007.85  4845.1 2006.13  4850.8 2004.63  4867.7 2002.55  4913.0 1999.28
  4918.5 1999.47  4958.2 1996.78  4986.4 1996.16  4992.0 1995.11  4994.8 1994.61
  4998.0 1995.11  5009.0 1995.56  5017.2 1997.08  5026.1 2000.56  5031.7 2001.54
  5039.4 2004.75  5048.7 2007.38  5128.2 2015.77  5190.0 2019.98  5250.3 2022.99
  5308.7 2027.35  5325.8 2029.29  5371.0 2032.78  5427.9 2036.71  5472.1 2038.89
#Mann=3,-1,0
  4691.7    0.16       0  4992.0    0.07       0  4998.0    0.16       0
Bank Sta=4992,4998
Exp/Cntr=0.3,0.1

Type RM Length L Ch R = 1,3525,298,298,298
BEGIN DESCRIPTION:
UNT 0075 IN HEWA 8.0
END DESCRIPTION:
XS GIS Cut Line= 3
      2697727.98     10088082.44      2697103.00     10088202.23
      2696760.10     10088529.55
#Sta/Elev= 30
  4513.9 2043.31  4551.5 2041.61  4584.7 2040.00  4600.2 2038.21  4645.8 2035.08
  4686.5 2030.76  4704.2 2028.12  4737.4 2025.07  4788.3 2020.81  4829.0 2018.64
  4910.5 2010.79  4974.5 1997.42  4982.8 1994.13  4992.0 1990.21  4999.1 1989.13
  5001.9 1988.63  5005.1 1989.13  5021.4 1991.73  5026.5 1991.49  5042.9 1993.09
  5073.4 1992.97  5083.6 1990.66  5093.8 1990.71  5114.1 1993.96  5150.0 1997.71
  5204.0 2002.14  5260.6 2008.01  5416.3 2019.63  5515.4 2024.95  5624.3 2033.17
#Mann=5,-1,0
  4513.9     0.1       0  4551.5    0.16       0  4982.8     0.1       0
  4999.1    0.07       0  5005.1     0.1       0
Bank Sta=4999.1,5005.1
Exp/Cntr=0.3,0.1

Type RM Length L Ch R = 1,3227,499,499,499
BEGIN DESCRIPTION:
UNT 0075 IN HEWA 7.0
END DESCRIPTION:
XS GIS Cut Line= 2
      2697300.90     10087775.16      2696650.40     10088259.13
#Sta/Elev= 30
  4735.1 2020.07  4786.6 2017.90  4828.2 2014.59  4878.3 2009.41  4888.1 2007.66
  4907.5 2004.01  4922.1 1999.97  4928.4 1998.82  4943.0 1994.78  4950.0 1991.85
  4957.6 1990.31  4963.8 1989.74  4986.8 1989.28  5013.9 1986.52  5043.1 1986.14
  5046.7 1985.50  5049.5 1985.00  5052.7 1985.50  5057.7 1985.61  5072.3 1988.11
  5078.5 1990.03  5099.6 1993.53  5157.8 1998.44  5227.3 2003.02  5358.0 2012.25
  5399.7 2014.62  5422.7 2015.22  5449.8 2017.76  5486.0 2018.93  5545.9 2021.89
#Mann=5,-1,0
  4735.1    0.16       0  4888.1     0.1       0  5046.7    0.07       0
  5052.7     0.1       0  5227.3    0.16       0
Bank Sta=5046.7,5052.7
Exp/Cntr=0.3,0.1

Type RM Length L Ch R = 1,2728,370,370,370
BEGIN DESCRIPTION:
UNT 0075 IN HEWA 6.0
END DESCRIPTION:
XS GIS Cut Line= 3
      2697165.51     10087410.56      2696811.34     10087504.31
      2696389.46     10087983.48
#Sta/Elev= 30
  4557.8 2022.20  4596.1 2019.23  4678.9 2016.27  4726.1 2012.91  4746.1 2012.09
  4803.0 2007.21  4834.0 2003.20  4896.1 1996.94  4923.1 1992.06  4927.1 1992.06
  4947.3 1987.94  4975.8 1980.11  4982.4 1977.22  4990.0 1976.82  4993.7 1975.81
  4996.4 1975.31  4999.7 1975.81  5010.9 1977.24  5017.5 1980.48  5025.1 1982.67
  5031.8 1983.19  5074.5 1983.61  5138.0 1985.82  5166.5 1987.83  5223.4 1996.33
  5287.0 2001.88  5343.9 2004.81  5415.0 2010.02  5542.2 2015.65  5562.6 2017.27
#Mann=4,-1,0
  4557.8     0.1       0  4726.1    0.16       0  4993.7    0.07       0
  4999.7    0.16       0
Bank Sta=4993.7,4999.7
Exp/Cntr=0.3,0.1

Type RM Length L Ch R = 1,2358,526,526,526
BEGIN DESCRIPTION:
UNT 0075 IN HEWA 5.0
END DESCRIPTION:
XS GIS Cut Line= 2
      2696899.88     10087108.48      2696108.21     10087483.48
#Sta/Elev= 30
  4572.2 2006.07  4576.0 2006.22  4593.3 2004.48  4695.2 1998.40  4928.3 1984.89
  4961.0 1981.06  4991.0 1973.94  4993.5 1972.27  4996.3 1971.77  4999.5 1972.27
  5005.3 1972.29  5019.3 1974.42  5049.6 1977.52  5059.2 1977.45  5064.8 1978.40
  5133.0 1980.26  5149.2 1981.25  5161.3 1983.88  5171.3 1986.87  5178.5 1989.87
  5191.7 1993.25  5201.2 1996.13  5224.0 1998.77  5229.5 1998.91  5246.7 2001.58
  5252.3 2001.51  5292.2 2004.63  5297.7 2004.53  5343.2 2008.78  5448.2 2013.20
#Mann=5,-1,0
  4572.2     0.1       0  4695.2    0.16       0  4993.5    0.07       0
  4999.5    0.16       0  5191.7    0.16       0
Bank Sta=4993.5,4999.5
Exp/Cntr=0.3,0.1

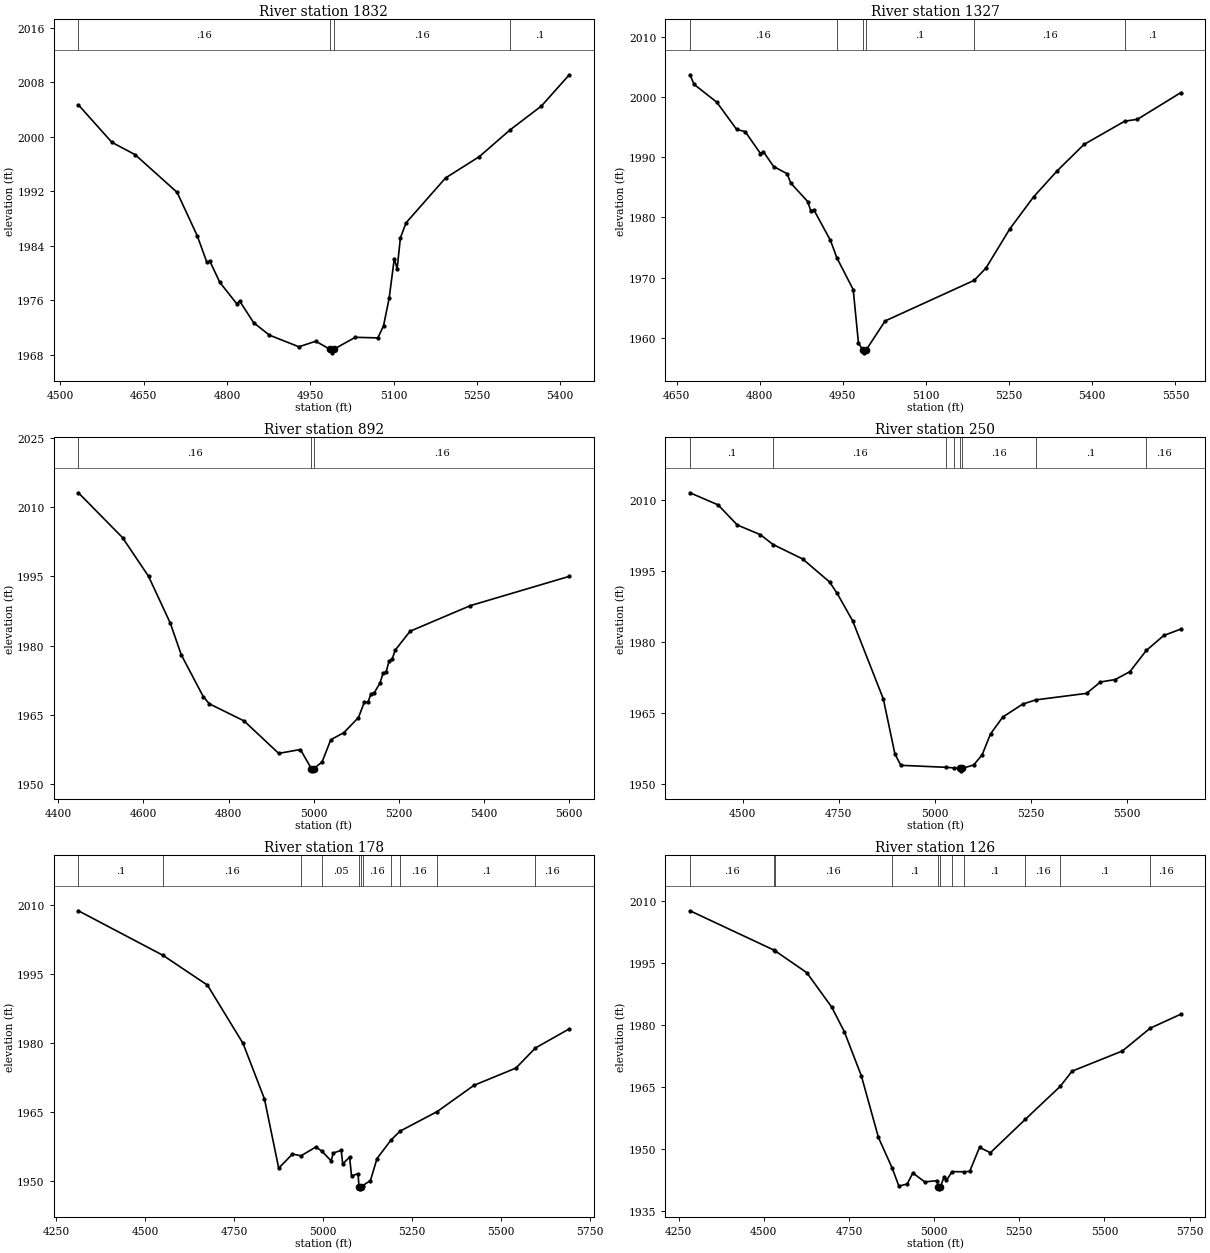
Type RM Length L Ch R = 1,1832,505,505,505
BEGIN DESCRIPTION:
UNT 0075 IN HEWA 4.0
END DESCRIPTION:
XS GIS Cut Line= 2
      2696879.07     10086707.43      2696009.29     10086863.68
#Sta/Elev= 30
  4532.7 2004.68  4592.9 1999.19  4634.9 1997.37  4710.4 1991.85  4746.7 1985.47
  4764.1 1981.56  4769.2 1981.78  4787.3 1978.65  4817.8 1975.50  4822.9 1975.92
  4848.3 1972.72  4876.5 1970.91  4929.6 1969.20  4960.0 1970.01  4986.0 1968.81
  4988.7 1968.31  4992.0 1968.81  5031.2 1970.59  5071.8 1970.50  5082.0 1972.27
  5092.1 1976.29  5101.4 1982.13  5106.5 1980.64  5112.4 1985.18  5122.6 1987.38
  5193.7 1993.96  5254.7 1997.10  5309.4 2000.98  5366.4 2004.52  5416.4 2009.09
#Mann=4,-1,0
  4532.7    0.16       0  4986.0    0.07       0  4992.0    0.16       0
  5309.4     0.1       0
Bank Sta=4986,4992
Exp/Cntr=0.3,0.1

Type RM Length L Ch R = 1,1327,435,435,435
BEGIN DESCRIPTION:
UNT 0075 IN HEWA 3.0
END DESCRIPTION:
XS GIS Cut Line= 2
      2696915.54     10086269.93      2696052.17     10086467.56
#Sta/Elev= 30
  4674.2 2003.69  4681.5 2002.10  4722.5 1999.14  4758.4 1994.61  4773.8 1994.25
  4801.4 1990.60  4806.5 1990.93  4825.1 1988.45  4849.4 1987.26  4855.9 1985.71
  4886.6 1982.63  4892.3 1981.04  4897.5 1981.28  4927.7 1976.17  4939.1 1973.30
  4968.7 1968.00  4978.2 1959.07  4986.2 1958.00  4989.0 1957.50  4992.2 1958.00
  5026.2 1962.79  5187.1 1969.55  5208.2 1971.58  5251.1 1978.07  5294.0 1983.39
  5337.0 1987.76  5385.0 1992.11  5458.6 1995.98  5481.6 1996.30  5559.9 2000.73
#Mann=6,-1,0
  4674.2    0.16       0  4939.1     0.1       0  4986.2    0.07       0
  4992.2     0.1       0  5187.1    0.16       0  5458.6     0.1       0
Bank Sta=4986.2,4992.2
Exp/Cntr=0.3,0.1

Type RM Length L Ch R = 1,892,642,642,642
BEGIN DESCRIPTION:
UNT 0075 IN HEWA 2.0
END DESCRIPTION:
XS GIS Cut Line= 3
      2697030.13     10086035.57      2696368.63     10085905.35
      2696024.89     10086238.67
#Sta/Elev= 30
  4447.2 2013.11  4550.8 2003.41  4612.0 1995.01  4662.9 1984.91  4689.0 1977.98
  4740.4 1968.98  4754.7 1967.41  4836.2 1963.71  4917.7 1956.67  4968.7 1957.51
  4994.3 1953.39  4997.0 1952.89  5000.3 1953.39  5019.6 1954.81  5040.0 1959.63
  5070.6 1961.15  5105.1 1964.44  5118.9 1967.78  5127.4 1967.75  5134.6 1969.60
  5141.6 1969.71  5155.7 1971.93  5162.9 1974.08  5169.9 1974.31  5177.0 1976.67
  5184.0 1977.02  5191.2 1979.02  5226.4 1983.13  5367.9 1988.67  5600.2 1995.01
#Mann=3,-1,0
  4447.2    0.16       0  4994.3    0.07       0  5000.3    0.16       0
Bank Sta=4994.3,5000.3
Exp/Cntr=0.3,0.1

Type RM Length L Ch R = 1,250,72,72,72
BEGIN DESCRIPTION:
Mapping XS d7478963
END DESCRIPTION:
XS GIS Cut Line= 4
      2697141.54     10085279.32      2696595.97     10085287.13
      2696490.50     10085371.77      2696242.66     10085914.17
#Sta/Elev= 30
  4363.0 2011.50  4436.1 2008.94  4486.1 2004.69  4546.1 2002.64  4579.2 2000.56
  4656.1 1997.51  4726.1 1992.65  4746.1 1990.21  4786.1 1984.45  4866.1 1967.90
  4896.1 1956.31  4911.5 1953.89  5028.7 1953.47  5050.6 1953.33  5065.0 1953.22
  5067.7 1952.72  5071.0 1953.22  5101.0 1953.96  5123.0 1956.08  5145.0 1960.53
  5176.8 1964.09  5228.3 1966.81  5262.6 1967.72  5395.0 1969.10  5430.8 1971.50
  5469.6 1972.02  5507.8 1973.71  5550.3 1978.17  5595.7 1981.33  5640.2 1982.69
#Mann=8,-1,0
  4363.0     0.1       0  4579.2    0.16       0  5028.7    0.05       0
  5050.6    0.16       0  5065.0    0.07       0  5071.0    0.16       0
  5262.6     0.1       0  5550.3    0.16       0
Bank Sta=5065,5071
Exp/Cntr=0.3,0.1

Type RM Length L Ch R = 1,178,52,52,52
BEGIN DESCRIPTION:
Mapping XS 501da944
END DESCRIPTION:
XS GIS Cut Line= 4
      2697150.62     10085238.95      2696534.78     10085228.54
      2696451.44     10085324.89      2696207.36     10085910.43
#Sta/Elev= 30
  4313.2 2008.64  4550.6 1998.98  4675.4 1992.52  4775.4 1979.87  4835.4 1967.85
  4875.4 1952.84  4914.0 1955.90  4938.2 1955.53  4979.6 1957.43  4996.7 1956.52
  5022.4 1954.43  5029.0 1956.14  5050.9 1956.71  5055.0 1953.77  5074.4 1955.23
  5079.8 1951.16  5098.2 1951.65  5100.6 1948.86  5103.4 1948.36  5106.6 1948.86
  5111.2 1949.07  5132.9 1950.16  5151.3 1954.93  5190.7 1958.95  5215.9 1960.86
  5320.5 1965.12  5423.6 1970.81  5541.2 1974.54  5595.9 1978.90  5690.9 1983.04
#Mann=11,-1,0
  4313.2     0.1       0  4550.6    0.16       0  4938.2     0.1       0
  4996.7    0.05       0  5100.6   0.035       0  5106.6    0.05       0
  5111.2    0.16       0  5190.7     0.1       0  5215.9    0.16       0
  5320.5     0.1       0  5595.9    0.16       0
Bank Sta=5100.6,5106.6
Exp/Cntr=0.3,0.1

Type RM Length L Ch R = 1,126,0,0,0
BEGIN DESCRIPTION:
UNT 0075 IN HEWA 1.0
END DESCRIPTION:
XS GIS Cut Line= 4
      2697150.67     10085214.21      2696516.55     10085175.15
      2696396.75     10085314.47      2696184.81     10085899.60
#Sta/Elev= 30
  4283.2 2007.70  4530.1 1998.16  4531.7 1998.07  4626.1 1992.71  4699.4 1984.35
  4736.3 1978.42  4786.4 1967.70  4836.5 1952.79  4876.7 1945.39  4896.6 1941.00
  4920.9 1941.49  4937.5 1944.17  4972.6 1942.01  5008.8 1942.31  5012.4 1940.83
  5015.2 1940.33  5018.4 1940.83  5029.7 1943.28  5036.3 1942.39  5052.8 1944.50
  5087.8 1944.46  5104.5 1944.56  5133.4 1950.38  5165.3 1949.08  5267.5 1957.15
  5370.4 1965.16  5405.1 1968.84  5552.9 1973.73  5634.7 1979.26  5724.6 1982.65
#Mann=11,-1,0
  4283.2    0.16       0  4530.1     0.1       0  4531.7    0.16       0
  4876.7     0.1       0  5012.4    0.07       0  5018.4     0.1       0
  5052.8    0.05       0  5087.8     0.1       0  5267.5    0.16       0
  5370.4     0.1       0  5634.7    0.16       0
Bank Sta=5012.4,5018.4
Exp/Cntr=0.3,0.1

Chan Stop Cuts=-1