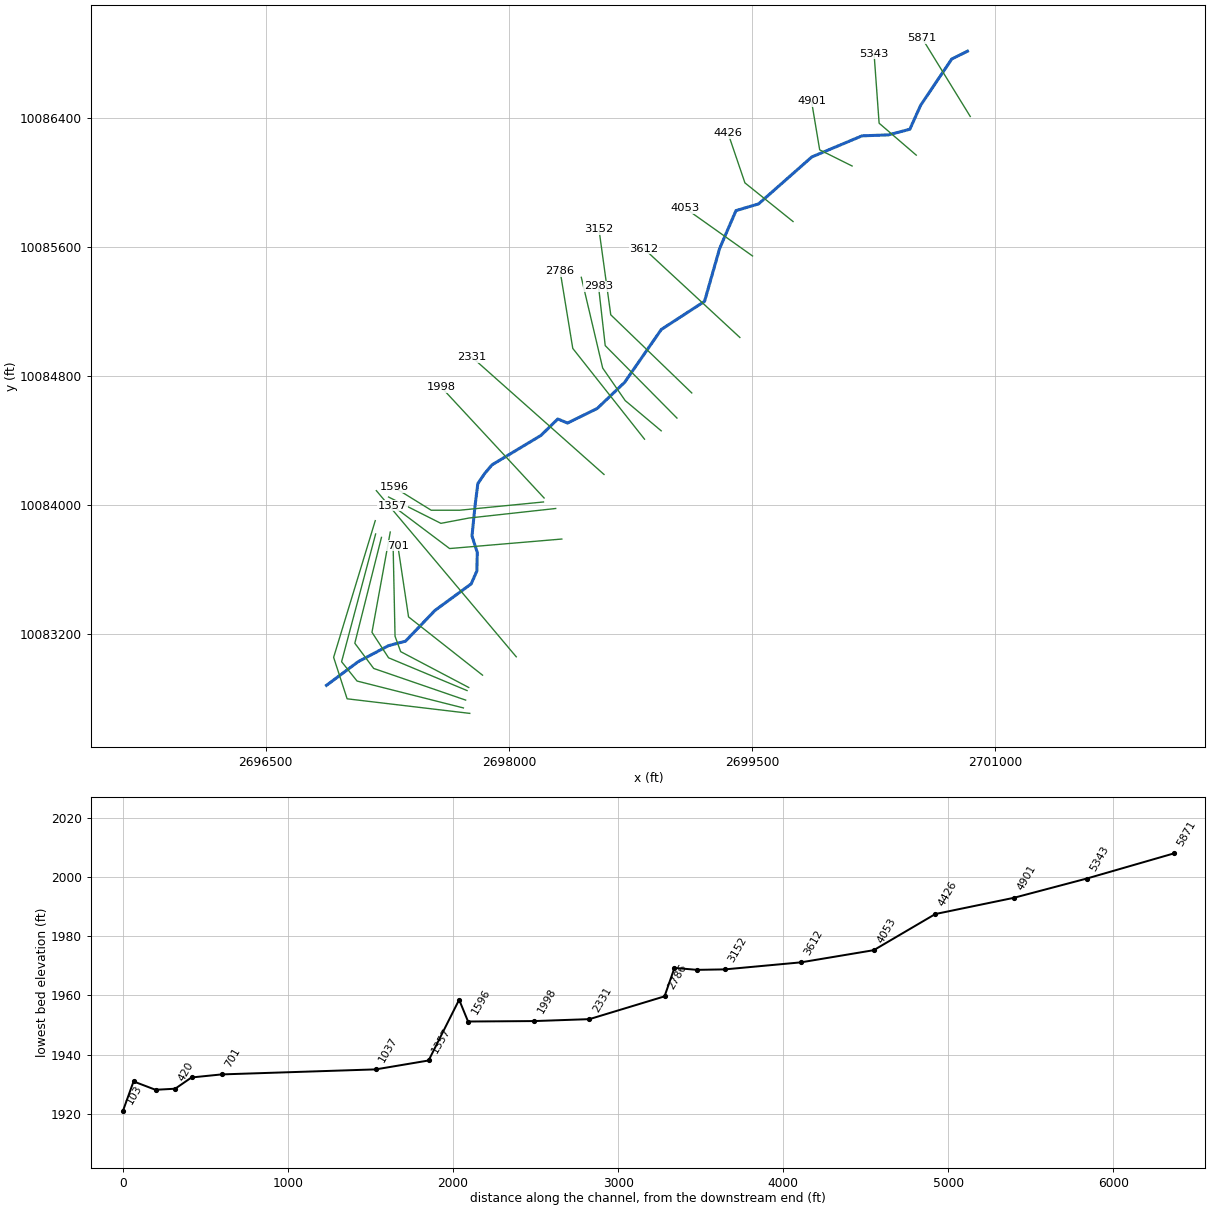
--- UNT 0076 IN HEWA.prj (project) ---

Proj Title=UNT 0076 IN HEWA Base Level Engineering
Current Plan=p01
Default Exp/Contr=0.3,0.1
English Units
Geom File=g01
Flow File=f01
Plan File=p01
Y Axis Title=Elevation
X Axis Title(PF)=Main Channel Distance
X Axis Title(XS)=Station
BEGIN DESCRIPTION:
UNT 0076 IN HEWA
END DESCRIPTION:
DSS Export Rating Curves= 0
DSS Export Rating Curve Sorted= 0
DSS Export Volume Flow Curves= 0
DXF OffsetX= 0
DXF OffsetY= 0
DXF ScaleX= 1
DXF ScaleY= 10

--- UNT 0076 IN HEWA.p01 (plan) ---

Plan Title=Multiple Run
Short Identifier=Multiple
Geom File=g01
Flow File=f01
Subcritical Flow
K Sum by GR= 0
Std Step Tol= 0.01
Critical Tol= 0.01
Num of Std Step Trials= 20
Max Error Tol= 0.3
Flow Tol Ratio= 0.001
Split Flow NTrial= 30
Split Flow Tol= 0.02
Split Flow Ratio= 0.02
Log Output Level= 0
Friction Slope Method= 1
Unsteady Friction Slope Method= 2
Unsteady Bridges Friction Slope Method= 1
Parabolic Critical Depth
Global Vel Dist=  1 , 1 , 1
Global Log Level= 0
CheckData=True
Encroach Param= -1, 0, 0, 0
BEGIN DESCRIPTION:
Multiple Run
END DESCRIPTION:

--- UNT 0076 IN HEWA.f01 (steady flow) ---

Flow Title=Multiple
Program Version=4.10
Number of Profiles= 7
Profile Names=10-year,25-year,50-year,1pct_min,100-year,1pct_plu,500-year
River Rch & RM=UNT 0076 IN HEWA,Reach-1         ,5871
    1189    1740    2219    2064    2792    3775    4415
River Rch & RM=UNT 0076 IN HEWA,Reach-1         ,4426
    1632    2428    3130    2940    3976    5377    6414
Boundary for River Rch & Prof#=UNT 0076 IN HEWA,Reach-1         , 1
Up Type= 0
Dn Type= 3
Dn Slope=0.015
Boundary for River Rch & Prof#=UNT 0076 IN HEWA,Reach-1         , 2
Up Type= 0
Dn Type= 3
Dn Slope=0.015
Boundary for River Rch & Prof#=UNT 0076 IN HEWA,Reach-1         , 3
Up Type= 0
Dn Type= 3
Dn Slope=0.015
Boundary for River Rch & Prof#=UNT 0076 IN HEWA,Reach-1         , 4
Up Type= 0
Dn Type= 3
Dn Slope=0.015
Boundary for River Rch & Prof#=UNT 0076 IN HEWA,Reach-1         , 5
Up Type= 0
Dn Type= 3
Dn Slope=0.015
Boundary for River Rch & Prof#=UNT 0076 IN HEWA,Reach-1         , 6
Up Type= 0
Dn Type= 3
Dn Slope=0.015
Boundary for River Rch & Prof#=UNT 0076 IN HEWA,Reach-1         , 7
Up Type= 0
Dn Type= 3
Dn Slope=0.015
DSS Import GetInterval= 0
DSS Import GetPeak= 0
DSS Import FillOption= 0

--- UNT 0076 IN HEWA.g01 (geometry) ---

Geom Title=Existing Conditions
Program Version=4.10

River Reach=UNT 0076 IN HEWA,Reach-1
Reach XY= 30
      2700830.84     10086815.36      2700733.39     10086766.62
      2700541.82     10086480.28      2700474.96     10086331.58
      2700342.99     10086296.48      2700179.77     10086290.59
      2699870.08     10086159.84      2699541.15     10085868.63
      2699401.89     10085827.13      2699301.15     10085592.62
      2699207.85     10085264.54      2698940.87     10085090.39
      2698714.99     10084762.97      2698545.73     10084600.88
      2698362.43      10084510.5      2698302.02     10084535.54
      2698198.47     10084433.73      2697896.25     10084251.38
      2697850.88     10084197.45      2697808.66     10084134.88
      2697791.23     10083995.78      2697772.72     10083810.27
      2697805.31     10083708.09      2697802.64     10083593.63
      2697767.68     10083513.45      2697544.46     10083349.25
      2697362.43     10083158.61       2697257.3     10083130.44
      2697070.55     10083031.42      2696874.45     10082884.58

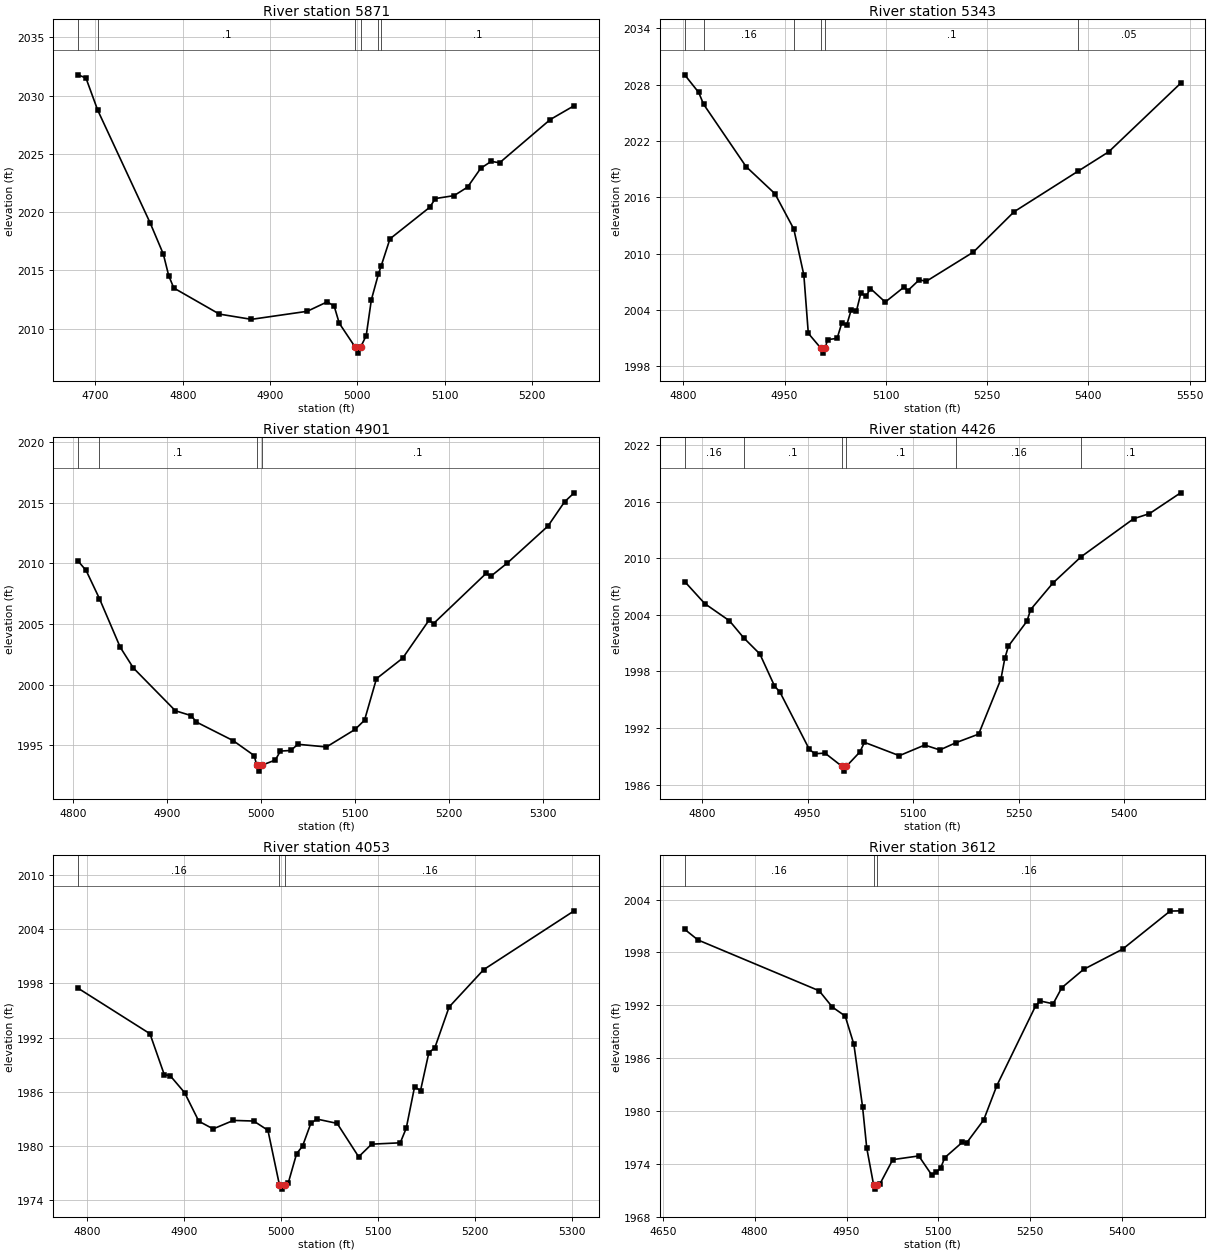
Type RM Length L Ch R = 1 ,5871    ,528,528,528
BEGIN DESCRIPTION:
UNT 0076 IN HEWA 13.0
END DESCRIPTION:
XS GIS Cut Line= 2
      2700847.78     10086410.58      2700550.92     10086894.94
#Sta/Elev= 30
  4680.3 2031.78  4689.2  2031.5  4702.6 2028.75  4762.7 2019.07  4777.8 2016.39
    4784 2014.53  4789.8 2013.48    4842 2011.24  4878.7 2010.79  4942.6 2011.48
  4965.5 2012.29  4973.5 2011.93  4979.3 2010.46  4997.7 2008.39  5000.4 2007.89
  5003.7 2008.39  5010.2 2009.39  5016.1 2012.47  5024.2 2014.68  5027.5 2015.41
  5037.4  2017.7  5082.8  2020.4  5089.5 2021.16  5110.8 2021.41  5126.3 2022.14
  5141.4 2023.76  5153.4 2024.35    5163 2024.23    5221 2027.94  5248.4 2029.13
#Mann= 6 ,-1 , 0
  4680.3     .16       0  4702.6      .1       0  4997.7     .07       0
  5003.7      .1       0  5024.2     .16       0  5027.5      .1       0
Bank Sta=4997.7,5003.7
XS Rating Curve= 0 ,0
Exp/Cntr=0.3,0.1

Type RM Length L Ch R = 1 ,5343    ,442,442,442
BEGIN DESCRIPTION:
UNT 0076 IN HEWA 12.0
END DESCRIPTION:
XS GIS Cut Line= 3
      2700514.42     10086171.01       2700285.3     10086368.89
      2700254.14     10086799.92
#Sta/Elev= 30
  4801.9 2029.05  4822.7 2027.17  4829.8 2025.93  4892.9 2019.27  4935.7 2016.38
  4963.6 2012.62  4978.5 2007.72  4985.1 2001.51    5004  1999.9  5006.7  1999.4
    5010  1999.9  5013.6 2000.84  5027.8 2000.97  5034.5 2002.56  5042.1 2002.41
  5048.7 2004.02  5056.4 2003.89    5063  2005.8  5070.6 2005.46  5077.2 2006.28
  5099.1 2004.84  5127.3 2006.46  5132.3 2006.04  5149.6 2007.22  5159.6 2007.04
  5229.8 2010.17    5290 2014.46  5384.3 2018.76  5430.3 2020.85  5536.8 2028.15
#Mann= 6 ,-1 , 0
  4801.9      .1       0  4829.8     .16       0  4963.6      .1       0
    5004     .07       0    5010      .1       0  5384.3     .05       0
Bank Sta=5004,5010
XS Rating Curve= 0 ,0
Exp/Cntr=0.3,0.1

Type RM Length L Ch R = 1 ,4901    ,475,475,475
BEGIN DESCRIPTION:
UNT 0076 IN HEWA 11.0
END DESCRIPTION:
XS GIS Cut Line= 3
      2700118.49     10086103.72      2699918.47     10086203.73
      2699868.46     10086503.76
#Sta/Elev= 30
  4805.6 2010.17    4814 2009.41  4828.2 2007.09  4850.3 2003.09  4864.3 2001.38
    4909 1997.86  4925.8 1997.46  4931.4 1996.93  4970.5  1995.4  4992.9 1994.17
  4995.5 1993.39  4998.2 1992.89  5001.5 1993.39  5015.3  1993.8  5020.8 1994.54
  5031.8 1994.59  5039.4  1995.1  5069.8 1994.88  5100.2 1996.32  5110.3 1997.08
    5123  2000.5  5150.9 2002.19  5178.8  2005.3  5183.8 2005.04  5239.6 2009.16
  5244.7 2008.93  5262.4 2010.03  5305.5 2013.06  5323.2 2015.06  5333.4  2015.8
#Mann= 4 ,-1 , 0
  4805.6     .16       0  4828.2      .1       0  4995.5     .07       0
  5001.5      .1       0
Bank Sta=4995.5,5001.5
XS Rating Curve= 0 ,0
Exp/Cntr=0.3,0.1

Type RM Length L Ch R = 1 ,4426    ,373,373,373
BEGIN DESCRIPTION:
UNT 0076 IN HEWA 10.0
END DESCRIPTION:
XS GIS Cut Line= 3
      2699754.04     10085759.53      2699457.17      10085999.1
      2699353.24     10086305.69
#Sta/Elev= 30
  4775.3 2007.55  4803.8 2005.21    4839 2003.38  4859.4 2001.56  4882.2 1999.86
    4903 1996.47  4910.9 1995.79  4952.6 1989.72  4960.5 1989.27  4974.9 1989.33
  4999.1 1987.92  5001.9 1987.42  5005.1 1987.92  5024.5 1989.46  5030.9 1990.48
  5080.5 1989.06  5116.6 1990.19  5138.1 1989.67  5161.4 1990.45  5193.3 1991.35
    5225  1997.2  5230.5 1999.39  5235.7  2000.7  5261.9 2003.33  5267.3 2004.58
  5298.9 2007.39  5338.8 2010.17  5413.7 2014.22  5436.2 2014.76  5480.5 2016.97
#Mann= 6 ,-1 , 0
  4775.3     .16       0  4859.4      .1       0  4999.1     .07       0
  5005.1      .1       0  5161.4     .16       0  5338.8      .1       0
Bank Sta=4999.1,5005.1
XS Rating Curve= 0 ,0
Exp/Cntr=0.3,0.1

Type RM Length L Ch R = 1 ,4053    ,441,441,441
BEGIN DESCRIPTION:
UNT 0076 IN HEWA 9.0
END DESCRIPTION:
XS GIS Cut Line= 2
      2699504.05     10085545.97      2699087.39     10085842.84
#Sta/Elev= 30
  4790.6 1997.46  4864.6 1992.43  4879.4 1987.89  4885.5 1987.78  4900.3 1985.91
    4915 1982.74  4929.8 1981.89  4950.7 1982.83  4971.6 1982.76  4986.3 1981.74
  4998.1 1975.72  5000.9 1975.22  5004.1 1975.72  5007.2 1975.87  5015.9 1979.15
    5022 1979.98  5030.6 1982.51  5036.8 1982.98  5057.7  1982.5  5079.9  1978.8
  5093.3  1980.2  5122.8 1980.35    5129 1981.97  5137.6 1986.56  5143.7 1986.12
  5152.3 1990.33  5158.5 1990.88  5173.2 1995.39  5208.9 1999.53  5302.2 2006.04
#Mann= 3 ,-1 , 0
  4790.6     .16       0  4998.1     .07       0  5004.1     .16       0
Bank Sta=4998.1,5004.1
XS Rating Curve= 0 ,0
Exp/Cntr=0.3,0.1

Type RM Length L Ch R = 1 ,3612    ,460,460,460
BEGIN DESCRIPTION:
UNT 0076 IN HEWA 8.0
END DESCRIPTION:
XS GIS Cut Line= 2
      2699425.95     10085040.74      2698832.83     10085592.23
#Sta/Elev= 30
  4685.7 2000.62  4707.4 1999.41  4905.3 1993.64  4926.8 1991.79  4947.8 1990.77
    4962 1987.56  4976.2 1980.46    4983 1975.79  4994.2 1971.61  4996.9 1971.11
  5000.2 1971.61  5004.5 1971.69  5025.5 1974.46    5068 1974.88  5089.5 1972.68
  5096.3 1973.01  5103.7 1973.51  5110.5 1974.69  5138.9 1976.42  5146.2 1976.37
    5174 1978.97  5195.5 1982.87    5259 1991.95  5266.4 1992.48  5287.4 1992.16
  5301.6 1993.99  5337.2 1996.07  5400.7 1998.36  5478.4 2002.69  5495.6 2002.72
#Mann= 3 ,-1 , 0
  4685.7     .16       0  4994.2     .07       0  5000.2     .16       0
Bank Sta=4994.2,5000.2
XS Rating Curve= 0 ,0
Exp/Cntr=0.3,0.1

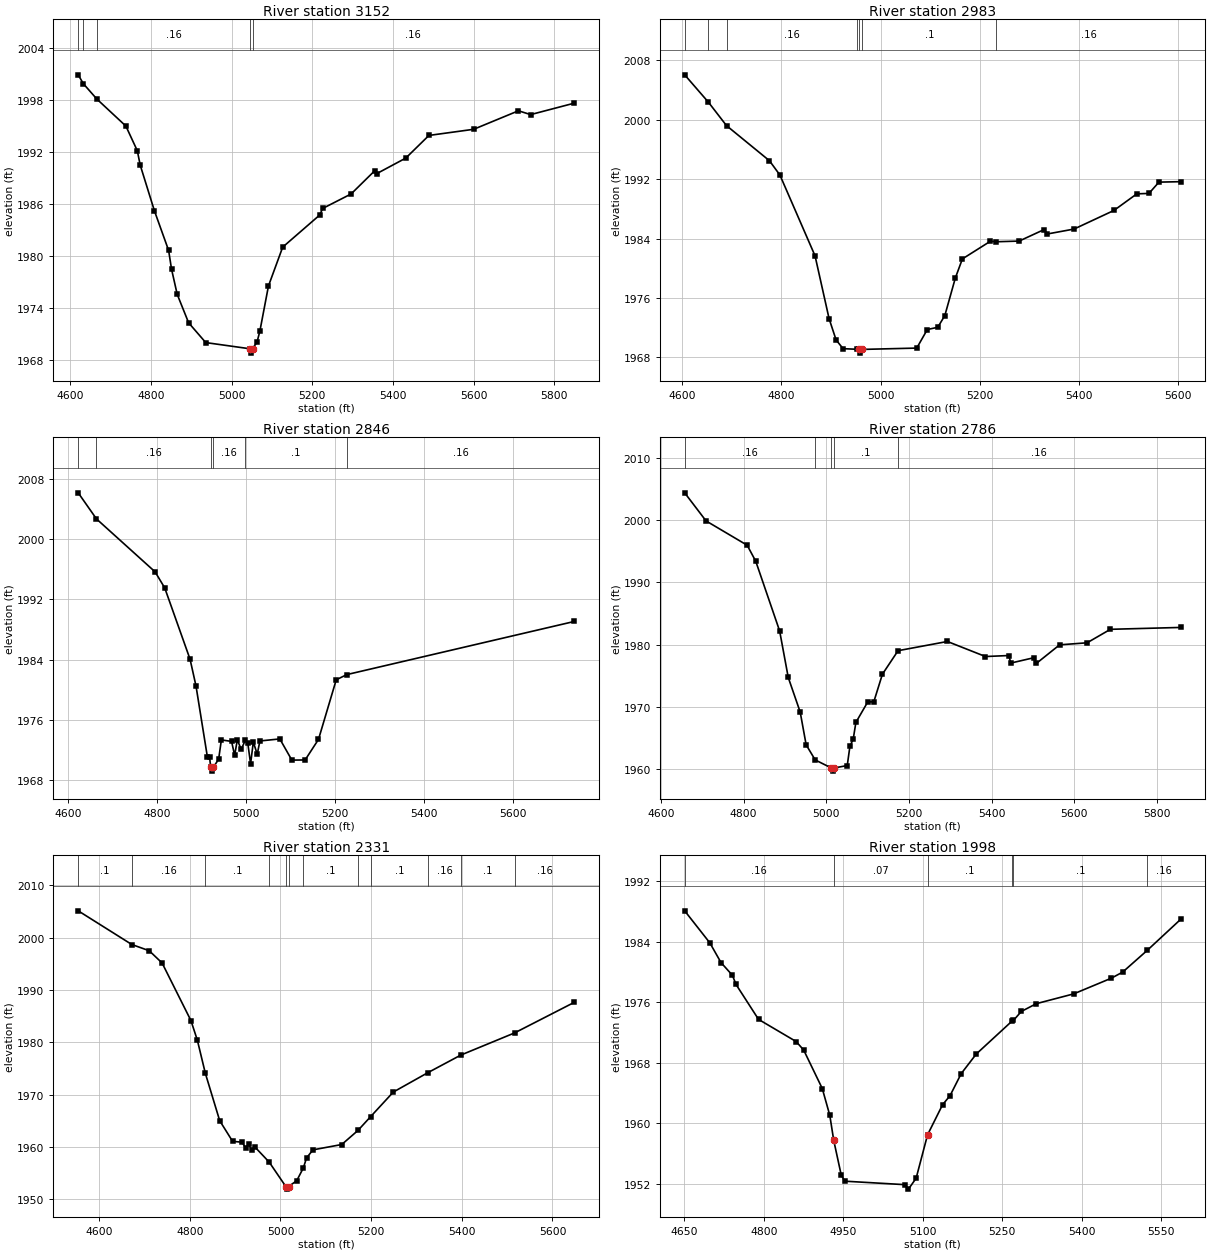
Type RM Length L Ch R = 1 ,3152    ,169,169,169
BEGIN DESCRIPTION:
UNT 0076 IN HEWA 7.0
END DESCRIPTION:
XS GIS Cut Line= 3
      2699129.06     10084697.01      2698629.05     10085181.39
       2698556.4     10085710.67
#Sta/Elev= 30
  4619.3 2000.93  4631.9 1999.91  4665.5 1998.13  4737.6    1995  4765.9 1992.15
  4773.1 1990.49  4808.3 1985.21  4843.6 1980.62  4850.8 1978.46  4864.9 1975.54
  4893.2 1972.25  4935.7 1969.96  5045.9 1969.24  5048.6 1968.74  5051.9 1969.24
    5063 1970.03    5070 1971.29  5091.3 1976.51  5126.6    1981  5218.6 1984.72
  5225.6 1985.47  5296.3 1987.15  5354.8 1989.83  5359.9  1989.5    5432  1991.3
  5489.4 1993.92  5600.4 1994.63  5711.5 1996.77  5741.8 1996.33  5849.7 1997.65
#Mann= 5 ,-1 , 0
  4619.3     .16       0  4631.9      .1       0  4665.5     .16       0
  5045.9     .07       0  5051.9     .16       0
Bank Sta=5045.9,5051.9
XS Rating Curve= 0 ,0
Exp/Cntr=0.3,0.1

Type RM Length L Ch R = 1 ,2983    ,137,137,137
BEGIN DESCRIPTION:
Mapping XS 3e5e8909
END DESCRIPTION:
XS GIS Cut Line= 3
      2699037.59     10084541.25       2698594.9     10084990.45
      2698553.67     10085357.17
#Sta/Elev= 30
  4605.1 2006.06  4653.1 2002.36  4689.4 1999.22    4776 1994.49  4797.1 1992.56
  4867.9 1981.68  4896.2 1973.22  4910.3 1970.36  4924.4 1969.18    4952  1969.1
  4956.7 1969.08  4959.5 1968.58  4962.7 1969.08  5072.9 1969.26  5094.2 1971.76
  5115.3 1972.06  5129.5 1973.64  5150.7  1978.7  5164.9 1981.27  5221.4 1983.65
  5233.5 1983.58  5279.3 1983.67  5329.6 1985.22  5336.4 1984.63    5390 1985.29
  5470.5  1987.8  5516.5 1990.03    5541 1990.09  5561.1 1991.61  5604.8 1991.67
#Mann= 7 ,-1 , 0
  4605.1     .16       0  4653.1      .1       0  4689.4     .16       0
    4952      .1       0  4956.7     .07       0  4962.7      .1       0
  5233.5     .16       0
Bank Sta=4956.7,4962.7
XS Rating Curve= 0 ,0
Exp/Cntr=0.3,0.1

Type RM Length L Ch R = 1 ,2846    ,60,60,60
BEGIN DESCRIPTION:
Mapping XS e2e003a4
END DESCRIPTION:
XS GIS Cut Line= 4
      2698940.37     10084462.25      2698718.17     10084649.73
      2698579.28     10084851.12      2698447.34     10085413.59
#Sta/Elev= 30
  4623.4 2006.13  4664.4 2002.67    4796 1995.65  4817.6 1993.52  4874.5 1984.05
  4887.8 1980.51  4913.4 1971.09  4918.3 1971.09  4920.7 1969.73  4923.5 1969.23
  4926.7 1969.73  4938.6 1970.82  4944.7 1973.37  4967.6 1973.17  4974.5 1971.32
  4980.5 1973.38  4989.3  1972.1  4998.4 1973.34    5004 1972.94  5010.3  1970.2
  5016.4 1973.09  5025.2 1971.47  5031.2 1973.23  5075.9  1973.5  5102.9 1970.69
  5132.7 1970.71  5162.7 1973.44  5202.5 1981.34  5226.3 1982.03  5736.5 1989.07
#Mann= 6 ,-1 , 0
  4623.4      .1       0  4664.4     .16       0  4920.7     .07       0
  4926.7     .16       0  4998.4      .1       0  5226.3     .16       0
Bank Sta=4920.7,4926.7
XS Rating Curve= 0 ,0
Exp/Cntr=0.3,0.1

Type RM Length L Ch R = 1 ,2786    ,455,455,455
BEGIN DESCRIPTION:
UNT 0076 IN HEWA 6.0
END DESCRIPTION:
XS GIS Cut Line= 3
      2698837.36     10084410.59      2698394.67     10084973.06
      2698316.83     10085450.47
#Sta/Elev= 30
  4657.7 2004.41  4709.4 1999.89  4808.8 1995.98  4829.6  1993.4  4887.4 1982.18
  4908.2  1974.7  4937.1 1969.13  4951.5 1963.86  4973.4 1961.43  5012.7 1960.13
  5015.4 1959.63  5018.7 1960.13  5050.9 1960.53  5057.3  1963.6  5065.4 1964.81
  5071.8 1967.47  5100.6 1970.78  5115.1 1970.78  5135.9 1975.22  5173.8 1979.01
  5293.1 1980.49  5385.2 1978.07  5441.6 1978.23  5446.6 1977.02    5503 1977.89
  5508.1 1976.95  5564.5 1979.95    5631 1980.28  5687.4 1982.45  5857.2 1982.75
#Mann= 5 ,-1 , 0
  4657.7     .16       0  4973.4      .1       0  5012.7     .07       0
  5018.7      .1       0  5173.8     .16       0
Bank Sta=5012.7,5018.7
XS Rating Curve= 0 ,0
Exp/Cntr=0.3,0.1

Type RM Length L Ch R = 1 ,2331    ,333,333,333
BEGIN DESCRIPTION:
UNT 0076 IN HEWA 5.0
END DESCRIPTION:
XS GIS Cut Line= 2
      2698587.36     10084191.83      2697770.91     10084919.87
#Sta/Elev= 30
  4553.9 2005.15  4672.1 1998.71  4710.5 1997.52  4738.9 1995.18  4802.5 1984.17
  4816.7 1980.41  4834.3 1974.09    4866 1965.02  4894.4 1961.08  4915.4 1960.91
  4922.9 1959.87  4929.6  1960.5  4937.1 1959.41  4943.8 1959.98  4975.2  1957.1
  5011.8 1952.44  5014.6 1951.94  5017.8 1952.44  5035.8 1953.54  5050.5    1956
  5057.5  1957.9  5071.7 1959.45  5135.2 1960.47  5170.8 1963.15  5199.1 1965.82
  5248.9  1970.5  5325.6 1974.23  5397.8 1977.57  5516.5 1981.81  5647.8 1987.64
#Mann= 12 ,-1 , 0
  4553.9      .1       0  4672.1     .16       0  4834.3      .1       0
  4975.2     .05       0  5011.8    .035       0  5017.8     .05       0
  5050.5      .1       0  5170.8     .05       0  5199.1      .1       0
  5325.6     .16       0  5397.8      .1       0  5516.5     .16       0
Bank Sta=5011.8,5017.8
XS Rating Curve= 0 ,0
Exp/Cntr=0.3,0.1

Type RM Length L Ch R = 1 ,1998    ,402,402,402
BEGIN DESCRIPTION:
UNT 0076 IN HEWA 4.0
END DESCRIPTION:
XS GIS Cut Line= 2
      2698217.62     10084045.94      2697582.79     10084732.81
#Sta/Elev= 30
  4650.9 1988.08  4698.4 1983.84  4719.4 1981.24  4740.9 1979.56  4747.7 1978.35
  4790.2 1973.73  4861.1  1970.8  4875.3 1969.68  4910.4 1964.59  4924.6 1961.04
    4932 1957.73  4946.2 1953.13    4953 1952.34  5066.4 1951.88  5072.9 1951.29
  5087.4 1952.73  5108.9 1958.46  5137.2 1962.44  5151.4 1963.65  5172.4 1966.56
  5200.8 1969.15  5268.5 1973.52  5270.9 1973.59  5285.8 1974.78  5314.2 1975.81
  5384.5  1977.1  5455.4 1979.17  5476.9 1979.98  5523.2 1982.85  5586.2 1986.95
#Mann= 6 ,-1 , 0
  4650.9     .16       0    4932     .07       0  5108.9      .1       0
  5268.5     .05       0  5270.9      .1       0  5523.2     .16       0
Bank Sta=4932,5108.9
XS Rating Curve= 0 ,0
Exp/Cntr=0.3,0.1

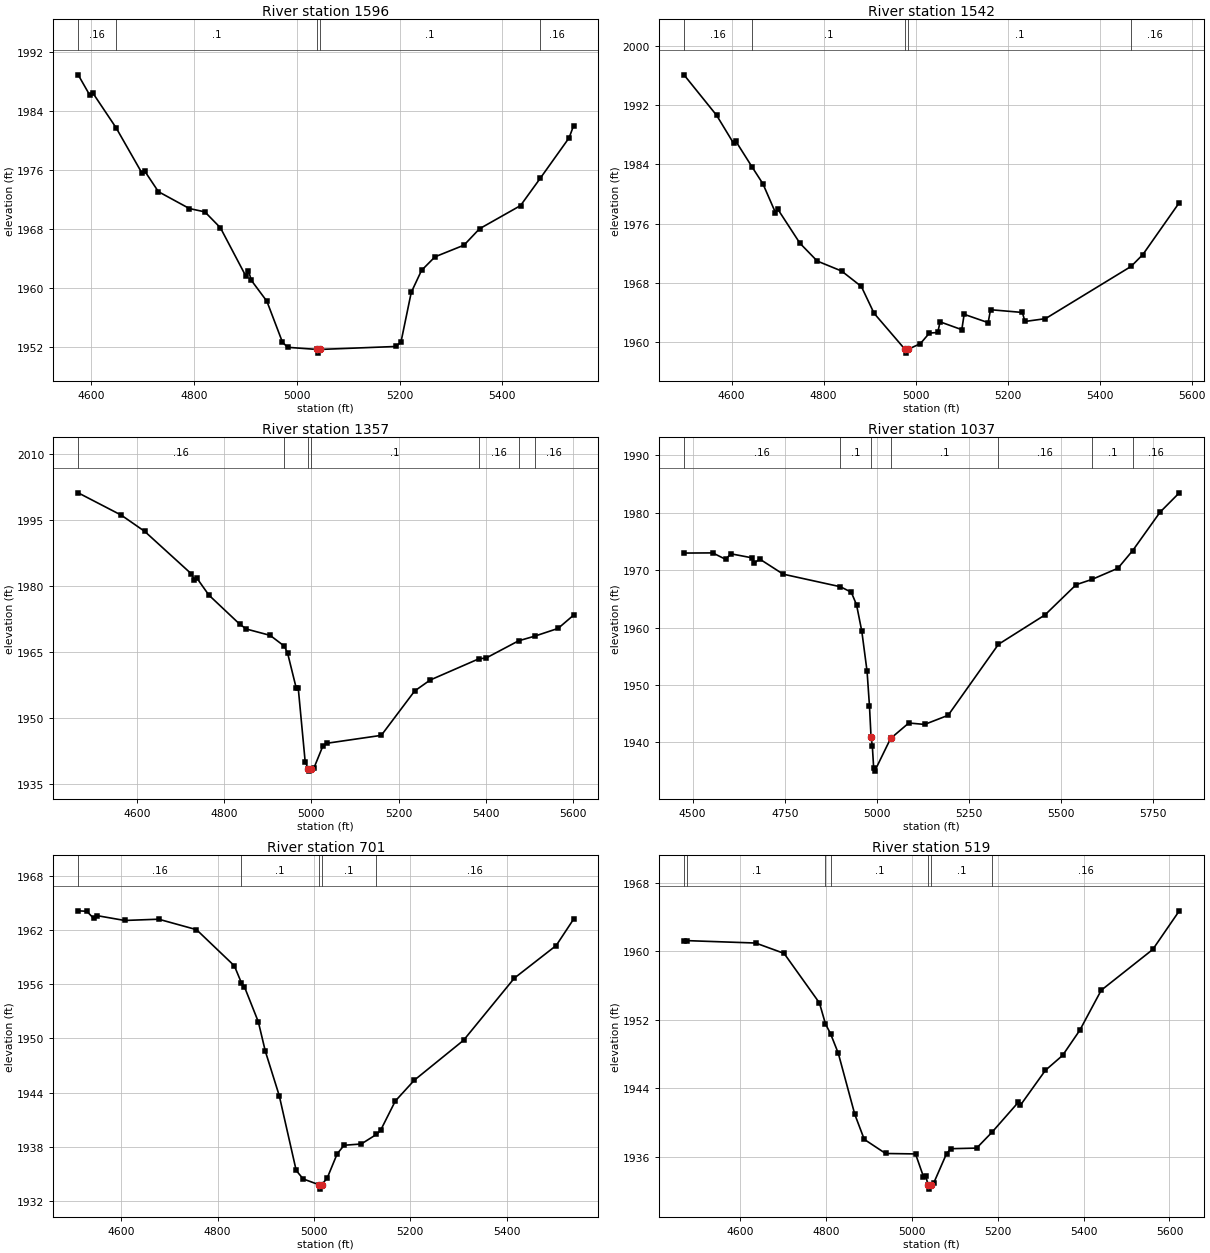
Type RM Length L Ch R = 1 ,1596    ,54,54,54
BEGIN DESCRIPTION:
Mapping XS 94879745
END DESCRIPTION:
XS GIS Cut Line= 4
       2698213.7     10084021.25      2697695.47     10083970.03
      2697520.99     10083970.03      2697293.05      10084111.3
#Sta/Elev= 30
  4574.9 1988.85  4597.8 1986.05  4602.9 1986.44  4648.6 1981.68  4698.9 1975.54
  4703.9 1975.85  4730.9 1973.02  4791.2 1970.73  4821.3 1970.28  4851.5 1968.13
  4901.1 1961.56  4906.1 1962.28  4911.8 1960.99  4941.9 1958.17  4972.1 1952.64
  4982.1 1951.93  5039.4 1951.64  5042.1 1951.14  5045.4 1951.64  5192.7 1952.04
  5202.7 1952.63  5222.7 1959.37  5242.7 1962.35  5268.9 1964.19  5325.3 1965.77
  5355.5 1967.99  5435.2 1971.13  5473.6 1974.83  5529.7 1980.31  5538.3 1981.93
#Mann= 5 ,-1 , 0
  4574.9     .16       0  4648.6      .1       0  5039.4     .07       0
  5045.4      .1       0  5473.6     .16       0
Bank Sta=5039.4,5045.4
XS Rating Curve= 0 ,0
Exp/Cntr=0.3,0.1

Type RM Length L Ch R = 1 ,1542    ,185,185,185
BEGIN DESCRIPTION:
UNT 0076 IN HEWA 3.0
END DESCRIPTION:
XS GIS Cut Line= 4
      2698289.04     10083980.77      2697754.34     10083921.74
      2697580.73     10083888.76      2697257.79     10084051.96
#Sta/Elev= 30
  4496.7 1996.12  4567.7 1990.64  4604.6 1986.85  4609.7 1987.11  4644.1 1983.72
  4668.3 1981.38  4695.5 1977.49  4700.5 1977.96  4748.8 1973.34  4786.3 1970.94
  4839.3 1969.59  4882.2  1967.5  4909.8 1963.88  4977.2 1958.99  4979.9 1958.49
  4983.2 1958.99  5010.4 1959.77  5030.1  1961.2  5048.2 1961.28  5053.3 1962.72
  5100.5 1961.66  5105.6 1963.74  5157.8 1962.61  5162.9 1964.36  5232.1 1963.99
  5237.7 1962.77  5282.3 1963.15  5468.5 1970.22    5494 1971.82  5573.2 1978.84
#Mann= 5 ,-1 , 0
  4496.7     .16       0  4644.1      .1       0  4977.2     .07       0
  4983.2      .1       0  5468.5     .16       0
Bank Sta=4977.2,4983.2
XS Rating Curve= 0 ,0
Exp/Cntr=0.3,0.1

Type RM Length L Ch R = 1 ,1357    ,320,320,320
BEGIN DESCRIPTION:
Mapping XS 4d6c0a86
END DESCRIPTION:
XS GIS Cut Line= 3
      2698327.22     10083791.53      2697634.55     10083732.51
      2697282.65     10083998.16
#Sta/Elev= 30
  4465.2 2001.24  4564.3 1996.15  4617.7 1992.48  4724.9 1982.81  4731.8 1981.44
  4736.8 1981.94    4765 1977.99  4835.3 1971.42  4850.9 1970.28  4905.5 1968.84
  4938.4 1966.36  4945.7 1964.73    4965 1956.98    4970 1956.81  4985.8 1940.14
  4992.9 1938.48  4995.6 1937.98  4998.9 1938.48  5005.9 1938.68    5026 1943.59
    5036 1944.32  5160.4 1946.11    5237  1956.2  5272.4 1958.68  5383.5 1963.48
  5401.4 1963.72  5475.3  1967.6    5512 1968.65  5565.9 1970.42  5601.3 1973.42
#Mann= 7 ,-1 , 0
  4465.2     .16       0  4938.4      .1       0  4992.9     .07       0
  4998.9      .1       0  5383.5     .16       0  5475.3      .1       0
    5512     .16       0
Bank Sta=4992.9,4998.9
XS Rating Curve= 0 ,0
Exp/Cntr=0.3,0.1

Type RM Length L Ch R = 1 ,1037    ,934,934,934
BEGIN DESCRIPTION:
UNT 0076 IN HEWA 2.0
END DESCRIPTION:
XS GIS Cut Line= 2
      2698045.69     10083061.63      2697182.28     10084091.48
#Sta/Elev= 30
  4476.5 1972.99  4554.4 1973.02  4589.5  1971.9  4603.8 1972.86  4661.1 1972.16
  4667.6 1971.26  4681.9 1971.95  4745.7 1969.31  4900.9 1967.12  4930.4 1966.17
  4944.7 1963.97    4959 1959.35  4973.3 1952.35  4979.8 1946.31 4983.96    1941
  4987.6  1939.3  4991.2 1935.48  4993.9 1934.98  5037.1 1940.67  5086.5 1943.37
  5129.4 1943.12  5193.2 1944.71  5329.6 1957.08    5456 1962.21  5540.6 1967.48
  5583.2 1968.39  5653.8 1970.34    5694 1973.43  5768.2 1980.12  5820.4 1983.49
#Mann= 7 ,-1 , 0
  4476.5     .16       0  4900.9      .1       0 4983.96     .07       0
  5037.1      .1       0  5329.6     .16       0  5583.2      .1       0
    5694     .16       0
Bank Sta=4983.96,5037.1
XS Rating Curve= 0 ,0
Exp/Cntr=0.3,0.1

Type RM Length L Ch R = 1 ,701     ,182,182,182
BEGIN DESCRIPTION:
Mapping XS 63579c90
END DESCRIPTION:
XS GIS Cut Line= 3
      2697837.65      10082947.8      2697381.08     10083308.89
      2697315.19     10083749.28
#Sta/Elev= 30
    4511 1964.17  4528.9 1964.12  4543.3 1963.32  4549.7 1963.64  4607.4  1963.1
  4677.9 1963.24  4756.4 1962.08    4835 1958.06  4849.6 1956.17  4855.8 1955.74
  4884.7 1951.84  4899.1  1948.6    4928 1943.66  4963.2 1935.35  4977.7 1934.41
  5009.9 1933.78  5012.7 1933.28  5015.9 1933.78  5027.3 1934.48  5048.2  1937.2
  5062.6 1938.15  5098.1 1938.29  5129.6 1939.35  5138.4 1939.82  5168.8 1943.06
  5208.2 1945.37  5310.3  1949.8  5415.7  1956.7  5502.5 1960.32  5538.4 1963.23
#Mann= 5 ,-1 , 0
    4511     .16       0  4849.6      .1       0  5009.9     .07       0
  5015.9      .1       0  5129.6     .16       0
Bank Sta=5009.9,5015.9
XS Rating Curve= 0 ,0
Exp/Cntr=0.3,0.1

Type RM Length L Ch R = 1 ,519     ,99,99,99
BEGIN DESCRIPTION:
Mapping XS 6327e061
END DESCRIPTION:
XS GIS Cut Line= 4
      2697752.59      10082871.4      2697332.47     10083093.62
      2697297.74      10083189.1      2697285.59      10083765.5
#Sta/Elev= 30
  4469.5 1961.27    4477 1961.26  4636.5 1960.98  4702.6 1959.77  4784.9 1953.99
  4798.9 1951.55    4811 1950.37  4828.9  1948.1  4867.3 1940.97  4889.3 1938.06
    4939 1936.41  5008.7 1936.36  5027.2  1933.7  5032.5 1933.81  5037.7 1932.75
  5040.4 1932.25  5043.7 1932.75  5051.2 1932.98    5081  1936.4    5091 1936.97
    5151 1937.04  5186.9  1938.9  5247.7 1942.37  5252.7 1942.03  5311.1 1946.12
  5351.1 1947.86  5391.1 1950.79  5441.1 1955.47  5561.1 1960.23  5622.9 1964.74
#Mann= 7 ,-1 , 0
  4469.5     .16       0    4477      .1       0  4798.9     .16       0
    4811      .1       0  5037.7     .07       0  5043.7      .1       0
  5186.9     .16       0
Bank Sta=5037.7,5043.7
XS Rating Curve= 0 ,0
Exp/Cntr=0.3,0.1

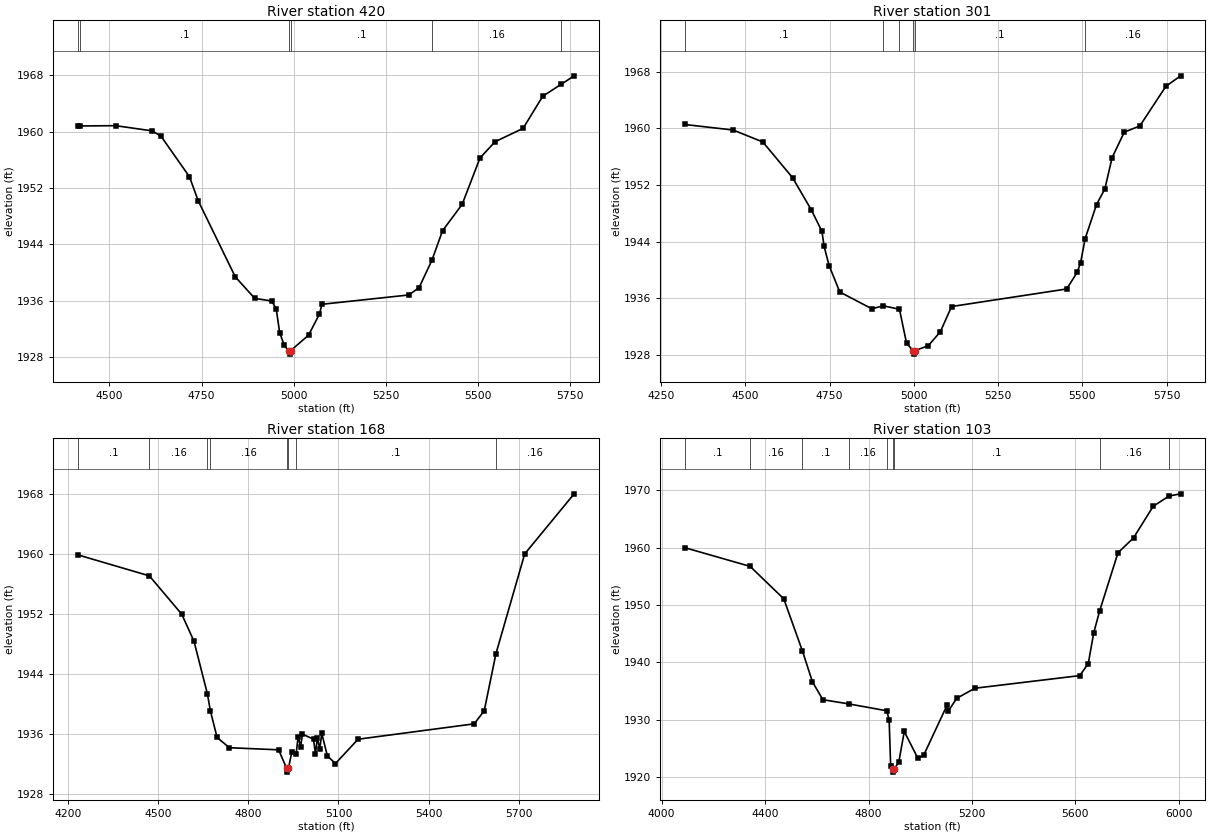
Type RM Length L Ch R = 1 ,420     ,119,119,119
BEGIN DESCRIPTION:
Mapping XS 58378828
END DESCRIPTION:
XS GIS Cut Line= 4
      2697742.18      10082852.3      2697257.81     10083055.42
      2697155.38     10083213.41      2697268.23     10083834.92
#Sta/Elev= 30
  4415.3 1960.81    4421 1960.81  4516.9 1960.85  4616.4 1960.11  4640.2 1959.33
    4717 1953.61  4740.7 1950.21  4841.2 1939.42  4894.2 1936.35  4940.5 1935.99
  4952.5 1934.82  4961.7 1931.51  4974.3 1929.68  4985.7 1928.95  4988.5 1928.45
  4991.7 1928.95  5040.1 1931.14  5069.6 1934.13  5076.4 1935.52  5312.1 1936.84
  5339.8 1937.88  5374.6 1941.75  5403.6 1945.96  5456.7 1949.69    5505 1956.26
  5545.9 1958.57    5622 1960.47  5675.4 1965.03  5725.4 1966.72  5760.5 1967.92
#Mann= 6 ,-1 , 0
  4415.3     .16       0    4421      .1       0  4985.7     .07       0
  4991.7      .1       0  5374.6     .16       0  5725.4      .1       0
Bank Sta=4985.7,4991.7
XS Rating Curve= 0 ,0
Exp/Cntr=0.3,0.1

Type RM Length L Ch R = 1 ,301     ,133,133,133
BEGIN DESCRIPTION:
Mapping XS 59a2a655
END DESCRIPTION:
XS GIS Cut Line= 4
      2697733.52     10082793.27       2697165.8     10082989.45
      2697049.48      10083145.7      2697213.93     10083801.75
#Sta/Elev= 30
    4320 1960.55  4463.7 1959.77  4551.9 1958.08  4640.2 1953.03  4695.7 1948.49
  4727.4 1945.44  4733.7 1943.34  4748.6 1940.61  4780.3 1936.87  4875.5  1934.5
  4909.6 1934.92  4957.4 1934.43  4978.4 1929.64  4997.8 1928.59  5000.5 1928.09
  5003.8 1928.59  5043.1 1929.29  5078.6 1931.24  5112.1 1934.82  5453.6  1937.3
  5484.6 1939.63  5494.9    1941  5508.3 1944.39  5542.2 1949.23    5567 1951.45
  5588.5 1955.87  5624.6 1959.47  5670.9 1960.35  5748.1 1965.95  5791.8 1967.43
#Mann= 6 ,-1 , 0
    4320      .1       0  4909.6     .16       0  4957.4      .1       0
  4997.8     .07       0  5003.8      .1       0  5508.3     .16       0
Bank Sta=4997.8,5003.8
XS Rating Curve= 0 ,0
Exp/Cntr=0.3,0.1

Type RM Length L Ch R = 1 ,168     ,65,65,65
BEGIN DESCRIPTION:
Mapping XS 2abcbeb8
END DESCRIPTION:
XS GIS Cut Line= 4
      2697719.61     10082744.66      2697063.37     10082911.32
      2696967.88     10083031.12      2697177.95     10083822.76
#Sta/Elev= 30
  4234.5 1959.82  4471.1 1957.04  4578.7 1951.94  4619.6 1948.33  4664.2 1941.32
  4673.8  1939.1  4696.4 1935.52  4737.3 1934.16  4901.1 1933.88  4927.6 1931.41
  4930.4 1930.91  4933.6 1931.41  4945.1 1933.63  4959.4 1933.38  4965.9 1935.64
  4973.9 1934.31  4980.3 1935.96    5017  1935.3  5023.5 1933.33  5029.9  1935.5
  5037.9 1933.96  5044.3 1936.08  5063.2 1933.07  5089.9 1932.05  5165.1 1935.29
  5551.5 1937.34  5584.8 1939.09  5623.6 1946.66  5719.3 1959.96  5883.8 1967.96
#Mann= 8 ,-1 , 0
  4234.5      .1       0  4471.1     .16       0  4664.2      .1       0
  4673.8     .16       0  4927.6     .07       0  4933.6     .16       0
  4959.4      .1       0  5623.6     .16       0
Bank Sta=4927.6,4933.6
XS Rating Curve= 0 ,0
Exp/Cntr=0.3,0.1

Type RM Length L Ch R = 1 ,103     ,0,0,0
BEGIN DESCRIPTION:
UNT 0076 IN HEWA 1.0
END DESCRIPTION:
XS GIS Cut Line= 4
      2697759.01     10082710.92      2697002.02     10082801.21
      2696918.69     10083058.15      2697175.63     10083905.37
#Sta/Elev= 30
    4089 1960.02  4342.1 1956.75  4472.2 1951.09  4544.4 1941.98    4583 1936.61
  4623.3 1933.49  4722.7 1932.76  4870.9 1931.55  4879.7  1929.9  4885.5 1921.94
  4893.1 1921.35  4895.8 1920.85  4899.1 1921.35  4917.1 1922.61  4938.1 1927.94
  4990.7 1923.28  5012.9 1923.76  5103.5 1932.52  5108.8 1931.51  5140.5 1933.72
  5211.5 1935.49  5616.8 1937.69  5649.7 1939.79  5670.7 1945.14  5693.9 1949.02
  5764.7 1959.13  5824.6 1961.72  5900.9 1967.24    5962 1969.03  6006.8 1969.41
#Mann= 9 ,-1 , 0
    4089      .1       0  4342.1     .16       0  4544.4      .1       0
  4722.7     .16       0  4870.9      .1       0  4893.1     .07       0
  4899.1      .1       0  5693.9     .16       0    5962      .1       0
Bank Sta=4893.1,4899.1
XS Rating Curve= 0 ,0
Exp/Cntr=0.3,0.1

Chan Stop Cuts=-1
Use User Specified Reach Order=0
Composite Channel Slope=5