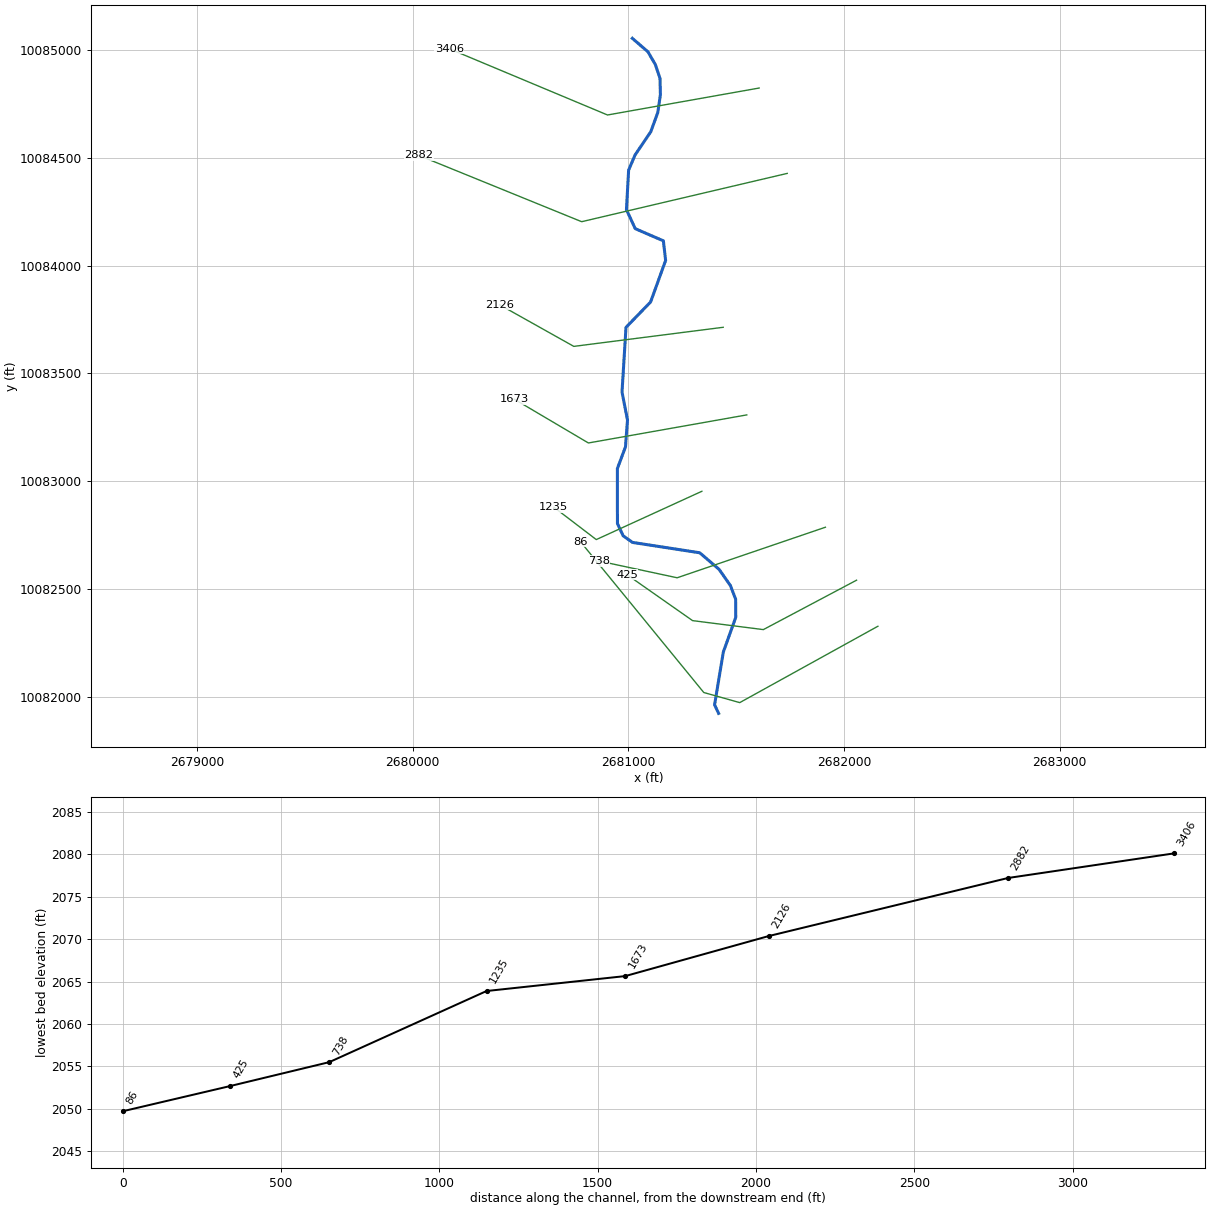
--- UNT 0078 IN HEWA.prj (project) ---

Proj Title=UNT 0078 IN HEWA Base Level Engineering
Current Plan=p01
Default Exp/Contr=0.3,0.1
English Units
Geom File=g01
Flow File=f01
Plan File=p01
BEGIN DESCRIPTION:
UNT 0078 IN HEWA
END DESCRIPTION:

--- UNT 0078 IN HEWA.p01 (plan) ---

Plan Title=Multiple Run
Short Identifier=Multiple
Geom File=g01
Flow File=f01
Subcritical Flow
K Sum by GR= 0
Std Step Tol= 0.01
Critical Tol= 0.01
Num of Std Step Trials= 20
Max Error Tol= 0.3
Flow Tol Ratio= 0.001
Split Flow NTrial= 30
Split Flow Tol= 0.02
Split Flow Ratio= 0.02
Log Output Level= 0
Friction Slope Method= 1
Unsteady Friction Slope Method= 2
Unsteady Bridges Friction Slope Method= 1
Parabolic Critical Depth
Global Vel Dist=  1 , 1 , 1
Global Log Level= 0
CheckData=True
Encroach Param= -1, 0, 0, 0
BEGIN DESCRIPTION:
Multiple Run
END DESCRIPTION:

--- UNT 0078 IN HEWA.f01 (steady flow) ---

Flow Title=Multiple
Number of Profiles=7
Profile Names=10-year,25-year,50-year,1pct_min,100-year,1pct_plu,500-year
River Rch & RM= UNT 0078 IN HEWA,Reach-1,3406
    1172    1703    2159    1994    2697    3648    4209
Boundary for River Rch & Prof#=UNT 0078 IN HEWA,Reach-1,1
Up Type=0
Dn Type=3
Dn Slope=0.005
Boundary for River Rch & Prof#=UNT 0078 IN HEWA,Reach-1,2
Up Type=0
Dn Type=3
Dn Slope=0.005
Boundary for River Rch & Prof#=UNT 0078 IN HEWA,Reach-1,3
Up Type=0
Dn Type=3
Dn Slope=0.005
Boundary for River Rch & Prof#=UNT 0078 IN HEWA,Reach-1,4
Up Type=0
Dn Type=3
Dn Slope=0.005
Boundary for River Rch & Prof#=UNT 0078 IN HEWA,Reach-1,5
Up Type=0
Dn Type=3
Dn Slope=0.005
Boundary for River Rch & Prof#=UNT 0078 IN HEWA,Reach-1,6
Up Type=0
Dn Type=3
Dn Slope=0.005
Boundary for River Rch & Prof#=UNT 0078 IN HEWA,Reach-1,7
Up Type=0
Dn Type=3
Dn Slope=0.005

--- UNT 0078 IN HEWA.g01 (geometry) ---

Geom Title=Existing Conditions

River Reach=UNT 0078 IN HEWA,Reach-1
Reach XY= 30
      2681018.47     10085053.73      2681090.68     10084991.52
      2681125.01     10084932.40      2681146.70     10084868.21
      2681148.55     10084792.47      2681136.41     10084709.59
      2681104.07     10084620.84      2681030.96     10084512.70
      2681001.21     10084442.59      2680991.14     10084259.16
      2681031.88     10084171.22      2681162.41     10084114.75
      2681172.79     10084023.69      2681102.98     10083831.10
      2680989.08     10083713.58      2680970.60     10083413.64
      2680996.01     10083283.79      2680986.67     10083159.48
      2680949.04     10083058.76      2680949.39     10082803.90
      2680975.81     10082747.08      2681019.54     10082716.39
      2681330.97     10082668.39      2681420.94     10082591.29
      2681473.24     10082516.28      2681497.46     10082453.28
      2681497.97     10082368.99      2681440.40     10082208.27
      2681399.80     10081963.33      2681418.47     10081923.73

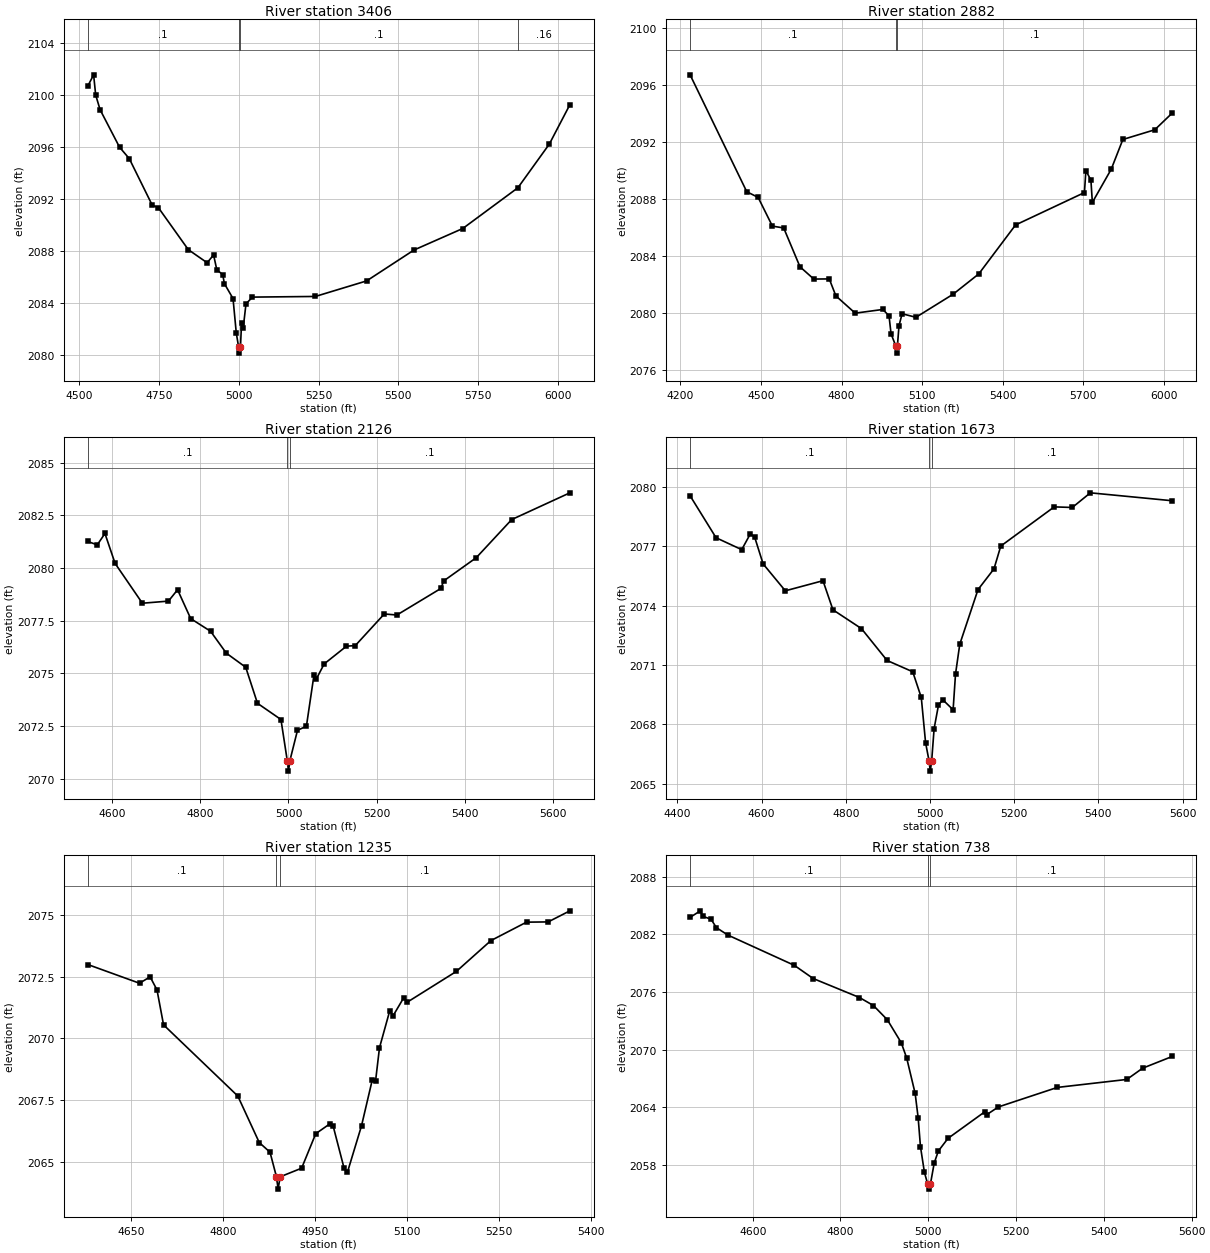
Type RM Length L Ch R = 1,3406,524,524,524
BEGIN DESCRIPTION:
UNT 0078 IN HEWA 4.0
END DESCRIPTION:
XS GIS Cut Line= 3
      2681606.45     10084823.32      2680903.35     10084698.32
      2680168.97     10085005.61
#Sta/Elev= 30
  4527.2 2100.70  4545.5 2101.57  4552.0 2100.01  4565.8 2098.88  4626.7 2095.99
  4657.2 2095.11  4729.1 2091.52  4748.6 2091.32  4842.1 2088.09  4901.1 2087.08
  4921.3 2087.68  4931.4 2086.54  4950.0 2086.16  4955.1 2085.47  4982.2 2084.32
  4992.4 2081.66  4999.5 2080.61  5002.3 2080.11  5005.5 2080.61  5009.0 2082.45
  5014.1 2082.05  5022.8 2083.91  5043.1 2084.43  5240.1 2084.48  5400.8 2085.68
  5549.0 2088.06  5701.9 2089.72  5874.5 2092.86  5973.0 2096.23  6037.4 2099.27
#Mann=4,-1,0
  4527.2     0.1       0  4999.5    0.07       0  5005.5     0.1       0
  5874.5    0.16       0
Bank Sta=4999.5,5005.5
Exp/Cntr=0.3,0.1

Type RM Length L Ch R = 1,2882,756,756,756
BEGIN DESCRIPTION:
UNT 0078 IN HEWA 3.0
END DESCRIPTION:
XS GIS Cut Line= 3
      2681736.66     10084427.48      2680783.56     10084203.53
      2680028.34     10084510.82
#Sta/Elev= 30
  4236.3 2096.71  4447.2 2088.52  4489.6 2088.12  4542.6 2086.11  4584.7 2085.98
  4645.3 2083.26  4696.7 2082.40  4754.3 2082.41  4778.9 2081.22  4850.8 2080.01
  4953.5 2080.27  4976.6 2079.83  4984.3 2078.56  5001.9 2077.71  5004.6 2077.21
  5007.9 2077.71  5013.9 2079.14  5025.4 2079.97  5076.8 2079.72  5215.4 2081.34
  5310.7 2082.76  5447.6 2086.19  5704.0 2088.46  5709.4 2090.00  5728.1 2089.33
  5733.5 2087.77  5803.8 2090.10  5847.0 2092.18  5965.8 2092.86  6030.7 2094.03
#Mann=3,-1,0
  4236.3     0.1       0  5001.9    0.07       0  5007.9     0.1       0
Bank Sta=5001.9,5007.9
Exp/Cntr=0.3,0.1

Type RM Length L Ch R = 1,2126,453,453,453
BEGIN DESCRIPTION:
Mapping XS c44922ca
END DESCRIPTION:
XS GIS Cut Line= 3
      2681439.82     10083713.95      2680747.10     10083625.40
      2680403.38     10083818.09
#Sta/Elev= 30
  4545.2 2081.26  4566.7 2081.10  4584.1 2081.64  4607.1 2080.22  4668.9 2078.33
  4728.0 2078.43  4748.7 2078.97  4778.4 2077.60  4823.4 2077.00  4859.1 2075.96
  4903.1 2075.29  4929.7 2073.58  4982.9 2072.81  4997.2 2070.86  5000.0 2070.36
  5003.2 2070.86  5020.4 2072.30  5040.6 2072.49  5057.6 2074.90  5062.7 2074.72
  5080.9 2075.45  5131.3 2076.29  5151.4 2076.32  5217.1 2077.82  5245.6 2077.77
  5345.2 2079.03  5351.8 2079.39  5425.4 2080.49  5505.7 2082.30  5637.6 2083.57
#Mann=3,-1,0
  4545.2     0.1       0  4997.2    0.07       0  5003.2     0.1       0
Bank Sta=4997.2,5003.2
Exp/Cntr=0.3,0.1

Type RM Length L Ch R = 1,1673,438,438,438
BEGIN DESCRIPTION:
Mapping XS 980e59f6
END DESCRIPTION:
XS GIS Cut Line= 3
      2681549.18     10083307.69      2680814.81     10083177.49
      2680471.06     10083380.61
#Sta/Elev= 30
  4430.3 2079.55  4492.0 2077.43  4552.9 2076.83  4573.2 2077.62  4583.4 2077.48
  4603.7 2076.11  4656.5 2074.75  4745.9 2075.26  4769.6 2073.79  4837.3 2072.84
  4898.2 2071.23  4959.1 2070.66  4979.4 2069.36  4989.6 2067.08  4998.0 2066.14
  5000.7 2065.64  5004.0 2066.14  5009.9 2067.79  5020.1 2068.96  5030.2 2069.25
  5055.0 2068.74  5060.7 2070.54  5070.8 2072.05  5114.1 2074.81  5152.1 2075.86
  5168.2 2077.01  5295.2 2078.99  5338.1 2078.96  5381.0 2079.70  5575.4 2079.30
#Mann=3,-1,0
  4430.3     0.1       0  4998.0    0.07       0  5004.0     0.1       0
Bank Sta=4998,5004
Exp/Cntr=0.3,0.1

Type RM Length L Ch R = 1,1235,497,497,497
BEGIN DESCRIPTION:
Mapping XS ab3167ac
END DESCRIPTION:
XS GIS Cut Line= 3
      2681340.82     10082953.51      2680851.27     10082729.57
      2680654.63     10082879.64
#Sta/Elev= 30
  4579.4 2073.00  4663.7 2072.24  4681.0 2072.50  4692.2 2071.97  4702.9 2070.55
  4823.9 2067.66  4858.9 2065.77  4876.4 2065.38  4886.9 2064.38  4889.6 2063.88
  4892.9 2064.38  4927.9 2064.73  4950.9 2066.13  4973.9 2066.53  4979.4 2066.43
  4997.0 2064.74  5002.5 2064.56  5025.5 2066.45  5043.0 2068.31  5048.5 2068.29
  5054.8 2069.62  5071.5 2071.12  5077.0 2070.92  5094.5 2071.66  5100.0 2071.47
  5180.1 2072.72  5236.3 2073.97  5294.4 2074.72  5329.7 2074.73  5365.1 2075.18
#Mann=3,-1,0
  4579.4     0.1       0  4886.9    0.07       0  4892.9     0.1       0
Bank Sta=4886.9,4892.9
Exp/Cntr=0.3,0.1

Type RM Length L Ch R = 1,738,313,313,313
BEGIN DESCRIPTION:
UNT 0078 IN HEWA 2.0
END DESCRIPTION:
XS GIS Cut Line= 3
      2681913.74     10082786.85      2681226.27     10082552.49
      2680862.55     10082630.43
#Sta/Elev= 30
  4457.4 2083.76  4480.7 2084.44  4486.0 2083.88  4505.2 2083.56  4517.3 2082.69
  4543.4 2081.92  4694.8 2078.77  4737.7 2077.40  4843.3 2075.42  4875.0 2074.59
  4906.7 2073.11  4938.4 2070.72  4950.8 2069.13  4970.1 2065.44  4976.9 2062.93
  4982.2 2059.91  4991.2 2057.24  4998.8 2055.99  5001.5 2055.49  5004.8 2055.99
  5013.5 2058.20  5022.9 2059.45  5044.9 2060.77  5128.3 2063.52  5133.6 2063.25
  5159.7 2064.04  5294.0 2066.07  5452.3 2066.90  5488.3 2068.07  5555.7 2069.29
#Mann=3,-1,0
  4457.4     0.1       0  4998.8    0.07       0  5004.8     0.1       0
Bank Sta=4998.8,5004.8
Exp/Cntr=0.3,0.1

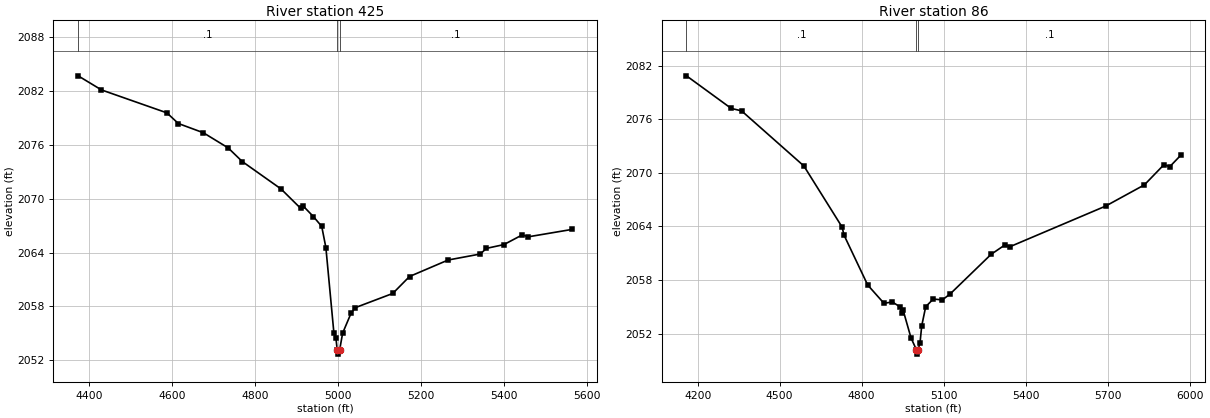
Type RM Length L Ch R = 1,425,339,339,339
BEGIN DESCRIPTION:
Mapping XS 8c4d6b8e
END DESCRIPTION:
XS GIS Cut Line= 4
      2682058.16     10082541.32      2681625.85     10082312.15
      2681297.73     10082353.82      2680993.22     10082567.23
#Sta/Elev= 30
  4372.6 2083.72  4428.8 2082.15  4586.6 2079.59  4614.3 2078.40  4674.6 2077.37
  4734.4 2075.68  4768.4 2074.16  4861.9 2071.10  4909.4 2068.93  4914.4 2069.24
  4939.9 2068.02  4960.1 2066.92  4970.1 2064.56  4989.4 2055.05  4994.4 2054.43
  4997.4 2053.17  5000.1 2052.67  5003.4 2053.17  5010.5 2055.01  5030.6 2057.21
  5040.7 2057.85  5131.4 2059.44  5171.8 2061.33  5264.9 2063.17  5342.5 2063.84
  5357.3 2064.47  5399.4 2064.89  5443.6 2065.97  5458.4 2065.76  5564.5 2066.59
#Mann=3,-1,0
  4372.6     0.1       0  4997.4    0.07       0  5003.4     0.1       0
Bank Sta=4997.4,5003.4
Exp/Cntr=0.3,0.1

Type RM Length L Ch R = 1,86,0,0,0
BEGIN DESCRIPTION:
UNT 0078 IN HEWA 1.0
END DESCRIPTION:
XS GIS Cut Line= 4
      2682157.10     10082327.77      2681516.48     10081973.61
      2681349.81     10082020.48      2680777.84     10082719.85
#Sta/Elev= 30
  4159.0 2080.86  4322.7 2077.21  4360.5 2076.94  4588.5 2070.77  4728.8 2063.91
  4735.1 2063.05  4822.1 2057.44  4881.7 2055.39  4912.4 2055.54  4940.9 2054.98
  4946.5 2054.31  4951.7 2054.63  4980.5 2051.53  5000.2 2050.20  5003.0 2049.70
  5006.2 2050.20  5013.6 2050.96  5019.8 2052.86  5034.4 2055.01  5062.2 2055.87
  5095.3 2055.77  5124.0 2056.44  5274.0 2060.88  5323.6 2061.91  5344.4 2061.75
  5692.5 2066.27  5834.7 2068.65  5906.5 2070.92  5927.3 2070.68  5967.6 2071.96
#Mann=3,-1,0
  4159.0     0.1       0  5000.2    0.07       0  5006.2     0.1       0
Bank Sta=5000.2,5006.2
Exp/Cntr=0.3,0.1

Chan Stop Cuts=-1