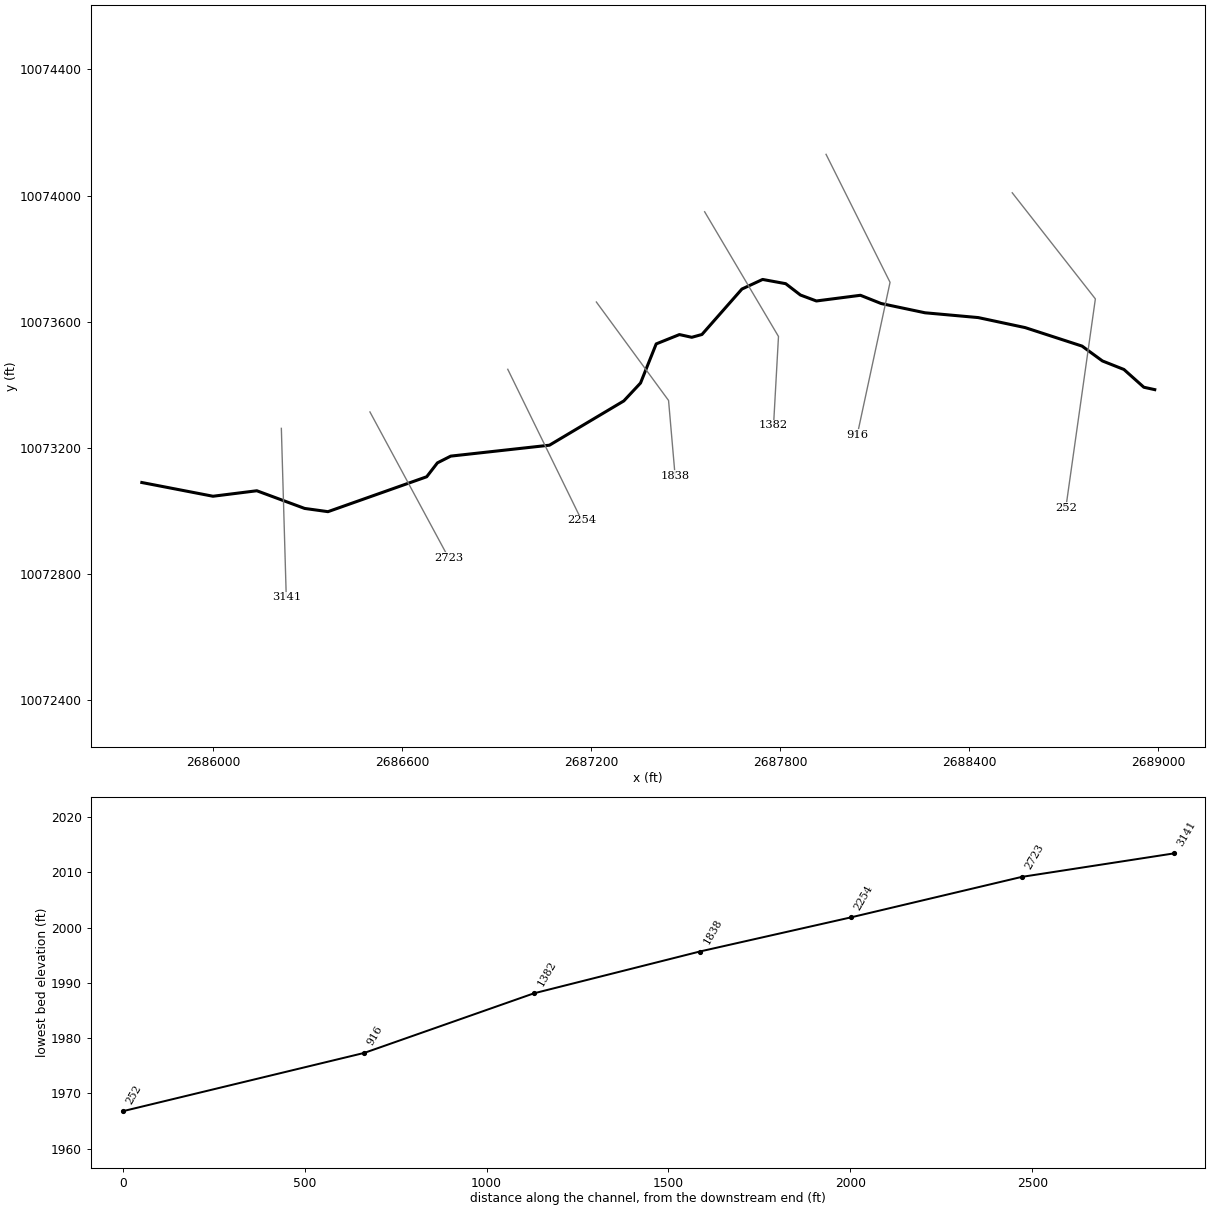
--- UNT 0079 IN HEWA.prj (project) ---

Proj Title=UNT 0079 IN HEWA Base Level Engineering
Current Plan=p01
Default Exp/Contr=0.3,0.1
English Units
Geom File=g01
Flow File=f01
Plan File=p01
BEGIN DESCRIPTION:
UNT 0079 IN HEWA
END DESCRIPTION:

--- UNT 0079 IN HEWA.p01 (plan) ---

Plan Title=Multiple Run
Short Identifier=Multiple
Geom File=g01
Flow File=f01
Subcritical Flow
K Sum by GR= 0
Std Step Tol= 0.01
Critical Tol= 0.01
Num of Std Step Trials= 20
Max Error Tol= 0.3
Flow Tol Ratio= 0.001
Split Flow NTrial= 30
Split Flow Tol= 0.02
Split Flow Ratio= 0.02
Log Output Level= 0
Friction Slope Method= 1
Unsteady Friction Slope Method= 2
Unsteady Bridges Friction Slope Method= 1
Parabolic Critical Depth
Global Vel Dist=  1 , 1 , 1
Global Log Level= 0
CheckData=True
Encroach Param= -1, 0, 0, 0
BEGIN DESCRIPTION:
Multiple Run
END DESCRIPTION:

--- UNT 0079 IN HEWA.f01 (steady flow) ---

Flow Title=Multiple
Number of Profiles=7
Profile Names=10-year,25-year,50-year,1pct_min,100-year,1pct_plu,500-year
River Rch & RM= UNT 0079 IN HEWA,Reach-1,3141
     709    1002    1248    1135    1535    2076    2320
Boundary for River Rch & Prof#=UNT 0079 IN HEWA,Reach-1,1
Up Type=0
Dn Type=3
Dn Slope=0.005
Boundary for River Rch & Prof#=UNT 0079 IN HEWA,Reach-1,2
Up Type=0
Dn Type=3
Dn Slope=0.005
Boundary for River Rch & Prof#=UNT 0079 IN HEWA,Reach-1,3
Up Type=0
Dn Type=3
Dn Slope=0.005
Boundary for River Rch & Prof#=UNT 0079 IN HEWA,Reach-1,4
Up Type=0
Dn Type=3
Dn Slope=0.005
Boundary for River Rch & Prof#=UNT 0079 IN HEWA,Reach-1,5
Up Type=0
Dn Type=3
Dn Slope=0.005
Boundary for River Rch & Prof#=UNT 0079 IN HEWA,Reach-1,6
Up Type=0
Dn Type=3
Dn Slope=0.005
Boundary for River Rch & Prof#=UNT 0079 IN HEWA,Reach-1,7
Up Type=0
Dn Type=3
Dn Slope=0.005

--- UNT 0079 IN HEWA.g01 (geometry) ---

Geom Title=Existing Conditions

River Reach=UNT 0079 IN HEWA,Reach-1
Reach XY= 30
      2685772.91     10073088.94      2685998.85     10073045.32
      2686137.95     10073062.74      2686289.74     10073006.64
      2686363.89     10072996.35      2686677.27     10073107.19
      2686711.29     10073151.27      2686753.62     10073172.70
      2687066.96     10073207.38      2687302.99     10073347.89
      2687356.05     10073404.71      2687405.81     10073528.91
      2687479.54     10073558.53      2687518.68     10073549.89
      2687551.02     10073558.81      2687677.94     10073703.08
      2687743.64     10073733.54      2687816.89     10073720.08
      2687863.64     10073684.08      2687914.24     10073665.20
      2688054.11     10073683.25      2688119.85     10073657.10
      2688259.03     10073627.72      2688427.95     10073612.49
      2688577.18     10073580.62      2688757.72     10073521.92
      2688822.27     10073474.81      2688890.53     10073447.77
      2688953.82     10073391.32      2688988.47     10073383.73

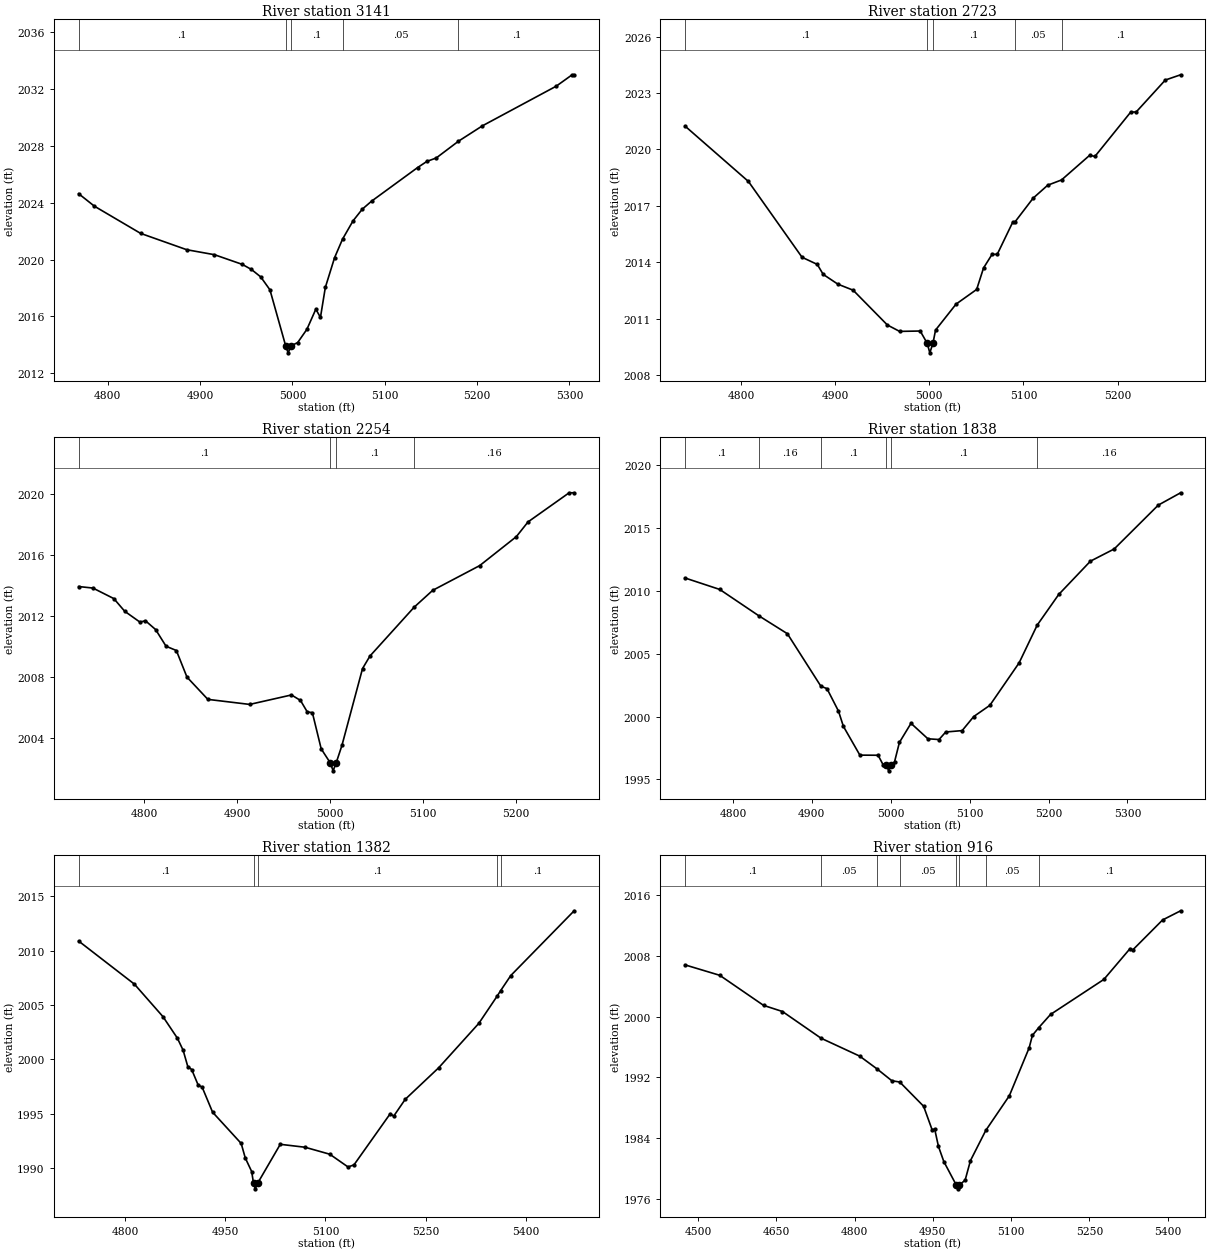
Type RM Length L Ch R = 1,3141,418,418,418
BEGIN DESCRIPTION:
UNT 0079 IN HEWA 7.0
END DESCRIPTION:
XS GIS Cut Line= 2
      2686215.85     10073260.82      2686231.48     10072724.35
#Sta/Elev= 30
  4768.4 2024.63  4785.5 2023.75  4835.5 2021.84  4885.5 2020.69  4915.5 2020.34
  4945.6 2019.66  4955.6 2019.30  4965.6 2018.78  4975.6 2017.87  4992.6 2013.94
  4995.3 2013.44  4998.6 2013.94  5005.6 2014.16  5015.6 2015.09  5025.3 2016.51
  5030.3 2015.93  5035.6 2018.04  5045.6 2020.13  5054.2 2021.43  5065.6 2022.72
  5075.6 2023.54  5085.6 2024.10  5135.6 2026.47  5145.6 2026.90  5155.7 2027.14
  5179.8 2028.32  5205.7 2029.40  5285.7 2032.19  5302.9 2032.99  5305.1 2032.99
#Mann=5,-1,0
  4768.4     0.1       0  4992.6    0.07       0  4998.6     0.1       0
  5054.2    0.05       0  5179.8     0.1       0
Bank Sta=4992.6,4998.6
Exp/Cntr=0.3,0.1

Type RM Length L Ch R = 1,2723,469,469,469
BEGIN DESCRIPTION:
UNT 0079 IN HEWA 6.0
END DESCRIPTION:
XS GIS Cut Line= 2
      2686497.09     10073312.92      2686747.11     10072849.35
#Sta/Elev= 30
  4740.4 2021.24  4807.7 2018.30  4864.7 2014.27  4880.9 2013.89  4887.2 2013.36
  4902.8 2012.84  4919.0 2012.52  4955.4 2010.67  4968.4 2010.33  4990.3 2010.35
  4997.8 2009.69  5000.5 2009.19  5003.8 2009.69  5006.6 2010.40  5028.4 2011.78
  5050.3 2012.56  5057.6 2013.70  5066.6 2014.42  5072.2 2014.43  5088.5 2016.12
  5090.9 2016.14  5110.3 2017.41  5125.8 2018.10  5140.5 2018.38  5170.4 2019.69
  5176.0 2019.63  5214.1 2021.99  5219.8 2021.99  5250.8 2023.69  5267.1 2023.97
#Mann=5,-1,0
  4740.4     0.1       0  4997.8    0.07       0  5003.8     0.1       0
  5090.9    0.05       0  5140.5     0.1       0
Bank Sta=4997.8,5003.8
Exp/Cntr=0.3,0.1

Type RM Length L Ch R = 1,2254,416,416,416
BEGIN DESCRIPTION:
UNT 0079 IN HEWA 5.0
END DESCRIPTION:
XS GIS Cut Line= 2
      2686934.62     10073448.28      2687168.99     10072969.13
#Sta/Elev= 30
  4729.4 2013.94  4744.8 2013.84  4767.3 2013.15  4779.0 2012.32  4795.4 2011.61
  4801.3 2011.70  4812.3 2011.12  4823.5 2010.03  4834.6 2009.75  4846.0 2008.01
  4868.5 2006.55  4913.5 2006.22  4958.5 2006.84  4968.2 2006.48  4975.5 2005.73
  4981.0 2005.68  4990.5 2003.31  5000.5 2002.37  5003.3 2001.87  5006.5 2002.37
  5012.8 2003.53  5035.0 2008.57  5043.0 2009.39  5090.6 2012.59  5110.5 2013.69
  5161.1 2015.31  5200.6 2017.21  5213.1 2018.17  5257.4 2020.08  5262.8 2020.08
#Mann=4,-1,0
  4729.4     0.1       0  5000.5    0.07       0  5006.5     0.1       0
  5090.6    0.16       0
Bank Sta=5000.5,5006.5
Exp/Cntr=0.3,0.1

Type RM Length L Ch R = 1,1838,456,456,456
BEGIN DESCRIPTION:
UNT 0079 IN HEWA 4.0
END DESCRIPTION:
XS GIS Cut Line= 3
      2687215.83     10073661.89      2687445.02     10073349.36
      2687465.85     10073109.82
#Sta/Elev= 30
  4739.4 2011.02  4783.3 2010.11  4832.7 2008.02  4869.0 2006.59  4911.5 2002.41
  4919.2 2002.22  4933.8 2000.43  4940.0 1999.22  4960.9 1996.93  4984.0 1996.92
  4990.2 1996.18  4994.5 1996.18  4997.3 1995.68  5000.5 1996.18  5004.8 1996.39
  5011.0 1997.94  5025.7 1999.46  5047.1 1998.23  5061.2 1998.17  5069.7 1998.77
  5090.5 1998.88  5105.2 2000.00  5125.6 2000.89  5162.7 2004.27  5185.6 2007.27
  5212.9 2009.71  5253.1 2012.36  5283.2 2013.33  5339.1 2016.82  5367.4 2017.80
#Mann=6,-1,0
  4739.4     0.1       0  4832.7    0.16       0  4911.5     0.1       0
  4994.5    0.07       0  5000.5     0.1       0  5185.6    0.16       0
Bank Sta=4994.5,5000.5
Exp/Cntr=0.3,0.1

Type RM Length L Ch R = 1,1382,466,466,466
BEGIN DESCRIPTION:
UNT 0079 IN HEWA 3.0
END DESCRIPTION:
XS GIS Cut Line= 3
      2687559.61     10073948.31      2687793.98     10073552.49
      2687778.35     10073271.22
#Sta/Elev= 30
  4730.6 2010.87  4814.1 2006.91  4856.9 2003.92  4878.4 2001.95  4887.0 2000.84
  4894.0 1999.34  4899.8 1999.07  4909.6 1997.63  4915.4 1997.46  4931.1 1995.15
  4973.9 1992.28  4980.0 1990.95  4989.6 1989.70  4992.4 1988.61  4995.1 1988.11
  4998.4 1988.61  5032.4 1992.20  5069.5 1991.93  5106.5 1991.29  5133.8 1990.12
  5142.7 1990.31  5197.1 1995.02  5202.1 1994.78  5219.4 1996.33  5269.5 1999.23
  5329.6 2003.31  5357.1 2005.82  5362.2 2006.31  5377.4 2007.70  5472.3 2013.65
#Mann=5,-1,0
  4730.6     0.1       0  4992.4    0.07       0  4998.4     0.1       0
  5357.1    0.16       0  5362.2     0.1       0
Bank Sta=4992.4,4998.4
Exp/Cntr=0.3,0.1

Type RM Length L Ch R = 1,916,664,664,664
BEGIN DESCRIPTION:
UNT 0079 IN HEWA 2.0
END DESCRIPTION:
XS GIS Cut Line= 3
      2687945.01     10074130.62      2688148.14     10073724.36
      2688043.97     10073239.95
#Sta/Elev= 30
  4475.2 2006.83  4541.6 2005.46  4625.5 2001.50  4661.8 2000.69  4735.8 1997.17
  4809.9 1994.81  4843.4 1993.11  4871.4 1991.57  4886.6 1991.40  4932.3 1988.21
  4948.5 1985.13  4953.6 1985.18  4960.7 1982.93  4971.0 1980.93  4994.9 1977.83
  4997.6 1977.33  5000.9 1977.83  5011.9 1978.48  5022.1 1981.05  5051.4 1985.02
  5096.6 1989.59  5134.6 1995.91  5140.8 1997.55  5152.9 1998.56  5175.5 2000.30
  5277.8 2004.92  5328.0 2008.98  5333.1 2008.80  5390.3 2012.75  5424.9 2013.96
#Mann=8,-1,0
  4475.2     0.1       0  4735.8    0.05       0  4843.4     0.1       0
  4886.6    0.05       0  4994.9    0.07       0  5000.9    0.05       0
  5051.4    0.05       0  5152.9     0.1       0
Bank Sta=4994.9,5000.9
Exp/Cntr=0.3,0.1

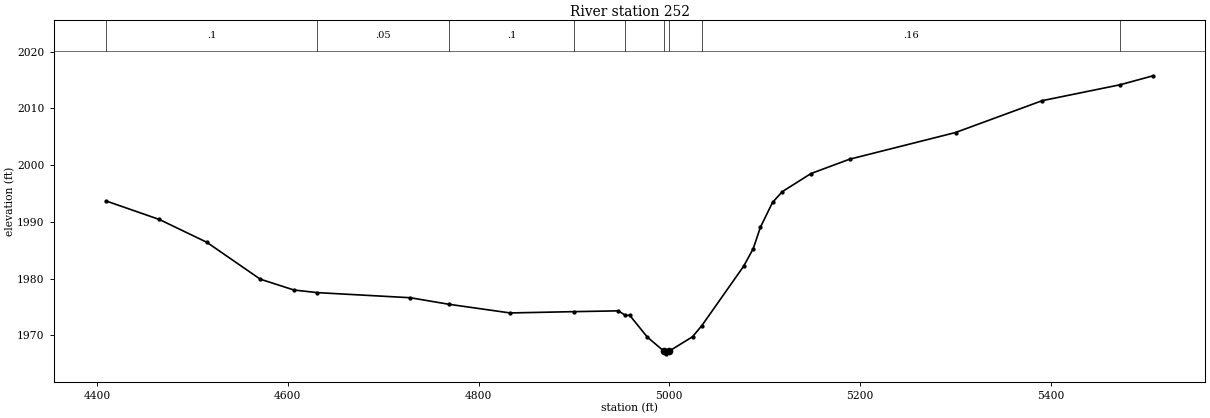
Type RM Length L Ch R = 1,252,0,0,0
BEGIN DESCRIPTION:
UNT 0079 IN HEWA 1.0
END DESCRIPTION:
XS GIS Cut Line= 3
      2688536.03     10074008.61      2688799.91     10073671.81
      2688706.17     10073008.67
#Sta/Elev= 30
  4409.6 1993.68  4465.3 1990.43  4515.0 1986.42  4571.1 1979.92  4606.4 1978.01
  4630.8 1977.55  4728.4 1976.65  4769.1 1975.49  4833.1 1973.97  4900.2 1974.20
  4946.6 1974.34  4954.0 1973.54  4958.4 1973.57  4976.9 1969.73  4994.1 1967.27
  4996.9 1966.77  5000.1 1967.27  5024.4 1969.79  5034.1 1971.74  5077.9 1982.19
  5088.0 1985.29  5095.5 1989.06  5108.2 1993.42  5118.3 1995.31  5148.6 1998.52
  5189.0 2001.04  5300.1 2005.74  5391.0 2011.35  5472.7 2014.15  5507.2 2015.73
#Mann=9,-1,0
  4409.6     0.1       0  4630.8    0.05       0  4769.1     0.1       0
  4900.2    0.05       0  4954.0     0.1       0  4994.1    0.07       0
  5000.1     0.1       0  5034.1    0.16       0  5472.7     0.1       0
Bank Sta=4994.1,5000.1
Exp/Cntr=0.3,0.1

Chan Stop Cuts=-1