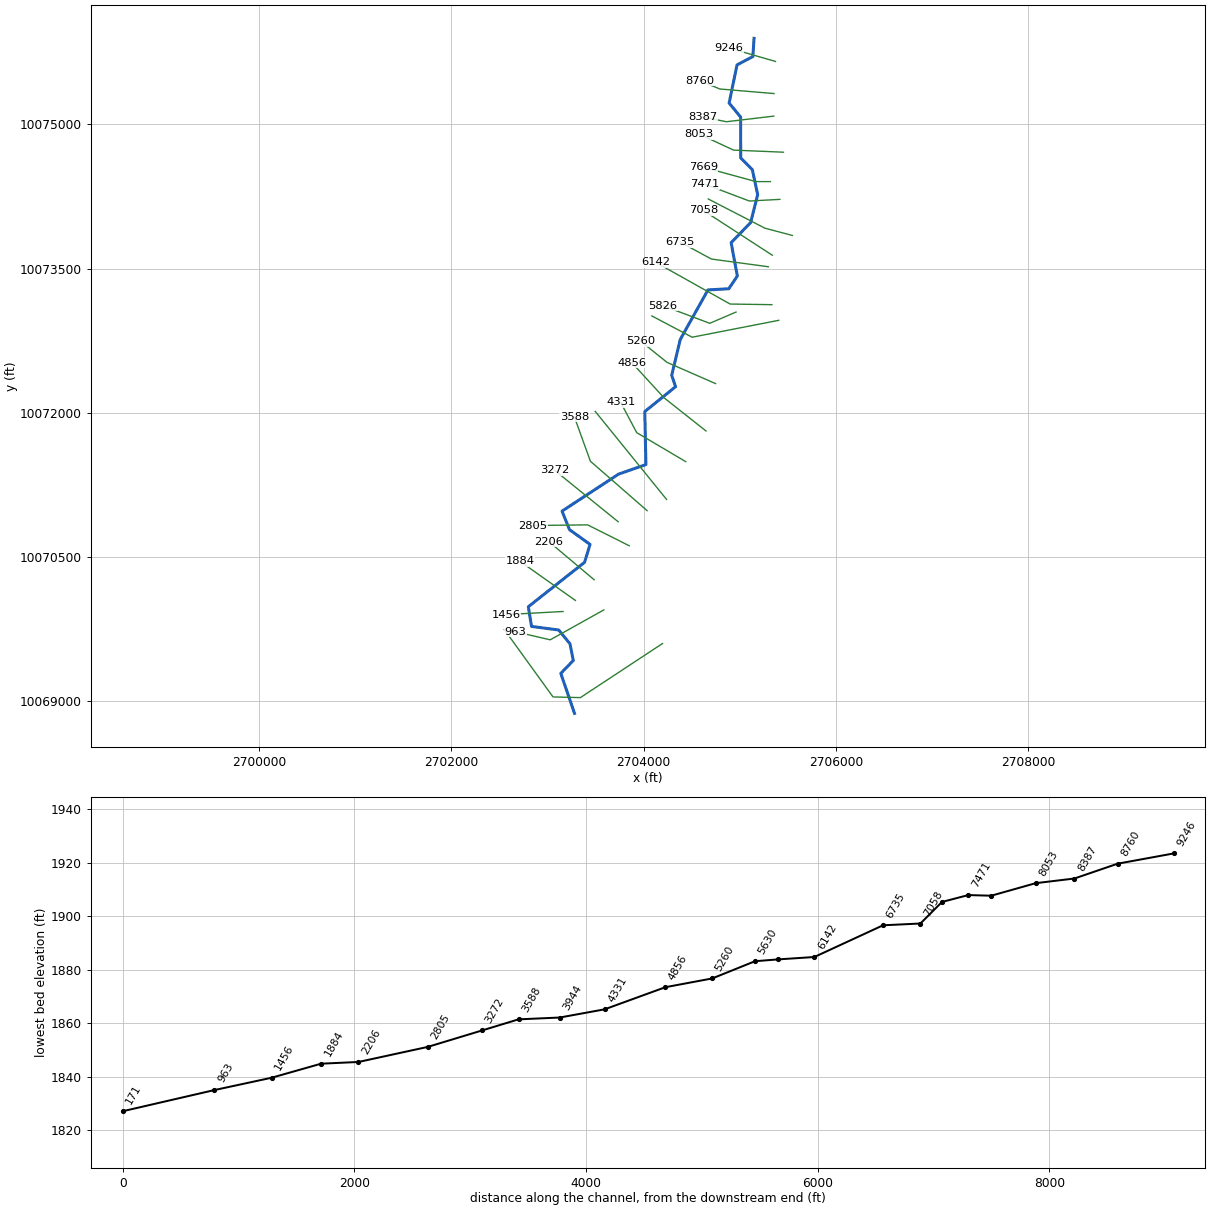
--- UNT 0080 IN HEWA.prj (project) ---

Proj Title=UNT 0080 IN HEWA Base Level Engineering
Current Plan=p01
Default Exp/Contr=0.3,0.1
English Units
Geom File=g01
Flow File=f01
Plan File=p01
BEGIN DESCRIPTION:
UNT 0080 IN HEWA
END DESCRIPTION:

--- UNT 0080 IN HEWA.p01 (plan) ---

Plan Title=Multiple Run
Short Identifier=Multiple
Geom File=g01
Flow File=f01
Subcritical Flow
K Sum by GR= 0
Std Step Tol= 0.01
Critical Tol= 0.01
Num of Std Step Trials= 20
Max Error Tol= 0.3
Flow Tol Ratio= 0.001
Split Flow NTrial= 30
Split Flow Tol= 0.02
Split Flow Ratio= 0.02
Log Output Level= 0
Friction Slope Method= 1
Unsteady Friction Slope Method= 2
Unsteady Bridges Friction Slope Method= 1
Parabolic Critical Depth
Global Vel Dist=  1 , 1 , 1
Global Log Level= 0
CheckData=True
Encroach Param= -1, 0, 0, 0
BEGIN DESCRIPTION:
Multiple Run
END DESCRIPTION:

--- UNT 0080 IN HEWA.f01 (steady flow) ---

Flow Title=Multiple
Number of Profiles=7
Profile Names=10-year,25-year,50-year,1pct_min,100-year,1pct_plu,500-year
River Rch & RM= UNT 0080 IN HEWA,Reach-1,9246
    1409    2084    2677    2506    3389    4583    5430
River Rch & RM= UNT 0080 IN HEWA,Reach-1,7058
    2046    3079    4000    3782    5115    6918    8367
Boundary for River Rch & Prof#=UNT 0080 IN HEWA,Reach-1,1
Up Type=0
Dn Type=3
Dn Slope=0.005
Boundary for River Rch & Prof#=UNT 0080 IN HEWA,Reach-1,2
Up Type=0
Dn Type=3
Dn Slope=0.005
Boundary for River Rch & Prof#=UNT 0080 IN HEWA,Reach-1,3
Up Type=0
Dn Type=3
Dn Slope=0.005
Boundary for River Rch & Prof#=UNT 0080 IN HEWA,Reach-1,4
Up Type=0
Dn Type=3
Dn Slope=0.005
Boundary for River Rch & Prof#=UNT 0080 IN HEWA,Reach-1,5
Up Type=0
Dn Type=3
Dn Slope=0.005
Boundary for River Rch & Prof#=UNT 0080 IN HEWA,Reach-1,6
Up Type=0
Dn Type=3
Dn Slope=0.005
Boundary for River Rch & Prof#=UNT 0080 IN HEWA,Reach-1,7
Up Type=0
Dn Type=3
Dn Slope=0.005

--- UNT 0080 IN HEWA.g01 (geometry) ---

Geom Title=Existing Conditions

River Reach=UNT 0080 IN HEWA,Reach-1
Reach XY= 30
      2705148.47     10075893.73      2705136.19     10075704.54
      2704971.37     10075617.50      2704889.14     10075220.67
      2705009.12     10075074.71      2705009.35     10074650.33
      2705130.77     10074527.64      2705186.13     10074267.95
      2705112.84     10073977.69      2704910.22     10073768.17
      2704974.48     10073421.16      2704885.38     10073289.39
      2704669.22     10073277.28      2704381.29     10072762.56
      2704292.01     10072388.80      2704332.41     10072270.77
      2704012.06     10072012.21      2704023.73     10071460.87
      2703739.51     10071361.61      2703151.67     10070976.87
      2703229.48     10070783.39      2703442.65     10070630.79
      2703385.97     10070444.62      2702801.10     10069982.65
      2702834.03     10069777.69      2703116.94     10069740.26
      2703234.15     10069596.69      2703268.67     10069423.39
      2703138.61     10069289.07      2703281.40     10068873.32

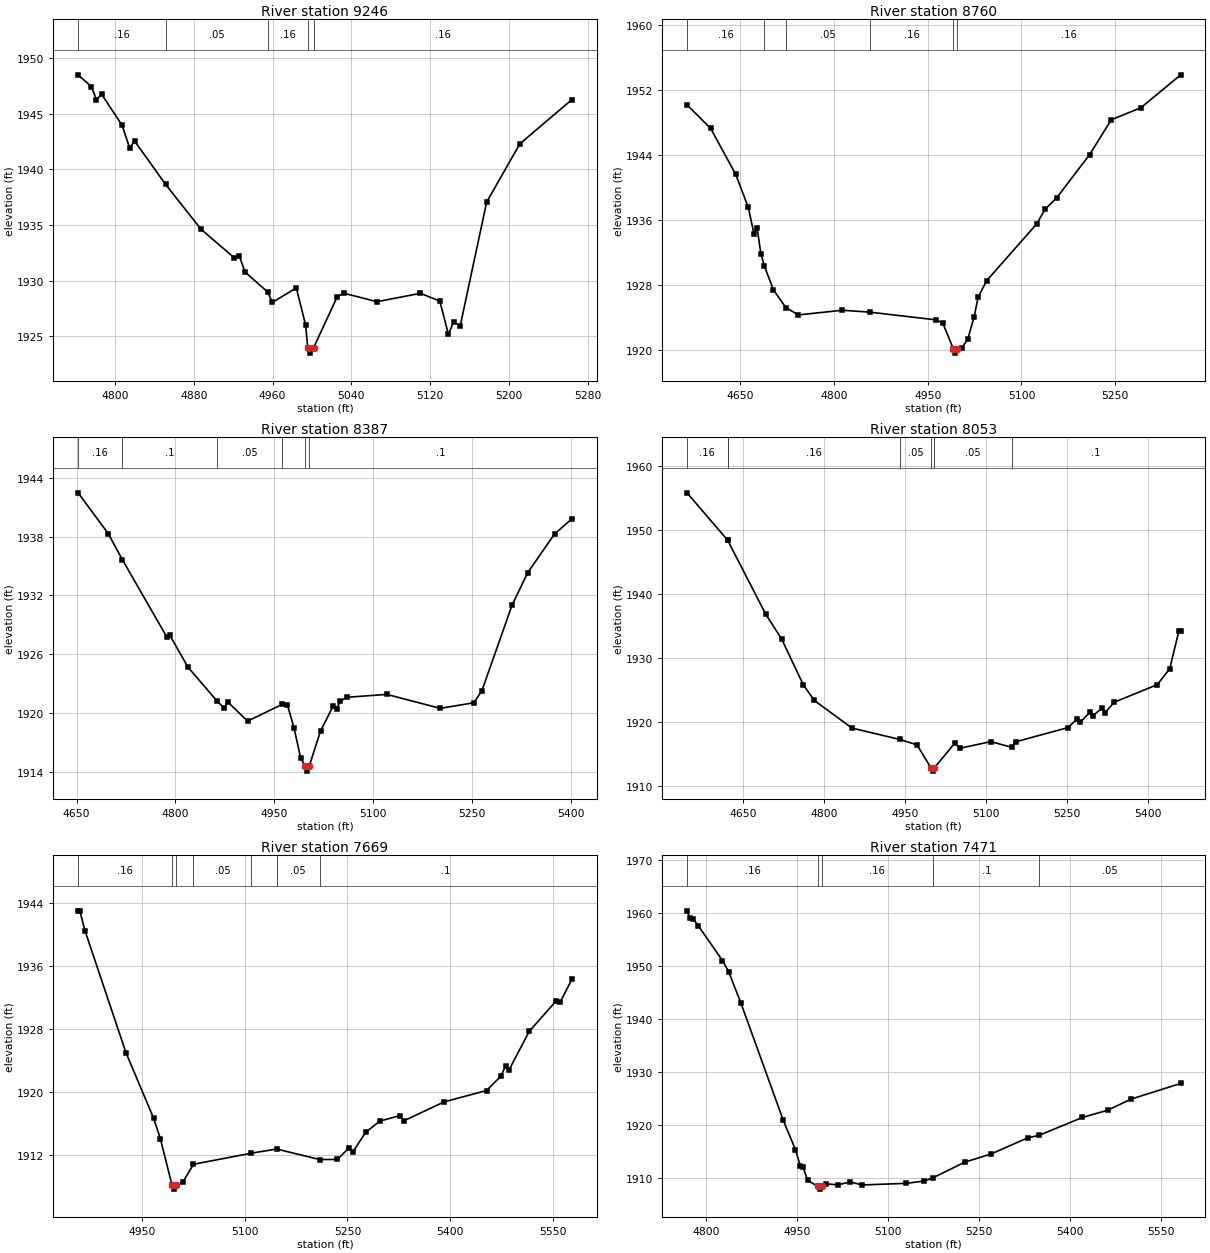
Type RM Length L Ch R = 1,9246,486,486,486
BEGIN DESCRIPTION:
UNT 0080 IN HEWA 18.0
END DESCRIPTION:
XS GIS Cut Line= 2
      2705371.35     10075653.56      2704889.57     10075792.45
#Sta/Elev= 30
  4762.5 1948.48  4775.9 1947.43  4781.1 1946.26  4786.4 1946.73  4807.1 1943.96
  4814.8 1941.93  4820.0 1942.52  4851.4 1938.63  4887.3 1934.61  4921.0 1932.05
  4926.2 1932.21  4932.0 1930.77  4954.9 1928.98  4959.9 1928.04  4984.1 1929.34
  4993.5 1926.02  4995.7 1923.98  4998.5 1923.48  5001.7 1923.98  5025.7 1928.55
  5032.4 1928.86  5066.0 1928.10  5110.1 1928.85  5129.8 1928.16  5138.6 1925.16
  5143.8 1926.27  5150.6 1925.94  5177.4 1937.05  5211.1 1942.28  5263.9 1946.25
#Mann=5,-1,0
  4762.5    0.16       0  4851.4    0.05       0  4954.9    0.16       0
  4995.7    0.07       0  5001.7    0.16       0
Bank Sta=4995.7,5001.7
Exp/Cntr=0.3,0.1

Type RM Length L Ch R = 1,8760,373,373,373
BEGIN DESCRIPTION:
UNT 0080 IN HEWA 17.0
END DESCRIPTION:
XS GIS Cut Line= 3
      2705356.21     10075319.35      2704791.93     10075367.09
      2704585.75     10075453.91
#Sta/Elev= 30
  4564.8 1950.22  4602.7 1947.30  4642.8 1941.64  4662.9 1937.58  4672.0 1934.30
  4677.0 1935.04  4683.0 1931.87  4688.7 1930.34  4703.0 1927.43  4723.0 1925.23
  4743.2 1924.34  4813.4 1924.91  4856.9 1924.68  4964.0 1923.72  4974.0 1923.34
  4991.1 1920.13  4993.8 1919.63  4997.1 1920.13  5004.1 1920.23  5014.1 1921.37
  5024.2 1924.09  5030.6 1926.52  5044.2 1928.55  5124.5 1935.56  5137.8 1937.36
  5156.1 1938.74  5209.0 1944.08  5243.6 1948.37  5291.1 1949.86  5354.8 1953.91
#Mann=6,-1,0
  4564.8    0.16       0  4688.7     0.1       0  4723.0    0.05       0
  4856.9    0.16       0  4991.1    0.07       0  4997.1    0.16       0
Bank Sta=4991.1,4997.1
Exp/Cntr=0.3,0.1

Type RM Length L Ch R = 1,8387,334,334,334
BEGIN DESCRIPTION:
Mapping XS fa493203
END DESCRIPTION:
XS GIS Cut Line= 3
      2705353.96     10075084.97      2704861.38     10075026.38
      2704612.65     10075076.13
#Sta/Elev= 30
  4652.3 1942.46  4698.1 1938.30  4719.7 1935.62  4786.7 1927.80  4791.8 1927.92
  4819.0 1924.70  4863.7 1921.20  4874.4 1920.50  4879.4 1921.15  4909.6 1919.19
  4962.6 1920.91  4970.0 1920.86  4980.1 1918.53  4990.2 1915.44  4997.2 1914.59
  5000.0 1914.09  5003.2 1914.59  5020.4 1918.17  5039.6 1920.73  5044.7 1920.43
  5050.6 1921.24  5060.6 1921.62  5121.1 1921.91  5202.3 1920.49  5253.3 1921.06
  5265.5 1922.30  5311.3 1931.02  5334.9 1934.31  5375.7 1938.26  5402.0 1939.80
#Mann=6,-1,0
  4652.3    0.16       0  4719.7     0.1       0  4863.7    0.05       0
  4962.6     0.1       0  4997.2    0.07       0  5003.2     0.1       0
Bank Sta=4997.2,5003.2
Exp/Cntr=0.3,0.1

Type RM Length L Ch R = 1,8053,384,384,384
BEGIN DESCRIPTION:
UNT 0080 IN HEWA 16.0
END DESCRIPTION:
XS GIS Cut Line= 3
      2705453.85     10074709.54      2704935.16     10074731.24
      2704577.07     10074898.35
#Sta/Elev= 30
  4546.8 1955.87  4621.9 1948.48  4622.0 1948.47  4692.3 1936.93  4722.3 1932.97
  4762.0 1925.88  4782.4 1923.41  4852.4 1919.08  4941.1 1917.30  4972.6 1916.46
  4998.7 1912.85  5001.5 1912.35  5004.7 1912.85  5042.6 1916.72  5052.6 1915.93
  5109.6 1916.97  5148.0 1916.07  5155.3 1916.93  5252.3 1919.16  5269.6 1920.55
  5275.2 1919.99  5292.5 1921.53  5298.0 1921.00  5315.4 1922.19  5320.9 1921.50
  5338.2 1923.13  5417.8 1925.88  5440.7 1928.36  5457.6 1934.24  5461.1 1934.24
#Mann=7,-1,0
  4546.8    0.16       0  4621.9     0.1       0  4622.0    0.16       0
  4941.1    0.05       0  4998.7    0.04       0  5004.7    0.05       0
  5148.0     0.1       0
Bank Sta=4998.7,5004.7
Exp/Cntr=0.3,0.1

Type RM Length L Ch R = 1,7669,198,198,198
BEGIN DESCRIPTION:
UNT 0080 IN HEWA 15.0
END DESCRIPTION:
XS GIS Cut Line= 3
      2705318.51     10074403.73      2705168.47     10074403.73
      2704618.49     10074553.72
#Sta/Elev= 30
  4857.1 1943.05  4859.6 1943.05  4867.1 1940.53  4927.1 1924.97  4967.1 1916.71
  4977.1 1914.07  4994.1 1908.16  4996.9 1907.66  5000.1 1908.16  5009.7 1908.51
  5025.4 1910.82  5109.8 1912.23  5146.5 1912.76  5209.7 1911.42  5235.2 1911.44
  5252.5 1912.92  5257.6 1912.36  5276.6 1914.90  5297.4 1916.32  5326.7 1917.01
  5331.9 1916.33  5390.7 1918.75  5452.8 1920.20  5473.6 1922.01  5480.5 1923.31
  5485.7 1922.83  5515.0 1927.71  5554.8 1931.64  5560.0 1931.40  5577.2 1934.32
#Mann=7,-1,0
  4857.1    0.16       0  4994.1    0.07       0  5000.1    0.16       0
  5025.4    0.05       0  5109.8     0.1       0  5146.5    0.05       0
  5209.7     0.1       0
Bank Sta=4994.1,5000.1
Exp/Cntr=0.3,0.1

Type RM Length L Ch R = 1,7471,227,227,227
BEGIN DESCRIPTION:
UNT 0080 IN HEWA 14.0
END DESCRIPTION:
XS GIS Cut Line= 3
      2705416.90     10074219.09      2705100.09     10074201.73
      2704635.73     10074377.49
#Sta/Elev= 30
  4768.7 1960.45  4773.7 1959.03  4778.7 1958.96  4787.2 1957.65  4827.2 1951.06
  4837.2 1948.98  4857.3 1943.12  4927.4 1920.89  4947.4 1915.37  4955.2 1912.36
  4960.2 1912.05  4967.4 1909.55  4984.5 1908.40  4987.2 1907.90  4990.5 1908.40
  4997.5 1908.91  5017.5 1908.71  5037.5 1909.25  5057.6 1908.69  5129.6 1908.99
  5159.7 1909.43  5174.3 1910.06  5226.7 1913.00  5269.5 1914.52  5330.0 1917.57
  5349.7 1918.09  5420.5 1921.44  5462.0 1922.80  5500.3 1924.88  5582.5 1927.86
#Mann=5,-1,0
  4768.7    0.16       0  4984.5    0.04       0  4990.5    0.16       0
  5174.3     0.1       0  5349.7    0.05       0
Bank Sta=4984.5,4990.5
Exp/Cntr=0.3,0.1

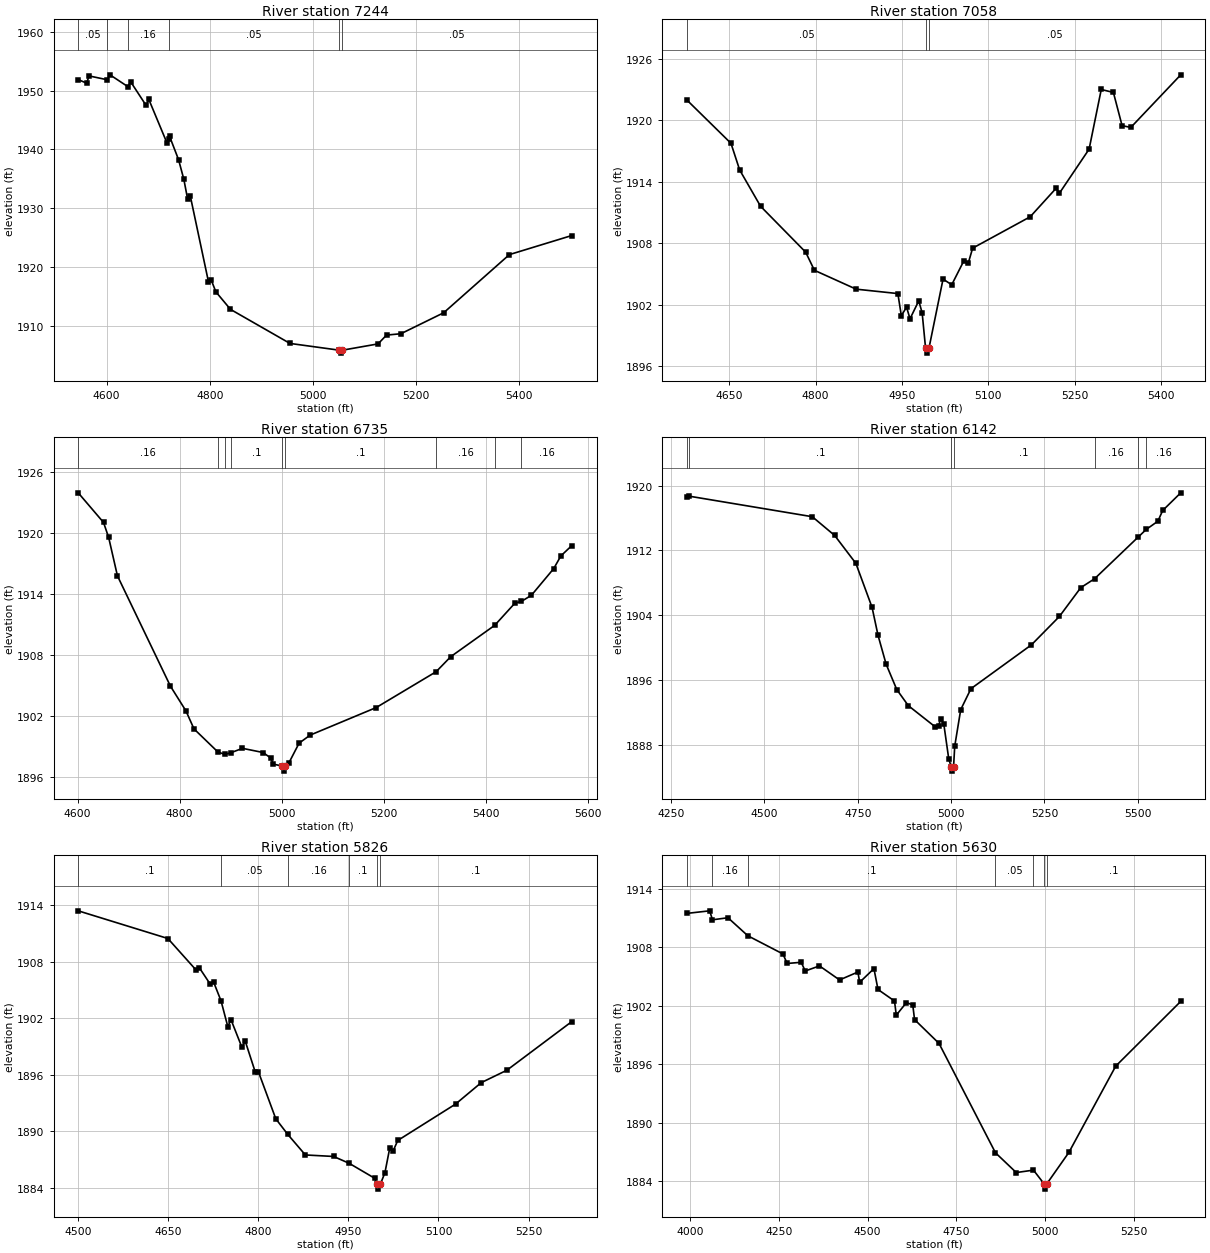
Type RM Length L Ch R = 1,7244,186,186,186
BEGIN DESCRIPTION:
Mapping XS 06bda790
END DESCRIPTION:
XS GIS Cut Line= 3
      2705546.46     10073843.92      2705261.04     10073919.35
      2704672.75     10074222.66
#Sta/Elev= 30
  4545.1 1951.89  4561.2 1951.29  4566.4 1952.51  4600.8 1951.87  4606.7 1952.70
  4641.5 1950.68  4646.9 1951.50  4676.8 1947.48  4682.0 1948.51  4717.1 1941.12
  4720.3 1941.79  4722.3 1942.21  4739.6 1938.27  4749.9 1934.91  4757.3 1931.51
  4762.5 1932.03  4797.6 1917.49  4802.8 1917.81  4812.0 1915.76  4840.3 1912.78
  4955.7 1906.98  5051.3 1905.83  5054.0 1905.33  5057.3 1905.83  5126.4 1906.90
  5142.9 1908.40  5170.7 1908.63  5253.7 1912.20  5381.1 1922.10  5502.2 1925.35
#Mann=6,-1,0
  4545.1    0.05       0  4600.8    0.08       0  4641.5    0.16       0
  4720.3    0.05       0  5051.3    0.04       0  5057.3    0.05       0
Bank Sta=5051.3,5057.3
Exp/Cntr=0.3,0.1

Type RM Length L Ch R = 1,7058,323,323,323
BEGIN DESCRIPTION:
Mapping XS b0bf046f
END DESCRIPTION:
XS GIS Cut Line= 2
      2705338.53     10073638.03      2704618.98     10074104.83
#Sta/Elev= 30
  4576.7 1921.94  4652.9 1917.74  4668.0 1915.14  4704.3 1911.60  4782.7 1907.12
  4797.9 1905.35  4870.4 1903.51  4942.9 1903.08  4948.9 1900.93  4958.0 1901.75
  4964.0 1900.62  4979.2 1902.37  4985.1 1901.20  4991.0 1897.77  4993.7 1897.27
  4997.0 1897.77  5021.4 1904.49  5036.5 1903.94  5057.6 1906.28  5065.5 1906.10
  5072.8 1907.51  5172.8 1910.57  5217.8 1913.35  5223.7 1912.88  5275.2 1917.17
  5296.3 1922.99  5317.4 1922.70  5332.5 1919.46  5347.7 1919.29  5434.4 1924.42
#Mann=3,-1,0
  4576.7    0.05       0  4991.0    0.04       0  4997.0    0.05       0
Bank Sta=4991,4997
Exp/Cntr=0.3,0.1

Type RM Length L Ch R = 1,6735,593,593,593
BEGIN DESCRIPTION:
UNT 0080 IN HEWA 13.0
END DESCRIPTION:
XS GIS Cut Line= 3
      2705297.62     10073518.13      2704705.13     10073598.43
      2704379.57     10073774.23
#Sta/Elev= 30
  4601.2 1923.95  4650.8 1921.04  4660.9 1919.56  4678.1 1915.79  4782.0 1904.95
  4812.3 1902.53  4828.2 1900.75  4875.1 1898.48  4889.0 1898.24  4901.1 1898.42
  4923.3 1898.84  4963.6 1898.43  4978.4 1897.90  4983.8 1897.29  5001.0 1897.10
  5003.8 1896.60  5007.0 1897.10  5014.1 1897.39  5034.3 1899.35  5056.0 1900.14
  5185.6 1902.85  5303.0 1906.37  5331.7 1907.85  5417.9 1910.93  5457.3 1913.10
  5470.2 1913.28  5489.8 1913.88  5533.5 1916.50  5547.6 1917.75  5569.1 1918.77
#Mann=9,-1,0
  4601.2    0.16       0  4875.1     0.1       0  4889.0    0.16       0
  4901.1     0.1       0  5001.0    0.07       0  5007.0     0.1       0
  5303.0    0.16       0  5417.9    0.05       0  5470.2    0.16       0
Bank Sta=5001,5007
Exp/Cntr=0.3,0.1

Type RM Length L Ch R = 1,6142,316,316,316
BEGIN DESCRIPTION:
UNT 0080 IN HEWA 12.0
END DESCRIPTION:
XS GIS Cut Line= 3
      2705333.72     10073123.81      2704899.68     10073130.32
      2704124.96     10073564.34
#Sta/Elev= 30
  4292.9 1918.65  4299.2 1918.69  4628.2 1916.16  4688.2 1913.84  4744.9 1910.40
  4788.3 1904.96  4804.2 1901.52  4825.9 1897.95  4854.5 1894.81  4885.3 1892.83
  4957.6 1890.20  4966.3 1890.29  4972.0 1891.21  4980.5 1890.53  4993.7 1886.24
  5000.5 1885.24  5003.2 1884.74  5006.5 1885.24  5009.7 1887.83  5025.7 1892.33
  5053.1 1894.92  5215.2 1900.34  5290.0 1903.84  5347.3 1907.40  5384.3 1908.50
  5500.2 1913.61  5522.6 1914.59  5553.7 1915.60  5566.7 1916.93  5615.0 1919.11
#Mann=7,-1,0
  4292.9    0.16       0  4299.2     0.1       0  5000.5    0.07       0
  5006.5     0.1       0  5384.3    0.16       0  5500.2    0.05       0
  5522.6    0.16       0
Bank Sta=5000.5,5006.5
Exp/Cntr=0.3,0.1

Type RM Length L Ch R = 1,5826,196,196,196
BEGIN DESCRIPTION:
UNT 0080 IN HEWA 11.0
END DESCRIPTION:
XS GIS Cut Line= 3
      2704961.21     10073047.22      2704687.77     10072930.03
      2704197.30     10073114.49
#Sta/Elev= 30
  4500.5 1913.40  4649.7 1910.46  4696.8 1907.10  4702.2 1907.34  4720.4 1905.59
  4725.8 1905.84  4738.2 1903.83  4749.4 1901.11  4754.8 1901.83  4773.0 1898.89
  4778.4 1899.57  4794.9 1896.32  4800.3 1896.32  4829.3 1891.31  4849.0 1889.67
  4878.5 1887.47  4925.5 1887.31  4951.5 1886.58  4994.0 1884.99  4997.2 1884.34
  5000.0 1883.84  5003.2 1884.34  5010.9 1885.58  5018.9 1888.19  5024.3 1887.86
  5032.3 1889.01  5128.4 1892.87  5171.2 1895.15  5213.9 1896.47  5322.0 1901.64
#Mann=6,-1,0
  4500.5     0.1       0  4738.2    0.05       0  4849.0    0.16       0
  4951.5     0.1       0  4997.2    0.07       0  5003.2     0.1       0
Bank Sta=4997.2,5003.2
Exp/Cntr=0.3,0.1

Type RM Length L Ch R = 1,5630,370,370,370
BEGIN DESCRIPTION:
Mapping XS 053b3bf0
END DESCRIPTION:
XS GIS Cut Line= 3
      2705405.31     10072961.04      2704504.72     10072785.27
      2704085.89     10073006.61
#Sta/Elev= 30
  3991.1 1911.46  4054.7 1911.72  4062.6 1910.80  4106.3 1911.01  4162.3 1909.16
  4261.0 1907.30  4273.2 1906.32  4312.6 1906.44  4324.1 1905.55  4364.2 1906.07
  4420.8 1904.63  4472.4 1905.44  4477.5 1904.39  4517.7 1905.79  4529.1 1903.65
  4575.6 1902.47  4580.7 1901.02  4609.4 1902.31  4627.1 1902.06  4632.2 1900.56
  4701.1 1898.12  4860.2 1886.90  4918.8 1884.87  4967.3 1885.12  4998.1 1883.67
  5000.9 1883.17  5004.1 1883.67  5067.2 1886.94  5199.2 1895.79  5382.4 1902.43
#Mann=7,-1,0
  3991.1     0.1       0  4062.6    0.16       0  4162.3     0.1       0
  4860.2    0.05       0  4967.3     0.1       0  4998.1    0.07       0
  5004.1     0.1       0
Bank Sta=4998.1,5004.1
Exp/Cntr=0.3,0.1

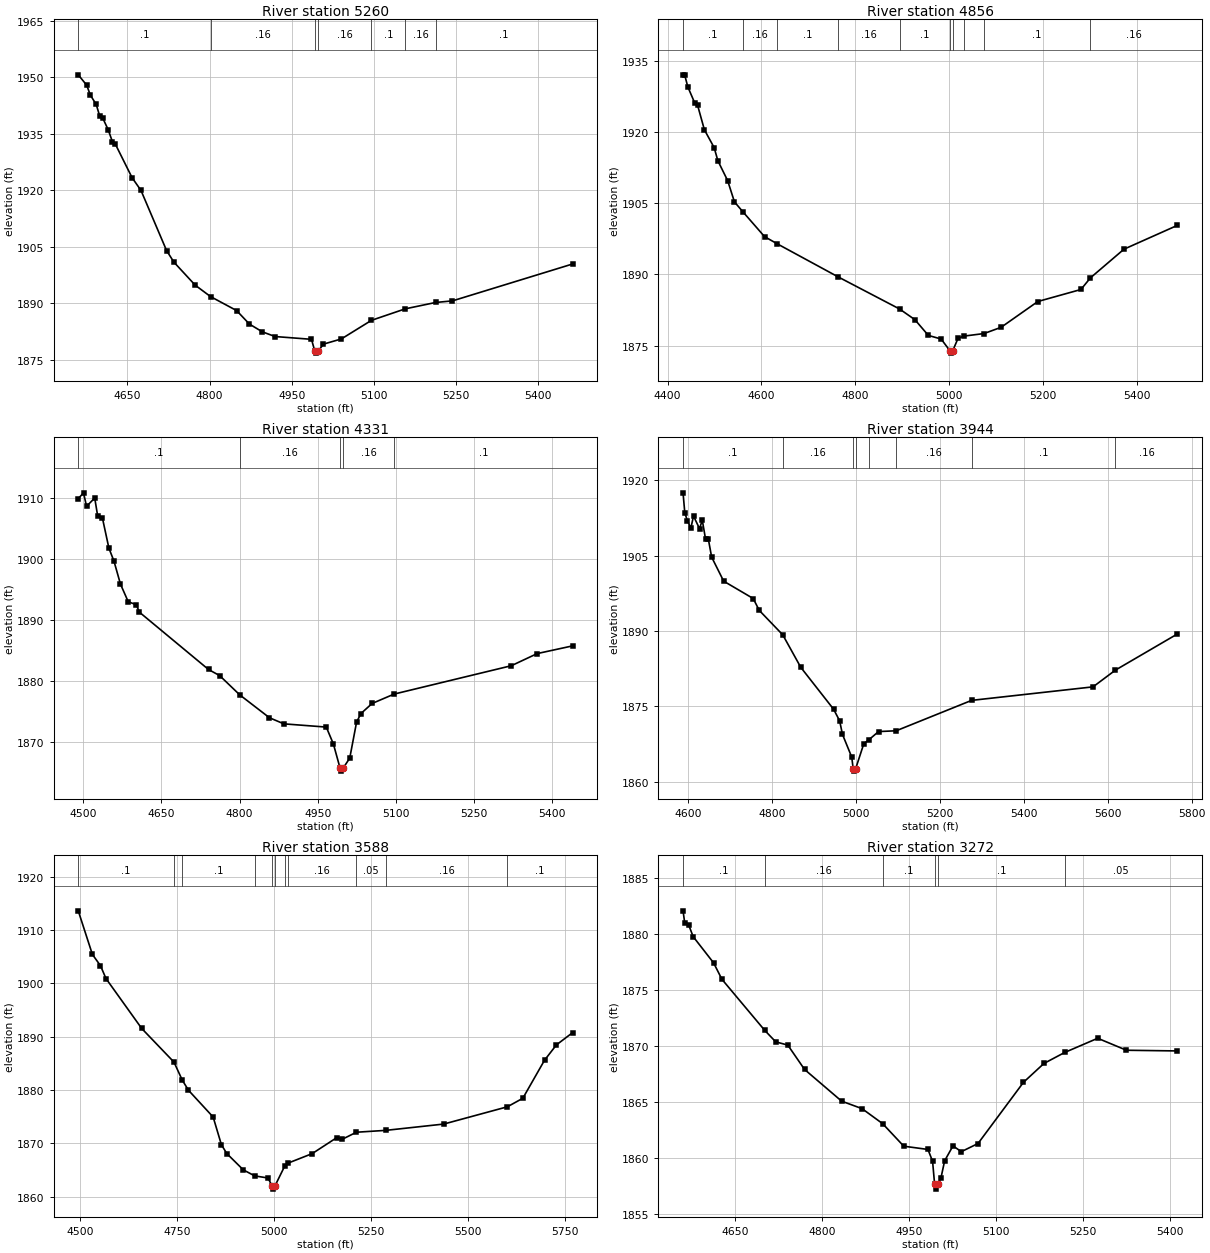
Type RM Length L Ch R = 1,5260,404,404,404
BEGIN DESCRIPTION:
UNT 0080 IN HEWA 10.0
END DESCRIPTION:
XS GIS Cut Line= 3
      2704748.49     10072302.88      2704242.89     10072524.21
      2703969.43     10072743.42
#Sta/Elev= 30
  4560.3 1950.69  4575.8 1947.92  4582.2 1945.35  4593.1 1942.81  4599.2 1939.86
  4604.6 1939.32  4614.9 1936.11  4622.6 1932.95  4628.0 1932.28  4658.6 1923.34
  4674.8 1919.97  4721.6 1903.96  4735.0 1900.89  4773.8 1894.78  4801.8 1891.75
  4849.4 1888.03  4872.8 1884.44  4896.2 1882.39  4919.6 1881.13  4986.1 1880.39
  4992.2 1877.22  4994.9 1876.72  4998.2 1877.22  5007.9 1879.11  5040.6 1880.49
  5095.5 1885.43  5157.2 1888.49  5212.6 1890.18  5243.5 1890.61  5462.7 1900.41
#Mann=7,-1,0
  4560.3     0.1       0  4801.8    0.16       0  4992.2    0.07       0
  4998.2    0.16       0  5095.5     0.1       0  5157.2    0.16       0
  5212.6     0.1       0
Bank Sta=4992.2,4998.2
Exp/Cntr=0.3,0.1

Type RM Length L Ch R = 1,4856,525,525,525
BEGIN DESCRIPTION:
UNT 0080 IN HEWA 9.0
END DESCRIPTION:
XS GIS Cut Line= 3
      2704648.73     10071810.21      2704212.51     10072155.29
      2703876.11     10072522.07
#Sta/Elev= 30
  4432.8 1932.01  4436.2 1932.01  4443.0 1929.47  4457.5 1926.14  4463.8 1925.61
  4478.3 1920.45  4499.1 1916.70  4507.1 1913.92  4527.9 1909.75  4542.4 1905.27
  4561.1 1903.11  4606.5 1897.97  4633.6 1896.45  4763.9 1889.47  4894.4 1882.74
  4927.1 1880.49  4955.9 1877.17  4983.1 1876.42  5001.8 1873.95  5004.6 1873.45
  5007.8 1873.95  5019.0 1876.54  5030.8 1877.02  5074.5 1877.57  5110.9 1878.88
  5189.2 1884.31  5281.1 1886.84  5301.5 1889.30  5372.9 1895.32  5486.7 1900.33
#Mann=10,-1,0
  4432.8     0.1       0  4561.1    0.16       0  4633.6     0.1       0
  4763.9    0.16       0  4894.4     0.1       0  5001.8    0.07       0
  5007.8     0.1       0  5030.8    0.16       0  5074.5     0.1       0
  5301.5    0.16       0
Bank Sta=5001.8,5007.8
Exp/Cntr=0.3,0.1

Type RM Length L Ch R = 1,4331,387,387,387
BEGIN DESCRIPTION:
UNT 0080 IN HEWA 8.0
END DESCRIPTION:
XS GIS Cut Line= 3
      2704438.22     10071491.22      2703928.22     10071792.87
      2703761.13     10072107.53
#Sta/Elev= 30
  4490.3 1909.83  4500.4 1910.79  4506.2 1908.58  4521.9 1909.94  4527.7 1906.93
  4536.5 1906.73  4549.1 1901.73  4558.9 1899.58  4571.3 1895.83  4586.2 1892.94
  4601.8 1892.44  4607.6 1891.23  4740.3 1881.83  4761.7 1880.83  4800.3 1877.67
  4857.3 1873.92  4885.0 1872.92  4966.4 1872.39  4980.1 1869.60  4992.8 1865.67
  4995.5 1865.17  4998.8 1865.67  5011.4 1867.30  5024.5 1873.19  5032.8 1874.60
  5054.3 1876.26  5096.6 1877.80  5321.6 1882.45  5371.3 1884.44  5439.1 1885.70
#Mann=5,-1,0
  4490.3     0.1       0  4800.3    0.16       0  4992.8    0.07       0
  4998.8    0.16       0  5096.6     0.1       0
Bank Sta=4992.8,4998.8
Exp/Cntr=0.3,0.1

Type RM Length L Ch R = 1,3944,356,356,356
BEGIN DESCRIPTION:
UNT 0080 IN HEWA 7.0
END DESCRIPTION:
XS GIS Cut Line= 2
      2704238.54     10071098.44      2703496.34     10072014.26
#Sta/Elev= 30
  4587.1 1917.49  4591.3 1913.49  4597.7 1911.90  4605.7 1910.47  4612.1 1912.86
  4626.5 1910.35  4632.9 1912.07  4640.9 1908.23  4647.3 1908.34  4655.3 1904.70
  4684.0 1899.91  4754.4 1896.46  4768.8 1894.10  4824.9 1889.23  4867.9 1882.76
  4946.2 1874.42  4960.6 1872.11  4967.2 1869.44  4989.4 1864.90  4992.8 1862.61
  4995.5 1862.11  4998.8 1862.61  5018.1 1867.55  5030.7 1868.38  5053.3 1869.98
  5095.4 1870.14  5275.3 1876.19  5564.9 1878.88  5618.4 1882.22  5765.9 1889.40
#Mann=8,-1,0
  4587.1     0.1       0  4824.9    0.16       0  4992.8    0.07       0
  4998.8    0.16       0  5030.7     0.1       0  5095.4    0.16       0
  5275.3     0.1       0  5618.4    0.16       0
Bank Sta=4992.8,4998.8
Exp/Cntr=0.3,0.1

Type RM Length L Ch R = 1,3588,316,316,316
BEGIN DESCRIPTION:
UNT 0080 IN HEWA 6.0
END DESCRIPTION:
XS GIS Cut Line= 3
      2704036.75     10070981.22      2703446.45     10071495.57
      2703279.34     10071957.84
#Sta/Elev= 30
  4496.0 1913.62  4532.4 1905.45  4553.3 1903.33  4567.5 1900.92  4659.6 1891.56
  4742.8 1885.25  4764.2 1881.87  4780.2 1879.97  4843.8 1874.95  4865.1 1869.76
  4878.9 1868.11  4921.6 1865.04  4951.0 1863.91  4985.2 1863.52  4996.5 1861.93
  4999.2 1861.43  5002.5 1861.93  5028.0 1865.70  5036.3 1866.29  5099.2 1868.09
  5162.8 1871.10  5177.0 1870.79  5213.2 1872.10  5288.9 1872.45  5438.3 1873.63
  5602.4 1876.87  5642.3 1878.47  5698.3 1885.61  5728.9 1888.48  5770.5 1890.77
#Mann=11,-1,0
  4496.0     0.1       0  4742.8    0.16       0  4764.2     0.1       0
  4951.0    0.16       0  4996.5    0.07       0  5002.5    0.16       0
  5028.0     0.1       0  5036.3    0.16       0  5213.2    0.05       0
  5288.9    0.16       0  5602.4     0.1       0
Bank Sta=4996.5,5002.5
Exp/Cntr=0.3,0.1

Type RM Length L Ch R = 1,3272,467,467,467
BEGIN DESCRIPTION:
Mapping XS 50fa0c53
END DESCRIPTION:
XS GIS Cut Line= 2
      2703735.09     10070866.22      2703073.29     10071402.17
#Sta/Elev= 30
  4560.4 1882.09  4563.4 1880.97  4569.9 1880.86  4577.8 1879.79  4613.0 1877.45
  4627.4 1875.98  4701.2 1871.42  4720.1 1870.40  4740.9 1870.11  4769.7 1867.94
  4833.6 1865.11  4868.8 1864.44  4904.3 1863.10  4940.7 1861.09  4982.3 1860.80
  4990.3 1859.75  4993.7 1857.76  4996.5 1857.26  4999.7 1857.76  5004.7 1858.25
  5011.1 1859.79  5025.5 1861.12  5039.8 1860.60  5068.6 1861.33  5146.9 1866.79
  5182.1 1868.47  5217.8 1869.45  5274.8 1870.72  5324.4 1869.65  5412.0 1869.59
#Mann=6,-1,0
  4560.4     0.1       0  4701.2    0.16       0  4904.3     0.1       0
  4993.7    0.07       0  4999.7     0.1       0  5217.8    0.05       0
Bank Sta=4993.7,4999.7
Exp/Cntr=0.3,0.1

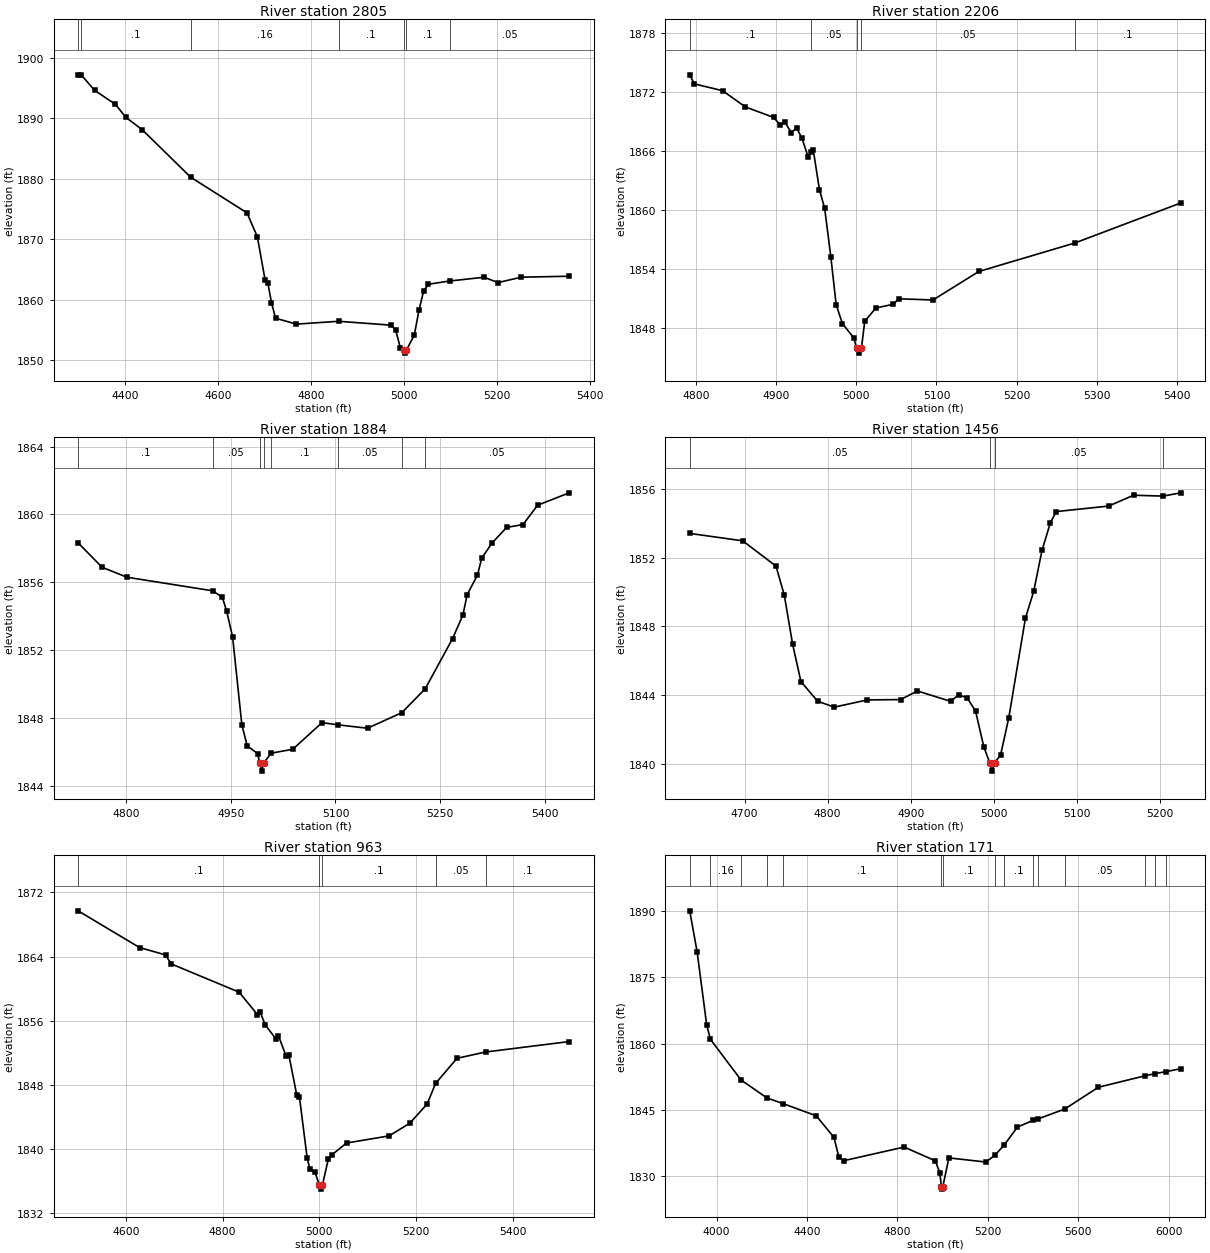
Type RM Length L Ch R = 1,2805,599,599,599
BEGIN DESCRIPTION:
UNT 0080 IN HEWA 5.0
END DESCRIPTION:
XS GIS Cut Line= 3
      2703850.13     10070616.64      2703418.24     10070833.67
      2702845.33     10070827.16
#Sta/Elev= 30
  4298.3 1897.20  4305.2 1897.18  4333.7 1894.64  4378.5 1892.32  4400.9 1890.17
  4436.6 1888.09  4540.3 1880.26  4661.6 1874.35  4683.9 1870.36  4700.6 1863.19
  4706.2 1862.81  4714.2 1859.50  4723.0 1856.91  4767.6 1855.93  4858.5 1856.40
  4971.4 1855.76  4981.4 1854.93  4991.4 1852.01  4998.4 1851.63  5001.2 1851.13
  5004.4 1851.63  5021.4 1854.12  5031.4 1858.24  5041.4 1861.38  5051.4 1862.53
  5097.5 1863.07  5171.4 1863.69  5201.5 1862.81  5251.5 1863.70  5354.6 1863.86
#Mann=7,-1,0
  4298.3    0.16       0  4305.2     0.1       0  4540.3    0.16       0
  4858.5     0.1       0  4998.4    0.07       0  5004.4     0.1       0
  5097.5    0.05       0
Bank Sta=4998.4,5004.4
Exp/Cntr=0.3,0.1

Type RM Length L Ch R = 1,2206,322,322,322
BEGIN DESCRIPTION:
UNT 0080 IN HEWA 4.0
END DESCRIPTION:
XS GIS Cut Line= 2
      2703485.50     10070262.94      2703016.80     10070657.86
#Sta/Elev= 30
  4792.1 1873.71  4797.9 1872.79  4833.1 1872.10  4861.7 1870.45  4896.8 1869.39
  4904.6 1868.67  4911.1 1868.89  4918.8 1867.85  4925.4 1868.32  4932.1 1867.31
  4939.7 1865.42  4943.8 1865.87  4946.2 1866.13  4954.0 1862.05  4960.5 1860.18
  4968.3 1855.19  4974.8 1850.42  4982.6 1848.49  4996.9 1847.03  5000.4 1845.99
  5003.2 1845.49  5006.4 1845.99  5010.5 1848.71  5024.3 1850.06  5046.3 1850.45
  5052.8 1851.00  5095.7 1850.88  5152.9 1853.77  5272.4 1856.65  5405.0 1860.72
#Mann=5,-1,0
  4792.1     0.1       0  4943.8    0.05       0  5000.4   0.035       0
  5006.4    0.05       0  5272.4     0.1       0
Bank Sta=5000.4,5006.4
Exp/Cntr=0.3,0.1

Type RM Length L Ch R = 1,1884,428,428,428
BEGIN DESCRIPTION:
UNT 0080 IN HEWA 3.0
END DESCRIPTION:
XS GIS Cut Line= 2
      2703290.22     10070048.07      2702715.09     10070453.91
#Sta/Elev= 30
  4731.1 1858.32  4765.4 1856.88  4801.1 1856.29  4923.8 1855.49  4937.8 1855.11
  4943.9 1854.31  4952.6 1852.75  4965.8 1847.58  4973.5 1846.34  4988.3 1845.89
  4991.4 1845.35  4994.1 1844.85  4997.4 1845.35  5007.8 1845.91  5038.8 1846.14
  5080.6 1847.71  5104.0 1847.58  5145.9 1847.38  5195.1 1848.30  5228.6 1849.71
  5267.8 1852.67  5282.6 1854.06  5288.7 1855.26  5303.5 1856.42  5309.6 1857.42
  5324.4 1858.31  5345.3 1859.23  5368.8 1859.40  5389.7 1860.54  5435.0 1861.27
#Mann=8,-1,0
  4731.1     0.1       0  4923.8    0.05       0  4991.4   0.035       0
  4997.4    0.05       0  5007.8     0.1       0  5104.0    0.05       0
  5195.1     0.1       0  5228.6    0.05       0
Bank Sta=4991.4,4997.4
Exp/Cntr=0.3,0.1

Type RM Length L Ch R = 1,1456,493,493,493
BEGIN DESCRIPTION:
UNT 0080 IN HEWA 2.0
END DESCRIPTION:
XS GIS Cut Line= 2
      2703162.16     10069933.07      2702571.55     10069900.61
#Sta/Elev= 30
  4633.9 1853.41  4697.7 1852.98  4737.8 1851.51  4747.8 1849.82  4757.8 1846.98
  4767.8 1844.80  4787.8 1843.66  4807.9 1843.31  4847.9 1843.73  4888.0 1843.75
  4908.0 1844.25  4948.1 1843.65  4958.1 1844.03  4968.1 1843.84  4978.1 1843.09
  4988.1 1841.00  4995.1 1840.09  4997.9 1839.59  5001.1 1840.09  5008.2 1840.51
  5018.2 1842.70  5038.2 1848.48  5048.2 1850.05  5058.2 1852.43  5068.2 1854.02
  5075.3 1854.68  5138.4 1855.00  5168.4 1855.63  5204.0 1855.58  5225.4 1855.77
#Mann=4,-1,0
  4633.9    0.05       0  4995.1   0.035       0  5001.1    0.05       0
  5204.0     0.1       0
Bank Sta=4995.1,5001.1
Exp/Cntr=0.3,0.1

Type RM Length L Ch R = 1,963,792,792,792
BEGIN DESCRIPTION:
Mapping XS b2a20fc0
END DESCRIPTION:
XS GIS Cut Line= 3
      2703586.43     10069949.31      2703028.77     10069638.34
      2702662.67     10069723.15
#Sta/Elev= 30
  4501.7 1869.71  4628.6 1865.13  4682.3 1864.21  4694.0 1863.09  4834.3 1859.56
  4872.0 1856.77  4877.7 1857.09  4888.0 1855.51  4909.7 1853.76  4915.4 1854.14
  4931.4 1851.56  4937.1 1851.68  4953.1 1846.78  4958.8 1846.50  4974.8 1838.84
  4980.6 1837.48  4990.8 1837.09  5000.2 1835.49  5002.9 1834.99  5006.2 1835.49
  5018.3 1838.69  5026.1 1839.28  5056.0 1840.74  5143.8 1841.63  5186.5 1843.20
  5222.6 1845.61  5239.9 1848.17  5284.2 1851.31  5343.6 1852.10  5516.0 1853.40
#Mann=5,-1,0
  4501.7     0.1       0  5000.2    0.07       0  5006.2     0.1       0
  5239.9    0.05       0  5343.6     0.1       0
Bank Sta=5000.2,5006.2
Exp/Cntr=0.3,0.1

Type RM Length L Ch R = 1,171,0,0,0
BEGIN DESCRIPTION:
UNT 0080 IN HEWA 1.0
END DESCRIPTION:
XS GIS Cut Line= 4
      2704196.46     10069599.82      2703342.30     10069037.32
      2703057.58     10069044.26      2702550.61     10069745.68
#Sta/Elev= 30
  3881.4 1890.05  3914.3 1880.73  3956.5 1864.22  3973.1 1860.97  4108.5 1851.77
  4223.3 1847.70  4293.6 1846.44  4441.4 1843.66  4519.7 1838.76  4540.7 1834.41
  4561.8 1833.49  4829.9 1836.59  4968.0 1833.48  4988.0 1830.75  4995.0 1827.57
  4997.8 1827.07  5001.0 1827.57  5028.0 1834.14  5191.7 1833.20  5231.6 1834.74
  5272.3 1837.02  5331.4 1841.11  5402.2 1842.68  5423.3 1842.97  5540.9 1845.20
  5689.5 1850.13  5893.8 1852.69  5940.1 1853.21  5989.2 1853.66  6054.4 1854.33
#Mann=15,-1,0
  3881.4     0.1       0  3973.1    0.16       0  4108.5     0.1       0
  4223.3    0.16       0  4293.6     0.1       0  4995.0    0.07       0
  5001.0     0.1       0  5231.6    0.05       0  5272.3     0.1       0
  5402.2    0.16       0  5423.3     0.1       0  5540.9    0.05       0
  5893.8     0.1       0  5940.1    0.05       0  5989.2     0.1       0
Bank Sta=4995,5001
Exp/Cntr=0.3,0.1

Chan Stop Cuts=-1