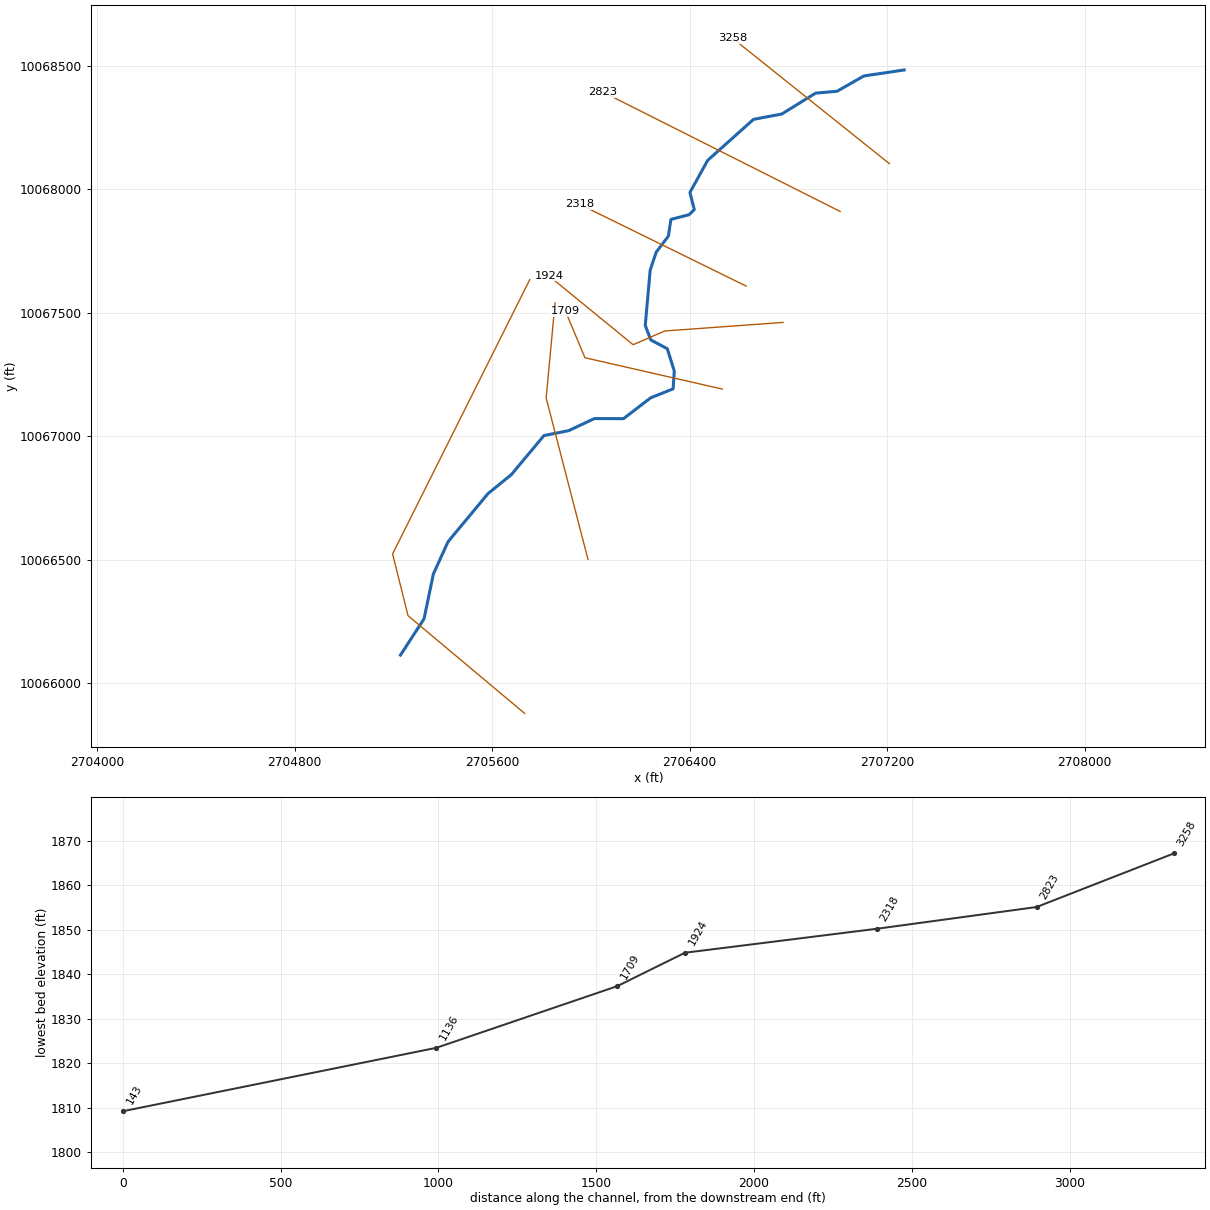
--- UNT 0081 IN HEWA.prj (project) ---

Proj Title=UNT 0081 IN HEWA Base Level Engineering
Current Plan=p01
Default Exp/Contr=0.3,0.1
English Units
Geom File=g01
Flow File=f01
Plan File=p01
Y Axis Title=Elevation
X Axis Title(PF)=Main Channel Distance
X Axis Title(XS)=Station
BEGIN DESCRIPTION:
UNT 0081 IN HEWA
END DESCRIPTION:
DSS Export Rating Curves= 0
DSS Export Rating Curve Sorted= 0
DSS Export Volume Flow Curves= 0
DXF OffsetX= 0
DXF OffsetY= 0
DXF ScaleX= 1
DXF ScaleY= 10

--- UNT 0081 IN HEWA.p01 (plan) ---

Plan Title=Multiple Run
Short Identifier=Multiple
Geom File=g01
Flow File=f01
Subcritical Flow
K Sum by GR= 0
Std Step Tol= 0.01
Critical Tol= 0.01
Num of Std Step Trials= 20
Max Error Tol= 0.3
Flow Tol Ratio= 0.001
Split Flow NTrial= 30
Split Flow Tol= 0.02
Split Flow Ratio= 0.02
Log Output Level= 0
Friction Slope Method= 1
Unsteady Friction Slope Method= 2
Unsteady Bridges Friction Slope Method= 1
Parabolic Critical Depth
Global Vel Dist=  1 , 1 , 1
Global Log Level= 0
CheckData=True
Encroach Param= -1, 0, 0, 0
BEGIN DESCRIPTION:
Multiple Run
END DESCRIPTION:

--- UNT 0081 IN HEWA.f01 (steady flow) ---

Flow Title=Multiple
Program Version=4.10
Number of Profiles= 7
Profile Names=10-year,25-year,50-year,1pct_min,100-year,1pct_plu,500-year
River Rch & RM=UNT 0081 IN HEWA,Reach-1         ,3258
    1545    2298    2963    2785    3766    5093    6082
Boundary for River Rch & Prof#=UNT 0081 IN HEWA,Reach-1         , 1
Up Type= 0
Dn Type= 3
Dn Slope=0.014
Boundary for River Rch & Prof#=UNT 0081 IN HEWA,Reach-1         , 2
Up Type= 0
Dn Type= 3
Dn Slope=0.014
Boundary for River Rch & Prof#=UNT 0081 IN HEWA,Reach-1         , 3
Up Type= 0
Dn Type= 3
Dn Slope=0.014
Boundary for River Rch & Prof#=UNT 0081 IN HEWA,Reach-1         , 4
Up Type= 0
Dn Type= 3
Dn Slope=0.014
Boundary for River Rch & Prof#=UNT 0081 IN HEWA,Reach-1         , 5
Up Type= 0
Dn Type= 3
Dn Slope=0.014
Boundary for River Rch & Prof#=UNT 0081 IN HEWA,Reach-1         , 6
Up Type= 0
Dn Type= 3
Dn Slope=0.014
Boundary for River Rch & Prof#=UNT 0081 IN HEWA,Reach-1         , 7
Up Type= 0
Dn Type= 3
Dn Slope=0.014
DSS Import GetInterval= 0
DSS Import GetPeak= 0
DSS Import FillOption= 0

--- UNT 0081 IN HEWA.g01 (geometry) ---

Geom Title=Existing Conditions
Program Version=4.10

River Reach=UNT 0081 IN HEWA,Reach-1
Reach XY= 30
      2707268.47     10068483.73      2707105.49     10068459.53
      2706996.86     10068397.61      2706910.03     10068389.95
      2706772.81     10068305.31      2706658.47     10068283.73
      2706472.84     10068117.82      2706400.86     10067987.62
      2706418.57     10067918.44      2706397.39     10067897.49
      2706323.81     10067878.39      2706313.76     10067811.12
      2706264.38       10067746.      2706239.91     10067673.13
       2706219.9     10067449.37      2706242.13     10067390.39
       2706309.2     10067354.71      2706337.53      10067263.7
      2706332.74      10067192.2      2706242.26     10067156.04
      2706131.75     10067071.36      2706014.06     10067071.81
      2705909.58     10067022.77      2705809.46     10067002.93
      2705677.49     10066844.71      2705582.78     10066767.67
      2705420.96      10066572.7      2705361.69      10066442.4
      2705323.97     10066260.88      2705228.47     10066113.73

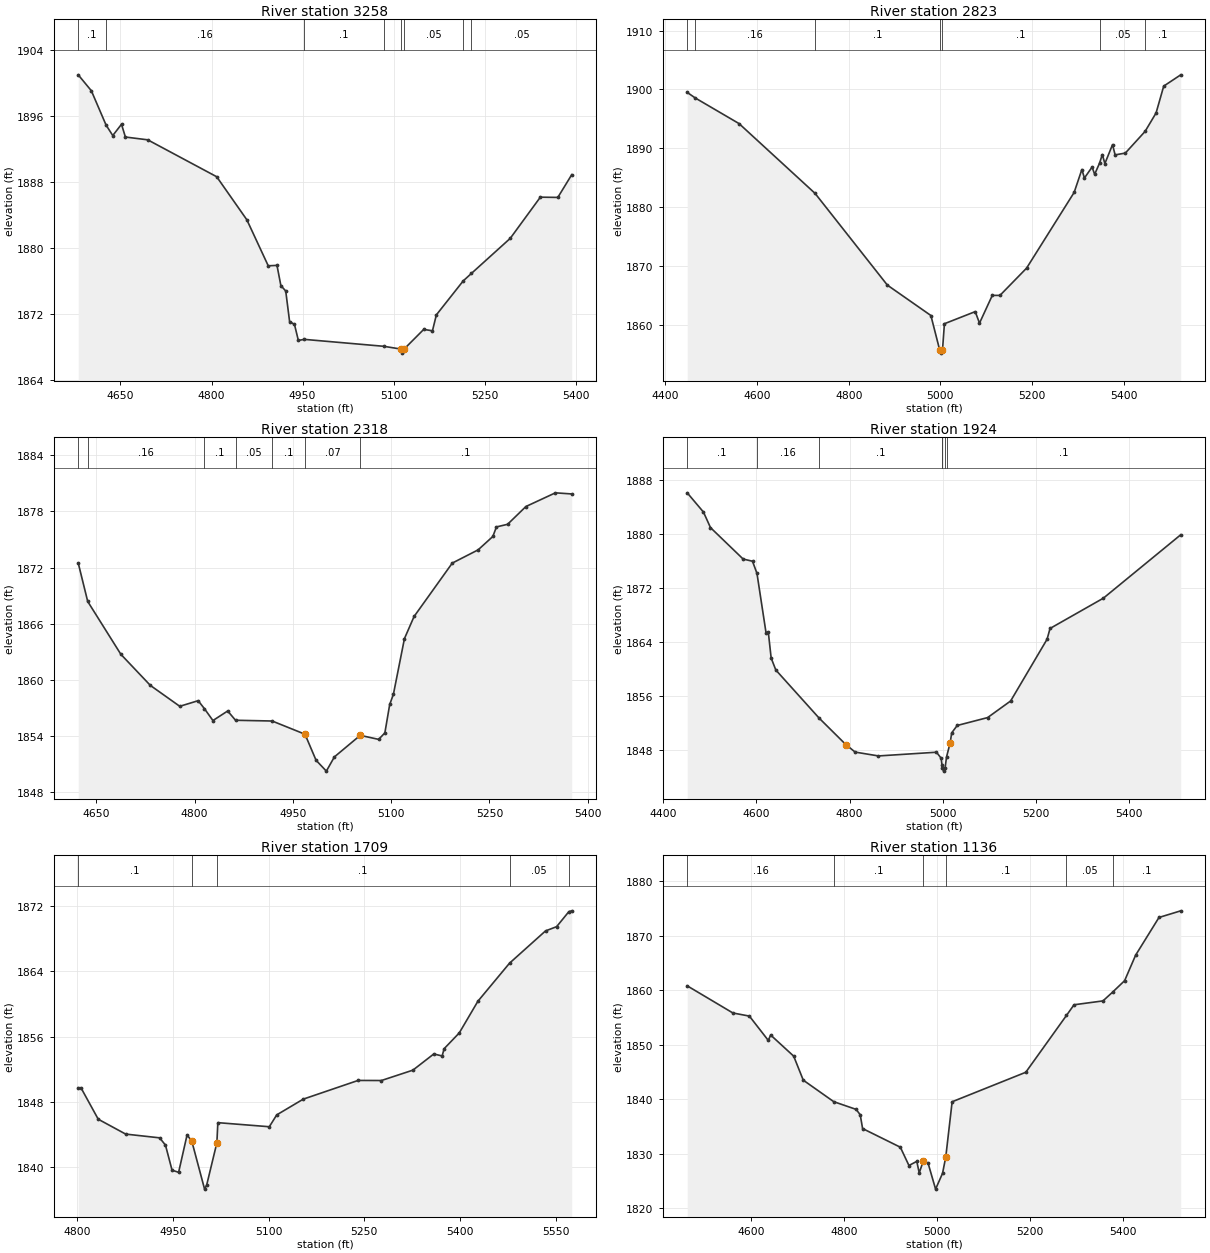
Type RM Length L Ch R = 1 ,3258    ,435,435,435
BEGIN DESCRIPTION:
UNT 0081 IN HEWA 5.0
END DESCRIPTION:
XS GIS Cut Line= 2
      2707208.98     10068104.11      2706574.21     10068611.93
#Sta/Elev= 30
  4580.4 1900.99    4602 1899.06  4626.3 1894.89  4637.3 1893.62  4651.7 1894.99
  4658.1 1893.44  4694.9  1893.1  4808.5 1888.62  4858.2 1883.39  4893.4 1877.81
  4907.8 1877.86  4914.2 1875.41  4922.2 1874.75  4928.6 1871.03  4936.6  1870.7
    4943 1868.75  4952.7 1868.88  5083.6 1868.04  5111.3 1867.71    5114 1867.21
  5117.3 1867.71  5149.5 1870.09  5163.9 1869.92  5170.3 1871.85  5214.6 1875.98
    5228 1876.88    5292 1881.14  5341.6 1886.14  5370.4 1886.11  5393.3 1888.87
#Mann= 8 ,-1 , 0
  4580.4      .1       0  4626.3     .16       0  4952.7      .1       0
  5083.6     .05       0  5111.3     .07       0  5117.3     .05       0
  5214.6      .1       0    5228     .05       0
Bank Sta=5111.3,5117.3
XS Rating Curve= 0 ,0
Exp/Cntr=0.3,0.1

Type RM Length L Ch R = 1 ,2823    ,505,505,505
BEGIN DESCRIPTION:
UNT 0081 IN HEWA 4.0
END DESCRIPTION:
XS GIS Cut Line= 2
      2707009.47     10067910.66      2706048.19     10068394.33
#Sta/Elev= 30
  4447.9  1899.5  4465.5 1898.55    4561 1894.19  4726.7 1882.32  4884.3 1866.72
  4979.2 1861.55  4998.5 1855.65  5001.2 1855.15  5004.5 1855.65  5008.7 1860.15
  5075.9 1862.21  5085.2 1860.25  5113.1 1864.97  5129.8 1864.97  5187.9 1869.61
  5291.6 1882.49  5308.4 1886.38    5314 1884.94  5330.7  1886.8  5336.3 1885.57
    5347 1887.47    5353 1888.93  5358.6  1887.4  5375.3 1890.62  5380.9 1888.87
  5403.2 1889.18  5446.2 1892.86  5470.2    1896  5486.9 1900.57    5524 1902.49
#Mann= 7 ,-1 , 0
  4447.9      .1       0  4465.5     .16       0  4726.7      .1       0
  4998.5     .07       0  5004.5      .1       0    5347     .05       0
  5446.2      .1       0
Bank Sta=4998.5,5004.5
XS Rating Curve= 0 ,0
Exp/Cntr=0.3,0.1

Type RM Length L Ch R = 1 ,2318    ,609,609,609
BEGIN DESCRIPTION:
UNT 0081 IN HEWA 3.0
END DESCRIPTION:
XS GIS Cut Line= 2
      2706628.57      10067608.4      2705952.49      10067940.4
#Sta/Elev= 30
  4622.4 1872.49  4636.9 1868.38  4687.5 1862.74  4732.5 1859.42  4777.4 1857.19
  4805.5 1857.79  4815.1 1856.93    4828 1855.67  4850.5 1856.69  4862.5  1855.7
  4918.4 1855.62  4968.5 1854.21  4985.4 1851.43  5001.1 1850.27  5013.4 1851.79
  5052.8 1854.09  5080.9 1853.66  5090.4 1854.35  5097.8 1857.39  5103.4 1858.46
  5120.3 1864.42    5135 1866.78  5193.3 1872.48  5232.7 1873.89  5255.2 1875.32
  5260.7 1876.34  5277.7 1876.62  5305.7 1878.52  5350.7 1879.98  5375.6 1879.86
#Mann= 7 ,-1 , 0
  4622.4      .1       0  4636.9     .16       0  4815.1      .1       0
  4862.5     .05       0  4918.4      .1       0  4968.5     .07       0
  5052.8      .1       0
Bank Sta=4968.5,5052.8
XS Rating Curve= 0 ,0
Exp/Cntr=0.3,0.1

Type RM Length L Ch R = 1 ,1924    ,215,215,215
BEGIN DESCRIPTION:
Mapping XS bdfcc89b
END DESCRIPTION:
XS GIS Cut Line= 4
      2706778.37     10067461.25      2706299.17     10067426.53
       2706170.7     10067370.97      2705829.79     10067649.58
#Sta/Elev= 30
  4451.2 1886.09  4486.1 1883.24  4501.2 1880.94  4571.4 1876.28  4591.5 1875.96
  4601.1 1874.16  4620.5  1865.4  4625.5 1865.45  4631.6 1861.62  4641.6 1859.85
  4734.6 1852.73    4792 1848.81  4812.1 1847.69  4862.2 1847.12  4986.9 1847.67
    4997 1846.78  4998.8 1845.76  4999.5 1845.37  5002.2 1844.87  5005.5 1845.37
  5008.6 1846.99 5016.36 1849.07  5019.6 1850.53  5031.4 1851.63  5096.8  1852.8
  5146.3 1855.26  5224.6  1864.4    5231    1866  5345.7 1870.49  5511.9 1879.88
#Mann= 7 ,-1 , 0
  4451.2      .1       0  4601.1     .16       0  4734.6      .1       0
  4998.8     .05       0  4999.5    .035       0  5005.5     .05       0
  5008.6      .1       0
Bank Sta=4792,5016.36
XS Rating Curve= 0 ,0
Exp/Cntr=0.3,0.1

Type RM Length L Ch R = 1 ,1709    ,573,573,573
BEGIN DESCRIPTION:
Mapping XS 35c47019
END DESCRIPTION:
XS GIS Cut Line= 3
      2706531.88     10067191.24      2705975.67      10067318.2
      2705897.09     10067505.57
#Sta/Elev= 30
  4801.6 1849.75  4805.9 1849.75    4833  1845.9    4876 1844.08  4929.2 1843.62
  4938.4 1842.73  4948.7 1839.66    4959  1839.4  4972.2 1843.96  4979.5 1843.26
  4999.7 1837.34    5003 1837.84 5018.99 1843.02  5020.5 1845.48  5101.2 1844.98
  5112.8 1846.43  5154.4 1848.36  5240.4 1850.65  5276.9 1850.64  5326.3 1851.91
    5359 1853.89  5372.1 1853.65  5375.3 1854.54    5399 1856.47  5428.2 1860.35
  5477.8 1865.01  5534.2 1868.96  5551.6 1869.48  5570.8 1871.32  5575.3 1871.42
#Mann= 5 ,-1 , 0
  4801.6      .1       0  4979.5     .07       0 5018.99      .1       0
  5477.8     .05       0  5570.8      .1       0
Bank Sta=4979.5,5018.99
XS Rating Curve= 0 ,0
Exp/Cntr=0.3,0.1

Type RM Length L Ch R = 1 ,1136    ,993,993,993
BEGIN DESCRIPTION:
UNT 0081 IN HEWA 2.0
END DESCRIPTION:
XS GIS Cut Line= 3
      2705987.76     10066502.07      2705818.48     10067154.97
      2705854.61      10067540.3
#Sta/Elev= 30
  4463.2 1860.83  4561.5 1855.84  4596.9 1855.27  4637.5 1850.81  4642.7 1851.79
  4692.2 1847.91  4712.8  1843.5  4778.3 1839.55  4826.5 1838.13  4835.3 1837.14
  4840.4 1834.61  4921.6 1831.18  4940.1 1827.82    4957 1828.58  4962.2 1826.45
  4971.1 1828.68  4981.4 1828.21  4997.4 1823.48  5012.4 1826.39 5019.35 1829.41
    5033 1839.53  5191.4 1844.95  5278.9 1855.39  5295.2 1857.35  5357.4 1858.06
    5378 1859.66    5404 1861.78  5427.7 1866.47  5477.9 1873.39  5524.7 1874.61
#Mann= 6 ,-1 , 0
  4463.2     .16       0  4778.3      .1       0  4971.1     .05       0
 5019.35      .1       0  5278.9     .05       0    5378      .1       0
Bank Sta=4971.1,5019.35
XS Rating Curve= 0 ,0
Exp/Cntr=0.3,0.1

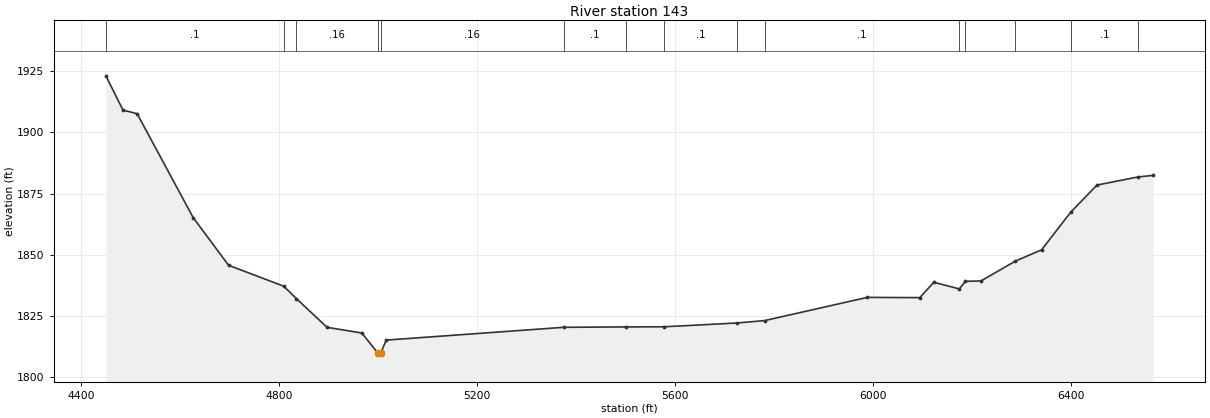
Type RM Length L Ch R = 1 ,143     ,0,0,0
BEGIN DESCRIPTION:
UNT 0081 IN HEWA 1.0
END DESCRIPTION:
XS GIS Cut Line= 4
      2705731.18     10065877.61      2705258.97     10066273.43
      2705196.47     10066523.43      2705752.01     10067634.52
#Sta/Elev= 30
  4449.4  1923.2  4483.9 1909.17  4512.5 1907.69  4625.7 1865.16  4697.3  1845.6
  4808.6 1837.06  4834.3 1831.97  4896.3  1820.2  4966.6 1817.87  4998.7 1809.72
  5001.5 1809.22  5004.7 1809.72    5016 1814.97  5374.6  1820.2  5499.6 1820.36
  5577.5 1820.42  5724.5 1821.97  5780.4 1822.95  5988.1 1832.46  6094.3 1832.36
  6122.3 1838.66  6174.1 1835.92  6186.1 1839.02    6218 1839.21  6286.5 1847.23
  6340.3 1851.95  6398.9  1867.3  6452.1 1878.46  6535.2 1881.78  6565.5 1882.43
#Mann= 15 ,-1 , 0
  4449.4      .1       0  4808.6     .05       0  4834.3     .16       0
  4998.7     .07       0  5004.7     .16       0  5374.6      .1       0
  5499.6     .05       0  5577.5      .1       0  5724.5     .05       0
  5780.4      .1       0  6174.1     .16       0  6186.1      .1       0
  6286.5     .05       0  6398.9      .1       0  6535.2     .16       0
Bank Sta=4998.7,5004.7
XS Rating Curve= 0 ,0
Exp/Cntr=0.3,0.1

Chan Stop Cuts=-1
Use User Specified Reach Order=0
Composite Channel Slope=5