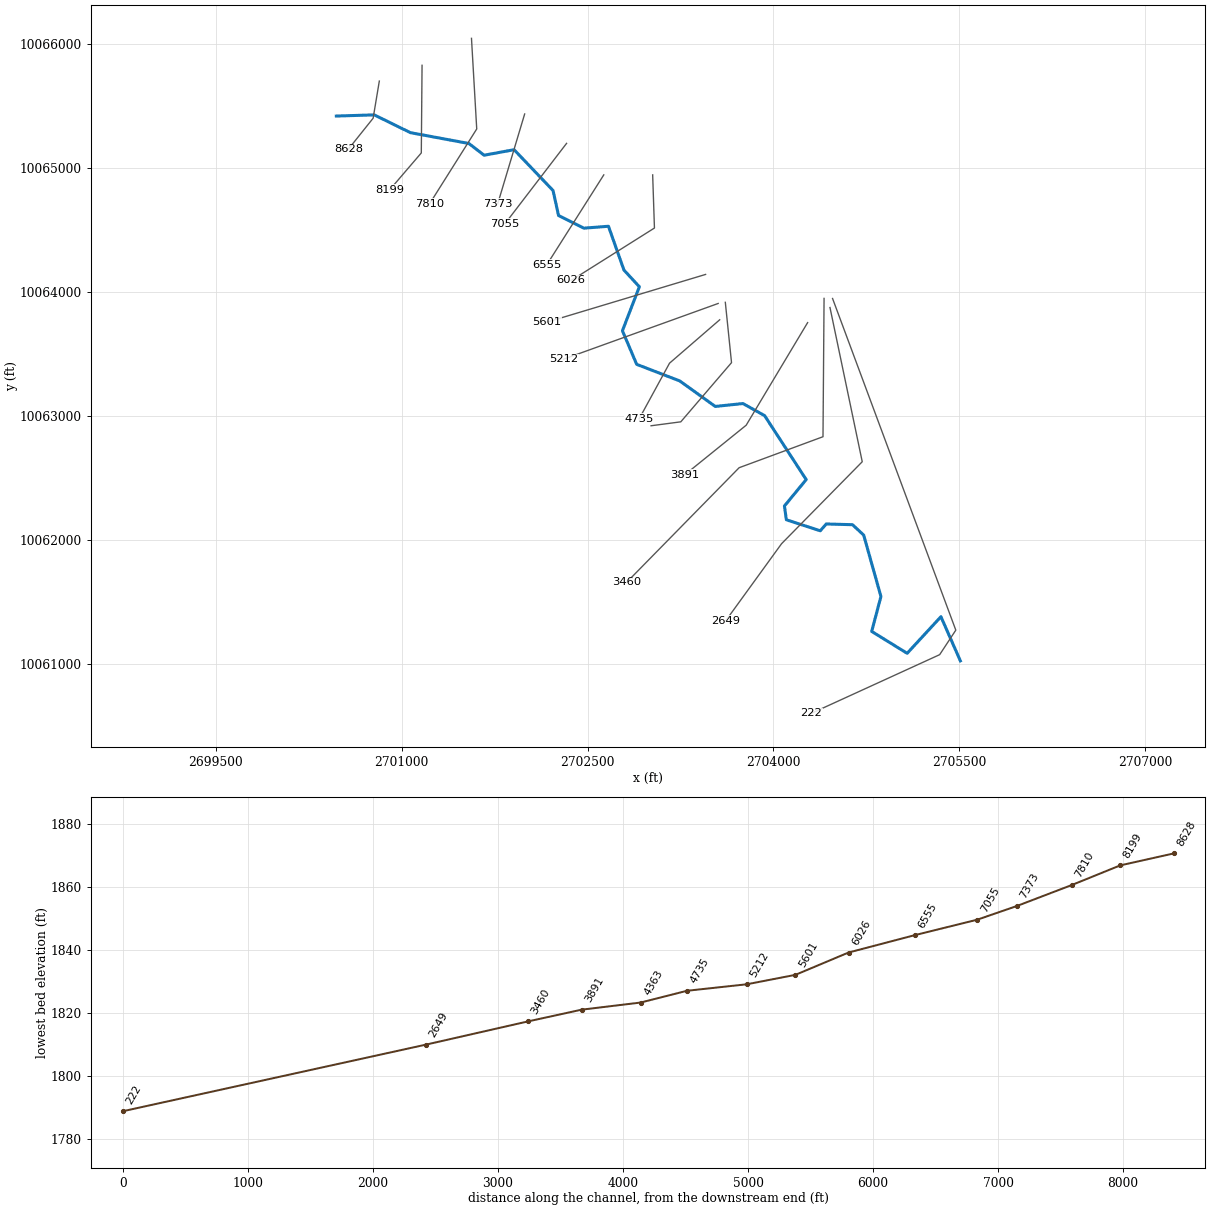
--- UNT 0082 IN HEWA.prj (project) ---

Proj Title=UNT 0082 IN HEWA Base Level Engineering
Current Plan=p01
Default Exp/Contr=0.3,0.1
English Units
Geom File=g01
Flow File=f01
Plan File=p01
Y Axis Title=Elevation
X Axis Title(PF)=Main Channel Distance
X Axis Title(XS)=Station
BEGIN DESCRIPTION:
UNT 0082 IN HEWA
END DESCRIPTION:
DSS Export Rating Curves= 0
DSS Export Rating Curve Sorted= 0
DSS Export Volume Flow Curves= 0
DXF OffsetX= 0
DXF OffsetY= 0
DXF ScaleX= 1
DXF ScaleY= 10

--- UNT 0082 IN HEWA.p01 (plan) ---

Plan Title=Multiple Run
Short Identifier=Multiple
Geom File=g01
Flow File=f01
Subcritical Flow
K Sum by GR= 0
Std Step Tol= 0.01
Critical Tol= 0.01
Num of Std Step Trials= 20
Max Error Tol= 0.3
Flow Tol Ratio= 0.001
Split Flow NTrial= 30
Split Flow Tol= 0.02
Split Flow Ratio= 0.02
Log Output Level= 0
Friction Slope Method= 1
Unsteady Friction Slope Method= 2
Unsteady Bridges Friction Slope Method= 1
Parabolic Critical Depth
Global Vel Dist=  1 , 1 , 1
Global Log Level= 0
CheckData=True
Encroach Param= -1, 0, 0, 0
BEGIN DESCRIPTION:
Multiple Run
END DESCRIPTION:

--- UNT 0082 IN HEWA.f01 (steady flow) ---

Flow Title=Multiple
Number of Profiles=7
Profile Names=10-year,25-year,50-year,1pct_min,100-year,1pct_plu,500-year
River Rch & RM= UNT 0082 IN HEWA,Reach-1,8628
    1283    1891    2425    2267    3066    4146    4899
River Rch & RM= UNT 0082 IN HEWA,Reach-1,8199
    2005    3011    3906    3687    4986    6743    8129
Boundary for River Rch & Prof#=UNT 0082 IN HEWA,Reach-1,1
Up Type=0
Dn Type=3
Dn Slope=0.005
Boundary for River Rch & Prof#=UNT 0082 IN HEWA,Reach-1,2
Up Type=0
Dn Type=3
Dn Slope=0.005
Boundary for River Rch & Prof#=UNT 0082 IN HEWA,Reach-1,3
Up Type=0
Dn Type=3
Dn Slope=0.005
Boundary for River Rch & Prof#=UNT 0082 IN HEWA,Reach-1,4
Up Type=0
Dn Type=3
Dn Slope=0.005
Boundary for River Rch & Prof#=UNT 0082 IN HEWA,Reach-1,5
Up Type=0
Dn Type=3
Dn Slope=0.005
Boundary for River Rch & Prof#=UNT 0082 IN HEWA,Reach-1,6
Up Type=0
Dn Type=3
Dn Slope=0.005
Boundary for River Rch & Prof#=UNT 0082 IN HEWA,Reach-1,7
Up Type=0
Dn Type=3
Dn Slope=0.005

--- UNT 0082 IN HEWA.g01 (geometry) ---

Geom Title=Existing Conditions

River Reach=UNT 0082 IN HEWA,Reach-1
Reach XY= 30
      2700471.68     10065421.30      2700777.25     10065430.93
      2701069.55     10065287.32      2701541.57     10065199.79
      2701664.26     10065105.21      2701906.34     10065149.70
      2702220.81     10064820.09      2702265.15     10064618.55
      2702469.81     10064516.38      2702668.05     10064531.78
      2702793.24     10064177.87      2702917.50     10064043.50
      2702780.73     10063688.28      2702895.84     10063417.20
      2703243.33     10063283.38      2703530.15     10063077.37
      2703753.67     10063100.65      2703928.39     10063003.25
      2704264.10     10062486.96      2704088.47     10062273.73
      2704104.12     10062162.53      2704377.84     10062073.61
      2704426.08     10062128.61      2704638.08     10062122.76
      2704728.27     10062038.75      2704867.50     10061543.24
      2704792.87     10061261.26      2705079.14     10061084.62
      2705351.67     10061380.32      2705508.47     10061023.73

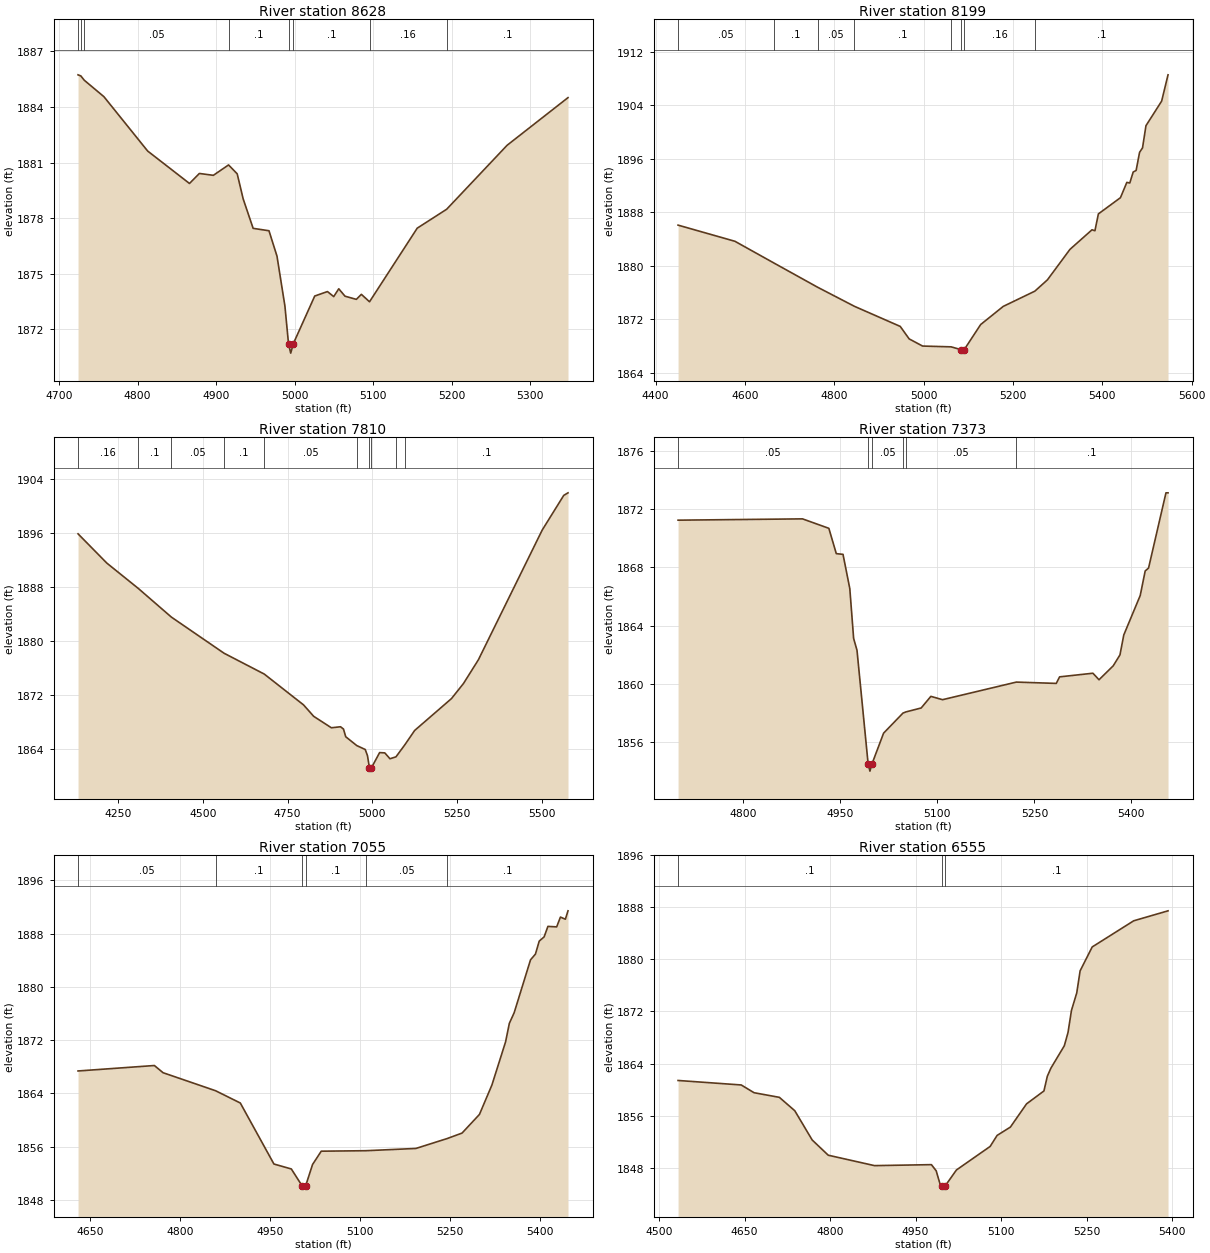
Type RM Length L Ch R = 1,8628,429,429,429
BEGIN DESCRIPTION:
UNT 0082 IN HEWA 14.0
END DESCRIPTION:
XS GIS Cut Line= 3
      2700818.47     10065703.76      2700768.47     10065403.73
      2700568.48     10065153.75
#Sta/Elev= 30
  4724.1 1885.73  4727.7 1885.67  4732.0 1885.44  4757.1 1884.55  4812.8 1881.62
  4866.1 1879.87  4878.7 1880.41  4896.5 1880.31  4915.9 1880.87  4926.9 1880.39
  4934.5 1879.04  4947.2 1877.45  4967.4 1877.32  4977.6 1875.95  4987.7 1873.26
  4992.3 1871.22  4995.1 1870.72  4998.3 1871.22  5025.7 1873.80  5041.9 1874.04
  5049.9 1873.77  5056.3 1874.19  5064.3 1873.79  5078.7 1873.62  5085.1 1873.89
  5095.5 1873.49  5156.3 1877.46  5193.8 1878.48  5270.8 1881.93  5348.4 1884.50
#Mann=8,-1,0
  4724.1    0.05       0  4727.7     0.1       0  4732.0    0.05       0
  4915.9     0.1       0  4992.3    0.07       0  4998.3     0.1       0
  5095.5    0.16       0  5193.8     0.1       0
Bank Sta=4992.3,4998.3
Exp/Cntr=0.3,0.1

Type RM Length L Ch R = 1,8199,389,389,389
BEGIN DESCRIPTION:
UNT 0082 IN HEWA 13.0
END DESCRIPTION:
XS GIS Cut Line= 3
      2701163.40     10065831.02      2701157.35     10065123.66
      2700903.99     10064828.07
#Sta/Elev= 30
  4450.4 1886.08  4577.7 1883.66  4664.6 1880.42  4763.0 1876.77  4845.2 1873.92
  4947.7 1870.91  4967.7 1869.04  4997.7 1867.97  5061.6 1867.85  5084.7 1867.41
  5087.5 1866.91  5090.7 1867.41  5127.7 1871.19  5178.3 1873.91  5249.0 1876.19
  5277.1 1877.88  5327.6 1882.45  5376.9 1885.38  5383.5 1885.24  5391.2 1887.76
  5440.6 1890.19  5454.9 1892.48  5461.5 1892.39  5469.1 1894.03  5475.7 1894.27
  5483.4 1896.98  5490.0 1897.65  5497.7 1900.97  5532.8 1904.65  5547.1 1908.59
#Mann=8,-1,0
  4450.4    0.05       0  4664.6     0.1       0  4763.0    0.05       0
  4845.2     0.1       0  5061.6    0.16       0  5084.7    0.07       0
  5090.7    0.16       0  5249.0     0.1       0
Bank Sta=5084.7,5090.7
Exp/Cntr=0.3,0.1

Type RM Length L Ch R = 1,7810,437,437,437
BEGIN DESCRIPTION:
UNT 0082 IN HEWA 12.0
END DESCRIPTION:
XS GIS Cut Line= 3
      2701562.40     10066048.68      2701604.73     10065317.12
      2701223.86     10064712.57
#Sta/Elev= 30
  4131.0 1895.89  4216.1 1891.54  4309.2 1887.77  4406.7 1883.52  4562.4 1878.15
  4681.0 1875.06  4797.1 1870.48  4827.1 1868.78  4879.3 1867.08  4906.4 1867.23
  4915.1 1866.89  4921.7 1865.75  4954.2 1864.44  4979.4 1863.85  4986.0 1862.93
  4991.7 1861.14  4994.4 1860.64  4997.7 1861.14  5021.8 1863.39  5037.1 1863.35
  5052.4 1862.48  5070.1 1862.76  5096.9 1864.59  5125.3 1866.68  5234.2 1871.42
  5269.6 1873.66  5313.7 1877.19  5502.1 1896.45  5565.7 1901.60  5578.3 1901.98
#Mann=10,-1,0
  4131.0    0.16       0  4309.2     0.1       0  4406.7    0.05       0
  4562.4     0.1       0  4681.0    0.05       0  4954.2     0.1       0
  4991.7    0.07       0  4997.7     0.1       0  5070.1    0.05       0
  5096.9     0.1       0
Bank Sta=4991.7,4997.7
Exp/Cntr=0.3,0.1

Type RM Length L Ch R = 1,7373,318,318,318
BEGIN DESCRIPTION:
UNT 0082 IN HEWA 11.0
END DESCRIPTION:
XS GIS Cut Line= 2
      2701991.64     10065438.02      2701774.00     10064712.57
#Sta/Elev= 30
  4699.2 1871.25  4891.6 1871.34  4932.3 1870.69  4943.8 1868.95  4954.2 1868.90
  4964.7 1866.54  4970.6 1863.12  4975.8 1862.31  4993.0 1854.50  4995.8 1854.00
  4999.0 1854.50  5016.9 1856.61  5046.9 1857.99  5051.4 1858.07  5075.0 1858.34
  5090.0 1859.14  5108.0 1858.91  5222.1 1860.12  5283.8 1860.03  5289.0 1860.48
  5340.5 1860.73  5349.9 1860.28  5371.9 1861.24  5382.3 1861.99  5388.2 1863.36
  5413.6 1866.07  5421.3 1867.76  5426.5 1867.96  5453.4 1873.13  5456.6 1873.13
#Mann=6,-1,0
  4699.2    0.05       0  4993.0    0.04       0  4999.0    0.05       0
  5046.9     0.1       0  5051.4    0.05       0  5222.1     0.1       0
Bank Sta=4993,4999
Exp/Cntr=0.3,0.1

Type RM Length L Ch R = 1,7055,500,500,500
BEGIN DESCRIPTION:
UNT 0082 IN HEWA 10.0
END DESCRIPTION:
XS GIS Cut Line= 2
      2702329.98     10065200.96      2701832.89     10064552.46
#Sta/Elev= 30
  4630.4 1867.38  4757.7 1868.20  4772.2 1867.12  4859.8 1864.41  4901.0 1862.57
  4957.1 1853.40  4986.1 1852.66  5004.0 1850.13  5006.7 1849.63  5010.0 1850.13
  5021.5 1853.33  5036.0 1855.33  5110.0 1855.40  5193.8 1855.74  5245.7 1857.22
  5270.8 1858.05  5299.8 1860.85  5320.6 1865.27  5343.4 1871.76  5349.7 1874.54
  5357.7 1876.13  5385.0 1884.08  5393.2 1884.94  5399.5 1886.89  5407.7 1887.53
  5414.0 1889.10  5428.6 1889.03  5434.9 1890.50  5443.1 1890.18  5447.5 1891.44
#Mann=6,-1,0
  4630.4    0.05       0  4859.8     0.1       0  5004.0    0.07       0
  5010.0     0.1       0  5110.0    0.05       0  5245.7     0.1       0
Bank Sta=5004,5010
Exp/Cntr=0.3,0.1

Type RM Length L Ch R = 1,6555,529,529,529
BEGIN DESCRIPTION:
UNT 0082 IN HEWA 9.0
END DESCRIPTION:
XS GIS Cut Line= 2
      2702630.25     10064946.41      2702169.84     10064220.04
#Sta/Elev= 30
  4533.1 1861.40  4644.0 1860.71  4666.5 1859.52  4710.9 1858.81  4738.0 1856.75
  4768.5 1852.26  4796.7 1849.92  4877.9 1848.32  4977.8 1848.47  4986.2 1847.52
  4993.1 1845.44  4996.0 1845.21  4998.8 1844.71  5002.0 1845.21  5021.7 1847.65
  5080.9 1851.27  5093.1 1852.96  5116.4 1854.24  5144.8 1857.81  5175.3 1859.79
  5181.2 1862.04  5187.5 1863.29  5211.1 1866.74  5217.6 1868.79  5223.6 1872.16
  5232.9 1874.86  5238.8 1878.24  5260.0 1881.91  5332.9 1885.93  5393.1 1887.46
#Mann=3,-1,0
  4533.1     0.1       0  4996.0    0.07       0  5002.0     0.1       0
Bank Sta=4996,5002
Exp/Cntr=0.3,0.1

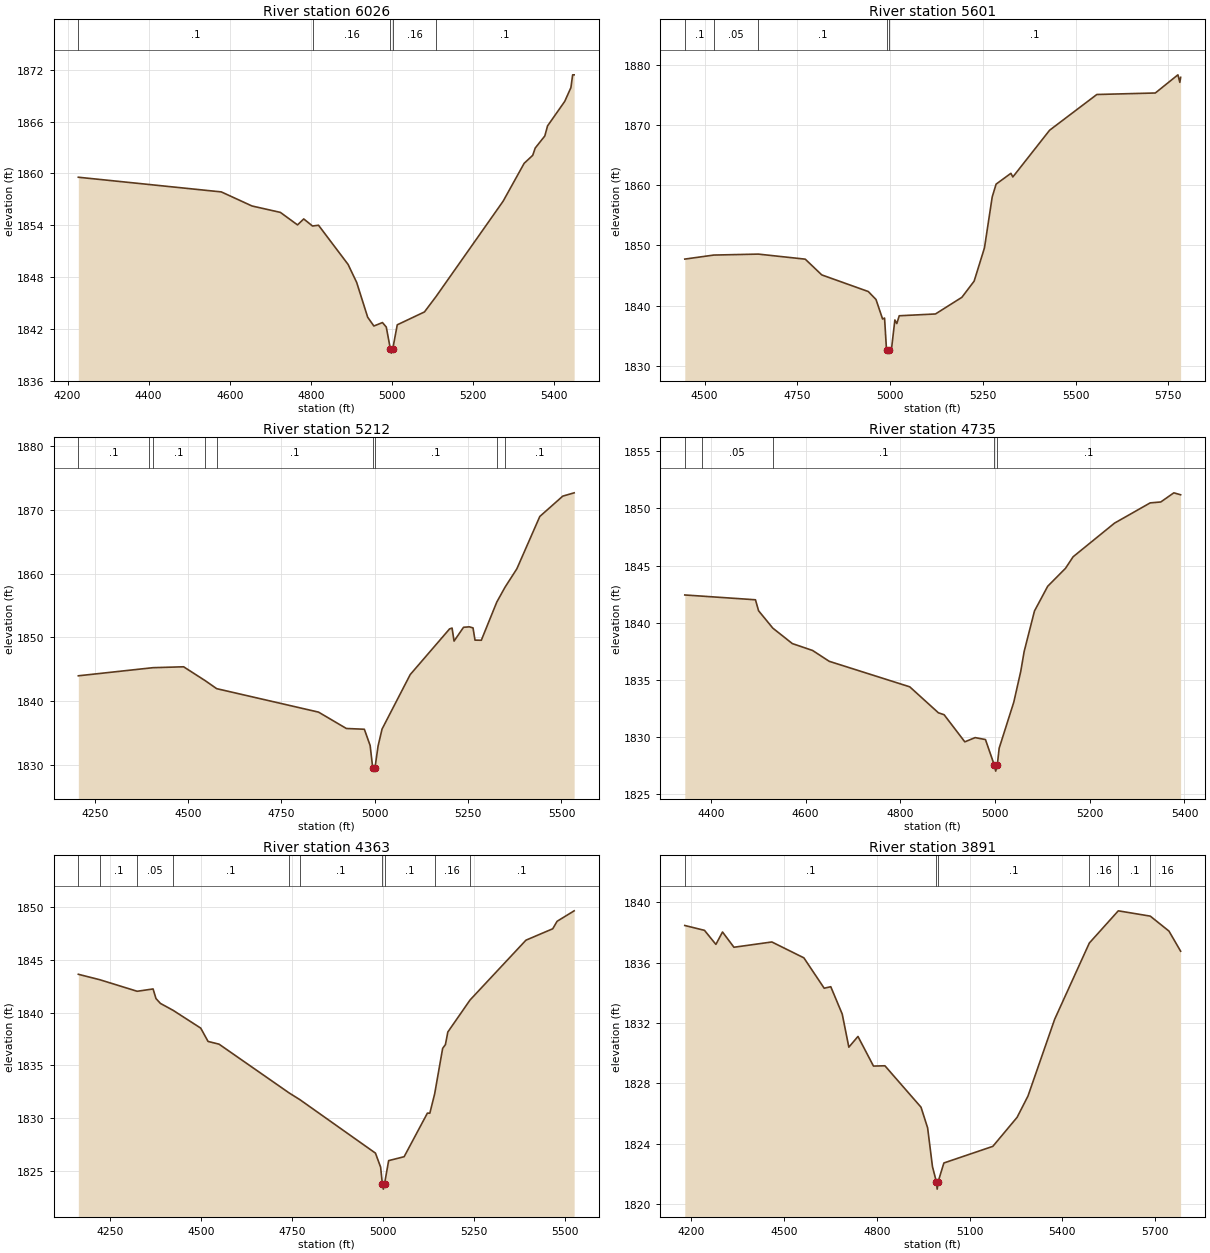
Type RM Length L Ch R = 1,6026,425,425,425
BEGIN DESCRIPTION:
UNT 0082 IN HEWA 8.0
END DESCRIPTION:
XS GIS Cut Line= 3
      2703024.93     10064946.46      2703039.23     10064517.43
      2702367.17     10064094.18
#Sta/Elev= 30
  4226.5 1859.56  4579.4 1857.86  4655.1 1856.23  4725.0 1855.49  4767.4 1854.04
  4782.7 1854.73  4804.4 1853.91  4819.2 1854.00  4892.2 1849.46  4913.4 1847.37
  4940.5 1843.35  4955.8 1842.33  4977.0 1842.73  4986.4 1842.21  4996.4 1839.69
  4999.1 1839.19  5002.4 1839.69  5013.5 1842.47  5080.6 1843.96  5109.3 1845.75
  5274.8 1856.79  5326.6 1861.17  5347.8 1862.10  5353.9 1862.94  5377.6 1864.34
  5384.3 1865.50  5426.7 1868.34  5442.0 1869.94  5446.3 1871.42  5450.0 1871.42
#Mann=5,-1,0
  4226.5     0.1       0  4804.4    0.16       0  4996.4    0.07       0
  5002.4    0.16       0  5109.3     0.1       0
Bank Sta=4996.4,5002.4
Exp/Cntr=0.3,0.1

Type RM Length L Ch R = 1,5601,389,389,389
BEGIN DESCRIPTION:
UNT 0082 IN HEWA 7.0
END DESCRIPTION:
XS GIS Cut Line= 2
      2703452.06     10064142.95      2702172.12     10063757.92
#Sta/Elev= 30
  4446.6 1847.72  4524.7 1848.39  4644.7 1848.55  4771.3 1847.71  4815.9 1845.09
  4941.2 1842.33  4962.0 1841.01  4979.8 1837.76  4985.1 1837.92  4990.4 1832.59
  4993.1 1832.09  4996.4 1832.59  5003.8 1832.77  5012.9 1837.60  5018.1 1837.00
  5024.7 1838.30  5122.4 1838.60  5193.6 1841.37  5226.6 1844.06  5254.4 1849.58
  5275.3 1858.05  5285.8 1860.18  5325.7 1861.98  5330.9 1861.37  5430.0 1869.14
  5557.3 1875.08  5715.0 1875.33  5775.9 1878.35  5781.1 1877.10  5783.2 1877.93
#Mann=5,-1,0
  4446.6     0.1       0  4524.7    0.05       0  4644.7     0.1       0
  4990.4    0.07       0  4996.4     0.1       0
Bank Sta=4990.4,4996.4
Exp/Cntr=0.3,0.1

Type RM Length L Ch R = 1,5212,477,477,477
BEGIN DESCRIPTION:
UNT 0082 IN HEWA 6.0
END DESCRIPTION:
XS GIS Cut Line= 2
      2703553.62     10063908.57      2702304.57     10063458.39
#Sta/Elev= 30
  4206.2 1844.00  4394.9 1845.20  4406.4 1845.27  4488.1 1845.41  4546.2 1843.23
  4576.6 1841.99  4849.4 1838.32  4923.9 1835.76  4972.1 1835.64  4987.6 1833.10
  4994.5 1829.59  4997.2 1829.09  5000.5 1829.59  5008.9 1833.03  5019.5 1835.67
  5094.9 1844.19  5200.2 1851.33  5207.0 1851.47  5212.3 1849.43  5237.7 1851.59
  5253.4 1851.66  5263.1 1851.49  5268.4 1849.58  5285.3 1849.56  5326.7 1855.53
  5348.8 1857.86  5380.5 1860.74  5441.9 1868.92  5503.3 1872.10  5533.9 1872.62
#Mann=9,-1,0
  4206.2     0.1       0  4394.9    0.05       0  4406.4     0.1       0
  4546.2    0.16       0  4576.6     0.1       0  4994.5    0.07       0
  5000.5     0.1       0  5326.7    0.05       0  5348.8     0.1       0
Bank Sta=4994.5,5000.5
Exp/Cntr=0.3,0.1

Type RM Length L Ch R = 1,4735,372,372,372
BEGIN DESCRIPTION:
UNT 0082 IN HEWA 5.0
END DESCRIPTION:
XS GIS Cut Line= 3
      2703565.86     10063776.74      2703160.89     10063426.37
      2702915.95     10062977.33
#Sta/Elev= 30
  4344.9 1842.43  4380.7 1842.33  4494.1 1842.01  4500.7 1841.05  4530.8 1839.53
  4572.0 1838.18  4614.7 1837.58  4649.9 1836.63  4819.9 1834.40  4880.4 1832.13
  4892.5 1831.96  4936.2 1829.59  4958.0 1829.96  4979.8 1829.79  4998.7 1827.53
  5001.4 1827.03  5004.7 1827.53  5008.7 1829.03  5039.6 1833.06  5054.3 1835.75
  5061.5 1837.49  5083.3 1841.03  5111.2 1843.19  5148.8 1844.76  5164.9 1845.77
  5252.3 1848.71  5327.6 1850.48  5350.0 1850.56  5377.6 1851.36  5391.9 1851.19
#Mann=5,-1,0
  4344.9     0.1       0  4380.7    0.05       0  4530.8     0.1       0
  4998.7    0.07       0  5004.7     0.1       0
Bank Sta=4998.7,5004.7
Exp/Cntr=0.3,0.1

Type RM Length L Ch R = 1,4363,472,472,472
BEGIN DESCRIPTION:
UNT 0082 IN HEWA 4.0
END DESCRIPTION:
XS GIS Cut Line= 4
      2703611.38     10063917.86      2703661.44     10063430.92
      2703251.90     10062953.12      2703012.08     10062921.45
#Sta/Elev= 30
  4163.9 1843.63  4223.2 1843.11  4325.4 1842.02  4369.1 1842.24  4377.0 1841.33
  4389.2 1840.87  4423.8 1840.22  4499.8 1838.53  4519.9 1837.27  4550.1 1837.01
  4743.3 1832.37  4771.7 1831.76  4979.3 1826.69  4993.5 1825.36  4998.2 1823.78
  5001.0 1823.28  5004.2 1823.78  5015.5 1825.98  5058.0 1826.35  5121.9 1830.48
  5128.5 1830.47  5141.7 1832.29  5163.7 1836.61  5171.3 1836.97  5177.9 1838.16
  5238.8 1841.19  5392.3 1846.86  5465.8 1847.94  5477.8 1848.65  5524.6 1849.64
#Mann=10,-1,0
  4163.9    0.05       0  4223.2     0.1       0  4325.4    0.05       0
  4423.8     0.1       0  4743.3    0.16       0  4771.7     0.1       0
  4998.2    0.07       0  5004.2     0.1       0  5141.7    0.16       0
  5238.8     0.1       0
Bank Sta=4998.2,5004.2
Exp/Cntr=0.3,0.1

Type RM Length L Ch R = 1,3891,431,431,431
BEGIN DESCRIPTION:
UNT 0082 IN HEWA 3.0
END DESCRIPTION:
XS GIS Cut Line= 3
      2704275.73     10063753.98      2703779.75     10062925.82
      2703283.74     10062525.38
#Sta/Elev= 30
  4179.3 1838.45  4242.9 1838.13  4279.8 1837.20  4301.2 1838.02  4338.2 1837.01
  4460.7 1837.36  4564.2 1836.31  4629.9 1834.30  4651.2 1834.40  4688.2 1832.59
  4709.6 1830.40  4739.1 1831.11  4789.3 1829.15  4826.2 1829.17  4942.9 1826.43
  4964.3 1825.06  4979.9 1822.50  4992.4 1821.51  4995.2 1821.01  4998.4 1821.51
  5016.8 1822.74  5175.1 1823.84  5253.5 1825.76  5288.7 1827.17  5375.0 1832.25
  5487.0 1837.29  5580.6 1839.42  5683.9 1839.07  5744.4 1838.08  5782.1 1836.75
#Mann=6,-1,0
  4179.3     0.1       0  4992.4    0.07       0  4998.4     0.1       0
  5487.0    0.16       0  5580.6     0.1       0  5683.9    0.16       0
Bank Sta=4992.4,4998.4
Exp/Cntr=0.3,0.1

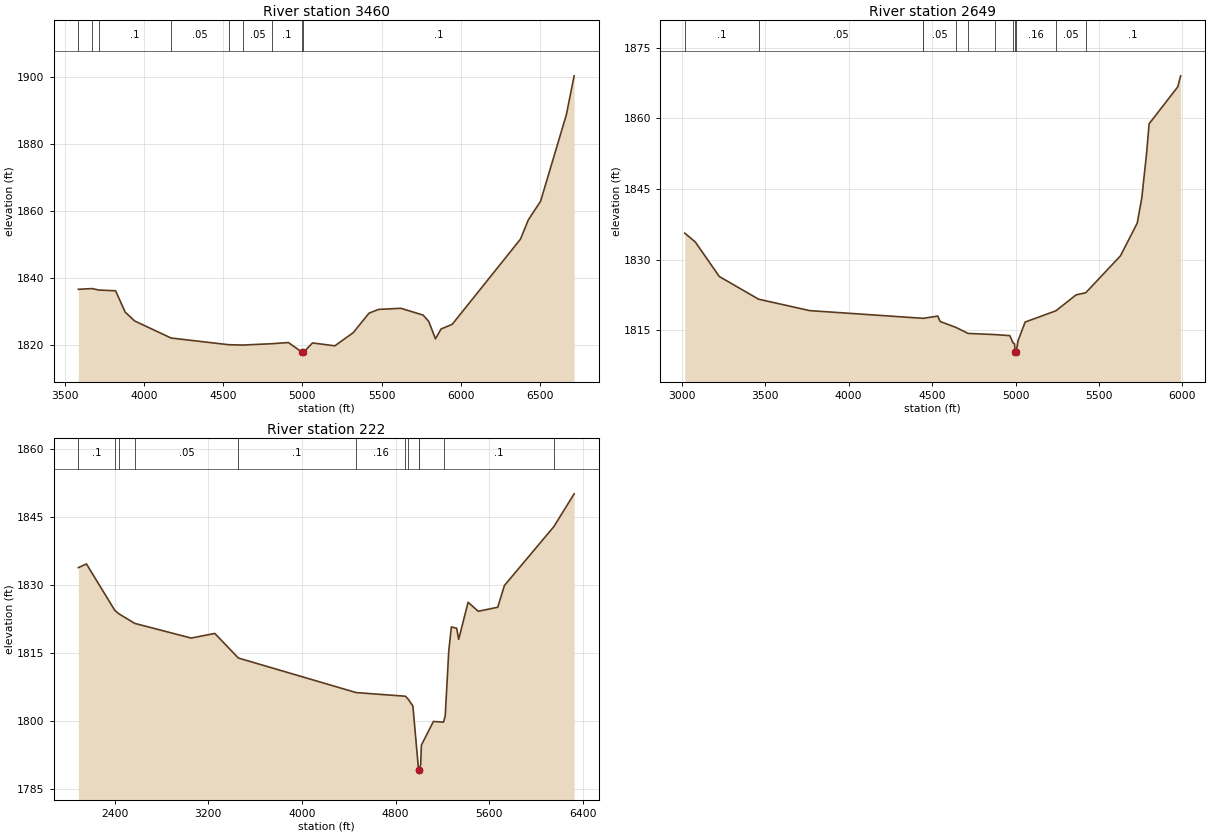
Type RM Length L Ch R = 1,3460,811,811,811
BEGIN DESCRIPTION:
Mapping XS fa07d726
END DESCRIPTION:
XS GIS Cut Line= 4
      2704408.40     10063949.53      2704399.78     10062832.89
      2703722.93     10062582.84      2702814.76     10061657.46
#Sta/Elev= 30
  3583.2 1836.61  3670.9 1836.83  3712.6 1836.39  3819.0 1836.17  3879.0 1829.83
  3939.0 1827.17  4169.3 1822.07  4533.5 1820.07  4624.2 1819.97  4807.2 1820.37
  4911.5 1820.72  4999.8 1817.76  5002.5 1817.26  5005.8 1817.76  5063.7 1820.60
  5205.0 1819.74  5321.4 1823.67  5421.1 1829.49  5480.5 1830.60  5621.9 1830.95
  5763.4 1828.91  5798.7 1827.02  5841.1 1821.83  5876.5 1824.76  5947.3 1826.17
  6378.6 1851.59  6428.2 1857.33  6505.9 1862.92  6668.5 1888.69  6718.0 1900.34
#Mann=9,-1,0
  3583.2     0.1       0  3670.9    0.05       0  3712.6     0.1       0
  4169.3    0.05       0  4533.5     0.1       0  4624.2    0.05       0
  4807.2     0.1       0  4999.8    0.07       0  5005.8     0.1       0
Bank Sta=4999.8,5005.8
Exp/Cntr=0.3,0.1

Type RM Length L Ch R = 1,2649,2427,2427,2427
BEGIN DESCRIPTION:
Mapping XS 2ee696c1
END DESCRIPTION:
XS GIS Cut Line= 4
      2704456.17     10063875.81      2704716.58     10062631.03
      2704065.54     10061969.57      2703612.95     10061345.31
#Sta/Elev= 30
  3018.4 1835.61  3081.8 1833.72  3224.9 1826.41  3460.2 1821.59  3766.3 1819.16
  4444.1 1817.53  4446.1 1817.52  4534.4 1818.00  4548.5 1816.85  4643.5 1815.59
  4715.5 1814.32  4876.7 1814.07  4965.7 1813.85  4984.9 1812.32  4994.0 1812.11
  4998.1 1810.42  5000.9 1809.92  5004.1 1810.42  5015.3 1812.78  5057.7 1816.73
  5242.0 1819.12  5362.8 1822.50  5420.6 1822.95  5628.8 1830.79  5729.3 1837.74
  5756.6 1843.08  5785.7 1852.69  5800.4 1858.82  5972.1 1866.68  5989.3 1869.02
#Mann=12,-1,0
  3018.4     0.1       0  3460.2    0.05       0  4444.1     0.1       0
  4446.1    0.05       0  4643.5     0.1       0  4715.5    0.16       0
  4876.7     0.1       0  4984.9    0.16       0  4998.1    0.07       0
  5004.1    0.16       0  5242.0    0.05       0  5420.6     0.1       0
Bank Sta=4998.1,5004.1
Exp/Cntr=0.3,0.1

Type RM Length L Ch R = 1,222,0,0,0
BEGIN DESCRIPTION:
UNT 0082 IN HEWA 2.0
END DESCRIPTION:
XS GIS Cut Line= 4
      2704477.00     10063948.74      2705471.79     10061271.65
      2705341.58     10061073.74      2704305.16     10060599.80
#Sta/Elev= 30
  2091.0 1833.77  2160.4 1834.58  2402.1 1824.37  2436.9 1823.60  2571.7 1821.49
  3054.1 1818.25  3255.9 1819.27  3457.2 1813.85  4462.0 1806.24  4883.6 1805.43
  4908.3 1804.74  4946.9 1803.27  4995.4 1789.21  4998.2 1788.71  5001.4 1789.21
  5013.5 1790.40  5019.5 1794.66  5121.9 1799.87  5208.5 1799.73  5222.9 1801.13
  5253.3 1815.46  5275.3 1820.70  5320.4 1820.42  5337.9 1817.98  5418.2 1826.14
  5504.6 1824.15  5671.1 1825.04  5728.2 1829.83  6151.0 1842.83  6323.5 1850.03
#Mann=12,-1,0
  2091.0     0.1       0  2402.1    0.05       0  2436.9     0.1       0
  2571.7    0.05       0  3457.2     0.1       0  4462.0    0.16       0
  4883.6     0.1       0  4908.3    0.16       0  4995.4    0.07       0
  5001.4    0.16       0  5208.5     0.1       0  6151.0    0.05       0
Bank Sta=4995.4,5001.4
Exp/Cntr=0.3,0.1

Chan Stop Cuts=-1