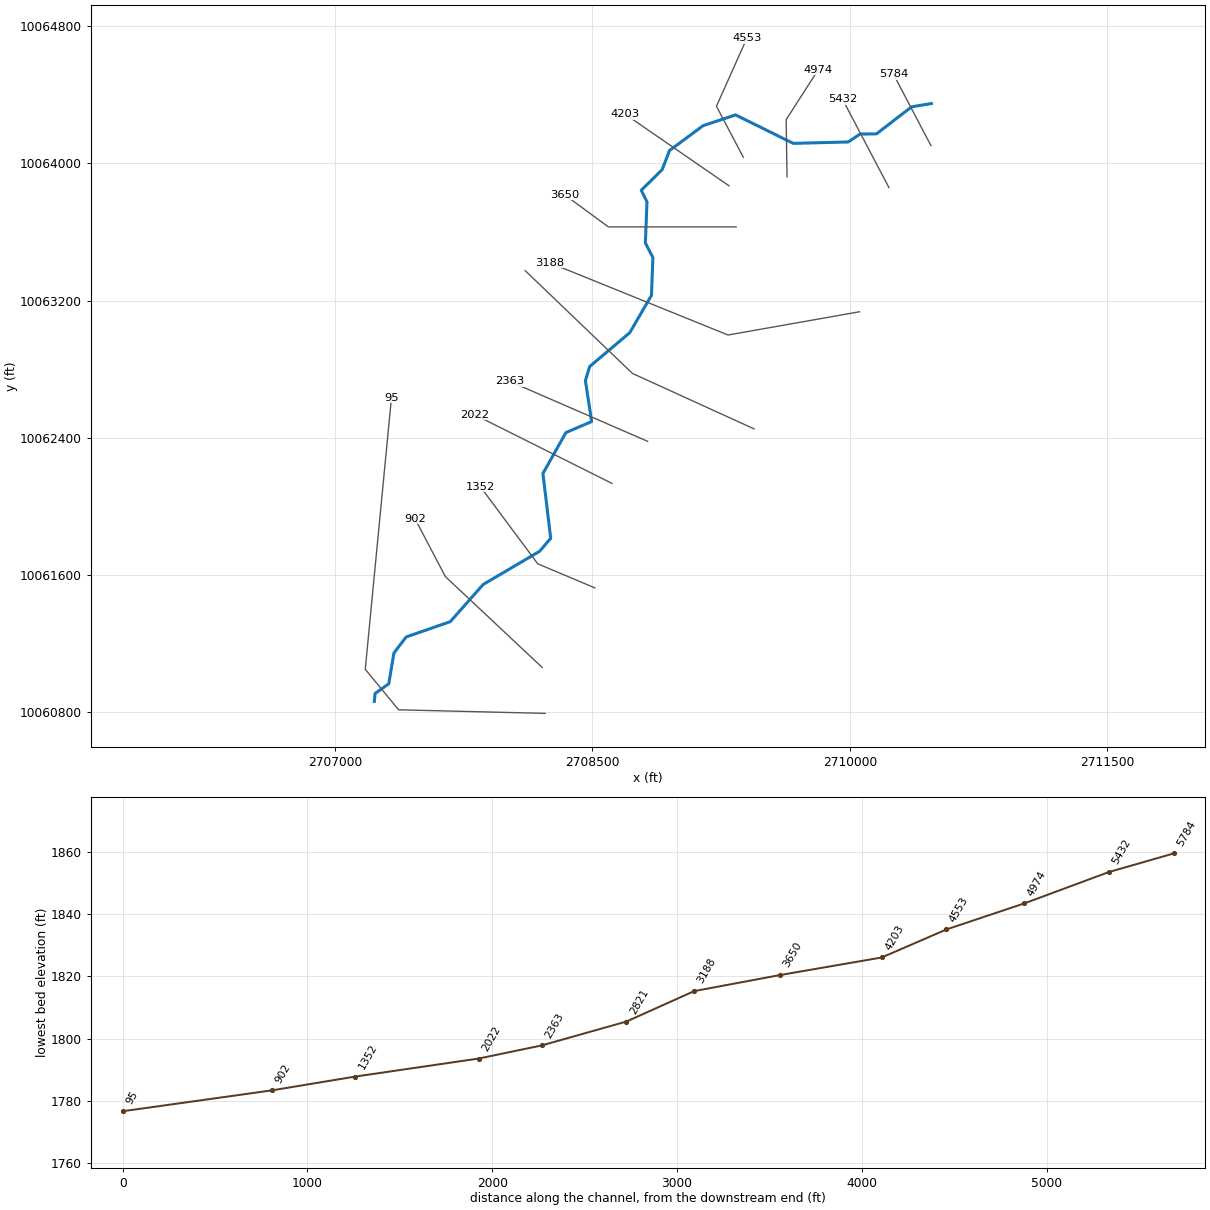
--- UNT 0083 IN HEWA.prj (project) ---

Proj Title=UNT 0083 IN HEWA Base Level Engineering
Current Plan=p01
Default Exp/Contr=0.3,0.1
English Units
Geom File=g01
Flow File=f01
Plan File=p01
BEGIN DESCRIPTION:
UNT 0083 IN HEWA
END DESCRIPTION:

--- UNT 0083 IN HEWA.p01 (plan) ---

Plan Title=Multiple Run
Short Identifier=Multiple
Geom File=g01
Flow File=f01
Subcritical Flow
K Sum by GR= 0
Std Step Tol= 0.01
Critical Tol= 0.01
Num of Std Step Trials= 20
Max Error Tol= 0.3
Flow Tol Ratio= 0.001
Split Flow NTrial= 30
Split Flow Tol= 0.02
Split Flow Ratio= 0.02
Log Output Level= 0
Friction Slope Method= 1
Unsteady Friction Slope Method= 2
Unsteady Bridges Friction Slope Method= 1
Parabolic Critical Depth
Global Vel Dist=  1 , 1 , 1
Global Log Level= 0
CheckData=True
Encroach Param= -1, 0, 0, 0
BEGIN DESCRIPTION:
Multiple Run
END DESCRIPTION:

--- UNT 0083 IN HEWA.f01 (steady flow) ---

Flow Title=Multiple
Number of Profiles=7
Profile Names=10-year,25-year,50-year,1pct_min,100-year,1pct_plu,500-year
River Rch & RM= UNT 0083 IN HEWA,Reach-1,5784
    1521    2266    2926    2753    3723    5035    6030
River Rch & RM= UNT 0083 IN HEWA,Reach-1,4203
    1893    2849    3702    3503    4737    6406    7758
Boundary for River Rch & Prof#=UNT 0083 IN HEWA,Reach-1,1
Up Type=0
Dn Type=3
Dn Slope=0.005
Boundary for River Rch & Prof#=UNT 0083 IN HEWA,Reach-1,2
Up Type=0
Dn Type=3
Dn Slope=0.005
Boundary for River Rch & Prof#=UNT 0083 IN HEWA,Reach-1,3
Up Type=0
Dn Type=3
Dn Slope=0.005
Boundary for River Rch & Prof#=UNT 0083 IN HEWA,Reach-1,4
Up Type=0
Dn Type=3
Dn Slope=0.005
Boundary for River Rch & Prof#=UNT 0083 IN HEWA,Reach-1,5
Up Type=0
Dn Type=3
Dn Slope=0.005
Boundary for River Rch & Prof#=UNT 0083 IN HEWA,Reach-1,6
Up Type=0
Dn Type=3
Dn Slope=0.005
Boundary for River Rch & Prof#=UNT 0083 IN HEWA,Reach-1,7
Up Type=0
Dn Type=3
Dn Slope=0.005

--- UNT 0083 IN HEWA.g01 (geometry) ---

Geom Title=Existing Conditions

River Reach=UNT 0083 IN HEWA,Reach-1
Reach XY= 30
      2710474.85     10064348.50      2710359.89     10064329.52
      2710154.98     10064171.74      2710059.68     10064170.76
      2709990.10     10064124.65      2709669.65     10064116.45
      2709334.24     10064282.33      2709145.34     10064219.99
      2708948.91     10064074.63      2708905.85     10063963.07
      2708784.28     10063843.12      2708817.65     10063774.94
      2708808.27     10063536.13      2708851.91     10063451.12
      2708843.92     10063230.92      2708717.46     10063013.24
      2708483.82     10062816.00      2708458.72     10062733.68
      2708495.14     10062494.99      2708345.15     10062430.80
      2708211.17     10062192.41      2708256.46     10061814.57
      2708191.34     10061738.58      2707862.80     10061545.49
      2707671.10     10061328.77      2707414.23     10061239.70
      2707342.96     10061146.59      2707312.43     10060966.50
      2707232.84     10060910.22      2707228.47     10060863.73

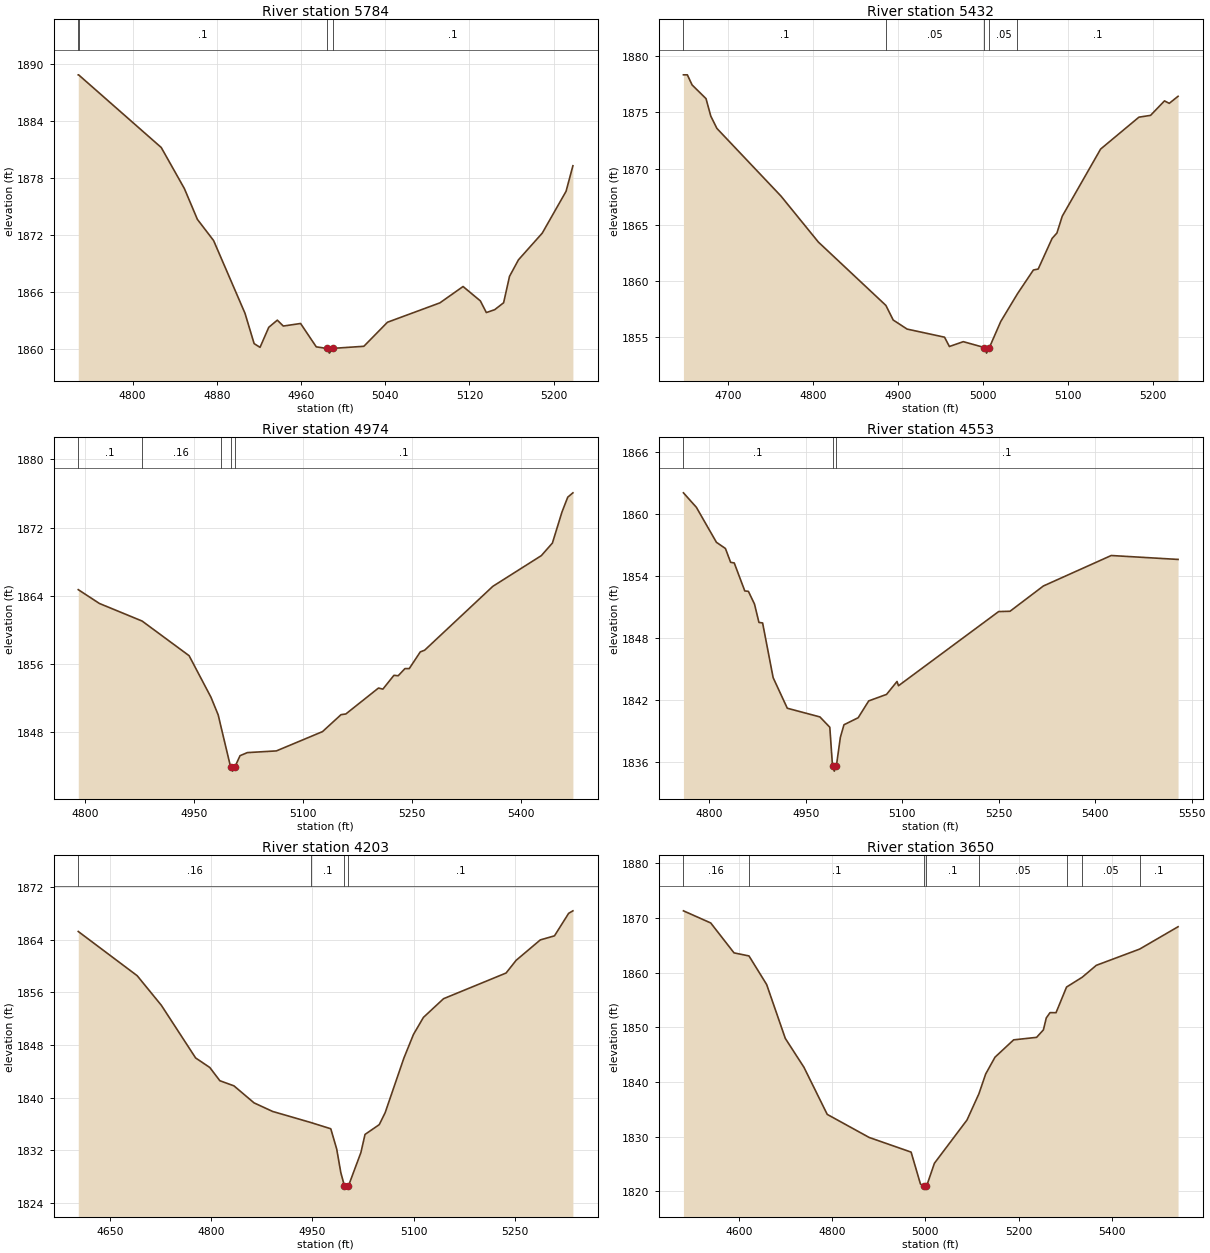
Type RM Length L Ch R = 1,5784,352,352,352
BEGIN DESCRIPTION:
UNT 0083 IN HEWA 13.0
END DESCRIPTION:
XS GIS Cut Line= 2
      2710472.51     10064103.61      2710254.17     10064519.48
#Sta/Elev= 30
  4748.5 1888.86  4748.8 1888.86  4827.3 1881.21  4849.3 1876.88  4861.6 1873.65
  4877.0 1871.42  4906.8 1863.77  4915.5 1860.57  4921.1 1860.18  4929.4 1862.29
  4937.5 1863.04  4943.2 1862.42  4959.6 1862.69  4974.5 1860.23  4984.3 1860.07
  4987.0 1859.57  4990.3 1860.07  5019.7 1860.29  5042.1 1862.82  5091.9 1864.86
  5113.9 1866.58  5130.3 1865.07  5136.0 1863.84  5143.9 1864.14  5152.4 1864.87
  5158.0 1867.65  5166.5 1869.39  5189.1 1872.20  5211.7 1876.60  5218.2 1879.29
#Mann=4,-1,0
  4748.5    0.16       0  4748.8     0.1       0  4984.3    0.07       0
  4990.3     0.1       0
Bank Sta=4984.3,4990.3
Exp/Cntr=0.3,0.1

Type RM Length L Ch R = 1,5432,458,458,458
BEGIN DESCRIPTION:
UNT 0083 IN HEWA 12.0
END DESCRIPTION:
XS GIS Cut Line= 2
      2710227.71     10063858.82      2709956.84     10064374.51
#Sta/Elev= 30
  4647.3 1878.35  4651.9 1878.35  4657.5 1877.45  4673.9 1876.23  4679.5 1874.68
  4686.7 1873.58  4762.1 1867.56  4806.2 1863.46  4885.7 1857.82  4894.3 1856.52
  4910.7 1855.71  4954.8 1854.99  4960.5 1854.16  4976.9 1854.59  5001.6 1854.07
  5004.3 1853.57  5007.6 1854.07  5021.0 1856.39  5040.7 1858.86  5059.4 1860.97
  5065.1 1861.06  5081.5 1863.79  5087.1 1864.26  5093.4 1865.76  5138.6 1871.74
  5183.7 1874.58  5197.4 1874.74  5213.8 1876.03  5219.4 1875.81  5229.8 1876.44
#Mann=5,-1,0
  4647.3     0.1       0  4885.7    0.05       0  5001.6   0.035       0
  5007.6    0.05       0  5040.7     0.1       0
Bank Sta=5001.6,5007.6
Exp/Cntr=0.3,0.1

Type RM Length L Ch R = 1,4974,421,421,421
BEGIN DESCRIPTION:
UNT 0083 IN HEWA 11.0
END DESCRIPTION:
XS GIS Cut Line= 3
      2709633.95     10063921.32      2709628.74     10064254.68
      2709816.22     10064546.31
#Sta/Elev= 30
  4791.0 1864.74  4820.1 1863.12  4878.8 1861.06  4943.4 1857.00  4973.4 1852.14
  4983.4 1850.06  4986.6 1848.90  5000.4 1843.97  5003.2 1843.47  5006.4 1843.97
  5013.4 1845.28  5023.4 1845.64  5063.4 1845.84  5126.8 1848.10  5152.3 1850.09
  5158.9 1850.17  5203.8 1853.21  5209.8 1853.08  5225.0 1854.70  5230.9 1854.65
  5240.2 1855.49  5246.1 1855.49  5261.3 1857.45  5267.2 1857.64  5361.0 1865.13
  5427.7 1868.73  5442.9 1870.20  5456.1 1873.85  5464.0 1875.58  5471.1 1876.09
#Mann=5,-1,0
  4791.0     0.1       0  4878.8    0.16       0  4986.6     0.1       0
  5000.4    0.07       0  5006.4     0.1       0
Bank Sta=5000.4,5006.4
Exp/Cntr=0.3,0.1

Type RM Length L Ch R = 1,4553,350,350,350
BEGIN DESCRIPTION:
UNT 0083 IN HEWA 10.0
END DESCRIPTION:
XS GIS Cut Line= 3
      2709378.74     10064035.92      2709222.49     10064332.80
      2709399.56     10064728.61
#Sta/Elev= 30
  4759.8 1862.05  4779.9 1860.65  4811.1 1857.26  4825.1 1856.66  4833.2 1855.32
  4838.8 1855.26  4855.2 1852.55  4860.8 1852.51  4870.3 1851.28  4877.2 1849.50
  4882.9 1849.45  4899.3 1844.15  4921.3 1841.19  4972.0 1840.35  4987.4 1839.35
  4991.6 1835.60  4994.4 1835.10  4997.6 1835.60  5003.8 1838.37  5009.4 1839.59
  5031.5 1840.27  5047.9 1841.90  5075.6 1842.53  5091.9 1843.78  5094.2 1843.37
  5249.9 1850.55  5267.6 1850.58  5319.5 1853.03  5425.0 1855.98  5528.9 1855.60
#Mann=3,-1,0
  4759.8     0.1       0  4991.6    0.07       0  4997.6     0.1       0
Bank Sta=4991.6,4997.6
Exp/Cntr=0.3,0.1

Type RM Length L Ch R = 1,4203,553,553,553
BEGIN DESCRIPTION:
UNT 0083 IN HEWA 9.0
END DESCRIPTION:
XS GIS Cut Line= 2
      2709295.44     10063869.24      2708692.35     10064285.16
#Sta/Elev= 30
  4603.3 1865.22  4690.6 1858.50  4726.4 1854.00  4777.1 1846.01  4798.1 1844.56
  4813.0 1842.55  4833.9 1841.77  4863.7 1839.18  4891.2 1837.88  4947.4 1836.21
  4977.3 1835.25  4986.1 1832.15  4992.2 1828.57  4997.5 1826.58  5000.2 1826.08
  5003.5 1826.58  5021.9 1831.64  5028.0 1834.39  5049.1 1835.88  5057.8 1837.69
  5085.5 1845.97  5099.7 1849.57  5114.5 1852.17  5144.3 1855.01  5236.9 1858.91
  5251.8 1860.84  5287.6 1863.94  5308.6 1864.56  5329.6 1867.98  5335.9 1868.36
#Mann=4,-1,0
  4603.3    0.16       0  4947.4     0.1       0  4997.5    0.07       0
  5003.5     0.1       0
Bank Sta=4997.5,5003.5
Exp/Cntr=0.3,0.1

Type RM Length L Ch R = 1,3650,462,462,462
BEGIN DESCRIPTION:
UNT 0083 IN HEWA 8.0
END DESCRIPTION:
XS GIS Cut Line= 3
      2709337.05     10063629.68      2708592.28     10063629.68
      2708337.03     10063817.21
#Sta/Elev= 30
  4480.8 1871.30  4539.4 1869.08  4589.4 1863.61  4621.5 1863.05  4659.4 1857.82
  4699.4 1847.97  4739.4 1842.69  4789.4 1834.07  4879.4 1829.85  4969.4 1827.17
  4989.4 1821.35  4996.4 1820.90  4999.1 1820.40  5002.4 1820.90  5019.4 1825.13
  5089.4 1833.05  5114.9 1837.84  5129.4 1841.45  5149.4 1844.53  5189.4 1847.70
  5238.7 1848.16  5253.3 1849.53  5259.5 1851.71  5267.5 1852.68  5280.4 1852.67
  5303.0 1857.36  5336.7 1859.16  5366.8 1861.33  5459.8 1864.30  5542.3 1868.39
#Mann=8,-1,0
  4480.8    0.16       0  4621.5     0.1       0  4996.4    0.07       0
  5002.4     0.1       0  5114.9    0.05       0  5303.0     0.1       0
  5336.7    0.05       0  5459.8     0.1       0
Bank Sta=4996.4,5002.4
Exp/Cntr=0.3,0.1

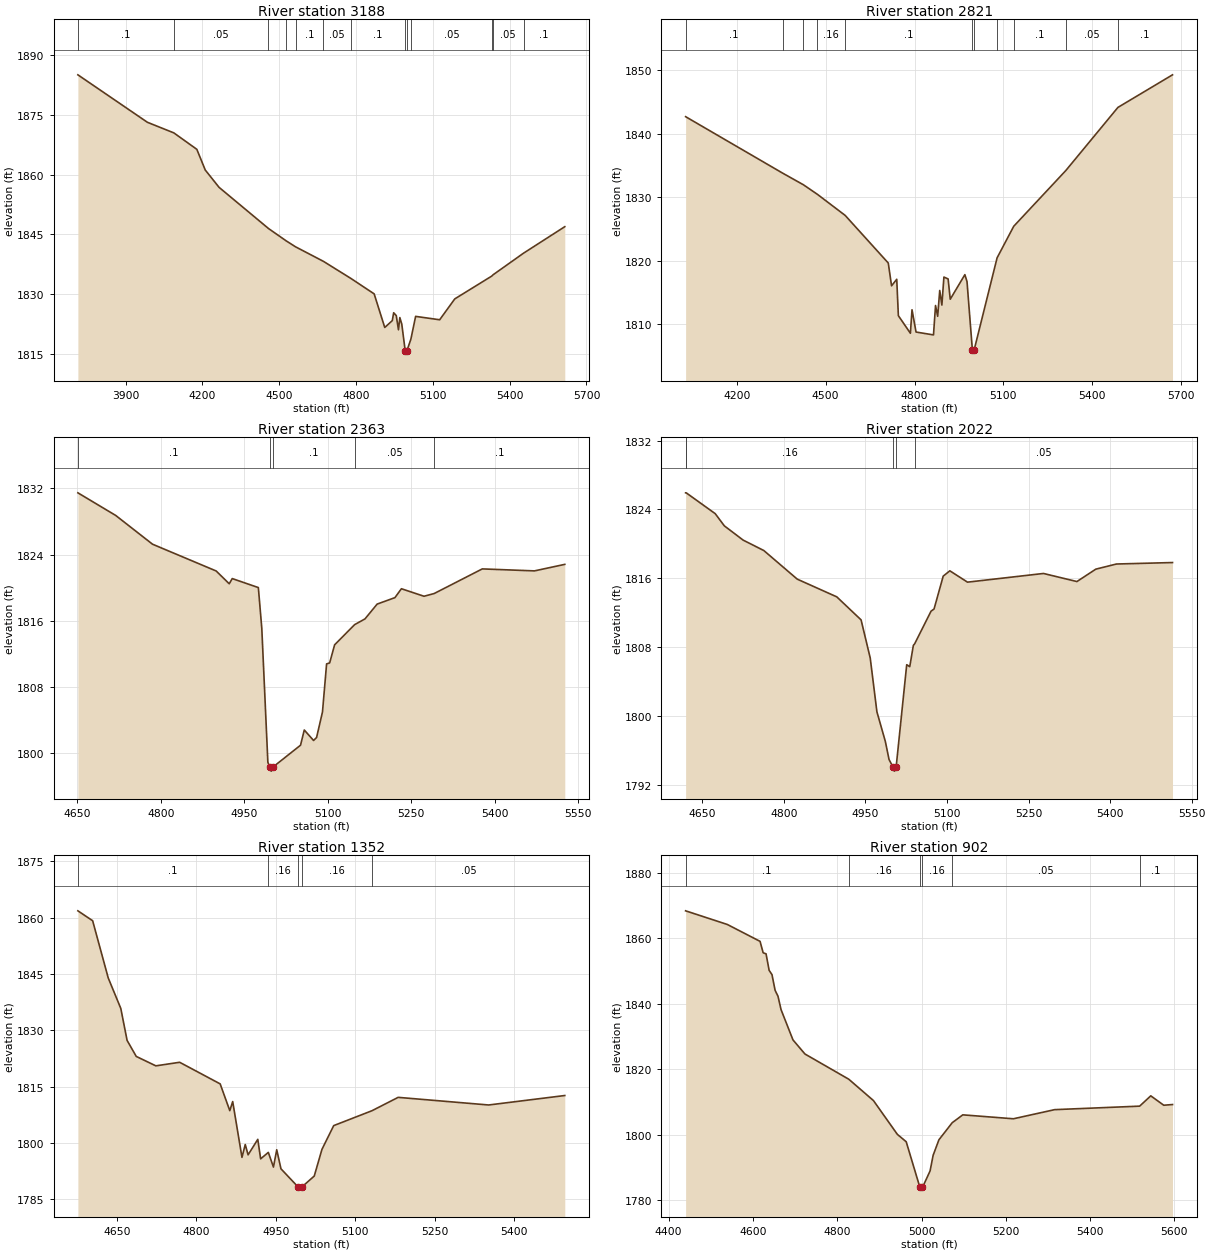
Type RM Length L Ch R = 1,3188,367,367,367
BEGIN DESCRIPTION:
UNT 0083 IN HEWA 7.0
END DESCRIPTION:
XS GIS Cut Line= 3
      2710055.87     10063134.90      2709290.20     10062999.47
      2708248.54     10063421.34
#Sta/Elev= 30
  3714.0 1885.01  3985.6 1873.11  4088.7 1870.46  4178.5 1866.34  4211.4 1861.15
  4265.5 1856.80  4458.2 1846.50  4528.3 1843.36  4564.4 1841.89  4672.7 1838.27
  4781.1 1833.94  4871.0 1830.11  4912.3 1821.69  4941.8 1823.41  4947.2 1825.38
  4957.3 1824.66  4965.9 1821.11  4971.3 1824.17  4978.9 1822.51  4992.4 1815.76
  4995.2 1815.26  4998.4 1815.76  5014.4 1818.77  5032.9 1824.47  5126.8 1823.62
  5185.8 1828.85  5330.7 1834.59  5335.3 1834.89  5454.3 1840.31  5615.4 1846.95
#Mann=13,-1,0
  3714.0     0.1       0  4088.7    0.05       0  4458.2     0.1       0
  4528.3    0.05       0  4564.4     0.1       0  4672.7    0.05       0
  4781.1     0.1       0  4992.4    0.07       0  4998.4     0.1       0
  5014.4    0.05       0  5330.7     0.1       0  5335.3    0.05       0
  5454.3     0.1       0
Bank Sta=4992.4,4998.4
Exp/Cntr=0.3,0.1

Type RM Length L Ch R = 1,2821,458,458,458
BEGIN DESCRIPTION:
UNT 0083 IN HEWA 6.0
END DESCRIPTION:
XS GIS Cut Line= 3
      2709441.21     10062452.61      2708732.91     10062775.51
      2708107.91     10063374.47
#Sta/Elev= 30
  4027.1 1842.70  4354.6 1833.81  4424.7 1831.98  4472.1 1830.47  4565.9 1827.15
  4711.4 1819.65  4722.5 1816.06  4740.0 1817.09  4745.5 1811.36  4786.1 1808.59
  4791.6 1812.29  4805.2 1808.78  4864.1 1808.33  4871.0 1812.96  4878.2 1811.26
  4885.2 1815.33  4892.4 1813.03  4899.3 1817.44  4913.5 1817.14  4920.7 1813.95
  4970.1 1817.82  4977.3 1816.73  4995.4 1805.96  4998.1 1805.46  5001.4 1805.96
  5078.9 1820.47  5135.1 1825.44  5311.0 1834.22  5486.9 1844.16  5671.2 1849.29
#Mann=11,-1,0
  4027.1     0.1       0  4354.6    0.16       0  4424.7     0.1       0
  4472.1    0.16       0  4565.9     0.1       0  4995.4    0.07       0
  5001.4     0.1       0  5078.9    0.05       0  5135.1     0.1       0
  5311.0    0.05       0  5486.9     0.1       0
Bank Sta=4995.4,5001.4
Exp/Cntr=0.3,0.1

Type RM Length L Ch R = 1,2363,341,341,341
BEGIN DESCRIPTION:
UNT 0083 IN HEWA 5.0
END DESCRIPTION:
XS GIS Cut Line= 2
      2708821.41     10062379.70      2708019.33     10062728.65
#Sta/Elev= 30
  4651.2 1831.47  4719.2 1828.73  4785.3 1825.25  4899.6 1822.01  4923.1 1820.46
  4928.5 1821.09  4975.4 1820.00  4981.6 1815.06  4992.5 1798.85  4995.8 1798.28
  4998.6 1797.78  5001.8 1798.28  5051.2 1800.92  5057.9 1802.76  5074.6 1801.49
  5080.0 1801.85  5090.6 1804.94  5098.0 1810.76  5103.5 1810.88  5112.4 1813.07
  5148.3 1815.51  5167.0 1816.21  5188.8 1818.00  5220.7 1818.78  5232.4 1819.86
  5273.0 1818.95  5291.3 1819.28  5377.7 1822.26  5471.4 1822.02  5525.9 1822.81
#Mann=5,-1,0
  4651.2     0.1       0  4995.8    0.07       0  5001.8     0.1       0
  5148.3    0.05       0  5291.3     0.1       0
Bank Sta=4995.8,5001.8
Exp/Cntr=0.3,0.1

Type RM Length L Ch R = 1,2022,670,670,670
BEGIN DESCRIPTION:
UNT 0083 IN HEWA 4.0
END DESCRIPTION:
XS GIS Cut Line= 2
      2708613.09     10062134.90      2707812.22     10062535.33
#Sta/Elev= 30
  4619.4 1825.93  4620.5 1825.93  4673.8 1823.51  4690.6 1822.09  4725.2 1820.43
  4763.2 1819.22  4824.7 1815.89  4897.4 1813.83  4942.1 1811.15  4958.9 1806.72
  4971.2 1800.46  4986.8 1796.99  4993.5 1794.91  5000.6 1794.06  5003.4 1793.56
  5006.6 1794.06  5026.0 1805.94  5031.6 1805.71  5038.2 1808.18  5040.8 1808.39
  5070.7 1812.16  5076.3 1812.42  5093.1 1816.24  5105.3 1816.86  5137.8 1815.54
  5277.5 1816.55  5339.0 1815.61  5373.7 1817.05  5411.7 1817.65  5514.8 1817.82
#Mann=5,-1,0
  4619.4     0.1       0  4620.5    0.16       0  5000.6    0.07       0
  5006.6    0.16       0  5040.8    0.05       0
Bank Sta=5000.6,5006.6
Exp/Cntr=0.3,0.1

Type RM Length L Ch R = 1,1352,450,450,450
BEGIN DESCRIPTION:
UNT 0083 IN HEWA 3.0
END DESCRIPTION:
XS GIS Cut Line= 3
      2708514.19     10061525.50      2708180.82     10061666.14
      2707847.47     10062114.09
#Sta/Elev= 30
  4575.9 1861.83  4603.8 1859.19  4633.3 1843.94  4657.0 1835.85  4668.9 1827.34
  4686.2 1823.07  4723.2 1820.56  4768.2 1821.51  4844.8 1815.76  4863.0 1808.63
  4868.5 1811.05  4886.0 1796.20  4892.2 1799.61  4897.6 1796.87  4915.9 1800.99
  4921.3 1795.80  4935.8 1797.52  4945.5 1793.61  4951.7 1798.22  4959.7 1793.15
  4992.6 1788.24  4995.3 1787.74  4998.6 1788.24  5022.6 1791.22  5037.2 1798.34
  5059.4 1804.65  5131.8 1808.62  5181.2 1812.17  5352.2 1810.14  5496.1 1812.66
#Mann=5,-1,0
  4575.9     0.1       0  4935.8    0.16       0  4992.6    0.07       0
  4998.6    0.16       0  5131.8    0.05       0
Bank Sta=4992.6,4998.6
Exp/Cntr=0.3,0.1

Type RM Length L Ch R = 1,902,807,807,807
BEGIN DESCRIPTION:
UNT 0083 IN HEWA 2.0
END DESCRIPTION:
XS GIS Cut Line= 3
      2708206.78     10061061.98      2707642.57     10061591.48
      2707464.95     10061929.38
#Sta/Elev= 30
  4440.2 1868.36  4539.2 1864.19  4616.9 1859.03  4624.2 1855.54  4631.1 1855.22
  4638.4 1850.17  4645.2 1848.87  4652.6 1844.05  4659.4 1842.28  4666.7 1838.17
  4695.0 1828.91  4723.4 1824.61  4827.4 1816.90  4886.0 1810.37  4942.7 1800.05
  4963.7 1797.79  4996.3 1783.81  4999.1 1783.31  5002.3 1783.81  5020.4 1788.88
  5027.6 1793.65  5041.4 1798.40  5073.0 1803.62  5098.0 1806.01  5218.1 1804.81
  5316.0 1807.60  5517.7 1808.67  5544.1 1811.82  5574.9 1808.95  5595.7 1809.16
#Mann=6,-1,0
  4440.2     0.1       0  4827.4    0.16       0  4996.3    0.07       0
  5002.3    0.16       0  5073.0    0.05       0  5517.7     0.1       0
Bank Sta=4996.3,5002.3
Exp/Cntr=0.3,0.1

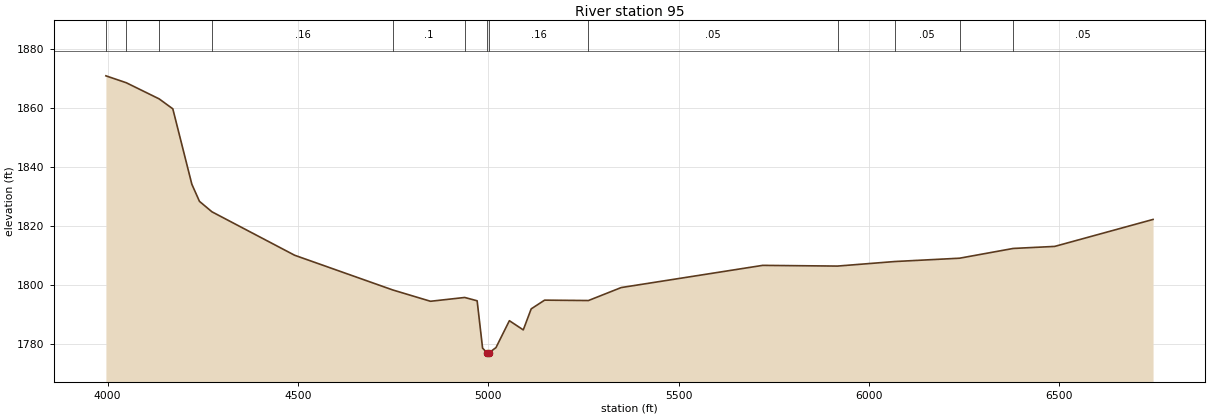
Type RM Length L Ch R = 1,95,0,0,0
BEGIN DESCRIPTION:
UNT 0083 IN HEWA 1.0
END DESCRIPTION:
XS GIS Cut Line= 4
      2708224.22     10060794.26      2707370.08     10060815.10
      2707175.63     10061051.21      2707328.42     10062634.59
#Sta/Elev= 30
  3995.6 1871.01  4049.2 1868.66  4135.6 1863.18  4171.4 1859.81  4221.4 1834.23
  4241.4 1828.43  4274.2 1824.88  4491.5 1810.14  4749.4 1798.36  4848.3 1794.53
  4938.3 1795.82  4970.9 1794.69  4985.2 1778.63  4996.6 1777.10  4999.3 1776.60
  5002.6 1777.10  5020.4 1778.82  5055.6 1787.94  5092.1 1784.82  5112.9 1791.95
  5148.1 1794.91  5263.3 1794.78  5349.3 1799.18  5721.0 1806.71  5917.6 1806.47
  6067.9 1808.01  6238.3 1809.14  6379.3 1812.45  6488.2 1813.14  6746.6 1822.29
#Mann=13,-1,0
  3995.6     0.1       0  4049.2    0.16       0  4135.6     0.1       0
  4274.2    0.16       0  4749.4     0.1       0  4938.3    0.16       0
  4996.6    0.07       0  5002.6    0.16       0  5263.3    0.05       0
  5917.6     0.1       0  6067.9    0.05       0  6238.3     0.1       0
  6379.3    0.05       0
Bank Sta=4996.6,5002.6
Exp/Cntr=0.3,0.1

Chan Stop Cuts=-1