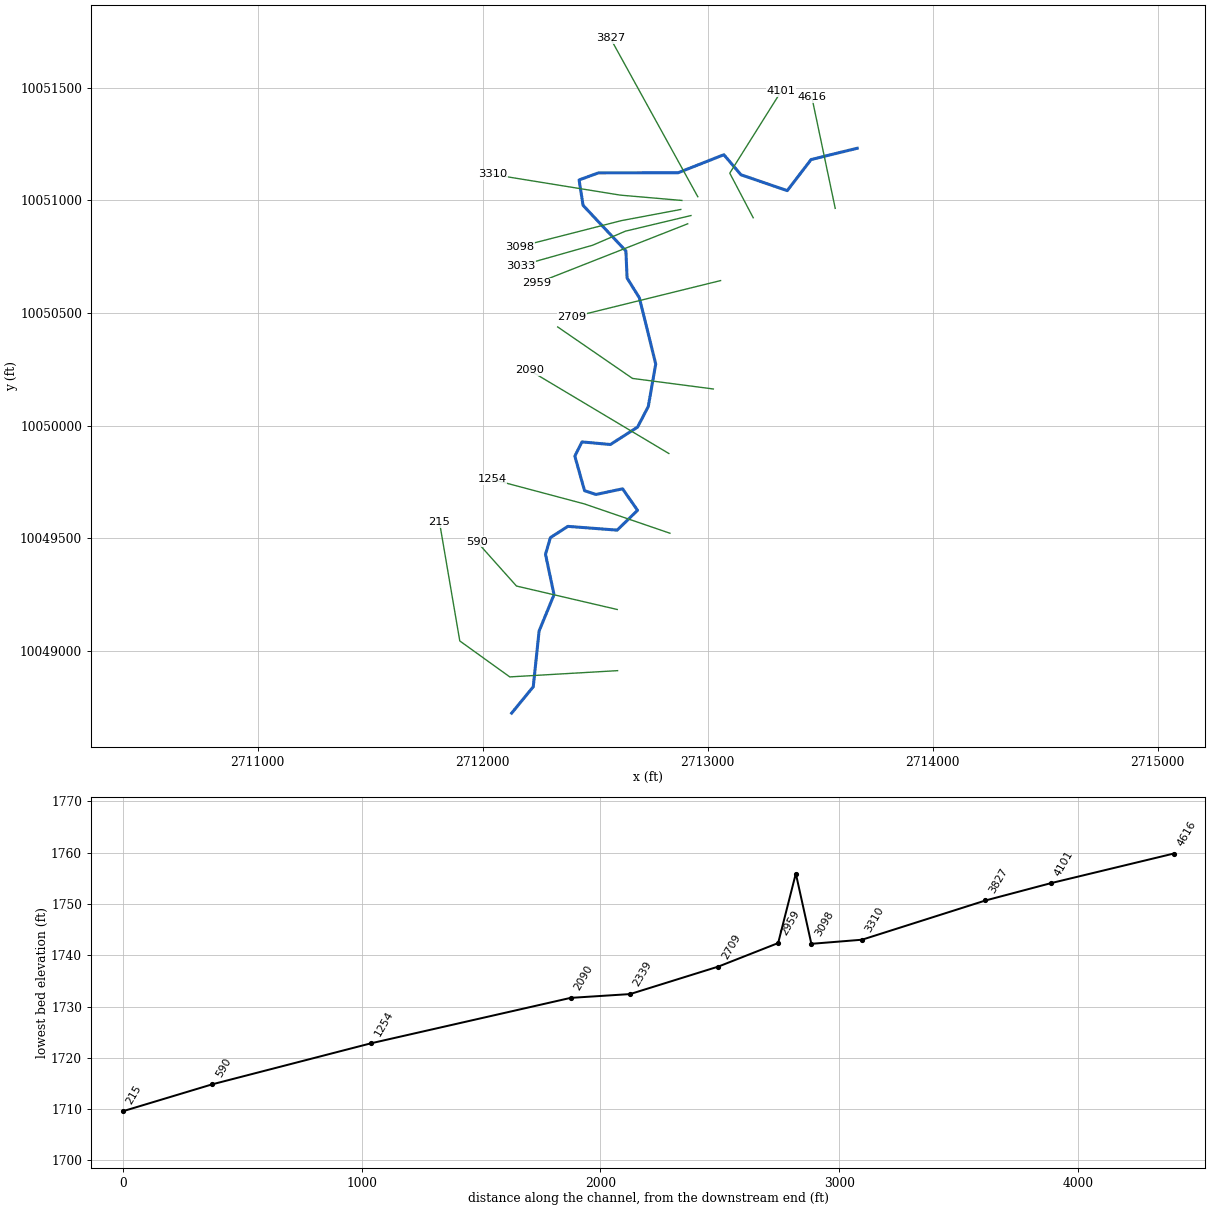
--- UNT 0084 IN HEWA.prj (project) ---

Proj Title=UNT 0084 IN HEWA Base Level Engineering
Current Plan=p01
Default Exp/Contr=0.3,0.1
English Units
Geom File=g01
Flow File=f01
Plan File=p01
BEGIN DESCRIPTION:
UNT 0084 IN HEWA
END DESCRIPTION:

--- UNT 0084 IN HEWA.p01 (plan) ---

Plan Title=Multiple Run
Short Identifier=Multiple
Geom File=g01
Flow File=f01
Subcritical Flow
K Sum by GR= 0
Std Step Tol= 0.01
Critical Tol= 0.01
Num of Std Step Trials= 20
Max Error Tol= 0.3
Flow Tol Ratio= 0.001
Split Flow NTrial= 30
Split Flow Tol= 0.02
Split Flow Ratio= 0.02
Log Output Level= 0
Friction Slope Method= 1
Unsteady Friction Slope Method= 2
Unsteady Bridges Friction Slope Method= 1
Parabolic Critical Depth
Global Vel Dist=  1 , 1 , 1
Global Log Level= 0
CheckData=True
Encroach Param= -1, 0, 0, 0
BEGIN DESCRIPTION:
Multiple Run
END DESCRIPTION:

--- UNT 0084 IN HEWA.f01 (steady flow) ---

Flow Title=Multiple
Number of Profiles=7
Profile Names=10-year,25-year,50-year,1pct_min,100-year,1pct_plu,500-year
River Rch & RM= UNT 0084 IN HEWA,Reach-1,4616
    1326    1956    2507    2344    3170    4286    5066
Boundary for River Rch & Prof#=UNT 0084 IN HEWA,Reach-1,1
Up Type=0
Dn Type=3
Dn Slope=0.005
Boundary for River Rch & Prof#=UNT 0084 IN HEWA,Reach-1,2
Up Type=0
Dn Type=3
Dn Slope=0.005
Boundary for River Rch & Prof#=UNT 0084 IN HEWA,Reach-1,3
Up Type=0
Dn Type=3
Dn Slope=0.005
Boundary for River Rch & Prof#=UNT 0084 IN HEWA,Reach-1,4
Up Type=0
Dn Type=3
Dn Slope=0.005
Boundary for River Rch & Prof#=UNT 0084 IN HEWA,Reach-1,5
Up Type=0
Dn Type=3
Dn Slope=0.005
Boundary for River Rch & Prof#=UNT 0084 IN HEWA,Reach-1,6
Up Type=0
Dn Type=3
Dn Slope=0.005
Boundary for River Rch & Prof#=UNT 0084 IN HEWA,Reach-1,7
Up Type=0
Dn Type=3
Dn Slope=0.005

--- UNT 0084 IN HEWA.g01 (geometry) ---

Geom Title=Existing Conditions

River Reach=UNT 0084 IN HEWA,Reach-1
Reach XY= 30
      2713664.19     10051231.87      2713459.34     10051181.75
      2713353.46     10051043.75      2713147.64     10051114.10
      2713071.64     10051203.19      2712868.58     10051123.25
      2712513.97     10051122.48      2712428.22     10051091.20
      2712445.81     10050978.42      2712636.19     10050775.74
      2712641.53     10050655.54      2712696.13     10050567.77
      2712768.78     10050273.83      2712735.63     10050084.90
      2712688.05     10049993.77      2712567.32     10049916.43
      2712441.07     10049927.98      2712409.33     10049864.73
      2712452.41     10049711.38      2712503.18     10049694.63
      2712621.47     10049719.71      2712688.01     10049624.20
      2712597.43     10049536.26      2712378.30     10049552.97
      2712300.64     10049503.03      2712278.95     10049429.01
      2712316.84     10049249.61      2712250.42     10049088.25
      2712224.44     10048840.69      2712128.47     10048723.73

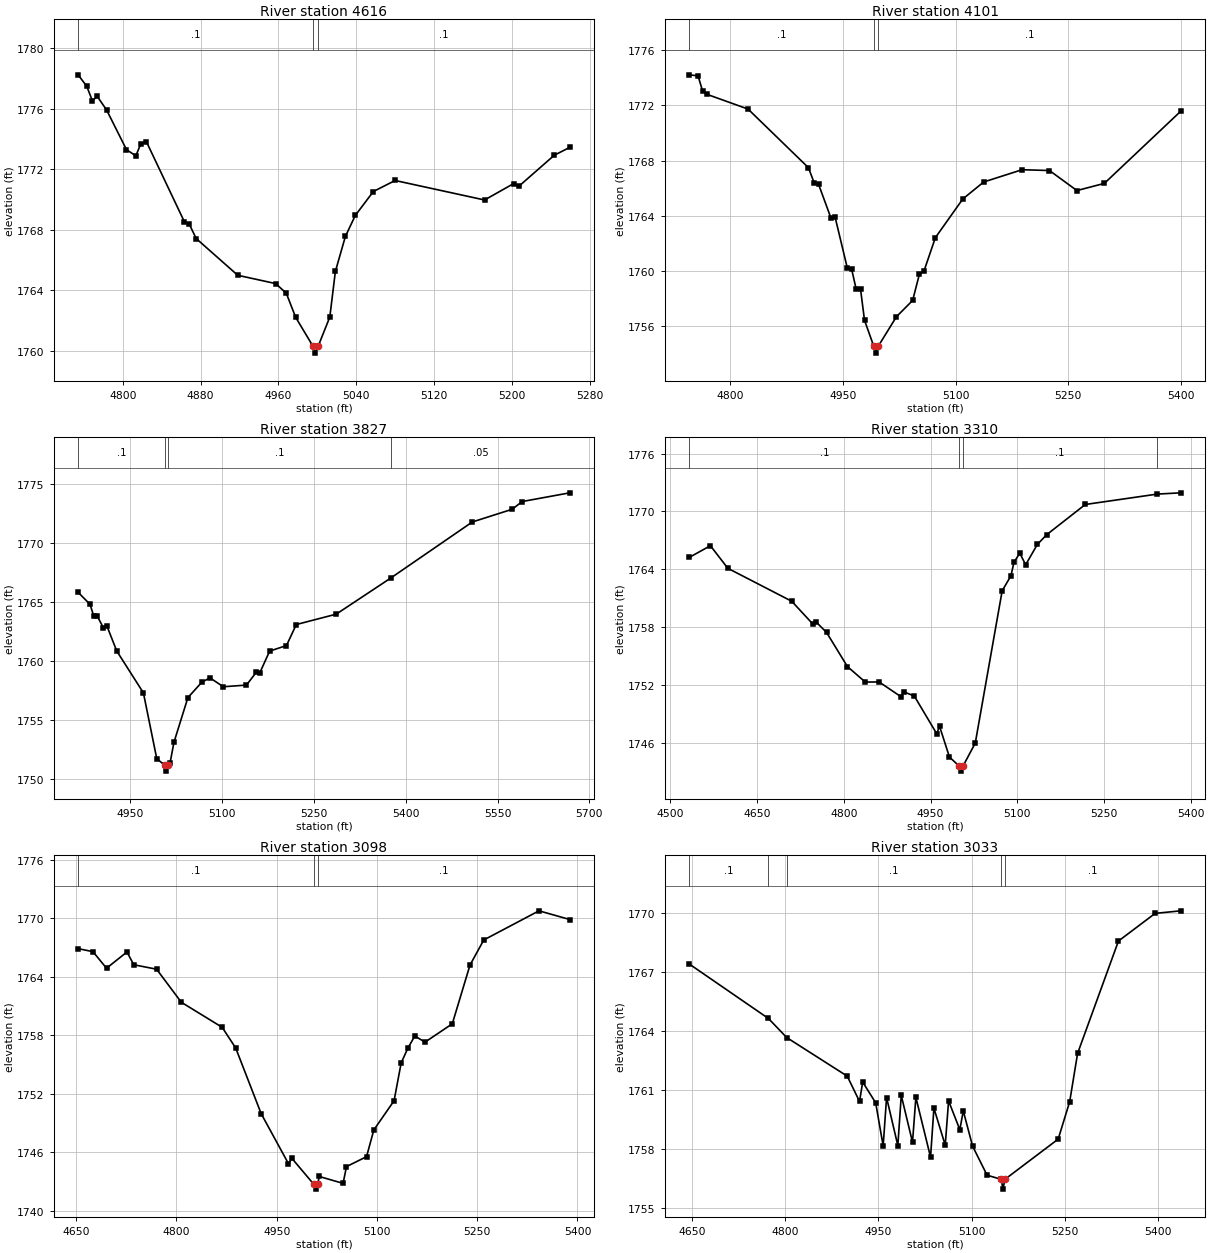
Type RM Length L Ch R = 1,4616,515,515,515
BEGIN DESCRIPTION:
UNT 0084 IN HEWA 9.0
END DESCRIPTION:
XS GIS Cut Line= 2
      2713566.60     10050965.05      2713462.54     10051459.32
#Sta/Elev= 30
  4754.2 1778.25  4763.1 1777.49  4768.8 1776.54  4773.9 1776.82  4783.5 1775.92
  4803.9 1773.30  4813.5 1772.89  4818.6 1773.69  4824.4 1773.82  4863.3 1768.54
  4868.4 1768.37  4875.5 1767.42  4918.2 1764.99  4957.2 1764.44  4968.1 1763.80
  4977.7 1762.21  4995.1 1760.34  4997.9 1759.84  5001.1 1760.34  5012.8 1762.23
  5018.5 1765.24  5028.8 1767.56  5039.0 1768.95  5057.5 1770.53  5079.9 1771.26
  5171.8 1769.97  5201.8 1771.06  5206.9 1770.87  5243.4 1772.93  5259.3 1773.45
#Mann=3,-1,0
  4754.2     0.1       0  4995.1    0.07       0  5001.1     0.1       0
Bank Sta=4995.1,5001.1
Exp/Cntr=0.3,0.1

Type RM Length L Ch R = 1,4101,274,274,274
BEGIN DESCRIPTION:
UNT 0084 IN HEWA 8.0
END DESCRIPTION:
XS GIS Cut Line= 3
      2713202.02     10050923.40      2713097.84     10051121.34
      2713327.00     10051485.92
#Sta/Elev= 30
  4745.6 1774.21  4757.3 1774.14  4763.4 1773.04  4769.1 1772.80  4823.9 1771.73
  4904.2 1767.49  4912.0 1766.38  4917.7 1766.29  4934.1 1763.86  4939.7 1763.92
  4956.1 1760.20  4961.8 1760.13  4967.8 1758.69  4973.6 1758.69  4978.9 1756.44
  4991.2 1754.56  4994.0 1754.06  4997.2 1754.56  5021.3 1756.69  5043.0 1757.88
  5051.9 1759.77  5057.9 1759.98  5073.2 1762.42  5109.7 1765.22  5137.5 1766.45
  5188.6 1767.34  5225.1 1767.28  5261.6 1765.83  5298.1 1766.35  5399.9 1771.58
#Mann=3,-1,0
  4745.6     0.1       0  4991.2    0.07       0  4997.2     0.1       0
Bank Sta=4991.2,4997.2
Exp/Cntr=0.3,0.1

Type RM Length L Ch R = 1,3827,517,517,517
BEGIN DESCRIPTION:
Mapping XS 67f75b8a
END DESCRIPTION:
XS GIS Cut Line= 2
      2712955.73     10051016.62      2712567.56     10051720.03
#Sta/Elev= 30
  4864.5 1765.83  4884.0 1764.81  4889.8 1763.86  4895.5 1763.84  4905.9 1762.81
  4911.6 1762.97  4927.6 1760.86  4971.2 1757.31  4993.0 1751.74  5006.0 1751.18
  5008.8 1750.68  5012.0 1751.18  5014.7 1751.36  5021.1 1753.12  5043.9 1756.91
  5066.8 1758.22  5080.0 1758.58  5101.8 1757.83  5139.6 1757.97  5155.7 1759.06
  5161.4 1759.01  5177.5 1760.85  5205.0 1761.32  5221.0 1763.10  5286.3 1763.98
  5375.7 1767.05  5508.7 1771.79  5574.0 1772.87  5590.0 1773.52  5667.9 1774.26
#Mann=4,-1,0
  4864.5     0.1       0  5006.0    0.07       0  5012.0     0.1       0
  5375.7    0.05       0
Bank Sta=5006,5012
Exp/Cntr=0.3,0.1

Type RM Length L Ch R = 1,3310,212,212,212
BEGIN DESCRIPTION:
UNT 0084 IN HEWA 7.0
END DESCRIPTION:
XS GIS Cut Line= 3
      2712884.97     10051000.16      2712611.65     10051023.72
      2712043.67     10051115.64
#Sta/Elev= 30
  4532.9 1765.22  4569.5 1766.44  4599.7 1764.09  4710.1 1760.67  4747.2 1758.26
  4752.2 1758.52  4770.3 1757.43  4806.3 1753.89  4837.2 1752.28  4861.1 1752.29
  4898.9 1750.76  4903.9 1751.26  4921.9 1750.83  4960.6 1746.92  4965.6 1747.68
  4982.7 1744.49  4999.9 1743.53  5002.7 1743.03  5005.9 1743.53  5027.3 1745.94
  5073.8 1761.76  5089.0 1763.32  5094.1 1764.70  5104.2 1765.67  5114.4 1764.46
  5134.6 1766.57  5150.7 1767.58  5217.5 1770.72  5342.1 1771.80  5382.6 1771.93
#Mann=4,-1,0
  4532.9     0.1       0  4999.9    0.07       0  5005.9     0.1       0
  5342.1    0.05       0
Bank Sta=4999.9,5005.9
Exp/Cntr=0.3,0.1

Type RM Length L Ch R = 1,3098,65,65,65
BEGIN DESCRIPTION:
UNT 0084 IN HEWA 6.0
END DESCRIPTION:
XS GIS Cut Line= 3
      2712880.27     10050960.09      2712616.36     10050910.61
      2712163.87     10050795.13
#Sta/Elev= 30
  4652.9 1766.90  4675.1 1766.59  4695.4 1764.89  4726.0 1766.56  4736.1 1765.25
  4770.3 1764.79  4807.3 1761.40  4868.4 1758.83  4888.7 1756.70  4926.7 1749.98
  4967.6 1744.84  4972.7 1745.39  5005.4 1742.73  5008.2 1742.23  5011.4 1742.73
  5013.6 1743.53  5049.3 1742.82  5054.4 1744.54  5084.4 1745.56  5095.3 1748.30
  5125.6 1751.30  5136.2 1755.18  5146.3 1756.70  5156.6 1757.94  5171.9 1757.31
  5212.7 1759.19  5239.2 1765.22  5259.8 1767.79  5342.4 1770.78  5388.4 1769.89
#Mann=3,-1,0
  4652.9     0.1       0  5005.4    0.07       0  5011.4     0.1       0
Bank Sta=5005.4,5011.4
Exp/Cntr=0.3,0.1

Type RM Length L Ch R = 1,3033,74,74,74
BEGIN DESCRIPTION:
Mapping XS 7234ac5b
END DESCRIPTION:
XS GIS Cut Line= 4
      2712925.63     10050933.15      2712633.97     10050863.71
      2712488.13     10050801.21      2712168.72     10050710.94
#Sta/Elev= 30
  4646.0 1767.42  4773.4 1764.64  4802.7 1763.67  4900.1 1761.70  4919.8 1760.41
  4924.9 1761.40  4945.8 1760.34  4957.8 1758.14  4963.3 1760.61  4981.4 1758.16
  4986.9 1760.72  5005.0 1758.33  5010.4 1760.62  5034.0 1757.57  5039.4 1760.07
  5057.6 1758.18  5063.0 1760.44  5081.1 1758.97  5086.6 1759.93  5101.6 1758.13
  5124.9 1756.65  5147.6 1756.44  5150.4 1755.94  5153.6 1756.44  5239.2 1758.49
  5257.7 1760.40  5270.4 1762.86  5336.1 1768.59  5395.1 1770.00  5436.4 1770.13
#Mann=5,-1,0
  4646.0     0.1       0  4773.4    0.05       0  4802.7     0.1       0
  5147.6    0.07       0  5153.6     0.1       0
Bank Sta=5147.6,5153.6
Exp/Cntr=0.3,0.1

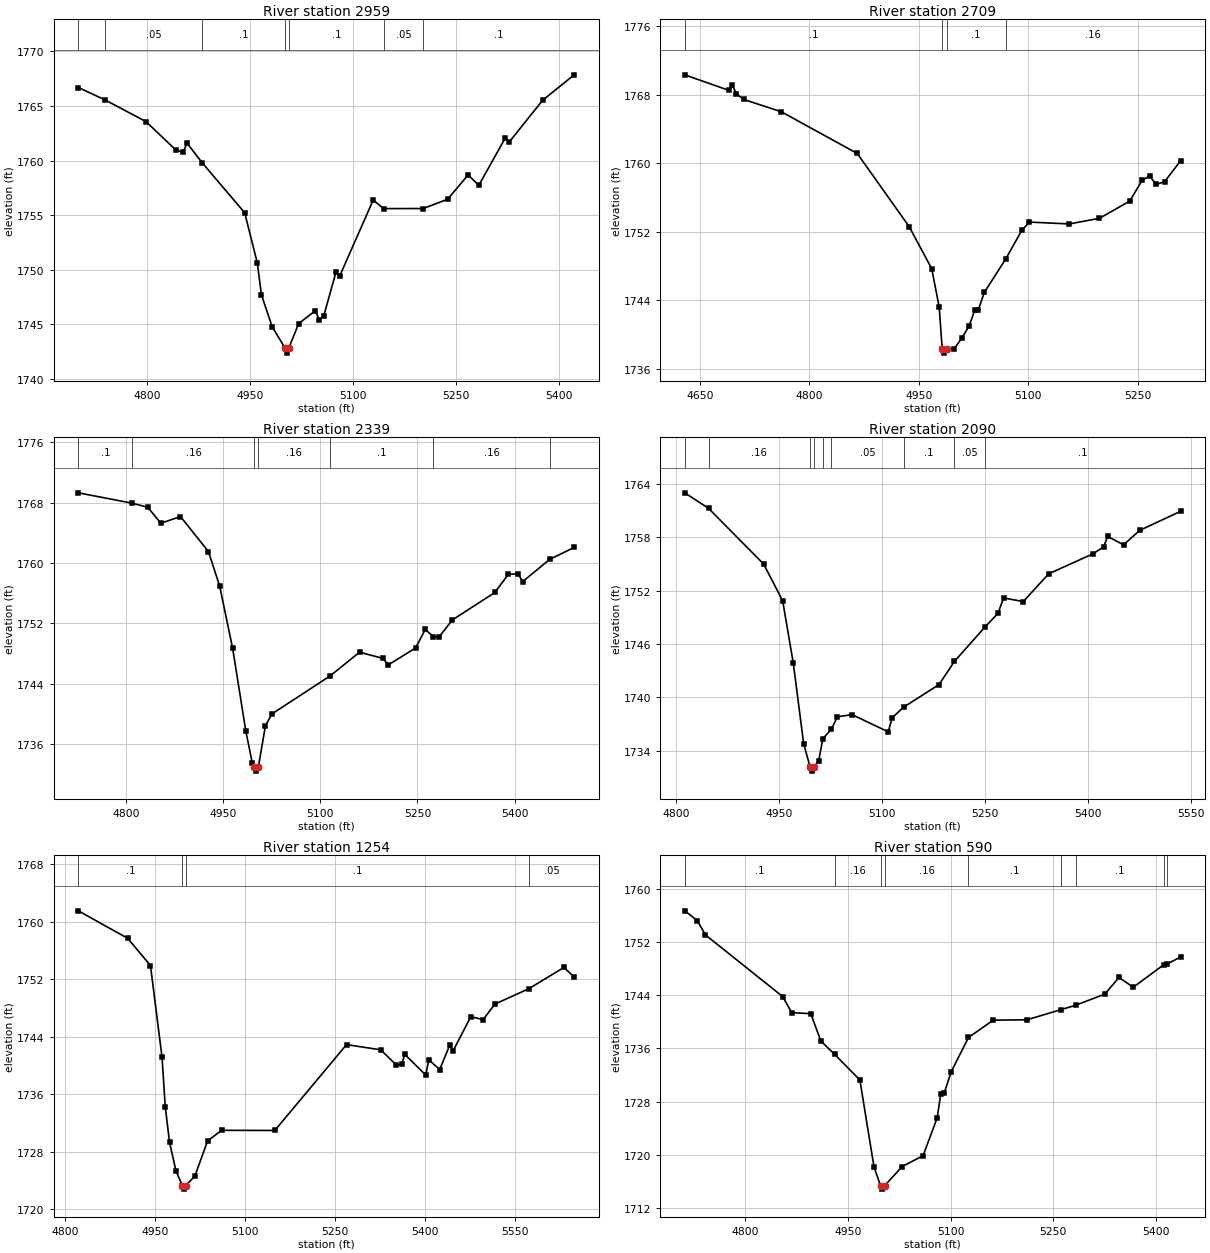
Type RM Length L Ch R = 1,2959,250,250,250
BEGIN DESCRIPTION:
UNT 0084 IN HEWA 5.0
END DESCRIPTION:
XS GIS Cut Line= 2
      2712910.89     10050896.45      2712239.29     10050632.52
#Sta/Elev= 30
  4699.9 1766.68  4738.3 1765.56  4798.4 1763.56  4842.2 1760.94  4852.6 1760.77
  4858.0 1761.60  4880.2 1759.79  4942.0 1755.22  4960.4 1750.62  4966.4 1747.71
  4981.9 1744.81  5000.4 1742.88  5003.1 1742.38  5006.4 1742.88  5020.6 1745.08
  5045.0 1746.27  5050.4 1745.41  5057.1 1745.79  5074.8 1749.78  5080.2 1749.42
  5129.0 1756.38  5144.4 1755.60  5202.0 1755.61  5237.4 1756.46  5267.2 1758.68
  5282.7 1757.73  5321.4 1762.08  5326.8 1761.68  5375.6 1765.51  5421.5 1767.84
#Mann=7,-1,0
  4699.9     0.1       0  4738.3    0.05       0  4880.2     0.1       0
  5000.4    0.07       0  5006.4     0.1       0  5144.4    0.05       0
  5202.0     0.1       0
Bank Sta=5000.4,5006.4
Exp/Cntr=0.3,0.1

Type RM Length L Ch R = 1,2709,370,370,370
BEGIN DESCRIPTION:
Mapping XS e6e5c20e
END DESCRIPTION:
XS GIS Cut Line= 2
      2713057.03     10050644.31      2712397.17     10050481.70
#Sta/Elev= 30
  4629.2 1770.31  4689.3 1768.50  4694.5 1769.08  4699.8 1768.11  4710.1 1767.43
  4761.6 1765.99  4865.6 1761.12  4936.7 1752.58  4967.6 1747.67  4977.9 1743.18
  4982.0 1738.30  4984.7 1737.80  4988.0 1738.30  4998.5 1738.31  5008.8 1739.55
  5019.1 1741.00  5026.4 1742.78  5031.6 1742.88  5039.7 1744.89  5068.9 1748.78
  5091.2 1752.15  5101.5 1753.11  5156.1 1752.89  5197.6 1753.55  5239.1 1755.56
  5256.0 1757.99  5266.3 1758.48  5275.4 1757.51  5286.9 1757.83  5308.8 1760.28
#Mann=4,-1,0
  4629.2     0.1       0  4982.0    0.07       0  4988.0     0.1       0
  5068.9    0.16       0
Bank Sta=4982,4988
Exp/Cntr=0.3,0.1

Type RM Length L Ch R = 1,2339,249,249,249
BEGIN DESCRIPTION:
UNT 0084 IN HEWA 4.0
END DESCRIPTION:
XS GIS Cut Line= 3
      2713024.90     10050163.01      2712665.55     10050209.88
      2712333.05     10050438.48
#Sta/Elev= 30
  4726.1 1769.29  4809.6 1767.91  4833.4 1767.37  4853.6 1765.26  4883.9 1766.15
  4927.1 1761.51  4944.4 1756.94  4964.5 1748.68  4984.7 1737.79  4994.8 1733.52
  4998.1 1732.93  5000.8 1732.43  5004.1 1732.93  5015.0 1738.40  5025.0 1740.00
  5114.9 1745.03  5160.5 1748.18  5196.3 1747.37  5205.1 1746.51  5247.1 1748.74
  5261.9 1751.19  5274.6 1750.24  5282.9 1750.15  5303.9 1752.46  5369.5 1756.09
  5390.5 1758.52  5405.4 1758.54  5412.6 1757.54  5454.0 1760.46  5492.0 1762.06
#Mann=7,-1,0
  4726.1     0.1       0  4809.6    0.16       0  4998.1    0.07       0
  5004.1    0.16       0  5114.9     0.1       0  5274.6    0.16       0
  5454.0    0.05       0
Bank Sta=4998.1,5004.1
Exp/Cntr=0.3,0.1

Type RM Length L Ch R = 1,2090,836,836,836
BEGIN DESCRIPTION:
Mapping XS b5d71019
END DESCRIPTION:
XS GIS Cut Line= 2
      2712827.00     10049876.56      2712207.23     10050246.33
#Sta/Elev= 30
  4812.9 1763.00  4847.4 1761.26  4927.6 1754.99  4955.3 1750.87  4970.8 1743.85
  4985.9 1734.79  4995.1 1732.19  4997.8 1731.69  5001.1 1732.19  5007.8 1732.82
  5013.7 1735.32  5026.3 1736.41  5035.0 1737.81  5056.5 1738.04  5109.0 1736.11
  5114.8 1737.70  5131.7 1738.90  5183.0 1741.43  5205.3 1744.03  5249.7 1747.89
  5268.6 1749.43  5277.0 1751.17  5305.6 1750.77  5342.6 1753.89  5406.8 1756.13
  5422.4 1756.91  5428.4 1758.09  5451.6 1757.15  5474.9 1758.77  5534.6 1760.92
#Mann=9,-1,0
  4812.9    0.05       0  4847.4    0.16       0  4995.1    0.07       0
  5001.1    0.16       0  5013.7     0.1       0  5026.3    0.05       0
  5131.7     0.1       0  5205.3    0.05       0  5249.7     0.1       0
Bank Sta=4995.1,5001.1
Exp/Cntr=0.3,0.1

Type RM Length L Ch R = 1,1254,664,664,664
BEGIN DESCRIPTION:
UNT 0084 IN HEWA 3.0
END DESCRIPTION:
XS GIS Cut Line= 3
      2712832.18     10049522.40      2712452.00     10049652.59
      2712042.00     10049761.58
#Sta/Elev= 30
  4822.2 1761.54  4904.4 1757.72  4942.4 1753.93  4961.7 1741.14  4967.0 1734.31
  4974.1 1729.37  4984.7 1725.42  4995.3 1723.33  4998.1 1722.83  5001.3 1723.33
  5016.4 1724.65  5037.5 1729.53  5060.9 1731.01  5149.5 1730.99  5269.1 1742.93
  5325.9 1742.21  5351.9 1740.11  5360.9 1740.18  5366.1 1741.57  5401.0 1738.70
  5406.2 1740.82  5424.3 1739.46  5441.2 1742.90  5446.4 1742.03  5476.0 1746.80
  5496.7 1746.42  5516.3 1748.57  5572.6 1750.70  5631.3 1753.66  5648.3 1752.34
#Mann=4,-1,0
  4822.2     0.1       0  4995.3    0.07       0  5001.3     0.1       0
  5572.6    0.05       0
Bank Sta=4995.3,5001.3
Exp/Cntr=0.3,0.1

Type RM Length L Ch R = 1,590,375,375,375
BEGIN DESCRIPTION:
UNT 0084 IN HEWA 2.0
END DESCRIPTION:
XS GIS Cut Line= 3
      2712597.84     10049183.84      2712149.92     10049288.01
      2711973.13     10049485.60
#Sta/Elev= 30
  4711.4 1756.68  4729.6 1755.22  4741.6 1753.06  4854.5 1743.79  4867.7 1741.37
  4895.6 1741.22  4910.3 1737.11  4930.3 1735.12  4967.4 1731.25  4988.0 1718.21
  4997.6 1715.34  5000.4 1714.84  5003.6 1715.34  5029.0 1718.22  5059.8 1719.87
  5080.4 1725.54  5085.8 1729.21  5091.0 1729.36  5100.9 1732.48  5126.2 1737.64
  5162.5 1740.24  5211.7 1740.30  5261.4 1741.82  5282.7 1742.48  5325.4 1744.15
  5346.3 1746.66  5367.2 1745.19  5412.1 1748.60  5417.0 1748.71  5436.4 1749.74
#Mann=9,-1,0
  4711.4     0.1       0  4930.3    0.16       0  4997.6    0.07       0
  5003.6    0.16       0  5126.2     0.1       0  5261.4    0.05       0
  5282.7     0.1       0  5412.1    0.05       0  5417.0     0.1       0
Bank Sta=4997.6,5003.6
Exp/Cntr=0.3,0.1

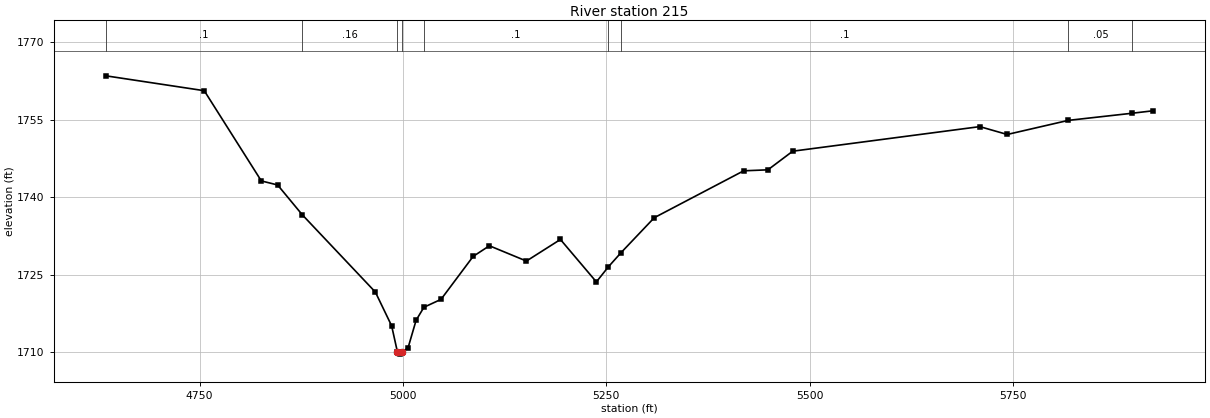
Type RM Length L Ch R = 1,215,0,0,0
BEGIN DESCRIPTION:
UNT 0084 IN HEWA 1.0
END DESCRIPTION:
XS GIS Cut Line= 4
      2712599.20     10048912.31      2712120.08     10048884.54
      2711897.86     10049044.26      2711807.85     10049570.43
#Sta/Elev= 30
  4634.9 1763.49  4755.8 1760.61  4826.0 1743.13  4846.0 1742.35  4876.3 1736.58
  4966.2 1721.60  4986.2 1715.06  4993.2 1710.08  4996.0 1709.58  4999.2 1710.08
  5006.3 1710.76  5016.3 1716.15  5025.9 1718.66  5046.9 1720.19  5086.4 1728.51
  5106.4 1730.57  5151.9 1727.61  5193.7 1731.79  5237.9 1723.57  5252.6 1726.48
  5268.2 1729.23  5309.1 1736.01  5419.0 1745.09  5448.8 1745.28  5479.3 1748.89
  5709.3 1753.65  5743.0 1752.13  5818.1 1754.86  5897.0 1756.25  5922.3 1756.72
#Mann=9,-1,0
  4634.9     0.1       0  4876.3    0.16       0  4993.2    0.07       0
  4999.2    0.16       0  5025.9     0.1       0  5252.6    0.16       0
  5268.2     0.1       0  5818.1    0.05       0  5897.0     0.1       0
Bank Sta=4993.2,4999.2
Exp/Cntr=0.3,0.1

Chan Stop Cuts=-1