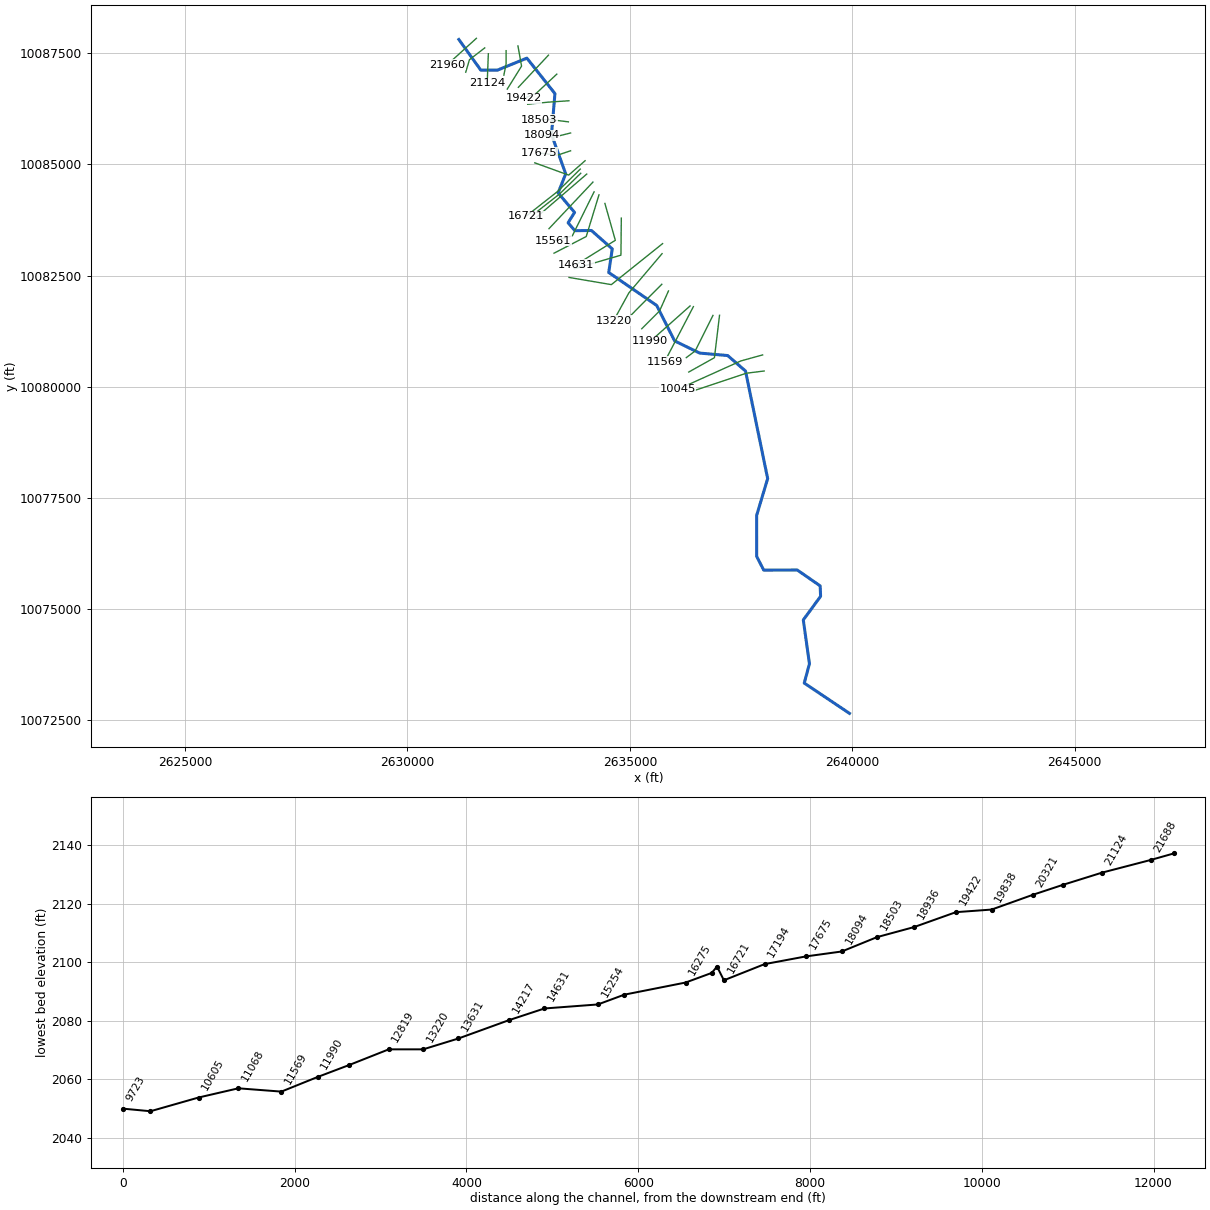
--- UNT 0085 IN HEWA.prj (project) ---

Proj Title=UNT 0085 IN HEWA Base Level Engineering
Current Plan=p01
Default Exp/Contr=0.3,0.1
English Units
Geom File=g01
Flow File=f01
Plan File=p01
Y Axis Title=Elevation
X Axis Title(PF)=Main Channel Distance
X Axis Title(XS)=Station
BEGIN DESCRIPTION:
UNT 0085 IN HEWA
END DESCRIPTION:
DSS Export Rating Curves= 0
DSS Export Rating Curve Sorted= 0
DSS Export Volume Flow Curves= 0
DXF OffsetX= 0
DXF OffsetY= 0
DXF ScaleX= 1
DXF ScaleY= 10

--- UNT 0085 IN HEWA.p01 (plan) ---

Plan Title=Multiple Run
Short Identifier=Multiple
Geom File=g01
Flow File=f01
Subcritical Flow
K Sum by GR= 0
Std Step Tol= 0.01
Critical Tol= 0.01
Num of Std Step Trials= 20
Max Error Tol= 0.3
Flow Tol Ratio= 0.001
Split Flow NTrial= 30
Split Flow Tol= 0.02
Split Flow Ratio= 0.02
Log Output Level= 0
Friction Slope Method= 1
Unsteady Friction Slope Method= 2
Unsteady Bridges Friction Slope Method= 1
Parabolic Critical Depth
Global Vel Dist=  1 , 1 , 1
Global Log Level= 0
CheckData=True
Encroach Param= -1, 0, 0, 0
BEGIN DESCRIPTION:
Multiple Run
END DESCRIPTION:

--- UNT 0085 IN HEWA.f01 (steady flow) ---

Flow Title=Multiple
Program Version=4.10
Number of Profiles= 7
Profile Names=10-year,25-year,50-year,1pct_min,100-year,1pct_plu,500-year
River Rch & RM=UNT 0085 IN HEWA,Reach-1         ,21960
     970    1399    1765    1624    2196    2970    3399
River Rch & RM=UNT 0085 IN HEWA,Reach-1         ,19838
    1653    2446    3141    2933    3966    5364    6332
River Rch & RM=UNT 0085 IN HEWA,Reach-1         ,13631
    2642    3998    5210    4930    6668    9017   10936
River Rch & RM=UNT 0085 IN HEWA,Reach-1         ,13220
    2642    3998    5210    4930    6668    9017   10936
River Rch & RM=UNT 0085 IN HEWA,Reach-1         ,10045
    3214    4901    6420    6103    8253   11161   13659
River Rch & RM=UNT 0085 IN HEWA,Reach-1         ,6180
    3479    5316    6972    6633    8970   12131   14873
Boundary for River Rch & Prof#=UNT 0085 IN HEWA,Reach-1         , 1
Up Type= 0
Dn Type= 3
Dn Slope=0.002
Boundary for River Rch & Prof#=UNT 0085 IN HEWA,Reach-1         , 2
Up Type= 0
Dn Type= 3
Dn Slope=0.002
Boundary for River Rch & Prof#=UNT 0085 IN HEWA,Reach-1         , 3
Up Type= 0
Dn Type= 3
Dn Slope=0.002
Boundary for River Rch & Prof#=UNT 0085 IN HEWA,Reach-1         , 4
Up Type= 0
Dn Type= 3
Dn Slope=0.002
Boundary for River Rch & Prof#=UNT 0085 IN HEWA,Reach-1         , 5
Up Type= 0
Dn Type= 3
Dn Slope=0.002
Boundary for River Rch & Prof#=UNT 0085 IN HEWA,Reach-1         , 6
Up Type= 0
Dn Type= 3
Dn Slope=0.002
Boundary for River Rch & Prof#=UNT 0085 IN HEWA,Reach-1         , 7
Up Type= 0
Dn Type= 3
Dn Slope=0.002
DSS Import GetInterval= 0
DSS Import GetPeak= 0
DSS Import FillOption= 0

--- UNT 0085 IN HEWA.g01 (geometry) ---

Geom Title=Existing Conditions
Program Version=4.10

River Reach=UNT 0085 IN HEWA,Reach-1
Reach XY= 30
      2631157.12     10087804.19      2631649.67     10087116.64
      2632022.99     10087115.24       2632686.1     10087385.94
      2633316.59     10086588.67      2633239.09     10085668.99
      2633558.88     10084785.17      2633388.15     10084355.81
      2633758.18     10083918.47      2633612.09     10083684.94
      2633765.34     10083507.64      2634137.89     10083511.64
      2634604.76     10083097.91      2634525.82     10082567.28
      2635603.83     10081826.59      2636006.68     10081029.54
      2636569.84     10080756.61       2637200.2     10080700.69
      2637600.01      10080353.4      2638097.88     10077936.29
      2637849.55      10077105.3      2637851.45     10076184.97
       2638009.9     10075877.36      2638762.46     10075881.25
      2639278.47     10075523.73      2639287.59      10075289.1
      2638898.81     10074758.48       2639037.1     10073773.34
      2638920.21     10073339.49      2639936.67     10072658.29

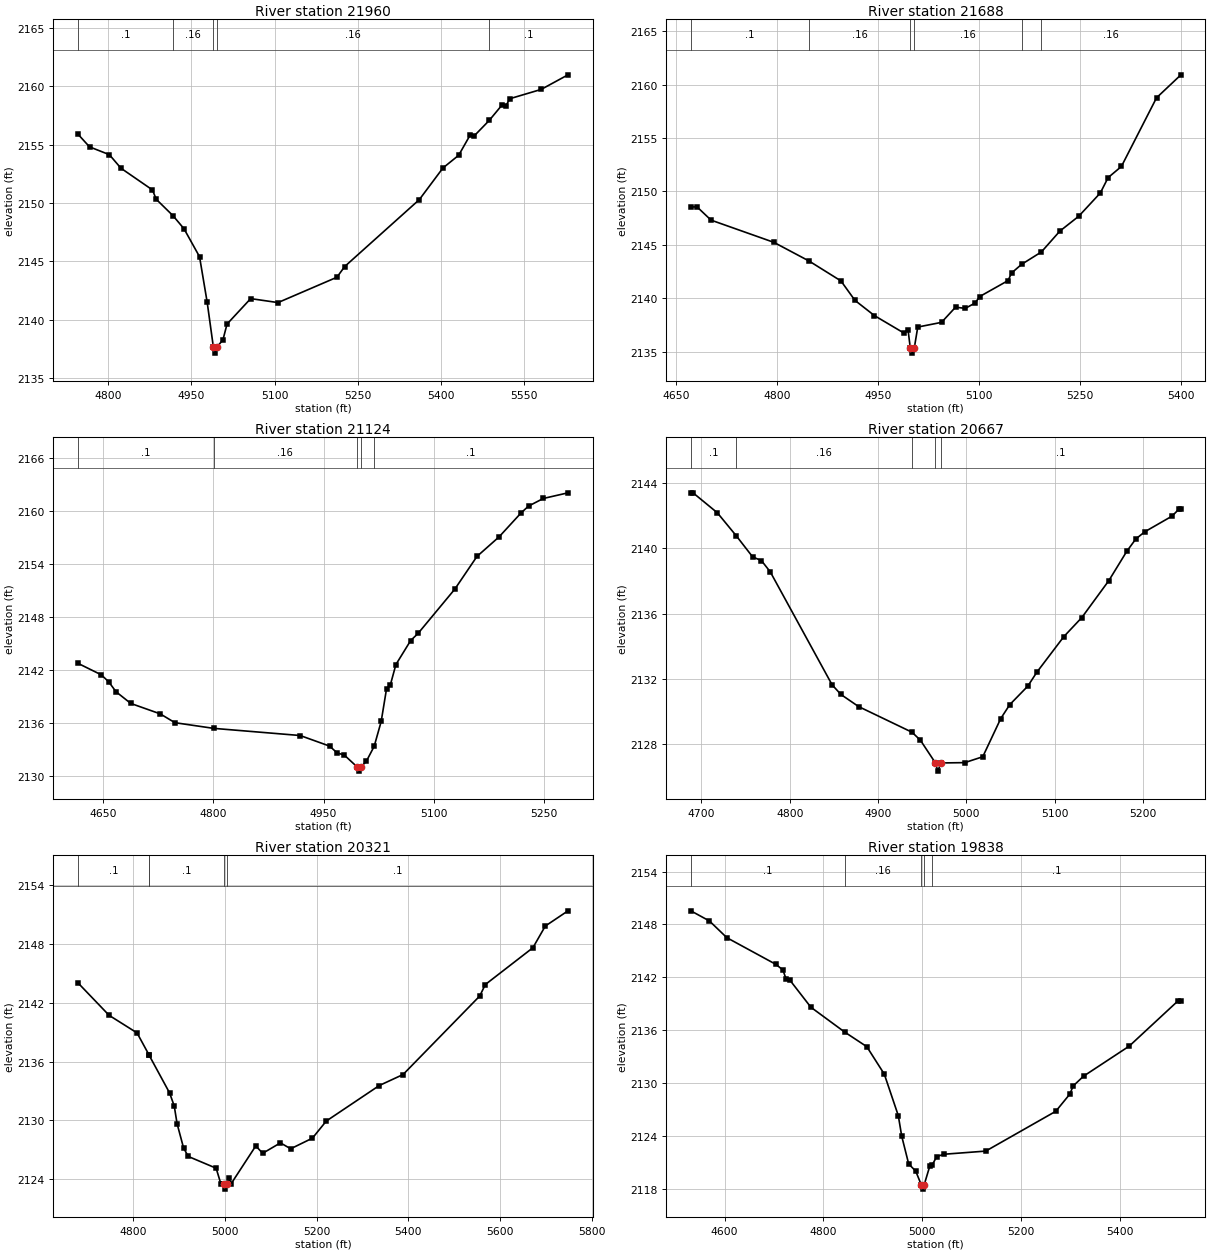
Type RM Length L Ch R = 1 ,21960   ,272,272,272
BEGIN DESCRIPTION:
UNT 0085 IN HEWA 46.0
END DESCRIPTION:
XS GIS Cut Line= 2
      2631551.07      10087830.8      2630895.77     10087237.92
#Sta/Elev= 30
  4745.2 2155.89  4766.1  2154.8  4801.9 2154.13  4822.8 2152.97  4879.6 2151.11
  4886.4 2150.31  4916.5 2148.91  4936.4 2147.79  4964.5 2145.39  4978.3 2141.48
  4989.5 2137.63  4992.2 2137.13  4995.5 2137.63  5006.7 2138.27  5014.1 2139.62
  5056.7  2141.8    5106 2141.46  5212.2 2143.63  5226.3 2144.55  5360.8 2150.28
  5403.4 2152.99  5431.8 2154.08  5452.8 2155.84  5460.2 2155.76  5486.8 2157.06
  5509.5 2158.36    5517 2158.29  5523.7 2158.92  5580.5 2159.72  5628.9 2160.97
#Mann= 5 ,-1 , 0
  4745.2      .1       0  4916.5     .16       0  4989.5     .07       0
  4995.5     .16       0  5486.8      .1       0
Bank Sta=4989.5,4995.5
XS Rating Curve= 0 ,0
Exp/Cntr=0.3,0.1

Type RM Length L Ch R = 1 ,21688   ,564,564,564
BEGIN DESCRIPTION:
UNT 0085 IN HEWA 45.0
END DESCRIPTION:
XS GIS Cut Line= 3
      2631738.72     10087615.89      2631394.96     10087350.26
      2631311.61     10087068.98
#Sta/Elev= 30
  4672.1 2148.55  4681.3 2148.56  4702.1 2147.32  4795.4 2145.24  4847.7 2143.49
    4895 2141.63  4915.8 2139.81  4944.8 2138.38  4988.3 2136.76  4994.6 2137.07
    4998 2135.37  5000.7 2134.87    5004 2135.37  5009.1 2137.31  5044.4 2137.75
  5065.2 2139.17  5079.7 2139.06  5094.2 2139.56  5101.2 2140.17  5143.2 2141.66
  5148.4 2142.37  5163.3 2143.18  5192.7 2144.34  5220.1 2146.29  5248.1 2147.68
  5280.2 2149.86  5291.8  2151.3  5311.5 2152.34  5363.7 2158.77  5399.9 2160.92
#Mann= 6 ,-1 , 0
  4672.1      .1       0  4847.7     .16       0    4998     .07       0
    5004     .16       0  5163.3      .1       0  5192.7     .16       0
Bank Sta=4998,5004
XS Rating Curve= 0 ,0
Exp/Cntr=0.3,0.1

Type RM Length L Ch R = 1 ,21124   ,457,457,457
BEGIN DESCRIPTION:
UNT 0085 IN HEWA 44.0
END DESCRIPTION:
XS GIS Cut Line= 2
       2631819.9     10087485.45      2631793.94     10086820.16
#Sta/Elev= 30
  4616.3 2142.76    4648 2141.46  4658.1 2140.67  4668.1 2139.54  4688.1 2138.22
  4728.1 2137.04  4748.1 2136.04  4800.6  2135.4  4918.2 2134.59  4958.3 2133.39
  4968.3 2132.63  4978.3 2132.37  4995.3 2131.06  4998.1 2130.56  5001.3 2131.06
  5008.3  2131.7  5018.8 2133.37  5028.3 2136.18  5035.6 2139.89  5040.6 2140.27
  5048.3 2142.62  5068.4 2145.34  5078.4 2146.14  5128.4 2151.16  5158.4 2154.85
  5188.5 2157.07  5218.5 2159.79  5228.5 2160.55  5248.5 2161.41  5282.1 2162.05
#Mann= 5 ,-1 , 0
  4616.3      .1       0  4800.6     .16       0  4995.3     .07       0
  5001.3     .16       0  5018.8      .1       0
Bank Sta=4995.3,5001.3
XS Rating Curve= 0 ,0
Exp/Cntr=0.3,0.1

Type RM Length L Ch R = 1 ,20667   ,346,346,346
BEGIN DESCRIPTION:
UNT 0085 IN HEWA 43.0
END DESCRIPTION:
XS GIS Cut Line= 3
      2632218.47     10087553.76      2632218.47     10087253.73
      2632168.46     10087003.71
#Sta/Elev= 30
    4688  2143.4  4690.5  2143.4    4718 2142.18  4739.6 2140.76    4758 2139.48
    4768 2139.25    4778 2138.56    4848 2131.65    4858 2131.06    4878 2130.32
  4938.5 2128.75    4948 2128.26    4965 2126.87  4967.8 2126.37    4971 2126.87
  4998.2 2126.89  5018.6 2127.25    5039 2129.59  5049.2 2130.44  5069.6 2131.57
  5079.8 2132.42  5110.4  2134.6  5130.8 2135.77  5161.4 2138.03  5181.8 2139.83
    5192 2140.58  5202.2 2141.02  5232.8 2141.97  5240.4 2142.38    5243 2142.38
#Mann= 5 ,-1 , 0
    4688      .1       0  4739.6     .16       0  4938.5      .1       0
    4965     .07       0    4971      .1       0
Bank Sta=4965,4971
XS Rating Curve= 0 ,0
Exp/Cntr=0.3,0.1

Type RM Length L Ch R = 1 ,20321   ,483,483,483
BEGIN DESCRIPTION:
UNT 0085 IN HEWA 42.0
END DESCRIPTION:
XS GIS Cut Line= 3
      2632485.24     10087660.68      2632566.37     10087206.33
      2632245.08     10086690.31
#Sta/Elev= 30
    4679 2144.02    4747 2140.71    4808 2138.92    4834 2136.69  4834.3 2136.65
  4879.1  2132.8  4889.2 2131.47  4895.4 2129.67  4909.5 2127.21  4919.7 2126.34
  4980.6 2125.14  4990.8 2123.57    4998 2123.51  5000.7 2123.01    5004 2123.51
  5008.1 2124.19  5013.2 2123.55  5067.1 2127.41  5082.2 2126.66  5120.9 2127.72
  5143.3 2127.12  5190.7  2128.2  5220.9 2129.94  5336.6 2133.56  5388.5 2134.68
  5555.9 2142.68  5567.9 2143.84  5671.8 2147.59  5698.9  2149.8  5748.4 2151.35
#Mann= 5 ,-1 , 0
    4679      .1       0    4834     .16       0  4834.3      .1       0
    4998     .07       0    5004      .1       0
Bank Sta=4998,5004
XS Rating Curve= 0 ,0
Exp/Cntr=0.3,0.1

Type RM Length L Ch R = 1 ,19838   ,416,416,416
BEGIN DESCRIPTION:
UNT 0085 IN HEWA 41.0
END DESCRIPTION:
XS GIS Cut Line= 2
      2633171.52     10087453.69      2632494.47     10086729.76
#Sta/Elev= 30
  4531.7 2149.54  4569.3 2148.39  4604.5 2146.49  4703.7 2143.46  4717.8 2142.83
  4724.7 2141.75    4732 2141.67  4774.5 2138.59  4842.6 2135.78  4887.6 2134.11
    4923 2130.99  4951.3 2126.28  4958.2 2123.95  4972.3 2120.79  4986.5 2119.98
  4997.7 2118.43  5000.4 2117.93  5003.7 2118.43  5014.8 2120.51  5020.3 2120.72
    5029 2121.62  5043.2 2121.89  5128.2 2122.25  5269.8 2126.77  5298.2 2128.72
    5305 2129.65    5326 2130.76  5418.3 2134.17  5516.8  2139.3  5522.9  2139.3
#Mann= 5 ,-1 , 0
  4531.7      .1       0  4842.6     .16       0  4997.7     .07       0
  5003.7     .16       0  5020.3      .1       0
Bank Sta=4997.7,5003.7
XS Rating Curve= 0 ,0
Exp/Cntr=0.3,0.1

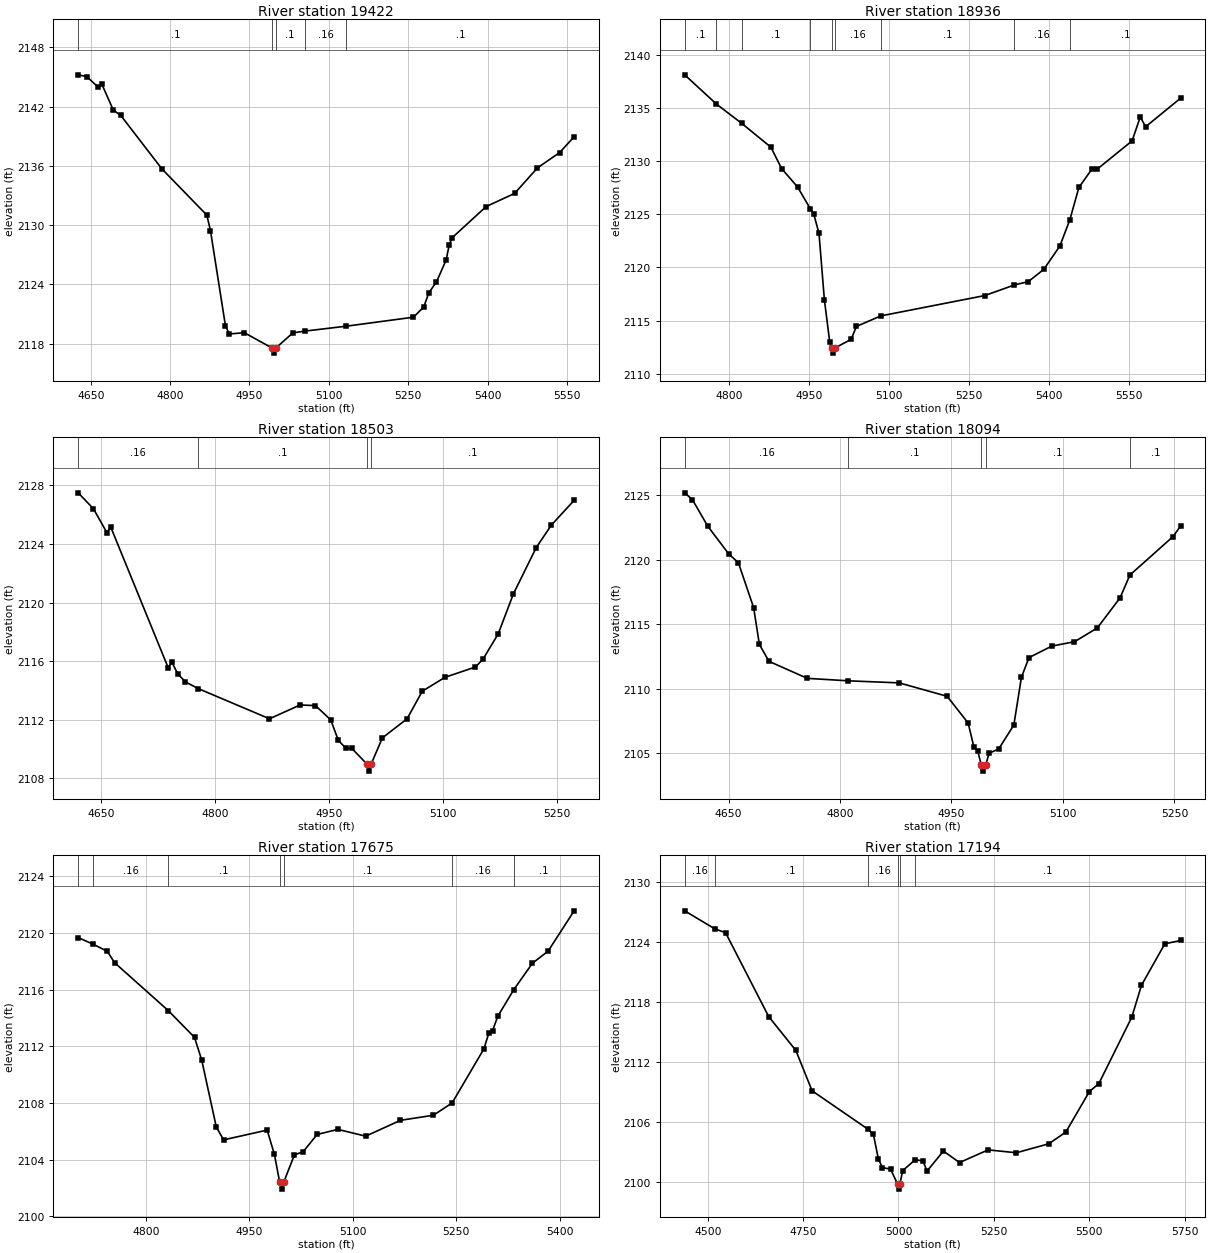
Type RM Length L Ch R = 1 ,19422   ,486,486,486
BEGIN DESCRIPTION:
UNT 0085 IN HEWA 40.0
END DESCRIPTION:
XS GIS Cut Line= 3
      2633359.05     10087026.63      2632895.51     10086594.34
      2632614.29     10086479.76
#Sta/Elev= 30
  4626.3 2145.23  4642.7 2145.04  4664.2 2143.97  4671.1 2144.27  4692.6 2141.66
  4706.7 2141.12  4784.4 2135.71  4869.4 2131.02  4876.3 2129.45  4904.6 2119.82
  4911.9 2118.98  4940.3 2119.11  4993.4 2117.54  4996.2 2117.04  4999.4 2117.54
  5032.1 2119.09  5054.6 2119.27  5133.2 2119.77  5260.1 2120.68  5279.5 2121.72
  5289.3 2123.17  5303.5 2124.25  5321.7 2126.46  5327.6 2127.99    5333 2128.72
  5397.3 2131.88  5451.3 2133.22  5494.5 2135.81  5536.2 2137.35  5563.8 2138.96
#Mann= 5 ,-1 , 0
  4626.3      .1       0  4993.4     .07       0  4999.4      .1       0
  5054.6     .16       0  5133.2      .1       0
Bank Sta=4993.4,4999.4
XS Rating Curve= 0 ,0
Exp/Cntr=0.3,0.1

Type RM Length L Ch R = 1 ,18936   ,433,433,433
BEGIN DESCRIPTION:
UNT 0085 IN HEWA 39.0
END DESCRIPTION:
XS GIS Cut Line= 3
      2633629.84     10086427.67      2633166.34     10086396.42
      2632703.16     10086349.58
#Sta/Elev= 30
  4716.8  2138.1  4776.4 2135.35    4824 2133.53  4878.5  2131.3  4898.6 2129.29
  4928.7 2127.55  4952.2 2125.53  4958.7 2125.05  4968.7  2123.2  4978.8 2116.96
  4988.8 2113.01  4993.1 2112.45  4995.8 2111.95  4999.1 2112.45  5028.9 2113.24
  5038.9 2114.46  5084.8 2115.45  5279.7 2117.36  5334.8 2118.35  5361.2 2118.67
  5390.3 2119.82  5420.4 2122.01  5439.3  2124.5  5456.1 2127.52  5480.7 2129.25
  5490.8 2129.25    5556  2131.9  5571.2 2134.15  5581.3 2133.22  5646.9 2135.91
#Mann= 9 ,-1 , 0
  4716.8      .1       0  4776.4     .16       0    4824      .1       0
  4952.2     .16       0  4993.1     .07       0  4999.1     .16       0
  5084.8      .1       0  5334.8     .16       0  5439.3      .1       0
Bank Sta=4993.1,4999.1
XS Rating Curve= 0 ,0
Exp/Cntr=0.3,0.1

Type RM Length L Ch R = 1 ,18503   ,409,409,409
BEGIN DESCRIPTION:
UNT 0085 IN HEWA 38.0
END DESCRIPTION:
XS GIS Cut Line= 3
      2633618.44     10085953.73      2633218.47     10086003.73
      2632968.46     10086003.73
#Sta/Elev= 30
  4619.5 2127.48  4639.6 2126.39  4657.3 2124.76  4662.3 2125.15  4737.9 2115.56
  4742.9 2115.93  4750.5 2115.14  4760.6 2114.59  4777.5 2114.13  4871.4 2112.07
  4911.7 2113.01  4931.9 2112.97    4952    2112  4962.1 2110.59  4972.2 2110.05
  4979.8 2110.05  4999.4    2109  5002.2  2108.5  5005.4    2109  5020.1 2110.77
  5052.6 2112.07  5072.6 2113.95  5102.6  2114.9  5142.6  2115.6  5152.6 2116.14
  5172.6 2117.86  5192.6 2120.59  5222.6 2123.74  5242.6 2125.28  5272.6 2126.97
#Mann= 4 ,-1 , 0
  4619.5     .16       0  4777.5      .1       0  4999.4     .07       0
  5005.4      .1       0
Bank Sta=4999.4,5005.4
XS Rating Curve= 0 ,0
Exp/Cntr=0.3,0.1

Type RM Length L Ch R = 1 ,18094   ,419,419,419
BEGIN DESCRIPTION:
UNT 0085 IN HEWA 37.0
END DESCRIPTION:
XS GIS Cut Line= 3
      2633668.49     10085703.74      2633268.47     10085603.73
      2633018.46     10085653.73
#Sta/Elev= 30
    4591 2125.17  4601.3 2124.65    4622 2122.59  4650.3 2120.43  4663.2 2119.76
  4683.8 2116.27  4691.5 2113.42  4704.4 2112.11    4756 2110.79  4811.1  2110.6
  4879.6 2110.44  4944.1  2109.4  4972.4 2107.33  4980.1 2105.48  4985.3 2105.16
    4990  2104.1  4992.8  2103.6    4996  2104.1  5000.8 2104.99  5013.5 2105.32
  5033.9 2107.17  5044.1 2110.87  5054.3  2112.4  5084.9 2113.29  5115.5 2113.63
  5146.1 2114.69  5176.7 2117.02  5190.1  2118.8  5248.1 2121.78  5258.3  2122.6
#Mann= 5 ,-1 , 0
    4591     .16       0  4811.1      .1       0    4990     .07       0
    4996      .1       0  5190.1      .1       0
Bank Sta=4990,4996
XS Rating Curve= 0 ,0
Exp/Cntr=0.3,0.1

Type RM Length L Ch R = 1 ,17675   ,481,481,481
BEGIN DESCRIPTION:
UNT 0085 IN HEWA 36.0
END DESCRIPTION:
XS GIS Cut Line= 3
       2633668.5     10085303.74      2633368.47     10085203.73
      2632968.44     10085253.74
#Sta/Elev= 30
  4701.6 2119.68  4723.7  2119.2  4743.8 2118.71  4754.3 2117.91  4832.5 2114.51
  4870.3 2112.63  4880.8 2111.02  4901.9  2106.3  4912.5 2105.39  4975.7 2106.08
  4986.2 2104.36  4993.8 2102.41  4996.5 2101.91  4999.8 2102.41  5015.2 2104.33
  5027.9 2104.55  5048.1 2105.77  5078.3 2106.13  5118.6 2105.65    5169 2106.77
  5216.9 2107.13    5244    2108    5290 2111.81  5297.5 2112.97  5302.6 2113.09
  5310.1 2114.11  5333.4    2116  5360.5 2117.87  5383.2 2118.72    5421 2121.57
#Mann= 7 ,-1 , 0
  4701.6      .1       0  4723.7     .16       0  4832.5      .1       0
  4993.8     .07       0  4999.8      .1       0    5244     .16       0
  5333.4      .1       0
Bank Sta=4993.8,4999.8
XS Rating Curve= 0 ,0
Exp/Cntr=0.3,0.1

Type RM Length L Ch R = 1 ,17194   ,473,473,473
BEGIN DESCRIPTION:
UNT 0085 IN HEWA 35.0
END DESCRIPTION:
XS GIS Cut Line= 3
      2633993.93     10085079.43      2633624.12     10084756.51
      2632863.73     10085032.54
#Sta/Elev= 30
  4439.6 2127.13    4518 2125.34  4546.8 2124.94  4659.7 2116.55  4730.9 2113.16
  4773.6 2109.11  4919.2 2105.29  4934.2 2104.76  4947.2 2102.31  4957.9 2101.42
  4979.1 2101.28  4997.7 2099.77  5000.5 2099.27  5003.7 2099.77    5011 2101.12
  5044.1 2102.22  5064.2 2102.09  5074.9 2101.08  5117.8 2103.08    5160 2101.93
    5235  2103.2  5308.9 2102.91    5394 2103.81  5438.6 2104.98  5500.4 2109.04
  5525.1 2109.83  5611.6 2116.49  5636.9 2119.68  5698.1 2123.83  5739.5 2124.16
#Mann= 6 ,-1 , 0
  4439.6     .16       0    4518      .1       0  4919.2     .16       0
  4997.7     .07       0  5003.7     .16       0  5044.1      .1       0
Bank Sta=4997.7,5003.7
XS Rating Curve= 0 ,0
Exp/Cntr=0.3,0.1

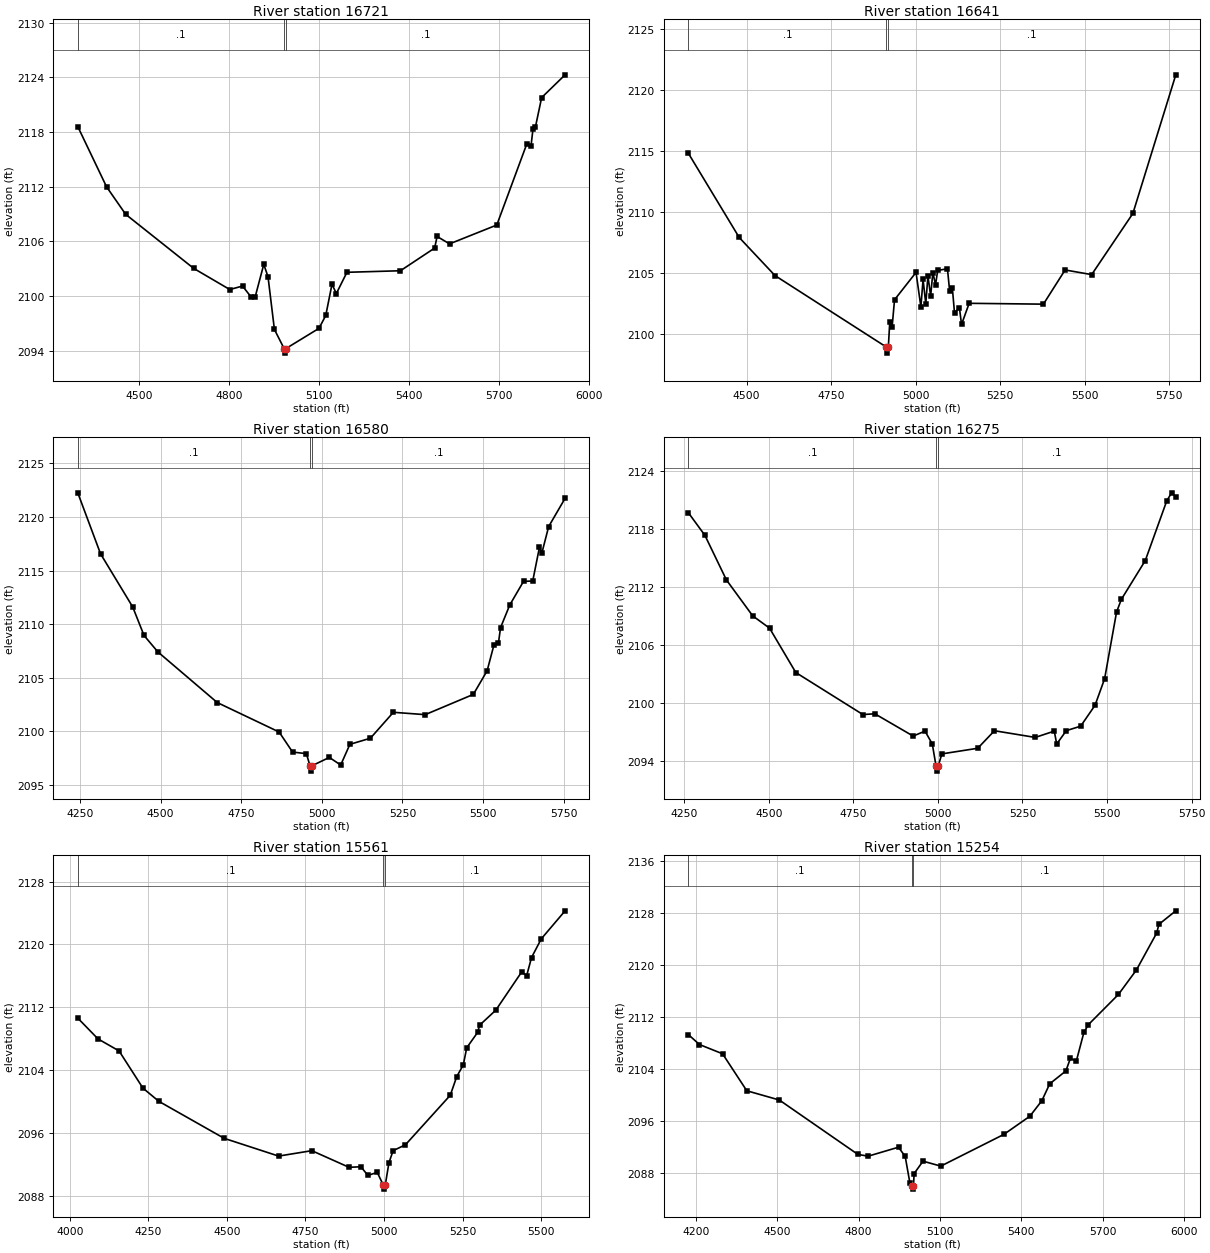
Type RM Length L Ch R = 1 ,16721   ,80,80,80
BEGIN DESCRIPTION:
UNT 0085 IN HEWA 34.0
END DESCRIPTION:
XS GIS Cut Line= 3
      2633886.15     10084891.58      2633375.71     10084388.09
      2632663.88     10083829.04
#Sta/Elev= 30
  4296.9 2118.61  4392.7    2112  4456.4 2108.98  4682.7 2103.05  4802.8 2100.73
  4845.3 2101.11  4873.6 2099.92  4887.7 2099.96    4916 2103.49  4930.1 2102.14
  4951.4 2096.35  4983.7 2094.25  4986.5 2093.75  4989.7 2094.25  5099.8 2096.47
  5122.3 2097.88  5143.1 2101.31  5157.6 2100.29  5192.8 2102.62  5370.9 2102.79
  5484.8 2105.28  5492.9 2106.55  5534.5 2105.74  5691.7 2107.81  5791.2 2116.68
  5805.6  2116.5    5812 2118.31  5820.1 2118.54  5840.9 2121.79    5919 2124.29
#Mann= 3 ,-1 , 0
  4296.9      .1       0  4983.7     .07       0  4989.7      .1       0
Bank Sta=4983.7,4989.7
XS Rating Curve= 0 ,0
Exp/Cntr=0.3,0.1

Type RM Length L Ch R = 1 ,16641   ,61,61,61
BEGIN DESCRIPTION:
Mapping XS 1aa1fac5
END DESCRIPTION:
XS GIS Cut Line= 3
      2633896.53      10084797.8      2633424.32       10084336.
      2632809.76     10083853.38
#Sta/Elev= 30
  4328.1  2114.8  4478.2 2107.92  4584.2  2104.8  4913.5 2098.95  4916.3 2098.45
  4919.5 2098.95  4923.7    2101  4930.7 2100.61  4937.8 2102.82  5001.4 2105.06
  5015.8 2102.24  5022.2 2104.48  5030.3 2102.49  5036.6 2104.78  5044.7 2103.12
  5051.1 2105.05  5059.2 2104.05  5065.5 2105.22  5094.4 2105.36  5100.8 2103.55
  5108.9 2103.78  5115.3 2101.74  5129.7 2102.18  5136.1  2100.8  5158.6 2102.53
  5378.3 2102.46  5442.5 2105.26  5521.1 2104.88  5643.1 2109.89    5770 2121.24
#Mann= 3 ,-1 , 0
  4328.1      .1       0  4913.5     .07       0  4919.5      .1       0
Bank Sta=4913.5,4919.5
XS Rating Curve= 0 ,0
Exp/Cntr=0.3,0.1

Type RM Length L Ch R = 1 ,16580   ,305,305,305
BEGIN DESCRIPTION:
Mapping XS 40041dd1
END DESCRIPTION:
XS GIS Cut Line= 2
      2634031.95     10084780.44      2632886.14     10083794.35
#Sta/Elev= 30
    4243 2122.25  4313.6 2116.56  4413.4  2111.6  4448.5 2108.94  4491.3 2107.41
  4675.6 2102.68  4867.6 2099.93  4909.3 2098.06  4952.1 2097.91  4963.4 2096.78
  4966.1 2096.28  4969.4 2096.78  5023.4 2097.56  5058.6 2096.85  5087.1 2098.78
  5150.7 2099.35    5222 2101.77  5320.8 2101.55    5470 2103.44  5512.8 2105.64
  5533.7 2108.02  5547.9 2108.22  5554.5 2109.67    5583 2111.78  5625.8 2113.99
  5654.3 2114.02  5675.2 2117.17  5682.9 2116.66  5703.7  2119.1  5754.7 2121.74
#Mann= 3 ,-1 , 0
    4243      .1       0  4963.4     .07       0  4969.4      .1       0
Bank Sta=4963.4,4969.4
XS Rating Curve= 0 ,0
Exp/Cntr=0.3,0.1

Type RM Length L Ch R = 1 ,16275   ,714,714,714
BEGIN DESCRIPTION:
UNT 0085 IN HEWA 33.0
END DESCRIPTION:
XS GIS Cut Line= 2
      2634170.82     10084599.86      2633182.35     10083552.43
#Sta/Elev= 30
  4262.9 2119.64  4311.5 2117.32    4375 2112.72  4452.7 2109.01  4502.5 2107.74
  4580.1 2103.16  4778.4 2098.82  4813.6  2098.9  4926.9  2096.6    4962 2097.11
  4983.5 2095.78  4994.7 2093.48  4997.4 2092.98  5000.7 2093.48  5011.8 2094.76
  5117.8 2095.34  5167.2 2097.15  5287.7 2096.46    5344 2097.11  5351.2 2095.78
  5379.6 2097.16    5422 2097.62  5464.5 2099.78  5492.8 2102.52    5528 2109.39
  5542.2 2110.71    5613 2114.72  5676.5 2120.89  5690.7 2121.71  5703.1 2121.31
#Mann= 3 ,-1 , 0
  4262.9      .1       0  4994.7     .07       0  5000.7      .1       0
Bank Sta=4994.7,5000.7
XS Rating Curve= 0 ,0
Exp/Cntr=0.3,0.1

Type RM Length L Ch R = 1 ,15561   ,307,307,307
BEGIN DESCRIPTION:
UNT 0085 IN HEWA 32.0
END DESCRIPTION:
XS GIS Cut Line= 3
      2634197.02     10084381.47      2633707.46     10083391.92
      2633275.21     10083277.35
#Sta/Elev= 30
  4025.3 2110.62  4089.7 2107.97  4156.7 2106.44  4232.7  2101.7  4283.2 2100.02
  4491.4  2095.3  4664.5 2093.04  4770.3 2093.73  4888.8 2091.61  4926.5 2091.68
  4948.8 2090.58  4978.6 2090.96    4998 2089.33  5000.8 2088.83    5004 2089.33
  5015.7 2092.18    5029 2093.73  5068.3 2094.48    5211 2100.79  5231.7 2103.18
  5252.4 2104.65  5263.4 2106.84  5298.4 2108.82  5304.2 2109.71  5355.9 2111.63
  5438.6 2116.52  5454.1 2116.02  5469.7 2118.34  5500.7 2120.72  5576.5 2124.29
#Mann= 3 ,-1 , 0
  4025.3      .1       0    4998     .07       0    5004      .1       0
Bank Sta=4998,5004
XS Rating Curve= 0 ,0
Exp/Cntr=0.3,0.1

Type RM Length L Ch R = 1 ,15254   ,623,623,623
BEGIN DESCRIPTION:
UNT 0085 IN HEWA 31.0
END DESCRIPTION:
XS GIS Cut Line= 3
      2634306.42     10084313.81      2634019.96      10083376.3
      2633296.01     10083001.31
#Sta/Elev= 30
  4173.5 2109.25    4214 2107.73  4299.1 2106.31  4388.4 2100.62  4508.2  2099.2
  4797.7 2090.83  4835.7 2090.56  4947.4 2091.94  4972.1 2090.51  4989.2 2086.48
  4996.6 2085.99  4999.4 2085.49  5002.6 2085.99  5004.9 2087.88  5037.7 2089.79
  5103.3 2089.03  5335.7 2093.91  5431.3  2096.7  5475.5 2099.08  5504.6 2101.69
  5564.1 2103.67  5580.6 2105.59  5602.7  2105.2  5630.5  2109.6    5647 2110.79
  5757.6 2115.43    5824  2119.2  5898.8 2124.89  5906.9 2126.22  5969.1  2128.3
#Mann= 3 ,-1 , 0
  4173.5      .1       0  4996.6     .07       0  5002.6      .1       0
Bank Sta=4996.6,5002.6
XS Rating Curve= 0 ,0
Exp/Cntr=0.3,0.1

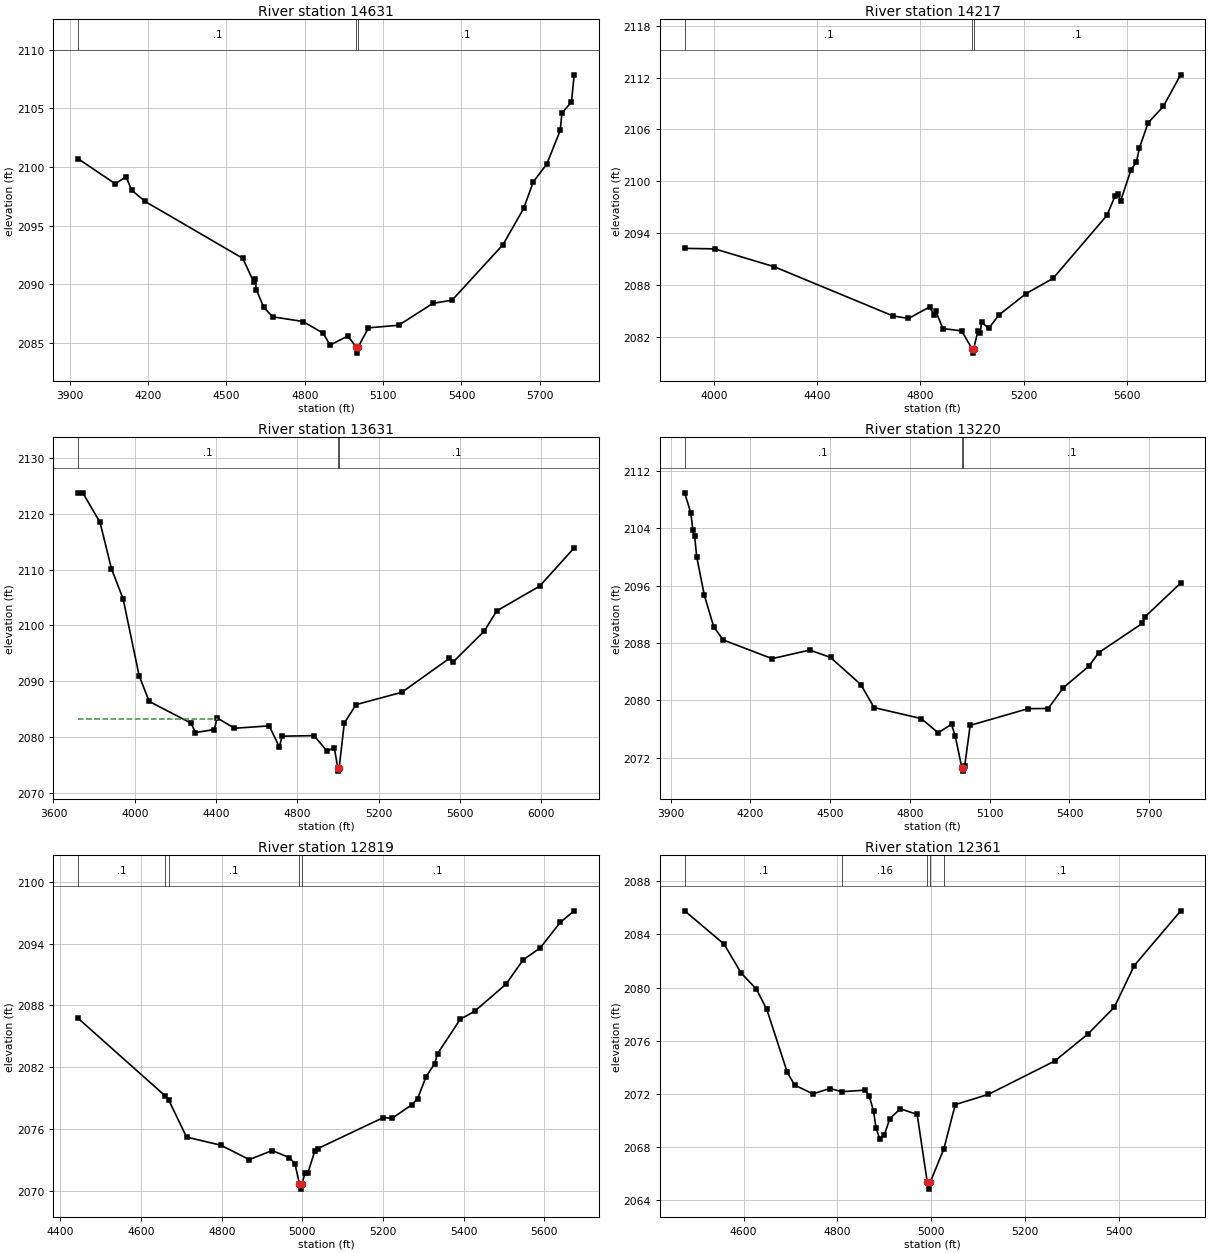
Type RM Length L Ch R = 1 ,14631   ,414,414,414
BEGIN DESCRIPTION:
UNT 0085 IN HEWA 30.0
END DESCRIPTION:
XS GIS Cut Line= 3
      2634439.67     10084120.09      2634674.05      10083291.1
      2633793.21     10082744.37
#Sta/Elev= 30
    3933  2100.7  4074.7 2098.57  4116.3 2099.17  4137.1 2098.03    4189 2097.06
  4563.1  2092.2    4604 2090.22  4609.2 2090.45  4615.1 2089.51  4643.2 2088.02
  4677.2 2087.21  4793.4 2086.81  4870.3 2085.81  4897.4  2084.8  4964.8 2085.57
  4998.1 2084.61  5000.9 2084.11  5004.1 2084.61  5043.9 2086.27  5159.6 2086.49
  5290.7 2088.36    5364 2088.63  5558.8 2093.37  5637.9 2096.46  5674.6 2098.72
  5726.5 2100.25  5777.9 2103.13  5784.4 2104.61    5821 2105.55  5831.2 2107.87
#Mann= 3 ,-1 , 0
    3933      .1       0  4998.1     .07       0  5004.1      .1       0
Bank Sta=4998.1,5004.1
XS Rating Curve= 0 ,0
Exp/Cntr=0.3,0.1

Type RM Length L Ch R = 1 ,14217   ,586,586,586
BEGIN DESCRIPTION:
UNT 0085 IN HEWA 29.0
END DESCRIPTION:
XS GIS Cut Line= 3
       2634808.6      10083790.2      2634799.92      10082956.9
      2633753.89     10082653.07
#Sta/Elev= 30
  3886.5 2092.23    4003 2092.17    4233 2090.11    4693 2084.42  4753.5 2084.11
  4835.9 2085.44  4854.1  2084.5  4859.3    2085  4887.6 2082.94  4959.9 2082.68
  5000.9  2080.6  5003.7  2080.1  5006.9  2080.6  5023.3 2082.67  5032.2 2082.43
  5037.4 2083.69    5065 2082.97  5104.5 2084.51  5210.4    2087  5314.9 2088.76
  5523.2 2096.04  5554.4 2098.25  5564.8 2098.53  5577.1 2097.77  5616.9 2101.34
  5637.7 2102.21  5649.4 2103.86  5682.9 2106.75  5741.9 2108.66  5809.1 2112.32
#Mann= 3 ,-1 , 0
  3886.5      .1       0  5000.9     .07       0  5006.9      .1       0
Bank Sta=5000.9,5006.9
XS Rating Curve= 0 ,0
Exp/Cntr=0.3,0.1

Type RM Length L Ch R = 1 ,13631   ,411,411,411
BEGIN DESCRIPTION:
UNT 0085 IN HEWA 28.0
END DESCRIPTION:
XS GIS Cut Line= 3
      2635736.03     10083217.06      2634584.96     10082295.17
      2633632.66     10082456.48
#Sta/Elev= 30
  3721.8 2123.67  3744.3 2123.79  3829.3 2118.48  3885.4 2110.17    3943 2104.74
  4021.4    2091    4071 2086.37  4277.5 2082.46  4298.3 2080.78  4391.1 2081.32
  4405.6 2083.41  4490.4 2081.55  4661.6 2081.98  4711.3 2078.21  4725.7 2080.13
  4882.5 2080.23  4946.5 2077.43  4981.8 2078.09  4999.6 2074.36  5002.3 2073.86
  5005.6 2074.36  5031.4 2082.49    5089 2085.79  5314.7 2088.01    5548 2094.08
  5568.3 2093.51  5720.4 2098.99  5781.2  2102.6  5992.7 2107.05  6162.4 2113.91
#Mann= 3 ,-1 , 0
  3721.8      .1       0  4999.6     .07       0  5005.6      .1       0
#XS Ineff= 2 , 0
         4402.61 2083.24
Permanent Ineff=
       F       F
Bank Sta=4999.6,5005.6
XS Rating Curve= 0 ,0
Exp/Cntr=0.3,0.1

Type RM Length L Ch R = 1 ,13220   ,401,401,401
BEGIN DESCRIPTION:
UNT 0085 IN HEWA 27.0
END DESCRIPTION:
XS GIS Cut Line= 3
      2635724.35     10082991.28      2634979.59     10082111.11
      2634636.55      10081487.4
#Sta/Elev= 30
  3953.2 2108.94  3976.4 2106.11  3984.1  2103.7  3990.7 2102.89  3998.4 2100.03
    4027 2094.67  4062.1  2090.3  4097.3 2088.44  4281.9 2085.82  4423.6 2087.02
  4501.6 2085.99  4615.9  2082.2  4665.3    2079  4842.2 2077.47  4906.3 2075.49
  4956.5 2076.67  4970.8 2074.98  4995.2 2070.64  4997.9 2070.14  5001.2 2070.64
  5005.9 2070.79  5026.7 2076.52  5244.6 2078.85    5320 2078.87  5377.1 2081.77
  5472.9 2084.77  5510.7 2086.67  5673.6 2090.73  5685.2 2091.69    5818 2096.35
#Mann= 3 ,-1 , 0
  3953.2      .1       0  4995.2     .07       0  5001.2      .1       0
Bank Sta=4995.2,5001.2
XS Rating Curve= 0 ,0
Exp/Cntr=0.3,0.1

Type RM Length L Ch R = 1 ,12819   ,458,458,458
BEGIN DESCRIPTION:
UNT 0085 IN HEWA 26.0
END DESCRIPTION:
XS GIS Cut Line= 3
      2635718.48     10082303.74      2635318.47     10081903.73
      2634852.12     10081431.07
#Sta/Elev= 30
  4444.2 2086.74  4659.4 2079.22  4669.1 2078.76  4712.9  2075.2  4797.8 2074.41
  4868.5 2073.01    4925 2073.89  4967.5 2073.21  4981.6 2072.61  4992.8 2070.64
  4995.5 2070.14  4998.8 2070.64  5006.4 2071.67  5013.4 2071.67  5031.1 2073.88
  5038.1 2074.08  5200.8  2077.1    5222 2077.02  5271.5 2078.34  5285.7 2078.93
  5306.9 2081.09  5328.1 2082.34  5335.1 2083.31  5391.7 2086.67  5427.1 2087.43
  5504.9 2090.07  5547.3 2092.43  5589.7 2093.59  5639.3 2096.07  5673.9  2097.2
#Mann= 5 ,-1 , 0
  4444.2      .1       0  4659.4     .16       0  4669.1      .1       0
  4992.8     .07       0  4998.8      .1       0
Bank Sta=4992.8,4998.8
XS Rating Curve= 0 ,0
Exp/Cntr=0.3,0.1

Type RM Length L Ch R = 1 ,12361   ,371,371,371
BEGIN DESCRIPTION:
UNT 0085 IN HEWA 25.0
END DESCRIPTION:
XS GIS Cut Line= 3
      2635868.47     10082153.74      2635668.47     10081703.73
      2635268.49     10081303.76
#Sta/Elev= 30
  4474.2 2085.78  4558.3 2083.27  4594.6  2081.1  4627.4 2079.87  4649.3 2078.36
  4693.1 2073.61  4708.8 2072.65  4747.8 2071.99    4784 2072.39  4809.9 2072.15
  4859.3 2072.27  4868.2  2071.8  4877.1 2070.69  4882.5 2069.43  4890.1  2068.6
  4900.3  2068.9  4911.9 2070.13  4934.5 2070.86  4970.2 2070.44  4991.9 2065.31
  4994.7 2064.81  4997.9 2065.31  5027.2 2067.85  5051.5 2071.18  5122.2 2071.95
  5263.6 2074.46  5334.3 2076.49  5390.9 2078.52  5433.3 2081.65  5532.3 2085.77
#Mann= 5 ,-1 , 0
  4474.2      .1       0  4809.9     .16       0  4991.9     .07       0
  4997.9     .16       0  5027.2      .1       0
Bank Sta=4991.9,4997.9
XS Rating Curve= 0 ,0
Exp/Cntr=0.3,0.1

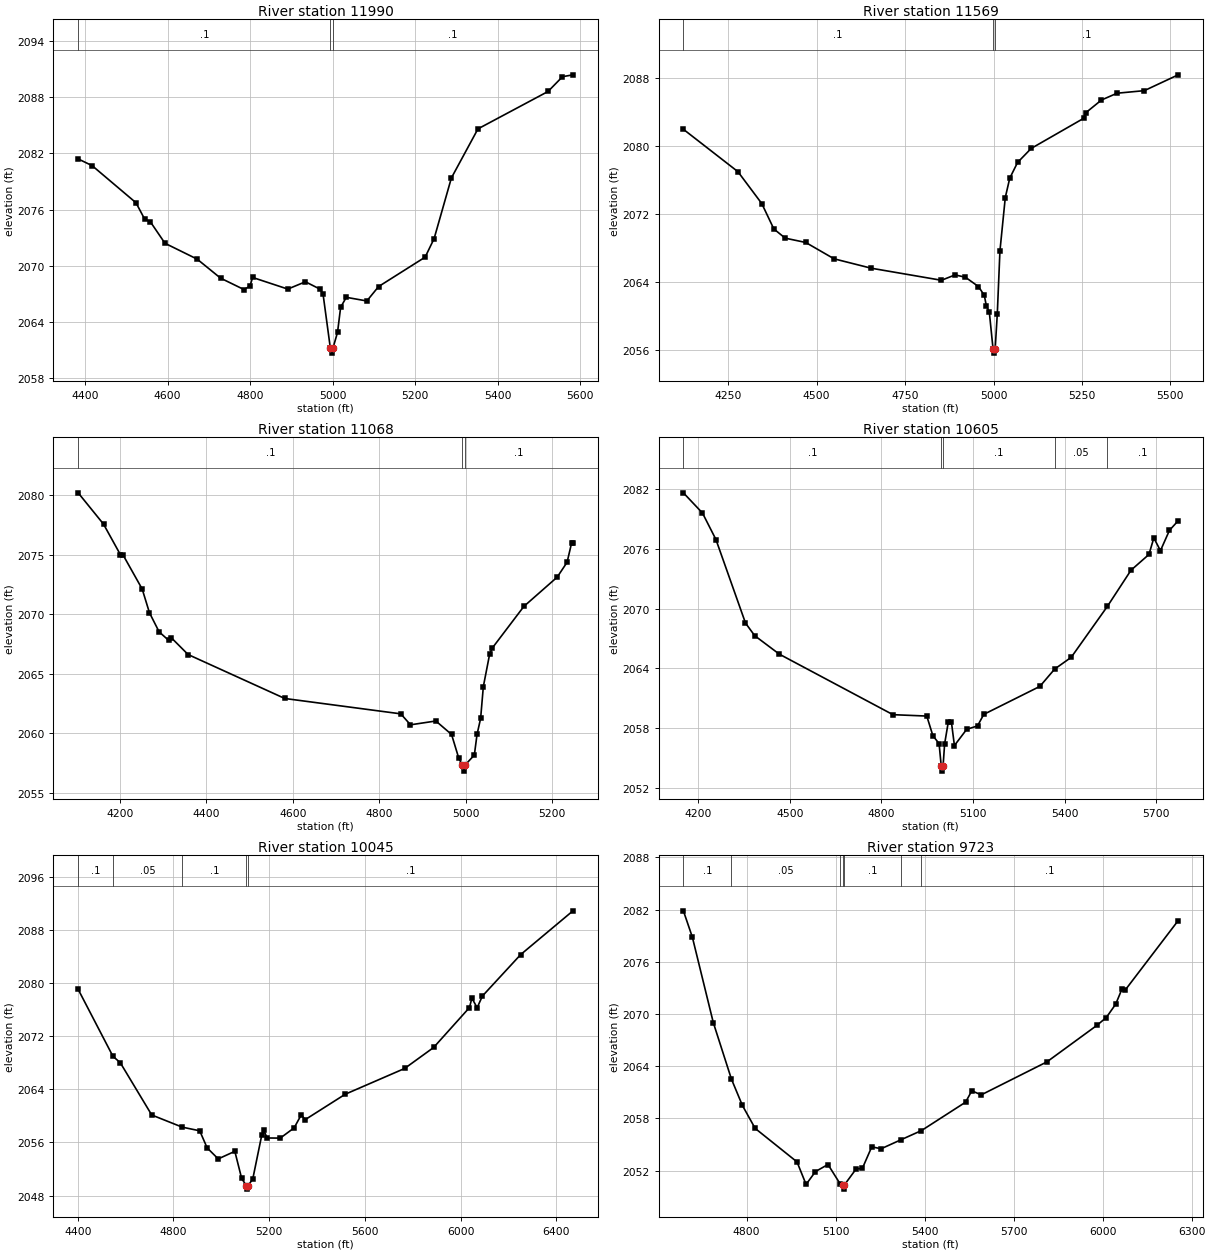
Type RM Length L Ch R = 1 ,11990   ,421,421,421
BEGIN DESCRIPTION:
UNT 0085 IN HEWA 24.0
END DESCRIPTION:
XS GIS Cut Line= 2
       2636353.9     10081815.65      2635458.05     10081018.75
#Sta/Elev= 30
  4383.1 2081.42    4417  2080.7  4523.2 2076.74  4544.1    2075  4558.3 2074.69
  4593.5 2072.41  4671.4 2070.72  4728.1 2068.69  4784.9 2067.47  4799.2 2067.83
  4805.9 2068.76  4891.1 2067.52  4933.8  2068.3  4968.9 2067.52  4976.4 2067.02
  4994.3 2061.18  4997.1 2060.68  5000.3 2061.18  5011.6  2062.9  5019.1 2065.57
  5032.8 2066.64  5082.6 2066.25  5111.1 2067.79  5223.9 2070.93  5245.7 2072.92
  5287.5 2079.39  5351.9 2084.63  5521.6 2088.62  5556.7  2090.2  5582.1  2090.4
#Mann= 3 ,-1 , 0
  4383.1      .1       0  4994.3     .07       0  5000.3      .1       0
Bank Sta=4994.3,5000.3
XS Rating Curve= 0 ,0
Exp/Cntr=0.3,0.1

Type RM Length L Ch R = 1 ,11569   ,501,501,501
BEGIN DESCRIPTION:
UNT 0085 IN HEWA 23.0
END DESCRIPTION:
XS GIS Cut Line= 2
      2636428.62     10081800.42      2635780.94     10080560.38
#Sta/Elev= 30
  4123.2 2081.99  4277.4 2077.01  4344.9 2073.26  4378.9 2070.28  4411.1  2069.2
  4469.2 2068.69  4549.3 2066.77    4654 2065.67  4852.8 2064.25  4891.3 2064.88
  4920.5 2064.61  4957.5 2063.51    4974 2062.48  4979.6 2061.28  4988.2  2060.5
  4998.7 2056.19  5001.5 2055.69  5004.7 2056.19  5010.7 2060.28  5018.2  2067.7
  5033.3 2073.97  5045.9 2076.24    5068 2078.09  5106.5 2079.74  5255.4 2083.29
  5261.1 2083.94  5305.2 2085.43  5349.4 2086.23  5426.4 2086.53  5522.2 2088.39
#Mann= 3 ,-1 , 0
  4123.2      .1       0  4998.7     .07       0  5004.7      .1       0
Bank Sta=4998.7,5004.7
XS Rating Curve= 0 ,0
Exp/Cntr=0.3,0.1

Type RM Length L Ch R = 1 ,11068   ,463,463,463
BEGIN DESCRIPTION:
UNT 0085 IN HEWA 22.0
END DESCRIPTION:
XS GIS Cut Line= 3
      2636868.45     10081603.69      2636468.47     10080803.73
      2636268.45     10080653.72
#Sta/Elev= 30
  4103.6 2080.19  4162.3 2077.56  4201.4 2074.99    4207    2075  4251.7 2072.11
  4268.5 2070.12  4290.8 2068.52  4313.2 2067.79  4318.8 2068.03  4357.9 2066.61
  4581.5 2062.92  4849.8 2061.63  4872.2 2060.71  4930.9 2061.03  4967.2  2059.9
    4984 2057.89  4992.2 2057.32  4994.9 2056.82  4998.2 2057.32  5019.9 2058.17
  5026.1  2059.9  5034.4 2061.24  5040.7 2063.92  5055.3 2066.65  5061.5 2067.16
  5134.4 2070.65  5211.5 2073.11  5234.4 2074.36  5244.9 2075.99    5248 2075.99
#Mann= 3 ,-1 , 0
  4103.6      .1       0  4992.2     .07       0  4998.2      .1       0
Bank Sta=4992.2,4998.2
XS Rating Curve= 0 ,0
Exp/Cntr=0.3,0.1

Type RM Length L Ch R = 1 ,10605   ,560,560,560
BEGIN DESCRIPTION:
UNT 0085 IN HEWA 21.0
END DESCRIPTION:
XS GIS Cut Line= 3
      2637016.05     10081605.92      2636901.47     10080652.77
      2636323.43     10080329.91
#Sta/Elev= 30
  4150.6 2081.62  4213.2 2079.59  4257.3 2076.93  4354.2 2068.54  4384.5 2067.27
    4465 2065.42  4837.6 2059.34  4948.5  2059.2  4968.6 2057.22  4988.8 2056.44
  4995.9 2054.17  4998.6 2053.67  5001.9 2054.17    5007 2056.41    5019  2058.6
  5029.1 2058.63  5039.1 2056.24  5079.4 2057.87  5114.8 2058.21  5135.3 2059.37
  5319.2 2062.18  5367.7 2063.92    5422  2065.1  5540.4 2070.21    5618 2073.85
  5676.8 2075.43  5692.8 2077.09  5714.5 2075.81    5744 2077.85  5772.7 2078.82
#Mann= 5 ,-1 , 0
  4150.6      .1       0  4995.9     .07       0  5001.9      .1       0
  5367.7     .05       0  5540.4      .1       0
Bank Sta=4995.9,5001.9
XS Rating Curve= 0 ,0
Exp/Cntr=0.3,0.1

Type RM Length L Ch R = 1 ,10045   ,322,322,322
BEGIN DESCRIPTION:
UNT 0085 IN HEWA 20.0
END DESCRIPTION:
XS GIS Cut Line= 3
      2637984.76     10080715.26      2637495.22     10080579.86
      2636073.39     10079939.25
#Sta/Elev= 30
  4401.7 2079.05  4546.8 2068.99  4577.8    2068  4709.1 2060.14  4836.5 2058.31
  4909.6 2057.76  4940.6 2055.19  4986.9 2053.53  5056.3 2054.67  5084.9 2050.58
    5105 2049.48  5107.8 2048.98    5111 2049.48  5131.2  2050.5  5169.3  2057.2
  5177.5 2057.81  5191.2 2056.68  5246.1 2056.66  5304.1  2058.2  5333.8 2060.16
  5350.4 2059.44  5517.9 2063.27  5765.7 2067.14  5886.9  2070.3  6036.7 2076.31
  6046.7 2077.74  6068.7 2076.28  6090.6 2078.04  6250.5 2084.28  6469.1 2090.87
#Mann= 5 ,-1 , 0
  4401.7      .1       0  4546.8     .05       0  4836.5      .1       0
    5105     .07       0    5111      .1       0
Bank Sta=5105,5111
XS Rating Curve= 0 ,0
Exp/Cntr=0.3,0.1

Type RM Length L Ch R = 1 ,9723    ,483,483,483
BEGIN DESCRIPTION:
UNT 0085 IN HEWA 19.0
END DESCRIPTION:
XS GIS Cut Line= 3
      2638018.46     10080353.73      2637618.47     10080303.73
      2636418.48     10079903.74
#Sta/Elev= 30
  4586.7 2081.85  4616.9 2078.83  4687.5 2069.01  4748.6 2062.52  4785.7 2059.48
  4828.6 2056.85  4969.7    2053  5000.3 2050.41    5032 2051.89  5074.1  2052.7
  5115.6 2050.45  5123.8 2050.37  5126.6 2049.87  5129.8 2050.37    5169 2052.19
  5190.1 2052.26  5221.7 2054.73  5253.3 2054.51  5318.7 2055.52  5389.3  2056.6
  5537.9 2059.86    5559 2061.17  5590.6  2060.7    5812 2064.49  5980.7 2068.69
  6012.3 2069.59  6043.9 2071.12    6065 2072.85  6075.5 2072.72  6254.7 2080.73
#Mann= 7 ,-1 , 0
  4586.7      .1       0  4748.6     .05       0  5115.6      .1       0
  5123.8    .035       0  5129.8      .1       0  5318.7     .05       0
  5389.3      .1       0
Bank Sta=5123.8,5129.8
XS Rating Curve= 0 ,0
Exp/Cntr=0.3,0.1