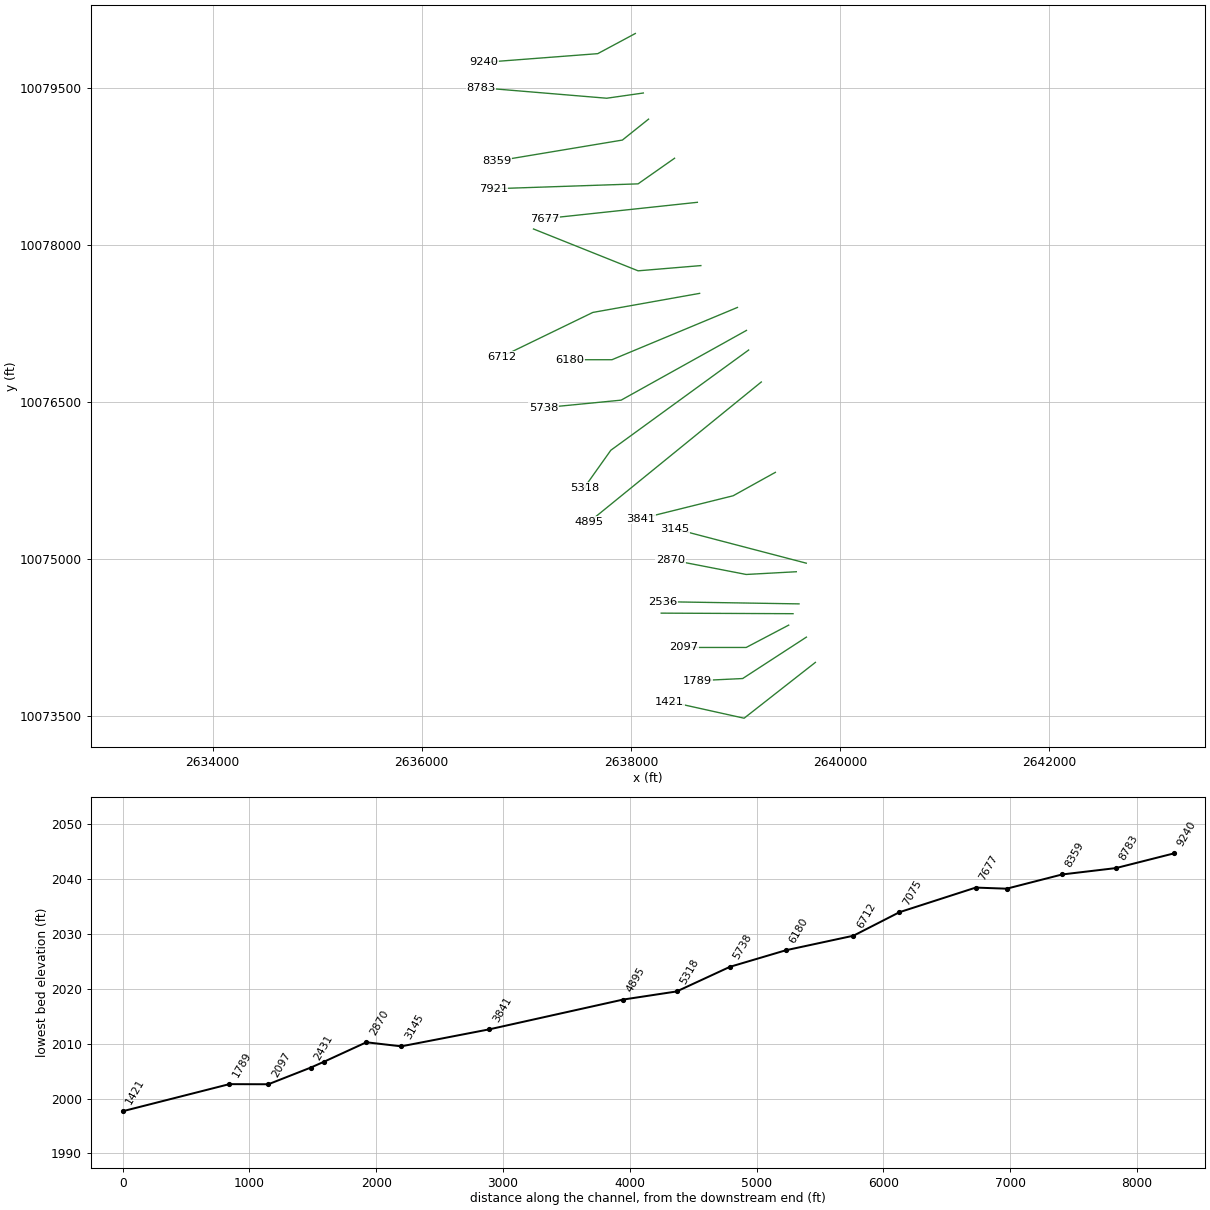
HEC-RAS study UNT 0085 IN HEWA.prj: UNT 0085 IN HEWA Base Level Engineering

--- UNT 0085 IN HEWA.g01 (geometry) --- (continued)

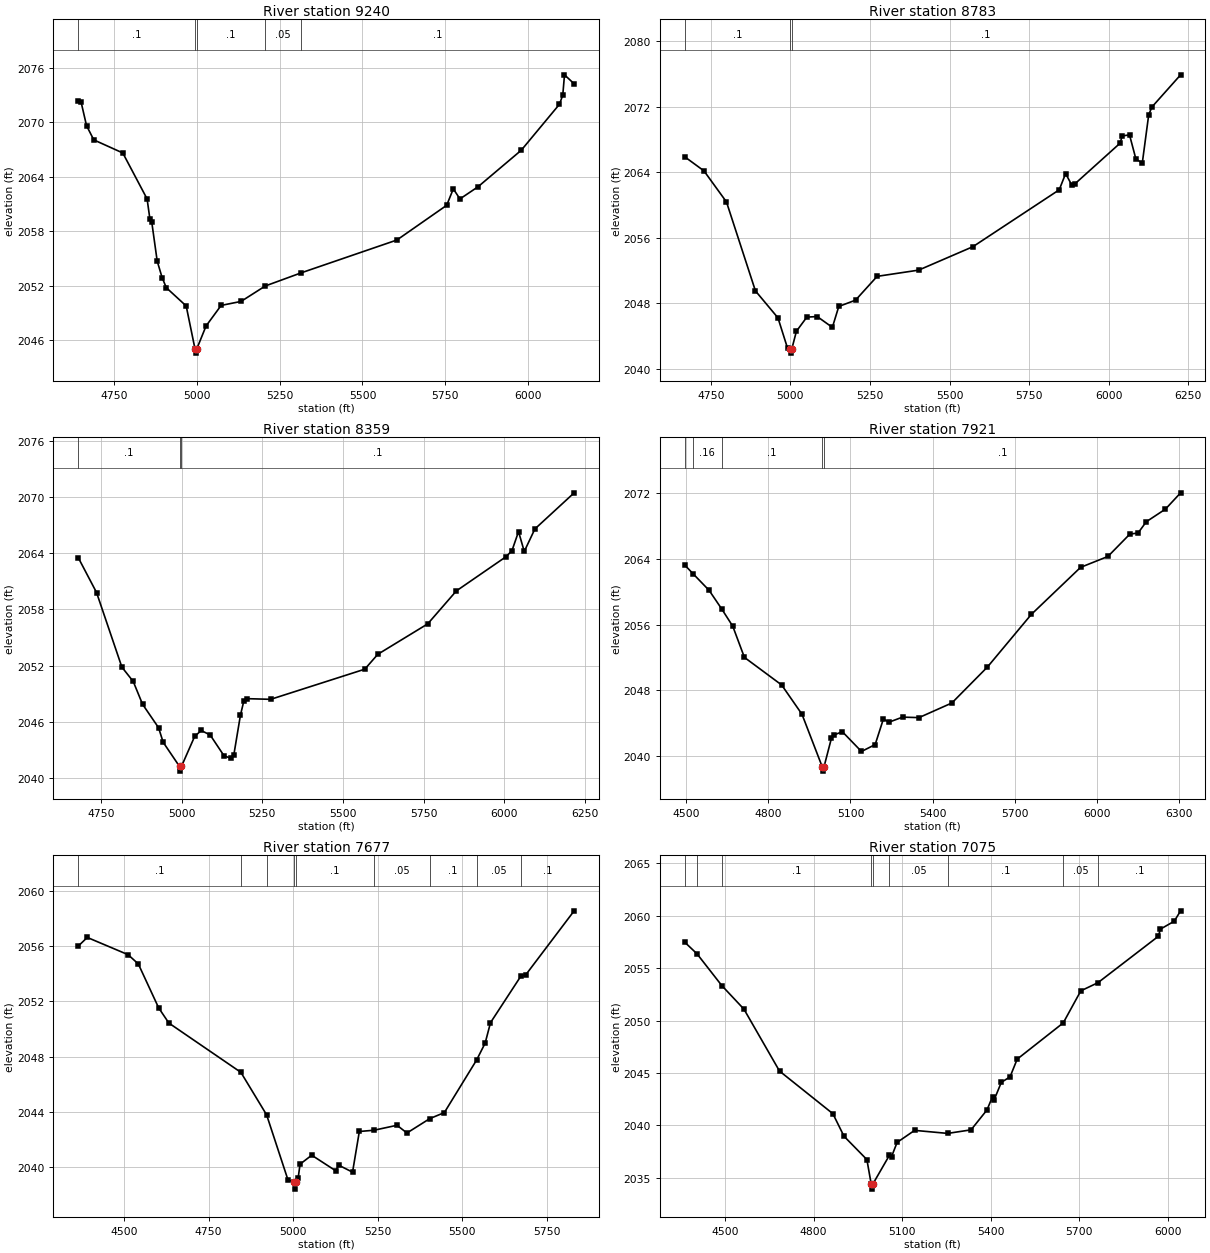
Type RM Length L Ch R = 1 ,9240    ,457,457,457
BEGIN DESCRIPTION:
UNT 0085 IN HEWA 18.0
END DESCRIPTION:
XS GIS Cut Line= 3
      2638042.08     10080022.56      2637682.72     10079829.86
      2636594.17     10079746.52
#Sta/Elev= 30
  4640.5 2072.36  4649.4 2072.21  4665.7 2069.64  4687.6 2068.08  4775.3 2066.64
  4848.8 2061.58  4857.4 2059.33    4863    2059  4879.3 2054.74  4894.2 2052.92
  4906.9 2051.81    4967  2049.8  4993.4 2045.11  4996.1 2044.61  4999.4 2045.11
  5027.1  2047.6  5072.6 2049.86  5132.8  2050.3  5206.1    2052  5314.9 2053.45
  5604.1 2057.06  5754.6 2060.88  5774.6 2062.69  5794.7 2061.58  5849.4 2062.92
  5980.1 2066.94  6095.6    2072  6105.6 2073.01  6110.8 2075.24    6140 2074.25
#Mann= 5 ,-1 , 0
  4640.5      .1       0  4993.4     .07       0  4999.4      .1       0
  5206.1     .05       0  5314.9      .1       0
Bank Sta=4993.4,4999.4
XS Rating Curve= 0 ,0
Exp/Cntr=0.3,0.1

Type RM Length L Ch R = 1 ,8783    ,424,424,424
BEGIN DESCRIPTION:
UNT 0085 IN HEWA 17.0
END DESCRIPTION:
XS GIS Cut Line= 3
      2638118.48     10079453.73      2637768.47     10079403.73
      2636568.49     10079503.73
#Sta/Elev= 30
  4667.9 2065.88  4728.5 2064.16  4799.2 2060.37  4890.1 2049.53  4960.9 2046.24
  4991.2 2042.51  4998.3 2042.44    5001 2041.94  5004.3 2042.44  5018.9 2044.61
  5051.6 2046.33  5084.2  2046.4  5131.8 2045.08  5151.9 2047.63  5204.6  2048.4
  5272.3  2051.3  5402.8 2052.06  5573.4 2054.92  5844.3 2061.85  5864.4 2063.83
  5884.4 2062.38  5894.5 2062.61    6035 2067.52  6042.5 2068.42  6065.1 2068.55
  6085.1 2065.61  6105.2 2065.11  6125.3 2070.98  6135.3 2071.94  6225.6 2075.87
#Mann= 3 ,-1 , 0
  4667.9      .1       0  4998.3     .07       0  5004.3      .1       0
Bank Sta=4998.3,5004.3
XS Rating Curve= 0 ,0
Exp/Cntr=0.3,0.1

Type RM Length L Ch R = 1 ,8359    ,438,438,438
BEGIN DESCRIPTION:
UNT 0085 IN HEWA 16.0
END DESCRIPTION:
XS GIS Cut Line= 3
      2638168.46     10079203.73      2637918.47     10079003.73
      2636718.47     10078803.73
#Sta/Elev= 30
  4679.9 2063.53  4736.7 2059.81  4815.2 2051.86  4850.4 2050.33  4879.2 2047.91
  4928.8 2045.41  4943.2 2043.85  4993.8 2041.28  4996.6 2040.78  4999.8 2041.28
  5040.6 2044.47  5060.9 2045.11  5088.8 2044.63  5131.8 2042.41  5154.7 2042.13
  5162.3 2042.55  5182.5 2046.73  5192.7  2048.2  5202.8  2048.5  5276.3 2048.43
  5567.8 2051.64  5608.3 2053.23  5762.9 2056.47  5851.6 2059.98  6006.2 2063.64
    6024 2064.28  6044.3  2066.3    6062 2064.18  6094.9 2066.58  6216.6 2070.43
#Mann= 3 ,-1 , 0
  4679.9      .1       0  4993.8     .07       0  4999.8      .1       0
Bank Sta=4993.8,4999.8
XS Rating Curve= 0 ,0
Exp/Cntr=0.3,0.1

Type RM Length L Ch R = 1 ,7921    ,244,244,244
BEGIN DESCRIPTION:
UNT 0085 IN HEWA 15.0
END DESCRIPTION:
XS GIS Cut Line= 3
      2638417.06     10078829.84      2638068.13     10078585.06
      2636683.05      10078538.2
#Sta/Elev= 30
  4494.2 2063.27  4524.1 2062.23  4583.6 2060.18  4629.1 2057.94  4669.9 2055.82
  4712.4 2052.03  4848.6 2048.67  4922.8 2045.11  4997.1 2038.69  4999.9 2038.19
  5003.1 2038.69  5030.2 2042.17  5040.2 2042.59  5070.2 2042.99  5140.2 2040.58
  5190.2 2041.42  5220.3 2044.54  5240.3 2044.14  5290.3 2044.76  5350.3  2044.7
  5470.4 2046.48  5600.5 2050.86  5760.6 2057.25  5940.7 2062.98  6040.7 2064.31
  6120.8 2067.03  6150.8 2067.16  6180.8 2068.53  6250.9 2070.07  6306.3 2072.05
#Mann= 5 ,-1 , 0
  4494.2      .1       0  4524.1     .16       0  4629.1      .1       0
  4997.1     .07       0  5003.1      .1       0
Bank Sta=4997.1,5003.1
XS Rating Curve= 0 ,0
Exp/Cntr=0.3,0.1

Type RM Length L Ch R = 1 ,7677    ,602,602,602
BEGIN DESCRIPTION:
UNT 0085 IN HEWA 14.0
END DESCRIPTION:
XS GIS Cut Line= 2
      2638635.11     10078408.71      2637176.75     10078252.46
#Sta/Elev= 30
  4364.5 2056.01  4391.3 2056.64    4512 2055.39  4542.2 2054.72  4602.5 2051.53
  4632.7 2050.43  4845.5 2046.86  4921.6 2043.78  4984.7 2039.07  5001.8 2038.89
  5004.5 2038.39  5007.8 2038.89  5014.8 2039.17  5020.6  2040.2  5055.1 2040.85
  5125.5 2039.73  5135.5 2040.12  5175.8 2039.62  5195.9 2042.57  5239.1 2042.66
  5307.3 2043.02  5336.7 2042.46    5404  2043.5  5447.3 2043.94  5542.9 2047.76
    5568 2048.98  5583.8 2050.46  5673.5 2053.83  5688.7 2053.95  5831.2 2058.57
#Mann= 9 ,-1 , 0
  4364.5      .1       0  4845.5     .16       0  4921.6      .1       0
  5001.8     .07       0  5007.8      .1       0  5239.1     .05       0
    5404      .1       0  5542.9     .05       0  5673.5      .1       0
Bank Sta=5001.8,5007.8
XS Rating Curve= 0 ,0
Exp/Cntr=0.3,0.1

Type RM Length L Ch R = 1 ,7075    ,363,363,363
BEGIN DESCRIPTION:
UNT 0085 IN HEWA 13.0
END DESCRIPTION:
XS GIS Cut Line= 3
       2638668.5     10077803.73      2638068.47     10077753.73
      2637068.51     10078153.72
#Sta/Elev= 30
  4363.7 2057.49  4405.3 2056.38  4489.2 2053.35  4564.4 2051.09  4684.8 2045.18
  4865.5 2041.11  4903.1 2038.96  4980.6 2036.73  4995.1 2034.41  4997.9 2033.91
  5001.1 2034.41  5057.1 2037.15  5064.1 2037.01  5082.9 2038.37  5142.2 2039.52
  5254.1 2039.23  5333.3 2039.57  5387.2 2041.47    5406 2042.74  5411.4 2042.43
  5435.7  2044.1  5465.3 2044.63  5489.5 2046.32  5645.4 2049.78  5704.9 2052.84
    5763 2053.62  5967.5 2058.05  5974.2 2058.73  6021.3 2059.49  6042.8 2060.48
#Mann= 9 ,-1 , 0
  4363.7      .1       0  4405.3     .16       0  4489.2      .1       0
  4995.1     .07       0  5001.1      .1       0  5057.1     .05       0
  5254.1      .1       0  5645.4     .05       0    5763      .1       0
Bank Sta=4995.1,5001.1
XS Rating Curve= 0 ,0
Exp/Cntr=0.3,0.1

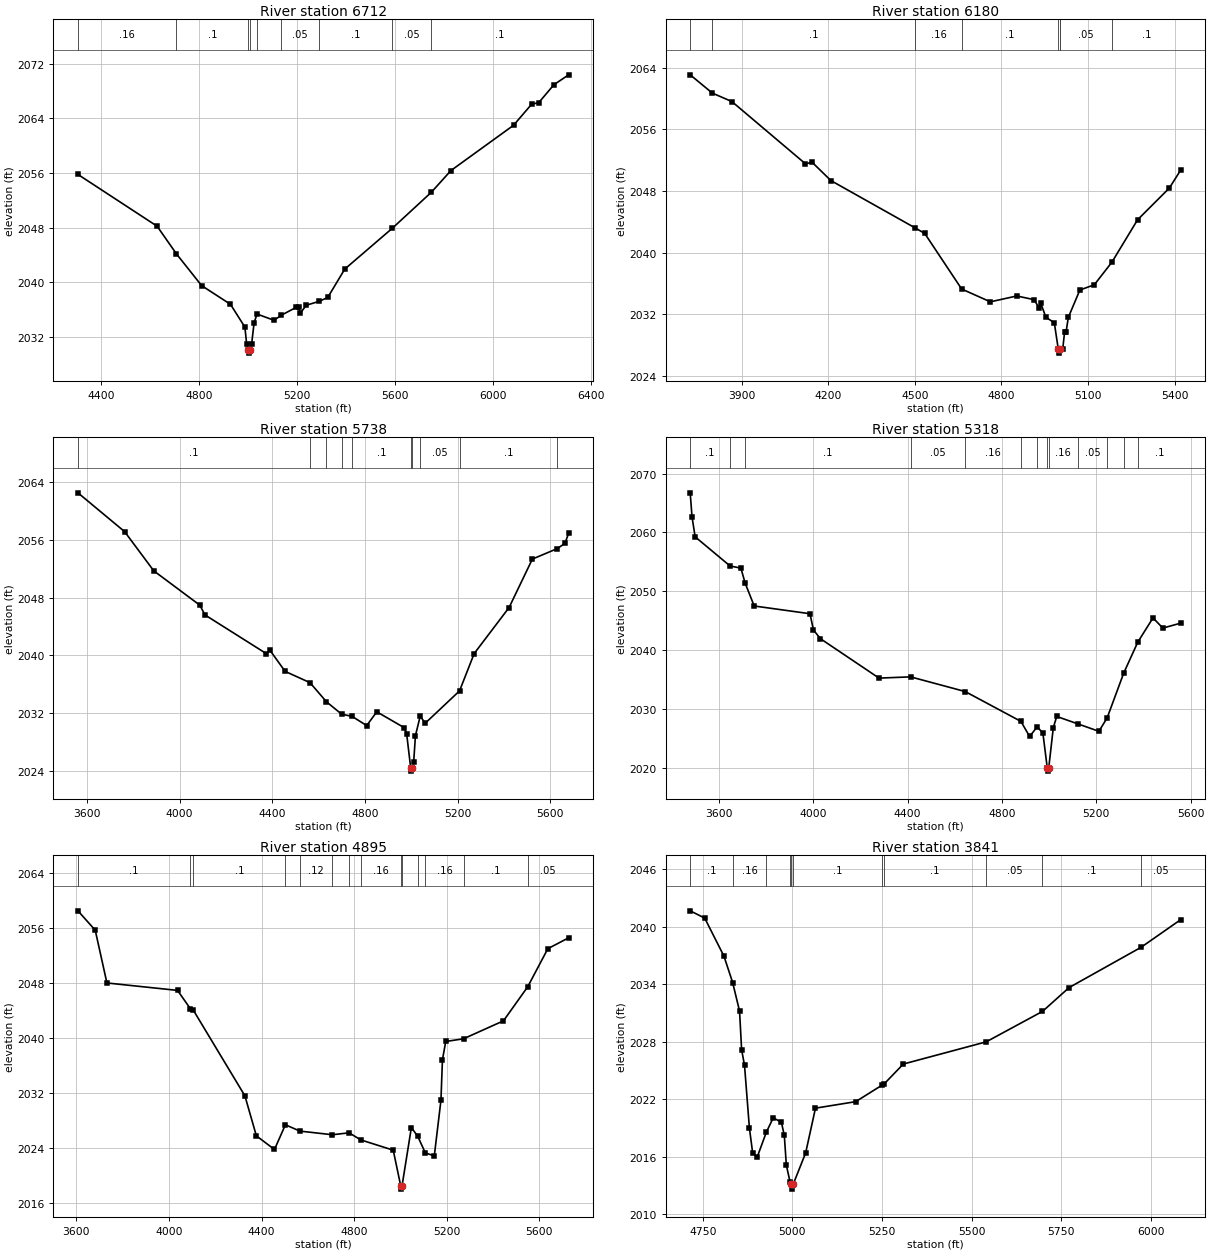
Type RM Length L Ch R = 1 ,6712    ,532,532,532
BEGIN DESCRIPTION:
UNT 0085 IN HEWA 12.0
END DESCRIPTION:
XS GIS Cut Line= 3
      2638656.68     10077538.19      2637635.84      10077355.9
      2636766.04     10076934.02
#Sta/Elev= 30
  4305.1  2055.8  4628.3 2048.22  4707.4 2044.16  4810.1 2039.52  4927.9 2036.78
  4986.8 2033.44    4994 2030.96  5001.2 2030.13  5003.9 2029.63  5007.2 2030.13
  5014.4    2031  5024.5  2034.1  5036.5 2035.35  5105.8 2034.44  5135.9 2035.19
  5197.2 2036.35  5207.2 2036.33  5212.3 2035.45  5237.8 2036.65    5290 2037.21
  5325.1 2037.78  5394.7 2041.94  5588.2  2047.9  5747.9 2053.18  5828.2 2056.37
  6083.8    2063  6158.3 2066.11  6186.4  2066.3  6248.6 2068.94  6308.8 2070.39
#Mann= 9 ,-1 , 0
  4305.1     .16       0  4707.4      .1       0  5001.2     .07       0
  5007.2      .1       0  5036.5     .16       0  5135.9     .05       0
    5290      .1       0  5588.2     .05       0  5747.9      .1       0
Bank Sta=5001.2,5007.2
XS Rating Curve= 0 ,0
Exp/Cntr=0.3,0.1

Type RM Length L Ch R = 1 ,6180    ,442,442,442
BEGIN DESCRIPTION:
UNT 0085 IN HEWA 11.0
END DESCRIPTION:
XS GIS Cut Line= 3
      2639018.44     10077403.72      2637818.47     10076903.73
      2637418.44     10076903.73
#Sta/Elev= 30
    3722 2063.07  3798.8  2060.7  3866.6  2059.6  4121.2 2051.54  4144.5 2051.73
  4209.5 2049.36  4501.5 2043.22  4534.5 2042.51  4662.5  2035.3    4762 2033.64
  4853.5  2034.4  4913.6 2033.92  4930.4 2032.85  4935.8 2033.53  4954.3 2031.64
  4983.5 2030.93  4997.3 2027.49  5000.1 2026.99  5003.3 2027.49  5004.3 2027.55
  5012.8 2027.58  5019.3 2029.79  5024.5 2029.79    5032 2031.62    5072 2035.17
    5122 2035.85    5183 2038.78    5272 2044.28    5382 2048.39    5422 2050.76
#Mann= 8 ,-1 , 0
    3722     .16       0  3798.8      .1       0  4501.5     .16       0
  4662.5      .1       0  4997.3     .07       0  5003.3      .1       0
  5004.3     .05       0    5183      .1       0
Bank Sta=4997.3,5003.3
XS Rating Curve= 0 ,0
Exp/Cntr=0.3,0.1

Type RM Length L Ch R = 1 ,5738    ,420,420,420
BEGIN DESCRIPTION:
UNT 0085 IN HEWA 10.0
END DESCRIPTION:
XS GIS Cut Line= 3
      2639104.57     10077184.01      2637906.67     10076517.36
      2637162.64     10076444.51
#Sta/Elev= 30
  3560.9 2062.53  3762.5 2057.15  3888.3 2051.72  4087.2 2046.96    4109 2045.62
  4374.2 2040.25  4390.2  2040.7  4455.4 2037.79  4562.6 2036.23  4633.8 2033.58
  4699.3 2031.86  4744.1 2031.56  4807.6 2030.28    4851 2032.19  4970.2 2029.98
  4980.2  2029.1  4997.3 2024.47  5000.1 2023.97  5003.3 2024.47  5010.4 2025.22
  5017.9 2028.87  5038.4 2031.57  5060.6 2030.62  5208.4 2035.09  5271.6 2040.26
  5422.3 2046.64  5522.8 2053.35  5630.1  2054.8  5663.5 2055.53  5679.4 2056.93
#Mann= 10 ,-1 , 0
  3560.9      .1       0  4562.6     .16       0  4633.8      .1       0
  4699.3     .16       0  4744.1      .1       0  4997.3     .07       0
  5003.3      .1       0  5038.4     .05       0  5208.4      .1       0
  5630.1     .05       0
Bank Sta=4997.3,5003.3
XS Rating Curve= 0 ,0
Exp/Cntr=0.3,0.1

Type RM Length L Ch R = 1 ,5318    ,423,423,423
BEGIN DESCRIPTION:
UNT 0085 IN HEWA 9.0
END DESCRIPTION:
XS GIS Cut Line= 4
      2639125.43     10076996.53      2637807.72     10076038.19
      2637552.51     10075678.81      2637562.88     10075678.81
#Sta/Elev= 30
    3478 2066.73  3485.8 2062.63    3499 2059.26  3647.2 2054.31    3693 2053.95
  3710.9 2051.41  3749.4 2047.52  3985.9 2046.21  4000.5 2043.46  4029.9 2041.98
  4278.7 2035.28  4412.4 2035.49  4643.9    2033  4880.4 2027.93  4917.1 2025.37
  4949.5 2027.02  4973.5 2025.92  4992.1 2019.99  4994.9 2019.49  4998.1 2019.99
  5017.6 2026.88  5032.2 2028.77  5120.2 2027.53  5210.9 2026.25  5245.9 2028.53
  5315.9 2036.11  5375.8 2041.39  5440.3  2045.5  5482.1 2043.77  5558.5 2044.62
#Mann= 13 ,-1 , 0
    3478      .1       0  3647.2     .16       0  3710.9      .1       0
  4412.4     .05       0  4643.9     .16       0  4880.4      .1       0
  4949.5     .16       0  4992.1     .07       0  4998.1     .16       0
  5120.2     .05       0  5245.9      .1       0  5315.9     .05       0
  5375.8      .1       0
Bank Sta=4992.1,4998.1
XS Rating Curve= 0 ,0
Exp/Cntr=0.3,0.1

Type RM Length L Ch R = 1 ,4895    ,1054,1054,1054
BEGIN DESCRIPTION:
UNT 0085 IN HEWA 8.0
END DESCRIPTION:
XS GIS Cut Line= 2
      2639246.41     10076690.99      2637601.99      10075353.6
#Sta/Elev= 30
  3606.8 2058.44  3681.5 2055.62  3731.9 2047.96  4037.1 2046.88  4091.9 2044.24
  4105.7 2043.98    4328 2031.56  4377.5 2025.75  4455.8 2023.77  4502.9 2027.36
  4565.5 2026.44  4705.9 2025.91    4778 2026.19  4828.7 2025.16  4968.7 2023.67
  5000.9 2018.51  5003.6 2018.01  5006.9 2018.51    5047 2026.95  5074.3  2025.7
  5107.5 2023.26  5146.1 2022.85  5174.8 2030.91  5181.3 2036.82  5195.6 2039.46
  5272.3 2039.85  5444.9 2042.46  5549.5  2047.4  5636.6 2052.94  5726.4 2054.52
#Mann= 14 ,-1 , 0
  3606.8      .1       0  4091.9     .16       0  4105.7      .1       0
  4502.9     .16       0  4565.5     .12       0  4705.9     .16       0
    4778     .12       0  4828.7     .16       0  5000.9     .07       0
  5006.9     .16       0  5074.3      .1       0  5107.5     .16       0
  5272.3      .1       0  5549.5     .05       0
Bank Sta=5000.9,5006.9
XS Rating Curve= 0 ,0
Exp/Cntr=0.3,0.1

Type RM Length L Ch R = 1 ,3841    ,696,696,696
BEGIN DESCRIPTION:
UNT 0085 IN HEWA 7.0
END DESCRIPTION:
XS GIS Cut Line= 3
      2639380.96     10075827.18      2638977.31     10075603.22
      2638097.11     10075384.47
#Sta/Elev= 30
  4714.9 2041.68  4755.4 2040.92  4809.1 2036.94  4833.3 2034.19  4852.6  2031.2
  4858.3 2027.17  4866.4 2025.54  4880.1 2018.96  4889.3 2016.34  4901.8 2015.95
  4927.3 2018.55  4946.5 2020.05  4969.3 2019.59  4977.4 2018.21  4983.1  2015.1
  4993.5 2013.34  4996.1  2013.1  4998.9  2012.6  5002.1  2013.1  5036.9 2016.38
  5064.3 2021.06  5176.5 2021.74  5250.7 2023.48  5255.3 2023.57  5309.3 2025.67
  5540.5 2027.99  5697.5 2031.17  5771.7 2033.66  5972.5 2037.87  6083.5 2040.77
#Mann= 11 ,-1 , 0
  4714.9      .1       0  4833.3     .16       0  4927.3     .05       0
  4993.5      .1       0  4996.1     .07       0  5002.1      .1       0
  5250.7     .05       0  5255.3      .1       0  5540.5     .05       0
  5697.5      .1       0  5972.5     .05       0
Bank Sta=4996.1,5002.1
XS Rating Curve= 0 ,0
Exp/Cntr=0.3,0.1

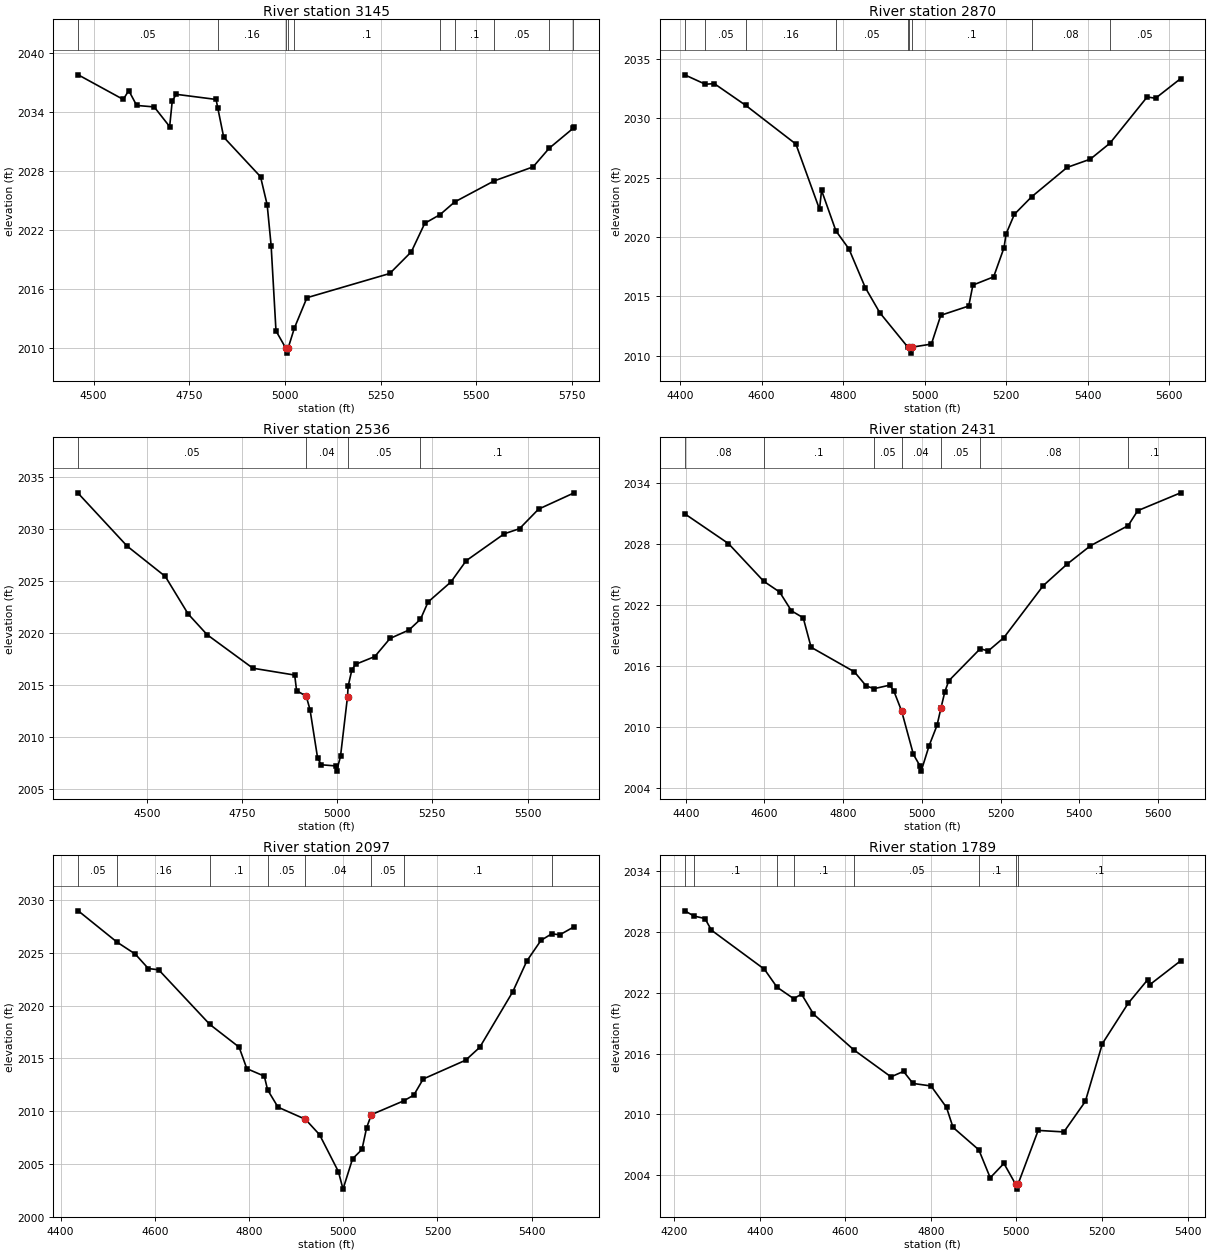
Type RM Length L Ch R = 1 ,3145    ,275,275,275
BEGIN DESCRIPTION:
UNT 0085 IN HEWA 6.0
END DESCRIPTION:
XS GIS Cut Line= 2
       2639676.3     10074958.71      2638422.24     10075286.53
#Sta/Elev= 30
  4459.7 2037.77  4577.4 2035.27  4591.8 2036.17  4612.5 2034.66  4658.3 2034.51
  4698.7 2032.51  4705.5 2035.13  4715.9 2035.79    4820 2035.27  4824.3 2034.44
  4839.9 2031.44  4936.2 2027.42  4953.6 2024.56  4963.9 2020.43  4976.6 2011.76
  5002.3    2010    5005  2009.5  5008.3    2010  5024.6 2012.04  5057.5 2015.13
    5274 2017.59  5330.3 2019.79  5365.5 2022.69  5405.4 2023.57  5443.4 2024.85
  5546.6 2026.99  5648.6 2028.42  5690.6 2030.31    5753 2032.33  5755.9 2032.52
#Mann= 10 ,-1 , 0
  4459.7     .05       0  4824.3     .16       0  5002.3     .07       0
  5008.3     .16       0  5024.6      .1       0  5405.4     .05       0
  5443.4      .1       0  5546.6     .05       0  5690.6      .1       0
    5753     .05       0
Bank Sta=5002.3,5008.3
XS Rating Curve= 0 ,0
Exp/Cntr=0.3,0.1

Type RM Length L Ch R = 1 ,2870    ,334,334,334
BEGIN DESCRIPTION:
UNT 0085 IN HEWA 5.0
END DESCRIPTION:
XS GIS Cut Line= 3
      2639581.07     10074876.86      2639101.87     10074850.81
      2638377.91     10074991.44
#Sta/Elev= 30
    4411 2033.63  4461.7 2032.84  4483.7 2032.89    4561 2031.06    4684 2027.81
    4742 2022.33    4747 2023.92  4782.3 2020.51  4814.2    2019  4854.3 2015.75
  4890.1 2013.63  4958.2 2010.77  4962.7 2010.74  4965.4 2010.24  4968.7 2010.74
  5016.6    2011  5039.7 2013.42  5108.3  2014.2  5118.5 2015.96  5169.4 2016.65
  5194.8 2019.09    5200 2020.26  5220.4 2021.91  5262.4 2023.37  5349.8 2025.85
  5406.6 2026.54  5454.8 2027.88  5546.3 2031.77  5566.8 2031.66  5628.4 2033.31
#Mann= 9 ,-1 , 0
    4411     .16       0  4461.7     .05       0    4561     .16       0
  4782.3     .05       0  4958.2      .1       0  4962.7     .07       0
  4968.7      .1       0  5262.4     .08       0  5454.8     .05       0
Bank Sta=4962.7,4968.7
XS Rating Curve= 0 ,0
Exp/Cntr=0.3,0.1

Type RM Length L Ch R = 1 ,2536    ,105,105,105
BEGIN DESCRIPTION:
Mapping XS 7b4720fa
END DESCRIPTION:
XS GIS Cut Line= 2
      2639607.04     10074569.56      2638305.01      10074590.4
#Sta/Elev= 30
  4320.2 2033.42  4448.8 2028.34  4548.8 2025.43  4608.8 2021.82  4658.8 2019.82
  4778.8  2016.6  4888.6 2015.94  4893.6 2014.44  4918.9 2013.91  4928.9  2012.6
  4948.9 2007.93  4958.9 2007.31  4995.9  2007.2  4998.6  2006.7  5008.9 2008.12
 5027.28 2013.85  5028.9 2014.86  5038.9 2016.46  5048.9 2016.98  5098.9 2017.72
  5138.9 2019.46  5188.9 2020.28  5218.9 2021.31  5238.9 2022.97  5298.9  2024.9
  5338.9 2026.94  5438.9 2029.53  5478.9 2030.02  5528.9  2031.9  5622.4 2033.47
#Mann= 4 ,-1 , 0
  4320.2     .05       0  4918.9     .04       0 5027.28     .05       0
  5218.9      .1       0
Bank Sta=4918.9,5027.28
XS Rating Curve= 0 ,0
Exp/Cntr=0.3,0.1

Type RM Length L Ch R = 1 ,2431    ,334,334,334
BEGIN DESCRIPTION:
Mapping XS 770bfdd6
END DESCRIPTION:
XS GIS Cut Line= 2
      2639549.81     10074475.81      2638289.32     10074481.02
#Sta/Elev= 30
  4397.2 2030.98  4508.5 2028.04  4598.1 2024.33  4638.5 2023.27  4668.5 2021.42
  4698.5 2020.73  4718.5 2017.83  4828.5 2015.41  4858.5 2014.02  4878.5 2013.75
  4918.5  2014.1  4928.5 2013.55  4948.5 2011.56  4978.5 2007.28  4995.5 2006.13
  4998.3 2005.63  5018.5 2008.14  5038.5 2010.13  5048.5 2011.83  5058.5 2013.46
  5068.5 2014.53  5148.5 2017.69  5168.5 2017.46  5208.5 2018.78  5308.6  2023.9
  5368.6    2026  5428.6 2027.83  5524.4 2029.81  5548.6 2031.28  5657.7 2033.04
#Mann= 7 ,-1 , 0
  4397.2     .08       0  4598.1      .1       0  4878.5     .05       0
  4948.5     .04       0  5048.5     .05       0  5148.5     .08       0
  5524.4      .1       0
Bank Sta=4948.5,5048.5
XS Rating Curve= 0 ,0
Exp/Cntr=0.3,0.1

Type RM Length L Ch R = 1 ,2097    ,308,308,308
BEGIN DESCRIPTION:
UNT 0085 IN HEWA 4.0
END DESCRIPTION:
XS GIS Cut Line= 3
       2639508.1     10074366.43      2639101.87      10074152.9
       2638508.1      10074152.9
#Sta/Elev= 30
  4437.6 2028.98  4519.8 2026.02  4558.7 2024.88  4586.4 2023.51  4608.4 2023.39
    4717 2018.21  4779.1 2016.06  4795.5 2014.02  4832.6 2013.31  4839.6 2012.01
  4861.7 2010.37  4919.9 2009.22  4949.9 2007.76  4989.9 2004.26  4999.7  2002.6
  5019.9 2005.47  5039.9 2006.36  5049.9 2008.44  5059.9 2009.66  5128.6 2010.97
  5149.9 2011.51  5169.9 2013.04  5259.9 2014.82  5289.9 2016.04  5359.9  2021.3
  5389.9 2024.23  5419.9 2026.18  5442.6  2026.8  5459.9 2026.71  5490.3 2027.47
#Mann= 8 ,-1 , 0
  4437.6     .05       0  4519.8     .16       0    4717      .1       0
  4839.6     .05       0  4919.9     .04       0  5059.9     .05       0
  5128.6      .1       0  5442.6     .05       0
Bank Sta=4919.9,5059.9
XS Rating Curve= 0 ,0
Exp/Cntr=0.3,0.1

Type RM Length L Ch R = 1 ,1789    ,841,841,841
BEGIN DESCRIPTION:
UNT 0085 IN HEWA 3.0
END DESCRIPTION:
XS GIS Cut Line= 3
       2639677.5     10074251.73      2639068.13      10073855.9
      2638635.88     10073835.07
#Sta/Elev= 30
  4224.5 2030.11  4246.7 2029.59  4271.9 2029.35    4287  2028.2  4410.9 2024.34
  4440.3 2022.57  4479.5 2021.43  4497.6 2021.89  4525.6 2019.91  4620.1 2016.37
  4706.8 2013.71  4736.1 2014.25  4758.2 2013.06  4800.4 2012.81  4836.6 2010.69
  4851.8 2008.72  4912.2  2006.5  4938.8 2003.74  4970.8 2005.16  4997.9 2003.12
  5000.6 2002.62  5003.9 2003.12  5050.9 2008.42    5111 2008.27  5161.1 2011.28
  5201.1    2017  5261.2 2020.97    5307 2023.31    5312 2022.82  5383.9 2025.17
#Mann= 8 ,-1 , 0
  4224.5     .05       0  4246.7      .1       0  4440.3     .16       0
  4479.5      .1       0  4620.1     .05       0  4912.2      .1       0
  4997.9     .07       0  5003.9      .1       0
Bank Sta=4997.9,5003.9
XS Rating Curve= 0 ,0
Exp/Cntr=0.3,0.1

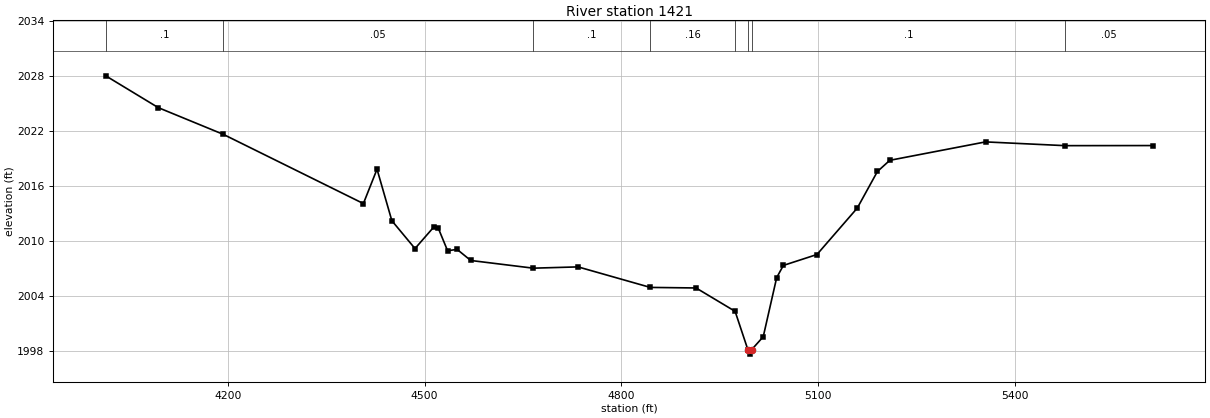
Type RM Length L Ch R = 1 ,1421    ,473,473,473
BEGIN DESCRIPTION:
Mapping XS c4cad072
END DESCRIPTION:
XS GIS Cut Line= 3
       2639763.5     10074010.36      2639082.11     10073476.53
      2638368.17     10073634.94
#Sta/Elev= 30
    4014 2028.06    4094 2024.59  4193.3 2021.67  4406.8 2014.12  4427.6 2017.87
  4450.2 2012.25  4485.5 2009.21  4514.4 2011.58  4520.7 2011.49  4535.2 2008.97
  4549.7 2009.12  4570.5 2007.91  4665.8 2007.07  4734.1 2007.21  4844.3 2004.97
  4914.1 2004.91  4973.6 2002.36    4993 1998.19  4995.8 1997.69    4999 1998.19
  5016.5 1999.59    5037 2006.04  5047.2 2007.37  5098.4 2008.56  5159.9 2013.63
  5190.6 2017.62  5209.5 2018.84  5355.5 2020.85  5476.7 2020.44  5610.9 2020.45
#Mann= 8 ,-1 , 0
    4014      .1       0  4193.3     .05       0  4665.8      .1       0
  4844.3     .16       0  4973.6      .1       0    4993     .07       0
    4999      .1       0  5476.7     .05       0
Bank Sta=4993,4999
XS Rating Curve= 0 ,0
Exp/Cntr=0.3,0.1