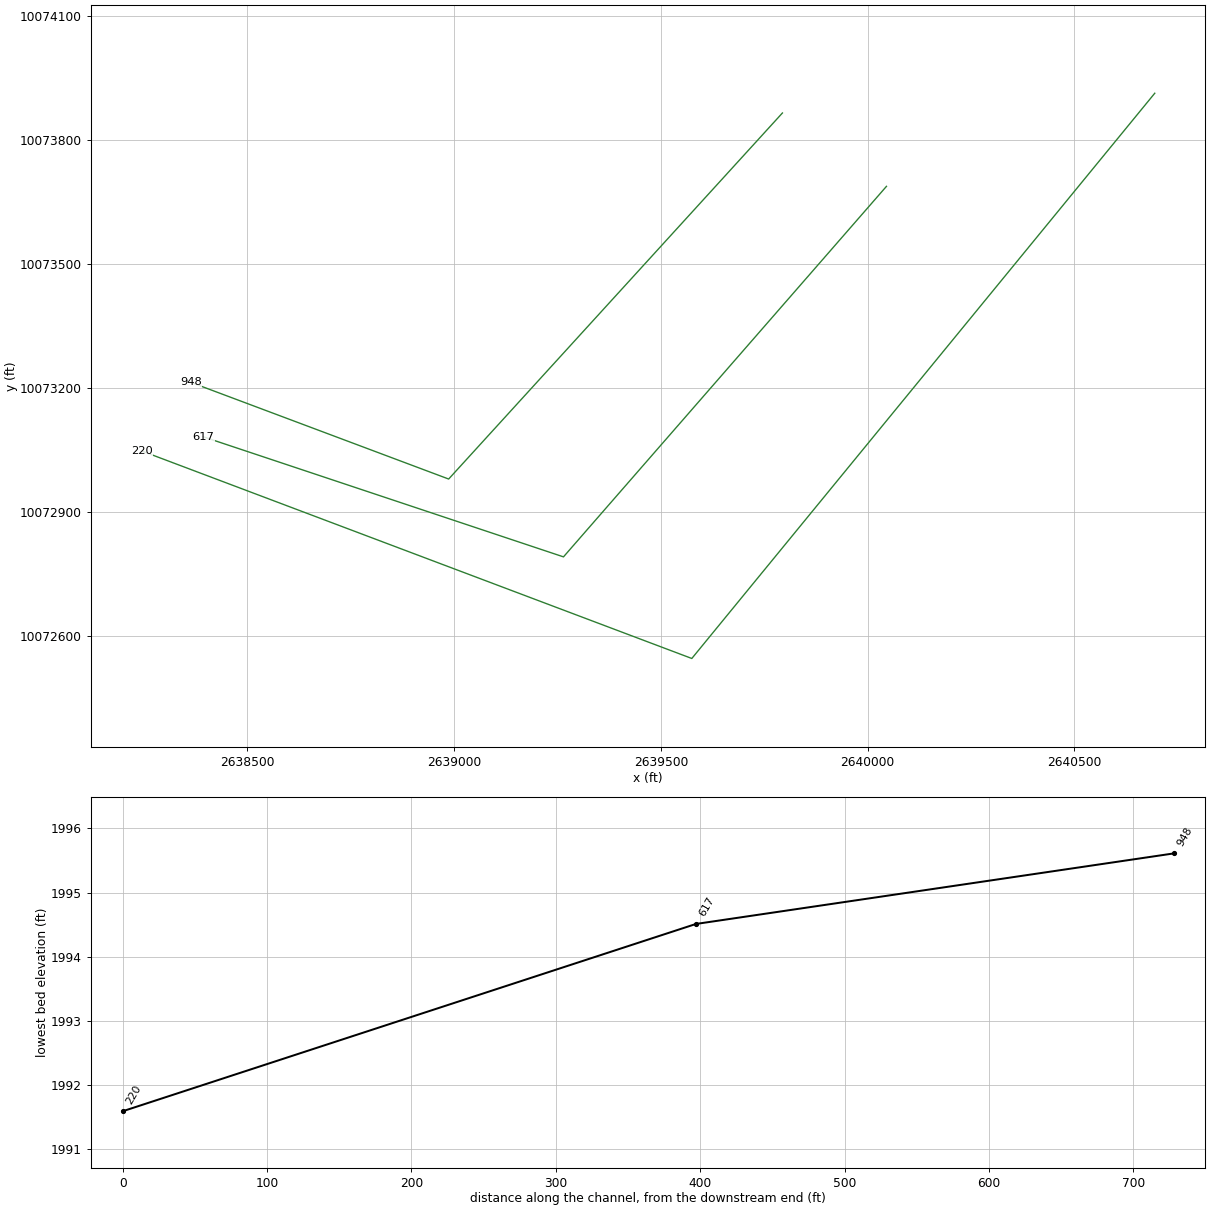
HEC-RAS study UNT 0085 IN HEWA.prj: UNT 0085 IN HEWA Base Level Engineering

--- UNT 0085 IN HEWA.g01 (geometry) --- (continued)

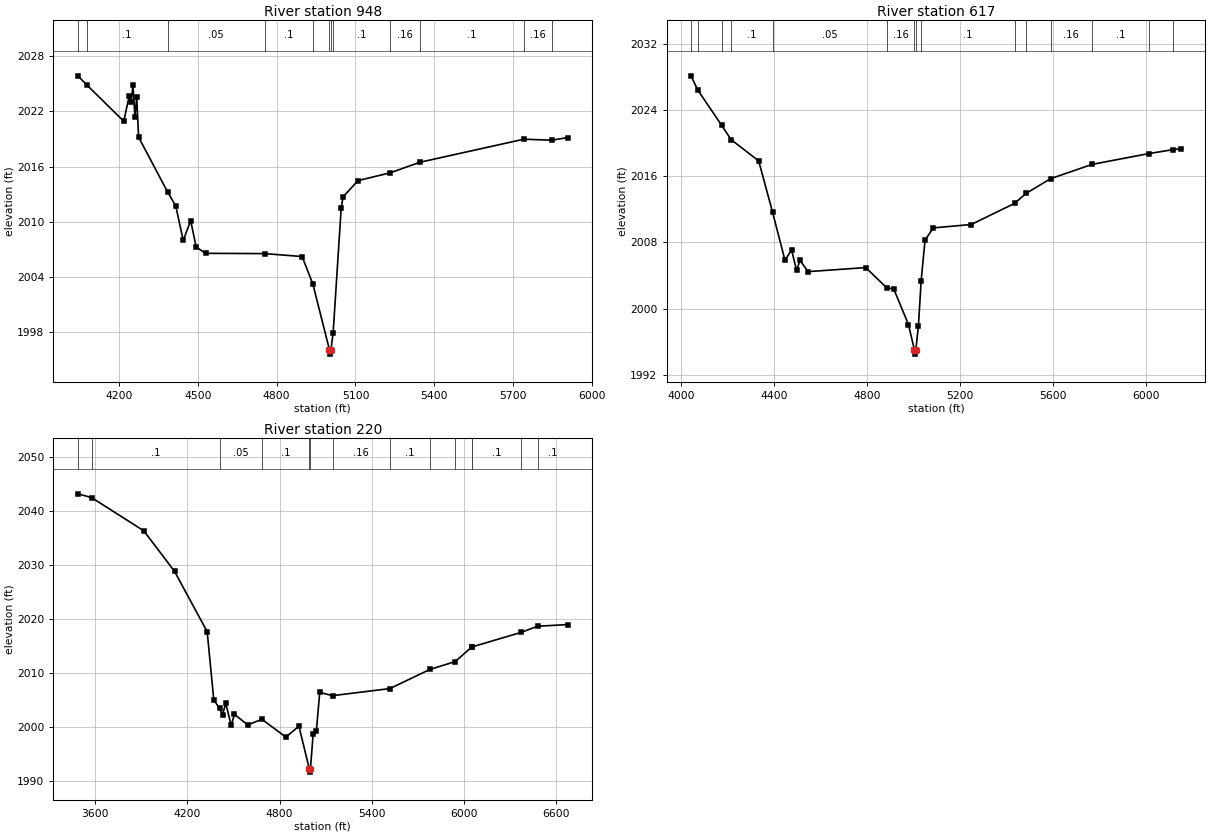
Type RM Length L Ch R = 1 ,948     ,331,331,331
BEGIN DESCRIPTION:
UNT 0085 IN HEWA 2.0
END DESCRIPTION:
XS GIS Cut Line= 3
      2639793.99     10073864.46      2638986.68     10072979.03
      2638362.55     10073213.08
#Sta/Elev= 30
  4043.5 2025.87  4076.6  2024.9    4218 2020.93    4239 2023.69  4246.4 2023.06
  4253.2 2024.85  4260.6 2021.34  4267.3 2023.57  4274.5  2019.2  4384.8 2013.25
    4416 2011.72  4444.4 2007.97  4472.7 2010.12  4493.7 2007.26  4529.5 2006.57
    4754 2006.54    4897 2006.22    4938 2003.22  5000.8 1996.11  5003.5 1995.61
  5006.8 1996.11    5015  1997.9  5045.9 2011.55  5053.1 2012.72  5109.9 2014.48
  5232.9 2015.33  5345.1 2016.47  5741.2 2018.98  5848.3 2018.87  5908.3 2019.16
#Mann= 12 ,-1 , 0
  4043.5     .16       0  4076.6      .1       0  4384.8     .05       0
    4754      .1       0    4938     .16       0  5000.8     .07       0
  5006.8     .16       0    5015      .1       0  5232.9     .16       0
  5345.1      .1       0  5741.2     .16       0  5848.3      .1       0
Bank Sta=5000.8,5006.8
XS Rating Curve= 0 ,0
Exp/Cntr=0.3,0.1

Type RM Length L Ch R = 1 ,617     ,397,397,397
BEGIN DESCRIPTION:
Mapping XS deec3e1a
END DESCRIPTION:
XS GIS Cut Line= 3
      2640045.64     10073687.02       2639264.4     10072790.77
      2638392.71     10073081.33
#Sta/Elev= 30
  4042.2 2028.11  4070.5 2026.42    4174 2022.13  4214.7  2020.4  4333.2 2017.84
  4393.2 2011.62  4446.2 2005.85  4474.7 2007.08  4496.5 2004.61  4510.8 2005.83
  4545.9 2004.47  4793.7 2004.96  4884.4 2002.51  4914.2 2002.39  4977.8 1998.08
  5003.3 1995.01  5006.1 1994.51  5009.3 1995.01  5020.6 1997.94  5032.3 2003.39
    5049 2008.26  5084.2 2009.75  5247.9 2010.16  5434.1 2012.71  5483.5 2013.91
  5589.1 2015.69    5768 2017.42  6011.4 2018.72    6117  2019.2    6150  2019.3
#Mann= 15 ,-1 , 0
  4042.2     .16       0  4070.5      .1       0    4174     .16       0
  4214.7      .1       0  4393.2     .05       0  4884.4     .16       0
  5003.3     .07       0  5009.3     .16       0  5032.3      .1       0
  5434.1     .16       0  5483.5      .1       0  5589.1     .16       0
    5768      .1       0  6011.4     .16       0    6117      .1       0
Bank Sta=5003.3,5009.3
XS Rating Curve= 0 ,0
Exp/Cntr=0.3,0.1

Type RM Length L Ch R = 1 ,220     ,0,0,0
BEGIN DESCRIPTION:
UNT 0085 IN HEWA 1.0
END DESCRIPTION:
XS GIS Cut Line= 3
       2640694.6     10073912.21      2639574.79       10072545.
      2638244.46     10073046.83
#Sta/Elev= 30
  3487.2 2043.19  3576.4 2042.49  3916.7 2036.32  4116.2 2028.81  4328.7 2017.64
  4371.7    2005  4409.2 2003.41  4428.8 2002.26  4449.9 2004.35  4485.1 2000.25
  4506.4 2002.31  4592.1 2000.35  4685.7 2001.38  4841.1 1998.08  4925.8 2000.12
  4994.6 1992.09  4997.3 1991.59  5000.6 1992.09  5018.4 1998.57  5039.2 1999.13
  5061.5 2006.37  5144.8 2005.77  5517.9 2007.08  5777.6 2010.62  5943.7 2012.09
    6051 2014.79  6051.3 2014.79  6372.7  2017.5    6480 2018.64  6676.3 2018.95
#Mann= 14 ,-1 , 0
  3487.2     .05       0  3576.4      .1       0  4409.2     .05       0
  4685.7      .1       0  4994.6     .07       0  5000.6      .1       0
  5144.8     .16       0  5517.9      .1       0  5777.6     .16       0
  5943.7      .1       0    6051     .16       0  6051.3      .1       0
  6372.7     .16       0    6480      .1       0
Bank Sta=4994.6,5000.6
XS Rating Curve= 0 ,0
Exp/Cntr=0.3,0.1

Chan Stop Cuts=-1
Use User Specified Reach Order=0
Composite Channel Slope=5