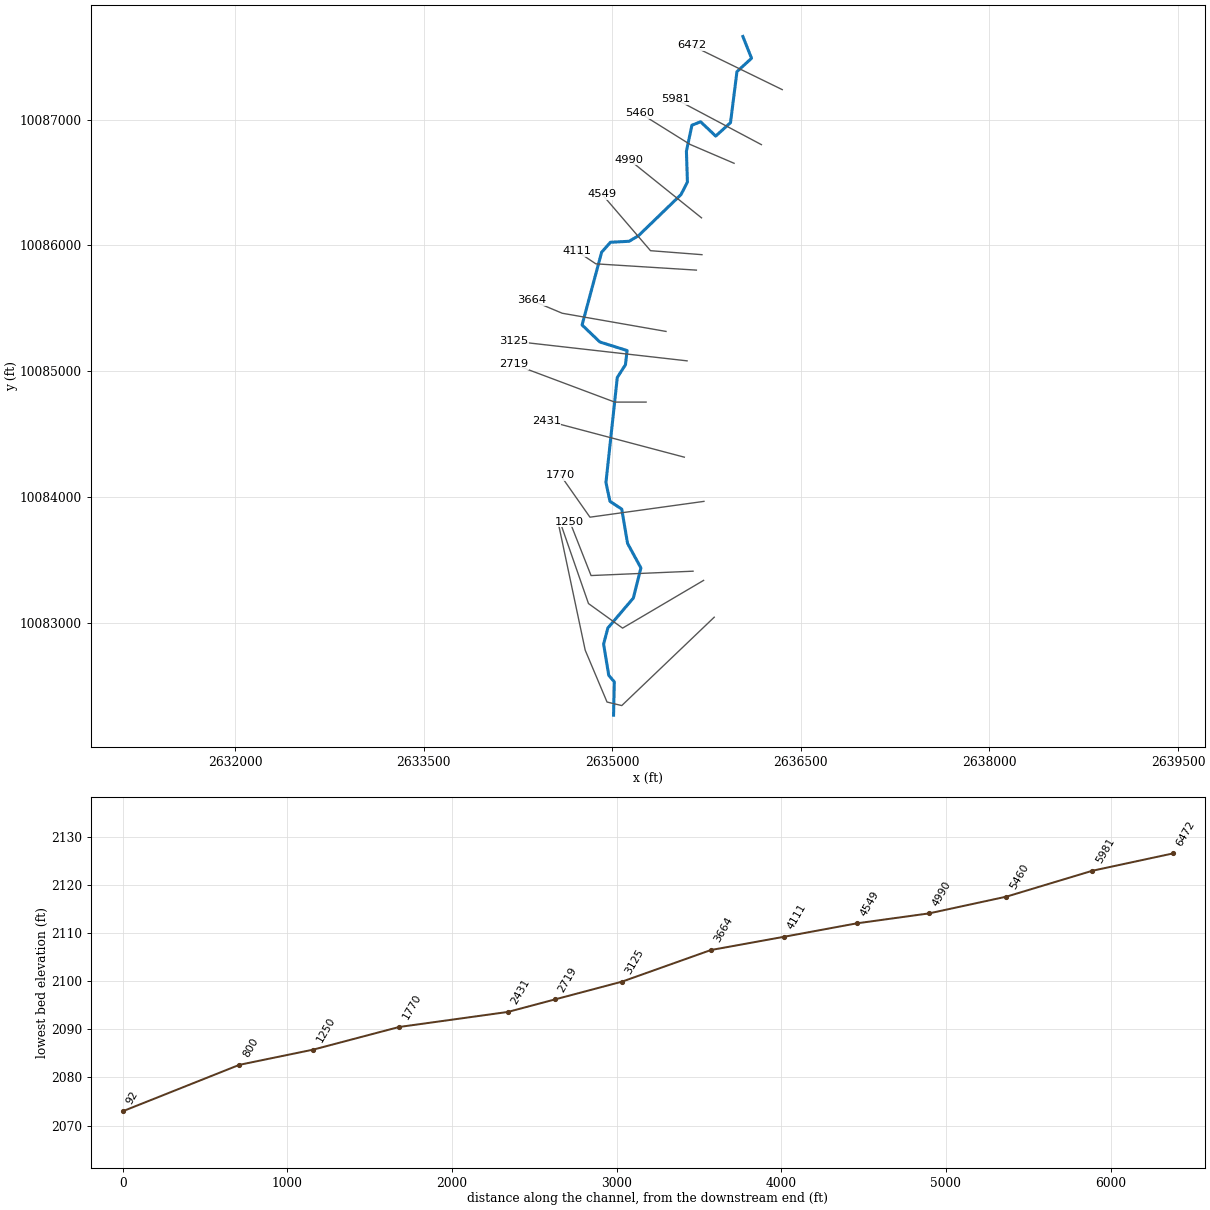
--- UNT 0086 IN HEWA.prj (project) ---

Proj Title=UNT 0086 IN HEWA Base Level Engineering
Current Plan=p01
Default Exp/Contr=0.3,0.1
English Units
Geom File=g01
Flow File=f01
Plan File=p01
BEGIN DESCRIPTION:
UNT 0086 IN HEWA
END DESCRIPTION:

--- UNT 0086 IN HEWA.p01 (plan) ---

Plan Title=Multiple Run
Short Identifier=Multiple
Geom File=g01
Flow File=f01
Subcritical Flow
K Sum by GR= 0
Std Step Tol= 0.01
Critical Tol= 0.01
Num of Std Step Trials= 20
Max Error Tol= 0.3
Flow Tol Ratio= 0.001
Split Flow NTrial= 30
Split Flow Tol= 0.02
Split Flow Ratio= 0.02
Log Output Level= 0
Friction Slope Method= 1
Unsteady Friction Slope Method= 2
Unsteady Bridges Friction Slope Method= 1
Parabolic Critical Depth
Global Vel Dist=  1 , 1 , 1
Global Log Level= 0
CheckData=True
Encroach Param= -1, 0, 0, 0
BEGIN DESCRIPTION:
Multiple Run
END DESCRIPTION:

--- UNT 0086 IN HEWA.f01 (steady flow) ---

Flow Title=Multiple
Number of Profiles=7
Profile Names=10-year,25-year,50-year,1pct_min,100-year,1pct_plu,500-year
River Rch & RM= UNT 0086 IN HEWA,Reach-1,6472
     948    1365    1720    1580    2137    2889    3298
River Rch & RM= UNT 0086 IN HEWA,Reach-1,5460
    1156    1679    2128    1965    2657    3594    4145
Boundary for River Rch & Prof#=UNT 0086 IN HEWA,Reach-1,1
Up Type=0
Dn Type=3
Dn Slope=0.005
Boundary for River Rch & Prof#=UNT 0086 IN HEWA,Reach-1,2
Up Type=0
Dn Type=3
Dn Slope=0.005
Boundary for River Rch & Prof#=UNT 0086 IN HEWA,Reach-1,3
Up Type=0
Dn Type=3
Dn Slope=0.005
Boundary for River Rch & Prof#=UNT 0086 IN HEWA,Reach-1,4
Up Type=0
Dn Type=3
Dn Slope=0.005
Boundary for River Rch & Prof#=UNT 0086 IN HEWA,Reach-1,5
Up Type=0
Dn Type=3
Dn Slope=0.005
Boundary for River Rch & Prof#=UNT 0086 IN HEWA,Reach-1,6
Up Type=0
Dn Type=3
Dn Slope=0.005
Boundary for River Rch & Prof#=UNT 0086 IN HEWA,Reach-1,7
Up Type=0
Dn Type=3
Dn Slope=0.005

--- UNT 0086 IN HEWA.g01 (geometry) ---

Geom Title=Existing Conditions

River Reach=UNT 0086 IN HEWA,Reach-1
Reach XY= 30
      2636038.31     10087662.50      2636107.18     10087489.30
      2635991.19     10087382.77      2635939.89     10086977.20
      2635822.19     10086870.13      2635701.82     10086984.16
      2635632.95     10086956.59      2635589.11     10086749.70
      2635597.11     10086504.25      2635545.98     10086404.76
      2635206.73     10086076.52      2635133.16     10086033.15
      2634984.34     10086025.26      2634914.46     10085945.83
      2634759.02     10085367.36      2634900.16     10085231.94
      2635117.15     10085163.83      2635104.08     10085050.86
      2635039.10     10084949.73      2634948.87     10084113.90
      2634980.65     10083964.41      2635074.26     10083902.38
      2635120.97     10083629.38      2635227.06     10083434.14
      2635166.80     10083194.42      2634964.19     10082956.40
      2634930.21     10082828.22      2634970.97     10082579.71
      2635015.42     10082528.09      2635009.41     10082262.41

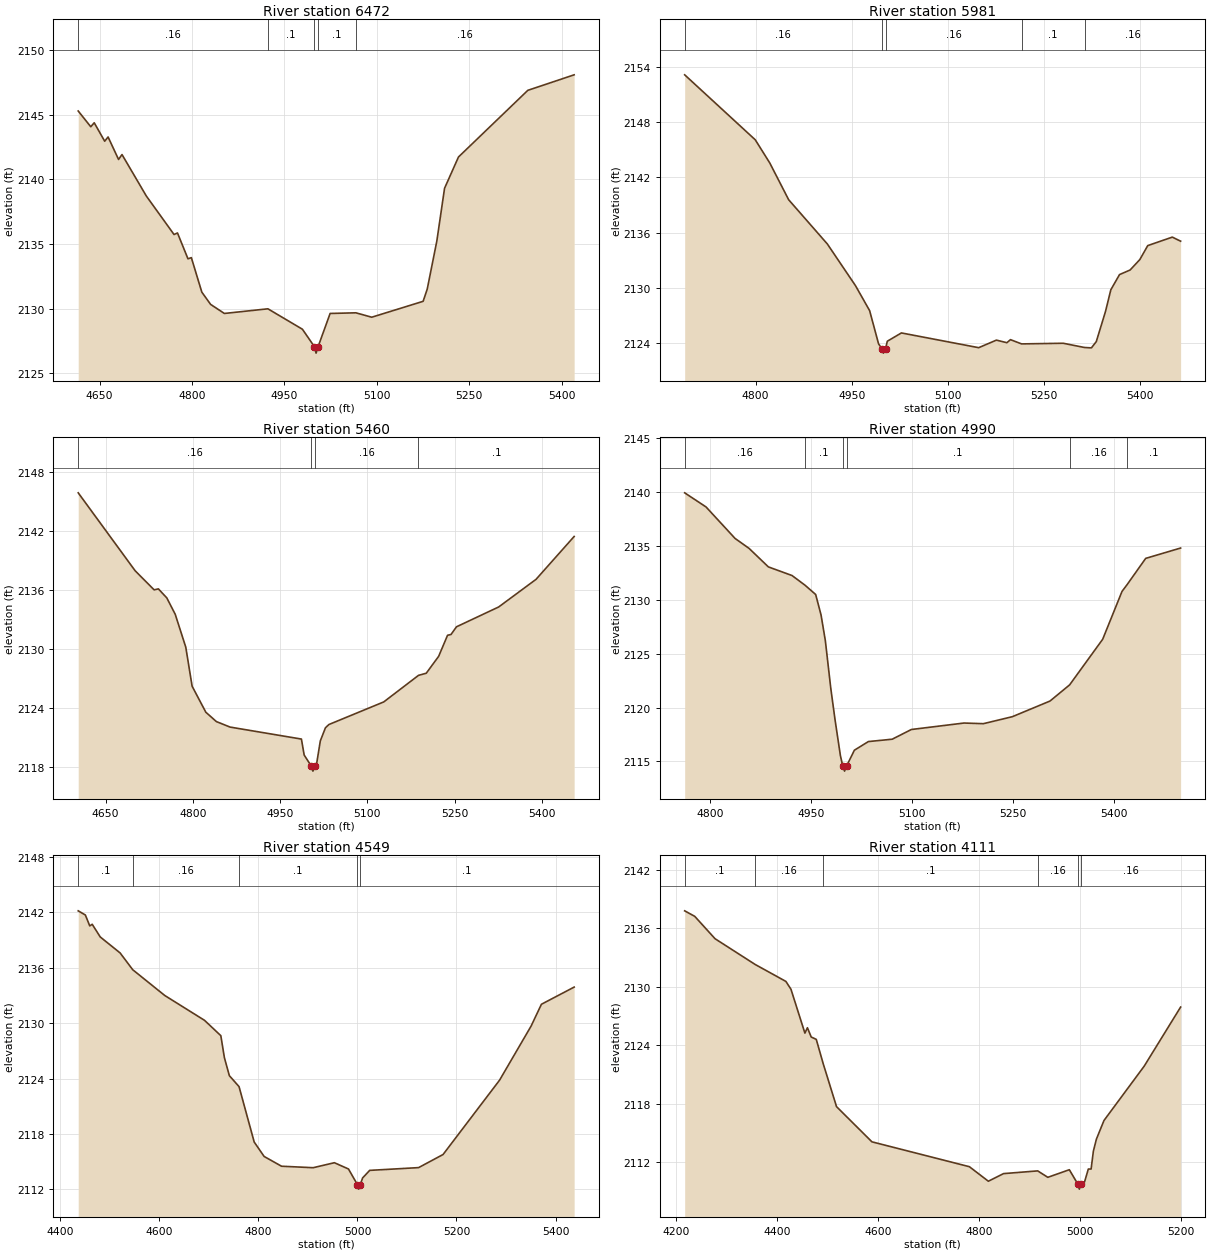
Type RM Length L Ch R = 1,6472,491,491,491
BEGIN DESCRIPTION:
UNT 0086 IN HEWA 11.0
END DESCRIPTION:
XS GIS Cut Line= 2
      2636351.73     10087239.72      2635628.05     10087592.74
#Sta/Elev= 30
  4615.2 2145.30  4635.6 2144.08  4641.2 2144.39  4658.2 2142.96  4663.7 2143.29
  4680.7 2141.55  4686.3 2141.93  4725.8 2138.72  4770.8 2135.74  4776.4 2135.86
  4793.4 2133.86  4798.9 2133.95  4815.9 2131.28  4830.2 2130.33  4852.5 2129.63
  4923.2 2129.99  4979.2 2128.41  4998.7 2127.06  5001.4 2126.56  5004.7 2127.06
  5024.2 2129.63  5066.0 2129.68  5091.8 2129.34  5175.2 2130.57  5181.9 2131.52
  5197.4 2135.22  5210.0 2139.32  5232.6 2141.74  5345.2 2146.90  5420.4 2148.10
#Mann=5,-1,0
  4615.2    0.16       0  4923.2     0.1       0  4998.7    0.07       0
  5004.7     0.1       0  5066.0    0.16       0
Bank Sta=4998.7,5004.7
Exp/Cntr=0.3,0.1

Type RM Length L Ch R = 1,5981,521,521,521
BEGIN DESCRIPTION:
UNT 0086 IN HEWA 10.0
END DESCRIPTION:
XS GIS Cut Line= 2
      2636185.78     10086802.04      2635502.24     10087164.95
#Sta/Elev= 30
  4689.2 2153.13  4799.4 2146.08  4822.0 2143.57  4851.5 2139.58  4911.8 2134.79
  4955.8 2130.26  4977.8 2127.56  4991.8 2123.95  4996.8 2123.45  4999.5 2122.95
  5002.8 2123.45  5005.4 2124.24  5027.4 2125.14  5148.0 2123.54  5175.6 2124.36
  5192.0 2124.08  5197.6 2124.41  5215.0 2123.95  5279.9 2124.02  5313.2 2123.56
  5323.9 2123.52  5331.5 2124.20  5345.9 2127.47  5354.2 2129.82  5367.8 2131.47
  5384.2 2131.96  5399.4 2133.09  5411.8 2134.61  5450.1 2135.53  5463.1 2135.09
#Mann=5,-1,0
  4689.2    0.16       0  4996.8    0.07       0  5002.8    0.16       0
  5215.0     0.1       0  5313.2    0.16       0
Bank Sta=4996.8,5002.8
Exp/Cntr=0.3,0.1

Type RM Length L Ch R = 1,5460,470,470,470
BEGIN DESCRIPTION:
UNT 0086 IN HEWA 9.0
END DESCRIPTION:
XS GIS Cut Line= 3
      2635968.45     10086653.74      2635618.47     10086803.73
      2635218.44     10087053.75
#Sta/Elev= 30
  4602.9 2145.89  4700.8 2137.96  4733.4 2136.02  4740.7 2136.12  4755.2 2135.20
  4769.7 2133.53  4787.8 2130.19  4798.7 2126.22  4822.3 2123.57  4840.4 2122.62
  4864.0 2122.06  4986.6 2120.84  4991.3 2119.22  5003.7 2118.08  5006.4 2117.58
  5009.7 2118.08  5012.6 2118.29  5019.1 2120.66  5027.9 2121.99  5033.8 2122.32
  5128.1 2124.62  5187.8 2127.32  5201.2 2127.54  5222.5 2129.26  5237.8 2131.40
  5243.7 2131.48  5253.1 2132.26  5325.7 2134.28  5389.9 2137.09  5455.4 2141.45
#Mann=4,-1,0
  4602.9    0.16       0  5003.7    0.07       0  5009.7    0.16       0
  5187.8     0.1       0
Bank Sta=5003.7,5009.7
Exp/Cntr=0.3,0.1

Type RM Length L Ch R = 1,4990,441,441,441
BEGIN DESCRIPTION:
UNT 0086 IN HEWA 8.0
END DESCRIPTION:
XS GIS Cut Line= 2
      2635709.27     10086219.59      2635133.87     10086682.03
#Sta/Elev= 30
  4761.6 2139.91  4793.4 2138.60  4836.6 2135.68  4857.4 2134.76  4886.2 2133.04
  4921.4 2132.24  4940.8 2131.34  4956.6 2130.48  4964.6 2128.58  4971.0 2126.19
  4979.0 2121.82  4985.4 2118.87  4993.4 2115.54  4996.8 2114.60  4999.6 2114.10
  5002.8 2114.60  5014.2 2116.04  5035.0 2116.84  5070.5 2117.06  5099.0 2117.96
  5177.4 2118.56  5206.2 2118.50  5249.4 2119.15  5305.4 2120.60  5334.6 2122.10
  5383.8 2126.33  5412.6 2130.77  5420.2 2131.40  5447.8 2133.83  5499.8 2134.79
#Mann=6,-1,0
  4761.6    0.16       0  4940.8     0.1       0  4996.8    0.07       0
  5002.8     0.1       0  5334.6    0.16       0  5420.2     0.1       0
Bank Sta=4996.8,5002.8
Exp/Cntr=0.3,0.1

Type RM Length L Ch R = 1,4549,438,438,438
BEGIN DESCRIPTION:
UNT 0086 IN HEWA 7.0
END DESCRIPTION:
XS GIS Cut Line= 3
      2635712.79     10085926.62      2635303.31     10085958.39
      2634918.54     10086406.71
#Sta/Elev= 30
  4436.1 2142.16  4450.5 2141.71  4459.4 2140.53  4464.4 2140.70  4480.6 2139.33
  4520.7 2137.60  4546.2 2135.78  4610.9 2132.99  4691.2 2130.30  4724.1 2128.64
  4731.3 2126.26  4741.3 2124.31  4760.9 2123.12  4791.5 2117.12  4811.5 2115.56
  4846.7 2114.50  4910.6 2114.34  4953.4 2114.88  4981.9 2114.20  4999.8 2112.52
  5002.5 2112.02  5005.8 2112.52  5010.4 2113.23  5024.7 2114.05  5123.5 2114.35
  5172.9 2115.77  5287.0 2123.82  5350.6 2129.67  5371.5 2132.04  5437.6 2133.90
#Mann=5,-1,0
  4436.1     0.1       0  4546.2    0.16       0  4760.9     0.1       0
  4999.8    0.07       0  5005.8     0.1       0
Bank Sta=4999.8,5005.8
Exp/Cntr=0.3,0.1

Type RM Length L Ch R = 1,4111,447,447,447
BEGIN DESCRIPTION:
UNT 0086 IN HEWA 6.0
END DESCRIPTION:
XS GIS Cut Line= 3
      2635668.46     10085803.73      2634868.47     10085853.73
      2634718.49     10085953.71
#Sta/Elev= 30
  4216.9 2137.79  4236.9 2137.22  4277.0 2134.93  4356.4 2132.29  4417.3 2130.55
  4427.3 2129.75  4454.9 2125.25  4459.9 2125.80  4467.4 2124.85  4477.4 2124.61
  4491.1 2122.12  4517.5 2117.71  4587.6 2114.10  4780.5 2111.55  4818.1 2110.06
  4848.1 2110.84  4915.8 2111.12  4935.8 2110.46  4978.4 2111.24  4995.4 2109.75
  4998.2 2109.25  5001.4 2109.75  5008.4 2109.97  5016.0 2111.31  5021.5 2111.31
  5026.0 2113.15  5032.0 2114.38  5047.0 2116.29  5126.6 2121.86  5198.7 2127.92
#Mann=6,-1,0
  4216.9     0.1       0  4356.4    0.16       0  4491.1     0.1       0
  4915.8    0.16       0  4995.4    0.07       0  5001.4    0.16       0
Bank Sta=4995.4,5001.4
Exp/Cntr=0.3,0.1

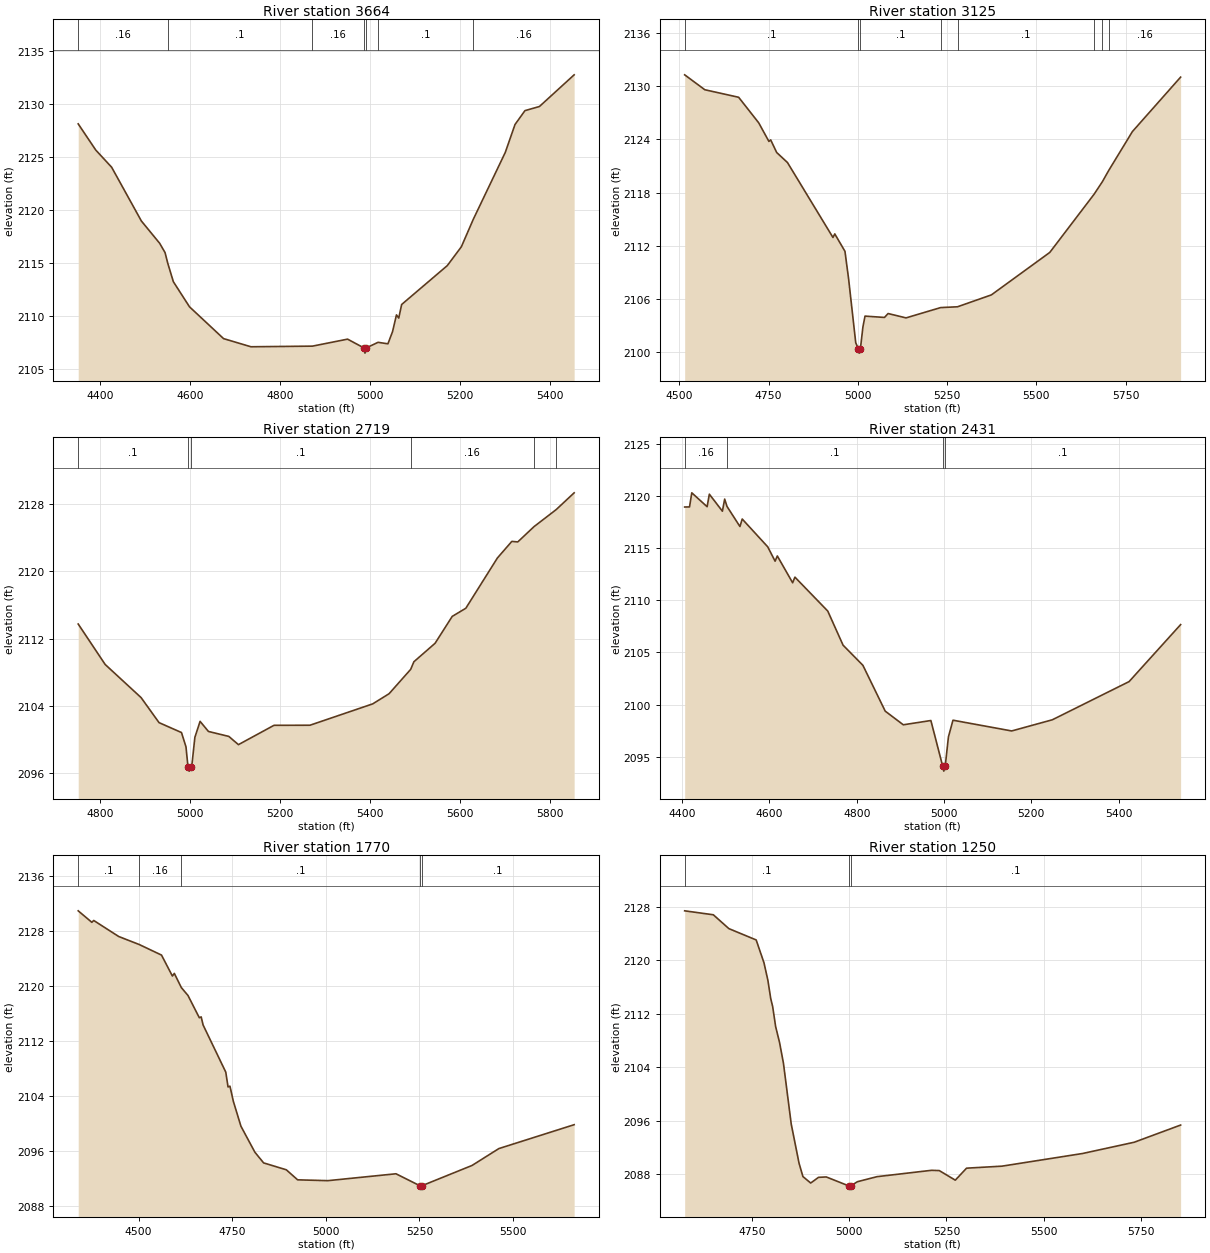
Type RM Length L Ch R = 1,3664,539,539,539
BEGIN DESCRIPTION:
UNT 0086 IN HEWA 5.0
END DESCRIPTION:
XS GIS Cut Line= 3
      2635426.85     10085315.95      2634600.86     10085460.68
      2634357.27     10085563.06
#Sta/Elev= 30
  4350.5 2128.12  4389.5 2125.65  4424.8 2124.03  4491.0 2118.95  4531.6 2116.85
  4543.6 2115.97  4549.8 2114.94  4562.1 2113.22  4598.0 2110.85  4673.7 2107.85
  4734.6 2107.08  4871.4 2107.14  4949.5 2107.80  4985.5 2106.98  4988.2 2106.48
  4991.5 2106.98  5017.2 2107.50  5039.2 2107.36  5049.4 2108.50  5058.2 2110.09
  5063.3 2109.79  5069.7 2111.07  5171.2 2114.74  5202.5 2116.52  5229.0 2119.11
  5300.1 2125.42  5321.8 2128.06  5343.9 2129.37  5376.1 2129.76  5453.3 2132.75
#Mann=7,-1,0
  4350.5    0.16       0  4549.8     0.1       0  4871.4    0.16       0
  4985.5    0.07       0  4991.5    0.16       0  5017.2     0.1       0
  5229.0    0.16       0
Bank Sta=4985.5,4991.5
Exp/Cntr=0.3,0.1

Type RM Length L Ch R = 1,3125,406,406,406
BEGIN DESCRIPTION:
UNT 0086 IN HEWA 4.0
END DESCRIPTION:
XS GIS Cut Line= 2
      2635594.52     10085081.83      2634214.34     10085238.07
#Sta/Elev= 30
  4515.1 2131.27  4571.5 2129.59  4666.3 2128.74  4722.5 2125.86  4751.0 2123.77
  4756.0 2123.94  4772.8 2122.52  4803.0 2121.39  4930.4 2112.95  4935.5 2113.35
  4964.0 2111.39  4974.1 2108.33  4994.2 2101.09  5001.3 2100.42  5004.0 2099.92
  5007.3 2100.42  5014.3 2102.87  5020.2 2104.09  5074.7 2103.94  5084.8 2104.38
  5135.1 2103.89  5232.0 2105.05  5279.2 2105.14  5374.1 2106.48  5537.6 2111.26
  5661.6 2117.81  5684.8 2119.22  5702.8 2120.50  5769.1 2124.88  5904.1 2131.01
#Mann=8,-1,0
  4515.1     0.1       0  5001.3    0.07       0  5007.3     0.1       0
  5232.0    0.16       0  5279.2     0.1       0  5661.6    0.16       0
  5684.8     0.1       0  5702.8    0.16       0
Bank Sta=5001.3,5007.3
Exp/Cntr=0.3,0.1

Type RM Length L Ch R = 1,2719,288,288,288
BEGIN DESCRIPTION:
UNT 0086 IN HEWA 3.0
END DESCRIPTION:
XS GIS Cut Line= 3
      2635268.46     10084753.73      2635018.47     10084753.73
      2634218.47     10085053.73
#Sta/Elev= 30
  4750.4 2113.74  4810.4 2108.93  4890.4 2104.99  4930.4 2102.01  4980.4 2100.83
  4990.4 2099.13  4994.9 2096.74  4997.6 2096.24  5000.9 2096.74  5003.1 2096.74
  5010.2 2100.26  5021.8 2102.16  5040.4 2100.96  5085.8 2100.37  5107.2 2099.39
  5186.4 2101.69  5266.5 2101.70  5406.2 2104.24  5442.7 2105.45  5490.8 2108.35
  5497.9 2109.25  5545.1 2111.45  5583.3 2114.65  5613.6 2115.62  5683.9 2121.60
  5716.0 2123.57  5729.3 2123.51  5765.5 2125.33  5814.7 2127.35  5854.8 2129.35
#Mann=6,-1,0
  4750.4     0.1       0  4994.9    0.07       0  5000.9     0.1       0
  5490.8    0.16       0  5765.5     0.1       0  5814.7    0.16       0
Bank Sta=4994.9,5000.9
Exp/Cntr=0.3,0.1

Type RM Length L Ch R = 1,2431,661,661,661
BEGIN DESCRIPTION:
UNT 0086 IN HEWA 2.0
END DESCRIPTION:
XS GIS Cut Line= 2
      2635572.47     10084315.41      2634474.42     10084606.20
#Sta/Elev= 30
  4406.0 2118.93  4417.1 2118.94  4422.3 2120.29  4457.4 2118.96  4462.5 2120.16
  4492.4 2118.53  4497.6 2119.69  4502.9 2118.99  4532.6 2117.06  4537.8 2117.78
  4596.3 2115.11  4613.1 2113.74  4618.2 2114.24  4653.3 2111.67  4658.5 2112.21
  4733.7 2108.96  4768.8 2105.69  4814.2 2103.76  4865.3 2099.37  4906.7 2098.06
  4969.9 2098.47  4996.8 2094.12  4999.5 2093.62  5002.8 2094.12  5010.1 2096.90
  5020.5 2098.50  5155.0 2097.47  5248.1 2098.54  5423.9 2102.20  5541.9 2107.66
#Mann=4,-1,0
  4406.0    0.16       0  4502.9     0.1       0  4996.8    0.07       0
  5002.8     0.1       0
Bank Sta=4996.8,5002.8
Exp/Cntr=0.3,0.1

Type RM Length L Ch R = 1,1770,520,520,520
BEGIN DESCRIPTION:
Mapping XS df9f64cc
END DESCRIPTION:
XS GIS Cut Line= 3
      2635728.74     10083963.84      2634821.62     10083837.97
      2634587.25     10084172.17
#Sta/Elev= 30
  4338.9 2130.92  4375.3 2129.25  4380.3 2129.52  4447.0 2127.19  4502.0 2126.02
  4561.3 2124.49  4590.4 2121.44  4595.5 2121.83  4614.2 2119.77  4632.0 2118.62
  4662.2 2115.39  4667.2 2115.51  4672.3 2114.34  4732.9 2107.48  4738.9 2105.33
  4744.0 2105.45  4753.1 2103.24  4773.3 2099.63  4810.6 2095.85  4833.9 2094.30
  4894.4 2093.30  4924.7 2091.84  5005.5 2091.72  5187.2 2092.72  5250.8 2090.99
  5253.5 2090.49  5256.8 2090.99  5390.4 2093.93  5461.9 2096.38  5662.9 2099.85
#Mann=5,-1,0
  4338.9     0.1       0  4502.0    0.16       0  4614.2     0.1       0
  5250.8    0.07       0  5256.8     0.1       0
Bank Sta=5250.8,5256.8
Exp/Cntr=0.3,0.1

Type RM Length L Ch R = 1,1250,450,450,450
BEGIN DESCRIPTION:
Mapping XS 38262a37
END DESCRIPTION:
XS GIS Cut Line= 3
      2635641.97     10083408.29      2634830.30     10083373.56
      2634661.04     10083803.21
#Sta/Elev= 30
  4577.6 2127.37  4651.2 2126.78  4691.2 2124.71  4761.3 2123.02  4781.3 2119.62
  4791.3 2117.02  4798.7 2114.26  4803.7 2113.06  4811.3 2110.08  4821.3 2107.72
  4831.3 2104.63  4851.4 2095.51  4871.4 2089.68  4881.4 2087.68  4901.4 2086.71
  4921.4 2087.56  4941.4 2087.62  4998.5 2086.30  5001.2 2085.80  5004.5 2086.30
  5021.5 2086.91  5071.6 2087.66  5211.7 2088.61  5231.7 2088.57  5272.9 2087.14
  5301.8 2088.93  5392.8 2089.23  5599.7 2091.12  5732.4 2092.80  5851.8 2095.37
#Mann=3,-1,0
  4577.6     0.1       0  4998.5    0.07       0  5004.5     0.1       0
Bank Sta=4998.5,5004.5
Exp/Cntr=0.3,0.1

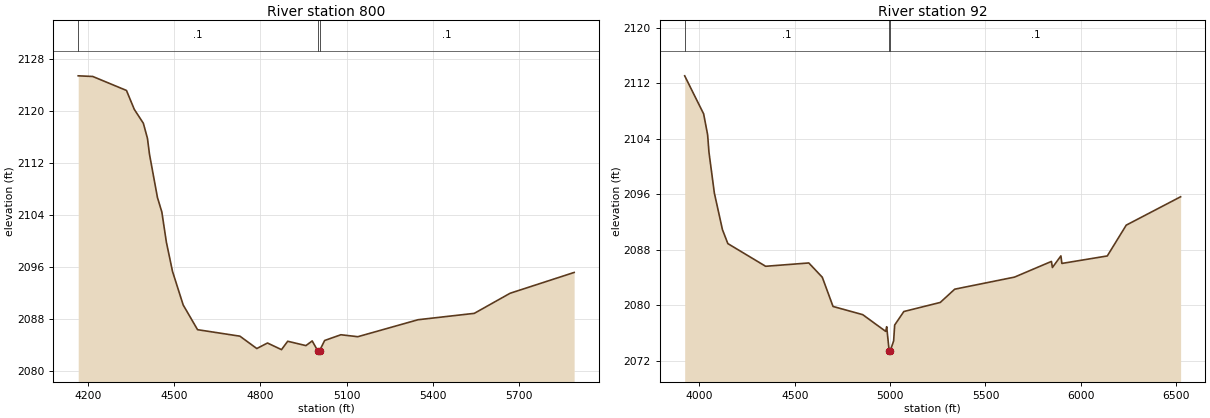
Type RM Length L Ch R = 1,800,708,708,708
BEGIN DESCRIPTION:
Mapping XS 3ae1a77d
END DESCRIPTION:
XS GIS Cut Line= 4
      2635725.72     10083335.17      2635081.17     10082955.38
      2634809.90     10083150.69      2634599.40     10083756.16
#Sta/Elev= 30
  4167.1 2125.43  4217.7 2125.33  4334.8 2123.18  4362.0 2120.27  4393.4 2118.14
  4407.7 2115.82  4414.8 2113.36  4442.5 2106.71  4457.7 2104.49  4473.4 2099.87
  4494.8 2095.35  4531.9 2090.19  4581.8 2086.39  4729.1 2085.39  4787.7 2083.49
  4824.8 2084.34  4873.5 2083.32  4895.1 2084.61  4958.4 2083.94  4980.2 2084.66
  4999.6 2083.13  5002.3 2082.63  5005.6 2083.13  5023.5 2084.73  5079.9 2085.61
  5138.8 2085.31  5348.0 2087.92  5543.5 2088.90  5667.9 2091.99  5890.5 2095.19
#Mann=3,-1,0
  4167.1     0.1       0  4999.6    0.07       0  5005.6     0.1       0
Bank Sta=4999.6,5005.6
Exp/Cntr=0.3,0.1

Type RM Length L Ch R = 1,92,0,0,0
BEGIN DESCRIPTION:
UNT 0086 IN HEWA 1.0
END DESCRIPTION:
XS GIS Cut Line= 5
      2635810.31     10083042.17      2635074.66     10082339.06
      2634957.47     10082367.27      2634783.86     10082779.60
      2634573.42     10083773.22
#Sta/Elev= 30
  3922.3 2113.10  4021.7 2107.62  4042.7 2104.60  4049.7 2102.09  4078.0 2096.20
  4120.4 2090.93  4148.7 2088.92  4346.9 2085.65  4573.3 2086.13  4644.1 2084.07
  4700.4 2079.86  4856.1 2078.68  4976.6 2076.27  4981.8 2076.94  4994.7 2073.49
  4997.5 2072.99  5000.7 2073.49  5018.3 2074.89  5023.7 2077.18  5071.8 2079.13
  5262.8 2080.44  5338.7 2082.35  5652.3 2084.09  5845.9 2086.35  5851.0 2085.47
  5895.6 2087.15  5900.7 2086.06  6138.9 2087.14  6238.3 2091.58  6523.5 2095.67
#Mann=3,-1,0
  3922.3     0.1       0  4994.7    0.07       0  5000.7     0.1       0
Bank Sta=4994.7,5000.7
Exp/Cntr=0.3,0.1

Chan Stop Cuts=-1