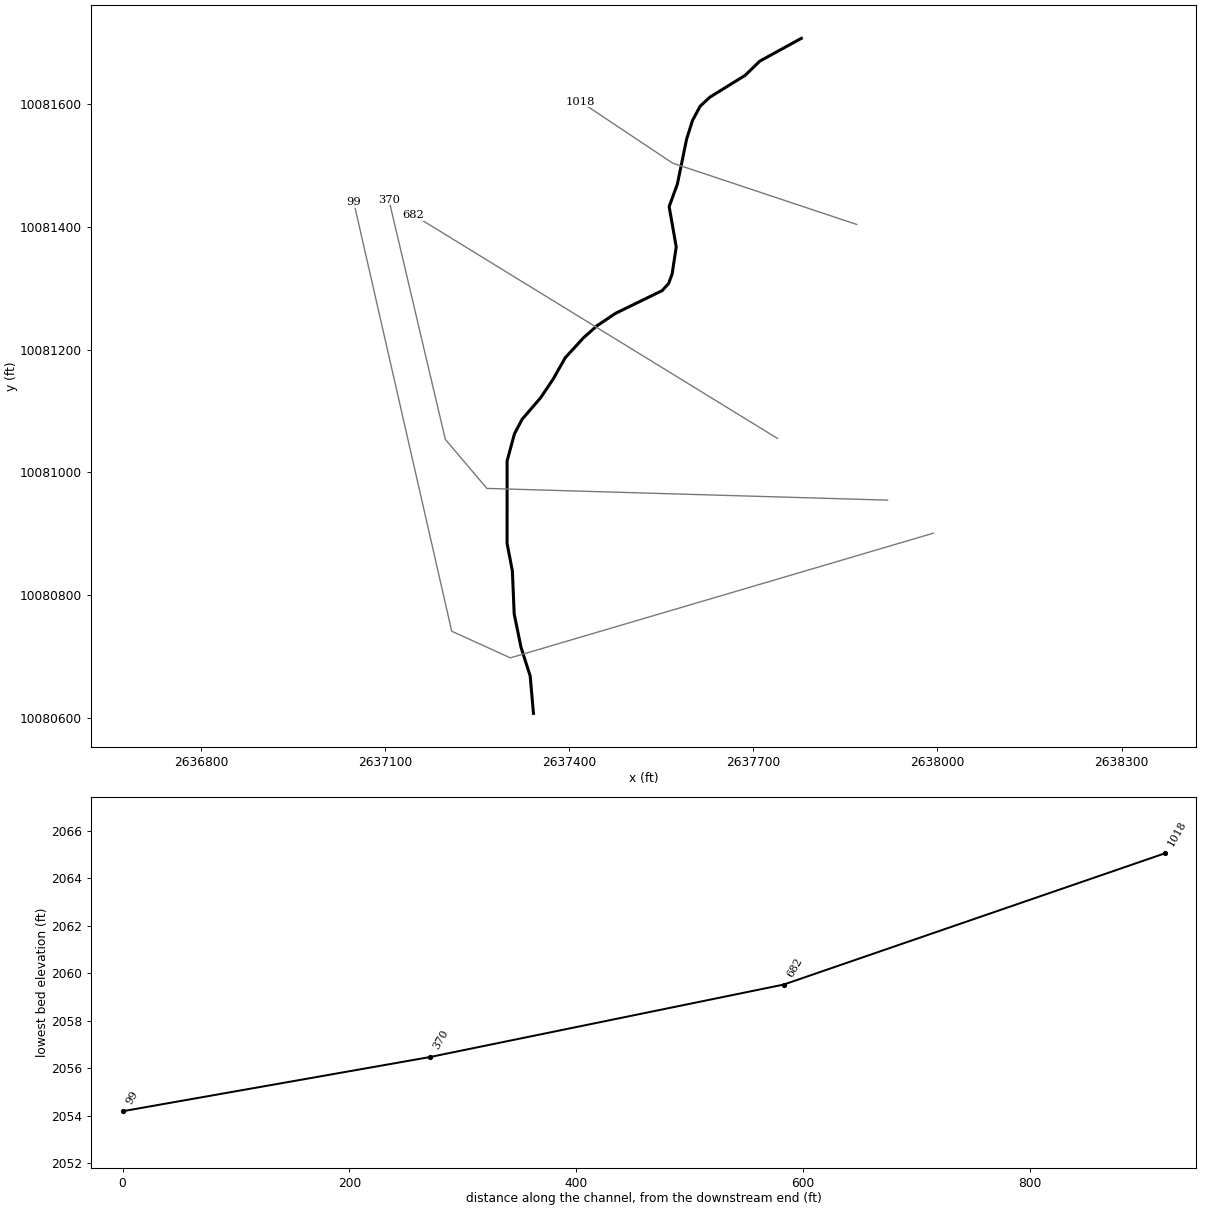
--- UNT 0087 IN HEWA.prj (project) ---

Proj Title=UNT 0087 IN HEWA Base Level Engineering
Current Plan=p01
Default Exp/Contr=0.3,0.1
English Units
Geom File=g01
Flow File=f01
Plan File=p01
Y Axis Title=Elevation
X Axis Title(PF)=Main Channel Distance
X Axis Title(XS)=Station
BEGIN DESCRIPTION:
UNT 0087 IN HEWA
END DESCRIPTION:
DSS Export Rating Curves= 0
DSS Export Rating Curve Sorted= 0
DSS Export Volume Flow Curves= 0
DXF OffsetX= 0
DXF OffsetY= 0
DXF ScaleX= 1
DXF ScaleY= 10

--- UNT 0087 IN HEWA.p01 (plan) ---

Plan Title=Multiple Run
Short Identifier=Multiple
Geom File=g01
Flow File=f01
Subcritical Flow
K Sum by GR= 0
Std Step Tol= 0.01
Critical Tol= 0.01
Num of Std Step Trials= 20
Max Error Tol= 0.3
Flow Tol Ratio= 0.001
Split Flow NTrial= 30
Split Flow Tol= 0.02
Split Flow Ratio= 0.02
Log Output Level= 0
Friction Slope Method= 1
Unsteady Friction Slope Method= 2
Unsteady Bridges Friction Slope Method= 1
Parabolic Critical Depth
Global Vel Dist=  1 , 1 , 1
Global Log Level= 0
CheckData=True
Encroach Param= -1, 0, 0, 0
BEGIN DESCRIPTION:
Multiple Run
END DESCRIPTION:

--- UNT 0087 IN HEWA.f01 (steady flow) ---

Flow Title=Multiple
Program Version=4.10
Number of Profiles= 7
Profile Names=10-year,25-year,50-year,1pct_min,100-year,1pct_plu,500-year
River Rch & RM=UNT 0087 IN HEWA,Reach-1         ,1018
    1036    1507    1912    1770    2393    3236    3748
Boundary for River Rch & Prof#=UNT 0087 IN HEWA,Reach-1         , 1
Up Type= 0
Dn Type= 3
Dn Slope=0.008
Boundary for River Rch & Prof#=UNT 0087 IN HEWA,Reach-1         , 2
Up Type= 0
Dn Type= 3
Dn Slope=0.008
Boundary for River Rch & Prof#=UNT 0087 IN HEWA,Reach-1         , 3
Up Type= 0
Dn Type= 3
Dn Slope=0.008
Boundary for River Rch & Prof#=UNT 0087 IN HEWA,Reach-1         , 4
Up Type= 0
Dn Type= 3
Dn Slope=0.008
Boundary for River Rch & Prof#=UNT 0087 IN HEWA,Reach-1         , 5
Up Type= 0
Dn Type= 3
Dn Slope=0.008
Boundary for River Rch & Prof#=UNT 0087 IN HEWA,Reach-1         , 6
Up Type= 0
Dn Type= 3
Dn Slope=0.008
Boundary for River Rch & Prof#=UNT 0087 IN HEWA,Reach-1         , 7
Up Type= 0
Dn Type= 3
Dn Slope=0.008
DSS Import GetInterval= 0
DSS Import GetPeak= 0
DSS Import FillOption= 0

--- UNT 0087 IN HEWA.g01 (geometry) ---

Geom Title=Existing Conditions
Program Version=4.10

River Reach=UNT 0087 IN HEWA,Reach-1
Reach XY= 28
      2637778.29     10081706.96      2637710.66     10081669.89
      2637686.62     10081646.61      2637629.38     10081611.21
      2637613.33     10081596.35      2637600.86     10081572.89
      2637591.29     10081542.61      2637576.29     10081469.48
      2637562.91      10081432.8      2637574.41     10081367.09
      2637567.75     10081322.97      2637562.05     10081307.69
       2637551.5     10081295.94      2637475.74     10081259.02
      2637445.46     10081238.78      2637423.53     10081219.23
      2637393.64     10081186.65      2637373.49     10081151.09
      2637353.32     10081121.15      2637323.39     10081086.41
      2637310.89     10081062.73      2637298.91     10081018.55
      2637298.89     10080883.91       2637307.5     10080839.12
      2637310.43     10080769.28      2637321.55     10080714.95
      2637336.53     10080667.96      2637341.83     10080607.22

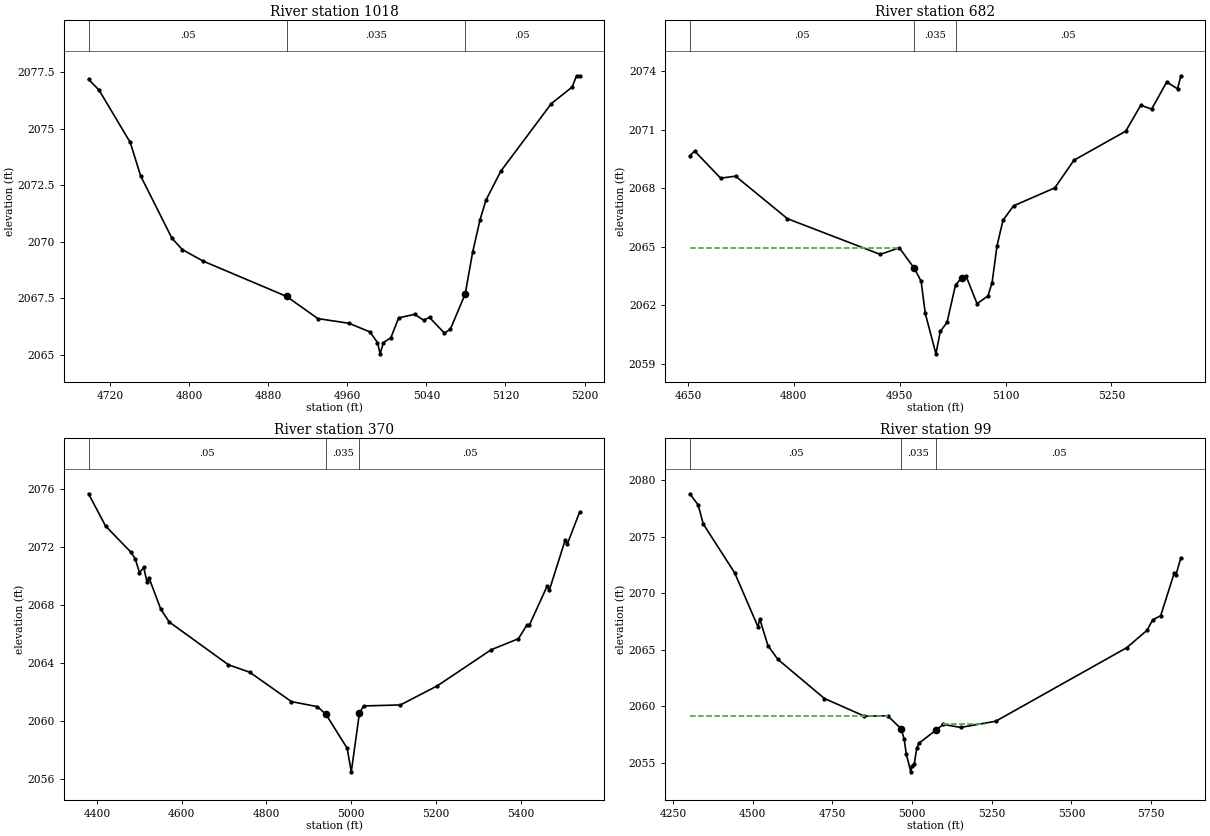
Type RM Length L Ch R = 1 ,1018    ,336,336,336
BEGIN DESCRIPTION:
UNT 0087 IN HEWA 2.0
END DESCRIPTION:
XS GIS Cut Line= 3
      2637868.49     10081403.72      2637568.47     10081503.73
      2637418.49     10081603.72
#Sta/Elev= 30
  4698.4 2077.18    4709 2076.71  4740.6 2074.39  4751.1 2072.91  4782.8 2070.15
  4793.3 2069.65  4814.4 2069.14  4898.7 2067.58  4930.3  2066.6  4961.9 2066.39
    4983 2066.01  4990.6 2065.54  4993.3 2065.04  4996.6 2065.54  5004.1 2065.75
    5012 2066.63  5028.2 2066.79  5037.2 2066.53  5043.2 2066.65  5058.2 2065.96
  5064.2 2066.12  5079.3 2067.69  5086.8 2069.53  5094.3 2070.97  5100.3 2071.84
  5115.3 2073.12  5166.4 2076.11  5187.4 2076.84  5191.9 2077.34  5194.9 2077.34
#Mann= 3 , 0 , 0
  4698.4     .05       0  4898.7    .035       0  5079.3     .05       0
Bank Sta=4898.7,5079.3
XS Rating Curve= 0 ,0
Exp/Cntr=0.3,0.1

Type RM Length L Ch R = 1 ,682     ,312,312,312
BEGIN DESCRIPTION:
Mapping XS 58042e21
END DESCRIPTION:
XS GIS Cut Line= 2
      2637739.32     10081055.18      2637146.38     10081419.26
#Sta/Elev= 30
  4652.7 2069.68  4659.5 2069.92  4696.2 2068.53  4717.5 2068.63    4791 2066.45
  4922.4 2064.62  4949.5 2064.96  4970.8  2063.9  4980.4 2063.25  4986.3 2061.59
  5001.4 2059.52  5007.6 2060.67  5017.1 2061.13  5029.2 2063.06  5038.4 2063.43
  5044.3 2063.49  5059.7 2062.09  5075.1 2062.49    5081 2063.17  5087.9 2065.05
  5096.4 2066.37  5111.4 2067.11  5169.8 2068.03    5197 2069.45  5270.4 2070.94
  5291.7 2072.27  5307.1 2072.07  5328.4 2073.46  5343.8 2073.11  5348.5 2073.78
#Mann= 3 ,-1 , 0
  4652.7     .05       0  4970.8    .035       0  5029.2     .05       0
#XS Ineff= 2 , 0
         4949.44 2064.96
Permanent Ineff=
       T       T
Bank Sta=4970.8,5038.4
XS Rating Curve= 0 ,0
Exp/Cntr=0.3,0.1

Type RM Length L Ch R = 1 ,370     ,271,271,271
BEGIN DESCRIPTION:
Mapping XS 4413b054
END DESCRIPTION:
XS GIS Cut Line= 4
      2637918.74     10080954.62      2637265.97     10080973.72
      2637198.26     10081053.58      2637106.24     10081444.23
#Sta/Elev= 30
  4379.9 2075.67  4420.2 2073.44  4480.2 2071.63  4490.2 2071.17  4500.2 2070.23
  4510.2 2070.58  4517.9 2069.58  4522.9 2069.85  4550.2 2067.72  4570.3 2066.82
  4710.3 2063.86  4760.3 2063.35  4858.9 2061.32  4920.4 2060.97  4940.4 2060.44
  4990.4  2058.1  5000.2 2056.47 5019.32 2060.51  5029.2 2061.02  5116.2 2061.09
  5203.4 2062.41  5330.4  2064.9  5394.7 2065.66  5415.1 2066.62  5420.3 2066.58
  5462.6  2069.3  5467.8 2069.02    5505 2072.46  5510.1 2072.19    5539 2074.39
#Mann= 3 , 0 , 0
  4379.9     .05       0  4940.4    .035       0 5019.32     .05       0
Bank Sta=4940.4,5019.32
XS Rating Curve= 0 ,0
Exp/Cntr=0.3,0.1

Type RM Length L Ch R = 1 ,99      ,0,0,0
BEGIN DESCRIPTION:
UNT 0087 IN HEWA 1.0
END DESCRIPTION:
XS GIS Cut Line= 4
      2637993.37     10080900.79      2637304.16     10080697.67
      2637208.67     10080741.08      2637049.19     10081439.69
#Sta/Elev= 30
  4303.3  2078.8  4329.3 2077.81  4345.4 2076.12  4443.9  2071.8  4516.9 2067.03
  4522.5 2067.72  4548.2 2065.36  4579.5 2064.14  4725.4 2060.68  4850.5 2059.12
  4923.5 2059.15  4965.2 2058.02  4975.6 2057.09  4981.8  2055.8  4996.2 2054.19
  4999.5 2054.69  5006.9 2054.84  5015.1 2056.33  5023.5 2056.76  5075.1 2057.88
  5098.2 2058.39  5152.6 2058.12  5262.8 2058.67  5673.1 2065.17    5737 2066.71
  5755.1 2067.65    5780 2068.01  5822.9 2071.82  5828.1 2071.64  5843.3 2073.14
#Mann= 3 , 0 , 0
  4303.3     .05       0  4965.2    .035       0  5075.1     .05       0
#XS Ineff= 2 ,-1
  4303.3 4923.69 2059.16 5097.97 5228.07 2058.39
Permanent Ineff=
       T       T
Bank Sta=4965.2,5075.1
XS Rating Curve= 0 ,0
Exp/Cntr=0.3,0.1

Chan Stop Cuts=-1
Use User Specified Reach Order=0
Composite Channel Slope=5