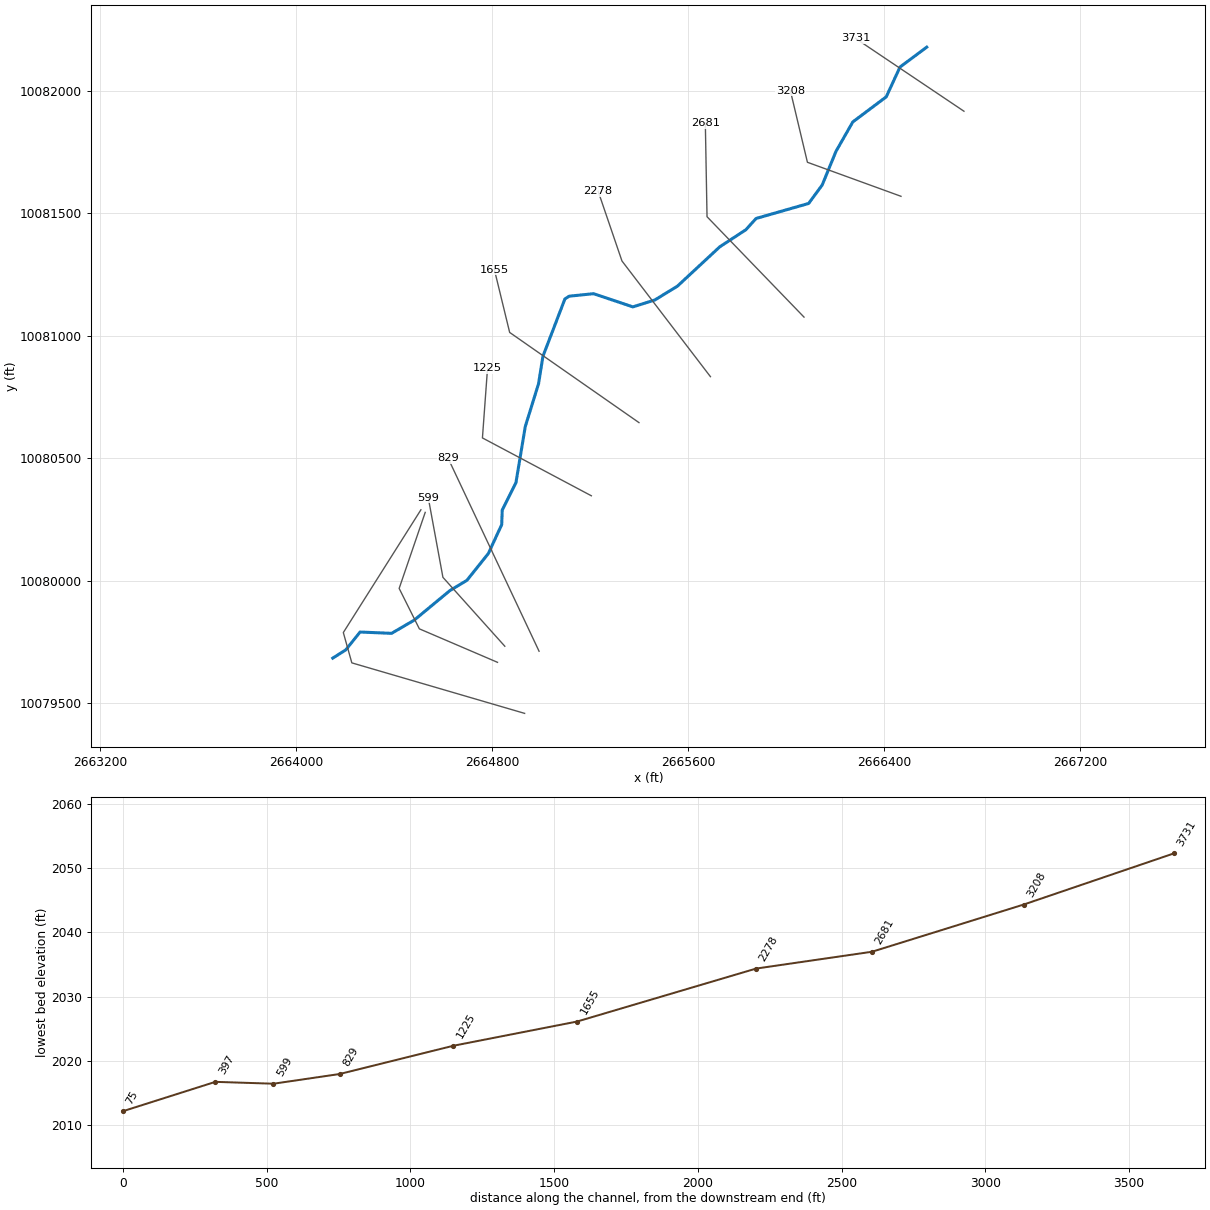
--- UNT 0089 IN HEWA.prj (project) ---

Proj Title=UNT 0089 IN HEWA Base Level Engineering
Current Plan=p01
Default Exp/Contr=0.3,0.1
English Units
Geom File=g01
Flow File=f01
Plan File=p01
Y Axis Title=Elevation
X Axis Title(PF)=Main Channel Distance
X Axis Title(XS)=Station
BEGIN DESCRIPTION:
UNT 0089 IN HEWA
END DESCRIPTION:
DSS Export Rating Curves= 0
DSS Export Rating Curve Sorted= 0
DSS Export Volume Flow Curves= 0
DXF OffsetX= 0
DXF OffsetY= 0
DXF ScaleX= 1
DXF ScaleY= 10

--- UNT 0089 IN HEWA.p01 (plan) ---

Plan Title=Multiple Run
Short Identifier=Multiple
Geom File=g01
Flow File=f01
Subcritical Flow
K Sum by GR= 0
Std Step Tol= 0.01
Critical Tol= 0.01
Num of Std Step Trials= 20
Max Error Tol= 0.3
Flow Tol Ratio= 0.001
Split Flow NTrial= 30
Split Flow Tol= 0.02
Split Flow Ratio= 0.02
Log Output Level= 0
Friction Slope Method= 1
Unsteady Friction Slope Method= 2
Unsteady Bridges Friction Slope Method= 1
Parabolic Critical Depth
Global Vel Dist=  1 , 1 , 1
Global Log Level= 0
CheckData=True
Encroach Param= -1, 0, 0, 0
BEGIN DESCRIPTION:
Multiple Run
END DESCRIPTION:

--- UNT 0089 IN HEWA.f01 (steady flow) ---

Flow Title=Multiple
Program Version=4.10
Number of Profiles= 7
Profile Names=10-year,25-year,50-year,1pct_min,100-year,1pct_plu,500-year
River Rch & RM=UNT 0089 IN HEWA,Reach-1         ,3731
    1351    1987    2542    2368    3202    4331    5085
Boundary for River Rch & Prof#=UNT 0089 IN HEWA,Reach-1         , 1
Up Type= 0
Dn Type= 3
Dn Slope=0.014
Boundary for River Rch & Prof#=UNT 0089 IN HEWA,Reach-1         , 2
Up Type= 0
Dn Type= 3
Dn Slope=0.014
Boundary for River Rch & Prof#=UNT 0089 IN HEWA,Reach-1         , 3
Up Type= 0
Dn Type= 3
Dn Slope=0.014
Boundary for River Rch & Prof#=UNT 0089 IN HEWA,Reach-1         , 4
Up Type= 0
Dn Type= 3
Dn Slope=0.014
Boundary for River Rch & Prof#=UNT 0089 IN HEWA,Reach-1         , 5
Up Type= 0
Dn Type= 3
Dn Slope=0.014
Boundary for River Rch & Prof#=UNT 0089 IN HEWA,Reach-1         , 6
Up Type= 0
Dn Type= 3
Dn Slope=0.014
Boundary for River Rch & Prof#=UNT 0089 IN HEWA,Reach-1         , 7
Up Type= 0
Dn Type= 3
Dn Slope=0.014
DSS Import GetInterval= 0
DSS Import GetPeak= 0
DSS Import FillOption= 0

--- UNT 0089 IN HEWA.g01 (geometry) ---

Geom Title=Existing Conditions
Program Version=4.10

River Reach=UNT 0089 IN HEWA,Reach-1
Reach XY= 30
      2666572.82     10082177.42      2666463.55     10082096.16
      2666407.52     10081974.64      2666270.93     10081872.18
      2666202.38     10081752.11      2666146.03      10081614.7
      2666090.72     10081539.45      2665876.25     10081478.19
      2665834.43     10081432.06      2665728.12     10081362.55
       2665555.1     10081201.82      2665462.76     10081145.36
      2665373.47     10081117.34      2665212.96     10081171.21
      2665113.77       10081161.      2665096.11     10081149.94
      2665006.23     10080915.59      2664988.46     10080803.83
      2664934.12     10080628.54      2664896.08     10080399.72
      2664840.19     10080287.98      2664838.04     10080228.51
      2664783.65     10080111.01        2664696.     10080001.32
      2664625.61     10079958.68      2664481.06     10079838.85
      2664388.63     10079784.92      2664259.99     10079790.29
      2664201.61     10079717.42      2664148.47     10079683.73

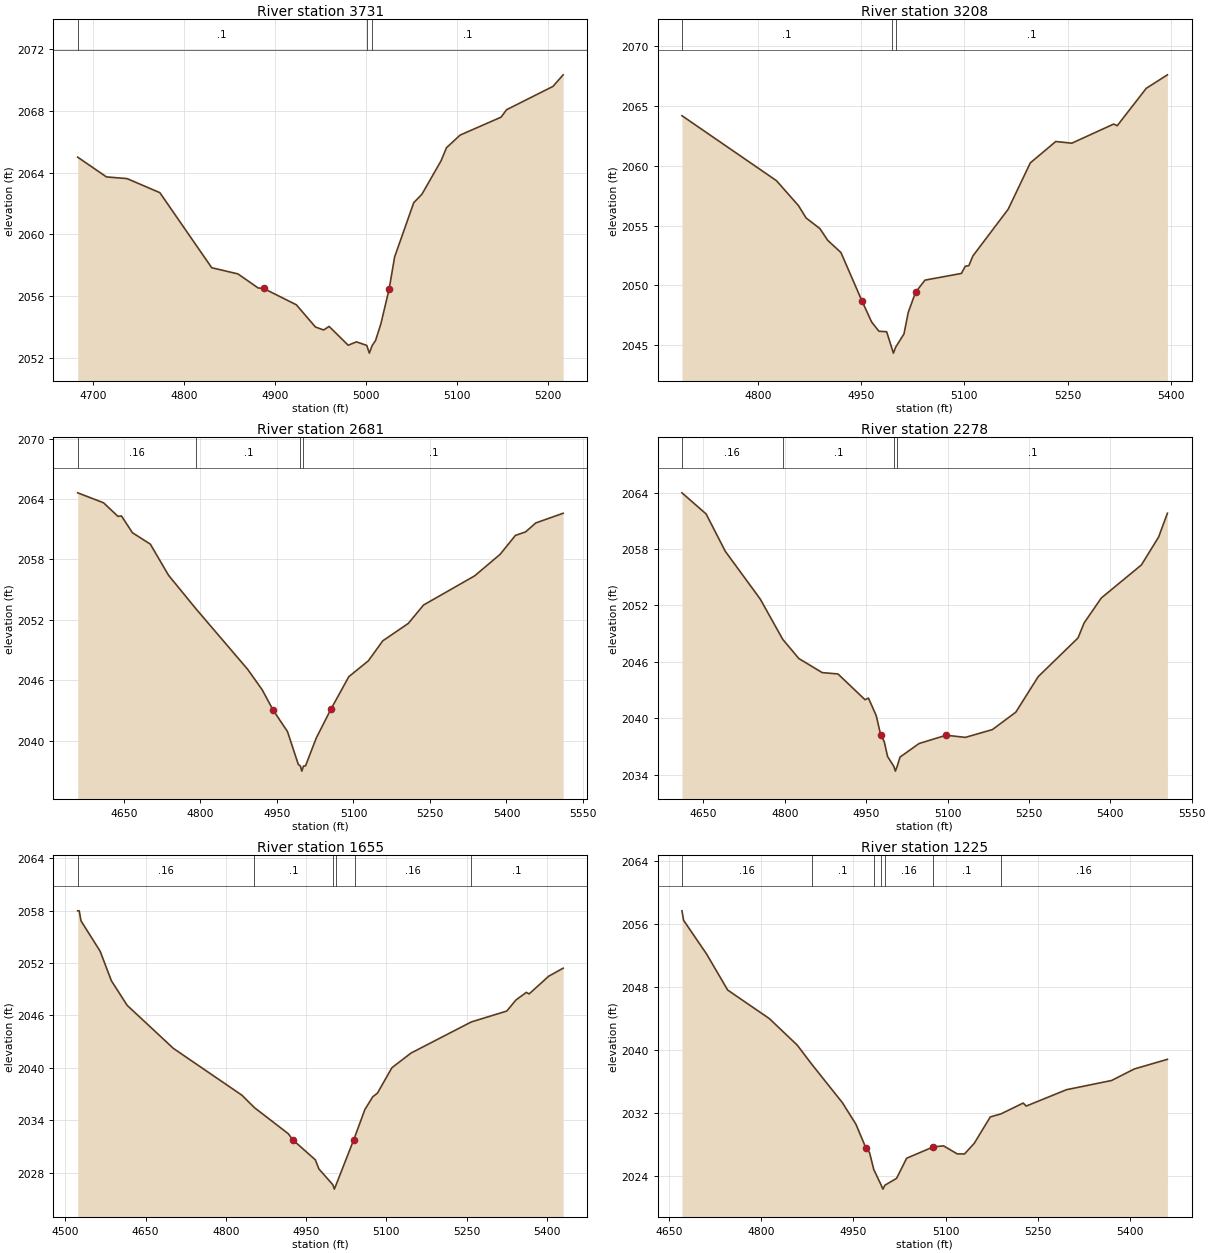
Type RM Length L Ch R = 1 ,3731    ,523,523,523
BEGIN DESCRIPTION:
UNT 0089 IN HEWA 6.0
END DESCRIPTION:
XS GIS Cut Line= 2
      2666724.67     10081915.87      2666281.84     10082213.39
#Sta/Elev= 30
  4683.1    2065  4714.7 2063.72  4737.4 2063.61  4773.4  2062.7  4830.4 2057.84
  4859.2 2057.44  4881.4 2056.53  4887.4  2056.5  4923.4 2055.44  4944.4    2054
  4953.4 2053.81  4959.4 2054.04  4980.4 2052.82  4989.4 2053.04  5000.8 2052.81
  5003.6 2052.31  5006.8 2052.81  5010.4 2053.12  5016.4 2054.23  5025.4 2056.47
  5031.4 2058.54  5052.4 2062.05  5061.4  2062.6  5082.4 2064.76  5088.4 2065.61
  5103.4 2066.43  5148.4 2067.59  5154.4 2068.07  5205.4 2069.58  5216.6 2070.33
#Mann= 3 ,-1 , 0
  4683.1      .1       0  5000.8     .07       0  5006.8      .1       0
Bank Sta=4887.4,5025.4
XS Rating Curve= 0 ,0
Exp/Cntr=0.3,0.1

Type RM Length L Ch R = 1 ,3208    ,527,527,527
BEGIN DESCRIPTION:
UNT 0089 IN HEWA 5.0
END DESCRIPTION:
XS GIS Cut Line= 3
      2666467.72     10081568.65      2666085.78     10081707.53
      2666016.39     10081998.98
#Sta/Elev= 30
  4689.3  2064.2  4826.8 2058.76  4858.8 2056.67  4869.9 2055.64  4889.9 2054.75
  4901.3 2053.77  4920.5 2052.75    4951 2048.71  4965.2 2046.93  4975.8 2046.16
    4987 2046.12  4994.1 2044.83  4996.8 2044.33  5000.1 2044.83  5012.2 2045.94
  5018.4 2047.74    5029 2049.42  5042.8 2050.44  5095.7    2051  5101.3  2051.6
  5106.5 2051.65  5112.4 2052.46  5163.8 2056.38  5195.9 2060.25  5232.9 2062.04
  5256.3  2061.9  5317.2  2063.5  5322.3 2063.36  5364.5 2066.49  5395.3 2067.62
#Mann= 3 ,-1 , 0
  4689.3      .1       0  4994.1     .07       0  5000.1      .1       0
Bank Sta=4951,5029
XS Rating Curve= 0 ,0
Exp/Cntr=0.3,0.1

Type RM Length L Ch R = 1 ,2681    ,403,403,403
BEGIN DESCRIPTION:
UNT 0089 IN HEWA 4.0
END DESCRIPTION:
XS GIS Cut Line= 3
      2666071.88     10081075.61      2665676.06     10081485.31
      2665669.12     10081867.27
#Sta/Elev= 30
  4559.4 2064.62  4610.1 2063.63  4638.4 2062.28  4645.3 2062.32  4666.7 2060.66
  4701.9 2059.52  4737.4 2056.44  4791.8 2053.07  4892.8 2047.08  4921.1 2045.06
  4942.4 2043.05  4970.7 2040.91  4991.8 2037.66    4996 2037.48  4998.8 2036.98
    5002 2037.48    5006  2037.5  5027.3 2040.29  5055.6 2043.11  5090.9 2046.36
  5129.1 2047.93  5157.5 2049.92  5207.5 2051.65  5237.5 2053.48  5337.5 2056.37
  5387.5 2058.51  5417.5 2060.39  5437.5 2060.74  5457.5 2061.63  5511.1 2062.59
#Mann= 4 ,-1 , 0
  4559.4     .16       0  4791.8      .1       0    4996     .07       0
    5002      .1       0
Bank Sta=4942.4,5055.6
XS Rating Curve= 0 ,0
Exp/Cntr=0.3,0.1

Type RM Length L Ch R = 1 ,2278    ,623,623,623
BEGIN DESCRIPTION:
UNT 0089 IN HEWA 3.0
END DESCRIPTION:
XS GIS Cut Line= 3
      2665689.93     10080832.56      2665328.84     10081304.75
      2665231.75     10081589.09
#Sta/Elev= 30
  4610.4 2063.97    4655 2061.72  4690.3 2057.75  4754.7 2052.67  4796.2 2048.38
  4825.9 2046.34    4869 2044.84    4898  2044.7  4947.9 2041.96  4954.2 2042.13
  4968.7 2040.24  4976.9 2038.16  4983.2 2037.52  4989.5 2035.91  5001.1 2034.86
  5003.8 2034.36  5007.1 2034.86  5012.3 2035.85  5047.6  2037.3  5097.5 2038.18
  5132.8 2037.95  5182.7 2038.78  5225.8 2040.63  5267.2 2044.42  5340.5 2048.53
  5351.7 2050.12  5383.4 2052.78  5457.4  2056.3  5489.1 2059.27  5505.3  2061.8
#Mann= 4 ,-1 , 0
  4610.4     .16       0  4796.2      .1       0  5001.1     .07       0
  5007.1      .1       0
Bank Sta=4976.9,5097.5
XS Rating Curve= 0 ,0
Exp/Cntr=0.3,0.1

Type RM Length L Ch R = 1 ,1655    ,430,430,430
BEGIN DESCRIPTION:
UNT 0089 IN HEWA 2.0
END DESCRIPTION:
XS GIS Cut Line= 3
      2665398.27     10080645.04       2664870.5     10081013.09
      2664808.16     10081269.39
#Sta/Elev= 30
  4523.1 2057.98    4526 2057.98  4529.3 2056.83    4565 2053.36    4586 2049.98
  4615.6 2047.15    4702 2042.22  4830.2 2036.85  4853.5 2035.43  4916.6 2032.45
  4925.2 2031.74  4967.2 2029.46  4973.9 2028.41    5000  2026.6  5002.7  2026.1
    5006  2026.6  5038.8 2031.73  5042.2 2032.29  5059.7 2035.21  5074.5 2036.68
  5083.3  2037.1  5110.3 2040.01  5146.1 2041.69  5258.6 2045.25    5325  2046.5
  5342.1 2047.77  5361.6 2048.64  5366.7 2048.46  5403.3 2050.49  5430.3 2051.41
#Mann= 6 ,-1 , 0
  4523.1     .16       0  4853.5      .1       0    5000     .07       0
    5006      .1       0  5042.2     .16       0  5258.6      .1       0
Bank Sta=4925.2,5038.8
XS Rating Curve= 0 ,0
Exp/Cntr=0.3,0.1

Type RM Length L Ch R = 1 ,1225    ,396,396,396
BEGIN DESCRIPTION:
Mapping XS 7c5fdfa7
END DESCRIPTION:
XS GIS Cut Line= 3
      2665203.87      10080346.4      2664759.39     10080582.53
      2664780.23     10080867.26
#Sta/Elev= 30
  4671.5 2057.71  4674.2  2056.5  4711.6 2052.21  4745.8 2047.64  4813.5 2044.01
  4858.8 2040.64  4882.4 2038.21  4932.3 2033.31  4954.3 2030.56  4970.6 2027.53
  4976.3 2026.97  4983.2 2024.82  4995.3 2022.83    4998 2022.33  5001.3 2022.83
  5020.2  2023.7  5036.6 2026.26  5079.9  2027.7  5096.6 2027.83  5118.8 2026.81
  5130.6  2026.8  5146.5 2028.16  5172.5 2031.51  5189.7 2031.89  5225.9 2033.27
  5230.9 2032.89  5296.3 2034.97  5369.6 2036.14  5406.6 2037.61  5460.3 2038.83
#Mann= 7 ,-1 , 0
  4671.5     .16       0  4882.4      .1       0  4983.2     .16       0
  4995.3     .07       0  5001.3     .16       0  5079.9      .1       0
  5189.7     .16       0
Bank Sta=4970.6,5079.9
XS Rating Curve= 0 ,0
Exp/Cntr=0.3,0.1

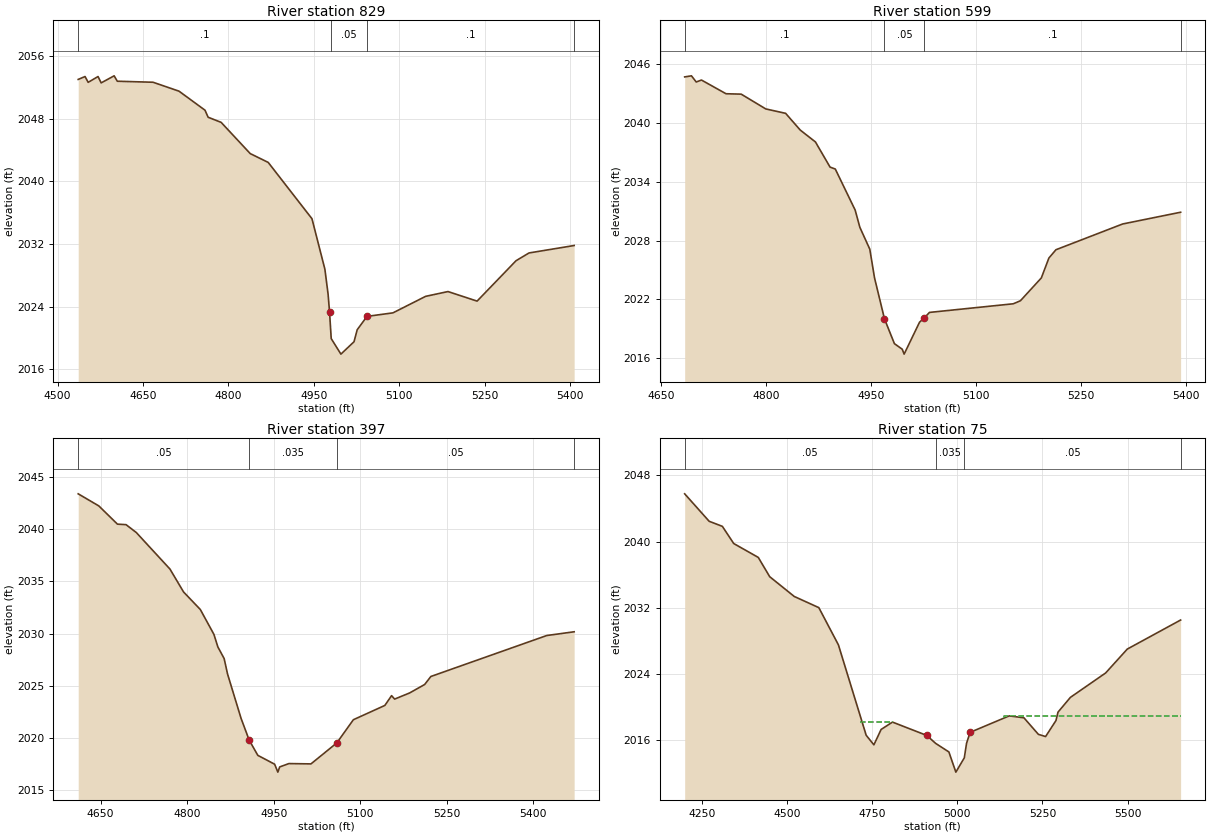
Type RM Length L Ch R = 1 ,829     ,230,230,230
BEGIN DESCRIPTION:
Mapping XS ab72b0c6
END DESCRIPTION:
XS GIS Cut Line= 2
       2664990.5     10079711.95      2664619.28     10080499.55
#Sta/Elev= 30
  4536.3    2053  4548.3 2053.37  4553.8 2052.63  4571.1 2053.37  4576.6 2052.56
  4599.4 2053.46  4604.9 2052.77  4667.7 2052.64  4713.3  2051.5  4758.9 2049.07
  4764.4 2048.17  4787.2 2047.52  4838.3 2043.53  4869.9  2042.4  4946.7 2035.21
  4969.4 2028.76    4975 2025.58  4977.5 2023.36  4980.5  2019.9  4997.5 2017.92
  5020.5  2019.5  5026.1 2021.03  5043.3 2022.74  5088.9 2023.19  5146.3  2025.3
  5185.5 2025.91  5236.6 2024.69    5305 2029.85  5327.8 2030.84    5407 2031.79
#Mann= 4 ,-1 , 0
  4536.3      .1       0  4980.5     .05       0  5043.3      .1       0
    5407      .1       0
Bank Sta=4977.5,5043.3
XS Rating Curve= 0 ,0
Exp/Cntr=0.3,0.1

Type RM Length L Ch R = 1 ,599     ,202,202,202
BEGIN DESCRIPTION:
Mapping XS 0fe6d0bc
END DESCRIPTION:
XS GIS Cut Line= 3
      2664850.73     10079732.31       2664598.1     10080013.59
      2664538.23     10080338.95
#Sta/Elev= 30
  4683.8 2044.72  4693.5 2044.83  4700.3  2044.2  4707.8  2044.4  4742.9    2043
  4764.6 2042.96  4799.7 2041.45  4828.1    2041    4849 2039.29  4870.7 2038.08
  4891.6 2035.51  4899.1 2035.31  4927.5 2031.12  4934.2 2029.36  4948.4 2027.13
  4955.2 2024.19  4969.4 2020.01  4983.6 2017.48  4994.8 2016.91  4997.5 2016.41
  5019.5 2019.67  5026.2  2020.1  5033.7 2020.67  5153.5 2021.55  5163.7 2021.86
  5193.6 2024.19  5204.4 2026.22  5214.5 2027.07  5309.8  2029.7  5392.7  2030.9
#Mann= 4 ,-1 , 0
  4683.8      .1       0  4969.4     .05       0  5026.2      .1       0
  5392.7     .05       0
Bank Sta=4969.4,5026.2
XS Rating Curve= 0 ,0
Exp/Cntr=0.3,0.1

Type RM Length L Ch R = 1 ,397     ,322,322,322
BEGIN DESCRIPTION:
Mapping XS dca9656b
END DESCRIPTION:
XS GIS Cut Line= 4
      2664820.92     10079666.64      2664501.96     10079803.34
      2664419.49     10079968.27      2664525.84     10080278.63
#Sta/Elev= 30
  4611.1 2043.41  4646.8 2042.25  4679.1  2040.5    4694 2040.45  4711.7  2039.7
  4770.1 2036.19  4793.7 2033.99  4822.7 2032.31  4846.3 2029.92  4853.1 2028.72
    4864  2027.6  4869.9 2026.12  4893.4 2021.85  4907.5 2019.76  4922.4 2018.31
  4951.5 2017.46  4957.1  2016.7  4960.3  2017.2  4976.2 2017.52  5014.5 2017.49
  5059.2  2019.5    5088 2021.73  5142.5  2023.1  5154.2 2024.04  5159.5 2023.71
  5185.5  2024.3  5211.5 2025.11  5222.3 2025.88  5423.1 2029.81  5470.6 2030.17
#Mann= 4 ,-1 , 0
  4611.1     .05       0  4907.5    .035       0  5059.2     .05       0
  5470.6     .05       0
Bank Sta=4907.5,5059.2
XS Rating Curve= 0 ,0
Exp/Cntr=0.3,0.1

Type RM Length L Ch R = 1 ,75      ,0,0,0
BEGIN DESCRIPTION:
UNT 0089 IN HEWA 1.0
END DESCRIPTION:
XS GIS Cut Line= 4
       2664931.6      10079458.3      2664226.35     10079664.45
      2664191.63     10079788.15      2664508.26     10080289.13
#Sta/Elev= 30
  4199.8 2045.77  4271.7 2042.45  4310.4 2041.84  4343.8 2039.76  4415.9 2038.08
  4449.4 2035.75  4521.5 2033.36  4593.6 2032.01  4651.1 2027.51  4732.6 2016.58
  4755.2 2015.42  4776.5 2017.28  4809.9 2018.17  4910.3 2016.56  4936.8 2015.59
  4975.4 2014.56  4995.9 2012.12  5020.7 2013.85  5027.3 2015.61  5037.7 2016.93
  5152.5 2018.92  5195.7 2018.69  5238.1 2016.69  5259.3 2016.42  5289.8 2018.36
  5295.7 2019.37  5332.2 2021.16  5435.6 2024.11  5499.2    2027  5655.7 2030.51
#Mann= 4 ,-1 , 0
  4199.8     .05       0  4936.8    .035       0  5020.7     .05       0
  5655.7     .05       0
#XS Ineff= 2 ,-1
 4713.85  4809.9 2018.18 5137.93  5655.7 2018.92
Permanent Ineff=
       T       T
Bank Sta=4910.3,5037.7
XS Rating Curve= 0 ,0
Exp/Cntr=0.3,0.1

Chan Stop Cuts=-1
Use User Specified Reach Order=0
Composite Channel Slope=5