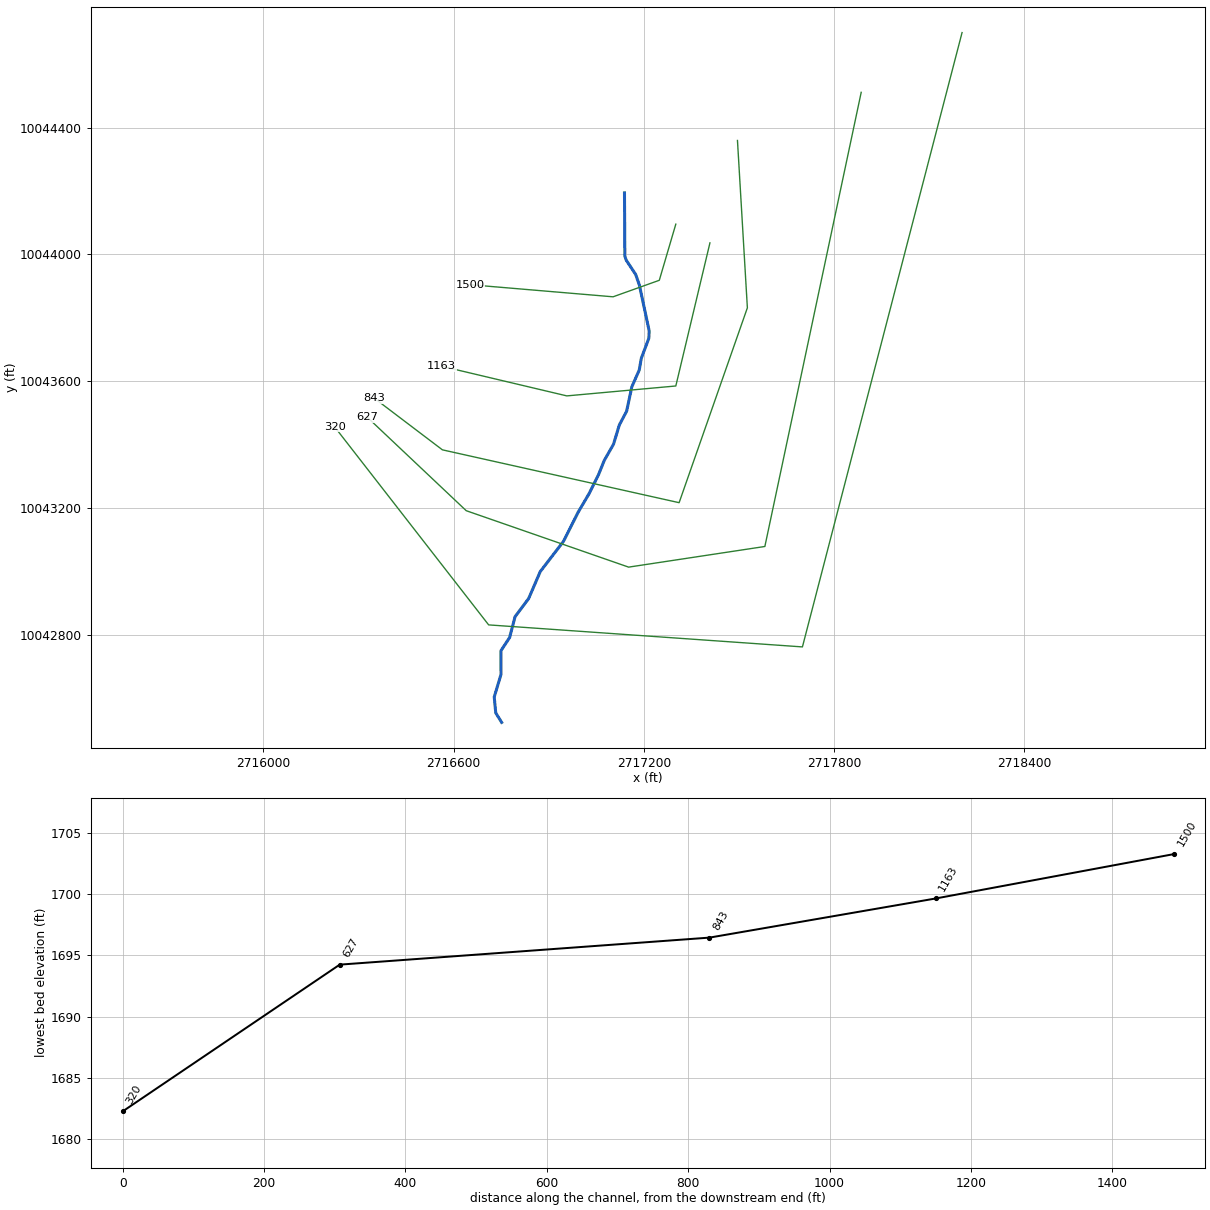
--- UNT 0091 IN HEWA.prj (project) ---

Proj Title=UNT 0091 IN HEWA Base Level Engineering
Current Plan=p01
Default Exp/Contr=0.3,0.1
English Units
Geom File=g01
Flow File=f01
Plan File=p01
Y Axis Title=Elevation
X Axis Title(PF)=Main Channel Distance
X Axis Title(XS)=Station
BEGIN DESCRIPTION:
UNT 0091 IN HEWA
END DESCRIPTION:
DSS Export Rating Curves= 0
DSS Export Rating Curve Sorted= 0
DSS Export Volume Flow Curves= 0
DXF OffsetX= 0
DXF OffsetY= 0
DXF ScaleX= 1
DXF ScaleY= 10

--- UNT 0091 IN HEWA.p01 (plan) ---

Plan Title=Multiple Run
Short Identifier=Multiple
Geom File=g01
Flow File=f01
Subcritical Flow
K Sum by GR= 0
Std Step Tol= 0.01
Critical Tol= 0.01
Num of Std Step Trials= 20
Max Error Tol= 0.3
Flow Tol Ratio= 0.001
Split Flow NTrial= 30
Split Flow Tol= 0.02
Split Flow Ratio= 0.02
Log Output Level= 0
Friction Slope Method= 1
Unsteady Friction Slope Method= 2
Unsteady Bridges Friction Slope Method= 1
Parabolic Critical Depth
Global Vel Dist=  1 , 1 , 1
Global Log Level= 0
CheckData=True
Encroach Param= -1, 0, 0, 0
BEGIN DESCRIPTION:
Multiple Run
END DESCRIPTION:

--- UNT 0091 IN HEWA.f01 (steady flow) ---

Flow Title=Multiple
Number of Profiles=7
Profile Names=10-year,25-year,50-year,1pct_min,100-year,1pct_plu,500-year
River Rch & RM= UNT 0091 IN HEWA,Reach-1,1500
     470     646     789     705     953    1289    1390
Boundary for River Rch & Prof#=UNT 0091 IN HEWA,Reach-1,1
Up Type=0
Dn Type=3
Dn Slope=0.005
Boundary for River Rch & Prof#=UNT 0091 IN HEWA,Reach-1,2
Up Type=0
Dn Type=3
Dn Slope=0.005
Boundary for River Rch & Prof#=UNT 0091 IN HEWA,Reach-1,3
Up Type=0
Dn Type=3
Dn Slope=0.005
Boundary for River Rch & Prof#=UNT 0091 IN HEWA,Reach-1,4
Up Type=0
Dn Type=3
Dn Slope=0.005
Boundary for River Rch & Prof#=UNT 0091 IN HEWA,Reach-1,5
Up Type=0
Dn Type=3
Dn Slope=0.005
Boundary for River Rch & Prof#=UNT 0091 IN HEWA,Reach-1,6
Up Type=0
Dn Type=3
Dn Slope=0.005
Boundary for River Rch & Prof#=UNT 0091 IN HEWA,Reach-1,7
Up Type=0
Dn Type=3
Dn Slope=0.005

--- UNT 0091 IN HEWA.g01 (geometry) ---

Geom Title=Existing Conditions
Program Version=4.10

River Reach=UNT 0091 IN HEWA,Reach-1
Reach XY= 27
       2717138.6     10044193.85      2717139.76     10043994.27
      2717144.21      10043981.4      2717173.93     10043936.57
       2717185.7     10043902.59      2717216.59     10043757.95
      2717215.35     10043735.04      2717191.68     10043672.43
      2717185.12     10043635.12       2717161.8     10043582.35
       2717145.3     10043505.04       2717122.4      10043462.1
      2717103.92      10043400.9      2717075.04     10043350.44
      2717056.45     10043304.57      2717026.52     10043244.54
      2716992.49     10043186.78      2716946.04     10043094.58
       2716872.8     10042999.29      2716836.31     10042914.47
      2716793.51     10042857.18      2716776.32     10042791.61
      2716748.96     10042749.87      2716749.03     10042674.71
      2716727.79     10042604.03      2716732.56     10042553.83
      2716751.29     10042523.79

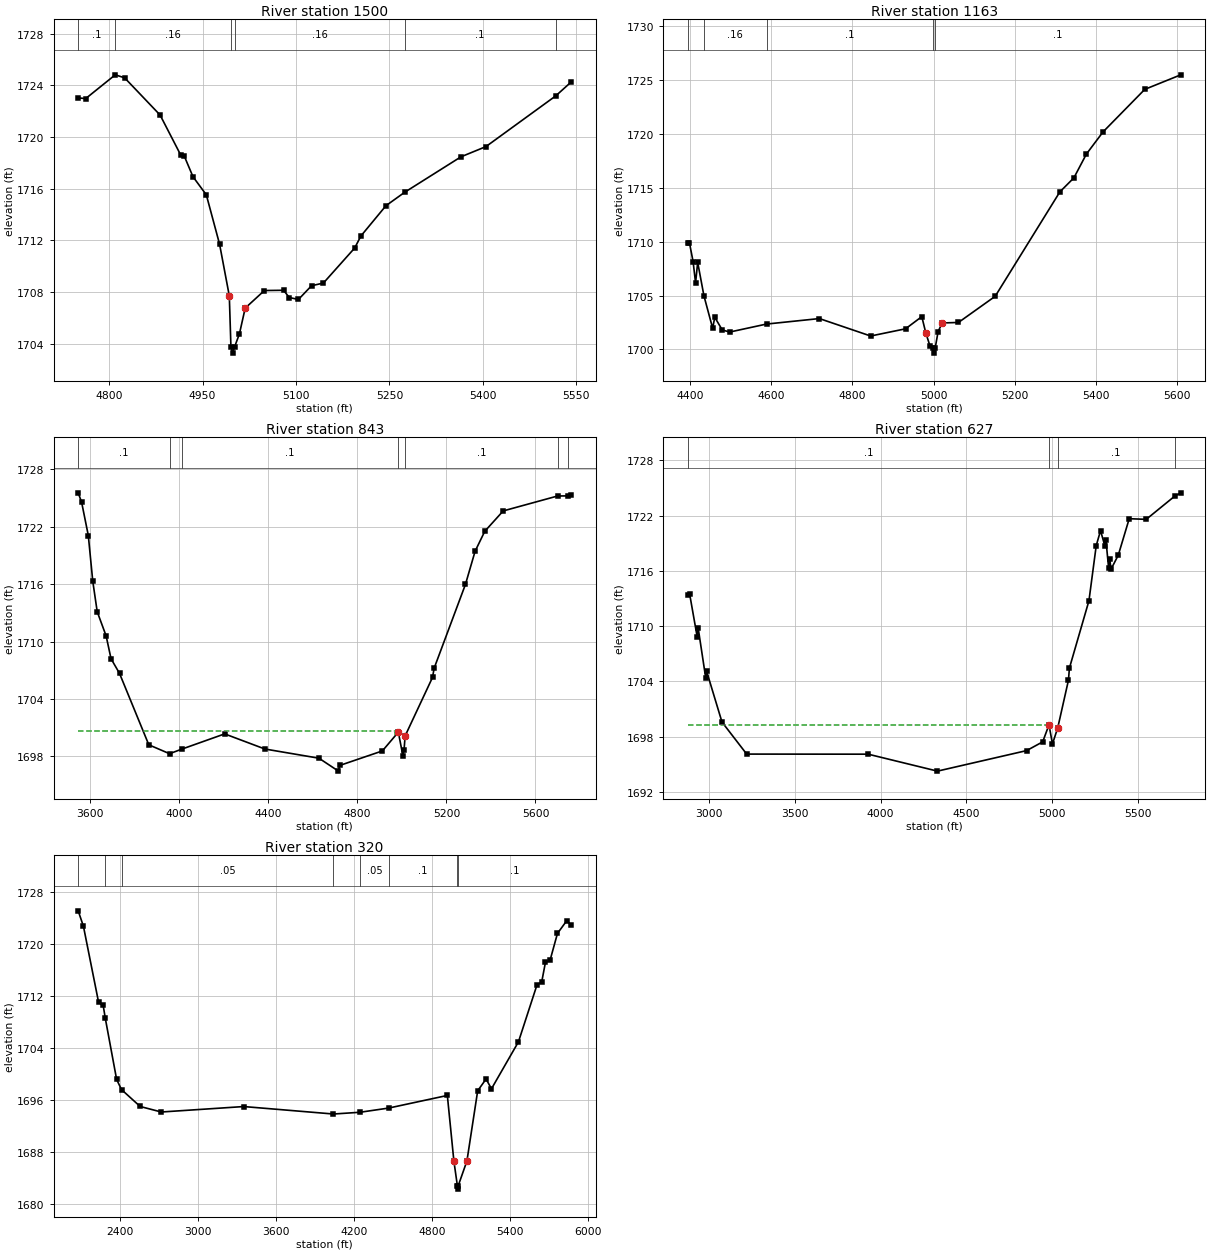
Type RM Length L Ch R = 1 ,1500    ,337,337,337
BEGIN DESCRIPTION:
UNT 0091 IN HEWA 3.0
END DESCRIPTION:
XS GIS Cut Line= 4
      2717300.47     10044095.25      2717248.39     10043918.19
      2717102.56      10043866.1      2716652.28      10043904.2
#Sta/Elev= 30
  4750.3 1723.03  4762.3 1722.97  4809.8 1724.81  4824.8 1724.58  4881.8  1721.7
  4915.2 1718.58  4920.4 1718.55  4934.6 1716.93    4956 1715.53  4977.3 1711.71
  4992.9 1707.72  4995.5 1703.79  4998.2 1703.29  5001.5 1703.79  5009.1 1704.77
  5018.4 1706.77  5049.2 1708.13    5080 1708.15  5089.2 1707.59  5103.9 1707.44
  5124.9  1708.5    5144 1708.71  5194.2 1711.42  5204.2 1712.35  5244.4 1714.69
  5274.5 1715.73  5364.8 1718.47  5404.9 1719.26  5516.9 1723.18  5541.6 1724.25
#Mann= 6 ,-1 , 0
  4750.3      .1       0  4809.8     .16       0  4995.5     .07       0
  5001.5     .16       0  5274.5      .1       0  5516.9     .16       0
Bank Sta=4992.9,5018.4
XS Rating Curve= 0 ,0
Exp/Cntr=0.3,0.1

Type RM Length L Ch R = 1 ,1163    ,320,320,320
BEGIN DESCRIPTION:
Mapping XS aac4f921
END DESCRIPTION:
XS GIS Cut Line= 4
      2717408.11     10044036.23      2717300.48     10043584.85
      2716956.73      10043553.6      2716562.15     10043647.06
#Sta/Elev= 30
  4394.5 1709.91  4398.4 1709.91  4407.4 1708.16  4413.5 1706.18  4418.7 1708.09
  4434.2 1704.97  4455.6 1701.97  4460.8 1702.99  4479.3 1701.81  4497.8 1701.62
  4588.3 1702.36  4718.6 1702.87    4845 1701.25    4931 1701.92    4971 1703.05
  4981.1  1701.5  4991.1 1700.34  4998.1 1700.16  5000.9 1699.66  5004.1 1700.16
  5011.2 1701.66  5021.2 1702.46  5061.4 1702.51  5151.9 1704.94  5311.3 1714.64
  5345.8 1715.94  5376.6 1718.15  5417.7 1720.21  5520.5 1724.16  5609.2 1725.51
#Mann= 5 ,-1 , 0
  4394.5      .1       0  4434.2     .16       0  4588.3      .1       0
  4998.1     .07       0  5004.1      .1       0
Bank Sta=4981.1,5021.2
XS Rating Curve= 0 ,0
Exp/Cntr=0.3,0.1

Type RM Length L Ch R = 1 ,843     ,523,523,523
BEGIN DESCRIPTION:
UNT 0091 IN HEWA 2.0
END DESCRIPTION:
XS GIS Cut Line= 5
      2717494.92     10044359.12      2717526.17     10043831.38
      2717310.89      10043216.8      2716564.37     10043383.46
      2716349.09     10043546.66
#Sta/Elev= 30
  3545.2 1725.53  3560.6 1724.55  3590.7 1721.07  3610.7  1716.3  3630.7 1713.11
  3670.8 1710.58  3692.8  1708.2  3730.9 1706.67  3862.5 1699.21  3955.7 1698.28
    4011 1698.76  4203.4 1700.35  4384.2 1698.77  4627.1 1697.81  4714.6 1696.46
  4720.1 1697.05    4912 1698.57  4983.7 1700.53  5004.2 1698.09  5009.3 1698.62
  5014.4 1700.14  5137.4 1706.25  5144.7 1707.21  5285.3 1715.96  5328.8 1719.43
  5372.2 1721.51    5455 1723.64  5699.7  1725.2  5744.8 1725.21  5760.1 1725.26
#Mann= 7 ,-1 , 0
  3545.2      .1       0  3955.7     .16       0    4011      .1       0
  4983.7     .07       0  5014.4      .1       0  5699.7     .05       0
  5744.8      .1       0
#XS Ineff= 2 , 0
       0 4968.91 1700.64               0
Permanent Ineff=
       T       T
Bank Sta=4983.7,5014.4
XS Rating Curve= 0 ,0
Exp/Cntr=0.3,0.1

Type RM Length L Ch R = 1 ,627     ,307,307,307
BEGIN DESCRIPTION:
Mapping XS c2a59ac4
END DESCRIPTION:
XS GIS Cut Line= 5
      2717885.16       10044511.      2717581.33     10043078.67
      2717151.65     10043013.56      2716639.49     10043191.52
      2716327.01     10043486.64
#Sta/Elev= 30
  2877.4  1713.4  2887.8 1713.48  2932.3 1708.77  2937.4 1709.79  2981.9 1704.31
  2987.1 1705.07  3076.1 1699.58    3220  1696.1  3927.5 1696.09  4331.1 1694.25
  4850.6 1696.48    4944 1697.43  4980.7 1699.28  5000.9  1697.2    5032 1698.98
  5094.2 1704.14  5099.5 1705.43  5213.4 1712.75  5255.9 1718.75  5280.9 1720.36
  5306.7 1718.67    5312  1719.4  5327.8 1716.35  5334.7 1717.26  5341.9 1716.17
  5384.4 1717.71  5447.9 1721.66    5547 1721.59  5712.4  1724.1  5748.2 1724.47
#Mann= 4 ,-1 , 0
  2877.4      .1       0  4980.7     .07       0    5032      .1       0
  5712.4     .05       0
#XS Ineff= 2 , 0
         4979.58 1699.23
Permanent Ineff=
       T       T
Bank Sta=4980.7,5032
XS Rating Curve= 0 ,0
Exp/Cntr=0.3,0.1

Type RM Length L Ch R = 1 ,320     ,0,0,0
BEGIN DESCRIPTION:
UNT 0091 IN HEWA 1.0
END DESCRIPTION:
XS GIS Cut Line= 4
      2718203.25     10044699.42      2717699.78     10042761.94
       2716710.2     10042831.38      2716224.11     10043456.35
#Sta/Elev= 30
  2081.5 1725.12    2122 1722.72  2238.4 1711.01  2273.4 1710.56  2289.5 1708.59
  2376.7 1699.15  2414.3 1697.58  2557.6 1694.98  2719.8 1694.13    3353 1694.97
  4042.1 1693.82  4245.8 1694.09    4467 1694.74  4916.7 1696.68  4966.8 1686.59
  4993.9 1682.75  4996.6 1682.25  4999.9 1682.75  5067.1 1686.59  5149.7  1697.4
    5214 1699.21  5255.7 1697.71  5462.8 1704.94  5605.8 1713.75  5641.1 1714.13
  5670.1 1717.19  5705.3 1717.48  5762.4 1721.64  5833.8  1723.6  5867.1 1722.93
#Mann= 8 ,-1 , 0
  2081.5     .05       0  2289.5      .1       0  2414.3     .05       0
  4042.1      .1       0  4245.8     .05       0    4467      .1       0
  4993.9     .07       0  4999.9      .1       0
Bank Sta=4966.8,5067.1
XS Rating Curve= 0 ,0
Exp/Cntr=0.3,0.1

Chan Stop Cuts=-1
Use User Specified Reach Order=0
Composite Channel Slope=5