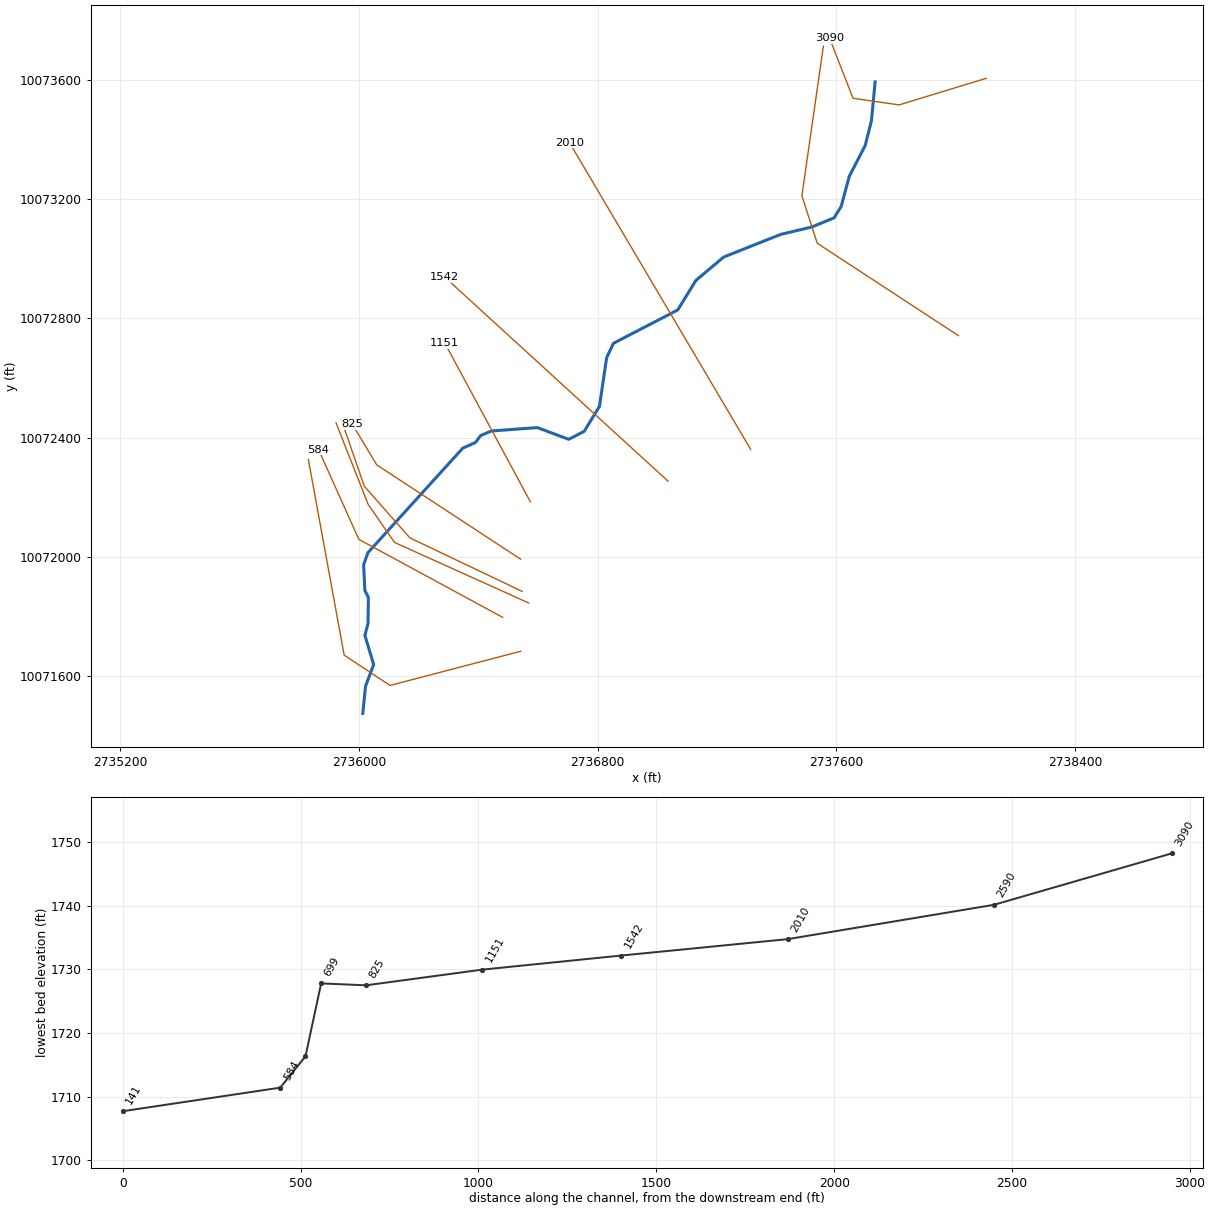
--- UNT 0092 IN HEWA.prj (project) ---

Proj Title=UNT 0092 IN HEWA Base Level Engineering
Current Plan=p01
Default Exp/Contr=0.3,0.1
English Units
Geom File=g01
Flow File=f01
Plan File=p01
BEGIN DESCRIPTION:
UNT 0092 IN HEWA
END DESCRIPTION:

--- UNT 0092 IN HEWA.p01 (plan) ---

Plan Title=Multiple Run
Short Identifier=Multiple
Geom File=g01
Flow File=f01
Subcritical Flow
K Sum by GR= 0
Std Step Tol= 0.01
Critical Tol= 0.01
Num of Std Step Trials= 20
Max Error Tol= 0.3
Flow Tol Ratio= 0.001
Split Flow NTrial= 30
Split Flow Tol= 0.02
Split Flow Ratio= 0.02
Log Output Level= 0
Friction Slope Method= 1
Unsteady Friction Slope Method= 2
Unsteady Bridges Friction Slope Method= 1
Parabolic Critical Depth
Global Vel Dist=  1 , 1 , 1
Global Log Level= 0
CheckData=True
Encroach Param= -1, 0, 0, 0
BEGIN DESCRIPTION:
Multiple Run
END DESCRIPTION:

--- UNT 0092 IN HEWA.f01 (steady flow) ---

Flow Title=Multiple
Number of Profiles=7
Profile Names=10-year,25-year,50-year,1pct_min,100-year,1pct_plu,500-year
River Rch & RM= UNT 0092 IN HEWA,Reach-1,3090
     703    1017    1290    1199    1621    2193    2572
Boundary for River Rch & Prof#=UNT 0092 IN HEWA,Reach-1,1
Up Type=0
Dn Type=3
Dn Slope=0.005
Boundary for River Rch & Prof#=UNT 0092 IN HEWA,Reach-1,2
Up Type=0
Dn Type=3
Dn Slope=0.005
Boundary for River Rch & Prof#=UNT 0092 IN HEWA,Reach-1,3
Up Type=0
Dn Type=3
Dn Slope=0.005
Boundary for River Rch & Prof#=UNT 0092 IN HEWA,Reach-1,4
Up Type=0
Dn Type=3
Dn Slope=0.005
Boundary for River Rch & Prof#=UNT 0092 IN HEWA,Reach-1,5
Up Type=0
Dn Type=3
Dn Slope=0.005
Boundary for River Rch & Prof#=UNT 0092 IN HEWA,Reach-1,6
Up Type=0
Dn Type=3
Dn Slope=0.005
Boundary for River Rch & Prof#=UNT 0092 IN HEWA,Reach-1,7
Up Type=0
Dn Type=3
Dn Slope=0.005

--- UNT 0092 IN HEWA.g01 (geometry) ---

Geom Title=Existing Conditions

River Reach=UNT 0092 IN HEWA,Reach-1
Reach XY= 30
      2737729.44     10073593.34      2737717.23     10073463.77
      2737696.09     10073379.72      2737642.90     10073276.61
      2737615.52     10073174.78      2737591.84     10073137.25
      2737517.34     10073106.52      2737414.15     10073082.07
      2737222.32     10073005.77      2737129.00     10072927.17
      2737068.35     10072828.13      2736853.21     10072716.47
      2736830.28     10072668.35      2736806.19     10072504.66
      2736754.97     10072420.91      2736703.29     10072394.10
      2736597.98     10072433.56      2736444.95     10072422.20
      2736408.67     10072407.00      2736390.73     10072383.35
      2736348.48     10072364.56      2736030.92     10072013.97
      2736016.30     10071973.17      2736020.47     10071886.76
      2736032.21     10071863.46      2736031.18     10071776.99
      2736020.71     10071736.24      2736050.02     10071638.15
      2736022.76     10071565.94      2736013.48     10071474.57

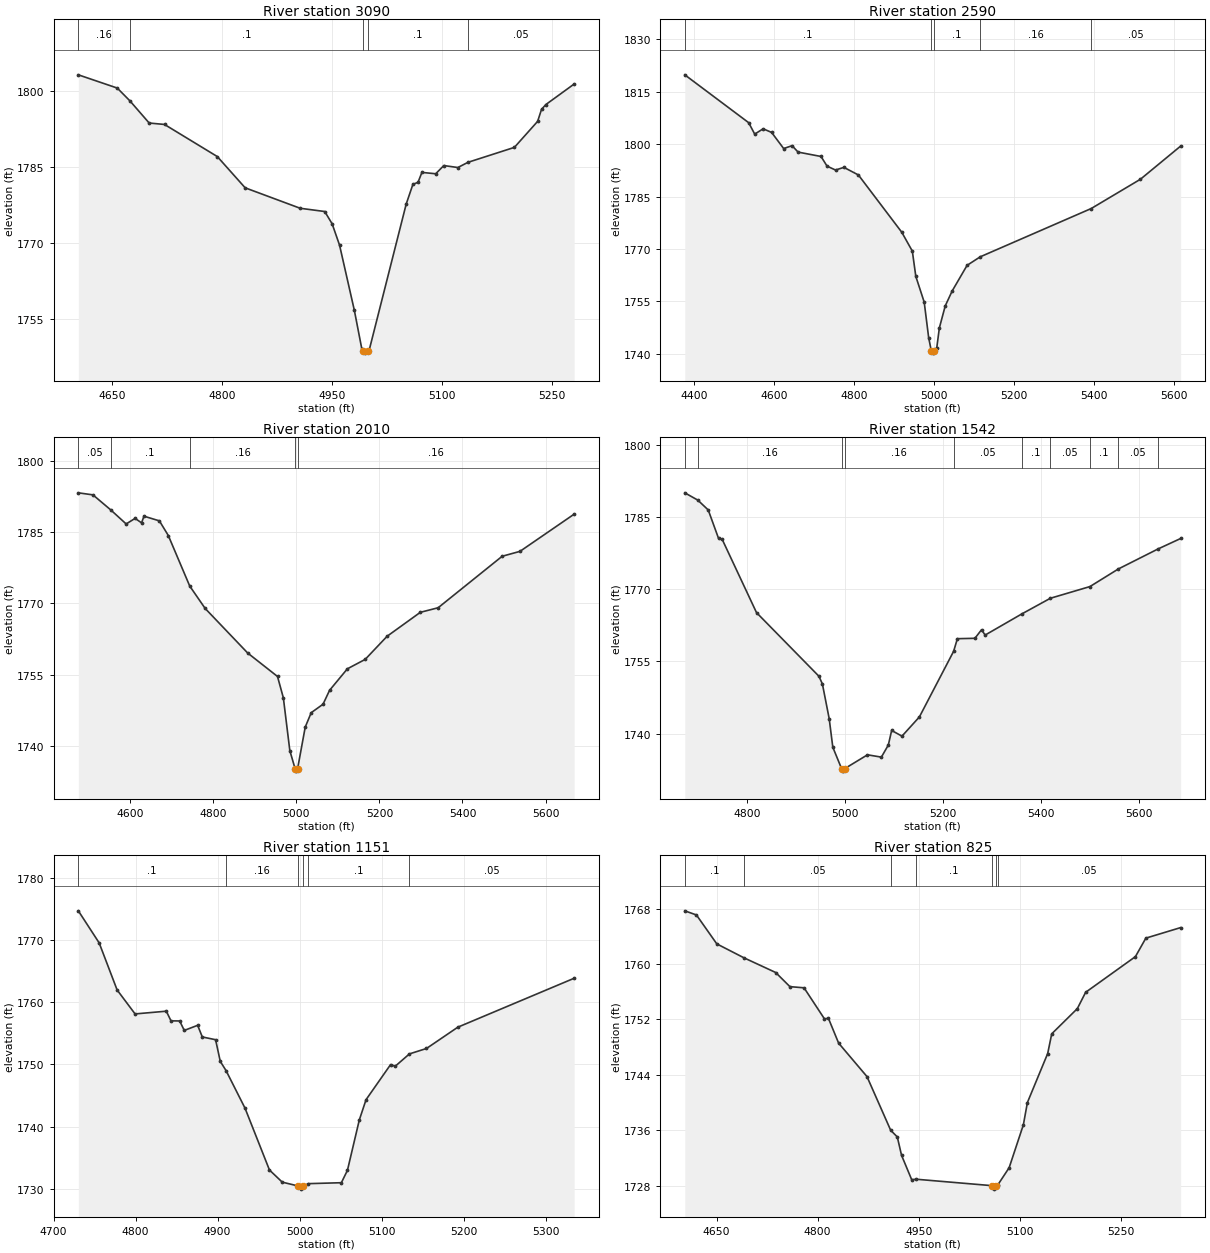
Type RM Length L Ch R = 1,3090,500,500,500
BEGIN DESCRIPTION:
UNT 0092 IN HEWA 6.0
END DESCRIPTION:
XS GIS Cut Line= 4
      2738100.83     10073605.32      2737809.68     10073516.26
      2737655.52     10073538.53      2737577.12     10073739.66
#Sta/Elev= 30
  4603.9 1803.11  4657.0 1800.50  4674.3 1797.97  4700.5 1793.61  4721.4 1793.33
  4793.4 1787.00  4831.4 1780.84  4906.4 1776.81  4939.9 1776.17  4950.0 1773.74
  4960.1 1769.54  4980.3 1756.68  4990.4 1749.13  4992.5 1748.76  4995.3 1748.26
  4998.5 1748.76  5000.6 1748.90  5051.0 1777.65  5060.1 1781.52  5067.1 1781.93
  5072.4 1783.88  5091.2 1783.61  5102.3 1785.23  5121.4 1784.84  5135.3 1785.87
  5198.5 1788.81  5230.2 1793.94  5235.5 1796.30  5241.4 1797.25  5280.0 1801.30
#Mann=5,-1,0
  4603.9    0.16       0  4674.3     0.1       0  4992.5    0.07       0
  4998.5     0.1       0  5135.3    0.05       0
Bank Sta=4992.5,4998.5
Exp/Cntr=0.3,0.1

Type RM Length L Ch R = 1,2590,580,580,580
BEGIN DESCRIPTION:
UNT 0092 IN HEWA 5.0
END DESCRIPTION:
XS GIS Cut Line= 4
      2738008.39     10072742.04      2737535.62     10073052.08
      2737484.24     10073211.37      2737556.17     10073713.20
#Sta/Elev= 30
  4377.2 1819.83  4536.9 1806.13  4552.0 1802.86  4573.1 1804.38  4594.2 1803.35
  4624.4 1798.73  4645.4 1799.55  4660.5 1797.71  4717.8 1796.46  4732.9 1793.69
  4754.0 1792.58  4775.0 1793.34  4811.2 1791.17  4919.7 1774.77  4946.1 1769.37
  4954.8 1762.14  4975.8 1754.76  4986.9 1744.62  4993.8 1740.67  4996.6 1740.17
  4999.8 1740.67  5007.3 1741.78  5013.7 1747.40  5028.4 1753.70  5045.7 1757.96
  5083.0 1765.30  5115.9 1767.74  5393.4 1781.56  5516.4 1789.94  5616.9 1799.43
#Mann=5,-1,0
  4377.2     0.1       0  4993.8    0.07       0  4999.8     0.1       0
  5115.9    0.16       0  5393.4    0.05       0
Bank Sta=4993.8,4999.8
Exp/Cntr=0.3,0.1

Type RM Length L Ch R = 1,2010,468,468,468
BEGIN DESCRIPTION:
UNT 0092 IN HEWA 4.0
END DESCRIPTION:
XS GIS Cut Line= 2
      2737312.60     10072360.55      2736706.05     10073389.25
#Sta/Elev= 30
  4474.8 1793.25  4510.0 1792.82  4552.5 1789.69  4590.0 1786.71  4611.5 1787.88
  4627.1 1786.94  4632.9 1788.34  4670.0 1787.36  4691.5 1784.28  4743.1 1773.66
  4780.3 1768.95  4882.8 1759.58  4954.5 1754.66  4968.6 1750.17  4984.2 1739.08
  4996.9 1735.27  4999.6 1734.77  5002.9 1735.27  5021.3 1744.03  5035.7 1747.05
  5064.2 1748.83  5079.9 1751.75  5122.8 1756.27  5165.7 1758.25  5218.5 1763.11
  5298.5 1768.14  5341.4 1769.10  5495.6 1779.92  5538.5 1780.95  5669.0 1788.77
#Mann=5,-1,0
  4474.8    0.05       0  4552.5     0.1       0  4743.1    0.16       0
  4996.9    0.07       0  5002.9    0.16       0
Bank Sta=4996.9,5002.9
Exp/Cntr=0.3,0.1

Type RM Length L Ch R = 1,1542,391,391,391
BEGIN DESCRIPTION:
UNT 0092 IN HEWA 3.0
END DESCRIPTION:
XS GIS Cut Line= 2
      2737035.91     10072253.71      2736288.26     10072938.25
#Sta/Elev= 30
  4672.3 1790.02  4698.8 1788.51  4720.2 1786.46  4741.2 1780.58  4748.6 1780.38
  4818.9 1765.13  4946.5 1751.91  4953.6 1750.31  4967.5 1743.10  4974.9 1737.16
  4992.9 1732.69  4995.6 1732.19  4998.9 1732.69  5045.8 1735.58  5074.2 1735.10
  5088.4 1737.61  5095.2 1740.64  5116.3 1739.46  5151.9 1743.45  5221.9 1757.09
  5229.6 1759.71  5265.4 1759.79  5279.0 1761.57  5286.3 1760.46  5361.2 1764.85
  5419.7 1768.11  5500.6 1770.54  5558.7 1774.20  5639.9 1778.36  5686.0 1780.53
#Mann=10,-1,0
  4672.3    0.05       0  4698.8    0.16       0  4992.9    0.07       0
  4998.9    0.16       0  5221.9    0.05       0  5361.2     0.1       0
  5419.7    0.05       0  5500.6     0.1       0  5558.7    0.05       0
  5639.9     0.1       0
Bank Sta=4992.9,4998.9
Exp/Cntr=0.3,0.1

Type RM Length L Ch R = 1,1151,326,326,326
BEGIN DESCRIPTION:
UNT 0092 IN HEWA 2.0
END DESCRIPTION:
XS GIS Cut Line= 2
      2736574.59     10072184.73      2736288.13     10072717.27
#Sta/Elev= 30
  4730.2 1774.67  4755.6 1769.52  4777.5 1761.96  4799.4 1758.11  4837.5 1758.55
  4843.2 1757.00  4853.8 1756.98  4859.4 1755.46  4875.7 1756.28  4881.4 1754.41
  4897.6 1753.97  4903.3 1750.49  4910.3 1749.02  4933.5 1742.97  4963.3 1733.04
  4978.9 1731.09  4998.5 1730.47  5001.2 1729.97  5004.5 1730.47  5010.9 1730.85
  5051.0 1731.00  5058.4 1732.99  5072.9 1741.09  5081.1 1744.34  5111.0 1749.97
  5116.7 1749.71  5134.0 1751.69  5154.8 1752.56  5193.0 1755.98  5334.9 1763.84
#Mann=6,-1,0
  4730.2     0.1       0  4910.3    0.16       0  4998.5    0.07       0
  5004.5    0.16       0  5010.9     0.1       0  5134.0    0.05       0
Bank Sta=4998.5,5004.5
Exp/Cntr=0.3,0.1

Type RM Length L Ch R = 1,825,126,126,126
BEGIN DESCRIPTION:
Mapping XS 6f1aabbf
END DESCRIPTION:
XS GIS Cut Line= 3
      2736542.08     10071991.98      2736060.27     10072308.41
      2735978.23     10072445.16
#Sta/Elev= 30
  4602.9 1767.67  4620.2 1767.07  4650.4 1762.90  4690.7 1760.89  4737.8 1758.77
  4758.9 1756.73  4779.9 1756.56  4810.1 1752.09  4816.1 1752.15  4831.2 1748.58
  4873.3 1743.75  4908.5 1736.00  4918.3 1735.04  4924.6 1732.39  4939.7 1728.86
  4946.1 1728.94  5058.9 1728.01  5061.6 1727.51  5064.9 1728.01  5067.6 1728.14
  5084.3 1730.60  5105.4 1736.79  5111.4 1740.01  5141.5 1747.08  5147.5 1749.92
  5185.5 1753.56  5197.8 1755.91  5271.7 1761.06  5287.2 1763.73  5338.8 1765.25
#Mann=7,-1,0
  4602.9     0.1       0  4690.7    0.05       0  4908.5    0.16       0
  4946.1     0.1       0  5058.9    0.07       0  5064.9     0.1       0
  5067.6    0.05       0
Bank Sta=5058.9,5064.9
Exp/Cntr=0.3,0.1

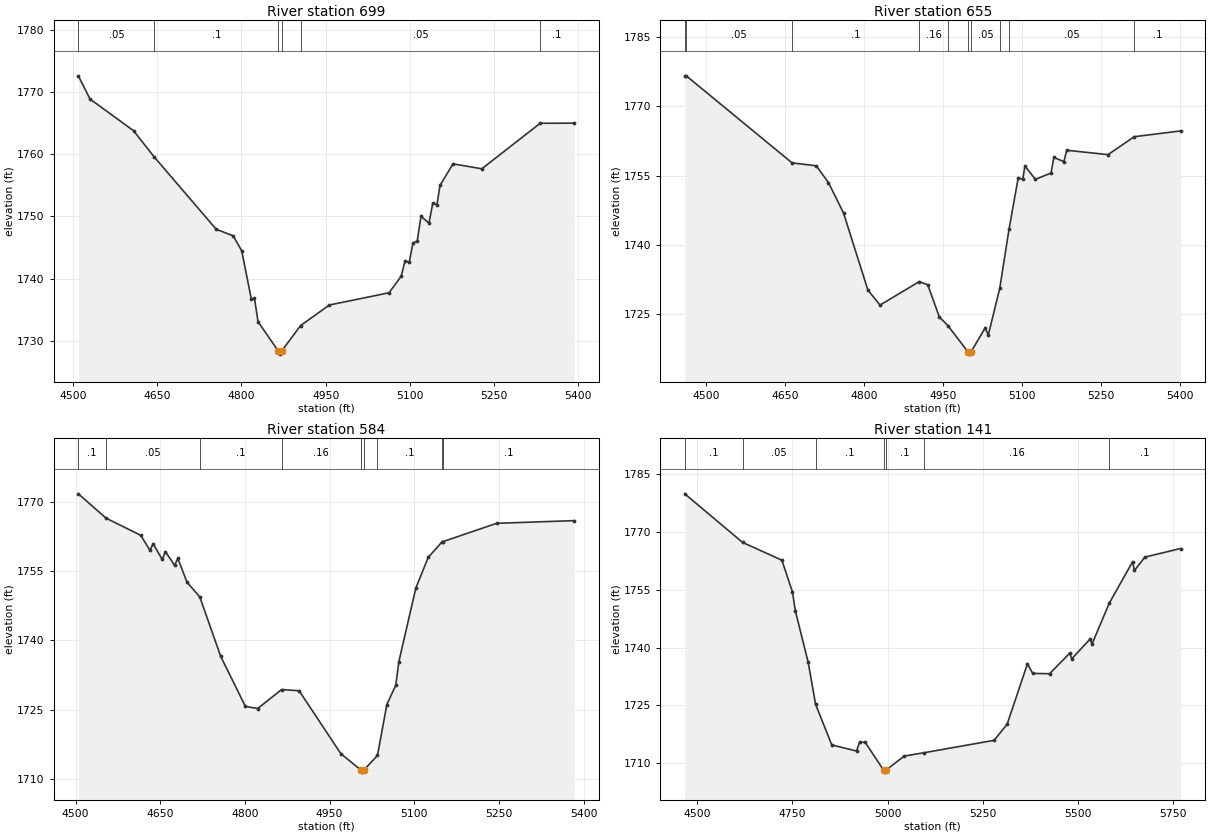
Type RM Length L Ch R = 1,699,44,44,44
BEGIN DESCRIPTION:
Mapping XS 7653bcf9
END DESCRIPTION:
XS GIS Cut Line= 4
      2736547.21     10071883.95      2736170.95     10072063.62
      2736018.61     10072236.80      2735941.89     10072459.13
#Sta/Elev= 30
  4509.7 1772.68  4530.5 1768.94  4608.0 1763.83  4645.1 1759.57  4755.3 1747.93
  4785.3 1746.89  4800.6 1744.47  4817.8 1736.65  4823.3 1736.80  4829.7 1733.04
  4865.7 1728.31  4868.4 1727.81  4871.7 1728.31  4905.5 1732.42  4956.6 1735.73
  5062.9 1737.70  5084.7 1740.39  5091.3 1742.84  5098.9 1742.64  5105.6 1745.74
  5113.1 1746.05  5119.8 1750.03  5134.0 1748.93  5140.7 1752.13  5148.3 1751.92
  5153.6 1755.00  5176.8 1758.49  5228.1 1757.69  5332.0 1765.03  5392.5 1765.05
#Mann=6,-1,0
  4509.7    0.05       0  4645.1     0.1       0  4865.7    0.04       0
  4871.7     0.1       0  4905.5    0.05       0  5332.0     0.1       0
Bank Sta=4865.7,4871.7
Exp/Cntr=0.3,0.1

Type RM Length L Ch R = 1,655,71,71,71
BEGIN DESCRIPTION:
Mapping XS 7378c01a
END DESCRIPTION:
XS GIS Cut Line= 4
      2736569.42     10071844.86      2736120.17     10072047.99
      2736031.63     10072175.60      2735923.88     10072449.51
#Sta/Elev= 30
  4459.2 1776.62  4462.0 1776.62  4663.1 1757.77  4709.2 1757.13  4732.4 1753.48
  4761.0 1746.91  4807.2 1730.25  4830.3 1726.96  4905.0 1732.05  4921.2 1731.36
  4943.1 1724.39  4959.5 1722.51  4997.5 1716.84  5000.2 1716.34  5003.5 1716.84
  5030.2 1722.01  5036.3 1720.50  5058.0 1730.58  5075.7 1743.43  5093.1 1754.52
  5101.8 1754.21  5105.9 1757.09  5125.8 1754.19  5155.5 1755.57  5160.9 1758.93
  5179.9 1758.05  5185.3 1760.50  5263.9 1759.55  5313.7 1763.43  5401.9 1764.69
#Mann=10,-1,0
  4459.2     0.1       0  4462.0    0.05       0  4663.1     0.1       0
  4905.0    0.16       0  4959.5    0.05       0  4997.5    0.04       0
  5003.5    0.05       0  5058.0     0.1       0  5075.7    0.05       0
  5313.7     0.1       0
Bank Sta=4997.5,5003.5
Exp/Cntr=0.3,0.1

Type RM Length L Ch R = 1,584,443,443,443
BEGIN DESCRIPTION:
Mapping XS b924db44
END DESCRIPTION:
XS GIS Cut Line= 3
      2736482.12     10071796.71      2736000.38     10072058.41
      2735865.36     10072359.60
#Sta/Elev= 30
  4504.9 1771.83  4554.0 1766.55  4615.5 1762.82  4631.7 1759.57  4637.4 1760.99
  4653.5 1757.58  4659.2 1759.28  4675.4 1756.29  4681.1 1757.82  4697.3 1752.67
  4720.1 1749.43  4757.1 1736.54  4800.8 1725.68  4822.7 1725.22  4864.9 1729.34
  4896.0 1729.08  4970.0 1715.40  5005.0 1711.91  5007.8 1711.41  5011.0 1711.91
  5034.8 1715.02  5051.4 1726.09  5067.2 1730.27  5072.7 1735.41  5102.8 1751.39
  5124.7 1758.04  5148.7 1761.33  5150.2 1761.43  5246.0 1765.43  5383.2 1766.01
#Mann=9,-1,0
  4504.9     0.1       0  4554.0    0.05       0  4720.1     0.1       0
  4864.9    0.16       0  5005.0    0.07       0  5011.0    0.16       0
  5034.8     0.1       0  5148.7    0.05       0  5150.2     0.1       0
Bank Sta=5005,5011
Exp/Cntr=0.3,0.1

Type RM Length L Ch R = 1,141,0,0,0
BEGIN DESCRIPTION:
UNT 0092 IN HEWA 1.0
END DESCRIPTION:
XS GIS Cut Line= 4
      2736542.31     10071682.94      2736104.76     10071568.35
      2735951.11     10071669.91      2735831.32     10072326.18
#Sta/Elev= 30
  4467.0 1779.88  4618.9 1767.28  4722.3 1762.66  4750.1 1754.41  4757.6 1749.56
  4791.4 1736.16  4810.9 1725.29  4853.4 1714.76  4918.5 1713.17  4926.8 1715.53
  4941.5 1715.41  4989.7 1708.20  4992.4 1707.70  4995.7 1708.20  5043.8 1711.86
  5095.3 1712.72  5280.2 1715.95  5314.4 1720.10  5367.7 1735.75  5381.8 1733.31
  5426.0 1733.22  5479.3 1738.56  5484.4 1737.10  5532.6 1742.23  5537.6 1740.91
  5582.8 1751.48  5644.2 1762.25  5649.2 1760.01  5676.6 1763.47  5770.6 1765.70
#Mann=7,-1,0
  4467.0     0.1       0  4618.9    0.05       0  4810.9     0.1       0
  4989.7    0.07       0  4995.7     0.1       0  5095.3    0.16       0
  5582.8     0.1       0
Bank Sta=4989.7,4995.7
Exp/Cntr=0.3,0.1

Chan Stop Cuts=-1