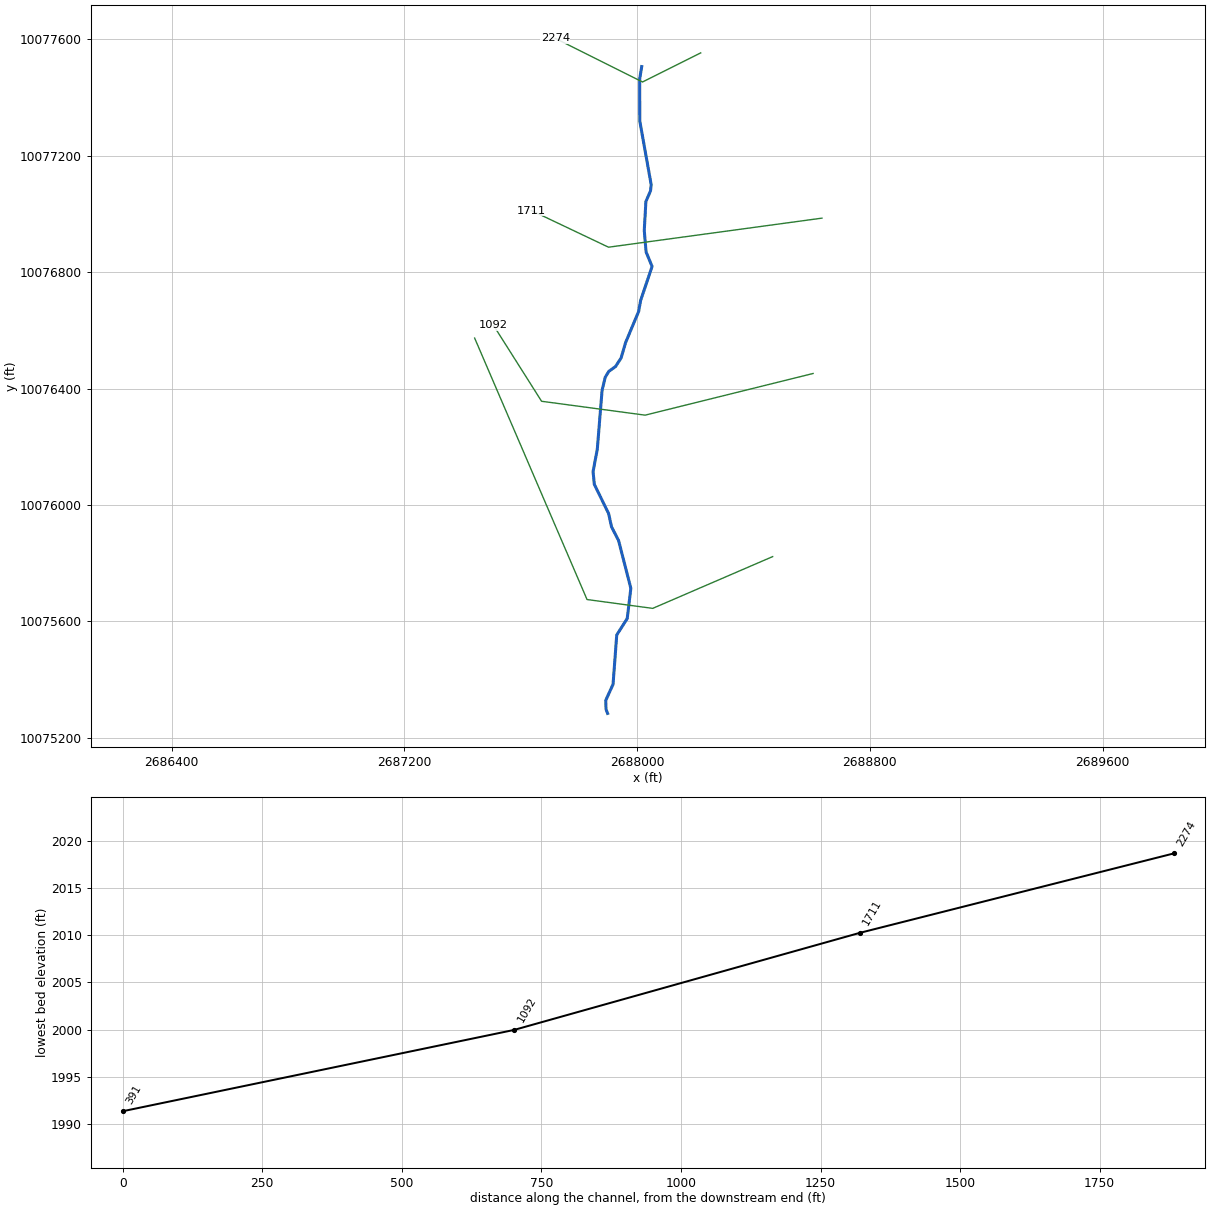
--- UNT 00931 IN HEWA.prj (project) ---

Proj Title=UNT 00931 IN HEWA Base Level Engineering
Current Plan=p01
Default Exp/Contr=0.3,0.1
English Units
Geom File=g01
Flow File=f01
Plan File=p01
BEGIN DESCRIPTION:
UNT 00931 IN HEWA
END DESCRIPTION:

--- UNT 00931 IN HEWA.p01 (plan) ---

Plan Title=Multiple Run
Short Identifier=Multiple
Geom File=g01
Flow File=f01
Subcritical Flow
K Sum by GR= 0
Std Step Tol= 0.01
Critical Tol= 0.01
Num of Std Step Trials= 20
Max Error Tol= 0.3
Flow Tol Ratio= 0.001
Split Flow NTrial= 30
Split Flow Tol= 0.02
Split Flow Ratio= 0.02
Log Output Level= 0
Friction Slope Method= 1
Unsteady Friction Slope Method= 2
Unsteady Bridges Friction Slope Method= 1
Parabolic Critical Depth
Global Vel Dist=  1 , 1 , 1
Global Log Level= 0
CheckData=True
Encroach Param= -1, 0, 0, 0
BEGIN DESCRIPTION:
Multiple Run
END DESCRIPTION:

--- UNT 00931 IN HEWA.f01 (steady flow) ---

Flow Title=Multiple
Number of Profiles=7
Profile Names=10-year,25-year,50-year,1pct_min,100-year,1pct_plu,500-year
River Rch & RM= UNT 00931 IN HEW,Reach-1,2274
     564     788     974     881    1192    1612    1779
Boundary for River Rch & Prof#=UNT 00931 IN HEW,Reach-1,1
Up Type=0
Dn Type=3
Dn Slope=0.005
Boundary for River Rch & Prof#=UNT 00931 IN HEW,Reach-1,2
Up Type=0
Dn Type=3
Dn Slope=0.005
Boundary for River Rch & Prof#=UNT 00931 IN HEW,Reach-1,3
Up Type=0
Dn Type=3
Dn Slope=0.005
Boundary for River Rch & Prof#=UNT 00931 IN HEW,Reach-1,4
Up Type=0
Dn Type=3
Dn Slope=0.005
Boundary for River Rch & Prof#=UNT 00931 IN HEW,Reach-1,5
Up Type=0
Dn Type=3
Dn Slope=0.005
Boundary for River Rch & Prof#=UNT 00931 IN HEW,Reach-1,6
Up Type=0
Dn Type=3
Dn Slope=0.005
Boundary for River Rch & Prof#=UNT 00931 IN HEW,Reach-1,7
Up Type=0
Dn Type=3
Dn Slope=0.005

--- UNT 00931 IN HEWA.g01 (geometry) ---

Geom Title=Existing Conditions

River Reach=UNT 00931 IN HEW,Reach-1
Reach XY= 30
      2688015.71     10077506.61      2688008.61     10077463.75
      2688009.18     10077319.03      2688048.21     10077100.91
      2688045.98     10077079.43      2688030.10     10077043.08
      2688024.46     10076943.70      2688030.78     10076869.24
      2688051.37     10076819.91      2688011.87     10076702.33
      2688005.12     10076665.12      2687960.29     10076557.95
      2687944.79     10076505.10      2687925.61     10076475.71
      2687902.50     10076459.10      2687890.23     10076438.67
      2687879.46     10076393.72      2687863.05     10076191.38
      2687848.55     10076115.01      2687852.82     10076070.94
      2687901.96     10075970.46      2687911.90     10075925.16
      2687936.19     10075877.79      2687978.34     10075713.57
      2687965.96     10075609.78      2687929.86     10075553.15
      2687917.21     10075383.64      2687892.15     10075328.57
      2687893.06     10075297.62      2687898.47     10075283.73

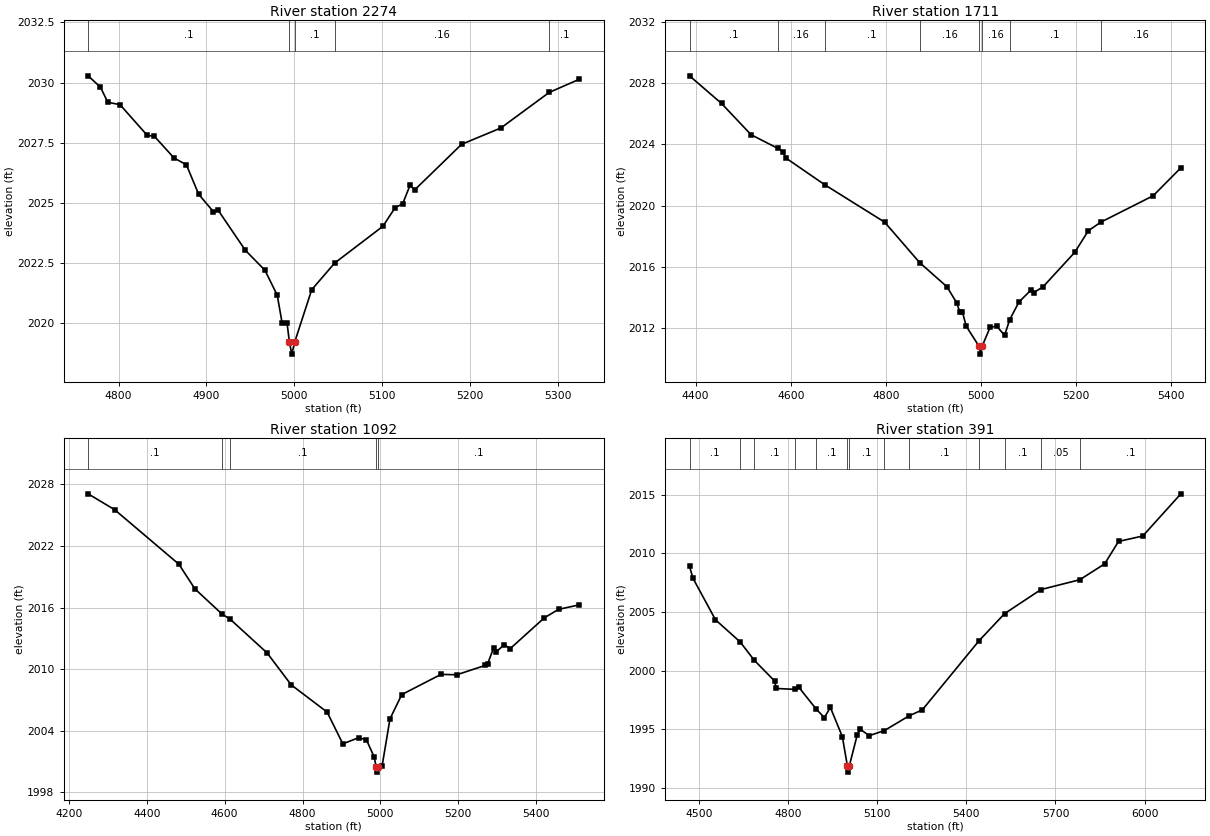
Type RM Length L Ch R = 1,2274,563,563,563
BEGIN DESCRIPTION:
UNT 00931 IN HEWA 4.0
END DESCRIPTION:
XS GIS Cut Line= 3
      2688218.46     10077553.73      2688018.47     10077453.73
      2687718.48     10077603.73
#Sta/Elev= 30
  4765.4 2030.28  4779.4 2029.81  4787.8 2029.18  4801.7 2029.08  4832.5 2027.81
  4840.9 2027.76  4863.2 2026.86  4877.2 2026.58  4891.2 2025.35  4907.9 2024.63
  4913.5 2024.68  4944.3 2023.02  4966.6 2022.19  4980.6 2021.15  4986.2 2019.98
  4991.8 2019.98  4994.4 2019.20  4997.1 2018.70  5000.4 2019.20  5019.8 2021.38
  5045.9 2022.49  5100.8 2024.02  5114.8 2024.80  5123.2 2024.95  5131.6 2025.72
  5137.1 2025.54  5190.3 2027.43  5235.0 2028.11  5290.0 2029.59  5324.4 2030.14
#Mann=5,-1,0
  4765.4     0.1       0  4994.4    0.07       0  5000.4     0.1       0
  5045.9    0.16       0  5290.0     0.1       0
Bank Sta=4994.4,5000.4
Exp/Cntr=0.3,0.1

Type RM Length L Ch R = 1,1711,619,619,619
BEGIN DESCRIPTION:
UNT 00931 IN HEWA 3.0
END DESCRIPTION:
XS GIS Cut Line= 3
      2688635.11     10076985.74      2687901.61     10076885.91
      2687636.87     10077011.78
#Sta/Elev= 30
  4387.2 2028.50  4454.5 2026.69  4516.7 2024.64  4573.3 2023.74  4584.0 2023.54
  4589.1 2023.13  4671.2 2021.37  4797.6 2018.91  4871.2 2016.26  4928.8 2014.67
  4949.0 2013.63  4956.1 2012.99  4961.2 2013.02  4969.2 2012.09  4996.4 2010.76
  4999.2 2010.26  5002.4 2010.76  5019.6 2012.03  5033.6 2012.08  5049.9 2011.49
  5060.5 2012.51  5080.2 2013.68  5106.0 2014.48  5111.0 2014.29  5130.7 2014.67
  5197.4 2016.93  5226.1 2018.35  5252.3 2018.91  5362.4 2020.64  5420.6 2022.47
#Mann=8,-1,0
  4387.2     0.1       0  4573.3    0.16       0  4671.2     0.1       0
  4871.2    0.16       0  4996.4    0.07       0  5002.4    0.16       0
  5060.5     0.1       0  5252.3    0.16       0
Bank Sta=4996.4,5002.4
Exp/Cntr=0.3,0.1

Type RM Length L Ch R = 1,1092,701,701,701
BEGIN DESCRIPTION:
UNT 00931 IN HEWA 2.0
END DESCRIPTION:
XS GIS Cut Line= 4
      2688604.75     10076451.89      2688027.48     10076308.66
      2687671.58     10076356.40      2687506.65     10076616.80
#Sta/Elev= 30
  4249.2 2027.09  4317.5 2025.54  4482.3 2020.23  4523.6 2017.82  4593.2 2015.37
  4614.0 2014.87  4709.0 2011.58  4770.8 2008.47  4863.2 2005.81  4903.5 2002.72
  4943.9 2003.31  4964.1 2003.11  4984.2 2001.42  4989.1 2000.46  4991.9 1999.96
  4995.1 2000.46  5004.4 2000.56  5024.6 2005.15  5054.9 2007.52  5155.8 2009.49
  5196.1 2009.45  5269.7 2010.37  5275.6 2010.53  5290.8 2012.07  5296.8 2011.66
  5318.3 2012.39  5333.2 2011.99  5421.3 2015.01  5457.8 2015.83  5511.3 2016.27
#Mann=5,-1,0
  4249.2     0.1       0  4593.2    0.16       0  4614.0     0.1       0
  4989.1    0.07       0  4995.1     0.1       0
Bank Sta=4989.1,4995.1
Exp/Cntr=0.3,0.1

Type RM Length L Ch R = 1,391,0,0,0
BEGIN DESCRIPTION:
UNT 00931 IN HEWA 1.0
END DESCRIPTION:
XS GIS Cut Line= 4
      2688465.83     10075822.54      2688053.52     10075644.59
      2687827.83     10075674.98      2687441.53     10076573.45
#Sta/Elev= 30
  4467.4 2008.89  4478.9 2007.88  4554.9 2004.33  4638.0 2002.44  4685.3 2000.88
  4753.9 1999.11  4759.3 1998.47  4824.0 1998.39  4835.3 1998.58  4894.7 1996.69
  4921.6 1995.98  4941.8 1996.85  4982.1 1994.36  4999.3 1991.83  5002.0 1991.33
  5005.3 1991.83  5032.6 1994.54  5042.7 1994.98  5072.9 1994.44  5123.9 1994.88
  5208.1 1996.15  5251.4 1996.64  5442.8 2002.55  5528.7 2004.86  5651.0 2006.91
  5781.9 2007.75  5865.4 2009.10  5912.5 2011.02  5994.0 2011.48  6122.2 2015.08
#Mann=13,-1,0
  4467.4     0.1       0  4638.0    0.16       0  4685.3     0.1       0
  4824.0    0.05       0  4894.7     0.1       0  4999.3    0.07       0
  5005.3     0.1       0  5123.9    0.05       0  5208.1     0.1       0
  5442.8    0.05       0  5528.7     0.1       0  5651.0    0.05       0
  5781.9     0.1       0
Bank Sta=4999.3,5005.3
Exp/Cntr=0.3,0.1

Chan Stop Cuts=-1