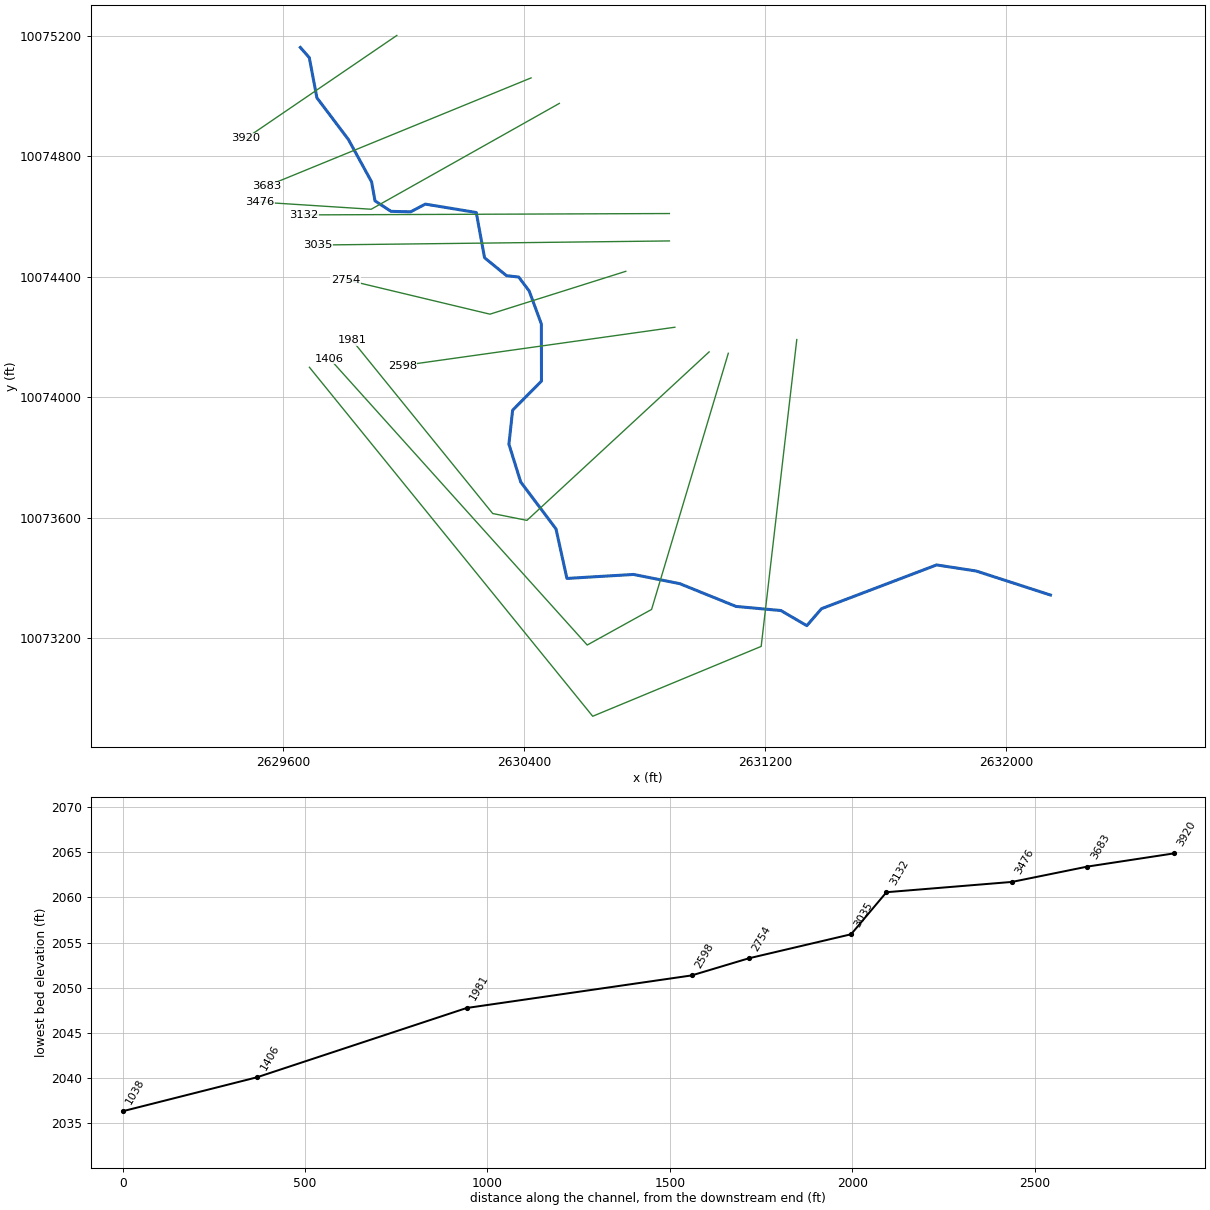
--- UNT 0094 IN HEWA.prj (project) ---

Proj Title=UNT 0094 IN HEWA Base Level Engineering
Current Plan=p01
Default Exp/Contr=0.3,0.1
English Units
Geom File=g01
Flow File=f01
Plan File=p01
BEGIN DESCRIPTION:
UNT 0094 IN HEWA
END DESCRIPTION:

--- UNT 0094 IN HEWA.p01 (plan) ---

Plan Title=Multiple Run
Short Identifier=Multiple
Geom File=g01
Flow File=f01
Subcritical Flow
K Sum by GR= 0
Std Step Tol= 0.01
Critical Tol= 0.01
Num of Std Step Trials= 20
Max Error Tol= 0.3
Flow Tol Ratio= 0.001
Split Flow NTrial= 30
Split Flow Tol= 0.02
Split Flow Ratio= 0.02
Log Output Level= 0
Friction Slope Method= 1
Unsteady Friction Slope Method= 2
Unsteady Bridges Friction Slope Method= 1
Parabolic Critical Depth
Global Vel Dist=  1 , 1 , 1
Global Log Level= 0
CheckData=True
Encroach Param= -1, 0, 0, 0
BEGIN DESCRIPTION:
Multiple Run
END DESCRIPTION:

--- UNT 0094 IN HEWA.f01 (steady flow) ---

Flow Title=Multiple
Number of Profiles=7
Profile Names=10-year,25-year,50-year,1pct_min,100-year,1pct_plu,500-year
River Rch & RM= UNT 0094 IN HEWA,Reach-1,3920
     926    1334    1683    1548    2093    2831    3240
Boundary for River Rch & Prof#=UNT 0094 IN HEWA,Reach-1,1
Up Type=0
Dn Type=3
Dn Slope=0.005
Boundary for River Rch & Prof#=UNT 0094 IN HEWA,Reach-1,2
Up Type=0
Dn Type=3
Dn Slope=0.005
Boundary for River Rch & Prof#=UNT 0094 IN HEWA,Reach-1,3
Up Type=0
Dn Type=3
Dn Slope=0.005
Boundary for River Rch & Prof#=UNT 0094 IN HEWA,Reach-1,4
Up Type=0
Dn Type=3
Dn Slope=0.005
Boundary for River Rch & Prof#=UNT 0094 IN HEWA,Reach-1,5
Up Type=0
Dn Type=3
Dn Slope=0.005
Boundary for River Rch & Prof#=UNT 0094 IN HEWA,Reach-1,6
Up Type=0
Dn Type=3
Dn Slope=0.005
Boundary for River Rch & Prof#=UNT 0094 IN HEWA,Reach-1,7
Up Type=0
Dn Type=3
Dn Slope=0.005

--- UNT 0094 IN HEWA.g01 (geometry) ---

Geom Title=Existing Conditions

River Reach=UNT 0094 IN HEWA,Reach-1
Reach XY= 30
      2629656.67     10075162.21      2629686.37     10075128.38
      2629711.65     10074995.05      2629816.31     10074856.44
      2629893.33     10074715.76      2629904.62     10074652.56
      2629957.91     10074617.69      2630023.26     10074616.16
      2630071.65     10074641.73      2630241.03     10074613.88
      2630268.58     10074463.61      2630341.50     10074404.05
      2630382.02     10074399.50      2630416.81     10074353.28
      2630457.38     10074243.28      2630457.65     10074053.95
      2630361.84     10073957.11      2630349.53     10073844.31
      2630388.63     10073718.80      2630505.95     10073562.67
      2630542.20     10073398.29      2630763.33     10073411.52
      2630917.27     10073380.85      2631104.09     10073305.24
      2631252.95     10073291.63      2631339.13     10073241.34
      2631387.93     10073297.77      2631770.19     10073443.11
      2631901.73     10073422.97      2632148.51     10073343.09

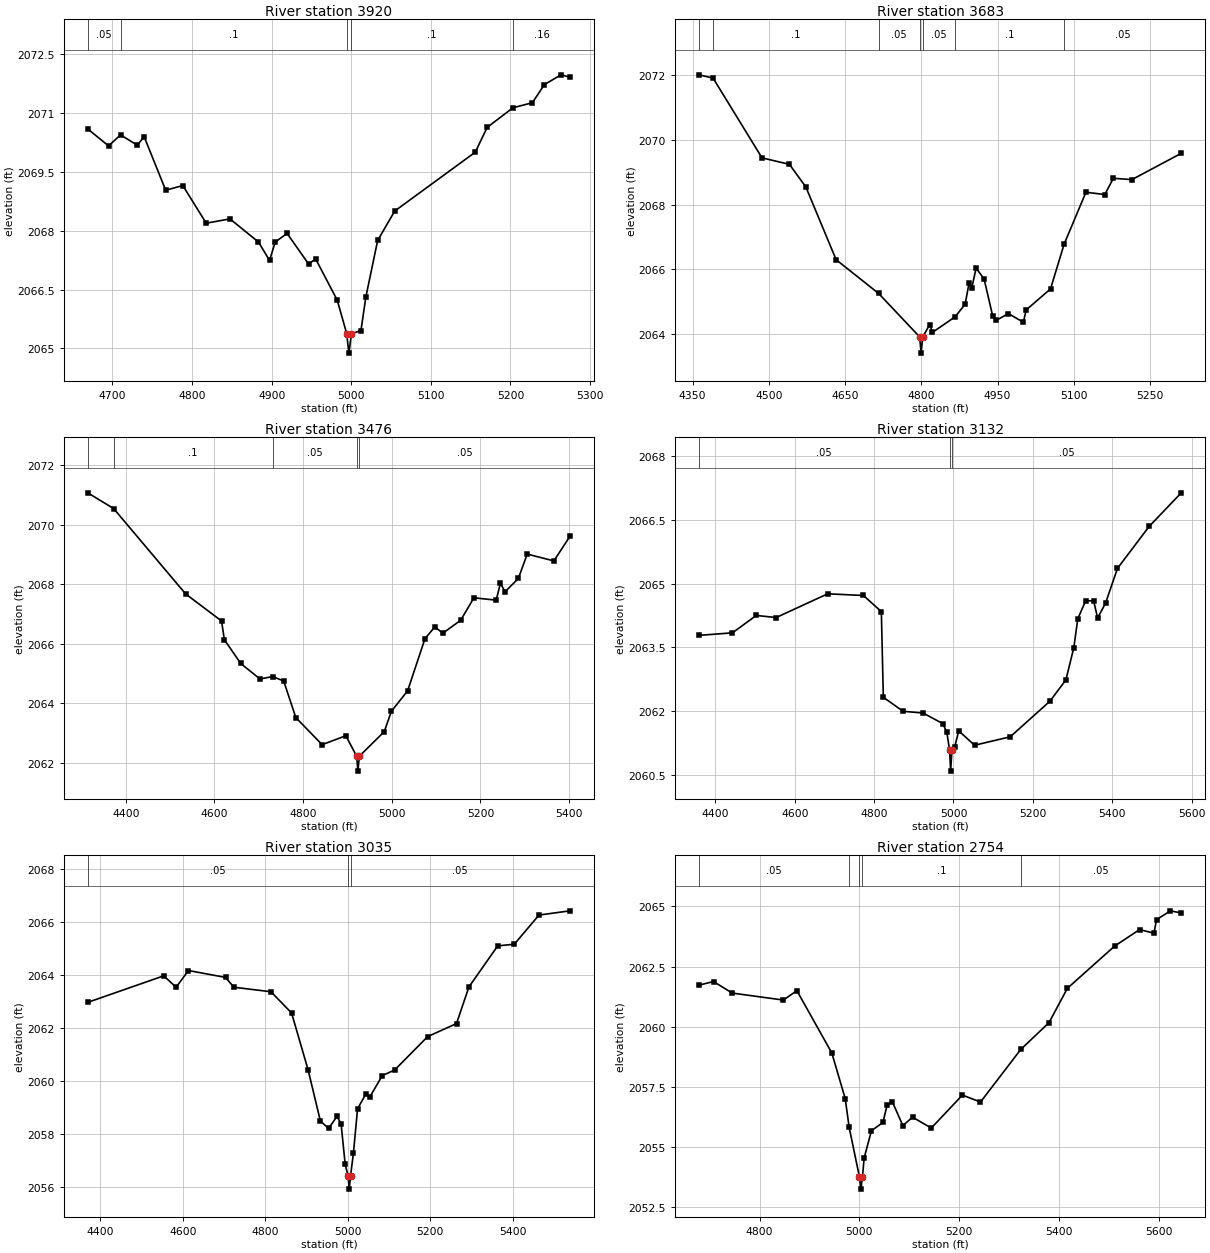
Type RM Length L Ch R = 1,3920,237,237,237
BEGIN DESCRIPTION:
UNT 0094 IN HEWA 7.0
END DESCRIPTION:
XS GIS Cut Line= 2
      2629977.14     10075202.03      2629476.53     10074860.70
#Sta/Elev= 30
  4669.0 2070.59  4695.1 2070.16  4710.2 2070.44  4731.0 2070.18  4739.9 2070.39
  4766.9 2069.03  4788.4 2069.15  4817.8 2068.19  4847.6 2068.30  4883.5 2067.71
  4897.4 2067.24  4904.5 2067.71  4919.4 2067.93  4946.5 2067.15  4955.3 2067.28
  4982.4 2066.23  4994.3 2065.38  4997.1 2064.88  5000.3 2065.38  5012.2 2065.45
  5018.4 2066.31  5033.2 2067.75  5054.7 2068.50  5155.9 2070.00  5170.8 2070.63
  5203.1 2071.13  5227.7 2071.26  5242.6 2071.72  5263.6 2071.97  5274.9 2071.91
#Mann=5,-1,0
  4669.0    0.05       0  4710.2     0.1       0  4994.3    0.07       0
  5000.3     0.1       0  5203.1    0.16       0
Bank Sta=4994.3,5000.3
Exp/Cntr=0.3,0.1

Type RM Length L Ch R = 1,3683,207,207,207
BEGIN DESCRIPTION:
UNT 0094 IN HEWA 6.0
END DESCRIPTION:
XS GIS Cut Line= 2
      2630423.10     10075060.97      2629544.83     10074701.47
#Sta/Elev= 30
  4362.5 2072.00  4390.1 2071.90  4486.4 2069.44  4540.4 2069.24  4572.8 2068.54
  4632.3 2066.30  4715.9 2065.26  4796.7 2063.92  4799.5 2063.42  4802.7 2063.92
  4816.5 2064.30  4821.9 2064.06  4866.5 2064.54  4886.2 2064.93  4894.0 2065.59
  4899.4 2065.44  4907.8 2066.04  4923.4 2065.71  4940.2 2064.58  4947.4 2064.43
  4971.4 2064.64  5000.8 2064.37  5006.2 2064.75  5054.2 2065.40  5081.0 2066.78
  5123.9 2068.38  5161.0 2068.31  5177.9 2068.81  5214.4 2068.77  5311.5 2069.58
#Mann=7,-1,0
  4362.5    0.16       0  4390.1     0.1       0  4715.9    0.05       0
  4796.7    0.07       0  4802.7    0.05       0  4866.5     0.1       0
  5081.0    0.05       0
Bank Sta=4796.7,4802.7
Exp/Cntr=0.3,0.1

Type RM Length L Ch R = 1,3476,344,344,344
BEGIN DESCRIPTION:
Mapping XS 06e643f4
END DESCRIPTION:
XS GIS Cut Line= 3
      2630517.01     10074976.27      2629892.00     10074624.70
      2629522.17     10074648.49
#Sta/Elev= 30
  4314.4 2071.08  4372.8 2070.55  4535.1 2067.68  4616.1 2066.77  4622.5 2066.14
  4659.4 2065.34  4702.8 2064.82  4731.5 2064.90  4756.3 2064.75  4783.7 2063.52
  4843.0 2062.61  4896.5 2062.91  4920.9 2062.22  4923.7 2061.72  4926.9 2062.22
  4983.2 2063.05  4999.1 2063.73  5035.8 2064.42  5075.1 2066.18  5097.2 2066.57
  5115.2 2066.36  5155.3 2066.79  5185.4 2067.55  5235.5 2067.47  5245.3 2068.04
  5255.5 2067.75  5285.6 2068.20  5305.6 2069.02  5365.7 2068.79  5402.1 2069.62
#Mann=5,-1,0
  4314.4    0.16       0  4372.8     0.1       0  4731.5    0.05       0
  4920.9    0.04       0  4926.9    0.05       0
Bank Sta=4920.9,4926.9
Exp/Cntr=0.3,0.1

Type RM Length L Ch R = 1,3132,97,97,97
BEGIN DESCRIPTION:
Mapping XS ca0d9f70
END DESCRIPTION:
XS GIS Cut Line= 2
      2630882.62     10074610.45      2629667.73     10074605.90
#Sta/Elev= 30
  4359.0 2063.78  4443.2 2063.84  4503.2 2064.25  4553.2 2064.20  4683.2 2064.76
  4773.2 2064.72  4818.3 2064.34  4823.3 2062.32  4873.2 2061.99  4923.2 2061.95
  4973.2 2061.70  4983.2 2061.50  4990.2 2061.08  4992.9 2060.58  4996.2 2061.08
  5003.2 2061.15  5013.2 2061.53  5053.2 2061.19  5143.2 2061.39  5243.2 2062.23
  5283.2 2062.73  5303.2 2063.49  5313.2 2064.17  5333.2 2064.60  5353.2 2064.59
  5363.2 2064.19  5383.2 2064.54  5413.2 2065.36  5493.2 2066.35  5573.9 2067.14
#Mann=3,-1,0
  4359.0    0.05       0  4990.2    0.04       0  4996.2    0.05       0
Bank Sta=4990.2,4996.2
Exp/Cntr=0.3,0.1

Type RM Length L Ch R = 1,3035,281,281,281
BEGIN DESCRIPTION:
Mapping XS ec836fd5
END DESCRIPTION:
XS GIS Cut Line= 2
      2630882.64     10074519.44      2629713.32     10074505.79
#Sta/Elev= 30
  4369.6 2062.96  4553.8 2063.96  4583.8 2063.53  4613.8 2064.16  4703.8 2063.90
  4723.8 2063.53  4813.8 2063.36  4863.8 2062.56  4903.8 2060.42  4933.8 2058.48
  4953.8 2058.21  4973.8 2058.66  4983.8 2058.39  4993.8 2056.86  5000.8 2056.42
  5003.6 2055.92  5006.8 2056.42  5013.8 2057.27  5023.8 2058.95  5043.8 2059.50
  5053.8 2059.40  5083.8 2060.20  5113.8 2060.41  5193.8 2061.67  5263.8 2062.16
  5293.8 2063.54  5363.8 2065.09  5403.8 2065.15  5463.8 2066.25  5539.0 2066.41
#Mann=3,-1,0
  4369.6    0.05       0  5000.8    0.04       0  5006.8    0.05       0
Bank Sta=5000.8,5006.8
Exp/Cntr=0.3,0.1

Type RM Length L Ch R = 1,2754,156,156,156
BEGIN DESCRIPTION:
UNT 0094 IN HEWA 5.0
END DESCRIPTION:
XS GIS Cut Line= 3
      2630737.84     10074418.51      2630286.47     10074276.16
      2629807.27     10074390.75
#Sta/Elev= 30
  4678.8 2061.73  4707.8 2061.88  4745.4 2061.40  4847.7 2061.11  4874.8 2061.50
  4944.8 2058.91  4971.7 2057.01  4979.5 2055.82  5000.2 2053.75  5002.9 2053.25
  5006.2 2053.75  5009.5 2054.54  5024.2 2055.68  5047.1 2056.02  5055.6 2056.74
  5066.1 2056.88  5087.1 2055.89  5106.5 2056.24  5144.1 2055.79  5206.4 2057.16
  5242.6 2056.87  5323.4 2059.06  5379.8 2060.17  5416.7 2061.60  5511.1 2063.35
  5561.3 2064.04  5590.1 2063.89  5595.2 2064.45  5623.0 2064.82  5644.8 2064.73
#Mann=5,-1,0
  4678.8    0.05       0  4979.5     0.1       0  5000.2    0.07       0
  5006.2     0.1       0  5323.4    0.05       0
Bank Sta=5000.2,5006.2
Exp/Cntr=0.3,0.1

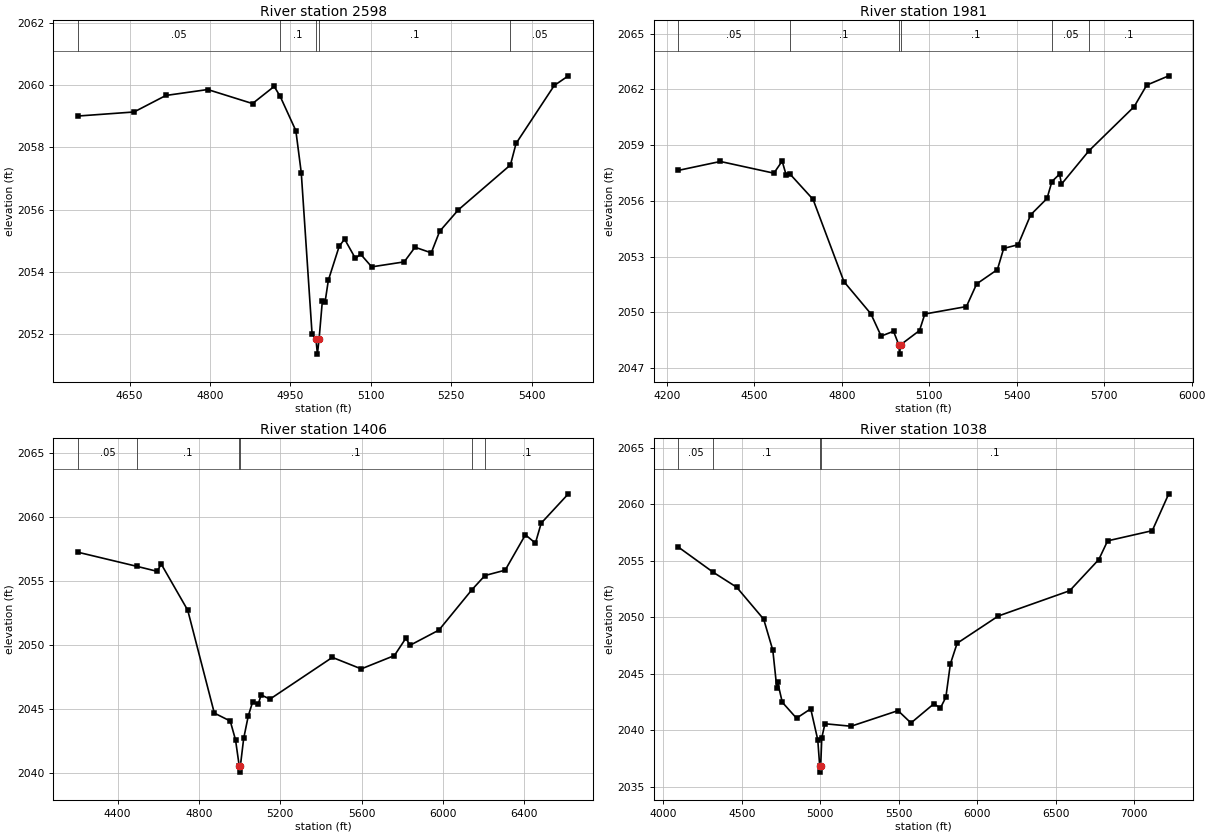
Type RM Length L Ch R = 1,2598,617,617,617
BEGIN DESCRIPTION:
UNT 0094 IN HEWA 4.0
END DESCRIPTION:
XS GIS Cut Line= 2
      2630900.83     10074232.76      2629995.35     10074105.36
#Sta/Elev= 30
  4553.8 2059.00  4658.4 2059.13  4717.8 2059.66  4795.8 2059.85  4879.3 2059.40
  4919.7 2059.95  4930.9 2059.63  4960.1 2058.53  4970.2 2057.18  4990.4 2051.99
  4997.5 2051.86  5000.3 2051.36  5003.5 2051.86  5009.5 2053.06  5014.5 2053.02
  5020.7 2053.73  5040.9 2054.82  5051.0 2055.05  5071.2 2054.43  5080.7 2054.57
  5101.5 2054.16  5162.1 2054.32  5182.3 2054.79  5212.6 2054.61  5228.2 2055.30
  5263.1 2055.99  5360.2 2057.43  5370.7 2058.12  5441.9 2059.98  5468.2 2060.29
#Mann=5,-1,0
  4553.8    0.05       0  4930.9     0.1       0  4997.5    0.07       0
  5003.5     0.1       0  5360.2    0.05       0
Bank Sta=4997.5,5003.5
Exp/Cntr=0.3,0.1

Type RM Length L Ch R = 1,1981,575,575,575
BEGIN DESCRIPTION:
UNT 0094 IN HEWA 3.0
END DESCRIPTION:
XS GIS Cut Line= 4
      2631014.62     10074150.86      2630409.41     10073591.15
      2630295.65     10073613.90      2629828.17     10074190.30
#Sta/Elev= 30
  4238.9 2057.64  4383.0 2058.12  4566.7 2057.49  4595.1 2058.14  4609.2 2057.37
  4620.4 2057.47  4701.1 2056.08  4807.1 2051.65  4899.5 2049.92  4934.7 2048.72
  4977.2 2048.98  4995.2 2048.25  4998.0 2047.75  5001.2 2048.25  5066.3 2049.02
  5084.6 2049.91  5227.2 2050.31  5262.4 2051.53  5333.5 2052.30  5355.1 2053.44
  5404.7 2053.64  5447.8 2055.25  5503.8 2056.13  5520.5 2057.04  5546.9 2057.44
  5553.4 2056.90  5647.3 2058.69  5802.7 2061.07  5845.8 2062.23  5921.4 2062.73
#Mann=6,-1,0
  4238.9    0.05       0  4620.4     0.1       0  4995.2    0.07       0
  5001.2     0.1       0  5520.5    0.05       0  5647.3     0.1       0
Bank Sta=4995.2,5001.2
Exp/Cntr=0.3,0.1

Type RM Length L Ch R = 1,1406,368,368,368
BEGIN DESCRIPTION:
UNT 0094 IN HEWA 2.0
END DESCRIPTION:
XS GIS Cut Line= 4
      2631078.31     10074146.27      2630823.50     10073295.37
      2630609.63     10073177.06      2629754.17     10074128.08
#Sta/Elev= 30
  4205.1 2057.24  4494.4 2056.14  4594.0 2055.75  4614.9 2056.31  4745.1 2052.71
  4875.8 2044.68  4954.1 2044.06  4980.2 2042.58  4998.1 2040.57  5000.8 2040.07
  5004.1 2040.57  5020.2 2042.70  5042.8 2044.46  5063.8 2045.53  5091.6 2045.37
  5105.9 2046.10  5149.4 2045.77  5456.3 2049.03  5598.3 2048.13  5761.3 2049.17
  5817.5 2050.52  5839.0 2049.98  5980.3 2051.16  6142.5 2054.31  6206.7 2055.42
  6306.2 2055.84  6405.6 2058.60  6454.9 2057.95  6483.3 2059.51  6616.9 2061.80
#Mann=6,-1,0
  4205.1    0.05       0  4494.4     0.1       0  4998.1    0.07       0
  5004.1     0.1       0  6142.5    0.05       0  6206.7     0.1       0
Bank Sta=4998.1,5004.1
Exp/Cntr=0.3,0.1

Type RM Length L Ch R = 1,1038,0,0,0
BEGIN DESCRIPTION:
UNT 0094 IN HEWA 1.0
END DESCRIPTION:
XS GIS Cut Line= 4
      2631305.85     10074191.84      2631187.53     10073172.51
      2630627.83     10072940.44      2629686.73     10074099.76
#Sta/Elev= 30
  4095.2 2056.22  4317.6 2053.99  4466.8 2052.67  4639.1 2049.84  4697.3 2047.09
  4722.7 2043.77  4727.8 2044.27  4757.7 2042.49  4848.3 2041.08  4938.9 2041.91
  4983.7 2039.17  4996.3 2036.81  4999.1 2036.31  5002.3 2036.81  5009.4 2039.35
  5029.5 2040.59  5196.1 2040.37  5495.3 2041.75  5577.8 2040.66  5724.2 2042.36
  5764.8 2041.97  5800.0 2042.93  5828.8 2045.88  5871.9 2047.71  6134.1 2050.12
  6589.5 2052.36  6774.8 2055.12  6830.9 2056.77  7115.4 2057.67  7220.5 2060.93
#Mann=4,-1,0
  4095.2    0.05       0  4317.6     0.1       0  4996.3    0.07       0
  5002.3     0.1       0
Bank Sta=4996.3,5002.3
Exp/Cntr=0.3,0.1

Chan Stop Cuts=-1