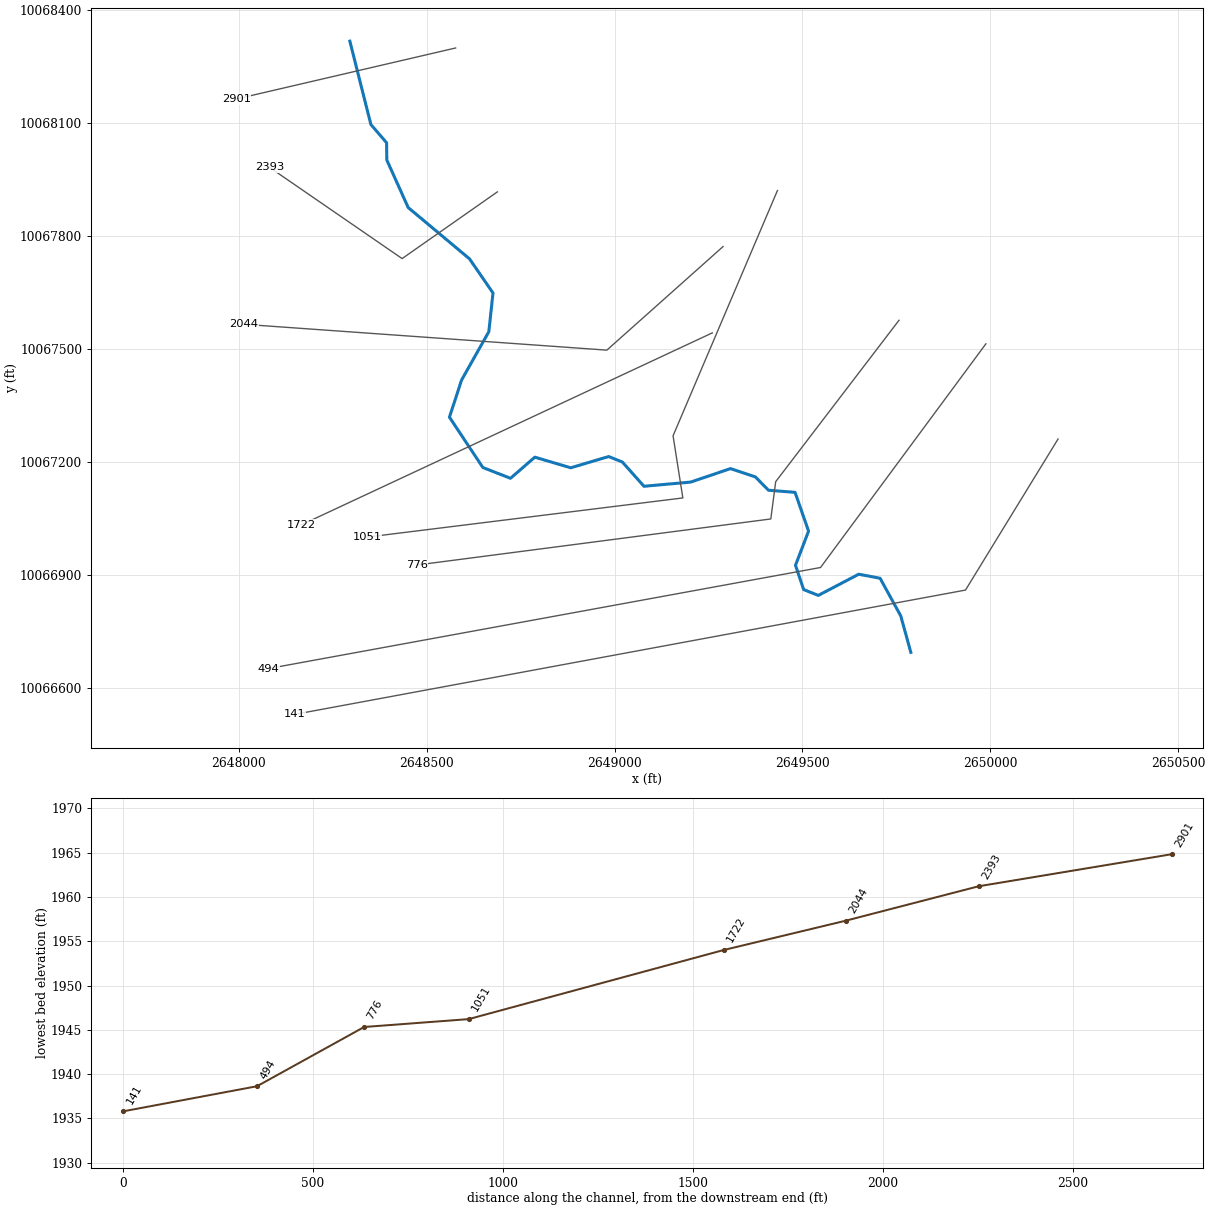
--- UNT 0095 IN HEWA.prj (project) ---

Proj Title=UNT 0095 IN HEWA Base Level Engineering
Current Plan=p01
Default Exp/Contr=0.3,0.1
English Units
Geom File=g01
Flow File=f01
Plan File=p01
BEGIN DESCRIPTION:
UNT 0095 IN HEWA
END DESCRIPTION:

--- UNT 0095 IN HEWA.p01 (plan) ---

Plan Title=Multiple Run
Short Identifier=Multiple
Geom File=g01
Flow File=f01
Subcritical Flow
K Sum by GR= 0
Std Step Tol= 0.01
Critical Tol= 0.01
Num of Std Step Trials= 20
Max Error Tol= 0.3
Flow Tol Ratio= 0.001
Split Flow NTrial= 30
Split Flow Tol= 0.02
Split Flow Ratio= 0.02
Log Output Level= 0
Friction Slope Method= 1
Unsteady Friction Slope Method= 2
Unsteady Bridges Friction Slope Method= 1
Parabolic Critical Depth
Global Vel Dist=  1 , 1 , 1
Global Log Level= 0
CheckData=True
Encroach Param= -1, 0, 0, 0
BEGIN DESCRIPTION:
Multiple Run
END DESCRIPTION:

--- UNT 0095 IN HEWA.f01 (steady flow) ---

Flow Title=Multiple
Number of Profiles=7
Profile Names=10-year,25-year,50-year,1pct_min,100-year,1pct_plu,500-year
River Rch & RM= UNT 0095 IN HEWA,Reach-1,2901
     757    1076    1345    1228    1660    2245    2527
Boundary for River Rch & Prof#=UNT 0095 IN HEWA,Reach-1,1
Up Type=0
Dn Type=3
Dn Slope=0.005
Boundary for River Rch & Prof#=UNT 0095 IN HEWA,Reach-1,2
Up Type=0
Dn Type=3
Dn Slope=0.005
Boundary for River Rch & Prof#=UNT 0095 IN HEWA,Reach-1,3
Up Type=0
Dn Type=3
Dn Slope=0.005
Boundary for River Rch & Prof#=UNT 0095 IN HEWA,Reach-1,4
Up Type=0
Dn Type=3
Dn Slope=0.005
Boundary for River Rch & Prof#=UNT 0095 IN HEWA,Reach-1,5
Up Type=0
Dn Type=3
Dn Slope=0.005
Boundary for River Rch & Prof#=UNT 0095 IN HEWA,Reach-1,6
Up Type=0
Dn Type=3
Dn Slope=0.005
Boundary for River Rch & Prof#=UNT 0095 IN HEWA,Reach-1,7
Up Type=0
Dn Type=3
Dn Slope=0.005

--- UNT 0095 IN HEWA.g01 (geometry) ---

Geom Title=Existing Conditions

River Reach=UNT 0095 IN HEWA,Reach-1
Reach XY= 30
      2648295.57     10068316.17      2648351.64     10068094.82
      2648393.39     10068046.36      2648393.92     10068000.81
      2648450.84     10067874.52      2648613.90     10067738.50
      2648676.52     10067647.78      2648665.44     10067545.02
      2648592.89     10067416.59      2648560.62     10067318.09
      2648649.54     10067184.61      2648723.08     10067155.87
      2648787.88     10067211.97      2648883.45     10067183.75
      2648984.45     10067213.71      2649020.91     10067198.95
      2649078.23     10067134.75      2649202.61     10067145.82
      2649308.51     10067181.62      2649374.84     10067159.56
      2649409.52     10067124.25      2649480.34     10067118.59
      2649516.29     10067015.71      2649481.48     10066924.88
      2649503.30     10066860.46      2649542.35     10066845.10
      2649649.80     10066901.30      2649706.62     10066890.62
      2649761.62     10066790.69      2649788.47     10066693.73

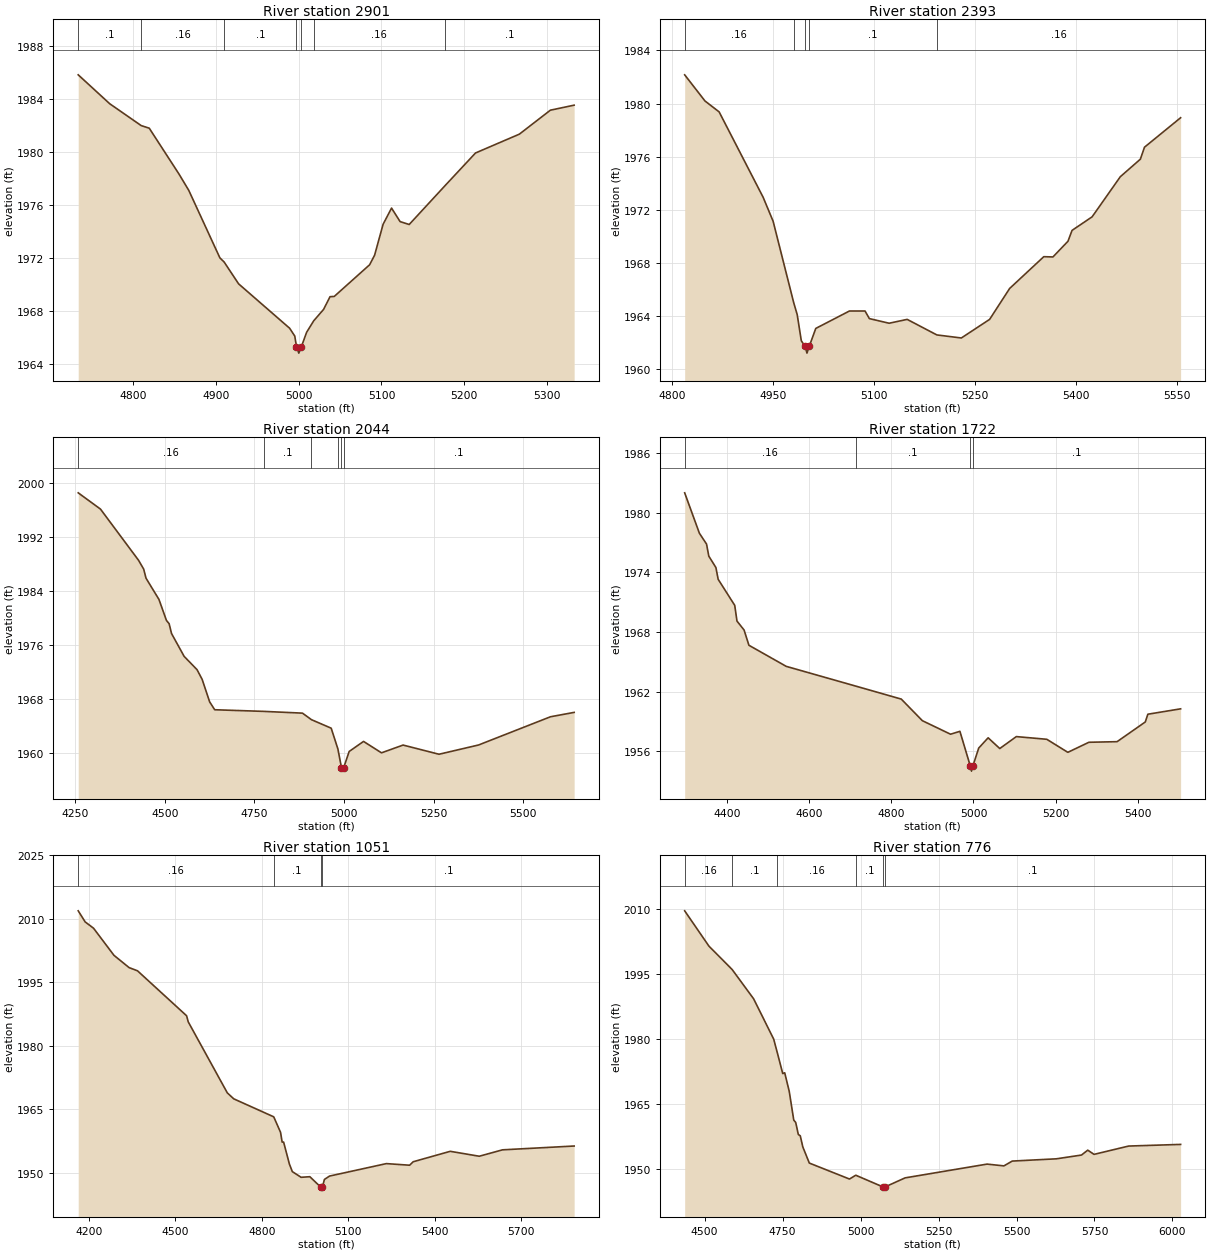
Type RM Length L Ch R = 1,2901,508,508,508
BEGIN DESCRIPTION:
UNT 0095 IN HEWA 5.0
END DESCRIPTION:
XS GIS Cut Line= 2
      2648577.11     10068298.10      2647993.72     10068162.67
#Sta/Elev= 30
  4733.8 1985.84  4771.8 1983.66  4809.8 1982.01  4819.6 1981.81  4855.6 1978.34
  4867.3 1977.12  4904.9 1972.02  4910.0 1971.71  4927.5 1970.06  4989.1 1966.71
  4995.3 1966.12  4997.4 1965.33  5000.2 1964.83  5003.4 1965.33  5009.6 1966.40
  5018.2 1967.27  5030.1 1968.13  5037.9 1969.09  5043.0 1969.11  5085.7 1971.50
  5091.7 1972.22  5102.0 1974.56  5112.2 1975.78  5122.5 1974.76  5133.5 1974.54
  5176.6 1977.46  5213.6 1979.94  5266.5 1981.36  5304.0 1983.17  5332.7 1983.55
#Mann=7,-1,0
  4733.8     0.1       0  4809.8    0.16       0  4910.0     0.1       0
  4997.4    0.07       0  5003.4     0.1       0  5018.2    0.16       0
  5176.6     0.1       0
Bank Sta=4997.4,5003.4
Exp/Cntr=0.3,0.1

Type RM Length L Ch R = 1,2393,349,349,349
BEGIN DESCRIPTION:
UNT 0095 IN HEWA 4.0
END DESCRIPTION:
XS GIS Cut Line= 3
      2648688.13     10067916.12      2648434.70     10067739.07
      2648082.02     10067981.10
#Sta/Elev= 30
  4818.6 1982.16  4848.8 1980.19  4869.8 1979.37  4935.2 1972.94  4950.0 1971.14
  4980.7 1964.99  4985.8 1964.11  4991.9 1962.14  4997.6 1961.71  5000.3 1961.21
  5003.6 1961.71  5013.4 1963.07  5063.4 1964.38  5086.6 1964.38  5093.0 1963.81
  5122.4 1963.46  5149.2 1963.75  5193.3 1962.58  5229.7 1962.35  5271.7 1963.75
  5301.5 1966.08  5352.2 1968.47  5365.8 1968.45  5388.1 1969.63  5394.2 1970.45
  5424.0 1971.47  5465.9 1974.49  5495.7 1975.81  5501.8 1976.71  5555.5 1978.93
#Mann=5,-1,0
  4818.6    0.16       0  4980.7     0.1       0  4997.6    0.07       0
  5003.6     0.1       0  5193.3    0.16       0
Bank Sta=4997.6,5003.6
Exp/Cntr=0.3,0.1

Type RM Length L Ch R = 1,2044,322,322,322
BEGIN DESCRIPTION:
UNT 0095 IN HEWA 3.0
END DESCRIPTION:
XS GIS Cut Line= 3
      2649288.80     10067771.00      2648979.49     10067496.06
      2648012.56     10067564.72
#Sta/Elev= 30
  4258.7 1998.55  4320.8 1996.14  4427.0 1988.56  4441.2 1987.26  4447.9 1985.90
  4483.9 1982.76  4504.8 1979.65  4512.3 1979.16  4519.0 1977.71  4554.1 1974.33
  4590.1 1972.36  4604.3 1970.93  4625.2 1967.60  4639.4 1966.42  4775.6 1966.18
  4884.1 1965.92  4909.3 1964.95  4964.3 1963.69  4983.0 1960.61  4993.0 1957.83
  4995.8 1957.33  4999.0 1957.83  5014.4 1960.24  5054.5 1961.73  5104.6 1960.04
  5164.8 1961.19  5265.0 1959.83  5375.3 1961.20  5575.8 1965.38  5641.9 1966.03
#Mann=6,-1,0
  4258.7    0.16       0  4775.6     0.1       0  4909.3    0.16       0
  4983.0     0.1       0  4993.0    0.07       0  4999.0     0.1       0
Bank Sta=4993,4999
Exp/Cntr=0.3,0.1

Type RM Length L Ch R = 1,1722,671,671,671
BEGIN DESCRIPTION:
UNT 0095 IN HEWA 2.0
END DESCRIPTION:
XS GIS Cut Line= 2
      2649260.14     10067541.88      2648166.18     10067032.13
#Sta/Elev= 30
  4297.2 1981.98  4333.0 1977.92  4350.4 1976.83  4355.9 1975.62  4373.2 1974.47
  4378.7 1973.29  4419.0 1970.67  4424.5 1969.09  4441.8 1968.19  4453.5 1966.66
  4544.3 1964.54  4714.0 1962.55  4824.3 1961.25  4875.6 1959.08  4944.2 1957.72
  4967.0 1958.01  4992.4 1954.51  4995.2 1954.01  4998.4 1954.51  5012.8 1956.33
  5035.7 1957.36  5064.0 1956.28  5104.3 1957.48  5178.4 1957.21  5229.7 1955.90
  5280.9 1956.91  5349.5 1956.97  5418.1 1958.95  5424.4 1959.73  5504.1 1960.27
#Mann=4,-1,0
  4297.2    0.16       0  4714.0     0.1       0  4992.4    0.07       0
  4998.4     0.1       0
Bank Sta=4992.4,4998.4
Exp/Cntr=0.3,0.1

Type RM Length L Ch R = 1,1051,275,275,275
BEGIN DESCRIPTION:
Mapping XS 972ec788
END DESCRIPTION:
XS GIS Cut Line= 4
      2649433.48     10067919.72      2649155.70     10067268.69
      2649181.75     10067103.76      2648341.64     10066999.83
#Sta/Elev= 30
  4163.2 2011.87  4187.4 2009.25  4216.4 2007.77  4287.3 2001.37  4339.9 1998.47
  4369.0 1997.72  4539.4 1987.11  4545.1 1985.67  4680.7 1968.92  4703.1 1967.51
  4841.8 1963.27  4865.5 1959.61  4871.0 1957.31  4876.1 1957.31  4896.3 1952.10
  4906.4 1950.34  4936.8 1949.00  4967.2 1949.14  5004.6 1946.71  5007.4 1946.21
  5010.6 1946.71  5017.8 1948.50  5035.5 1949.29  5232.7 1952.23  5313.4 1951.85
  5325.9 1952.67  5454.4 1955.13  5555.2 1953.97  5635.8 1955.48  5884.5 1956.38
#Mann=4,-1,0
  4163.2    0.16       0  4841.8     0.1       0  5004.6    0.07       0
  5010.6     0.1       0
Bank Sta=5004.6,5010.6
Exp/Cntr=0.3,0.1

Type RM Length L Ch R = 1,776,282,282,282
BEGIN DESCRIPTION:
Mapping XS 8b830091
END DESCRIPTION:
XS GIS Cut Line= 4
      2649756.95     10067575.33      2649428.82     10067146.93
      2649415.80     10067047.97      2648473.24     10066925.59
#Sta/Elev= 30
  4436.2 2009.61  4513.9 2001.46  4588.2 1996.07  4657.2 1989.29  4721.6 1979.97
  4733.5 1976.74  4750.6 1972.01  4756.9 1972.20  4771.4 1967.91  4785.9 1961.27
  4792.2 1960.71  4800.5 1957.95  4806.8 1957.63  4815.0 1955.06  4835.8 1951.34
  4964.6 1947.65  4984.7 1948.53  5072.3 1945.82  5075.0 1945.32  5078.3 1945.82
  5142.9 1947.92  5405.7 1951.10  5459.6 1950.69  5486.4 1951.80  5627.6 1952.32
  5708.2 1953.19  5728.4 1954.32  5748.6 1953.35  5859.5 1955.27  6026.1 1955.65
#Mann=6,-1,0
  4436.2    0.16       0  4588.2     0.1       0  4733.5    0.16       0
  4984.7     0.1       0  5072.3    0.07       0  5078.3     0.1       0
Bank Sta=5072.3,5078.3
Exp/Cntr=0.3,0.1

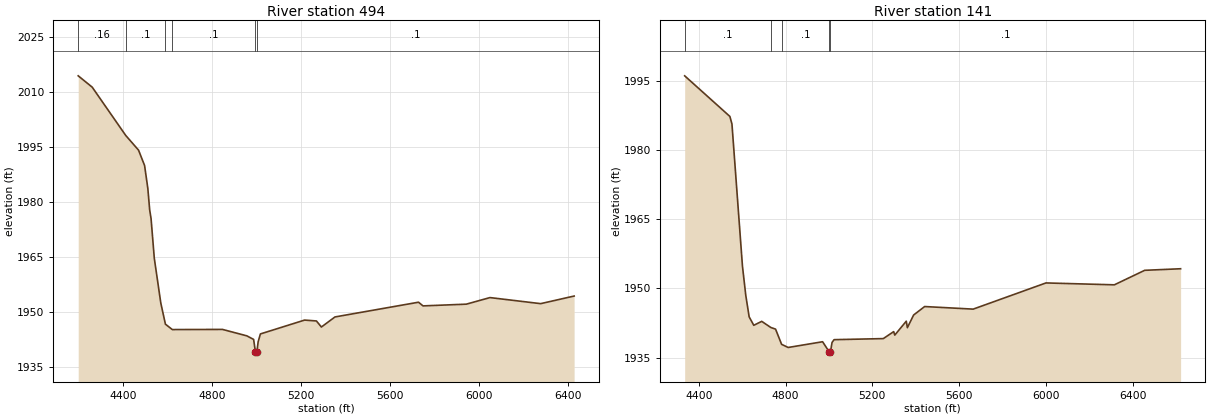
Type RM Length L Ch R = 1,494,353,353,353
BEGIN DESCRIPTION:
Mapping XS f181b660
END DESCRIPTION:
XS GIS Cut Line= 3
      2649988.21     10067512.86      2649548.12     10066919.13
      2648079.36     10066650.90
#Sta/Elev= 30
  4197.4 2014.33  4260.3 2011.25  4411.2 1998.12  4469.0 1994.11  4496.1 1989.94
  4510.7 1983.74  4519.1 1977.84  4525.3 1975.49  4539.9 1964.68  4569.2 1952.51
  4589.9 1946.78  4620.9 1945.31  4846.7 1945.35  4956.4 1943.60  4986.9 1942.63
  4995.3 1939.13  4998.0 1938.63  5001.3 1939.13  5007.3 1942.00  5017.4 1944.12
  5216.3 1947.89  5269.6 1947.65  5291.9 1946.00  5352.9 1948.74  5729.0 1952.75
  5749.3 1951.75  5944.1 1952.22  6050.6 1954.01  6278.8 1952.36  6429.5 1954.43
#Mann=6,-1,0
  4197.4    0.16       0  4411.2     0.1       0  4589.9    0.16       0
  4620.9     0.1       0  4995.3    0.07       0  5001.3     0.1       0
Bank Sta=4995.3,5001.3
Exp/Cntr=0.3,0.1

Type RM Length L Ch R = 1,141,0,0,0
BEGIN DESCRIPTION:
UNT 0095 IN HEWA 1.0
END DESCRIPTION:
XS GIS Cut Line= 3
      2650180.22     10067260.14      2649933.93     10066859.21
      2648147.92     10066529.11
#Sta/Elev= 30
  4334.7 1996.03  4543.1 1987.24  4552.7 1985.60  4601.1 1954.85  4616.5 1948.49
  4632.0 1943.86  4653.3 1942.03  4690.0 1942.88  4731.8 1941.56  4753.8 1941.20
  4781.6 1937.91  4811.9 1937.23  4970.7 1938.47  5001.0 1936.29  5003.8 1935.79
  5007.0 1936.29  5014.2 1938.31  5023.6 1938.92  5250.6 1939.15  5298.4 1940.66
  5303.5 1939.91  5356.5 1942.92  5361.6 1941.51  5390.4 1944.26  5441.3 1946.09
  5665.0 1945.53  6000.6 1951.20  6315.9 1950.79  6455.8 1953.93  6621.5 1954.27
#Mann=5,-1,0
  4334.7     0.1       0  4731.8    0.05       0  4781.6     0.1       0
  5001.0    0.07       0  5007.0     0.1       0
Bank Sta=5001,5007
Exp/Cntr=0.3,0.1

Chan Stop Cuts=-1