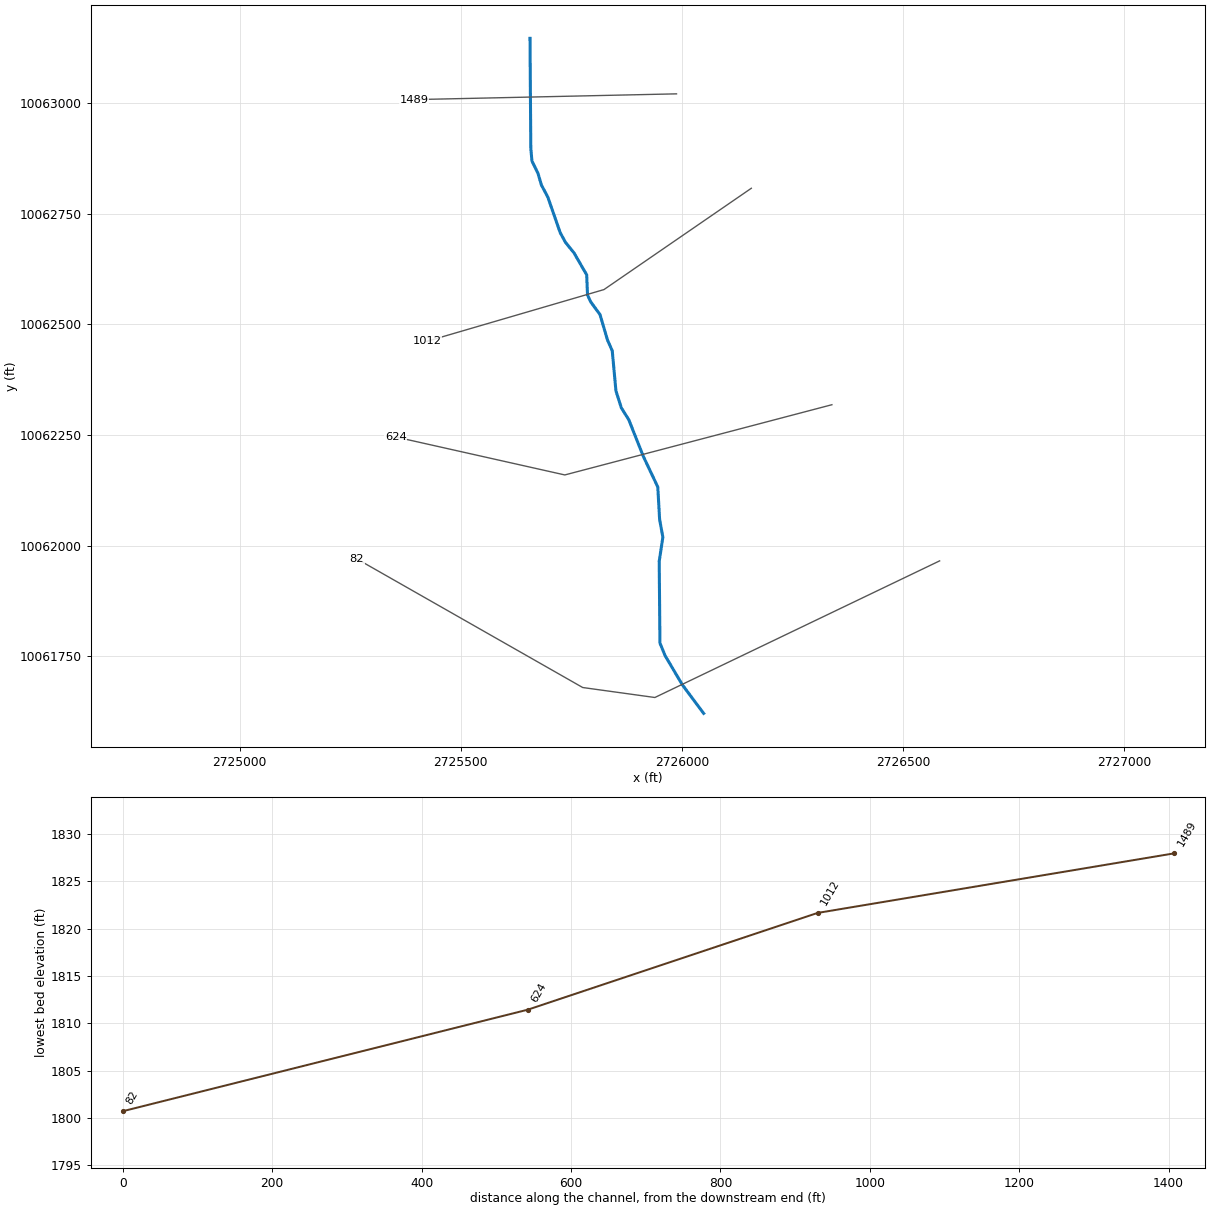
--- UNT 0096 IN HEWA.prj (project) ---

Proj Title=UNT 0096 IN HEWA Base Level Engineering
Current Plan=p01
Default Exp/Contr=0.3,0.1
English Units
Geom File=g01
Flow File=f01
Plan File=p01
Y Axis Title=Elevation
X Axis Title(PF)=Main Channel Distance
X Axis Title(XS)=Station
BEGIN DESCRIPTION:
UNT 0096 IN HEWA
END DESCRIPTION:
DSS Export Rating Curves= 0
DSS Export Rating Curve Sorted= 0
DSS Export Volume Flow Curves= 0
DXF OffsetX= 0
DXF OffsetY= 0
DXF ScaleX= 1
DXF ScaleY= 10

--- UNT 0096 IN HEWA.p01 (plan) ---

Plan Title=Multiple Run
Short Identifier=Multiple
Geom File=g01
Flow File=f01
Subcritical Flow
K Sum by GR= 0
Std Step Tol= 0.01
Critical Tol= 0.01
Num of Std Step Trials= 20
Max Error Tol= 0.3
Flow Tol Ratio= 0.001
Split Flow NTrial= 30
Split Flow Tol= 0.02
Split Flow Ratio= 0.02
Log Output Level= 0
Friction Slope Method= 1
Unsteady Friction Slope Method= 2
Unsteady Bridges Friction Slope Method= 1
Parabolic Critical Depth
Global Vel Dist=  1 , 1 , 1
Global Log Level= 0
CheckData=True
Encroach Param= -1, 0, 0, 0
BEGIN DESCRIPTION:
Multiple Run
END DESCRIPTION:

--- UNT 0096 IN HEWA.f01 (steady flow) ---

Flow Title=Multiple
Program Version=4.10
Number of Profiles= 7
Profile Names=10-year,25-year,50-year,1pct_min,100-year,1pct_plu,500-year
River Rch & RM=UNT 0096 IN HEWA,Reach-1         ,1489
     405     569     707     646     874    1182    1338
Boundary for River Rch & Prof#=UNT 0096 IN HEWA,Reach-1         , 1
Up Type= 0
Dn Type= 3
Dn Slope=0.02
Boundary for River Rch & Prof#=UNT 0096 IN HEWA,Reach-1         , 2
Up Type= 0
Dn Type= 3
Dn Slope=0.02
Boundary for River Rch & Prof#=UNT 0096 IN HEWA,Reach-1         , 3
Up Type= 0
Dn Type= 3
Dn Slope=0.02
Boundary for River Rch & Prof#=UNT 0096 IN HEWA,Reach-1         , 4
Up Type= 0
Dn Type= 3
Dn Slope=0.02
Boundary for River Rch & Prof#=UNT 0096 IN HEWA,Reach-1         , 5
Up Type= 0
Dn Type= 3
Dn Slope=0.02
Boundary for River Rch & Prof#=UNT 0096 IN HEWA,Reach-1         , 6
Up Type= 0
Dn Type= 3
Dn Slope=0.02
Boundary for River Rch & Prof#=UNT 0096 IN HEWA,Reach-1         , 7
Up Type= 0
Dn Type= 3
Dn Slope=0.02
DSS Import GetInterval= 0
DSS Import GetPeak= 0
DSS Import FillOption= 0

--- UNT 0096 IN HEWA.g01 (geometry) ---

Geom Title=Existing Conditions
Program Version=4.10

River Reach=UNT 0096 IN HEWA,Reach-1
Reach XY= 27
      2725656.38     10063147.18       2725658.2     10062898.63
      2725660.77     10062869.69      2725674.35     10062842.03
      2725682.23     10062815.29      2725696.71       10062788.
      2725724.57     10062707.92      2725736.39     10062686.09
       2725756.2     10062661.45      2725784.62     10062612.13
      2725786.47      10062566.5      2725793.67     10062551.12
      2725814.74     10062522.28      2725831.59     10062465.03
      2725842.39     10062440.63      2725850.71     10062350.01
      2725862.98     10062311.27      2725879.86     10062284.38
      2725913.02     10062200.92      2725945.39     10062132.45
      2725949.54     10062059.07       2725956.9     10062018.74
      2725948.63     10061964.41      2725950.27     10061779.37
      2725962.13     10061750.54       2726001.1     10061684.77
      2726049.09     10061620.32

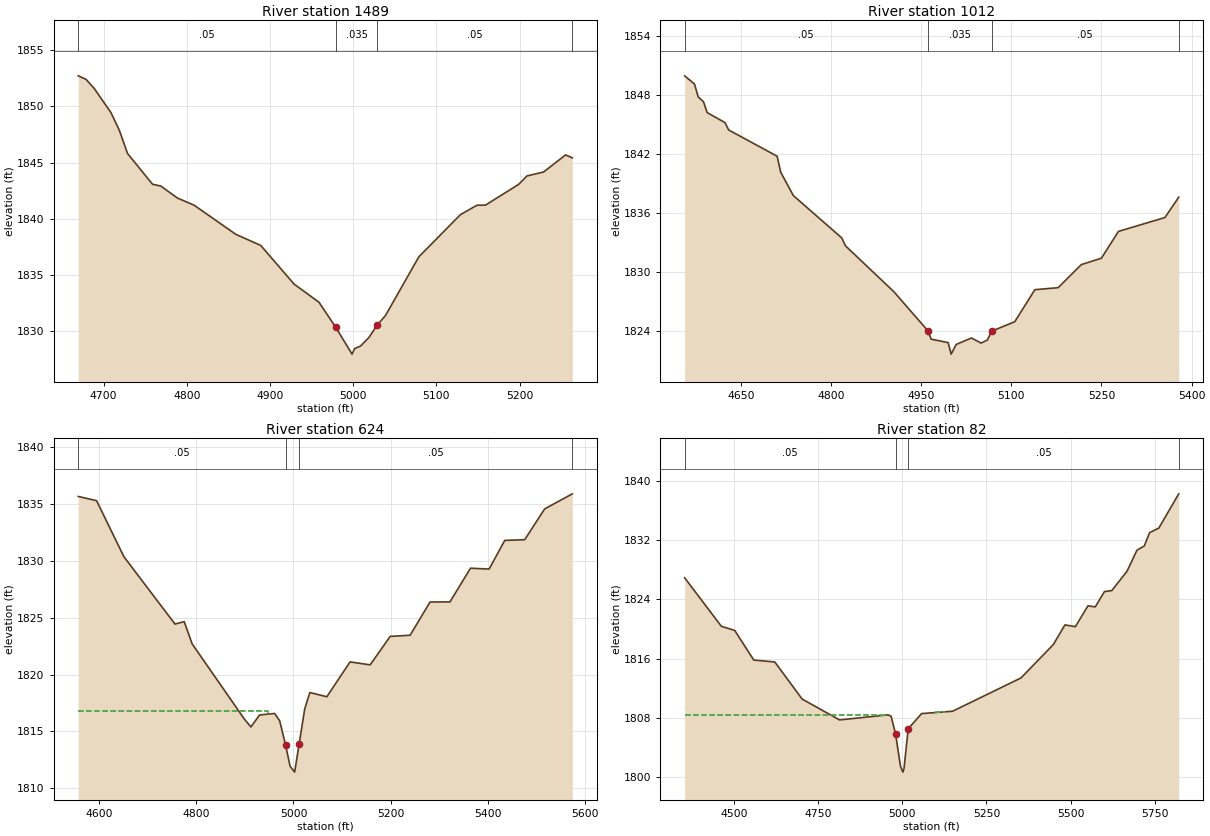
Type RM Length L Ch R = 1 ,1489    ,477,477,477
BEGIN DESCRIPTION:
UNT 0096 IN HEWA 3.0
END DESCRIPTION:
XS GIS Cut Line= 2
      2725987.77     10063021.61      2725394.01     10063008.58
#Sta/Elev= 30
  4669.5 1852.71  4678.8  1852.4  4688.8 1851.58  4708.8 1849.44  4718.8 1847.89
  4728.8  1845.8  4758.8 1843.07  4768.8 1842.91  4788.8 1841.84  4808.8 1841.21
  4858.9 1838.62  4888.9 1837.63  4928.9  1834.2  4958.9 1832.58  4978.9 1830.37
  4998.6 1827.97  5001.9 1828.47  5008.9 1828.69  5018.9 1829.45  5028.9 1830.55
  5038.9 1831.41  5078.9 1836.62  5128.9 1840.37  5148.9 1841.21  5158.9 1841.21
  5198.9 1843.06  5208.9 1843.81  5228.9 1844.16  5255.3 1845.68  5263.4 1845.42
#Mann= 4 ,-1 , 0
  4669.5     .05       0  4978.9    .035       0  5028.9     .05       0
  5263.4     .05       0
Bank Sta=4978.9,5028.9
XS Rating Curve= 0 ,0
Exp/Cntr=0.3,0.1

Type RM Length L Ch R = 1 ,1012    ,388,388,388
BEGIN DESCRIPTION:
UNT 0096 IN HEWA 2.0
END DESCRIPTION:
XS GIS Cut Line= 3
      2726156.98     10062808.05      2725823.67      10062578.9
      2725423.01     10062461.82
#Sta/Elev= 30
  4556.7 1849.95  4573.1 1849.11  4579.2 1847.81    4588 1847.32  4594.1 1846.22
  4623.9 1845.19  4629.9 1844.45  4710.5 1841.78  4716.5 1840.15  4737.5 1837.78
    4818 1833.48  4824.1 1832.68  4904.6 1828.02  4961.2 1824.05  4966.8 1823.19
    4995 1822.84    5000 1821.67  5008.3 1822.65  5033.7 1823.31  5049.9 1822.79
  5060.4 1823.11  5067.2    1824  5105.8 1824.96  5139.3 1828.22  5177.9 1828.42
  5216.6 1830.77    5250 1831.42  5278.3 1834.14  5355.6 1835.55  5378.6 1837.62
#Mann= 4 ,-1 , 0
  4556.7     .05       0  4961.2    .035       0  5067.2     .05       0
  5378.6     .05       0
Bank Sta=4961.2,5067.2
XS Rating Curve= 0 ,0
Exp/Cntr=0.3,0.1

Type RM Length L Ch R = 1 ,624     ,542,542,542
BEGIN DESCRIPTION:
Mapping XS 2f2e7bec
END DESCRIPTION:
XS GIS Cut Line= 3
      2726339.29     10062318.48      2725735.13     10062159.63
      2725352.84     10062245.44
#Sta/Elev= 30
  4557.2 1835.64  4594.9 1835.27  4651.1 1830.35  4756.3 1824.43  4775.2 1824.65
  4791.4  1822.7  4899.3 1816.07  4912.5  1815.4  4930.3 1816.45  4961.3 1816.58
  4971.7 1815.93 4983.64 1813.83  4993.1 1811.95  5002.4 1811.43 5011.59 1813.87
  5023.1 1816.97  5033.7 1818.42  5068.7 1818.05  5116.4 1821.11  5157.8 1820.85
    5199 1823.35    5240 1823.45    5281 1826.37    5322 1826.38  5364.3 1829.34
  5402.5 1829.26  5434.7 1831.78  5475.7 1831.84  5516.7 1834.54  5573.7 1835.87
#Mann= 4 ,-1 , 0
  4557.2     .05       0 4983.64    .035       0 5011.59     .05       0
  5573.7     .05       0
#XS Ineff= 2 , 0
          4947.5 1816.83
Permanent Ineff=
       T       T
Bank Sta=4983.64,5011.59
XS Rating Curve= 0 ,0
Exp/Cntr=0.3,0.1

Type RM Length L Ch R = 1 ,82      ,0,0,0
BEGIN DESCRIPTION:
UNT 0096 IN HEWA 1.0
END DESCRIPTION:
XS GIS Cut Line= 4
      2726582.91     10061965.27      2725938.79     10061656.23
      2725775.59      10061678.8      2725264.96      10061969.6
#Sta/Elev= 30
    4354 1826.89  4462.9 1820.35  4502.7 1819.79  4559.1  1815.8  4621.5 1815.54
  4702.8 1810.54  4813.8 1807.73  4957.9 1808.41  4966.8 1808.23    4980 1805.87
    4995 1801.42    5002 1800.69  5005.2 1801.19  5017.6 1806.53  5057.4 1808.58
  5149.5  1808.9  5352.5 1813.39  5448.5 1817.89    5483 1820.54  5513.9  1820.3
  5551.3 1823.11    5573 1822.97  5600.3 1825.03  5621.9 1825.16  5667.2 1827.77
  5696.9 1830.62  5718.5 1831.18  5734.3 1832.98  5761.7 1833.59  5820.8 1838.21
#Mann= 4 ,-1 , 0
    4354     .05       0    4980    .035       0  5017.6     .05       0
  5820.8      .1       0
#XS Ineff= 2 ,-1
    4354 4957.82 1808.41 5098.72  5126.4 1808.76
Permanent Ineff=
       T       T
Bank Sta=4980,5017.6
XS Rating Curve= 0 ,0
Exp/Cntr=0.3,0.1

Chan Stop Cuts=-1
Use User Specified Reach Order=0
Composite Channel Slope=5