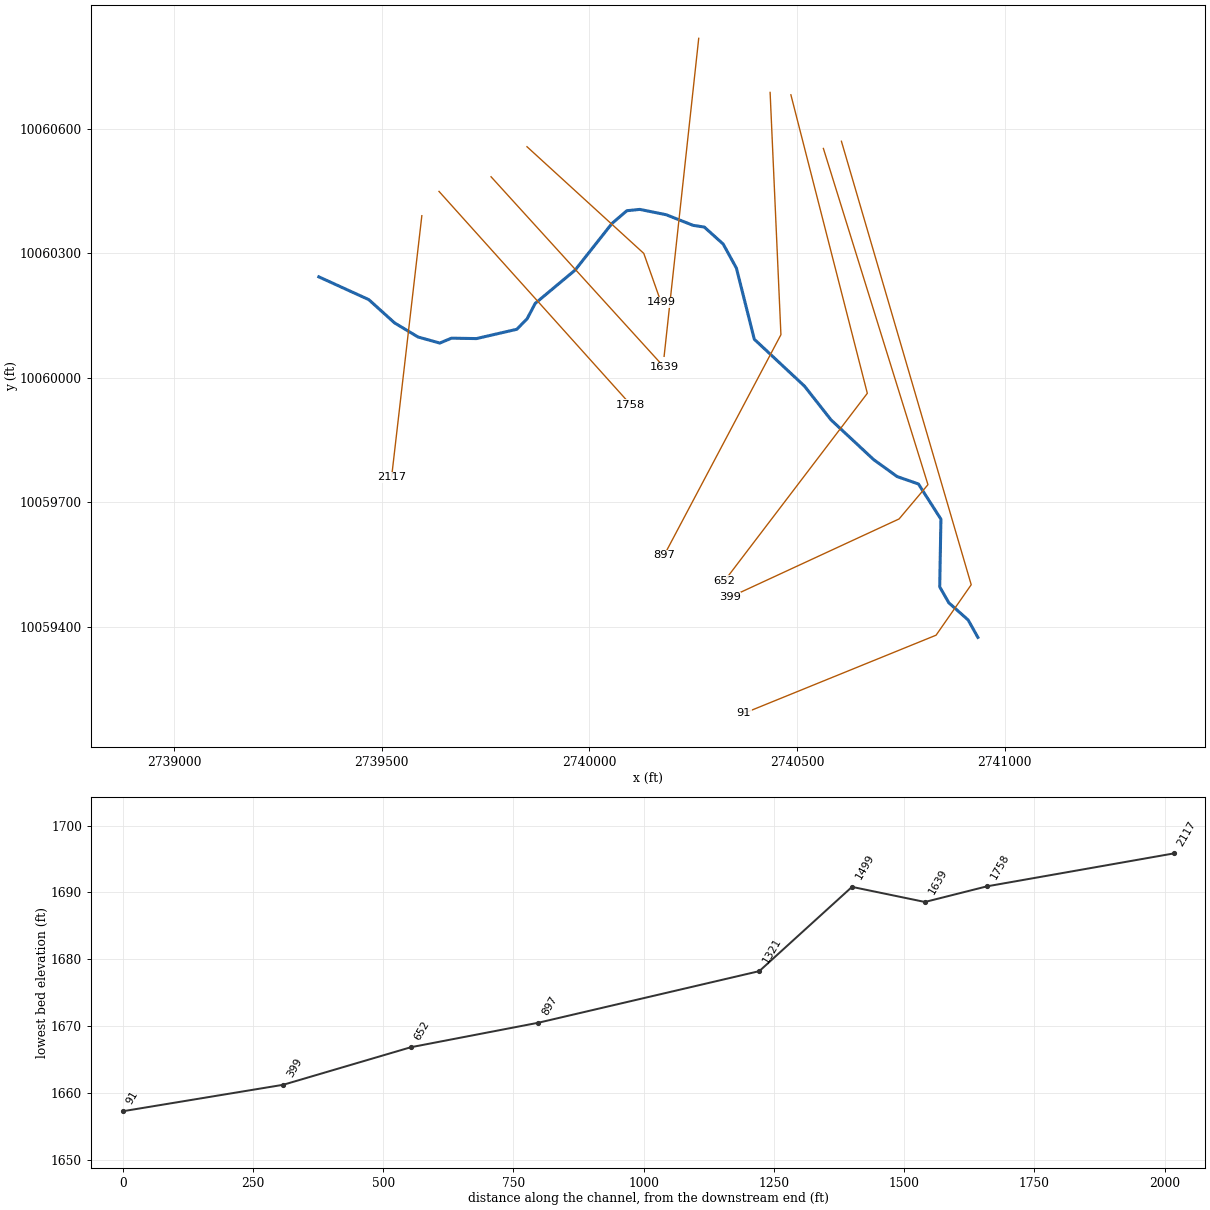
--- UNT 0097 IN HEWA.prj (project) ---

Proj Title=UNT 0097 IN HEWA Base Level Engineering
Current Plan=p01
Default Exp/Contr=0.3,0.1
English Units
Geom File=g01
Flow File=f01
Plan File=p01
Y Axis Title=Elevation
X Axis Title(PF)=Main Channel Distance
X Axis Title(XS)=Station
BEGIN DESCRIPTION:
UNT 0097 IN HEWA
END DESCRIPTION:
DSS Export Rating Curves= 0
DSS Export Rating Curve Sorted= 0
DSS Export Volume Flow Curves= 0
DXF OffsetX= 0
DXF OffsetY= 0
DXF ScaleX= 1
DXF ScaleY= 10

--- UNT 0097 IN HEWA.p01 (plan) ---

Plan Title=Multiple Run
Short Identifier=Multiple
Geom File=g01
Flow File=f01
Subcritical Flow
K Sum by GR= 0
Std Step Tol= 0.01
Critical Tol= 0.01
Num of Std Step Trials= 20
Max Error Tol= 0.3
Flow Tol Ratio= 0.001
Split Flow NTrial= 30
Split Flow Tol= 0.02
Split Flow Ratio= 0.02
Log Output Level= 0
Friction Slope Method= 1
Unsteady Friction Slope Method= 2
Unsteady Bridges Friction Slope Method= 1
Parabolic Critical Depth
Global Vel Dist=  1 , 1 , 1
Global Log Level= 0
CheckData=True
Encroach Param= -1, 0, 0, 0
BEGIN DESCRIPTION:
Multiple Run
END DESCRIPTION:

--- UNT 0097 IN HEWA.f01 (steady flow) ---

Flow Title=Multiple
Program Version=4.10
Number of Profiles= 7
Profile Names=10-year,25-year,50-year,1pct_min,100-year,1pct_plu,500-year
River Rch & RM=UNT 0097 IN HEWA,Reach-1         ,2117
     363     506     625     569     769    1040    1165
Boundary for River Rch & Prof#=UNT 0097 IN HEWA,Reach-1         , 1
Up Type= 0
Dn Type= 3
Dn Slope=0.014
Boundary for River Rch & Prof#=UNT 0097 IN HEWA,Reach-1         , 2
Up Type= 0
Dn Type= 3
Dn Slope=0.014
Boundary for River Rch & Prof#=UNT 0097 IN HEWA,Reach-1         , 3
Up Type= 0
Dn Type= 3
Dn Slope=0.014
Boundary for River Rch & Prof#=UNT 0097 IN HEWA,Reach-1         , 4
Up Type= 0
Dn Type= 3
Dn Slope=0.014
Boundary for River Rch & Prof#=UNT 0097 IN HEWA,Reach-1         , 5
Up Type= 0
Dn Type= 3
Dn Slope=0.014
Boundary for River Rch & Prof#=UNT 0097 IN HEWA,Reach-1         , 6
Up Type= 0
Dn Type= 3
Dn Slope=0.014
Boundary for River Rch & Prof#=UNT 0097 IN HEWA,Reach-1         , 7
Up Type= 0
Dn Type= 3
Dn Slope=0.014
DSS Import GetInterval= 0
DSS Import GetPeak= 0
DSS Import FillOption= 0

--- UNT 0097 IN HEWA.g01 (geometry) ---

Geom Title=Existing Conditions
Program Version=4.10

River Reach=UNT 0097 IN HEWA,Reach-1
Reach XY= 30
      2739348.97      10060242.9      2739469.17     10060188.13
      2739531.57     10060131.85      2739587.71     10060098.15
      2739640.11     10060083.48      2739668.47     10060095.26
      2739728.38     10060094.25      2739825.78     10060116.69
      2739850.67     10060142.31      2739870.02       10060179.
      2739966.06     10060259.17      2740054.53     10060371.15
      2740090.62     10060402.15      2740121.83      10060405.3
      2740185.18     10060392.52      2740250.07     10060366.91
      2740277.21     10060362.72      2740322.49     10060321.94
       2740354.4     10060263.91      2740397.47     10060092.62
      2740518.28     10059979.84       2740582.1     10059898.65
      2740684.65     10059803.01      2740741.39     10059762.02
      2740792.65     10059744.23       2740846.8     10059659.46
      2740843.89     10059496.57      2740865.71     10059458.29
      2740912.33     10059416.77       2740935.8     10059374.83

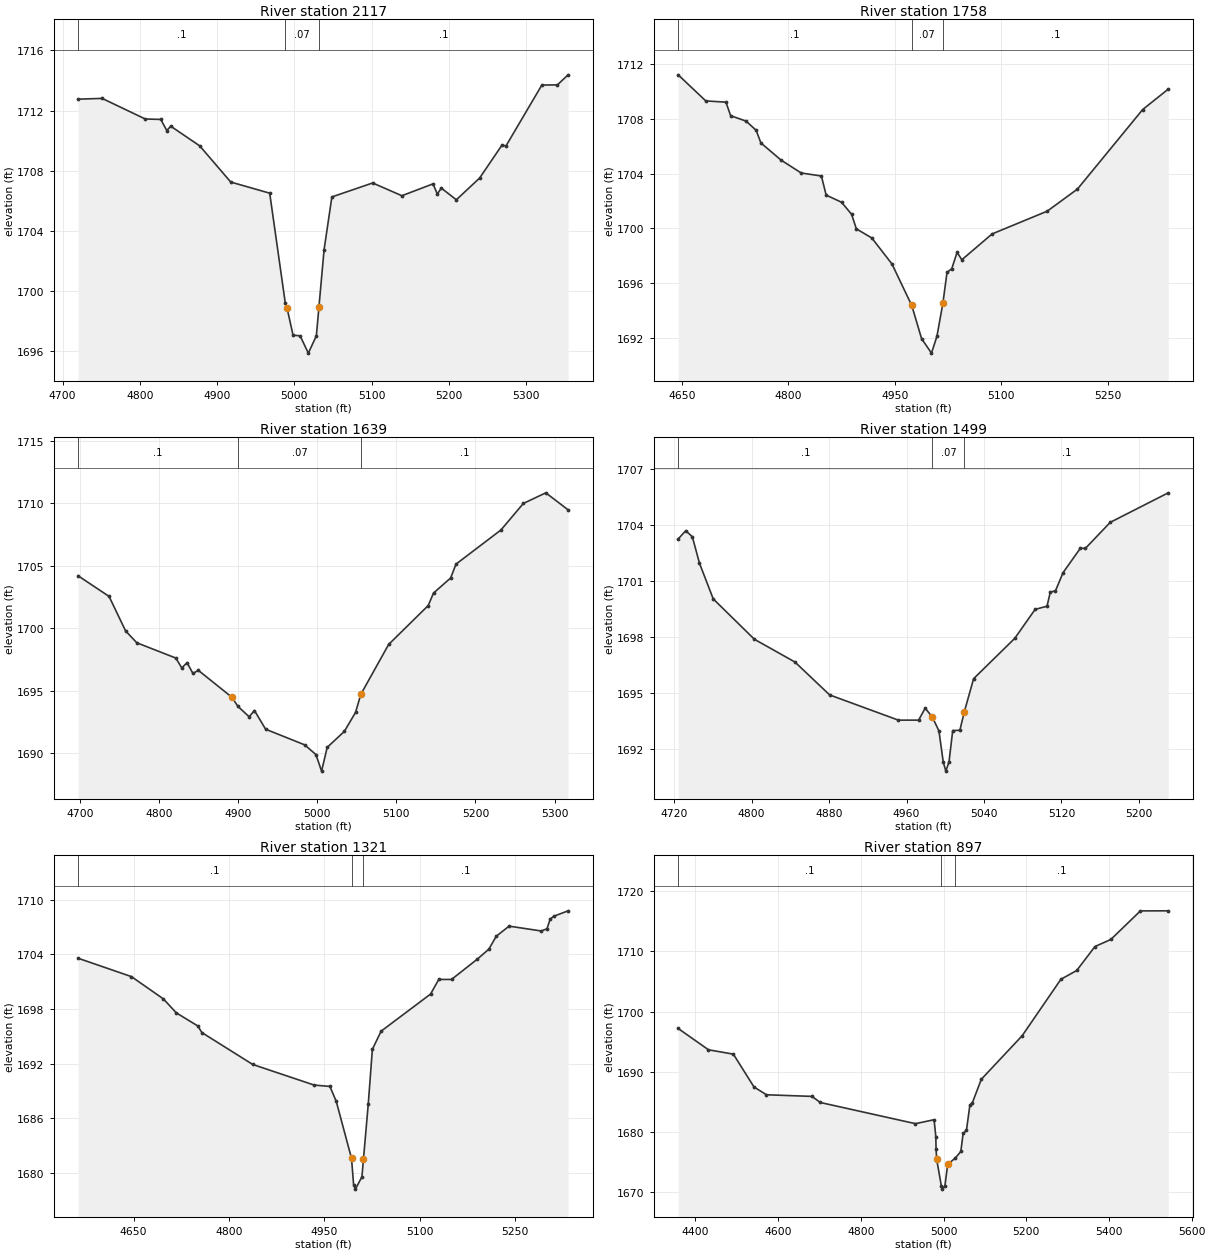
Type RM Length L Ch R = 1 ,2117    ,359,359,359
BEGIN DESCRIPTION:
UNT 0097 IN HEWA 4.0
END DESCRIPTION:
XS GIS Cut Line= 2
        2739597.     10060390.14      2739524.08     10059759.95
#Sta/Elev= 30
  4719.9 1712.76  4751.1 1712.81  4806.9 1711.44    4827 1711.41  4834.8 1710.67
  4839.9 1710.96  4877.4 1709.65  4917.6 1707.24    4968  1706.5  4988.1 1699.21
 4990.34 1698.88  4998.2 1697.05  5007.4    1697    5018 1695.85  5028.4    1697
  5031.7  1698.9  5038.4 1702.74  5048.5 1706.25  5101.3 1707.18  5139.1 1706.33
  5179.4 1707.12    5185 1706.44  5190.1 1706.84  5209.6 1706.06  5239.8 1707.51
  5268.8 1709.71  5273.8 1709.64  5320.3  1713.7  5340.4 1713.71  5354.3 1714.38
#Mann= 3 ,-1 , 0
  4719.9      .1       0  4988.1     .07       0  5031.7      .1       0
Bank Sta=4990.34,5031.7
XS Rating Curve= 0 ,0
Exp/Cntr=0.3,0.1

Type RM Length L Ch R = 1 ,1758    ,119,119,119
BEGIN DESCRIPTION:
Mapping XS b7484328
END DESCRIPTION:
XS GIS Cut Line= 2
      2739638.33     10060448.64      2740100.14     10059934.75
#Sta/Elev= 30
  4644.6 1711.19  4683.5 1709.29  4711.9  1709.2  4718.6 1708.21  4740.3 1707.82
  4754.5 1707.15  4761.2 1706.23  4789.6 1704.98  4818.1 1704.04  4846.5 1703.82
  4853.2 1702.43  4874.9 1701.91  4889.1 1701.03  4895.8 1699.97  4917.5 1699.31
  4945.9 1697.42  4973.9 1694.39  4987.7 1691.98  5001.7 1690.92  5009.4 1692.15
 5017.73 1694.54  5023.6  1696.8  5030.3 1697.07  5037.8 1698.26  5044.5 1697.72
  5087.1  1699.6  5164.9 1701.26  5207.5 1702.87  5299.4 1708.66  5335.5 1710.15
#Mann= 3 ,-1 , 0
  4644.6      .1       0  4973.9     .07       0 5017.73      .1       0
Bank Sta=4973.9,5017.73
XS Rating Curve= 0 ,0
Exp/Cntr=0.3,0.1

Type RM Length L Ch R = 1 ,1639    ,140,140,140
BEGIN DESCRIPTION:
Mapping XS 65c31947
END DESCRIPTION:
XS GIS Cut Line= 2
      2739763.65     10060483.88      2740180.31     10060025.57
#Sta/Elev= 30
  4697.8  1704.2    4737 1702.55  4757.9 1699.79  4772.1 1698.84  4821.4 1697.62
  4828.9 1696.83  4835.6 1697.25    4843 1696.39  4849.8 1696.64  4892.4 1694.48
  4899.8 1693.76    4914 1692.93  4920.8 1693.42  4934.9 1691.93  4984.3 1690.68
  4998.5  1689.9  5005.6 1688.58  5012.7 1690.48  5034.3 1691.75  5048.5 1693.27
  5055.2 1694.72  5090.4 1698.71  5140.4 1701.82  5147.1 1702.82  5168.7 1704.02
  5175.5 1705.13  5232.3 1707.86  5260.6 1709.98    5289 1710.83  5317.2 1709.47
#Mann= 3 ,-1 , 0
  4697.8      .1       0  4899.8     .07       0  5055.2      .1       0
Bank Sta=4892.4,5055.2
XS Rating Curve= 0 ,0
Exp/Cntr=0.3,0.1

Type RM Length L Ch R = 1 ,1499    ,178,178,178
BEGIN DESCRIPTION:
Mapping XS 903b2860
END DESCRIPTION:
XS GIS Cut Line= 3
      2739850.17     10060556.24      2740131.41     10060299.31
      2740173.07     10060181.28
#Sta/Elev= 30
  4724.2 1703.27    4732 1703.71  4738.8 1703.39  4746.2 1701.97  4760.4 1700.06
  4802.9  1697.9  4844.8 1696.68  4880.6 1694.92  4951.6 1693.57  4972.5 1693.57
  4979.3 1694.21  4986.7 1693.73  4993.5 1692.99  4997.9 1691.34  5000.6 1690.84
  5003.9 1691.34  5007.7 1693.01  5015.1 1693.03 5019.77 1694.03  5029.3 1695.79
  5071.8 1697.95  5092.8  1699.5  5105.1 1699.67  5108.5 1700.43  5113.8 1700.49
  5121.7 1701.47  5139.5 1702.77  5144.8 1702.77  5170.4 1704.16  5230.3 1705.74
#Mann= 3 ,-1 , 0
  4724.2      .1       0  4986.7     .07       0 5019.77      .1       0
Bank Sta=4986.7,5019.77
XS Rating Curve= 0 ,0
Exp/Cntr=0.3,0.1

Type RM Length L Ch R = 1 ,1321    ,424,424,424
BEGIN DESCRIPTION:
UNT 0097 IN HEWA 3.0
END DESCRIPTION:
XS GIS Cut Line= 2
      2740263.66     10060817.17      2740180.33      10060051.6
#Sta/Elev= 30
  4562.8 1703.57  4646.7 1701.55    4697  1699.1  4717.1 1697.58  4750.9 1696.14
  4757.4 1695.41  4837.3 1691.91  4933.8 1689.65  4958.6  1689.5  4968.6 1687.85
 4992.55  1681.6  4995.8 1678.73  4998.6 1678.23  5008.9 1679.58 5011.36 1681.57
  5018.9 1687.61  5025.3 1693.57    5039 1695.56  5116.8 1699.64  5129.6 1701.24
  5149.7 1701.24  5189.9 1703.45  5208.3 1704.56  5220.1 1705.99  5240.2 1707.09
  5290.5 1706.56  5299.7  1706.8  5304.8 1707.87  5310.6 1708.18  5332.9 1708.77
#Mann= 3 ,-1 , 0
  4562.8      .1       0 4992.55     .07       0 5011.36      .1       0
Bank Sta=4992.55,5011.36
XS Rating Curve= 0 ,0
Exp/Cntr=0.3,0.1

Type RM Length L Ch R = 1 ,897     ,245,245,245
BEGIN DESCRIPTION:
UNT 0097 IN HEWA 2.0
END DESCRIPTION:
XS GIS Cut Line= 3
      2740435.54     10060686.99      2740461.58     10060103.66
      2740180.34     10059572.43
#Sta/Elev= 30
  4358.4 1697.19  4431.7 1693.65  4491.8 1692.93  4541.8 1687.47  4571.9 1686.18
    4682 1685.91    4702  1684.9  4932.2 1681.38 4977.14 1682.04  4981.4 1679.22
 4981.93 1677.13 4983.52 1675.44  4994.8 1671.01  4997.5 1670.51  5003.4 1671.06
  5010.1 1674.67 5028.07 1675.63  5041.8 1676.76  5047.4 1679.75  5055.4 1680.26
  5063.8  1684.5  5069.4 1684.79  5091.4 1688.76  5190.1 1695.98  5283.8 1705.36
  5322.1 1706.82  5366.1  1710.8  5404.5 1711.97  5476.1 1716.72  5543.4 1716.73
#Mann= 3 ,-1 , 0
  4358.4      .1       0  4994.8     .07       0 5028.07      .1       0
Bank Sta=4983.52,5010.1
XS Rating Curve= 0 ,0
Exp/Cntr=0.3,0.1

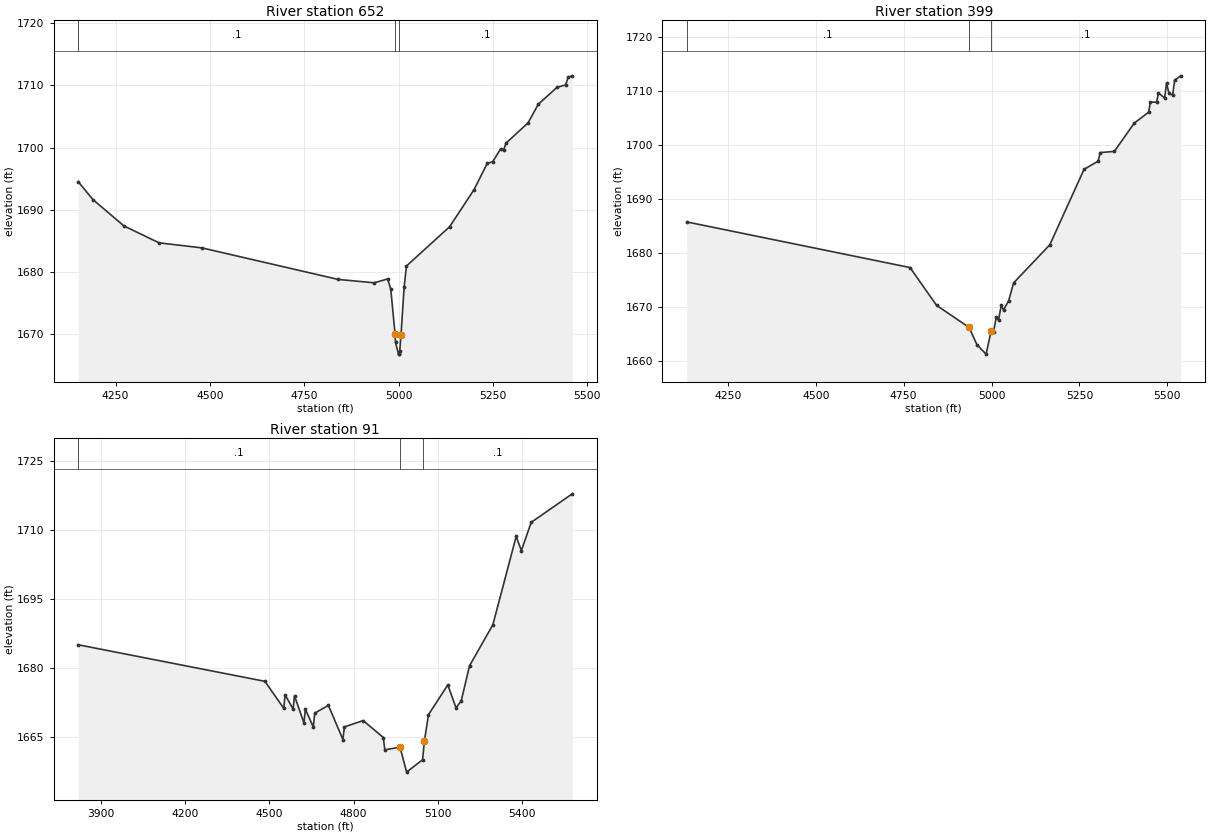
Type RM Length L Ch R = 1 ,652     ,245,245,245
BEGIN DESCRIPTION:
Mapping XS f18c5007
END DESCRIPTION:
XS GIS Cut Line= 3
      2740485.58     10060681.22       2740669.6     10059962.51
      2740325.83     10059511.09
#Sta/Elev= 30
  4151.2 1694.55  4189.9 1691.68  4272.5 1687.43  4365.4 1684.72  4478.9 1683.91
  4840.2 1678.84  4935.9  1678.3  4971.2 1678.92  4979.5 1677.28 4990.91 1670.06
  4992.1 1668.71  5000.1 1666.84  5000.6 1666.84  5003.3 1667.34  5006.6 1669.91
  5014.9 1677.61  5021.1    1681  5135.5 1687.31  5199.9 1693.24  5235.3 1697.49
  5249.8 1697.77  5270.6  1699.8  5278.9  1699.7  5285.2 1700.76  5343.3 1703.99
  5370.4 1706.98  5420.3 1709.71  5443.1 1710.09  5449.4 1711.32  5460.5 1711.55
#Mann= 3 ,-1 , 0
  4151.2      .1       0 4990.91     .07       0  5000.6      .1       0
Bank Sta=4990.91,5006.6
XS Rating Curve= 0 ,0
Exp/Cntr=0.3,0.1

Type RM Length L Ch R = 1 ,399     ,308,308,308
BEGIN DESCRIPTION:
Mapping XS 64862b35
END DESCRIPTION:
XS GIS Cut Line= 4
      2740563.83     10060552.01      2740815.57     10059742.52
      2740746.13     10059660.05      2740338.14     10059471.25
#Sta/Elev= 30
    4133 1685.73  4768.2 1677.27  4843.7 1670.26  4936.1 1666.18  4958.5 1662.97
  4984.6 1661.22  4999.1 1665.59  5005.7 1665.36  5013.4 1668.02    5020 1667.56
  5027.7 1670.27  5034.3 1669.41  5048.6  1671.1  5062.9 1674.43  5165.9  1681.5
  5263.1 1695.47  5303.4    1697  5308.9 1698.58  5349.3  1698.8  5406.1 1704.05
  5446.5 1706.05    5452 1707.94  5469.4 1707.93  5474.9 1709.62  5492.3  1708.7
  5497.8 1711.43  5504.7 1709.56  5515.2 1709.23  5520.7    1712  5538.1 1712.81
#Mann= 3 ,-1 , 0
    4133      .1       0  4936.1     .07       0  4999.1      .1       0
Bank Sta=4936.1,4999.1
XS Rating Curve= 0 ,0
Exp/Cntr=0.3,0.1

Type RM Length L Ch R = 1 ,91      ,0,0,0
BEGIN DESCRIPTION:
UNT 0097 IN HEWA 1.0
END DESCRIPTION:
XS GIS Cut Line= 4
      2740607.24     10060569.35      2740919.74     10059501.63
       2740835.1     10059380.11      2740372.11     10059191.88
#Sta/Elev= 30
  3818.7 1684.99  4483.9 1677.03  4550.8 1671.17    4556 1674.08  4584.2 1670.99
  4589.4 1673.87  4622.9 1667.98  4628.1 1670.94  4656.3 1667.09  4661.5 1670.11
  4710.2  1671.8  4761.8 1664.36    4767  1667.1  4833.9 1668.49  4905.9  1664.8
  4911.1 1662.11  4965.5 1662.69  4988.8 1657.26  5045.8 1659.96  5051.9 1663.93
  5066.7 1669.76  5135.6 1676.25    5165 1671.25  5183.6 1672.83  5213.2 1680.44
  5296.2 1689.35  5379.2 1708.58  5397.9  1705.5  5432.7 1711.65  5579.1 1717.86
#Mann= 3 ,-1 , 0
  3818.7      .1       0  4965.5     .07       0  5045.8      .1       0
Bank Sta=4965.5,5051.9
XS Rating Curve= 0 ,0
Exp/Cntr=0.3,0.1

Chan Stop Cuts=-1
Use User Specified Reach Order=0
Composite Channel Slope=5