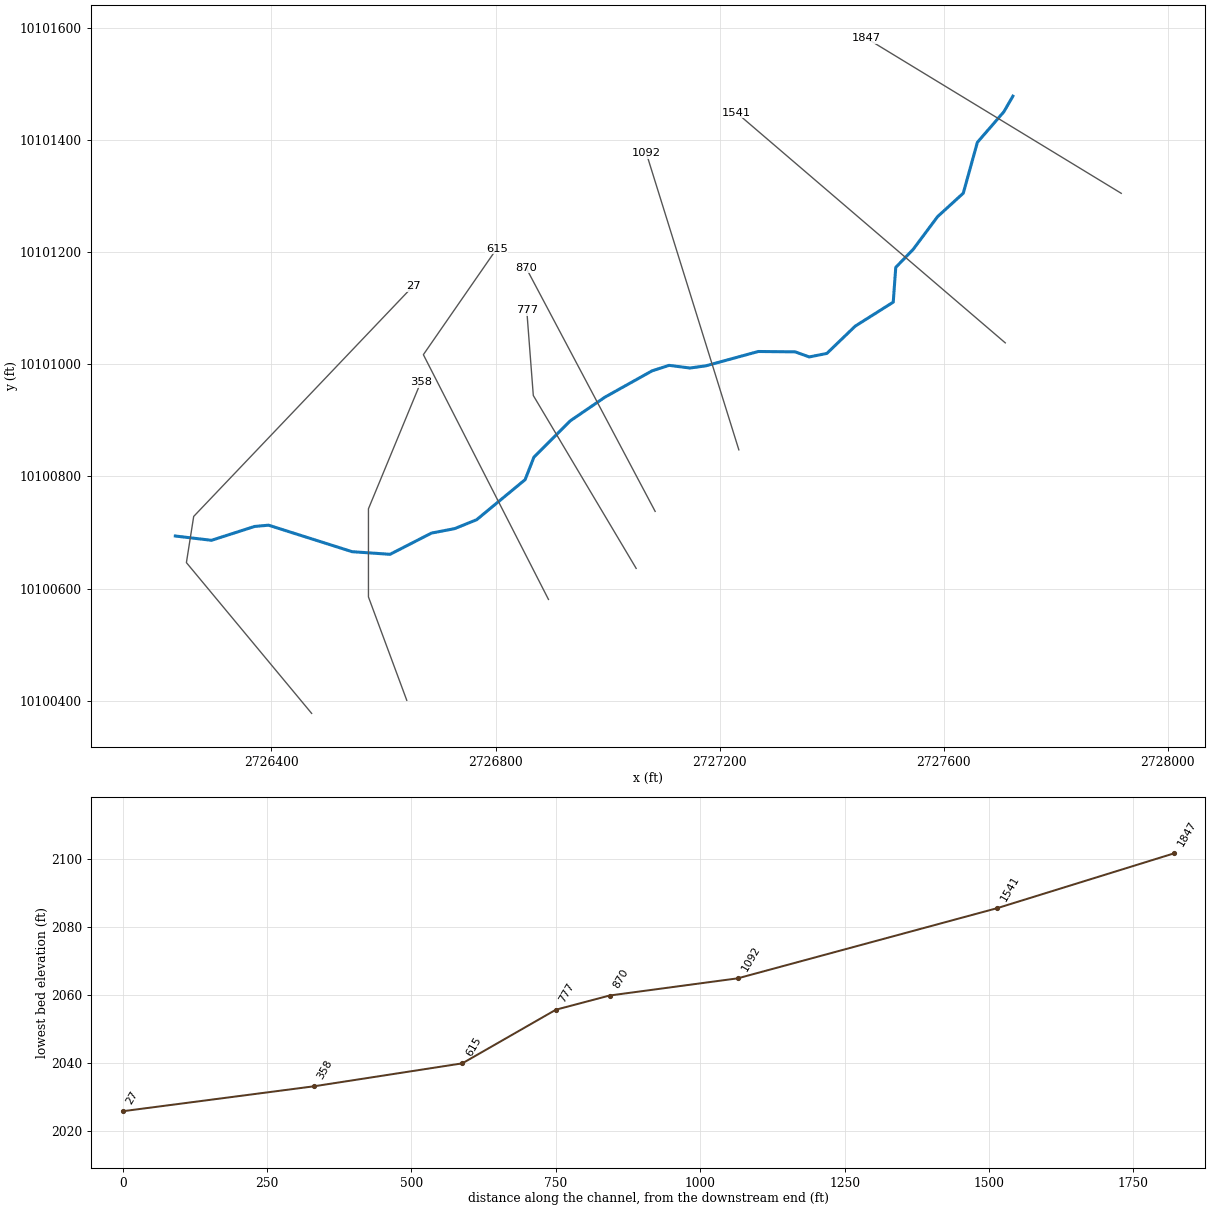
--- UNT 0098 IN HEWA.prj (project) ---

Proj Title=UNT 0098 IN HEWA Base Level Engineering
Current Plan=p01
Default Exp/Contr=0.3,0.1
English Units
Geom File=g01
Flow File=f01
Plan File=p01
BEGIN DESCRIPTION:
UNT 0098 IN HEWA
END DESCRIPTION:

--- UNT 0098 IN HEWA.p01 (plan) ---

Plan Title=Multiple Run
Short Identifier=Multiple
Geom File=g01
Flow File=f01
Subcritical Flow
K Sum by GR= 0
Std Step Tol= 0.01
Critical Tol= 0.01
Num of Std Step Trials= 20
Max Error Tol= 0.3
Flow Tol Ratio= 0.001
Split Flow NTrial= 30
Split Flow Tol= 0.02
Split Flow Ratio= 0.02
Log Output Level= 0
Friction Slope Method= 1
Unsteady Friction Slope Method= 2
Unsteady Bridges Friction Slope Method= 1
Parabolic Critical Depth
Global Vel Dist=  1 , 1 , 1
Global Log Level= 0
CheckData=True
Encroach Param= -1, 0, 0, 0
BEGIN DESCRIPTION:
Multiple Run
END DESCRIPTION:

--- UNT 0098 IN HEWA.f01 (steady flow) ---

Flow Title=Multiple
Number of Profiles=7
Profile Names=10-year,25-year,50-year,1pct_min,100-year,1pct_plu,500-year
River Rch & RM= UNT 0098 IN HEWA,Reach-1,1847
     183     242     288     254     344     465     487
Boundary for River Rch & Prof#=UNT 0098 IN HEWA,Reach-1,1
Up Type=0
Dn Type=3
Dn Slope=0.005
Boundary for River Rch & Prof#=UNT 0098 IN HEWA,Reach-1,2
Up Type=0
Dn Type=3
Dn Slope=0.005
Boundary for River Rch & Prof#=UNT 0098 IN HEWA,Reach-1,3
Up Type=0
Dn Type=3
Dn Slope=0.005
Boundary for River Rch & Prof#=UNT 0098 IN HEWA,Reach-1,4
Up Type=0
Dn Type=3
Dn Slope=0.005
Boundary for River Rch & Prof#=UNT 0098 IN HEWA,Reach-1,5
Up Type=0
Dn Type=3
Dn Slope=0.005
Boundary for River Rch & Prof#=UNT 0098 IN HEWA,Reach-1,6
Up Type=0
Dn Type=3
Dn Slope=0.005
Boundary for River Rch & Prof#=UNT 0098 IN HEWA,Reach-1,7
Up Type=0
Dn Type=3
Dn Slope=0.005

--- UNT 0098 IN HEWA.g01 (geometry) ---

Geom Title=Existing Conditions

River Reach=UNT 0098 IN HEWA,Reach-1
Reach XY= 30
      2727723.54     10101478.84      2727707.48     10101451.06
      2727660.16     10101396.40      2727635.00     10101305.66
      2727589.15     10101263.86      2727545.59     10101205.40
      2727514.49     10101173.27      2727510.00     10101111.22
      2727442.09     10101068.36      2727391.51     10101019.64
      2727360.01     10101013.39      2727334.96     10101022.47
      2727269.12     10101023.11      2727175.37     10100997.50
      2727147.15     10100993.59      2727109.83     10100998.37
      2727079.43     10100988.54      2726995.24     10100941.51
      2726933.61     10100899.41      2726868.51     10100834.31
      2726852.88     10100794.37      2726766.35     10100722.83
      2726727.14     10100706.92      2726685.69     10100698.95
      2726611.78     10100661.06      2726544.08     10100665.74
      2726394.82     10100713.07      2726369.85     10100710.76
      2726292.99     10100686.07      2726228.47     10100693.73

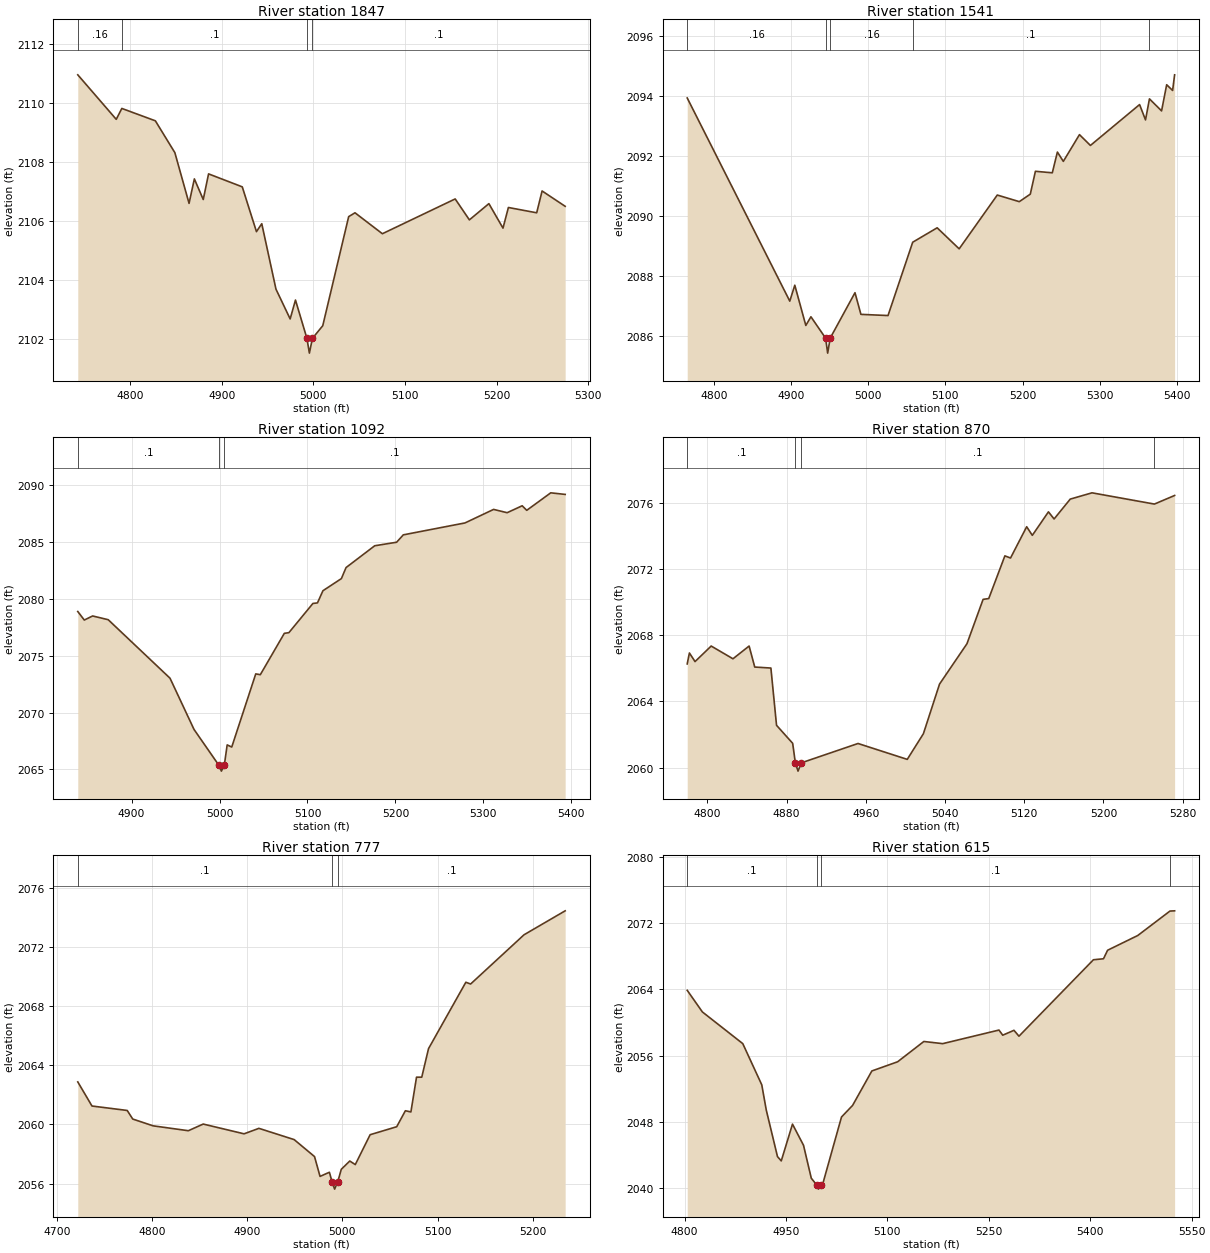
Type RM Length L Ch R = 1,1847,306,306,306
BEGIN DESCRIPTION:
UNT 0098 IN HEWA 3.0
END DESCRIPTION:
XS GIS Cut Line= 2
      2727917.01     10101305.43      2727462.38     10101582.11
#Sta/Elev= 30
  4742.7 2110.96  4784.7 2109.45  4790.8 2109.82  4827.4 2109.40  4848.7 2108.32
  4864.2 2106.60  4870.0 2107.43  4879.7 2106.73  4885.5 2107.60  4922.3 2107.16
  4937.8 2105.64  4943.6 2105.91  4959.1 2103.69  4974.6 2102.68  4980.4 2103.32
  4992.9 2102.02  4995.6 2101.52  4998.9 2102.02  5010.2 2102.45  5038.5 2106.15
  5045.4 2106.28  5075.3 2105.57  5154.8 2106.75  5170.3 2106.04  5191.6 2106.59
  5207.0 2105.76  5212.9 2106.46  5243.8 2106.28  5249.7 2107.02  5274.9 2106.50
#Mann=4,-1,0
  4742.7    0.16       0  4790.8     0.1       0  4992.9    0.07       0
  4998.9     0.1       0
Bank Sta=4992.9,4998.9
Exp/Cntr=0.3,0.1

Type RM Length L Ch R = 1,1541,449,449,449
BEGIN DESCRIPTION:
Mapping XS 41247b92
END DESCRIPTION:
XS GIS Cut Line= 2
      2727709.96     10101038.52      2727230.23     10101449.35
#Sta/Elev= 30
  4765.4 2093.93  4898.3 2087.17  4904.8 2087.70  4919.1 2086.36  4925.7 2086.65
  4944.7 2085.94  4947.4 2085.44  4950.7 2085.94  4982.8 2087.45  4990.5 2086.73
  5025.6 2086.69  5057.6 2089.13  5089.3 2089.61  5117.8 2088.91  5167.2 2090.70
  5195.7 2090.48  5210.0 2090.73  5216.6 2091.49  5238.5 2091.44  5245.1 2092.13
  5252.8 2091.82  5273.7 2092.71  5287.9 2092.35  5351.6 2093.71  5359.3 2093.20
  5364.4 2093.90  5380.1 2093.50  5386.7 2094.37  5394.4 2094.18  5397.0 2094.70
#Mann=5,-1,0
  4765.4    0.16       0  4944.7    0.07       0  4950.7    0.16       0
  5057.6     0.1       0  5364.4    0.16       0
Bank Sta=4944.7,4950.7
Exp/Cntr=0.3,0.1

Type RM Length L Ch R = 1,1092,222,222,222
BEGIN DESCRIPTION:
Mapping XS c968b5ef
END DESCRIPTION:
XS GIS Cut Line= 2
      2727234.38     10100847.56      2727069.32     10101376.72
#Sta/Elev= 30
  4838.8 2078.89  4846.2 2078.14  4855.7 2078.50  4873.4 2078.17  4943.7 2073.02
  4971.0 2068.51  4999.4 2065.34  5002.1 2064.84  5005.4 2065.34  5008.7 2067.15
  5013.9 2066.96  5041.2 2073.40  5046.4 2073.33  5073.7 2076.97  5078.9 2077.03
  5106.2 2079.60  5111.4 2079.65  5117.6 2080.72  5138.6 2081.79  5143.9 2082.76
  5176.5 2084.68  5201.4 2084.99  5209.0 2085.64  5279.2 2086.69  5311.7 2087.88
  5327.1 2087.59  5344.2 2088.20  5349.4 2087.80  5376.7 2089.34  5393.1 2089.20
#Mann=3,-1,0
  4838.8     0.1       0  4999.4    0.07       0  5005.4     0.1       0
Bank Sta=4999.4,5005.4
Exp/Cntr=0.3,0.1

Type RM Length L Ch R = 1,870,93,93,93
BEGIN DESCRIPTION:
Mapping XS 9eb9f416
END DESCRIPTION:
XS GIS Cut Line= 2
      2727084.99     10100737.69      2726854.52     10101172.60
#Sta/Elev= 30
  4779.7 2066.27  4781.9 2066.93  4787.6 2066.41  4803.9 2067.35  4825.9 2066.58
  4842.2 2067.35  4847.9 2066.08  4864.2 2066.02  4869.9 2062.56  4886.2 2061.47
  4888.9 2060.29  4891.6 2059.79  4894.9 2060.29  4952.2 2061.46  5001.9 2060.50
  5018.2 2062.05  5034.5 2065.05  5062.2 2067.49  5078.5 2070.17  5084.2 2070.22
  5100.5 2072.80  5106.2 2072.67  5122.5 2074.56  5128.2 2074.04  5144.5 2075.46
  5150.2 2075.03  5166.5 2076.23  5188.5 2076.61  5251.5 2075.93  5271.9 2076.45
#Mann=4,-1,0
  4779.7     0.1       0  4888.9    0.07       0  4894.9     0.1       0
  5251.5    0.16       0
Bank Sta=4888.9,4894.9
Exp/Cntr=0.3,0.1

Type RM Length L Ch R = 1,777,162,162,162
BEGIN DESCRIPTION:
Mapping XS 65a31c02
END DESCRIPTION:
XS GIS Cut Line= 3
      2727051.07     10100635.95      2726867.49     10100944.52
      2726855.78     10101096.82
#Sta/Elev= 30
  4722.1 2062.87  4737.0 2061.24  4774.0 2060.94  4779.8 2060.36  4801.2 2059.90
  4838.2 2059.57  4853.8 2060.02  4896.7 2059.36  4912.3 2059.73  4949.3 2058.97
  4970.7 2057.82  4976.5 2056.48  4986.3 2056.76  4989.1 2056.12  4991.8 2055.62
  4995.1 2056.12  4998.8 2056.96  5007.7 2057.52  5013.5 2057.28  5029.1 2059.30
  5057.0 2059.84  5066.1 2060.92  5071.9 2060.84  5077.8 2063.19  5083.3 2063.19
  5090.4 2065.12  5129.6 2069.61  5134.6 2069.49  5190.7 2072.82  5233.9 2074.44
#Mann=3,-1,0
  4722.1     0.1       0  4989.1    0.07       0  4995.1     0.1       0
Bank Sta=4989.1,4995.1
Exp/Cntr=0.3,0.1

Type RM Length L Ch R = 1,615,257,257,257
BEGIN DESCRIPTION:
UNT 0098 IN HEWA 2.0
END DESCRIPTION:
XS GIS Cut Line= 3
      2726894.55     10100580.55      2726671.25     10101017.45
      2726802.31     10101206.75
#Sta/Elev= 30
  4803.9 2063.88  4826.3 2061.27  4886.1 2057.44  4914.2 2052.46  4920.8 2049.43
  4937.4 2043.80  4943.0 2043.28  4959.6 2047.72  4975.9 2045.17  4987.4 2041.19
  4995.4 2040.37  4998.1 2039.87  5001.4 2040.37  5004.0 2040.39  5032.1 2048.58
  5048.5 2049.98  5077.0 2054.14  5115.1 2055.25  5153.9 2057.70  5181.8 2057.44
  5265.0 2059.08  5270.6 2058.46  5287.2 2059.05  5294.6 2058.34  5404.7 2067.57
  5419.6 2067.69  5425.7 2068.72  5470.3 2070.50  5517.9 2073.45  5524.8 2073.48
#Mann=4,-1,0
  4803.9     0.1       0  4995.4    0.07       0  5001.4     0.1       0
  5517.9    0.16       0
Bank Sta=4995.4,5001.4
Exp/Cntr=0.3,0.1

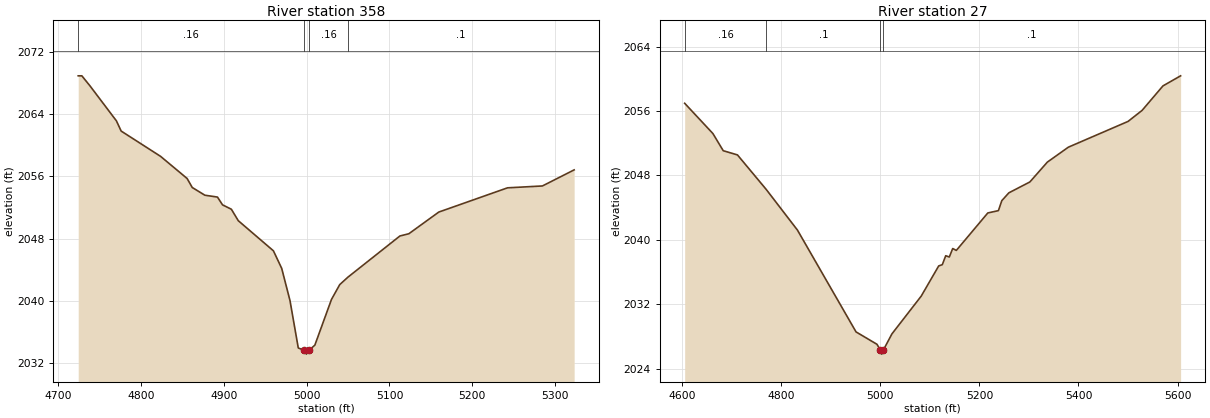
Type RM Length L Ch R = 1,358,331,331,331
BEGIN DESCRIPTION:
Mapping XS 8303ae8a
END DESCRIPTION:
XS GIS Cut Line= 4
      2726641.58     10100400.49      2726573.21     10100584.98
      2726573.21     10100742.31      2726666.53     10100968.00
#Sta/Elev= 30
  4724.5 2068.96  4728.9 2068.96  4738.6 2067.68  4770.6 2063.16  4776.3 2061.85
  4823.9 2058.59  4855.9 2055.74  4862.1 2054.58  4877.3 2053.59  4892.5 2053.35
  4898.6 2052.35  4909.3 2051.78  4917.6 2050.31  4960.0 2046.43  4970.0 2044.17
  4980.0 2040.02  4990.0 2033.92  4997.0 2033.63  4999.8 2033.13  5003.0 2033.63
  5010.0 2034.29  5030.0 2040.16  5040.0 2042.08  5049.9 2043.04  5112.6 2048.34
  5123.4 2048.63  5159.5 2051.42  5242.4 2054.54  5284.5 2054.78  5322.8 2056.85
#Mann=4,-1,0
  4724.5    0.16       0  4997.0    0.07       0  5003.0    0.16       0
  5049.9     0.1       0
Bank Sta=4997,5003
Exp/Cntr=0.3,0.1

Type RM Length L Ch R = 1,27,0,0,0
BEGIN DESCRIPTION:
UNT 0098 IN HEWA 1.0
END DESCRIPTION:
XS GIS Cut Line= 4
      2726471.78     10100377.13      2726248.25     10100646.25
      2726261.27     10100728.71      2726652.68     10101139.59
#Sta/Elev= 30
  4605.3 2056.96  4662.3 2053.20  4683.1 2051.07  4711.8 2050.55  4769.9 2046.26
  4832.9 2041.21  4951.1 2028.57  4993.4 2027.03  5000.2 2026.31  5003.0 2025.81
  5006.2 2026.31  5023.5 2028.32  5082.7 2033.02  5117.9 2036.76  5125.2 2036.92
  5132.1 2038.03  5139.3 2037.87  5146.2 2038.92  5153.5 2038.69  5217.0 2043.34
  5238.4 2043.63  5245.3 2044.87  5259.5 2045.84  5301.9 2047.19  5337.1 2049.65
  5379.6 2051.51  5500.1 2054.71  5528.4 2056.08  5570.5 2059.12  5606.1 2060.37
#Mann=4,-1,0
  4605.3    0.16       0  4769.9     0.1       0  5000.2    0.07       0
  5006.2     0.1       0
Bank Sta=5000.2,5006.2
Exp/Cntr=0.3,0.1

Chan Stop Cuts=-1