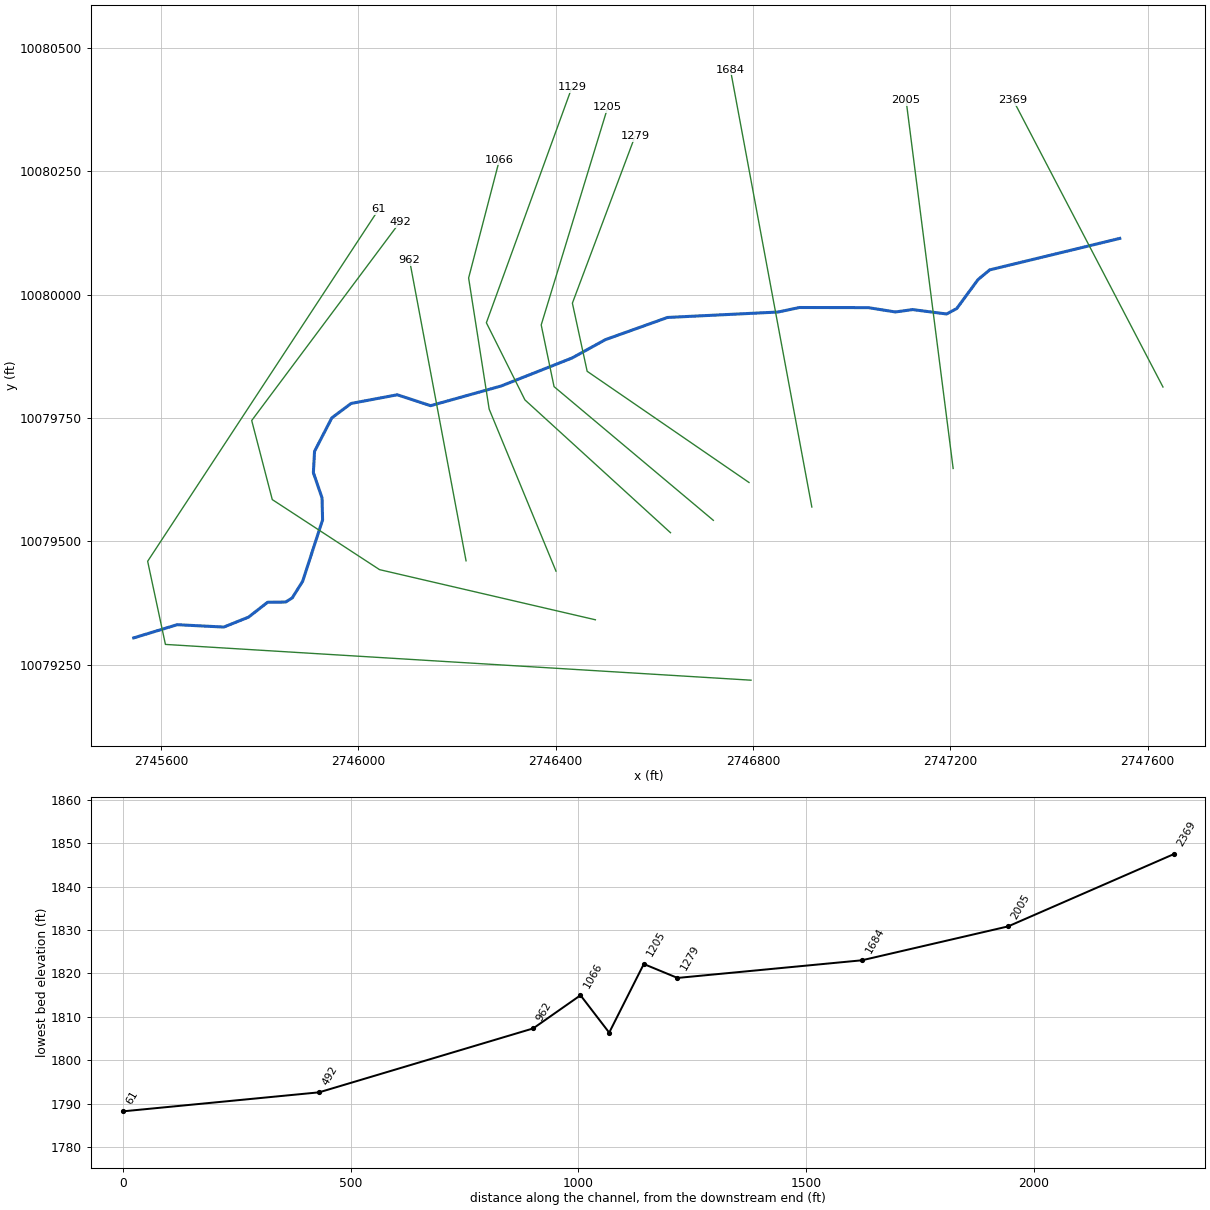
--- UNT 0099 IN HEWA.prj (project) ---

Proj Title=UNT 0099 IN HEWA Base Level Engineering
Current Plan=p01
Default Exp/Contr=0.3,0.1
English Units
Geom File=g01
Flow File=f01
Plan File=p01
BEGIN DESCRIPTION:
UNT 0099 IN HEWA
END DESCRIPTION:

--- UNT 0099 IN HEWA.p01 (plan) ---

Plan Title=Multiple Run
Short Identifier=Multiple
Geom File=g01
Flow File=f01
Subcritical Flow
K Sum by GR= 0
Std Step Tol= 0.01
Critical Tol= 0.01
Num of Std Step Trials= 20
Max Error Tol= 0.3
Flow Tol Ratio= 0.001
Split Flow NTrial= 30
Split Flow Tol= 0.02
Split Flow Ratio= 0.02
Log Output Level= 0
Friction Slope Method= 1
Unsteady Friction Slope Method= 2
Unsteady Bridges Friction Slope Method= 1
Parabolic Critical Depth
Global Vel Dist=  1 , 1 , 1
Global Log Level= 0
CheckData=True
Encroach Param= -1, 0, 0, 0
BEGIN DESCRIPTION:
Multiple Run
END DESCRIPTION:

--- UNT 0099 IN HEWA.f01 (steady flow) ---

Flow Title=Multiple
Number of Profiles=7
Profile Names=10-year,25-year,50-year,1pct_min,100-year,1pct_plu,500-year
River Rch & RM= UNT 0099 IN HEWA,Reach-1,2369
     258     348     421     376     508     687     739
Boundary for River Rch & Prof#=UNT 0099 IN HEWA,Reach-1,1
Up Type=0
Dn Type=3
Dn Slope=0.005
Boundary for River Rch & Prof#=UNT 0099 IN HEWA,Reach-1,2
Up Type=0
Dn Type=3
Dn Slope=0.005
Boundary for River Rch & Prof#=UNT 0099 IN HEWA,Reach-1,3
Up Type=0
Dn Type=3
Dn Slope=0.005
Boundary for River Rch & Prof#=UNT 0099 IN HEWA,Reach-1,4
Up Type=0
Dn Type=3
Dn Slope=0.005
Boundary for River Rch & Prof#=UNT 0099 IN HEWA,Reach-1,5
Up Type=0
Dn Type=3
Dn Slope=0.005
Boundary for River Rch & Prof#=UNT 0099 IN HEWA,Reach-1,6
Up Type=0
Dn Type=3
Dn Slope=0.005
Boundary for River Rch & Prof#=UNT 0099 IN HEWA,Reach-1,7
Up Type=0
Dn Type=3
Dn Slope=0.005

--- UNT 0099 IN HEWA.g01 (geometry) ---

Geom Title=Existing Conditions

River Reach=UNT 0099 IN HEWA,Reach-1
Reach XY= 30
      2747543.47     10080113.73      2747279.92     10080049.98
      2747256.06     10080030.21      2747213.08     10079971.72
      2747192.43     10079960.59      2747123.62     10079969.54
      2747088.59     10079964.71      2747033.67     10079973.47
      2746894.10     10079973.74      2746850.97     10079964.59
      2746626.62     10079953.56      2746500.60     10079908.55
      2746433.50     10079871.58      2746289.59     10079814.77
      2746146.47     10079774.86      2746078.91     10079796.93
      2745985.42     10079779.41      2745946.29     10079750.20
      2745911.25     10079682.44      2745908.86     10079639.16
      2745926.41     10079588.15      2745927.53     10079543.54
      2745887.06     10079418.97      2745865.93     10079385.42
      2745852.59     10079377.10      2745816.11     10079376.68
      2745777.43     10079346.48      2745727.31     10079326.40
      2745632.76     10079331.22      2745544.71     10079304.45

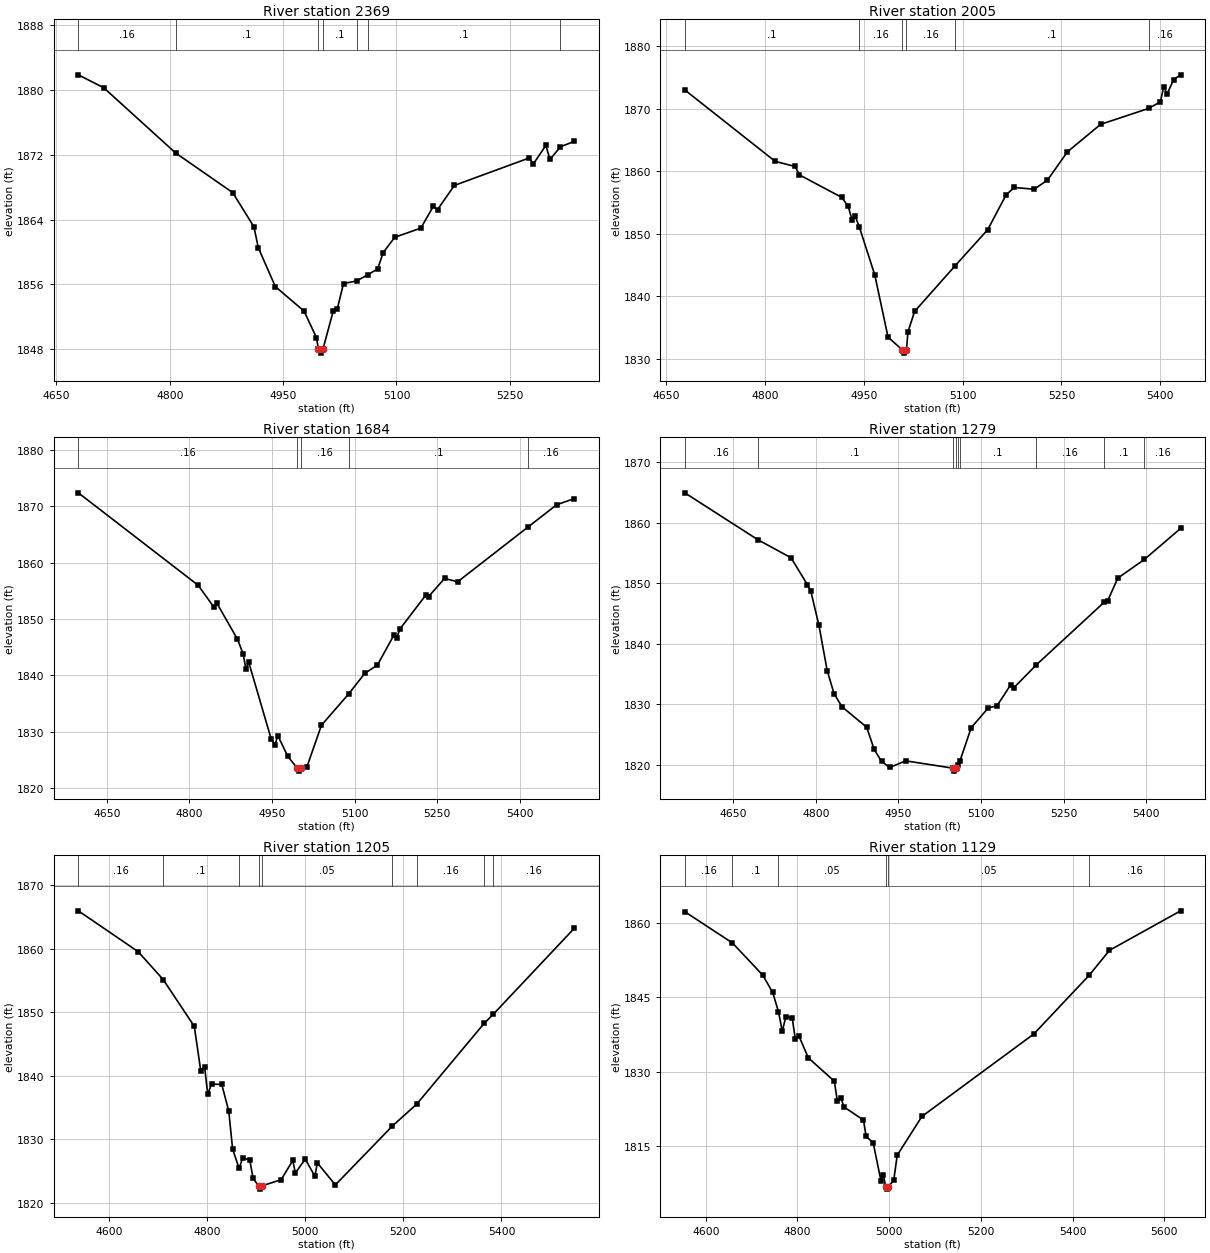
Type RM Length L Ch R = 1,2369,364,364,364
BEGIN DESCRIPTION:
UNT 0099 IN HEWA 5.0
END DESCRIPTION:
XS GIS Cut Line= 2
      2747631.06     10079812.67      2747327.27     10080394.21
#Sta/Elev= 30
  4679.0 1881.84  4712.7 1880.24  4807.6 1872.22  4883.3 1867.32  4911.4 1863.10
  4917.1 1860.54  4939.7 1855.74  4977.7 1852.72  4994.1 1849.45  4996.7 1848.04
  4999.5 1847.54  5002.7 1848.04  5016.2 1852.69  5021.8 1853.04  5029.9 1856.12
  5047.1 1856.43  5061.9 1857.19  5075.1 1857.92  5082.4 1859.93  5097.6 1861.81
  5132.2 1862.95  5148.7 1865.62  5154.3 1865.23  5176.6 1868.21  5275.5 1871.59
  5281.2 1870.87  5297.6 1873.13  5303.2 1871.42  5316.9 1872.97  5335.1 1873.63
#Mann=7,-1,0
  4679.0    0.16       0  4807.6     0.1       0  4996.7    0.07       0
  5002.7     0.1       0  5047.1    0.16       0  5061.9     0.1       0
  5316.9    0.16       0
Bank Sta=4996.7,5002.7
Exp/Cntr=0.3,0.1

Type RM Length L Ch R = 1,2005,321,321,321
BEGIN DESCRIPTION:
UNT 0099 IN HEWA 4.0
END DESCRIPTION:
XS GIS Cut Line= 2
      2747205.72     10079647.69      2747110.24     10080394.21
#Sta/Elev= 30
  4678.4 1872.98  4815.6 1861.55  4845.8 1860.73  4852.3 1859.39  4916.4 1855.80
  4926.4 1854.36  4932.1 1852.23  4937.1 1852.75  4943.2 1851.09  4966.8 1843.36
  4986.9 1833.42  5008.8 1831.36  5011.6 1830.86  5014.8 1831.36  5017.2 1834.29
  5027.3 1837.55  5087.9 1844.74  5138.2 1850.62  5166.2 1856.21  5178.5 1857.37
  5208.7 1857.09  5228.9 1858.55  5259.1 1863.07  5309.5 1867.47  5382.6 1870.03
  5400.3 1871.08  5405.4 1873.51  5410.5 1872.33  5420.4 1874.65  5431.0 1875.40
#Mann=6,-1,0
  4678.4     0.1       0  4943.2    0.16       0  5008.8    0.07       0
  5014.8    0.16       0  5087.9     0.1       0  5382.6    0.16       0
Bank Sta=5008.8,5014.8
Exp/Cntr=0.3,0.1

Type RM Length L Ch R = 1,1684,405,405,405
BEGIN DESCRIPTION:
UNT 0099 IN HEWA 3.0
END DESCRIPTION:
XS GIS Cut Line= 2
      2746919.26     10079569.58      2746754.32     10080455.05
#Sta/Elev= 30
  4598.3 1872.38  4816.1 1855.98  4845.0 1852.05  4850.1 1852.79  4887.3 1846.44
  4897.5 1843.88  4902.8 1841.13  4907.9 1842.33  4948.4 1828.81  4955.5 1827.69
  4960.6 1829.35  4978.9 1825.64  4996.2 1823.54  4999.0 1823.04  5002.2 1823.54
  5013.4 1823.75  5039.9 1831.17  5089.3 1836.72  5118.8 1840.39  5141.6 1841.84
  5171.6 1847.16  5176.6 1846.59  5182.3 1848.21  5229.4 1854.23  5234.5 1853.98
  5263.7 1857.21  5287.2 1856.60  5415.0 1866.30  5467.1 1870.26  5499.0 1871.35
#Mann=5,-1,0
  4598.3    0.16       0  4996.2    0.07       0  5002.2    0.16       0
  5089.3     0.1       0  5415.0    0.16       0
Bank Sta=4996.2,5002.2
Exp/Cntr=0.3,0.1

Type RM Length L Ch R = 1,1279,74,74,74
BEGIN DESCRIPTION:
Mapping XS dc481c50
END DESCRIPTION:
XS GIS Cut Line= 4
      2746791.95     10079619.27      2746463.85     10079844.52
      2746433.90     10079982.54      2746560.83     10080320.58
#Sta/Elev= 30
  4562.0 1864.97  4694.3 1857.24  4754.8 1854.24  4784.6 1849.80  4790.7 1848.74
  4805.6 1843.06  4820.5 1835.60  4833.1 1831.75  4847.5 1829.60  4892.2 1826.23
  4905.9 1822.56  4919.2 1820.58  4934.1 1819.57  4963.0 1820.67  5048.1 1819.47
  5050.9 1818.97  5054.1 1819.47  5057.9 1819.92  5061.5 1820.62  5082.0 1826.14
  5113.2 1829.44  5128.8 1829.75  5153.7 1833.24  5159.1 1832.72  5200.6 1836.56
  5323.1 1846.85  5329.9 1847.14  5348.2 1850.87  5396.4 1853.95  5462.3 1859.09
#Mann=9,-1,0
  4562.0    0.16       0  4694.3     0.1       0  5048.1    0.07       0
  5054.1     0.1       0  5057.9    0.05       0  5061.5     0.1       0
  5200.6    0.16       0  5323.1     0.1       0  5396.4    0.16       0
Bank Sta=5048.1,5054.1
Exp/Cntr=0.3,0.1

Type RM Length L Ch R = 1,1205,76,76,76
BEGIN DESCRIPTION:
Mapping XS fc2644f4
END DESCRIPTION:
XS GIS Cut Line= 4
      2746719.63     10079542.62      2746396.73     10079813.45
      2746370.69     10079938.45      2746505.73     10080379.93
#Sta/Elev= 30
  4537.4 1865.98  4659.4 1859.55  4710.3 1855.17  4773.8 1847.80  4786.9 1840.84
  4794.7 1841.44  4801.2 1837.15  4809.0 1838.71  4829.8 1838.66  4844.1 1834.45
  4851.9 1828.49  4865.1 1825.45  4872.7 1827.13  4887.0 1826.75  4893.6 1823.89
  4904.9 1822.68  4907.6 1822.18  4910.9 1822.68  4950.8 1823.66  4974.6 1826.69
  4979.8 1824.72  5000.0 1826.90  5019.6 1824.21  5024.7 1826.31  5061.3 1822.84
  5177.2 1832.08  5227.4 1835.57  5364.5 1848.25  5383.7 1849.73  5548.2 1863.21
#Mann=9,-1,0
  4537.4    0.16       0  4710.3     0.1       0  4865.1    0.05       0
  4904.9    0.04       0  4910.9    0.05       0  5177.2     0.1       0
  5227.4    0.16       0  5364.5     0.1       0  5383.7    0.16       0
Bank Sta=4904.9,4910.9
Exp/Cntr=0.3,0.1

Type RM Length L Ch R = 1,1129,63,63,63
BEGIN DESCRIPTION:
UNT 0099 IN HEWA 2.0
END DESCRIPTION:
XS GIS Cut Line= 4
      2746632.78     10079517.54      2746337.67     10079786.61
      2746259.54     10079942.86      2746432.85     10080419.47
#Sta/Elev= 30
  4554.3 1862.22  4658.3 1855.91  4724.3 1849.44  4745.9 1845.96  4758.5 1842.10
  4766.9 1838.13  4774.3 1840.95  4788.5 1840.88  4795.3 1836.53  4802.7 1837.28
  4823.6 1832.79  4880.4 1828.08  4887.1 1824.02  4894.6 1824.72  4901.3 1822.90
  4943.9 1820.26  4949.7 1816.95  4965.1 1815.68  4981.9 1808.08  4987.5 1809.13
  4992.2 1806.85  4994.9 1806.35  4998.2 1806.85  5009.9 1808.12  5017.5 1813.18
  5071.4 1820.99  5315.5 1837.60  5435.8 1849.38  5480.4 1854.44  5635.5 1862.39
#Mann=6,-1,0
  4554.3    0.16       0  4658.3     0.1       0  4758.5    0.05       0
  4992.2    0.04       0  4998.2    0.05       0  5435.8    0.16       0
Bank Sta=4992.2,4998.2
Exp/Cntr=0.3,0.1

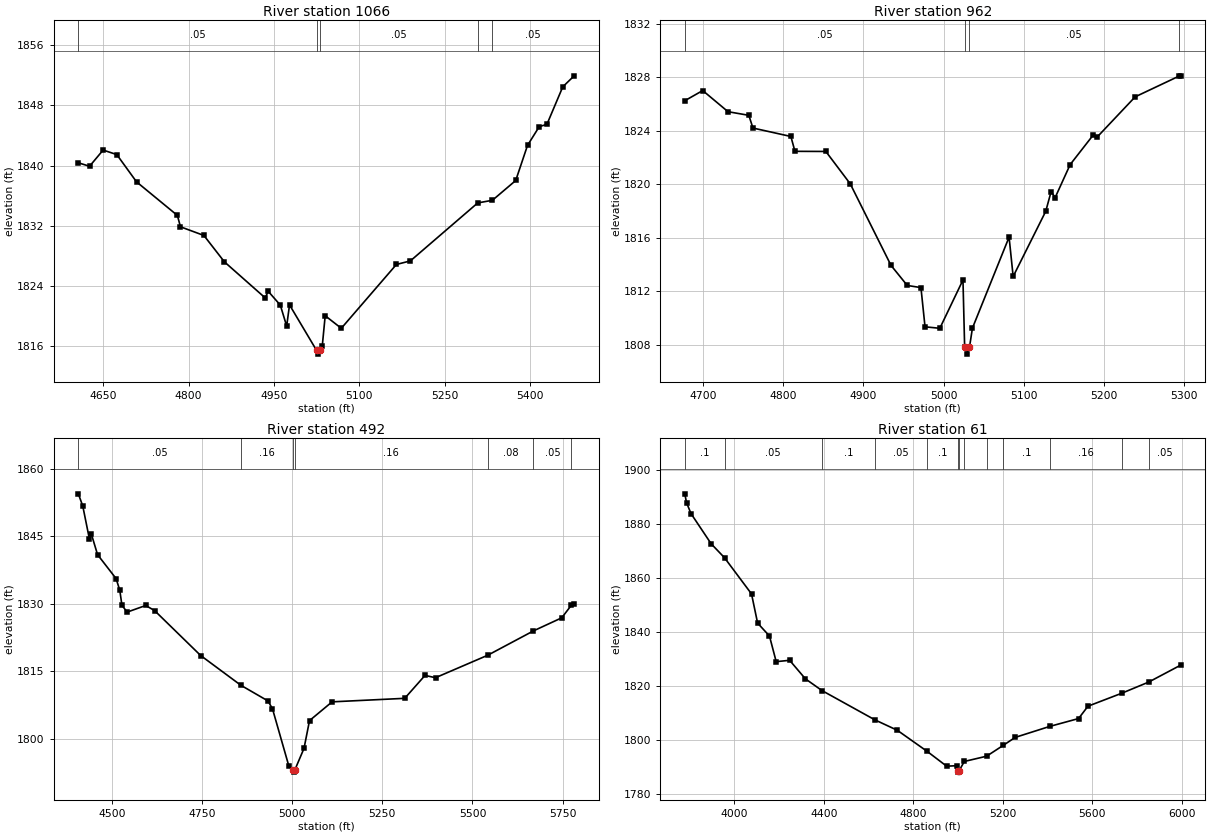
Type RM Length L Ch R = 1,1066,104,104,104
BEGIN DESCRIPTION:
Mapping XS e069da89
END DESCRIPTION:
XS GIS Cut Line= 4
      2746400.65     10079439.71      2746265.22     10079767.87
      2746223.55     10080033.50      2746286.05     10080273.09
#Sta/Elev= 30
  4606.1 1840.38  4625.8 1839.92  4649.7 1842.07  4673.7 1841.47  4708.4 1837.85
  4780.2 1833.39  4785.6 1831.88  4826.8 1830.73  4862.8 1827.23  4934.5 1822.44
  4939.9 1823.31  4961.1 1821.48  4972.3 1818.69  4977.3 1821.51  5024.8 1815.47
  5027.5 1814.97  5030.8 1815.47  5034.9 1816.08  5040.0 1820.07  5068.3 1818.40
  5165.2 1826.88  5189.7 1827.35  5308.1 1835.05  5333.9 1835.40  5374.9 1838.03
  5395.6 1842.69  5416.3 1845.19  5429.7 1845.48  5457.6 1850.47  5477.6 1851.93
#Mann=5,-1,0
  4606.1    0.05       0  5024.8    0.04       0  5030.8    0.05       0
  5308.1    0.08       0  5333.9    0.05       0
Bank Sta=5024.8,5030.8
Exp/Cntr=0.3,0.1

Type RM Length L Ch R = 1,962,470,470,470
BEGIN DESCRIPTION:
Mapping XS 817a2c94
END DESCRIPTION:
XS GIS Cut Line= 2
      2746218.34     10079460.61      2746103.87     10080069.35
#Sta/Elev= 30
  4676.8 1826.25  4699.2 1827.01  4730.8 1825.43  4756.8 1825.16  4761.9 1824.21
  4809.3 1823.58  4814.4 1822.47  4853.0 1822.46  4883.5 1820.04  4934.4 1813.95
  4954.7 1812.45  4971.8 1812.29  4976.9 1809.36  4995.4 1809.25  5024.3 1812.86
  5026.4 1807.82  5029.2 1807.32  5032.4 1807.82  5036.1 1809.26  5081.9 1816.06
  5087.0 1813.12  5127.7 1817.99  5134.4 1819.46  5139.5 1819.02  5158.2 1821.48
  5186.9 1823.68  5192.0 1823.54  5239.4 1826.54  5293.9 1828.08  5296.2 1828.11
#Mann=4,-1,0
  4676.8    0.05       0  5026.4    0.04       0  5032.4    0.05       0
  5293.9    0.08       0
Bank Sta=5026.4,5032.4
Exp/Cntr=0.3,0.1

Type RM Length L Ch R = 1,492,431,431,431
BEGIN DESCRIPTION:
Mapping XS 689606a4
END DESCRIPTION:
XS GIS Cut Line= 5
      2746480.49     10079341.17      2746042.98     10079442.74
      2745825.54     10079584.66      2745783.87     10079744.82
      2746084.09     10080146.41
#Sta/Elev= 30
  4406.5 1854.39  4418.8 1851.68  4437.1 1844.41  4442.2 1845.57  4459.9 1840.87
  4511.2 1835.57  4521.5 1832.98  4527.5 1829.63  4542.0 1828.12  4593.4 1829.59
  4617.9 1828.47  4745.9 1818.48  4857.3 1811.88  4932.7 1808.39  4945.2 1806.64
  4990.6 1793.93  5001.3 1793.08  5004.1 1792.58  5007.3 1793.08  5032.7 1797.87
  5047.9 1804.02  5110.6 1808.19  5312.1 1808.97  5368.4 1814.06  5397.5 1813.55
  5542.4 1818.54  5669.3 1823.95  5747.7 1826.85  5774.2 1829.62  5782.2 1829.87
#Mann=7,-1,0
  4406.5    0.05       0  4857.3    0.16       0  5001.3    0.07       0
  5007.3    0.16       0  5542.4    0.08       0  5669.3    0.05       0
  5774.2    0.08       0
Bank Sta=5001.3,5007.3
Exp/Cntr=0.3,0.1

Type RM Length L Ch R = 1,61,0,0,0
BEGIN DESCRIPTION:
UNT 0099 IN HEWA 1.0
END DESCRIPTION:
XS GIS Cut Line= 4
      2746796.02     10079218.78      2745608.96     10079291.26
      2745572.93     10079459.66      2746041.67     10080173.18
#Sta/Elev= 30
  3779.1 1891.35  3786.7 1888.11  3806.7 1884.04  3896.9 1872.83  3956.5 1867.66
  4077.2 1854.25  4104.4 1843.43  4157.4 1838.64  4187.4 1829.14  4247.5 1829.64
  4317.7 1822.79  4392.0 1818.42  4628.3 1807.57  4728.4 1803.71  4862.1 1795.87
  4948.8 1790.40  4995.5 1790.57  4998.6 1788.69  5001.3 1788.19  5004.6 1788.69
  5027.8 1792.14  5127.4 1794.09  5201.8 1798.11  5255.0 1801.06  5409.7 1805.14
  5538.3 1808.05  5580.4 1812.63  5730.2 1817.40  5851.3 1821.56  5994.3 1827.84
#Mann=13,-1,0
  3779.1     0.1       0  3956.5    0.05       0  4392.0     0.1       0
  4628.3    0.05       0  4862.1     0.1       0  4998.6    0.07       0
  5004.6     0.1       0  5027.8    0.05       0  5127.4    0.16       0
  5201.8     0.1       0  5409.7    0.16       0  5730.2    0.08       0
  5851.3    0.05       0
Bank Sta=4998.6,5004.6
Exp/Cntr=0.3,0.1

Chan Stop Cuts=-1