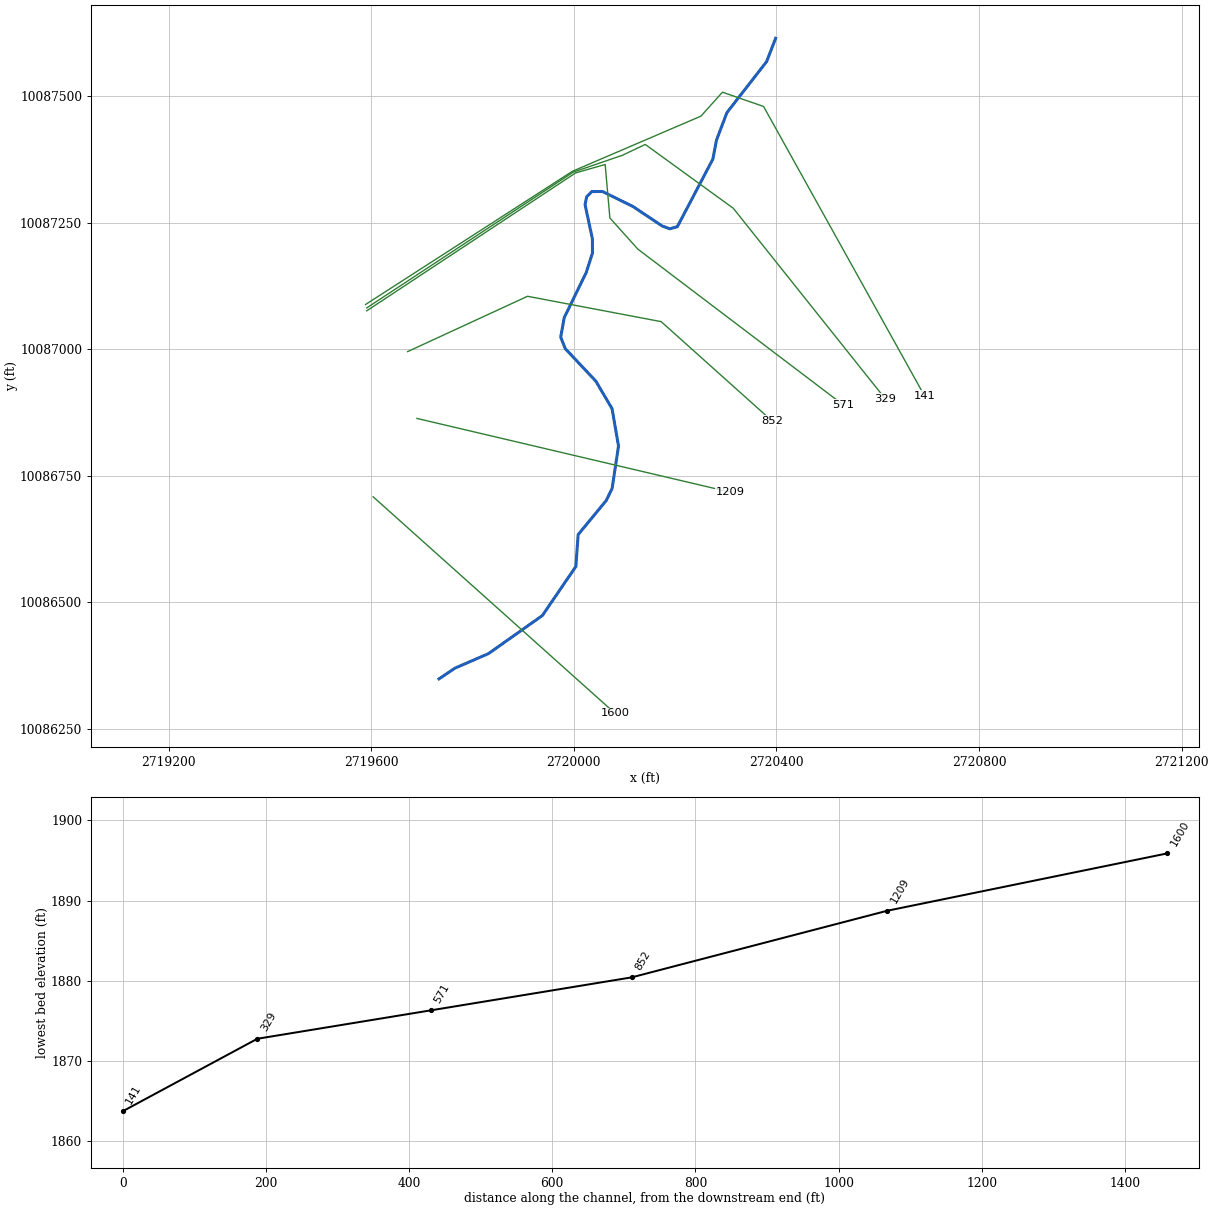
--- UNT 0100 IN HEWA.prj (project) ---

Proj Title=UNT 0100 IN HEWA Base Level Engineering
Current Plan=p01
Default Exp/Contr=0.3,0.1
English Units
Geom File=g01
Flow File=f01
Plan File=p01
Y Axis Title=Elevation
X Axis Title(PF)=Main Channel Distance
X Axis Title(XS)=Station
BEGIN DESCRIPTION:
UNT 0100 IN HEWA
END DESCRIPTION:
DSS Export Rating Curves= 0
DSS Export Rating Curve Sorted= 0
DSS Export Volume Flow Curves= 0
DXF OffsetX= 0
DXF OffsetY= 0
DXF ScaleX= 1
DXF ScaleY= 10

--- UNT 0100 IN HEWA.p01 (plan) ---

Plan Title=Multiple Run
Short Identifier=Multiple
Geom File=g01
Flow File=f01
Subcritical Flow
K Sum by GR= 0
Std Step Tol= 0.01
Critical Tol= 0.01
Num of Std Step Trials= 20
Max Error Tol= 0.3
Flow Tol Ratio= 0.001
Split Flow NTrial= 30
Split Flow Tol= 0.02
Split Flow Ratio= 0.02
Log Output Level= 0
Friction Slope Method= 1
Unsteady Friction Slope Method= 2
Unsteady Bridges Friction Slope Method= 1
Parabolic Critical Depth
Global Vel Dist=  1 , 1 , 1
Global Log Level= 0
CheckData=True
Encroach Param= -1, 0, 0, 0
BEGIN DESCRIPTION:
Multiple Run
END DESCRIPTION:

--- UNT 0100 IN HEWA.f01 (steady flow) ---

Flow Title=Multiple
Program Version=4.10
Number of Profiles= 7
Profile Names=10-year,25-year,50-year,1pct_min,100-year,1pct_plu,500-year
River Rch & RM=UNT 0100 IN HEWA,Reach-1         ,1600
     604     865    1088    1004    1357    1835    2116
Boundary for River Rch & Prof#=UNT 0100 IN HEWA,Reach-1         , 1
Up Type= 0
Dn Type= 3
Dn Slope=0.049
Boundary for River Rch & Prof#=UNT 0100 IN HEWA,Reach-1         , 2
Up Type= 0
Dn Type= 3
Dn Slope=0.049
Boundary for River Rch & Prof#=UNT 0100 IN HEWA,Reach-1         , 3
Up Type= 0
Dn Type= 3
Dn Slope=0.049
Boundary for River Rch & Prof#=UNT 0100 IN HEWA,Reach-1         , 4
Up Type= 0
Dn Type= 3
Dn Slope=0.049
Boundary for River Rch & Prof#=UNT 0100 IN HEWA,Reach-1         , 5
Up Type= 0
Dn Type= 3
Dn Slope=0.049
Boundary for River Rch & Prof#=UNT 0100 IN HEWA,Reach-1         , 6
Up Type= 0
Dn Type= 3
Dn Slope=0.049
Boundary for River Rch & Prof#=UNT 0100 IN HEWA,Reach-1         , 7
Up Type= 0
Dn Type= 3
Dn Slope=0.049
DSS Import GetInterval= 0
DSS Import GetPeak= 0
DSS Import FillOption= 0

--- UNT 0100 IN HEWA.g01 (geometry) ---

Geom Title=Existing Conditions
Program Version=4.10

River Reach=UNT 0100 IN HEWA,Reach-1
Reach XY= 30
      2719733.71     10086348.77      2719765.15     10086369.99
      2719831.17     10086398.56      2719937.88     10086473.97
      2720003.99      10086570.8      2720008.47     10086633.73
      2720063.86     10086700.93      2720075.57     10086724.97
      2720088.19     10086808.55      2720075.46     10086882.38
      2720043.53     10086936.64       2719983.2     10087000.81
      2719974.03     10087023.75      2719981.05     10087062.34
      2720024.25     10087150.83      2720036.78     10087189.53
      2720036.63     10087217.97      2720022.13     10087285.28
      2720025.26     10087300.69      2720035.49     10087311.19
      2720056.59     10087311.27       2720117.4     10087281.26
      2720173.93     10087243.36      2720189.52     10087237.63
      2720204.36     10087241.77      2720274.58     10087375.34
      2720281.57     10087412.45      2720302.19      10087466.9
      2720380.54     10087567.59      2720398.47     10087613.73

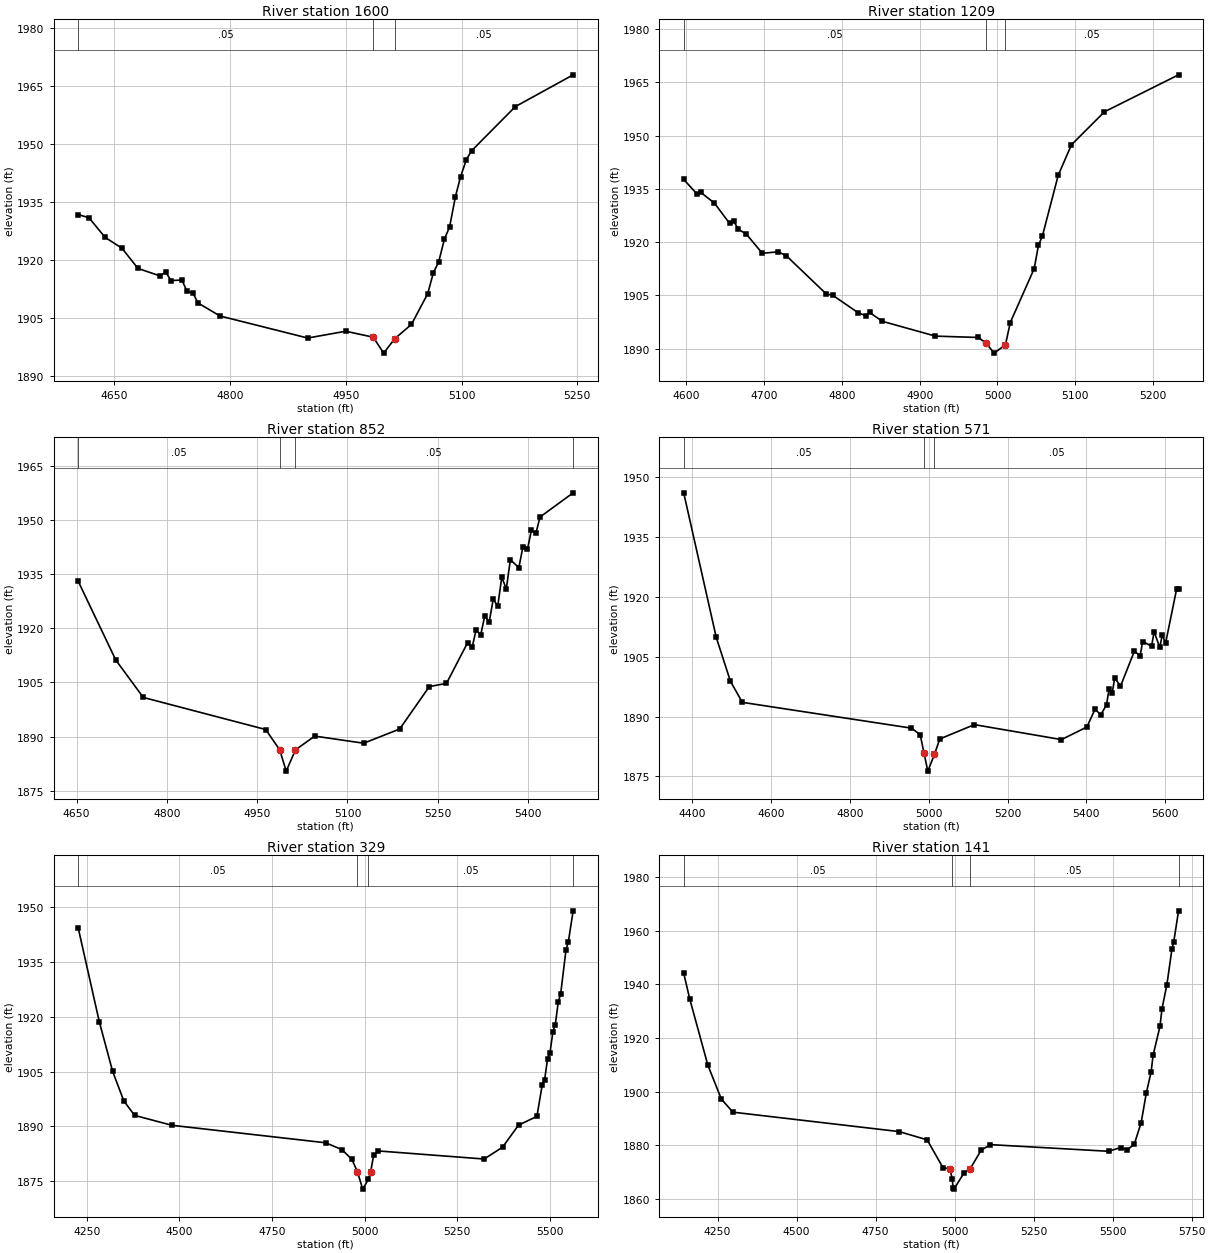
Type RM Length L Ch R = 1 ,1600    ,391,391,391
BEGIN DESCRIPTION:
UNT 0100 IN HEWA 2.0
END DESCRIPTION:
XS GIS Cut Line= 2
      2719603.62     10086708.46      2720081.42     10086280.72
#Sta/Elev= 30
  4603.3 1931.77  4617.2 1930.93  4638.1 1925.85  4659.8 1923.07  4680.7 1917.82
  4709.2 1915.89  4716.7 1916.88  4723.4 1914.67  4737.6 1914.82  4744.3 1911.85
  4751.8  1911.5  4758.5 1908.87  4786.9 1905.51  4900.6  1899.8  4949.9 1901.56
  4985.6 1900.01    4999 1895.89  5013.4 1899.62  5035.1 1903.34  5056.1 1911.27
  5063.5 1916.73  5070.3 1919.48  5077.8 1925.45  5084.5 1928.56    5092 1936.38
  5098.7 1941.55  5106.2 1946.01  5112.9 1948.27  5169.7 1959.72  5244.6 1967.95
#Mann= 3 , 0 , 0
  4603.3     .05       0  4985.6    .035       0  5013.4     .05       0
Bank Sta=4985.6,5013.4
XS Rating Curve= 0 ,0
Exp/Cntr=0.3,0.1

Type RM Length L Ch R = 1 ,1209    ,357,357,357
BEGIN DESCRIPTION:
Mapping XS 5d972f7a
END DESCRIPTION:
XS GIS Cut Line= 2
      2719690.11     10086863.17      2720308.92     10086717.57
#Sta/Elev= 30
  4596.9 1937.69  4613.4 1933.71  4618.6 1934.06  4636.3 1931.03  4655.8 1925.31
  4660.9    1926  4667.1 1923.65  4677.4 1922.26  4697.9 1916.87  4718.5 1917.28
  4728.8 1916.16  4780.1  1905.4  4788.1 1905.08  4821.2 1900.09  4830.5 1899.31
  4835.6 1900.21    4852 1897.71  4920.3 1893.53  4975.3 1893.15  4985.6 1891.53
  4995.6 1888.74  5010.2 1891.06  5016.4 1897.34  5047.2 1912.58  5052.6  1919.1
  5057.7 1921.74    5078 1938.84    5095 1947.44  5137.4 1956.73  5232.6 1967.15
#Mann= 3 , 0 , 0
  4596.9     .05       0  4985.6    .035       0  5010.2     .05       0
Bank Sta=4985.6,5010.2
XS Rating Curve= 0 ,0
Exp/Cntr=0.3,0.1

Type RM Length L Ch R = 1 ,852     ,281,281,281
BEGIN DESCRIPTION:
Mapping XS 78f7dbd5
END DESCRIPTION:
XS GIS Cut Line= 4
      2719671.87     10086995.13      2719908.51     10087104.35
      2720172.43     10087054.29      2720390.78     10086858.69
#Sta/Elev= 30
  4652.7 1932.96    4715 1911.21  4760.7 1900.84  4964.2 1891.95  4987.5 1886.31
  4998.2 1880.43 5013.64 1886.31  5045.6 1890.13    5127 1888.16  5186.8 1892.09
  5236.1 1903.85  5264.6 1904.73  5299.7 1916.01  5307.2 1914.71  5313.9 1919.56
  5321.4 1918.07  5328.1 1923.35  5335.6 1921.77  5342.3 1928.07  5349.8  1926.1
  5356.5  1934.2    5364 1930.85  5370.7 1938.97  5384.9  1936.8  5391.6 1942.55
  5399.1 1941.82  5405.8 1947.19  5413.3 1946.35    5420  1950.8  5475.1 1957.51
#Mann= 4 ,-1 , 0
  4652.7     .05       0  4987.5    .035       0 5013.64     .05       0
  5475.1     .16       0
Bank Sta=4987.5,5013.64
XS Rating Curve= 0 ,0
Exp/Cntr=0.3,0.1

Type RM Length L Ch R = 1 ,571     ,242,242,242
BEGIN DESCRIPTION:
Mapping XS a09533d4
END DESCRIPTION:
XS GIS Cut Line= 6
      2719590.95     10087075.59      2720003.48       10087348.
      2720061.82     10087364.67      2720071.19     10087258.94
       2720126.4     10087197.48      2720531.63     10086890.17
#Sta/Elev= 30
    4378 1946.11  4460.6 1909.87  4496.7 1898.83  4526.9 1893.56  4955.6  1887.1
  4978.3 1885.49  4987.9  1880.9  4997.7 1876.31 5014.55 1880.51  5028.1 1884.38
  5115.9 1887.97    5337 1884.22  5401.5 1887.38  5422.3 1891.86  5436.8 1890.41
  5451.4 1892.99  5457.7 1896.88  5465.9 1895.96  5472.2 1899.72  5486.8 1897.61
  5522.1  1906.4  5536.7 1905.22    5543 1908.81  5565.8 1907.66  5572.1 1911.27
  5586.6 1907.34  5592.9 1910.52  5601.2 1908.36  5629.1 1921.88  5634.2 1921.88
#Mann= 3 , 0 , 0
    4378     .05       0  4987.9    .035       0 5014.55     .05       0
Bank Sta=4987.9,5014.55
XS Rating Curve= 0 ,0
Exp/Cntr=0.3,0.1

Type RM Length L Ch R = 1 ,329     ,188,188,188
BEGIN DESCRIPTION:
Mapping XS 0ee670eb
END DESCRIPTION:
XS GIS Cut Line= 6
      2719591.01     10087081.36      2719998.79     10087349.57
      2720096.19      10087382.9      2720140.98     10087404.25
      2720314.94     10087278.04      2720614.53     10086902.34
#Sta/Elev= 30
  4227.1 1944.24  4283.7 1918.69  4319.7 1905.07    4350 1896.96  4379.1 1892.98
  4479.9 1890.26  4894.9 1885.47  4938.8  1883.6    4966 1880.91  4980.7 1877.52
  4995.1 1872.77  5010.1 1875.43  5016.2 1877.33  5024.7 1882.16  5037.6 1883.23
  5322.9 1881.02  5372.5 1884.25  5415.7  1890.3  5465.4 1892.71  5479.8 1901.37
  5486.2 1902.74  5494.2 1908.54  5500.6 1910.06  5508.6 1915.96    5515 1917.81
    5523 1924.09  5529.4 1926.17  5543.8  1938.3  5550.2 1940.52  5563.2 1949.03
#Mann= 4 ,-1 , 0
  4227.1     .05       0  4980.7    .035       0  5010.1     .05       0
  5563.2     .16       0
Bank Sta=4980.7,5016.2
XS Rating Curve= 0 ,0
Exp/Cntr=0.3,0.1

Type RM Length L Ch R = 1 ,141     ,0,0,0
BEGIN DESCRIPTION:
UNT 0100 IN HEWA 1.0
END DESCRIPTION:
XS GIS Cut Line= 6
       2719588.6     10087088.08      2719997.06     10087351.13
      2720250.96     10087460.07       2720293.5     10087507.38
      2720374.66     10087479.17      2720692.36     10086907.91
#Sta/Elev= 30
  4142.7 1944.24  4161.5 1934.74  4219.3 1909.87  4261.8  1897.3  4298.4 1892.41
  4824.7 1885.17  4913.1 1882.09  4963.2 1871.72  4984.9 1871.31  4992.8 1867.36
    4995 1864.23  4997.8 1863.73  5029.2 1869.66  5048.4 1871.15    5084 1878.25
  5113.4 1880.31  5487.4 1877.83  5525.1 1879.24  5546.9 1878.35  5568.6 1880.52
  5590.3 1888.51  5606.3  1899.4  5621.8 1907.43  5628.1 1913.67  5649.8 1924.38
  5656.2 1930.97  5671.5 1939.78  5687.5 1953.06  5693.3 1955.83  5708.6 1967.44
#Mann= 4 ,-1 , 0
  4142.7     .05       0  4992.8    .035       0  5048.4     .05       0
  5708.6     .16       0
Bank Sta=4984.9,5048.4
XS Rating Curve= 0 ,0
Exp/Cntr=0.3,0.1

Chan Stop Cuts=-1
Use User Specified Reach Order=0
Composite Channel Slope=5