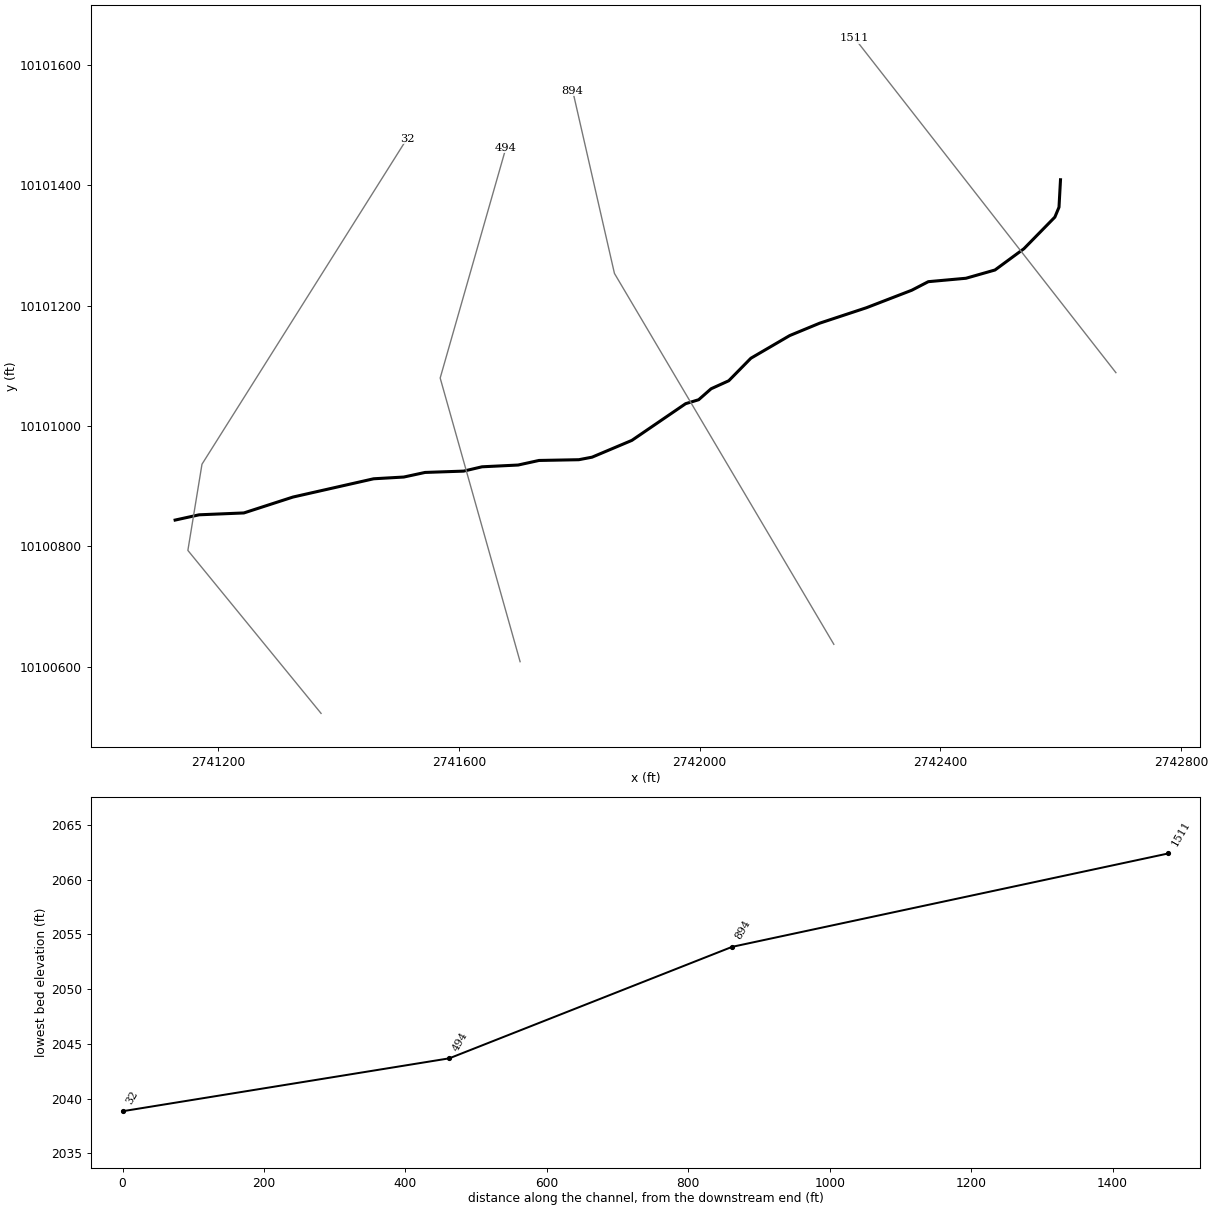
--- UNT 0101 IN HEWA.prj (project) ---

Proj Title=UNT 0101 IN HEWA Base Level Engineering
Current Plan=p01
Default Exp/Contr=0.3,0.1
English Units
Geom File=g01
Flow File=f01
Plan File=p01
BEGIN DESCRIPTION:
UNT 0101 IN HEWA
END DESCRIPTION:

--- UNT 0101 IN HEWA.p01 (plan) ---

Plan Title=Multiple Run
Short Identifier=Multiple
Geom File=g01
Flow File=f01
Subcritical Flow
K Sum by GR= 0
Std Step Tol= 0.01
Critical Tol= 0.01
Num of Std Step Trials= 20
Max Error Tol= 0.3
Flow Tol Ratio= 0.001
Split Flow NTrial= 30
Split Flow Tol= 0.02
Split Flow Ratio= 0.02
Log Output Level= 0
Friction Slope Method= 1
Unsteady Friction Slope Method= 2
Unsteady Bridges Friction Slope Method= 1
Parabolic Critical Depth
Global Vel Dist=  1 , 1 , 1
Global Log Level= 0
CheckData=True
Encroach Param= -1, 0, 0, 0
BEGIN DESCRIPTION:
Multiple Run
END DESCRIPTION:

--- UNT 0101 IN HEWA.f01 (steady flow) ---

Flow Title=Multiple
Number of Profiles=7
Profile Names=10-year,25-year,50-year,1pct_min,100-year,1pct_plu,500-year
River Rch & RM= UNT 0101 IN HEWA,Reach-1,1511
     491     689     854     778    1052    1422    1597
Boundary for River Rch & Prof#=UNT 0101 IN HEWA,Reach-1,1
Up Type=0
Dn Type=3
Dn Slope=0.005
Boundary for River Rch & Prof#=UNT 0101 IN HEWA,Reach-1,2
Up Type=0
Dn Type=3
Dn Slope=0.005
Boundary for River Rch & Prof#=UNT 0101 IN HEWA,Reach-1,3
Up Type=0
Dn Type=3
Dn Slope=0.005
Boundary for River Rch & Prof#=UNT 0101 IN HEWA,Reach-1,4
Up Type=0
Dn Type=3
Dn Slope=0.005
Boundary for River Rch & Prof#=UNT 0101 IN HEWA,Reach-1,5
Up Type=0
Dn Type=3
Dn Slope=0.005
Boundary for River Rch & Prof#=UNT 0101 IN HEWA,Reach-1,6
Up Type=0
Dn Type=3
Dn Slope=0.005
Boundary for River Rch & Prof#=UNT 0101 IN HEWA,Reach-1,7
Up Type=0
Dn Type=3
Dn Slope=0.005

--- UNT 0101 IN HEWA.g01 (geometry) ---

Geom Title=Existing Conditions

River Reach=UNT 0101 IN HEWA,Reach-1
Reach XY= 30
      2742599.76     10101409.26      2742597.25     10101363.60
      2742590.38     10101347.17      2742538.93     10101294.63
      2742490.88     10101259.30      2742442.70     10101245.58
      2742380.05     10101239.90      2742352.65     10101225.69
      2742277.28     10101196.60      2742199.62     10101170.95
      2742149.82     10101150.37      2742085.20     10101112.65
      2742048.48     10101075.26      2742019.14     10101061.94
      2741998.47     10101043.73      2741976.75     10101037.13
      2741887.46     10100976.16      2741821.31     10100948.25
      2741799.29     10100944.04      2741733.14     10100942.80
      2741698.45     10100935.20      2741638.48     10100932.27
      2741607.90     10100925.09      2741543.82     10100922.89
      2741508.50     10100915.25      2741458.37     10100912.36
      2741324.20     10100881.97      2741242.70     10100855.58
      2741168.37     10100852.49      2741128.47     10100843.73

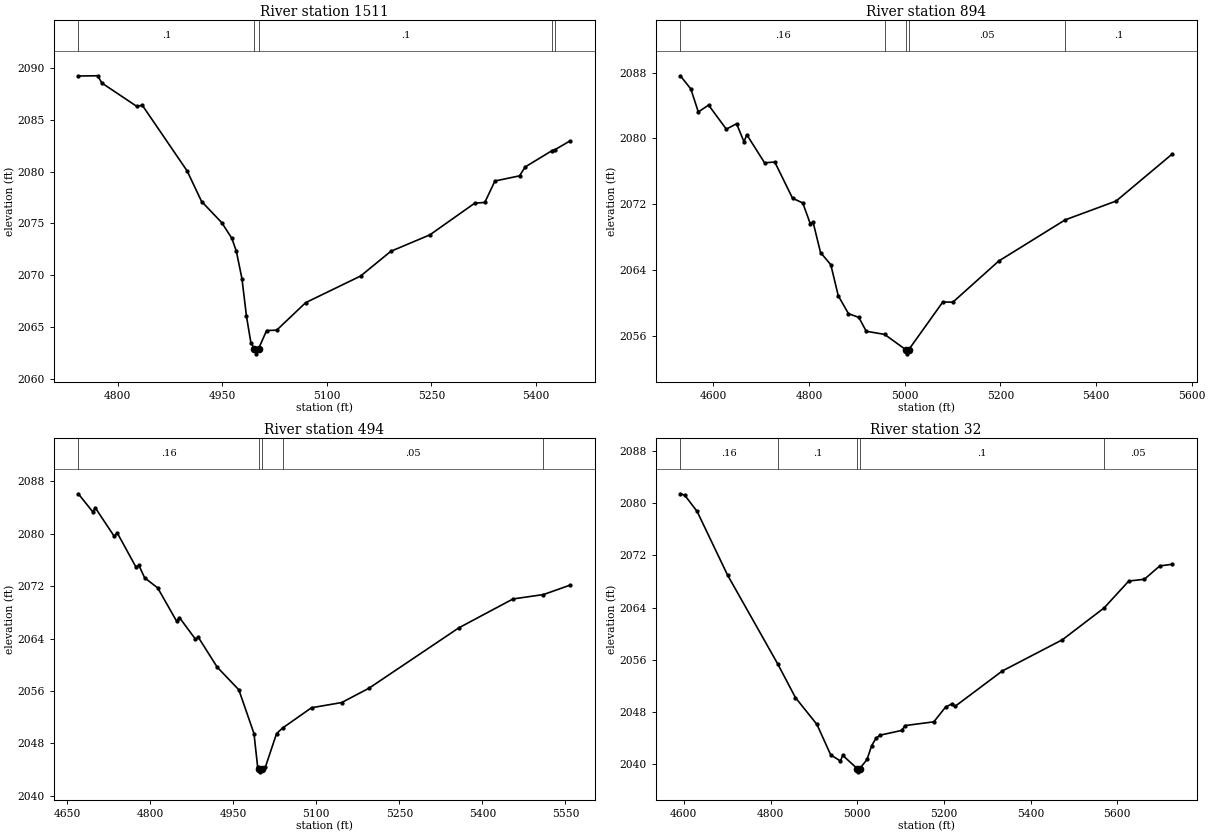
Type RM Length L Ch R = 1,1511,617,617,617
BEGIN DESCRIPTION:
UNT 0101 IN HEWA 3.0
END DESCRIPTION:
XS GIS Cut Line= 2
      2742691.82     10101088.71      2742257.79     10101644.27
#Sta/Elev= 30
  4743.8 2089.24  4771.4 2089.26  4777.8 2088.55  4827.5 2086.31  4835.6 2086.41
  4899.8 2080.07  4920.6 2077.11  4949.6 2075.06  4964.0 2073.55  4970.4 2072.31
  4978.5 2069.64  4984.9 2066.04  4991.3 2063.45  4996.3 2062.89  4999.1 2062.39
  5002.3 2062.89  5013.8 2064.64  5028.3 2064.68  5069.9 2067.34  5148.6 2069.91
  5192.0 2072.30  5248.0 2073.89  5312.3 2076.95  5326.7 2077.02  5341.2 2079.09
  5376.5 2079.59  5384.6 2080.45  5423.2 2082.03  5427.3 2082.12  5448.8 2082.96
#Mann=5,-1,0
  4743.8     0.1       0  4996.3    0.07       0  5002.3     0.1       0
  5423.2    0.16       0  5427.3     0.1       0
Bank Sta=4996.3,5002.3
Exp/Cntr=0.3,0.1

Type RM Length L Ch R = 1,894,400,400,400
BEGIN DESCRIPTION:
UNT 0101 IN HEWA 2.0
END DESCRIPTION:
XS GIS Cut Line= 3
      2742223.09     10100637.28      2741858.50     10101253.63
      2741789.05     10101557.48
#Sta/Elev= 30
  4531.1 2087.61  4553.0 2086.01  4568.6 2083.22  4590.1 2084.05  4627.2 2081.13
  4648.6 2081.79  4664.2 2079.59  4670.0 2080.46  4707.1 2077.05  4728.5 2077.14
  4765.6 2072.75  4787.0 2072.17  4802.7 2069.65  4808.5 2069.86  4824.1 2066.16
  4845.6 2064.68  4861.2 2060.91  4882.6 2058.73  4904.1 2058.29  4919.7 2056.60
  4958.1 2056.22  5002.5 2054.36  5005.2 2053.86  5008.5 2054.36  5079.6 2060.14
  5101.0 2060.14  5196.6 2065.12  5335.5 2070.12  5442.2 2072.41  5558.9 2078.09
#Mann=5,-1,0
  4531.1    0.16       0  4958.1    0.05       0  5002.5   0.035       0
  5008.5    0.05       0  5335.5     0.1       0
Bank Sta=5002.5,5008.5
Exp/Cntr=0.3,0.1

Type RM Length L Ch R = 1,494,462,462,462
BEGIN DESCRIPTION:
Mapping XS 66b4c288
END DESCRIPTION:
XS GIS Cut Line= 3
      2741701.74     10100608.41      2741568.92     10101079.78
      2741678.28     10101462.54
#Sta/Elev= 30
  4670.3 2086.06  4696.1 2083.34  4701.3 2083.88  4735.3 2079.56  4740.5 2080.12
  4774.5 2074.87  4779.7 2075.15  4790.1 2073.25  4813.7 2071.71  4847.8 2066.64
  4853.0 2067.19  4881.8 2063.90  4887.0 2064.19  4921.0 2059.65  4960.2 2056.18
  4987.5 2049.52  4994.2 2044.38  4996.4 2044.18  4999.2 2043.68  5002.4 2044.18
  5008.3 2044.45  5028.3 2049.52  5039.4 2050.37  5091.4 2053.45  5145.9 2054.24
  5195.3 2056.43  5357.5 2065.63  5455.3 2070.03  5510.3 2070.70  5558.1 2072.13
#Mann=5,-1,0
  4670.3    0.16       0  4996.4    0.07       0  5002.4    0.16       0
  5039.4    0.05       0  5510.3     0.1       0
Bank Sta=4996.4,5002.4
Exp/Cntr=0.3,0.1

Type RM Length L Ch R = 1,32,0,0,0
BEGIN DESCRIPTION:
UNT 0101 IN HEWA 1.0
END DESCRIPTION:
XS GIS Cut Line= 4
      2741370.98     10100522.51      2741149.65     10100793.32
      2741173.09     10100936.55      2741513.85     10101477.60
#Sta/Elev= 30
  4592.0 2081.44  4602.0 2081.23  4630.7 2078.73  4701.0 2068.97  4816.3 2055.42
  4857.5 2050.22  4907.1 2046.11  4938.8 2041.46  4961.4 2040.50  4966.4 2041.39
  5000.0 2039.35  5002.7 2038.85  5006.0 2039.35  5022.7 2040.75  5033.4 2042.87
  5043.5 2044.00  5053.6 2044.48  5103.8 2045.21  5109.7 2045.93  5176.8 2046.51
  5203.9 2048.77  5219.2 2049.28  5225.4 2048.86  5334.6 2054.29  5473.6 2059.09
  5569.7 2063.96  5626.5 2068.07  5662.6 2068.35  5698.1 2070.39  5726.3 2070.64
#Mann=5,-1,0
  4592.0    0.16       0  4816.3     0.1       0  5000.0    0.07       0
  5006.0     0.1       0  5569.7    0.05       0
Bank Sta=5000,5006
Exp/Cntr=0.3,0.1

Chan Stop Cuts=-1