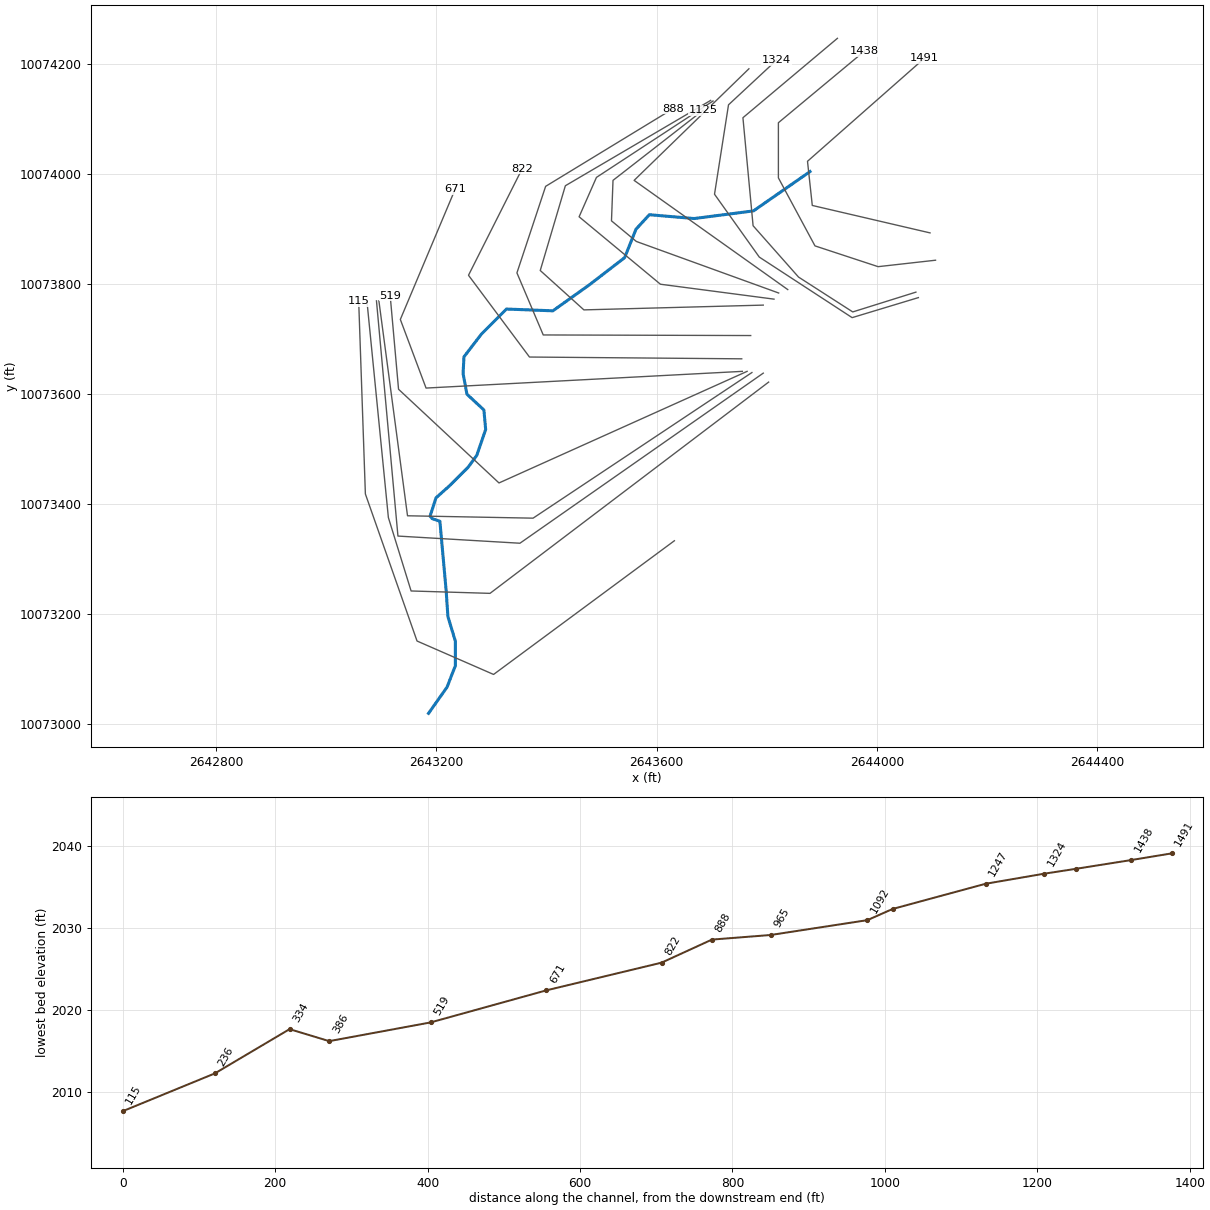
--- UNT 0102 IN HEWA.prj (project) ---

Proj Title=UNT 0102 IN HEWA Base Level Engineering
Current Plan=p01
Default Exp/Contr=0.3,0.1
English Units
Geom File=g01
Flow File=f01
Plan File=p01
Y Axis Title=Elevation
X Axis Title(PF)=Main Channel Distance
X Axis Title(XS)=Station
BEGIN DESCRIPTION:
UNT 0102 IN HEWA
END DESCRIPTION:
DSS Export Rating Curves= 0
DSS Export Rating Curve Sorted= 0
DSS Export Volume Flow Curves= 0
DXF OffsetX= 0
DXF OffsetY= 0
DXF ScaleX= 1
DXF ScaleY= 10

--- UNT 0102 IN HEWA.p01 (plan) ---

Plan Title=Multiple Run
Short Identifier=Multiple
Geom File=g01
Flow File=f01
Subcritical Flow
K Sum by GR= 0
Std Step Tol= 0.01
Critical Tol= 0.01
Num of Std Step Trials= 20
Max Error Tol= 0.3
Flow Tol Ratio= 0.001
Split Flow NTrial= 30
Split Flow Tol= 0.02
Split Flow Ratio= 0.02
Log Output Level= 0
Friction Slope Method= 1
Unsteady Friction Slope Method= 2
Unsteady Bridges Friction Slope Method= 1
Parabolic Critical Depth
Global Vel Dist=  1 , 1 , 1
Global Log Level= 0
CheckData=True
Encroach Param= -1, 0, 0, 0
BEGIN DESCRIPTION:
Multiple Run
END DESCRIPTION:

--- UNT 0102 IN HEWA.f01 (steady flow) ---

Flow Title=Multiple
Program Version=4.10
Number of Profiles= 7
Profile Names=10-year,25-year,50-year,1pct_min,100-year,1pct_plu,500-year
River Rch & RM=UNT 0102 IN HEWA,Reach-1         ,1491
      38      43      45      36      48      65      54
Boundary for River Rch & Prof#=UNT 0102 IN HEWA,Reach-1         , 1
Up Type= 0
Dn Type= 3
Dn Slope=0.038
Boundary for River Rch & Prof#=UNT 0102 IN HEWA,Reach-1         , 2
Up Type= 0
Dn Type= 3
Dn Slope=0.038
Boundary for River Rch & Prof#=UNT 0102 IN HEWA,Reach-1         , 3
Up Type= 0
Dn Type= 3
Dn Slope=0.038
Boundary for River Rch & Prof#=UNT 0102 IN HEWA,Reach-1         , 4
Up Type= 0
Dn Type= 3
Dn Slope=0.038
Boundary for River Rch & Prof#=UNT 0102 IN HEWA,Reach-1         , 5
Up Type= 0
Dn Type= 3
Dn Slope=0.038
Boundary for River Rch & Prof#=UNT 0102 IN HEWA,Reach-1         , 6
Up Type= 0
Dn Type= 3
Dn Slope=0.038
Boundary for River Rch & Prof#=UNT 0102 IN HEWA,Reach-1         , 7
Up Type= 0
Dn Type= 3
Dn Slope=0.038
DSS Import GetInterval= 0
DSS Import GetPeak= 0
DSS Import FillOption= 0

--- UNT 0102 IN HEWA.g01 (geometry) ---

Geom Title=Existing Conditions
Program Version=4.10

River Reach=UNT 0102 IN HEWA,Reach-1
Reach XY= 28
      2643878.44      10074004.7      2643775.66     10073933.17
      2643668.02     10073919.28      2643586.77     10073926.22
      2643562.47     10073899.84      2643541.86     10073848.15
      2643477.49     10073798.46      2643411.66     10073751.51
      2643327.48     10073754.75      2643282.15     10073709.42
      2643250.31     10073667.87      2643248.69     10073637.65
       2643255.7     10073599.87      2643286.46     10073571.27
       2643289.7     10073535.66      2643273.51     10073488.71
      2643257.86     10073467.12      2643224.41     10073433.67
      2643199.58     10073411.54      2643188.79     10073378.08
      2643192.57     10073373.77       2643206.6     10073368.91
      2643217.93     10073243.18      2643221.17     10073195.69
      2643234.66      10073150.9      2643234.66     10073106.11
      2643219.55     10073067.26      2643185.97     10073019.59

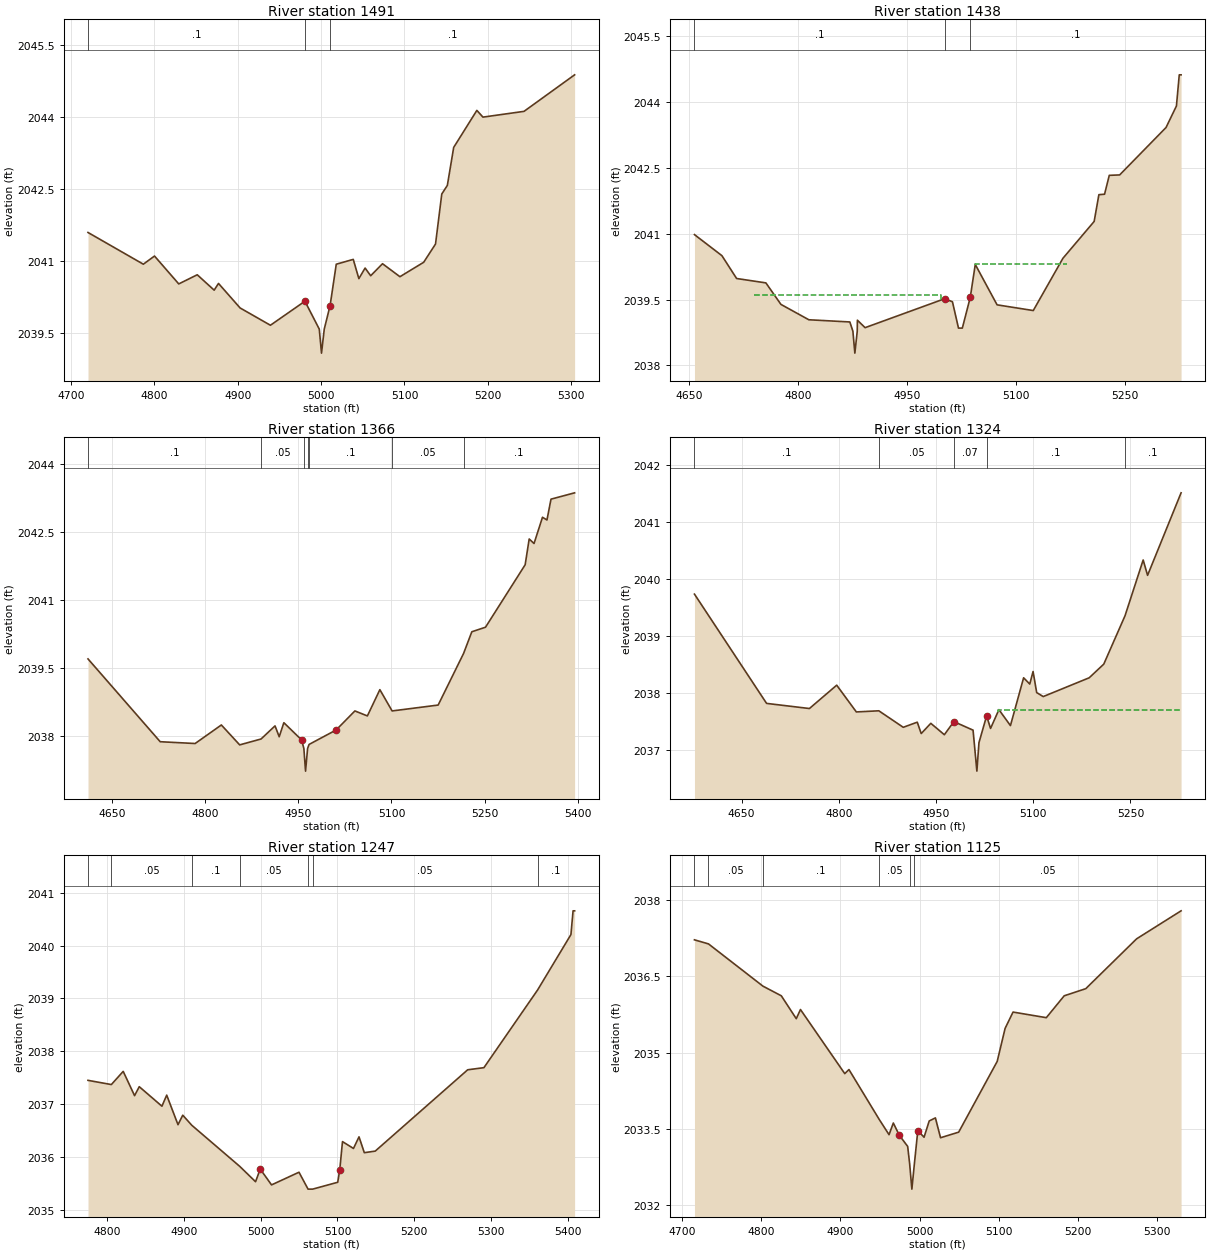
Type RM Length L Ch R = 1 ,1491    ,53,53,53
BEGIN DESCRIPTION:
UNT 0102 IN HEWA 6.3
END DESCRIPTION:
XS GIS Cut Line= 4
      2644096.16     10073893.19      2643882.45     10073943.09
      2643873.77     10074023.39      2644086.44     10074211.11
#Sta/Elev= 30
  4720.3  2041.6  4786.7 2040.94  4800.1 2041.11  4829.2 2040.53  4851.4 2040.72
  4871.7  2040.4  4876.9 2040.54  4902.8 2040.03  4939.2 2039.67  4980.6 2040.17
  4997.8 2039.59  5000.5 2039.09  5003.8 2039.59  5010.8 2040.08  5018.2 2040.94
  5038.6 2041.04  5045.3 2040.64  5052.8 2040.86  5059.5  2040.7  5073.7 2040.95
  5094.6 2040.68  5123.1 2040.98  5137.3 2041.36  5144.8  2042.4  5151.5 2042.58
  5159.1 2043.37  5186.9 2044.14  5194.2    2044  5243.5 2044.12  5304.2 2044.88
#Mann= 3 , 0 , 0
  4720.3      .1       0  4980.6     .07       0  5010.8      .1       0
Bank Sta=4980.6,5010.8
XS Rating Curve= 0 ,0
Exp/Cntr=0.3,0.1

Type RM Length L Ch R = 1 ,1438    ,72,72,72
BEGIN DESCRIPTION:
Mapping XS 7d77bbfa1
END DESCRIPTION:
XS GIS Cut Line= 6
      2644106.13     10073843.51      2644001.93     10073831.79
      2643887.35     10073869.55      2643820.94     10073993.24
      2643820.94      10074093.5      2643977.23     10074223.74
#Sta/Elev= 30
  4657.7 2040.98  4695.5  2040.5  4715.7 2039.98    4756 2039.88  4776.7 2039.39
  4815.1 2039.04  4871.5 2038.99  4875.7 2038.78  4878.4 2038.28  4881.7 2038.78
  4881.9 2039.03  4892.5 2038.86  5002.1 2039.52  5012.7 2039.45    5021 2038.85
  5026.3 2038.85 5037.21 2039.55  5044.1  2040.3  5074.1 2039.38  5123.9 2039.25
  5164.7 2040.44  5207.7 2041.28  5214.2 2041.89    5222  2041.9  5228.5 2042.33
  5242.8 2042.34  5306.6 2043.42  5320.9 2043.91  5324.8 2044.62  5327.3 2044.62
#Mann= 3 , 0 , 0
  4657.7      .1       0  5002.1     .07       0 5037.21      .1       0
#XS Ineff= 2 ,-1
 4739.53 4996.51  2039.6 5044.19 5169.77 2040.32
Permanent Ineff=
       T       T
Bank Sta=5002.1,5037.21
XS Rating Curve= 0 ,0
Exp/Cntr=0.3,0.1

Type RM Length L Ch R = 1 ,1366    ,42,42,42
BEGIN DESCRIPTION:
Mapping XS 7d77bbfa
END DESCRIPTION:
XS GIS Cut Line= 6
       2644070.5     10073785.47      2643955.87     10073749.49
      2643857.49     10073812.88      2643775.02      10073906.2
      2643756.58      10074102.6      2643928.04     10074246.93
#Sta/Elev= 30
  4611.6  2039.7  4727.8 2037.87    4784 2037.83  4826.2 2038.24  4855.7  2037.8
  4890.1 2037.93  4912.6 2038.22  4919.3 2037.98  4926.8 2038.29  4955.3 2037.91
    4959 2037.72  4961.7 2037.22    4965 2037.72  4967.4 2037.81    5011 2038.13
  5041.1 2038.55  5061.2 2038.44  5081.3 2039.02    5101 2038.55  5175.1 2038.68
    5216 2039.82  5229.3  2040.3  5251.3  2040.4  5315.1 2041.78  5321.6 2042.35
  5329.4 2042.25    5343 2042.83  5350.2 2042.77  5356.7 2043.23  5394.7 2043.37
#Mann= 7 ,-1 , 0
  4611.6      .1       0  4890.1     .05       0    4959     .07       0
    4965     .05       0  4967.4      .1       0    5101     .05       0
    5216      .1       0
#XS Ineff= 2 , 0
         4826.16 2038.22
Permanent Ineff=
       T       T
Bank Sta=4955.3,5011
XS Rating Curve= 0 ,0
Exp/Cntr=0.3,0.1

Type RM Length L Ch R = 1 ,1324    ,77,77,77
BEGIN DESCRIPTION:
Mapping XS 1e8e8133
END DESCRIPTION:
XS GIS Cut Line= 6
      2644074.99     10073775.52      2643954.77     10073739.11
      2643786.29     10073849.18      2643705.01     10073963.48
      2643730.41     10074126.04      2643817.64     10074207.35
#Sta/Elev= 30
  4577.2 2039.73  4688.5 2037.81  4754.6 2037.72  4796.7 2038.13    4827 2037.66
  4861.7 2037.68  4899.4 2037.39    4921 2037.48  4927.1 2037.28  4941.9 2037.46
  4962.8 2037.26  4977.5 2037.49  5007.1 2037.34    5013 2036.62  5016.2 2037.12
    5028 2037.59  5034.1 2037.37    5047  2037.7  5064.8 2037.42  5085.1 2038.26
  5094.6 2038.15  5099.7 2038.37  5105.3    2038  5115.4 2037.93  5186.3 2038.26
  5208.8  2038.5  5241.6 2039.35  5269.6 2040.33  5276.4 2040.06  5328.1 2041.51
#Mann= 5 ,-1 , 0
  4577.2      .1       0  4861.7     .05       0  4977.5     .07       0
    5028      .1       0  5241.6      .1       0
#XS Ineff= 2 , 0
                         5045.35          2037.7
Permanent Ineff=
       T       T
Bank Sta=4977.5,5028
XS Rating Curve= 0 ,0
Exp/Cntr=0.3,0.1

Type RM Length L Ch R = 1 ,1247    ,122,122,122
BEGIN DESCRIPTION:
Mapping XS 12da78eb
END DESCRIPTION:
XS GIS Cut Line= 3
      2643837.93     10073790.12       2643559.1     10073988.67
      2643767.42     10074191.56
#Sta/Elev= 30
  4775.4 2037.45  4805.8 2037.37  4821.2 2037.62    4836 2037.16  4842.1 2037.33
  4871.6 2036.96  4877.8 2037.17  4892.5 2036.61  4898.7 2036.79  4910.4  2036.6
  4972.9 2035.82  4993.4 2035.53  4999.5 2035.77  5014.2 2035.47  5049.9 2035.71
  5061.7 2035.39  5067.7 2035.39  5100.3 2035.52 5102.91 2035.75  5106.5 2036.29
  5120.8 2036.16    5128 2036.38  5134.9 2036.08  5149.1 2036.11  5269.4 2037.65
  5290.5 2037.69  5360.3 2039.16  5403.7 2040.21  5406.5 2040.66  5408.5 2040.66
#Mann= 7 ,-1 , 0
  4775.4      .1       0  4805.8     .05       0  4910.4      .1       0
  4972.9     .05       0  5061.7    .035       0  5067.7     .05       0
  5360.3      .1       0
Bank Sta=4999.5,5102.91
XS Rating Curve= 0 ,0
Exp/Cntr=0.3,0.1

Type RM Length L Ch R = 1 ,1125    ,33,33,33
BEGIN DESCRIPTION:
Mapping XS 2bc08767
END DESCRIPTION:
XS GIS Cut Line= 5
      2643821.45     10073783.88      2643563.16     10073877.61
      2643518.02     10073915.11       2643520.8     10073988.72
      2643684.11     10074116.05
#Sta/Elev= 30
  4715.9 2037.22  4733.6 2037.14  4802.3 2036.31  4825.5 2036.12  4844.4 2035.67
  4849.7 2035.85  4905.6 2034.59  4910.9 2034.67  4949.1 2033.69  4961.5 2033.39
  4966.9 2033.62  4974.4 2033.38    4985 2033.16  4987.5 2032.82  4990.3 2032.32
  4993.5 2032.82  4997.8 2033.47  5005.7 2033.34  5012.2 2033.66    5020 2033.72
  5026.5 2033.33  5049.4 2033.44    5098 2034.83    5108 2035.48    5118  2035.8
    5160 2035.69  5182.6 2036.12  5209.8 2036.26    5274 2037.24  5330.1 2037.79
#Mann= 6 ,-1 , 0
  4715.9      .1       0  4733.6     .05       0  4802.3      .1       0
  4949.1     .05       0  4987.5    .035       0  4993.5     .05       0
Bank Sta=4974.4,4997.8
XS Rating Curve= 0 ,0
Exp/Cntr=0.3,0.1

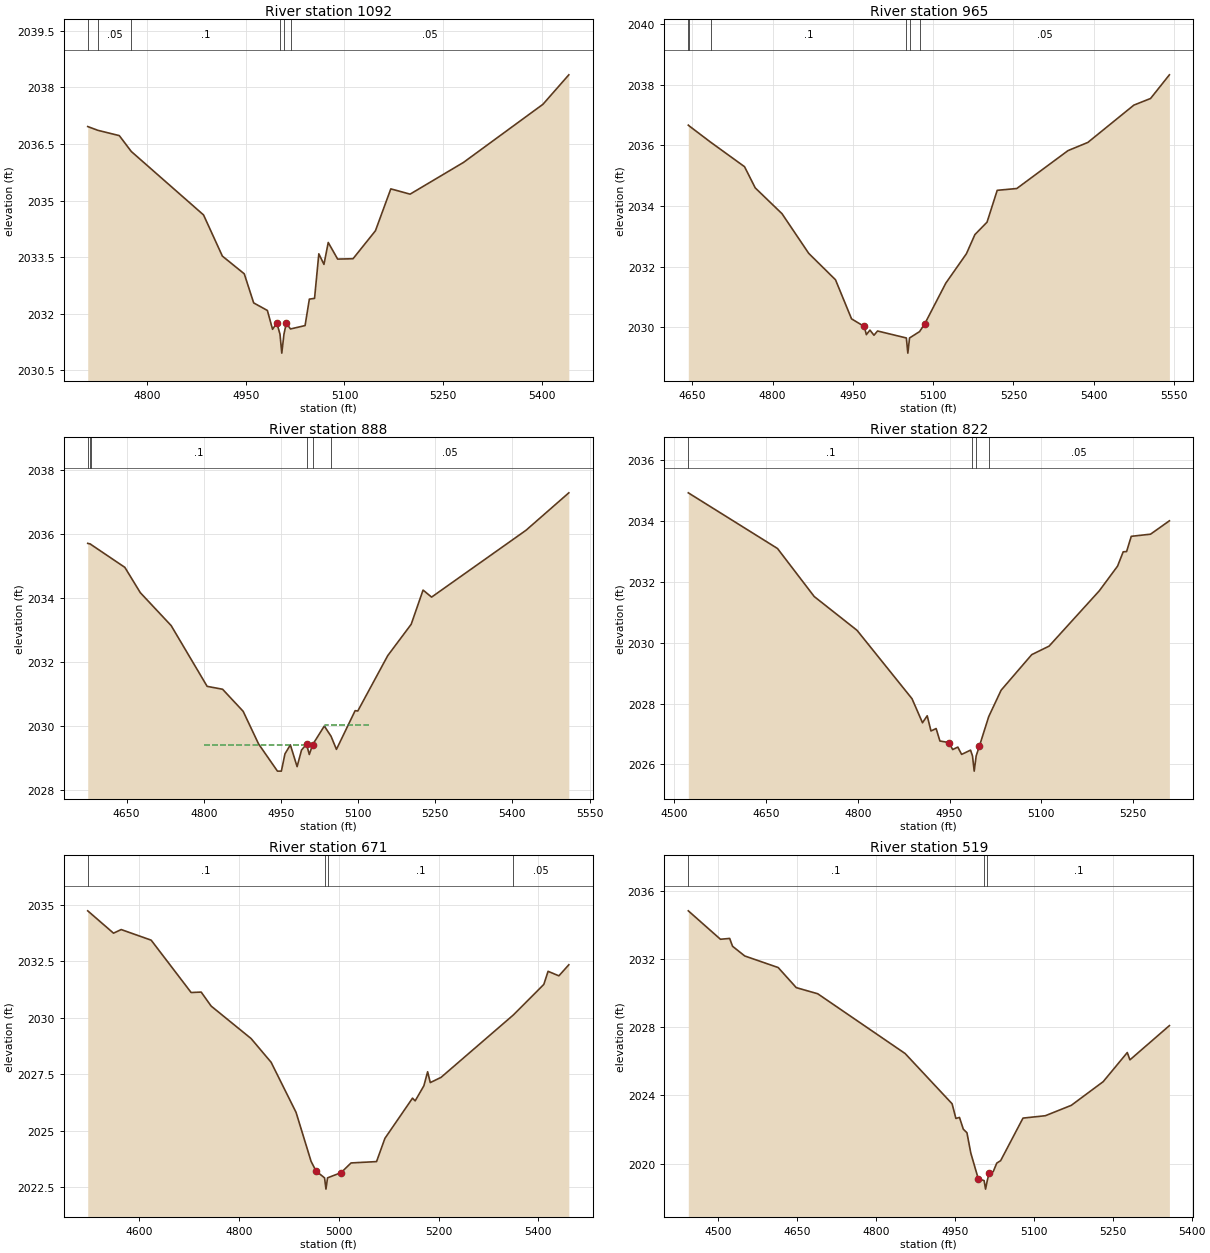
Type RM Length L Ch R = 1 ,1092    ,127,127,127
BEGIN DESCRIPTION:
Mapping XS dc2adcc7
END DESCRIPTION:
XS GIS Cut Line= 5
        2643813.     10073772.74      2643606.84     10073799.86
      2643459.27     10073922.48      2643490.74     10073994.09
      2643702.31     10074132.97
#Sta/Elev= 30
  4709.8 2036.96  4725.3 2036.86  4757.8 2036.72    4776  2036.3  4885.8 2034.62
  4914.4 2033.53  4947.7 2033.06    4962 2032.29  4982.8 2032.09  4990.7 2031.59
  4997.2 2031.76    5002 2031.46  5004.7 2030.96    5008 2031.46  5011.5 2031.75
    5018  2031.6  5040.1 2031.69  5046.6 2032.39  5054.5 2032.41    5061 2033.59
  5068.8 2033.31  5075.3 2033.89  5089.6 2033.45    5113 2033.46    5147  2034.2
  5170.4 2035.31  5199.7 2035.17  5280.8 2036.01  5401.6 2037.55  5440.9 2038.33
#Mann= 6 ,-1 , 0
  4709.8      .1       0  4725.3     .05       0    4776      .1       0
    5002     .07       0    5008      .1       0    5018     .05       0
Bank Sta=4997.2,5011.5
XS Rating Curve= 0 ,0
Exp/Cntr=0.3,0.1

Type RM Length L Ch R = 1 ,965     ,77,77,77
BEGIN DESCRIPTION:
Mapping XS 6d9d2094
END DESCRIPTION:
XS GIS Cut Line= 5
      2643793.49     10073761.89      2643467.95     10073753.21
      2643388.74     10073824.82      2643434.31      10073978.9
      2643698.02     10074134.09
#Sta/Elev= 30
  4642.3 2036.67  4644.3 2036.64  4683.9 2036.11  4747.4  2035.3  4767.4  2034.6
  4817.4 2033.75  4867.4 2032.44  4917.4 2031.57  4947.4 2030.28    4971 2030.03
  4975.1 2029.76  4981.8 2029.91  4989.3 2029.74    4996 2029.88  5049.8 2029.65
  5052.6 2029.15  5055.8 2029.65  5074.5 2029.86    5084 2030.11  5123.6 2031.46
  5162.1 2032.43  5177.9 2033.06  5200.6 2033.47  5219.6 2034.52  5256.2 2034.58
  5351.9 2035.83    5389  2036.1  5474.9 2037.33  5506.2 2037.55  5541.4 2038.33
#Mann= 6 ,-1 , 0
  4642.3      .1       0  4644.3     .05       0  4683.9      .1       0
  5049.8     .07       0  5055.8      .1       0  5074.5     .05       0
Bank Sta=4971,5084
XS Rating Curve= 0 ,0
Exp/Cntr=0.3,0.1

Type RM Length L Ch R = 1 ,888     ,66,66,66
BEGIN DESCRIPTION:
Mapping XS 325062bd
END DESCRIPTION:
XS GIS Cut Line= 5
      2643770.69     10073706.55      2643394.17     10073707.63
      2643346.42     10073820.48      2643398.51     10073977.81
      2643629.49     10074118.79
#Sta/Elev= 30
  4574.3 2035.71  4579.5 2035.69    4581 2035.67  4646.5 2034.96  4676.5 2034.17
  4736.5 2033.14  4806.5 2031.24  4836.5 2031.15  4876.5 2030.46  4906.5 2029.44
  4943.2 2028.59  4950.8 2028.59  4957.8 2029.13  4968.3 2029.41  4981.4 2028.73
    4990 2029.25  4999.7 2029.43  5005.1 2029.11  5011.7 2029.42  5034.3    2030
  5047.4 2029.68  5057.9 2029.27  5094.2 2030.48  5099.4 2030.47  5157.6  2032.2
  5203.2 2033.18  5226.3 2034.25  5242.9 2034.03  5426.5 2036.12  5509.7 2037.29
#Mann= 6 ,-1 , 0
  4574.3      .1       0  4579.5     .05       0    4581      .1       0
  4999.7     .07       0  5011.7      .1       0  5047.4     .05       0
#XS Ineff= 2 ,-1
 4799.42 4997.38 2029.41 5035.76 5122.09 2030.04
Permanent Ineff=
       T       T
Bank Sta=4999.7,5011.7
XS Rating Curve= 0 ,0
Exp/Cntr=0.3,0.1

Type RM Length L Ch R = 1 ,822     ,151,151,151
BEGIN DESCRIPTION:
Mapping XS 623abeaa
END DESCRIPTION:
XS GIS Cut Line= 4
      2643754.41     10073664.23      2643369.21     10073667.48
      2643258.53     10073816.14      2643355.76     10074009.53
#Sta/Elev= 30
  4522.6 2034.93  4668.5  2033.1  4728.6 2031.52  4798.6 2030.41  4888.6 2028.16
  4905.7 2027.37  4913.4  2027.6  4919.6  2027.1    4928 2027.18  4934.2 2026.77
  4948.8 2026.72  4955.1 2026.49  4963.5 2026.57  4969.7 2026.33  4984.3 2026.47
  4987.5 2026.28  4990.3 2025.78  4993.5 2026.28  4998.9 2026.61    5014 2027.57
  5034.3 2028.44  5084.4 2029.61  5112.8 2029.89    5195 2031.71  5224.8 2032.52
    5234 2032.99  5239.6    2033  5247.2  2033.5  5278.7 2033.57  5309.6 2034.01
#Mann= 4 ,-1 , 0
  4522.6      .1       0  4987.5     .07       0  4993.5      .1       0
    5014     .05       0
Bank Sta=4948.8,4998.9
XS Rating Curve= 0 ,0
Exp/Cntr=0.3,0.1

Type RM Length L Ch R = 1 ,671     ,152,152,152
BEGIN DESCRIPTION:
Mapping XS e257ba04
END DESCRIPTION:
XS GIS Cut Line= 4
      2643755.52     10073641.44      2643181.49     10073611.06
      2643134.83     10073735.84      2643234.08     10073972.09
#Sta/Elev= 30
  4496.7 2034.74  4548.4 2033.75  4563.8 2033.91  4623.9 2033.44    4704 2031.12
  4724.1 2031.14  4744.1 2030.52  4824.2 2029.08  4864.3 2028.03  4914.3 2025.81
  4944.4 2023.64  4954.4 2023.21  4971.4 2022.91  4974.2 2022.41  4977.4 2022.91
  5004.5 2023.14  5024.5 2023.57  5075.6 2023.63  5092.4 2024.66  5147.7 2026.44
    5153 2026.32  5170.5 2026.99    5178 2027.61  5183.3 2027.13  5204.8 2027.36
    5350 2030.13  5410.9 2031.48  5419.4 2032.06  5441.1 2031.86    5461 2032.35
#Mann= 4 ,-1 , 0
  4496.7      .1       0  4971.4     .07       0  4977.4      .1       0
    5350     .05       0
Bank Sta=4954.4,5004.5
XS Rating Curve= 0 ,0
Exp/Cntr=0.3,0.1

Type RM Length L Ch R = 1 ,519     ,133,133,133
BEGIN DESCRIPTION:
Mapping XS 150a59fe
END DESCRIPTION:
XS GIS Cut Line= 4
      2643764.16     10073641.44      2643313.87     10073438.54
      2643131.58     10073608.89      2643116.41     10073779.02
#Sta/Elev= 30
  4443.5 2034.84  4504.6 2033.17  4522.1 2033.22  4527.6 2032.76  4550.7 2032.19
  4614.3 2031.51  4648.7 2030.33  4689.5 2029.97  4855.6 2026.46  4944.8 2023.51
    4952 2022.65  4958.8 2022.71  4966.1 2022.02    4973 2021.81  4980.3 2020.62
  4994.5 2019.11  5005.6    2019  5008.4  2018.5  5011.6    2019  5015.5 2019.47
  5022.8 2019.52  5029.7 2020.03    5037 2020.17  5079.5 2022.67    5122 2022.81
  5171.3 2023.42  5231.9 2024.81  5277.7 2026.52  5282.7 2026.09  5357.7  2028.1
#Mann= 3 ,-1 , 0
  4443.5      .1       0  5005.6     .07       0  5011.6      .1       0
Bank Sta=4994.5,5015.5
XS Rating Curve= 0 ,0
Exp/Cntr=0.3,0.1

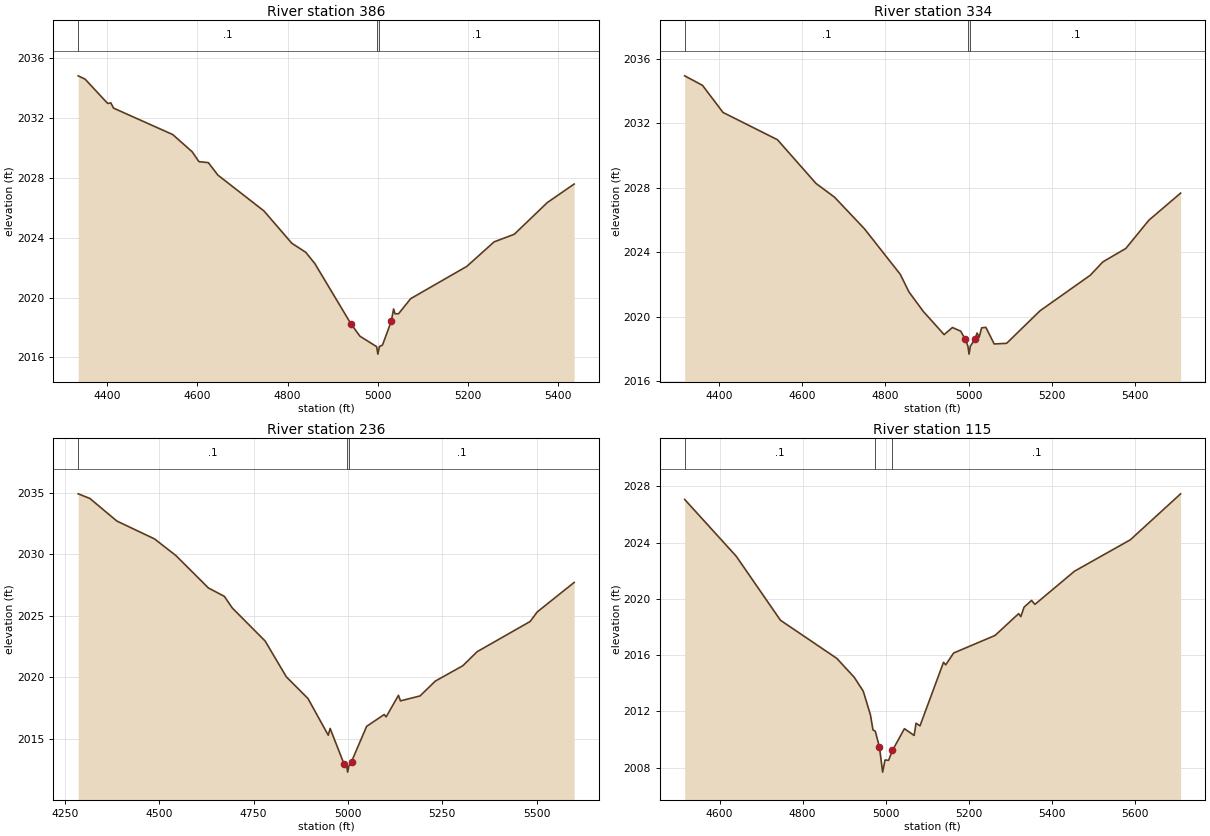
Type RM Length L Ch R = 1 ,386     ,52,52,52
BEGIN DESCRIPTION:
Mapping XS 5e09b925
END DESCRIPTION:
XS GIS Cut Line= 4
      2643772.89      10073639.3      2643375.72     10073374.52
      2643147.85     10073378.86      2643095.89     10073769.67
#Sta/Elev= 30
  4335.7 2034.84  4350.9 2034.62  4401.1 2032.99    4408 2033.03    4414 2032.68
  4545.3 2030.91  4588.3 2029.76  4603.3  2029.1  4624.3 2029.03  4645.3  2028.2
  4747.5  2025.8  4809.2 2023.64  4840.3 2023.03  4860.3 2022.28  4940.3 2018.25
  4960.3 2017.42  4997.3 2016.72  5000.1 2016.22  5003.3 2016.72  5010.3 2016.83
  5029.9 2018.43  5034.9 2019.24  5038.1 2018.92  5045.9 2018.92  5072.7 2019.93
  5197.2 2022.09  5257.7 2023.73  5302.5 2024.24  5375.7 2026.36  5435.2  2027.6
#Mann= 3 ,-1 , 0
  4335.7      .1       0  4997.3     .07       0  5003.3      .1       0
Bank Sta=4940.3,5029.9
XS Rating Curve= 0 ,0
Exp/Cntr=0.3,0.1

Type RM Length L Ch R = 1 ,334     ,98,98,98
BEGIN DESCRIPTION:
Mapping XS 268f5cd9
END DESCRIPTION:
XS GIS Cut Line= 4
      2643793.49      10073638.2      2643351.85     10073328.94
      2643130.49     10073341.96      2643091.52      10073769.6
#Sta/Elev= 30
  4318.2 2034.93    4361 2034.34  4410.2 2032.66  4540.9 2030.97  4633.4 2028.26
  4677.8 2027.41  4749.3 2025.46  4835.6 2022.63  4856.4 2021.54  4890.8 2020.33
  4940.9 2018.89  4960.9 2019.33  4980.9  2019.1    4991 2018.62    4998 2018.18
  5000.7 2017.68    5004 2018.18 5014.79 2018.59    5020 2018.99    5025 2018.73
    5031 2019.31    5041 2019.34  5061.1 2018.31  5090.9 2018.35  5171.2 2020.37
  5291.7 2022.57  5321.9  2023.4    5377 2024.23  5432.3 2025.98  5508.5 2027.66
#Mann= 3 ,-1 , 0
  4318.2      .1       0    4998     .07       0    5004      .1       0
Bank Sta=4991,5014.79
XS Rating Curve= 0 ,0
Exp/Cntr=0.3,0.1

Type RM Length L Ch R = 1 ,236     ,121,121,121
BEGIN DESCRIPTION:
Mapping XS e7959d39
END DESCRIPTION:
XS GIS Cut Line= 5
      2643803.24     10073621.92      2643297.59      10073237.8
      2643154.36     10073242.14      2643113.13      10073375.6
      2643074.16     10073769.69
#Sta/Elev= 30
  4285.5  2034.9  4316.6 2034.52  4387.8 2032.69  4487.6 2031.24  4543.8  2029.9
  4630.6 2027.25  4672.8 2026.57  4693.6 2025.63  4780.8 2022.94    4837 2020.03
  4894.3 2018.27    4948 2015.29    4953 2015.84  4989.7 2012.96  4996.7 2012.79
  4999.4 2012.29  5002.7 2012.79  5009.7 2013.15  5049.7 2016.01  5096.2 2016.97
  5101.4 2016.78    5134 2018.53  5139.3 2018.08  5191.1 2018.48  5231.8 2019.69
  5304.4 2020.93  5342.3 2022.07    5483 2024.53  5501.5  2025.3  5599.5  2027.7
#Mann= 3 ,-1 , 0
  4285.5      .1       0  4996.7     .07       0  5002.7      .1       0
Bank Sta=4989.7,5009.7
XS Rating Curve= 0 ,0
Exp/Cntr=0.3,0.1

Type RM Length L Ch R = 1 ,115     ,0,0,0
BEGIN DESCRIPTION:
UNT 0102 IN HEWA 1.2
END DESCRIPTION:
XS GIS Cut Line= 5
      2643632.19     10073333.45      2643304.03     10073090.37
      2643165.14     10073151.14      2643071.39      10073418.5
      2643059.25     10073768.99
#Sta/Elev= 30
  4515.9 2027.07  4640.1 2023.03  4746.5 2018.48  4882.1 2015.77  4924.3 2014.42
  4945.9 2013.43  4963.1 2011.76  4969.3 2010.68  4974.8 2010.59  4984.9 2009.45
  4992.5 2007.68  4998.2 2008.54  5006.8 2008.52  5016.1 2009.22  5044.9 2010.77
  5068.3 2010.29  5072.9 2011.16  5082.4 2010.97  5139.1 2015.49  5144.4 2015.31
  5163.4 2016.15  5263.2  2017.4  5319.9 2018.95  5325.2 2018.74    5333 2019.41
  5350.9 2019.89  5359.2 2019.61  5454.5 2021.97  5588.8  2024.2  5709.9 2027.47
#Mann= 3 ,-1 , 0
  4515.9      .1       0  4974.8     .07       0  5016.1      .1       0
Bank Sta=4984.9,5016.1
XS Rating Curve= 0 ,0
Exp/Cntr=0.3,0.1

Chan Stop Cuts=-1
Use User Specified Reach Order=0
Composite Channel Slope=5