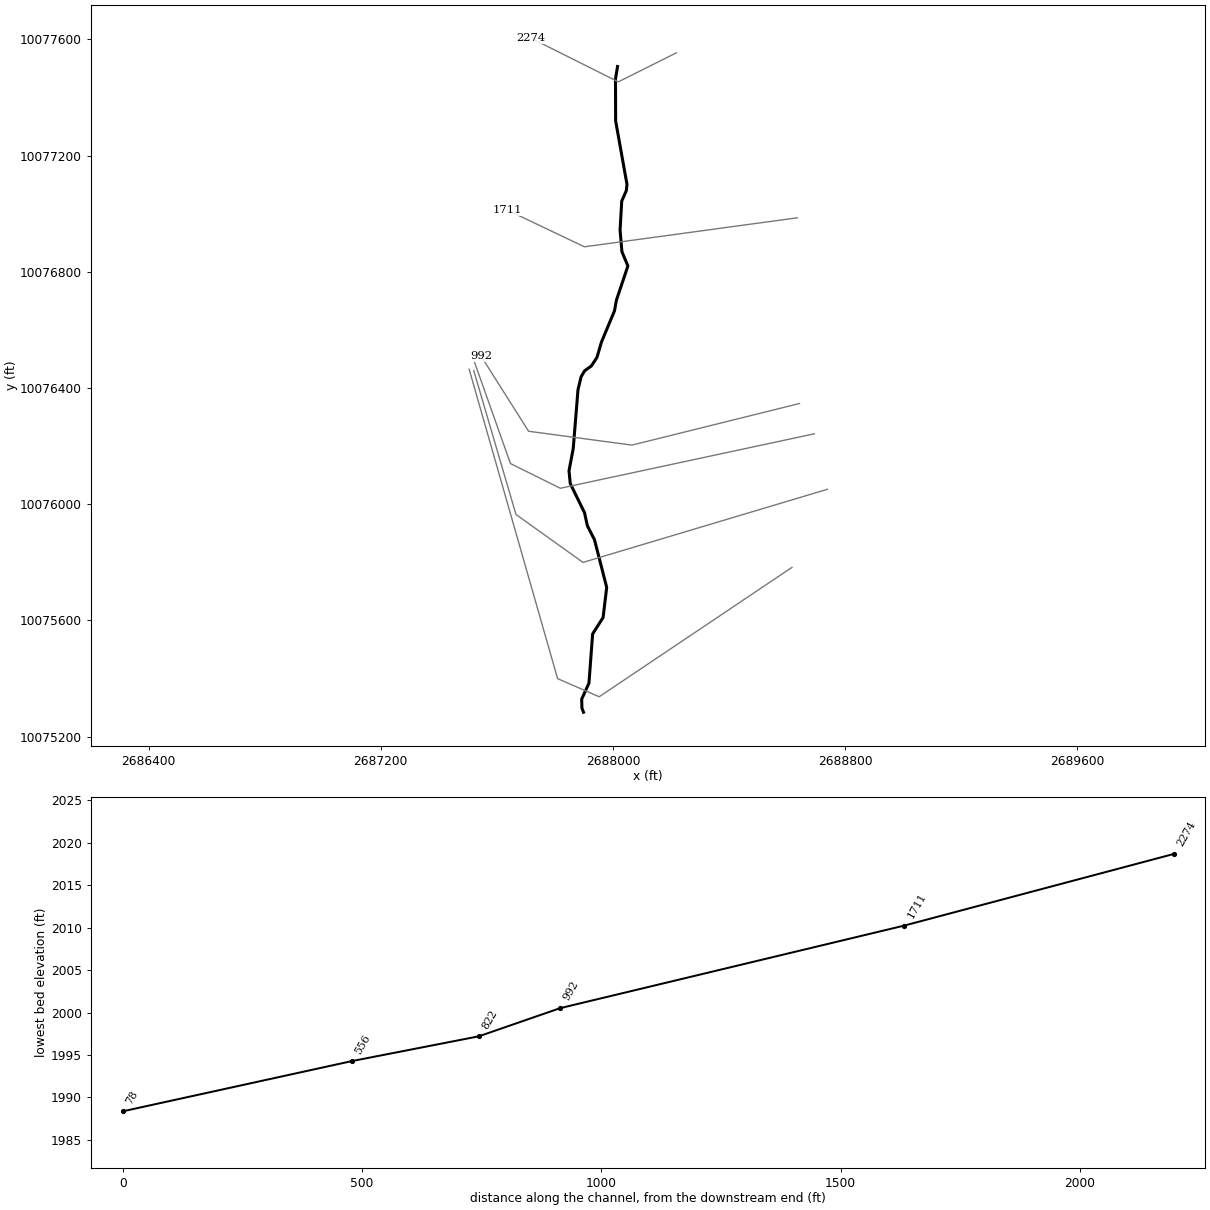
--- UNT 0103 IN HEWA.prj (project) ---

Proj Title=UNT 0103 IN HEWA Base Level Engineering
Current Plan=p01
Default Exp/Contr=0.3,0.1
English Units
Geom File=g01
Flow File=f01
Plan File=p01
Y Axis Title=Elevation
X Axis Title(PF)=Main Channel Distance
X Axis Title(XS)=Station
BEGIN DESCRIPTION:
UNT 0103 IN HEWA
END DESCRIPTION:
DSS Export Rating Curves= 0
DSS Export Rating Curve Sorted= 0
DSS Export Volume Flow Curves= 0
DXF OffsetX= 0
DXF OffsetY= 0
DXF ScaleX= 1
DXF ScaleY= 10

--- UNT 0103 IN HEWA.p01 (plan) ---

Plan Title=Multiple Run
Program Version=4.10
Short Identifier=Multiple
Geom File=g01
Flow File=f01
Subcritical Flow
K Sum by GR= 0
Std Step Tol= 0.01
Critical Tol= 0.01
Num of Std Step Trials= 20
Max Error Tol= 0.3
Flow Tol Ratio= 0.001
Split Flow NTrial= 30
Split Flow Tol= 0.02
Split Flow Ratio= 0.02
Log Output Level= 0
Friction Slope Method= 1
Unsteady Friction Slope Method= 2
Unsteady Bridges Friction Slope Method= 1
Parabolic Critical Depth
Global Vel Dist= 1 , 1 , 1
Global Log Level= 0
CheckData=True
Encroach Param=-1 ,0,0, 0
BEGIN DESCRIPTION:
Multiple Run
END DESCRIPTION:
Computation Interval=1HOUR
Output Interval=1HOUR
Run HTab= 0
Run UNet= 0
Run PostProcess= 0
Run WQNet= 0
UNET Theta= 1
UNET Theta Warmup= 1
UNET ZTol= 0.02
UNET ZSATol= 0.05
UNET MxIter= 20
UNET MaxInSteps= 0
UNET DtIC= 0
UNET DtMin= 0
UNET MaxCRTS= 20
UNET WFStab= 2
UNET SFStab= 1
UNET WFX= 1
UNET SFX= 1
UNET DSS MLevel= 4
UNET DZMax Abort= 100
UNET Convert EG Bridges= 0
UNET Use Existing IB Tables=-1
UNET Froude Reduction=False
UNET Froude Limit= 1
UNET Froude Power= 10
UNET Time Slicing=0,0, 5
UNET Junction Losses=0
Instantaneous Interval=1HOUR
Write IC File= 0
Write IC File at Sim End=0
Echo Input=False
Echo Parameters=False
Echo Output=False
Write Detailed= 0
WQ AD Non Conservative
WQ ULTIMATE=-1
WQ Max Comp Step=1HOUR
WQ Output Interval=15MIN
WQ Output Selected Increments= 0
WQ Output face flow=0
WQ Output face velocity=0
WQ Output face area=0
WQ Output face dispersion=0
WQ Output cell volume=0
WQ Output cell surface area=0
WQ Output cell continuity=0
WQ Output cumulative cell continuity=0
WQ Output face conc=0
WQ Output face dconc_dx=0
WQ Output face courant=0
WQ Output face peclet=0
WQ Output face adv mass=0
WQ Output face disp mass=0
WQ Output cell mass=0
WQ Output cell source sink temp=0
WQ Output cell source sink nsm=0
WQ Output MaxMinRange=-1
WQ Daily Max Min Mean=-1
WQ Daily Range=0
WQ Daily Time=0
WQ Create Restart=0
WQ Fixed Restart=0
WQ System Summary=0
WQ Use Fixed Temperature=0
Sorting and Armoring Iterations= 10
XS Update Threshold= 0.02
Hydraulics Update Threshold= 0.02
Energy Slope Method= 1
Volume Change Method= 0
XS Weighting Method= 0
Number of US Weighted Cross Sections= 1
Number of DS Weighted Cross Sections= 1
Upstream XS Weight=0.25
Main XS Weight=0.5
Downstream XS Weight=0.25
Number of DS XS's Weighted with US Boundary= 1
Upstream Boundary Weight= 1
Weight of XSs Associated with US Boundary= 0
Number of US XS's Weighted with DS Boundary= 1
Downstream Boundary Weight= 0.5
Weight of XSs Associated with DS Boundary= 0.5
Sediment Output Level= 4
Mass or Volume Output= 0
Output Increment Type= 1
Profile and TS Output Increment= 10
XS Output Flag= 0
XS Output Increment= 10
Disregard all LS=0
Disregard all Conn=0
Disregard all Breaches=0
Disregard all Pumps=0

--- UNT 0103 IN HEWA.f01 (steady flow) ---

Flow Title=Multiple
Number of Profiles=7
Profile Names=10-year,25-year,50-year,1pct_min,100-year,1pct_plu,500-year
River Rch & RM= UNT,Reach-1,2274
     564     788     974     881    1192    1612    1779
Boundary for River Rch & Prof#=UNT,Reach-1,1
Up Type=0
Dn Type=3
Dn Slope=0.005
Boundary for River Rch & Prof#=UNT,Reach-1,2
Up Type=0
Dn Type=3
Dn Slope=0.005
Boundary for River Rch & Prof#=UNT,Reach-1,3
Up Type=0
Dn Type=3
Dn Slope=0.005
Boundary for River Rch & Prof#=UNT,Reach-1,4
Up Type=0
Dn Type=3
Dn Slope=0.005
Boundary for River Rch & Prof#=UNT,Reach-1,5
Up Type=0
Dn Type=3
Dn Slope=0.005
Boundary for River Rch & Prof#=UNT,Reach-1,6
Up Type=0
Dn Type=3
Dn Slope=0.005
Boundary for River Rch & Prof#=UNT,Reach-1,7
Up Type=0
Dn Type=3
Dn Slope=0.005

--- UNT 0103 IN HEWA.g01 (geometry) ---

Geom Title=Existing Conditions
Program Version=4.10

River Reach=UNT             ,Reach-1
Reach XY= 30
      2688015.71     10077506.61      2688008.61     10077463.75
      2688009.18     10077319.03      2688048.21     10077100.91
      2688045.98     10077079.43       2688030.1     10077043.08
      2688024.46      10076943.7      2688030.78     10076869.24
      2688051.37     10076819.91      2688011.87     10076702.33
      2688005.12     10076665.12      2687960.29     10076557.95
      2687944.79      10076505.1      2687925.61     10076475.71
       2687902.5      10076459.1      2687890.23     10076438.67
      2687879.46     10076393.72      2687863.05     10076191.38
      2687848.55     10076115.01      2687852.82     10076070.94
      2687901.96     10075970.46       2687911.9     10075925.16
      2687936.19     10075877.79      2687978.34     10075713.57
      2687965.96     10075609.78      2687929.86     10075553.15
      2687917.21     10075383.64      2687892.15     10075328.57
      2687893.06     10075297.62      2687898.47     10075283.73

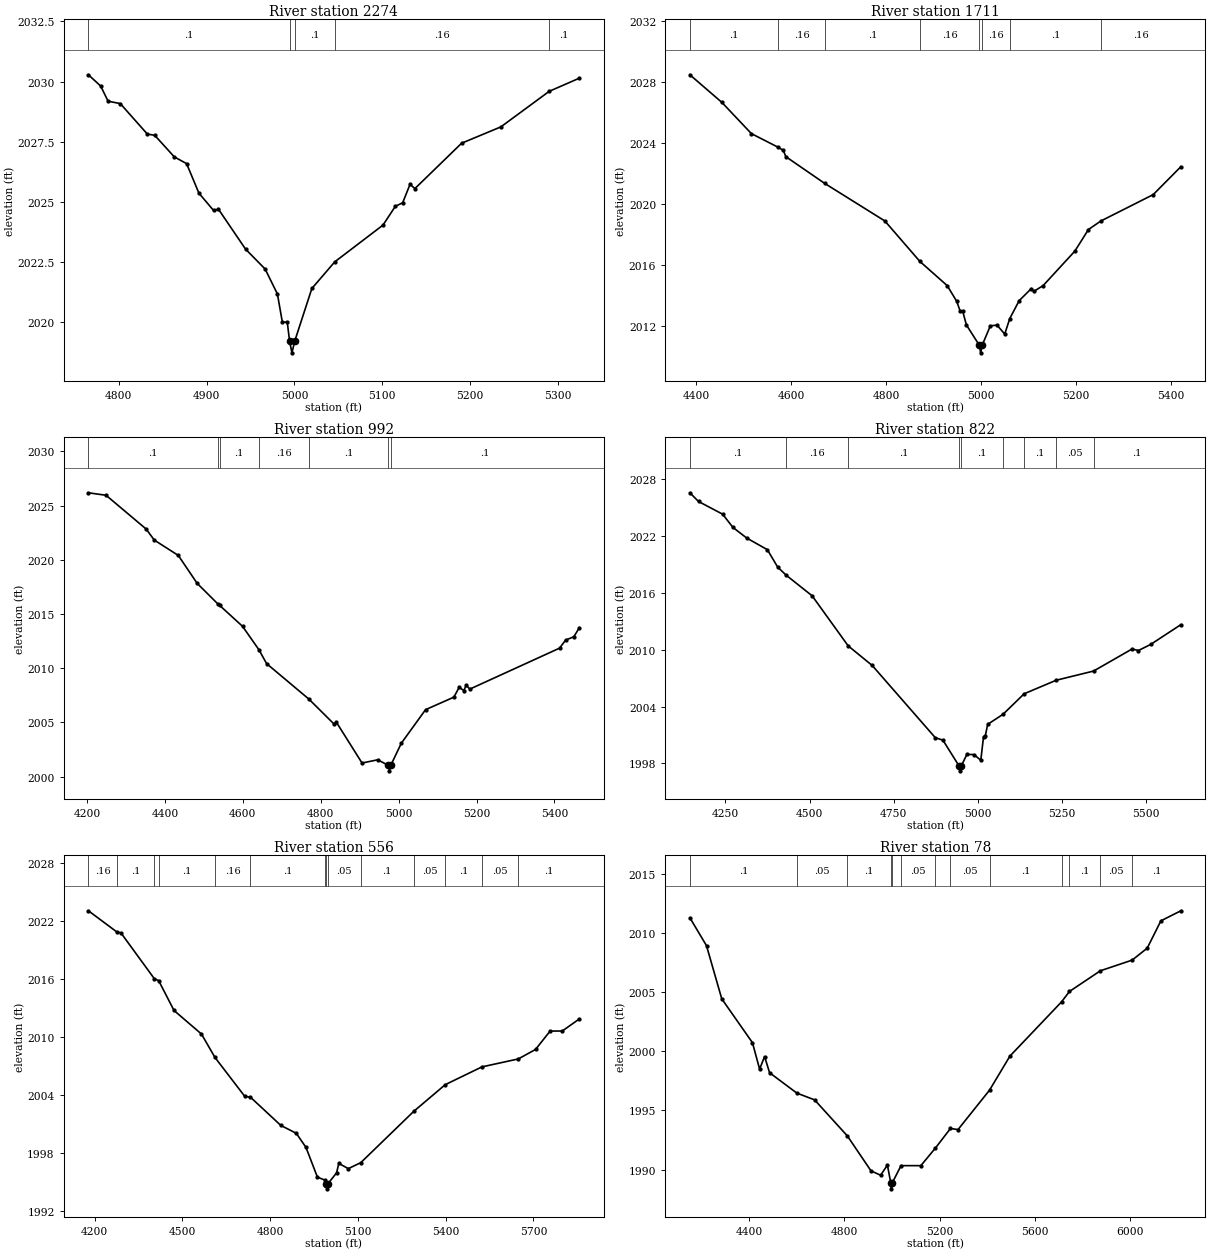
Type RM Length L Ch R = 1 ,2274    ,563,563,563
BEGIN DESCRIPTION:
UNT 0103 IN HEWA 4.0
END DESCRIPTION:
XS GIS Cut Line= 3
      2688218.46     10077553.73      2688018.47     10077453.73
      2687718.48     10077603.73
#Sta/Elev= 30
  4765.4 2030.28  4779.4 2029.81  4787.8 2029.18  4801.7 2029.08  4832.5 2027.81
  4840.9 2027.76  4863.2 2026.86  4877.2 2026.58  4891.2 2025.35  4907.9 2024.63
  4913.5 2024.68  4944.3 2023.02  4966.6 2022.19  4980.6 2021.15  4986.2 2019.98
  4991.8 2019.98  4994.4  2019.2  4997.1  2018.7  5000.4  2019.2  5019.8 2021.38
  5045.9 2022.49  5100.8 2024.02  5114.8  2024.8  5123.2 2024.95  5131.6 2025.72
  5137.1 2025.54  5190.3 2027.43    5235 2028.11    5290 2029.59  5324.4 2030.14
#Mann= 5 ,-1 , 0
  4765.4      .1       0  4994.4     .07       0  5000.4      .1       0
  5045.9     .16       0    5290      .1       0
Bank Sta=4994.4,5000.4
XS Rating Curve= 0 ,0
Exp/Cntr=0.3,0.1

Type RM Length L Ch R = 1 ,1711    ,719,719,719
BEGIN DESCRIPTION:
UNT 0103 IN HEWA 3.0
END DESCRIPTION:
XS GIS Cut Line= 3
      2688635.11     10076985.74      2687901.61     10076885.91
      2687636.87     10077011.78
#Sta/Elev= 30
  4387.2  2028.5  4454.5 2026.69  4516.7 2024.64  4573.3 2023.74    4584 2023.54
  4589.1 2023.13  4671.2 2021.37  4797.6 2018.91  4871.2 2016.26  4928.8 2014.67
    4949 2013.63  4956.1 2012.99  4961.2 2013.02  4969.2 2012.09  4996.4 2010.76
  4999.2 2010.26  5002.4 2010.76  5019.6 2012.03  5033.6 2012.08  5049.9 2011.49
  5060.5 2012.51  5080.2 2013.68    5106 2014.48    5111 2014.29  5130.7 2014.67
  5197.4 2016.93  5226.1 2018.35  5252.3 2018.91  5362.4 2020.64  5420.6 2022.47
#Mann= 8 ,-1 , 0
  4387.2      .1       0  4573.3     .16       0  4671.2      .1       0
  4871.2     .16       0  4996.4     .07       0  5002.4     .16       0
  5060.5      .1       0  5252.3     .16       0
Bank Sta=4996.4,5002.4
XS Rating Curve= 0 ,0
Exp/Cntr=0.3,0.1

Type RM Length L Ch R = 1 ,992     ,170,170,170
BEGIN DESCRIPTION:
UNT 0103 IN HEWA 2.0
END DESCRIPTION:
XS GIS Cut Line= 4
      2688642.48     10076346.41      2688065.24     10076203.19
      2687709.34     10076250.93      2687545.25     10076510.01
#Sta/Elev= 30
  4203.6 2026.18  4248.9 2025.95    4352 2022.83  4372.6 2021.82  4434.4  2020.4
  4482.7 2017.83  4535.3 2015.95  4540.6 2015.79  4599.3 2013.86  4641.2 2011.71
  4661.1 2010.42  4769.9 2007.14  4835.2 2004.81  4840.3 2005.01  4906.1 2001.25
  4946.4 2001.55  4973.7 2001.03  4976.4 2000.53  4979.7 2001.03    5007 2003.08
  5069.1 2006.17    5142 2007.33  5155.3 2008.23  5167.5 2007.94  5173.5 2008.43
  5182.8 2008.07  5413.3 2011.85  5428.6 2012.59  5449.8  2012.9  5464.1 2013.74
#Mann= 7 ,-1 , 0
  4203.6      .1       0  4535.3     .16       0  4540.6      .1       0
  4641.2     .16       0  4769.9      .1       0  4973.7     .07       0
  4979.7      .1       0
Bank Sta=4973.7,4979.7
XS Rating Curve= 0 ,0
Exp/Cntr=0.3,0.1

Type RM Length L Ch R = 1 ,822     ,266,266,266
BEGIN DESCRIPTION:
UNT 0103 IN HEWA 2.01
END DESCRIPTION:
XS GIS Cut Line= 4
      2688693.59     10076242.15      2687818.64     10076054.66
      2687646.77     10076139.73      2687522.38     10076490.43
#Sta/Elev= 30
  4144.2 2026.58  4169.9 2025.66  4241.5 2024.32  4272.2 2022.92  4313.1  2021.8
  4374.4 2020.57  4405.1 2018.73  4430.4 2017.87  4507.4  2015.7  4614.5 2010.41
  4685.9 2008.34  4873.4 2000.71    4896 2000.45  4944.2 1997.71  4946.9 1997.21
  4950.2 1997.71  4967.2 1998.94  4988.1 1998.93  5008.5 1998.33  5016.6  2000.8
  5021.7 2000.87    5029 2002.12  5074.8 2003.19  5137.3 2005.35  5232.6 2006.78
  5343.6 2007.75  5457.9 2010.08  5476.9 2009.92  5513.1 2010.56  5602.9 2012.65
#Mann= 9 ,-1 , 0
  4144.2      .1       0  4430.4     .16       0  4614.5      .1       0
  4944.2     .07       0  4950.2      .1       0  5074.8     .05       0
  5137.3      .1       0  5232.6     .05       0  5343.6      .1       0
Bank Sta=4944.2,4950.2
XS Rating Curve= 0 ,0
Exp/Cntr=0.3,0.1

Type RM Length L Ch R = 1 ,556     ,478,478,478
BEGIN DESCRIPTION:
UNT 0103 IN HEWA 2.02
END DESCRIPTION:
XS GIS Cut Line= 4
      2688738.77     10076051.18      2687896.77     10075799.45
      2687665.86     10075964.38      2687520.34     10076459.86
#Sta/Elev= 30
  4178.3 2023.03  4274.7 2020.86  4289.9 2020.73  4403.4 2016.02  4418.7  2015.8
  4471.1 2012.72  4564.8 2010.29  4611.2 2007.86  4713.3 2003.83  4732.3 2003.76
  4836.2 2000.84  4889.3 2000.02  4922.4 1998.56  4961.4 1995.49  4986.3 1995.19
  4990.9 1994.78  4993.6 1994.28  4996.9 1994.78    5027 1995.94  5034.5 1996.91
  5067.1 1996.37  5109.8 1996.99  5290.8 2002.29  5398.5 2005.05    5524 2006.89
  5648.3 2007.71  5707.2 2008.69  5757.1 2010.59  5798.8  2010.6  5857.3 2011.85
#Mann= 14 ,-1 , 0
  4178.3     .16       0  4274.7      .1       0  4403.4     .16       0
  4418.7      .1       0  4611.2     .16       0  4732.3      .1       0
  4986.3     .05       0  4990.9    .035       0  4996.9     .05       0
  5109.8      .1       0  5290.8     .05       0  5398.5      .1       0
    5524     .05       0  5648.3      .1       0
Bank Sta=4990.9,4996.9
XS Rating Curve= 0 ,0
Exp/Cntr=0.3,0.1

Type RM Length L Ch R = 1 ,78      ,0,0,0
BEGIN DESCRIPTION:
UNT 0103 IN HEWA 1.0
END DESCRIPTION:
XS GIS Cut Line= 4
      2688616.52     10075782.23      2687952.42     10075336.89
      2687809.19     10075399.39       2687504.5      10076464.5
#Sta/Elev= 30
  4150.6 2011.28  4220.5 2008.92  4284.6 2004.43  4413.7 2000.72  4443.7 1998.49
  4464.7 1999.55  4485.7 1998.18  4600.4 1996.46  4674.8 1995.89  4812.6 1992.84
  4911.9 1989.89  4952.5 1989.52  4980.8 1990.38  4995.1 1988.87  4997.9 1988.37
  5001.1 1988.87  5038.2 1990.33  5121.4 1990.33    5182  1991.8  5245.9 1993.47
  5277.7 1993.38  5410.1 1996.71  5495.9 1999.59  5712.7 2004.17    5746 2005.05
  5876.1  2006.8  6009.5  2007.7  6072.9 2008.71  6130.3 2011.02  6214.3 2011.87
#Mann= 13 ,-1 , 0
  4150.6      .1       0  4600.4     .05       0  4812.6      .1       0
  4995.1     .07       0  5001.1      .1       0  5038.2     .05       0
    5182      .1       0  5245.9     .05       0  5410.1      .1       0
  5712.7     .05       0    5746      .1       0  5876.1     .05       0
  6009.5      .1       0
Bank Sta=4995.1,5001.1
XS Rating Curve= 0 ,0
Exp/Cntr=0.3,0.1

Chan Stop Cuts=-1
Use User Specified Reach Order=0
Composite Channel Slope=5