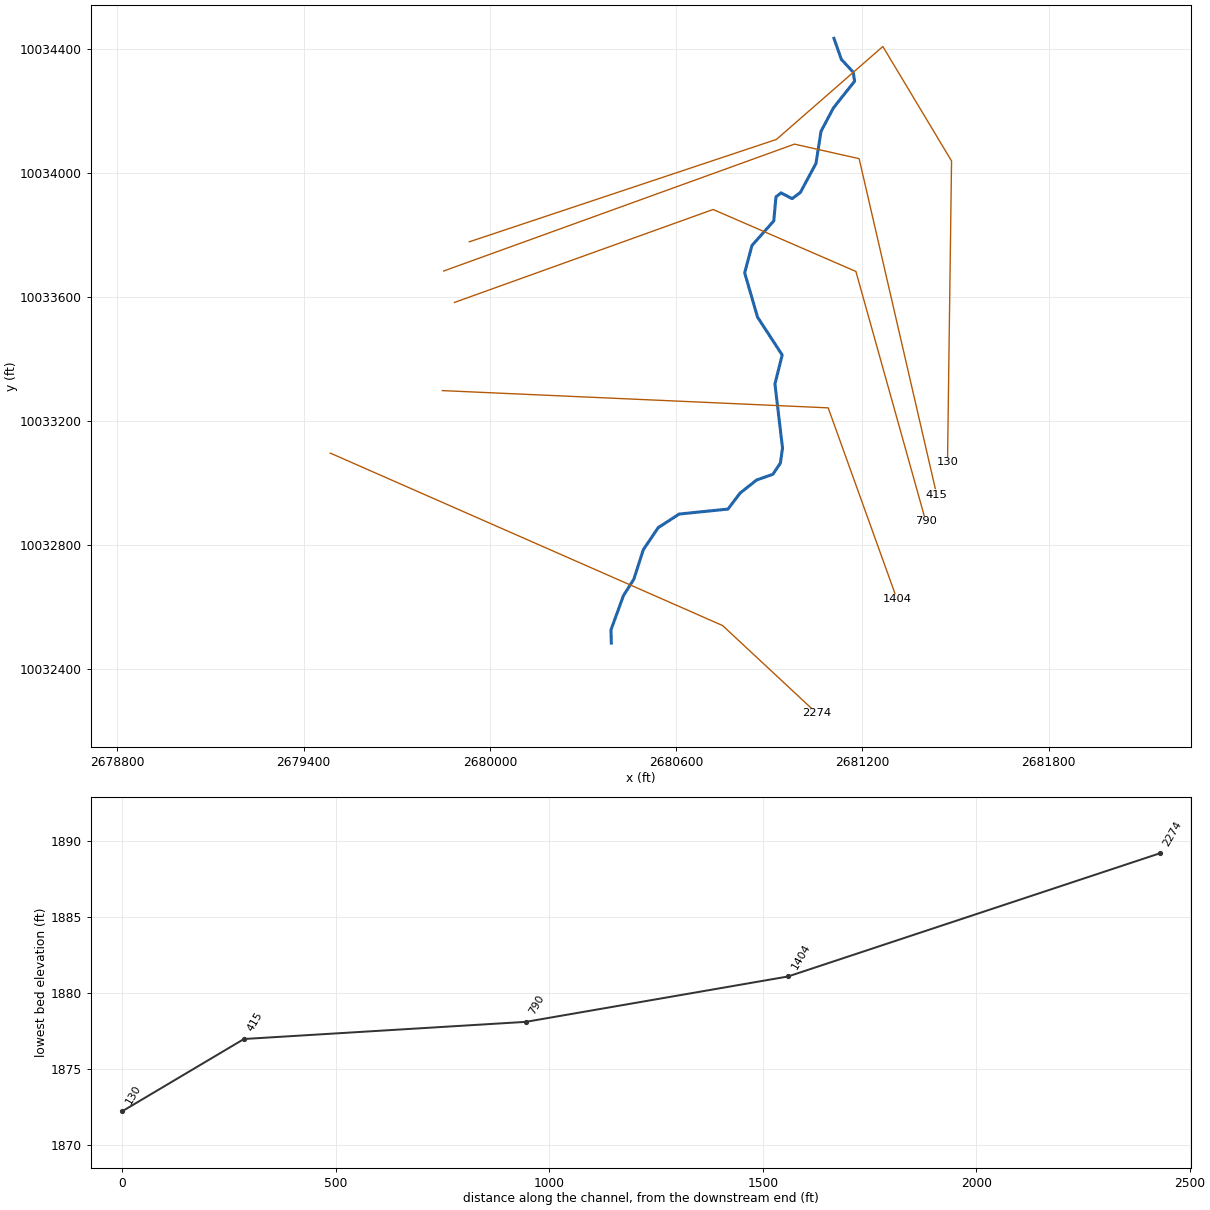
--- UNT 1003 IN HEWA.prj (project) ---

Proj Title=UNT 1003 IN HEWA Base Level Engineering
Current Plan=p01
Default Exp/Contr=0.3,0.1
English Units
Geom File=g01
Flow File=f01
Plan File=p01
Y Axis Title=Elevation
X Axis Title(PF)=Main Channel Distance
X Axis Title(XS)=Station
BEGIN DESCRIPTION:
UNT 1003 IN HEWA
END DESCRIPTION:
DSS Export Rating Curves= 0
DSS Export Rating Curve Sorted= 0
DSS Export Volume Flow Curves= 0
DXF OffsetX= 0
DXF OffsetY= 0
DXF ScaleX= 1
DXF ScaleY= 10

--- UNT 1003 IN HEWA.p01 (plan) ---

Plan Title=Multiple Run
Short Identifier=Multiple
Geom File=g01
Flow File=f01
Subcritical Flow
K Sum by GR= 0
Std Step Tol= 0.01
Critical Tol= 0.01
Num of Std Step Trials= 20
Max Error Tol= 0.3
Flow Tol Ratio= 0.001
Split Flow NTrial= 30
Split Flow Tol= 0.02
Split Flow Ratio= 0.02
Log Output Level= 0
Friction Slope Method= 1
Unsteady Friction Slope Method= 2
Unsteady Bridges Friction Slope Method= 1
Parabolic Critical Depth
Global Vel Dist=  1 , 1 , 1
Global Log Level= 0
CheckData=True
Encroach Param= -1, 0, 0, 0
BEGIN DESCRIPTION:
Multiple Run
END DESCRIPTION:

--- UNT 1003 IN HEWA.f01 (steady flow) ---

Flow Title=Multiple
Number of Profiles=7
Profile Names=10-year,25-year,50-year,1pct_min,100-year,1pct_plu,500-year
River Rch & RM= UNT 1003 IN HEWA,Reach-1,2274
    1112    1618    2055    1904    2575    3483    4041
Boundary for River Rch & Prof#=UNT 1003 IN HEWA,Reach-1,1
Up Type=0
Dn Type=3
Dn Slope=0.005
Boundary for River Rch & Prof#=UNT 1003 IN HEWA,Reach-1,2
Up Type=0
Dn Type=3
Dn Slope=0.005
Boundary for River Rch & Prof#=UNT 1003 IN HEWA,Reach-1,3
Up Type=0
Dn Type=3
Dn Slope=0.005
Boundary for River Rch & Prof#=UNT 1003 IN HEWA,Reach-1,4
Up Type=0
Dn Type=3
Dn Slope=0.005
Boundary for River Rch & Prof#=UNT 1003 IN HEWA,Reach-1,5
Up Type=0
Dn Type=3
Dn Slope=0.005
Boundary for River Rch & Prof#=UNT 1003 IN HEWA,Reach-1,6
Up Type=0
Dn Type=3
Dn Slope=0.005
Boundary for River Rch & Prof#=UNT 1003 IN HEWA,Reach-1,7
Up Type=0
Dn Type=3
Dn Slope=0.005

--- UNT 1003 IN HEWA.g01 (geometry) ---

Geom Title=Existing Conditions
Program Version=4.10

River Reach=UNT 1003 IN HEWA,Reach-1
Reach XY= 30
      2680391.13     10032485.05      2680390.08      10032527.8
      2680430.23       10032638.      2680463.69       10032691.
      2680494.27     10032786.06       2680542.1     10032856.94
      2680609.74     10032900.86      2680767.07     10032916.94
      2680806.14     10032968.56      2680859.52     10033010.75
      2680911.33     10033028.79      2680935.81     10033064.72
      2680942.74     10033113.58       2680918.3     10033320.11
      2680941.61     10033413.52      2680862.26      10033535.3
      2680820.82     10033678.18      2680844.25     10033766.24
      2680914.58     10033845.37      2680921.62     10033922.75
      2680938.04     10033935.78      2680973.62     10033917.19
       2681000.2     10033937.01      2681050.49     10034030.58
      2681066.86     10034134.37      2681106.82     10034209.71
      2681174.86      10034295.3      2681170.77     10034324.38
      2681132.26     10034365.92      2681108.47     10034433.73

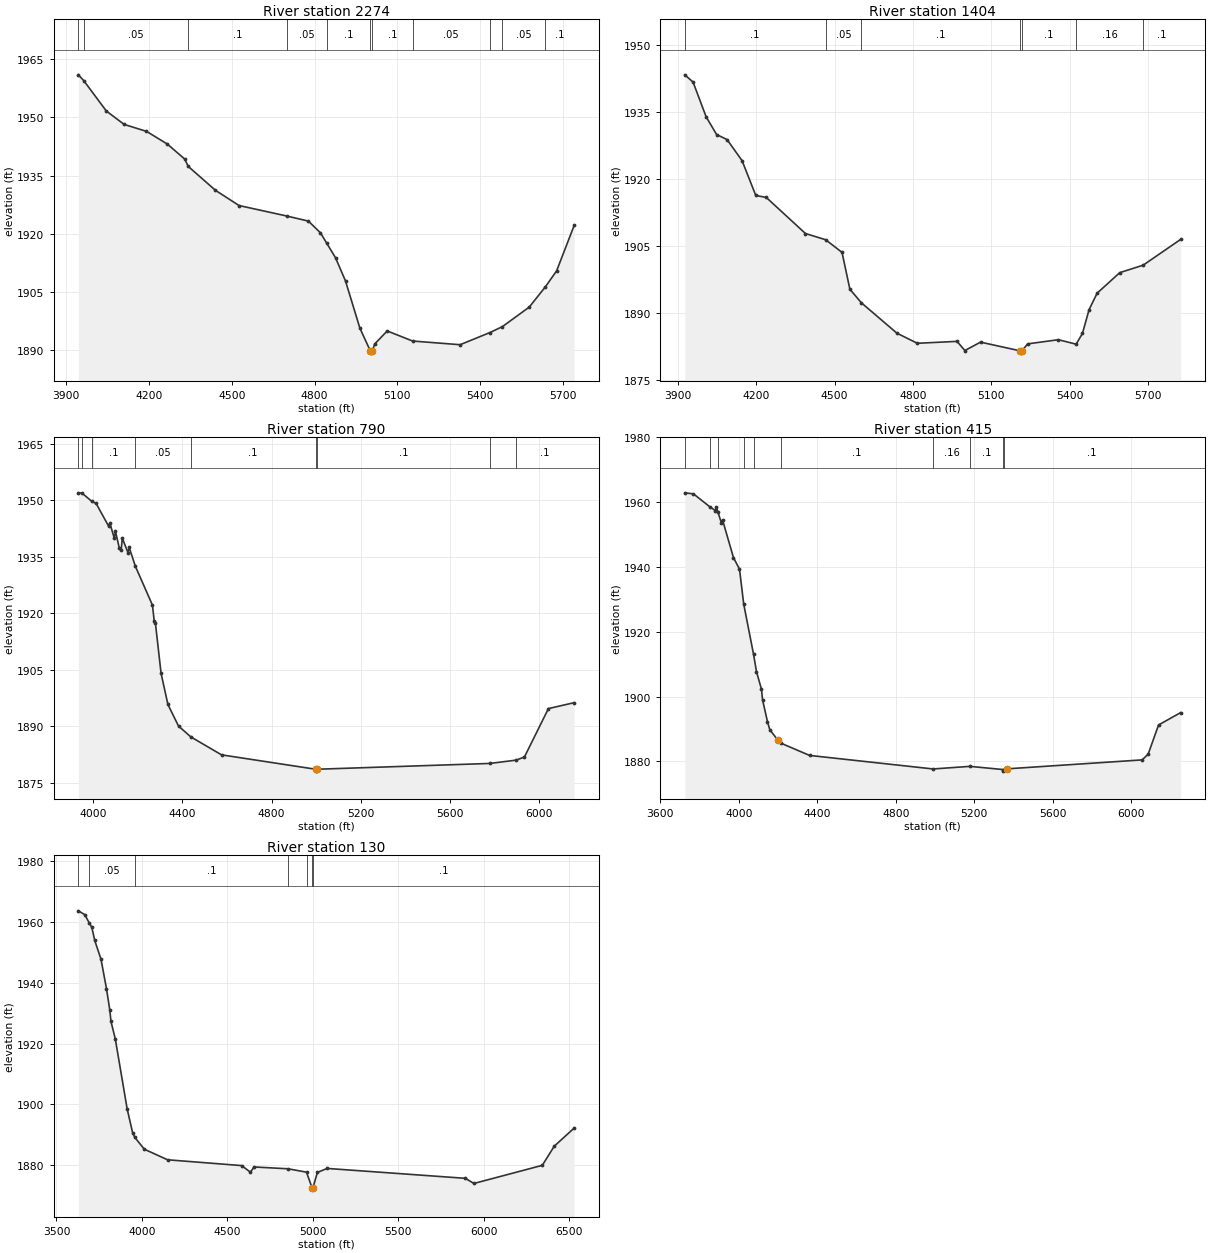
Type RM Length L Ch R = 1 ,2274    ,870,870,870
BEGIN DESCRIPTION:
UNT 1003 IN HEWA 3.0
END DESCRIPTION:
XS GIS Cut Line= 3
      2679485.65     10033097.27      2680749.58      10032541.7
      2681053.38     10032258.61
#Sta/Elev= 30
  3944.4 1960.97  3963.7  1959.5  4045.8 1951.64  4110.3 1948.18  4191.3 1946.39
  4266.8 1943.11  4329.8 1939.24  4342.3 1937.36  4441.1 1931.18  4526.4 1927.26
  4700.9 1924.53  4777.7 1923.24  4821.4 1920.22  4844.3 1917.52    4876 1913.78
  4912.1  1907.8  4964.2 1895.63  5002.5 1889.69  5005.2 1889.19  5008.5 1889.69
    5018 1891.55  5063.1 1894.91  5155.1 1892.31  5327.2 1891.36    5435 1894.49
  5480.5 1896.03  5577.6 1901.06  5636.1 1906.29  5676.8 1910.41  5740.3 1922.12
#Mann= 11 ,-1 , 0
  3944.4      .1       0  3963.7     .05       0  4342.3      .1       0
  4700.9     .05       0  4844.3      .1       0  5002.5     .07       0
  5008.5      .1       0  5155.1     .05       0    5435      .1       0
  5480.5     .05       0  5636.1      .1       0
Bank Sta=5002.5,5008.5
XS Rating Curve= 0 ,0
Exp/Cntr=0.3,0.1

Type RM Length L Ch R = 1 ,1404    ,614,614,614
BEGIN DESCRIPTION:
UNT 1003 IN HEWA 2.0
END DESCRIPTION:
XS GIS Cut Line= 3
      2679846.82     10033298.64      2681089.86     10033243.09
      2681311.41     10032626.89
#Sta/Elev= 30
  3926.3 1943.32    3958 1941.69    4008 1933.93  4048.1 1929.97  4088.1 1928.84
  4145.7 1924.12  4198.2 1916.34  4238.3  1915.9  4388.4 1907.83  4465.8 1906.44
  4528.5 1903.61  4558.6 1895.37  4602.9 1892.32  4738.8 1885.54    4817 1883.28
    4969 1883.71    4999 1881.66  5059.1 1883.54  5211.3 1881.58    5214 1881.08
  5217.3 1881.58  5239.7 1883.15  5357.2 1884.08  5425.2 1883.08  5449.4 1885.49
  5474.8 1890.81  5505.5 1894.48  5592.3 1899.08  5681.9 1900.75  5825.4 1906.51
#Mann= 7 ,-1 , 0
  3926.3      .1       0  4465.8     .05       0  4602.9      .1       0
  5211.3     .07       0  5217.3      .1       0  5425.2     .16       0
  5681.9      .1       0
Bank Sta=5211.3,5217.3
XS Rating Curve= 0 ,0
Exp/Cntr=0.3,0.1

Type RM Length L Ch R = 1 ,790     ,660,660,660
BEGIN DESCRIPTION:
Mapping XS fa8a96ad
END DESCRIPTION:
XS GIS Cut Line= 4
      2679885.75     10033582.75       2680719.1     10033882.23
      2681179.17     10033682.58      2681404.38     10032877.01
#Sta/Elev= 30
    3933 1951.96  3949.5 1951.89  3993.3  1949.7  4012.7 1949.14  4068.8 1943.12
  4074.2 1943.92  4094.3 1939.93  4099.6 1941.72  4116.5 1937.34    4125 1936.83
  4130.3 1939.88  4155.7 1936.08    4161  1937.5  4188.7 1932.48  4265.3 1922.16
  4273.3 1917.95  4278.6  1917.4    4304 1904.06  4334.7 1895.78  4382.2 1890.06
  4437.4 1887.18  4575.2 1882.41  4997.4 1878.59  5000.2 1878.09  5003.4 1878.59
  5778.6 1880.13  5896.5 1881.01  5933.5 1881.84  6041.1 1894.69  6156.5 1896.26
#Mann= 9 ,-1 , 0
    3933      .1       0  3949.5     .05       0  3993.3      .1       0
  4188.7     .05       0  4437.4      .1       0  4997.4     .07       0
  5003.4      .1       0  5778.6     .16       0  5896.5      .1       0
Bank Sta=4997.4,5003.4
XS Rating Curve= 0 ,0
Exp/Cntr=0.3,0.1

Type RM Length L Ch R = 1 ,415     ,285,285,285
BEGIN DESCRIPTION:
Mapping XS 6902bf98
END DESCRIPTION:
XS GIS Cut Line= 4
      2679851.04     10033683.99      2680981.26     10034092.84
      2681189.59     10034045.97      2681439.58     10032962.68
#Sta/Elev= 30
    3725  1962.9  3769.2 1962.58    3851 1958.66  3881.2  1957.4  3886.5 1958.58
  3893.6 1956.99  3911.8 1953.57  3917.2 1954.57  3973.1 1942.89  4003.8 1939.33
  4025.3 1928.53  4075.4 1913.04  4090.4 1907.68  4115.7 1902.27  4121.1 1899.05
  4146.4 1892.23  4158.3 1889.75  4200.8 1886.42  4213.1 1885.64    4361 1881.81
  4990.5 1877.63  5178.4 1878.43    5345 1877.46  5347.7 1876.96    5351 1877.46
  5368.5 1877.67  6056.1 1880.43  6086.7 1882.19  6139.7 1891.21  6252.2 1895.03
#Mann= 10 ,-1 , 0
    3725     .05       0    3851      .1       0  3893.6     .05       0
  4025.3      .1       0  4075.4     .05       0  4213.1      .1       0
  4990.5     .16       0  5178.4      .1       0    5345     .07       0
    5351      .1       0
Bank Sta=4200.8,5368.5
XS Rating Curve= 0 ,0
Exp/Cntr=0.3,0.1

Type RM Length L Ch R = 1 ,130     ,0,0,0
BEGIN DESCRIPTION:
UNT 1003 IN HEWA 1.0
END DESCRIPTION:
XS GIS Cut Line= 5
      2679933.52     10033778.07      2680923.09     10034107.92
      2681265.97      10034407.4      2681487.33     10034038.48
      2681474.32     10033067.46
#Sta/Elev= 30
    3628 1963.62  3665.9 1962.35  3691.7 1959.66    3707 1958.18  3723.9 1953.89
  3760.8 1947.67  3792.4  1938.1  3812.4  1930.9  3818.8 1927.29    3844 1921.59
  3913.6 1898.54  3945.3 1890.77  3957.8 1889.23  4013.8 1885.32  4149.7 1881.84
    4583 1879.93  4634.6 1877.76  4655.7 1879.48  4854.6 1878.88  4962.4 1877.77
  4994.5  1872.7  4997.3  1872.2  5000.5  1872.7    5026 1877.68    5083    1879
  5891.4 1875.75  5941.4 1874.06  6341.4 1880.02  6411.4 1886.31  6527.7 1892.26
#Mann= 7 ,-1 , 0
    3628      .1       0  3691.7     .05       0  3957.8      .1       0
  4854.6     .16       0  4962.4      .1       0  4994.5     .07       0
  5000.5      .1       0
Bank Sta=4994.5,5000.5
XS Rating Curve= 0 ,0
Exp/Cntr=0.3,0.1

Chan Stop Cuts=-1
Use User Specified Reach Order=0
Composite Channel Slope=5