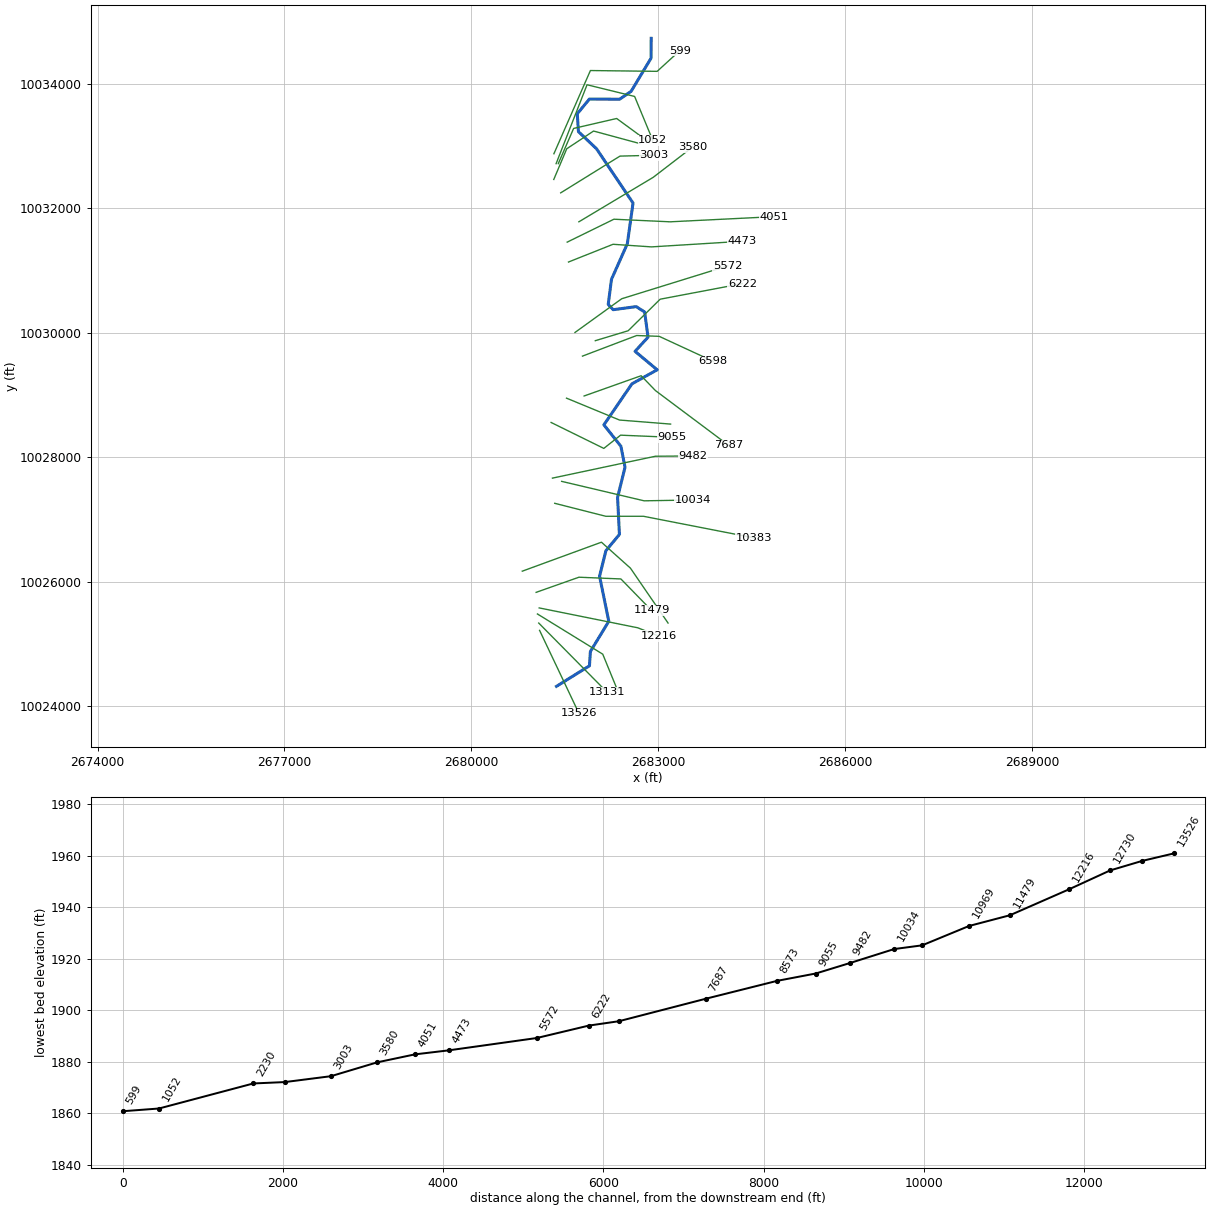
--- UNT 1004 IN HEWA.prj (project) ---

Proj Title=UNT 1004 IN HEWA Base Level Engineering
Current Plan=p01
Default Exp/Contr=0.3,0.1
English Units
Geom File=g01
Flow File=f01
Plan File=p01
Y Axis Title=Elevation
X Axis Title(PF)=Main Channel Distance
X Axis Title(XS)=Station
BEGIN DESCRIPTION:
UNT 1004 IN HEWA
END DESCRIPTION:
DSS Export Rating Curves= 0
DSS Export Rating Curve Sorted= 0
DSS Export Volume Flow Curves= 0
DXF OffsetX= 0
DXF OffsetY= 0
DXF ScaleX= 1
DXF ScaleY= 10

--- UNT 1004 IN HEWA.p01 (plan) ---

Plan Title=Multiple Run
Short Identifier=Multiple
Geom File=g01
Flow File=f01
Subcritical Flow
K Sum by GR= 0
Std Step Tol= 0.01
Critical Tol= 0.01
Num of Std Step Trials= 20
Max Error Tol= 0.3
Flow Tol Ratio= 0.001
Split Flow NTrial= 30
Split Flow Tol= 0.02
Split Flow Ratio= 0.02
Log Output Level= 0
Friction Slope Method= 1
Unsteady Friction Slope Method= 2
Unsteady Bridges Friction Slope Method= 1
Parabolic Critical Depth
Global Vel Dist=  1 , 1 , 1
Global Log Level= 0
CheckData=True
Encroach Param= -1, 0, 0, 0
BEGIN DESCRIPTION:
Multiple Run
END DESCRIPTION:

--- UNT 1004 IN HEWA.f01 (steady flow) ---

Flow Title=Multiple
Number of Profiles=7
Profile Names=10-year,25-year,50-year,1pct_min,100-year,1pct_plu,500-year
River Rch & RM= UNT 1004 IN HEWA,Reach-1,13526
    1934    2900    3759    3546    4796    6486    7808
River Rch & RM= UNT 1004 IN HEWA,Reach-1,10383
    2327    3514    4574    4329    5855    7918    9600
River Rch & RM= UNT 1004 IN HEWA,Reach-1,6222
    3183    4859    6371    6066    8204   11095   13615
Boundary for River Rch & Prof#=UNT 1004 IN HEWA,Reach-1,1
Up Type=0
Dn Type=3
Dn Slope=0.005
Boundary for River Rch & Prof#=UNT 1004 IN HEWA,Reach-1,2
Up Type=0
Dn Type=3
Dn Slope=0.005
Boundary for River Rch & Prof#=UNT 1004 IN HEWA,Reach-1,3
Up Type=0
Dn Type=3
Dn Slope=0.005
Boundary for River Rch & Prof#=UNT 1004 IN HEWA,Reach-1,4
Up Type=0
Dn Type=3
Dn Slope=0.005
Boundary for River Rch & Prof#=UNT 1004 IN HEWA,Reach-1,5
Up Type=0
Dn Type=3
Dn Slope=0.005
Boundary for River Rch & Prof#=UNT 1004 IN HEWA,Reach-1,6
Up Type=0
Dn Type=3
Dn Slope=0.005
Boundary for River Rch & Prof#=UNT 1004 IN HEWA,Reach-1,7
Up Type=0
Dn Type=3
Dn Slope=0.005

--- UNT 1004 IN HEWA.g01 (geometry) ---

Geom Title=Existing Conditions
Program Version=4.10

River Reach=UNT 1004 IN HEWA,Reach-1
Reach XY= 30
      2681368.47     10024323.73      2681897.52     10024653.39
      2681912.16     10024882.24      2682207.82     10025368.46
      2682059.62     10026093.26      2682161.68     10026502.45
      2682378.47     10026763.73      2682349.01     10027358.93
      2682468.54     10027844.26       2682402.2     10028180.61
      2682129.02     10028524.04      2682579.48     10029183.02
      2682984.67     10029408.43      2682629.59      10029705.3
      2682838.01     10029932.54      2682783.32     10030336.67
      2682648.42     10030423.63      2682278.77     10030374.41
      2682198.61     10030458.38      2682251.09     10030862.68
      2682505.63     10031434.88      2682596.97     10032088.16
      2682010.19     10032960.34       2681720.6     10033234.58
      2681702.21      10033521.5      2681896.15     10033758.16
       2682382.7     10033755.59      2682567.56     10033883.66
      2682886.14     10034414.79      2682888.47     10034733.73

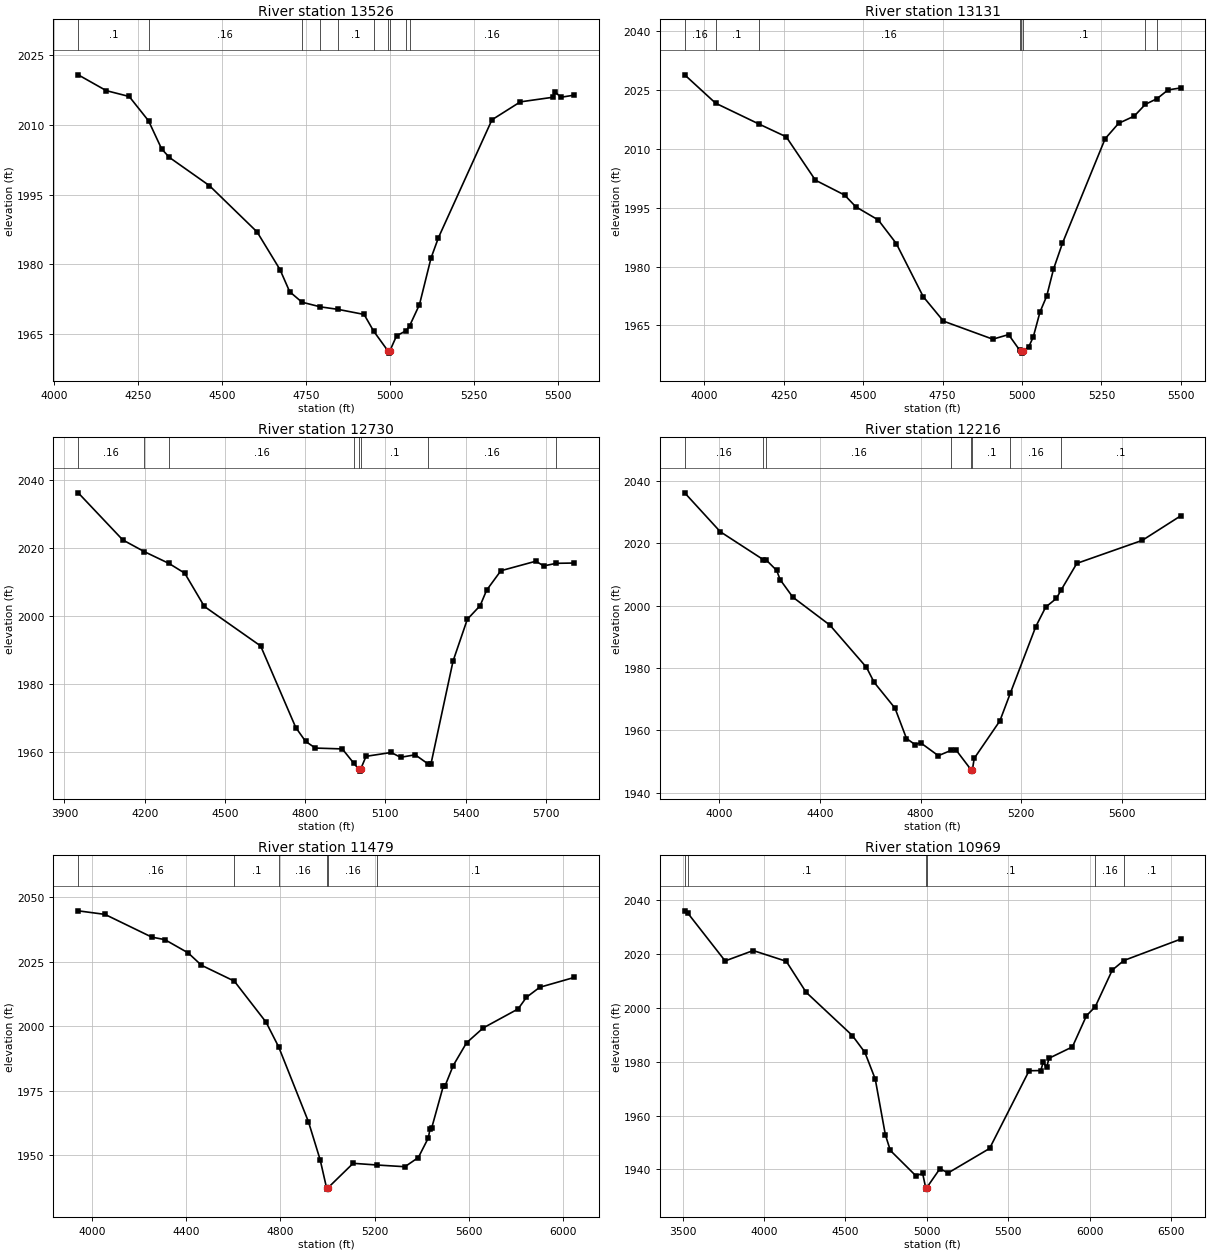
Type RM Length L Ch R = 1 ,13526   ,395,395,395
BEGIN DESCRIPTION:
UNT 1004 IN HEWA 27.0
END DESCRIPTION:
XS GIS Cut Line= 2
      2681096.79     10025222.29      2681728.73     10023888.97
#Sta/Elev= 30
  4072.7 2020.83  4156.2 2017.42  4224.4 2016.16    4282 2010.91  4320.9 2004.86
  4343.7 2003.04  4462.9 1996.95  4604.9 1986.96  4673.1 1978.84  4701.9 1974.07
  4738.4 1971.82  4793.5 1970.81  4845.1 1970.28  4923.2 1969.18  4951.7 1965.58
    4994 1961.34  4996.8 1960.84    5000 1961.34  5019.8 1964.56  5047.4 1965.64
  5058.4 1966.68    5088  1971.3  5122.4 1981.34  5144.5 1985.74  5303.7 2011.14
    5388    2015  5485.6    2016  5491.2 2017.17  5508.4 2015.99  5548.2 2016.45
#Mann= 10 ,-1 , 0
  4072.7      .1       0    4282     .16       0  4738.4      .1       0
  4793.5     .05       0  4845.1      .1       0  4951.7     .05       0
    4994    .035       0    5000     .05       0  5047.4      .1       0
  5058.4     .16       0
Bank Sta=4994,5000
XS Rating Curve= 0 ,0
Exp/Cntr=0.3,0.1

Type RM Length L Ch R = 1 ,13131   ,401,401,401
BEGIN DESCRIPTION:
UNT 1004 IN HEWA 26.0
END DESCRIPTION:
XS GIS Cut Line= 2
      2681082.93     10025340.29      2682180.12     10024229.22
#Sta/Elev= 30
  3937.9 2028.82  4035.2  2021.6  4171.5  2016.3  4257.5 2013.04  4349.5 2001.99
  4441.4  1998.2  4476.8 1995.21  4547.5 1991.85  4604.1 1985.86    4689 1972.32
  4752.6 1966.09  4908.1 1961.49  4957.7 1962.66  4992.3 1958.73  4997.1 1958.44
  4999.8 1957.94  5003.1 1958.44  5021.3 1959.56  5035.4 1962.04  5056.7 1968.43
  5077.8 1972.47  5099.1 1979.31  5127.4 1985.94  5261.7 2012.54  5304.1 2016.46
  5353.6 2018.32  5388.3  2021.3  5425.2 2022.75  5459.7 2024.97  5499.4 2025.48
#Mann= 8 ,-1 , 0
  3937.9     .16       0  4035.2      .1       0  4171.5     .16       0
  4992.3      .1       0  4997.1     .07       0  5003.1      .1       0
  5388.3      .1       0  5425.2     .16       0
Bank Sta=4997.1,5003.1
XS Rating Curve= 0 ,0
Exp/Cntr=0.3,0.1

Type RM Length L Ch R = 1 ,12730   ,514,514,514
BEGIN DESCRIPTION:
UNT 1004 IN HEWA 25.0
END DESCRIPTION:
XS GIS Cut Line= 3
       2681062.1     10025486.14      2682110.69     10024840.31
       2682346.8     10024263.92
#Sta/Elev= 30
  3951.4 2036.21  4117.8 2022.35  4198.4 2018.89    4291  2015.4  4349.6 2012.55
    4423 2002.75  4633.6  1991.1  4764.9 1967.08  4801.6    1963  4838.3 1961.03
  4938.8 1960.78  4982.2 1956.53  5001.1 1954.74  5003.9 1954.24  5007.1 1954.74
  5027.6  1958.6  5121.6 1959.73  5156.8 1958.31  5211.4 1959.05  5260.2 1956.33
  5270.2 1956.28    5353 1986.65  5406.4 1998.97  5454.4 2002.99  5478.4 2007.52
  5531.8 2013.26  5662.6 2016.07    5692 2014.68    5739 2015.45  5805.8 2015.53
#Mann= 8 ,-1 , 0
  3951.4     .16       0  4198.4      .1       0    4291     .16       0
  4982.2      .1       0  5001.1     .07       0  5007.1      .1       0
  5260.2     .16       0    5739      .1       0
Bank Sta=5001.1,5007.1
XS Rating Curve= 0 ,0
Exp/Cntr=0.3,0.1

Type RM Length L Ch R = 1 ,12216   ,737,737,737
BEGIN DESCRIPTION:
UNT 1004 IN HEWA 24.0
END DESCRIPTION:
XS GIS Cut Line= 3
      2681089.83     10025583.37      2682673.19     10025263.92
      2683004.98     10025132.59
#Sta/Elev= 30
  3861.8 2036.14  4003.2 2023.68  4173.9 2014.74  4185.5 2014.65  4227.7 2011.25
  4241.1 2008.33  4291.9 2002.68  4439.1 1993.73  4584.7 1980.18  4615.3 1975.36
  4698.2 1967.08  4743.8 1957.36  4778.5 1955.38  4799.7 1956.01  4870.4 1951.85
  4922.1 1953.59  4941.8 1953.58    5000  1947.4  5002.7  1946.9    5006  1947.4
  5013.2    1951  5115.2 1963.01  5156.5 1971.85    5258 1993.25  5297.4  1999.5
  5339.6 2002.26  5359.5 2005.08  5421.2 2013.52  5681.5  2020.9  5833.9 2028.74
#Mann= 8 ,-1 , 0
  3861.8     .16       0  4173.9      .1       0  4185.5     .16       0
  4922.1      .1       0    5000     .07       0    5006      .1       0
  5156.5     .16       0  5359.5      .1       0
Bank Sta=5000,5006
XS Rating Curve= 0 ,0
Exp/Cntr=0.3,0.1

Type RM Length L Ch R = 1 ,11479   ,510,510,510
BEGIN DESCRIPTION:
UNT 1004 IN HEWA 23.0
END DESCRIPTION:
XS GIS Cut Line= 4
      2681041.29     10025833.38      2681728.75     10026076.42
      2682402.36     10026048.64      2682894.43     10025542.71
#Sta/Elev= 30
  3939.9 2044.78  4053.6  2043.4  4252.9 2034.58  4308.1 2033.62  4407.4 2028.47
  4463.9 2023.68  4603.7 2017.52  4738.8  2001.6  4792.5 1991.99    4919    1963
    4969 1948.18    4996 1937.36  4998.8 1936.86    5002 1937.36  5109.1 1946.87
  5212.5  1946.2  5329.3 1945.55  5386.4 1949.12  5428.8 1956.71  5435.8 1960.06
    5443 1960.53  5492.4 1976.77  5499.6 1976.81  5534.8  1984.8  5591.4  1993.6
  5662.2 1999.36  5810.6 2006.73  5846.1 2011.25  5902.6 2015.13    6049 2018.94
#Mann= 6 ,-1 , 0
  3939.9     .16       0  4603.7      .1       0  4792.5     .16       0
    4996     .07       0    5002     .16       0  5212.5      .1       0
Bank Sta=4996,5002
XS Rating Curve= 0 ,0
Exp/Cntr=0.3,0.1

Type RM Length L Ch R = 1 ,10969   ,586,586,586
BEGIN DESCRIPTION:
UNT 1004 IN HEWA 21.0
END DESCRIPTION:
XS GIS Cut Line= 4
      2680819.01     10026173.64      2682089.86     10026638.92
      2682555.14     10026222.26      2683159.32     10025340.28
#Sta/Elev= 30
    3512 2035.95  3529.7 2035.21  3760.6 2017.36    3933 2021.21    4136 2017.23
  4258.1 2005.73    4542 1989.69  4618.9 1983.46  4682.8 1973.54  4744.9 1952.86
  4775.4 1947.06  4931.5  1937.7  4974.1  1938.5  4992.8  1933.2  4995.5  1932.7
  4998.8  1933.2  5080.2 1940.28  5130.3  1938.7  5385.3 1947.79    5628 1976.62
  5699.8 1976.69  5714.7 1979.75  5735.7 1977.91  5750.6 1981.26  5894.1 1985.47
  5980.7 1997.06  6034.3 2000.34  6139.1 2013.97    6210 2017.51    6559 2025.44
#Mann= 6 ,-1 , 0
    3512     .16       0  3529.7      .1       0  4992.8     .07       0
  4998.8      .1       0  6034.3     .16       0    6210      .1       0
Bank Sta=4992.8,4998.8
XS Rating Curve= 0 ,0
Exp/Cntr=0.3,0.1

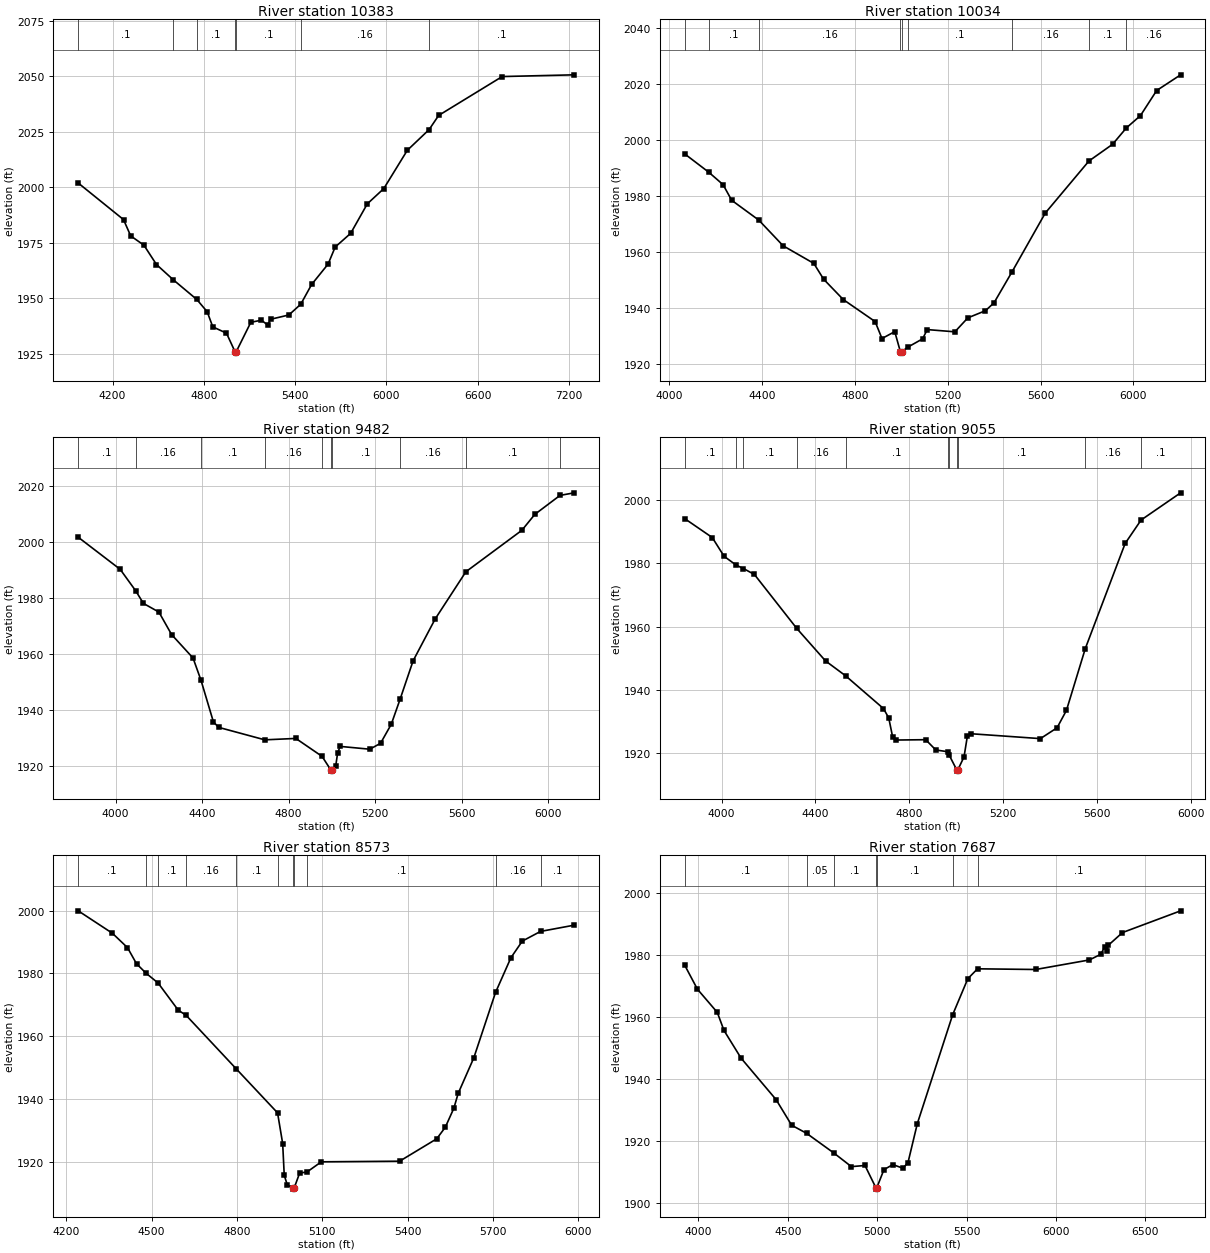
Type RM Length L Ch R = 1 ,10383   ,349,349,349
BEGIN DESCRIPTION:
UNT 1004 IN HEWA 20.0
END DESCRIPTION:
XS GIS Cut Line= 4
      2681339.81     10027263.93       2682159.3     10027055.59
      2682763.47     10027055.59      2684540.27     10026708.56
#Sta/Elev= 30
  3974.1 2001.88  4271.9 1985.39  4319.1 1978.04  4406.1 1973.84  4488.6 1965.13
  4599.7 1958.21  4753.6 1949.38  4821.7 1943.87  4858.8 1937.03  4948.8 1934.18
  5005.8 1925.69  5008.6 1925.19  5011.8 1925.69  5108.8 1939.09  5178.8 1940.04
  5218.8 1937.88  5238.8 1940.45  5358.8 1942.39  5437.1 1947.24  5508.5 1956.14
  5616.8 1965.34  5663.2    1973  5765.2  1979.2  5874.5 1992.49  5982.7 1999.35
  6137.4 2016.62  6280.7 2025.96  6343.6 2032.35  6761.2 2049.87  7234.2 2050.65
#Mann= 7 ,-1 , 0
  3974.1      .1       0  4599.7     .16       0  4753.6      .1       0
  5005.8     .07       0  5011.8      .1       0  5437.1     .16       0
  6280.7      .1       0
Bank Sta=5005.8,5011.8
XS Rating Curve= 0 ,0
Exp/Cntr=0.3,0.1

Type RM Length L Ch R = 1 ,10034   ,552,552,552
BEGIN DESCRIPTION:
UNT 1004 IN HEWA 19.0
END DESCRIPTION:
XS GIS Cut Line= 3
      2681450.93     10027616.36      2682774.75     10027303.85
      2683551.63     10027316.87
#Sta/Elev= 30
  4066.4 1995.01    4170 1988.46  4231.8 1984.01    4269 1978.41  4385.7 1971.33
  4490.8 1962.13  4622.9 1955.84  4665.2 1950.19  4749.8 1942.91    4887 1935.04
  4916.7 1928.97  4971.7 1931.44  4995.9 1924.25  4998.6 1923.75  5001.9 1924.25
  5027.6 1925.88  5091.4 1928.84  5111.9 1932.17  5230.7 1931.37  5286.6 1936.36
  5362.7 1938.93  5399.6 1941.76  5477.7 1952.91  5620.4 1973.85  5808.5 1992.46
  5910.4 1998.44    5970 2004.31  6030.4 2008.68  6100.4 2017.67  6203.6 2023.28
#Mann= 9 ,-1 , 0
  4066.4     .16       0    4170      .1       0  4385.7     .16       0
  4995.9     .07       0  5001.9     .16       0  5027.6      .1       0
  5477.7     .16       0  5808.5      .1       0    5970     .16       0
Bank Sta=4995.9,5001.9
XS Rating Curve= 0 ,0
Exp/Cntr=0.3,0.1

Type RM Length L Ch R = 1 ,9482    ,427,427,427
BEGIN DESCRIPTION:
UNT 1004 IN HEWA 18.0
END DESCRIPTION:
XS GIS Cut Line= 3
      2681303.38     10027668.43      2682957.05       10028020.
       2683560.3     10028024.34
#Sta/Elev= 30
  3827.1 2001.68  4021.2 1990.24  4092.8 1982.61  4128.8 1978.09  4200.3 1975.01
    4259    1967  4358.2 1958.64  4395.1 1950.69  4452.3 1935.91  4476.4 1933.93
  4690.2 1929.48  4833.7 1929.98  4954.9 1923.59  4994.8 1918.83  4997.5 1918.33
  5000.8 1918.83  5018.2 1920.18    5027 1924.82  5038.7 1927.14  5175.9 1926.14
  5225.5 1928.25  5275.1 1935.03  5316.7 1944.13  5376.1 1957.64  5478.3 1972.57
  5620.2 1989.37  5879.2 2004.15  5939.2 2009.83  6055.6 2016.58    6121  2017.5
#Mann= 10 ,-1 , 0
  3827.1      .1       0  4092.8     .16       0  4395.1      .1       0
  4690.2     .16       0  4954.9      .1       0  4994.8     .07       0
  5000.8      .1       0  5316.7     .16       0  5620.2      .1       0
  6055.6     .16       0
Bank Sta=4994.8,5000.8
XS Rating Curve= 0 ,0
Exp/Cntr=0.3,0.1

Type RM Length L Ch R = 1 ,9055    ,482,482,482
BEGIN DESCRIPTION:
UNT 1004 IN HEWA 17.0
END DESCRIPTION:
XS GIS Cut Line= 4
      2681281.73     10028562.52      2682128.05     10028145.87
      2682397.15     10028358.54      2683224.81     10028323.87
#Sta/Elev= 30
  3842.9  1994.2  3960.5 1988.21    4011 1982.27  4062.8 1979.45  4093.7 1978.38
  4140.2 1976.52  4320.7 1959.45  4443.4 1949.16  4528.8 1944.46  4690.6 1934.07
    4713 1931.11  4729.9 1924.99  4742.1 1924.11  4870.5 1924.22  4913.8 1920.96
  4964.1 1920.42  4970.6 1919.36  5002.2 1914.77  5004.9 1914.27  5008.2 1914.77
    5034 1918.77  5048.5 1925.44  5062.9 1926.11  5359.7 1924.56  5430.8 1927.99
  5470.8 1933.51  5551.2 1953.08    5721 1986.33    5789 1993.75  5957.6 2002.36
#Mann= 11 ,-1 , 0
  3842.9      .1       0  4062.8     .16       0  4093.7      .1       0
  4320.7     .16       0  4528.8      .1       0  4964.1     .05       0
  4970.6      .1       0  5002.2     .07       0  5008.2      .1       0
  5551.2     .16       0    5789      .1       0
Bank Sta=5002.2,5008.2
XS Rating Curve= 0 ,0
Exp/Cntr=0.3,0.1

Type RM Length L Ch R = 1 ,8573    ,886,886,886
BEGIN DESCRIPTION:
UNT 1004 IN HEWA 16.0
END DESCRIPTION:
XS GIS Cut Line= 3
      2681529.12     10028953.15      2682379.79      10028601.6
      2683200.06      10028536.5
#Sta/Elev= 30
  4242.1  1999.9  4362.1 1992.78  4415.3  1988.2    4447 1983.08  4480.1 1980.11
    4523 1976.94  4593.5 1968.34  4621.7 1966.65  4798.2  1949.6  4942.8 1935.67
  4960.8 1925.92  4966.3 1915.85  4977.2 1912.71  4995.8 1911.92  4998.6 1911.42
  5001.8 1911.92  5020.5 1916.54  5046.2 1916.86  5096.6  1920.1  5371.9  1920.3
  5502.3 1927.42  5532.4 1931.08  5562.5 1937.14  5577.7 1941.85  5632.7 1953.17
  5709.1 1973.96  5763.1 1984.99  5803.2 1990.28  5867.2 1993.35  5985.4 1995.34
#Mann= 11 ,-1 , 0
  4242.1      .1       0  4480.1     .16       0    4523      .1       0
  4621.7     .16       0  4798.2      .1       0  4942.8     .05       0
  4995.8    .035       0  5001.8     .05       0  5046.2      .1       0
  5709.1     .16       0  5867.2      .1       0
Bank Sta=4995.8,5001.8
XS Rating Curve= 0 ,0
Exp/Cntr=0.3,0.1

Type RM Length L Ch R = 1 ,7687    ,1089,1089,1089
BEGIN DESCRIPTION:
UNT 1004 IN HEWA 14.0
END DESCRIPTION:
XS GIS Cut Line= 4
      2681811.23     10028987.89      2682727.01      10029313.4
      2682957.05     10029074.69      2684133.22     10028193.64
#Sta/Elev= 30
  3923.6 1976.79    3995 1969.02  4105.8 1961.56  4143.5 1955.71  4239.1 1946.77
  4434.6 1933.41  4521.8 1925.14  4605.2 1922.53  4757.8 1916.17  4855.8 1911.78
  4931.7 1912.15  4992.2 1905.02    4995 1904.52  4998.2 1905.02  5037.7  1910.8
  5087.4 1912.44  5143.9 1911.27  5172.2 1913.08  5224.4 1925.65  5422.1  1960.8
  5506.9 1972.43  5561.1 1975.61  5886.1 1975.39  6186.2 1978.47  6250.8 1980.31
  6271.6 1982.67  6286.2 1981.46  6292.4 1983.21  6371.6 1987.31  6696.6 1994.32
#Mann= 7 ,-1 , 0
  3923.6      .1       0  4605.2     .05       0  4757.8      .1       0
  4992.2     .07       0  4998.2      .1       0  5422.1     .16       0
  5561.1      .1       0
Bank Sta=4992.2,4998.2
XS Rating Curve= 0 ,0
Exp/Cntr=0.3,0.1

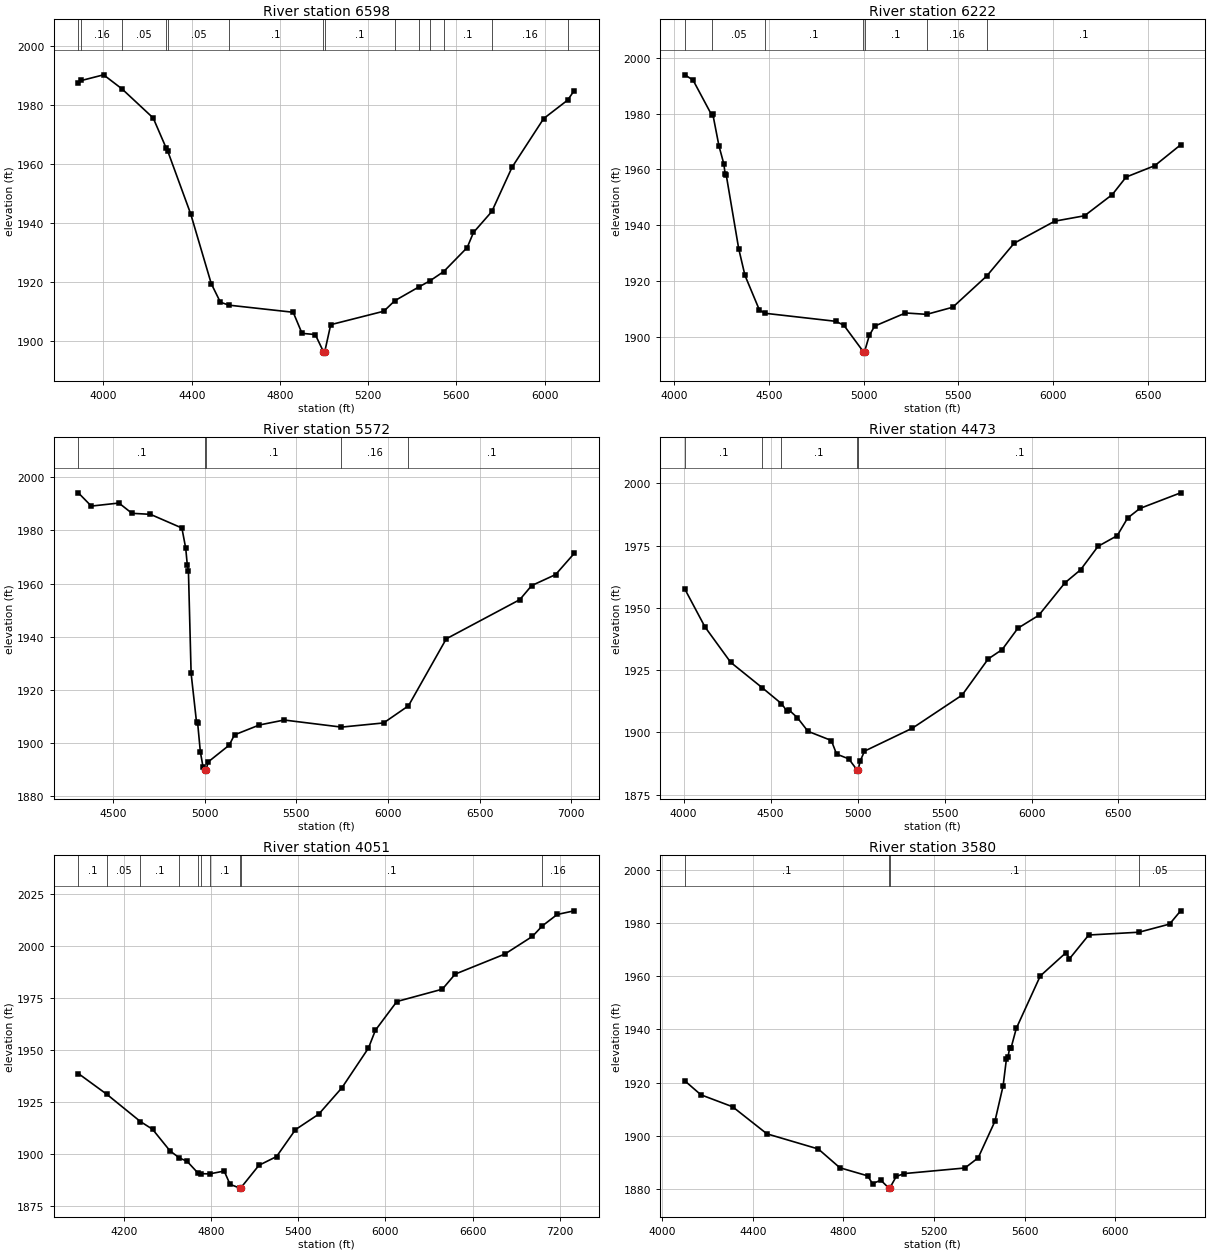
Type RM Length L Ch R = 1 ,6598    ,376,376,376
BEGIN DESCRIPTION:
UNT 1004 IN HEWA 12.0
END DESCRIPTION:
XS GIS Cut Line= 4
      2681785.15      10029628.5      2682654.96     10029959.24
      2683016.94     10029946.21      2683883.84     10029545.31
#Sta/Elev= 30
    3886 1987.28  3900.3 1988.26  4000.5 1990.18  4083.7 1985.42  4225.4 1975.54
  4284.8 1965.24  4290.9 1964.39  4395.4 1942.99  4488.7 1919.32    4530 1913.04
  4569.1 1912.04  4860.1 1909.63  4900.1 1902.48  4960.2 1902.07  4997.2 1896.27
  4999.9 1895.77  5003.2 1896.27  5030.2 1905.42  5271.1 1909.99  5320.5 1913.54
  5431.5 1918.29  5480.2  1920.3  5542.4 1923.43    5649 1931.59  5677.4  1936.7
  5760.7 1943.82  5852.5 1958.85  5995.8 1975.35  6104.4  1981.6  6133.9 1984.81
#Mann= 14 ,-1 , 0
    3886      .1       0  3900.3     .16       0  4083.7     .05       0
  4284.8      .1       0  4290.9     .05       0  4569.1      .1       0
  4997.2     .07       0  5003.2      .1       0  5320.5     .16       0
  5431.5      .1       0  5480.2     .16       0  5542.4      .1       0
  5760.7     .16       0  6104.4      .1       0
Bank Sta=4997.2,5003.2
XS Rating Curve= 0 ,0
Exp/Cntr=0.3,0.1

Type RM Length L Ch R = 1 ,6222    ,650,650,650
BEGIN DESCRIPTION:
UNT 1004 IN HEWA 11.0
END DESCRIPTION:
XS GIS Cut Line= 4
      2681991.32     10029876.33      2682519.11     10030036.06
        2683033.       10030543.      2684352.44       10030793.
#Sta/Elev= 30
  4056.7 1993.98  4100.1  1992.1    4199 1979.51  4204.1    1980  4237.1 1968.41
  4262.7 1961.99    4270  1958.2  4275.2 1958.08  4341.1 1931.57    4374    1922
  4450.7 1909.49  4479.6 1908.38  4853.5 1905.49    4896 1904.08    4999 1894.57
  5001.7 1894.07    5005 1894.57  5030.3 1900.43  5058.6 1903.78  5221.2 1908.49
  5332.9 1907.99  5470.6 1910.55  5650.3 1921.79  5794.6 1933.53  6008.9 1941.45
  6165.8 1943.38  6312.6 1951.01  6385.2 1957.28  6536.5 1961.37  6672.9 1968.85
#Mann= 7 ,-1 , 0
  4056.7      .1       0    4199     .05       0  4479.6      .1       0
    4999     .07       0    5005      .1       0  5332.9     .16       0
  5650.3      .1       0
Bank Sta=4999,5005
XS Rating Curve= 0 ,0
Exp/Cntr=0.3,0.1

Type RM Length L Ch R = 1 ,5572    ,1099,1099,1099
BEGIN DESCRIPTION:
UNT 1004 IN HEWA 9.0
END DESCRIPTION:
XS GIS Cut Line= 3
      2681664.93     10030008.27      2682414.95     10030549.95
      2684114.87     10031077.27
#Sta/Elev= 30
  4310.6  1994.2  4381.3  1989.2  4532.1 1990.35  4603.3 1986.47  4703.9 1986.09
  4875.6 1980.93  4896.5 1973.28    4905 1967.04  4911.2 1964.84  4925.9  1926.1
  4955.3 1907.77  4961.5 1907.43  4976.2 1896.59  4990.9 1890.79  5002.6 1889.75
  5005.4 1889.25  5008.6 1889.75  5018.1 1892.67  5133.2 1899.02  5162.7 1902.93
  5298.1 1906.65  5433.7 1908.52  5746.2 1905.85  5975.9 1907.42  6111.6 1913.88
  6317.9 1939.14  6718.9 1953.91    6784 1959.23  6914.4 1963.37  7015.6 1971.33
#Mann= 5 ,-1 , 0
  4310.6      .1       0  5002.6     .07       0  5008.6      .1       0
  5746.2     .16       0  6111.6      .1       0
Bank Sta=5002.6,5008.6
XS Rating Curve= 0 ,0
Exp/Cntr=0.3,0.1

Type RM Length L Ch R = 1 ,4473    ,422,422,422
BEGIN DESCRIPTION:
UNT 1004 IN HEWA 7.0
END DESCRIPTION:
XS GIS Cut Line= 4
       2681560.8     10031140.23      2682276.06     10031424.95
      2682894.11     10031383.28      2684352.42     10031473.56
#Sta/Elev= 30
  4006.8 1957.55  4122.7 1942.34  4270.6 1928.13  4452.8 1917.88  4562.1 1911.58
  4594.2  1908.6    4607 1908.91  4653.6 1905.96  4714.7 1900.46  4849.2 1896.76
  4879.3 1891.31  4949.4 1889.39  4996.6 1884.97  4999.3 1884.47  5002.6 1884.97
  5016.2 1888.65  5039.6 1892.48  5315.2 1901.71  5600.8 1914.97  5751.1  1929.5
  5831.3 1933.25  5921.5 1941.81  6041.7    1947    6192 1960.02  6282.1 1965.27
  6382.3 1974.67  6492.6 1978.96  6552.7 1986.05  6622.8 1989.87  6857.2 1996.15
#Mann= 5 ,-1 , 0
  4006.8      .1       0  4452.8     .05       0  4562.1      .1       0
  4996.6     .07       0  5002.6      .1       0
Bank Sta=4996.6,5002.6
XS Rating Curve= 0 ,0
Exp/Cntr=0.3,0.1

Type RM Length L Ch R = 1 ,4051    ,471,471,471
BEGIN DESCRIPTION:
UNT 1004 IN HEWA 6.0
END DESCRIPTION:
XS GIS Cut Line= 4
      2681539.91     10031459.65      2682289.95     10031827.72
      2683192.72     10031786.06      2684864.92     10031869.32
#Sta/Elev= 30
  3886.1 1938.56  4083.2  1928.5  4313.6 1915.43  4396.9 1911.73  4516.7 1901.37
  4581.4 1897.93  4634.7 1896.31  4707.1 1890.85  4731.4 1890.34  4790.5 1890.25
  4890.3 1891.61  4930.3 1885.24  4997.4 1883.41  5000.2 1882.91  5003.4 1883.41
  5129.5 1894.38  5250.7 1898.58  5380.8 1911.54    5541 1918.99  5701.2 1931.74
  5883.3 1950.79  5931.4  1959.4  6078.9 1973.21    6392 1979.15  6480.3  1986.4
  6822.6 1996.06  7012.8 2004.59  7080.4 2009.62    7183 2015.12  7299.6 2016.87
#Mann= 10 ,-1 , 0
  3886.1      .1       0  4083.2     .05       0  4313.6      .1       0
  4581.4     .16       0  4707.1      .1       0  4731.4     .16       0
  4790.5      .1       0  4997.4     .07       0  5003.4      .1       0
  7080.4     .16       0
Bank Sta=4997.4,5003.4
XS Rating Curve= 0 ,0
Exp/Cntr=0.3,0.1

Type RM Length L Ch R = 1 ,3580    ,577,577,577
BEGIN DESCRIPTION:
UNT 1004 IN HEWA 5.0
END DESCRIPTION:
XS GIS Cut Line= 3
      2681727.42     10031786.05      2682921.89     10032501.34
      2683553.64      10032987.3
#Sta/Elev= 30
    4100 1920.64  4171.1 1915.38    4311 1910.87  4462.5 1900.67  4689.5 1894.95
  4784.8 1887.87  4907.3 1884.83  4928.8 1881.89  4965.6 1883.18  4999.6 1880.32
  5002.3 1879.82  5005.6 1880.32  5033.7  1884.6  5068.7 1885.68    5337 1887.79
  5395.4 1891.62  5469.3 1905.39  5505.6 1918.79  5520.1 1928.87  5526.4 1929.45
  5534.6 1933.05    5541 1933.16  5563.6 1940.39  5669.6 1960.18  5783.8 1969.01
  5798.3 1966.63  5883.5 1975.61  6105.6 1976.67  6240.5 1979.73  6289.3 1984.73
#Mann= 4 ,-1 , 0
    4100      .1       0  4999.6     .07       0  5005.6      .1       0
  6105.6     .05       0
Bank Sta=4999.6,5005.6
XS Rating Curve= 0 ,0
Exp/Cntr=0.3,0.1

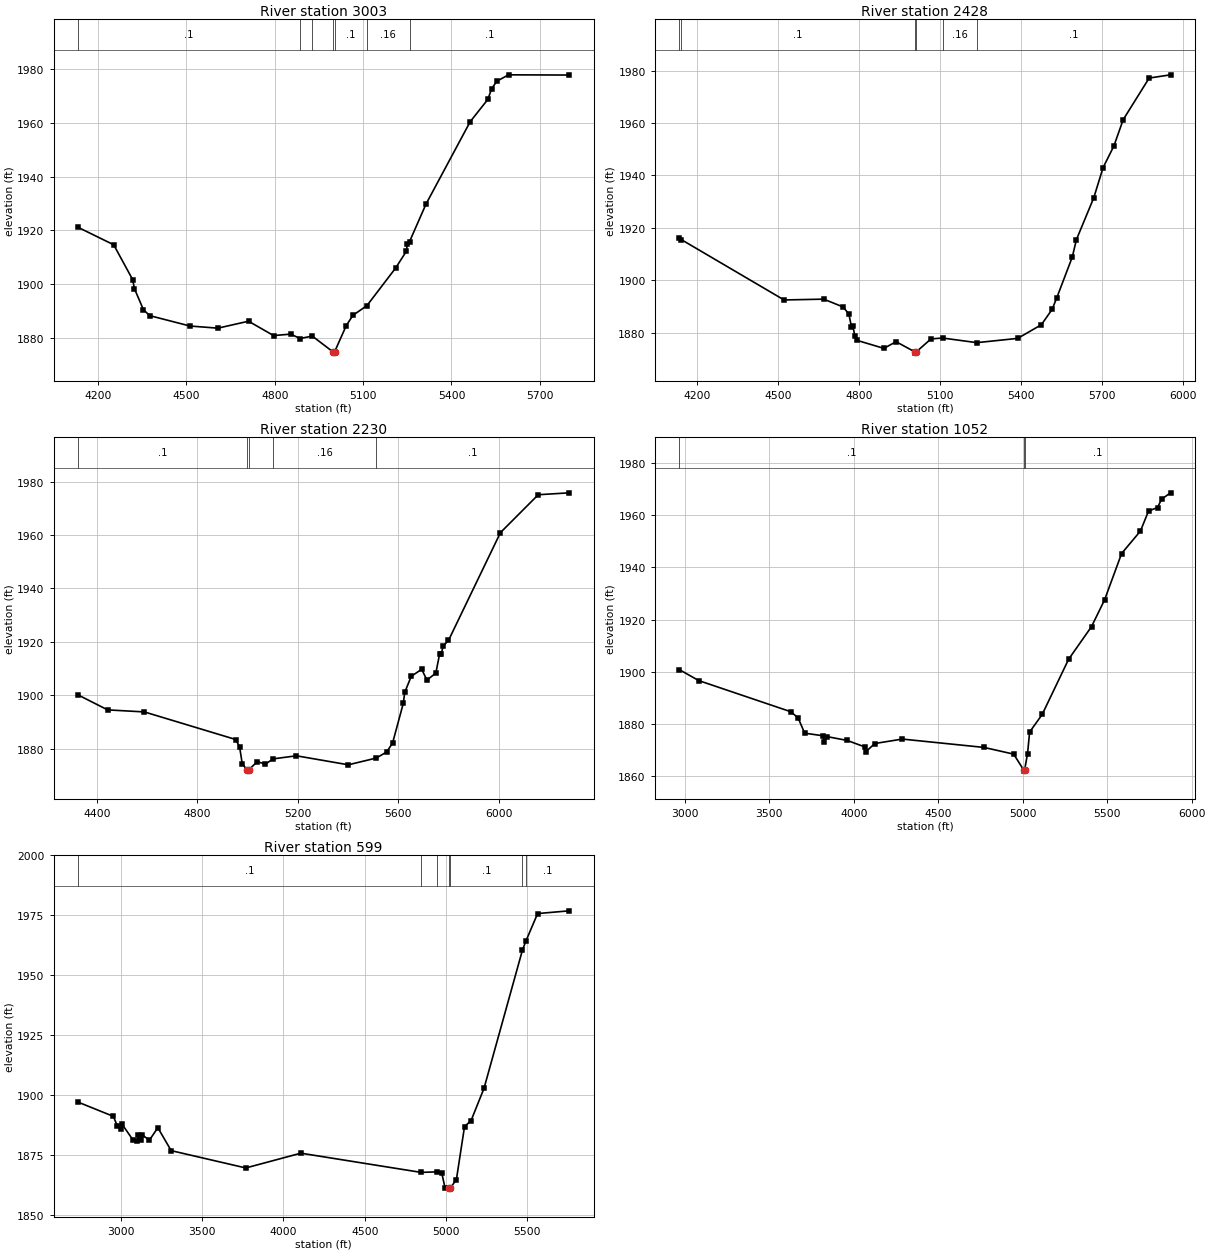
Type RM Length L Ch R = 1 ,3003    ,575,575,575
BEGIN DESCRIPTION:
UNT 1004 IN HEWA 4.0
END DESCRIPTION:
XS GIS Cut Line= 3
       2681435.8     10032251.35      2682387.17     10032841.61
      2682934.59     10032855.47
#Sta/Elev= 30
  4132.5 1921.15  4253.3 1914.68  4317.6 1901.77  4323.9 1898.34  4354.3 1890.57
  4375.5 1888.37  4512.5 1884.51    4607 1883.72    4711  1886.3    4796 1880.97
  4853.9  1881.5  4886.3 1879.88  4927.4 1880.78  4997.3 1874.95  5000.1 1874.45
  5003.3 1874.95  5042.8 1884.68  5065.3 1888.48  5113.1 1892.11  5210.6 1906.08
  5247.2 1912.35  5249.9 1915.07  5257.6 1915.86  5313.4 1929.78  5463.5 1960.39
  5523.5 1968.68  5535.9 1972.52  5553.5 1975.38  5593.5 1977.78  5799.7  1977.7
#Mann= 7 ,-1 , 0
  4132.5      .1       0  4886.3     .16       0  4927.4      .1       0
  4997.3     .07       0  5003.3      .1       0  5113.1     .16       0
  5257.6      .1       0
Bank Sta=4997.3,5003.3
XS Rating Curve= 0 ,0
Exp/Cntr=0.3,0.1

Type RM Length L Ch R = 1 ,2428    ,394,394,394
BEGIN DESCRIPTION:
UNT 1004 IN HEWA 2.0
END DESCRIPTION:
XS GIS Cut Line= 4
      2681324.66      10032466.6        2681533.     10032959.67
      2681963.56     10033244.39      2682705.04     10033043.43
#Sta/Elev= 30
  4134.4 1916.02  4141.3 1915.52  4522.1 1892.47  4669.2 1892.78  4741.3 1889.77
  4762.4 1887.04  4771.5 1882.33  4777.4 1882.54  4784.1 1878.72  4792.5 1877.04
    4892 1873.98    4937 1876.54  5006.2 1872.67  5008.9 1872.17  5012.2 1872.67
  5066.3 1877.59  5109.2 1877.94  5236.4 1876.17  5387.8  1877.8  5475.5 1883.02
  5515.3 1888.88  5532.9  1893.4  5589.8 1908.81  5605.4 1915.54  5669.5 1931.46
  5704.1    1943    5744 1951.23  5778.6 1961.31  5874.8 1977.19  5954.1 1978.42
#Mann= 6 ,-1 , 0
  4134.4     .05       0  4141.3      .1       0  5006.2     .07       0
  5012.2      .1       0  5109.2     .16       0  5236.4      .1       0
Bank Sta=5006.2,5012.2
XS Rating Curve= 0 ,0
Exp/Cntr=0.3,0.1

Type RM Length L Ch R = 1 ,2230    ,1178,1178,1178
BEGIN DESCRIPTION:
Mapping XS 24f00a88
END DESCRIPTION:
XS GIS Cut Line= 4
      2681396.76     10032720.27       2681643.3     10033286.28
      2682334.27       10033446.      2682841.24     10033074.46
#Sta/Elev= 30
  4325.2 1900.15  4442.8 1894.55  4588.9 1893.79  4953.2 1883.45  4968.4 1880.52
  4978.7 1874.33  4998.1 1872.13  5000.8 1871.63  5004.1 1872.13  5038.7 1875.16
    5071 1874.25  5101.4 1876.21  5194.2 1877.37    5401    1874    5512 1876.52
  5553.4 1878.78  5577.1 1882.17  5619.8 1897.04  5625.3 1901.08  5651.4 1907.13
  5692.9 1909.75  5713.8 1905.69  5749.3 1908.35    5764 1915.35  5770.2 1915.33
  5778.6 1918.49  5799.5 1920.53  6006.4  1960.9  6156.9 1975.08  6280.3 1975.79
#Mann= 5 ,-1 , 0
  4325.2      .1       0  4998.1     .07       0  5004.1      .1       0
  5101.4     .16       0    5512      .1       0
Bank Sta=4998.1,5004.1
XS Rating Curve= 0 ,0
Exp/Cntr=0.3,0.1

Type RM Length L Ch R = 1 ,1052    ,453,453,453
BEGIN DESCRIPTION:
Mapping XS daaa3331
END DESCRIPTION:
XS GIS Cut Line= 4
      2681362.04     10032720.28      2681858.58     10033987.67
      2682622.47     10033800.17      2682913.08     10033097.86
#Sta/Elev= 30
  2967.3 1900.79  3082.3  1896.6    3625 1884.72  3669.1 1882.42    3709 1876.46
  3817.6 1875.47  3822.9 1872.98  3840.9 1875.15  3961.3 1873.67  4064.4  1871.2
  4069.8 1869.29  4124.1  1872.5  4286.9  1874.2  4771.1    1871  4946.2 1868.43
    5005 1862.42  5007.7 1861.92    5011 1862.42  5028.5 1868.65  5040.6 1876.89
    5115 1883.63  5271.3 1904.76  5407.1  1917.3  5484.2 1927.51  5585.2 1945.31
    5697 1953.94  5744.8 1961.61    5798 1962.91  5821.9 1966.14  5875.1 1968.56
#Mann= 3 ,-1 , 0
  2967.3      .1       0    5005     .07       0    5011      .1       0
Bank Sta=5005,5011
XS Rating Curve= 0 ,0
Exp/Cntr=0.3,0.1

Type RM Length L Ch R = 1 ,599     ,0,0,0
BEGIN DESCRIPTION:
UNT 1004 IN HEWA 1.0
END DESCRIPTION:
XS GIS Cut Line= 4
      2681326.75     10032879.65      2681912.68     10034216.43
      2682984.72     10034203.41      2683344.21     10034532.57
#Sta/Elev= 30
  2738.2 1897.14  2954.9 1891.21  2978.3 1887.37  3001.6 1885.95  3007.1 1888.05
  3077.2 1881.21  3100.6 1880.85    3106 1883.56    3124 1881.16  3129.4 1883.64
  3176.2 1881.25  3228.4 1886.47  3310.4 1876.91    3769 1869.69  4107.5 1875.85
  4846.6 1867.84  4945.3 1868.07  4973.6  1867.6  4993.6 1861.46  5020.6 1861.36
  5023.4 1860.86  5026.6 1861.36  5063.6 1864.84  5113.6 1886.96  5153.6  1889.4
  5233.6 1902.95  5469.2 1960.45  5490.1 1964.19  5562.8 1975.78  5757.3 1976.92
#Mann= 7 ,-1 , 0
  2738.2      .1       0  4846.6     .05       0  4945.3      .1       0
  5020.6     .07       0  5026.6      .1       0  5469.2     .16       0
  5490.1      .1       0
Bank Sta=5020.6,5026.6
XS Rating Curve= 0 ,0
Exp/Cntr=0.3,0.1

Chan Stop Cuts=-1
Use User Specified Reach Order=0
Composite Channel Slope=5