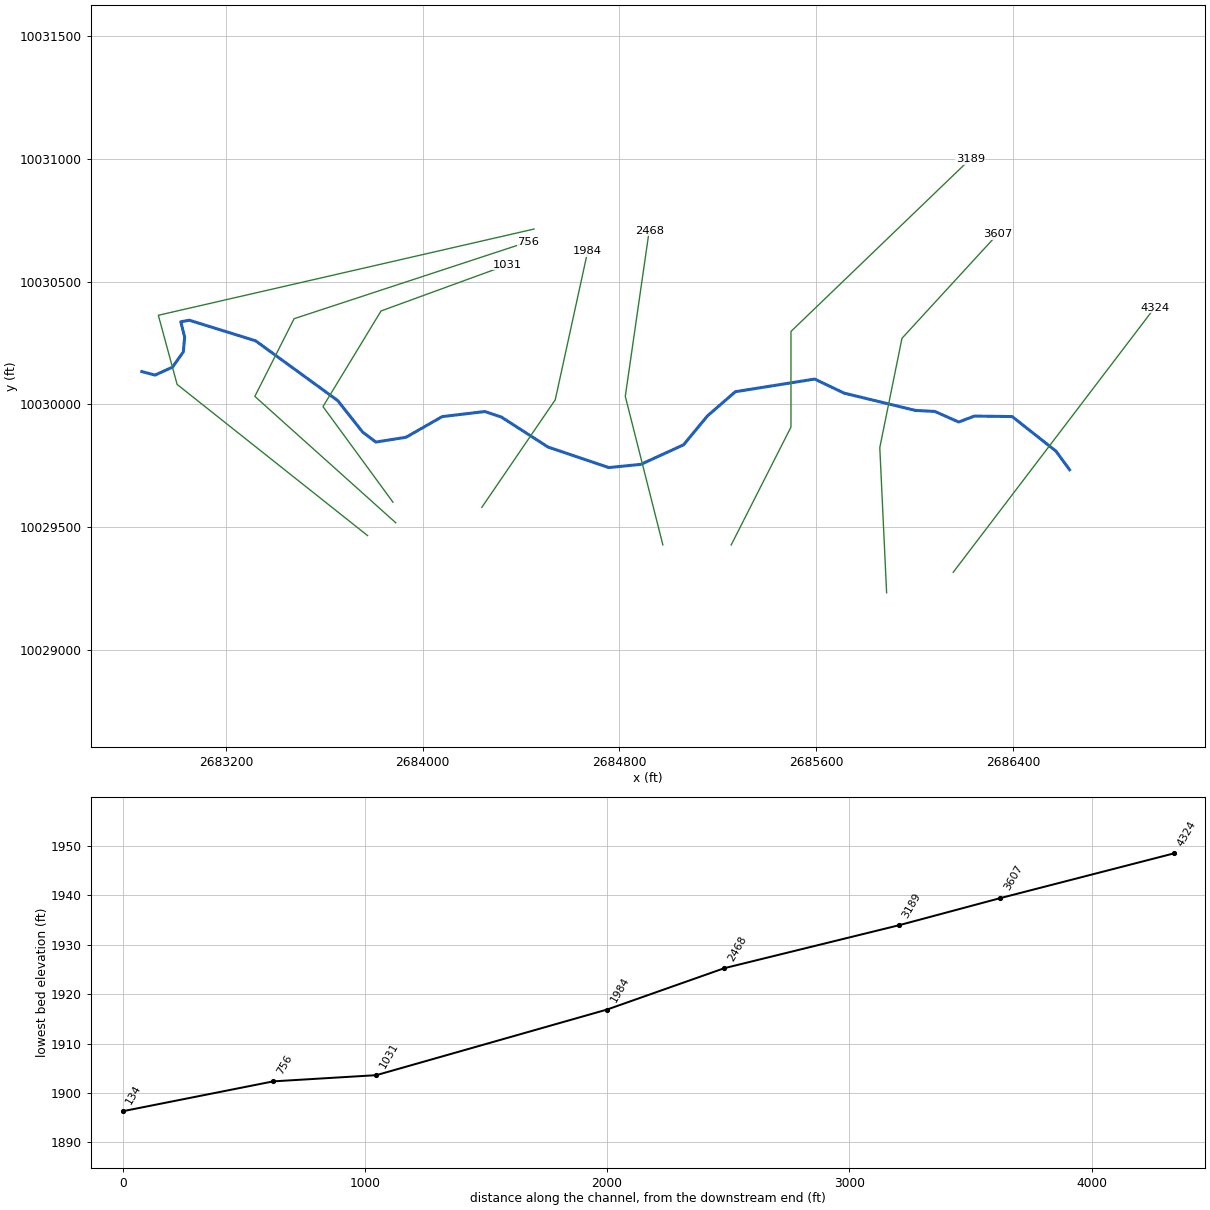
--- UNT 1005 IN HEWA.prj (project) ---

Proj Title=UNT 1005 IN HEWA Base Level Engineering
Current Plan=p01
Default Exp/Contr=0.3,0.1
English Units
Geom File=g01
Flow File=f01
Plan File=p01
Y Axis Title=Elevation
X Axis Title(PF)=Main Channel Distance
X Axis Title(XS)=Station
BEGIN DESCRIPTION:
UNT 1005 IN HEWA
END DESCRIPTION:
DSS Export Rating Curves= 0
DSS Export Rating Curve Sorted= 0
DSS Export Volume Flow Curves= 0
DXF OffsetX= 0
DXF OffsetY= 0
DXF ScaleX= 1
DXF ScaleY= 10

--- UNT 1005 IN HEWA.p01 (plan) ---

Plan Title=Multiple Run
Short Identifier=Multiple
Geom File=g01
Flow File=f01
Subcritical Flow
K Sum by GR= 0
Std Step Tol= 0.01
Critical Tol= 0.01
Num of Std Step Trials= 20
Max Error Tol= 0.3
Flow Tol Ratio= 0.001
Split Flow NTrial= 30
Split Flow Tol= 0.02
Split Flow Ratio= 0.02
Log Output Level= 0
Friction Slope Method= 1
Unsteady Friction Slope Method= 2
Unsteady Bridges Friction Slope Method= 1
Parabolic Critical Depth
Global Vel Dist=  1 , 1 , 1
Global Log Level= 0
CheckData=True
Encroach Param= -1, 0, 0, 0
BEGIN DESCRIPTION:
Multiple Run
END DESCRIPTION:

--- UNT 1005 IN HEWA.f01 (steady flow) ---

Flow Title=Multiple
Program Version=4.10
Number of Profiles= 7
Profile Names=10-year,25-year,50-year,1pct_min,100-year,1pct_plu,500-year
River Rch & RM=UNT 1005 IN HEWA,Reach-1         ,4324
    1360    2000    2558    2384    3225    4361    5123
Boundary for River Rch & Prof#=UNT 1005 IN HEWA,Reach-1         , 1
Up Type= 0
Dn Type= 3
Dn Slope=0.01
Boundary for River Rch & Prof#=UNT 1005 IN HEWA,Reach-1         , 2
Up Type= 0
Dn Type= 3
Dn Slope=0.01
Boundary for River Rch & Prof#=UNT 1005 IN HEWA,Reach-1         , 3
Up Type= 0
Dn Type= 3
Dn Slope=0.01
Boundary for River Rch & Prof#=UNT 1005 IN HEWA,Reach-1         , 4
Up Type= 0
Dn Type= 3
Dn Slope=0.01
Boundary for River Rch & Prof#=UNT 1005 IN HEWA,Reach-1         , 5
Up Type= 0
Dn Type= 3
Dn Slope=0.01
Boundary for River Rch & Prof#=UNT 1005 IN HEWA,Reach-1         , 6
Up Type= 0
Dn Type= 3
Dn Slope=0.01
Boundary for River Rch & Prof#=UNT 1005 IN HEWA,Reach-1         , 7
Up Type= 0
Dn Type= 3
Dn Slope=0.01
DSS Import GetInterval= 0
DSS Import GetPeak= 0
DSS Import FillOption= 0

--- UNT 1005 IN HEWA.g01 (geometry) ---

Geom Title=Existing Conditions
Program Version=4.10

River Reach=UNT 1005 IN HEWA,Reach-1
Reach XY= 30
      2686630.58     10029734.63      2686575.12     10029810.37
      2686397.19     10029950.81      2686243.75     10029952.78
      2686179.53     10029928.59       2686082.9     10029971.69
      2686004.02     10029975.71      2685714.39     10030045.96
      2685594.06      10030103.3      2685271.82     10030051.91
      2685158.56     10029953.76      2685061.18     10029835.95
      2684887.35     10029756.43      2684756.89     10029743.39
      2684509.85     10029827.06      2684320.97      10029948.5
      2684253.06     10029971.21      2684079.75     10029950.63
      2683932.46     10029866.54      2683809.98     10029847.11
      2683756.27     10029887.69      2683654.71     10030016.04
      2683321.15     10030258.83      2683051.79     10030342.45
      2683017.06     10030336.25      2683032.53     10030273.99
      2683027.37     10030214.27      2682983.28     10030151.83
      2682912.29     10030119.45      2682858.47     10030133.73

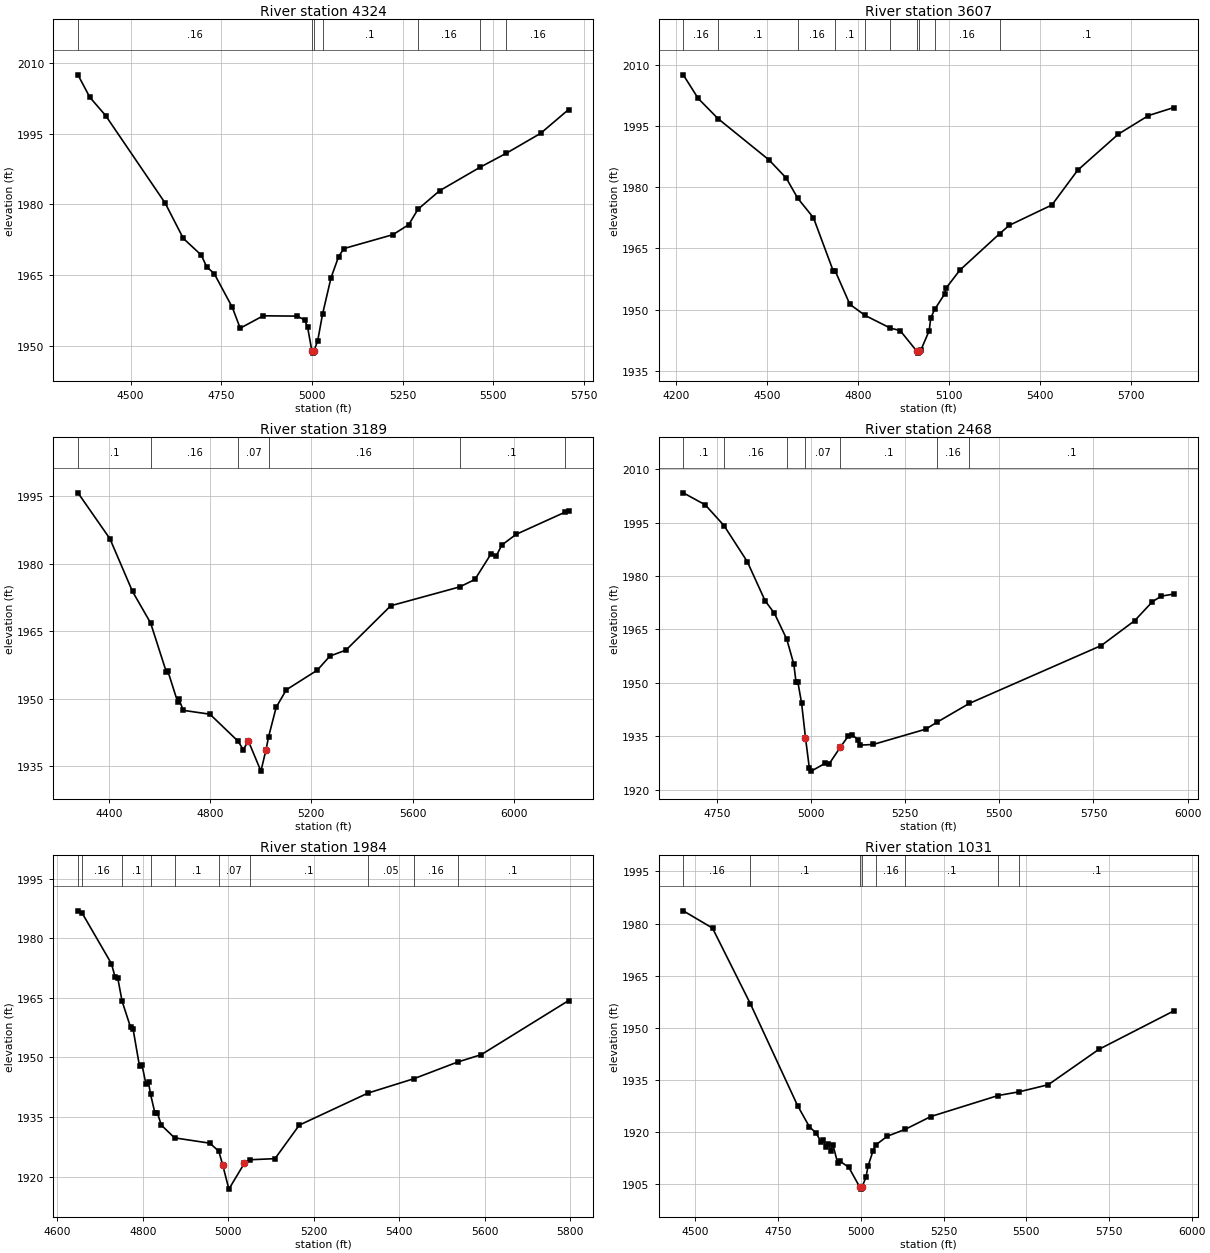
Type RM Length L Ch R = 1 ,4324    ,717,717,717
BEGIN DESCRIPTION:
UNT 1005 IN HEWA 9.0
END DESCRIPTION:
XS GIS Cut Line= 2
      2686157.55     10029317.72      2686976.99      10030394.1
#Sta/Elev= 30
  4354.6 2007.47  4387.3 2002.71  4430.8 1998.84  4595.1 1980.26    4645 1972.78
  4694.9 1969.21  4709.4 1966.74  4730.2 1965.32  4780.1 1958.16    4802 1953.72
  4865.4 1956.35  4958.9 1956.28  4979.7 1955.48    4988 1953.89  4999.5 1948.93
  5002.3 1948.43  5005.5 1948.93  5015.7 1951.06    5029 1956.69  5052.4 1964.42
  5073.3  1968.9  5087.8 1970.61    5223 1973.56  5266.6 1975.68    5292 1978.94
  5351.8 1982.88  5462.9 1987.84  5535.9 1990.84  5630.4 1995.06  5707.4  2000.1
#Mann= 7 ,-1 , 0
  4354.6     .16       0  4999.5     .07       0  5005.5     .16       0
    5029      .1       0    5292     .16       0  5462.9      .1       0
  5535.9     .16       0
Bank Sta=4999.5,5005.5
XS Rating Curve= 0 ,0
Exp/Cntr=0.3,0.1

Type RM Length L Ch R = 1 ,3607    ,418,418,418
BEGIN DESCRIPTION:
UNT 1005 IN HEWA 8.0
END DESCRIPTION:
XS GIS Cut Line= 4
      2685886.73     10029234.41      2685858.96     10029824.69
      2685949.23     10030269.13      2686338.12     10030692.74
#Sta/Elev= 30
    4223  2007.5  4272.4 2001.71    4338 1996.76  4506.4 1986.65  4562.7 1982.25
  4600.8  1977.3  4652.8 1972.52  4717.9 1959.53  4724.4 1959.53  4772.9 1951.34
  4822.9 1948.63  4906.7 1945.51  4938.8 1944.92  4993.6 1939.89  4996.4 1939.39
  4999.6 1939.89  5006.8 1940.04  5034.9  1944.9    5040 1948.04  5053.1 1950.11
  5085.6 1953.84  5090.7 1955.32  5136.2 1959.71  5266.9 1968.59  5298.7 1970.65
  5439.9 1975.65    5525 1984.16  5659.4    1993  5758.6 1997.53  5842.5  1999.5
#Mann= 10 ,-1 , 0
    4223     .16       0    4338      .1       0  4600.8     .16       0
  4724.4      .1       0  4822.9     .16       0  4906.7      .1       0
  4993.6     .07       0  4999.6      .1       0  5053.1     .16       0
  5266.9      .1       0
Bank Sta=4993.6,4999.6
XS Rating Curve= 0 ,0
Exp/Cntr=0.3,0.1

Type RM Length L Ch R = 1 ,3189    ,721,721,721
BEGIN DESCRIPTION:
UNT 1005 IN HEWA 7.0
END DESCRIPTION:
XS GIS Cut Line= 4
      2685254.79     10029428.86      2685497.85     10029908.02
      2685497.85     10030296.91        2686227.     10030998.29
#Sta/Elev= 30
  4278.5 1995.76  4404.9 1985.54    4494 1973.84  4565.5 1966.84  4627.6 1955.94
  4633.2 1956.23  4672.1 1949.31  4677.7 1949.83  4694.4 1947.42  4799.8 1946.56
  4911.5 1940.53  4931.5 1938.66  4951.5 1940.64  5001.2 1933.91  5021.5  1938.7
  5031.5 1941.54  5061.5  1948.1  5101.5 1951.98    5224 1956.35  5273.7 1959.48
  5337.2 1960.81    5514 1970.66  5786.2 1974.85  5846.4  1976.5  5910.2  1982.2
  5931.3  1981.8  5952.6 1984.15  6009.2 1986.53  6201.3 1991.43  6216.4 1991.66
#Mann= 6 ,-1 , 0
  4278.5      .1       0  4565.5     .16       0  4911.5     .07       0
  5031.5     .16       0  5786.2      .1       0  6201.3     .16       0
Bank Sta=4951.5,5021.5
XS Rating Curve= 0 ,0
Exp/Cntr=0.3,0.1

Type RM Length L Ch R = 1 ,2468    ,484,484,484
BEGIN DESCRIPTION:
UNT 1005 IN HEWA 5.0
END DESCRIPTION:
XS GIS Cut Line= 3
      2684977.01     10029428.88      2684824.23     10030033.02
      2684921.45     10030706.58
#Sta/Elev= 30
  4659.9 2003.33  4718.4 1999.95  4768.2 1994.13  4829.9 1984.05  4877.3 1973.05
  4902.1 1969.52  4934.9 1962.26  4953.7 1955.24  4959.4 1950.33  4964.5 1950.19
  4974.4 1944.26  4984.7 1934.57    4995 1926.04  5000.1 1925.23  5036.2 1927.39
  5046.6  1927.1  5077.3 1931.96  5098.1 1935.02  5108.4 1935.44  5123.5  1934.1
  5129.1 1932.52  5164.5 1932.71    5304    1937  5334.3 1938.96  5419.8 1944.22
  5770.8 1960.48  5859.7 1967.48  5906.4 1972.77  5930.4 1974.35  5963.6 1974.92
#Mann= 7 ,-1 , 0
  4659.9      .1       0  4768.2     .16       0  4934.9      .1       0
  4984.7     .07       0  5077.3      .1       0  5334.3     .16       0
  5419.8      .1       0
Bank Sta=4984.7,5077.3
XS Rating Curve= 0 ,0
Exp/Cntr=0.3,0.1

Type RM Length L Ch R = 1 ,1984    ,953,953,953
BEGIN DESCRIPTION:
UNT 1005 IN HEWA 4.0
END DESCRIPTION:
XS GIS Cut Line= 3
      2684240.92     10029581.65      2684539.51     10030019.13
      2684671.46     10030623.32
#Sta/Elev= 30
    4648  1986.9  4658.3 1986.24  4726.3 1973.62  4735.2 1970.13  4741.3  1969.9
  4751.3 1964.16  4771.1 1957.61  4777.2 1957.04  4792.1 1947.77  4798.1 1948.06
    4807 1943.32  4813.1 1943.75  4817.9 1940.75    4828 1936.07    4834 1936.05
  4842.9    1933  4874.1 1929.77  4956.7 1928.43  4977.6 1926.41  4986.5 1923.03
  5001.2 1916.87  5037.3 1923.35  5050.1 1924.26  5109.1 1924.54    5166 1932.98
  5326.9 1941.05  5434.6 1944.67  5536.2 1948.84  5591.8 1950.71  5796.1 1964.31
#Mann= 10 ,-1 , 0
    4648      .1       0  4658.3     .16       0  4751.3      .1       0
  4817.9     .16       0  4874.1      .1       0  4977.6     .07       0
  5050.1      .1       0  5326.9     .05       0  5434.6     .16       0
  5536.2      .1       0
Bank Sta=4986.5,5037.3
XS Rating Curve= 0 ,0
Exp/Cntr=0.3,0.1

Type RM Length L Ch R = 1 ,1031    ,425,425,425
BEGIN DESCRIPTION:
UNT 1005 IN HEWA 2.0
END DESCRIPTION:
XS GIS Cut Line= 4
      2683879.82     10029602.43      2683595.07     10029991.35
      2683831.18     10030380.24      2684344.31     10030567.47
#Sta/Elev= 30
  4463.1 1983.66  4551.5 1978.69  4665.9 1956.94    4809 1927.57  4844.5 1921.53
  4865.4 1919.66    4880 1917.11  4886.2  1917.7  4894.7 1915.64  4900.9 1916.63
  4909.3 1914.71  4915.5 1916.37  4930.2    1911  4936.4 1911.66  4963.4 1909.89
  4997.2  1904.1  4999.9  1903.6  5003.2  1904.1  5015.7  1907.1  5021.5 1910.15
    5037 1914.67  5045.2 1916.31  5079.7 1918.81  5134.5 1920.82  5211.5 1924.48
  5415.1 1930.53  5479.2 1931.61  5566.5 1933.63  5719.2 1943.79  5946.3 1954.88
#Mann= 8 ,-1 , 0
  4463.1     .16       0  4665.9      .1       0  4997.2     .07       0
  5003.2      .1       0  5045.2     .16       0  5134.5      .1       0
  5415.1     .16       0  5479.2      .1       0
Bank Sta=4997.2,5003.2
XS Rating Curve= 0 ,0
Exp/Cntr=0.3,0.1

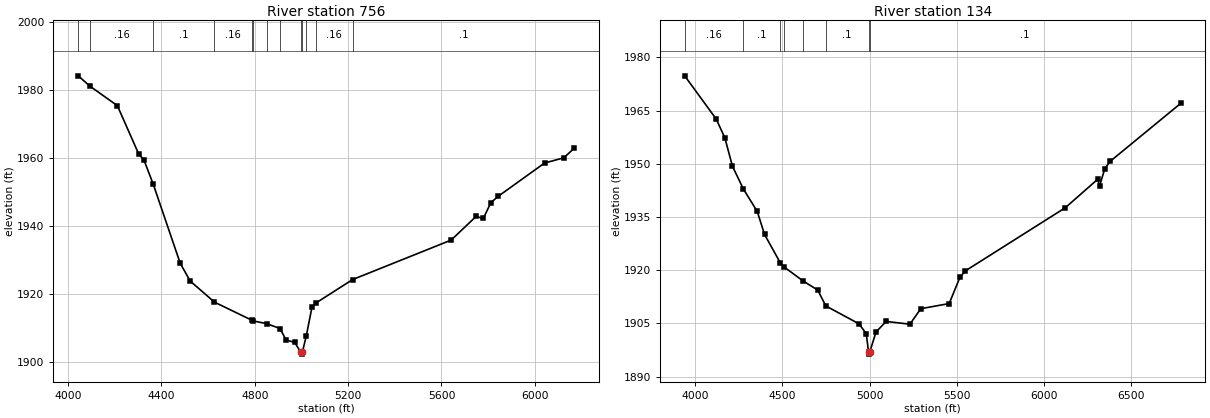
Type RM Length L Ch R = 1 ,756     ,622,622,622
BEGIN DESCRIPTION:
Mapping XS 46d1df5a
END DESCRIPTION:
XS GIS Cut Line= 4
       2683890.9     10029518.97      2683318.02     10030032.83
      2683477.74      10030348.8       2684429.1     10030661.29
#Sta/Elev= 30
  4043.5  1984.1  4093.8 1981.06  4211.3 1975.33  4303.2 1961.06  4324.9 1959.42
  4365.1 1952.24  4480.4 1929.07    4523 1923.83  4627.2 1917.63  4787.2 1912.32
  4791.4 1912.13  4850.8 1911.31  4908.4 1909.87  4933.9 1906.51    4971 1905.79
  4997.7 1902.85  5000.5 1902.35  5003.7 1902.85  5021.1 1907.81  5045.3 1916.22
  5062.9 1917.41  5218.9 1924.24  5641.5 1935.85  5747.9 1942.78  5779.7 1942.23
  5811.5 1946.84  5843.3 1948.72  6041.5 1958.48  6124.4 1960.02  6168.5 1962.83
#Mann= 13 ,-1 , 0
  4043.5      .1       0  4093.8     .16       0  4365.1      .1       0
  4627.2     .16       0  4787.2      .1       0  4791.4     .16       0
  4850.8      .1       0  4908.4     .16       0  4997.7     .07       0
  5003.7     .16       0  5021.1      .1       0  5062.9     .16       0
  5218.9      .1       0
Bank Sta=4997.7,5003.7
XS Rating Curve= 0 ,0
Exp/Cntr=0.3,0.1

Type RM Length L Ch R = 1 ,134     ,0,0,0
BEGIN DESCRIPTION:
UNT 1005 IN HEWA 1.0
END DESCRIPTION:
XS GIS Cut Line= 4
      2683776.33     10029466.87      2683002.05     10030081.44
      2682925.66     10030362.69      2684453.44     10030713.39
#Sta/Elev= 30
  3938.7 1974.78  4119.9 1962.58  4169.5 1957.27  4212.8 1949.31    4276 1942.84
  4355.4 1936.54    4397 1930.08  4487.7 1922.05    4509  1920.9  4618.2 1916.95
    4703 1914.36  4748.7 1909.91    4940 1904.84  4981.4 1902.05  4994.6 1896.81
  4997.3 1896.31  5000.6 1896.81  5037.4 1902.55  5095.4 1905.53  5231.8 1904.75
  5294.5 1909.12  5457.5 1910.57  5519.1 1917.97  5549.9 1919.77  6124.5  1937.6
  6309.1 1945.58  6321.5 1943.78  6350.2 1948.53    6381 1950.64  6786.2 1966.99
#Mann= 8 ,-1 , 0
  3938.7     .16       0    4276      .1       0  4487.7     .16       0
    4509      .1       0  4618.2     .16       0  4748.7      .1       0
  4994.6     .07       0  5000.6      .1       0
Bank Sta=4994.6,5000.6
XS Rating Curve= 0 ,0
Exp/Cntr=0.3,0.1

Chan Stop Cuts=-1
Use User Specified Reach Order=0
Composite Channel Slope=5