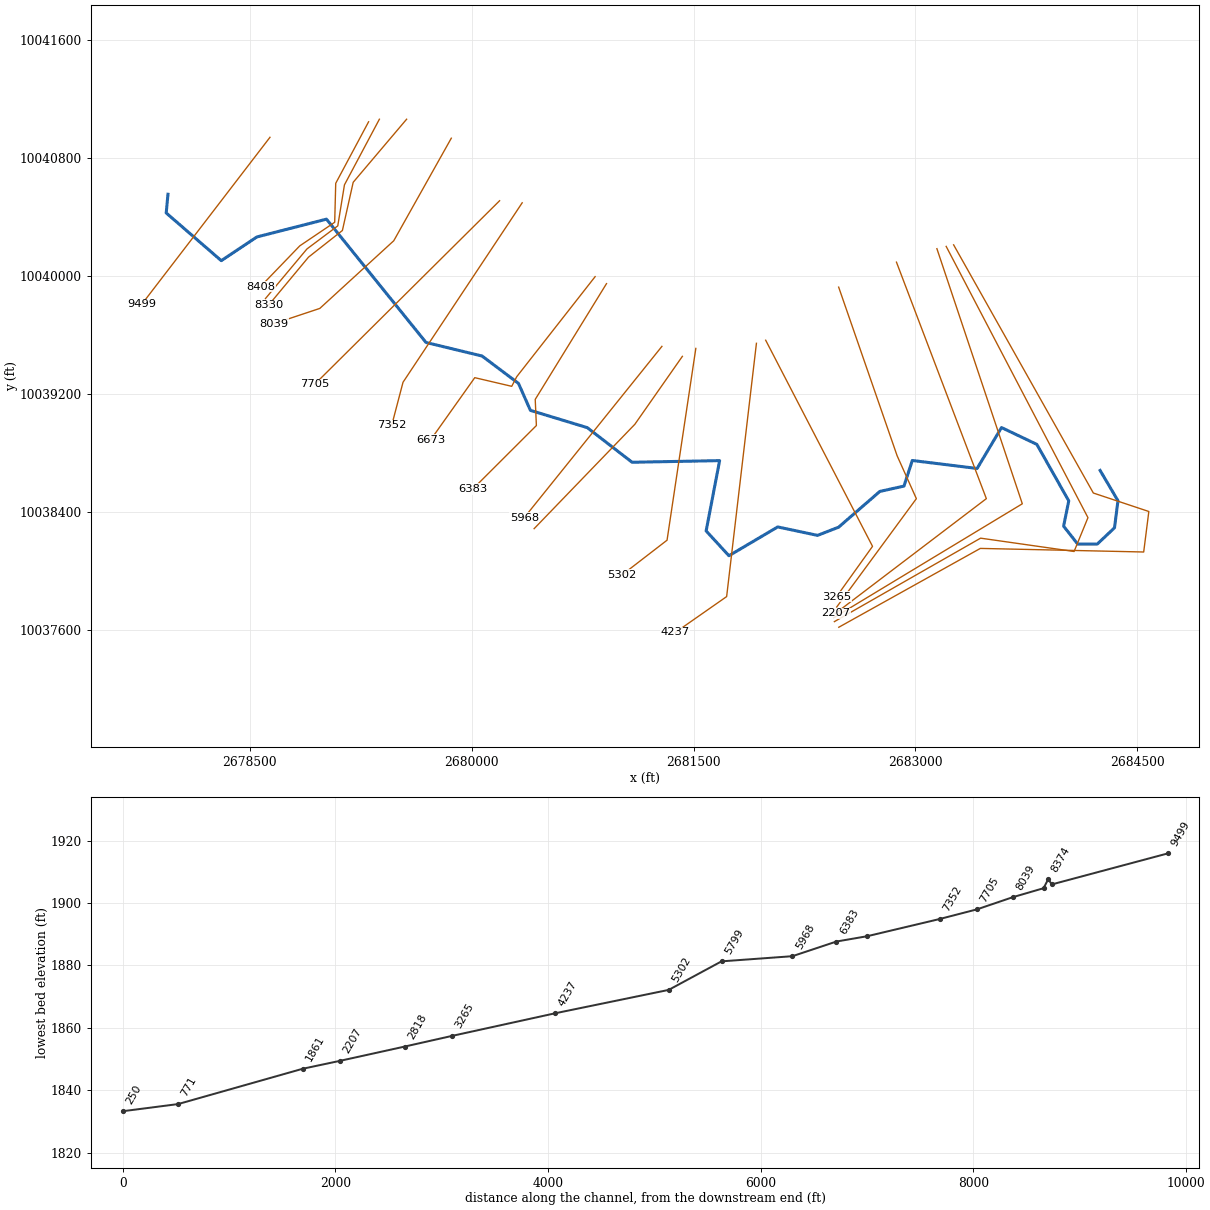
--- UNT 1006 IN HEWA.prj (project) ---

Proj Title=UNT 1006 IN HEWA Base Level Engineering
Current Plan=p01
Default Exp/Contr=0.3,0.1
English Units
Geom File=g01
Flow File=f01
Plan File=p01
Y Axis Title=Elevation
X Axis Title(PF)=Main Channel Distance
X Axis Title(XS)=Station
BEGIN DESCRIPTION:
UNT 1006 IN HEWA
END DESCRIPTION:
DSS Export Rating Curves= 0
DSS Export Rating Curve Sorted= 0
DSS Export Volume Flow Curves= 0
DXF OffsetX= 0
DXF OffsetY= 0
DXF ScaleX= 1
DXF ScaleY= 10

--- UNT 1006 IN HEWA.p01 (plan) ---

Plan Title=Multiple Run
Short Identifier=Multiple
Geom File=g01
Flow File=f01
Subcritical Flow
K Sum by GR= 0
Std Step Tol= 0.01
Critical Tol= 0.01
Num of Std Step Trials= 20
Max Error Tol= 0.3
Flow Tol Ratio= 0.001
Split Flow NTrial= 30
Split Flow Tol= 0.02
Split Flow Ratio= 0.02
Log Output Level= 0
Friction Slope Method= 1
Unsteady Friction Slope Method= 2
Unsteady Bridges Friction Slope Method= 1
Parabolic Critical Depth
Global Vel Dist=  1 , 1 , 1
Global Log Level= 0
CheckData=True
Encroach Param= -1, 0, 0, 0
BEGIN DESCRIPTION:
Multiple Run
END DESCRIPTION:

--- UNT 1006 IN HEWA.f01 (steady flow) ---

Flow Title=Multiple
Number of Profiles=7
Profile Names=10-year,25-year,50-year,1pct_min,100-year,1pct_plu,500-year
River Rch & RM= UNT 1006 IN HEWA,Reach-1,9499
    1372    2025    2596    2427    3282    4438    5241
River Rch & RM= UNT 1006 IN HEWA,Reach-1,8374
    1632    2418    3108    2907    3932    5317    6296
Boundary for River Rch & Prof#=UNT 1006 IN HEWA,Reach-1,1
Up Type=0
Dn Type=3
Dn Slope=0.005
Boundary for River Rch & Prof#=UNT 1006 IN HEWA,Reach-1,2
Up Type=0
Dn Type=3
Dn Slope=0.005
Boundary for River Rch & Prof#=UNT 1006 IN HEWA,Reach-1,3
Up Type=0
Dn Type=3
Dn Slope=0.005
Boundary for River Rch & Prof#=UNT 1006 IN HEWA,Reach-1,4
Up Type=0
Dn Type=3
Dn Slope=0.005
Boundary for River Rch & Prof#=UNT 1006 IN HEWA,Reach-1,5
Up Type=0
Dn Type=3
Dn Slope=0.005
Boundary for River Rch & Prof#=UNT 1006 IN HEWA,Reach-1,6
Up Type=0
Dn Type=3
Dn Slope=0.005
Boundary for River Rch & Prof#=UNT 1006 IN HEWA,Reach-1,7
Up Type=0
Dn Type=3
Dn Slope=0.005

--- UNT 1006 IN HEWA.g01 (geometry) ---

Geom Title=Existing Conditions
Program Version=4.10

River Reach=UNT 1006 IN HEWA,Reach-1
Reach XY= 30
      2677947.78     10040554.02      2677935.73     10040427.36
      2678308.11     10040104.28       2678548.8     10040264.91
      2679019.19     10040385.31      2679691.72      10039550.4
      2680071.07     10039458.35      2680316.92     10039273.19
      2680397.56     10039090.55      2680781.82     10038973.58
      2681084.85     10038739.12      2681676.58     10038750.21
      2681585.38     10038274.08      2681739.54     10038106.18
      2682069.32     10038301.25      2682338.42     10038244.01
      2682480.83     10038299.41      2682759.36     10038541.62
      2682922.51     10038577.64      2682978.96     10038751.07
      2683417.07      10038697.1       2683581.8     10038974.19
      2683820.77     10038860.07      2684036.47     10038477.71
      2684001.64     10038306.32      2684096.84     10038185.05
      2684228.69     10038184.76      2684345.76     10038295.32
      2684369.05     10038478.67      2684248.47     10038683.73

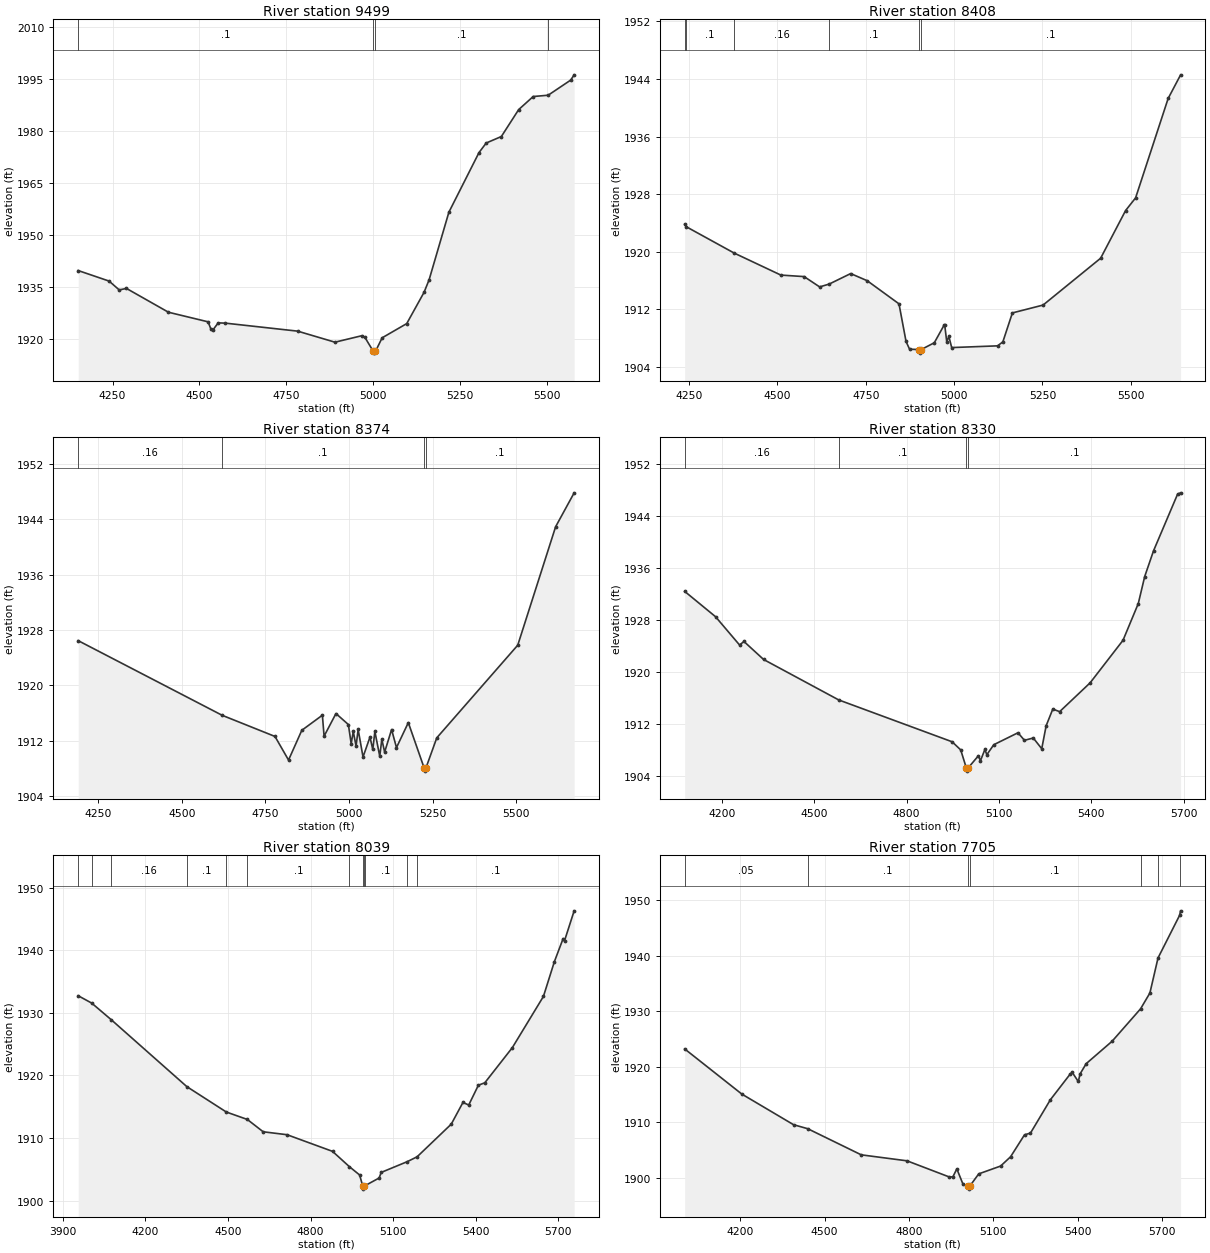
Type RM Length L Ch R = 1 ,9499    ,1091,1091,1091
BEGIN DESCRIPTION:
UNT 1006 IN HEWA 14.0
END DESCRIPTION:
XS GIS Cut Line= 2
      2678637.15     10040939.68       2677769.8     10039807.79
#Sta/Elev= 30
  4151.4 1939.72  4240.2 1936.68  4269.3 1934.13  4290.1 1934.56  4410.9 1927.68
  4524.9 1924.91  4533.1 1922.77  4539.4 1922.66  4553.9 1924.61  4574.7 1924.53
  4782.4 1922.22  4889.6 1919.03  4967.3 1920.91  4975.5 1920.46    5000 1916.37
  5002.7 1915.87    5006 1916.37  5025.4  1920.3    5096  1924.4  5145.9 1933.45
  5160.4 1937.07  5217.2 1956.58  5303.7 1973.78  5324.5 1976.56  5368.1 1978.44
  5417.9 1986.22  5459.6 1989.99  5502.7 1990.37  5567.5 1994.74  5577.4 1996.26
#Mann= 4 ,-1 , 0
  4151.4      .1       0    5000     .07       0    5006      .1       0
  5502.7     .16       0
Bank Sta=5000,5006
XS Rating Curve= 0 ,0
Exp/Cntr=0.3,0.1

Type RM Length L Ch R = 1 ,8408    ,34,34,34
BEGIN DESCRIPTION:
UNT 1006 IN HEWA 13.0
END DESCRIPTION:
XS GIS Cut Line= 5
      2679303.84     10041044.74      2679081.61     10040628.07
      2679074.67     10040364.18      2678838.56     10040204.46
      2678573.28     10039928.85
#Sta/Elev= 30
  4237.4 1923.82  4241.5 1923.49  4377.7 1919.82  4509.7 1916.77  4575.5 1916.56
  4619.4 1915.13  4646.3 1915.52  4707.3 1916.98    4754 1915.99    4844 1912.78
    4864 1907.56    4874 1906.48    4901 1906.44  4903.8 1905.94    4907 1906.44
    4944 1907.38  4971.3 1909.79  4973.6 1909.79  4979.2 1907.52  4985.2 1908.25
  4993.2 1906.71    5123 1906.95    5138  1907.5    5165 1911.52  5251.9 1912.61
  5414.8 1919.11  5485.5 1925.73  5513.8 1927.49  5605.9 1941.28  5641.2 1944.56
#Mann= 6 ,-1 , 0
  4237.4     .16       0  4241.5      .1       0  4377.7     .16       0
  4646.3      .1       0    4901     .07       0    4907      .1       0
Bank Sta=4901,4907
XS Rating Curve= 0 ,0
Exp/Cntr=0.3,0.1

Type RM Length L Ch R = 1 ,8374    ,44,44,44
BEGIN DESCRIPTION:
Mapping XS 44d8f711
END DESCRIPTION:
XS GIS Cut Line= 5
      2679376.75      10041062.1      2679140.64     10040617.66
       2679095.5     10040339.88      2678887.17     10040183.63
      2678606.68     10039847.74
#Sta/Elev= 30
  4190.5 1926.45  4620.7 1915.67  4778.8 1912.61  4819.3  1909.2    4859  1913.5
  4920.5 1915.68  4925.6 1912.65  4961.1 1915.92  4998.2 1914.33  5006.6 1911.56
  5012.8 1913.34  5021.2 1911.22  5027.4 1913.62    5042 1909.64  5062.8 1912.52
  5071.2 1910.73  5077.4 1913.33    5092 1909.75  5098.2  1912.2  5106.6 1910.35
  5127.4 1913.61    5142    1911  5177.4 1914.61  5224.4  1908.1  5227.2  1907.6
  5230.4  1908.1  5262.5 1912.41  5504.6  1925.8  5617.8 1942.91  5673.2 1947.81
#Mann= 4 ,-1 , 0
  4190.5     .16       0  4620.7      .1       0  5224.4     .07       0
  5230.4      .1       0
Bank Sta=5224.4,5230.4
XS Rating Curve= 0 ,0
Exp/Cntr=0.3,0.1

Type RM Length L Ch R = 1 ,8330    ,291,291,291
BEGIN DESCRIPTION:
UNT 1006 IN HEWA 12.0
END DESCRIPTION:
XS GIS Cut Line= 5
      2679560.75     10041062.06      2679199.67     10040635.02
      2679126.75     10040308.63      2678897.58     10040128.07
      2678626.78     10039801.72
#Sta/Elev= 30
  4080.1 1932.41  4180.2 1928.51  4258.2 1924.15  4272.5 1924.69  4336.2 1921.92
  4579.9 1915.69  4948.1 1909.24  4975.9 1907.99  4994.1 1905.22  4996.8 1904.72
  5000.1 1905.22  5033.6  1907.1  5039.9 1906.31  5054.4 1908.06  5060.7 1907.25
  5083.3 1908.79  5161.8 1910.63  5182.7 1909.47  5211.5 1909.82  5238.9 1908.17
  5253.2 1911.71  5274.8 1914.28    5297 1913.88  5395.9 1918.32  5502.7 1924.88
  5552.2 1930.53    5573 1934.69  5601.7 1938.66  5679.8 1947.39  5689.6 1947.59
#Mann= 4 ,-1 , 0
  4080.1     .16       0  4579.9      .1       0  4994.1     .07       0
  5000.1      .1       0
Bank Sta=4994.1,5000.1
XS Rating Curve= 0 ,0
Exp/Cntr=0.3,0.1

Type RM Length L Ch R = 1 ,8039    ,334,334,334
BEGIN DESCRIPTION:
UNT 1006 IN HEWA 11.0
END DESCRIPTION:
XS GIS Cut Line= 4
      2679862.88     10040933.65      2679473.97     10040239.18
      2678973.97     10039780.85      2678662.46     10039677.01
#Sta/Elev= 30
  3955.6 1932.75  4004.5 1931.58  4075.1 1928.94  4350.4 1918.22  4493.9 1914.16
  4570.3 1912.97  4627.9    1911  4714.7 1910.53  4879.9 1907.87  4941.3 1905.42
  4978.5 1904.09  4989.7 1902.33  4992.5 1901.83  4995.7 1902.33    4998 1902.38
  5049.4 1903.61  5056.8  1904.5  5150.9 1906.21  5187.4    1907  5311.5 1912.22
    5354 1915.69    5375 1915.28  5410.2 1918.45  5433.4 1918.83  5533.6 1924.46
  5646.5 1932.64  5686.4 1938.21  5718.1 1941.89  5723.3 1941.56  5758.2 1946.33
#Mann= 12 ,-1 , 0
  3955.6     .16       0  4004.5      .1       0  4075.1     .16       0
  4350.4      .1       0  4493.9     .05       0  4570.3      .1       0
  4941.3     .05       0  4989.7     .07       0  4995.7     .05       0
    4998      .1       0  5150.9     .05       0  5187.4      .1       0
Bank Sta=4989.7,4995.7
XS Rating Curve= 0 ,0
Exp/Cntr=0.3,0.1

Type RM Length L Ch R = 1 ,7705    ,353,353,353
BEGIN DESCRIPTION:
UNT 1006 IN HEWA 10.0
END DESCRIPTION:
XS GIS Cut Line= 2
      2680189.24     10040510.01      2678940.14     10039267.85
#Sta/Elev= 30
  4003.3 1923.23  4206.3 1915.09  4390.1 1909.57  4440.4 1908.85  4630.5 1904.14
  4793.2 1903.06  4941.7 1900.18  4955.8 1900.16    4970 1901.61  4991.2 1898.94
  5009.4 1898.46  5012.1 1897.96  5015.4 1898.46  5047.8 1900.71  5125.5 1902.12
  5160.9 1903.79  5210.4 1907.75  5231.6 1908.06  5302.3 1914.07    5373 1918.72
  5380.1 1918.99  5401.3 1917.36  5408.4 1918.78  5429.6 1920.58  5521.5 1924.61
  5622.7 1930.46  5655.8 1933.31  5684.6 1939.62  5761.2  1947.3  5764.9 1948.12
#Mann= 7 ,-1 , 0
  4003.3     .05       0  4440.4      .1       0  5009.4     .07       0
  5015.4      .1       0  5622.7     .16       0  5684.6      .1       0
  5761.2     .16       0
Bank Sta=5009.4,5015.4
XS Rating Curve= 0 ,0
Exp/Cntr=0.3,0.1

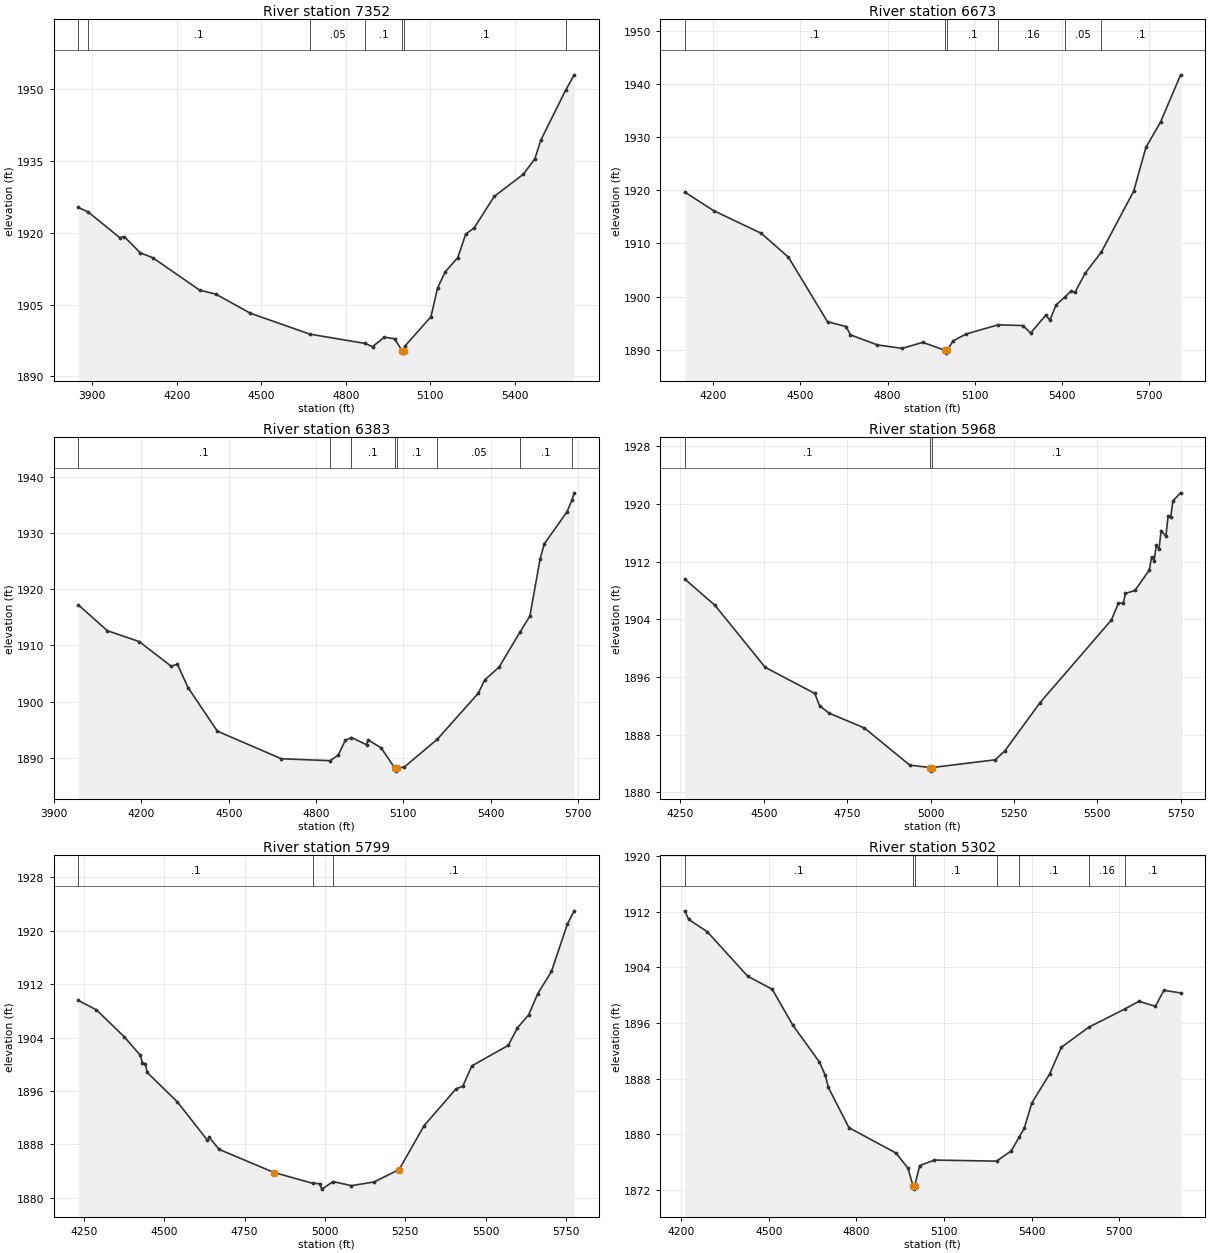
Type RM Length L Ch R = 1 ,7352    ,679,679,679
BEGIN DESCRIPTION:
UNT 1006 IN HEWA 9.0
END DESCRIPTION:
XS GIS Cut Line= 3
      2680342.02     10040496.12      2679536.47     10039280.85
      2679460.09      10038989.2
#Sta/Elev= 30
    3851 1925.29  3885.3 1924.37  3998.5 1918.96  4013.6 1919.21  4070.7 1915.82
  4115.8 1914.77  4281.3 1908.02  4338.4 1907.19  4461.8 1903.18  4672.5 1898.82
    4868 1896.88  4894.9  1896.2    4937 1898.18  4973.1 1897.86  5000.2 1895.35
  5002.9 1894.85  5006.2 1895.35  5009.2 1896.27  5102.4 1902.46  5125.6 1908.45
  5153.6 1911.89  5197.6 1914.82  5225.8 1919.73  5255.9 1921.04  5326.7 1927.59
  5430.1 1932.23  5471.4 1935.51  5492.1 1939.34  5579.9 1949.75  5610.5 1953.01
#Mann= 7 ,-1 , 0
    3851     .05       0  3885.3      .1       0  4672.5     .05       0
    4868      .1       0  5000.2     .07       0  5006.2      .1       0
  5579.9     .16       0
Bank Sta=5000.2,5006.2
XS Rating Curve= 0 ,0
Exp/Cntr=0.3,0.1

Type RM Length L Ch R = 1 ,6673    ,290,290,290
BEGIN DESCRIPTION:
UNT 1006 IN HEWA 8.0
END DESCRIPTION:
XS GIS Cut Line= 5
      2680835.08     10039996.12      2680305.15      10039318.5
       2680271.3      10039253.4      2680021.48     10039311.96
      2679723.97     10038891.96
#Sta/Elev= 30
  4102.8 1919.68  4201.9 1916.18  4365.6 1911.92  4458.7 1907.45  4593.5 1895.27
  4657.7 1894.36  4672.2  1892.8  4765.3  1890.9  4850.3 1890.26  4920.9 1891.39
  4999.2 1889.86    5002 1889.36  5005.2 1889.86  5024.8 1891.66  5070.1 1892.96
  5180.4 1894.69  5265.3 1894.55    5292 1893.14  5343.7 1896.49  5358.5 1895.59
  5379.4 1898.44  5410.4 1899.95  5429.9    1901  5444.6 1900.83  5480.3 1904.46
  5534.8 1908.36  5646.2 1919.84  5688.3 1928.08  5738.7 1932.87  5807.7 1941.75
#Mann= 6 ,-1 , 0
  4102.8      .1       0  4999.2     .07       0  5005.2      .1       0
  5180.4     .16       0  5410.4     .05       0  5534.8      .1       0
Bank Sta=4999.2,5005.2
XS Rating Curve= 0 ,0
Exp/Cntr=0.3,0.1

Type RM Length L Ch R = 1 ,6383    ,415,415,415
BEGIN DESCRIPTION:
UNT 1006 IN HEWA 7.0
END DESCRIPTION:
XS GIS Cut Line= 4
      2680911.94     10039948.74      2680430.15     10039164.86
      2680437.97     10038987.77      2680008.58     10038558.39
#Sta/Elev= 30
    3983 1917.22  4082.8 1912.62  4192.2 1910.69  4302.3 1906.31  4323.6 1906.65
  4360.3  1902.5  4460.9 1894.76  4681.1 1889.85  4848.1 1889.51  4876.4 1890.48
  4900.8 1893.12  4921.4 1893.63  4973.8 1892.35  4978.8 1893.21  5024.3 1891.77
  5071.4 1888.15  5074.1 1887.65  5077.4 1888.15  5104.1  1888.4  5217.1 1893.32
  5358.6 1901.54  5379.9 1903.86  5429.3 1906.14  5502.1 1912.43  5535.4 1915.24
  5570.8 1925.45  5584.9 1928.07  5662.7 1933.74  5679.9 1935.85  5687.6 1937.14
#Mann= 8 ,-1 , 0
    3983      .1       0  4848.1     .05       0  4921.4      .1       0
  5071.4     .07       0  5077.4      .1       0  5217.1     .05       0
  5502.1      .1       0  5679.9     .16       0
Bank Sta=5071.4,5077.4
XS Rating Curve= 0 ,0
Exp/Cntr=0.3,0.1

Type RM Length L Ch R = 1 ,5968    ,666,666,666
BEGIN DESCRIPTION:
UNT 1006 IN HEWA 6.0
END DESCRIPTION:
XS GIS Cut Line= 2
       2681286.5     10039523.94      2680355.95     10038364.22
#Sta/Elev= 30
  4263.1 1909.59  4353.7 1905.94  4504.1 1897.35  4652.9 1893.73  4667.3 1892.02
  4696.1 1890.98  4801.9 1888.93  4937.8 1883.78  4998.8 1883.45  5001.5 1882.95
  5004.8 1883.45  5193.8 1884.52  5222.6 1885.74  5328.2 1892.44  5542.7 1903.93
  5563.5 1906.26  5577.9 1906.24  5584.3 1907.59  5613.1 1908.01  5656.3 1910.86
  5662.7 1912.64  5670.7 1912.13  5677.1 1914.31  5685.1 1913.72  5691.5  1916.3
  5705.9 1915.53  5712.3  1918.3  5720.3 1918.15  5726.7 1920.41    5750 1921.55
#Mann= 3 ,-1 , 0
  4263.1      .1       0  4998.8     .07       0  5004.8      .1       0
Bank Sta=4998.8,5004.8
XS Rating Curve= 0 ,0
Exp/Cntr=0.3,0.1

Type RM Length L Ch R = 1 ,5799    ,497,497,497
BEGIN DESCRIPTION:
Mapping XS 872fef9e
END DESCRIPTION:
XS GIS Cut Line= 3
      2681424.76     10039456.36      2681103.61     10038996.33
      2680422.82     10038289.52
#Sta/Elev= 30
  4232.8 1909.57  4289.2 1908.16  4375.5 1904.13  4426.1 1901.34  4432.2 1900.17
    4441  1900.1  4447.1 1898.78  4540.9 1894.37  4634.6 1888.61  4640.7 1889.05
  4670.4 1887.26  4841.7 1883.79  4962.1 1882.17  4983.2 1882.12  4990.1  1881.3
  5025.6 1882.43  5082.2 1881.82    5153 1882.38  5230.7 1884.23  5308.6 1890.83
  5407.7 1896.32  5428.7 1896.72    5457 1899.77  5570.2 1902.84  5598.5 1905.45
  5633.8 1907.43  5662.1  1910.6  5704.5 1913.91  5754.2 1921.02  5775.2    1923
#Mann= 3 ,-1 , 0
  4232.8      .1       0  4962.1     .07       0  5025.6      .1       0
Bank Sta=4841.7,5230.7
XS Rating Curve= 0 ,0
Exp/Cntr=0.3,0.1

Type RM Length L Ch R = 1 ,5302    ,1065,1065,1065
BEGIN DESCRIPTION:
UNT 1006 IN HEWA 5.0
END DESCRIPTION:
XS GIS Cut Line= 3
      2681515.64       10039510.       2681321.2     10038211.41
      2681015.66     10037975.31
#Sta/Elev= 30
  4211.7  1912.1  4224.7 1910.88  4288.8  1909.1  4427.1 1902.72  4511.3 1900.85
  4582.1 1895.68  4673.1  1890.4  4693.3 1888.49  4703.8 1886.75  4774.2 1880.98
    4936 1877.33  4976.4 1875.17  4993.6 1872.66  4996.4 1872.16  4999.6 1872.66
  5016.8 1875.55  5067.4 1876.33  5280.1 1876.18  5330.3 1877.64  5358.5 1879.69
  5375.1 1880.91  5401.1 1884.54  5461.8 1888.67  5502.2 1892.52  5596.2  1895.4
  5719.5 1898.01  5768.2 1899.12  5824.4 1898.39  5853.4 1900.69  5910.9 1900.32
#Mann= 7 ,-1 , 0
  4211.7      .1       0  4993.6     .07       0  4999.6      .1       0
  5280.1     .16       0  5358.5      .1       0  5596.2     .16       0
  5719.5      .1       0
Bank Sta=4993.6,4999.6
XS Rating Curve= 0 ,0
Exp/Cntr=0.3,0.1

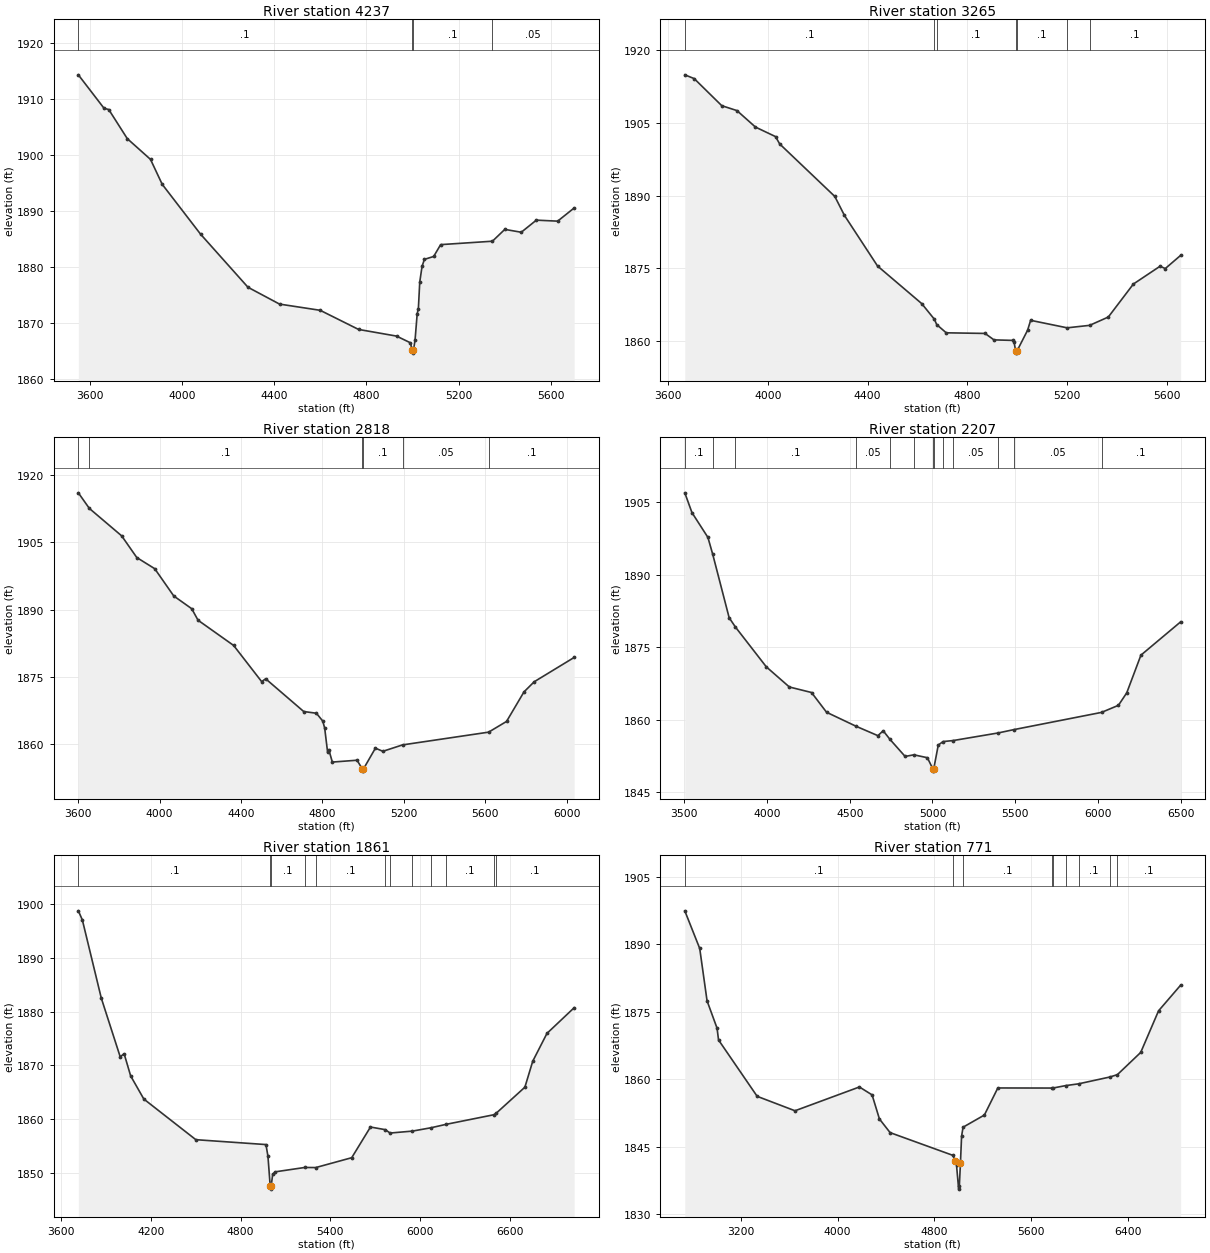
Type RM Length L Ch R = 1 ,4237    ,972,972,972
BEGIN DESCRIPTION:
UNT 1006 IN HEWA 3.0
END DESCRIPTION:
XS GIS Cut Line= 3
      2681925.36     10039544.69      2681723.97     10037829.46
      2681376.71     10037586.38
#Sta/Elev= 30
    3550 1914.35  3661.7 1908.37  3681.9 1908.16  3762.4 1902.96  3863.1 1899.26
  3913.9 1894.81  4080.2 1885.92    4286 1876.44  4422.8 1873.44  4599.2 1872.33
  4765.5 1868.92  4930.4 1867.73  4990.8 1866.53  4997.9 1865.19  5000.6 1864.69
  5003.9 1865.19  5010.9  1867.1    5020 1871.73  5025.1 1872.63  5031.1 1877.39
  5041.1 1880.17  5051.2 1881.42  5091.5 1881.94  5121.7 1884.05  5346.4 1884.66
    5400 1886.77  5471.5 1886.26  5536.9 1888.42  5629.3 1888.24  5700.9 1890.59
#Mann= 4 ,-1 , 0
    3550      .1       0  4997.9     .07       0  5003.9      .1       0
  5346.4     .05       0
Bank Sta=4997.9,5003.9
XS Rating Curve= 0 ,0
Exp/Cntr=0.3,0.1

Type RM Length L Ch R = 1 ,3265    ,447,447,447
BEGIN DESCRIPTION:
UNT 1006 IN HEWA 2.0
END DESCRIPTION:
XS GIS Cut Line= 3
      2681987.86     10039565.58      2682710.08     10038169.74
      2682467.02     10037829.45
#Sta/Elev= 30
  3666.6 1914.95  3704.3 1914.17    3815 1908.57  3875.8 1907.56  3950.2 1904.15
  4030.8 1902.18  4047.3 1900.67  4268.7 1889.81  4307.3 1885.89  4440.2 1875.43
  4617.3 1867.67  4668.4 1864.42  4677.5 1863.33  4715.8 1861.63  4871.7  1861.5
  4907.2 1860.17  4982.4 1860.06    4988 1859.68  4994.3 1857.93    4997 1857.43
  5000.3 1857.93  5042.3 1862.17  5054.5 1864.21    5201 1862.66  5291.1 1863.17
  5366.2 1864.89  5466.8 1871.71  5573.9 1875.39  5594.8 1874.91  5656.4 1877.63
#Mann= 7 ,-1 , 0
  3666.6      .1       0  4668.4     .16       0  4677.5      .1       0
  4994.3     .07       0  5000.3      .1       0    5201     .05       0
  5291.1      .1       0
Bank Sta=4994.3,5000.3
XS Rating Curve= 0 ,0
Exp/Cntr=0.3,0.1

Type RM Length L Ch R = 1 ,2818    ,611,611,611
BEGIN DESCRIPTION:
Mapping XS feacd886
END DESCRIPTION:
XS GIS Cut Line= 4
      2682481.24     10039925.01      2682876.22     10038783.49
      2683006.43     10038492.69      2682468.24      10037759.2
#Sta/Elev= 30
    3601 1916.06  3655.2 1912.58    3814 1906.46  3888.2 1901.63  3976.4 1899.14
  4069.9 1893.06  4158.1 1890.22  4189.3 1887.65  4364.2 1882.02  4501.8 1873.96
  4521.5 1874.59  4708.5 1867.29  4770.8 1866.91  4801.9 1865.17  4811.5  1863.6
  4825.9 1858.18  4831.4 1858.82  4849.1 1856.02  4970.5 1856.43  4996.2  1854.5
  4998.9    1854  5002.2  1854.5  5060.7 1859.12  5097.4 1858.42  5194.2 1859.85
  5616.9 1862.69  5705.1 1865.08  5790.8 1871.67    5841 1873.93  6037.3 1879.35
#Mann= 6 ,-1 , 0
    3601     .05       0  3655.2      .1       0  4996.2     .07       0
  5002.2      .1       0  5194.2     .05       0  5616.9      .1       0
Bank Sta=4996.2,5002.2
XS Rating Curve= 0 ,0
Exp/Cntr=0.3,0.1

Type RM Length L Ch R = 1 ,2207    ,346,346,346
BEGIN DESCRIPTION:
Mapping XS aa749e35
END DESCRIPTION:
XS GIS Cut Line= 3
      2682871.88     10040094.25      2683479.52     10038492.69
      2682459.56     10037715.79
#Sta/Elev= 30
  3503.8 1906.93  3547.1 1902.84  3643.4 1897.72  3672.6 1894.21  3771.7 1881.12
  3809.2 1879.21  3996.3 1870.96  4135.4  1866.8  4269.3 1865.66    4360 1861.58
  4539.3 1858.67  4670.2 1856.74  4702.3 1857.75  4743.2 1855.97  4834.6 1852.45
  4887.8 1852.78  4969.2 1852.18  5001.7 1849.91  5004.5 1849.41  5007.7 1849.91
  5034.9  1854.8  5063.9 1855.52  5124.8 1855.73  5396.7  1857.3  5490.2 1857.98
  6021.1 1861.55  6123.2 1863.01  6173.4 1865.59  6259.1 1873.38  6498.9 1880.26
#Mann= 13 ,-1 , 0
  3503.8      .1       0  3672.6     .05       0  3809.2      .1       0
  4539.3     .05       0  4743.2      .1       0  4887.8     .16       0
  5001.7     .07       0  5007.7     .16       0  5063.9      .1       0
  5124.8     .05       0  5396.7      .1       0  5490.2     .05       0
  6021.1      .1       0
Bank Sta=5001.7,5007.7
XS Rating Curve= 0 ,0
Exp/Cntr=0.3,0.1

Type RM Length L Ch R = 1 ,1861    ,1173,1173,1173
BEGIN DESCRIPTION:
Mapping XS c699fab8
END DESCRIPTION:
XS GIS Cut Line= 3
      2683145.31     10040185.41      2683722.57     10038457.97
      2682446.56     10037685.41
#Sta/Elev= 30
    3716 1898.81  3742.9 1897.11  3869.3 1882.54  3995.7 1871.59    4022 1872.16
  4065.7 1868.02  4153.6 1863.71  4501.1 1856.13  4969.7 1855.22    4983 1853.03
  4998.3 1847.41    5001 1846.91  5004.3 1847.41  5014.6  1849.7  5032.9 1850.14
  5229.3 1850.95  5302.1 1850.93  5542.7 1852.77    5668 1858.49  5766.8    1858
  5799.1 1857.37  5948.2 1857.73  6073.5 1858.36  6172.9 1858.99  6492.1 1860.78
  6506.4 1861.02  6699.8 1865.92  6752.2 1870.76  6847.2 1875.95    7029 1880.74
#Mann= 12 ,-1 , 0
    3716      .1       0  4998.3     .07       0  5004.3      .1       0
  5229.3     .16       0  5302.1      .1       0  5766.8     .05       0
  5799.1      .1       0  5948.2     .05       0  6073.5     .16       0
  6172.9      .1       0  6492.1     .05       0  6506.4      .1       0
Bank Sta=4998.3,5004.3
XS Rating Curve= 0 ,0
Exp/Cntr=0.3,0.1

Type RM Length L Ch R = 1 ,771     ,521,521,521
BEGIN DESCRIPTION:
Mapping XS 3270ff60
END DESCRIPTION:
XS GIS Cut Line= 5
      2683207.96     10040200.89      2684166.28      10038364.1
      2684072.53     10038134.94      2683440.59     10038225.21
      2682452.24     10037659.95
#Sta/Elev= 30
  2737.7 1897.46    2861 1889.09  2921.6 1877.45  3004.3 1871.36  3016.5 1868.75
  3335.6 1856.22  3648.1 1853.01  4180.2  1858.3    4285 1856.54  4345.6 1851.19
  4433.9 1848.15  4952.3  1843.1  4970.9 1841.93  4982.7 1840.89  5000.1 1835.59
  5005.8 1836.25  5015.1 1841.45  5024.4 1847.38  5036.8 1849.36  5212.7 1852.06
  5323.8 1858.08  5772.6 1858.06  5776.6 1858.05  5883.4  1858.6  5991.1    1859
  6248.3 1860.51  6311.6 1861.04  6504.3 1865.98  6651.7 1875.23    6834 1880.93
#Mann= 9 ,-1 , 0
  2737.7      .1       0  4952.3     .07       0  5036.8      .1       0
  5772.6     .05       0  5776.6      .1       0  5883.4     .16       0
  5991.1      .1       0  6248.3     .05       0  6311.6      .1       0
Bank Sta=4970.9,5015.1
XS Rating Curve= 0 ,0
Exp/Cntr=0.3,0.1

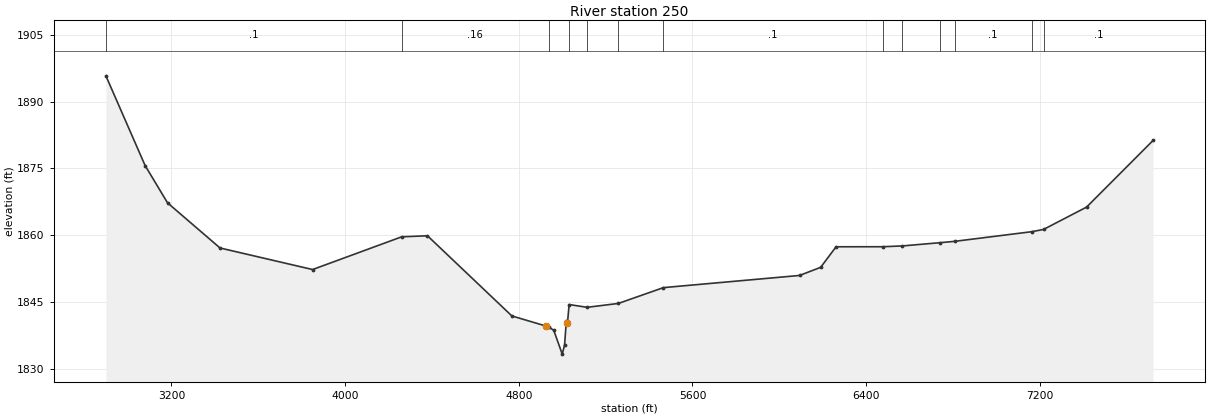
Type RM Length L Ch R = 1 ,250     ,0,0,0
BEGIN DESCRIPTION:
UNT 1006 IN HEWA 1.0
END DESCRIPTION:
XS GIS Cut Line= 6
      2683258.31     10040211.29      2684202.74     10038530.77
      2684577.74     10038405.77      2684543.02     10038131.46
      2683438.85     10038155.77      2682481.95     10037621.85
#Sta/Elev= 30
  2897.8 1895.78  3078.5 1875.63  3181.8 1867.26  3423.5 1857.13    3850 1852.29
  4260.6 1859.64  4379.2 1859.87  4768.1 1841.87    4924 1839.62    4937  1839.4
  4960.9 1838.66    5000  1833.3  5010.8 1835.35  5018.9 1840.69  5024.1 1840.27
  5031.8 1844.43  5114.8 1843.81  5258.7 1844.68  5466.1 1848.23  6093.1 1850.96
  6190.6 1852.79  6261.5  1857.4  6476.1 1857.41  6566.7 1857.59  6740.9 1858.32
  6807.7 1858.62  7161.9 1860.78  7217.1 1861.29  7415.6 1866.31  7721.8 1881.27
#Mann= 13 ,-1 , 0
  2897.8      .1       0  4260.6     .16       0    4937     .07       0
  5031.8     .16       0  5114.8      .1       0  5258.7     .16       0
  5466.1      .1       0  6476.1     .16       0  6566.7      .1       0
  6740.9     .16       0  6807.7      .1       0  7161.9     .05       0
  7217.1      .1       0
Bank Sta=4924,5024.1
XS Rating Curve= 0 ,0
Exp/Cntr=0.3,0.1

Chan Stop Cuts=-1
Use User Specified Reach Order=0
Composite Channel Slope=5