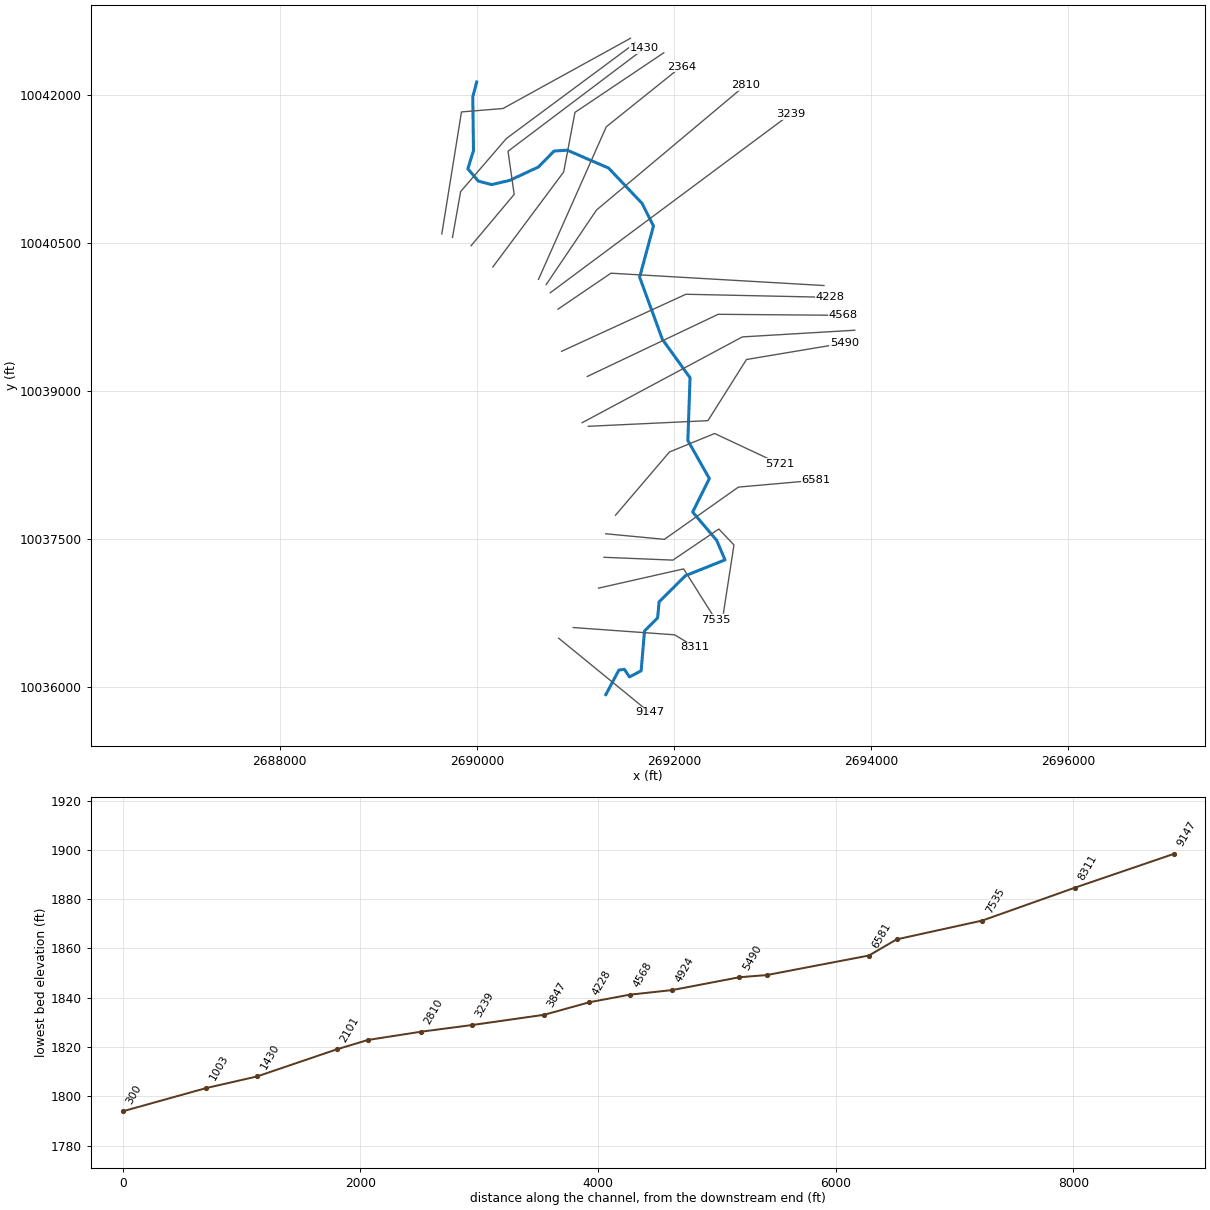
--- UNT 1007 IN HEWA.prj (project) ---

Proj Title=UNT 1007 IN HEWA Base Level Engineering
Current Plan=p01
Default Exp/Contr=0.3,0.1
English Units
Geom File=g01
Flow File=f01
Plan File=p01
Y Axis Title=Elevation
X Axis Title(PF)=Main Channel Distance
X Axis Title(XS)=Station
BEGIN DESCRIPTION:
UNT 1007 IN HEWA
END DESCRIPTION:
DSS Export Rating Curves= 0
DSS Export Rating Curve Sorted= 0
DSS Export Volume Flow Curves= 0
DXF OffsetX= 0
DXF OffsetY= 0
DXF ScaleX= 1
DXF ScaleY= 10

--- UNT 1007 IN HEWA.p01 (plan) ---

Plan Title=Multiple Run
Short Identifier=Multiple
Geom File=g01
Flow File=f01
Subcritical Flow
K Sum by GR= 0
Std Step Tol= 0.01
Critical Tol= 0.01
Num of Std Step Trials= 20
Max Error Tol= 0.3
Flow Tol Ratio= 0.001
Split Flow NTrial= 30
Split Flow Tol= 0.02
Split Flow Ratio= 0.02
Log Output Level= 0
Friction Slope Method= 1
Unsteady Friction Slope Method= 2
Unsteady Bridges Friction Slope Method= 1
Parabolic Critical Depth
Global Vel Dist=  1 , 1 , 1
Global Log Level= 0
CheckData=True
Encroach Param= -1, 0, 0, 0
BEGIN DESCRIPTION:
Multiple Run
END DESCRIPTION:

--- UNT 1007 IN HEWA.f01 (steady flow) ---

Flow Title=Multiple
Program Version=4.10
Number of Profiles= 7
Profile Names=10-year,25-year,50-year,1pct_min,100-year,1pct_plu,500-year
River Rch & RM=UNT 1007 IN HEWA,Reach-1         ,9147
    1275    1878    2406    2247    3039    4110    4850
River Rch & RM=UNT 1007 IN HEWA,Reach-1         ,6581
    2154    3265    4264    4053    5481    7412    9061
River Rch & RM=UNT 1007 IN HEWA,Reach-1         ,5721
    2154    3265    4264    4053    5481    7412    9061
River Rch & RM=UNT 1007 IN HEWA,Reach-1         ,5490
    2699    4125    5416    5171    6994    9458   11668
River Rch & RM=UNT 1007 IN HEWA,Reach-1         ,4924
    2699    4125    5416    5171    6994    9458   11668
Boundary for River Rch & Prof#=UNT 1007 IN HEWA,Reach-1         , 1
Up Type= 0
Dn Type= 3
Dn Slope=0.013
Boundary for River Rch & Prof#=UNT 1007 IN HEWA,Reach-1         , 2
Up Type= 0
Dn Type= 3
Dn Slope=0.013
Boundary for River Rch & Prof#=UNT 1007 IN HEWA,Reach-1         , 3
Up Type= 0
Dn Type= 3
Dn Slope=0.013
Boundary for River Rch & Prof#=UNT 1007 IN HEWA,Reach-1         , 4
Up Type= 0
Dn Type= 3
Dn Slope=0.013
Boundary for River Rch & Prof#=UNT 1007 IN HEWA,Reach-1         , 5
Up Type= 0
Dn Type= 3
Dn Slope=0.013
Boundary for River Rch & Prof#=UNT 1007 IN HEWA,Reach-1         , 6
Up Type= 0
Dn Type= 3
Dn Slope=0.013
Boundary for River Rch & Prof#=UNT 1007 IN HEWA,Reach-1         , 7
Up Type= 0
Dn Type= 3
Dn Slope=0.013
DSS Import GetInterval= 0
DSS Import GetPeak= 0
DSS Import FillOption= 0

--- UNT 1007 IN HEWA.g01 (geometry) ---

Geom Title=Existing Conditions

River Reach=UNT 1007 IN HEWA,Reach-1
Reach XY= 30
      2691308.47     10035923.73      2691440.33     10036171.61
      2691496.02     10036180.21      2691548.04     10036102.81
      2691666.40     10036164.52      2691700.71     10036568.16
      2691833.31     10036701.16      2691849.03     10036864.08
      2692115.74     10037128.91      2692517.31     10037289.52
      2692433.39     10037486.58      2692189.28     10037774.35
      2692358.47     10038113.73      2692140.46     10038499.29
      2692162.60     10039135.83      2691881.83     10039525.21
      2691651.09     10040154.96      2691791.77     10040674.08
      2691676.31     10040902.81      2691336.68     10041260.90
      2690916.74     10041442.57      2690783.49     10041433.66
      2690624.72     10041272.46      2690332.45     10041136.19
      2690149.71     10041093.59      2690015.56     10041128.80
      2689908.54     10041253.61      2689965.72     10041439.22
      2689958.71     10041983.89      2689998.47     10042133.73

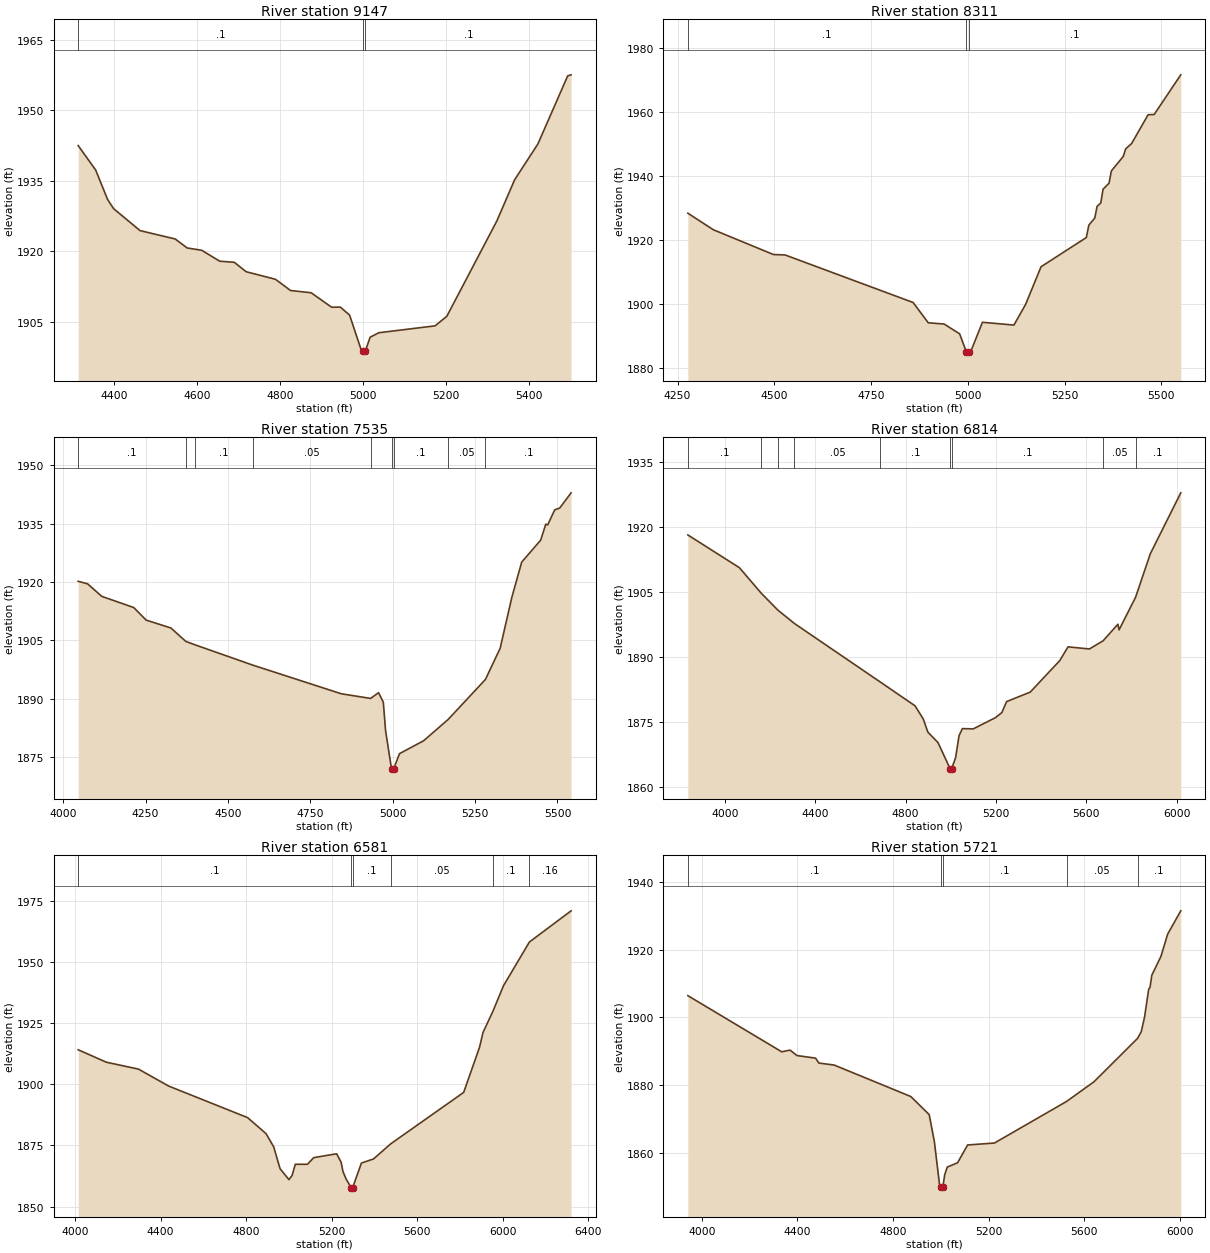
Type RM Length L Ch R = 1,9147,836,836,836
BEGIN DESCRIPTION:
UNT 1007 IN HEWA 20.0
END DESCRIPTION:
XS GIS Cut Line= 2
      2690830.32     10036494.96      2691750.44     10035744.11
#Sta/Elev= 30
  4313.2 1942.48  4355.3 1937.29  4384.1 1931.03  4398.4 1929.09  4462.3 1924.41
  4547.0 1922.63  4575.8 1920.72  4610.9 1920.23  4654.0 1917.91  4689.2 1917.68
  4717.9 1915.67  4788.4 1914.07  4824.9 1911.68  4874.5 1911.20  4924.0 1908.12
  4944.8 1908.15  4967.1 1906.46  4994.9 1899.11  4999.3 1898.87  5002.0 1898.37
  5005.3 1898.87  5016.6 1901.75  5037.4 1902.70  5173.1 1904.17  5201.4 1906.20
  5321.8 1926.44  5364.8 1935.22  5420.8 1942.82  5492.6 1957.29  5500.8 1957.52
#Mann=3,-1,0
  4313.2     0.1       0  4999.3    0.07       0  5005.3     0.1       0
Bank Sta=4999.3,5005.3
Exp/Cntr=0.3,0.1

Type RM Length L Ch R = 1,8311,776,776,776
BEGIN DESCRIPTION:
UNT 1007 IN HEWA 19.0
END DESCRIPTION:
XS GIS Cut Line= 3
      2690977.88     10036603.48      2692006.53     10036529.69
      2692214.18     10036404.23
#Sta/Elev= 30
  4276.5 1928.37  4342.5 1923.18  4497.7 1915.44  4527.7 1915.31  4858.6 1900.44
  4897.8 1894.09  4938.8 1893.70  4978.9 1890.63  4995.9 1885.10  4998.7 1884.60
  5001.9 1885.10  5009.0 1885.50  5037.8 1894.25  5119.2 1893.38  5149.3 1899.82
  5189.4 1911.63  5306.3 1920.75  5312.8 1924.63  5328.3 1926.89  5334.1 1930.49
  5343.8 1931.59  5349.6 1935.88  5365.1 1937.77  5371.0 1941.57  5402.0 1946.16
  5407.9 1948.48  5423.4 1950.17  5466.1 1959.18  5481.6 1959.23  5550.4 1971.65
#Mann=3,-1,0
  4276.5     0.1       0  4995.9    0.07       0  5001.9     0.1       0
Bank Sta=4995.9,5001.9
Exp/Cntr=0.3,0.1

Type RM Length L Ch R = 1,7535,721,721,721
BEGIN DESCRIPTION:
UNT 1007 IN HEWA 17.0
END DESCRIPTION:
XS GIS Cut Line= 3
      2691234.00     10037002.79      2692097.67     10037198.10
      2692423.20     10036681.59
#Sta/Elev= 30
  4045.4 1920.17  4074.0 1919.51  4117.1 1916.28  4214.0 1913.41  4251.8 1910.17
  4326.8 1908.15  4372.1 1904.69  4398.8 1903.85  4575.0 1898.60  4843.8 1891.22
  4932.8 1890.02  4957.1 1891.50  4971.5 1889.04  4978.3 1881.78  4996.5 1871.81
  4999.3 1871.31  5002.5 1871.81  5020.7 1875.81  5093.7 1879.12  5168.2 1884.60
  5281.4 1894.90  5326.1 1902.92  5361.6 1916.04  5391.5 1925.10  5449.2 1930.77
  5464.5 1934.85  5470.4 1934.68  5491.6 1938.53  5506.9 1939.02  5541.4 1942.93
#Mann=9,-1,0
  4045.4     0.1       0  4372.1    0.05       0  4398.8     0.1       0
  4575.0    0.05       0  4932.8     0.1       0  4996.5    0.07       0
  5002.5     0.1       0  5168.2    0.05       0  5281.4     0.1       0
Bank Sta=4996.5,5002.5
Exp/Cntr=0.3,0.1

Type RM Length L Ch R = 1,6814,233,233,233
BEGIN DESCRIPTION:
UNT 1007 IN HEWA 16.0
END DESCRIPTION:
XS GIS Cut Line= 5
      2691290.44     10037315.64      2691988.39     10037286.99
      2692454.54     10037602.10      2692608.19     10037440.64
      2692501.42     10036750.53
#Sta/Elev= 30
  3835.6 1918.24  4063.8 1910.68  4161.1 1904.75  4233.9 1900.89  4307.3 1897.79
  4688.0 1884.25  4841.4 1878.77  4877.4 1875.78  4898.4 1872.68  4943.3 1870.26
  4997.2 1864.18  5000.0 1863.68  5003.2 1864.18  5021.2 1866.81  5036.2 1871.86
  5051.1 1873.50  5099.1 1873.44  5197.4 1876.03  5225.7 1877.19  5246.8 1879.74
  5351.3 1881.93  5482.4 1889.22  5518.9 1892.39  5613.6 1891.90  5674.3 1893.79
  5739.7 1897.62  5744.8 1896.31  5817.8 1903.83  5883.2 1913.90  6018.0 1927.97
#Mann=9,-1,0
  3835.6     0.1       0  4161.1    0.05       0  4233.9     0.1       0
  4307.3    0.05       0  4688.0     0.1       0  4997.2    0.07       0
  5003.2     0.1       0  5674.3    0.05       0  5817.8     0.1       0
Bank Sta=4997.2,5003.2
Exp/Cntr=0.3,0.1

Type RM Length L Ch R = 1,6581,860,860,860
BEGIN DESCRIPTION:
UNT 1007 IN HEWA 15.0
END DESCRIPTION:
XS GIS Cut Line= 4
      2691307.75     10037554.00      2691902.36     10037497.57
      2692653.23     10038027.09      2693438.79     10038096.53
#Sta/Elev= 30
  4014.4 1914.20  4145.7 1909.11  4296.4 1906.27  4437.0 1899.35  4806.7 1886.40
  4892.9 1879.83  4928.6 1874.44  4958.2 1865.52  5000.0 1861.00  5014.8 1862.76
  5029.6 1867.30  5086.2 1867.28  5115.8 1870.02  5222.9 1871.59  5243.8 1868.14
  5252.5 1864.29  5267.3 1861.23  5291.3 1857.62  5294.1 1857.12  5297.3 1857.62
  5338.7 1867.80  5395.3 1869.48  5475.7 1875.67  5816.8 1896.73  5891.0 1915.21
  5907.2 1921.25  5953.0 1929.84  6003.0 1940.42  6124.2 1958.33  6319.1 1971.10
#Mann=6,-1,0
  4014.4     0.1       0  5291.3    0.07       0  5297.3     0.1       0
  5475.7    0.05       0  5953.0     0.1       0  6124.2    0.16       0
Bank Sta=5291.3,5297.3
Exp/Cntr=0.3,0.1

Type RM Length L Ch R = 1,5721,231,231,231
BEGIN DESCRIPTION:
UNT 1007 IN HEWA 13.0
END DESCRIPTION:
XS GIS Cut Line= 4
      2691406.67     10037742.34      2691953.57     10038382.99
      2692411.91     10038570.49      2693068.18     10038263.19
#Sta/Elev= 30
  3941.4 1906.37  4334.0 1889.78  4369.1 1890.28  4397.7 1888.67  4475.6 1887.90
  4489.9 1886.44  4553.6 1885.86  4874.1 1876.56  4951.1 1871.21  4972.7 1863.24
  4994.3 1850.53  5002.0 1849.69  5004.7 1849.19  5008.0 1849.69  5015.9 1853.42
  5026.7 1855.71  5069.9 1856.98  5111.8 1862.24  5224.0 1862.81  5525.6 1875.09
  5640.9 1880.94  5823.5 1893.79  5838.3 1895.74  5851.9 1899.94  5869.3 1908.22
  5874.8 1908.79  5882.5 1912.41  5920.4 1917.93  5948.8 1924.56  6003.6 1931.44
#Mann=5,-1,0
  3941.4     0.1       0  5002.0    0.07       0  5008.0     0.1       0
  5525.6    0.05       0  5823.5     0.1       0
Bank Sta=5002,5008
Exp/Cntr=0.3,0.1

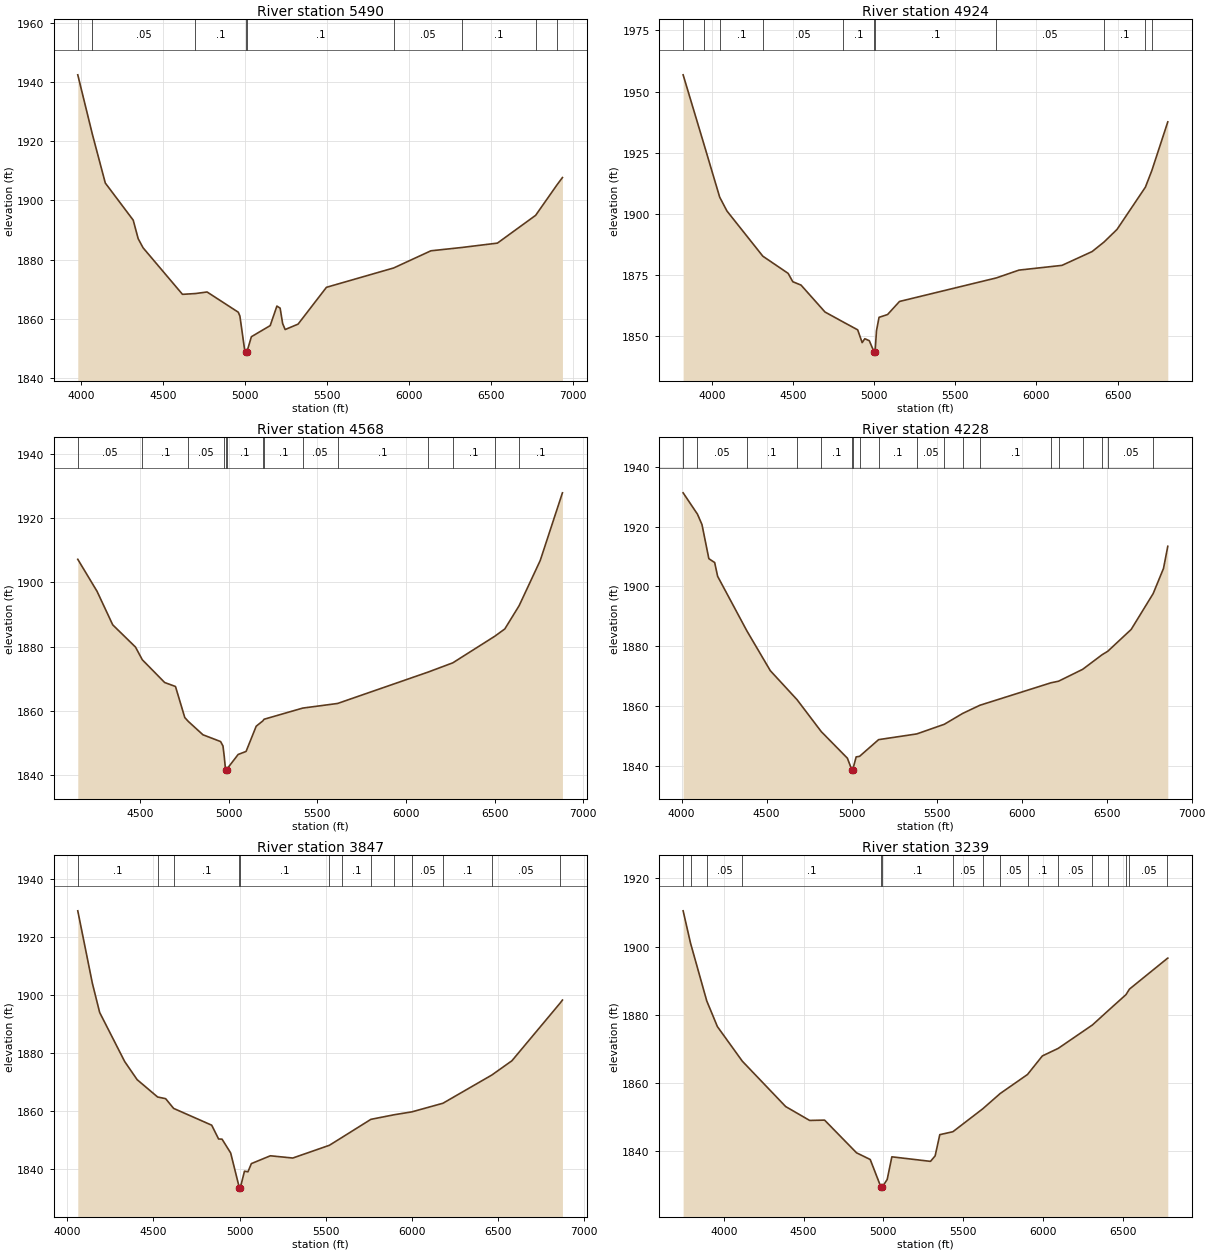
Type RM Length L Ch R = 1,5490,566,566,566
BEGIN DESCRIPTION:
UNT 1007 IN HEWA 12.0
END DESCRIPTION:
XS GIS Cut Line= 4
      2691130.62     10038643.41      2692344.20     10038700.70
      2692734.82     10039320.49      2693729.61     10039487.16
#Sta/Elev= 30
  3980.0 1942.56  4069.7 1922.29  4148.0 1905.90  4318.2 1893.34  4348.3 1887.08
  4378.3 1883.98  4618.6 1868.21  4698.0 1868.48  4768.7 1869.01  4958.9 1862.16
  4968.9 1860.88  4999.0 1848.93  5006.0 1848.80  5008.7 1848.30  5012.0 1848.80
  5039.0 1853.86  5153.7 1857.62  5194.6 1864.24  5214.3 1863.54  5229.6 1858.33
  5244.9 1856.29  5323.7 1858.12  5496.8 1870.59  5907.0 1877.15  6134.0 1882.96
  6321.0 1884.07  6539.6 1885.56  6772.8 1894.97  6902.2 1905.23  6936.2 1907.76
#Mann=9,-1,0
  3980.0     0.1       0  4069.7    0.05       0  4698.0     0.1       0
  5006.0    0.07       0  5012.0     0.1       0  5907.0    0.05       0
  6321.0     0.1       0  6772.8    0.05       0  6902.2     0.1       0
Bank Sta=5006,5012
Exp/Cntr=0.3,0.1

Type RM Length L Ch R = 1,4924,356,356,356
BEGIN DESCRIPTION:
UNT 1007 IN HEWA 11.0
END DESCRIPTION:
XS GIS Cut Line= 3
      2691068.12     10038679.85      2692693.16     10039549.66
      2693833.67     10039617.36
#Sta/Elev= 30
  3823.8 1956.87  3949.9 1928.97  4048.9 1906.88  4093.8 1901.19  4314.8 1882.72
  4470.7 1875.70  4499.3 1872.29  4550.1 1870.91  4697.6 1859.91  4811.4 1855.76
  4899.1 1852.61  4926.7 1847.39  4943.0 1848.98  4970.6 1848.18  5000.1 1843.59
  5002.9 1843.09  5006.1 1843.59  5015.1 1852.30  5030.7 1857.72  5083.2 1858.87
  5156.7 1864.21  5754.0 1873.85  5892.7 1877.03  6157.9 1878.97  6343.5 1884.62
  6417.0 1888.53  6496.9 1893.68  6671.5 1910.94  6711.3 1917.75  6809.5 1937.64
#Mann=11,-1,0
  3823.8     0.1       0  3949.9    0.05       0  4048.9     0.1       0
  4314.8    0.05       0  4811.4     0.1       0  5000.1    0.07       0
  5006.1     0.1       0  5754.0    0.05       0  6417.0     0.1       0
  6671.5    0.05       0  6711.3     0.1       0
Bank Sta=5000.1,5006.1
Exp/Cntr=0.3,0.1

Type RM Length L Ch R = 1,4568,340,340,340
BEGIN DESCRIPTION:
UNT 1007 IN HEWA 10.0
END DESCRIPTION:
XS GIS Cut Line= 3
      2691120.22     10039148.61      2692448.37     10039778.82
      2693713.74     10039768.41
#Sta/Elev= 30
  4147.9 1907.13  4256.6 1897.18  4345.2 1886.74  4473.6 1879.83  4512.1 1875.88
  4638.3 1868.80  4699.4 1867.56  4751.9 1857.90  4771.8 1856.69  4854.4 1852.54
  4954.0 1850.43  4967.6 1849.04  4974.6 1845.80  4981.8 1841.73  4984.6 1841.23
  4987.8 1841.73  5053.0 1846.41  5097.9 1847.36  5155.0 1855.21  5192.6 1856.86
  5199.5 1857.37  5417.5 1860.84  5614.5 1862.28  6123.1 1872.00  6264.6 1874.92
  6502.1 1883.21  6558.1 1885.46  6639.0 1892.70  6758.1 1906.76  6883.4 1927.81
#Mann=14,-1,0
  4147.9    0.05       0  4512.1     0.1       0  4771.8    0.05       0
  4974.6     0.1       0  4981.8    0.07       0  4987.8     0.1       0
  5192.6    0.05       0  5199.5     0.1       0  5417.5    0.05       0
  5614.5     0.1       0  6123.1    0.05       0  6264.6     0.1       0
  6502.1    0.05       0  6639.0     0.1       0
Bank Sta=4981.8,4987.8
Exp/Cntr=0.3,0.1

Type RM Length L Ch R = 1,4228,381,381,381
BEGIN DESCRIPTION:
UNT 1007 IN HEWA 9.0
END DESCRIPTION:
XS GIS Cut Line= 3
      2690859.87     10039403.84      2692120.24     10039981.95
      2693583.67     10039950.70
#Sta/Elev= 30
  4009.2 1931.32  4093.7 1924.16  4120.0 1920.71  4160.5 1909.28  4194.7 1907.99
  4212.0 1903.39  4384.0 1885.12  4521.9 1871.79  4679.3 1862.07  4821.7 1851.38
  4975.3 1842.49  5000.8 1838.66  5003.6 1838.16  5006.8 1838.66  5026.8 1842.92
  5046.8 1843.11  5158.8 1848.70  5383.0 1850.61  5545.6 1853.85  5653.4 1857.48
  5754.2 1860.20  6172.7 1867.73  6217.2 1868.26  6359.0 1872.24  6473.6 1877.14
  6506.5 1878.28  6644.3 1885.59  6773.7 1897.60  6834.4 1906.02  6859.6 1913.43
#Mann=19,-1,0
  4009.2     0.1       0  4093.7    0.05       0  4384.0     0.1       0
  4679.3    0.05       0  4821.7     0.1       0  5000.8    0.07       0
  5006.8     0.1       0  5046.8    0.05       0  5158.8     0.1       0
  5383.0    0.05       0  5545.6     0.1       0  5653.4    0.05       0
  5754.2     0.1       0  6172.7    0.05       0  6217.2     0.1       0
  6359.0    0.05       0  6473.6     0.1       0  6506.5    0.05       0
  6773.7     0.1       0
Bank Sta=5000.8,5006.8
Exp/Cntr=0.3,0.1

Type RM Length L Ch R = 1,3847,608,608,608
BEGIN DESCRIPTION:
UNT 1007 IN HEWA 8.0
END DESCRIPTION:
XS GIS Cut Line= 3
      2690823.37     10039830.91      2691359.82     10040195.49
      2693521.30     10040070.49
#Sta/Elev= 30
  4060.6 1928.89  4145.5 1903.90  4187.7 1893.89  4332.8 1877.01  4405.3 1870.75
  4524.2 1864.78  4570.6 1864.21  4617.2 1860.85  4838.1 1855.08  4878.1 1850.33
  4898.2 1850.27  4948.3 1845.51  4998.4 1833.56  5001.2 1833.06  5004.4 1833.56
  5028.4 1839.24  5048.4 1839.02  5068.5 1841.85  5178.6 1844.54  5308.9 1843.77
  5521.1 1848.15  5592.4 1850.78  5762.3 1857.09  5899.1 1858.69  6000.1 1859.66
  6180.6 1862.63  6464.4 1872.35  6581.0 1877.26  6862.0 1897.20  6874.3 1898.16
#Mann=13,-1,0
  4060.6     0.1       0  4524.2    0.05       0  4617.2     0.1       0
  4998.4    0.07       0  5004.4     0.1       0  5521.1    0.05       0
  5592.4     0.1       0  5762.3    0.05       0  5899.1     0.1       0
  6000.1    0.05       0  6180.6     0.1       0  6464.4    0.05       0
  6862.0     0.1       0
Bank Sta=4998.4,5004.4
Exp/Cntr=0.3,0.1

Type RM Length L Ch R = 1,3239,429,429,429
BEGIN DESCRIPTION:
UNT 1007 IN HEWA 7.0
END DESCRIPTION:
XS GIS Cut Line= 2
      2690745.25     10039997.58      2693181.85     10041809.41
#Sta/Elev= 30
  3745.5 1910.49  3791.9 1901.01  3893.4 1884.10  3960.2 1876.55  4116.3 1866.41
  4387.8 1853.11  4538.0 1849.04  4631.8 1849.13  4832.1 1839.54  4917.6 1837.59
  4985.5 1829.40  4988.3 1828.90  4991.5 1829.40  5024.0 1831.73  5053.2 1838.37
  5295.1 1837.04  5324.3 1838.64  5353.5 1844.87  5435.6 1845.73  5621.9 1852.42
  5731.6 1856.92  5903.0 1862.51  5996.0 1867.95  6095.7 1870.17  6309.8 1877.03
  6409.1 1881.26  6520.2 1885.93  6541.5 1887.53  6779.6 1896.56  6781.9 1896.62
#Mann=16,-1,0
  3745.5    0.16       0  3791.9     0.1       0  3893.4    0.05       0
  4116.3     0.1       0  4985.5    0.07       0  4991.5     0.1       0
  5435.6    0.05       0  5621.9     0.1       0  5731.6    0.05       0
  5903.0     0.1       0  6095.7    0.05       0  6309.8     0.1       0
  6409.1    0.05       0  6520.2     0.1       0  6541.5    0.05       0
  6779.6    0.16       0
Bank Sta=4985.5,4991.5
Exp/Cntr=0.3,0.1

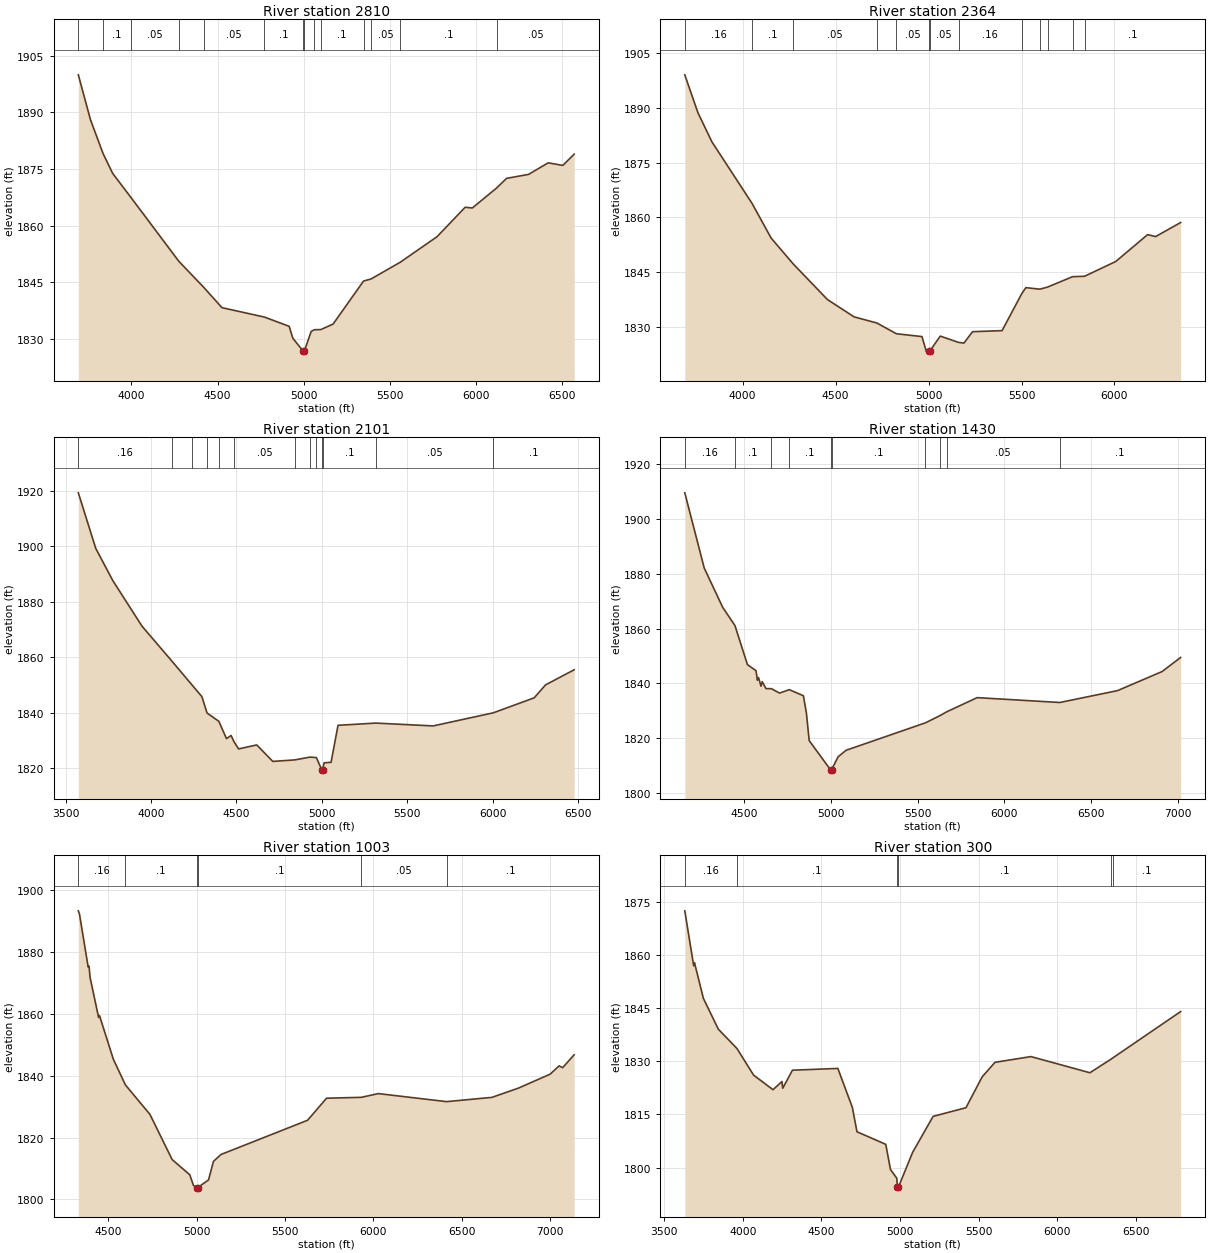
Type RM Length L Ch R = 1,2810,446,446,446
BEGIN DESCRIPTION:
UNT 1007 IN HEWA 6.0
END DESCRIPTION:
XS GIS Cut Line= 3
      2690703.56     10040080.89      2691213.99     10040836.12
      2692723.94     10042101.35
#Sta/Elev= 30
  3691.2 1899.95  3761.7 1888.06  3834.6 1879.13  3890.6 1873.84  4000.1 1867.26
  4275.6 1850.51  4419.8 1843.64  4525.9 1838.24  4772.4 1835.75  4916.7 1833.29
  4937.5 1830.16  4998.3 1826.69  5001.0 1826.19  5004.3 1826.69  5044.2 1831.92
  5062.0 1832.39  5100.3 1832.43  5171.7 1833.89  5348.8 1845.30  5392.2 1845.84
  5561.7 1850.27  5775.4 1857.03  5939.3 1864.85  5981.0 1864.66  6121.5 1869.93
  6180.0 1872.51  6307.5 1873.56  6422.0 1876.63  6506.6 1875.94  6572.7 1878.92
#Mann=14,-1,0
  3691.2    0.16       0  3834.6     0.1       0  4000.1    0.05       0
  4275.6     0.1       0  4419.8    0.05       0  4772.4     0.1       0
  4998.3    0.07       0  5004.3     0.1       0  5062.0    0.05       0
  5100.3     0.1       0  5348.8    0.16       0  5392.2    0.05       0
  5561.7     0.1       0  6121.5    0.05       0
Bank Sta=4998.3,5004.3
Exp/Cntr=0.3,0.1

Type RM Length L Ch R = 1,2364,263,263,263
BEGIN DESCRIPTION:
UNT 1007 IN HEWA 5.0
END DESCRIPTION:
XS GIS Cut Line= 3
      2690625.43     10040132.95      2691312.95     10041679.87
      2692073.07     10042289.00
#Sta/Elev= 30
  3688.8 1899.06  3759.3 1888.70  3834.5 1880.72  4050.5 1863.86  4153.3 1854.35
  4271.6 1847.30  4455.7 1837.54  4599.2 1832.78  4721.8 1831.10  4826.8 1828.16
  4964.4 1827.38  4987.7 1823.36  4999.8 1823.35  5002.6 1822.85  5005.8 1823.35
  5062.9 1827.51  5161.4 1825.79  5190.1 1825.60  5236.6 1828.72  5395.4 1829.01
  5501.4 1839.16  5523.5 1840.78  5598.9 1840.37  5639.8 1840.93  5774.3 1843.78
  5839.1 1843.90  6006.8 1847.94  6178.1 1855.30  6221.3 1854.77  6355.7 1858.61
#Mann=13,-1,0
  3688.8    0.16       0  4050.5     0.1       0  4271.6    0.05       0
  4721.8     0.1       0  4826.8    0.05       0  4999.8   0.035       0
  5005.8    0.05       0  5161.4    0.16       0  5501.4     0.1       0
  5598.9    0.05       0  5639.8     0.1       0  5774.3    0.05       0
  5839.1     0.1       0
Bank Sta=4999.8,5005.8
Exp/Cntr=0.3,0.1

Type RM Length L Ch R = 1,2101,671,671,671
BEGIN DESCRIPTION:
UNT 1007 IN HEWA 4.0
END DESCRIPTION:
XS GIS Cut Line= 4
      2690161.90     10040257.98      2690880.66     10041221.53
      2690995.24     10041825.70      2691896.30     10042429.87
#Sta/Elev= 30
  3574.7 1919.19  3676.6 1899.21  3776.6 1887.59  3947.6 1871.18  4122.7 1858.60
  4241.5 1849.94  4297.9 1845.84  4328.0 1839.95  4397.3 1836.94  4441.7 1830.73
  4468.8 1831.85  4486.1 1829.57  4512.6 1827.02  4618.9 1828.46  4712.8 1822.53
  4841.7 1823.07  4930.3 1824.08  4967.9 1823.90  4999.2 1819.53  5002.0 1819.03
  5005.2 1819.53  5013.1 1822.03  5053.9 1822.20  5094.6 1835.52  5316.1 1836.32
  5651.5 1835.30  6004.3 1840.03  6242.8 1845.41  6308.8 1850.05  6476.6 1855.51
#Mann=13,-1,0
  3574.7    0.16       0  4122.7    0.05       0  4241.5     0.1       0
  4328.0    0.05       0  4397.3     0.1       0  4486.1    0.05       0
  4841.7     0.1       0  4930.3    0.05       0  4967.9     0.1       0
  4999.2    0.07       0  5005.2     0.1       0  5316.1    0.05       0
  6004.3     0.1       0
Bank Sta=4999.2,5005.2
Exp/Cntr=0.3,0.1

Type RM Length L Ch R = 1,1430,427,427,427
BEGIN DESCRIPTION:
UNT 1007 IN HEWA 3.0
END DESCRIPTION:
XS GIS Cut Line= 4
      2689941.11     10040473.44      2690378.58     10040994.23
      2690316.08     10041431.73      2691698.06     10042473.43
#Sta/Elev= 30
  4160.9 1909.52  4272.8 1882.07  4379.5 1867.70  4449.3 1861.14  4521.3 1846.87
  4570.7 1844.65  4578.5 1841.18  4585.0 1842.18  4599.3 1839.00  4605.9 1840.68
  4627.9 1838.13  4659.5 1838.09  4706.0 1836.48  4762.1 1837.74  4843.3 1835.52
  4860.7 1829.16  4876.6 1819.16  4999.2 1808.53  5001.9 1808.03  5005.2 1808.53
  5042.6 1813.23  5088.7 1815.63  5545.4 1825.64  5627.7 1828.23  5667.3 1829.65
  5843.1 1834.83  6318.7 1833.06  6650.8 1837.39  6906.9 1844.34  7013.6 1849.48
#Mann=10,-1,0
  4160.9    0.16       0  4449.3     0.1       0  4659.5    0.05       0
  4762.1     0.1       0  4999.2    0.07       0  5005.2     0.1       0
  5545.4    0.05       0  5627.7     0.1       0  5667.3    0.05       0
  6318.7     0.1       0
Bank Sta=4999.2,5005.2
Exp/Cntr=0.3,0.1

Type RM Length L Ch R = 1,1003,703,703,703
BEGIN DESCRIPTION:
Mapping XS 8ac4be3d
END DESCRIPTION:
XS GIS Cut Line= 4
      2689752.89     10040558.51      2689835.37     10041022.96
      2690299.78     10041561.16      2691604.61     10042527.86
#Sta/Elev= 30
  4330.0 1893.38  4336.8 1892.24  4385.7 1875.19  4390.8 1875.46  4396.2 1871.91
  4444.8 1858.87  4449.9 1859.46  4528.3 1845.35  4596.6 1837.04  4735.1 1827.54
  4861.1 1812.89  4960.9 1807.97  4981.8 1804.52  4999.6 1803.83  5002.4 1803.33
  5005.6 1803.83  5066.9 1806.30  5094.8 1812.30  5137.5 1814.54  5627.6 1825.61
  5735.0 1832.75  5931.3 1833.03  6028.3 1834.24  6414.4 1831.64  6671.1 1833.02
  6821.4 1836.02  7000.9 1840.54  7051.0 1843.20  7071.8 1842.64  7136.5 1846.81
#Mann=6,-1,0
  4330.0    0.16       0  4596.6     0.1       0  4999.6    0.07       0
  5005.6     0.1       0  5931.3    0.05       0  6414.4     0.1       0
Bank Sta=4999.6,5005.6
Exp/Cntr=0.3,0.1

Type RM Length L Ch R = 1,300,0,0,0
BEGIN DESCRIPTION:
UNT 1007 IN HEWA 1.0
END DESCRIPTION:
XS GIS Cut Line= 4
      2689644.39     10040593.27      2689844.05     10041830.25
      2690265.05     10041864.98      2691558.49     10042576.80
#Sta/Elev= 30
  3632.0 1872.61  3688.6 1857.06  3693.6 1857.94  3750.3 1847.83  3845.2 1839.13
  3963.2 1833.69  4069.3 1826.14  4192.8 1822.01  4249.5 1824.33  4254.6 1822.43
  4316.4 1827.53  4604.9 1828.03  4697.1 1817.01  4726.4 1810.12  4909.5 1806.56
  4939.6 1799.43  4979.7 1796.96  4983.4 1794.39  4986.2 1793.89  4989.4 1794.39
  5080.1 1804.28  5210.5 1814.47  5419.3 1816.92  5522.6 1825.67  5604.0 1829.76
  5832.2 1831.38  6207.2 1826.81  6342.1 1830.67  6353.2 1831.02  6783.8 1844.11
#Mann=6,-1,0
  3632.0    0.16       0  3963.2     0.1       0  4983.4    0.07       0
  4989.4     0.1       0  6342.1    0.16       0  6353.2     0.1       0
Bank Sta=4983.4,4989.4
Exp/Cntr=0.3,0.1

Chan Stop Cuts=-1