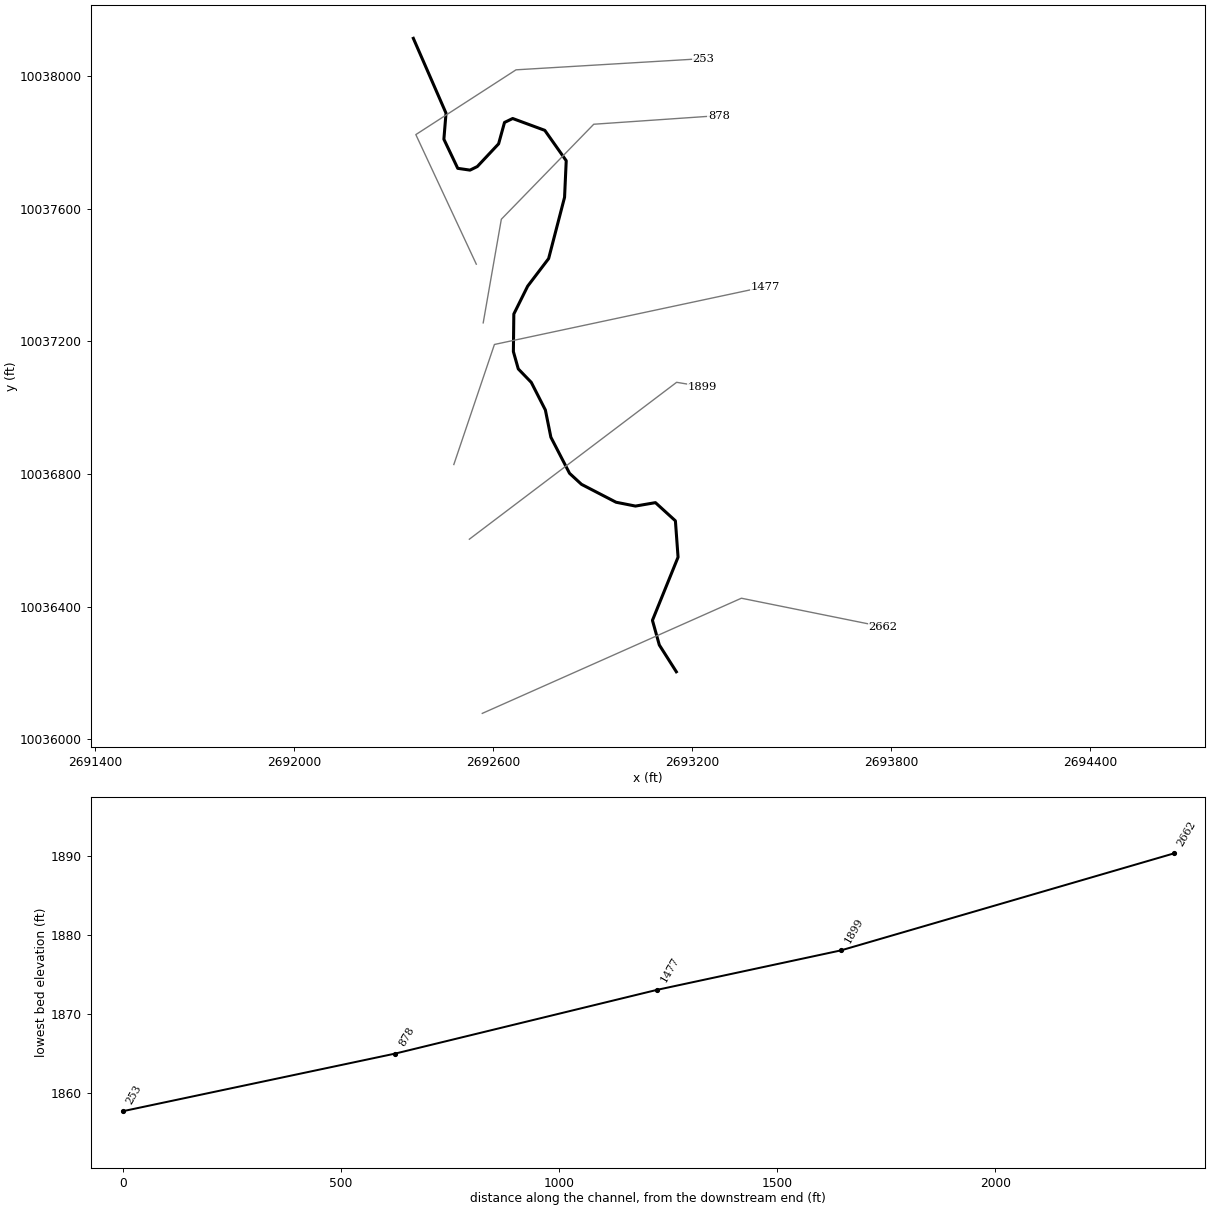
--- UNT 1008 IN HEWA.prj (project) ---

Proj Title=UNT 1008 IN HEWA Base Level Engineering
Current Plan=p01
Default Exp/Contr=0.3,0.1
English Units
Geom File=g01
Flow File=f01
Plan File=p01
Y Axis Title=Elevation
X Axis Title(PF)=Main Channel Distance
X Axis Title(XS)=Station
BEGIN DESCRIPTION:
UNT 1008 IN HEWA
END DESCRIPTION:
DSS Export Rating Curves= 0
DSS Export Rating Curve Sorted= 0
DSS Export Volume Flow Curves= 0
DXF OffsetX= 0
DXF OffsetY= 0
DXF ScaleX= 1
DXF ScaleY= 10

--- UNT 1008 IN HEWA.p01 (plan) ---

Plan Title=Multiple Run
Short Identifier=Multiple
Geom File=g01
Flow File=f01
Subcritical Flow
K Sum by GR= 0
Std Step Tol= 0.01
Critical Tol= 0.01
Num of Std Step Trials= 20
Max Error Tol= 0.3
Flow Tol Ratio= 0.001
Split Flow NTrial= 30
Split Flow Tol= 0.02
Split Flow Ratio= 0.02
Log Output Level= 0
Friction Slope Method= 1
Unsteady Friction Slope Method= 2
Unsteady Bridges Friction Slope Method= 1
Parabolic Critical Depth
Global Vel Dist=  1 , 1 , 1
Global Log Level= 0
CheckData=True
Encroach Param= -1, 0, 0, 0
BEGIN DESCRIPTION:
Multiple Run
END DESCRIPTION:

--- UNT 1008 IN HEWA.f01 (steady flow) ---

Flow Title=Multiple
Number of Profiles=7
Profile Names=10-year,25-year,50-year,1pct_min,100-year,1pct_plu,500-year
River Rch & RM= UNT 1008 IN HEWA,Reach-1,2662
    1388    2062    2657    2498    3378    4569    5458
Boundary for River Rch & Prof#=UNT 1008 IN HEWA,Reach-1,1
Up Type=0
Dn Type=3
Dn Slope=0.005
Boundary for River Rch & Prof#=UNT 1008 IN HEWA,Reach-1,2
Up Type=0
Dn Type=3
Dn Slope=0.005
Boundary for River Rch & Prof#=UNT 1008 IN HEWA,Reach-1,3
Up Type=0
Dn Type=3
Dn Slope=0.005
Boundary for River Rch & Prof#=UNT 1008 IN HEWA,Reach-1,4
Up Type=0
Dn Type=3
Dn Slope=0.005
Boundary for River Rch & Prof#=UNT 1008 IN HEWA,Reach-1,5
Up Type=0
Dn Type=3
Dn Slope=0.005
Boundary for River Rch & Prof#=UNT 1008 IN HEWA,Reach-1,6
Up Type=0
Dn Type=3
Dn Slope=0.005
Boundary for River Rch & Prof#=UNT 1008 IN HEWA,Reach-1,7
Up Type=0
Dn Type=3
Dn Slope=0.005

--- UNT 1008 IN HEWA.g01 (geometry) ---

Geom Title=Existing Conditions
Program Version=4.10

River Reach=UNT 1008 IN HEWA,Reach-1
Reach XY= 30
      2693151.52     10036203.73      2693100.17     10036284.48
      2693079.43     10036358.79      2693156.69     10036549.29
      2693148.68     10036658.88      2693088.47     10036713.73
      2693028.25     10036703.38      2692969.77     10036714.92
      2692865.53      10036768.9      2692829.44     10036802.21
      2692773.18     10036910.97      2692756.63     10036992.99
      2692714.17     10037076.25      2692674.89       10037117.
      2692660.15     10037169.19      2692661.49     10037282.46
      2692703.23     10037366.47      2692766.41     10037449.59
      2692814.45     10037634.41      2692819.47     10037744.74
      2692754.88     10037836.28      2692658.02     10037872.01
      2692633.39     10037860.09      2692615.59     10037795.65
      2692551.38     10037727.15      2692529.39     10037716.37
      2692492.39     10037721.73      2692450.58      10037809.5
      2692457.02     10037888.08      2692358.47     10038113.73

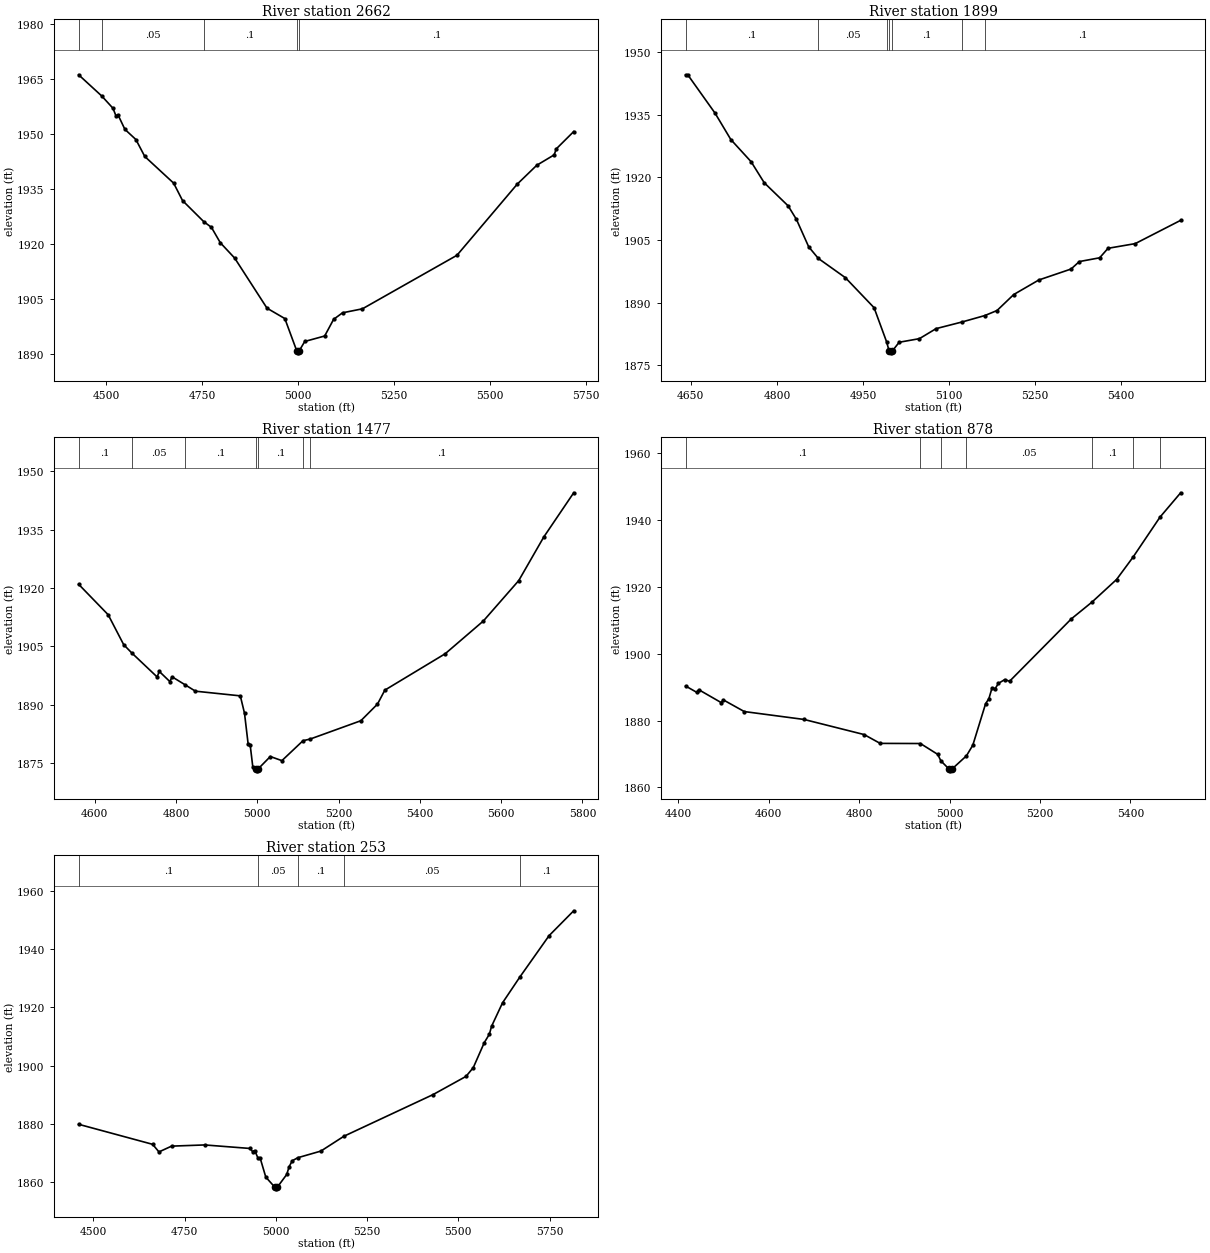
Type RM Length L Ch R = 1 ,2662    ,763,763,763
BEGIN DESCRIPTION:
UNT 1008 IN HEWA 3.0
END DESCRIPTION:
XS GIS Cut Line= 3
      2692566.42      10036078.3      2693347.67     10036425.53
      2693775.39     10036339.12
#Sta/Elev= 30
  4427.5 1966.07  4487.9 1960.28  4517.3 1956.92  4524.9 1954.87  4530.4 1955.11
  4548.2  1951.2  4576.9 1948.42  4600.1  1943.8  4675.4 1936.53  4698.6 1931.78
    4754 1926.03  4773.9 1924.49  4797.1 1920.29  4834.6  1916.1  4918.9 1902.45
  4965.4 1899.62  4996.6 1890.78  4999.3 1890.28  5002.6 1890.78  5017.3 1893.38
  5069.3 1894.87  5092.6 1899.41  5115.8 1901.19  5167.8 1902.28  5414.3 1916.87
  5571.6 1936.27  5622.4  1941.4    5668 1944.25  5673.1 1945.85  5718.8 1950.59
#Mann= 5 ,-1 , 0
  4427.5      .1       0  4487.9     .05       0    4754      .1       0
  4996.6     .07       0  5002.6      .1       0
Bank Sta=4996.6,5002.6
XS Rating Curve= 0 ,0
Exp/Cntr=0.3,0.1

Type RM Length L Ch R = 1 ,1899    ,422,422,422
BEGIN DESCRIPTION:
UNT 1008 IN HEWA 2.0
END DESCRIPTION:
XS GIS Cut Line= 3
       2692527.4     10036603.51      2693152.36     10037076.57
      2693230.47     10037063.55
#Sta/Elev= 30
  4640.8 1944.51  4644.6 1944.51  4692.3 1935.31  4719.7 1929.02  4755.1 1923.71
  4777.9 1918.69  4819.6 1913.16  4834.1 1909.91  4855.4 1903.37  4872.2 1900.59
  4919.4 1895.98  4969.4  1888.8  4991.2 1880.65  4995.5 1878.51  4998.2 1878.01
  5001.5 1878.51  5013.1 1880.54  5048.4  1881.4  5077.5  1883.8  5122.7 1885.39
  5162.5 1886.93  5183.7 1888.13  5212.8 1891.95  5256.5 1895.43  5312.7 1898.05
  5327.2 1899.84  5362.6 1900.74  5377.2 1903.01  5424.6 1904.13  5503.8  1909.7
#Mann= 7 ,-1 , 0
  4640.8      .1       0  4872.2     .05       0  4991.2      .1       0
  4995.5     .07       0  5001.5      .1       0  5122.7     .05       0
  5162.5      .1       0
Bank Sta=4995.5,5001.5
XS Rating Curve= 0 ,0
Exp/Cntr=0.3,0.1

Type RM Length L Ch R = 1 ,1477    ,599,599,599
BEGIN DESCRIPTION:
Mapping XS dfa1138d
END DESCRIPTION:
XS GIS Cut Line= 3
      2692480.58     10036828.66      2692602.98     10037190.64
      2693420.66     10037365.11
#Sta/Elev= 30
  4560.3 1920.96    4633 1913.13  4671.2 1905.44  4691.1 1903.31  4753.5 1897.14
  4758.8 1898.56  4784.9 1895.94  4790.2 1897.18  4823.3 1895.06  4847.8 1893.48
  4958.2 1892.28  4968.5 1887.81  4977.4 1879.94  4982.5 1879.61  4988.9 1874.03
  4996.1 1873.51  4998.9 1873.01  5002.1 1873.51    5032 1876.69  5060.5 1875.63
  5112.4 1880.75  5130.1 1881.18  5254.8 1885.89  5295.7 1890.16  5313.8 1893.75
  5462.4 1903.11  5556.3 1911.53  5643.3 1921.91  5704.9 1933.11  5778.5 1944.47
#Mann= 7 ,-1 , 0
  4560.3      .1       0  4691.1     .05       0  4823.3      .1       0
  4996.1     .07       0  5002.1      .1       0  5112.4     .05       0
  5130.1      .1       0
Bank Sta=4996.1,5002.1
XS Rating Curve= 0 ,0
Exp/Cntr=0.3,0.1

Type RM Length L Ch R = 1 ,878     ,625,625,625
BEGIN DESCRIPTION:
Mapping XS 8e7ec632
END DESCRIPTION:
XS GIS Cut Line= 4
      2692569.13     10037255.77      2692623.81     10037568.24
      2692902.46      10037854.7      2693280.01     10037880.74
#Sta/Elev= 30
  4415.8 1890.34    4440 1888.48  4445.1 1889.22  4494.4 1885.39  4499.5 1886.17
  4545.7 1882.69  4677.9 1880.33  4810.8 1875.81  4846.3 1873.17  4935.4 1873.13
  4973.6 1869.89  4980.6 1867.95  4998.9 1865.46  5001.6 1864.96  5004.9 1865.46
  5037.2 1869.45  5051.3 1872.64  5079.6 1885.06  5086.8 1886.53  5093.7 1889.72
  5100.9 1889.58  5107.9 1891.12    5122 1892.26  5132.6 1891.75    5269 1910.39
  5314.7 1915.41  5369.2 1922.18  5405.7 1928.87  5465.3 1940.83  5511.1 1948.13
#Mann= 7 ,-1 , 0
  4415.8      .1       0  4935.4     .05       0  4980.6    .035       0
  5037.2     .05       0  5314.7      .1       0  5405.7     .05       0
  5465.3      .1       0
Bank Sta=4998.9,5004.9
XS Rating Curve= 0 ,0
Exp/Cntr=0.3,0.1

Type RM Length L Ch R = 1 ,253     ,0,0,0
BEGIN DESCRIPTION:
UNT 1008 IN HEWA 1.0
END DESCRIPTION:
XS GIS Cut Line= 4
      2692548.31     10037432.79        2692366.     10037823.45
      2692668.08     10038018.77      2693233.14     10038052.62
#Sta/Elev= 30
  4459.2 1879.85  4662.1 1872.96  4679.4 1870.35    4714 1872.34  4804.8 1872.75
    4929 1871.54  4935.9 1870.49  4941.8  1870.8  4951.1 1868.16    4957 1868.14
  4972.2  1861.7  4997.4 1858.16  5000.2 1857.66  5003.4 1858.16  5029.6  1862.6
  5036.1 1865.24  5044.7 1867.31  5059.9 1868.36  5123.2 1870.64  5186.5 1875.75
  5430.7 1890.06  5520.9 1896.31  5540.9 1899.33    5571 1907.91    5585 1910.82
    5591 1913.54  5621.1 1921.61  5668.3 1930.43  5748.7  1944.7  5816.1 1953.24
#Mann= 5 ,-1 , 0
  4459.2      .1       0  4951.1     .05       0  5059.9      .1       0
  5186.5     .05       0  5668.3      .1       0
Bank Sta=4997.4,5003.4
XS Rating Curve= 0 ,0
Exp/Cntr=0.3,0.1

Chan Stop Cuts=-1
Use User Specified Reach Order=0
Composite Channel Slope=5