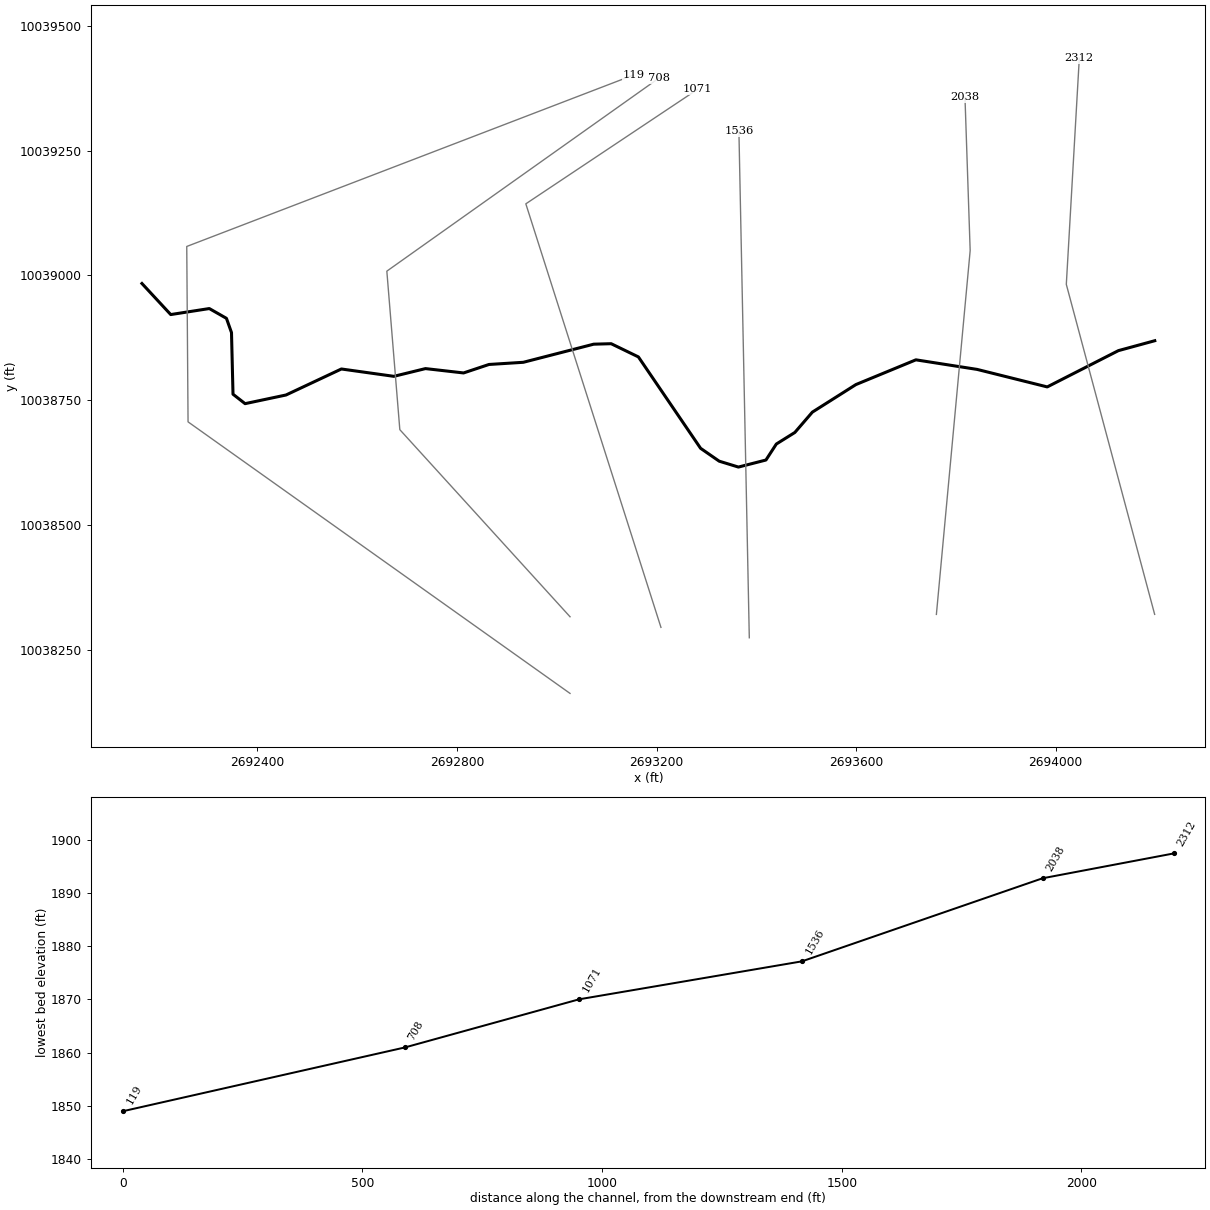
--- UNT 1009 IN HEWA.prj (project) ---

Proj Title=UNT 1009 IN HEWA Base Level Engineering
Current Plan=p01
Default Exp/Contr=0.3,0.1
English Units
Geom File=g01
Flow File=f01
Plan File=p01
BEGIN DESCRIPTION:
UNT 1009 IN HEWA
END DESCRIPTION:

--- UNT 1009 IN HEWA.p01 (plan) ---

Plan Title=Multiple Run
Short Identifier=Multiple
Geom File=g01
Flow File=f01
Subcritical Flow
K Sum by GR= 0
Std Step Tol= 0.01
Critical Tol= 0.01
Num of Std Step Trials= 20
Max Error Tol= 0.3
Flow Tol Ratio= 0.001
Split Flow NTrial= 30
Split Flow Tol= 0.02
Split Flow Ratio= 0.02
Log Output Level= 0
Friction Slope Method= 1
Unsteady Friction Slope Method= 2
Unsteady Bridges Friction Slope Method= 1
Parabolic Critical Depth
Global Vel Dist=  1 , 1 , 1
Global Log Level= 0
CheckData=True
Encroach Param= -1, 0, 0, 0
BEGIN DESCRIPTION:
Multiple Run
END DESCRIPTION:

--- UNT 1009 IN HEWA.f01 (steady flow) ---

Flow Title=Multiple
Number of Profiles=7
Profile Names=10-year,25-year,50-year,1pct_min,100-year,1pct_plu,500-year
River Rch & RM= UNT 1009 IN HEWA,Reach-1,2312
     669     950    1189    1088    1472    1990    2250
Boundary for River Rch & Prof#=UNT 1009 IN HEWA,Reach-1,1
Up Type=0
Dn Type=3
Dn Slope=0.005
Boundary for River Rch & Prof#=UNT 1009 IN HEWA,Reach-1,2
Up Type=0
Dn Type=3
Dn Slope=0.005
Boundary for River Rch & Prof#=UNT 1009 IN HEWA,Reach-1,3
Up Type=0
Dn Type=3
Dn Slope=0.005
Boundary for River Rch & Prof#=UNT 1009 IN HEWA,Reach-1,4
Up Type=0
Dn Type=3
Dn Slope=0.005
Boundary for River Rch & Prof#=UNT 1009 IN HEWA,Reach-1,5
Up Type=0
Dn Type=3
Dn Slope=0.005
Boundary for River Rch & Prof#=UNT 1009 IN HEWA,Reach-1,6
Up Type=0
Dn Type=3
Dn Slope=0.005
Boundary for River Rch & Prof#=UNT 1009 IN HEWA,Reach-1,7
Up Type=0
Dn Type=3
Dn Slope=0.005

--- UNT 1009 IN HEWA.g01 (geometry) ---

Geom Title=Existing Conditions

River Reach=UNT 1009 IN HEWA,Reach-1
Reach XY= 30
      2694198.59     10038869.03      2694125.66     10038849.15
      2693983.05     10038776.43      2693842.54     10038811.52
      2693719.78     10038830.72      2693599.54     10038781.13
      2693512.28     10038725.90      2693477.14     10038685.12
      2693440.05     10038661.95      2693419.22     10038629.89
      2693364.06     10038615.78      2693325.49     10038627.60
      2693288.21     10038653.40      2693163.58     10038836.56
      2693108.98     10038863.04      2693073.97     10038862.09
      2692932.91     10038825.78      2692864.09     10038821.42
      2692813.14     10038804.43      2692736.80     10038813.15
      2692673.46     10038797.65      2692568.24     10038812.37
      2692457.23     10038760.23      2692375.21     10038742.88
      2692351.02     10038761.81      2692347.99     10038885.31
      2692337.87     10038913.89      2692303.50     10038933.50
      2692226.19     10038921.45      2692168.47     10038983.73

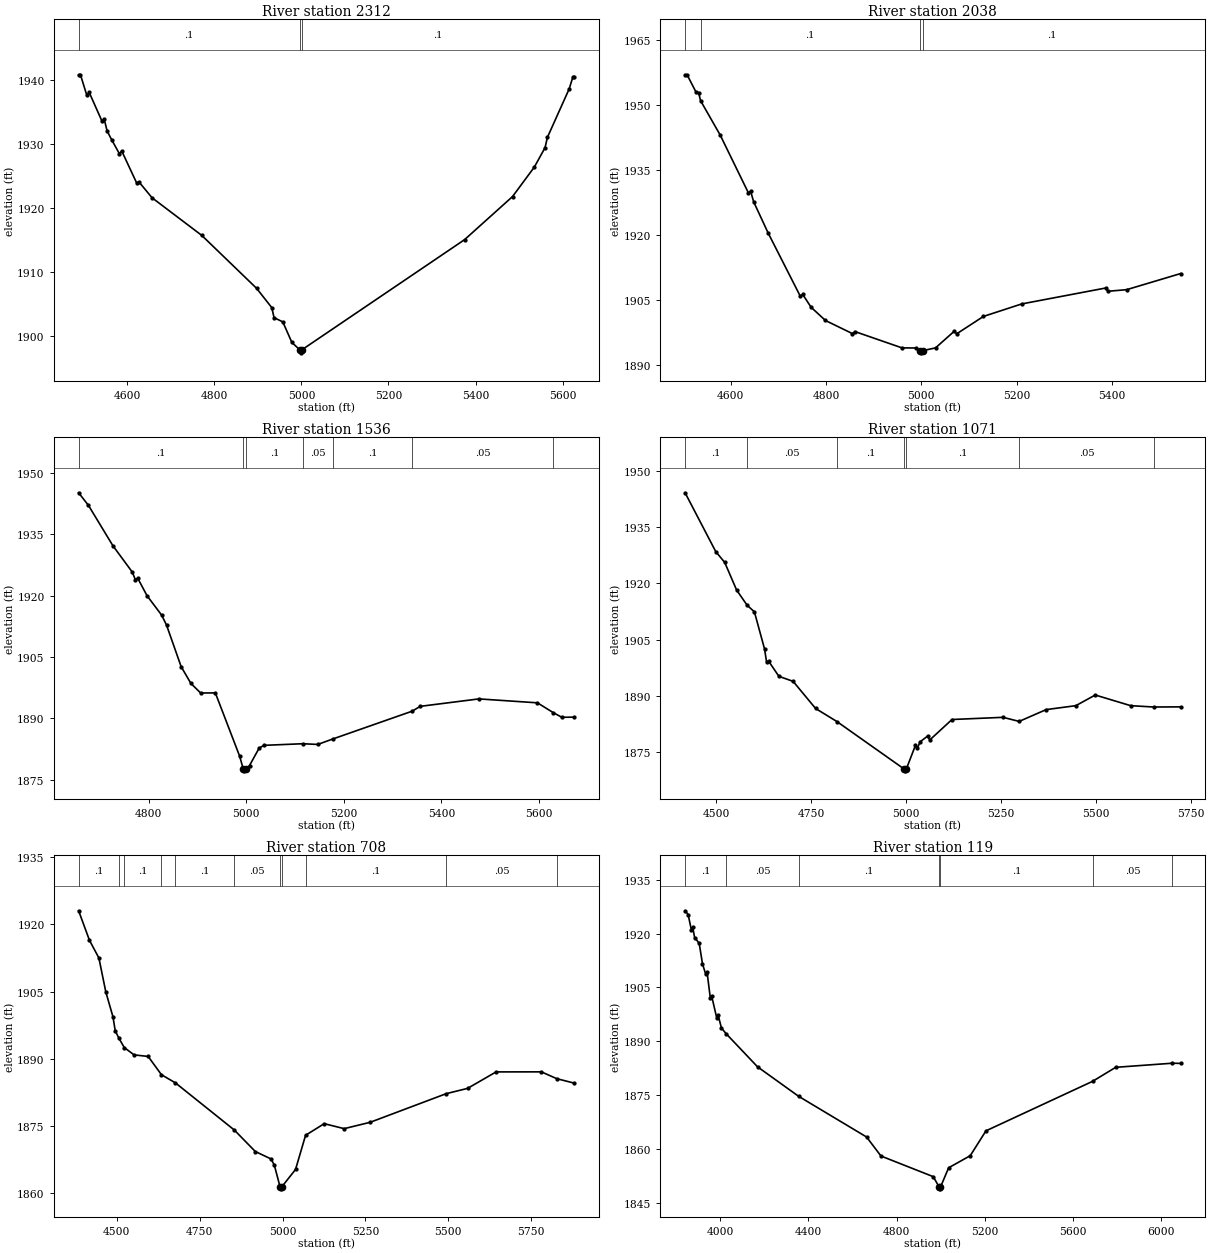
Type RM Length L Ch R = 1,2312,274,274,274
BEGIN DESCRIPTION:
UNT 1009 IN HEWA 5.0
END DESCRIPTION:
XS GIS Cut Line= 3
      2694198.36     10038320.52      2694021.28     10038981.95
      2694047.32     10039435.08
#Sta/Elev= 30
  4488.1 1940.77  4492.3 1940.77  4507.0 1937.55  4512.2 1938.05  4541.8 1933.53
  4547.0 1933.83  4553.5 1932.01  4563.9 1930.65  4581.9 1928.44  4587.1 1928.89
  4621.9 1923.83  4627.1 1924.03  4656.8 1921.59  4770.9 1915.73  4897.0 1907.47
  4931.9 1904.46  4937.1 1902.90  4957.3 1902.23  4978.0 1899.04  4995.7 1897.91
  4998.4 1897.41  5001.7 1897.91  5374.9 1915.06  5485.1 1921.78  5535.2 1926.38
  5559.8 1929.41  5565.2 1931.01  5615.3 1938.58  5623.5 1940.38  5626.7 1940.38
#Mann=3,-1,0
  4488.1     0.1       0  4995.7    0.07       0  5001.7     0.1       0
Bank Sta=4995.7,5001.7
Exp/Cntr=0.3,0.1

Type RM Length L Ch R = 1,2038,502,502,502
BEGIN DESCRIPTION:
UNT 1009 IN HEWA 4.0
END DESCRIPTION:
XS GIS Cut Line= 3
      2693760.86     10038320.45      2693828.57     10039049.66
      2693818.16     10039356.93
#Sta/Elev= 30
  4504.5 1956.88  4508.7 1956.88  4527.8 1952.80  4532.8 1952.77  4537.0 1950.90
  4578.1 1942.98  4637.1 1929.69  4642.1 1929.97  4648.4 1927.57  4678.5 1920.44
  4746.4 1905.76  4751.4 1906.20  4768.9 1903.25  4799.0 1900.20  4855.7 1897.17
  4860.7 1897.65  4959.7 1893.88  4989.9 1893.86  4996.9 1893.24  4999.7 1892.74
  5002.9 1893.24  5030.0 1893.88  5069.3 1897.73  5074.3 1897.12  5130.5 1901.14
  5210.8 1904.02  5386.8 1907.69  5391.8 1906.94  5431.0 1907.31  5544.3 1911.03
#Mann=4,-1,0
  4504.5    0.16       0  4537.0     0.1       0  4996.9    0.07       0
  5002.9     0.1       0
Bank Sta=4996.9,5002.9
Exp/Cntr=0.3,0.1

Type RM Length L Ch R = 1,1536,465,465,465
BEGIN DESCRIPTION:
UNT 1009 IN HEWA 3.0
END DESCRIPTION:
XS GIS Cut Line= 2
      2693385.87     10038273.64      2693365.04     10039289.03
#Sta/Elev= 30
  4656.4 1945.17  4676.5 1942.09  4726.5 1932.24  4766.5 1925.74  4772.5 1923.94
  4777.5 1924.27  4796.5 1920.00  4826.5 1915.24  4836.5 1912.82  4866.5 1902.63
  4886.5 1898.53  4906.5 1896.18  4936.6 1896.21  4986.6 1880.66  4993.6 1877.64
  4996.3 1877.14  4999.6 1877.64  5006.6 1878.43  5026.6 1882.75  5036.6 1883.38
  5115.4 1883.77  5146.6 1883.60  5177.4 1884.94  5339.8 1891.73  5356.6 1892.92
  5476.7 1894.74  5596.7 1893.78  5629.0 1891.39  5646.7 1890.24  5672.0 1890.28
#Mann=7,-1,0
  4656.4     0.1       0  4993.6    0.07       0  4999.6     0.1       0
  5115.4    0.05       0  5177.4     0.1       0  5339.8    0.05       0
  5629.0     0.1       0
Bank Sta=4993.6,4999.6
Exp/Cntr=0.3,0.1

Type RM Length L Ch R = 1,1071,363,363,363
BEGIN DESCRIPTION:
UNT 1009 IN HEWA 2.0
END DESCRIPTION:
XS GIS Cut Line= 3
      2693208.77     10038294.50      2692937.95     10039143.41
      2693281.70     10039372.58
#Sta/Elev= 30
  4418.4 1944.16  4499.0 1928.49  4522.6 1925.60  4554.1 1918.20  4581.8 1914.15
  4600.8 1912.41  4627.5 1902.50  4633.0 1898.95  4638.3 1899.25  4665.2 1895.22
  4702.7 1893.87  4761.8 1886.64  4817.9 1883.16  4994.7 1870.51  4997.4 1870.01
  5000.7 1870.51  5024.6 1876.79  5029.9 1876.07  5036.9 1877.75  5056.8 1879.29
  5062.1 1878.22  5120.9 1883.70  5255.2 1884.28  5297.5 1883.19  5368.7 1886.34
  5446.8 1887.39  5497.9 1890.23  5591.0 1887.39  5651.9 1887.03  5722.6 1887.07
#Mann=7,-1,0
  4418.4     0.1       0  4581.8    0.05       0  4817.9     0.1       0
  4994.7    0.07       0  5000.7     0.1       0  5297.5    0.05       0
  5651.9     0.1       0
Bank Sta=4994.7,5000.7
Exp/Cntr=0.3,0.1

Type RM Length L Ch R = 1,708,589,589,589
BEGIN DESCRIPTION:
Mapping XS 1b852081
END DESCRIPTION:
XS GIS Cut Line= 4
      2693026.55     10038315.73      2692685.39     10038690.75
      2692659.35     10039008.46      2693204.83     10039395.49
#Sta/Elev= 30
  4385.0 1923.02  4417.7 1916.43  4446.1 1912.49  4467.0 1904.90  4488.6 1899.35
  4495.4 1896.24  4506.9 1894.53  4522.7 1892.50  4552.2 1890.87  4594.7 1890.52
  4634.8 1886.44  4676.8 1884.63  4854.6 1874.10  4917.8 1869.31  4965.2 1867.65
  4975.2 1866.28  4992.3 1861.48  4995.1 1860.98  4998.3 1861.48  5039.2 1865.30
  5069.5 1872.93  5125.7 1875.52  5185.9 1874.41  5264.0 1875.82  5493.9 1882.22
  5558.0 1883.39  5644.1 1887.07  5780.7 1887.08  5827.1 1885.56  5879.6 1884.57
#Mann=11,-1,0
  4385.0     0.1       0  4506.9    0.05       0  4522.7     0.1       0
  4634.8    0.05       0  4676.8     0.1       0  4854.6    0.05       0
  4992.3   0.035       0  4998.3    0.05       0  5069.5     0.1       0
  5493.9    0.05       0  5827.1     0.1       0
Bank Sta=4992.3,4998.3
Exp/Cntr=0.3,0.1

Type RM Length L Ch R = 1,119,0,0,0
BEGIN DESCRIPTION:
UNT 1009 IN HEWA 1.0
END DESCRIPTION:
XS GIS Cut Line= 4
      2693026.51     10038162.12      2692260.91     10038706.38
      2692258.31     10039057.94      2693153.83     10039401.57
#Sta/Elev= 30
  3839.7 1926.33  3853.4 1925.29  3868.2 1921.02  3874.3 1921.78  3882.9 1918.89
  3903.8 1917.27  3918.6 1911.60  3933.4 1908.65  3939.5 1909.24  3954.3 1902.02
  3960.4 1902.60  3983.8 1896.40  3989.9 1897.24  4004.7 1893.72  4026.5 1892.11
  4168.6 1882.93  4355.4 1874.72  4663.9 1863.40  4729.1 1858.12  4966.4 1852.38
  4993.4 1849.49  4996.2 1848.99  4999.4 1849.49  5036.4 1854.85  5134.5 1858.21
  5205.8 1865.12  5690.2 1878.90  5794.9 1882.79  6051.7 1883.93  6089.8 1883.88
#Mann=7,-1,0
  3839.7     0.1       0  4026.5    0.05       0  4355.4     0.1       0
  4993.4    0.07       0  4999.4     0.1       0  5690.2    0.05       0
  6051.7     0.1       0
Bank Sta=4993.4,4999.4
Exp/Cntr=0.3,0.1

Chan Stop Cuts=-1