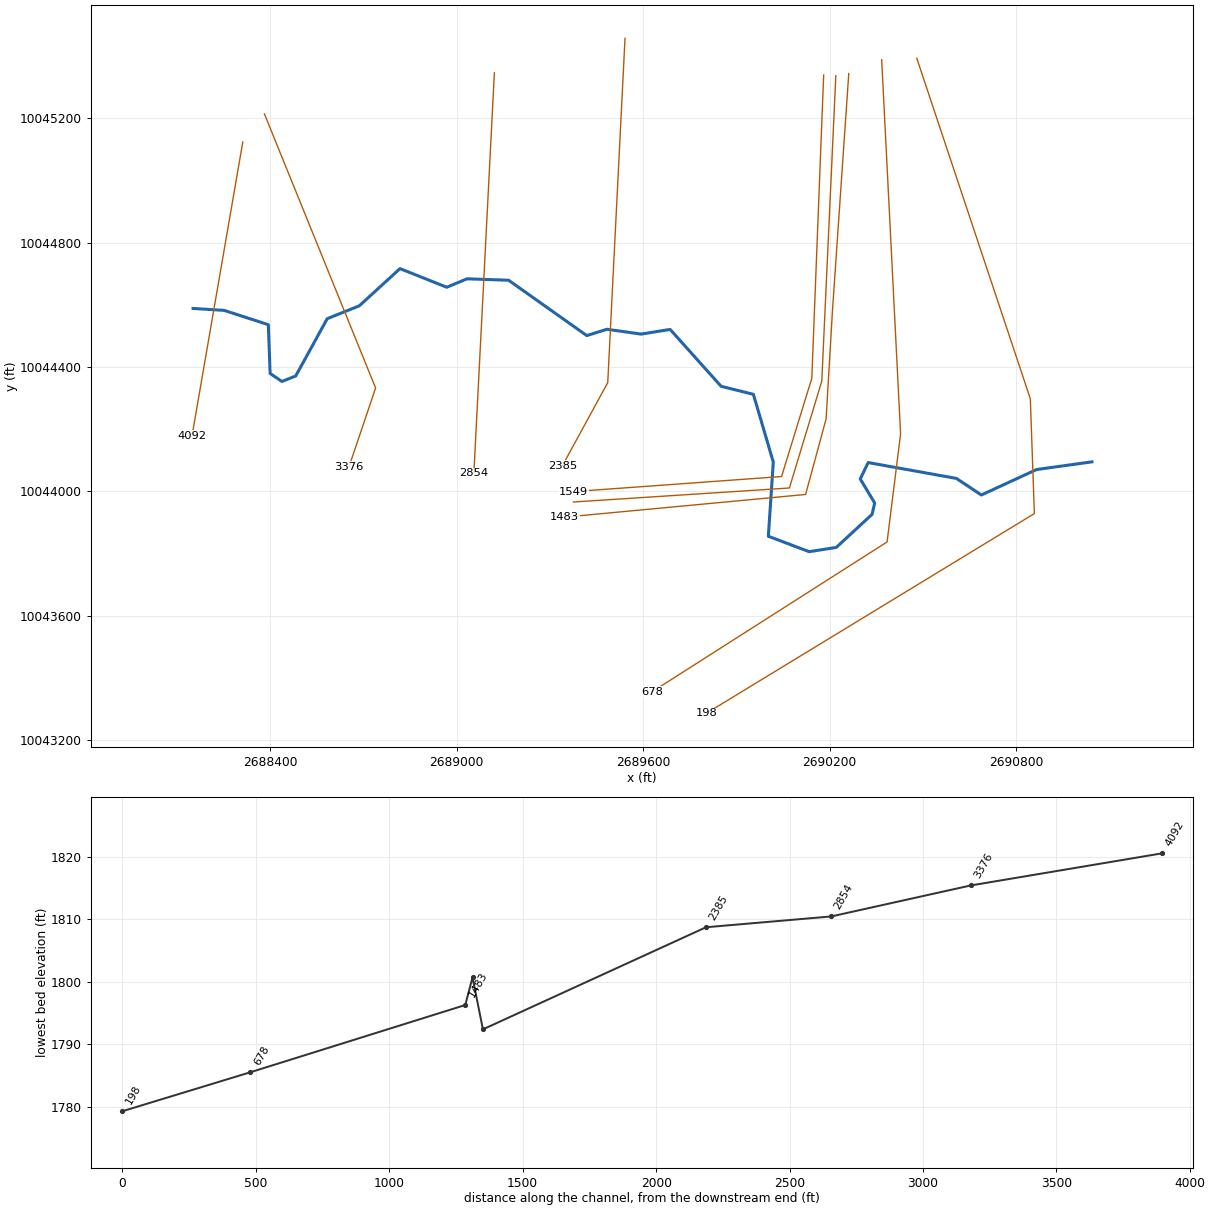
--- UNT 1010 IN HEWA.prj (project) ---

Proj Title=UNT 1010 IN HEWA Base Level Engineering
Current Plan=p01
Default Exp/Contr=0.3,0.1
English Units
Geom File=g01
Flow File=f01
Plan File=p01
Y Axis Title=Elevation
X Axis Title(PF)=Main Channel Distance
X Axis Title(XS)=Station
BEGIN DESCRIPTION:
UNT 1010 IN HEWA
END DESCRIPTION:
DSS Export Rating Curves= 0
DSS Export Rating Curve Sorted= 0
DSS Export Volume Flow Curves= 0
DXF OffsetX= 0
DXF OffsetY= 0
DXF ScaleX= 1
DXF ScaleY= 10

--- UNT 1010 IN HEWA.p01 (plan) ---

Plan Title=Multiple Run
Short Identifier=Multiple
Geom File=g01
Flow File=f01
Subcritical Flow
K Sum by GR= 0
Std Step Tol= 0.01
Critical Tol= 0.01
Num of Std Step Trials= 20
Max Error Tol= 0.3
Flow Tol Ratio= 0.001
Split Flow NTrial= 30
Split Flow Tol= 0.02
Split Flow Ratio= 0.02
Log Output Level= 0
Friction Slope Method= 1
Unsteady Friction Slope Method= 2
Unsteady Bridges Friction Slope Method= 1
Parabolic Critical Depth
Global Vel Dist=  1 , 1 , 1
Global Log Level= 0
CheckData=True
Encroach Param= -1, 0, 0, 0
BEGIN DESCRIPTION:
Multiple Run
END DESCRIPTION:

--- UNT 1010 IN HEWA.f01 (steady flow) ---

Flow Title=Multiple
Number of Profiles=7
Profile Names=10-year,25-year,50-year,1pct_min,100-year,1pct_plu,500-year
River Rch & RM= UNT 1010 IN HEWA,Reach-1,4092
    1009    1463    1854    1715    2320    3137    3627
Boundary for River Rch & Prof#=UNT 1010 IN HEWA,Reach-1,1
Up Type=0
Dn Type=3
Dn Slope=0.005
Boundary for River Rch & Prof#=UNT 1010 IN HEWA,Reach-1,2
Up Type=0
Dn Type=3
Dn Slope=0.005
Boundary for River Rch & Prof#=UNT 1010 IN HEWA,Reach-1,3
Up Type=0
Dn Type=3
Dn Slope=0.005
Boundary for River Rch & Prof#=UNT 1010 IN HEWA,Reach-1,4
Up Type=0
Dn Type=3
Dn Slope=0.005
Boundary for River Rch & Prof#=UNT 1010 IN HEWA,Reach-1,5
Up Type=0
Dn Type=3
Dn Slope=0.005
Boundary for River Rch & Prof#=UNT 1010 IN HEWA,Reach-1,6
Up Type=0
Dn Type=3
Dn Slope=0.005
Boundary for River Rch & Prof#=UNT 1010 IN HEWA,Reach-1,7
Up Type=0
Dn Type=3
Dn Slope=0.005

--- UNT 1010 IN HEWA.g01 (geometry) ---

Geom Title=Existing Conditions
Program Version=4.10

River Reach=UNT 1010 IN HEWA,Reach-1
Reach XY= 30
      2688152.65     10044587.92      2688252.59     10044581.71
      2688394.66     10044535.64      2688400.45     10044378.75
      2688438.41     10044352.97      2688482.88     10044370.81
      2688584.06     10044554.97      2688687.28     10044596.36
       2688818.1     10044716.06      2688968.47     10044656.13
      2689033.69     10044683.28      2689167.44     10044678.65
       2689418.7     10044500.63      2689483.85     10044520.96
      2689593.43     10044505.43      2689686.95      10044520.4
      2689850.86      10044337.4      2689954.62     10044311.63
      2690018.67     10044093.57      2690002.75     10043854.97
      2690133.98     10043805.37      2690221.06     10043819.03
      2690336.37      10043925.5      2690344.72     10043962.05
      2690298.28     10044039.42      2690323.82     10044092.06
      2690607.47     10044041.09      2690687.74     10043987.74
      2690865.48     10044069.65      2691043.29     10044094.35

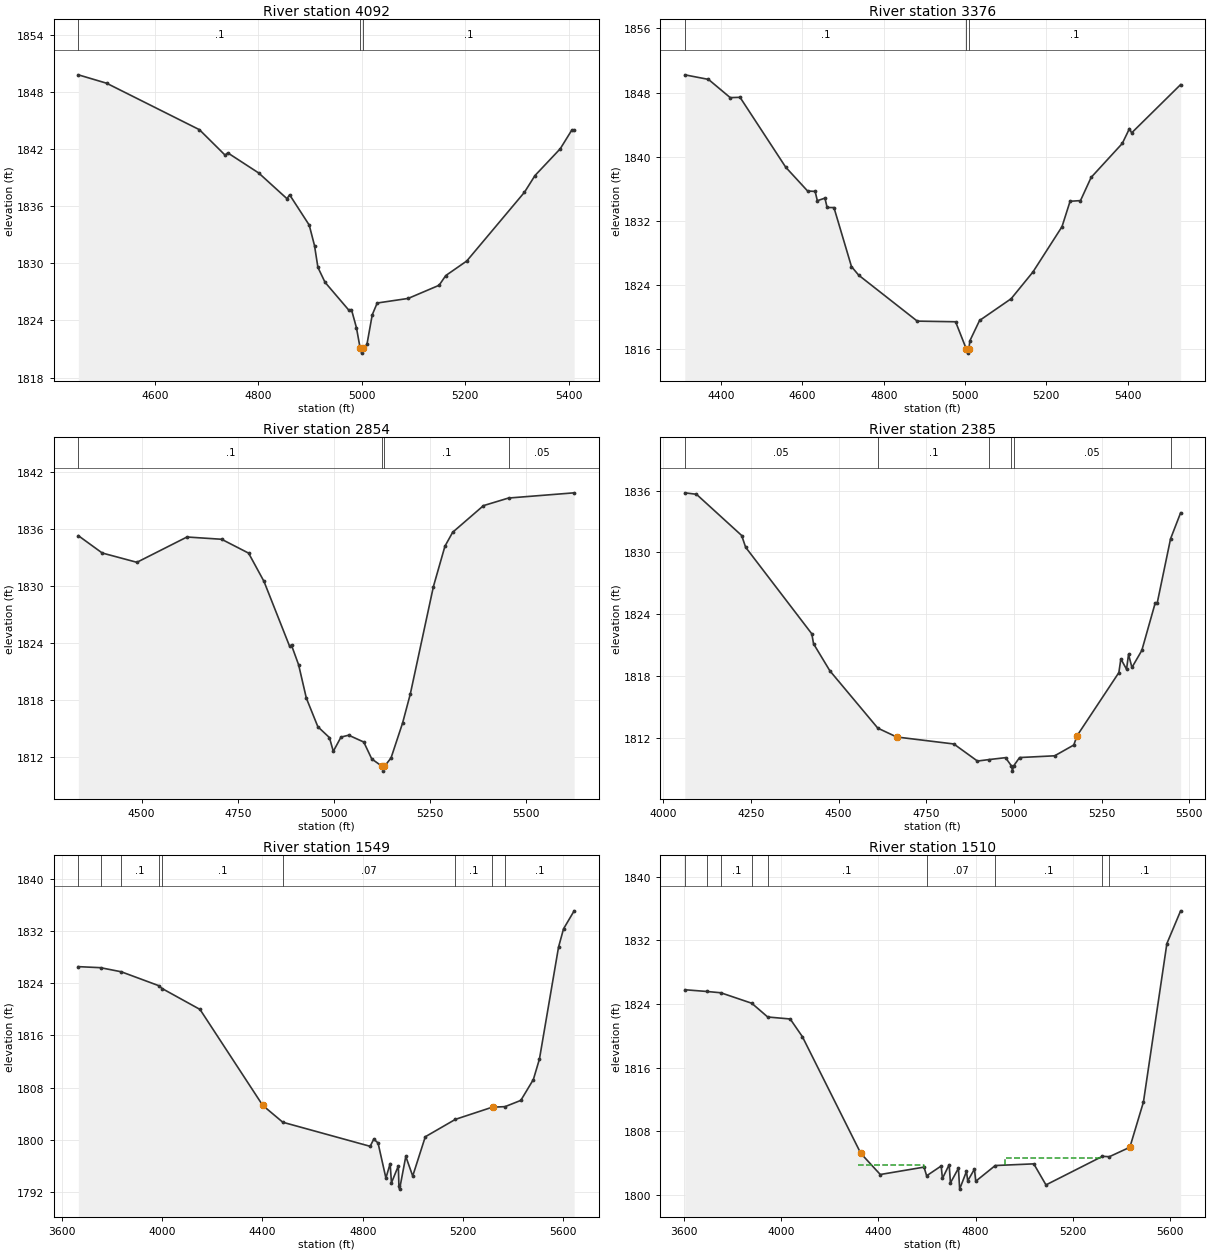
Type RM Length L Ch R = 1 ,4092    ,716,716,716
BEGIN DESCRIPTION:
UNT 1010 IN HEWA 8.0
END DESCRIPTION:
XS GIS Cut Line= 2
       2688312.6     10045123.53      2688149.41     10044179.13
#Sta/Elev= 30
    4452 1849.78  4506.6  1848.9  4686.1 1844.02  4735.7 1841.35  4740.8 1841.59
  4800.6 1839.48  4855.3 1836.78  4860.4 1837.19  4898.3 1834.01  4908.5 1831.86
  4915.1 1829.57  4928.8 1828.01    4975 1825.07    4980 1825.13  4989.6 1823.23
  4996.8 1821.07  4999.5 1820.57  5002.8 1821.07  5009.9 1821.49  5020.1 1824.59
  5029.7 1825.83  5089.5 1826.31  5149.3 1827.69  5162.2 1828.71  5202.8 1830.24
  5314.4 1837.46  5334.7 1839.21  5383.5 1842.02  5405.5 1843.95  5410.4 1843.95
#Mann= 3 ,-1 , 0
    4452      .1       0  4996.8     .07       0  5002.8      .1       0
Bank Sta=4996.8,5002.8
XS Rating Curve= 0 ,0
Exp/Cntr=0.3,0.1

Type RM Length L Ch R = 1 ,3376    ,522,522,522
BEGIN DESCRIPTION:
UNT 1010 IN HEWA 7.0
END DESCRIPTION:
XS GIS Cut Line= 3
      2688382.07      10045213.8      2688739.69     10044331.91
       2688653.8     10044077.67
#Sta/Elev= 30
  4310.4 1850.21  4368.6 1849.64  4422.2 1847.36  4446.3  1847.4  4558.8 1838.66
  4612.6 1835.69  4631.1 1835.64  4636.5 1834.48  4655.2  1834.8  4660.6 1833.63
  4677.4 1833.62  4720.5 1826.25  4738.3 1825.17  4882.4 1819.43  4976.7 1819.35
  5003.2 1815.93    5006 1815.43  5009.2 1815.93  5011.9 1816.98  5035.7 1819.51
  5113.4 1822.23    5167 1825.57  5238.5 1831.23  5258.4 1834.41    5284 1834.49
  5310.2 1837.39  5386.8 1841.63  5404.5 1843.49  5409.8 1842.95  5530.4 1848.99
#Mann= 3 ,-1 , 0
  4310.4      .1       0  5003.2     .07       0  5009.2      .1       0
Bank Sta=5003.2,5009.2
XS Rating Curve= 0 ,0
Exp/Cntr=0.3,0.1

Type RM Length L Ch R = 1 ,2854    ,469,469,469
BEGIN DESCRIPTION:
UNT 1010 IN HEWA 6.0
END DESCRIPTION:
XS GIS Cut Line= 2
      2689121.64     10045345.82       2689055.7     10044058.21
#Sta/Elev= 30
  4335.6 1835.31  4397.8 1833.48  4487.9  1832.5  4618.1 1835.17  4708.2 1834.93
  4778.3 1833.47  4818.3 1830.49  4884.9 1823.65  4889.9 1823.75  4908.4 1821.69
  4928.5 1818.17  4958.5 1815.15  4988.5 1814.01  4998.6 1812.56  5018.6 1814.06
  5038.6 1814.26  5077.8 1813.54  5098.7 1811.75  5125.7 1810.97  5128.5 1810.47
  5131.7 1810.97  5148.8 1811.87  5178.8 1815.55  5198.8  1818.6  5258.9 1829.94
  5288.9  1834.2    5309 1835.67  5389.1 1838.48  5454.2 1839.28  5624.9 1839.83
#Mann= 4 ,-1 , 0
  4335.6      .1       0  5125.7     .07       0  5131.7      .1       0
  5454.2     .05       0
Bank Sta=5125.7,5131.7
XS Rating Curve= 0 ,0
Exp/Cntr=0.3,0.1

Type RM Length L Ch R = 1 ,2385    ,836,836,836
BEGIN DESCRIPTION:
UNT 1010 IN HEWA 5.0
END DESCRIPTION:
XS GIS Cut Line= 3
      2689541.78     10045456.94      2689486.22     10044349.27
      2689340.39     10044081.92
#Sta/Elev= 30
  4061.3  1835.8  4094.5 1835.66  4223.5 1831.65  4234.7 1830.51  4423.4 1822.09
  4428.4 1821.12    4475 1818.49  4611.6 1812.92  4665.3 1812.06  4828.3 1811.38
  4895.6 1809.72  4927.9 1809.86  4975.7 1810.05  4992.7 1809.24  4995.4 1808.74
  4998.7 1809.24  5015.7 1810.06  5115.8 1810.23  5170.4 1811.28  5179.2 1812.16
  5298.8 1818.32  5304.5 1819.65  5320.7 1818.65  5326.4 1820.09  5336.1 1818.82
  5364.3 1820.48  5402.3 1825.07    5408 1825.06  5446.2 1831.33  5474.9 1833.86
#Mann= 6 ,-1 , 0
  4061.3     .05       0  4611.6      .1       0  4927.9     .05       0
  4992.7     .04       0  4998.7     .05       0  5446.2      .1       0
Bank Sta=4665.3,5179.2
XS Rating Curve= 0 ,0
Exp/Cntr=0.3,0.1

Type RM Length L Ch R = 1 ,1549    ,39,39,39
BEGIN DESCRIPTION:
Mapping XS e385a672
END DESCRIPTION:
XS GIS Cut Line= 4
      2690180.66      10045338.8      2690142.47     10044363.16
      2690045.25     10044047.18      2689376.19     10043998.65
#Sta/Elev= 30
  3665.7 1826.58  3754.2 1826.42    3837 1825.79  3985.5 1823.67  4000.2 1823.21
  4151.1    1820  4401.3 1805.25  4481.4 1802.66  4829.8 1798.96  4844.1 1800.06
  4861.2 1799.48  4892.6 1794.08  4909.5 1796.31  4914.7 1793.35  4942.2 1795.95
  4944.4 1792.88  4947.2 1792.38  4971.9 1797.41  4999.5 1794.39  5049.7 1800.43
    5170 1803.11  5316.5 1804.97  5320.4 1804.98  5367.8 1805.06  5430.7 1806.02
  5480.8 1809.23    5505 1812.37  5581.1 1829.56  5601.1 1832.39  5643.5 1835.16
#Mann= 9 ,-1 , 0
  3665.7      .1       0  3754.2     .05       0    3837      .1       0
  3985.5     .05       0  4000.2      .1       0  4481.4     .07       0
    5170      .1       0  5316.5     .16       0  5367.8      .1       0
Bank Sta=4401.3,5320.4
XS Rating Curve= 0 ,0
Exp/Cntr=0.3,0.1

Type RM Length L Ch R = 1 ,1510    ,27,27,27
BEGIN DESCRIPTION:
UNT 1010 IN HEWA 4.0
END DESCRIPTION:
XS GIS Cut Line= 4
      2690219.73     10045336.66      2690174.59     10044354.04
      2690070.42     10044010.29      2689375.93     10043965.15
#Sta/Elev= 30
  3604.1  1825.8  3695.5 1825.58    3752 1825.42  3879.4  1824.1  3945.1 1822.37
  4037.5 1822.12  4087.5  1819.9  4327.8 1805.21  4407.9 1802.55  4587.8 1803.48
  4598.5 1802.39  4658.3 1803.62  4663.5 1802.05  4691.2 1803.79  4696.4 1801.49
  4729.3 1803.34  4734.3 1800.71  4762.3 1802.94  4767.5 1801.75  4795.2 1803.23
  4800.4  1801.7  4880.7 1803.68  5039.1 1803.89  5089.2 1801.24  5321.4 1804.84
  5349.8 1804.79  5434.2 1805.98    5490 1811.67  5586.4 1831.61  5642.9 1835.73
#Mann= 9 ,-1 , 0
  3604.1      .1       0  3695.5     .05       0    3752      .1       0
  3879.4     .05       0  3945.1      .1       0  4598.5     .07       0
  4880.7      .1       0  5321.4     .16       0  5349.8      .1       0
#XS Ineff= 2 ,-1
 4315.34 4589.49 1803.75 4920.45  5319.6 1804.61
Permanent Ineff=
       F       F
Bank Sta=4327.8,5434.2
XS Rating Curve= 0 ,0
Exp/Cntr=0.3,0.1

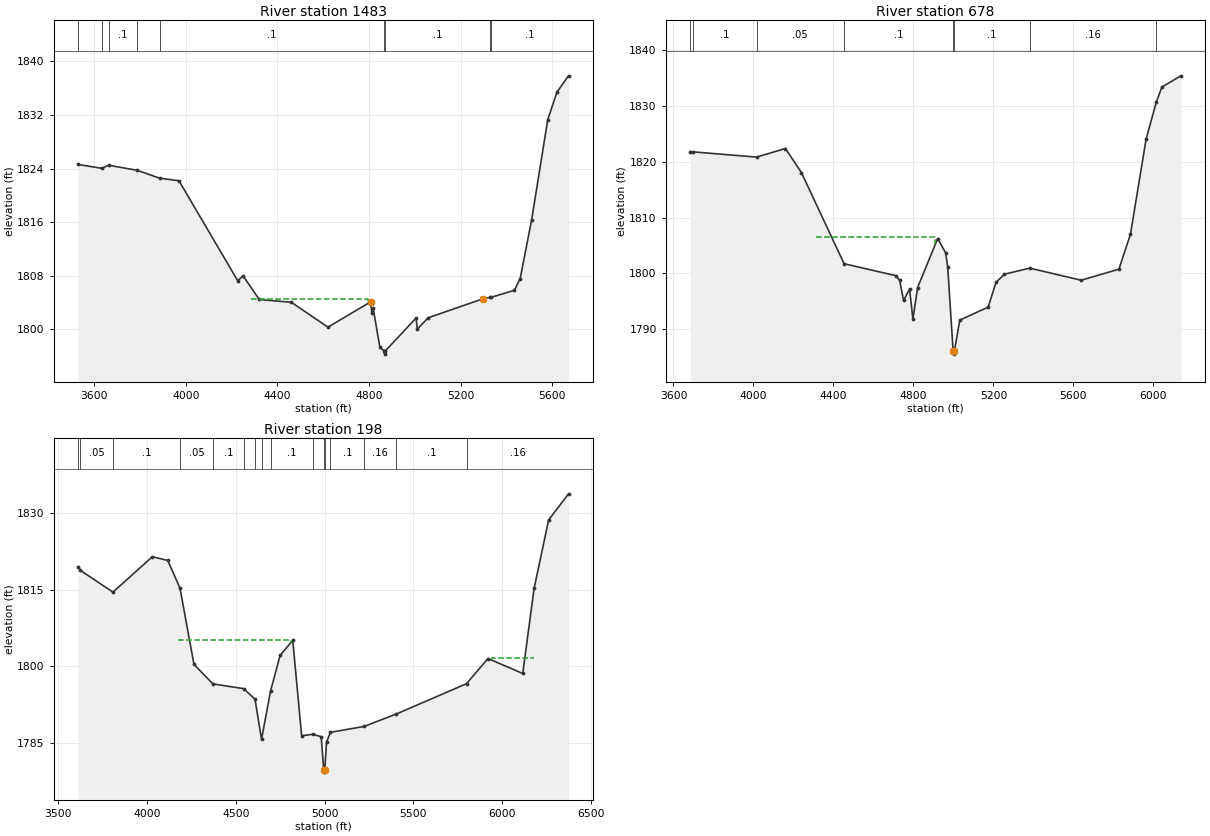
Type RM Length L Ch R = 1 ,1483    ,805,805,805
BEGIN DESCRIPTION:
UNT 1010 IN HEWA 3.0
END DESCRIPTION:
XS GIS Cut Line= 5
      2690261.39     10045343.59      2690209.31     10044586.68
      2690188.48     10044232.51       2690122.5     10043989.46
      2689348.16     10043916.54
#Sta/Elev= 30
  3528.8  1824.6  3632.3 1824.03  3662.4 1824.49  3788.3 1823.72  3884.8 1822.56
  3969.7 1822.17  4226.1 1807.26  4250.4 1807.95  4320.5 1804.44  4460.7 1804.02
    4621 1800.31  4806.8 1804.08    4813 1802.46  4818.2 1803.13  4847.7 1797.29
    4866 1796.78  4868.7 1796.28    4872 1796.78  5006.1 1801.68  5011.1 1800.02
  5058.9 1801.71    5300 1804.57  5327.5 1804.74  5332.2 1804.75  5435.4 1805.81
  5460.7 1807.57  5510.9 1816.36  5581.2 1831.29  5621.4 1835.41  5671.9 1837.84
#Mann= 9 ,-1 , 0
  3528.8      .1       0  3632.3     .05       0  3662.4      .1       0
  3788.3     .05       0  3884.8      .1       0    4866     .07       0
    4872      .1       0  5327.5     .16       0  5332.2      .1       0
#XS Ineff= 1 ,-1
 4282.67 4796.88 1804.58
Permanent Ineff=
       F
Bank Sta=4806.8,5300
XS Rating Curve= 0 ,0
Exp/Cntr=0.3,0.1

Type RM Length L Ch R = 1 ,678     ,480,480,480
BEGIN DESCRIPTION:
Mapping XS 1bbf6d7b
END DESCRIPTION:
XS GIS Cut Line= 4
      2690367.21     10045388.18      2690428.05     10044184.37
      2690384.59      10043836.7      2689628.39     10043354.29
#Sta/Elev= 30
  3684.8 1821.83  3696.9  1821.8  4015.2 1820.86  4159.9  1822.4    4240 1818.07
  4453.1 1801.73  4710.6  1799.6  4730.6 1798.79  4750.6 1795.14  4780.6 1797.19
  4797.5 1791.79  4820.7 1797.44    4921 1806.25  4961.3 1803.66  4971.4 1801.08
  4998.6 1786.01  5001.4 1785.51  5004.6 1786.01  5031.9 1791.62  5173.5 1793.94
  5213.3 1798.41  5254.5 1799.84  5380.9 1800.94  5639.2 1798.77  5827.4 1800.75
    5885 1806.98  5963.7 1824.11  6014.5 1830.72  6042.5 1833.44  6137.5 1835.44
#Mann= 8 ,-1 , 0
  3684.8     .05       0  3696.9      .1       0  4015.2     .05       0
  4453.1      .1       0  4998.6     .07       0  5004.6      .1       0
  5380.9     .16       0  6014.5      .1       0
#XS Ineff= 1 ,-1
 4314.77 4909.66 1806.51
Permanent Ineff=
       F
Bank Sta=4998.6,5004.6
XS Rating Curve= 0 ,0
Exp/Cntr=0.3,0.1

Type RM Length L Ch R = 1 ,198     ,0,0,0
BEGIN DESCRIPTION:
UNT 1010 IN HEWA 1.0
END DESCRIPTION:
XS GIS Cut Line= 4
      2690480.19     10045392.59      2690845.27     10044297.37
       2690858.3     10043927.96      2689802.85     10043285.14
#Sta/Elev= 30
  3612.9 1819.52    3625 1818.81  3809.3 1814.53  4031.2 1821.47  4117.7 1820.73
  4186.5  1815.3  4265.2 1800.37    4372 1796.54  4544.8 1795.62  4608.7 1793.54
  4645.3  1785.7  4696.3 1795.19  4750.1 1802.15    4821 1805.07  4871.1 1786.39
  4933.3 1786.67  4981.1  1786.2    4995 1779.76  4997.8 1779.26    5001 1779.76
  5011.2 1785.15  5033.2 1787.06  5222.3 1788.21  5404.5 1790.66  5798.9 1796.59
  5919.6 1801.52  6115.2 1798.59  6179.2 1815.27  6260.8 1828.66  6372.8 1833.79
#Mann= 16 ,-1 , 0
  3612.9      .1       0    3625     .05       0  3809.3      .1       0
  4186.5     .05       0    4372      .1       0  4544.8     .05       0
  4608.7      .1       0  4645.3     .16       0  4696.3      .1       0
  4933.3     .16       0    4995     .07       0    5001     .16       0
  5033.2      .1       0  5222.3     .16       0  5404.5      .1       0
  5798.9     .16       0
#XS Ineff= 2 ,-1
  4176.7 4809.09 1805.22 5940.91 6181.25 1801.71
Permanent Ineff=
       F       F
Bank Sta=4995,5001
XS Rating Curve= 0 ,0
Exp/Cntr=0.3,0.1

Chan Stop Cuts=-1
Use User Specified Reach Order=0
Composite Channel Slope=5