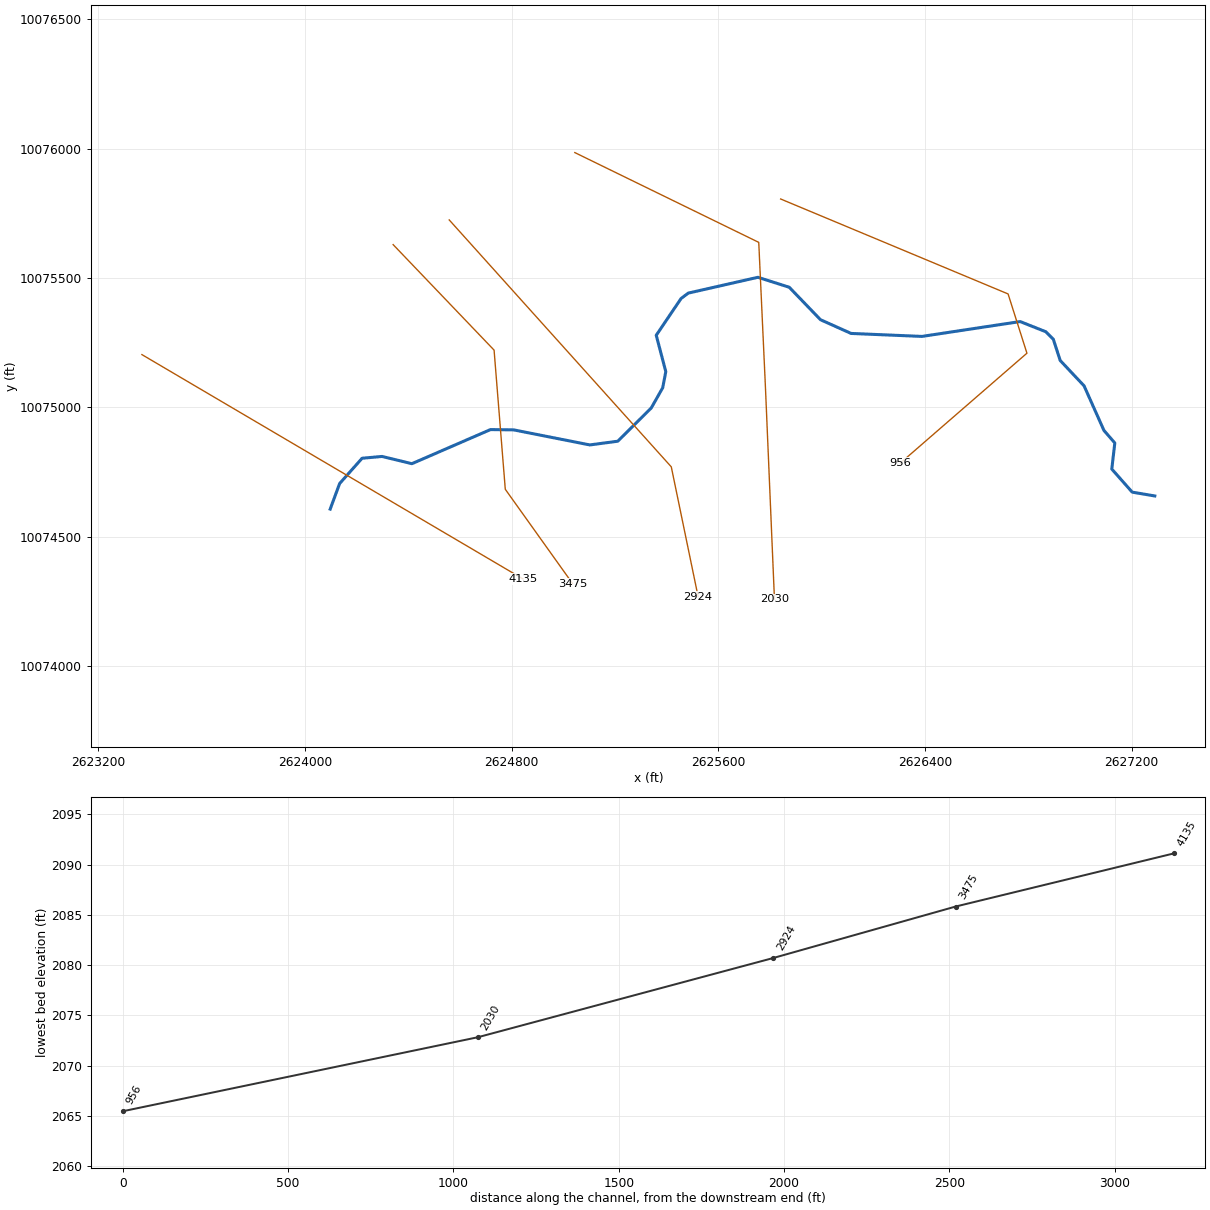
--- UNT 1012 IN HEWA.prj (project) ---

Proj Title=UNT 1012 IN HEWA Base Level Engineering
Current Plan=p01
Default Exp/Contr=0.3,0.1
English Units
Geom File=g01
Flow File=f01
Plan File=p01
Y Axis Title=Elevation
X Axis Title(PF)=Main Channel Distance
X Axis Title(XS)=Station
BEGIN DESCRIPTION:
UNT 1012 IN HEWA
END DESCRIPTION:
DSS Export Rating Curves= 0
DSS Export Rating Curve Sorted= 0
DSS Export Volume Flow Curves= 0
DXF OffsetX= 0
DXF OffsetY= 0
DXF ScaleX= 1
DXF ScaleY= 10

--- UNT 1012 IN HEWA.p01 (plan) ---

Plan Title=Multiple Run
Short Identifier=Multiple
Geom File=g01
Flow File=f01
Subcritical Flow
K Sum by GR= 0
Std Step Tol= 0.01
Critical Tol= 0.01
Num of Std Step Trials= 20
Max Error Tol= 0.3
Flow Tol Ratio= 0.001
Split Flow NTrial= 30
Split Flow Tol= 0.02
Split Flow Ratio= 0.02
Log Output Level= 0
Friction Slope Method= 1
Unsteady Friction Slope Method= 2
Unsteady Bridges Friction Slope Method= 1
Parabolic Critical Depth
Global Vel Dist=  1 , 1 , 1
Global Log Level= 0
CheckData=True
Encroach Param= -1, 0, 0, 0
BEGIN DESCRIPTION:
Multiple Run
END DESCRIPTION:

--- UNT 1012 IN HEWA.f01 (steady flow) ---

Flow Title=Multiple
Program Version=4.10
Number of Profiles= 7
Profile Names=10-year,25-year,50-year,1pct_min,100-year,1pct_plu,500-year
River Rch & RM=UNT 1012 IN HEWA,Reach-1         ,4135
     941    1349    1695    1552    2099    2839    3219
Boundary for River Rch & Prof#=UNT 1012 IN HEWA,Reach-1         , 1
Up Type= 0
Dn Type= 3
Dn Slope=0.006
Boundary for River Rch & Prof#=UNT 1012 IN HEWA,Reach-1         , 2
Up Type= 0
Dn Type= 3
Dn Slope=0.006
Boundary for River Rch & Prof#=UNT 1012 IN HEWA,Reach-1         , 3
Up Type= 0
Dn Type= 3
Dn Slope=0.006
Boundary for River Rch & Prof#=UNT 1012 IN HEWA,Reach-1         , 4
Up Type= 0
Dn Type= 3
Dn Slope=0.006
Boundary for River Rch & Prof#=UNT 1012 IN HEWA,Reach-1         , 5
Up Type= 0
Dn Type= 3
Dn Slope=0.006
Boundary for River Rch & Prof#=UNT 1012 IN HEWA,Reach-1         , 6
Up Type= 0
Dn Type= 3
Dn Slope=0.006
Boundary for River Rch & Prof#=UNT 1012 IN HEWA,Reach-1         , 7
Up Type= 0
Dn Type= 3
Dn Slope=0.006
DSS Import GetInterval= 0
DSS Import GetPeak= 0
DSS Import FillOption= 0

--- UNT 1012 IN HEWA.g01 (geometry) ---

Geom Title=Existing Conditions
Program Version=4.10

River Reach=UNT 1012 IN HEWA,Reach-1
Reach XY= 30
      2624098.25     10074606.17      2624134.77       10074705.
      2624221.72     10074802.82       2624298.9     10074809.81
      2624414.46      10074781.8      2624718.52     10074913.69
      2624807.97     10074912.62      2625103.04     10074854.35
      2625211.17     10074868.69      2625340.65     10074997.13
      2625385.05     10075075.25      2625397.04     10075137.74
      2625360.04     10075278.42      2625456.02     10075420.37
      2625484.01     10075441.48      2625753.62     10075502.61
      2625874.73     10075464.11      2625995.74     10075338.56
      2626114.19     10075285.48      2626388.26     10075273.98
      2626768.53     10075331.41      2626867.79     10075292.01
      2626896.75     10075263.04       2626923.4     10075180.92
      2627015.93     10075082.68      2627092.53     10074910.67
      2627134.73     10074861.98      2627123.09     10074761.02
      2627202.07      10074671.8      2627289.41     10074657.04

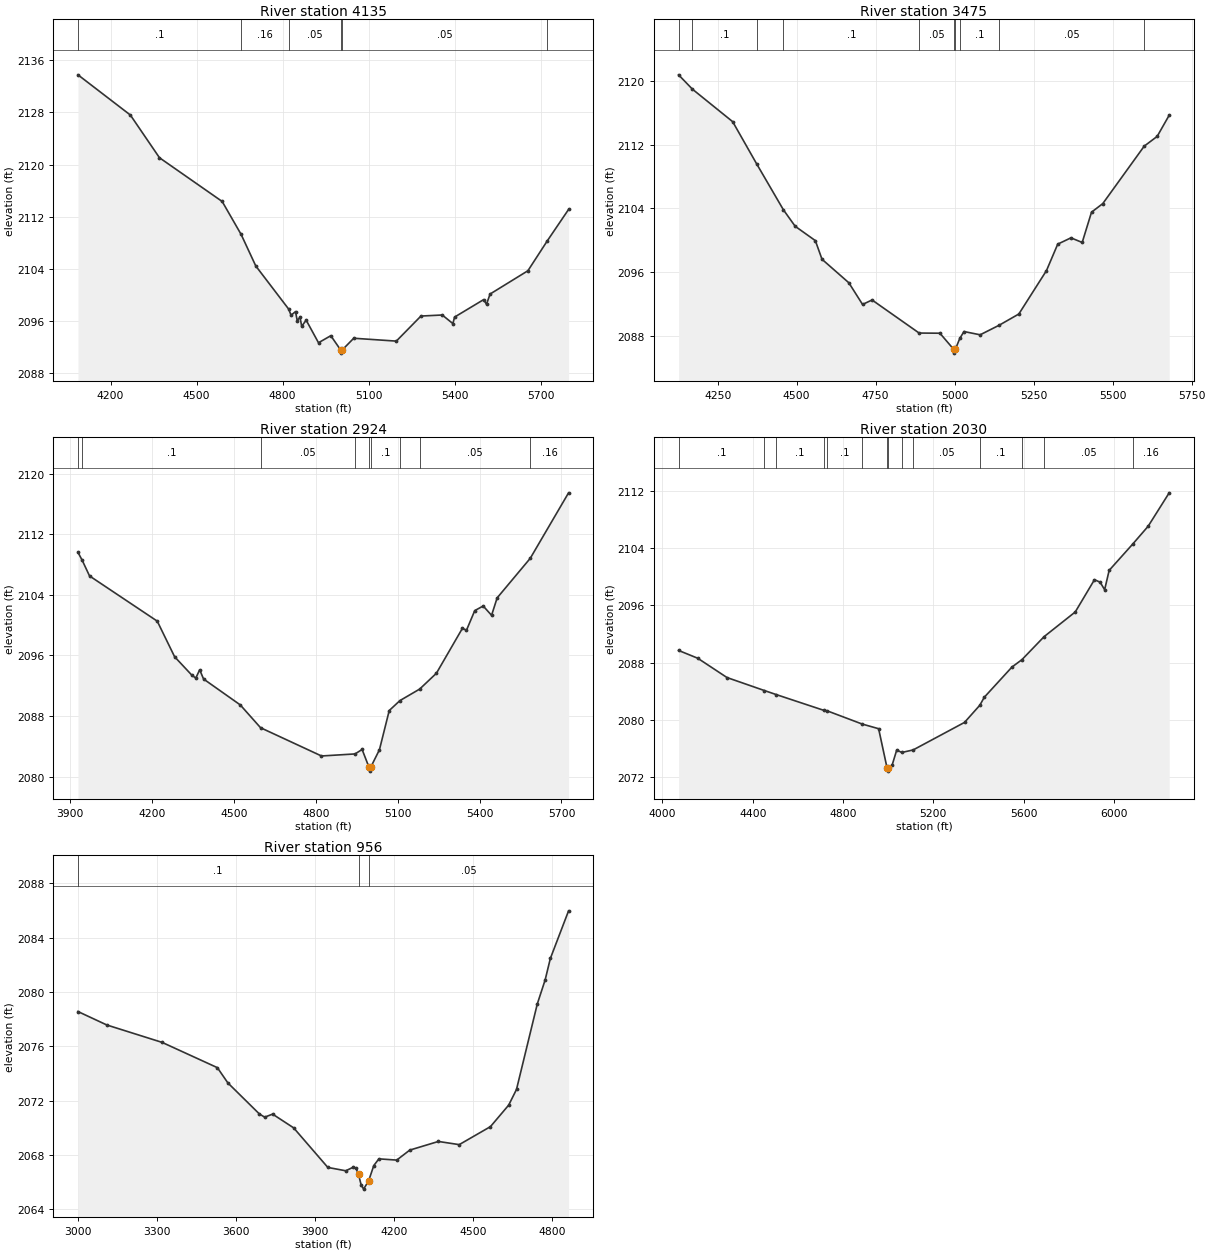
Type RM Length L Ch R = 1 ,4135    ,660,660,660
BEGIN DESCRIPTION:
UNT 1012 IN HEWA 8.0
END DESCRIPTION:
XS GIS Cut Line= 2
      2623369.67     10075203.61      2624844.44      10074336.1
#Sta/Elev= 30
  4086.1 2133.74  4268.9 2127.58  4370.4 2121.04  4589.1 2114.34  4655.2 2109.29
  4706.3 2104.46  4820.7 2097.87  4829.3 2096.92  4844.9 2097.47  4850.7  2096.1
  4860.6 2096.61  4866.4 2095.22    4882 2096.16    4925  2092.7  4967.9 2093.78
    5002 2091.61  5004.8 2091.11    5008 2091.61  5047.9 2093.39  5196.4 2092.95
  5282.3 2096.79  5356.6 2096.95  5393.7 2095.63  5399.5 2096.63    5501 2099.31
  5510.9 2098.59  5523.3 2100.16  5655.3 2103.73  5723.2 2108.33  5797.1 2113.12
#Mann= 6 ,-1 , 0
  4086.1      .1       0  4655.2     .16       0  4820.7     .05       0
    5002     .04       0    5008     .05       0  5723.2     .16       0
Bank Sta=5002,5008
XS Rating Curve= 0 ,0
Exp/Cntr=0.3,0.1

Type RM Length L Ch R = 1 ,3475    ,551,551,551
BEGIN DESCRIPTION:
UNT 1012 IN HEWA 7.0
END DESCRIPTION:
XS GIS Cut Line= 4
      2624341.86     10075628.98      2624732.49     10075220.99
      2624775.89     10074682.79      2625036.12     10074318.47
#Sta/Elev= 30
  4126.4 2120.76  4170.2 2118.96  4297.6 2114.88  4373.1 2109.61  4458.1 2103.82
  4495.4 2101.75  4559.2 2099.95  4580.3 2097.61  4665.2 2094.66  4708.6 2091.94
  4738.7  2092.5  4887.6 2088.35  4953.3 2088.33  4996.5 2086.33  4999.2 2085.83
  5002.5 2086.33  5016.2 2087.67  5029.6 2088.54  5080.7 2088.13  5140.3 2089.32
  5203.1 2090.74  5290.6 2096.19  5326.2 2099.51    5368  2100.3  5403.6 2099.72
  5433.1 2103.52  5468.8  2104.6  5599.9 2111.81  5640.8 2113.03  5678.9 2115.69
#Mann= 10 ,-1 , 0
  4126.4     .16       0  4170.2      .1       0  4373.1     .16       0
  4458.1      .1       0  4887.6     .05       0  4996.5    .035       0
  5002.5     .05       0  5016.2      .1       0  5140.3     .05       0
  5599.9     .16       0
Bank Sta=4996.5,5002.5
XS Rating Curve= 0 ,0
Exp/Cntr=0.3,0.1

Type RM Length L Ch R = 1 ,2924    ,894,894,894
BEGIN DESCRIPTION:
UNT 1012 IN HEWA 6.0
END DESCRIPTION:
XS GIS Cut Line= 3
      2624558.89     10075724.45      2625418.26      10074769.6
      2625522.15     10074267.45
#Sta/Elev= 30
  3928.6 2109.61  3944.5 2108.53    3971 2106.49  4219.1 2100.52  4282.7 2095.82
  4346.6 2093.36  4360.4 2093.01  4374.6  2094.1  4388.8 2092.88  4523.3 2089.46
  4597.6 2086.45  4820.8 2082.72  4943.8 2082.99  4969.6 2083.58    4995 2081.22
  4997.7 2080.72    5001 2081.22  5033.1 2083.54    5069 2088.72  5108.1 2090.03
  5180.4 2091.55  5241.8 2093.64  5337.2 2099.58    5352 2099.32  5382.3 2101.91
  5413.2 2102.52  5443.9 2101.29  5464.3 2103.59  5585.7 2108.82    5726 2117.46
#Mann= 9 ,-1 , 0
  3928.6     .16       0  3944.5      .1       0  4597.6     .05       0
  4943.8      .1       0    4995     .07       0    5001      .1       0
  5108.1     .16       0  5180.4     .05       0  5585.7     .16       0
Bank Sta=4995,5001
XS Rating Curve= 0 ,0
Exp/Cntr=0.3,0.1

Type RM Length L Ch R = 1 ,2030    ,1074,1074,1074
BEGIN DESCRIPTION:
UNT 1012 IN HEWA 4.0
END DESCRIPTION:
XS GIS Cut Line= 4
        2625045.     10075984.87       2625756.8     10075637.65
      2625782.84     10075073.42      2625817.53     10074258.06
#Sta/Elev= 30
  4071.7 2089.71  4156.6 2088.62  4286.2 2085.92  4452.2  2084.1  4504.3 2083.54
  4713.7 2081.35  4728.7 2081.28  4884.9 2079.42  4957.7 2078.77  4994.7 2073.34
  4997.5 2072.84  5000.7 2073.34  5017.8 2073.71  5037.8 2075.78  5060.4 2075.45
  5110.5  2075.8  5338.1 2079.65  5405.9 2082.05  5425.8 2083.17  5548.3 2087.39
  5592.4 2088.42  5690.7 2091.64  5828.6 2095.09  5913.7  2099.6  5938.6 2099.25
  5958.7  2098.2  5978.7  2100.9  6083.7  2104.6  6151.4 2107.07  6244.6 2111.74
#Mann= 14 ,-1 , 0
  4071.7      .1       0  4452.2     .05       0  4504.3      .1       0
  4713.7     .05       0  4728.7      .1       0  4884.9     .05       0
  4994.7    .035       0  5000.7     .05       0  5060.4      .1       0
  5110.5     .05       0  5405.9      .1       0  5592.4     .16       0
  5690.7     .05       0  6083.7     .16       0
Bank Sta=4994.7,5000.7
XS Rating Curve= 0 ,0
Exp/Cntr=0.3,0.1

Type RM Length L Ch R = 1 ,956     ,0,0,0
BEGIN DESCRIPTION:
UNT 1012 IN HEWA 1.0
END DESCRIPTION:
XS GIS Cut Line= 4
     2625841.505    10075805.412     2626721.714    10075438.225
      2626794.63    10075209.058     2626305.047    10074784.579
#Sta/Elev= 30
    30002078.559 3109.822077.567 3319.492076.287 3529.152074.427 3569.092073.302
 3688.892071.012 3708.862070.782 3738.812071.006 3818.692069.994 3948.48 2067.08
 4016.492066.834 4045.512067.104 4055.182067.026 4064.852066.565 4074.532065.823
  4084.22065.483 4103.542066.106 4122.89 2067.22 4142.232067.712 4209.932067.621
 4259.342068.356 4368.052068.993  4447.12068.759 4565.692070.085 4634.86 2071.67
 4664.512072.824 4743.562079.127 4773.212080.884 4792.972082.465 4862.152085.974
#Mann= 3 , 0 , 0
    3000      .1       0 4064.85    .035       0 4103.54     .05       0
Bank Sta=4064.85,4103.54
XS Rating Curve= 0 ,0
Exp/Cntr=0.3,0.1

Chan Stop Cuts=-1
Use User Specified Reach Order=0
Composite Channel Slope=5