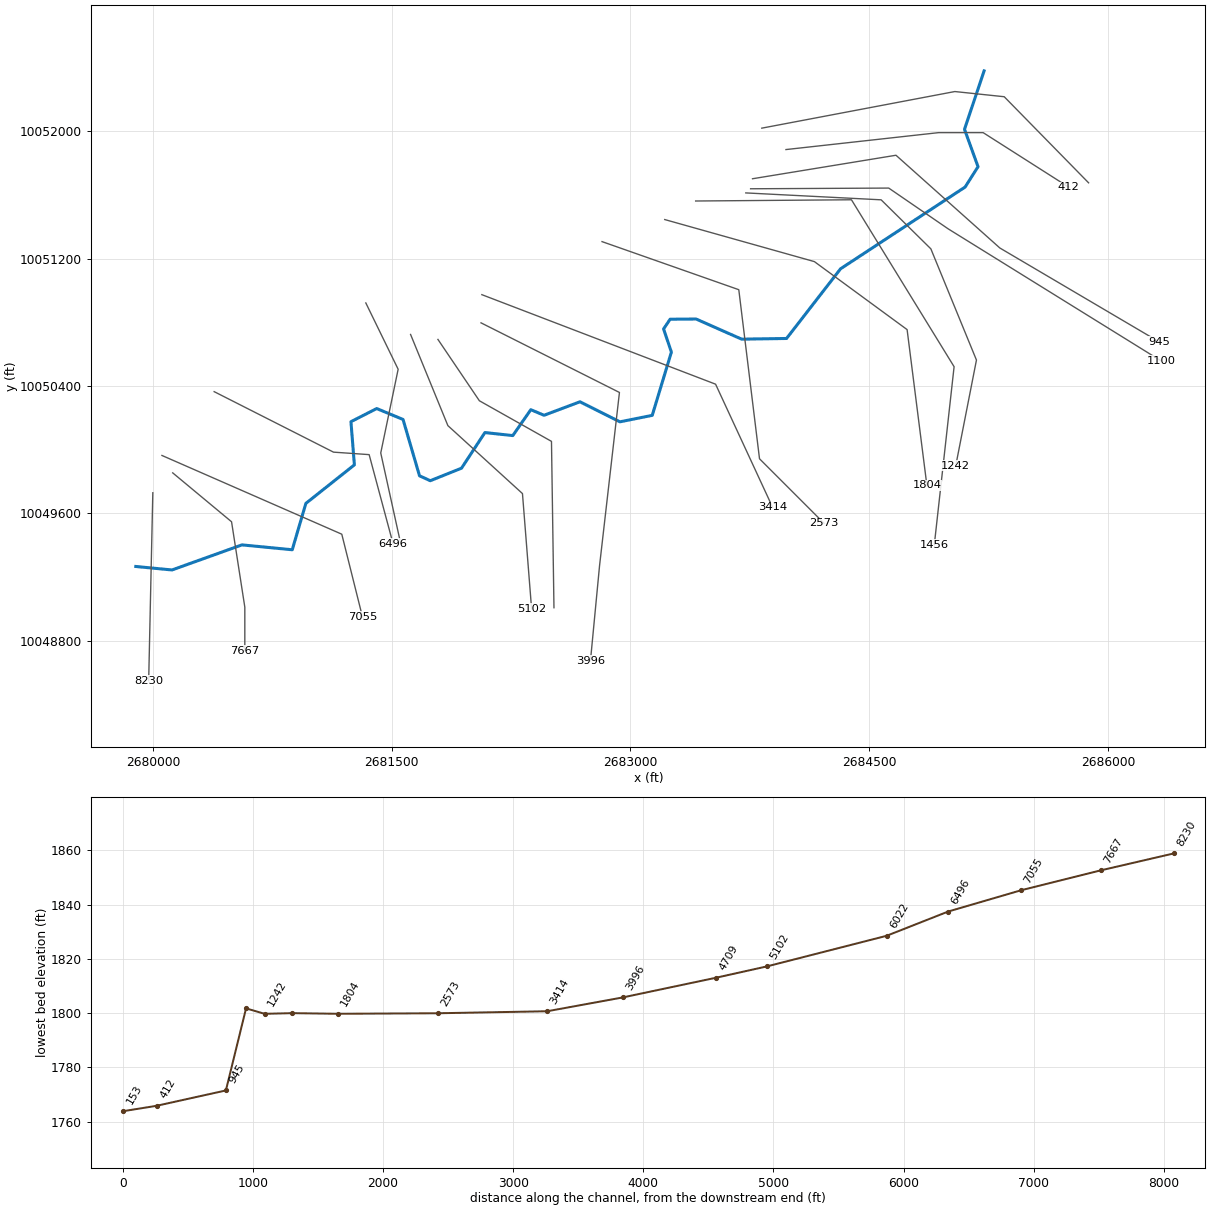
--- UNT 1013 IN HEWA.prj (project) ---

Proj Title=UNT 1013 IN HEWA Base Level Engineering
Current Plan=p01
Default Exp/Contr=0.3,0.1
English Units
Geom File=g01
Flow File=f01
Plan File=p01
BEGIN DESCRIPTION:
UNT 1013 IN HEWA
END DESCRIPTION:

--- UNT 1013 IN HEWA.p01 (plan) ---

Plan Title=Multiple Run
Short Identifier=Multiple
Geom File=g01
Flow File=f01
Subcritical Flow
K Sum by GR= 0
Std Step Tol= 0.01
Critical Tol= 0.01
Num of Std Step Trials= 20
Max Error Tol= 0.3
Flow Tol Ratio= 0.001
Split Flow NTrial= 30
Split Flow Tol= 0.02
Split Flow Ratio= 0.02
Log Output Level= 0
Friction Slope Method= 1
Unsteady Friction Slope Method= 2
Unsteady Bridges Friction Slope Method= 1
Parabolic Critical Depth
Global Vel Dist=  1 , 1 , 1
Global Log Level= 0
CheckData=True
Encroach Param= -1, 0, 0, 0
BEGIN DESCRIPTION:
Multiple Run
END DESCRIPTION:

--- UNT 1013 IN HEWA.f01 (steady flow) ---

Flow Title=Multiple
Number of Profiles=7
Profile Names=10-year,25-year,50-year,1pct_min,100-year,1pct_plu,500-year
River Rch & RM= UNT 1013 IN HEWA,Reach-1,8230
    2110    3173    4121    3892    5264    7119    8594
Boundary for River Rch & Prof#=UNT 1013 IN HEWA,Reach-1,1
Up Type=0
Dn Type=3
Dn Slope=0.005
Boundary for River Rch & Prof#=UNT 1013 IN HEWA,Reach-1,2
Up Type=0
Dn Type=3
Dn Slope=0.005
Boundary for River Rch & Prof#=UNT 1013 IN HEWA,Reach-1,3
Up Type=0
Dn Type=3
Dn Slope=0.005
Boundary for River Rch & Prof#=UNT 1013 IN HEWA,Reach-1,4
Up Type=0
Dn Type=3
Dn Slope=0.005
Boundary for River Rch & Prof#=UNT 1013 IN HEWA,Reach-1,5
Up Type=0
Dn Type=3
Dn Slope=0.005
Boundary for River Rch & Prof#=UNT 1013 IN HEWA,Reach-1,6
Up Type=0
Dn Type=3
Dn Slope=0.005
Boundary for River Rch & Prof#=UNT 1013 IN HEWA,Reach-1,7
Up Type=0
Dn Type=3
Dn Slope=0.005

--- UNT 1013 IN HEWA.g01 (geometry) ---

Geom Title=Existing Conditions

River Reach=UNT 1013 IN HEWA,Reach-1
Reach XY= 30
      2679892.10     10049266.52      2680119.37     10049244.63
      2680558.80     10049402.26      2680874.93     10049371.61
      2680960.55     10049663.01      2681265.40     10049905.02
      2681243.85     10050176.48      2681405.72     10050258.98
      2681571.18     10050190.32      2681674.70     10049836.39
      2681742.45     10049805.46      2681938.57     10049884.16
      2682085.67     10050108.06      2682260.73     10050089.06
      2682374.23     10050251.83      2682457.36     10050216.71
      2682682.99     10050301.42      2682934.09     10050175.53
      2683137.17     10050216.20      2683257.51     10050613.73
      2683208.49     10050759.18      2683249.48     10050820.33
      2683412.60     10050821.66      2683698.86     10050695.09
      2683981.13     10050699.31      2684320.55     10051137.21
      2685103.30     10051650.93      2685184.49     10051778.83
      2685099.44     10052013.73      2685222.48     10052380.70

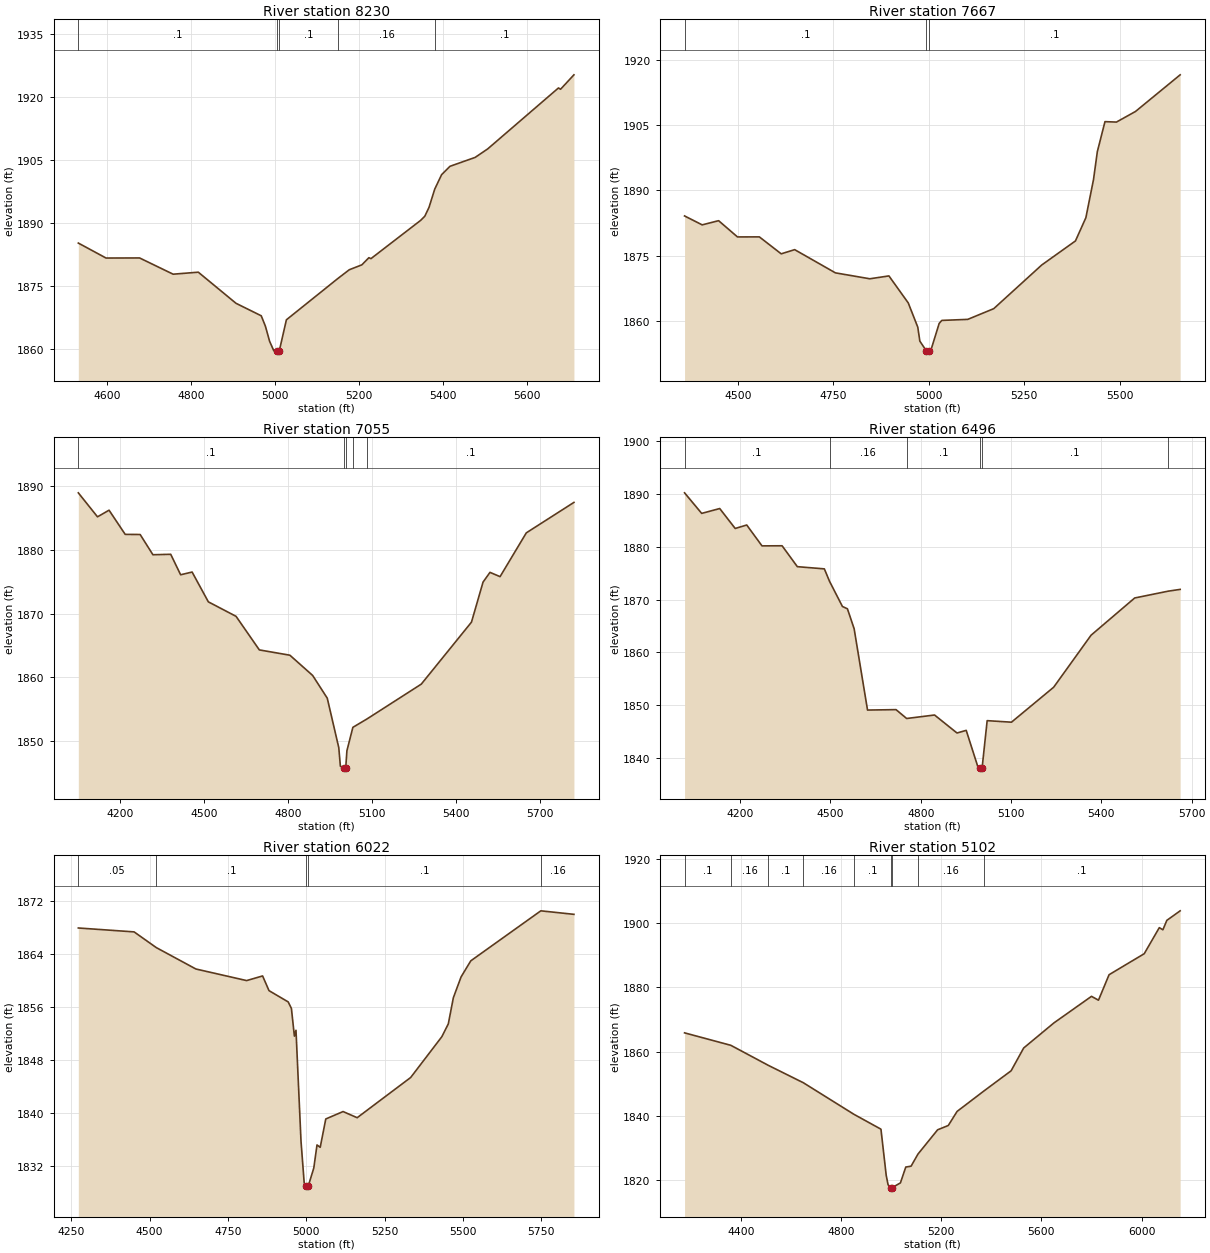
Type RM Length L Ch R = 1,8230,563,563,563
BEGIN DESCRIPTION:
UNT 1013 IN HEWA 17.0
END DESCRIPTION:
XS GIS Cut Line= 2
      2679998.76     10049729.78      2679972.74     10048548.17
#Sta/Elev= 30
  4531.0 1885.15  4597.1 1881.58  4677.1 1881.60  4757.1 1877.73  4817.1 1878.21
  4907.1 1870.79  4967.2 1867.82  4977.2 1865.32  4987.2 1861.73  4997.2 1859.48
  5004.2 1859.42  5006.9 1858.92  5010.2 1859.42  5027.2 1866.86  5150.4 1876.74
  5177.2 1878.79  5207.2 1879.96  5223.9 1881.66  5228.9 1881.44  5347.3 1890.55
  5357.3 1891.55  5367.3 1893.65  5380.9 1897.99  5397.3 1901.44  5417.3 1903.44
  5477.3 1905.56  5507.3 1907.59  5676.0 1922.11  5681.0 1921.80  5712.9 1925.24
#Mann=5,-1,0
  4531.0     0.1       0  5004.2    0.07       0  5010.2     0.1       0
  5150.4    0.16       0  5380.9     0.1       0
Bank Sta=5004.2,5010.2
Exp/Cntr=0.3,0.1

Type RM Length L Ch R = 1,7667,612,612,612
BEGIN DESCRIPTION:
UNT 1013 IN HEWA 16.0
END DESCRIPTION:
XS GIS Cut Line= 4
      2680123.79     10049854.80      2680493.56     10049547.53
      2680576.89     10049011.07      2680576.89     10048736.83
#Sta/Elev= 30
  4360.2 1884.15  4406.4 1882.10  4449.4 1883.06  4498.8 1879.33  4556.1 1879.34
  4613.3 1875.45  4648.6 1876.41  4755.3 1871.08  4845.4 1869.72  4895.4 1870.38
  4946.0 1864.18  4971.0 1858.61  4976.4 1855.40  4993.6 1853.15  4996.4 1852.65
  4999.6 1853.15  5006.7 1853.71  5027.0 1859.47  5033.9 1860.16  5101.9 1860.40
  5169.9 1862.86  5295.8 1872.90  5383.9 1878.41  5411.2 1883.75  5431.2 1892.51
  5441.2 1898.91  5461.2 1905.80  5491.2 1905.70  5541.2 1908.14  5658.1 1916.55
#Mann=3,-1,0
  4360.2     0.1       0  4993.6    0.07       0  4999.6     0.1       0
Bank Sta=4993.6,4999.6
Exp/Cntr=0.3,0.1

Type RM Length L Ch R = 1,7055,559,559,559
BEGIN DESCRIPTION:
UNT 1013 IN HEWA 15.0
END DESCRIPTION:
XS GIS Cut Line= 3
      2680056.08     10049964.19      2681186.26     10049469.41
      2681316.45     10048948.68
#Sta/Elev= 30
  4049.6 1888.91  4118.1 1885.15  4159.4 1886.19  4217.1 1882.40  4270.5 1882.38
  4316.1 1879.21  4379.7 1879.28  4415.1 1876.07  4456.1 1876.50  4514.1 1871.83
  4613.1 1869.56  4696.3 1864.30  4805.4 1863.47  4886.7 1860.30  4938.9 1856.74
  4980.1 1848.98  4985.7 1846.09  4998.9 1845.81  5001.7 1845.31  5004.9 1845.81
  5009.1 1848.50  5030.4 1852.17  5080.7 1853.48  5274.8 1858.94  5454.1 1868.65
  5495.4 1874.92  5520.2 1876.45  5556.2 1875.78  5650.0 1882.64  5820.1 1887.41
#Mann=5,-1,0
  4049.6     0.1       0  4998.9    0.07       0  5004.9     0.1       0
  5030.4    0.16       0  5080.7     0.1       0
Bank Sta=4998.9,5004.9
Exp/Cntr=0.3,0.1

Type RM Length L Ch R = 1,6496,474,474,474
BEGIN DESCRIPTION:
UNT 1013 IN HEWA 14.0
END DESCRIPTION:
XS GIS Cut Line= 4
      2680384.21     10050365.23      2681134.18     10049985.03
      2681358.14     10049969.41      2681508.93     10049407.84
#Sta/Elev= 30
  4015.1 1890.25  4072.0 1886.35  4132.0 1887.27  4183.4 1883.49  4221.7 1884.15
  4272.4 1880.19  4339.2 1880.21  4389.9 1876.25  4479.6 1875.83  4496.9 1873.47
  4539.7 1868.70  4556.3 1868.26  4578.6 1864.48  4623.1 1849.06  4717.8 1849.14
  4753.1 1847.46  4845.8 1848.12  4920.4 1844.71  4951.0 1845.21  4990.6 1838.15
  4997.6 1837.98  5000.3 1837.48  5003.6 1837.98  5020.6 1847.05  5101.4 1846.76
  5241.6 1853.39  5365.8 1863.25  5510.8 1870.31  5621.8 1871.60  5661.9 1871.94
#Mann=6,-1,0
  4015.1     0.1       0  4496.9    0.16       0  4753.1     0.1       0
  4997.6    0.07       0  5003.6     0.1       0  5621.8    0.16       0
Bank Sta=4997.6,5003.6
Exp/Cntr=0.3,0.1

Type RM Length L Ch R = 1,6022,920,920,920
BEGIN DESCRIPTION:
UNT 1013 IN HEWA 13.0
END DESCRIPTION:
XS GIS Cut Line= 4
      2681337.29     10050922.57      2681540.43     10050505.86
      2681431.06     10049979.82      2681556.06     10049412.10
#Sta/Elev= 30
  4272.3 1867.93  4450.4 1867.34  4521.2 1864.97  4647.6 1861.74  4809.6 1859.99
  4860.6 1860.69  4881.1 1858.47  4942.3 1856.77  4952.6 1855.78  4962.1 1851.60
  4967.2 1852.49  4983.2 1835.77  4993.4 1829.43  5000.6 1829.01  5003.4 1828.51
  5006.6 1829.01  5024.0 1831.69  5034.3 1835.18  5044.5 1834.82  5062.3 1839.10
  5117.5 1840.22  5162.5 1839.29  5333.3 1845.36  5433.0 1851.53  5453.5 1853.46
  5469.6 1857.41  5494.4 1860.56  5525.2 1862.97  5748.8 1870.52  5854.5 1869.99
#Mann=5,-1,0
  4272.3    0.05       0  4521.2     0.1       0  5000.6    0.07       0
  5006.6     0.1       0  5748.8    0.16       0
Bank Sta=5000.6,5006.6
Exp/Cntr=0.3,0.1

Type RM Length L Ch R = 1,5102,393,393,393
BEGIN DESCRIPTION:
UNT 1013 IN HEWA 11.0
END DESCRIPTION:
XS GIS Cut Line= 4
      2681618.56     10050724.60      2681852.93     10050151.70
      2682321.68     10049724.61      2682378.97     10049000.70
#Sta/Elev= 30
  4174.9 1865.87  4359.8 1861.99  4509.3 1855.76  4649.3 1850.34  4852.5 1840.46
  4959.3 1835.88  4980.2 1821.54  4987.7 1818.58  4998.9 1817.72  5001.6 1817.22
  5004.9 1817.72  5037.0 1819.16  5058.4 1824.09  5079.6 1824.37  5107.1 1828.13
  5185.6 1835.69  5228.2 1837.03  5263.3 1841.41  5372.1 1847.87  5479.1 1854.06
  5529.2 1861.15  5649.6 1868.94  5800.1 1877.24  5828.0 1876.04  5870.3 1883.97
  6010.7 1890.51  6070.9 1898.62  6085.2 1897.96  6101.0 1900.89  6154.2 1903.86
#Mann=9,-1,0
  4174.9     0.1       0  4359.8    0.16       0  4509.3     0.1       0
  4649.3    0.16       0  4852.5     0.1       0  4998.9    0.07       0
  5004.9     0.1       0  5107.1    0.16       0  5372.1     0.1       0
Bank Sta=4998.9,5004.9
Exp/Cntr=0.3,0.1

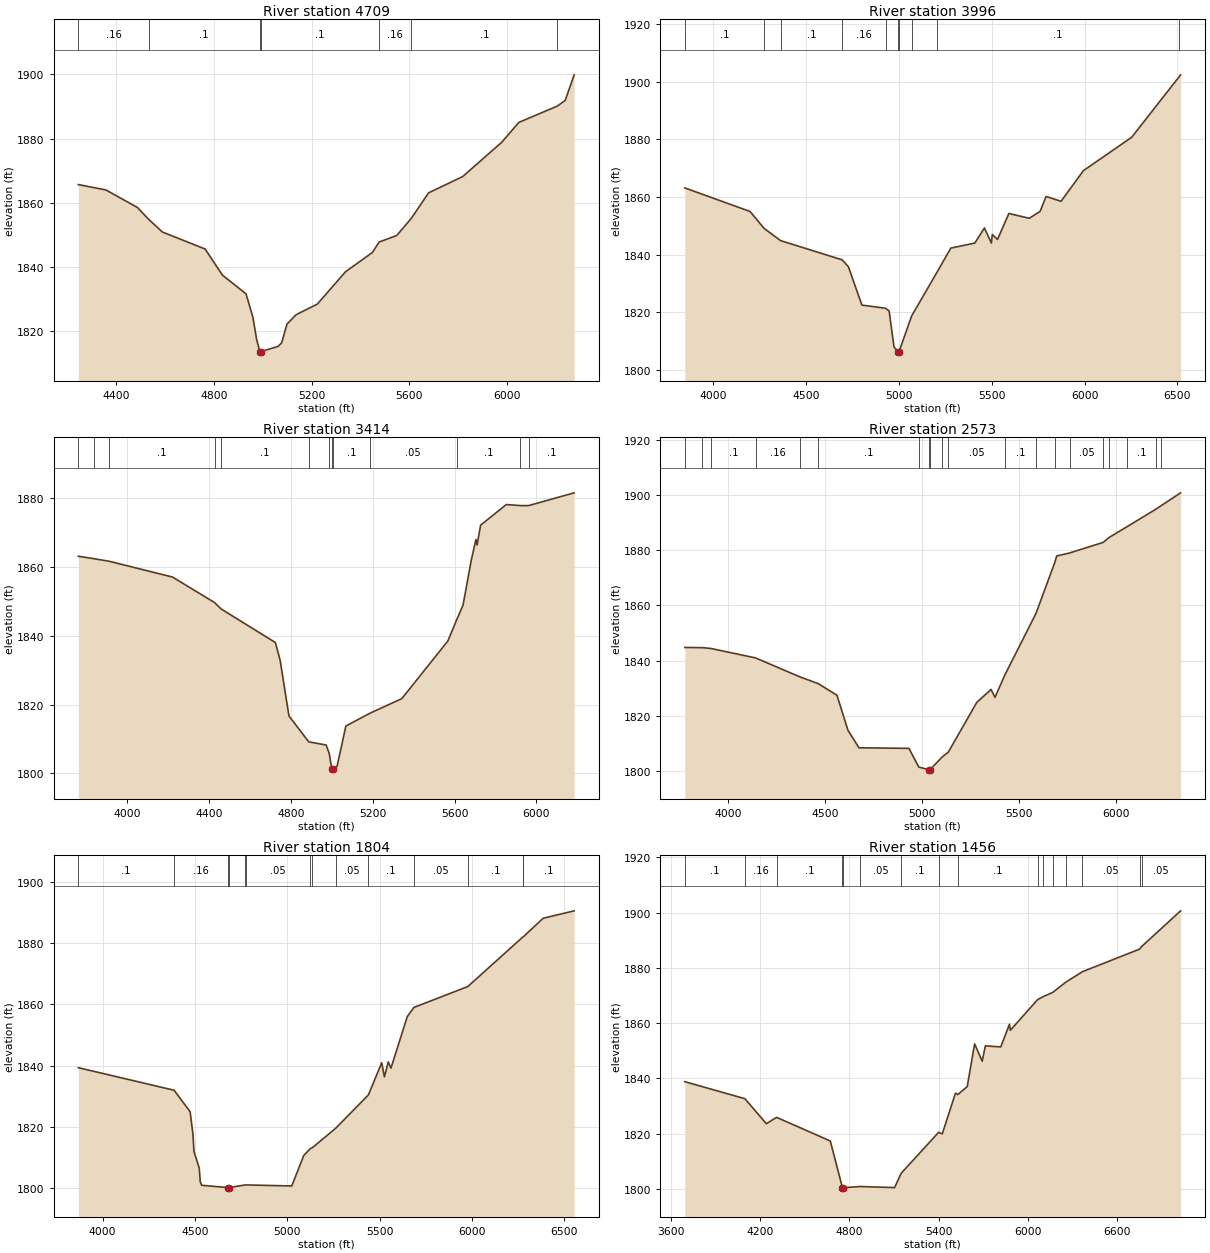
Type RM Length L Ch R = 1,4709,713,713,713
BEGIN DESCRIPTION:
UNT 1013 IN HEWA 10.0
END DESCRIPTION:
XS GIS Cut Line= 4
      2681790.46     10050693.33      2682050.85     10050307.95
      2682503.97     10050052.74      2682519.58     10049007.31
#Sta/Elev= 30
  4244.8 1865.63  4358.2 1863.94  4487.0 1858.47  4532.4 1854.82  4588.9 1850.83
  4764.1 1845.51  4834.9 1837.37  4931.7 1831.52  4959.7 1824.25  4975.0 1817.32
  4988.0 1813.52  4990.7 1813.02  4994.0 1813.52  5063.0 1815.12  5077.6 1816.24
  5099.3 1822.07  5136.9 1825.02  5223.6 1828.32  5339.0 1838.41  5449.0 1844.43
  5476.8 1847.70  5549.0 1849.74  5608.6 1855.09  5679.0 1863.03  5819.0 1868.13
  5979.0 1878.84  6049.1 1885.04  6206.8 1890.13  6239.1 1891.92  6275.5 1899.88
#Mann=7,-1,0
  4244.8    0.16       0  4532.4     0.1       0  4988.0    0.07       0
  4994.0     0.1       0  5476.8    0.16       0  5608.6     0.1       0
  6206.8    0.16       0
Bank Sta=4988,4994
Exp/Cntr=0.3,0.1

Type RM Length L Ch R = 1,3996,582,582,582
BEGIN DESCRIPTION:
UNT 1013 IN HEWA 9.0
END DESCRIPTION:
XS GIS Cut Line= 4
      2682061.23     10050797.55      2682931.06     10050360.03
      2682806.06     10049271.49      2682748.77     10048672.58
#Sta/Elev= 30
  3846.5 1863.13  4198.0 1854.96  4274.7 1849.03  4362.6 1844.84  4694.4 1838.16
  4727.7 1835.79  4800.6 1822.46  4927.9 1821.37  4947.3 1820.40  4973.4 1807.95
  4994.6 1806.29  4997.4 1805.79  5000.6 1806.29  5068.8 1818.73  5206.1 1833.97
  5279.5 1842.24  5408.9 1843.99  5460.6 1849.23  5498.1 1843.99  5503.1 1846.96
  5531.1 1845.25  5592.2 1854.25  5702.2 1852.59  5760.4 1854.98  5792.8 1860.17
  5873.3 1858.48  5994.0 1869.13  6254.1 1880.72  6506.9 1901.51  6517.5 1902.38
#Mann=10,-1,0
  3846.5     0.1       0  4274.7    0.16       0  4362.6     0.1       0
  4694.4    0.16       0  4927.9     0.1       0  4994.6    0.07       0
  5000.6     0.1       0  5068.8    0.16       0  5206.1     0.1       0
  6506.9    0.16       0
Bank Sta=4994.6,5000.6
Exp/Cntr=0.3,0.1

Type RM Length L Ch R = 1,3414,841,841,841
BEGIN DESCRIPTION:
UNT 1013 IN HEWA 7.0
END DESCRIPTION:
XS GIS Cut Line= 3
      2682066.44     10050974.63      2683535.22     10050412.11
      2683893.41     10049638.64
#Sta/Elev= 30
  3759.8 1863.13  3835.9 1862.43  3912.0 1861.66  4220.4 1857.09  4426.5 1849.66
  4458.4 1847.81  4723.6 1838.06  4747.1 1832.86  4790.0 1816.72  4886.9 1809.19
  4972.0 1808.27  4987.2 1805.75  4999.7 1801.18  5002.4 1800.68  5005.7 1801.18
  5025.5 1802.11  5068.4 1813.79  5185.2 1817.48  5341.9 1821.75  5567.1 1838.49
  5609.7 1844.56  5641.4 1848.91  5681.7 1861.97  5704.6 1868.02  5710.1 1866.40
  5727.5 1872.18  5853.1 1878.16  5922.2 1877.86  5962.2 1877.86  6185.0 1881.57
#Mann=13,-1,0
  3759.8     0.1       0  3835.9    0.16       0  3912.0     0.1       0
  4426.5    0.16       0  4458.4     0.1       0  4886.9    0.16       0
  4987.2     0.1       0  4999.7    0.07       0  5005.7     0.1       0
  5185.2    0.05       0  5609.7     0.1       0  5922.2    0.05       0
  5962.2     0.1       0
Bank Sta=4999.7,5005.7
Exp/Cntr=0.3,0.1

Type RM Length L Ch R = 1,2573,769,769,769
BEGIN DESCRIPTION:
UNT 1013 IN HEWA 6.0
END DESCRIPTION:
XS GIS Cut Line= 4
      2682821.65     10051307.96      2683681.06     10051005.86
      2683811.26     10049943.36      2684216.72     10049537.91
#Sta/Elev= 30
  3775.8 1844.76  3866.1 1844.69  3910.6 1844.39  4140.3 1840.97  4371.7 1834.02
  4463.7 1831.64  4559.8 1827.44  4616.5 1814.75  4673.1 1808.40  4930.7 1808.19
  4981.4 1801.42  5033.0 1800.44  5035.7 1799.94  5039.0 1800.44  5100.8 1804.99
  5133.8 1806.85  5280.2 1824.84  5353.8 1829.54  5374.0 1826.67  5424.4 1834.71
  5585.2 1857.07  5681.1 1875.33  5692.2 1877.91  5758.4 1879.00  5932.1 1882.85
  5960.3 1884.55  6052.7 1888.45  6204.0 1894.90  6229.6 1896.12  6330.6 1900.80
#Mann=20,-1,0
  3775.8     0.1       0  3866.1    0.05       0  3910.6     0.1       0
  4140.3    0.16       0  4371.7     0.1       0  4463.7     0.1       0
  4981.4    0.16       0  5033.0    0.07       0  5039.0    0.16       0
  5100.8     0.1       0  5133.8    0.05       0  5424.4     0.1       0
  5585.2    0.05       0  5681.1     0.1       0  5758.4    0.05       0
  5932.1     0.1       0  5960.3    0.05       0  6052.7     0.1       0
  6204.0    0.05       0  6229.6     0.1       0
Bank Sta=5033,5039
Exp/Cntr=0.3,0.1

Type RM Length L Ch R = 1,1804,348,348,348
BEGIN DESCRIPTION:
UNT 1013 IN HEWA 4.0
END DESCRIPTION:
XS GIS Cut Line= 4
      2683215.68     10051446.64      2684155.94     10051182.44
      2684738.75     10050755.05      2684862.90     10049777.29
#Sta/Elev= 30
  3868.2 1839.33  4386.8 1831.98  4473.6 1824.98  4489.0 1817.62  4494.3 1812.05
  4523.1 1806.56  4528.3 1802.19  4535.9 1801.01  4678.3 1800.25  4681.1 1799.75
  4684.3 1800.25  4771.1 1801.11  4773.6 1801.12  5024.0 1800.78  5088.9 1810.72
  5125.0 1812.99  5135.2 1813.24  5261.6 1819.58  5439.0 1830.46  5511.0 1840.95
  5525.7 1836.35  5546.6 1841.22  5561.2 1839.19  5649.6 1855.99  5685.3 1858.97
  5977.1 1865.77  6275.7 1881.95  6278.6 1882.04  6385.4 1888.04  6553.2 1890.46
#Mann=14,-1,0
  3868.2     0.1       0  4386.8    0.16       0  4678.3   0.033       0
  4684.3    0.16       0  4771.1     0.1       0  4773.6    0.05       0
  5125.0    0.16       0  5135.2     0.1       0  5261.6    0.05       0
  5439.0     0.1       0  5685.3    0.05       0  5977.1     0.1       0
  6275.7    0.05       0  6278.6     0.1       0
Bank Sta=4678.3,4684.3
Exp/Cntr=0.3,0.1

Type RM Length L Ch R = 1,1456,214,214,214
BEGIN DESCRIPTION:
UNT 1013 IN HEWA 3.0
END DESCRIPTION:
XS GIS Cut Line= 4
      2683409.98     10051563.21      2684389.06     10051570.98
      2685034.04     10050521.92      2684909.70     10049402.89
#Sta/Elev= 30
  3692.0 1838.85  4096.6 1832.68  4240.5 1823.65  4310.0 1825.93  4671.1 1817.39
  4752.9 1800.48  4755.7 1799.98  4758.9 1800.48  4868.5 1800.92  5103.8 1800.54
  5148.0 1805.71  5400.2 1820.53  5424.6 1819.96  5513.1 1834.67  5529.2 1834.18
  5592.7 1837.08  5642.2 1852.51  5693.2 1846.24  5714.5 1851.79  5818.3 1851.41
  5876.8 1859.61  5882.6 1857.42  6066.1 1868.51  6101.0 1869.54  6169.1 1871.17
  6256.2 1874.85  6368.0 1878.62  6752.5 1886.78  6765.8 1887.69  7028.5 1900.63
#Mann=16,-1,0
  3692.0     0.1       0  4096.6    0.16       0  4310.0     0.1       0
  4752.9   0.033       0  4758.9     0.1       0  4868.5    0.05       0
  5148.0     0.1       0  5400.2    0.05       0  5529.2     0.1       0
  6066.1    0.05       0  6101.0     0.1       0  6169.1    0.05       0
  6256.2     0.1       0  6368.0    0.05       0  6752.5     0.1       0
  6765.8    0.05       0
Bank Sta=4752.9,4758.9
Exp/Cntr=0.3,0.1

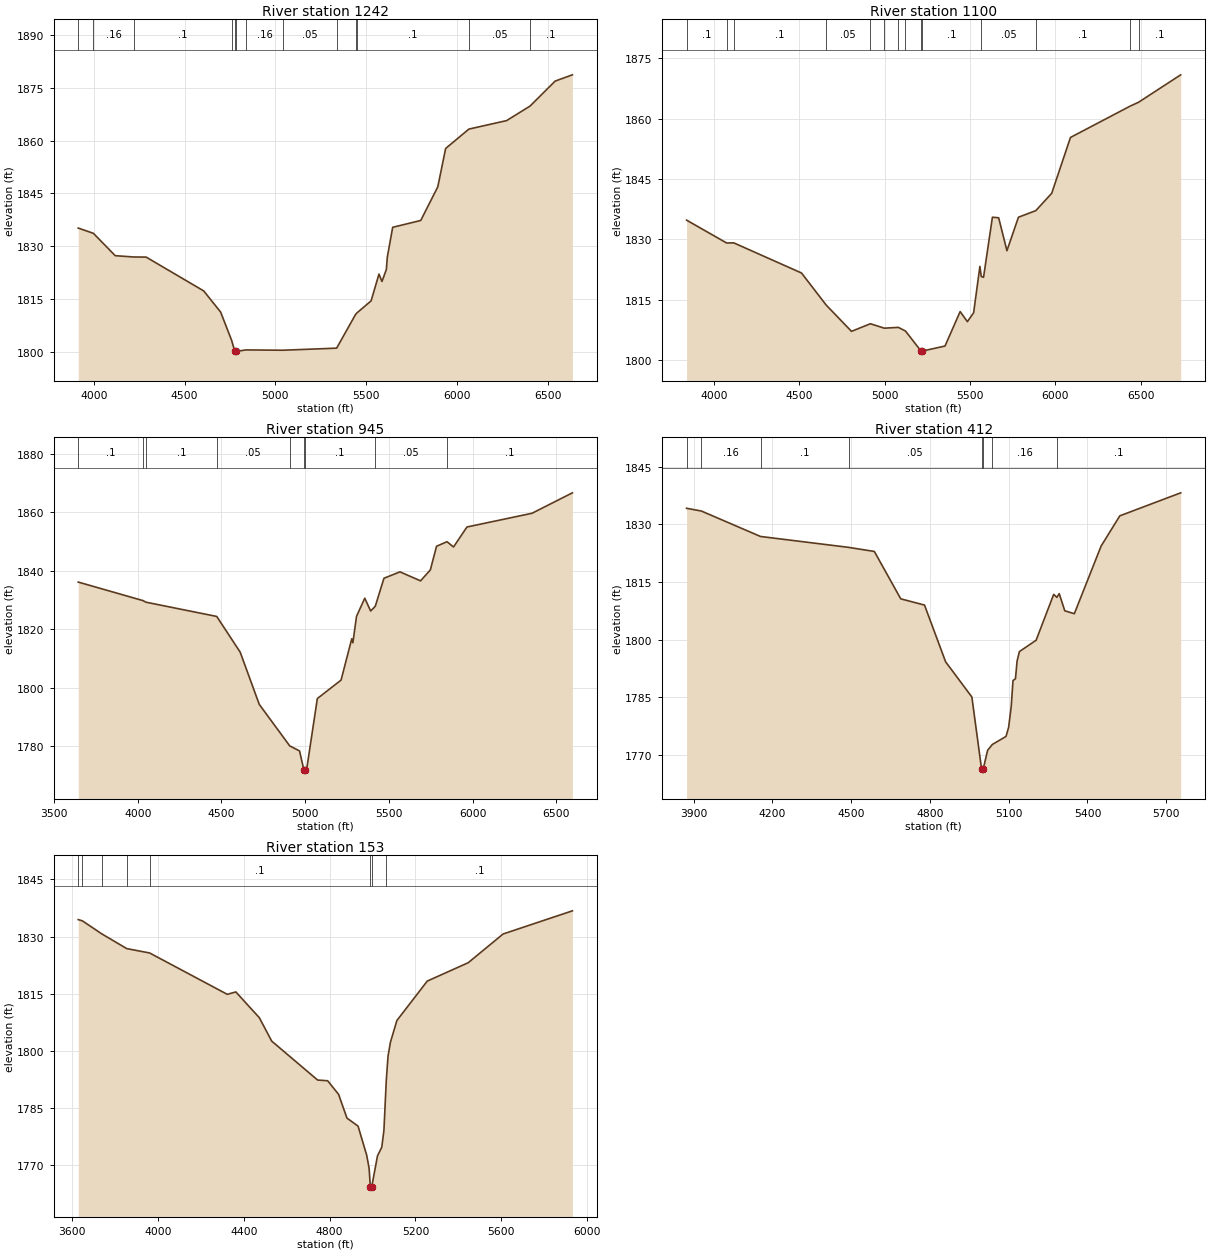
Type RM Length L Ch R = 1,1242,142,142,142
BEGIN DESCRIPTION:
Mapping XS df70e325
END DESCRIPTION:
XS GIS Cut Line= 5
      2683724.92     10051614.06      2684575.57     10051570.66
      2684888.07     10051262.50      2685174.53     10050563.72
      2685044.32     10049899.63
#Sta/Elev= 30
  3914.1 1835.19  3997.5 1833.70  4117.9 1827.36  4219.3 1826.99  4288.1 1826.96
  4605.5 1817.37  4698.7 1811.37  4758.6 1803.44  4776.9 1800.24  4779.7 1799.74
  4782.9 1800.24  4839.0 1800.65  5041.3 1800.56  5337.8 1801.15  5442.2 1810.72
  5449.6 1811.14  5527.6 1814.55  5570.9 1822.14  5587.6 1820.05  5611.6 1823.46
  5617.0 1826.98  5646.5 1835.40  5801.1 1837.34  5895.1 1846.88  5938.3 1857.75
  6066.4 1863.24  6274.0 1865.64  6403.5 1869.77  6541.5 1876.84  6636.7 1878.62
#Mann=13,-1,0
  3914.1     0.1       0  3997.5    0.16       0  4219.3     0.1       0
  4758.6    0.05       0  4776.9    0.07       0  4782.9    0.05       0
  4839.0    0.16       0  5041.3    0.05       0  5337.8     0.1       0
  5442.2    0.05       0  5449.6     0.1       0  6066.4    0.05       0
  6403.5     0.1       0
Bank Sta=4776.9,4782.9
Exp/Cntr=0.3,0.1

Type RM Length L Ch R = 1,1100,155,155,155
BEGIN DESCRIPTION:
Mapping XS 390f6907
END DESCRIPTION:
XS GIS Cut Line= 4
      2683755.24     10051640.11      2684623.31     10051644.45
      2684996.58     10051388.37      2686333.36     10050559.39
#Sta/Elev= 30
  3840.2 1834.80  4074.9 1829.12  4117.1 1829.14  4513.4 1821.66  4657.6 1813.71
  4806.1 1807.16  4916.6 1809.05  4998.7 1807.95  5080.1 1808.15  5122.1 1807.25
  5213.7 1802.25  5216.4 1801.75  5219.7 1802.25  5353.7 1803.51  5442.3 1812.07
  5484.8 1809.57  5521.4 1811.80  5558.0 1823.30  5566.1 1820.80  5579.3 1820.59
  5631.3 1835.52  5667.9 1835.38  5716.3 1827.20  5783.7 1835.52  5885.6 1837.16
  5978.6 1841.47  6088.4 1855.34  6438.2 1863.13  6487.3 1864.09  6733.9 1870.90
#Mann=14,-1,0
  3840.2     0.1       0  4074.9    0.16       0  4117.1     0.1       0
  4657.6    0.05       0  4916.6    0.16       0  4998.7    0.05       0
  5080.1    0.16       0  5122.1     0.1       0  5213.7   0.035       0
  5219.7     0.1       0  5566.1    0.05       0  5885.6     0.1       0
  6438.2    0.05       0  6487.3     0.1       0
Bank Sta=5213.7,5219.7
Exp/Cntr=0.3,0.1

Type RM Length L Ch R = 1,945,533,533,533
BEGIN DESCRIPTION:
UNT 1013 IN HEWA 2.0
END DESCRIPTION:
XS GIS Cut Line= 4
      2683767.35     10051703.08      2684668.81     10051850.73
      2685321.56     10051267.92      2686323.72     10050677.49
#Sta/Elev= 30
  3644.7 1836.07  4031.8 1829.73  4048.0 1829.21  4472.1 1824.32  4612.1 1812.11
  4725.8 1794.29  4908.0 1780.08  4966.6 1778.36  4992.0 1771.96  4994.7 1771.46
  4998.0 1771.96  5009.2 1772.12  5072.8 1796.26  5214.6 1802.57  5278.4 1816.69
  5285.1 1815.32  5306.8 1824.35  5356.2 1830.56  5391.3 1826.18  5418.8 1827.79
  5470.7 1837.37  5566.3 1839.56  5689.3 1836.49  5747.8 1840.22  5784.9 1848.31
  5847.2 1849.86  5886.4 1848.07  5966.5 1854.89  6355.0 1859.58  6596.4 1866.57
#Mann=9,-1,0
  3644.7     0.1       0  4031.8    0.16       0  4048.0     0.1       0
  4472.1    0.05       0  4908.0     0.1       0  4992.0    0.07       0
  4998.0     0.1       0  5418.8    0.05       0  5847.2     0.1       0
Bank Sta=4992,4998
Exp/Cntr=0.3,0.1

Type RM Length L Ch R = 1,412,259,259,259
BEGIN DESCRIPTION:
Mapping XS dafe43a2
END DESCRIPTION:
XS GIS Cut Line= 4
      2683977.46     10051886.46      2684936.68     10051992.80
      2685216.63     10051992.80      2685754.16     10051650.34
#Sta/Elev= 30
  3872.7 1834.20  3929.3 1833.48  4154.5 1826.86  4489.7 1824.03  4588.1 1822.96
  4688.7 1810.63  4779.2 1809.01  4859.6 1794.24  4959.6 1785.08  4996.6 1766.29
  4999.3 1765.79  5002.6 1766.29  5019.6 1771.21  5037.4 1772.72  5089.6 1774.82
  5099.6 1777.19  5109.6 1782.70  5116.2 1789.36  5125.6 1789.82  5131.8 1794.43
  5140.8 1796.91  5204.3 1799.85  5271.2 1811.79  5283.5 1811.02  5292.3 1811.98
  5313.5 1807.52  5349.9 1806.76  5451.9 1824.36  5523.1 1832.23  5755.1 1838.22
#Mann=8,-1,0
  3872.7     0.1       0  3929.3    0.16       0  4154.5     0.1       0
  4489.7    0.05       0  4996.6   0.035       0  5002.6    0.05       0
  5037.4    0.16       0  5283.5     0.1       0
Bank Sta=4996.6,5002.6
Exp/Cntr=0.3,0.1

Type RM Length L Ch R = 1,153,0,0,0
BEGIN DESCRIPTION:
UNT 1013 IN HEWA 1.0
END DESCRIPTION:
XS GIS Cut Line= 4
      2683825.60     10052021.02      2685038.68     10052251.04
      2685349.01     10052218.49      2685879.33     10051677.35
#Sta/Elev= 30
  3627.5 1834.48  3646.9 1834.15  3736.9 1830.75  3853.7 1826.87  3960.3 1825.73
  4322.5 1814.88  4362.4 1815.51  4472.1 1808.74  4529.5 1802.62  4743.7 1792.40
  4790.7 1792.21  4841.6 1788.64  4880.7 1782.41  4932.4 1780.32  4972.6 1772.69
  4983.9 1769.25  4989.7 1764.29  4992.4 1763.79  4995.7 1764.29  5022.9 1772.50
  5043.0 1774.81  5053.0 1779.25  5064.0 1792.35  5072.1 1798.66  5083.2 1802.29
  5113.4 1808.01  5255.0 1818.35  5446.0 1823.17  5608.6 1830.70  5931.9 1836.78
#Mann=8,-1,0
  3627.5     0.1       0  3646.9    0.16       0  3736.9     0.1       0
  3853.7    0.16       0  3960.3     0.1       0  4989.7    0.07       0
  4995.7     0.1       0  5064.0     0.1       0
Bank Sta=4989.7,4995.7
Exp/Cntr=0.3,0.1

Chan Stop Cuts=-1