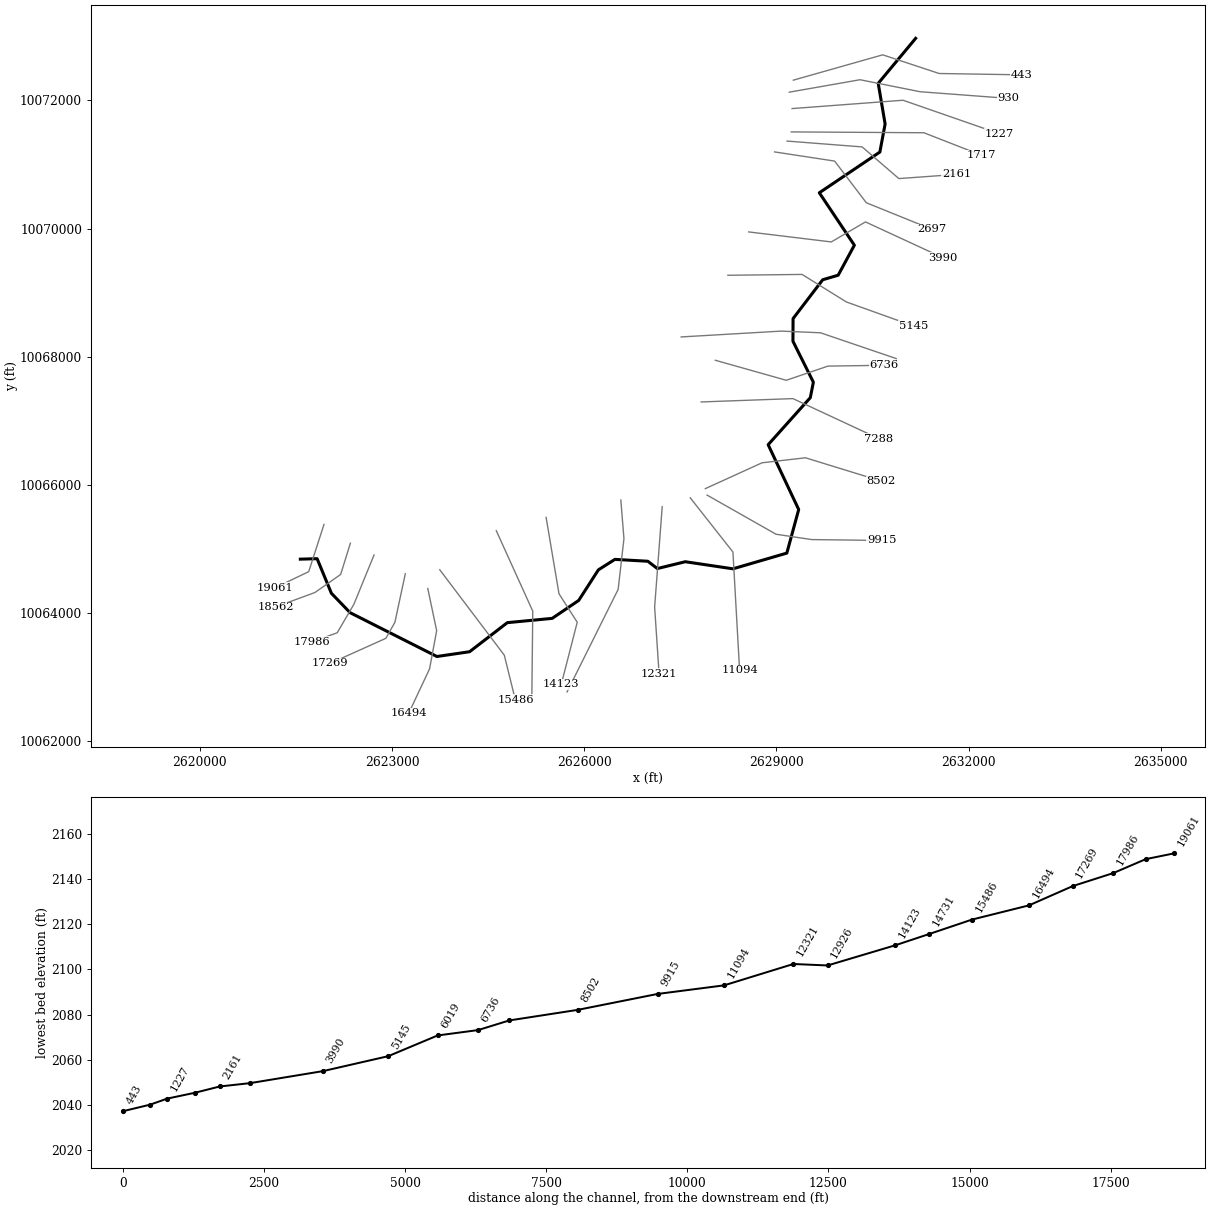
--- UNT 1014 IN HEWA.prj (project) ---

Proj Title=UNT 1014 IN HEWA Base Level Engineering
Current Plan=p01
Default Exp/Contr=0.3,0.1
English Units
Geom File=g01
Flow File=f01
Plan File=p01
Y Axis Title=Elevation
X Axis Title(PF)=Main Channel Distance
X Axis Title(XS)=Station
BEGIN DESCRIPTION:
UNT 1014 IN HEWA
END DESCRIPTION:
DSS Export Rating Curves= 0
DSS Export Rating Curve Sorted= 0
DSS Export Volume Flow Curves= 0
DXF OffsetX= 0
DXF OffsetY= 0
DXF ScaleX= 1
DXF ScaleY= 10

--- UNT 1014 IN HEWA.p01 (plan) ---

Plan Title=Multiple Run
Short Identifier=Multiple
Geom File=g01
Flow File=f01
Subcritical Flow
K Sum by GR= 0
Std Step Tol= 0.01
Critical Tol= 0.01
Num of Std Step Trials= 20
Max Error Tol= 0.3
Flow Tol Ratio= 0.001
Split Flow NTrial= 30
Split Flow Tol= 0.02
Split Flow Ratio= 0.02
Log Output Level= 0
Friction Slope Method= 1
Unsteady Friction Slope Method= 2
Unsteady Bridges Friction Slope Method= 1
Parabolic Critical Depth
Global Vel Dist=  1 , 1 , 1
Global Log Level= 0
CheckData=True
Encroach Param= -1, 0, 0, 0
BEGIN DESCRIPTION:
Multiple Run
END DESCRIPTION:

--- UNT 1014 IN HEWA.f01 (steady flow) ---

Flow Title=Multiple
Number of Profiles=7
Profile Names=10-year,25-year,50-year,1pct_min,100-year,1pct_plu,500-year
River Rch & RM= UNT 1014 IN HEWA,Reach-1,19061
     947    1363    1718    1578    2135    2887    3295
River Rch & RM= UNT 1014 IN HEWA,Reach-1,17986
    1686    2500    3213    3004    4063    5495    6502
River Rch & RM= UNT 1014 IN HEWA,Reach-1,12926
    2111    3158    4084    3837    5189    7017    8388
River Rch & RM= UNT 1014 IN HEWA,Reach-1,9915
    2430    3655    4742    4468    6043    8172    9826
River Rch & RM= UNT 1014 IN HEWA,Reach-1,6736
    2829    4275    5564    5256    7108    9613   11616
Boundary for River Rch & Prof#=UNT 1014 IN HEWA,Reach-1,1
Up Type=0
Dn Type=3
Dn Slope=0.005
Boundary for River Rch & Prof#=UNT 1014 IN HEWA,Reach-1,2
Up Type=0
Dn Type=3
Dn Slope=0.005
Boundary for River Rch & Prof#=UNT 1014 IN HEWA,Reach-1,3
Up Type=0
Dn Type=3
Dn Slope=0.005
Boundary for River Rch & Prof#=UNT 1014 IN HEWA,Reach-1,4
Up Type=0
Dn Type=3
Dn Slope=0.005
Boundary for River Rch & Prof#=UNT 1014 IN HEWA,Reach-1,5
Up Type=0
Dn Type=3
Dn Slope=0.005
Boundary for River Rch & Prof#=UNT 1014 IN HEWA,Reach-1,6
Up Type=0
Dn Type=3
Dn Slope=0.005
Boundary for River Rch & Prof#=UNT 1014 IN HEWA,Reach-1,7
Up Type=0
Dn Type=3
Dn Slope=0.005

--- UNT 1014 IN HEWA.g01 (geometry) ---

Geom Title=Existing Conditions
Program Version=4.10

River Reach=UNT 1014 IN HEWA,Reach-1
Reach XY= 30
      2621569.09     10064834.36       2621830.8     10064841.58
       2622053.9     10064301.27      2622345.62     10063998.39
      2623700.81     10063313.49      2624211.32     10063388.22
      2624800.23     10063842.27       2625500.9     10063909.24
      2625914.53     10064189.48      2626221.77     10064667.16
      2626479.68     10064830.79      2626993.61     10064801.65
      2627141.98     10064687.34      2627578.36     10064794.28
      2628322.28     10064683.44      2629163.59     10064928.92
      2629348.95     10065609.78      2628872.19     10066622.44
       2629530.2     10067357.12      2629577.98     10067599.14
      2629259.06     10068239.17      2629261.19     10068592.64
      2629723.68     10069199.51      2629965.04     10069270.17
      2630218.12     10069738.95      2629670.88     10070558.23
      2630616.22     10071194.73      2630698.11     10071633.62
      2630590.44     10072268.02      2631174.84      10072971.1

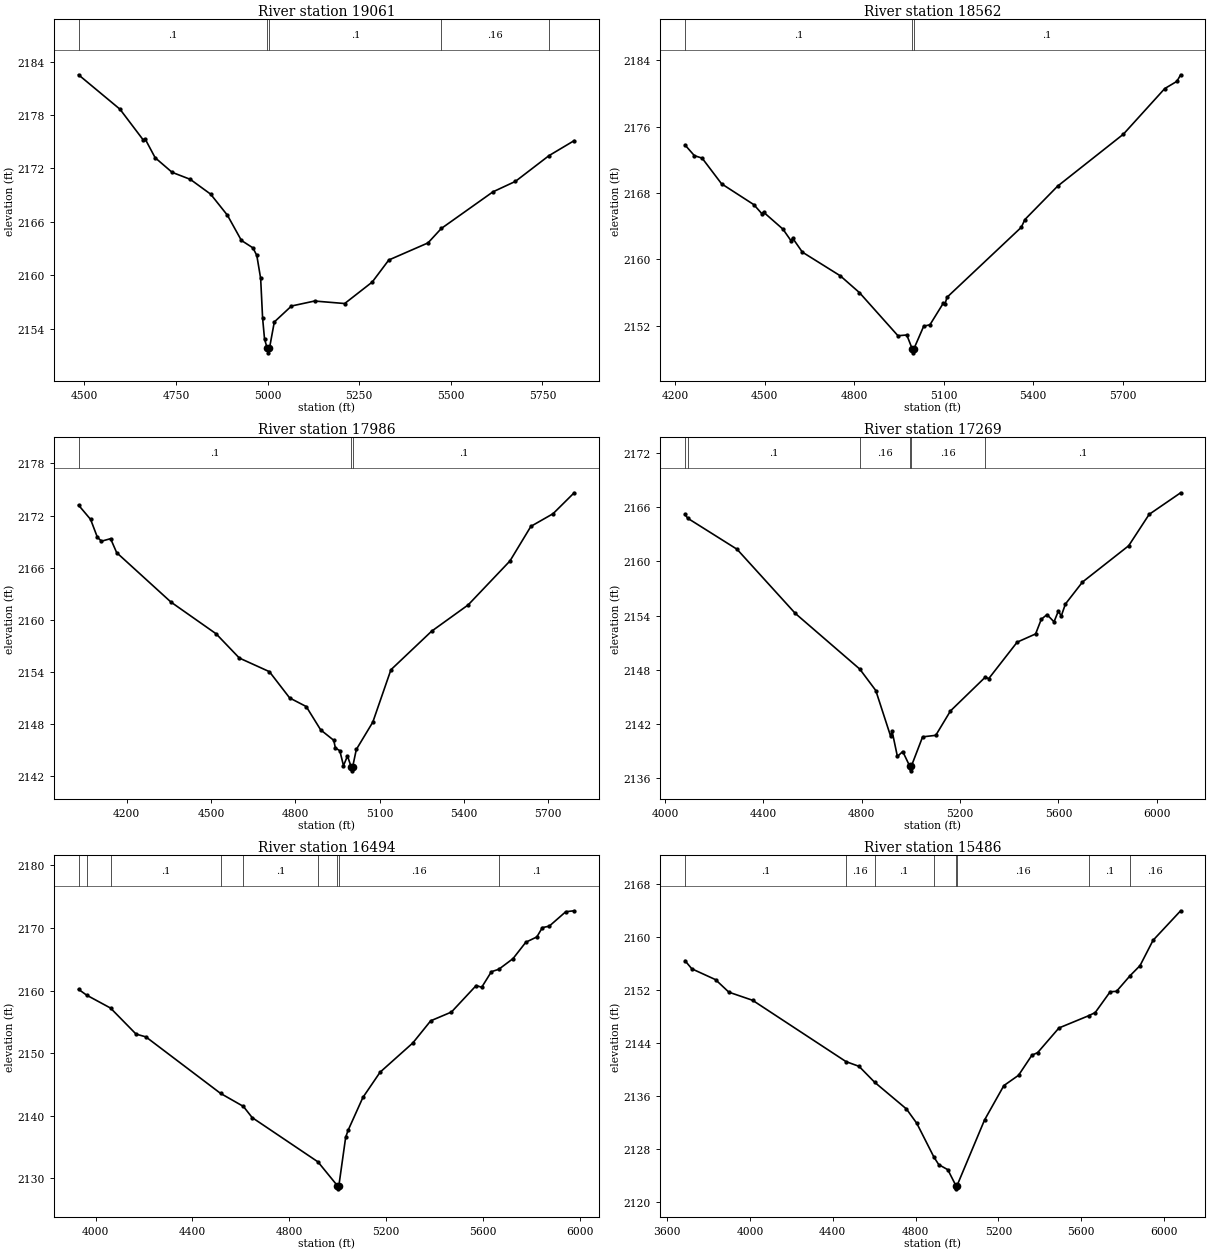
Type RM Length L Ch R = 1 ,19061   ,499,499,499
BEGIN DESCRIPTION:
UNT 1014 IN HEWA 39.0
END DESCRIPTION:
XS GIS Cut Line= 3
      2621938.17     10065376.79      2621699.45     10064638.94
      2621178.66     10064389.39
#Sta/Elev= 30
  4483.7 2182.52  4596.9 2178.65  4660.9 2175.17  4666.1 2175.27  4692.9  2173.2
  4739.2 2171.56  4788.9 2170.77  4844.3 2169.11  4890.2 2166.74  4928.3 2163.91
  4959.9 2163.07  4970.4 2162.22  4980.9 2159.64  4986.2 2155.19  4991.5 2152.83
  4998.9 2151.78  5001.7 2151.28  5004.9 2151.78  5018.2 2154.75    5065 2156.54
    5128  2157.1  5210.3 2156.82  5285.4 2159.23  5330.7 2161.71  5437.7 2163.63
    5474 2165.25  5615.1 2169.37  5676.2 2170.54  5767.8 2173.43  5836.7 2175.12
#Mann= 5 ,-1 , 0
  4483.7      .1       0  4998.9     .07       0  5004.9      .1       0
    5474     .16       0  5767.8      .1       0
Bank Sta=4998.9,5004.9
XS Rating Curve= 0 ,0
Exp/Cntr=0.3,0.1

Type RM Length L Ch R = 1 ,18562   ,576,576,576
BEGIN DESCRIPTION:
UNT 1014 IN HEWA 38.0
END DESCRIPTION:
XS GIS Cut Line= 4
      2622350.49      10065083.8      2622198.58     10064595.53
      2621797.11     10064313.42      2621178.59     10064085.54
#Sta/Elev= 30
  4233.4 2173.78  4264.9 2172.49  4290.9 2172.19    4356  2169.1  4464.1 2166.59
  4491.4 2165.49  4496.6 2165.69  4561.7 2163.64    4589 2162.23  4594.2 2162.56
  4626.8 2160.87  4753.8 2158.02  4818.2 2155.99  4947.2  2150.8  4976.8 2150.89
  4994.8 2149.24  4997.5 2148.74  5000.8 2149.24  5033.5 2151.95  5054.4 2152.12
  5098.8  2154.7  5104.9 2154.62  5111.6 2155.43  5360.6 2163.86  5372.5 2164.79
  5482.4 2168.82  5702.9 2175.08  5841.4 2180.57  5882.1 2181.44  5894.6 2182.23
#Mann= 3 ,-1 , 0
  4233.4      .1       0  4994.8     .07       0  5000.8      .1       0
Bank Sta=4994.8,5000.8
XS Rating Curve= 0 ,0
Exp/Cntr=0.3,0.1

Type RM Length L Ch R = 1 ,17986   ,717,717,717
BEGIN DESCRIPTION:
UNT 1014 IN HEWA 37.0
END DESCRIPTION:
XS GIS Cut Line= 4
      2622719.41     10064899.35      2622404.75     10064128.95
      2622144.33     10063684.08      2621753.69     10063543.01
#Sta/Elev= 30
  4029.1  2173.2  4072.1 2171.55  4096.1  2169.5  4110.8 2169.04  4143.2 2169.33
  4164.8 2167.72    4358 2162.02  4518.4 2158.37  4601.2 2155.57  4708.1    2154
  4780.2 2150.97  4839.1 2149.98  4890.5 2147.29  4936.9 2146.09  4942.8 2145.21
  4958.5 2144.89  4971.6 2143.17  4985.8 2144.28  4998.5 2143.07  5001.2 2142.57
  5004.5 2143.07  5017.2 2145.03  5075.8 2148.18  5140.3 2154.22  5284.9 2158.66
  5414.9 2161.69  5563.7 2166.76  5638.2 2170.75  5717.1 2172.21  5792.1 2174.62
#Mann= 3 ,-1 , 0
  4029.1      .1       0  4998.5     .07       0  5004.5      .1       0
Bank Sta=4998.5,5004.5
XS Rating Curve= 0 ,0
Exp/Cntr=0.3,0.1

Type RM Length L Ch R = 1 ,17269   ,775,775,775
BEGIN DESCRIPTION:
UNT 1014 IN HEWA 35.0
END DESCRIPTION:
XS GIS Cut Line= 4
      2623207.69     10064606.34      2623044.94     10063846.84
      2622903.88     10063597.27      2622035.83     10063206.65
#Sta/Elev= 30
  4081.7  2165.2  4092.9 2164.78  4293.4 2161.35  4530.3 2154.25  4792.4 2148.09
  4857.5 2145.72  4918.1 2140.64  4923.8 2141.22  4945.4 2138.42  4967.1 2138.97
  4995.9 2137.33  4998.7 2136.83  5001.9 2137.33  5047.9 2140.59  5101.4 2140.76
  5161.2 2143.46  5302.8  2147.2  5316.6 2147.03  5432.3 2151.07  5507.3 2151.98
  5530.4  2153.6  5553.6 2154.12  5582.2 2153.32  5599.9 2154.51  5611.6 2153.96
  5628.5 2155.29  5697.9 2157.72  5885.8 2161.74    5969 2165.21    6097  2167.6
#Mann= 6 ,-1 , 0
  4081.7     .16       0  4092.9      .1       0  4792.4     .16       0
  4995.9     .07       0  5001.9     .16       0  5302.8      .1       0
Bank Sta=4995.9,5001.9
XS Rating Curve= 0 ,0
Exp/Cntr=0.3,0.1

Type RM Length L Ch R = 1 ,16494   ,1008,1008,1008
BEGIN DESCRIPTION:
UNT 1014 IN HEWA 33.0
END DESCRIPTION:
XS GIS Cut Line= 4
      2623558.38     10064376.38      2623697.28     10063716.63
      2623586.17     10063119.41      2623259.79     10062424.97
#Sta/Elev= 30
  3928.9 2160.21  3962.2 2159.28  4061.2 2157.21  4166.7 2153.05  4207.5  2152.6
  4516.4 2143.56  4610.4 2141.49  4646.8  2139.7  4918.8 2132.62  4999.2 2128.81
  5001.9 2128.31  5005.2 2128.81  5033.3 2136.55  5043.4 2137.67  5104.5 2142.92
  5175.7 2146.96  5310.9 2151.63  5384.8 2155.17  5470.5 2156.57  5572.8 2160.81
  5595.6 2160.53  5635.7 2163.02  5666.4 2163.41  5725.1 2165.11    5778 2167.73
  5823.6 2168.58  5846.4 2170.07  5874.8  2170.3  5943.2 2172.61  5977.9 2172.76
#Mann= 9 ,-1 , 0
  3928.9      .1       0  3962.2     .16       0  4061.2      .1       0
  4516.4     .16       0  4610.4      .1       0  4918.8     .16       0
  4999.2     .07       0  5005.2     .16       0  5666.4      .1       0
Bank Sta=4999.2,5005.2
XS Rating Curve= 0 ,0
Exp/Cntr=0.3,0.1

Type RM Length L Ch R = 1 ,15486   ,755,755,755
BEGIN DESCRIPTION:
UNT 1014 IN HEWA 31.0
END DESCRIPTION:
XS GIS Cut Line= 3
      2623745.86     10064668.05      2624752.84     10063334.68
      2624926.44     10062633.34
#Sta/Elev= 30
  3686.6 2156.41  3719.6 2155.18    3834 2153.55  3898.6 2151.66    4013 2150.44
  4464.3  2141.2  4527.1 2140.49  4602.2  2138.1    4756 2134.07    4806 2131.91
  4888.7 2126.82  4912.2 2125.68  4955.9 2124.92  4994.5 2122.54  4997.3 2122.04
  5000.5 2122.54  5133.1 2132.41  5226.4 2137.59  5297.2 2139.14  5361.9 2142.17
  5389.4 2142.55  5492.4 2146.27  5635.6 2148.11  5667.5 2148.59  5739.7 2151.72
  5770.5 2151.79  5836.1 2154.15  5883.9 2155.66  5946.8 2159.47    6080 2163.92
#Mann= 8 ,-1 , 0
  3686.6      .1       0  4464.3     .16       0  4602.2      .1       0
  4888.7     .16       0  4994.5     .07       0  5000.5     .16       0
  5635.6      .1       0  5836.1     .16       0
Bank Sta=4994.5,5000.5
XS Rating Curve= 0 ,0
Exp/Cntr=0.3,0.1

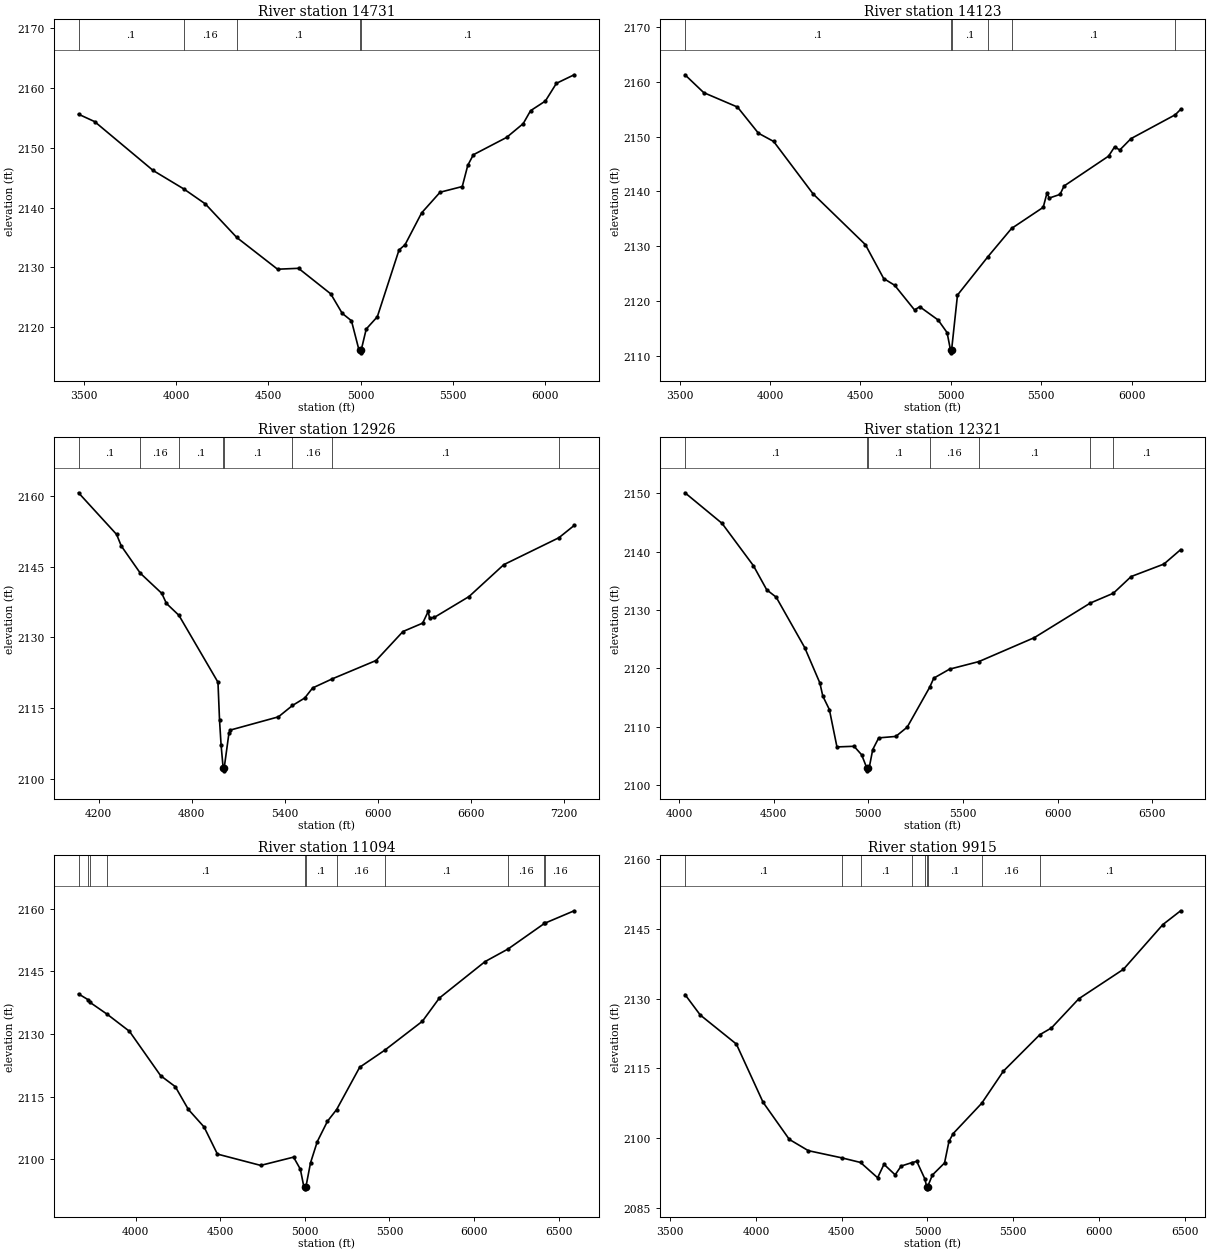
Type RM Length L Ch R = 1 ,14731   ,608,608,608
BEGIN DESCRIPTION:
UNT 1014 IN HEWA 30.0
END DESCRIPTION:
XS GIS Cut Line= 3
      2624627.85      10065279.1      2625197.28     10064022.18
       2625183.4     10062717.65
#Sta/Elev= 30
  3472.6 2155.64  3559.9  2154.4  3876.6 2146.22  4043.7 2143.11  4159.2 2140.63
  4329.8    2135  4550.7 2129.69  4664.2 2129.84  4838.8 2125.56  4900.9  2122.3
  4950.9 2121.06    4991 2116.24    4998 2116.19  5000.7 2115.69    5004 2116.19
    5031 2119.68    5091 2121.73  5208.5 2132.91    5241 2133.78    5331 2139.12
    5431 2142.58    5551 2143.53    5581 2147.09    5611 2148.85    5791 2151.75
    5881 2154.06    5921 2156.23    6001 2157.84    6061 2160.81  6157.1 2162.24
#Mann= 5 ,-1 , 0
  3472.6      .1       0  4043.7     .16       0  4329.8      .1       0
    4998     .07       0    5004      .1       0
Bank Sta=4998,5004
XS Rating Curve= 0 ,0
Exp/Cntr=0.3,0.1

Type RM Length L Ch R = 1 ,14123   ,1197,1197,1197
BEGIN DESCRIPTION:
UNT 1014 IN HEWA 29.0
END DESCRIPTION:
XS GIS Cut Line= 4
      2625405.61      10065487.5        2625607.     10064293.02
      2625891.73     10063848.57      2625642.03     10062877.53
#Sta/Elev= 30
  3529.3 2161.23  3633.1 2157.98  3819.7 2155.36  3935.6  2150.6  4019.9  2149.1
  4238.1 2139.56    4527 2130.34  4628.4 2124.17  4689.2 2122.94  4799.2 2118.45
  4827.8 2119.04  4929.8 2116.62  4979.2 2114.33  4998.1 2111.15  5000.8 2110.65
  5004.1 2111.15  5036.7 2121.16  5205.6 2128.16  5335.6 2133.27    5511 2137.12
  5531.6  2139.7  5544.8 2138.81  5603.9 2139.47  5626.3    2141  5872.3 2146.43
  5906.2 2148.13  5934.3 2147.54  5996.2 2149.61  6241.6 2153.96  6271.1 2154.94
#Mann= 6 ,-1 , 0
  3529.3      .1       0  4998.1     .07       0  5004.1      .1       0
  5205.6     .16       0  5335.6      .1       0  6241.6     .16       0
Bank Sta=4998.1,5004.1
XS Rating Curve= 0 ,0
Exp/Cntr=0.3,0.1

Type RM Length L Ch R = 1 ,12926   ,605,605,605
BEGIN DESCRIPTION:
UNT 1014 IN HEWA 26.0
END DESCRIPTION:
XS GIS Cut Line= 4
      2626572.28      10065758.3      2626620.89     10065154.13
      2626530.61     10064362.46      2625732.84     10062759.98
#Sta/Elev= 30
  4071.2 2160.62  4316.6  2151.8  4346.7 2149.36  4469.9 2143.57  4607.5 2139.33
  4637.6 2137.19  4718.1 2134.67  4969.6 2120.51  4979.7 2112.44  4989.7 2107.21
  5003.2 2102.25    5006 2101.75  5009.2 2102.25  5040.1 2109.68  5050.1 2110.39
  5358.9 2113.18  5449.7 2115.59  5528.6 2117.17  5579.4  2119.3    5707 2121.24
    5988 2125.11  6161.5 2131.25  6288.2 2133.02  6323.8 2135.49  6332.8 2134.08
    6363 2134.23  6586.9 2138.65  6810.8  2145.4  7165.7  2151.1  7264.2  2153.7
#Mann= 8 ,-1 , 0
  4071.2      .1       0  4469.9     .16       0  4718.1      .1       0
  5003.2     .07       0  5009.2      .1       0  5449.7     .16       0
    5707      .1       0  7165.7     .16       0
Bank Sta=5003.2,5009.2
XS Rating Curve= 0 ,0
Exp/Cntr=0.3,0.1

Type RM Length L Ch R = 1 ,12321   ,1227,1227,1227
BEGIN DESCRIPTION:
UNT 1014 IN HEWA 25.0
END DESCRIPTION:
XS GIS Cut Line= 3
      2627218.12     10065654.18      2627100.06     10064084.68
       2627169.5     10063043.02
#Sta/Elev= 30
  4031.5 2150.07  4227.2 2144.83    4393 2137.57  4463.2 2133.44  4513.3 2132.17
  4663.7 2123.54    4744 2117.46  4759.5 2115.21  4794.1 2112.91  4834.2  2106.5
  4924.5 2106.61  4964.6 2105.15  4991.7  2102.9  4994.4  2102.4  4997.7  2102.9
  5004.7 2102.97  5023.2 2106.05  5054.8 2108.05  5145.1  2108.3  5205.3 2109.89
  5323.8 2116.72  5345.6 2118.29  5428.8 2119.83  5583.8 2121.13    5877 2125.24
  6172.7 2131.17  6294.2 2132.85  6388.1 2135.71  6561.1 2137.85  6649.4 2140.32
#Mann= 7 ,-1 , 0
  4031.5      .1       0  4991.7     .07       0  4997.7      .1       0
  5323.8     .16       0  5583.8      .1       0  6172.7     .16       0
  6294.2      .1       0
Bank Sta=4991.7,4997.7
XS Rating Curve= 0 ,0
Exp/Cntr=0.3,0.1

Type RM Length L Ch R = 1 ,11094   ,1179,1179,1179
BEGIN DESCRIPTION:
UNT 1014 IN HEWA 22.0
END DESCRIPTION:
XS GIS Cut Line= 3
      2627655.62       10065793.      2628322.28     10064945.79
      2628426.44     10063098.68
#Sta/Elev= 30
  3663.3 2139.62  3720.5 2138.22  3731.4 2137.59  3833.4 2134.73  3964.2 2130.67
  4148.6 2120.04    4235 2117.42  4312.2 2111.97  4405.2 2107.76  4483.8 2101.28
  4739.5 2098.57  4933.7 2100.55  4973.8 2097.66  4993.8  2093.6  5000.8 2093.46
  5003.6 2092.96  5006.8 2093.46  5033.9 2099.18  5073.9 2104.27    5134 2109.14
  5188.1 2111.94  5324.3 2122.06  5472.9 2126.16  5694.9 2133.08  5795.1 2138.63
  6065.5 2147.37  6200.8 2150.37  6415.2 2156.48  6420.8 2156.59  6591.4 2159.52
#Mann= 11 ,-1 , 0
  3663.3     .16       0  3720.5      .1       0  3731.4     .16       0
  3833.4      .1       0  5000.8     .07       0  5006.8      .1       0
  5188.1     .16       0  5472.9      .1       0  6200.8     .16       0
  6415.2      .1       0  6420.8     .16       0
Bank Sta=5000.8,5006.8
XS Rating Curve= 0 ,0
Exp/Cntr=0.3,0.1

Type RM Length L Ch R = 1 ,9915    ,1413,1413,1413
BEGIN DESCRIPTION:
UNT 1014 IN HEWA 19.0
END DESCRIPTION:
XS GIS Cut Line= 4
      2627919.46     10065834.71      2628995.89     10065223.57
      2629551.45     10065140.24      2630641.77     10065126.35
#Sta/Elev= 30
  3586.1 2130.86  3675.2 2126.46  3885.7 2120.23  4041.5 2107.73  4194.4 2099.77
  4305.4 2097.35  4501.6  2095.8  4609.6 2094.82  4709.2 2091.54  4746.4 2094.42
  4811.5 2092.17  4846.7 2094.05  4909.2 2094.79  4937.7 2095.05  4984.1 2091.35
  4995.4 2089.66  4998.2 2089.16  5001.4 2089.66  5028.8 2092.13  5099.5 2094.71
  5125.5 2099.37  5150.1 2101.03  5316.4 2107.53  5442.7 2114.42    5655 2122.24
  5722.7 2123.68  5882.7 2129.96  6142.8 2136.28  6372.8 2145.88  6476.1 2148.83
#Mann= 9 ,-1 , 0
  3586.1      .1       0  4501.6     .05       0  4609.6      .1       0
  4909.2     .16       0  4984.1      .1       0  4995.4     .07       0
  5001.4      .1       0  5316.4     .16       0    5655      .1       0
Bank Sta=4995.4,5001.4
XS Rating Curve= 0 ,0
Exp/Cntr=0.3,0.1

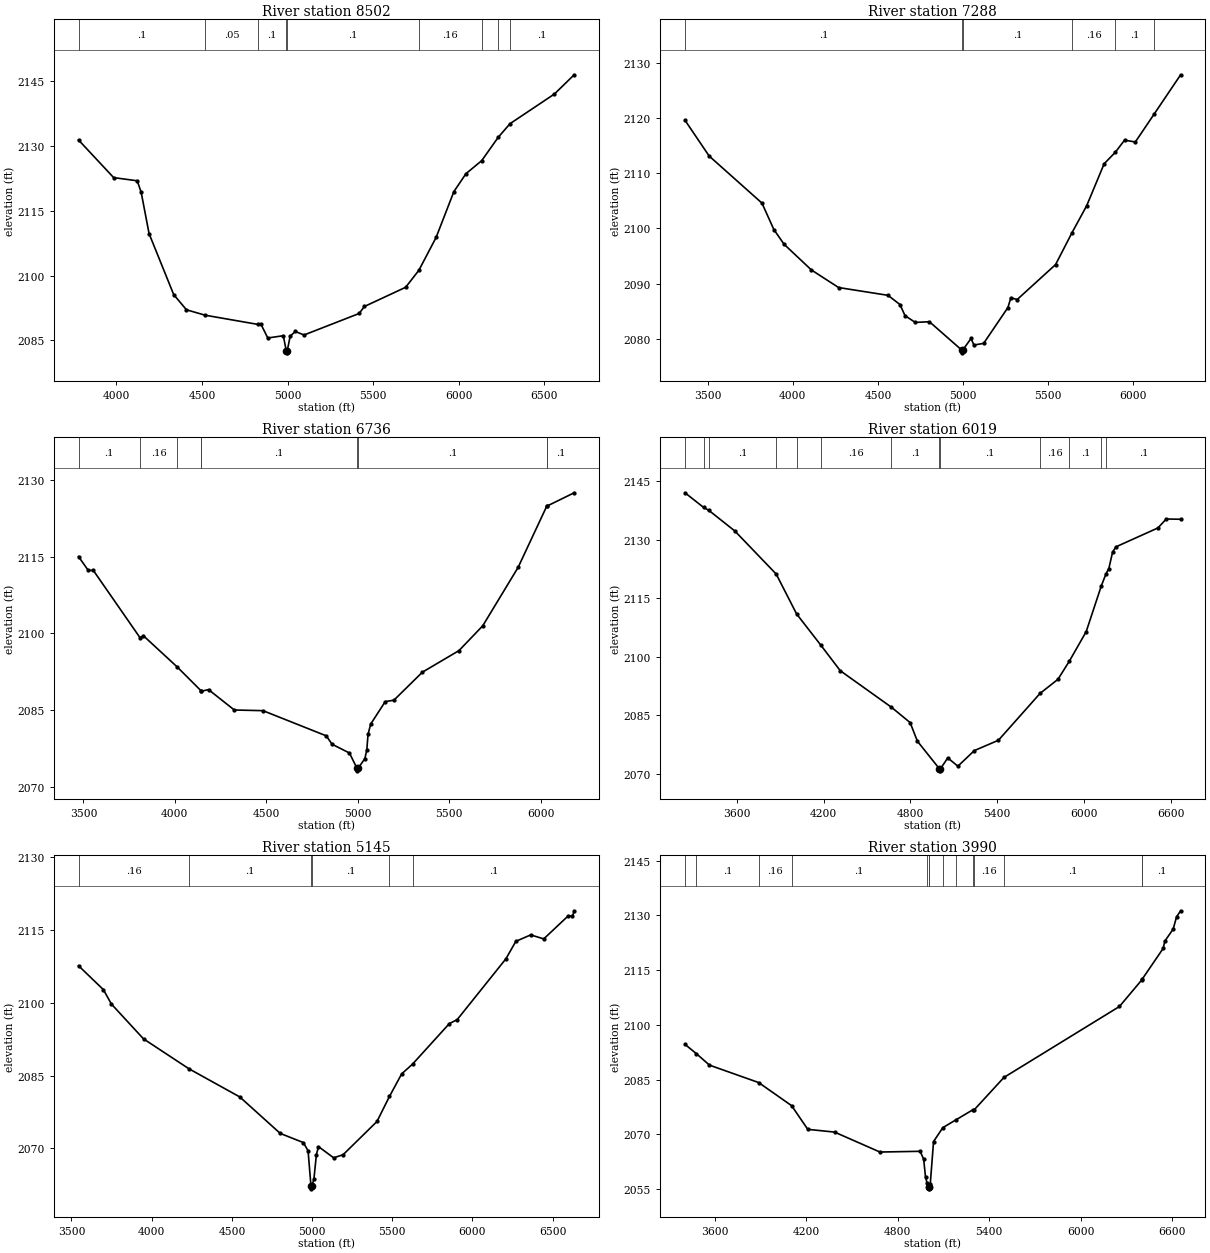
Type RM Length L Ch R = 1 ,8502    ,1214,1214,1214
BEGIN DESCRIPTION:
UNT 1014 IN HEWA 16.0
END DESCRIPTION:
XS GIS Cut Line= 4
      2627891.76     10065936.26      2628777.14     10066339.89
      2629454.23     10066418.02      2630639.08     10066053.45
#Sta/Elev= 30
  3779.5  2131.4  3984.7 2122.69  4122.5 2121.95  4145.6 2119.25  4191.6 2109.72
  4335.4  2095.6    4410 2092.09    4519 2090.84  4827.4 2088.71  4844.5 2088.78
  4884.7 2085.57  4975.3 2086.09  4992.5 2082.63  4995.2 2082.13  4998.5 2082.63
  5015.6 2086.01  5045.8 2087.07  5096.3 2086.26  5418.3 2091.24    5449 2092.86
  5689.7  2097.3  5766.9 2101.23  5867.5 2108.83  5971.3 2119.44    6042  2123.6
  6133.8 2126.61  6230.9 2132.05  6299.6 2135.18  6558.6 2142.04  6673.8 2146.49
#Mann= 9 ,-1 , 0
  3779.5      .1       0    4519     .05       0  4827.4      .1       0
  4992.5     .07       0  4998.5      .1       0  5766.9     .16       0
  6133.8      .1       0  6230.9     .16       0  6299.6      .1       0
Bank Sta=4992.5,4998.5
XS Rating Curve= 0 ,0
Exp/Cntr=0.3,0.1

Type RM Length L Ch R = 1 ,7288    ,552,552,552
BEGIN DESCRIPTION:
UNT 1014 IN HEWA 13.0
END DESCRIPTION:
XS GIS Cut Line= 3
       2627826.6     10067290.41      2629258.91      10067342.5
      2630598.71     10066718.13
#Sta/Elev= 30
  3366.4 2119.59  3508.4 2113.11  3818.6 2104.58  3888.6 2099.78  3948.7 2097.12
  4108.8 2092.47  4268.9 2089.28  4559.1 2087.87  4629.1  2086.2  4659.1 2084.18
  4719.2 2082.96  4802.2 2083.09  4992.1 2077.95  4994.9 2077.45  4998.1 2077.95
  5046.4 2080.05  5063.7 2078.87  5120.5 2079.16  5263.2 2085.65  5280.6 2087.43
  5317.7 2087.11  5543.2 2093.44  5640.3 2099.25  5725.9  2104.1  5828.6 2111.71
  5893.3 2113.76  5948.5 2115.99  6011.6 2115.65  6122.9 2120.74  6277.8 2127.83
#Mann= 6 ,-1 , 0
  3366.4      .1       0  4992.1     .07       0  4998.1      .1       0
  5640.3     .16       0  5893.3      .1       0  6122.9     .16       0
Bank Sta=4992.1,4998.1
XS Rating Curve= 0 ,0
Exp/Cntr=0.3,0.1

Type RM Length L Ch R = 1 ,6736    ,717,717,717
BEGIN DESCRIPTION:
UNT 1014 IN HEWA 12.0
END DESCRIPTION:
XS GIS Cut Line= 4
      2628047.93     10067941.47      2629154.75     10067628.95
      2629805.79     10067850.31      2630678.16     10067863.33
#Sta/Elev= 30
  3473.3    2115  3525.8 2112.33  3554.4 2112.29  3810.1 2099.14  3827.1 2099.58
  4013.2 2093.45  4142.1 2088.85  4144.3 2088.71  4184.1 2089.04  4325.3 2085.06
    4482 2084.93    4828 2080.02  4859.7 2078.38  4954.7 2076.67  4995.9 2073.69
  4998.6 2073.19  5001.9 2073.69  5039.2 2075.58  5049.8  2077.3  5056.3 2080.29
  5070.9 2082.32  5150.5  2086.7  5197.7 2086.97  5353.7 2092.44  5553.7 2096.65
  5683.7 2101.49  5877.1 2112.89  6033.4 2124.81  6033.6 2124.82  6183.5 2127.44
#Mann= 9 ,-1 , 0
  3473.3      .1       0  3810.1     .16       0  4013.2      .1       0
  4142.1     .16       0  4144.3      .1       0  4995.9     .07       0
  5001.9      .1       0  6033.4     .16       0  6033.6      .1       0
Bank Sta=4995.9,5001.9
XS Rating Curve= 0 ,0
Exp/Cntr=0.3,0.1

Type RM Length L Ch R = 1 ,6019    ,874,874,874
BEGIN DESCRIPTION:
UNT 1014 IN HEWA 11.0
END DESCRIPTION:
XS GIS Cut Line= 4
      2627514.15     10068306.04      2629076.62     10068397.18
       2629688.6     10068371.14      2630871.68     10067968.12
#Sta/Elev= 30
  3240.9 2142.01  3369.7 2138.26  3405.4 2137.52  3585.8 2132.22  3871.6  2121.2
    4013 2110.97  4180.1    2103  4314.7 2096.45  4668.8 2087.09  4797.9 2083.16
  4847.9 2078.41  5000.9 2071.31  5003.7 2070.81  5006.9 2071.31  5058.1 2074.12
  5128.2    2072  5241.7 2075.99  5408.4 2078.64  5696.1 2090.63  5819.9 2094.24
  5899.1 2098.91  6015.3 2106.45  6119.5 2118.13  6152.4 2121.27    6172 2122.62
  6198.1 2126.86  6221.3 2128.17  6511.6 2133.01  6569.1  2135.3  6668.4 2135.23
#Mann= 13 ,-1 , 0
  3240.9      .1       0  3369.7     .16       0  3405.4      .1       0
  3871.6     .16       0    4013      .1       0  4180.1     .16       0
  4668.8      .1       0  5000.9     .07       0  5006.9      .1       0
  5696.1     .16       0  5899.1      .1       0  6119.5     .16       0
  6152.4      .1       0
Bank Sta=5000.9,5006.9
XS Rating Curve= 0 ,0
Exp/Cntr=0.3,0.1

Type RM Length L Ch R = 1 ,5145    ,1155,1155,1155
BEGIN DESCRIPTION:
UNT 1014 IN HEWA 9.0
END DESCRIPTION:
XS GIS Cut Line= 4
      2628243.33     10069269.58      2629402.14      10069282.6
      2630092.25     10068852.91      2631145.17     10068475.94
#Sta/Elev= 30
  3543.8 2107.63  3698.9  2102.7  3748.9 2099.73    3949 2092.56  4232.1  2086.4
    4549  2080.6  4801.5 2073.08  4945.7 2071.19    4975  2069.5  4993.3 2062.16
    4996 2061.66  4999.3 2062.16  5011.6 2063.74    5027 2068.73    5040 2070.36
  5134.2 2068.06  5193.1 2068.68  5404.6 2075.54  5482.5  2080.7  5558.6 2085.35
  5626.2 2087.35  5855.6  2095.7  5904.6 2096.52  6208.8 2109.07  6270.4 2112.65
  6362.7 2113.98  6444.4 2113.16  6598.2 2117.94  6623.6  2117.8    6634 2118.95
#Mann= 6 ,-1 , 0
  3543.8     .16       0  4232.1      .1       0  4993.3     .07       0
  4999.3      .1       0  5482.5     .16       0  5626.2      .1       0
Bank Sta=4993.3,4999.3
XS Rating Curve= 0 ,0
Exp/Cntr=0.3,0.1

Type RM Length L Ch R = 1 ,3990    ,1293,1293,1293
BEGIN DESCRIPTION:
UNT 1014 IN HEWA 8.0
END DESCRIPTION:
XS GIS Cut Line= 4
      2628568.84     10069946.66      2629857.87     10069790.41
      2630391.73     10070102.91      2631602.69       10069543.
#Sta/Elev= 30
    3405 2094.67  3480.1 2092.11  3565.8 2088.97  3888.1  2084.2  4104.5 2077.86
  4210.5 2071.37  4385.9 2070.62  4683.9 2065.15  4947.5 2065.35  4970.7 2063.18
  4982.7 2058.29  4992.4 2056.76  5002.4 2055.56  5005.2 2055.06  5008.4 2055.56
    5014 2056.42  5035.5 2068.03  5096.3 2071.83  5179.7 2073.91  5291.2 2076.68
  5300.1 2076.63  5497.2  2085.6  6254.9 2105.05  6401.1 2112.32  6404.9 2112.59
  6541.4 2120.96  6552.6 2122.97  6607.5 2126.29  6629.5 2129.64  6656.2 2131.29
#Mann= 14 ,-1 , 0
    3405     .16       0  3480.1      .1       0  3888.1     .16       0
  4104.5      .1       0  4992.4     .16       0  5002.4     .07       0
  5008.4     .16       0  5096.3      .1       0  5179.7     .16       0
  5291.2      .1       0  5300.1     .16       0  5497.2      .1       0
  6401.1     .05       0  6404.9      .1       0
Bank Sta=5002.4,5008.4
XS Rating Curve= 0 ,0
Exp/Cntr=0.3,0.1

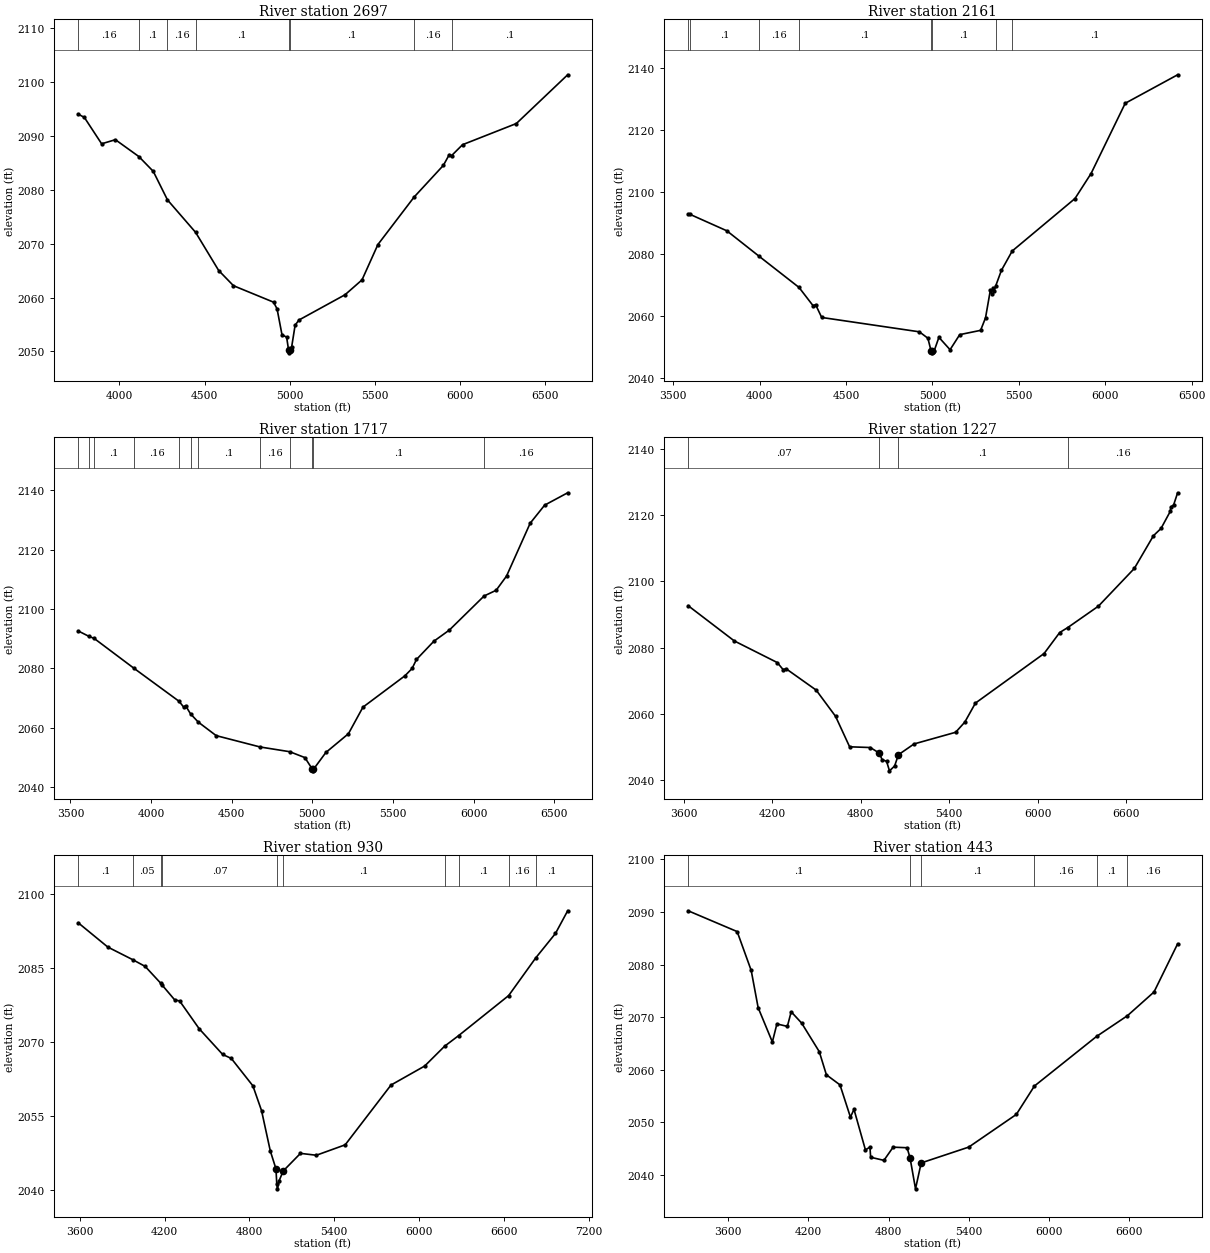
Type RM Length L Ch R = 1 ,2697    ,536,536,536
BEGIN DESCRIPTION:
UNT 1014 IN HEWA 6.0
END DESCRIPTION:
XS GIS Cut Line= 4
      2628972.49     10071196.66      2629909.95     10071053.43
      2630404.75     10070402.39      2631433.39     10069985.72
#Sta/Elev= 30
  3757.5 2094.02  3793.9 2093.39  3895.1 2088.51    3976 2089.27  4113.6 2086.15
  4198.5  2083.4  4282.1  2078.1  4447.4 2072.08  4582.9 2065.01  4669.8 2062.19
  4905.1 2059.14  4925.9  2057.9    4955 2053.07  4982.1 2052.66  4993.6 2050.24
  4996.4 2049.74  4999.6 2050.24  5011.2 2050.74    5032 2054.88  5054.8 2055.83
  5325.2 2060.51    5425 2063.27  5518.5 2069.83    5731 2078.63    5903 2084.51
  5937.9 2086.51  5951.7 2086.33  6015.6 2088.34  6331.9 2092.27  6633.4 2101.31
#Mann= 8 ,-1 , 0
  3757.5     .16       0  4113.6      .1       0  4282.1     .16       0
  4447.4      .1       0  4993.6     .07       0  4999.6      .1       0
    5731     .16       0  5951.7      .1       0
Bank Sta=4993.6,4999.6
XS Rating Curve= 0 ,0
Exp/Cntr=0.3,0.1

Type RM Length L Ch R = 1 ,2161    ,444,444,444
BEGIN DESCRIPTION:
UNT 1014 IN HEWA 5.0
END DESCRIPTION:
XS GIS Cut Line= 4
      2629167.77     10071365.93      2630339.64     10071274.79
      2630912.56       10070780.      2631810.99      10070845.1
#Sta/Elev= 30
  3585.7 2093.06  3596.5 2092.93  3809.8 2087.62  3997.4 2079.37  4227.5 2069.36
  4308.6 2063.48  4323.5  2063.8  4358.7 2059.68    4924 2055.05  4973.4 2052.98
  4992.3 2048.77  4995.1 2048.27  4998.3 2048.77  5009.6 2048.89  5037.1 2053.27
  5101.7 2049.28  5157.7 2054.14  5278.4 2055.52  5306.9 2059.54  5335.4 2068.63
    5342 2067.39  5349.6  2069.3  5356.3 2068.32  5365.5 2069.79    5399 2074.88
  5461.5 2081.11  5824.8 2098.03  5917.9  2106.1  6115.6 2128.75  6418.9 2137.94
#Mann= 8 ,-1 , 0
  3585.7     .16       0  3596.5      .1       0  3997.4     .16       0
  4227.5      .1       0  4992.3     .07       0  4998.3      .1       0
  5365.5     .16       0  5461.5      .1       0
Bank Sta=4992.3,4998.3
XS Rating Curve= 0 ,0
Exp/Cntr=0.3,0.1

Type RM Length L Ch R = 1 ,1717    ,490,490,490
BEGIN DESCRIPTION:
UNT 1014 IN HEWA 4.0
END DESCRIPTION:
XS GIS Cut Line= 3
      2629232.85     10071509.16      2631303.18     10071496.14
      2632201.58      10071144.6
#Sta/Elev= 30
  3548.3  2092.6  3613.3 2090.82  3647.5 2090.07  3894.1 2080.02  4173.9 2068.89
  4203.9 2066.83  4213.9 2067.43  4244.8 2064.67  4292.8 2061.89  4403.9 2057.33
  4676.9  2053.5  4860.4 2051.91  4953.9 2049.93  5000.9 2045.97  5003.7 2045.47
  5006.9 2045.97  5083.9 2051.65  5223.9 2057.97  5313.9 2066.92    5574 2077.48
  5618.7 2079.96  5645.8 2082.99  5753.7 2089.14  5849.8  2092.9  6065.2 2104.38
  6139.8  2106.3  6204.2 2111.08  6350.8 2128.89  6440.5 2134.98  6583.4 2139.15
#Mann= 12 ,-1 , 0
  3548.3      .1       0  3613.3     .16       0  3647.5      .1       0
  3894.1     .16       0  4173.9      .1       0  4244.8     .05       0
  4292.8      .1       0  4676.9     .16       0  4860.4      .1       0
  5000.9     .07       0  5006.9      .1       0  6065.2     .16       0
Bank Sta=5000.9,5006.9
XS Rating Curve= 0 ,0
Exp/Cntr=0.3,0.1

Type RM Length L Ch R = 1 ,1227    ,297,297,297
BEGIN DESCRIPTION:
UNT 1014 IN HEWA 2.0
END DESCRIPTION:
XS GIS Cut Line= 3
      2629245.92     10071873.75      2630977.66     10072003.95
      2632474.28     10071483.39
#Sta/Elev= 30
  3629.2  2092.7  3942.6 2082.06  4233.8 2075.55  4273.6 2073.42  4293.6 2073.68
  4497.6 2067.25  4629.4 2059.33  4724.8 2050.14  4865.2 2049.92  4925.4 2048.26
  4945.5 2046.25  4975.5 2045.77  4995.3 2042.89  5030.1 2044.34  5055.8 2047.74
  5161.9    2051  5444.3 2054.52  5506.6  2057.6  5578.4 2063.32  6044.3 2078.27
  6150.2  2084.6  6205.2 2086.11  6413.1 2092.56  6656.6 2103.93  6786.3  2113.8
  6837.9    2116  6900.1 2121.11  6905.4 2122.51  6923.1 2123.06  6950.4 2126.75
#Mann= 4 ,-1 , 0
  3629.2     .07       0  4925.4     .05       0  5055.8      .1       0
  6205.2     .16       0
Bank Sta=4925.4,5055.8
XS Rating Curve= 0 ,0
Exp/Cntr=0.3,0.1

Type RM Length L Ch R = 1 ,930     ,487,487,487
BEGIN DESCRIPTION:
Mapping XS ac86a5e0
END DESCRIPTION:
XS GIS Cut Line= 4
      2629202.08     10072130.03      2630306.27     10072324.48
      2631243.77     10072136.98      2632624.61      10072032.9
#Sta/Elev= 30
  3589.1 2094.11  3798.7 2089.19  3974.1 2086.65  4062.7 2085.28  4172.9 2081.87
  4182.5 2081.51  4272.2 2078.48  4306.4 2078.29    4445 2072.65    4611 2067.45
  4671.9 2066.65  4824.7  2061.1  4885.9 2056.08  4947.9 2047.91  4987.9 2044.29
  4993.7 2041.15  4998.6 2040.25  5008.3 2041.76  5038.9 2043.86  5161.2 2047.43
  5273.4 2047.05  5477.4 2049.16  5801.4 2061.26  6039.6 2065.11  6180.6 2069.12
  6279.9 2071.27  6633.8 2079.38  6824.9 2086.99  6964.7 2091.95  7051.1 2096.54
#Mann= 10 ,-1 , 0
  3589.1      .1       0  3974.1     .05       0  4172.9      .1       0
  4182.5     .07       0  4993.7     .05       0  5038.9      .1       0
  6180.6     .16       0  6279.9      .1       0  6633.8     .16       0
  6824.9      .1       0
Bank Sta=4987.9,5038.9
XS Rating Curve= 0 ,0
Exp/Cntr=0.3,0.1

Type RM Length L Ch R = 1 ,443     ,0,0,0
BEGIN DESCRIPTION:
UNT 1014 IN HEWA 1.0
END DESCRIPTION:
XS GIS Cut Line= 4
      2629264.58     10072317.53      2630660.44     10072713.37
      2631542.38      10072421.7       2632825.3      10072400.9
#Sta/Elev= 30
  3300.3 2090.23  3667.1 2086.27  3772.1 2078.88  3824.1 2071.79  3930.5 2065.26
  3964.4  2068.7  4042.7 2068.23  4071.4 2071.01  4149.6 2068.86  4281.4 2063.43
  4334.8 2059.02  4436.5  2057.1  4514.8 2050.96  4541.3 2052.44  4626.9 2044.73
  4660.8 2045.27    4666 2043.33  4765.4 2042.74  4834.2 2045.25  4938.7 2045.14
    4961 2043.19  5001.7 2037.32    5044 2042.25  5399.9 2045.26  5756.2 2051.48
  5891.4 2056.88  6356.5 2066.32  6587.8 2070.27  6786.3 2074.77  6963.2 2083.94
#Mann= 6 ,-1 , 0
  3300.3      .1       0    4961     .05       0    5044      .1       0
  5891.4     .16       0  6356.5      .1       0  6587.8     .16       0
Bank Sta=4961,5044
XS Rating Curve= 0 ,0
Exp/Cntr=0.3,0.1

Chan Stop Cuts=-1
Use User Specified Reach Order=0
Composite Channel Slope=5