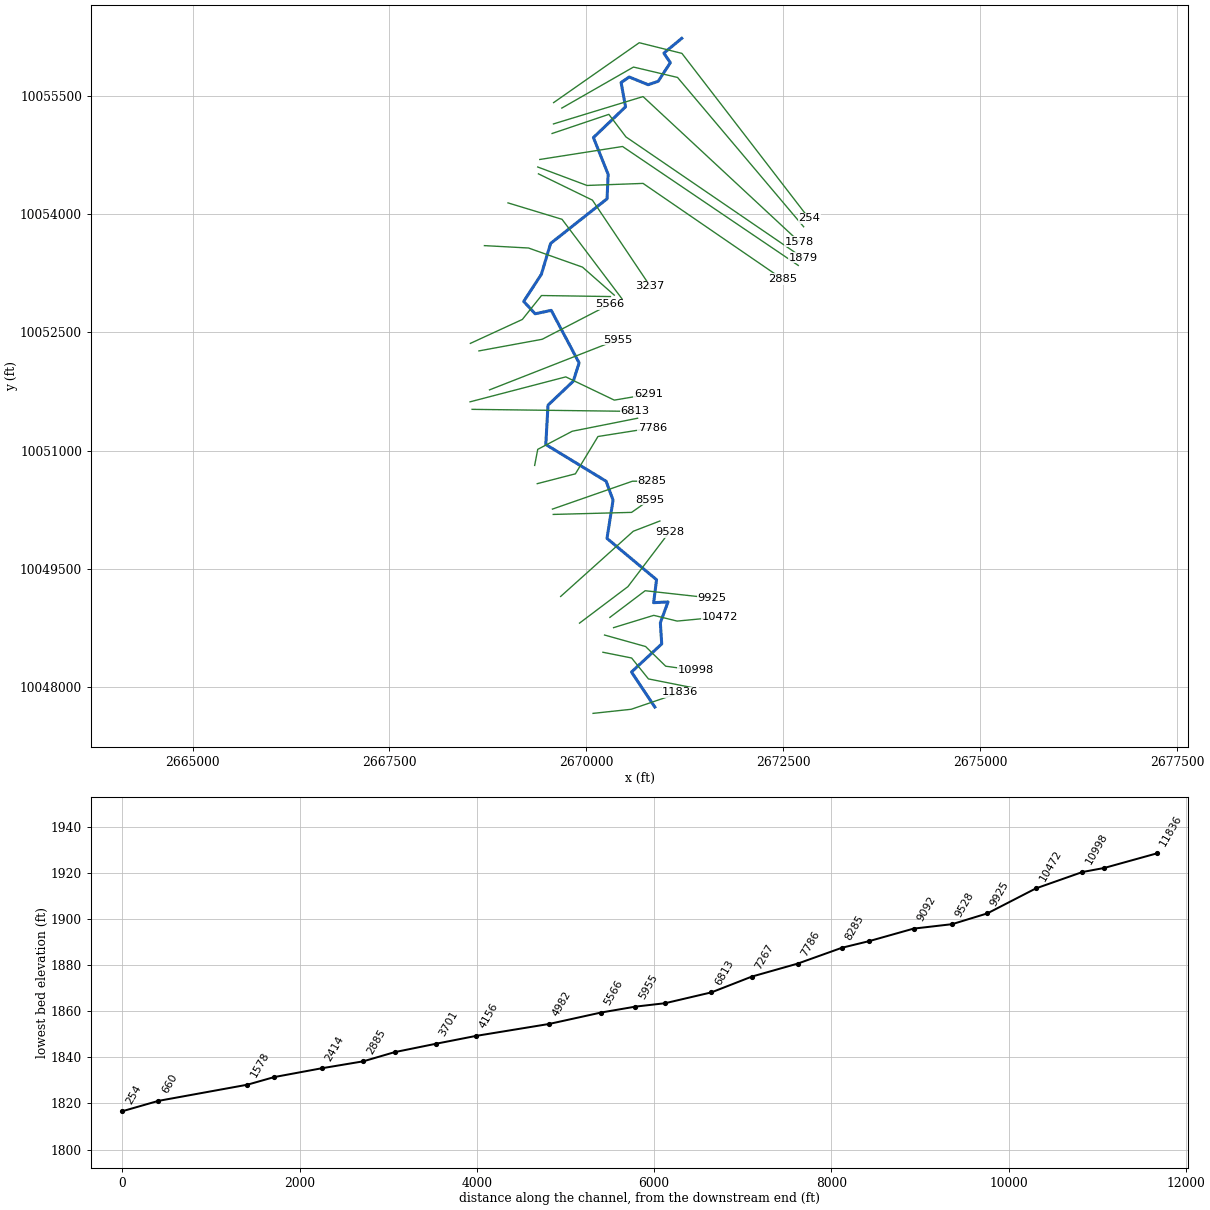
--- UNT 1015 IN HEWA.prj (project) ---

Proj Title=UNT 1015 IN HEWA Base Level Engineering
Current Plan=p01
Default Exp/Contr=0.3,0.1
English Units
Geom File=g01
Flow File=f01
Plan File=p01
Y Axis Title=Elevation
X Axis Title(PF)=Main Channel Distance
X Axis Title(XS)=Station
BEGIN DESCRIPTION:
UNT 1015 IN HEWA
END DESCRIPTION:
DSS Export Rating Curves= 0
DSS Export Rating Curve Sorted= 0
DSS Export Volume Flow Curves= 0
DXF OffsetX= 0
DXF OffsetY= 0
DXF ScaleX= 1
DXF ScaleY= 10

--- UNT 1015 IN HEWA.p01 (plan) ---

Plan Title=Multiple Run
Short Identifier=Multiple
Geom File=g01
Flow File=f01
Subcritical Flow
K Sum by GR= 0
Std Step Tol= 0.01
Critical Tol= 0.01
Num of Std Step Trials= 20
Max Error Tol= 0.3
Flow Tol Ratio= 0.001
Split Flow NTrial= 30
Split Flow Tol= 0.02
Split Flow Ratio= 0.02
Log Output Level= 0
Friction Slope Method= 1
Unsteady Friction Slope Method= 2
Unsteady Bridges Friction Slope Method= 1
Parabolic Critical Depth
Global Vel Dist=  1 , 1 , 1
Global Log Level= 0
CheckData=True
Encroach Param= -1, 0, 0, 0
BEGIN DESCRIPTION:
Multiple Run
END DESCRIPTION:

--- UNT 1015 IN HEWA.f01 (steady flow) ---

Flow Title=Multiple
Program Version=4.10
Number of Profiles= 7
Profile Names=10-year,25-year,50-year,1pct_min,100-year,1pct_plu,500-year
River Rch & RM=UNT 1015 IN HEWA,Reach-1         ,11836
    1225    1797    2295    2138    2891    3910    4585
River Rch & RM=UNT 1015 IN HEWA,Reach-1         ,9925
    2094    3159    4111    3893    5265    7120    8640
River Rch & RM=UNT 1015 IN HEWA,Reach-1         ,6813
    2300    3468    4510    4265    5768    7800    9439
Boundary for River Rch & Prof#=UNT 1015 IN HEWA,Reach-1         , 1
Up Type= 0
Dn Type= 3
Dn Slope=0.006
Boundary for River Rch & Prof#=UNT 1015 IN HEWA,Reach-1         , 2
Up Type= 0
Dn Type= 3
Dn Slope=0.006
Boundary for River Rch & Prof#=UNT 1015 IN HEWA,Reach-1         , 3
Up Type= 0
Dn Type= 3
Dn Slope=0.006
Boundary for River Rch & Prof#=UNT 1015 IN HEWA,Reach-1         , 4
Up Type= 0
Dn Type= 3
Dn Slope=0.006
Boundary for River Rch & Prof#=UNT 1015 IN HEWA,Reach-1         , 5
Up Type= 0
Dn Type= 3
Dn Slope=0.006
Boundary for River Rch & Prof#=UNT 1015 IN HEWA,Reach-1         , 6
Up Type= 0
Dn Type= 3
Dn Slope=0.006
Boundary for River Rch & Prof#=UNT 1015 IN HEWA,Reach-1         , 7
Up Type= 0
Dn Type= 3
Dn Slope=0.006
DSS Import GetInterval= 0
DSS Import GetPeak= 0
DSS Import FillOption= 0

--- UNT 1015 IN HEWA.g01 (geometry) ---

Geom Title=Existing Conditions
Program Version=4.10

River Reach=UNT 1015 IN HEWA,Reach-1
Reach XY= 30
      2670868.47     10047743.73      2670572.67     10048188.36
      2670956.33     10048544.66      2670938.96      10048813.4
      2671036.16     10049078.12       2670853.5     10049068.61
      2670890.64      10049360.1      2670261.58     10049885.08
      2670338.57     10050370.12      2670250.89     10050610.15
      2669484.68     10051076.88       2669512.9     10051576.61
      2669833.75     10051880.87      2669907.61     10052113.26
       2669553.8     10052780.28      2669349.68     10052736.57
      2669204.23     10052893.51      2669427.97     10053237.27
      2669546.45     10053630.33      2670262.25     10054196.73
      2670276.04     10054507.73      2670089.39     10054973.87
      2670496.95     10055364.44      2670440.78     10055672.89
      2670543.59      10055743.3      2670784.25     10055645.19
      2670911.43     10055688.36      2671065.71      10055925.1
      2670983.42     10056046.01      2671210.43     10056234.14

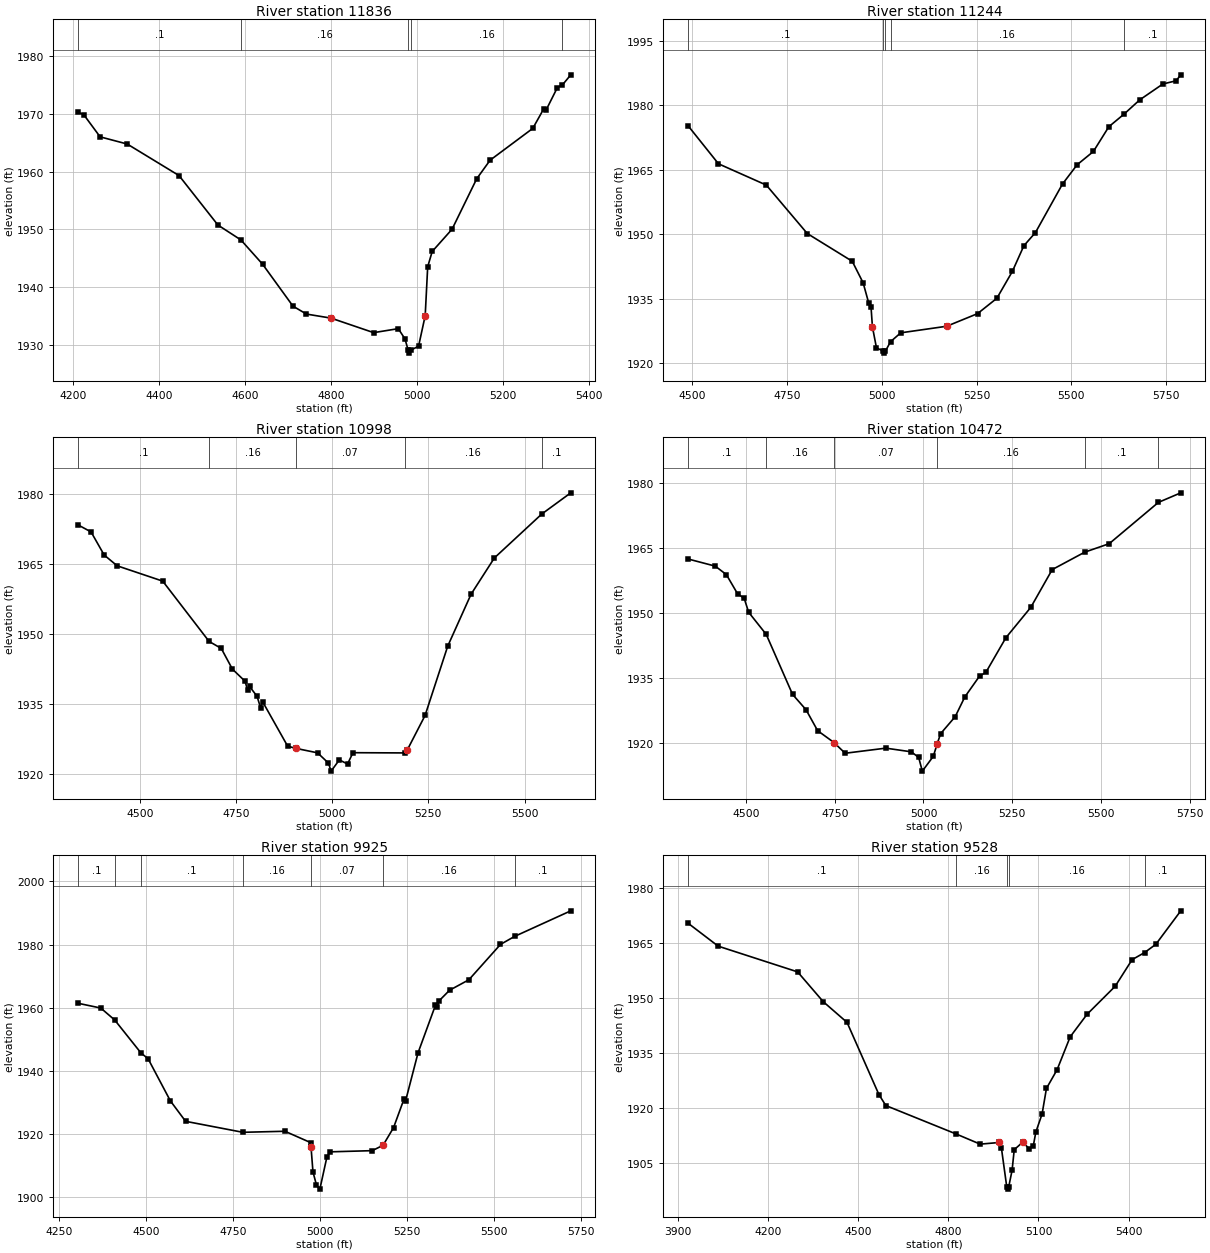
Type RM Length L Ch R = 1 ,11836   ,592,592,592
BEGIN DESCRIPTION:
UNT 1015 IN HEWA 25.0
END DESCRIPTION:
XS GIS Cut Line= 3
      2670084.67     10047662.98      2670569.08     10047715.07
      2671193.82     10047928.52
#Sta/Elev= 30
  4210.8 1970.27  4224.7 1969.76  4262.2 1965.99  4325.3 1964.75  4445.9  1959.3
  4536.5 1950.75  4590.1 1948.17  4640.4 1943.99  4711.3 1936.73  4742.6 1935.36
  4799.9 1934.66  4899.2 1932.15  4956.5 1932.84  4972.1 1931.07  4979.6 1929.11
  4982.3 1928.61  4985.6 1929.11  5003.8 1929.82  5019.2 1935.08    5025 1943.53
  5035.5 1946.18  5081.8 1950.03  5139.1 1958.74  5170.4 1961.96  5269.7 1967.45
  5295.7 1970.89    5301 1970.66    5327 1974.51  5338.8 1974.97  5358.2 1976.71
#Mann= 5 ,-1 , 0
  4210.8      .1       0  4590.1     .16       0  4979.6     .07       0
  4985.6     .16       0  5338.8      .1       0
Bank Sta=4799.9,5019.2
XS Rating Curve= 0 ,0
Exp/Cntr=0.3,0.1

Type RM Length L Ch R = 1 ,11244   ,246,246,246
BEGIN DESCRIPTION:
UNT 1015 IN HEWA 24.0
END DESCRIPTION:
XS GIS Cut Line= 4
      2670209.75     10048439.01      2670574.28     10048366.11
      2670787.83     10048100.48      2671364.73     10047986.14
#Sta/Elev= 30
  4488.4 1975.27  4568.7  1966.4    4695 1961.44  4803.2 1950.15  4921.8 1943.69
  4950.6 1938.66    4965 1934.06  4971.4 1933.05 4975.11 1928.41  4985.8  1923.5
  5003.6 1922.79  5006.4 1922.29  5009.6 1922.79  5022.9 1924.95  5049.8 1927.02
  5171.1 1928.55  5252.6 1931.49  5303.6 1935.07  5344.4 1941.31  5374.9 1947.31
  5405.5 1950.39  5476.9  1961.7  5515.6 1966.19  5558.4 1969.27  5599.2 1975.04
  5639.1 1977.96  5680.8  1981.3  5741.9    1985  5776.7 1985.74  5789.1 1987.13
#Mann= 5 ,-1 , 0
  4488.4      .1       0  5003.6     .07       0  5009.6      .1       0
  5022.9     .16       0  5639.1      .1       0
Bank Sta=4975.11,5171.1
XS Rating Curve= 0 ,0
Exp/Cntr=0.3,0.1

Type RM Length L Ch R = 1 ,10998   ,526,526,526
BEGIN DESCRIPTION:
UNT 1015 IN HEWA 23.0
END DESCRIPTION:
XS GIS Cut Line= 4
      2670230.58     10048657.76      2670751.37     10048511.94
      2671006.58     10048261.94      2671385.16     10048210.08
#Sta/Elev= 30
  4339.8 1973.29  4373.6 1971.78  4407.7 1966.83  4441.5 1964.52  4559.8 1961.24
  4680.3 1948.32  4711.9 1946.82  4740.8 1942.39  4773.8 1939.78  4780.1 1937.94
  4785.3 1938.69  4804.9 1936.55  4814.2 1934.08  4819.4  1935.4  4884.4 1925.88
  4905.5 1925.41  4962.1 1924.45  4990.4 1922.25  4997.3 1920.53  5018.7 1922.94
    5040 1922.05  5054.1 1924.48  5188.4 1924.43  5195.6 1925.13  5241.4 1932.45
  5300.3 1947.31  5360.9 1958.43  5421.5 1966.21  5544.7 1975.62    5620 1980.16
#Mann= 5 ,-1 , 0
  4339.8      .1       0  4680.3     .16       0  4905.5     .07       0
  5188.4     .16       0  5544.7      .1       0
Bank Sta=4905.5,5195.6
XS Rating Curve= 0 ,0
Exp/Cntr=0.3,0.1

Type RM Length L Ch R = 1 ,10472   ,547,547,547
BEGIN DESCRIPTION:
UNT 1015 IN HEWA 22.0
END DESCRIPTION:
XS GIS Cut Line= 4
      2670345.16     10048751.54      2670855.53     10048907.77
      2671152.41     10048834.86      2671699.28     10048886.94
#Sta/Elev= 30
  4336.4 1962.42  4413.1 1960.77  4444.4 1958.81  4475.8  1954.4  4494.6 1953.33
  4507.2 1950.11  4556.7    1945  4630.9 1931.14  4668.9 1927.59  4701.6 1922.75
  4747.7 1920.01  4779.1 1917.53  4893.8 1918.71  4965.8 1917.86  4986.4 1916.56
  4996.7  1913.4  5027.6 1916.81  5038.5 1919.67  5048.2 1922.05  5089.4 1925.99
  5116.4 1930.53    5158 1935.36  5175.9 1936.23  5232.2 1944.22  5302.5 1951.25
  5362.8 1959.97  5454.5    1964  5523.5 1965.96  5662.1  1975.5  5725.2 1977.71
#Mann= 6 ,-1 , 0
  4336.4      .1       0  4556.7     .16       0  4747.7     .07       0
  5038.5     .16       0  5454.5      .1       0  5662.1     .16       0
Bank Sta=4747.7,5038.5
XS Rating Curve= 0 ,0
Exp/Cntr=0.3,0.1

Type RM Length L Ch R = 1 ,9925    ,397,397,397
BEGIN DESCRIPTION:
UNT 1015 IN HEWA 21.0
END DESCRIPTION:
XS GIS Cut Line= 3
      2670298.23     10048881.72      2670746.16     10049220.27
      2671594.32     10049126.61
#Sta/Elev= 30
  4305.5  1961.4  4370.8 1959.89  4410.8  1956.1  4486.4 1945.64  4506.4 1943.88
  4570.6  1930.5  4614.3 1924.03  4778.7 1920.55  4899.5 1920.88  4973.5 1917.28
 4974.55 1915.77    4980 1908.05    4990 1903.89  4999.8 1902.56  5020.2 1912.79
  5030.3 1914.37  5150.2 1914.74  5181.2 1916.43  5211.4 1922.02    5241 1930.95
    5246 1930.52  5281.8 1945.73  5331.8  1960.8  5336.8  1960.2  5342.2 1962.18
  5372.3 1965.53  5427.7 1968.84  5518.5 1980.04  5559.2 1982.58  5720.3 1990.67
#Mann= 7 ,-1 , 0
  4305.5      .1       0  4410.8     .16       0  4486.4      .1       0
  4778.7     .16       0  4973.5     .07       0  5181.2     .16       0
  5559.2      .1       0
Bank Sta=4974.55,5181.2
XS Rating Curve= 0 ,0
Exp/Cntr=0.3,0.1

Type RM Length L Ch R = 1 ,9528    ,436,436,436
BEGIN DESCRIPTION:
UNT 1015 IN HEWA 20.0
END DESCRIPTION:
XS GIS Cut Line= 3
      2669912.86     10048808.84      2670527.41     10049272.36
      2671053.47      10049965.1
#Sta/Elev= 30
    3934  1970.3  4034.2 1964.05  4298.6 1957.04  4383.9 1948.92    4463 1943.29
  4569.2 1923.62  4592.1 1920.64    4826  1912.9  4906.1 1910.13  4969.2 1910.58
  4976.9 1908.98  4994.7 1898.38  4997.5 1897.88  5000.7 1898.38  5012.3 1903.03
  5019.4 1908.63  5047.6 1910.66  5069.6 1908.86    5083 1909.73  5091.3 1913.42
  5112.1 1918.35  5126.6 1925.31    5162  1930.4  5205.6 1939.36  5261.8  1945.5
  5355.4 1953.13  5411.6 1960.37  5453.3 1962.31  5490.6 1964.55  5573.6 1973.67
#Mann= 5 ,-1 , 0
    3934      .1       0    4826     .16       0  4994.7     .07       0
  5000.7     .16       0  5453.3      .1       0
Bank Sta=4969.2,5047.6
XS Rating Curve= 0 ,0
Exp/Cntr=0.3,0.1

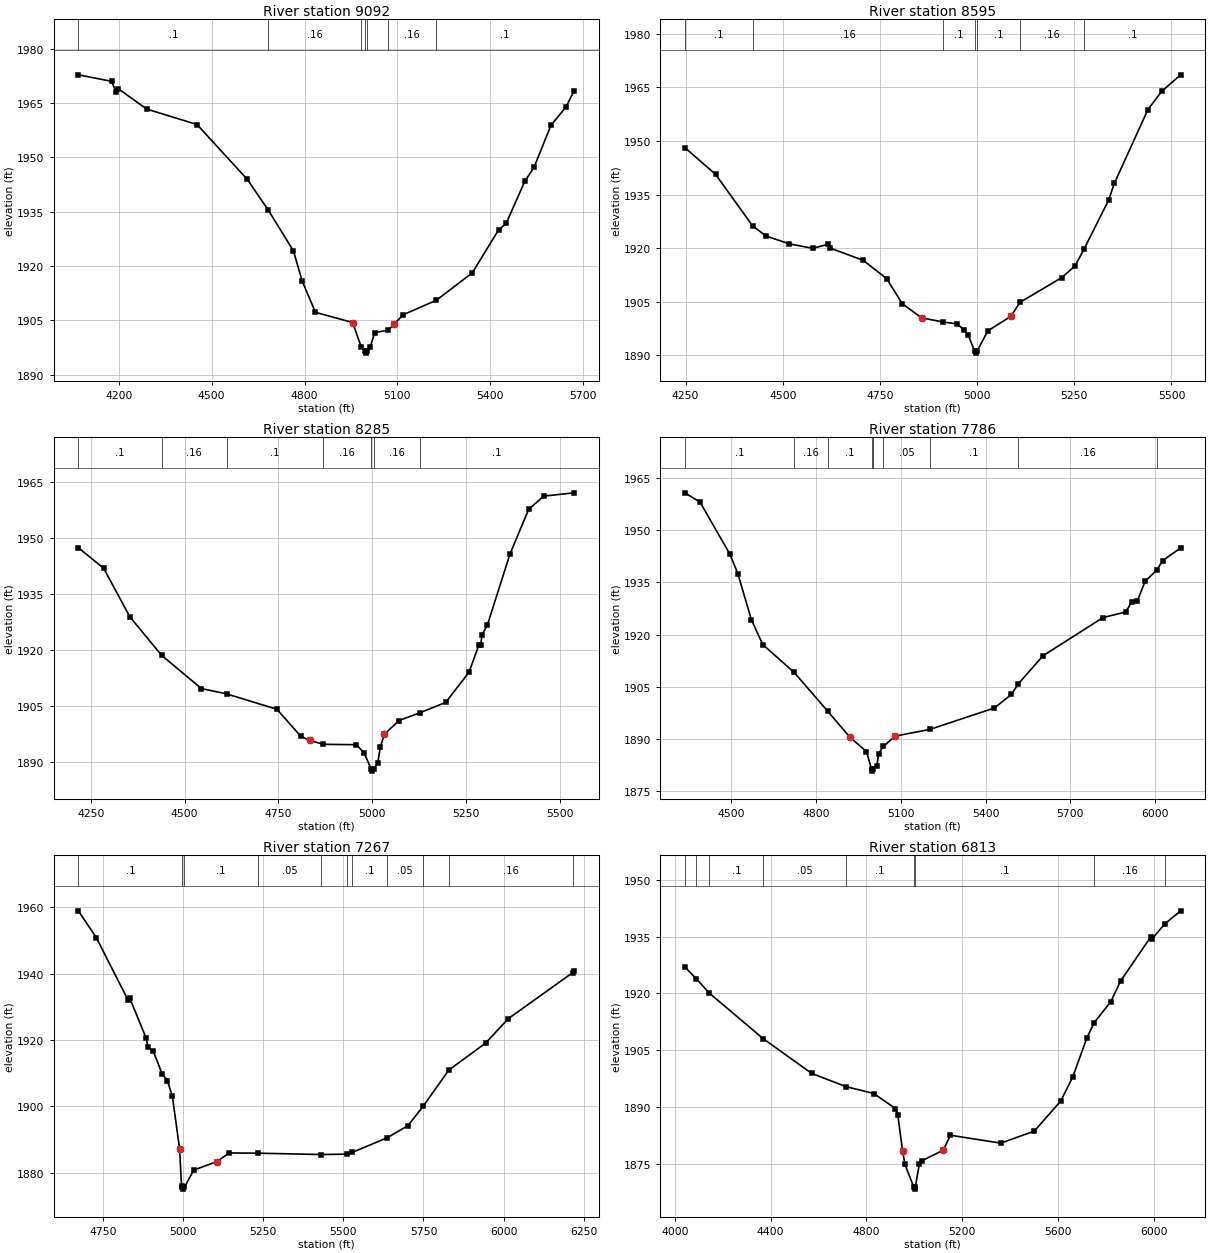
Type RM Length L Ch R = 1 ,9092    ,497,497,497
BEGIN DESCRIPTION:
UNT 1015 IN HEWA 19.0
END DESCRIPTION:
XS GIS Cut Line= 3
      2669673.24     10049147.35      2670595.12     10049975.48
      2670933.53     10050105.64
#Sta/Elev= 30
  4069.3 1972.79  4176.6    1971  4190.8 1968.17  4197.6    1969  4290.3 1963.33
  4452.7 1959.07  4615.4 1943.89  4683.6 1935.35  4764.2 1924.17  4792.6 1915.82
  4835.2 1907.21  4955.5 1904.39  4983.6 1897.55  4995.1 1896.44  4997.9 1895.94
  5001.1 1896.44  5012.3 1897.55  5026.5  1901.6    5071 1902.28  5090.1    1904
  5118.5 1906.53  5225.7 1910.53  5342.2 1918.13  5426.8 1929.95  5451.4 1931.76
  5511.4 1943.34  5541.4 1947.22  5596.1 1958.86  5644.2 1963.85  5671.1 1968.39
#Mann= 7 ,-1 , 0
  4069.3      .1       0  4683.6     .16       0  4983.6      .1       0
  4995.1     .07       0  5001.1      .1       0    5071     .16       0
  5225.7      .1       0
Bank Sta=4955.5,5090.1
XS Rating Curve= 0 ,0
Exp/Cntr=0.3,0.1

Type RM Length L Ch R = 1 ,8595    ,310,310,310
BEGIN DESCRIPTION:
UNT 1015 IN HEWA 18.0
END DESCRIPTION:
XS GIS Cut Line= 3
      2669579.45     10050189.02      2670574.28     10050215.07
      2670803.44     10050376.52
#Sta/Elev= 30
    4248 1948.15    4327 1940.67  4422.7 1926.17  4457.1 1923.37  4517.1 1921.16
  4577.1 1919.93  4615.6 1921.01  4620.6 1920.04  4707.2 1916.54  4767.2 1911.44
  4807.2 1904.43  4857.2 1900.43  4912.9 1899.27  4947.3 1898.74  4967.3 1897.08
  4977.3 1895.56  4993.7 1891.05  4996.5 1890.55  4999.7 1891.05  5027.3 1896.77
  5087.3 1900.89    5110 1904.77  5217.3 1911.68    5252 1914.98  5275.5  1919.8
  5338.2  1933.4    5353 1938.14  5439.2 1958.77  5474.9 1963.93  5523.5 1968.54
#Mann= 7 ,-1 , 0
    4248      .1       0  4422.7     .16       0  4912.9      .1       0
  4993.7     .07       0  4999.7      .1       0    5110     .16       0
  5275.5      .1       0
Bank Sta=4857.2,5087.3
XS Rating Curve= 0 ,0
Exp/Cntr=0.3,0.1

Type RM Length L Ch R = 1 ,8285    ,499,499,499
BEGIN DESCRIPTION:
UNT 1015 IN HEWA 17.0
END DESCRIPTION:
XS GIS Cut Line= 3
      2669569.08     10050256.73       2670584.7      10050610.9
       2670829.5      10050610.9
#Sta/Elev= 30
    4217 1947.46  4284.5 1941.94    4354 1928.98  4438.8 1918.64  4544.7 1909.75
  4611.7 1908.32  4745.9  1904.2  4809.4 1896.96  4833.2 1895.87  4869.8 1894.82
  4957.7 1894.71  4977.9 1892.51  4997.1 1888.14  4999.8 1887.64  5003.1 1888.14
  5014.3  1889.9  5021.2 1893.97  5031.8 1897.51  5071.2 1901.18  5125.7 1903.23
  5195.4 1906.03  5257.6 1914.16  5283.4 1921.33  5288.7 1921.52  5291.9  1924.1
  5306.4 1926.77  5366.4 1945.74  5416.4 1957.75  5456.4 1961.26  5537.4 1962.14
#Mann= 7 ,-1 , 0
    4217      .1       0  4438.8     .16       0  4611.7      .1       0
  4869.8     .16       0  4997.1     .07       0  5003.1     .16       0
  5125.7      .1       0
Bank Sta=4833.2,5031.8
XS Rating Curve= 0 ,0
Exp/Cntr=0.3,0.1

Type RM Length L Ch R = 1 ,7786    ,519,519,519
BEGIN DESCRIPTION:
UNT 1015 IN HEWA 16.0
END DESCRIPTION:
XS GIS Cut Line= 4
       2669376.4     10050579.66      2669860.74     10050704.65
       2670147.2     10051178.61      2670839.91     10051287.98
#Sta/Elev= 30
  4334.9 1960.75  4388.7  1958.1  4494.2 1943.16  4522.9  1937.5  4570.4 1924.31
    4611 1917.13  4722.2 1909.12  4840.7 1897.99  4919.7 1890.48  4977.9  1886.4
  4996.2 1881.26    4999 1880.76  5002.2 1881.26  5014.8 1882.24    5021 1885.81
  5037.9 1887.85  5079.4 1890.82  5202.9 1892.76  5430.7  1898.9  5491.4 1902.82
  5515.2 1905.81  5602.8 1913.91  5815.4  1924.9  5896.4 1926.51  5916.6 1929.38
  5936.9 1929.68  5964.5 1935.32  6005.1 1938.49  6026.9 1941.27  6090.2 1944.91
#Mann= 9 ,-1 , 0
  4334.9      .1       0  4722.2     .16       0  4840.7      .1       0
  4996.2     .07       0  5002.2      .1       0  5037.9     .05       0
  5202.9      .1       0  5515.2     .16       0  6005.1      .1       0
Bank Sta=4919.7,5079.4
XS Rating Curve= 0 ,0
Exp/Cntr=0.3,0.1

Type RM Length L Ch R = 1 ,7267    ,454,454,454
BEGIN DESCRIPTION:
UNT 1015 IN HEWA 15.0
END DESCRIPTION:
XS GIS Cut Line= 4
      2669343.38     10050811.39      2669382.44     10051015.41
      2669820.81     10051245.45      2670649.77     10051410.37
#Sta/Elev= 30
  4672.5 1958.96  4728.5 1950.91  4827.5 1932.11  4832.6 1932.77  4884.4 1920.55
    4890 1917.82  4906.4 1916.68  4934.1 1909.83  4950.5 1907.81  4966.1 1903.09
  4988.7  1887.2  4994.6 1876.17  4997.3  1875.6    5000  1875.1  5003.3  1875.6
  5033.1 1880.85  5104.9 1883.39  5143.4    1886  5232.6 1885.93  5430.3 1885.53
  5510.7 1885.65  5527.9 1886.17  5635.2 1890.51  5701.9 1894.25  5748.8 1900.03
  5829.2 1910.97  5943.9  1919.1  6015.2 1926.49  6215.5 1940.31  6220.5 1940.68
#Mann= 11 ,-1 , 0
  4672.5      .1       0  4997.3     .07       0  5003.3      .1       0
  5232.6     .05       0  5430.3      .1       0  5510.7     .05       0
  5527.9      .1       0  5635.2     .05       0  5748.8      .1       0
  5829.2     .16       0  6215.5      .1       0
Bank Sta=4988.7,5104.9
XS Rating Curve= 0 ,0
Exp/Cntr=0.3,0.1

Type RM Length L Ch R = 1 ,6813    ,522,522,522
BEGIN DESCRIPTION:
UNT 1015 IN HEWA 14.0
END DESCRIPTION:
XS GIS Cut Line= 2
      2668549.11     10051523.22      2670619.45     10051497.18
#Sta/Elev= 30
  4041.5    1927  4089.2 1923.86  4144.3 1920.04  4368.9 1908.02  4570.9 1898.86
  4714.5 1895.35  4830.9 1893.53  4920.9 1889.57  4930.9 1887.92  4950.9 1878.36
  4960.9 1874.79  4997.9 1868.77  5000.7 1868.27  5003.9 1868.77  5020.9 1874.92
  5030.9 1875.76  5120.9 1878.55  5150.9 1882.51    5361 1880.42    5501  1883.6
    5611 1891.52    5661 1897.83    5721 1908.29  5751.2 1912.26    5821 1917.84
    5861 1923.24  5987.4 1934.91  5992.4 1934.37    6045 1938.28    6112  1941.8
#Mann= 9 ,-1 , 0
  4041.5      .1       0  4089.2     .05       0  4144.3      .1       0
  4368.9     .05       0  4714.5      .1       0  4997.9     .07       0
  5003.9      .1       0  5751.2     .16       0    6045      .1       0
Bank Sta=4950.9,5120.9
XS Rating Curve= 0 ,0
Exp/Cntr=0.3,0.1

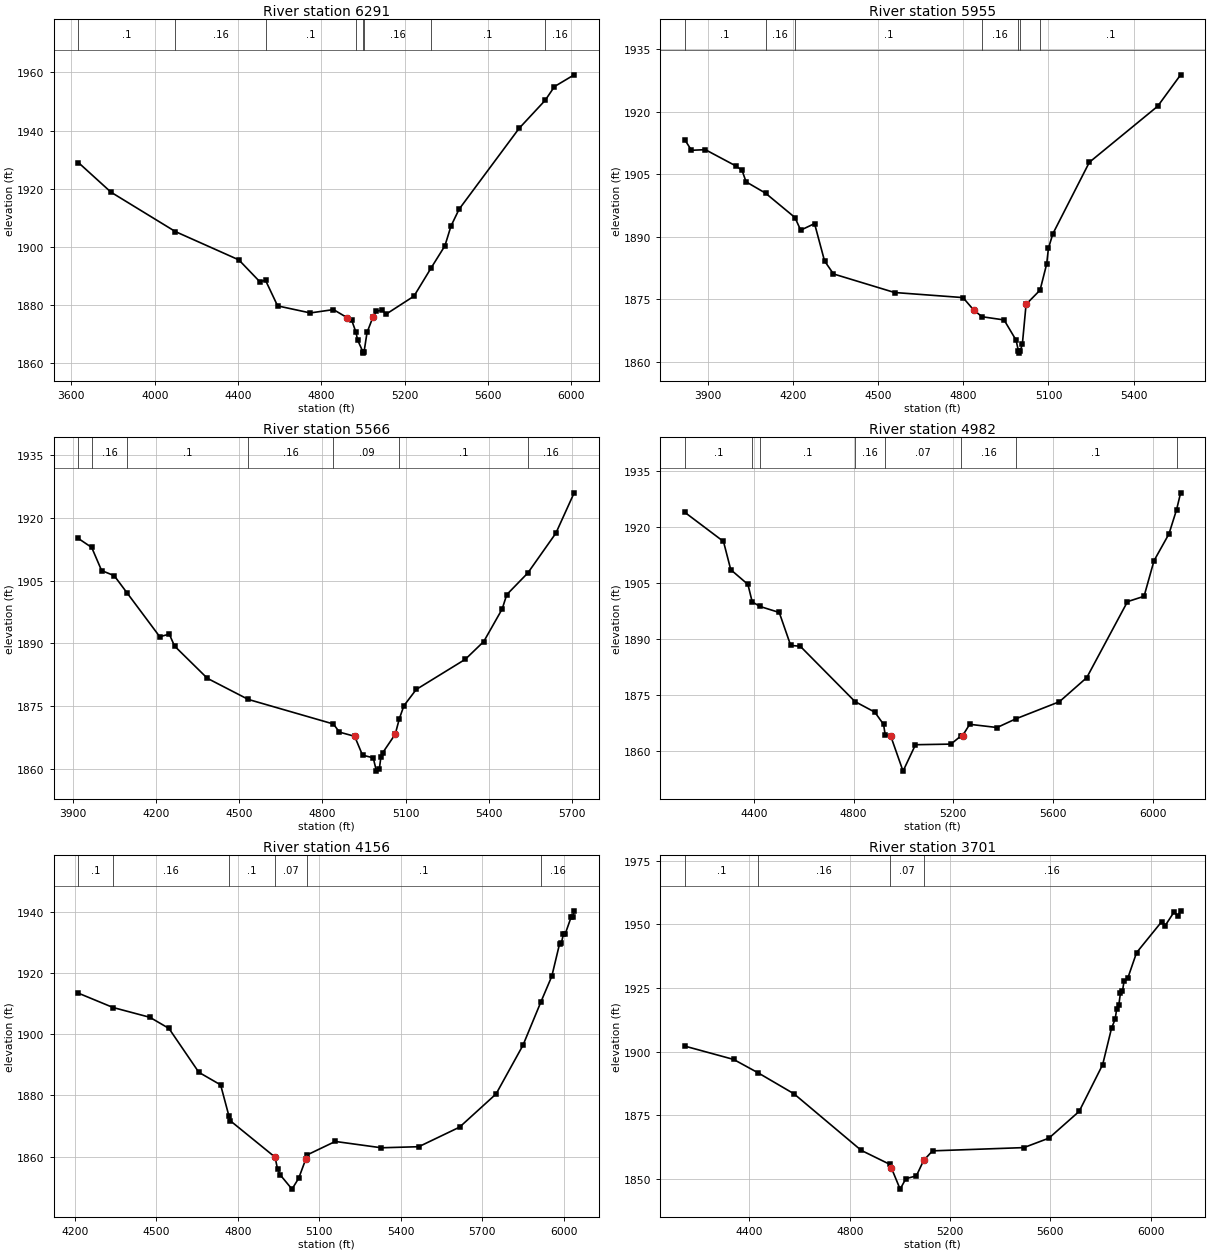
Type RM Length L Ch R = 1 ,6291    ,336,336,336
BEGIN DESCRIPTION:
UNT 1015 IN HEWA 13.0
END DESCRIPTION:
XS GIS Cut Line= 4
      2668523.07     10051618.71      2669738.35     10051935.55
      2670354.67     10051640.41       2670788.7      10051714.2
#Sta/Elev= 30
  3633.5 1929.06  3790.5 1918.85  4099.4 1905.32  4403.8  1895.6  4503.8 1888.14
  4531.9 1888.57  4589.9 1879.79  4746.7 1877.37  4857.9 1878.52  4922.8 1875.78
    4945 1874.95  4965.8 1870.74  4973.7 1868.09  4998.9 1864.06  5001.6 1863.56
  5004.9 1864.06    5019 1870.65  5047.2 1875.92  5064.3 1877.96  5092.5 1878.37
  5109.6 1876.91  5244.3 1883.14  5326.7 1892.85  5392.7 1900.43  5421.7 1907.19
  5460.7    1913    5749 1940.81  5873.8 1950.42  5918.6 1955.16    6013 1959.19
#Mann= 8 ,-1 , 0
  3633.5      .1       0  4099.4     .16       0  4531.9      .1       0
  4965.8     .16       0  4998.9     .07       0  5004.9     .16       0
  5326.7      .1       0  5873.8     .16       0
Bank Sta=4922.8,5047.2
XS Rating Curve= 0 ,0
Exp/Cntr=0.3,0.1

Type RM Length L Ch R = 1 ,5955    ,389,389,389
BEGIN DESCRIPTION:
UNT 1015 IN HEWA 12.0
END DESCRIPTION:
XS GIS Cut Line= 2
      2668770.46     10051770.62      2670398.07     10052408.64
#Sta/Elev= 30
  3817.7 1913.24  3841.2 1910.72  3890.1 1910.87  3998.2 1906.95  4019.6  1905.9
  4033.7 1903.16  4102.3 1900.44    4206  1894.6  4226.3 1891.56  4275.2 1893.14
  4310.4 1884.18  4341.9 1881.06  4557.2 1876.61  4798.6 1875.39  4835.9 1872.44
  4865.6  1870.8  4943.4 1870.03  4985.8 1865.17  4994.1 1862.57  4996.8 1862.07
  5000.1 1862.57  5007.8 1864.17    5021 1873.77  5070.3 1877.18  5093.7 1883.48
  5099.7 1887.17  5115.2 1890.67  5244.1 1907.85  5484.9 1921.28  5565.9 1928.82
#Mann= 7 ,-1 , 0
  3817.7      .1       0  4102.3     .16       0    4206      .1       0
  4865.6     .16       0  4994.1     .07       0  5000.1     .16       0
  5070.3      .1       0
Bank Sta=4835.9,5021
XS Rating Curve= 0 ,0
Exp/Cntr=0.3,0.1

Type RM Length L Ch R = 1 ,5566    ,584,584,584
BEGIN DESCRIPTION:
UNT 1015 IN HEWA 11.0
END DESCRIPTION:
XS GIS Cut Line= 3
      2668635.94     10052265.42      2669438.87     10052412.98
      2670301.32     10052859.38
#Sta/Elev= 30
  3920.4 1915.08  3968.6 1912.93  4004.3 1907.41  4049.7 1906.19  4096.7 1902.02
    4214  1891.6  4248.3 1892.23  4267.1 1889.39  4385.6 1881.67    4533 1876.63
  4839.8 1870.76  4861.9 1868.81  4916.5 1867.82  4944.9 1863.32  4983.5 1862.68
  4995.1  1859.5  5005.6 1860.09  5011.3 1862.89  5017.8  1863.9  5062.9 1868.32
  5077.7 1872.03  5094.2 1875.13  5138.5    1879  5315.6 1886.22    5382 1890.46
  5448.4 1898.23  5464.9 1901.66  5540.8 1906.83    5642 1916.34  5707.9 1925.98
#Mann= 7 ,-1 , 0
  3920.4      .1       0  3968.6     .16       0  4096.7      .1       0
    4533     .16       0  4839.8     .09       0  5077.7      .1       0
  5540.8     .16       0
Bank Sta=4916.5,5062.9
XS Rating Curve= 0 ,0
Exp/Cntr=0.3,0.1

Type RM Length L Ch R = 1 ,4982    ,826,826,826
BEGIN DESCRIPTION:
UNT 1015 IN HEWA 10.0
END DESCRIPTION:
XS GIS Cut Line= 4
      2668527.36     10052360.88      2669187.13     10052664.72
      2669430.19     10052968.54      2670305.24     10052955.54
#Sta/Elev= 30
  4122.1 1923.81  4277.4 1916.01  4306.6 1908.46  4375.5 1904.52  4392.7 1899.85
    4424 1898.62  4501.3 1897.01  4547.2 1888.19  4585.7 1887.97  4805.3 1873.17
  4884.9 1870.34  4920.1 1867.06  4926.5 1864.32    4949 1863.91  4998.3 1854.55
  5048.2 1861.62  5190.7 1861.78  5232.2 1864.05  5237.5 1864.05  5265.8 1867.08
  5375.8 1866.22  5451.3 1868.55  5625.9 1873.12  5735.9 1879.58  5899.4 1899.91
  5965.9 1901.34  6005.9 1910.87  6065.9 1918.04  6096.5 1924.53  6112.7 1929.03
#Mann= 8 ,-1 , 0
  4122.1      .1       0  4392.7     .16       0    4424      .1       0
  4805.3     .16       0  4926.5     .07       0  5232.2     .16       0
  5451.3      .1       0  6096.5     .16       0
Bank Sta=4949,5237.5
XS Rating Curve= 0 ,0
Exp/Cntr=0.3,0.1

Type RM Length L Ch R = 1 ,4156    ,455,455,455
BEGIN DESCRIPTION:
UNT 1015 IN HEWA 8.0
END DESCRIPTION:
XS GIS Cut Line= 4
      2668705.33     10053602.22      2669265.26     10053571.84
      2669951.02     10053328.78       2670354.1     10052973.38
#Sta/Elev= 30
  4212.7 1913.43  4340.8 1908.73  4476.2 1905.53  4546.3  1901.9  4656.5 1887.54
  4736.6 1883.44  4767.1  1873.3  4772.6 1871.68  4936.9 1859.82  4946.6 1855.78
  4957.1  1853.9  4999.4 1849.35  5024.2 1852.92  5049.8 1859.07  5055.1 1860.53
  5158.8 1864.94  5328.6 1862.87  5466.2 1863.22  5616.5 1869.62  5750.9 1880.47
  5849.9 1896.39    5916 1910.58  5956.1 1918.96  5984.6 1929.53  5991.3 1929.81
  5998.8 1932.76  6005.5  1932.8  6027.3 1938.31  6033.9 1938.33  6038.4 1940.35
#Mann= 6 ,-1 , 0
  4212.7      .1       0  4340.8     .16       0  4767.1      .1       0
  4936.9     .07       0  5055.1      .1       0    5916     .16       0
Bank Sta=4936.9,5049.8
XS Rating Curve= 0 ,0
Exp/Cntr=0.3,0.1

Type RM Length L Ch R = 1 ,3701    ,464,464,464
BEGIN DESCRIPTION:
UNT 1015 IN HEWA 7.0
END DESCRIPTION:
XS GIS Cut Line= 3
      2669004.83     10054144.76       2669690.6     10053936.42
      2670450.15     10052929.48
#Sta/Elev= 30
    4142 1902.13  4336.9 1896.89  4435.1 1891.59  4577.5 1883.39  4845.8 1861.16
  4959.6 1855.67  4965.8 1854.34    5001 1845.92  5024.1 1850.03  5065.8 1851.13
  5094.9 1857.21  5130.3 1860.96  5494.6 1862.24  5594.5 1865.95  5715.2 1876.47
  5808.9 1894.83  5844.3 1909.13  5858.9 1912.76  5865.1 1916.87  5873.4 1918.24
  5879.7 1922.82    5888 1923.65  5894.3 1927.73  5908.8 1928.72  5944.2 1938.86
  6044.1    1951  6058.7 1949.53  6094.1 1954.88  6108.7 1953.33    6120  1955.3
#Mann= 4 ,-1 , 0
    4142      .1       0  4435.1     .16       0  4959.6     .07       0
  5094.9     .16       0
Bank Sta=4965.8,5094.9
XS Rating Curve= 0 ,0
Exp/Cntr=0.3,0.1

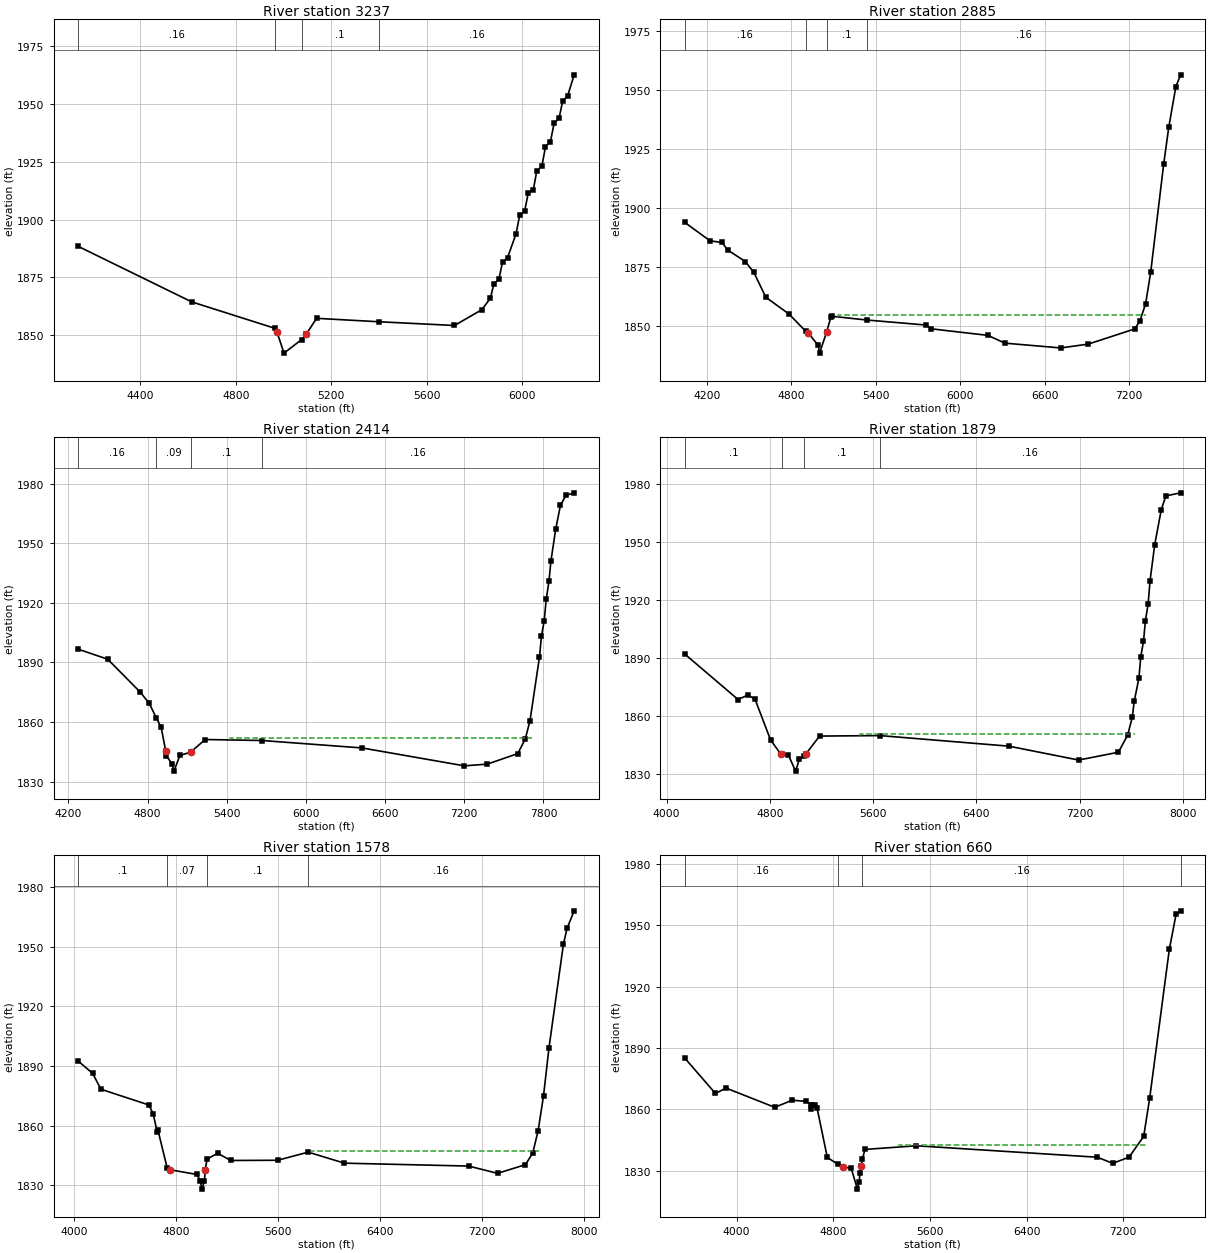
Type RM Length L Ch R = 1 ,3237    ,352,352,352
BEGIN DESCRIPTION:
UNT 1015 IN HEWA 6.0
END DESCRIPTION:
XS GIS Cut Line= 3
      2669391.17     10054513.65      2670076.89     10054179.48
      2670809.36     10053087.26
#Sta/Elev= 30
  4139.8 1888.43  4615.1 1864.44    4966 1852.94    4972  1851.5  5001.8 1842.29
  5075.8 1848.16  5095.1 1850.54  5138.3 1857.34  5398.2 1855.86  5716.2 1854.24
  5830.4 1861.05  5866.4 1865.97  5881.4 1872.26  5902.4 1874.26  5917.4 1881.66
  5938.4  1883.5  5974.4 1893.96  5989.4 1901.91  6010.4 1903.87  6025.4 1911.55
  6046.4 1912.84  6061.4 1921.22  6082.5 1923.06  6097.5 1931.58  6118.5  1933.8
  6133.5 1941.67  6154.5 1943.89  6169.5 1951.21  6190.5 1953.59  6217.7 1962.63
#Mann= 4 ,-1 , 0
  4139.8     .16       0    4966     .09       0  5075.8      .1       0
  5398.2     .16       0
Bank Sta=4972,5095.1
XS Rating Curve= 0 ,0
Exp/Cntr=0.3,0.1

Type RM Length L Ch R = 1 ,2885    ,471,471,471
BEGIN DESCRIPTION:
UNT 1015 IN HEWA 5.0
END DESCRIPTION:
XS GIS Cut Line= 4
      2669382.48     10054600.47      2670007.44     10054366.11
      2670719.25     10054392.15       2672488.7     10053177.82
#Sta/Elev= 30
  4041.9 1893.72  4221.1 1885.94  4306.6 1885.23  4347.3 1882.01  4472.1 1877.15
  4532.6 1872.57  4618.1 1862.01  4783.3 1854.87  4900.5 1847.66  4920.5 1846.82
  4990.6  1841.6  5000.3 1838.32  5050.1 1847.21  5080.6 1853.55  5090.6 1853.93
  5340.8 1852.33  5758.8 1850.22  5794.7 1848.62  6196.9 1845.85  6318.2 1842.55
  6715.1 1840.52  6909.3 1842.12    7240 1848.55  7276.3 1851.73  7318.7 1859.16
  7354.6 1872.51  7447.3 1918.48  7483.2 1934.03  7533.9 1951.33  7567.7  1956.3
#Mann= 4 ,-1 , 0
  4041.9     .16       0  4900.5     .07       0  5050.1      .1       0
  5340.8     .16       0
#XS Ineff= 1 ,-1
 5134.09    7325 1854.69
Permanent Ineff=
       T
Bank Sta=4920.5,5050.1
XS Rating Curve= 0 ,0
Exp/Cntr=0.3,0.1

Type RM Length L Ch R = 1 ,2414    ,535,535,535
BEGIN DESCRIPTION:
UNT 1015 IN HEWA 4.0
END DESCRIPTION:
XS GIS Cut Line= 3
      2669408.51     10054695.97      2670458.83      10054860.9
      2672689.72     10053350.49
#Sta/Elev= 30
  4275.5 1896.67  4498.2 1891.63  4745.4 1875.01    4813  1869.4    4865 1862.29
  4903.1 1857.36  4938.2 1845.21  4943.5 1842.96    4984 1839.01  5000.6 1835.29
  5044.8 1843.17  5125.8 1844.83  5237.1 1851.21    5667 1850.71  6424.9 1846.97
  7200.8 1837.95  7374.5 1838.81  7605.2 1844.11  7662.2 1851.45  7698.1 1860.66
    7770 1892.78    7785 1903.21    7806 1911.08  7820.9 1921.78  7841.9 1930.86
  7856.9 1941.15  7892.8  1957.1  7928.8  1969.1  7970.9  1974.2  8032.8 1975.42
#Mann= 4 ,-1 , 0
  4275.5     .16       0    4865     .09       0  5125.8      .1       0
    5667     .16       0
#XS Ineff= 1 ,-1
  5423.3 7713.07 1852.04
Permanent Ineff=
       T
Bank Sta=4938.2,5125.8
XS Rating Curve= 0 ,0
Exp/Cntr=0.3,0.1

Type RM Length L Ch R = 1 ,1879    ,301,301,301
BEGIN DESCRIPTION:
UNT 1015 IN HEWA 3.0
END DESCRIPTION:
XS GIS Cut Line= 4
      2669564.78     10055025.84      2670285.22     10055268.88
      2670502.24     10054982.43      2672750.47     10053445.99
#Sta/Elev= 30
  4140.6 1891.94  4553.6 1868.46    4630 1870.82  4684.7 1868.65  4805.3 1847.58
  4883.2  1840.4  4893.8 1840.14  4943.2 1839.81  4999.2 1831.47  5028.5 1837.64
  5063.9 1839.49  5078.5 1840.25  5184.6 1849.58  5653.1 1849.83    6652 1844.37
  7193.2 1837.19  7501.3 1841.23  7573.1  1850.1  7608.9 1859.41  7623.9 1867.62
  7659.8 1879.38  7674.7 1890.64  7695.6 1898.46  7710.6 1909.27  7731.5 1917.78
  7746.5  1929.9  7782.3  1948.3  7833.2 1966.52    7869 1973.66  7983.4 1975.25
#Mann= 4 ,-1 , 0
  4140.6      .1       0  4893.8     .07       0  5063.9      .1       0
  5653.1     .16       0
#XS Ineff= 1 ,-1
 5497.73 7631.82 1850.84
Permanent Ineff=
       T
Bank Sta=4883.2,5078.5
XS Rating Curve= 0 ,0
Exp/Cntr=0.3,0.1

Type RM Length L Ch R = 1 ,1578    ,1006,1006,1006
BEGIN DESCRIPTION:
UNT 1015 IN HEWA 2.0
END DESCRIPTION:
XS GIS Cut Line= 3
      2669582.14     10055147.37      2670719.25     10055494.58
      2672698.43     10053654.29
#Sta/Elev= 30
    4031 1892.43  4142.9 1886.33  4208.5 1878.33    4585 1870.42  4617.9 1866.09
  4650.7 1856.76  4655.9 1857.79  4727.7 1838.95  4754.3 1837.85  4961.6 1835.54
  4989.1 1832.15  4999.4 1828.17  5020.5 1832.09  5027.2 1837.92  5041.4  1843.3
    5125 1846.15  5227.1 1842.56    5595 1842.66  5835.4 1846.75  6118.8 1841.21
    7095 1839.75  7321.7 1836.09  7540.6 1840.48  7597.3 1846.29  7639.8 1857.52
  7682.3 1875.13  7724.8 1899.07  7838.2 1951.16  7866.5  1959.1  7922.5 1967.93
#Mann= 4 ,-1 , 0
    4031      .1       0  4727.7     .07       0  5041.4      .1       0
  5835.4     .16       0
#XS Ineff= 1 ,-1
 5859.09 7643.18 1847.23
Permanent Ineff=
       T
Bank Sta=4754.3,5027.2
XS Rating Curve= 0 ,0
Exp/Cntr=0.3,0.1

Type RM Length L Ch R = 1 ,660     ,406,406,406
BEGIN DESCRIPTION:
Mapping XS 1e3bd2b1
END DESCRIPTION:
XS GIS Cut Line= 4
      2669688.26     10055348.61        2670598.     10055869.46
      2671157.03     10055737.51      2672757.73     10053841.67
#Sta/Elev= 30
  3571.3 1885.05    3825 1867.81  3912.6 1870.44  4315.5 1861.06  4460.8 1864.52
  4573.1 1863.94  4616.2 1862.38  4618.9 1860.29    4624 1862.38  4650.9 1861.98
  4666.3 1860.65  4750.9 1836.59  4835.6 1833.35  4876.9 1832.05  4948.9 1831.27
    5000 1821.13  5015.1 1824.77  5020.8 1829.12  5031.1 1832.35  5041.3 1835.76
  5062.5  1840.5  5488.2 1842.29    6986 1836.69  7113.4 1833.71  7248.6 1836.74
  7369.5 1846.87  7418.9 1865.42  7581.5 1938.08  7638.7  1955.6  7675.2 1956.93
#Mann= 4 ,-1 , 0
  3571.3     .16       0  4835.6     .07       0  5041.3     .16       0
  7675.2     .16       0
#XS Ineff= 1 ,-1
 5343.75 7392.05 1842.43
Permanent Ineff=
       T
Bank Sta=4876.9,5031.1
XS Rating Curve= 0 ,0
Exp/Cntr=0.3,0.1

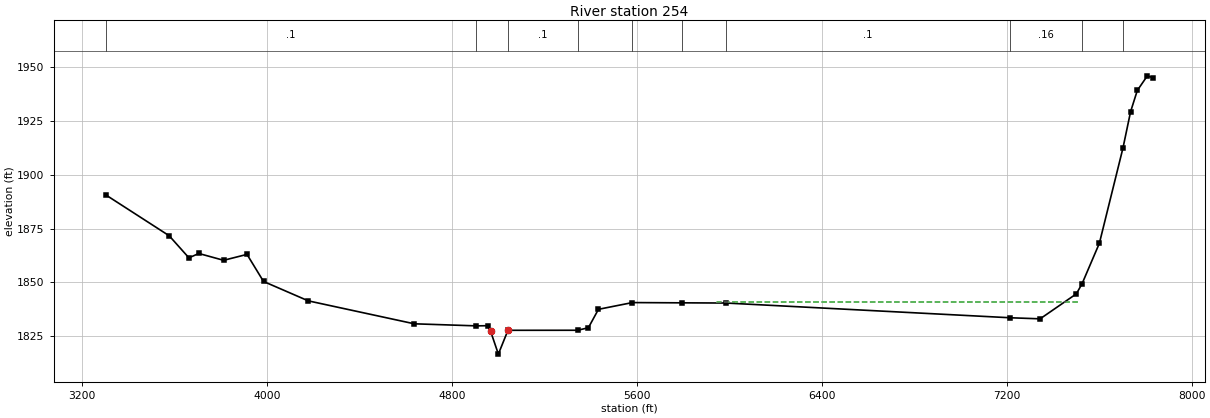
Type RM Length L Ch R = 1 ,254     ,0,0,0
BEGIN DESCRIPTION:
UNT 1015 IN HEWA 1.0
END DESCRIPTION:
XS GIS Cut Line= 4
      2669584.15     10055418.09      2670670.92     10056178.48
      2671212.58     10056043.07      2672826.04     10053947.31
#Sta/Elev= 30
  3302.6 1890.59  3576.4 1871.64  3661.8 1861.38  3704.7  1863.4    3812 1860.23
  3913.1 1862.98  3984.6  1850.4  4178.2 1841.39  4636.8 1830.73  4904.8 1829.77
  4954.5 1829.85  4966.6  1827.4  5000.6 1816.64  5042.1 1827.71  5343.9 1827.73
  5390.1  1828.9  5433.6 1837.46  5580.4 1840.59  5796.2 1840.47  5985.7 1840.38
  7214.3 1833.54  7344.5 1833.04  7501.2 1844.64  7525.9 1849.33  7600.9 1868.17
  7702.9 1912.41  7735.8 1929.25  7764.9 1939.13  7808.4 1945.94  7832.2 1945.04
#Mann= 10 ,-1 , 0
  3302.6      .1       0  4904.8     .07       0  5042.1      .1       0
  5343.9     .16       0  5580.4      .1       0  5796.2     .05       0
  5985.7      .1       0  7214.3     .16       0  7525.9      .1       0
  7702.9     .16       0
#XS Ineff= 1 ,-1
 5946.54 7513.02 1840.79
Permanent Ineff=
       T
Bank Sta=4966.6,5042.1
XS Rating Curve= 0 ,0
Exp/Cntr=0.3,0.1

Chan Stop Cuts=-1
Use User Specified Reach Order=0
Composite Channel Slope=5