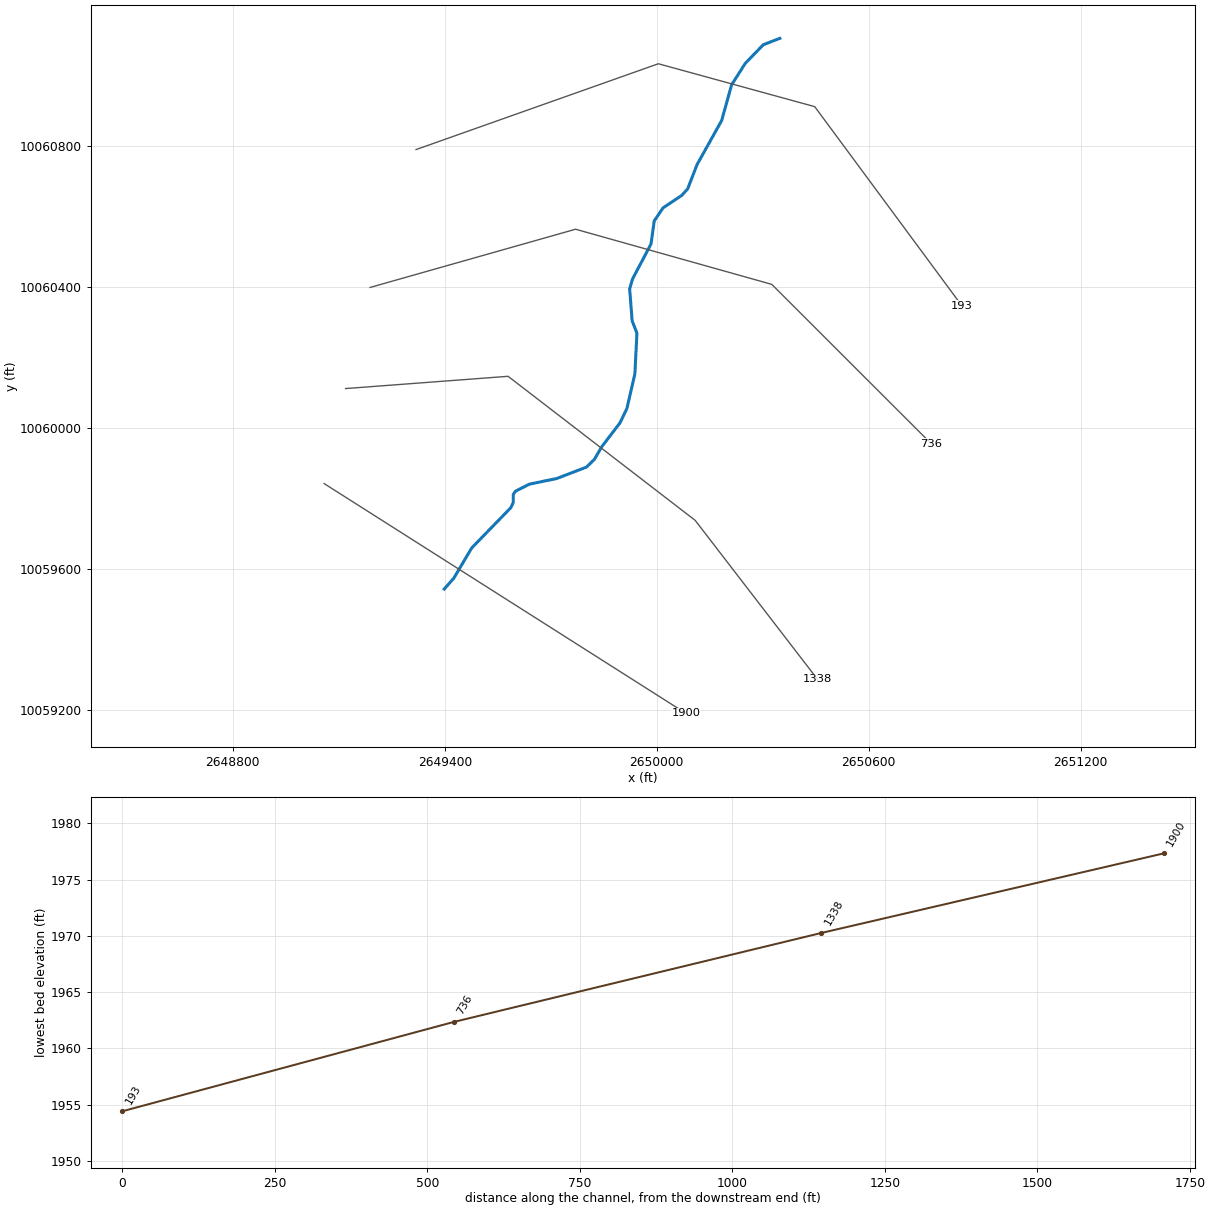
--- UNT 1017 IN HEWA.prj (project) ---

Proj Title=UNT 1017 IN HEWA Base Level Engineering
Current Plan=p01
Default Exp/Contr=0.3,0.1
English Units
Geom File=g01
Flow File=f01
Plan File=p01
Y Axis Title=Elevation
X Axis Title(PF)=Main Channel Distance
X Axis Title(XS)=Station
BEGIN DESCRIPTION:
UNT 1017 IN HEWA
END DESCRIPTION:
DSS Export Rating Curves= 0
DSS Export Rating Curve Sorted= 0
DSS Export Volume Flow Curves= 0
DXF OffsetX= 0
DXF OffsetY= 0
DXF ScaleX= 1
DXF ScaleY= 10

--- UNT 1017 IN HEWA.p01 (plan) ---

Plan Title=Multiple Run
Short Identifier=Multiple
Geom File=g01
Flow File=f01
Subcritical Flow
K Sum by GR= 0
Std Step Tol= 0.01
Critical Tol= 0.01
Num of Std Step Trials= 20
Max Error Tol= 0.3
Flow Tol Ratio= 0.001
Split Flow NTrial= 30
Split Flow Tol= 0.02
Split Flow Ratio= 0.02
Log Output Level= 0
Friction Slope Method= 1
Unsteady Friction Slope Method= 2
Unsteady Bridges Friction Slope Method= 1
Parabolic Critical Depth
Global Vel Dist=  1 , 1 , 1
Global Log Level= 0
CheckData=True
Encroach Param= -1, 0, 0, 0
BEGIN DESCRIPTION:
Multiple Run
END DESCRIPTION:

--- UNT 1017 IN HEWA.f01 (steady flow) ---

Flow Title=Multiple
Program Version=4.10
Number of Profiles= 7
Profile Names=10-year,25-year,50-year,1pct_min,100-year,1pct_plu,500-year
River Rch & RM=UNT 1017 IN HEWA,Reach-1         ,1900
     695     985    1230    1121    1516    2051    2303
Boundary for River Rch & Prof#=UNT 1017 IN HEWA,Reach-1         , 1
Up Type= 0
Dn Type= 3
Dn Slope=0.015
Boundary for River Rch & Prof#=UNT 1017 IN HEWA,Reach-1         , 2
Up Type= 0
Dn Type= 3
Dn Slope=0.015
Boundary for River Rch & Prof#=UNT 1017 IN HEWA,Reach-1         , 3
Up Type= 0
Dn Type= 3
Dn Slope=0.015
Boundary for River Rch & Prof#=UNT 1017 IN HEWA,Reach-1         , 4
Up Type= 0
Dn Type= 3
Dn Slope=0.015
Boundary for River Rch & Prof#=UNT 1017 IN HEWA,Reach-1         , 5
Up Type= 0
Dn Type= 3
Dn Slope=0.015
Boundary for River Rch & Prof#=UNT 1017 IN HEWA,Reach-1         , 6
Up Type= 0
Dn Type= 3
Dn Slope=0.015
Boundary for River Rch & Prof#=UNT 1017 IN HEWA,Reach-1         , 7
Up Type= 0
Dn Type= 3
Dn Slope=0.015
DSS Import GetInterval= 0
DSS Import GetPeak= 0
DSS Import FillOption= 0

--- UNT 1017 IN HEWA.g01 (geometry) ---

Geom Title=Existing Conditions
Program Version=4.10

River Reach=UNT 1017 IN HEWA,Reach-1
Reach XY= 30
      2649398.47     10059543.73      2649425.23      10059574.1
      2649476.39     10059660.25      2649587.13     10059774.32
      2649593.79     10059789.12      2649593.95     10059812.15
      2649600.59     10059821.09       2649639.4     10059840.74
      2649717.17     10059856.85      2649801.06     10059889.13
      2649823.49     10059910.83      2649843.82     10059946.13
      2649896.18     10060014.68      2649915.51     10060054.95
      2649938.12     10060153.09      2649943.93     10060268.56
      2649930.34     10060303.74       2649923.3     10060394.17
      2649931.62     10060422.32      2649983.77     10060520.97
      2649992.96     10060586.66      2650018.26     10060623.81
      2650071.01     10060658.89      2650087.61     10060677.37
      2650114.19     10060746.06      2650183.83     10060870.94
      2650212.08     10060972.24      2650250.69     10061032.88
      2650301.72     10061085.65      2650348.47     10061103.73

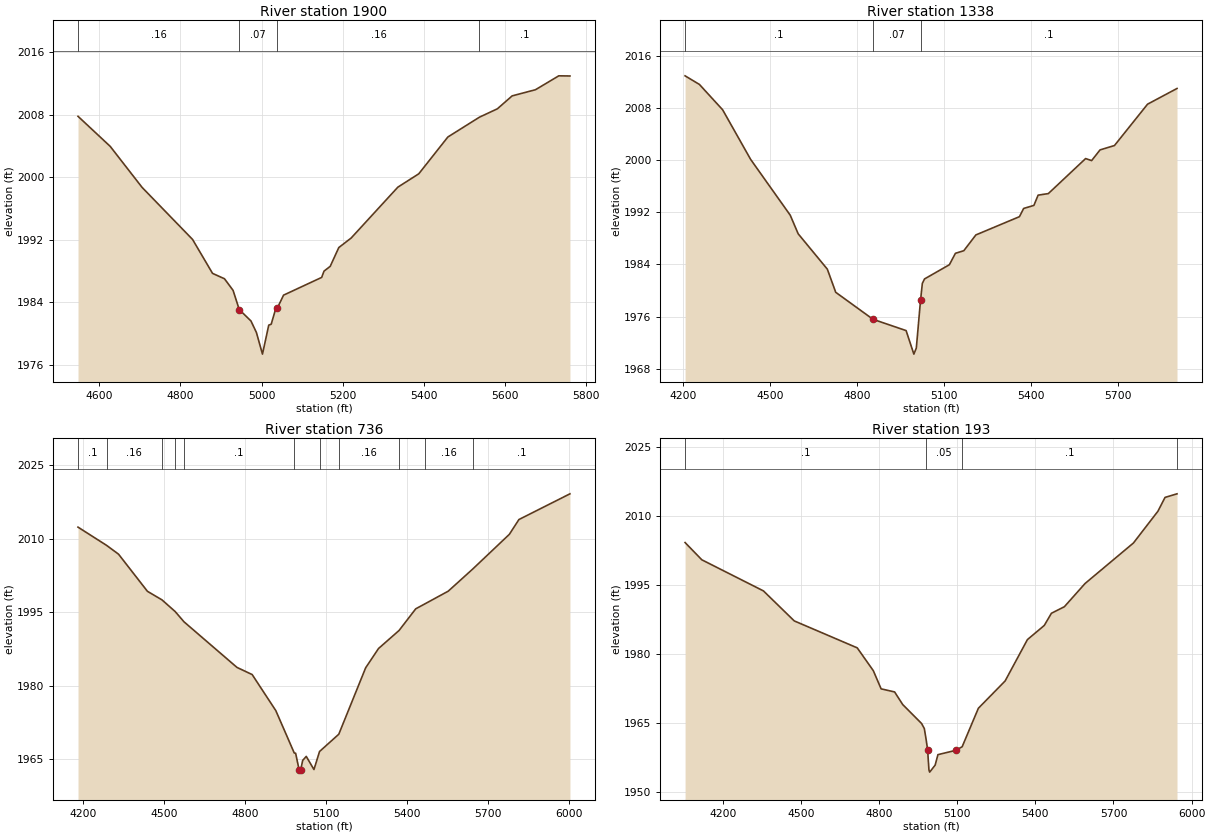
Type RM Length L Ch R = 1 ,1900    ,562,562,562
BEGIN DESCRIPTION:
UNT 1017 IN HEWA 4.0
END DESCRIPTION:
XS GIS Cut Line= 2
      2649058.36     10059842.52      2650082.67     10059191.47
#Sta/Elev= 30
  4547.3 2007.81  4626.7 2003.96  4705.4  1998.7  4829.9 1992.03  4879.2 1987.68
  4908.7 1986.99  4929.9  1985.5  4945.1 1983.04    4974 1981.58  4987.4 1980.11
  5002.4 1977.33  5017.9 1981.05  5023.9 1981.16  5033.2 1982.81  5039.1 1983.23
  5054.4 1984.89  5148.4 1987.16  5154.3 1987.97  5169.5 1988.58  5190.7 1990.99
  5221.2 1992.21  5336.4 1998.73    5388 2000.44  5459.8 2005.16  5537.7  2007.7
  5581.9 2008.77  5618.4 2010.43    5676 2011.22  5733.5    2013    5761 2012.98
#Mann= 4 ,-1 , 0
  4547.3     .16       0  4945.1     .07       0  5039.1     .16       0
  5537.7      .1       0
Bank Sta=4945.1,5039.1
XS Rating Curve= 0 ,0
Exp/Cntr=0.3,0.1

Type RM Length L Ch R = 1 ,1338    ,602,602,602
BEGIN DESCRIPTION:
UNT 1017 IN HEWA 3.0
END DESCRIPTION:
XS GIS Cut Line= 4
      2649119.11     10060111.59      2649579.23     10060146.32
      2650108.74     10059738.33      2650455.25     10059287.87
#Sta/Elev= 30
  4206.4 2012.93  4255.9 2011.61  4336.1 2007.72  4432.8 2000.11  4569.4 1991.56
  4596.9  1988.7  4697.5 1983.28  4726.5 1979.73  4855.2 1975.59  4969.4 1973.86
  4996.2 1970.25  5004.7 1971.18  5019.2  1978.5  5025.5  1981.1    5033 1981.78
  5118.8 1983.96  5139.6 1985.71  5168.6 1986.11  5210.3 1988.53  5360.7 1991.33
  5375.2 1992.59  5410.6 1993.06  5425.1 1994.63  5460.4 1994.87  5589.1 2000.24
  5609.9 1999.93  5638.9 2001.57  5688.7 2002.24  5802.9 2008.58  5904.6 2010.99
#Mann= 3 , 0 , 0
  4206.4      .1       0  4855.2     .07       0  5019.2      .1       0
Bank Sta=4855.2,5019.2
XS Rating Curve= 0 ,0
Exp/Cntr=0.3,0.1

Type RM Length L Ch R = 1 ,736     ,543,543,543
BEGIN DESCRIPTION:
UNT 1017 IN HEWA 2.0
END DESCRIPTION:
XS GIS Cut Line= 4
      2649188.56     10060398.04       2649770.2     10060562.98
      2650325.75     10060406.73      2650777.11     10059955.38
#Sta/Elev= 30
  4182.2 2012.37  4287.8 2008.65  4332.1 2006.85    4439 1999.27  4492.8 1997.52
  4541.6 1995.14  4574.1 1993.05  4770.3 1983.73  4826.5 1982.27  4914.1  1974.9
  4982.2 1966.26  4987.3 1966.21  5000.1 1962.85  5002.9 1962.35  5006.1 1962.85
  5013.5 1964.75  5026.6 1965.56  5055.1 1962.88  5075.8 1966.56    5147 1970.09
  5246.5 1983.66    5294 1987.59    5370 1991.27  5431.6 1995.69  5464.4 1996.67
  5551.8 1999.29  5642.2  2003.8    5778  2010.9  5813.4 2013.92  6002.2 2019.17
#Mann= 11 ,-1 , 0
  4182.2      .1       0  4287.8     .16       0  4492.8      .1       0
  4541.6     .16       0  4574.1      .1       0  4982.2     .05       0
  5075.8      .1       0    5147     .16       0    5370      .1       0
  5464.4     .16       0  5642.2      .1       0
Bank Sta=5000.1,5006.1
XS Rating Curve= 0 ,0
Exp/Cntr=0.3,0.1

Type RM Length L Ch R = 1 ,193     ,0,0,0
BEGIN DESCRIPTION:
UNT 1017 IN HEWA 1.0
END DESCRIPTION:
XS GIS Cut Line= 4
      2649318.78     10060788.67      2650004.57     10061031.73
      2650447.28      10060910.2      2650863.96     10060345.96
#Sta/Elev= 30
  4055.8 2004.32  4120.1 2000.57  4356.6 1993.81  4474.8 1987.29  4716.6 1981.43
  4778.3 1976.47  4808.2 1972.52    4860 1971.85  4891.1 1969.11  4963.7 1964.98
  4974.1 1963.88  4981.4 1961.37  4986.6  1959.3  4991.8 1954.92  4994.6 1954.42
  5015.6 1955.94  5026.3 1958.22  5095.1 1959.16  5119.3 1959.94  5181.5  1968.3
  5284.1 1974.23  5369.7 1983.22  5434.4  1986.3  5461.9 1988.95  5511.6 1990.37
    5591 1995.42  5776.8 2004.23  5870.8 2011.14  5897.9 2014.13  5943.9 2014.91
#Mann= 4 ,-1 , 0
  4055.8      .1       0  4981.4     .05       0  5119.3      .1       0
  5943.9      .1       0
Bank Sta=4986.6,5095.1
XS Rating Curve= 0 ,0
Exp/Cntr=0.3,0.1

Chan Stop Cuts=-1
Use User Specified Reach Order=0
Composite Channel Slope=5