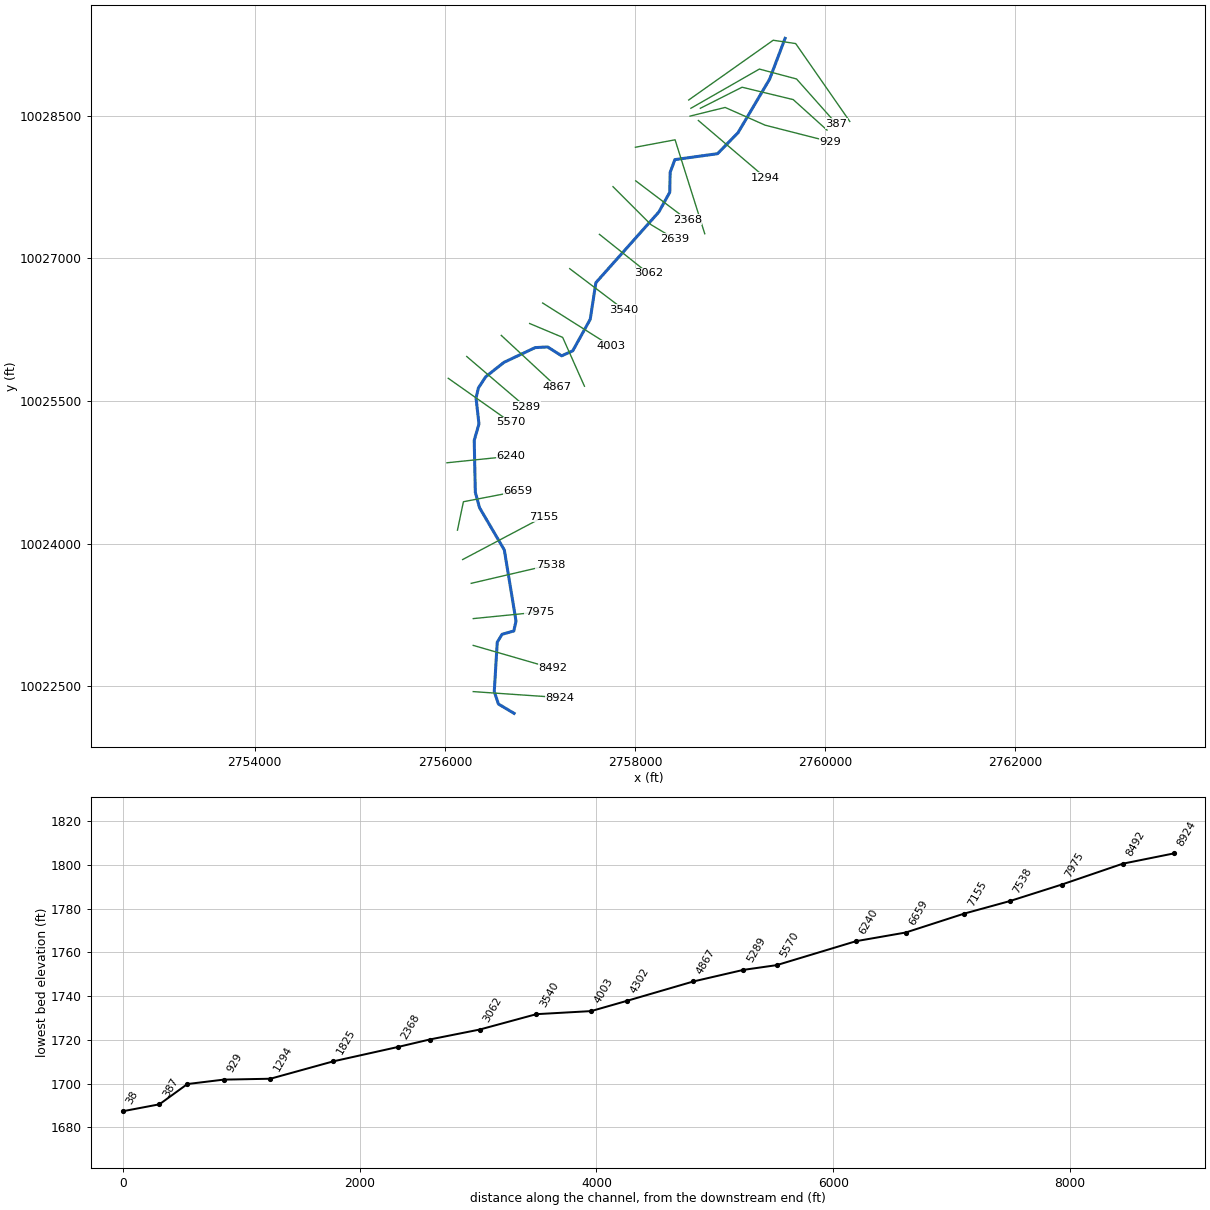
--- UNT 1018 IN HEWA.prj (project) ---

Proj Title=UNT 1018 IN HEWA Base Level Engineering
Current Plan=p01
Default Exp/Contr=0.3,0.1
English Units
Geom File=g01
Flow File=f01
Plan File=p01
Y Axis Title=Elevation
X Axis Title(PF)=Main Channel Distance
X Axis Title(XS)=Station
BEGIN DESCRIPTION:
UNT 1018 IN HEWA
END DESCRIPTION:
DSS Export Rating Curves= 0
DSS Export Rating Curve Sorted= 0
DSS Export Volume Flow Curves= 0
DXF OffsetX= 0
DXF OffsetY= 0
DXF ScaleX= 1
DXF ScaleY= 10

--- UNT 1018 IN HEWA.p01 (plan) ---

Plan Title=Multiple Run
Short Identifier=Multiple
Geom File=g01
Flow File=f01
Subcritical Flow
K Sum by GR= 0
Std Step Tol= 0.01
Critical Tol= 0.01
Num of Std Step Trials= 20
Max Error Tol= 0.3
Flow Tol Ratio= 0.001
Split Flow NTrial= 30
Split Flow Tol= 0.02
Split Flow Ratio= 0.02
Log Output Level= 0
Friction Slope Method= 1
Unsteady Friction Slope Method= 2
Unsteady Bridges Friction Slope Method= 1
Parabolic Critical Depth
Global Vel Dist=  1 , 1 , 1
Global Log Level= 0
CheckData=True
Encroach Param= -1, 0, 0, 0
BEGIN DESCRIPTION:
Multiple Run
END DESCRIPTION:

--- UNT 1018 IN HEWA.f01 (steady flow) ---

Flow Title=Multiple
Number of Profiles=7
Profile Names=10-year,25-year,50-year,1pct_min,100-year,1pct_plu,500-year
River Rch & RM= UNT 1018 IN HEWA,Reach-1,8924
     927    1355    1730    1617    2187    2957    3508
River Rch & RM= UNT 1018 IN HEWA,Reach-1,5570
    1649    2483    3232    3075    4158    5624    6916
River Rch & RM= UNT 1018 IN HEWA,Reach-1,1294
    2464    3783    4989    4802    6494    8782   11059
Boundary for River Rch & Prof#=UNT 1018 IN HEWA,Reach-1,1
Up Type=0
Dn Type=3
Dn Slope=0.005
Boundary for River Rch & Prof#=UNT 1018 IN HEWA,Reach-1,2
Up Type=0
Dn Type=3
Dn Slope=0.005
Boundary for River Rch & Prof#=UNT 1018 IN HEWA,Reach-1,3
Up Type=0
Dn Type=3
Dn Slope=0.005
Boundary for River Rch & Prof#=UNT 1018 IN HEWA,Reach-1,4
Up Type=0
Dn Type=3
Dn Slope=0.005
Boundary for River Rch & Prof#=UNT 1018 IN HEWA,Reach-1,5
Up Type=0
Dn Type=3
Dn Slope=0.005
Boundary for River Rch & Prof#=UNT 1018 IN HEWA,Reach-1,6
Up Type=0
Dn Type=3
Dn Slope=0.005
Boundary for River Rch & Prof#=UNT 1018 IN HEWA,Reach-1,7
Up Type=0
Dn Type=3
Dn Slope=0.005

--- UNT 1018 IN HEWA.g01 (geometry) ---

Geom Title=Existing Conditions
Program Version=4.10

River Reach=UNT 1018 IN HEWA,Reach-1
Reach XY= 30
      2756728.47     10022213.73      2756563.55     10022311.93
      2756519.69     10022443.81      2756551.12     10022962.67
      2756602.06     10023045.89      2756725.01     10023080.39
      2756748.47     10023183.55      2756625.57     10023932.53
      2756364.75      10024376.9      2756320.43     10024539.23
       2756308.8     10025085.31      2756358.73     10025257.57
      2756328.04     10025530.96      2756352.86     10025636.62
      2756429.56     10025754.18      2756622.21      10025906.1
      2756949.79     10026060.63      2757080.53     10026067.97
      2757228.28     10025974.46       2757345.2     10026026.98
       2757528.9     10026358.55      2757588.52     10026743.68
      2758250.84     10027487.46      2758365.55      10027694.9
      2758369.59     10027903.51      2758419.17     10028038.17
      2758868.01     10028100.45      2759083.35     10028320.85
      2759415.92     10028884.78      2759578.47     10029313.73

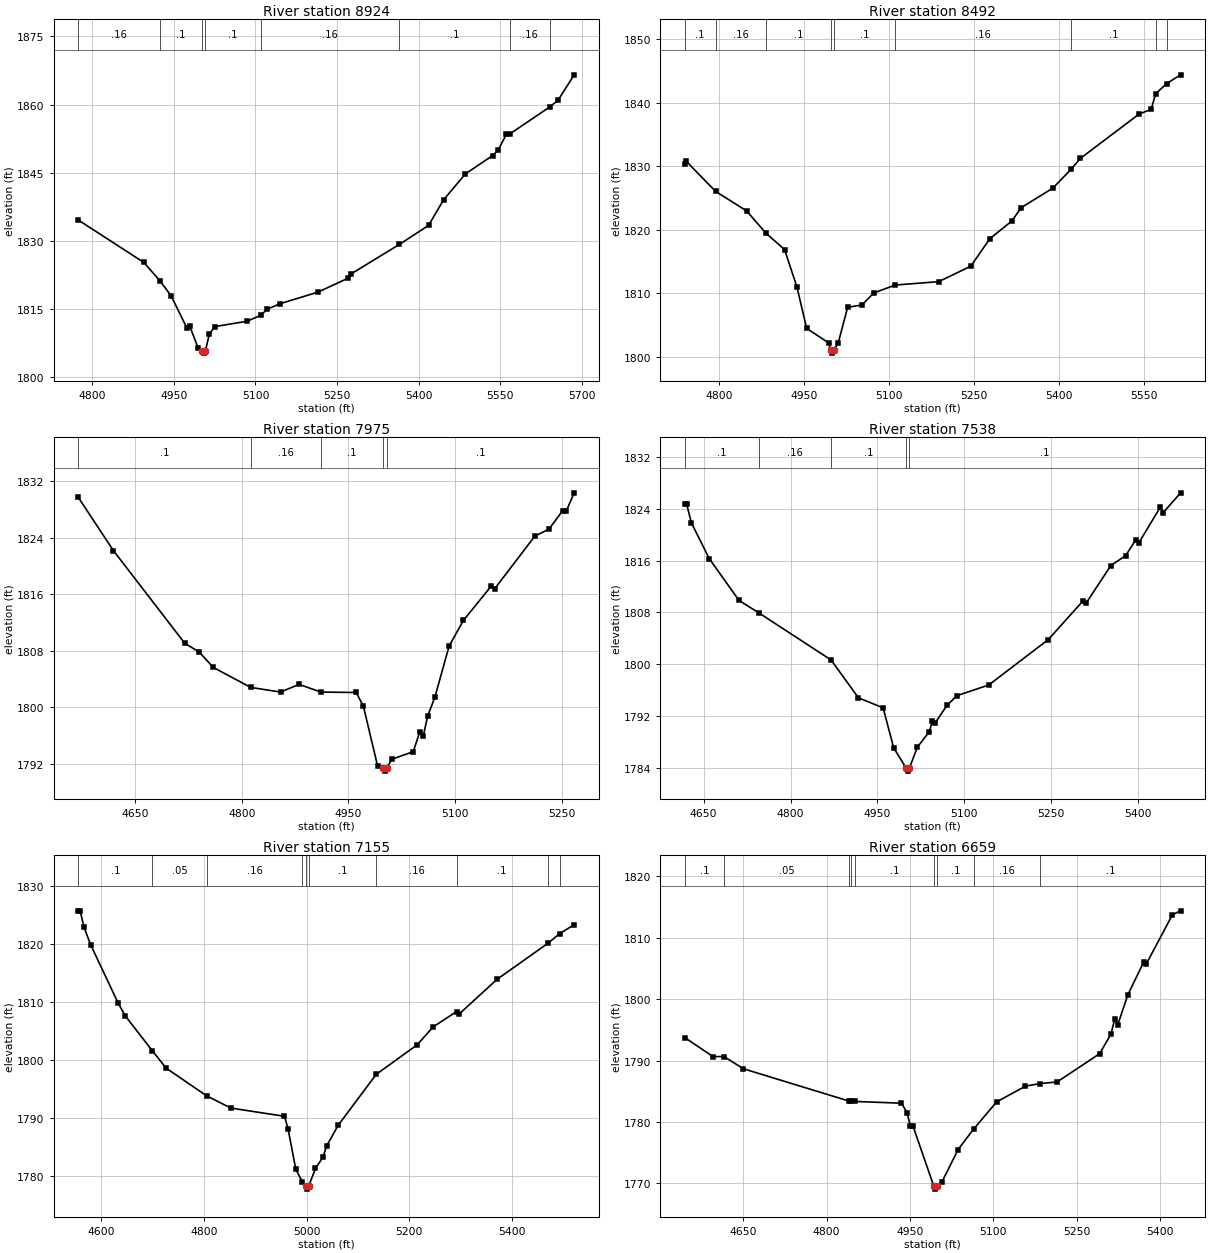
Type RM Length L Ch R = 1 ,8924    ,432,432,432
BEGIN DESCRIPTION:
UNT 1018 IN HEWA 20.0
END DESCRIPTION:
XS GIS Cut Line= 2
      2756298.27      10022442.7      2757208.03      10022380.2
#Sta/Elev= 30
  4774.2 1834.57  4894.7 1825.24  4924.6 1821.15  4944.8  1817.9  4973.9  1810.8
  4978.9 1811.26  4994.9 1806.31  5001.9 1805.78  5004.7 1805.28  5007.9 1805.78
    5015 1809.43    5025 1811.11  5085.1 1812.31  5109.4 1813.61    5122 1814.97
  5145.3 1816.16  5215.4 1818.73  5270.2 1821.77  5275.6  1822.7  5364.7 1829.21
  5418.3  1833.4    5446 1839.03  5486.1 1844.74  5536.2 1848.77  5546.2 1849.97
  5561.4 1853.44  5568.8 1853.61  5641.8 1859.52  5656.5 1860.94  5686.1 1866.54
#Mann= 8 ,-1 , 0
  4774.2     .16       0  4924.6      .1       0  5001.9     .07       0
  5007.9      .1       0  5109.4     .16       0  5364.7      .1       0
  5568.8     .16       0  5641.8      .1       0
Bank Sta=5001.9,5007.9
XS Rating Curve= 0 ,0
Exp/Cntr=0.3,0.1

Type RM Length L Ch R = 1 ,8492    ,517,517,517
BEGIN DESCRIPTION:
UNT 1018 IN HEWA 19.0
END DESCRIPTION:
XS GIS Cut Line= 2
       2756298.3     10022928.81      2757138.55     10022685.76
#Sta/Elev= 30
  4739.9 1830.32  4742.7 1830.75  4794.2 1826.03  4848.8 1822.97  4882.8 1819.48
    4916 1816.86  4937.9 1810.92  4954.8 1804.47  4993.6 1802.19  4997.3 1801.07
  5000.1 1800.57  5003.3 1801.07  5010.7 1802.22  5027.2 1807.79  5052.4 1808.15
  5073.2 1810.04  5111.2 1811.29  5187.7 1811.82  5244.5 1814.26  5278.1 1818.59
  5316.9 1821.37  5333.4 1823.47  5389.3 1826.55  5421.2  1829.5  5437.5 1831.21
  5541.6 1838.22  5562.5 1838.93  5570.7 1841.41  5589.9 1843.01  5614.6 1844.38
#Mann= 9 ,-1 , 0
  4739.9      .1       0  4794.2     .16       0  4882.8      .1       0
  4997.3     .07       0  5003.3      .1       0  5111.2     .16       0
  5421.2      .1       0  5570.7     .16       0  5589.9      .1       0
Bank Sta=4997.3,5003.3
XS Rating Curve= 0 ,0
Exp/Cntr=0.3,0.1

Type RM Length L Ch R = 1 ,7975    ,437,437,437
BEGIN DESCRIPTION:
UNT 1018 IN HEWA 18.0
END DESCRIPTION:
XS GIS Cut Line= 2
      2756299.37     10023210.52      2756993.61     10023279.95
#Sta/Elev= 30
    4570 1829.73  4619.3 1822.21  4719.8 1809.08  4739.9 1807.86    4760 1805.66
  4812.6 1802.84  4854.5 1802.18  4880.6 1803.27  4911.3 1802.18    4961 1802.12
  4971.1 1800.19  4991.2 1791.68  4998.2 1791.49    5001 1790.99  5004.2 1791.49
  5011.3 1792.68  5041.4 1793.75  5050.5 1796.59  5055.5 1795.99  5061.5 1798.78
  5071.6 1801.42  5091.7 1808.68  5111.8 1812.31    5151 1817.18    5156 1816.82
  5212.3 1824.24  5232.4 1825.26  5251.5 1827.84  5256.5 1827.77  5267.7 1830.38
#Mann= 5 ,-1 , 0
    4570      .1       0  4812.6     .16       0  4911.3      .1       0
  4998.2     .07       0  5004.2      .1       0
Bank Sta=4998.2,5004.2
XS Rating Curve= 0 ,0
Exp/Cntr=0.3,0.1

Type RM Length L Ch R = 1 ,7538    ,383,383,383
BEGIN DESCRIPTION:
UNT 1018 IN HEWA 17.0
END DESCRIPTION:
XS GIS Cut Line= 2
      2756277.44     10023581.58      2757110.86     10023776.04
#Sta/Elev= 30
  4617.5 1824.79  4620.6 1824.79  4628.8 1821.86  4659.6 1816.33    4711 1809.86
  4745.6 1807.91  4869.9 1800.65  4917.3 1794.79  4959.8 1793.25    4978 1787.07
  4999.3 1783.96  5002.1 1783.46  5005.3 1783.96    5019 1787.18  5039.6 1789.56
  5044.9 1791.26    5050 1790.97  5070.4 1793.67  5087.4 1795.13  5142.2 1796.78
  5244.9  1803.8  5305.3 1809.83  5310.4 1809.47  5352.9 1815.25  5378.4 1816.77
  5395.5 1819.18  5400.6 1818.67    5438 1824.24  5443.2 1823.43  5473.3 1826.49
#Mann= 5 ,-1 , 0
  4617.5      .1       0  4745.6     .16       0  4869.9      .1       0
  4999.3     .07       0  5005.3      .1       0
Bank Sta=4999.3,5005.3
XS Rating Curve= 0 ,0
Exp/Cntr=0.3,0.1

Type RM Length L Ch R = 1 ,7155    ,496,496,496
BEGIN DESCRIPTION:
UNT 1018 IN HEWA 16.0
END DESCRIPTION:
XS GIS Cut Line= 2
      2756187.21     10023831.59      2757041.38     10024282.98
#Sta/Elev= 30
  4555.4 1825.72  4558.9 1825.72  4566.6 1822.87  4579.4 1819.87  4632.6 1809.89
  4647.3 1807.56  4699.5 1801.62  4726.5 1798.61  4805.3 1793.84  4852.7 1791.73
  4957.1 1790.31    4964 1788.18  4979.1 1781.18  4991.8 1779.03  4998.2 1778.26
  5000.9 1777.76  5004.2 1778.26  5017.5 1781.33  5031.9 1783.25  5039.5 1785.25
  5061.5 1788.74  5135.8 1797.54  5215.6 1802.63  5246.8 1805.72  5292.4 1808.36
    5298 1807.98  5371.2 1813.91  5470.1 1820.11  5493.3 1821.79  5521.5 1823.33
#Mann= 10 ,-1 , 0
  4555.4      .1       0  4699.5     .05       0  4805.3     .16       0
  4991.8      .1       0  4998.2     .07       0  5004.2      .1       0
  5135.8     .16       0  5292.4      .1       0  5470.1     .16       0
  5493.3      .1       0
Bank Sta=4998.2,5004.2
XS Rating Curve= 0 ,0
Exp/Cntr=0.3,0.1

Type RM Length L Ch R = 1 ,6659    ,419,419,419
BEGIN DESCRIPTION:
UNT 1018 IN HEWA 15.0
END DESCRIPTION:
XS GIS Cut Line= 3
      2756132.71     10024141.12       2756195.2     10024439.69
      2756771.56     10024550.79
#Sta/Elev= 30
  4544.8 1793.75  4595.4 1790.67  4615.4 1790.65  4650.4 1788.67  4840.1 1783.42
  4843.2 1783.48  4851.6 1783.35  4934.6 1783.07  4944.8 1781.52  4950.2 1779.43
  4955.3 1779.36  4992.7 1769.58  4995.5 1769.08  4998.7 1769.58  5007.1 1770.19
  5036.5 1775.53  5064.2 1778.83  5105.8 1783.28  5157.7 1785.85  5184.6 1786.27
  5214.6 1786.53  5291.1 1791.13  5311.4 1794.31  5318.4 1796.81  5323.5 1795.79
    5342 1800.74  5370.3 1806.04  5375.4 1805.81  5422.1 1813.76  5436.8 1814.39
#Mann= 9 ,-1 , 0
  4544.8      .1       0  4615.4     .05       0  4840.1      .1       0
  4843.2     .16       0  4851.6      .1       0  4992.7     .07       0
  4998.7      .1       0  5064.2     .16       0  5184.6      .1       0
Bank Sta=4992.7,4998.7
XS Rating Curve= 0 ,0
Exp/Cntr=0.3,0.1

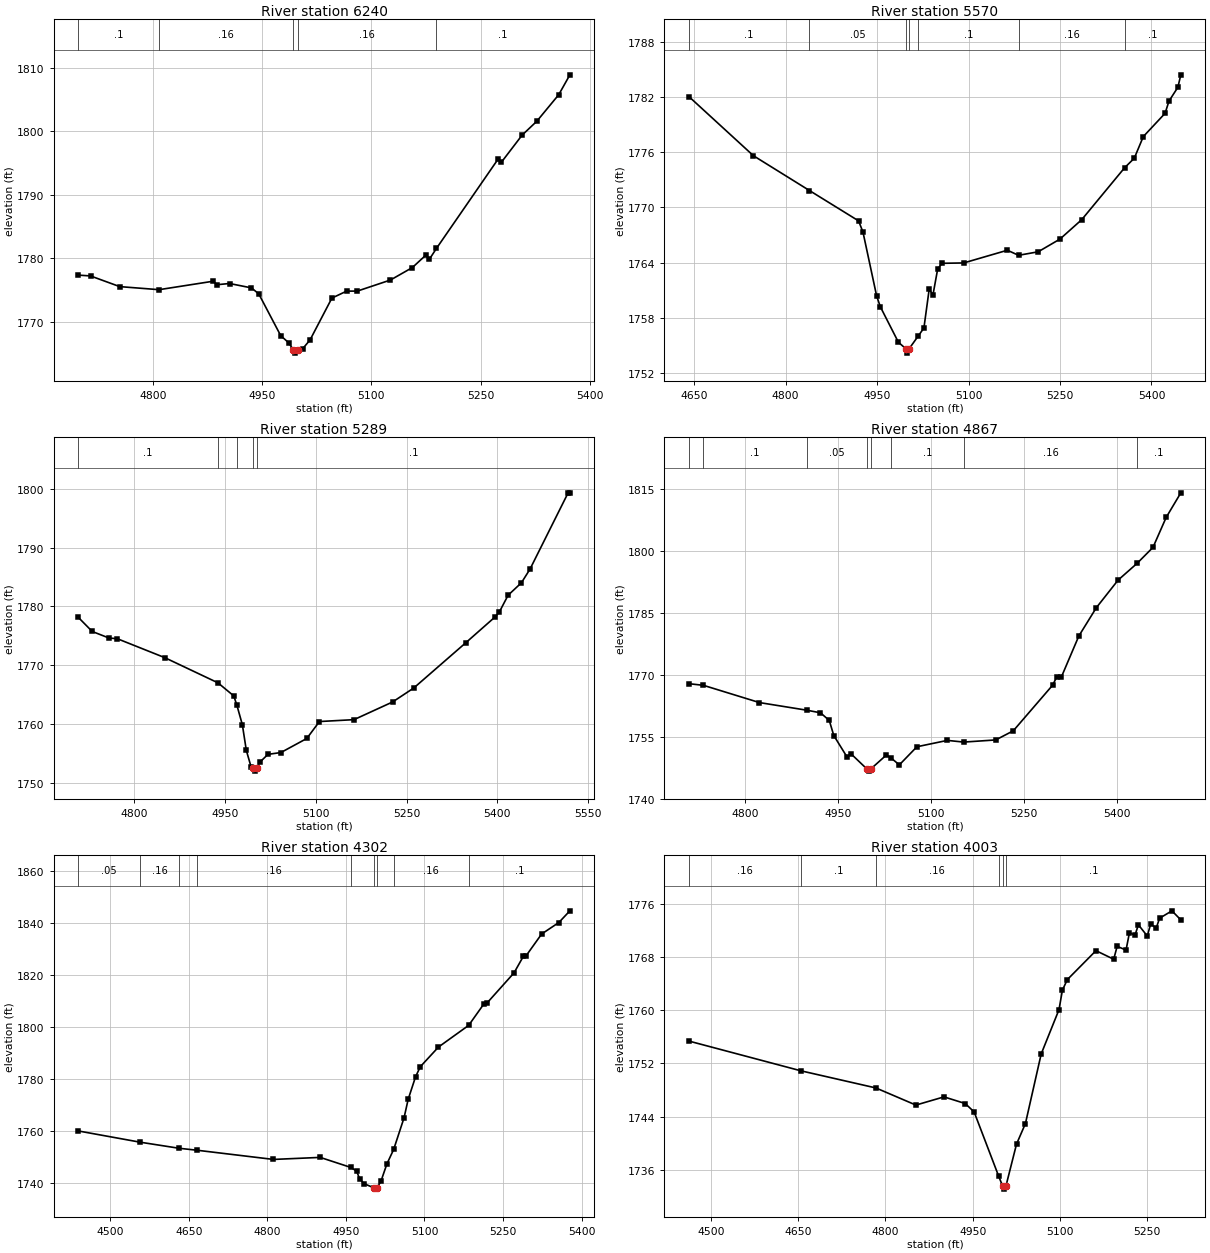
Type RM Length L Ch R = 1 ,6240    ,670,670,670
BEGIN DESCRIPTION:
UNT 1018 IN HEWA 14.0
END DESCRIPTION:
XS GIS Cut Line= 2
      2756021.55     10024849.41      2756693.69      10024918.7
#Sta/Elev= 30
  4697.1 1777.38  4714.1 1777.25  4754.3 1775.57  4808.3 1775.09  4882.8 1776.42
  4887.8 1775.87  4905.1 1776.06  4935.3 1775.37  4945.3 1774.43  4975.5 1767.86
  4986.8 1766.71  4992.6 1765.62  4995.3 1765.12  4998.6 1765.62  5005.6 1765.81
  5015.7 1767.18  5045.8 1773.77    5066 1774.86  5080.8 1774.87  5126.3 1776.61
  5156.4 1778.57  5174.8 1780.51  5179.8 1779.88  5189.5 1781.58  5273.8 1795.55
  5278.8 1795.13  5307.2 1799.38  5327.3 1801.55  5357.5 1805.73  5372.8 1808.85
#Mann= 5 ,-1 , 0
  4697.1      .1       0  4808.3     .16       0  4992.6     .07       0
  4998.6     .16       0  5189.5      .1       0
Bank Sta=4992.6,4998.6
XS Rating Curve= 0 ,0
Exp/Cntr=0.3,0.1

Type RM Length L Ch R = 1 ,5570    ,281,281,281
BEGIN DESCRIPTION:
UNT 1018 IN HEWA 13.0
END DESCRIPTION:
XS GIS Cut Line= 2
      2756035.48     10025738.31      2756694.31     10025273.66
#Sta/Elev= 30
  4641.9 1782.02  4747.4 1775.61  4839.2 1771.83  4919.8 1768.53    4927 1767.31
  4949.4 1760.37  4955.5 1759.19  4985.1 1755.34  4996.9 1754.66  4999.7 1754.16
  5002.9 1754.66  5017.8 1756.04  5026.9 1756.89  5035.6 1761.13  5041.7 1760.47
  5049.4 1763.28  5056.5 1763.92  5092.2 1763.96  5163.7 1765.34  5182.1 1764.79
  5214.2 1765.17  5249.9 1766.55  5285.6 1768.66  5355.9  1774.3  5371.8 1775.34
  5386.6 1777.69  5422.3 1780.22  5428.7 1781.55  5443.2 1783.04  5448.1  1784.4
#Mann= 7 ,-1 , 0
  4641.9      .1       0  4839.2     .05       0  4996.9    .035       0
  5002.9     .05       0  5017.8      .1       0  5182.1     .16       0
  5355.9      .1       0
Bank Sta=4996.9,5002.9
XS Rating Curve= 0 ,0
Exp/Cntr=0.3,0.1

Type RM Length L Ch R = 1 ,5289    ,422,422,422
BEGIN DESCRIPTION:
UNT 1018 IN HEWA 12.0
END DESCRIPTION:
XS GIS Cut Line= 2
      2756229.93     10025967.46      2756847.96     10025439.71
#Sta/Elev= 30
  4707.1 1778.16  4730.4 1775.73  4757.8 1774.63  4772.1 1774.49  4850.1 1771.29
  4938.2    1767  4964.3 1764.78  4969.4 1763.22  4978.5 1759.88  4985.1  1755.5
  4992.8 1752.76  4996.4 1752.49  4999.1 1751.99  5002.4 1752.49  5007.1 1753.48
  5020.8 1754.84  5042.2 1755.15    5085 1757.54  5105.9 1760.42    5163 1760.74
  5226.7 1763.74  5261.8 1766.12  5347.4 1773.78  5396.8 1778.26  5403.4 1779.08
  5417.7 1781.89  5439.7 1784.01  5453.9 1786.33  5516.9  1799.3  5519.8  1799.3
#Mann= 5 ,-1 , 0
  4707.1      .1       0  4938.2     .05       0  4969.4      .1       0
  4996.4     .07       0  5002.4      .1       0
Bank Sta=4996.4,5002.4
XS Rating Curve= 0 ,0
Exp/Cntr=0.3,0.1

Type RM Length L Ch R = 1 ,4867    ,565,565,565
BEGIN DESCRIPTION:
UNT 1018 IN HEWA 11.0
END DESCRIPTION:
XS GIS Cut Line= 2
      2756593.33     10026189.22      2757176.05     10025648.13
#Sta/Elev= 30
  4708.8 1767.83    4732 1767.44  4822.6 1763.27  4899.4 1761.42  4921.3  1760.8
  4935.5 1758.95  4942.8 1755.31  4963.8 1750.22  4971.2 1750.81  4996.5  1747.2
  4999.3  1746.7  5002.5  1747.2  5027.8 1750.59  5035.6 1749.86  5048.8 1748.21
  5077.2 1752.59  5126.5 1754.13  5152.9 1753.72  5204.7 1754.24  5233.1 1756.45
  5296.6 1767.46  5303.4 1769.47  5310.7  1769.4  5339.1 1779.37  5367.4 1786.21
  5402.6 1792.88  5433.4 1796.94    5459 1800.79  5480.3 1808.03    5504 1813.97
#Mann= 8 ,-1 , 0
  4708.8     .05       0    4732      .1       0  4899.4     .05       0
  4996.5    .035       0  5002.5     .05       0  5035.6      .1       0
  5152.9     .16       0  5433.4      .1       0
Bank Sta=4996.5,5002.5
XS Rating Curve= 0 ,0
Exp/Cntr=0.3,0.1

Type RM Length L Ch R = 1 ,4302    ,299,299,299
BEGIN DESCRIPTION:
UNT 1018 IN HEWA 10.0
END DESCRIPTION:
XS GIS Cut Line= 3
      2756891.92     10026314.24      2757239.15      10026168.4
      2757468.32      10025654.5
#Sta/Elev= 30
  4438.5 1760.11  4556.6  1755.8  4631.1 1753.46  4665.6  1752.7  4811.6 1749.17
  4900.9 1749.95  4958.9 1746.13  4970.5  1744.7    4976 1741.77  4984.5 1739.88
  5003.4 1738.27  5006.1 1737.77  5009.4 1738.27    5017 1740.84  5028.3 1747.45
  5041.3 1753.05  5061.1  1765.2  5068.9 1772.23    5083 1780.88  5092.1 1784.76
  5126.8 1792.31  5184.5 1800.64  5213.7 1808.91  5219.2 1809.14  5271.1 1820.78
  5288.9 1827.12  5294.4 1827.41  5323.9 1835.71  5356.7 1840.11  5377.8  1844.6
#Mann= 9 ,-1 , 0
  4438.5     .05       0  4556.6     .16       0  4631.1     .05       0
  4665.6     .16       0  4958.9      .1       0  5003.4     .07       0
  5009.4      .1       0  5041.3     .16       0  5184.5      .1       0
Bank Sta=5003.4,5009.4
XS Rating Curve= 0 ,0
Exp/Cntr=0.3,0.1

Type RM Length L Ch R = 1 ,4003    ,463,463,463
BEGIN DESCRIPTION:
UNT 1018 IN HEWA 9.0
END DESCRIPTION:
XS GIS Cut Line= 2
      2757028.52     10026529.98      2757743.54     10026078.75
#Sta/Elev= 30
  4462.4 1755.35  4654.8 1750.89  4783.6 1748.32  4852.4 1745.75  4900.7 1746.98
  4937.2 1745.98  4952.5 1744.72  4994.5 1735.12  5001.3 1733.63    5004 1733.13
  5007.3 1733.63  5025.4 1739.89  5040.7 1742.97  5067.8 1753.42  5098.4 1760.07
  5104.3    1763  5112.7 1764.58    5162 1768.93  5192.5 1767.64  5198.4 1769.58
  5213.7 1769.02  5219.6 1771.65    5229 1771.22  5234.9 1772.82  5250.2 1771.13
  5256.1 1772.95  5265.5 1772.31  5271.4  1773.8  5292.6 1774.91  5307.9 1773.55
#Mann= 6 ,-1 , 0
  4462.4     .16       0  4654.8      .1       0  4783.6     .16       0
  4994.5      .1       0  5001.3     .07       0  5007.3      .1       0
Bank Sta=5001.3,5007.3
XS Rating Curve= 0 ,0
Exp/Cntr=0.3,0.1

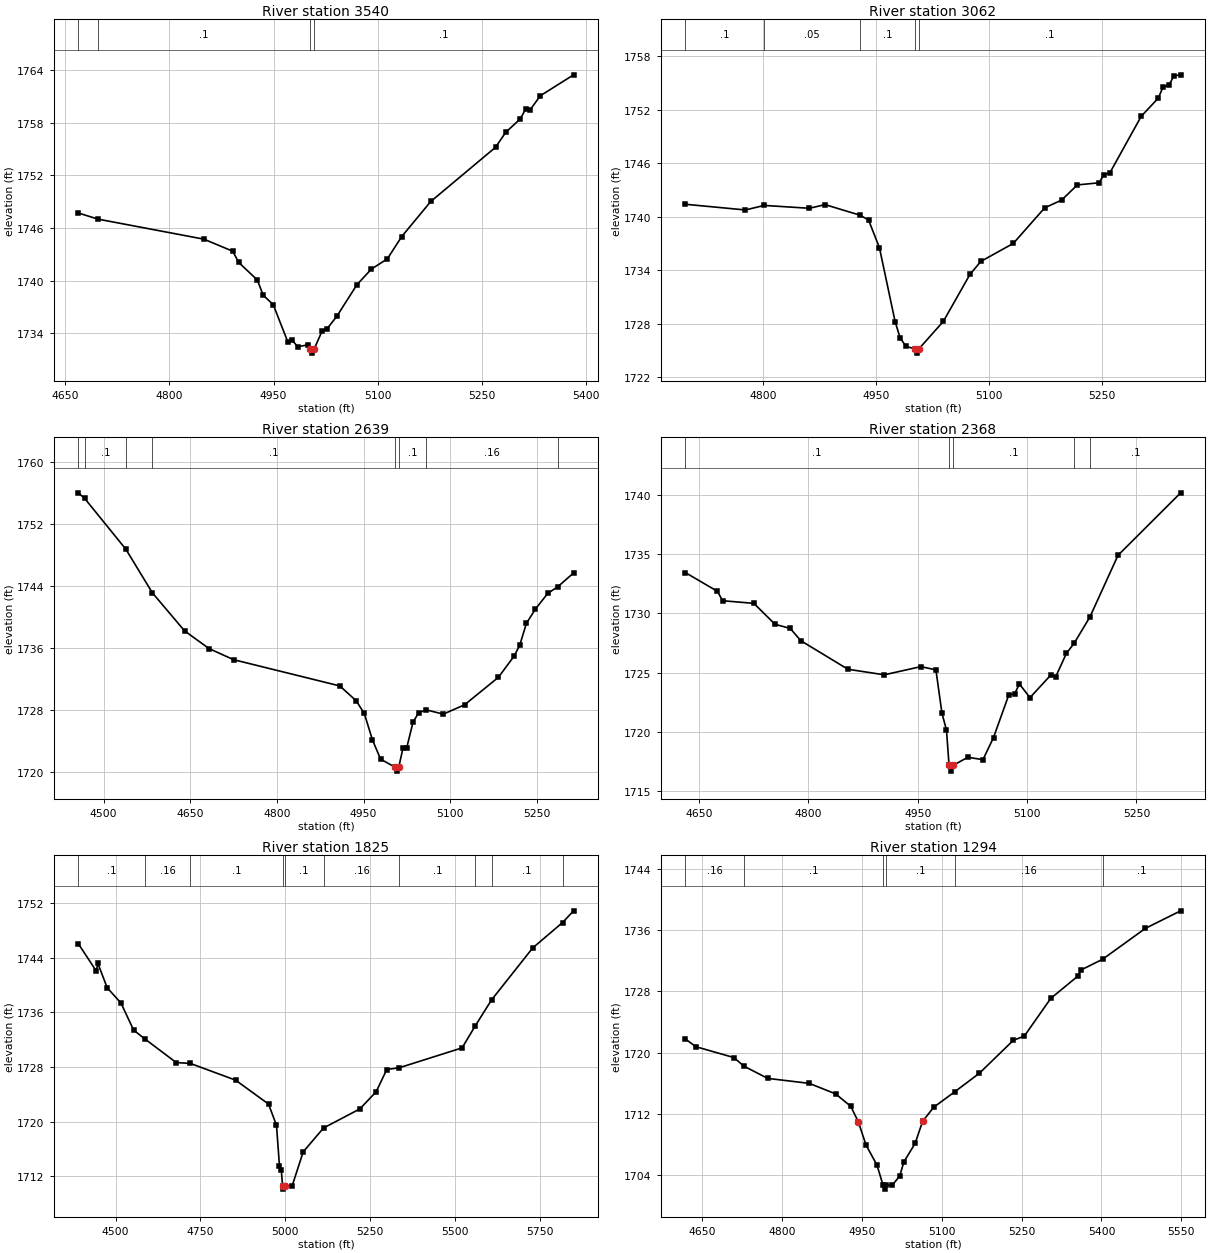
Type RM Length L Ch R = 1 ,3540    ,478,478,478
BEGIN DESCRIPTION:
UNT 1018 IN HEWA 8.0
END DESCRIPTION:
XS GIS Cut Line= 2
      2757313.25     10026891.09      2757882.69     10026460.53
#Sta/Elev= 30
  4668.6 1747.72  4696.8 1747.02  4849.6 1744.73  4891.3 1743.35  4899.6 1742.09
  4926.7 1740.06    4935 1738.34  4949.5 1737.26  4970.4 1733.04  4976.6 1733.22
  4984.9 1732.44  4999.5 1732.67  5002.7 1732.22  5005.5 1731.72  5008.7 1732.22
  5020.3  1734.3  5026.6 1734.45  5041.1 1735.91  5070.2 1739.53  5091.1 1741.32
  5113.9 1742.47  5134.8 1745.03  5176.6 1749.03    5270 1755.22  5284.6 1756.92
  5305.4 1758.44  5313.7 1759.61    5320 1759.51  5334.5  1761.1  5382.5 1763.49
#Mann= 4 ,-1 , 0
  4668.6     .16       0  4696.8      .1       0  5002.7     .07       0
  5008.7      .1       0
Bank Sta=5002.7,5008.7
XS Rating Curve= 0 ,0
Exp/Cntr=0.3,0.1

Type RM Length L Ch R = 1 ,3062    ,423,423,423
BEGIN DESCRIPTION:
UNT 1018 IN HEWA 7.0
END DESCRIPTION:
XS GIS Cut Line= 2
       2757625.8     10027252.16      2758139.66     10026842.46
#Sta/Elev= 30
  4696.7  1741.4  4776.4 1740.76  4801.3 1741.27  4861.3 1740.95  4882.1 1741.36
  4928.6 1740.17  4939.8 1739.63  4954.2 1736.53    4975 1728.24  4981.5 1726.44
  4989.4 1725.44  5000.8 1725.19  5003.6 1724.69  5006.8 1725.19    5039 1728.25
  5074.3 1733.52  5088.7 1734.98  5131.9 1737.01  5173.5    1741    5196 1741.87
  5216.8 1743.57  5245.6 1743.81    5252 1744.72    5260 1744.93  5301.7 1751.29
  5324.1  1753.3  5330.5 1754.55  5338.5 1754.77  5344.9 1755.82  5353.9 1755.93
#Mann= 5 ,-1 , 0
  4696.7      .1       0  4801.3     .05       0  4928.6      .1       0
  5000.8     .07       0  5006.8      .1       0
Bank Sta=5000.8,5006.8
XS Rating Curve= 0 ,0
Exp/Cntr=0.3,0.1

Type RM Length L Ch R = 1 ,2639    ,271,271,271
BEGIN DESCRIPTION:
UNT 1018 IN HEWA 6.0
END DESCRIPTION:
XS GIS Cut Line= 3
      2757768.43     10027753.77      2758168.47     10027353.73
      2758418.48     10027203.72
#Sta/Elev= 30
  4456.3 1756.06  4467.4 1755.33  4538.7 1748.77  4584.4 1743.16  4640.2 1738.24
  4682.6 1735.95    4725 1734.52  4908.9 1731.13  4937.2 1729.22  4951.3 1727.58
  4965.5 1724.14  4979.6 1721.67  5004.9 1720.63  5007.6 1720.13  5010.9 1720.63
  5018.5 1723.18  5024.9 1723.18  5035.6 1726.44  5045.4 1727.67  5058.3 1728.04
  5088.1 1727.49    5125  1728.7  5183.4 1732.24  5210.6 1734.98  5220.3 1736.37
  5231.9 1739.21  5247.5 1741.05  5268.9 1743.08  5286.3 1743.94  5313.6 1745.72
#Mann= 8 ,-1 , 0
  4456.3     .05       0  4467.4      .1       0  4538.7     .05       0
  4584.4      .1       0  5004.9     .07       0  5010.9      .1       0
  5058.3     .16       0  5286.3      .1       0
Bank Sta=5004.9,5010.9
XS Rating Curve= 0 ,0
Exp/Cntr=0.3,0.1

Type RM Length L Ch R = 1 ,2368    ,543,543,543
BEGIN DESCRIPTION:
UNT 1018 IN HEWA 5.0
END DESCRIPTION:
XS GIS Cut Line= 2
       2758007.7     10027814.69      2758549.39     10027404.95
#Sta/Elev= 30
  4631.4 1733.45  4675.3 1731.87  4682.5 1731.07  4725.3 1730.85  4754.4 1729.08
  4775.2 1728.73  4789.8 1727.69  4854.3 1725.28  4904.2 1724.81  4954.2  1725.5
    4975 1725.23  4983.3 1721.56  4989.5 1720.13    4993 1717.17  4995.7 1716.67
    4999 1717.17  5018.7 1717.84  5039.5 1717.64    5054 1719.51  5074.9 1723.11
  5083.2 1723.22  5089.4 1724.04    5104 1722.88  5133.1 1724.83  5139.4 1724.66
  5153.9 1726.62  5164.5 1727.47  5186.2  1729.7  5224.7 1734.91  5310.6 1740.19
#Mann= 5 ,-1 , 0
  4631.4      .1       0    4993     .07       0    4999      .1       0
  5164.5     .16       0  5186.2      .1       0
Bank Sta=4993,4999
XS Rating Curve= 0 ,0
Exp/Cntr=0.3,0.1

Type RM Length L Ch R = 1 ,1825    ,531,531,531
BEGIN DESCRIPTION:
UNT 1018 IN HEWA 4.0
END DESCRIPTION:
XS GIS Cut Line= 3
      2758004.81     10028168.41      2758421.44     10028246.53
      2758733.42     10027258.61
#Sta/Elev= 30
  4390.3 1746.06  4443.1 1742.07  4448.1 1743.16  4475.4 1739.61  4516.1 1737.37
  4553.3 1733.41    4588 1732.06  4678.9 1728.66  4720.7 1728.53    4854 1726.08
    4951 1722.58  4974.4 1719.48  4983.3 1713.51  4988.6 1712.91  4992.4 1710.63
  4995.1 1710.13  4998.4 1710.63  5020.9 1710.65  5053.2 1715.59  5113.1 1719.08
  5220.1 1721.87  5268.1 1724.38  5299.5 1727.64  5336.4  1727.9  5521.6 1730.81
  5560.3 1734.03  5608.5 1737.84  5729.5 1745.43  5817.7 1749.16  5850.2 1750.87
#Mann= 10 ,-1 , 0
  4390.3      .1       0    4588     .16       0  4720.7      .1       0
  4992.4     .07       0  4998.4      .1       0  5113.1     .16       0
  5336.4      .1       0  5560.3     .16       0  5608.5      .1       0
  5817.7     .16       0
Bank Sta=4992.4,4998.4
XS Rating Curve= 0 ,0
Exp/Cntr=0.3,0.1

Type RM Length L Ch R = 1 ,1294    ,395,395,395
BEGIN DESCRIPTION:
UNT 1018 IN HEWA 3.0
END DESCRIPTION:
XS GIS Cut Line= 2
      2758666.34     10028449.66      2759374.07     10027846.01
#Sta/Elev= 30
  4618.5 1721.79  4638.2 1720.78  4709.6 1719.36  4728.4 1718.24  4773.2 1716.64
  4851.2 1715.99  4900.6 1714.62  4929.1    1713  4943.4 1710.96  4957.7 1707.96
  4978.5  1705.3  4989.8 1702.68  4992.6 1702.18  4995.8 1702.68  5007.1 1702.69
  5021.4 1703.93  5028.7 1705.71  5049.9 1708.14  5064.2 1711.05  5085.1 1712.88
  5124.6  1714.9  5170.7 1717.31  5234.4 1721.61  5255.2 1722.17  5304.8 1727.09
  5355.2 1729.97  5361.7  1730.8    5402 1732.19  5482.5 1736.23  5548.7 1738.52
#Mann= 6 ,-1 , 0
  4618.5     .16       0  4728.4      .1       0  4989.8     .07       0
  4995.8      .1       0  5124.6     .16       0    5402      .1       0
Bank Sta=4943.4,5064.2
XS Rating Curve= 0 ,0
Exp/Cntr=0.3,0.1

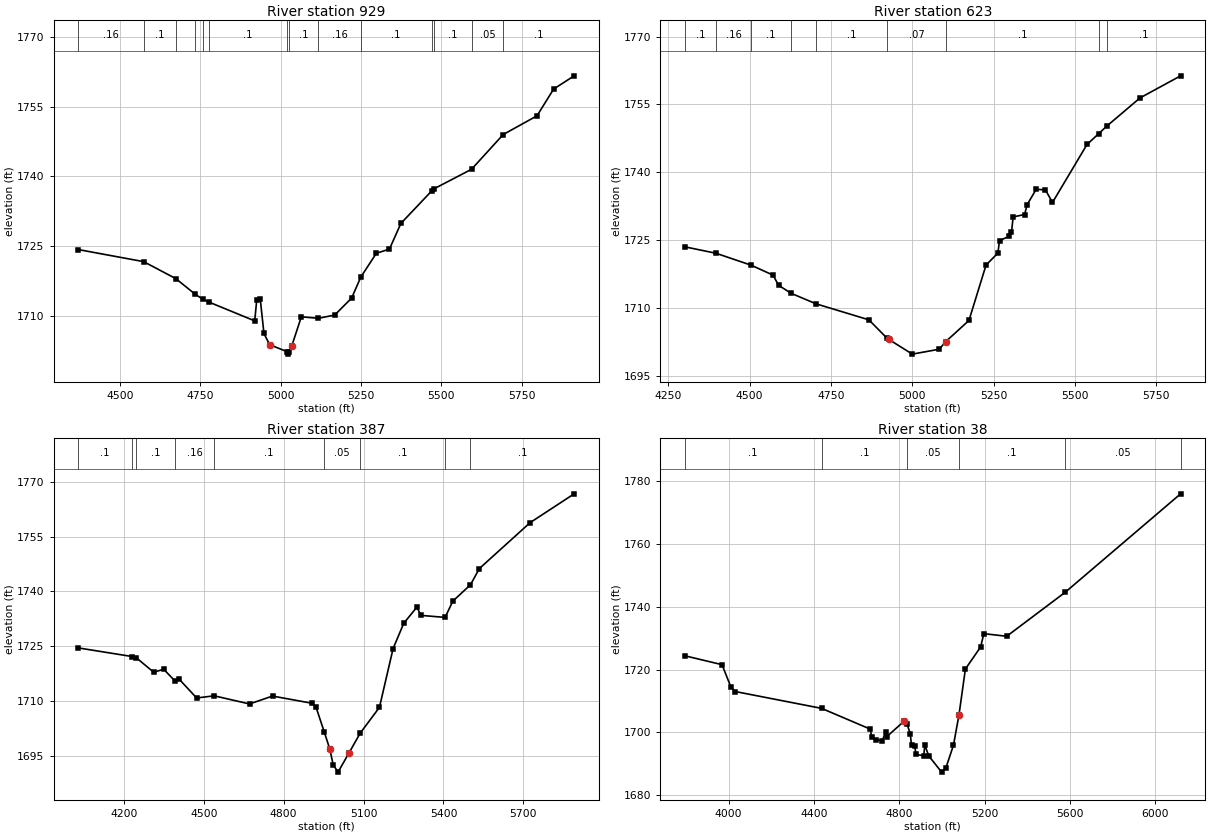
Type RM Length L Ch R = 1 ,929     ,306,306,306
BEGIN DESCRIPTION:
UNT 1018 IN HEWA 2.0
END DESCRIPTION:
XS GIS Cut Line= 4
      2758579.08     10028495.75      2758948.05      10028586.9
      2759369.06     10028400.27      2760050.51     10028226.65
#Sta/Elev= 30
  4369.7 1724.25  4572.9 1721.66  4673.4    1718  4733.4 1714.65    4757  1713.6
  4776.3 1712.96  4918.9 1708.92  4925.2 1713.44  4936.2 1713.59  4947.6 1706.21
  4965.4  1703.8  5020.7 1702.27  5023.4 1701.77  5026.7 1702.27  5034.6  1703.6
    5064 1709.79  5117.2 1709.48    5168 1710.17  5220.8 1713.84  5249.1 1718.32
  5297.5 1723.45  5338.3 1724.35  5374.1 1729.88  5469.7 1736.84  5478.1 1737.35
    5594 1741.52  5692.5 1748.98  5797.9 1753.02  5849.5 1758.76  5913.5 1761.61
#Mann= 14 ,-1 , 0
  4369.7     .16       0  4572.9      .1       0  4673.4     .16       0
  4733.4      .1       0    4757     .16       0  4776.3      .1       0
  5020.7     .07       0  5026.7      .1       0  5117.2     .16       0
  5249.1      .1       0  5469.7     .05       0  5478.1      .1       0
    5594     .05       0  5692.5      .1       0
Bank Sta=4965.4,5034.6
XS Rating Curve= 0 ,0
Exp/Cntr=0.3,0.1

Type RM Length L Ch R = 1 ,623     ,236,236,236
BEGIN DESCRIPTION:
Mapping XS 23af85a6
END DESCRIPTION:
XS GIS Cut Line= 4
      2758687.61     10028578.21        2759126.     10028799.58
       2759664.2     10028669.37      2760019.78     10028348.48
#Sta/Elev= 30
    4301 1723.49  4396.7 1722.07  4504.8 1719.43  4572.4 1717.22  4589.1 1714.98
  4627.9  1713.2  4704.7 1710.87  4866.7 1707.34  4923.3 1703.21  4928.4 1702.99
  5000.2 1699.75  5082.7 1700.83  5103.3 1702.54  5174.3  1707.2  5226.8 1719.45
  5263.1  1722.1  5268.3 1724.88  5298.8 1725.83    5305 1726.69  5310.1  1730.1
  5345.5 1730.64  5352.6 1732.76    5381 1736.22  5409.3 1736.08    5431  1733.3
  5537.1 1746.13  5572.9 1748.52  5598.5 1750.23    5700 1756.43  5824.8 1761.32
#Mann= 9 ,-1 , 0
    4301      .1       0  4396.7     .16       0  4504.8      .1       0
  4627.9     .16       0  4704.7      .1       0  4923.3     .07       0
  5103.3      .1       0  5572.9     .05       0  5598.5      .1       0
Bank Sta=4928.4,5103.3
XS Rating Curve= 0 ,0
Exp/Cntr=0.3,0.1

Type RM Length L Ch R = 1 ,387     ,309,309,309
BEGIN DESCRIPTION:
Mapping XS 504db6d3
END DESCRIPTION:
XS GIS Cut Line= 4
      2758587.77      10028578.2      2759308.29     10028990.55
      2759698.92     10028886.38      2760115.57     10028417.65
#Sta/Elev= 30
  4029.1 1724.51  4230.3 1722.16  4245.9 1721.87  4312.1 1717.85  4349.5 1718.67
  4393.2 1715.36  4408.5 1715.88  4473.3 1710.79    4539 1711.39  4671.9 1709.16
  4758.2 1711.32  4905.6 1709.36  4921.6 1708.27  4952.6 1701.44  4973.3 1696.79
  4985.8 1692.53  5004.1 1690.48  5045.7 1695.78  5087.1 1701.13  5159.6 1708.22
  5210.9 1724.34    5251 1731.27  5300.5 1735.71  5314.7 1733.43  5406.1 1732.87
  5435.2 1737.33  5501.5 1741.82  5534.7 1746.25  5725.3 1758.83  5890.7 1766.73
#Mann= 9 ,-1 , 0
  4029.1      .1       0  4230.3     .16       0  4245.9      .1       0
  4393.2     .16       0    4539      .1       0  4952.6     .05       0
  5087.1      .1       0  5406.1     .05       0  5501.5      .1       0
Bank Sta=4973.3,5045.7
XS Rating Curve= 0 ,0
Exp/Cntr=0.3,0.1

Type RM Length L Ch R = 1 ,38      ,0,0,0
BEGIN DESCRIPTION:
UNT 1018 IN HEWA 1.0
END DESCRIPTION:
XS GIS Cut Line= 4
      2758564.81     10028665.17      2759453.68     10029293.63
      2759689.79     10029258.91      2760259.22     10028439.49
#Sta/Elev= 30
  3794.5  1724.4  3969.1 1721.56  4010.9 1714.39  4031.8 1712.99  4435.6 1707.64
  4664.6 1701.01  4670.7 1698.51    4693 1697.48  4721.2 1697.39    4736 1700.22
  4742.1 1698.65  4822.1  1703.5  4836.9 1702.54  4851.7  1699.6  4857.8 1695.82
  4872.6 1695.64  4878.7 1692.94    4915 1692.53    4920 1695.93  4938.5 1692.48
  4998.9 1687.31  5019.3 1688.74  5054.5 1695.93    5080 1705.44  5110.3 1720.17
  5181.8 1727.22  5196.7 1731.45    5304 1730.61  5578.2 1744.63  6119.6 1776.02
#Mann= 6 ,-1 , 0
  3794.5      .1       0  4435.6      .1       0  4836.9     .05       0
    5080      .1       0  5578.2     .05       0  6119.6      .1       0
Bank Sta=4822.1,5080
XS Rating Curve= 0 ,0
Exp/Cntr=0.3,0.1

Chan Stop Cuts=-1
Use User Specified Reach Order=0
Composite Channel Slope=5