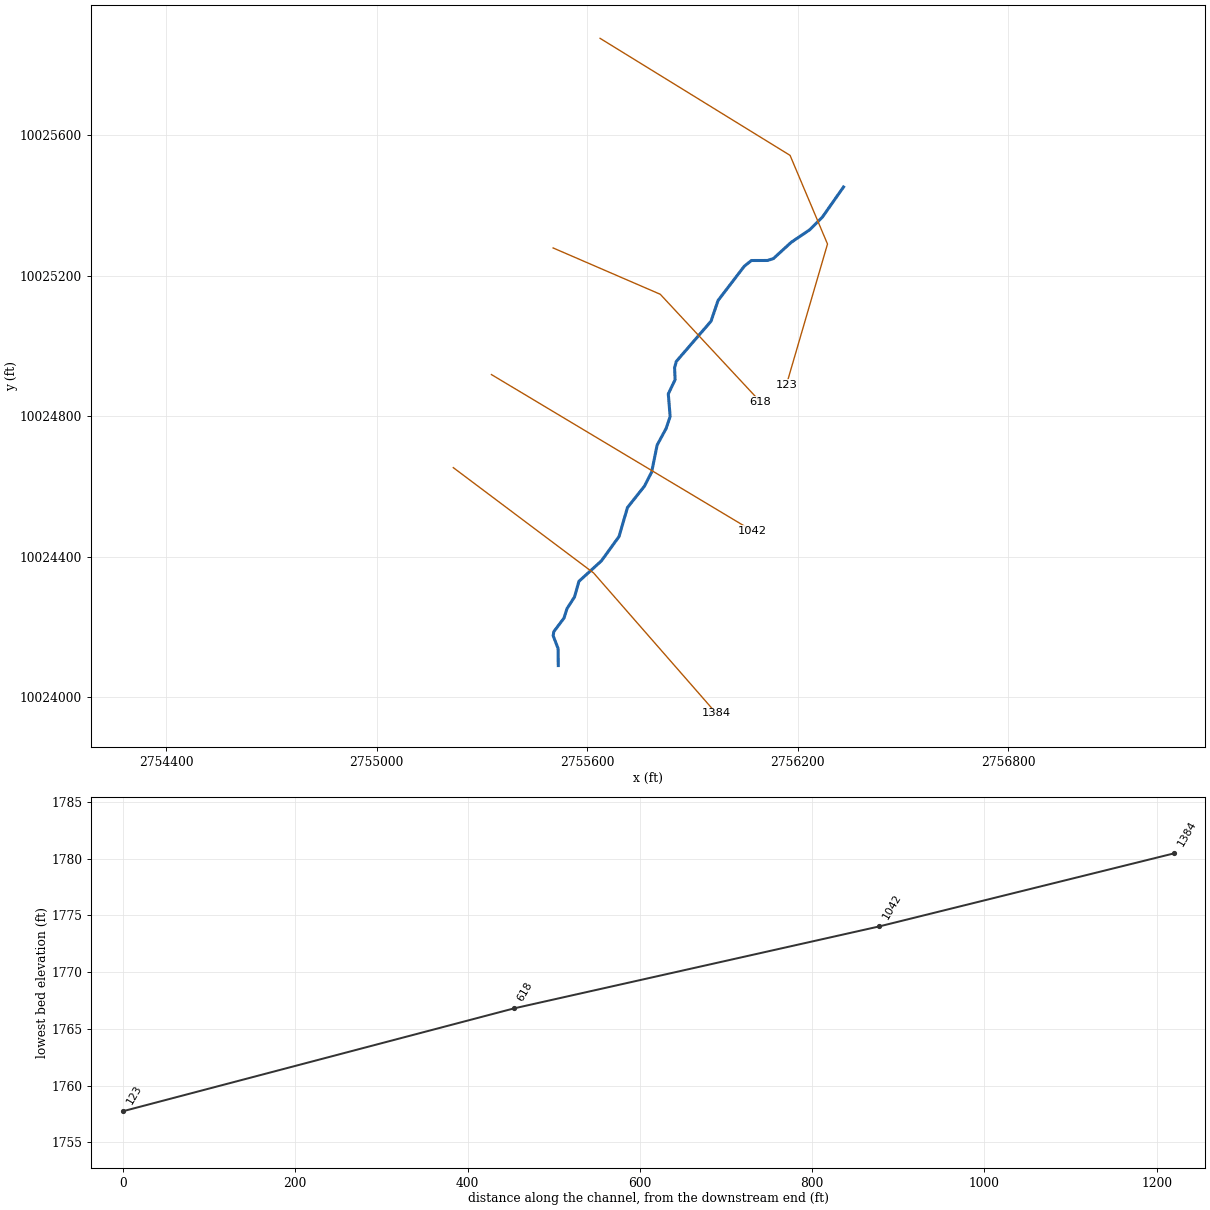
--- UNT 1019 IN HEWA.prj (project) ---

Proj Title=UNT 1019 IN HEWA Base Level Engineering
Current Plan=p01
Default Exp/Contr=0.3,0.1
English Units
Geom File=g01
Flow File=f01
Plan File=p01
Y Axis Title=Elevation
X Axis Title(PF)=Main Channel Distance
X Axis Title(XS)=Station
BEGIN DESCRIPTION:
UNT 1019 IN HEWA
END DESCRIPTION:
DSS Export Rating Curves= 0
DSS Export Rating Curve Sorted= 0
DSS Export Volume Flow Curves= 0
DXF OffsetX= 0
DXF OffsetY= 0
DXF ScaleX= 1
DXF ScaleY= 10

--- UNT 1019 IN HEWA.p01 (plan) ---

Plan Title=Multiple Run
Short Identifier=Multiple
Geom File=g01
Flow File=f01
Subcritical Flow
K Sum by GR= 0
Std Step Tol= 0.01
Critical Tol= 0.01
Num of Std Step Trials= 20
Max Error Tol= 0.3
Flow Tol Ratio= 0.001
Split Flow NTrial= 30
Split Flow Tol= 0.02
Split Flow Ratio= 0.02
Log Output Level= 0
Friction Slope Method= 1
Unsteady Friction Slope Method= 2
Unsteady Bridges Friction Slope Method= 1
Parabolic Critical Depth
Global Vel Dist=  1 , 1 , 1
Global Log Level= 0
CheckData=True
Encroach Param= -1, 0, 0, 0
BEGIN DESCRIPTION:
Multiple Run
END DESCRIPTION:

--- UNT 1019 IN HEWA.f01 (steady flow) ---

Flow Title=Multiple
Number of Profiles=7
Profile Names=10-year,25-year,50-year,1pct_min,100-year,1pct_plu,500-year
River Rch & RM= UNT 1019 IN HEWA,Reach-1,1384
     941    1379    1762    1649    2230    3016    3587
Boundary for River Rch & Prof#=UNT 1019 IN HEWA,Reach-1,1
Up Type=0
Dn Type=3
Dn Slope=0.005
Boundary for River Rch & Prof#=UNT 1019 IN HEWA,Reach-1,2
Up Type=0
Dn Type=3
Dn Slope=0.005
Boundary for River Rch & Prof#=UNT 1019 IN HEWA,Reach-1,3
Up Type=0
Dn Type=3
Dn Slope=0.005
Boundary for River Rch & Prof#=UNT 1019 IN HEWA,Reach-1,4
Up Type=0
Dn Type=3
Dn Slope=0.005
Boundary for River Rch & Prof#=UNT 1019 IN HEWA,Reach-1,5
Up Type=0
Dn Type=3
Dn Slope=0.005
Boundary for River Rch & Prof#=UNT 1019 IN HEWA,Reach-1,6
Up Type=0
Dn Type=3
Dn Slope=0.005
Boundary for River Rch & Prof#=UNT 1019 IN HEWA,Reach-1,7
Up Type=0
Dn Type=3
Dn Slope=0.005

--- UNT 1019 IN HEWA.g01 (geometry) ---

Geom Title=Existing Conditions
Program Version=4.10

River Reach=UNT 1019 IN HEWA,Reach-1
Reach XY= 30
      2755517.76     10024089.94      2755517.17     10024138.65
      2755503.22     10024174.79      2755504.92      10024186.4
      2755534.15     10024225.37      2755542.57     10024251.98
      2755564.13     10024285.53      2755576.63     10024329.85
      2755640.55     10024387.95      2755690.98      10024457.4
      2755714.98     10024539.88      2755763.48     10024601.01
      2755783.89      10024640.9      2755799.72     10024718.22
       2755825.2     10024765.14      2755836.75     10024799.56
      2755831.45     10024863.69      2755850.88     10024904.24
      2755849.39      10024938.5      2755854.26     10024956.23
      2755953.49     10025071.06      2755973.22      10025129.7
      2756048.09     10025227.41      2756068.47     10025243.73
       2756114.3     10025243.84      2756131.17     10025249.25
      2756181.89     10025295.53      2756234.81     10025331.39
      2756270.86     10025367.35       2756331.1     10025453.16

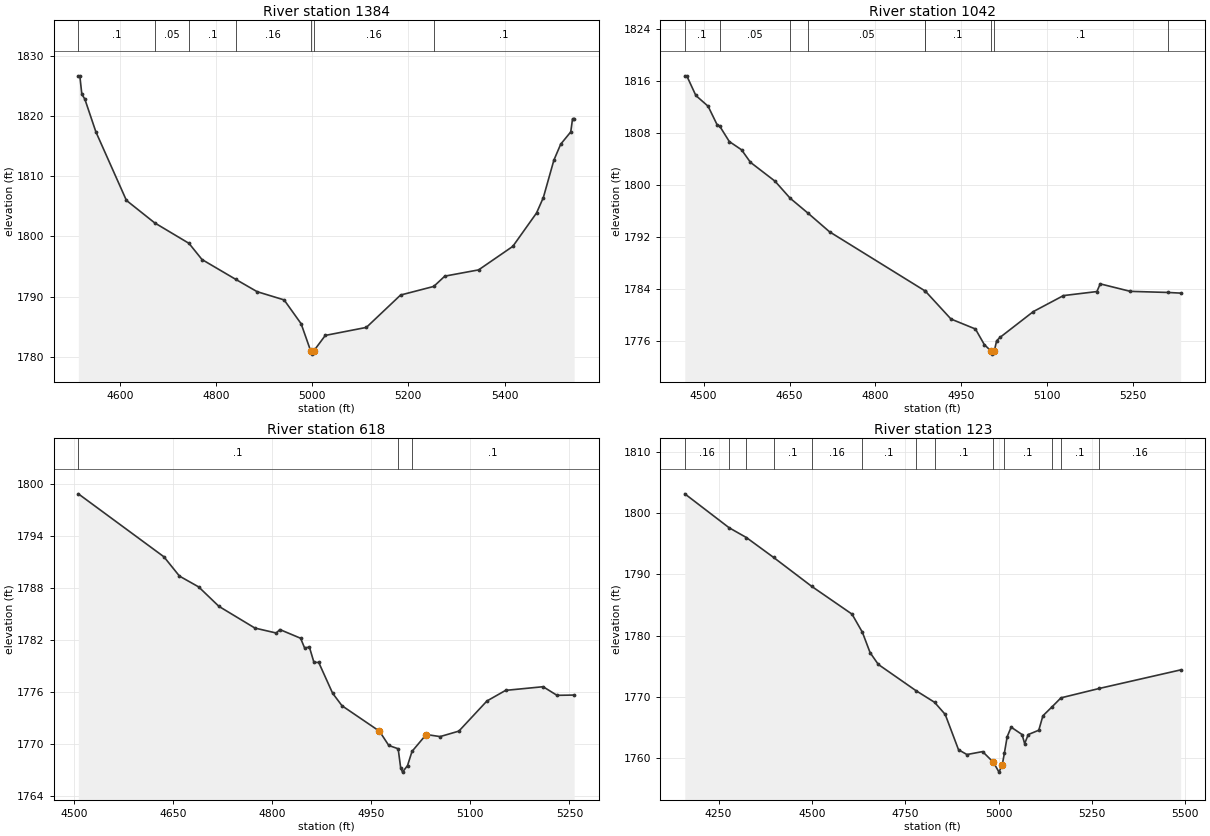
Type RM Length L Ch R = 1 ,1384    ,342,342,342
BEGIN DESCRIPTION:
UNT 1019 IN HEWA 2.0
END DESCRIPTION:
XS GIS Cut Line= 3
      2755218.47     10024653.73      2755618.47     10024353.73
      2755968.46     10023953.74
#Sta/Elev= 30
  4513.4  1826.7  4516.5  1826.7  4520.7 1823.64  4526.9 1822.84  4549.9 1817.39
  4613.4    1806  4672.1 1802.27  4743.6 1798.86  4770.7 1796.17    4841 1792.87
  4885.3 1790.83  4941.5 1789.46  4976.9  1785.5  4996.9 1780.95  4999.6 1780.45
  5002.9 1780.95  5027.2 1783.56  5112.6 1784.89  5183.8 1790.27  5252.8  1791.7
  5275.8 1793.41  5346.1 1794.45  5417.3 1798.36  5466.6  1803.9  5480.8 1806.47
  5502.7 1812.68  5516.9 1815.34  5537.8 1817.38  5541.6 1819.58  5544.9 1819.58
#Mann= 7 ,-1 , 0
  4513.4      .1       0  4672.1     .05       0  4743.6      .1       0
    4841     .16       0  4996.9     .07       0  5002.9     .16       0
  5252.8      .1       0
Bank Sta=4996.9,5002.9
XS Rating Curve= 0 ,0
Exp/Cntr=0.3,0.1

Type RM Length L Ch R = 1 ,1042    ,424,424,424
BEGIN DESCRIPTION:
Mapping XS 4abca22a
END DESCRIPTION:
XS GIS Cut Line= 2
      2755327.18     10024918.84      2756070.21     10024474.41
#Sta/Elev= 30
  4467.1 1816.76  4470.9 1816.69  4486.4 1813.74  4507.8 1812.09  4523.4 1809.27
    4528 1809.04  4544.8 1806.67  4566.2  1805.4  4581.7 1803.48  4624.5 1800.59
  4651.1 1797.96  4682.9 1795.62  4719.8 1792.81  4886.2 1783.75  4887.4 1783.67
  4931.9 1779.41  4974.6 1777.88  4990.2 1775.47  5001.6 1774.52  5004.4 1774.02
  5007.6 1774.52  5011.6 1776.07  5017.4 1776.58  5075.8 1780.56  5128.3 1783.01
  5186.7 1783.63  5192.5 1784.81    5245 1783.66    5311 1783.49  5332.9 1783.39
#Mann= 9 ,-1 , 0
  4467.1      .1       0    4528     .05       0  4651.1      .1       0
  4682.9     .05       0  4886.2     .16       0  4887.4      .1       0
  5001.6     .07       0  5007.6      .1       0    5311     .16       0
Bank Sta=5001.6,5007.6
XS Rating Curve= 0 ,0
Exp/Cntr=0.3,0.1

Type RM Length L Ch R = 1 ,618     ,454,454,454
BEGIN DESCRIPTION:
Mapping XS 2748e846
END DESCRIPTION:
XS GIS Cut Line= 3
      2755503.06     10025279.51      2755808.59     10025147.57
      2756093.35     10024841.98
#Sta/Elev= 30
  4506.6 1798.83  4636.2 1791.58  4659.7 1789.36  4688.7 1788.12  4719.4 1785.88
  4773.9 1783.38  4806.2 1782.81  4811.6 1783.21    4843 1782.21    4849 1781.11
  4856.4 1781.18  4863.2 1779.44  4870.5 1779.42  4891.5 1775.88  4905.7 1774.44
  4962.4 1771.51  4976.5 1769.87  4990.7 1769.49  4994.5  1767.3  4997.3  1766.8
  5004.9 1767.56  5011.7 1769.19  5033.2 1771.13  5054.2 1770.89  5082.6 1771.52
  5125.1 1774.99  5153.4 1776.21  5210.1 1776.63  5231.1 1775.64  5257.1 1775.67
#Mann= 3 ,-1 , 0
  4506.6      .1       0  4990.7     .05       0  5011.7      .1       0
Bank Sta=4962.4,5033.2
XS Rating Curve= 0 ,0
Exp/Cntr=0.3,0.1

Type RM Length L Ch R = 1 ,123     ,0,0,0
BEGIN DESCRIPTION:
UNT 1019 IN HEWA 1.0
END DESCRIPTION:
XS GIS Cut Line= 4
        2755637.     10025876.62      2756178.67     10025543.28
      2756285.44     10025290.68      2756168.24     10024889.61
#Sta/Elev= 30
  4159.4 1803.15    4278 1797.62  4324.3 1796.02  4397.1 1792.78  4499.6 1788.04
  4607.3 1783.52  4635.1 1780.56  4655.8 1777.23  4677.8 1775.31  4778.5 1771.04
  4828.3 1769.14  4856.9 1767.16  4892.6 1761.39  4915.1 1760.61  4957.1 1761.09
  4986.2 1759.33    5001 1757.74  5009.9 1758.98  5015.4 1760.83  5022.9 1763.52
  5033.6 1765.08  5062.8 1763.87  5069.7 1762.39  5079.4 1763.87  5107.6 1764.58
  5118.6 1766.93  5142.2 1768.34    5167 1769.86  5270.1  1771.4  5487.5 1774.42
#Mann= 13 ,-1 , 0
  4159.4     .16       0    4278     .05       0  4324.3     .16       0
  4397.1      .1       0  4499.6     .16       0  4635.1      .1       0
  4778.5     .05       0  4828.3      .1       0  4986.2     .05       0
  5015.4      .1       0  5142.2     .05       0    5167      .1       0
  5270.1     .16       0
Bank Sta=4986.2,5009.9
XS Rating Curve= 0 ,0
Exp/Cntr=0.3,0.1

Chan Stop Cuts=-1
Use User Specified Reach Order=0
Composite Channel Slope=5