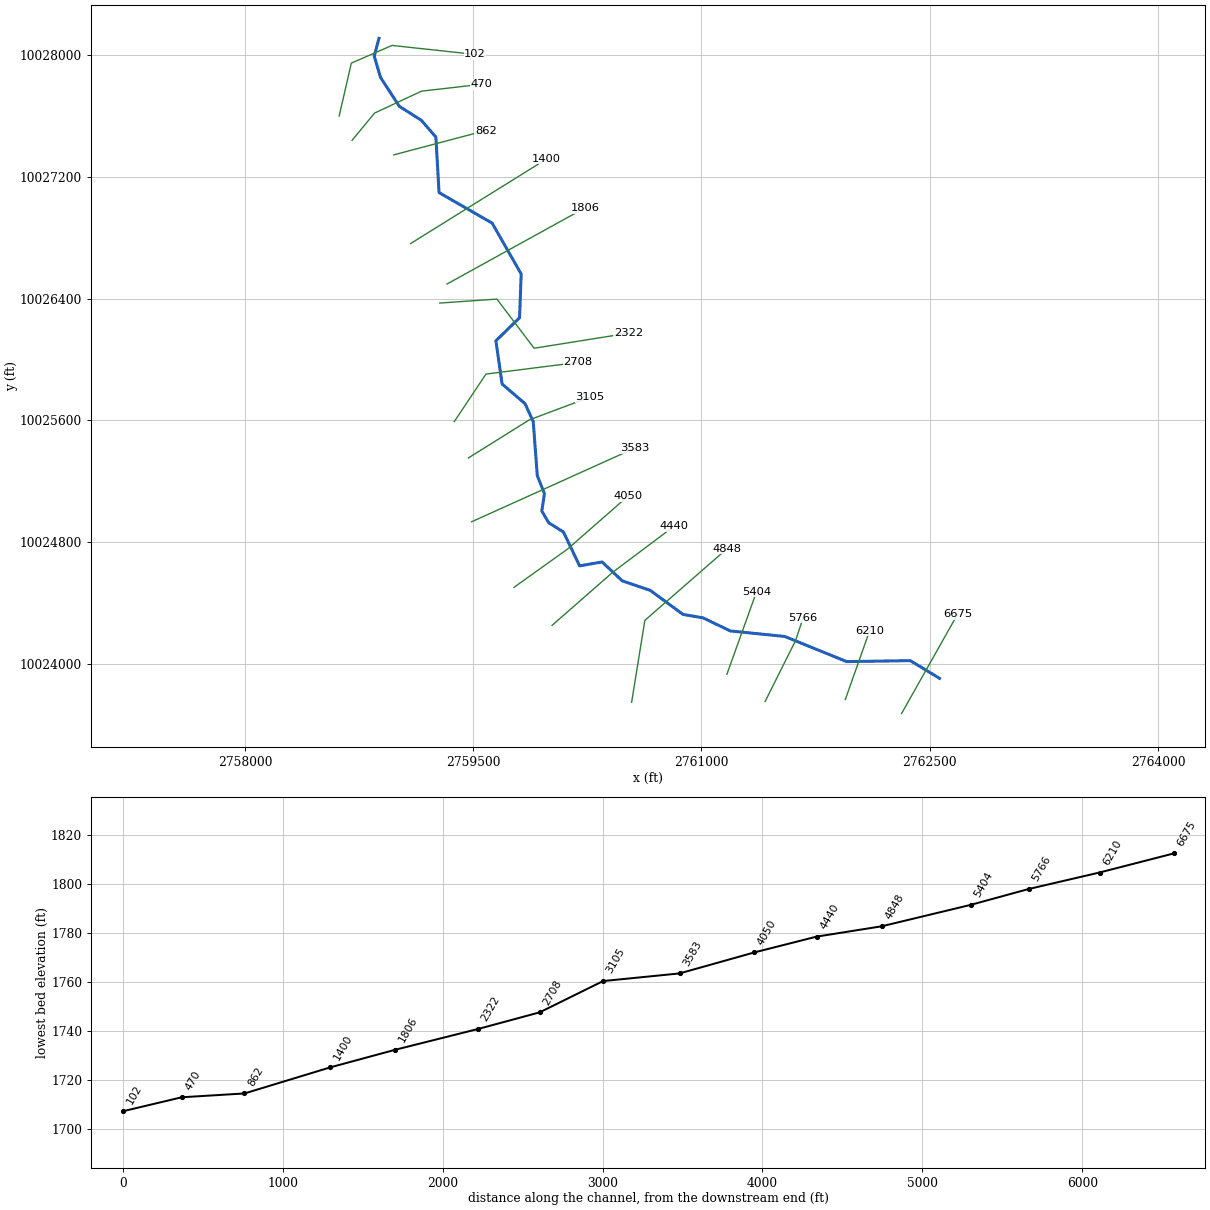
--- UNT 1020 IN HEWA.prj (project) ---

Proj Title=UNT 1020 IN HEWA Base Level Engineering
Current Plan=p01
Default Exp/Contr=0.3,0.1
English Units
Geom File=g01
Flow File=f01
Plan File=p01
BEGIN DESCRIPTION:
UNT 1020 IN HEWA
END DESCRIPTION:

--- UNT 1020 IN HEWA.p01 (plan) ---

Plan Title=Multiple Run
Short Identifier=Multiple
Geom File=g01
Flow File=f01
Subcritical Flow
K Sum by GR= 0
Std Step Tol= 0.01
Critical Tol= 0.01
Num of Std Step Trials= 20
Max Error Tol= 0.3
Flow Tol Ratio= 0.001
Split Flow NTrial= 30
Split Flow Tol= 0.02
Split Flow Ratio= 0.02
Log Output Level= 0
Friction Slope Method= 1
Unsteady Friction Slope Method= 2
Unsteady Bridges Friction Slope Method= 1
Parabolic Critical Depth
Global Vel Dist=  1 , 1 , 1
Global Log Level= 0
CheckData=True
Encroach Param= -1, 0, 0, 0
BEGIN DESCRIPTION:
Multiple Run
END DESCRIPTION:

--- UNT 1020 IN HEWA.f01 (steady flow) ---

Flow Title=Multiple
Number of Profiles=7
Profile Names=10-year,25-year,50-year,1pct_min,100-year,1pct_plu,500-year
River Rch & RM= UNT 1020 IN HEWA,Reach-1,6675
     803    1165    1480    1377    1862    2518    2959
River Rch & RM= UNT 1020 IN HEWA,Reach-1,5766
    1248    1852    2388    2252    3046    4119    4975
Boundary for River Rch & Prof#=UNT 1020 IN HEWA,Reach-1,1
Up Type=0
Dn Type=3
Dn Slope=0.005
Boundary for River Rch & Prof#=UNT 1020 IN HEWA,Reach-1,2
Up Type=0
Dn Type=3
Dn Slope=0.005
Boundary for River Rch & Prof#=UNT 1020 IN HEWA,Reach-1,3
Up Type=0
Dn Type=3
Dn Slope=0.005
Boundary for River Rch & Prof#=UNT 1020 IN HEWA,Reach-1,4
Up Type=0
Dn Type=3
Dn Slope=0.005
Boundary for River Rch & Prof#=UNT 1020 IN HEWA,Reach-1,5
Up Type=0
Dn Type=3
Dn Slope=0.005
Boundary for River Rch & Prof#=UNT 1020 IN HEWA,Reach-1,6
Up Type=0
Dn Type=3
Dn Slope=0.005
Boundary for River Rch & Prof#=UNT 1020 IN HEWA,Reach-1,7
Up Type=0
Dn Type=3
Dn Slope=0.005

--- UNT 1020 IN HEWA.g01 (geometry) ---

Geom Title=Existing Conditions

River Reach=UNT 1020 IN HEWA,Reach-1
Reach XY= 30
      2762564.38     10023905.56      2762372.83     10024021.82
      2761954.01     10024015.57      2761547.27     10024180.74
      2761189.78     10024216.91      2761010.19     10024303.23
      2760879.24     10024325.34      2760663.42     10024483.63
      2760479.41     10024546.13      2760347.00     10024670.32
      2760199.28     10024644.57      2760093.42     10024866.81
      2759996.18     10024927.97      2759951.12     10025005.00
      2759968.08     10025119.52      2759921.15     10025238.25
      2759894.68     10025592.31      2759841.16     10025710.10
      2759690.23     10025839.40      2759649.39     10026123.29
      2759804.76     10026275.25      2759815.45     10026562.48
      2759624.74     10026896.79      2759275.76     10027097.33
      2759254.86     10027462.24      2759158.95     10027572.75
      2759014.46     10027664.45      2758890.88     10027854.73
      2758849.96     10027993.79      2758880.91     10028111.02

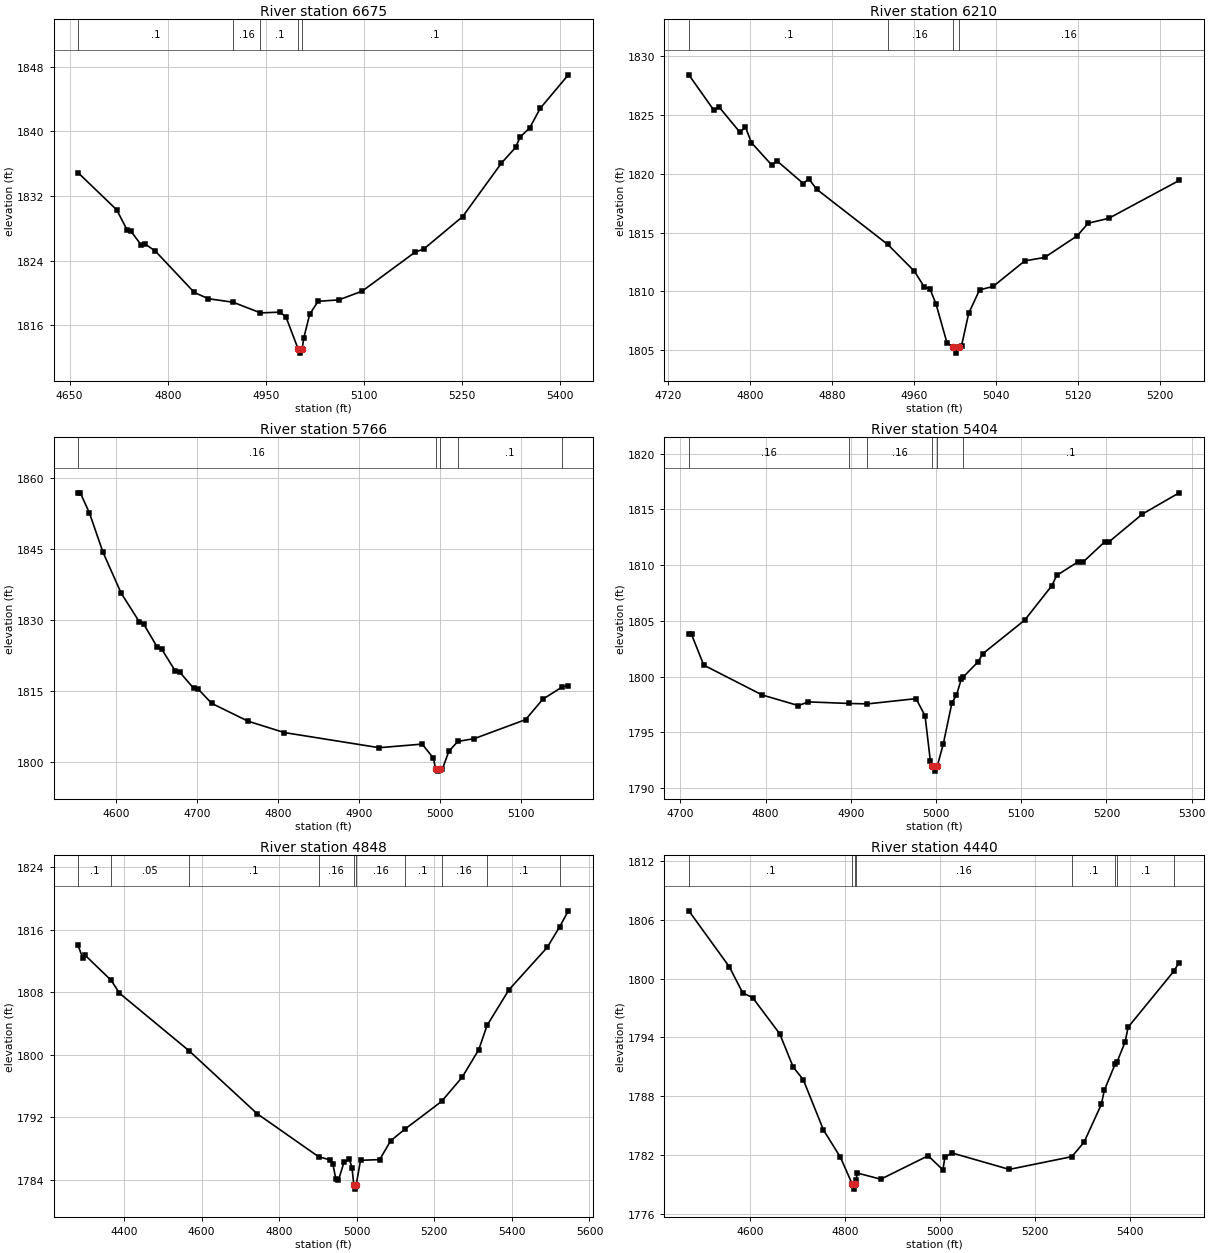
Type RM Length L Ch R = 1,6675,465,465,465
BEGIN DESCRIPTION:
UNT 1020 IN HEWA 15.0
END DESCRIPTION:
XS GIS Cut Line= 2
      2762315.53     10023675.33      2762683.54     10024328.03
#Sta/Elev= 30
  4663.0 1834.90  4722.1 1830.30  4738.0 1827.81  4743.8 1827.65  4759.7 1825.94
  4765.4 1826.08  4781.3 1825.18  4840.6 1820.08  4862.2 1819.30  4900.0 1818.87
  4941.8 1817.55  4971.1 1817.64  4980.7 1817.06  4999.4 1813.07  5002.1 1812.57
  5005.4 1813.07  5008.1 1814.49  5017.0 1817.38  5029.8 1818.98  5061.6 1819.16
  5097.4 1820.25  5177.8 1825.05  5191.6 1825.47  5250.8 1829.47  5310.1 1836.09
  5331.7 1838.03  5338.5 1839.30  5353.4 1840.46  5369.3 1842.86  5412.3 1847.01
#Mann=5,-1,0
  4663.0     0.1       0  4900.0    0.16       0  4941.8     0.1       0
  4999.4    0.07       0  5005.4     0.1       0
Bank Sta=4999.4,5005.4
Exp/Cntr=0.3,0.1

Type RM Length L Ch R = 1,6210,444,444,444
BEGIN DESCRIPTION:
UNT 1020 IN HEWA 14.0
END DESCRIPTION:
XS GIS Cut Line= 2
      2761945.21     10023766.09      2762104.93     10024217.47
#Sta/Elev= 30
  4740.0 1828.41  4764.4 1825.41  4769.7 1825.66  4790.0 1823.52  4795.3 1823.98
  4801.1 1822.65  4820.9 1820.75  4826.2 1821.09  4851.8 1819.17  4857.1 1819.58
  4864.8 1818.69  4934.2 1814.00  4960.3 1811.72  4970.1 1810.36  4975.4 1810.24
  4981.5 1808.91  4992.1 1805.64  4998.0 1805.26  5000.7 1804.76  5004.0 1805.26
  5006.3 1805.37  5013.3 1808.14  5023.9 1810.13  5037.2 1810.43  5068.1 1812.60
  5087.5 1812.89  5119.3 1814.73  5130.0 1815.80  5150.2 1816.22  5218.8 1819.43
#Mann=4,-1,0
  4740.0     0.1       0  4934.2    0.16       0  4998.0    0.07       0
  5004.0    0.16       0
Bank Sta=4998,5004
Exp/Cntr=0.3,0.1

Type RM Length L Ch R = 1,5766,362,362,362
BEGIN DESCRIPTION:
UNT 1020 IN HEWA 13.0
END DESCRIPTION:
XS GIS Cut Line= 3
      2761418.46     10023753.72      2761618.47     10024153.73
      2761668.45     10024303.69
#Sta/Elev= 30
  4553.3 1856.91  4556.1 1856.91  4567.3 1852.66  4584.1 1844.33  4606.4 1835.71
  4628.8 1829.64  4634.4 1829.09  4651.1 1824.26  4656.7 1823.79  4673.5 1819.15
  4679.1 1818.90  4695.9 1815.55  4701.5 1815.39  4718.2 1812.35  4762.9 1808.59
  4807.7 1806.17  4925.1 1802.96  4978.2 1803.72  4992.1 1800.71  4994.7 1798.50
  4997.5 1798.00  5000.7 1798.50  5003.2 1798.50  5011.1 1802.20  5022.1 1804.28
  5042.7 1804.89  5105.9 1808.91  5127.0 1813.21  5150.9 1815.81  5158.6 1816.12
#Mann=5,-1,0
  4553.3    0.16       0  4994.7    0.07       0  5000.7    0.16       0
  5022.1     0.1       0  5150.9    0.16       0
Bank Sta=4994.7,5000.7
Exp/Cntr=0.3,0.1

Type RM Length L Ch R = 1,5404,556,556,556
BEGIN DESCRIPTION:
UNT 1020 IN HEWA 12.0
END DESCRIPTION:
XS GIS Cut Line= 2
      2761167.42     10023932.73      2761361.86     10024474.38
#Sta/Elev= 30
  4709.8 1803.79  4713.0 1803.79  4727.3 1801.04  4795.9 1798.36  4838.4 1797.41
  4850.2 1797.74  4897.4 1797.60  4919.5 1797.56  4976.5 1798.03  4987.1 1796.49
  4993.3 1792.45  4995.6 1792.03  4998.3 1791.53  5001.6 1792.03  5008.4 1793.93
  5018.7 1797.68  5024.0 1798.35  5029.6 1799.78  5031.6 1799.95  5049.4 1801.34
  5054.7 1802.05  5104.0 1805.07  5135.9 1808.16  5141.6 1809.08  5167.0 1810.32
  5172.4 1810.27  5197.8 1812.08  5203.1 1812.10  5242.1 1814.58  5285.3 1816.49
#Mann=6,-1,0
  4709.8    0.16       0  4897.4     0.1       0  4919.5    0.16       0
  4995.6    0.07       0  5001.6    0.16       0  5031.6     0.1       0
Bank Sta=4995.6,5001.6
Exp/Cntr=0.3,0.1

Type RM Length L Ch R = 1,4848,408,408,408
BEGIN DESCRIPTION:
UNT 1020 IN HEWA 11.0
END DESCRIPTION:
XS GIS Cut Line= 3
      2760541.24     10023748.28      2760628.04     10024286.46
      2761169.68     10024758.66
#Sta/Elev= 30
  4281.8 1813.99  4294.1 1812.33  4299.2 1812.77  4367.4 1809.51  4388.6 1807.87
  4568.1 1800.49  4743.1 1792.45  4902.1 1786.92  4932.0 1786.52  4938.6 1785.96
  4946.2 1784.10  4952.8 1783.89  4967.1 1786.21  4981.3 1786.58  4987.9 1785.51
  4992.6 1783.28  4995.3 1782.78  4998.6 1783.28  5009.8 1786.47  5059.2 1786.56
  5087.6 1788.97  5123.7 1790.44  5218.7 1794.01  5271.8 1797.11  5314.5 1800.63
  5336.1 1803.75  5392.4 1808.31  5491.1 1813.74  5523.3 1816.39  5545.5 1818.42
#Mann=10,-1,0
  4281.8     0.1       0  4367.4    0.05       0  4568.1     0.1       0
  4902.1    0.16       0  4992.6    0.07       0  4998.6    0.16       0
  5123.7     0.1       0  5218.7    0.16       0  5336.1     0.1       0
  5523.3    0.16       0
Bank Sta=4992.6,4998.6
Exp/Cntr=0.3,0.1

Type RM Length L Ch R = 1,4440,390,390,390
BEGIN DESCRIPTION:
UNT 1020 IN HEWA 10.0
END DESCRIPTION:
XS GIS Cut Line= 3
      2760018.49     10024253.75      2760418.47     10024603.73
      2760818.49     10024903.75
#Sta/Elev= 30
  4471.8 1806.90  4556.7 1801.22  4585.2 1798.54  4606.1 1798.05  4663.0 1794.37
  4691.5 1790.97  4712.4 1789.71  4755.1 1784.57  4790.7 1781.79  4815.7 1779.04
  4818.4 1778.54  4821.7 1779.04  4823.6 1779.51  4826.3 1780.18  4875.6 1779.55
  4975.3 1781.94  5006.4 1780.50  5010.6 1781.81  5025.2 1782.23  5146.0 1780.55
  5277.6 1781.85  5303.3 1783.32  5339.7 1787.18  5346.0 1788.62  5369.2 1791.34
  5372.4 1791.46  5389.7 1793.54  5396.0 1795.04  5491.9 1800.73  5503.3 1801.63
#Mann=8,-1,0
  4471.8     0.1       0  4815.7    0.07       0  4821.7     0.1       0
  4823.6    0.16       0  5277.6     0.1       0  5369.2    0.16       0
  5372.4     0.1       0  5491.9    0.16       0
Bank Sta=4815.7,4821.7
Exp/Cntr=0.3,0.1

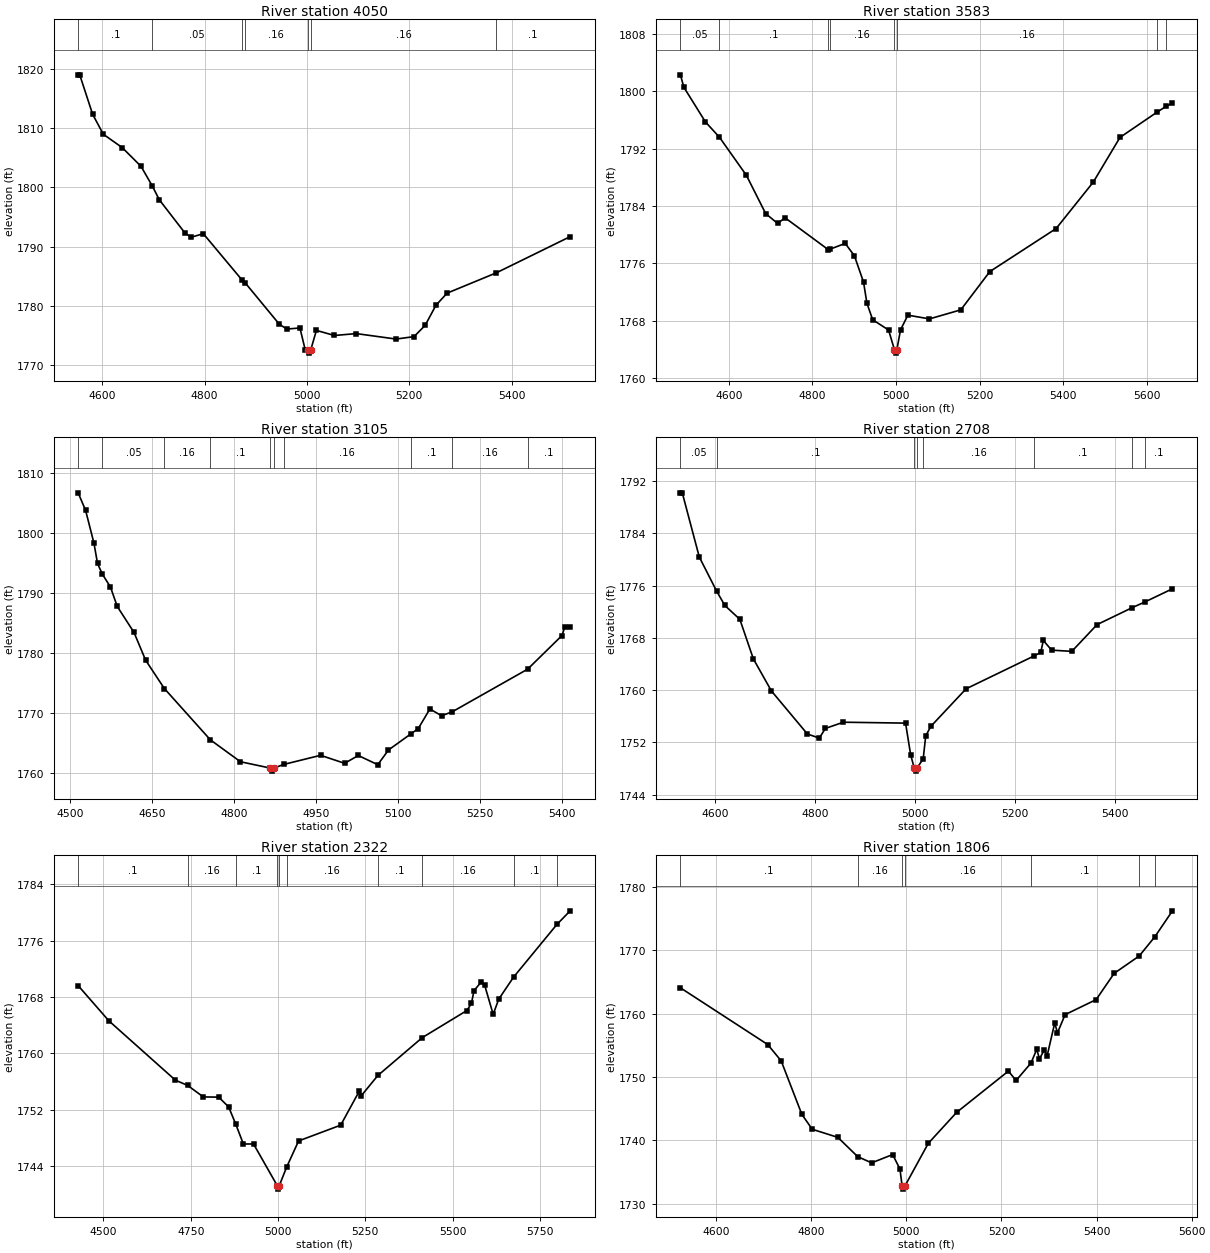
Type RM Length L Ch R = 1,4050,467,467,467
BEGIN DESCRIPTION:
UNT 1020 IN HEWA 9.0
END DESCRIPTION:
XS GIS Cut Line= 3
      2759768.44     10024503.71      2760118.47     10024753.73
      2760518.50     10025103.76
#Sta/Elev= 30
  4552.7 1818.94  4555.8 1818.94  4581.0 1812.30  4601.9 1808.93  4638.8 1806.69
  4675.6 1803.53  4697.9 1800.18  4711.3 1797.90  4761.6 1792.29  4773.9 1791.59
  4797.3 1792.19  4873.0 1784.39  4878.7 1783.96  4946.0 1776.93  4960.7 1776.12
  4986.2 1776.31  4996.6 1772.60  5001.2 1772.57  5004.0 1772.07  5007.2 1772.57
  5018.4 1775.90  5053.6 1775.04  5096.3 1775.36  5174.1 1774.44  5209.2 1774.85
  5231.0 1776.75  5251.9 1780.11  5273.8 1782.17  5370.0 1785.59  5514.4 1791.69
#Mann=7,-1,0
  4552.7     0.1       0  4697.9    0.05       0  4873.0     0.1       0
  4878.7    0.16       0  5001.2    0.07       0  5007.2    0.16       0
  5370.0     0.1       0
Bank Sta=5001.2,5007.2
Exp/Cntr=0.3,0.1

Type RM Length L Ch R = 1,3583,478,478,478
BEGIN DESCRIPTION:
UNT 1020 IN HEWA 8.0
END DESCRIPTION:
XS GIS Cut Line= 2
      2759489.17     10024934.04      2760562.10     10025418.42
#Sta/Elev= 30
  4484.1 1802.28  4492.2 1800.56  4543.9 1795.72  4577.5 1793.58  4641.9 1788.28
  4688.1 1782.94  4716.7 1781.57  4734.4 1782.36  4837.6 1777.93  4841.4 1777.97
  4878.3 1778.79  4900.3 1777.07  4922.2 1773.40  4930.3 1770.45  4944.1 1768.15
  4982.1 1766.72  4996.0 1764.00  4998.8 1763.50  5002.0 1764.00  5010.7 1766.74
  5028.3 1768.79  5080.0 1768.27  5154.9 1769.53  5224.3 1774.86  5383.0 1780.86
  5472.0 1787.34  5535.8 1793.56  5625.0 1797.10  5646.7 1797.91  5661.3 1798.31
#Mann=8,-1,0
  4484.1    0.05       0  4577.5     0.1       0  4837.6    0.05       0
  4841.4    0.16       0  4996.0    0.07       0  5002.0    0.16       0
  5625.0     0.1       0  5646.7    0.16       0
Bank Sta=4996,5002
Exp/Cntr=0.3,0.1

Type RM Length L Ch R = 1,3105,397,397,397
BEGIN DESCRIPTION:
UNT 1020 IN HEWA 7.0
END DESCRIPTION:
XS GIS Cut Line= 3
      2759468.43     10025353.71      2759868.47     10025603.73
      2760268.42     10025753.72
#Sta/Elev= 30
  4515.3 1806.67  4528.9 1803.76  4544.2 1798.29  4550.7 1794.93  4559.5 1793.15
  4574.3 1791.01  4586.7 1787.78  4617.4 1783.44  4638.6 1778.83  4672.8 1774.12
  4756.9 1765.58  4811.9 1761.94  4866.7 1760.88  4869.5 1760.38  4872.7 1760.88
  4890.7 1761.49  4958.2 1763.01  5002.2 1761.68  5027.1 1762.98  5062.7 1761.45
  5082.3 1763.90  5123.1 1766.57  5136.6 1767.45  5157.9 1770.72  5179.3 1769.59
  5199.0 1770.26  5336.5 1777.34  5399.1 1782.92  5404.5 1784.36  5414.2 1784.40
#Mann=10,-1,0
  4515.3     0.1       0  4559.5    0.05       0  4672.8    0.16       0
  4756.9     0.1       0  4866.7    0.07       0  4872.7     0.1       0
  4890.7    0.16       0  5123.1     0.1       0  5199.0    0.16       0
  5336.5     0.1       0
Bank Sta=4866.7,4872.7
Exp/Cntr=0.3,0.1

Type RM Length L Ch R = 1,2708,386,386,386
BEGIN DESCRIPTION:
UNT 1020 IN HEWA 6.0
END DESCRIPTION:
XS GIS Cut Line= 3
      2759375.77     10025592.48      2759584.09     10025904.97
      2760188.22     10025981.35
#Sta/Elev= 30
  4530.1 1790.19  4533.8 1790.19  4567.8 1780.37  4602.4 1775.16  4618.9 1772.95
  4649.0 1770.82  4676.0 1764.77  4712.1 1759.86  4784.2 1753.26  4808.0 1752.64
  4820.2 1754.12  4856.3 1755.07  4980.6 1754.93  4990.7 1750.11  4997.8 1748.08
  5000.5 1747.58  5003.8 1748.08  5015.9 1749.47  5020.9 1752.97  5031.0 1754.42
  5101.6 1760.18  5238.3 1765.24  5251.1 1765.76  5256.2 1767.59  5272.9 1766.10
  5313.3 1765.92  5363.7 1770.01  5433.8 1772.60  5459.7 1773.49  5514.6 1775.50
#Mann=8,-1,0
  4530.1    0.05       0  4602.4     0.1       0  4997.8    0.07       0
  5003.8     0.1       0  5015.9    0.16       0  5238.3     0.1       0
  5433.8    0.16       0  5459.7     0.1       0
Bank Sta=4997.8,5003.8
Exp/Cntr=0.3,0.1

Type RM Length L Ch R = 1,2322,516,516,516
BEGIN DESCRIPTION:
UNT 1020 IN HEWA 5.0
END DESCRIPTION:
XS GIS Cut Line= 4
      2759280.79     10026371.53      2759655.82     10026397.57
      2759900.61     10026074.65      2760520.41     10026173.61
#Sta/Elev= 30
  4427.6 1769.62  4515.5 1764.63  4705.9 1756.22  4741.1 1755.47  4786.1 1753.84
  4830.0 1753.81  4858.5 1752.43  4878.3 1750.05  4900.7 1747.17  4929.8 1747.17
  4997.6 1741.27  5000.3 1740.77  5003.6 1741.27  5024.5 1743.88  5058.8 1747.60
  5179.4 1749.84  5233.2 1754.71  5238.3 1754.01  5285.8 1756.88  5413.0 1762.25
  5540.8 1766.09  5553.8 1767.11  5561.0 1768.90  5581.3 1770.11  5591.4 1769.71
  5615.9 1765.55  5631.9 1767.70  5674.3 1770.82  5798.4 1778.29  5836.4 1780.22
#Mann=10,-1,0
  4427.6     0.1       0  4741.1    0.16       0  4878.3     0.1       0
  4997.6    0.07       0  5003.6     0.1       0  5024.5    0.16       0
  5285.8     0.1       0  5413.0    0.16       0  5674.3     0.1       0
  5798.4    0.16       0
Bank Sta=4997.6,5003.6
Exp/Cntr=0.3,0.1

Type RM Length L Ch R = 1,1806,406,406,406
BEGIN DESCRIPTION:
UNT 1020 IN HEWA 4.0
END DESCRIPTION:
XS GIS Cut Line= 2
      2759327.66     10026496.51      2760233.71     10026996.40
#Sta/Elev= 30
  4524.8 1764.05  4708.5 1755.10  4736.7 1752.53  4780.2 1744.09  4802.0 1741.75
  4855.9 1740.47  4897.5 1737.44  4926.9 1736.45  4971.1 1737.76  4986.5 1735.48
  4991.0 1732.81  4993.7 1732.31  4997.0 1732.81  5046.1 1739.53  5105.7 1744.41
  5214.6 1750.92  5230.7 1749.44  5262.0 1752.18  5274.2 1754.35  5279.9 1752.85
  5290.3 1754.29  5296.0 1753.32  5312.0 1758.51  5317.8 1756.95  5333.8 1759.82
  5399.1 1762.19  5437.0 1766.33  5489.7 1769.07  5522.9 1772.13  5559.6 1776.19
#Mann=7,-1,0
  4524.8     0.1       0  4897.5    0.16       0  4991.0    0.07       0
  4997.0    0.16       0  5262.0     0.1       0  5489.7    0.05       0
  5522.9     0.1       0
Bank Sta=4991,4997
Exp/Cntr=0.3,0.1

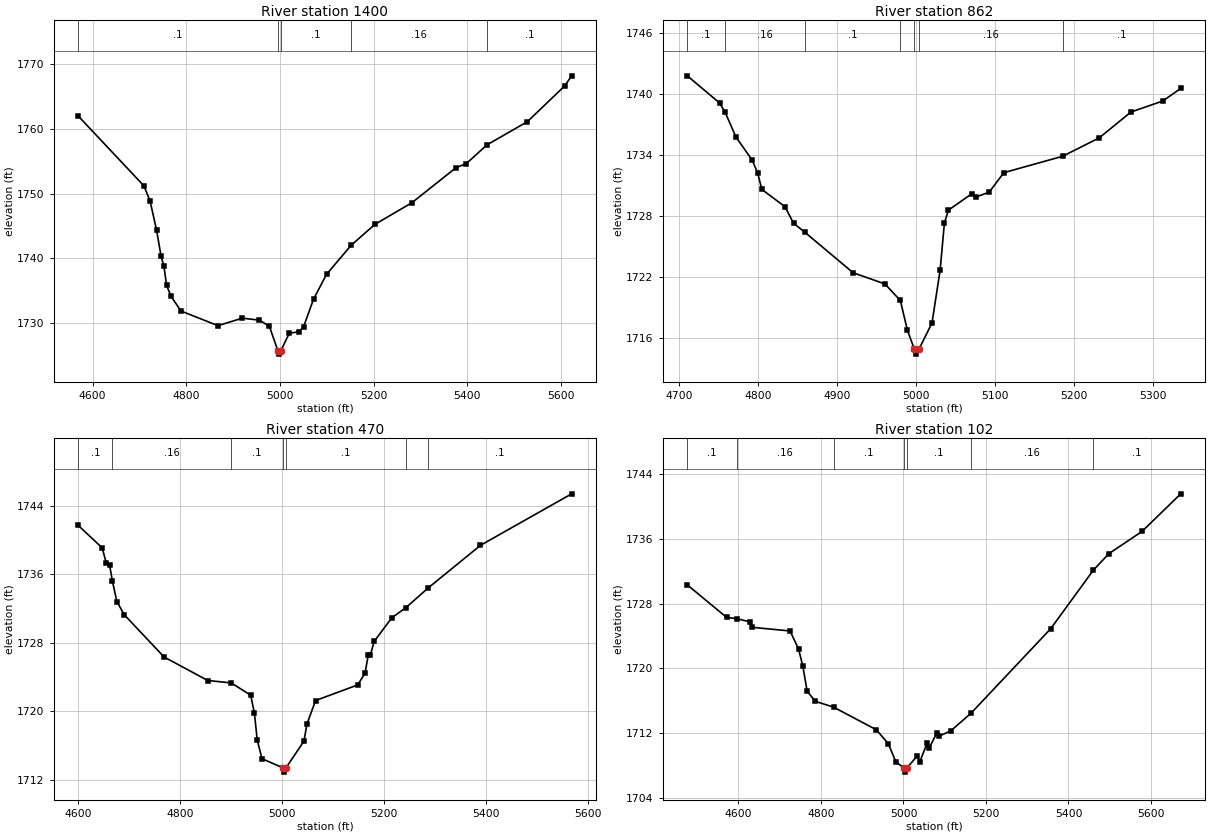
Type RM Length L Ch R = 1,1400,538,538,538
BEGIN DESCRIPTION:
UNT 1020 IN HEWA 3.0
END DESCRIPTION:
XS GIS Cut Line= 2
      2759088.14     10026762.18      2759983.10     10027318.92
#Sta/Elev= 30
  4569.2 1762.01  4709.6 1751.18  4722.7 1748.84  4736.7 1744.28  4746.2 1740.28
  4752.1 1738.80  4758.0 1735.78  4767.4 1734.08  4788.7 1731.80  4867.7 1729.53
  4919.7 1730.69  4956.3 1730.38  4977.5 1729.43  4995.8 1725.62  4998.5 1725.12
  5001.8 1725.62  5020.0 1728.35  5041.3 1728.59  5050.7 1729.39  5072.0 1733.66
  5099.6 1737.48  5152.4 1742.00  5203.0 1745.22  5282.1 1748.58  5376.5 1754.02
  5397.8 1754.61  5442.2 1757.53  5528.8 1761.14  5607.9 1766.64  5623.2 1768.23
#Mann=5,-1,0
  4569.2     0.1       0  4995.8    0.07       0  5001.8     0.1       0
  5152.4    0.16       0  5442.2     0.1       0
Bank Sta=4995.8,5001.8
Exp/Cntr=0.3,0.1

Type RM Length L Ch R = 1,862,392,392,392
BEGIN DESCRIPTION:
UNT 1020 IN HEWA 2.0
END DESCRIPTION:
XS GIS Cut Line= 2
      2758978.89     10027345.48      2759583.04     10027505.20
#Sta/Elev= 30
  4710.4 1741.82  4751.3 1739.15  4758.3 1738.24  4772.0 1735.80  4792.7 1733.51
  4799.6 1732.23  4804.8 1730.64  4834.1 1728.94  4845.0 1727.31  4859.2 1726.43
  4920.4 1722.44  4960.6 1721.34  4980.2 1719.71  4989.2 1716.77  4997.9 1714.93
  5000.6 1714.43  5003.9 1714.93  5020.3 1717.50  5030.6 1722.70  5036.0 1727.33
  5041.1 1728.60  5071.0 1730.23  5076.2 1729.90  5092.7 1730.37  5111.3 1732.29
  5185.6 1733.90  5232.0 1735.71  5272.3 1738.26  5312.5 1739.34  5335.3 1740.58
#Mann=7,-1,0
  4710.4     0.1       0  4758.3    0.16       0  4859.2     0.1       0
  4980.2    0.16       0  4997.9    0.07       0  5003.9    0.16       0
  5185.6     0.1       0
Bank Sta=4997.9,5003.9
Exp/Cntr=0.3,0.1

Type RM Length L Ch R = 1,470,368,368,368
BEGIN DESCRIPTION:
Mapping XS d7cc042e
END DESCRIPTION:
XS GIS Cut Line= 4
      2758704.49     10027441.13      2758852.05     10027619.94
      2759161.08     10027764.04      2759553.23     10027808.76
#Sta/Elev= 30
  4600.9 1741.71  4648.0 1739.08  4655.9 1737.29  4662.4 1737.07  4667.9 1735.22
  4676.7 1732.81  4691.1 1731.27  4769.2 1726.33  4854.9 1723.58  4901.0 1723.30
  4939.1 1721.86  4946.4 1719.75  4951.9 1716.61  4961.2 1714.44  5002.3 1713.37
  5005.1 1712.87  5008.3 1713.37  5043.4 1716.49  5049.5 1718.51  5066.3 1721.24
  5148.8 1723.06  5163.2 1724.42  5169.5 1726.53  5173.7 1726.53  5181.1 1728.14
  5215.7 1730.91  5243.3 1732.09  5287.5 1734.42  5389.6 1739.38  5568.4 1745.40
#Mann=7,-1,0
  4600.9     0.1       0  4667.9    0.16       0  4901.0     0.1       0
  5002.3    0.07       0  5008.3     0.1       0  5243.3    0.16       0
  5287.5     0.1       0
Bank Sta=5002.3,5008.3
Exp/Cntr=0.3,0.1

Type RM Length L Ch R = 1,102,0,0,0
BEGIN DESCRIPTION:
UNT 1020 IN HEWA 1.0
END DESCRIPTION:
XS GIS Cut Line= 4
      2758619.42     10027600.86      2758699.27     10027948.07
      2758966.64     10028064.39      2759511.81     10028005.36
#Sta/Elev= 30
  4476.0 1730.32  4571.3 1726.30  4596.2 1726.14  4627.8 1725.74  4632.9 1725.07
  4725.2 1724.62  4745.7 1722.38  4756.0 1720.29  4766.6 1717.15  4786.8 1715.91
  4830.5 1715.20  4934.6 1712.39  4963.5 1710.66  4981.5 1708.43  5001.9 1707.66
  5004.7 1707.16  5007.9 1707.66  5033.8 1709.17  5039.3 1708.40  5057.2 1710.72
  5062.7 1710.17  5080.7 1711.99  5086.1 1711.60  5115.0 1712.28  5163.9 1714.45
  5357.0 1724.90  5460.7 1732.16  5497.8 1734.17  5578.3 1736.93  5672.2 1741.58
#Mann=7,-1,0
  4476.0     0.1       0  4596.2    0.16       0  4830.5     0.1       0
  5001.9    0.07       0  5007.9     0.1       0  5163.9    0.16       0
  5460.7     0.1       0
Bank Sta=5001.9,5007.9
Exp/Cntr=0.3,0.1

Chan Stop Cuts=-1