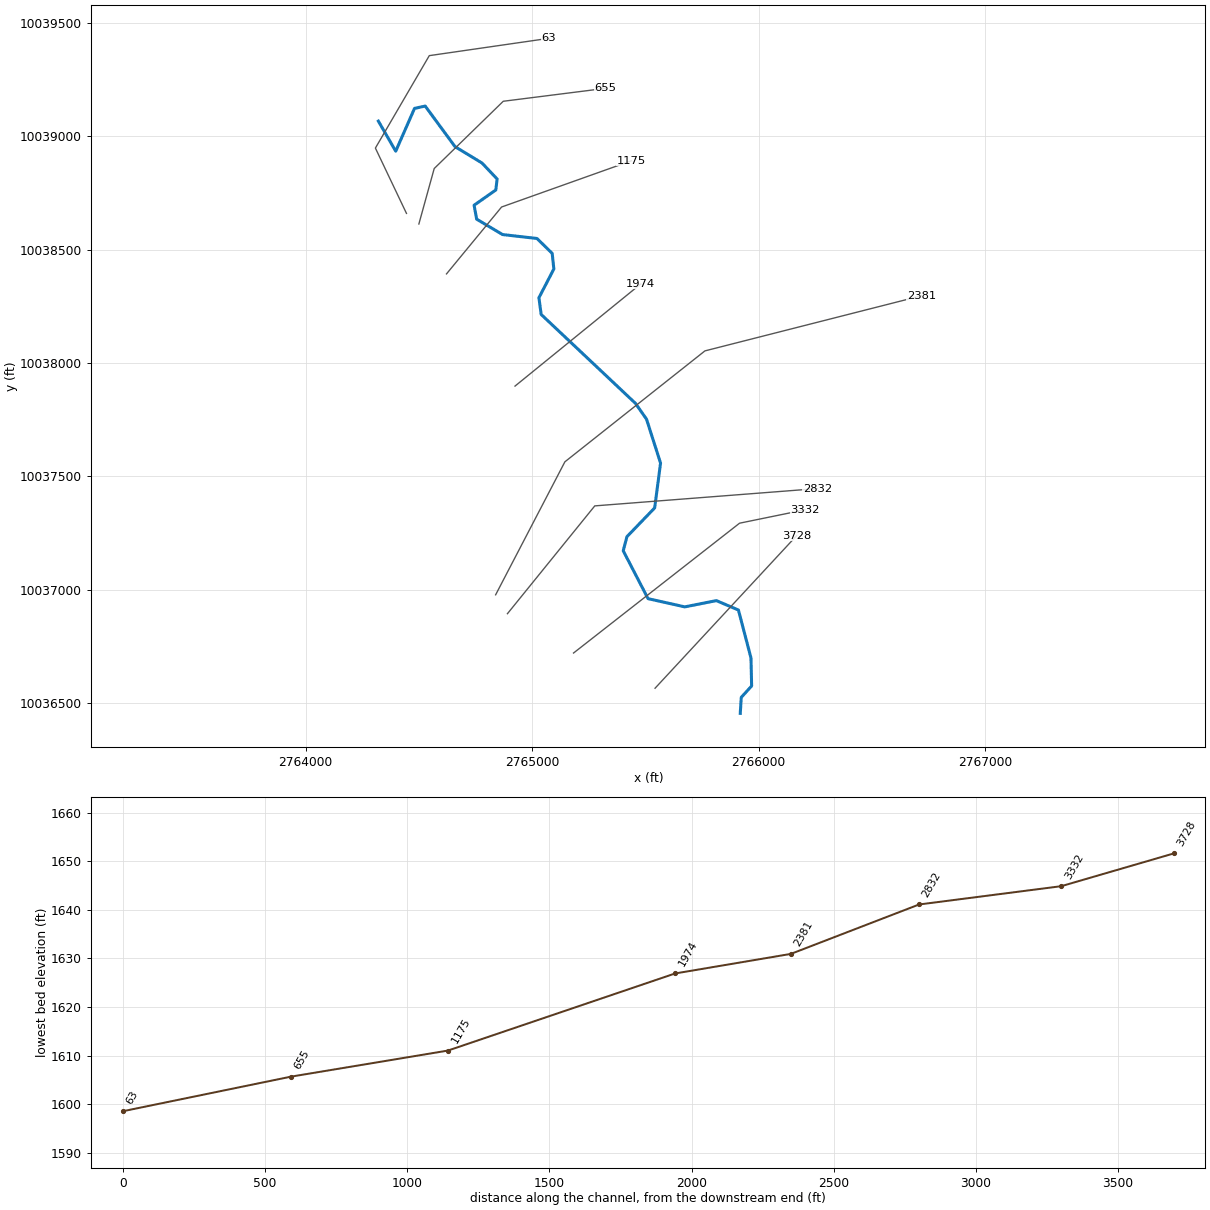
--- UNT 1023 IN HEWA.prj (project) ---

Proj Title=UNT 1023 IN HEWA Base Level Engineering
Current Plan=p01
Default Exp/Contr=0.3,0.1
English Units
Geom File=g01
Flow File=f01
Plan File=p01
Y Axis Title=Elevation
X Axis Title(PF)=Main Channel Distance
X Axis Title(XS)=Station
BEGIN DESCRIPTION:
UNT 1023 IN HEWA
END DESCRIPTION:
DSS Export Rating Curves= 0
DSS Export Rating Curve Sorted= 0
DSS Export Volume Flow Curves= 0
DXF OffsetX= 0
DXF OffsetY= 0
DXF ScaleX= 1
DXF ScaleY= 10

--- UNT 1023 IN HEWA.p01 (plan) ---

Plan Title=Multiple Run
Short Identifier=Multiple
Geom File=g01
Flow File=f01
Subcritical Flow
K Sum by GR= 0
Std Step Tol= 0.01
Critical Tol= 0.01
Num of Std Step Trials= 20
Max Error Tol= 0.3
Flow Tol Ratio= 0.001
Split Flow NTrial= 30
Split Flow Tol= 0.02
Split Flow Ratio= 0.02
Log Output Level= 0
Friction Slope Method= 1
Unsteady Friction Slope Method= 2
Unsteady Bridges Friction Slope Method= 1
Parabolic Critical Depth
Global Vel Dist=  1 , 1 , 1
Global Log Level= 0
CheckData=True
Encroach Param= -1, 0, 0, 0
BEGIN DESCRIPTION:
Multiple Run
END DESCRIPTION:

--- UNT 1023 IN HEWA.f01 (steady flow) ---

Flow Title=Multiple
Number of Profiles=7
Profile Names=10-year,25-year,50-year,1pct_min,100-year,1pct_plu,500-year
River Rch & RM= UNT 1023 IN HEWA,Reach-1,3728
    1037    1526    1956    1835    2482    3356    4013
Boundary for River Rch & Prof#=UNT 1023 IN HEWA,Reach-1,1
Up Type=0
Dn Type=3
Dn Slope=0.005
Boundary for River Rch & Prof#=UNT 1023 IN HEWA,Reach-1,2
Up Type=0
Dn Type=3
Dn Slope=0.005
Boundary for River Rch & Prof#=UNT 1023 IN HEWA,Reach-1,3
Up Type=0
Dn Type=3
Dn Slope=0.005
Boundary for River Rch & Prof#=UNT 1023 IN HEWA,Reach-1,4
Up Type=0
Dn Type=3
Dn Slope=0.005
Boundary for River Rch & Prof#=UNT 1023 IN HEWA,Reach-1,5
Up Type=0
Dn Type=3
Dn Slope=0.005
Boundary for River Rch & Prof#=UNT 1023 IN HEWA,Reach-1,6
Up Type=0
Dn Type=3
Dn Slope=0.005
Boundary for River Rch & Prof#=UNT 1023 IN HEWA,Reach-1,7
Up Type=0
Dn Type=3
Dn Slope=0.005

--- UNT 1023 IN HEWA.g01 (geometry) ---

Geom Title=Existing Conditions
Program Version=4.10

River Reach=UNT 1023 IN HEWA,Reach-1
Reach XY= 30
      2765918.47     10036453.73      2765922.82     10036524.31
       2765968.6     10036574.73      2765965.73     10036698.23
       2765910.4     10036909.72      2765813.04     10036951.39
      2765673.57     10036923.75      2765511.51       10036960.
      2765401.94     10037171.19      2765418.23     10037233.44
      2765540.69     10037360.38       2765566.7     10037558.25
      2765504.67     10037752.18      2765455.82     10037822.02
       2765039.8      10038214.2      2765029.89      10038287.9
       2765095.8     10038414.94      2765088.47     10038483.73
      2765021.44     10038549.44      2764869.71     10038566.75
      2764755.22     10038634.54       2764743.8      10038696.2
      2764839.66     10038763.44      2764845.39      10038812.1
      2764778.67     10038882.51      2764659.65     10038954.73
      2764528.02     10039133.88      2764480.98     10039123.57
      2764397.97      10038934.7      2764321.33     10039067.47

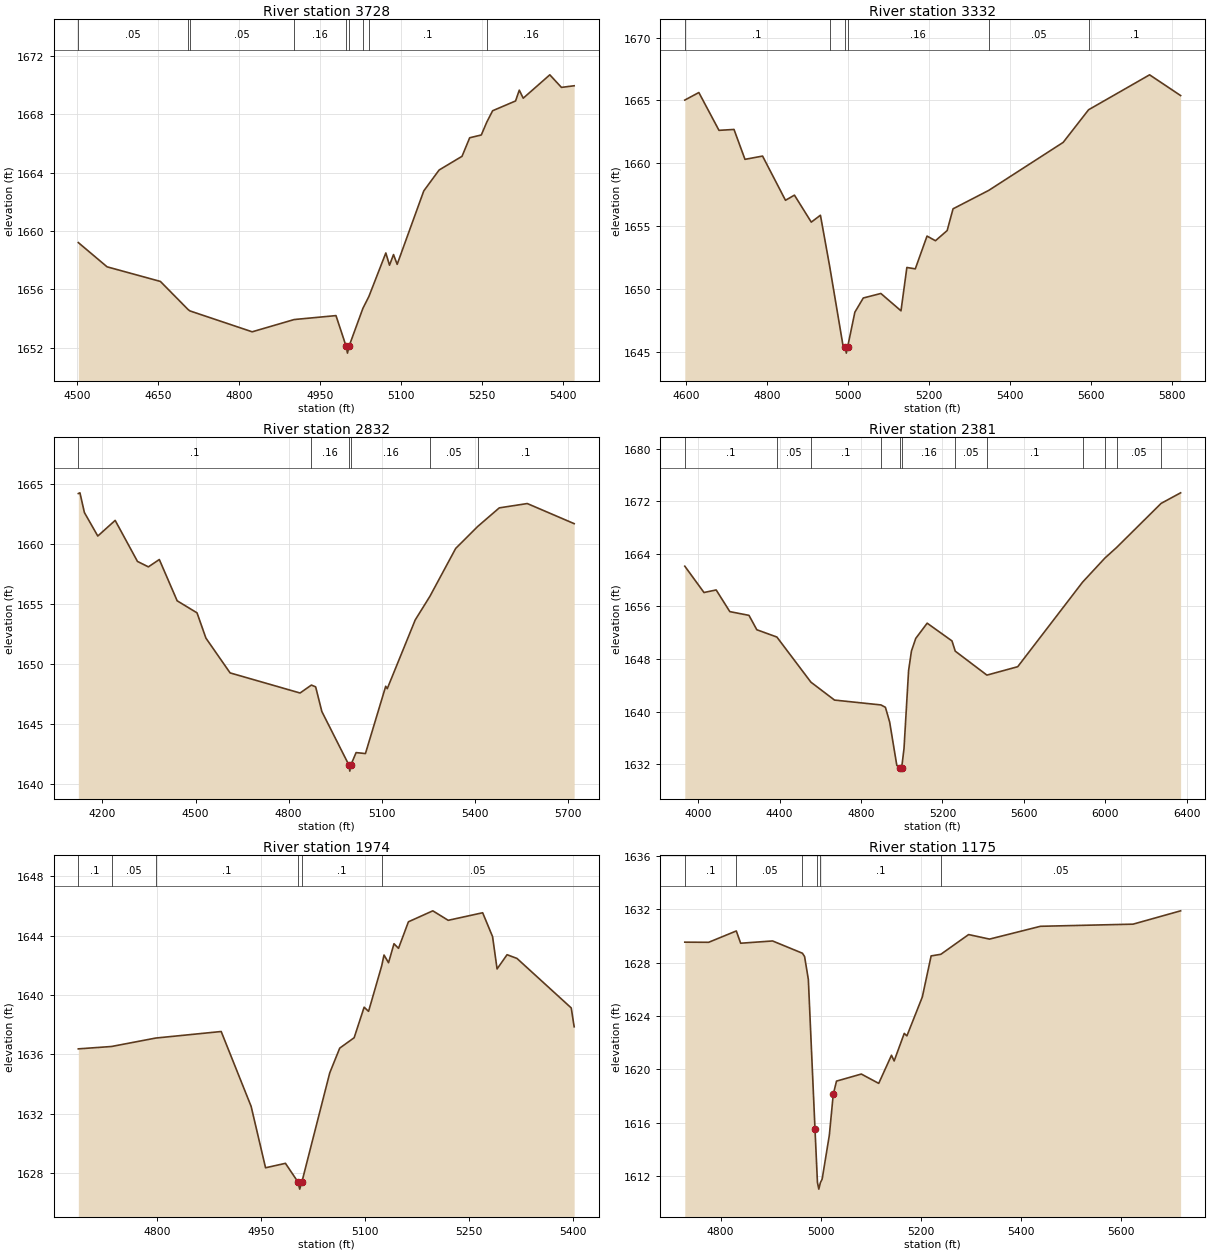
Type RM Length L Ch R = 1 ,3728    ,396,396,396
BEGIN DESCRIPTION:
UNT 1023 IN HEWA 6.0
END DESCRIPTION:
XS GIS Cut Line= 2
      2765542.41     10036564.67      2766167.41     10037238.28
#Sta/Elev= 30
  4501.9  1659.2  4555.2 1657.54    4654 1656.54  4705.2 1654.62  4708.8 1654.52
  4824.1 1653.09  4901.9 1653.93  4979.4  1654.2  4997.9 1652.13  5000.7 1651.63
  5003.9 1652.13  5029.2 1654.69  5040.5 1655.52  5071.8 1658.49  5078.6 1657.65
    5086 1658.38  5092.8 1657.71  5142.1 1662.74  5170.5 1664.17    5213 1665.11
  5227.2 1666.38  5248.7 1666.57    5259 1667.46  5269.7 1668.23  5312.2  1668.9
  5319.1 1669.64  5326.4 1669.09  5375.7 1670.69  5397.2 1669.83  5420.8 1669.94
#Mann= 9 ,-1 , 0
  4501.9     .05       0  4705.2      .1       0  4708.8     .05       0
  4901.9     .16       0  4997.9     .07       0  5003.9     .16       0
  5029.2     .05       0  5040.5      .1       0    5259     .16       0
Bank Sta=4997.9,5003.9
XS Rating Curve= 0 ,0
Exp/Cntr=0.3,0.1

Type RM Length L Ch R = 1 ,3332    ,500,500,500
BEGIN DESCRIPTION:
UNT 1023 IN HEWA 5.0
END DESCRIPTION:
XS GIS Cut Line= 3
      2765182.66     10036720.09      2765915.31     10037293.01
      2766203.47     10037352.03
#Sta/Elev= 30
  4597.7 1665.03  4632.4 1665.63  4682.1 1662.62  4719.2 1662.69  4746.3 1660.31
  4789.7 1660.57  4846.3 1657.05  4868.4 1657.46    4910 1655.31  4932.6 1655.86
  4955.4 1651.79  4988.7 1645.41  4993.8 1645.38  4996.5 1644.88  4999.8 1645.38
  5017.6 1648.14  5038.4 1649.27  5081.8 1649.63  5131.5 1648.25    5146  1651.7
  5166.8 1651.59  5195.8  1654.2  5216.6 1653.83  5245.5 1654.64    5260 1656.37
  5348.2 1657.84  5531.9 1661.66  5594.7 1664.26  5745.3 1667.04  5821.9 1665.39
#Mann= 6 ,-1 , 0
  4597.7      .1       0  4955.4     .16       0  4993.8     .07       0
  4999.8     .16       0  5348.2     .05       0  5594.7      .1       0
Bank Sta=4993.8,4999.8
XS Rating Curve= 0 ,0
Exp/Cntr=0.3,0.1

Type RM Length L Ch R = 1 ,2832    ,451,451,451
BEGIN DESCRIPTION:
UNT 1023 IN HEWA 4.0
END DESCRIPTION:
XS GIS Cut Line= 3
      2764890.98     10036893.67      2765276.42      10037369.4
      2766259.08     10037445.79
#Sta/Elev= 30
  4122.3 1664.17  4127.5 1664.23  4141.9 1662.59    4185 1660.64    4241 1661.94
  4312.9 1658.53  4348.1 1658.08  4383.3 1658.69  4440.8 1655.26  4504.8 1654.26
  4533.5 1652.16  4611.4 1649.27  4836.9  1647.6  4873.4 1648.26  4887.1 1648.11
  4907.1 1646.06  4994.4 1641.61  4997.2 1641.11  5000.4 1641.61  5017.5 1642.65
  5047.6 1642.57  5112.9 1648.16  5117.9 1647.96    5208 1653.67  5255.5 1655.64
  5338.4 1659.61  5409.6 1661.44  5478.9 1662.98  5569.1 1663.34  5720.2 1661.67
#Mann= 6 ,-1 , 0
  4122.3      .1       0  4873.4     .16       0  4994.4     .07       0
  5000.4     .16       0  5255.5     .05       0  5409.6      .1       0
Bank Sta=4994.4,5000.4
XS Rating Curve= 0 ,0
Exp/Cntr=0.3,0.1

Type RM Length L Ch R = 1 ,2381    ,407,407,407
BEGIN DESCRIPTION:
UNT 1023 IN HEWA 3.0
END DESCRIPTION:
XS GIS Cut Line= 4
      2764838.93     10036977.05      2765144.47     10037563.84
      2765762.53     10038053.43      2766717.43     10038296.49
#Sta/Elev= 30
  3934.6 1662.14  4028.9 1658.13  4088.7 1658.52  4155.8 1655.22  4249.9 1654.65
  4288.4 1652.46  4386.9 1651.35    4554 1644.48    4670 1641.75    4898 1641.01
    4920 1640.65  4940.8 1638.41    4976  1631.8  4993.8 1631.43  4996.6 1630.93
  4999.8 1631.43  5011.3 1634.36  5033.8 1646.23  5047.8 1649.21    5069 1651.14
  5125.1 1653.46  5246.9 1650.76    5263  1649.2  5418.5 1645.55  5569.8 1646.83
  5888.2  1659.7  5998.2 1663.38  6055.7 1664.99  6274.1  1671.7    6370 1673.31
#Mann= 12 ,-1 , 0
  3934.6      .1       0  4386.9     .05       0    4554      .1       0
    4898     .16       0  4993.8     .07       0  4999.8     .16       0
    5263     .05       0  5418.5      .1       0  5888.2     .05       0
  5998.2      .1       0  6055.7     .05       0  6274.1      .1       0
Bank Sta=4993.8,4999.8
XS Rating Curve= 0 ,0
Exp/Cntr=0.3,0.1

Type RM Length L Ch R = 1 ,1974    ,799,799,799
BEGIN DESCRIPTION:
UNT 1023 IN HEWA 2.0
END DESCRIPTION:
XS GIS Cut Line= 2
      2764924.37     10037898.02      2765479.52     10038349.08
#Sta/Elev= 30
    4686 1636.36  4733.9 1636.52  4797.8 1637.09  4892.1 1637.53  4935.3 1632.48
  4956.1 1628.34  4984.8 1628.64  5002.6  1627.4  5005.4  1626.9  5008.6  1627.4
  5048.7 1634.74  5063.1 1636.41  5083.9 1637.11  5098.3 1639.17  5104.7 1638.89
  5123.6 1641.95    5127 1642.69  5133.5 1642.17  5141.4 1643.45  5147.9 1643.14
  5162.2 1644.93  5197.4 1645.67  5219.6 1645.03  5269.3 1645.54  5283.6 1643.93
  5290.1 1641.75  5304.5 1642.71  5318.8 1642.46  5397.1 1639.12  5401.3 1637.85
#Mann= 6 ,-1 , 0
    4686      .1       0  4733.9     .05       0  4797.8      .1       0
  5002.6     .07       0  5008.6      .1       0  5123.6     .05       0
Bank Sta=5002.6,5008.6
XS Rating Curve= 0 ,0
Exp/Cntr=0.3,0.1

Type RM Length L Ch R = 1 ,1175    ,551,551,551
BEGIN DESCRIPTION:
Mapping XS e631e63a
END DESCRIPTION:
XS GIS Cut Line= 3
      2764622.07     10038393.18      2764865.15     10038688.36
      2765438.03     10038892.34
#Sta/Elev= 30
  4728.6 1629.54  4776.3 1629.53  4831.5 1630.38  4840.2 1629.46    4904 1629.63
  4963.6 1628.71  4967.9 1628.46  4975.4 1626.75  4988.7 1615.52  4993.6 1611.52
  4996.3 1611.02  4999.6 1611.52    5003 1611.77  5017.4 1615.08  5025.2 1618.14
  5031.7 1619.12  5081.2 1619.65    5116 1618.95  5141.5 1621.06  5146.8 1620.63
    5167  1622.7  5172.3 1622.51  5203.1 1625.43  5220.7 1628.51  5240.1 1628.63
  5295.6 1630.11  5337.4 1629.77  5439.1 1630.73  5624.1 1630.89  5719.1 1631.89
#Mann= 6 ,-1 , 0
  4728.6      .1       0  4831.5     .05       0  4963.6      .1       0
  4993.6     .07       0  4999.6      .1       0  5240.1     .05       0
Bank Sta=4988.7,5025.2
XS Rating Curve= 0 ,0
Exp/Cntr=0.3,0.1

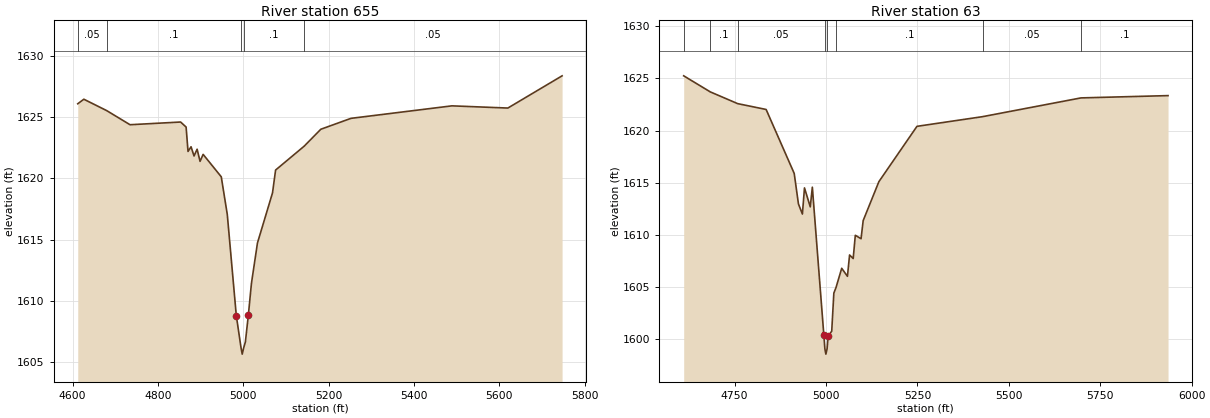
Type RM Length L Ch R = 1 ,655     ,592,592,592
BEGIN DESCRIPTION:
Mapping XS 2ae0149c
END DESCRIPTION:
XS GIS Cut Line= 4
      2764500.09     10038613.35      2764567.79      10038858.1
      2764872.48     10039154.98      2765324.53     10039212.14
#Sta/Elev= 30
  4612.1 1626.09  4626.4 1626.46    4680 1625.53  4734.6 1624.38  4853.1  1624.6
    4866 1624.19  4870.5  1622.2  4877.6 1622.58  4884.6 1621.83  4891.8 1622.38
  4898.7 1621.39  4905.9 1621.96  4948.4 1620.13  4962.5 1617.06  4983.6 1608.81
  4994.8 1606.16  4997.5 1605.66  5000.8 1606.16  5004.9 1606.65  5011.9 1608.85
  5019.1 1611.43  5033.2 1614.73  5068.5 1618.82  5075.7 1620.68  5142.7 1622.63
  5181.7 1624.01  5252.4  1624.9    5489 1625.92    5620 1625.74  5747.1 1628.37
#Mann= 5 ,-1 , 0
  4612.1     .05       0    4680      .1       0  4994.8     .07       0
  5000.8      .1       0  5142.7     .05       0
Bank Sta=4983.6,5011.9
XS Rating Curve= 0 ,0
Exp/Cntr=0.3,0.1

Type RM Length L Ch R = 1 ,63      ,0,0,0
BEGIN DESCRIPTION:
UNT 1023 IN HEWA 1.0
END DESCRIPTION:
XS GIS Cut Line= 4
      2764445.39     10038660.19      2764308.24     10038948.38
      2764546.09     10039356.37      2765073.67     10039432.73
#Sta/Elev= 30
  4610.9 1625.25  4683.5 1623.71  4758.5 1622.58  4836.3 1622.02  4913.1 1615.88
  4924.7 1612.95  4935.5 1611.98  4941.2 1614.49    4957 1612.67  4962.7 1614.56
  4994.1 1600.38    4997 1599.03  4999.7 1598.53    5003 1599.03  5005.7 1600.23
  5015.7 1600.74  5021.5 1604.39  5027.4 1604.92    5043 1606.77  5058.7    1606
  5064.5 1608.05  5074.4 1607.71  5080.2 1609.94  5095.9 1609.61  5101.7 1611.35
  5144.7 1615.09  5248.8  1620.4  5428.3 1621.33  5697.3 1623.13  5935.4 1623.35
#Mann= 8 ,-1 , 0
  4610.9     .05       0  4683.5      .1       0  4758.5     .05       0
    4997     .04       0    5003     .05       0  5027.4      .1       0
  5428.3     .05       0  5697.3      .1       0
Bank Sta=4994.1,5005.7
XS Rating Curve= 0 ,0
Exp/Cntr=0.3,0.1

Chan Stop Cuts=-1
Use User Specified Reach Order=0
Composite Channel Slope=5