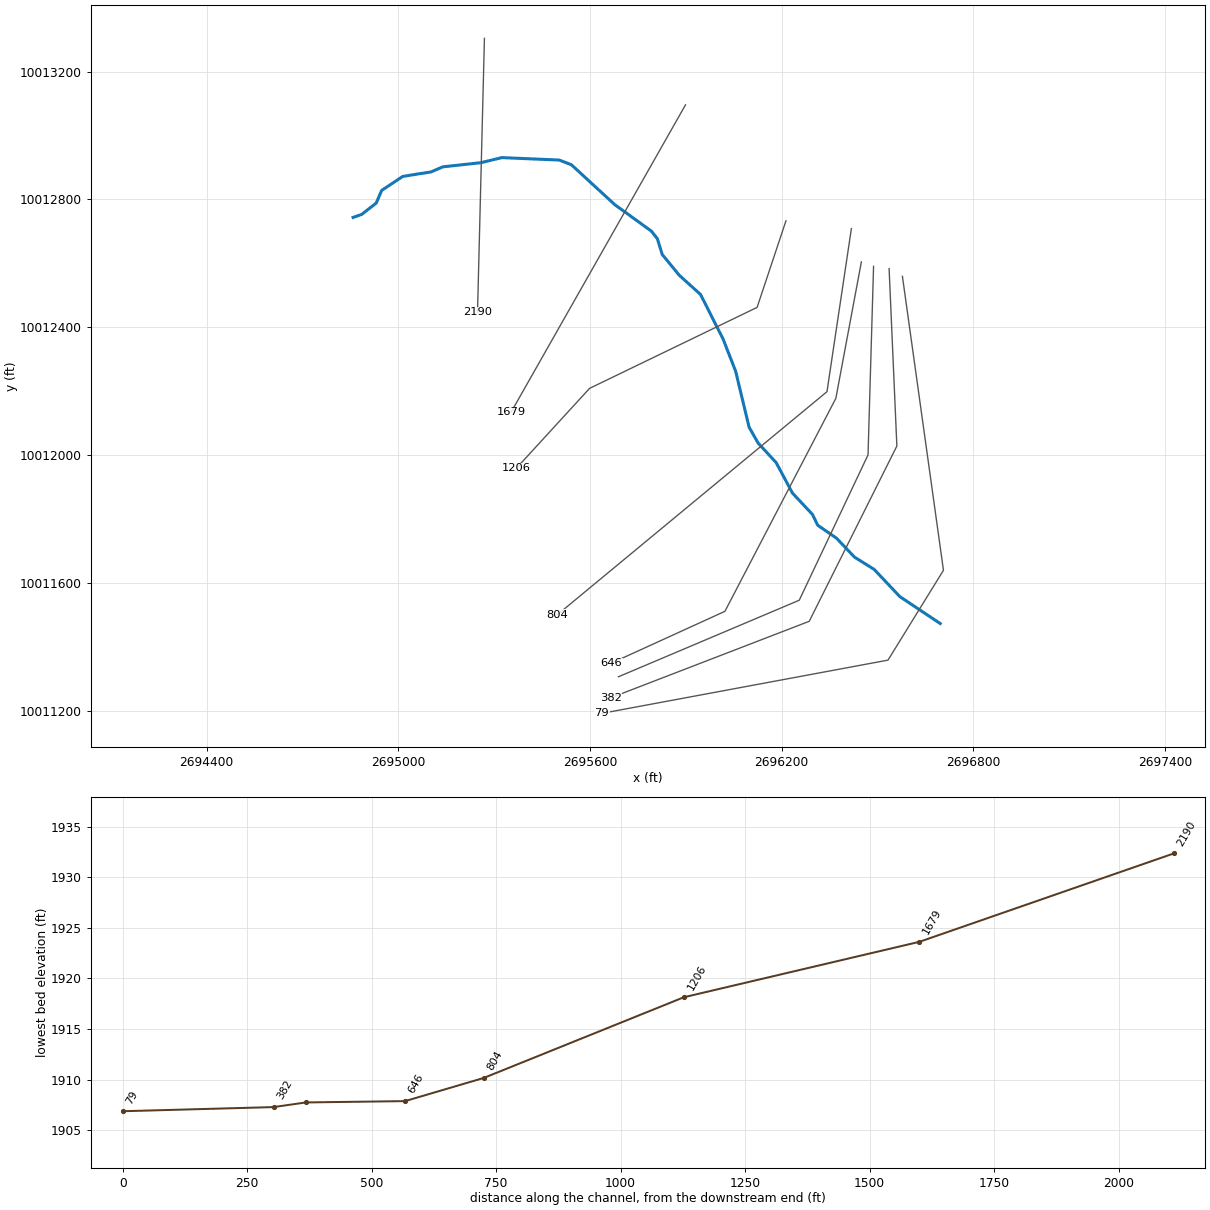
--- UNT 1025 IN HEWA.prj (project) ---

Proj Title=UNT 1025 IN HEWA Base Level Engineering
Current Plan=p01
Default Exp/Contr=0.3,0.1
English Units
Geom File=g01
Flow File=f01
Plan File=p01
BEGIN DESCRIPTION:
UNT 1025 IN HEWA
END DESCRIPTION:

--- UNT 1025 IN HEWA.p01 (plan) ---

Plan Title=Multiple Run
Short Identifier=Multiple
Geom File=g01
Flow File=f01
Subcritical Flow
K Sum by GR= 0
Std Step Tol= 0.01
Critical Tol= 0.01
Num of Std Step Trials= 20
Max Error Tol= 0.3
Flow Tol Ratio= 0.001
Split Flow NTrial= 30
Split Flow Tol= 0.02
Split Flow Ratio= 0.02
Log Output Level= 0
Friction Slope Method= 1
Unsteady Friction Slope Method= 2
Unsteady Bridges Friction Slope Method= 1
Parabolic Critical Depth
Global Vel Dist=  1 , 1 , 1
Global Log Level= 0
CheckData=True
Encroach Param= -1, 0, 0, 0
BEGIN DESCRIPTION:
Multiple Run
END DESCRIPTION:

--- UNT 1025 IN HEWA.f01 (steady flow) ---

Flow Title=Multiple
Number of Profiles=7
Profile Names=10-year,25-year,50-year,1pct_min,100-year,1pct_plu,500-year
River Rch & RM= UNT 1025 IN HEWA,Reach-1,2190
    1285    1873    2384    2211    2990    4043    4699
Boundary for River Rch & Prof#=UNT 1025 IN HEWA,Reach-1,1
Up Type=0
Dn Type=3
Dn Slope=0.005
Boundary for River Rch & Prof#=UNT 1025 IN HEWA,Reach-1,2
Up Type=0
Dn Type=3
Dn Slope=0.005
Boundary for River Rch & Prof#=UNT 1025 IN HEWA,Reach-1,3
Up Type=0
Dn Type=3
Dn Slope=0.005
Boundary for River Rch & Prof#=UNT 1025 IN HEWA,Reach-1,4
Up Type=0
Dn Type=3
Dn Slope=0.005
Boundary for River Rch & Prof#=UNT 1025 IN HEWA,Reach-1,5
Up Type=0
Dn Type=3
Dn Slope=0.005
Boundary for River Rch & Prof#=UNT 1025 IN HEWA,Reach-1,6
Up Type=0
Dn Type=3
Dn Slope=0.005
Boundary for River Rch & Prof#=UNT 1025 IN HEWA,Reach-1,7
Up Type=0
Dn Type=3
Dn Slope=0.005

--- UNT 1025 IN HEWA.g01 (geometry) ---

Geom Title=Existing Conditions

River Reach=UNT 1025 IN HEWA,Reach-1
Reach XY= 30
      2694858.47     10012743.73      2694885.41     10012753.40
      2694930.76     10012788.73      2694947.85     10012828.38
      2695013.89     10012872.21      2695102.26     10012886.25
      2695139.08     10012902.15      2695258.52     10012915.15
      2695323.92     10012931.04      2695503.34     10012923.43
      2695541.43     10012908.93      2695677.39     10012783.86
      2695792.16     10012700.89      2695810.67     10012677.22
      2695826.14     10012627.60      2695879.67     10012562.49
      2695945.96     10012502.61      2696016.56     10012362.94
      2696055.75     10012262.58      2696097.94     10012087.18
      2696126.45     10012037.21      2696182.72     10011976.30
      2696233.65     10011880.94      2696296.32     10011814.07
      2696312.77     10011780.26      2696371.52     10011739.74
      2696427.80     10011680.60      2696489.21     10011642.27
      2696569.66     10011557.02      2696696.15     10011472.64

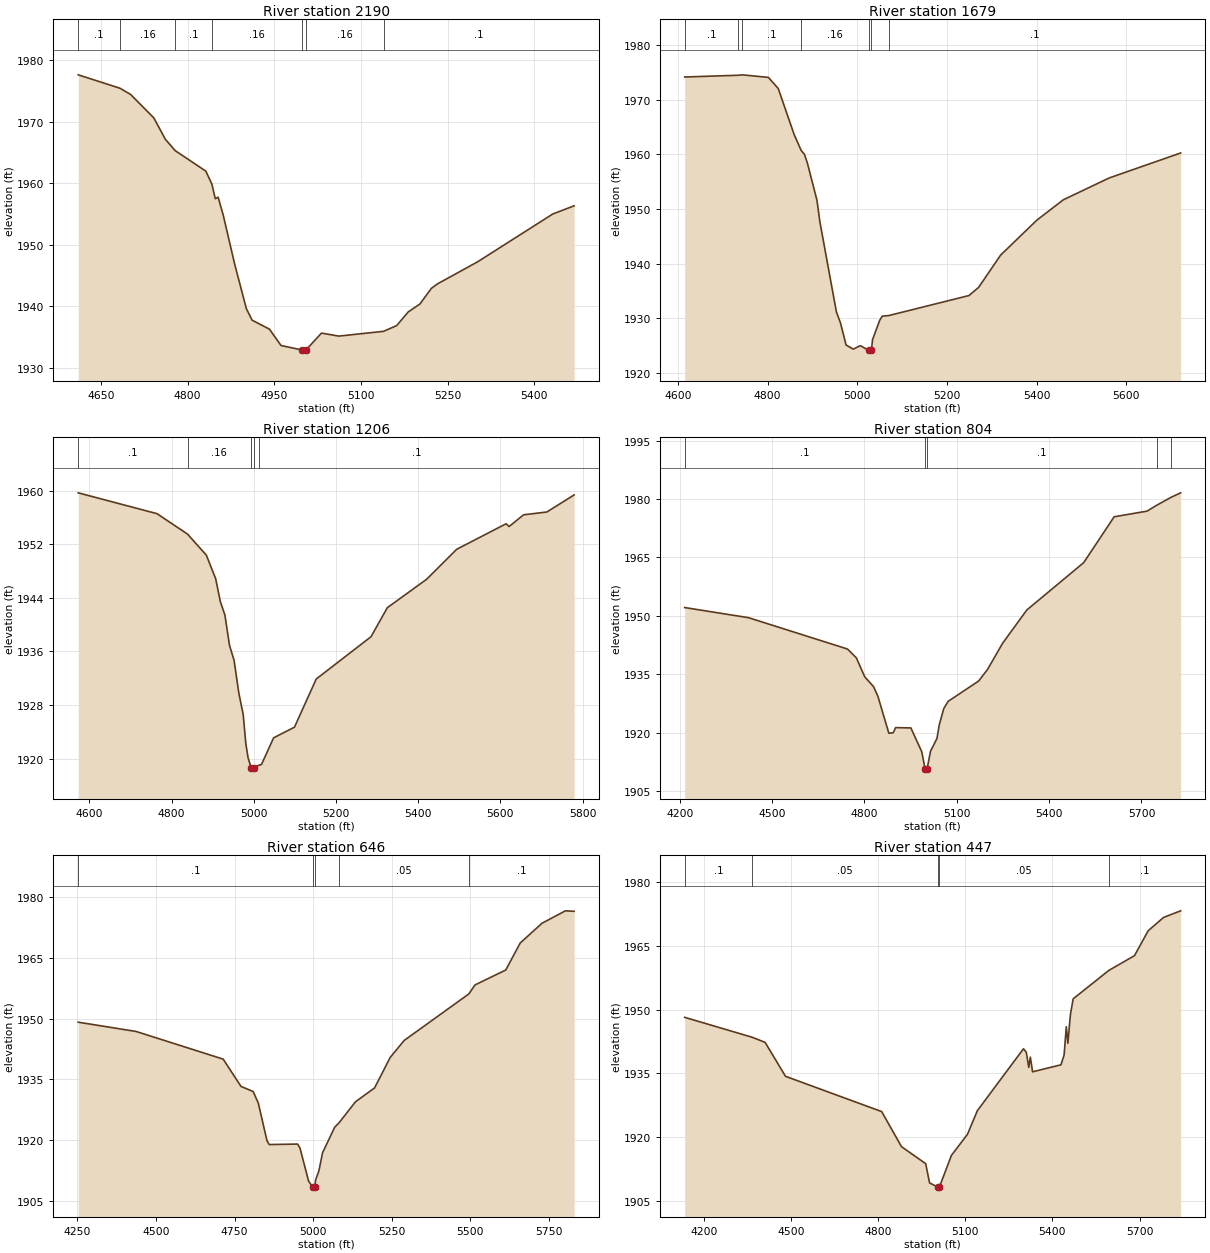
Type RM Length L Ch R = 1,2190,511,511,511
BEGIN DESCRIPTION:
UNT 1025 IN HEWA 4.0
END DESCRIPTION:
XS GIS Cut Line= 2
      2695269.48     10013304.40      2695247.83     10012446.88
#Sta/Elev= 30
  4610.9 1977.64  4683.1 1975.46  4701.6 1974.44  4741.6 1970.64  4761.6 1967.16
  4778.6 1965.31  4831.6 1961.97  4842.1 1959.87  4847.9 1957.49  4852.9 1957.73
  4861.7 1954.83  4881.7 1946.77  4901.7 1939.61  4911.7 1937.72  4941.7 1936.26
  4961.7 1933.60  4998.7 1932.86  5001.4 1932.36  5004.7 1932.86  5031.7 1935.62
  5061.7 1935.13  5139.2 1935.91  5161.7 1936.84  5181.8 1939.07  5201.8 1940.34
  5221.8 1942.90  5231.8 1943.60  5301.8 1947.22  5431.8 1955.00  5468.7 1956.33
#Mann=7,-1,0
  4610.9     0.1       0  4683.1    0.16       0  4778.6     0.1       0
  4842.1    0.16       0  4998.7    0.07       0  5004.7    0.16       0
  5139.2     0.1       0
Bank Sta=4998.7,5004.7
Exp/Cntr=0.3,0.1

Type RM Length L Ch R = 1,1679,473,473,473
BEGIN DESCRIPTION:
UNT 1025 IN HEWA 3.0
END DESCRIPTION:
XS GIS Cut Line= 2
      2695898.84     10013096.11      2695352.71     10012133.89
#Sta/Elev= 30
  4614.9 1974.17  4734.4 1974.49  4743.1 1974.57  4801.6 1974.10  4823.6 1972.07
  4859.1 1963.64  4874.7 1960.74  4882.1 1960.01  4888.5 1958.46  4910.1 1951.58
  4916.6 1947.63  4953.4 1931.16  4962.6 1929.12  4975.0 1925.11  4990.9 1924.35
  5006.8 1924.99  5025.4 1924.12  5028.1 1923.62  5031.4 1924.12  5034.1 1926.11
  5050.0 1929.63  5055.8 1930.39  5070.4 1930.50  5249.1 1934.16  5270.7 1935.66
  5319.7 1941.56  5400.4 1947.95  5459.6 1951.69  5562.0 1955.69  5721.3 1960.26
#Mann=7,-1,0
  4614.9     0.1       0  4734.4    0.16       0  4743.1     0.1       0
  4874.7    0.16       0  5025.4    0.07       0  5031.4    0.16       0
  5070.4     0.1       0
Bank Sta=5025.4,5031.4
Exp/Cntr=0.3,0.1

Type RM Length L Ch R = 1,1206,402,402,402
BEGIN DESCRIPTION:
UNT 1025 IN HEWA 2.0
END DESCRIPTION:
XS GIS Cut Line= 4
      2696213.25     10012733.11      2696122.96     10012462.25
      2695598.66     10012208.78      2695369.49     10011958.79
#Sta/Elev= 30
  4572.6 1959.68  4764.3 1956.57  4838.7 1953.52  4884.5 1950.37  4907.1 1946.87
  4918.6 1943.43  4929.7 1941.42  4940.8 1936.91  4952.0 1934.67  4963.4 1929.83
  4974.2 1926.57  4980.4 1922.31  4986.0 1920.14  4993.4 1918.64  4996.1 1918.14
  4999.4 1918.64  5012.1 1919.01  5018.6 1919.13  5048.2 1923.11  5098.9 1924.70
  5151.9 1931.89  5285.2 1938.20  5324.9 1942.53  5420.8 1946.79  5493.7 1951.25
  5613.9 1955.06  5621.3 1954.65  5656.5 1956.40  5713.2 1956.82  5779.6 1959.37
#Mann=5,-1,0
  4572.6     0.1       0  4838.7    0.16       0  4993.4    0.07       0
  4999.4    0.16       0  5012.1     0.1       0
Bank Sta=4993.4,4999.4
Exp/Cntr=0.3,0.1

Type RM Length L Ch R = 1,804,158,158,158
BEGIN DESCRIPTION:
Mapping XS 0b9806d8
END DESCRIPTION:
XS GIS Cut Line= 3
      2696418.10     10012708.81      2696341.71     10012198.37
      2695497.97     10011500.46
#Sta/Elev= 30
  4216.0 1952.15  4423.4 1949.55  4745.0 1941.50  4773.7 1939.23  4801.2 1934.34
  4829.7 1931.84  4844.0 1929.31  4879.2 1919.89  4893.5 1920.01  4901.3 1921.33
  4950.8 1921.25  4986.0 1915.17  4997.3 1910.66  5000.1 1910.16  5003.3 1910.66
  5014.7 1915.28  5035.5 1918.52  5043.3 1922.12  5057.7 1926.22  5072.0 1928.08
  5171.0 1933.29  5199.6 1936.23  5249.1 1943.01  5327.3 1951.51  5512.3 1963.68
  5611.2 1975.45  5718.1 1976.90  5749.5 1978.41  5797.1 1980.49  5827.1 1981.60
#Mann=5,-1,0
  4216.0     0.1       0  4997.3    0.07       0  5003.3     0.1       0
  5749.5    0.16       0  5797.1     0.1       0
Bank Sta=4997.3,5003.3
Exp/Cntr=0.3,0.1

Type RM Length L Ch R = 1,646,199,199,199
BEGIN DESCRIPTION:
Mapping XS ba40ff2c
END DESCRIPTION:
XS GIS Cut Line= 4
      2696449.34     10012604.57      2696369.49     10012177.53
      2696022.27     10011510.87      2695665.83     10011348.22
#Sta/Elev= 30
  4252.6 1949.11  4436.6 1946.82  4713.9 1939.98  4770.5 1933.25  4809.0 1931.99
  4825.5 1929.16  4853.2 1919.85  4860.4 1918.88  4950.6 1919.00  4958.1 1918.03
  4985.8 1909.81  4999.3 1908.37  5002.0 1907.87  5005.3 1908.37  5007.9 1910.14
  5018.3 1912.33  5030.0 1916.85  5068.6 1923.16  5082.9 1924.29  5134.9 1929.46
  5195.5 1932.87  5245.4 1940.42  5289.6 1944.59  5495.6 1956.10  5515.2 1958.32
  5612.9 1962.00  5658.9 1968.67  5728.0 1973.54  5802.6 1976.62  5830.5 1976.50
#Mann=5,-1,0
  4252.6     0.1       0  4999.3    0.07       0  5005.3     0.1       0
  5082.9    0.05       0  5495.6     0.1       0
Bank Sta=4999.3,5005.3
Exp/Cntr=0.3,0.1

Type RM Length L Ch R = 1,447,65,65,65
BEGIN DESCRIPTION:
Mapping XS 4a634e36
END DESCRIPTION:
XS GIS Cut Line= 4
      2696487.54     10012590.75      2696470.18     10012000.45
      2696254.91     10011545.59      2695688.92     10011306.00
#Sta/Elev= 30
  4133.2 1948.20  4366.0 1943.50  4410.3 1942.30  4480.4 1934.31  4811.9 1926.00
  4880.1 1917.74  4963.5 1913.73  4976.7 1909.21  5004.8 1908.24  5007.5 1907.74
  5010.8 1908.24  5052.0 1915.68  5107.3 1920.64  5141.5 1926.22  5300.2 1940.79
  5310.0 1939.97  5318.5 1936.42  5323.9 1938.83  5331.7 1935.37  5429.5 1937.02
  5440.3 1939.34  5447.8 1945.98  5453.2 1942.09  5462.0 1948.86  5471.5 1952.56
  5594.6 1959.26  5682.7 1962.72  5730.0 1968.60  5782.8 1971.72  5841.6 1973.28
#Mann=5,-1,0
  4133.2     0.1       0  4366.0    0.05       0  5004.8    0.04       0
  5010.8    0.05       0  5594.6     0.1       0
Bank Sta=5004.8,5010.8
Exp/Cntr=0.3,0.1

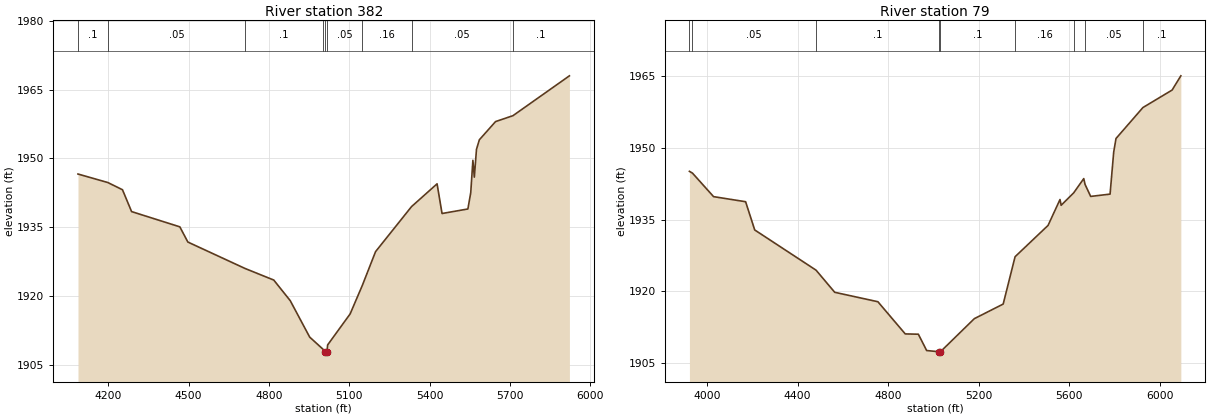
Type RM Length L Ch R = 1,382,303,303,303
BEGIN DESCRIPTION:
Mapping XS 3d6986d2
END DESCRIPTION:
XS GIS Cut Line= 4
      2696536.16     10012583.73      2696560.46     10012028.23
      2696286.16     10011479.62      2695664.64     10011240.04
#Sta/Elev= 30
  4087.0 1946.60  4198.2 1944.75  4253.2 1943.17  4287.2 1938.40  4467.4 1935.07
  4497.4 1931.75  4711.0 1925.98  4818.3 1923.45  4879.8 1918.95  4952.4 1911.00
  5002.0 1908.36  5010.9 1907.78  5013.7 1907.28  5016.9 1907.78  5019.5 1909.29
  5103.4 1916.05  5149.1 1922.29  5198.4 1929.65  5332.7 1939.48  5428.2 1944.46
  5446.8 1937.98  5543.3 1938.97  5554.0 1942.54  5562.0 1949.59  5567.4 1945.92
  5575.4 1951.99  5586.2 1954.08  5646.6 1958.05  5711.7 1959.34  5922.5 1968.04
#Mann=9,-1,0
  4087.0     0.1       0  4198.2    0.05       0  4711.0     0.1       0
  5002.0    0.05       0  5010.9    0.07       0  5016.9    0.05       0
  5149.1    0.16       0  5332.7    0.05       0  5711.7     0.1       0
Bank Sta=5010.9,5016.9
Exp/Cntr=0.3,0.1

Type RM Length L Ch R = 1,79,0,0,0
BEGIN DESCRIPTION:
UNT 1025 IN HEWA 1.0
END DESCRIPTION:
XS GIS Cut Line= 4
      2696577.82     10012559.50      2696706.29     10011639.34
      2696532.68     10011358.09      2695636.86     10011191.42
#Sta/Elev= 30
  3921.9 1945.13  3935.5 1944.75  4028.7 1939.83  4170.1 1938.77  4210.4 1932.86
  4481.4 1924.44  4563.8 1919.81  4754.4 1917.84  4875.3 1911.10  4933.2 1911.04
  4969.9 1907.62  5024.8 1907.37  5027.6 1906.87  5030.8 1907.37  5180.4 1914.29
  5307.9 1917.35  5360.5 1927.26  5506.1 1933.81  5558.9 1939.23  5564.0 1938.02
  5619.4 1940.63  5663.9 1943.61  5669.5 1942.40  5694.4 1939.88  5780.1 1940.36
  5796.1 1949.16  5806.3 1952.00  5925.2 1958.48  6054.1 1962.14  6092.7 1965.12
#Mann=9,-1,0
  3921.9     0.1       0  3935.5    0.05       0  4481.4     0.1       0
  5024.8    0.07       0  5030.8     0.1       0  5360.5    0.16       0
  5619.4     0.1       0  5669.5    0.05       0  5925.2     0.1       0
Bank Sta=5024.8,5030.8
Exp/Cntr=0.3,0.1

Chan Stop Cuts=-1