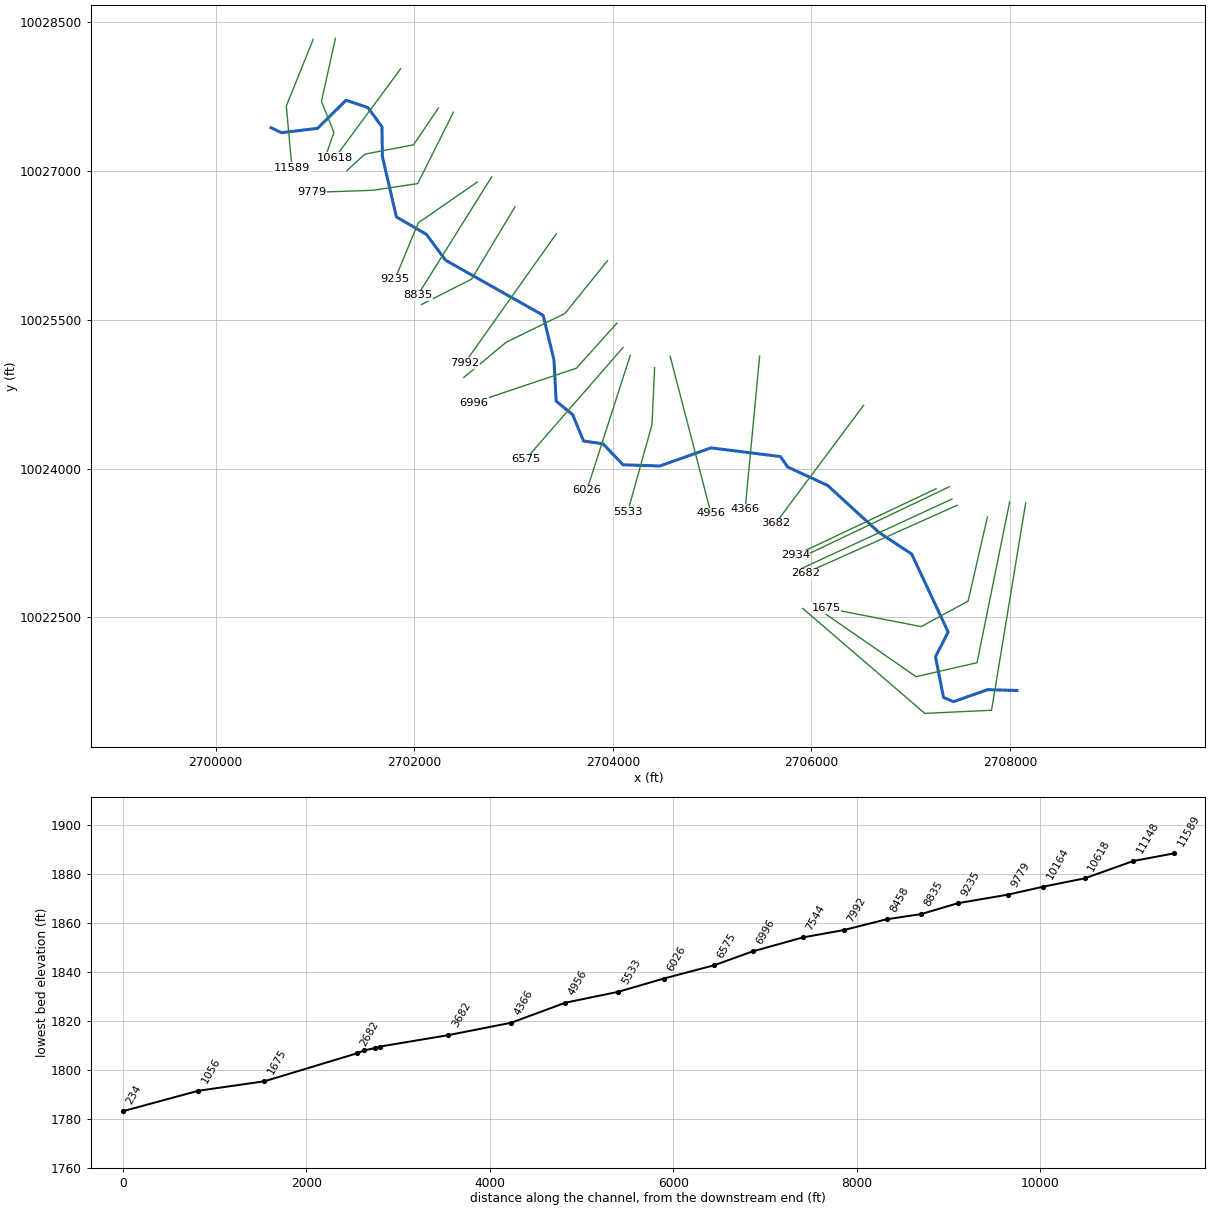
--- UNT 1028 IN HEWA.prj (project) ---

Proj Title=UNT 1028 IN HEWA Base Level Engineering
Current Plan=p01
Default Exp/Contr=0.3,0.1
English Units
Geom File=g01
Flow File=f01
Plan File=p01
Y Axis Title=Elevation
X Axis Title(PF)=Main Channel Distance
X Axis Title(XS)=Station
BEGIN DESCRIPTION:
UNT 1028 IN HEWA
END DESCRIPTION:
DSS Export Rating Curves= 0
DSS Export Rating Curve Sorted= 0
DSS Export Volume Flow Curves= 0
DXF OffsetX= 0
DXF OffsetY= 0
DXF ScaleX= 1
DXF ScaleY= 10

--- UNT 1028 IN HEWA.p01 (plan) ---

Plan Title=Multiple Run
Short Identifier=Multiple
Geom File=g01
Flow File=f01
Subcritical Flow
K Sum by GR= 0
Std Step Tol= 0.01
Critical Tol= 0.01
Num of Std Step Trials= 20
Max Error Tol= 0.3
Flow Tol Ratio= 0.001
Split Flow NTrial= 30
Split Flow Tol= 0.02
Split Flow Ratio= 0.02
Log Output Level= 0
Friction Slope Method= 1
Unsteady Friction Slope Method= 2
Unsteady Bridges Friction Slope Method= 1
Parabolic Critical Depth
Global Vel Dist=  1 , 1 , 1
Global Log Level= 0
CheckData=True
Encroach Param= -1, 0, 0, 0
BEGIN DESCRIPTION:
Multiple Run
END DESCRIPTION:

--- UNT 1028 IN HEWA.f01 (steady flow) ---

Flow Title=Multiple
Number of Profiles=7
Profile Names=10-year,25-year,50-year,1pct_min,100-year,1pct_plu,500-year
River Rch & RM= UNT 1028 IN HEWA,Reach-1,11589
    2144    3216    4169    3932    5318    7191    8652
River Rch & RM= UNT 1028 IN HEWA,Reach-1,2765
    2188    3283    4257    4016    5431    7345    8839
Boundary for River Rch & Prof#=UNT 1028 IN HEWA,Reach-1,1
Up Type=0
Dn Type=3
Dn Slope=0.005
Boundary for River Rch & Prof#=UNT 1028 IN HEWA,Reach-1,2
Up Type=0
Dn Type=3
Dn Slope=0.005
Boundary for River Rch & Prof#=UNT 1028 IN HEWA,Reach-1,3
Up Type=0
Dn Type=3
Dn Slope=0.005
Boundary for River Rch & Prof#=UNT 1028 IN HEWA,Reach-1,4
Up Type=0
Dn Type=3
Dn Slope=0.005
Boundary for River Rch & Prof#=UNT 1028 IN HEWA,Reach-1,5
Up Type=0
Dn Type=3
Dn Slope=0.005
Boundary for River Rch & Prof#=UNT 1028 IN HEWA,Reach-1,6
Up Type=0
Dn Type=3
Dn Slope=0.005
Boundary for River Rch & Prof#=UNT 1028 IN HEWA,Reach-1,7
Up Type=0
Dn Type=3
Dn Slope=0.005

--- UNT 1028 IN HEWA.g01 (geometry) ---

Geom Title=Existing Conditions
Program Version=4.10

River Reach=UNT 1028 IN HEWA,Reach-1
Reach XY= 30
      2700558.47     10027433.73      2700663.42     10027383.43
      2701026.97     10027427.35      2701314.09      10027710.9
      2701534.92     10027635.51      2701675.62     10027442.55
      2701679.44     10027144.28      2701820.91     10026534.65
      2702122.69     10026359.52      2702315.78     10026098.73
      2703298.09     10025543.73       2703407.2      10025093.8
      2703429.15       10024679.      2703595.65     10024542.05
      2703705.09     10024277.21      2703901.13     10024248.27
      2704103.33      10024037.3      2704472.64     10024025.63
      2704988.44     10024207.76      2705687.08     10024120.49
      2705760.37     10024015.34      2706162.54     10023829.56
      2706680.04     10023355.38      2707008.66     10023138.54
        2707376.     10022352.48       2707248.6     10022103.66
      2707329.13     10021694.36      2707430.32     10021650.92
      2707773.97     10021772.04      2708068.47     10021763.73

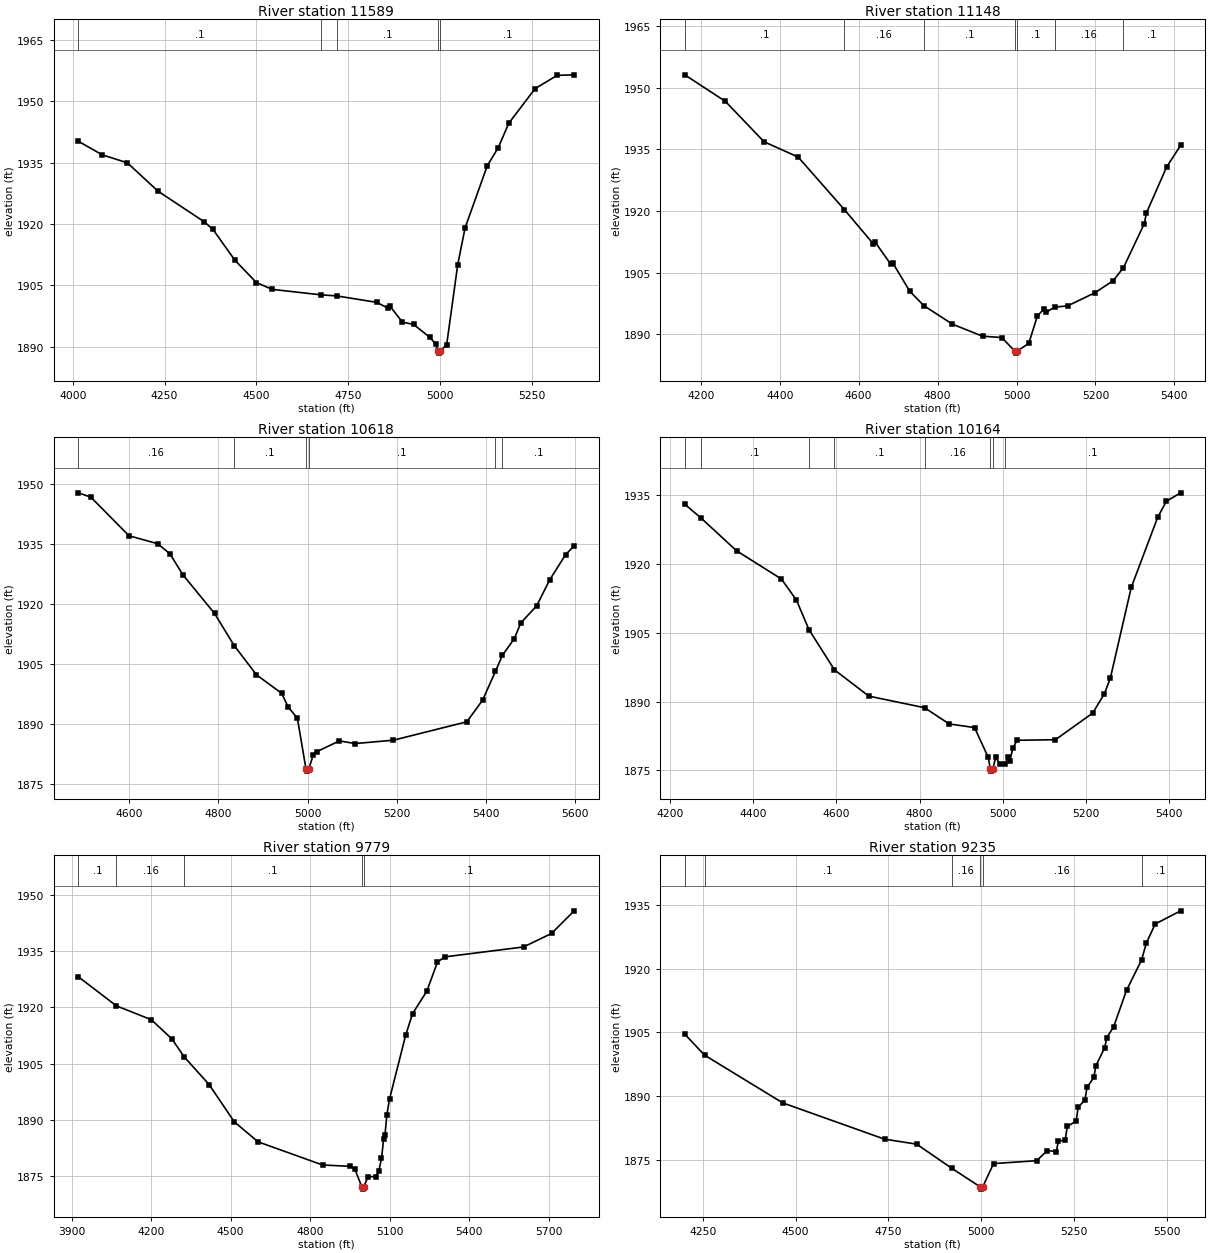
Type RM Length L Ch R = 1 ,11589   ,441,441,441
BEGIN DESCRIPTION:
UNT 1028 IN HEWA 23.0
END DESCRIPTION:
XS GIS Cut Line= 3
      2700983.03     10028323.85      2700712.19     10027651.96
       2700769.4      10027027.8
#Sta/Elev= 30
  4014.9 1940.24  4079.7 1936.93  4148.6 1934.96  4231.9 1928.05    4358 1920.55
  4381.6 1918.72  4441.3 1911.19  4500.4 1905.69  4543.3 1904.04  4676.5  1902.7
  4719.2 1902.44  4827.9 1900.87  4857.9  1899.5    4863 1900.06  4898.2 1896.02
  4928.3 1895.49    4973  1892.3  4988.6 1890.68  4995.6 1888.96  4998.4 1888.46
  5001.6 1888.96  5018.7 1890.53  5048.8 1910.09  5068.9 1919.09  5129.2 1934.22
  5159.3 1938.69    5188 1944.64  5259.7 1953.11    5320 1956.35  5366.1 1956.47
#Mann= 5 ,-1 , 0
  4014.9      .1       0  4676.5     .05       0  4719.2      .1       0
  4995.6     .07       0  5001.6      .1       0
Bank Sta=4995.6,5001.6
XS Rating Curve= 0 ,0
Exp/Cntr=0.3,0.1

Type RM Length L Ch R = 1 ,11148   ,530,530,530
BEGIN DESCRIPTION:
UNT 1028 IN HEWA 22.0
END DESCRIPTION:
XS GIS Cut Line= 4
      2701206.98     10028334.23      2701066.36     10027698.83
      2701191.36     10027386.33      2701103.13     10027132.04
#Sta/Elev= 30
  4159.4 1953.15  4262.3 1946.68  4360.2 1936.85  4446.7 1933.12  4563.8 1920.32
  4637.3 1911.96  4642.4 1912.33  4680.9 1907.07    4686  1907.4  4729.7 1900.41
  4765.1 1896.94  4837.2 1892.44    4914 1889.49  4962.5 1889.17  4995.8 1885.87
  4998.5 1885.37  5001.8 1885.87  5031.1 1887.73  5052.6 1894.35  5070.2 1896.22
  5075.6 1895.35  5096.7 1896.58  5129.4 1896.87  5199.2  1900.1  5244.8    1903
  5271.1  1906.2  5323.7 1916.87  5329.4 1919.55  5380.7 1930.76  5415.9 1935.96
#Mann= 7 ,-1 , 0
  4159.4      .1       0  4563.8     .16       0  4765.1      .1       0
  4995.8     .07       0  5001.8      .1       0  5096.7     .16       0
  5271.1      .1       0
Bank Sta=4995.8,5001.8
XS Rating Curve= 0 ,0
Exp/Cntr=0.3,0.1

Type RM Length L Ch R = 1 ,10618   ,454,454,454
BEGIN DESCRIPTION:
UNT 1028 IN HEWA 21.0
END DESCRIPTION:
XS GIS Cut Line= 2
      2701863.24     10028026.98       2701202.6     10027132.25
#Sta/Elev= 30
  4485.7 1947.72  4513.7 1946.65  4599.3 1937.01  4663.8 1935.02  4691.1 1932.52
  4720.4 1927.25  4791.3 1917.62  4835.6 1909.56  4885.3 1902.32  4941.7 1897.71
  4956.3 1894.32  4977.1 1891.47  4996.4 1878.79  4999.1 1878.29  5002.4 1878.79
  5012.6 1882.29    5021 1883.17  5071.2 1885.83  5106.6 1885.17  5192.2    1886
  5357.2  1890.6  5392.7 1896.02  5421.2 1903.16  5436.9 1907.18  5463.6 1911.33
  5478.3 1915.28  5513.8 1919.53    5543    1926  5578.5 1932.27  5597.9 1934.52
#Mann= 6 ,-1 , 0
  4485.7     .16       0  4835.6      .1       0  4996.4     .07       0
  5002.4      .1       0  5421.2     .16       0  5436.9      .1       0
Bank Sta=4996.4,5002.4
XS Rating Curve= 0 ,0
Exp/Cntr=0.3,0.1

Type RM Length L Ch R = 1 ,10164   ,385,385,385
BEGIN DESCRIPTION:
UNT 1028 IN HEWA 20.0
END DESCRIPTION:
XS GIS Cut Line= 4
      2702243.41     10027631.08      2701993.44     10027261.33
      2701503.86     10027167.58      2701322.52     10027001.79
#Sta/Elev= 30
  4236.4 1933.02  4274.2 1930.13  4360.6 1922.89  4468.5 1916.73  4504.5 1912.13
  4534.4 1905.72  4595.8 1896.93  4678.2 1891.21  4812.1 1888.68  4871.1 1885.15
  4932.1 1884.35  4965.1 1877.84  4969.9 1875.36  4972.6 1874.86  4975.9 1875.36
  4983.1  1877.9  4993.2 1876.34  5005.3 1876.33    5012 1877.85  5017.1 1877.17
  5023.8  1879.8    5034 1881.58  5126.3 1881.71  5215.8 1887.51  5244.1 1891.76
  5258.3 1895.18  5308.3 1914.89  5371.8 1930.17  5392.7 1933.69  5426.9 1935.52
#Mann= 8 ,-1 , 0
  4236.4     .16       0  4274.2      .1       0  4534.4     .16       0
  4595.8      .1       0  4812.1     .16       0  4969.9     .07       0
  4975.9     .16       0  5005.3      .1       0
Bank Sta=4969.9,4975.9
XS Rating Curve= 0 ,0
Exp/Cntr=0.3,0.1

Type RM Length L Ch R = 1 ,9779    ,544,544,544
BEGIN DESCRIPTION:
UNT 1028 IN HEWA 19.0
END DESCRIPTION:
XS GIS Cut Line= 4
      2702394.48     10027589.46      2702035.11     10026870.71
      2701581.98       10026803.      2700973.08     10026782.18
#Sta/Elev= 30
  3925.7 1928.14  4069.3  1920.4  4201.2  1916.7  4278.7  1911.6  4325.9 1906.75
  4419.2 1899.45  4514.2 1889.53  4603.6 1884.21  4847.2 1878.04  4949.5 1877.68
  4968.6 1877.05  4995.9 1872.11  4998.6 1871.61  5001.9 1872.11  5019.1 1874.93
  5049.4 1874.94  5059.5  1876.4  5069.7  1879.8  5077.9 1884.96  5082.9 1886.13
  5089.9 1891.37    5100 1895.59  5160.7 1912.53  5186.7  1918.3    5241 1924.34
    5281 1932.07  5309.2 1933.44  5605.6 1936.07  5711.3 1939.66  5796.7 1945.69
#Mann= 5 ,-1 , 0
  3925.7      .1       0  4069.3     .16       0  4325.9      .1       0
  4995.9     .07       0  5001.9      .1       0
Bank Sta=4995.9,5001.9
XS Rating Curve= 0 ,0
Exp/Cntr=0.3,0.1

Type RM Length L Ch R = 1 ,9235    ,400,400,400
BEGIN DESCRIPTION:
UNT 1028 IN HEWA 18.0
END DESCRIPTION:
XS GIS Cut Line= 3
      2702634.07     10026886.33      2702040.31     10026474.88
      2701806.27     10025907.97
#Sta/Elev= 30
  4201.3 1904.56  4254.4 1899.64  4465.1 1888.41  4739.3 1879.88  4825.8 1878.71
  4920.7 1873.02  4997.7 1868.63  5000.4 1868.13  5003.7 1868.63  5033.1 1874.14
    5149 1874.81  5178.3  1877.2  5202.2 1876.97  5207.6 1879.41  5226.2 1879.67
  5231.6 1882.88  5255.5 1884.09  5260.9 1887.35  5279.4 1889.14  5284.8 1892.03
  5303.3 1894.42  5308.7 1897.13  5332.7 1901.43  5338.1 1903.77  5356.6  1906.3
  5391.3  1914.9  5431.8    1922  5444.6 1925.98  5468.5 1930.47    5537 1933.57
#Mann= 6 ,-1 , 0
  4201.3     .16       0  4254.4      .1       0  4920.7     .16       0
  4997.7     .07       0  5003.7     .16       0  5431.8      .1       0
Bank Sta=4997.7,5003.7
XS Rating Curve= 0 ,0
Exp/Cntr=0.3,0.1

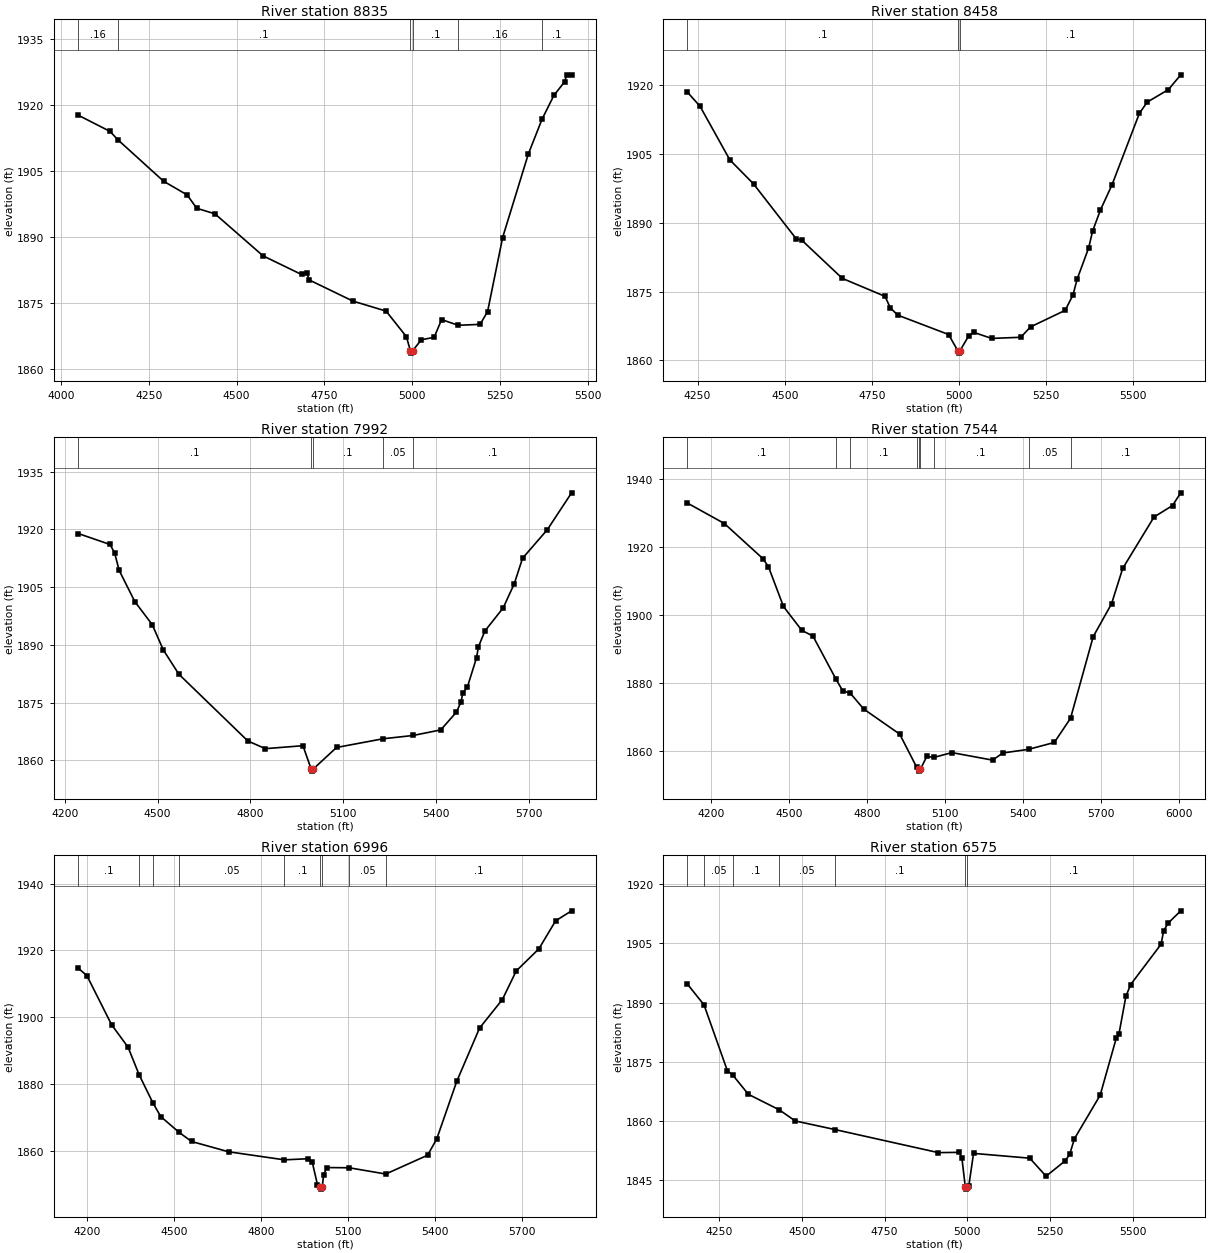
Type RM Length L Ch R = 1 ,8835    ,377,377,377
BEGIN DESCRIPTION:
UNT 1028 IN HEWA 17.0
END DESCRIPTION:
XS GIS Cut Line= 2
      2702779.91     10026938.43      2702036.05     10025747.21
#Sta/Elev= 30
  4049.2 1917.69    4140    1914  4161.2 1912.17  4292.2  1902.7  4359.4 1899.59
  4386.5 1896.56  4438.4  1895.3  4575.2 1885.77  4684.9 1881.53  4700.3 1881.93
  4706.2 1880.31  4831.2 1875.49  4925.6 1873.22  4983.4 1867.41  4994.9 1864.18
  4997.7 1863.68  5000.9 1864.18  5025.8 1866.71  5062.4 1867.27  5083.6 1871.29
  5130.9    1870  5193.3 1870.21  5214.5 1873.12  5257.3 1889.91  5330.1 1908.79
  5369.3 1916.74  5403.2 1922.17  5433.9 1925.29  5439.8 1926.85  5453.6 1926.79
#Mann= 6 ,-1 , 0
  4049.2     .16       0  4161.2      .1       0  4994.9     .07       0
  5000.9      .1       0  5130.9     .16       0  5369.3      .1       0
Bank Sta=4994.9,5000.9
XS Rating Curve= 0 ,0
Exp/Cntr=0.3,0.1

Type RM Length L Ch R = 1 ,8458    ,466,466,466
BEGIN DESCRIPTION:
UNT 1028 IN HEWA 16.0
END DESCRIPTION:
XS GIS Cut Line= 3
      2703014.29     10026636.36      2702576.77     10025907.17
      2702072.54     10025652.45
#Sta/Elev= 30
  4220.8 1918.53  4257.1 1915.43  4342.7 1903.73  4410.5  1898.5  4533.1  1886.5
  4548.7 1886.23  4665.3 1877.87  4787.8 1873.95  4803.3  1871.4  4824.7 1869.84
  4970.2 1865.62  4996.6 1862.06  4999.4 1861.56  5002.6 1862.06  5028.5  1865.4
  5042.4 1866.09  5093.6 1864.77  5177.2 1865.02  5205.1 1867.28  5304.6  1870.9
    5327 1874.26  5338.8 1877.68  5371.8  1884.5  5383.4 1888.22  5405.7 1892.79
    5439 1898.31  5517.4 1913.88  5539.8 1916.34  5600.7 1919.08  5636.1  1922.3
#Mann= 3 ,-1 , 0
  4220.8      .1       0  4996.6     .07       0  5002.6      .1       0
Bank Sta=4996.6,5002.6
XS Rating Curve= 0 ,0
Exp/Cntr=0.3,0.1

Type RM Length L Ch R = 1 ,7992    ,448,448,448
BEGIN DESCRIPTION:
UNT 1028 IN HEWA 15.0
END DESCRIPTION:
XS GIS Cut Line= 2
      2703430.94      10026365.5      2702509.06     10025063.41
#Sta/Elev= 30
  4243.4 1918.94  4346.3 1916.09  4361.1  1913.9  4375.8 1909.36  4426.3 1901.26
  4482.9 1895.23  4518.6 1888.67    4569 1882.35  4791.8 1865.01  4848.4    1863
  4970.2 1863.77  4996.8 1857.66  4999.5 1857.16  5002.8 1857.66  5078.7 1863.31
  5229.7 1865.58  5326.3 1866.43  5415.8 1867.88  5466.2 1872.48    5481 1875.08
  5487.1 1877.46  5501.9 1879.04  5531.5 1886.66  5537.6 1889.49  5558.5  1893.6
  5617.6  1899.6  5653.3 1905.86  5680.3 1912.51  5760.4 1919.94  5838.8 1929.52
#Mann= 5 ,-1 , 0
  4243.4      .1       0  4996.8     .07       0  5002.8      .1       0
  5229.7     .05       0  5326.3      .1       0
Bank Sta=4996.8,5002.8
XS Rating Curve= 0 ,0
Exp/Cntr=0.3,0.1

Type RM Length L Ch R = 1 ,7544    ,548,548,548
BEGIN DESCRIPTION:
UNT 1028 IN HEWA 14.0
END DESCRIPTION:
XS GIS Cut Line= 4
      2703946.54     10026094.64      2703519.48     10025563.42
      2702925.73     10025271.75      2702499.38     10024918.19
#Sta/Elev= 30
  4110.2 1933.03  4252.4 1927.01  4401.2 1916.63    4422 1914.28  4479.6  1902.6
    4550 1895.58  4593.2 1893.86  4680.8 1881.31  4706.8 1877.86  4737.4 1876.99
  4788.6 1872.39  4926.6 1865.03  4991.7 1855.31  4999.8 1854.64  5002.5 1854.14
  5005.8 1854.64  5030.8 1858.46  5057.6 1858.17  5127.2 1859.59  5283.7 1857.38
  5323.1 1859.48  5422.2 1860.56    5521 1862.57  5583.4 1869.68  5670.6 1893.72
    5741 1903.36    5784 1913.79  5904.5 1928.93  5975.5  1932.3  6007.2 1936.04
#Mann= 9 ,-1 , 0
  4110.2      .1       0  4680.8     .05       0  4737.4      .1       0
  4991.7     .05       0  4999.8    .035       0  5005.8     .05       0
  5057.6      .1       0  5422.2     .05       0  5583.4      .1       0
Bank Sta=4999.8,5005.8
XS Rating Curve= 0 ,0
Exp/Cntr=0.3,0.1

Type RM Length L Ch R = 1 ,6996    ,421,421,421
BEGIN DESCRIPTION:
UNT 1028 IN HEWA 13.0
END DESCRIPTION:
XS GIS Cut Line= 3
       2704040.3     10025464.44      2703634.06     10025011.33
      2702597.58     10024662.37
#Sta/Elev= 30
  4168.6 1914.68  4198.5 1912.45  4283.7 1897.73  4340.5 1890.99  4379.2 1882.63
  4425.9 1874.35  4453.4 1870.17  4516.7 1865.45  4559.5 1862.71  4687.4 1859.62
  4880.3  1857.2  4962.4 1857.54  4975.8 1856.63  4994.1 1849.74  5004.3 1848.92
    5007 1848.42  5010.3 1848.92  5015.2 1852.53  5025.7 1854.89  5103.6 1854.82
  5229.6 1852.95  5373.9 1858.58  5405.6 1863.46  5474.5 1880.72  5553.3 1896.71
    5632 1905.27  5679.9 1913.85    5758 1920.47  5815.7 1928.87  5870.8 1931.87
#Mann= 9 ,-1 , 0
  4168.6      .1       0  4379.2     .05       0  4425.9      .1       0
  4516.7     .05       0  4880.3      .1       0  5004.3     .07       0
  5010.3      .1       0  5103.6     .05       0  5229.6      .1       0
Bank Sta=5004.3,5010.3
XS Rating Curve= 0 ,0
Exp/Cntr=0.3,0.1

Type RM Length L Ch R = 1 ,6575    ,549,549,549
BEGIN DESCRIPTION:
UNT 1028 IN HEWA 12.0
END DESCRIPTION:
XS GIS Cut Line= 2
      2704102.85      10025219.7      2703123.64     10024094.66
#Sta/Elev= 30
  4153.7 1894.71    4204 1889.44  4274.5 1872.77  4291.4  1871.6  4338.1 1866.77
  4431.4 1862.84  4479.8 1860.02  4599.8 1857.84  4912.5 1851.99  4976.1 1852.06
  4983.6 1850.61    4994 1843.24  4996.7 1842.74    5000 1843.24  5004.6 1843.63
  5018.8  1851.8  5188.8 1850.58  5238.1 1846.02  5295.1 1849.86  5309.4 1851.52
  5323.6 1855.48  5401.5 1866.53  5450.8 1881.16  5458.4 1882.07  5479.3 1891.56
  5493.6 1894.57  5585.7  1904.8  5593.3 1908.13  5606.7 1910.13  5645.2 1913.27
#Mann= 7 ,-1 , 0
  4153.7      .1       0    4204     .05       0  4291.4      .1       0
  4431.4     .05       0  4599.8      .1       0    4994     .07       0
    5000      .1       0
Bank Sta=4994,5000
XS Rating Curve= 0 ,0
Exp/Cntr=0.3,0.1

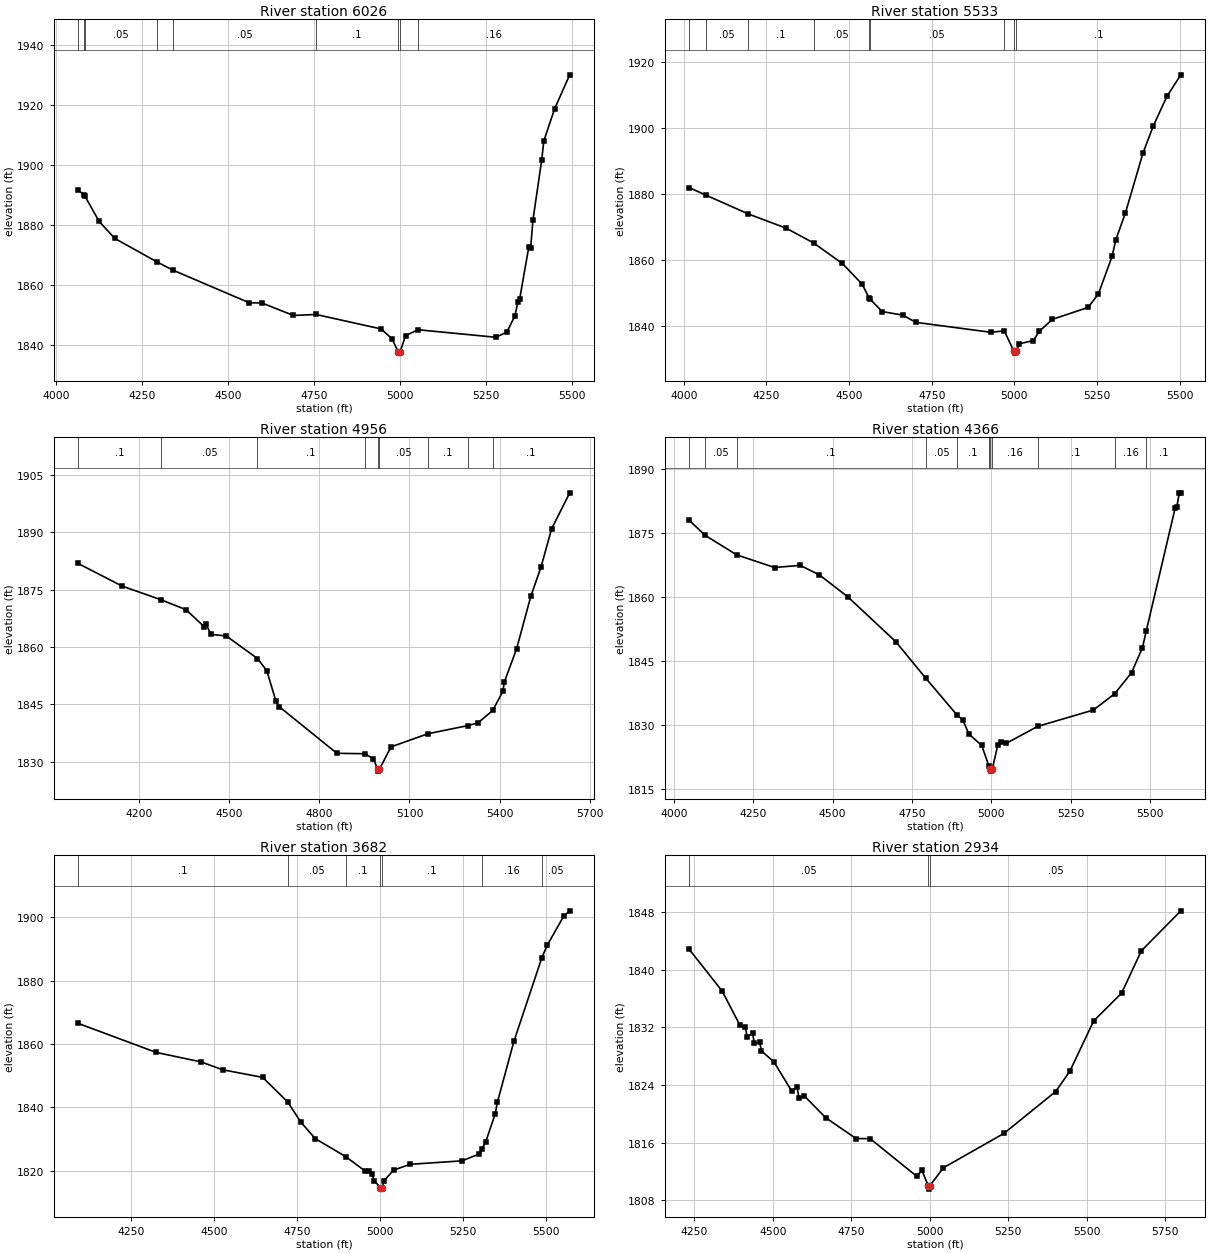
Type RM Length L Ch R = 1 ,6026    ,493,493,493
BEGIN DESCRIPTION:
UNT 1028 IN HEWA 11.0
END DESCRIPTION:
XS GIS Cut Line= 2
      2704175.74     10025141.57      2703738.22     10023782.14
#Sta/Elev= 30
  4064.7 1891.75  4080.5 1890.12  4084.6 1889.63  4125.5 1881.26  4171.4 1875.53
  4294.2  1867.7  4339.4 1865.01  4561.6 1854.12  4598.9 1854.02  4689.9 1849.88
    4756  1850.2  4944.9 1845.38  4976.4 1842.11  4994.4 1837.82  4997.1 1837.32
  5000.4 1837.82  5015.9 1843.16  5052.2 1845.11  5277.8 1842.61  5309.9 1844.28
  5333.5  1849.7    5342 1854.25  5347.2 1855.21    5374 1872.74  5379.3 1872.32
  5386.1 1881.77  5411.4 1901.66  5417.6 1908.08  5449.1 1918.79  5492.8 1930.08
#Mann= 9 ,-1 , 0
  4064.7     .16       0  4080.5      .1       0  4084.6     .05       0
  4294.2      .1       0  4339.4     .05       0    4756      .1       0
  4994.4     .07       0  5000.4      .1       0  5052.2     .16       0
Bank Sta=4994.4,5000.4
XS Rating Curve= 0 ,0
Exp/Cntr=0.3,0.1

Type RM Length L Ch R = 1 ,5533    ,577,577,577
BEGIN DESCRIPTION:
UNT 1028 IN HEWA 10.0
END DESCRIPTION:
XS GIS Cut Line= 3
      2704420.52      10025016.5      2704394.48     10024443.63
      2704149.68      10023563.4
#Sta/Elev= 30
  4016.4 1881.97  4068.1 1879.64    4195 1874.01  4309.5 1869.71  4392.3 1865.25
  4479.6 1859.03  4539.7 1852.74  4559.8 1848.72    4562 1848.41  4600.1 1844.49
  4662.4 1843.42  4702.2 1841.23  4928.3 1838.24  4969.3 1838.65    4999 1832.43
  5001.7 1831.93    5005 1832.43  5015.3 1834.77  5056.8 1835.71  5075.6 1838.54
    5115 1842.15  5222.9 1845.74    5254 1849.82  5295.6 1861.19  5306.9 1866.22
    5336 1874.36    5389 1892.43  5420.1 1900.59  5461.6 1909.59  5503.5 1916.07
#Mann= 9 ,-1 , 0
  4016.4      .1       0  4068.1     .05       0    4195      .1       0
  4392.3     .05       0  4559.8      .1       0    4562     .05       0
  4969.3      .1       0    4999     .07       0    5005      .1       0
Bank Sta=4999,5005
XS Rating Curve= 0 ,0
Exp/Cntr=0.3,0.1

Type RM Length L Ch R = 1 ,4956    ,590,590,590
BEGIN DESCRIPTION:
UNT 1028 IN HEWA 9.0
END DESCRIPTION:
XS GIS Cut Line= 2
      2704576.78     10025131.09      2704988.11     10023548.26
#Sta/Elev= 30
  3997.6 1881.88  4144.1 1875.95  4274.7 1872.34  4356.5 1869.77  4417.5 1865.28
  4422.7 1866.09  4439.2 1863.32  4490.8 1862.88  4594.3 1856.97  4625.4 1853.78
  4655.6 1845.82  4666.5 1844.37  4858.4 1832.15  4951.2 1832.04    4980 1830.71
  4994.1 1827.98  4996.8 1827.48  5000.1 1827.98  5038.4 1833.83    5162 1837.29
  5294.7 1839.42  5327.7 1840.11  5376.8 1843.37  5410.4 1848.35  5415.6 1850.84
  5456.2  1859.5  5503.4 1873.23  5537.3 1880.88  5572.7 1890.95    5633 1900.39
#Mann= 9 ,-1 , 0
  3997.6      .1       0  4274.7     .05       0  4594.3      .1       0
  4951.2     .05       0  4994.1    .035       0  5000.1     .05       0
    5162      .1       0  5294.7     .05       0  5376.8      .1       0
Bank Sta=4994.1,5000.1
XS Rating Curve= 0 ,0
Exp/Cntr=0.3,0.1

Type RM Length L Ch R = 1 ,4366    ,684,684,684
BEGIN DESCRIPTION:
UNT 1028 IN HEWA 8.0
END DESCRIPTION:
XS GIS Cut Line= 2
      2705477.82     10025131.14      2705331.98     10023589.43
#Sta/Elev= 30
  4048.3 1877.98  4098.6 1874.48  4197.8 1869.92  4316.9 1866.96  4397.3 1867.46
  4457.5 1865.28  4547.9 1860.09  4698.6 1849.62  4793.2 1841.07  4892.4 1832.38
  4909.5 1831.33  4929.6 1827.95  4969.8 1825.31  4991.7 1820.59  4996.9  1819.8
  4999.7  1819.3  5002.9  1819.8    5020  1825.3  5030.1 1826.16  5047.7 1825.83
  5145.8 1829.77  5321.4  1833.6  5388.6 1837.42  5441.9 1842.38    5476  1848.2
  5487.8 1852.07  5579.3 1880.97  5584.3 1881.21  5592.2 1884.44  5596.9 1884.44
#Mann= 11 ,-1 , 0
  4048.3      .1       0  4098.6     .05       0  4197.8      .1       0
  4793.2     .05       0  4892.4      .1       0  4991.7     .16       0
  4996.9     .07       0  5002.9     .16       0  5145.8      .1       0
  5388.6     .16       0  5487.8      .1       0
Bank Sta=4996.9,5002.9
XS Rating Curve= 0 ,0
Exp/Cntr=0.3,0.1

Type RM Length L Ch R = 1 ,3682    ,748,748,748
BEGIN DESCRIPTION:
UNT 1028 IN HEWA 7.0
END DESCRIPTION:
XS GIS Cut Line= 2
      2706524.71     10024636.36      2705639.27     10023448.83
#Sta/Elev= 30
  4090.9 1866.51  4326.1 1857.35  4461.6 1854.35  4526.2 1851.88  4647.2 1849.48
  4722.9 1841.66  4761.8  1835.4  4805.2 1830.19  4896.9 1824.52  4954.9 1820.02
  4968.2 1819.83  4976.6 1818.93  4982.8 1816.93  5001.8 1814.75  5004.5 1814.25
  5007.8 1814.75  5012.1  1816.8  5041.3 1820.24  5091.3 1822.07  5247.7 1823.17
  5297.7 1825.24  5307.8 1827.02  5318.5 1828.96  5347.7 1837.96    5354 1841.57
    5404 1860.82  5487.9  1887.1  5504.1 1891.08  5554.1 1900.31  5572.2 1901.99
#Mann= 7 ,-1 , 0
  4090.9      .1       0  4722.9     .05       0  4896.9      .1       0
  5001.8     .07       0  5007.8      .1       0  5307.8     .16       0
  5487.9     .05       0
Bank Sta=5001.8,5007.8
XS Rating Curve= 0 ,0
Exp/Cntr=0.3,0.1

Type RM Length L Ch R = 1 ,2934    ,50,50,50
BEGIN DESCRIPTION:
UNT 1028 IN HEWA 6.0
END DESCRIPTION:
XS GIS Cut Line= 2
      2707253.83     10023796.05      2705837.23     10023125.94
#Sta/Elev= 30
  4233.4 1842.85  4338.7 1837.03  4395.3 1832.29  4412.5 1832.02    4418 1830.67
  4435.3 1831.23  4440.8 1829.81    4458 1829.93  4463.5 1828.75  4503.5 1827.21
  4560.1 1823.16  4577.3 1823.69  4582.9 1822.26  4600.1  1822.5  4668.3 1819.47
  4764.9 1816.58  4810.4 1816.55  4958.4 1811.34  4975.2 1812.14    4995 1810.05
  4997.7 1809.55    5001 1810.05  5043.5 1812.51  5236.6 1817.29  5401.4  1823.1
  5446.9 1825.94  5522.6 1832.91  5611.7 1836.77  5674.5 1842.64  5800.5  1848.2
#Mann= 3 ,-1 , 0
  4233.4     .05       0    4995     .04       0    5001     .05       0
Bank Sta=4995,5001
XS Rating Curve= 0 ,0
Exp/Cntr=0.3,0.1

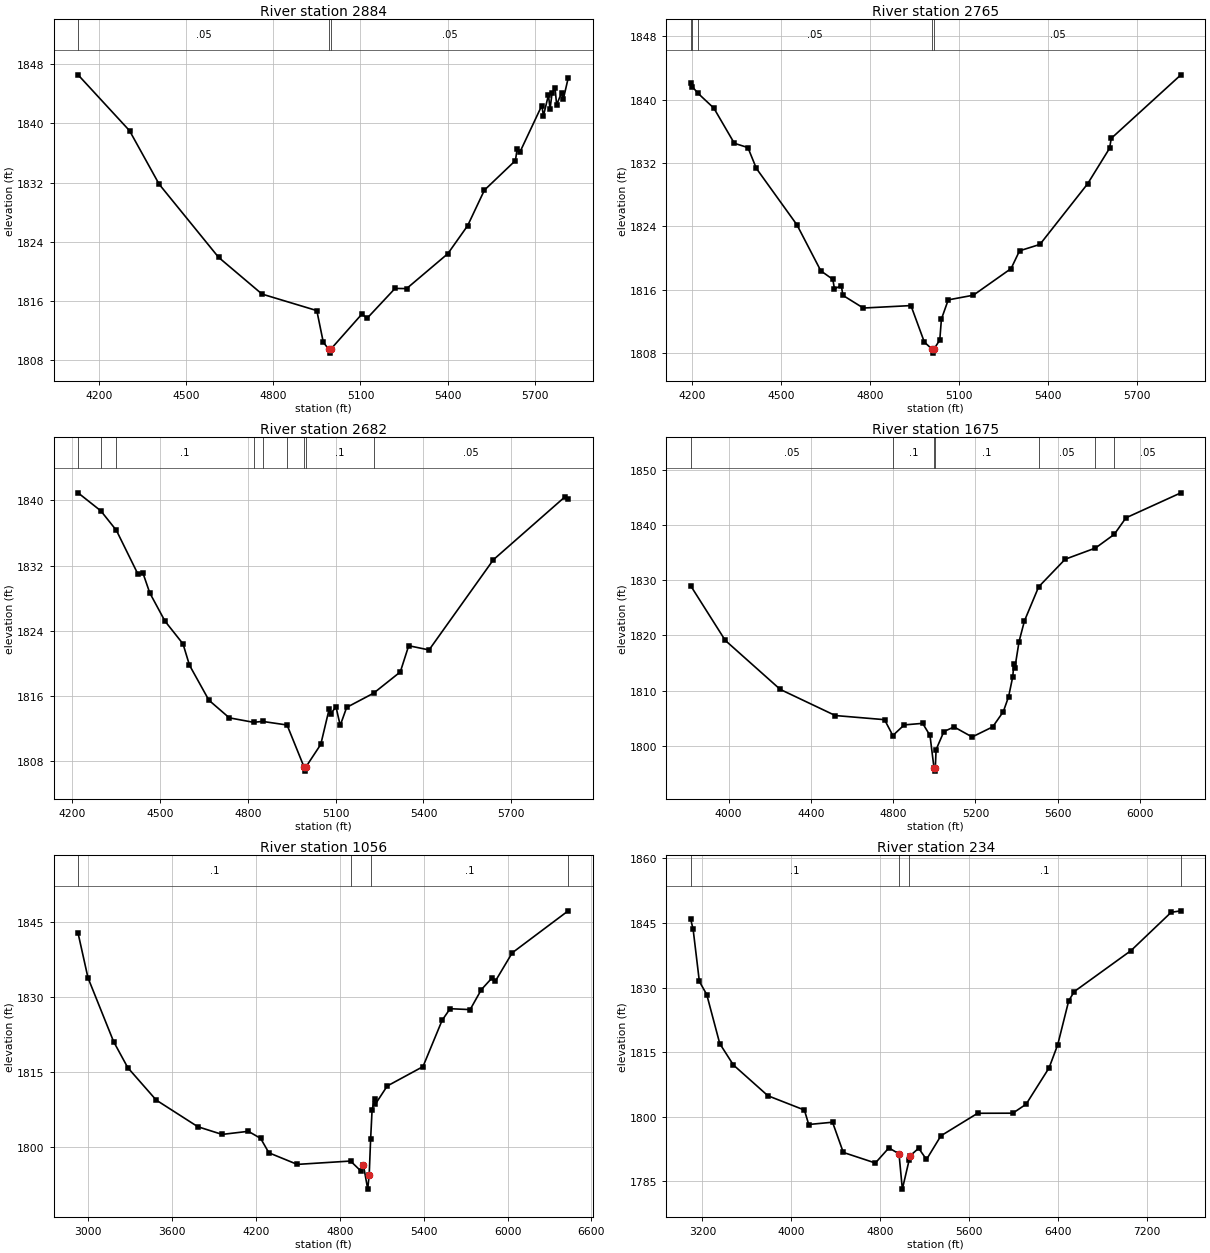
Type RM Length L Ch R = 1 ,2884    ,119,119,119
BEGIN DESCRIPTION:
UNT 1028 IN HEWA 5.0
END DESCRIPTION:
XS GIS Cut Line= 2
      2707389.26     10023816.88      2705868.43     10023091.19
#Sta/Elev= 30
  4129.2 1846.55  4306.2 1839.01  4408.1 1831.78  4612.3 1821.92  4761.6 1816.96
    4950 1814.73  4972.2 1810.47  4991.3 1809.49  4994.1 1808.99  4997.3 1809.49
  5105.4 1814.28  5122.6 1813.68  5218.9 1817.72  5258.7  1817.7  5400.4 1822.41
  5468.5 1826.19  5526.2 1830.99  5632.8 1834.98  5638.4 1836.49  5648.1 1836.11
  5723.6 1842.41  5729.1 1841.01  5746.3 1843.83  5751.8 1841.94  5758.9 1844.12
    5769 1844.73  5774.5 1842.51  5791.7 1844.16  5797.2 1843.23  5814.3 1846.13
#Mann= 3 ,-1 , 0
  4129.2     .05       0  4991.3     .04       0  4997.3     .05       0
Bank Sta=4991.3,4997.3
XS Rating Curve= 0 ,0
Exp/Cntr=0.3,0.1

Type RM Length L Ch R = 1 ,2765    ,83,83,83
BEGIN DESCRIPTION:
UNT 1028 IN HEWA 4.0
END DESCRIPTION:
XS GIS Cut Line= 2
      2707413.56     10023691.88      2705913.18     10022998.87
#Sta/Elev= 30
  4194.4 1842.05  4199.7 1841.62  4219.2 1840.78  4272.5 1838.91  4341.4 1834.48
  4387.2 1833.94  4415.7 1831.31  4552.5 1824.19  4633.1 1818.38  4673.5 1817.31
    4679  1816.1    4702 1816.53  4707.5 1815.29  4776.3 1813.69  4936.9    1814
  4982.1 1809.39  5008.2  1808.5  5010.9    1808  5014.2  1808.5  5034.1 1809.65
  5039.6 1812.29  5062.6 1814.72  5147.3 1815.31  5274.5 1818.67    5303 1820.91
  5371.8 1821.72  5532.4 1829.36  5606.7 1833.86  5612.2  1835.1  5847.1 1843.12
#Mann= 5 ,-1 , 0
  4194.4     .05       0  4199.7      .1       0  4219.2     .05       0
  5008.2     .04       0  5014.2     .05       0
Bank Sta=5008.2,5014.2
XS Rating Curve= 0 ,0
Exp/Cntr=0.3,0.1

Type RM Length L Ch R = 1 ,2682    ,1007,1007,1007
BEGIN DESCRIPTION:
UNT 1028 IN HEWA 3.0
END DESCRIPTION:
XS GIS Cut Line= 2
       2707465.7     10023629.41      2705937.85     10022945.35
#Sta/Elev= 30
  4220.4 1840.93  4298.1 1838.72  4351.4 1836.32  4425.5 1830.91  4442.1 1831.08
  4465.3 1828.65  4517.2 1825.19  4578.9 1822.39  4600.9 1819.78  4667.3 1815.48
  4736.9 1813.32  4819.8 1812.77  4850.4 1812.88  4934.2 1812.44  4992.3 1807.28
    4995 1806.78  4998.3 1807.28  5049.3 1810.06    5078  1814.4  5083.5 1813.84
  5101.2 1814.66  5115.8 1812.39  5137.7  1814.6  5229.5 1816.34  5320.9 1818.95
  5349.6 1822.17  5419.1 1821.65  5638.8 1832.72  5881.7 1840.39  5894.4 1840.16
#Mann= 9 ,-1 , 0
  4220.4      .1       0  4298.1     .05       0  4351.4      .1       0
  4819.8     .05       0  4850.4     .16       0  4934.2      .1       0
  4992.3     .07       0  4998.3      .1       0  5229.5     .05       0
Bank Sta=4992.3,4998.3
XS Rating Curve= 0 ,0
Exp/Cntr=0.3,0.1

Type RM Length L Ch R = 1 ,1675    ,721,721,721
BEGIN DESCRIPTION:
UNT 1028 IN HEWA 2.0
END DESCRIPTION:
XS GIS Cut Line= 4
      2707771.21     10023511.31      2707576.77     10022664.11
      2707104.55     10022407.17      2706146.24     10022594.66
#Sta/Elev= 30
  3815.7 1829.01  3983.5 1819.11    4251 1810.21  4518.5 1805.47    4758 1804.72
  4798.3 1801.84  4853.8 1803.77  4943.2 1804.05    4979 1801.86  4998.8 1795.88
  5001.5 1795.38  5004.8 1795.88  5008.7 1799.29  5046.7 1802.57  5096.1  1803.4
  5183.9 1801.58  5283.8 1803.41  5335.3 1806.16  5361.2 1808.89  5381.6 1812.55
  5386.8 1814.89  5391.9 1814.16  5412.1  1818.9  5438.3 1822.65  5507.4 1828.83
  5636.3 1833.84  5783.5 1835.87  5874.9 1838.35  5931.8 1841.35    6199 1845.89
#Mann= 7 ,-1 , 0
  3815.7     .05       0  4798.3      .1       0  4998.8     .07       0
  5004.8      .1       0  5507.4     .05       0  5783.5      .1       0
  5874.9     .05       0
Bank Sta=4998.8,5004.8
XS Rating Curve= 0 ,0
Exp/Cntr=0.3,0.1

Type RM Length L Ch R = 1 ,1056    ,822,822,822
BEGIN DESCRIPTION:
Mapping XS 631f0d80
END DESCRIPTION:
XS GIS Cut Line= 4
      2707995.02     10023663.21      2707666.89     10022043.41
      2707052.31     10021902.79       2706048.5     10022599.74
#Sta/Elev= 30
    2929 1842.75  2999.9 1833.81  3183.5 1821.01  3284.9  1815.8  3487.7 1809.33
  3785.5 1803.99    3959 1802.45  4146.7 1803.07  4234.5 1801.66  4293.7 1798.77
  4496.4 1796.45  4877.6 1797.12  4949.4 1795.18  4969.9 1796.27  5000.4  1791.5
  5011.1 1794.41  5021.2 1801.52  5031.5 1807.31  5048.9 1809.46  5054.1 1808.47
  5139.9 1812.14  5395.6 1816.02  5532.7 1825.31  5589.5 1827.61  5732.7 1827.43
    5813 1831.43  5890.7 1833.82  5911.6 1833.06  6033.9  1838.8  6434.2  1847.2
#Mann= 4 ,-1 , 0
    2929      .1       0  4877.6     .07       0  5021.2      .1       0
  6434.2     .05       0
Bank Sta=4969.9,5011.1
XS Rating Curve= 0 ,0
Exp/Cntr=0.3,0.1

Type RM Length L Ch R = 1 ,234     ,0,0,0
BEGIN DESCRIPTION:
UNT 1028 IN HEWA 1.0
END DESCRIPTION:
XS GIS Cut Line= 4
      2708156.48     10023652.83      2707812.73     10021564.25
      2707140.85       10021533.       2705911.7     10022590.28
#Sta/Elev= 30
  3095.3 1845.83  3116.8 1843.55  3172.9 1831.42  3239.2 1828.38  3356.5 1816.97
  3478.9 1812.01  3789.9 1804.85    4118 1801.53    4157 1798.17  4371.3  1798.7
  4468.1 1791.68  4756.5 1789.22  4878.1 1792.73  4969.3 1791.36  4999.4 1783.15
  5060.5  1789.9  5070.6 1790.93  5146.2 1792.65  5216.6 1790.04  5346.4 1795.54
  5676.7 1800.78  5993.3  1800.8  6113.3 1802.89  6319.6 1811.33  6397.5 1816.71
  6496.3 1826.92  6546.7 1829.07    7057 1838.59    7418 1847.48  7505.9 1847.83
#Mann= 4 ,-1 , 0
  3095.3      .1       0  4969.3     .07       0  5060.5      .1       0
  7505.9     .05       0
Bank Sta=4969.3,5070.6
XS Rating Curve= 0 ,0
Exp/Cntr=0.3,0.1

Chan Stop Cuts=-1
Use User Specified Reach Order=0
Composite Channel Slope=5