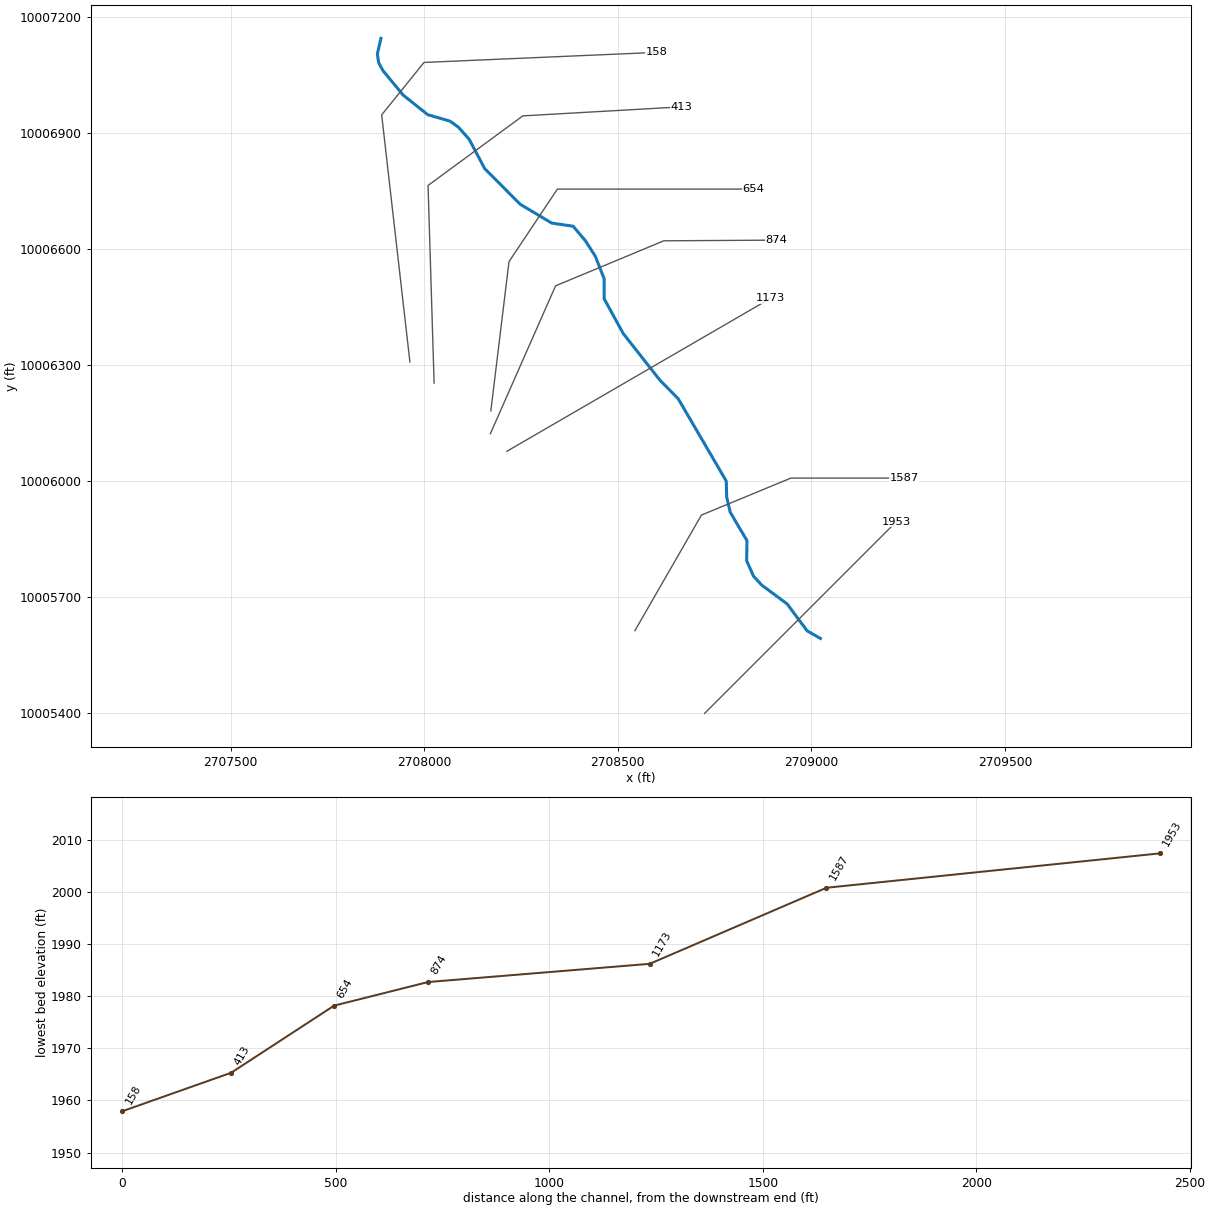
--- UNT 1030 IN HEWA.prj (project) ---

Proj Title=UNT 1030 IN HEWA Base Level Engineering
Current Plan=p01
Default Exp/Contr=0.3,0.1
English Units
Geom File=g01
Flow File=f01
Plan File=p01
Y Axis Title=Elevation
X Axis Title(PF)=Main Channel Distance
X Axis Title(XS)=Station
BEGIN DESCRIPTION:
UNT 1030 IN HEWA
END DESCRIPTION:
DSS File=dss
DSS Export Rating Curves= 0
DSS Export Rating Curve Sorted= 0
DSS Export Volume Flow Curves= 0
DXF OffsetX= 0
DXF OffsetY= 0
DXF ScaleX= 1
DXF ScaleY= 10

--- UNT 1030 IN HEWA.p01 (plan) ---

Plan Title=Multiple Run
Program Version=4.10
Short Identifier=Multiple Run
Geom File=g01
Flow File=f01
Subcritical Flow
K Sum by GR= 0
Std Step Tol= 0.01
Critical Tol= 0.01
Num of Std Step Trials= 20
Max Error Tol= 0.3
Flow Tol Ratio= 0.001
Split Flow NTrial= 30
Split Flow Tol= 0.02
Split Flow Ratio= 0.02
Log Output Level= 0
Friction Slope Method= 1
Unsteady Friction Slope Method= 2
Unsteady Bridges Friction Slope Method= 1
Parabolic Critical Depth
Global Vel Dist= 1 , 1 , 1
Global Log Level= 0
CheckData=True
Encroach Param=-1 ,0,0, 0
BEGIN DESCRIPTION:
Multiple Run
END DESCRIPTION:
Computation Interval=1HOUR
Output Interval=1HOUR
Run HTab= 0
Run UNet= 0
Run PostProcess= 0
Run WQNet= 0
UNET Theta= 1
UNET Theta Warmup= 1
UNET ZTol= 0.02
UNET ZSATol= 0.05
UNET MxIter= 20
UNET MaxInSteps= 0
UNET DtIC= 0
UNET DtMin= 0
UNET MaxCRTS= 20
UNET WFStab= 2
UNET SFStab= 1
UNET WFX= 1
UNET SFX= 1
UNET DSS MLevel= 4
UNET DZMax Abort= 100
UNET Convert EG Bridges= 0
UNET Use Existing IB Tables=-1
UNET Froude Reduction=False
UNET Froude Limit= 1
UNET Froude Power= 10
UNET Time Slicing=0,0, 5
UNET Junction Losses=0
Instantaneous Interval=1HOUR
DSS File=dss
Write IC File= 0
Write IC File at Sim End=0
Echo Input=False
Echo Parameters=False
Echo Output=False
Write Detailed= 0
WQ AD Non Conservative
WQ ULTIMATE=-1
WQ Max Comp Step=1HOUR
WQ Output Interval=15MIN
WQ Output Selected Increments= 0
WQ Output face flow=0
WQ Output face velocity=0
WQ Output face area=0
WQ Output face dispersion=0
WQ Output cell volume=0
WQ Output cell surface area=0
WQ Output cell continuity=0
WQ Output cumulative cell continuity=0
WQ Output face conc=0
WQ Output face dconc_dx=0
WQ Output face courant=0
WQ Output face peclet=0
WQ Output face adv mass=0
WQ Output face disp mass=0
WQ Output cell mass=0
WQ Output cell source sink temp=0
WQ Output cell source sink nsm=0
WQ Output MaxMinRange=-1
WQ Daily Max Min Mean=-1
WQ Daily Range=0
WQ Daily Time=0
WQ Create Restart=0
WQ Fixed Restart=0
WQ System Summary=0
WQ Use Fixed Temperature=0
Sorting and Armoring Iterations= 10
XS Update Threshold= 0.02
Hydraulics Update Threshold= 0.02
Energy Slope Method= 1
Volume Change Method= 0
XS Weighting Method= 0
Number of US Weighted Cross Sections= 1
Number of DS Weighted Cross Sections= 1
Upstream XS Weight=0.25
Main XS Weight=0.5
Downstream XS Weight=0.25
Number of DS XS's Weighted with US Boundary= 1
Upstream Boundary Weight= 1
Weight of XSs Associated with US Boundary= 0
Number of US XS's Weighted with DS Boundary= 1
Downstream Boundary Weight= 0.5
Weight of XSs Associated with DS Boundary= 0.5
Sediment Output Level= 4
Mass or Volume Output= 0
Output Increment Type= 1
Profile and TS Output Increment= 10
XS Output Flag= 0
XS Output Increment= 10
Disregard all LS=0
Disregard all Conn=0
Disregard all Breaches=0
Disregard all Pumps=0

--- UNT 1030 IN HEWA.f01 (steady flow) ---

Flow Title=Multiple
Program Version=4.10
Number of Profiles= 7
Profile Names=10-year,25-year,50-year,1pct_min,100-year,1pct_plu,500-year
River Rch & RM=UNT 1030 IN HEWA,Reach-1         ,1953
     422     576     702     627     848    1147    1232
Boundary for River Rch & Prof#=UNT 1030 IN HEWA,Reach-1         , 1
Up Type= 0
Dn Type= 3
Dn Slope=0.01
Boundary for River Rch & Prof#=UNT 1030 IN HEWA,Reach-1         , 2
Up Type= 0
Dn Type= 3
Dn Slope=0.01
Boundary for River Rch & Prof#=UNT 1030 IN HEWA,Reach-1         , 3
Up Type= 0
Dn Type= 3
Dn Slope=0.01
Boundary for River Rch & Prof#=UNT 1030 IN HEWA,Reach-1         , 4
Up Type= 0
Dn Type= 3
Dn Slope=0.01
Boundary for River Rch & Prof#=UNT 1030 IN HEWA,Reach-1         , 5
Up Type= 0
Dn Type= 3
Dn Slope=0.01
Boundary for River Rch & Prof#=UNT 1030 IN HEWA,Reach-1         , 6
Up Type= 0
Dn Type= 3
Dn Slope=0.01
Boundary for River Rch & Prof#=UNT 1030 IN HEWA,Reach-1         , 7
Up Type= 0
Dn Type= 3
Dn Slope=0.01
DSS Import GetInterval= 0
DSS Import GetPeak= 0
DSS Import FillOption= 0

--- UNT 1030 IN HEWA.g01 (geometry) ---

Geom Title=Existing Conditions
Program Version=4.10

River Reach=UNT 1030 IN HEWA,Reach-1
Reach XY= 30
      2709023.47     10005593.73      2708989.03     10005613.41
      2708937.57     10005682.83      2708871.98     10005731.39
      2708850.61     10005754.64       2708832.9     10005794.45
      2708833.72     10005846.45      2708790.48     10005919.66
      2708781.32     10005959.25      2708780.26     10006000.16
      2708656.11     10006212.84      2708609.24     10006260.44
      2708514.11     10006381.37       2708464.9       10006471.
      2708465.06     10006522.38      2708442.18     10006580.65
       2708416.3     10006621.11      2708384.76     10006658.48
      2708329.73      10006666.5      2708248.48     10006714.83
      2708156.33     10006807.26      2708116.28     10006882.99
      2708088.73     10006913.99      2708066.95     10006929.85
      2708009.54     10006946.35      2707945.44     10006997.49
       2707893.1       10007061.      2707882.59     10007080.79
      2707879.17     10007103.72      2707888.47     10007143.73

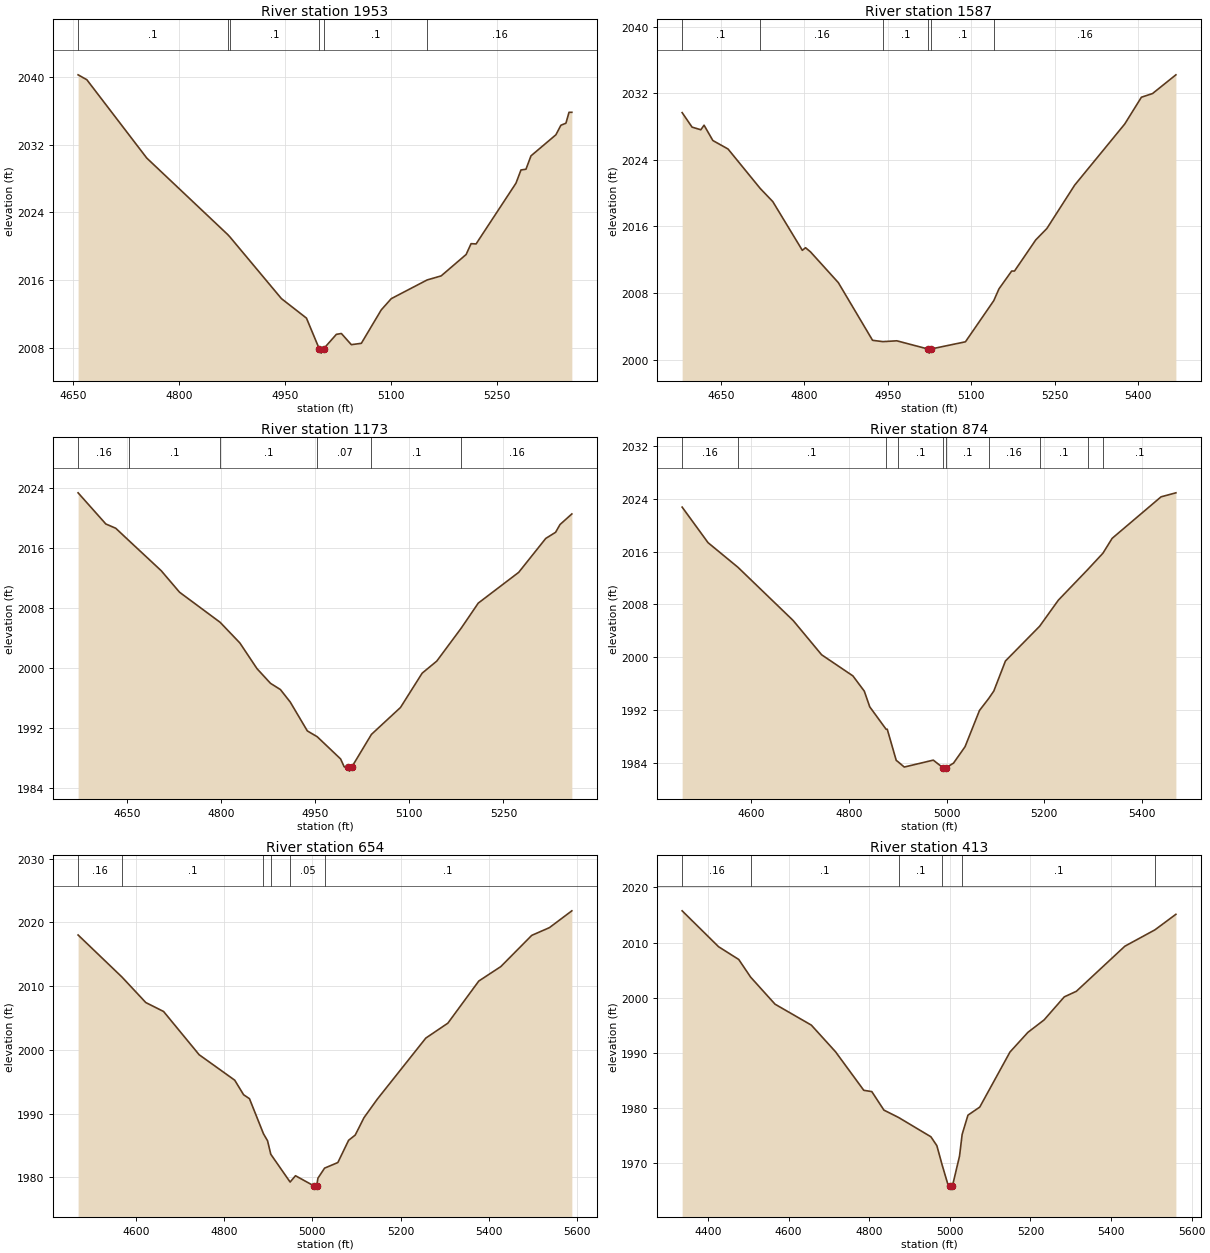
Type RM Length L Ch R = 1 ,1953    ,780,780,780
BEGIN DESCRIPTION:
UNT 1030 IN HEWA 4.0
END DESCRIPTION:
XS GIS Cut Line= 2
      2708724.36     10005400.24      2709219.12       10005895.
#Sta/Elev= 30
  4656.7 2040.27  4669.1 2039.69    4754 2030.43  4868.7 2021.39  4871.8 2021.11
  4944.9 2013.81  4980.3 2011.51  4998.5 2007.87  5001.2 2007.37  5004.5 2007.87
  5022.7 2009.59  5029.8 2009.69  5043.9 2008.37  5058.1 2008.53  5086.3 2012.48
  5100.5 2013.81  5151.3 2016.02  5171.2  2016.5  5206.6 2019.03  5213.6 2020.31
  5220.7 2020.28  5277.3 2027.47  5284.3 2029.02  5291.4 2029.11  5298.5 2030.69
  5333.8 2033.18  5340.9 2034.31    5348 2034.55  5352.4 2035.84  5356.4 2035.84
#Mann= 6 ,-1 , 0
  4656.7      .1       0  4868.7     .16       0  4871.8      .1       0
  4998.5     .07       0  5004.5      .1       0  5151.3     .16       0
Bank Sta=4998.5,5004.5
XS Rating Curve= 0 ,0
Exp/Cntr=0.3,0.1

Type RM Length L Ch R = 1 ,1587    ,414,414,414
BEGIN DESCRIPTION:
Mapping XS e9e5528a
END DESCRIPTION:
XS GIS Cut Line= 4
      2708544.28     10005613.82      2708716.16     10005912.45
      2708947.07     10006007.93      2709240.45     10006007.93
#Sta/Elev= 30
  4580.4 2029.67  4598.2 2027.93    4614 2027.61  4619.8 2028.16  4635.6 2026.32
  4662.9  2025.3  4720.8 2020.56  4743.4 2018.98  4796.5 2013.13  4802.3 2013.44
  4811.1 2012.95  4861.2 2009.25  4922.8 2002.32  4941.4 2002.16  4966.4 2002.26
  5022.1 2001.28  5024.8 2000.78  5028.1 2001.28  5089.8 2002.14  5140.8 2007.09
    5150 2008.49  5172.9 2010.64    5178 2010.64  5216.2 2014.38  5236.2 2015.75
  5286.2 2020.96  5376.2  2028.3  5406.2 2031.52  5426.2 2031.96  5468.2 2034.21
#Mann= 6 ,-1 , 0
  4580.4      .1       0  4720.8     .16       0  4941.4      .1       0
  5022.1     .07       0  5028.1      .1       0  5140.8     .16       0
Bank Sta=5022.1,5028.1
XS Rating Curve= 0 ,0
Exp/Cntr=0.3,0.1

Type RM Length L Ch R = 1 ,1173    ,519,519,519
BEGIN DESCRIPTION:
UNT 1030 IN HEWA 3.0
END DESCRIPTION:
XS GIS Cut Line= 2
       2708213.9     10006077.29      2708894.81     10006472.32
#Sta/Elev= 30
  4571.8 2023.36    4616  2019.2  4631.8 2018.63  4653.3 2016.94  4704.3 2012.96
  4733.6 2010.08  4798.2 2006.07  4829.7 2003.31    4857 1999.88  4878.5 1997.92
  4894.3 1997.09    4910 1995.42  4937.3 1991.56  4953.1 1990.78  4990.3 1987.82
  4996.1 1986.76  5001.8 1986.69  5004.6 1986.19  5007.8 1986.69  5039.5  1991.1
  5085.8 1994.69  5120.4 1999.28  5143.6 2000.88  5182.4 2005.26  5209.8 2008.63
  5274.3 2012.74  5317.4 2017.27  5333.1 2018.09  5340.1 2019.12    5359 2020.54
#Mann= 6 ,-1 , 0
  4571.8     .16       0  4653.3      .1       0  4798.2      .1       0
  4953.1     .07       0  5039.5      .1       0  5182.4     .16       0
Bank Sta=5001.8,5007.8
XS Rating Curve= 0 ,0
Exp/Cntr=0.3,0.1

Type RM Length L Ch R = 1 ,874     ,220,220,220
BEGIN DESCRIPTION:
Mapping XS 97d446e7
END DESCRIPTION:
XS GIS Cut Line= 4
      2708171.04     10006122.55      2708339.43     10006504.46
      2708618.94     10006620.78       2708908.9     10006622.51
#Sta/Elev= 30
  4459.1 2022.78  4512.1 2017.38  4573.2 2013.65  4686.3 2005.56  4744.5 2000.36
  4808.4 1997.16  4831.7 1994.85  4842.9 1992.46  4876.3 1989.06  4878.7 1989.06
  4897.1 1984.33  4900.8 1984.12  4913.5 1983.32  4972.9 1984.37  4992.9  1983.2
  4995.6  1982.7  4998.9  1983.2  5014.3 1983.92  5037.9 1986.41  5067.4 1991.91
  5086.3 1993.73  5096.7 1994.86  5120.5 1999.42  5190.5  2004.7  5228.8 2008.66
  5289.1 2013.32  5319.9 2015.78  5338.8 2018.04  5438.8 2024.34  5469.2 2024.95
#Mann= 10 ,-1 , 0
  4459.1     .16       0  4573.2      .1       0  4876.3     .16       0
  4900.8      .1       0  4992.9     .07       0  4998.9      .1       0
  5086.3     .16       0  5190.5      .1       0  5289.1     .16       0
  5319.9      .1       0
Bank Sta=4992.9,4998.9
XS Rating Curve= 0 ,0
Exp/Cntr=0.3,0.1

Type RM Length L Ch R = 1 ,654     ,241,241,241
BEGIN DESCRIPTION:
UNT 1030 IN HEWA 2.0
END DESCRIPTION:
XS GIS Cut Line= 4
      2708172.26     10006181.47      2708219.13     10006566.89
      2708344.13     10006754.39      2708849.32     10006754.39
#Sta/Elev= 30
  4469.4 2018.01  4568.8 2011.42  4622.8 2007.42  4663.1 2006.02  4743.7 1999.24
  4824.3 1995.25  4844.4 1992.97  4857.7 1992.35  4889.5 1986.84  4898.7 1985.75
    4906 1983.64  4949.8 1979.28    4962 1980.27  5003.9 1978.67  5006.6 1978.17
  5009.9 1978.67  5012.9 1979.89  5027.9 1981.46    5058 1982.34  5082.4 1985.83
  5097.3 1986.64  5117.3 1989.38  5147.3 1992.27  5257.3 2001.85  5307.3 2004.19
  5377.3 2010.79  5427.3 2013.06  5497.3 2017.95  5537.3 2019.16  5588.2  2021.8
#Mann= 6 ,-1 , 0
  4469.4     .16       0  4568.8      .1       0  4889.5     .16       0
    4906      .1       0  4949.8     .05       0  5027.9      .1       0
Bank Sta=5003.9,5009.9
XS Rating Curve= 0 ,0
Exp/Cntr=0.3,0.1

Type RM Length L Ch R = 1 ,413     ,255,255,255
BEGIN DESCRIPTION:
Mapping XS cca64d42
END DESCRIPTION:
XS GIS Cut Line= 4
      2708025.74     10006253.37      2708010.11     10006763.76
      2708254.91     10006943.44      2708664.95      10006966.8
#Sta/Elev= 30
  4335.9 2015.76  4426.3 2009.25  4476.3 2006.94  4505.8 2003.74  4566.4 1998.83
  4656.4 1995.04  4716.4 1990.21  4786.5 1983.22  4806.5 1982.98  4836.5 1979.63
  4872.9 1978.29  4953.1 1974.79  4967.8 1973.19  4980.9  1969.7  4994.8 1966.26
  5000.3  1965.8    5003  1965.3  5006.3  1965.8  5024.1 1971.29  5030.6 1975.23
    5045 1978.71  5074.3 1980.18  5149.3 1990.16  5193.8 1993.73  5233.9 1995.98
    5284 2000.16    5314 2001.17  5434.2 2009.34  5509.1 2012.32  5560.9 2015.13
#Mann= 6 ,-1 , 0
  4335.9     .16       0  4505.8      .1       0  4872.9      .1       0
  4980.9     .05       0  5030.6      .1       0  5509.1     .16       0
Bank Sta=5000.3,5006.3
XS Rating Curve= 0 ,0
Exp/Cntr=0.3,0.1

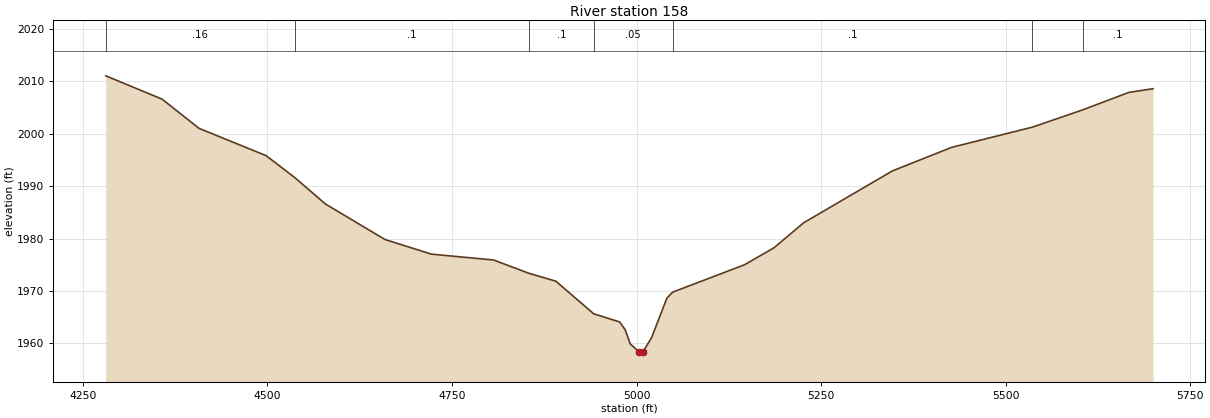
Type RM Length L Ch R = 1 ,158     ,0,0,0
BEGIN DESCRIPTION:
UNT 1030 IN HEWA 1.0
END DESCRIPTION:
XS GIS Cut Line= 4
      2707963.24     10006308.01      2707890.32     10006946.05
       2707999.7     10007081.46      2708601.28     10007107.51
#Sta/Elev= 30
    4281 2011.08  4357.2 2006.63  4407.5 2001.03  4498.1 1995.84    4537 1991.64
  4578.6 1986.59  4659.2 1979.81    4722 1977.02  4806.3  1975.9  4854.3 1973.35
  4890.6 1971.85  4941.8 1965.63    4977 1964.06  4984.5 1962.57  4991.4 1959.85
  5002.8 1958.42  5005.5 1957.92  5008.8 1958.42  5020.2 1961.06    5041 1968.63
  5048.8 1969.76  5146.1 1974.99  5186.1 1978.24  5226.1    1983  5346.3 1992.91
  5426.3  1997.4  5536.1 2001.28    5604 2004.57  5666.6 2007.91  5699.4 2008.62
#Mann= 7 ,-1 , 0
    4281     .16       0    4537      .1       0  4854.3      .1       0
  4941.8     .05       0  5048.8      .1       0  5536.1     .16       0
    5604      .1       0
Bank Sta=5002.8,5008.8
XS Rating Curve= 0 ,0
Exp/Cntr=0.3,0.1

Chan Stop Cuts=-1
Use User Specified Reach Order=0
Composite Channel Slope=5