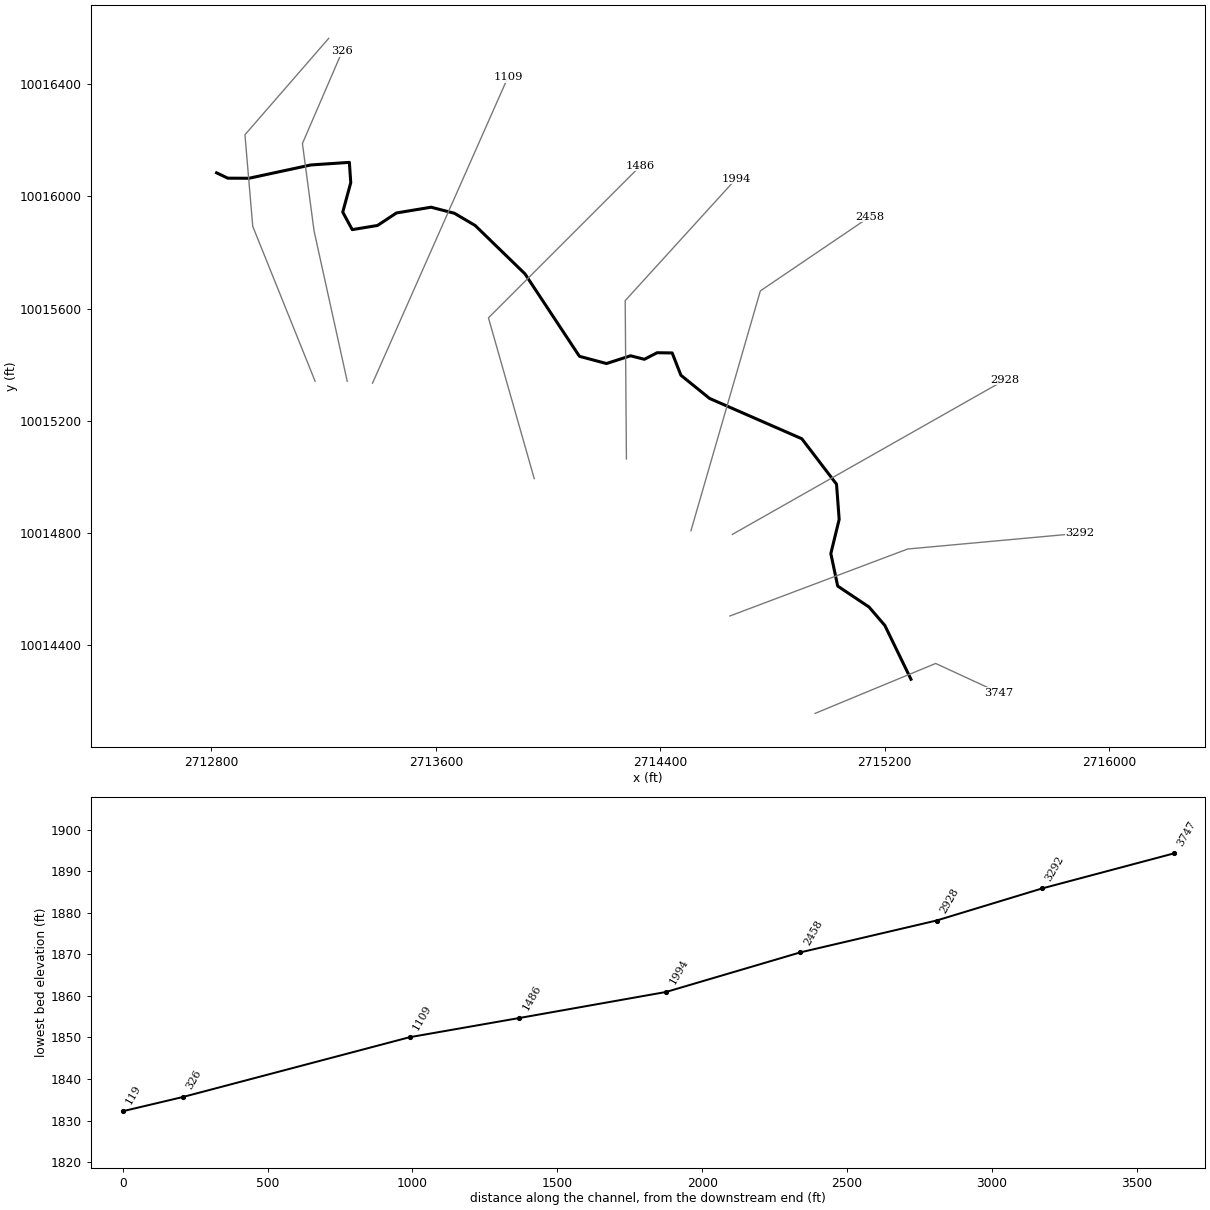
--- UNT 1031 IN HEWA.prj (project) ---

Proj Title=UNT 1031 IN HEWA Base Level Engineering
Current Plan=p01
Default Exp/Contr=0.3,0.1
English Units
Geom File=g01
Flow File=f01
Plan File=p01
BEGIN DESCRIPTION:
UNT 1031 IN HEWA
END DESCRIPTION:

--- UNT 1031 IN HEWA.p01 (plan) ---

Plan Title=Multiple Run
Short Identifier=Multiple
Geom File=g01
Flow File=f01
Subcritical Flow
K Sum by GR= 0
Std Step Tol= 0.01
Critical Tol= 0.01
Num of Std Step Trials= 20
Max Error Tol= 0.3
Flow Tol Ratio= 0.001
Split Flow NTrial= 30
Split Flow Tol= 0.02
Split Flow Ratio= 0.02
Log Output Level= 0
Friction Slope Method= 1
Unsteady Friction Slope Method= 2
Unsteady Bridges Friction Slope Method= 1
Parabolic Critical Depth
Global Vel Dist=  1 , 1 , 1
Global Log Level= 0
CheckData=True
Encroach Param= -1, 0, 0, 0
BEGIN DESCRIPTION:
Multiple Run
END DESCRIPTION:

--- UNT 1031 IN HEWA.f01 (steady flow) ---

Flow Title=Multiple
Number of Profiles=7
Profile Names=10-year,25-year,50-year,1pct_min,100-year,1pct_plu,500-year
River Rch & RM= UNT 1031 IN HEWA,Reach-1,3747
     934    1347    1702    1571    2125    2874    3306
Boundary for River Rch & Prof#=UNT 1031 IN HEWA,Reach-1,1
Up Type=0
Dn Type=3
Dn Slope=0.005
Boundary for River Rch & Prof#=UNT 1031 IN HEWA,Reach-1,2
Up Type=0
Dn Type=3
Dn Slope=0.005
Boundary for River Rch & Prof#=UNT 1031 IN HEWA,Reach-1,3
Up Type=0
Dn Type=3
Dn Slope=0.005
Boundary for River Rch & Prof#=UNT 1031 IN HEWA,Reach-1,4
Up Type=0
Dn Type=3
Dn Slope=0.005
Boundary for River Rch & Prof#=UNT 1031 IN HEWA,Reach-1,5
Up Type=0
Dn Type=3
Dn Slope=0.005
Boundary for River Rch & Prof#=UNT 1031 IN HEWA,Reach-1,6
Up Type=0
Dn Type=3
Dn Slope=0.005
Boundary for River Rch & Prof#=UNT 1031 IN HEWA,Reach-1,7
Up Type=0
Dn Type=3
Dn Slope=0.005

--- UNT 1031 IN HEWA.g01 (geometry) ---

Geom Title=Existing Conditions

River Reach=UNT 1031 IN HEWA,Reach-1
Reach XY= 30
      2715293.79     10014278.41      2715200.83     10014470.04
      2715144.31     10014535.92      2715032.59     10014610.62
      2715008.18     10014726.44      2715037.92     10014848.23
      2715028.47     10014973.73      2714904.71     10015135.80
      2714576.07     10015279.39      2714473.74     10015362.11
      2714442.55     10015441.68      2714388.69     10015442.38
      2714343.43     10015419.00      2714294.28     10015431.53
      2714208.32     10015403.88      2714111.97     10015429.68
      2713917.87     10015723.55      2713740.30     10015895.96
      2713666.25     10015939.56      2713583.15     10015961.17
      2713459.66     10015940.67      2713392.05     10015896.05
      2713301.95     10015881.30      2713268.19     10015943.63
      2713296.75     10016048.78      2713291.79     10016121.01
      2713154.28     10016111.80      2712933.88     10016064.34
      2712858.37     10016064.69      2712818.47     10016083.73

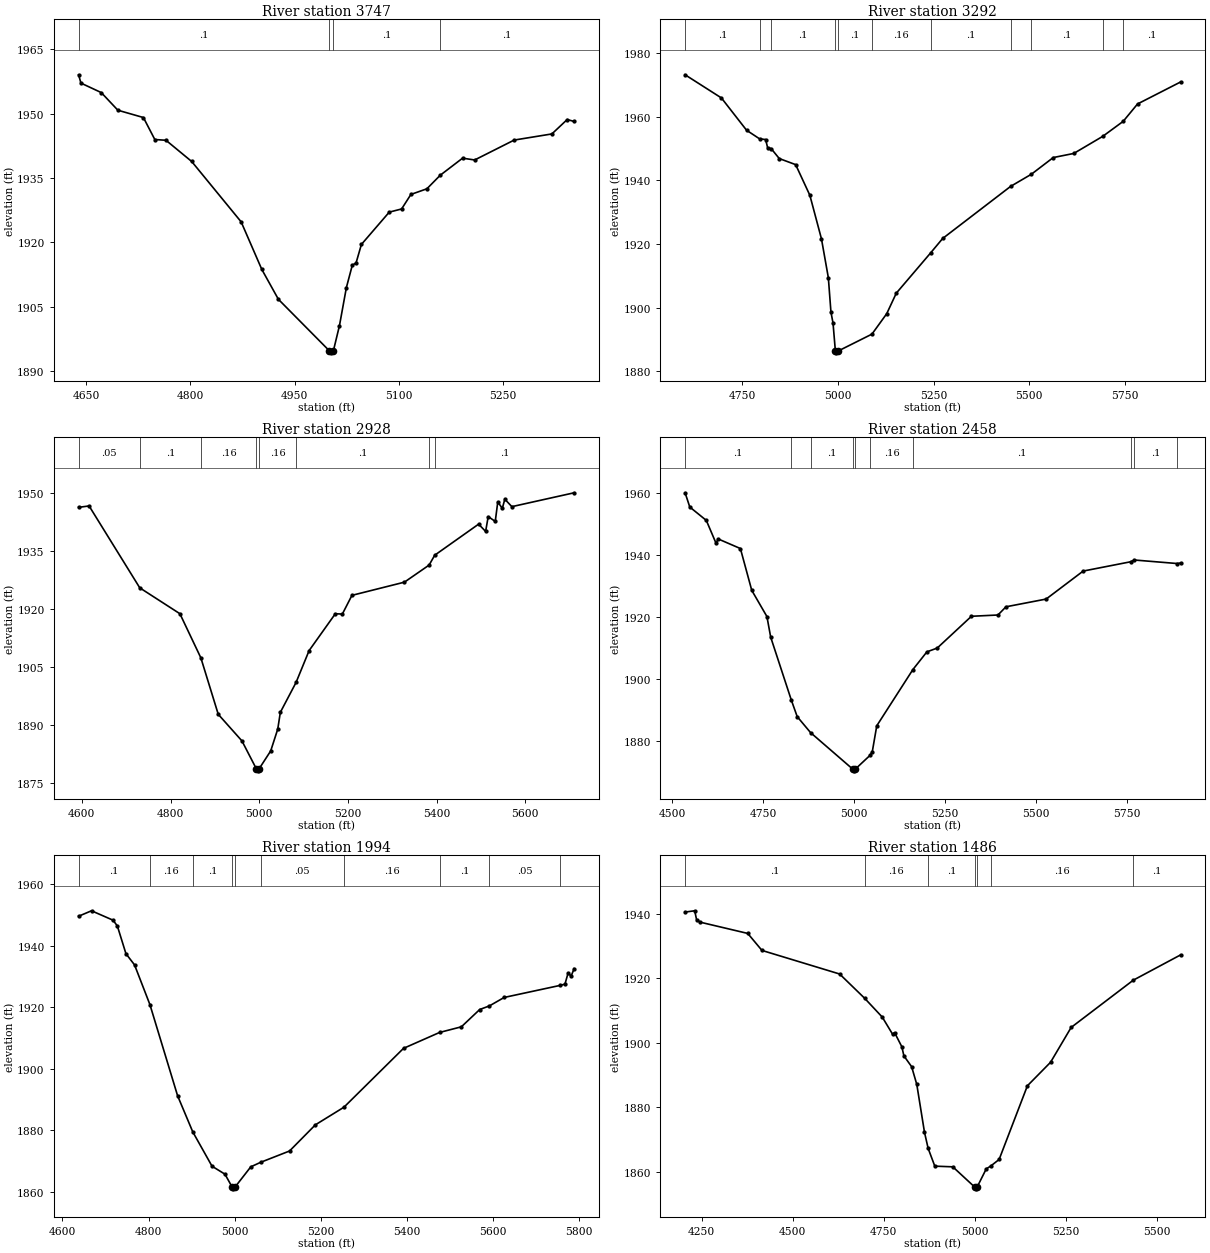
Type RM Length L Ch R = 1,3747,455,455,455
BEGIN DESCRIPTION:
UNT 1031 IN HEWA 7.0
END DESCRIPTION:
XS GIS Cut Line= 3
      2714952.23     10014156.74      2715381.89     10014334.68
      2715607.57     10014230.53
#Sta/Elev= 30
  4639.0 1959.07  4642.3 1957.13  4671.6 1954.92  4695.5 1950.81  4732.3 1949.10
  4748.7 1943.98  4764.8 1943.80  4801.8 1938.86  4873.0 1924.79  4902.8 1913.69
  4926.7 1906.72  4999.9 1894.75  5002.7 1894.25  5005.9 1894.75  5014.6 1900.59
  5024.6 1909.48  5033.1 1914.68  5038.5 1915.20  5046.2 1919.52  5086.3 1927.05
  5104.1 1927.79  5117.5 1931.18  5140.5 1932.49  5159.8 1935.66  5191.9 1939.63
  5209.3 1939.21  5266.2 1943.85  5320.5 1945.28  5342.6 1948.64  5352.6 1948.18
#Mann=4,-1,0
  4639.0     0.1       0  4999.9    0.07       0  5005.9     0.1       0
  5159.8     0.1       0
Bank Sta=4999.9,5005.9
Exp/Cntr=0.3,0.1

Type RM Length L Ch R = 1,3292,364,364,364
BEGIN DESCRIPTION:
UNT 1031 IN HEWA 6.0
END DESCRIPTION:
XS GIS Cut Line= 3
      2714648.34     10014503.94      2715282.07     10014742.67
      2715896.40     10014798.91
#Sta/Elev= 30
  4601.1 1973.12  4695.9 1965.85  4761.7 1955.70  4795.6 1953.01  4811.4 1952.79
  4816.8 1950.13  4825.9 1949.94  4847.0 1946.82  4889.8 1944.91  4926.9 1935.29
  4957.2 1921.61  4975.2 1909.41  4982.0 1898.58  4987.4 1895.19  4993.6 1886.32
  4996.4 1885.82  4999.6 1886.32  5089.1 1891.70  5127.7 1898.12  5152.6 1904.55
  5242.6 1917.24  5273.7 1921.72  5451.1 1938.07  5505.6 1941.91  5562.5 1947.13
  5616.1 1948.42  5691.8 1953.79  5745.2 1958.50  5782.7 1963.96  5895.2 1970.87
#Mann=11,-1,0
  4601.1     0.1       0  4795.6    0.05       0  4825.9     0.1       0
  4993.6    0.07       0  4999.6     0.1       0  5089.1    0.16       0
  5242.6     0.1       0  5451.1    0.05       0  5505.6     0.1       0
  5691.8    0.05       0  5745.2     0.1       0
Bank Sta=4993.6,4999.6
Exp/Cntr=0.3,0.1

Type RM Length L Ch R = 1,2928,470,470,470
BEGIN DESCRIPTION:
UNT 1031 IN HEWA 5.0
END DESCRIPTION:
XS GIS Cut Line= 2
      2714657.09     10014794.77      2715629.30     10015345.98
#Sta/Elev= 30
  4592.7 1946.32  4616.3 1946.68  4730.6 1925.48  4821.1 1918.78  4868.4 1907.35
  4907.6 1892.74  4961.0 1885.86  4993.6 1878.61  4996.4 1878.11  4999.6 1878.61
  5025.9 1883.27  5041.8 1888.93  5047.6 1893.25  5083.1 1901.00  5112.5 1909.24
  5171.6 1918.77  5187.5 1918.70  5209.1 1923.54  5327.4 1926.95  5383.1 1931.37
  5395.8 1933.93  5494.8 1941.97  5510.6 1940.08  5516.4 1943.93  5532.3 1942.67
  5538.0 1947.72  5548.2 1946.06  5553.9 1948.42  5569.8 1946.50  5710.3 1950.09
#Mann=8,-1,0
  4592.7    0.05       0  4730.6     0.1       0  4868.4    0.16       0
  4993.6    0.07       0  4999.6    0.16       0  5083.1     0.1       0
  5383.1    0.05       0  5395.8     0.1       0
Bank Sta=4993.6,4999.6
Exp/Cntr=0.3,0.1

Type RM Length L Ch R = 1,2458,464,464,464
BEGIN DESCRIPTION:
UNT 1031 IN HEWA 4.0
END DESCRIPTION:
XS GIS Cut Line= 3
      2714509.49     10014807.73      2714756.89     10015662.81
      2715147.48     10015927.54
#Sta/Elev= 30
  4536.0 1959.95  4548.9 1955.36  4594.3 1951.06  4621.3 1943.63  4626.5 1945.11
  4688.0 1942.00  4719.2 1928.55  4760.9 1920.11  4771.3 1913.46  4827.8 1893.28
  4844.1 1887.90  4880.9 1882.75  4997.3 1870.95  5000.0 1870.45  5003.3 1870.95
  5044.6 1875.47  5050.6 1876.67  5062.8 1884.95  5162.1 1903.05  5200.6 1908.75
  5229.0 1909.97  5323.0 1920.20  5395.9 1920.61  5417.9 1923.25  5528.3 1925.74
  5630.1 1934.75  5760.5 1937.74  5770.9 1938.31  5889.2 1937.17  5898.0 1937.36
#Mann=10,-1,0
  4536.0     0.1       0  4827.8    0.16       0  4880.9     0.1       0
  4997.3    0.07       0  5003.3     0.1       0  5044.6    0.16       0
  5162.1     0.1       0  5760.5    0.05       0  5770.9     0.1       0
  5889.2    0.05       0
Bank Sta=4997.3,5003.3
Exp/Cntr=0.3,0.1

Type RM Length L Ch R = 1,1994,508,508,508
BEGIN DESCRIPTION:
UNT 1031 IN HEWA 3.0
END DESCRIPTION:
XS GIS Cut Line= 3
      2714279.46     10015063.85      2714275.12     10015628.09
      2714670.09     10016062.12
#Sta/Elev= 30
  4637.7 1949.62  4667.6 1951.39  4717.6 1948.33  4727.6 1946.46  4747.6 1937.43
  4767.6 1933.78  4803.3 1920.86  4867.6 1891.20  4902.8 1879.46  4947.6 1868.28
  4977.6 1865.69  4994.6 1861.42  4997.3 1860.92  5000.6 1861.42  5037.6 1868.08
  5060.5 1869.55  5127.6 1873.23  5187.6 1881.74  5254.0 1887.48  5392.4 1906.63
  5476.1 1911.80  5526.8 1913.64  5569.4 1919.27  5591.9 1920.44  5626.2 1923.19
  5756.4 1927.12  5767.4 1927.53  5774.8 1931.19  5781.6 1930.12  5788.8 1932.57
#Mann=10,-1,0
  4637.7     0.1       0  4803.3    0.16       0  4902.8     0.1       0
  4994.6    0.07       0  5000.6     0.1       0  5060.5    0.05       0
  5254.0    0.16       0  5476.1     0.1       0  5591.9    0.05       0
  5756.4     0.1       0
Bank Sta=4994.6,5000.6
Exp/Cntr=0.3,0.1

Type RM Length L Ch R = 1,1486,377,377,377
BEGIN DESCRIPTION:
UNT 1031 IN HEWA 2.0
END DESCRIPTION:
XS GIS Cut Line= 3
      2713950.82     10014993.74      2713787.61     10015566.68
      2714329.30     10016108.37
#Sta/Elev= 30
  4204.3 1940.52  4230.7 1940.92  4235.9 1938.13  4245.9 1937.38  4376.5 1933.89
  4415.5 1928.62  4629.0 1921.30  4697.9 1913.75  4746.2 1907.92  4774.8 1902.56
  4780.0 1903.11  4800.0 1898.71  4805.6 1895.89  4826.8 1892.55  4841.0 1887.05
  4862.2 1872.17  4872.2 1867.20  4890.5 1861.68  4940.0 1861.47  5000.6 1855.14
  5003.4 1854.64  5006.6 1855.14  5031.9 1860.84  5044.4 1861.73  5067.3 1863.76
  5145.0 1886.62  5208.7 1893.92  5265.2 1904.72  5435.9 1919.38  5566.1 1927.24
#Mann=7,-1,0
  4204.3     0.1       0  4697.9    0.16       0  4872.2     0.1       0
  5000.6    0.07       0  5006.6     0.1       0  5044.4    0.16       0
  5435.9     0.1       0
Bank Sta=5000.6,5006.6
Exp/Cntr=0.3,0.1

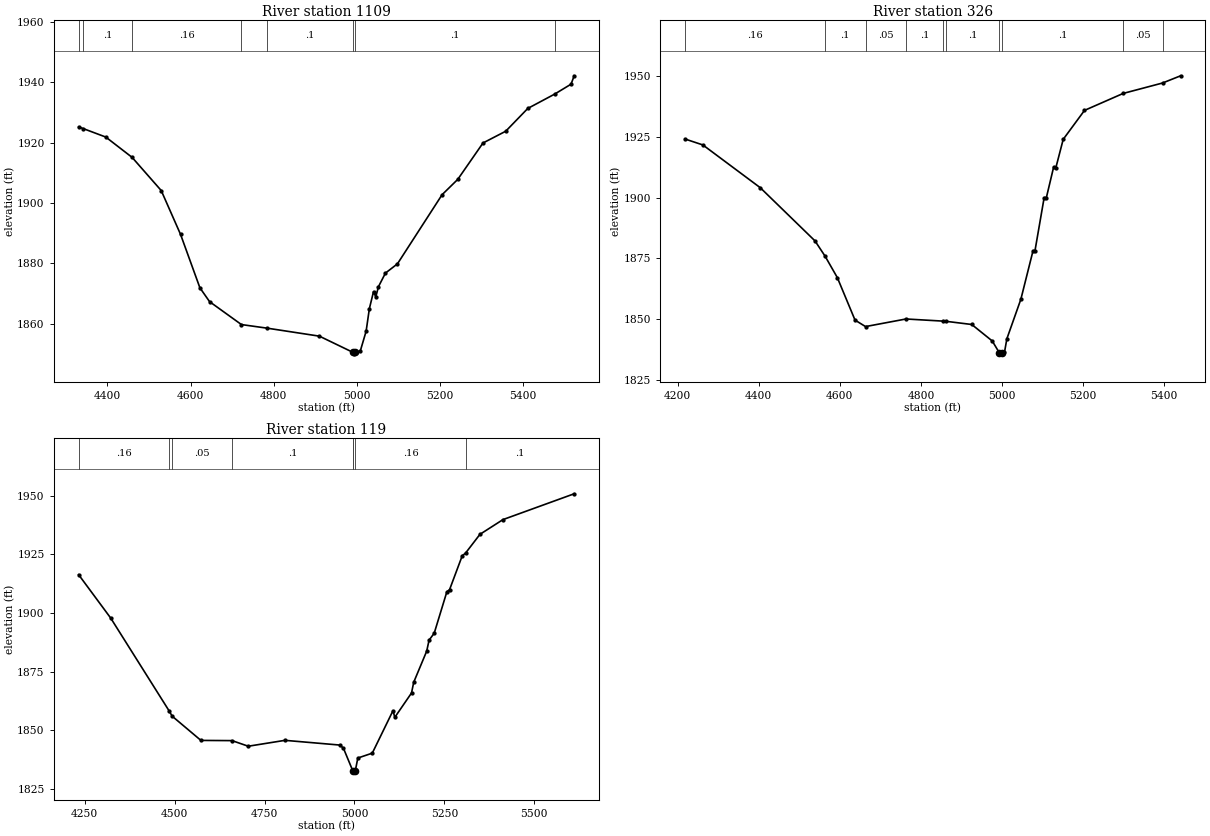
Type RM Length L Ch R = 1,1109,783,783,783
BEGIN DESCRIPTION:
Mapping XS 11a0be5c
END DESCRIPTION:
XS GIS Cut Line= 2
      2713374.41     10015334.02      2713857.08     10016424.37
#Sta/Elev= 30
  4330.8 1925.24  4341.5 1924.69  4396.1 1921.87  4459.5 1915.13  4529.5 1904.15
  4576.0 1889.63  4622.6 1871.92  4645.9 1867.33  4722.5 1859.74  4785.2 1858.53
  4910.1 1855.90  4990.8 1850.54  4993.6 1850.04  4996.8 1850.54  5008.5 1850.94
  5022.6 1857.55  5030.4 1865.03  5040.4 1870.66  5045.8 1868.91  5052.3 1872.30
  5069.1 1876.80  5097.9 1879.85  5205.4 1902.77  5243.1 1907.85  5303.8 1919.90
  5358.5 1923.80  5411.6 1931.35  5476.4 1936.11  5515.7 1939.39  5523.2 1942.17
#Mann=8,-1,0
  4330.8    0.16       0  4341.5     0.1       0  4459.5    0.16       0
  4722.5    0.05       0  4785.2     0.1       0  4990.8    0.07       0
  4996.8     0.1       0  5476.4    0.05       0
Bank Sta=4990.8,4996.8
Exp/Cntr=0.3,0.1

Type RM Length L Ch R = 1,326,207,207,207
BEGIN DESCRIPTION:
Mapping XS 6be4a492
END DESCRIPTION:
XS GIS Cut Line= 4
      2713284.14     10015340.97      2713166.08     10015875.71
      2713124.42     10016188.21      2713266.76     10016518.03
#Sta/Elev= 30
  4218.5 1924.14  4262.3 1921.71  4403.9 1904.09  4538.8 1882.19  4563.7 1875.89
  4593.9 1867.07  4637.6 1849.54  4663.5 1846.88  4763.3 1850.01  4854.7 1849.13
  4862.0 1849.05  4925.5 1847.74  4976.0 1840.95  4993.2 1836.15  4995.9 1835.65
  4999.2 1836.15  5006.2 1836.33  5012.1 1841.88  5046.6 1858.16  5076.6 1878.14
  5081.4 1878.14  5104.0 1900.01  5109.4 1899.96  5127.5 1912.67  5132.9 1912.34
  5151.0 1924.02  5203.5 1935.94  5298.9 1942.93  5395.9 1947.22  5440.6 1950.20
#Mann=10,-1,0
  4218.5    0.16       0  4563.7     0.1       0  4663.5    0.05       0
  4763.3     0.1       0  4854.7    0.05       0  4862.0     0.1       0
  4993.2    0.07       0  4999.2     0.1       0  5298.9    0.05       0
  5395.9     0.1       0
Bank Sta=4993.2,4999.2
Exp/Cntr=0.3,0.1

Type RM Length L Ch R = 1,119,0,0,0
BEGIN DESCRIPTION:
UNT 1031 IN HEWA 1.0
END DESCRIPTION:
XS GIS Cut Line= 4
      2713169.55     10015341.01      2712947.33     10015893.07
      2712919.56     10016219.46      2713218.16     10016563.20
#Sta/Elev= 30
  4233.0 1916.30  4322.2 1897.80  4484.0 1858.38  4493.2 1855.96  4573.1 1845.64
  4659.6 1845.55  4704.7 1843.16  4806.8 1845.67  4959.2 1843.66  4969.3 1842.33
  4995.2 1832.75  4996.4 1832.74  4999.1 1832.24  5002.4 1832.74  5009.4 1838.13
  5049.6 1840.21  5107.2 1858.32  5112.2 1855.48  5158.7 1865.86  5164.8 1870.44
  5200.9 1883.70  5207.5 1888.39  5221.8 1891.35  5256.9 1908.98  5264.5 1909.93
  5299.7 1924.36  5309.1 1925.54  5349.0 1933.51  5413.0 1939.79  5611.0 1950.80
#Mann=8,-1,0
  4233.0    0.16       0  4484.0     0.1       0  4493.2    0.05       0
  4659.6     0.1       0  4995.2    0.16       0  4996.4    0.07       0
  5002.4    0.16       0  5309.1     0.1       0
Bank Sta=4996.4,5002.4
Exp/Cntr=0.3,0.1

Chan Stop Cuts=-1