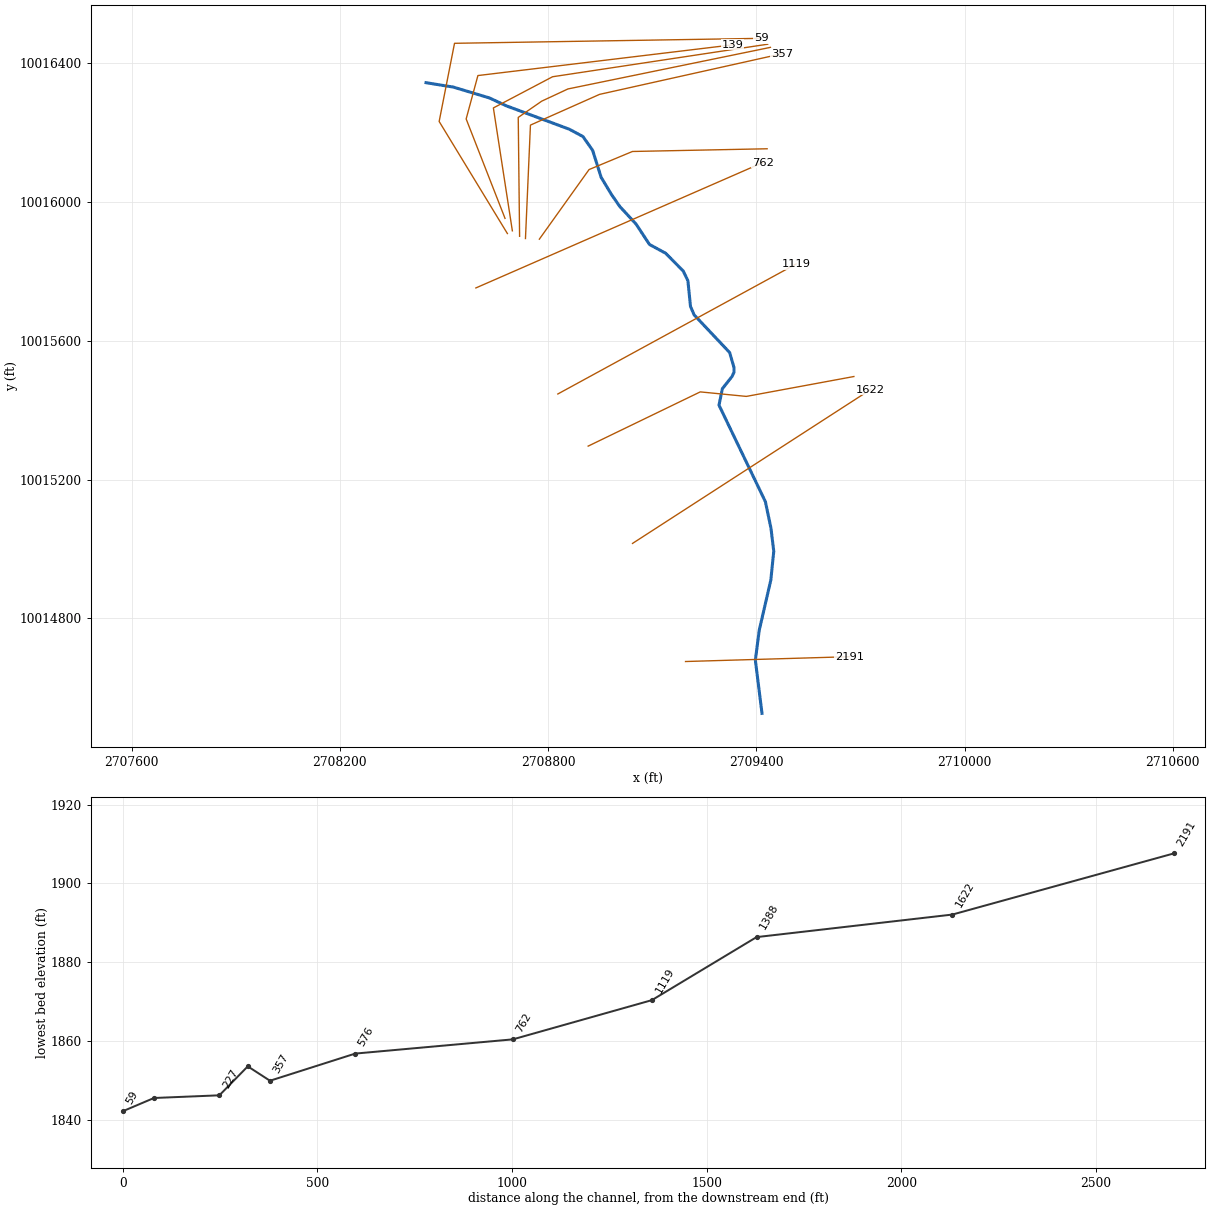
--- UNT 1033 IN HEWA.prj (project) ---

Proj Title=UNT 1033 IN HEWA Base Level Engineering
Current Plan=p01
Default Exp/Contr=0.3,0.1
English Units
Geom File=g01
Flow File=f01
Plan File=p01
Y Axis Title=Elevation
X Axis Title(PF)=Main Channel Distance
X Axis Title(XS)=Station
BEGIN DESCRIPTION:
UNT 1033 IN HEWA
END DESCRIPTION:
DSS Export Rating Curves= 0
DSS Export Rating Curve Sorted= 0
DSS Export Volume Flow Curves= 0
DXF OffsetX= 0
DXF OffsetY= 0
DXF ScaleX= 1
DXF ScaleY= 10

--- UNT 1033 IN HEWA.p01 (plan) ---

Plan Title=Multiple Run
Short Identifier=Multiple
Geom File=g01
Flow File=f01
Subcritical Flow
K Sum by GR= 0
Std Step Tol= 0.01
Critical Tol= 0.01
Num of Std Step Trials= 20
Max Error Tol= 0.3
Flow Tol Ratio= 0.001
Split Flow NTrial= 30
Split Flow Tol= 0.02
Split Flow Ratio= 0.02
Log Output Level= 0
Friction Slope Method= 1
Unsteady Friction Slope Method= 2
Unsteady Bridges Friction Slope Method= 1
Parabolic Critical Depth
Global Vel Dist=  1 , 1 , 1
Global Log Level= 0
CheckData=True
Encroach Param= -1, 0, 0, 0
BEGIN DESCRIPTION:
Multiple Run
END DESCRIPTION:

--- UNT 1033 IN HEWA.f01 (steady flow) ---

Flow Title=Multiple
Program Version=4.10
Number of Profiles= 7
Profile Names=10-year,25-year,50-year,1pct_min,100-year,1pct_plu,500-year
River Rch & RM=UNT 1033 IN HEWA,Reach-1         ,2191
     353     477     577     513     693     938     994
Boundary for River Rch & Prof#=UNT 1033 IN HEWA,Reach-1         , 1
Up Type= 0
Dn Type= 3
Dn Slope=0.024
Boundary for River Rch & Prof#=UNT 1033 IN HEWA,Reach-1         , 2
Up Type= 0
Dn Type= 3
Dn Slope=0.024
Boundary for River Rch & Prof#=UNT 1033 IN HEWA,Reach-1         , 3
Up Type= 0
Dn Type= 3
Dn Slope=0.024
Boundary for River Rch & Prof#=UNT 1033 IN HEWA,Reach-1         , 4
Up Type= 0
Dn Type= 3
Dn Slope=0.024
Boundary for River Rch & Prof#=UNT 1033 IN HEWA,Reach-1         , 5
Up Type= 0
Dn Type= 3
Dn Slope=0.024
Boundary for River Rch & Prof#=UNT 1033 IN HEWA,Reach-1         , 6
Up Type= 0
Dn Type= 3
Dn Slope=0.024
Boundary for River Rch & Prof#=UNT 1033 IN HEWA,Reach-1         , 7
Up Type= 0
Dn Type= 3
Dn Slope=0.024
DSS Import GetInterval= 0
DSS Import GetPeak= 0
DSS Import FillOption= 0

--- UNT 1033 IN HEWA.g01 (geometry) ---

Geom Title=Existing Conditions
Program Version=4.10

River Reach=UNT 1033 IN HEWA,Reach-1
Reach XY= 30
      2709416.36     10014526.48      2709397.22     10014679.95
      2709408.34     10014765.73       2709441.7     10014910.28
      2709450.25     10014993.37      2709442.21     10015059.85
       2709426.1     10015136.49      2709292.43     10015414.59
      2709302.18     10015462.07      2709330.38     10015497.74
      2709335.66      10015509.5      2709335.75     10015522.71
      2709323.13     10015566.19      2709220.76     10015674.73
      2709210.31     10015699.24      2709202.82     10015773.13
       2709189.4     10015801.11      2709138.64     10015852.35
      2709092.22     10015877.52       2709053.3      10015936.5
      2709006.53     10015987.08      2708983.01      10016020.9
       2708952.9     10016070.86      2708928.29     10016148.84
      2708900.36     10016188.64      2708861.54     10016209.47
      2708679.56     10016277.09      2708631.07     10016299.72
      2708527.36     10016330.93      2708448.47     10016343.73

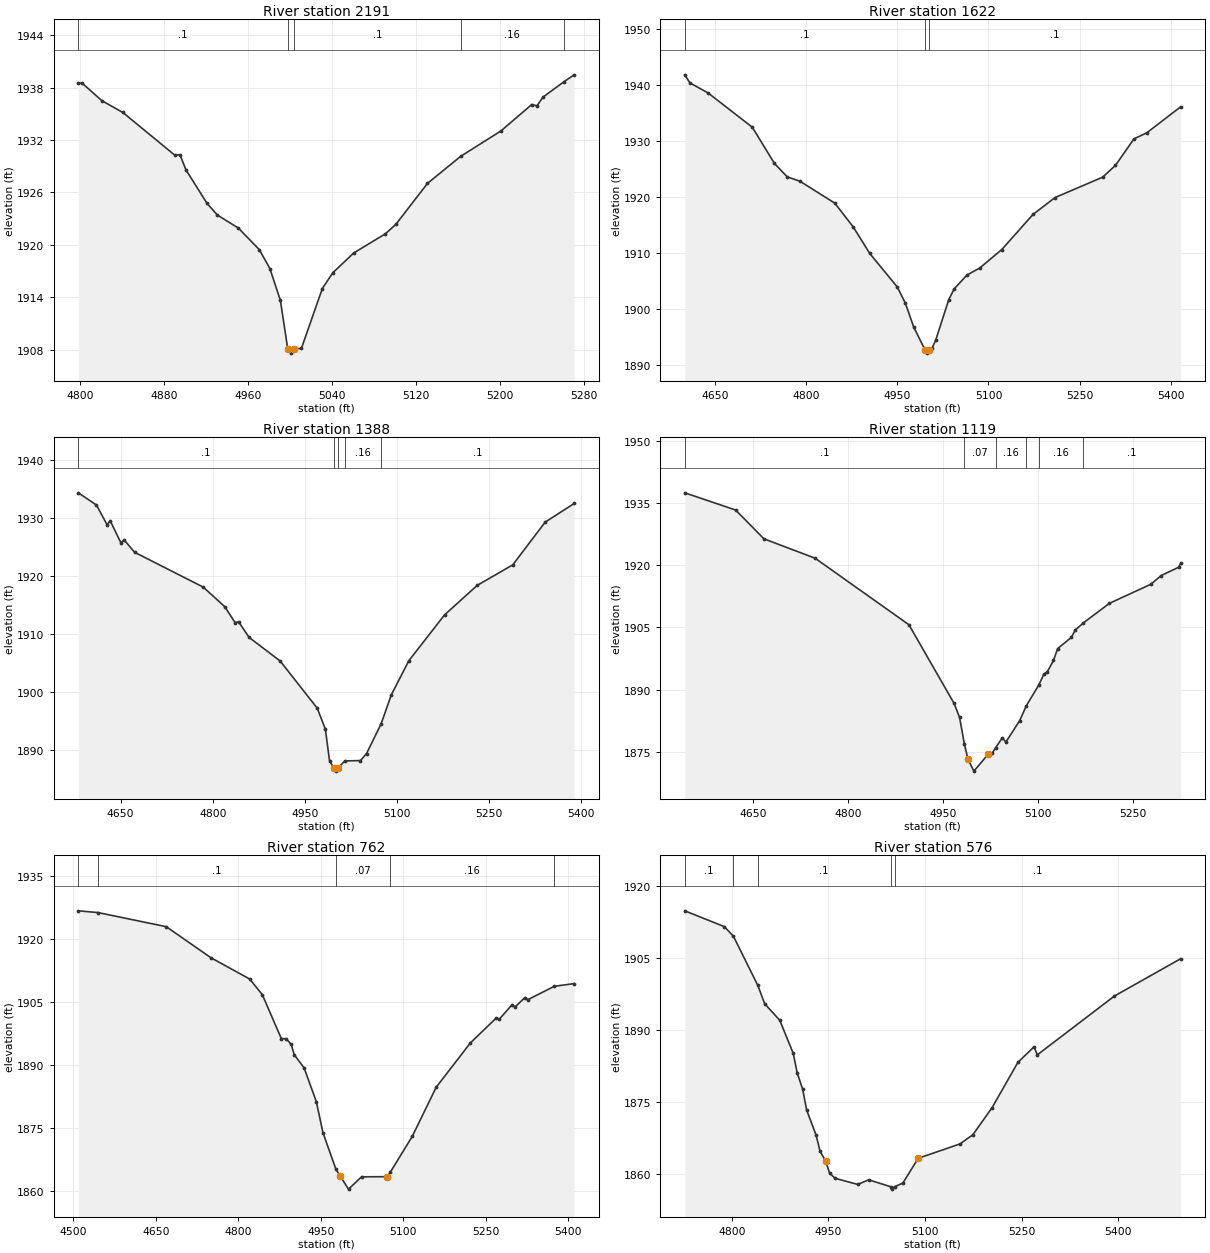
Type RM Length L Ch R = 1 ,2191    ,569,569,569
BEGIN DESCRIPTION:
UNT 1033 IN HEWA 5.0
END DESCRIPTION:
XS GIS Cut Line= 2
      2709196.05      10014675.9      2709668.25     10014689.79
#Sta/Elev= 30
  4798.5 1938.51  4802.2 1938.51  4820.9 1936.51  4840.9 1935.16  4890.3 1930.28
  4895.3 1930.32    4901  1928.6    4921 1924.77    4931 1923.41    4951 1921.92
    4971 1919.44    4981 1917.29    4991 1913.64    4998  1908.1  5000.8  1907.6
    5004  1908.1    5011 1908.13    5031    1915    5041 1916.81    5061 1919.08
    5091 1921.26    5101 1922.34  5131.1 1927.03  5162.7 1930.13  5201.1 1933.04
  5230.5 1936.07  5235.5 1935.92  5241.1 1936.91  5261.2 1938.68  5270.9 1939.47
#Mann= 5 ,-1 , 0
  4798.5      .1       0    4998     .07       0    5004      .1       0
  5162.7     .16       0  5261.2      .1       0
Bank Sta=4998,5004
XS Rating Curve= 0 ,0
Exp/Cntr=0.3,0.1

Type RM Length L Ch R = 1 ,1622    ,503,503,503
BEGIN DESCRIPTION:
UNT 1033 IN HEWA 4.0
END DESCRIPTION:
XS GIS Cut Line= 2
      2709043.29     10015016.19      2709729.32     10015459.68
#Sta/Elev= 30
  4599.7 1941.74  4608.1 1940.31  4638.4 1938.48    4711 1932.38  4747.3 1925.94
  4768.4 1923.54  4789.5 1922.75  4846.9 1918.84  4877.2  1914.6  4904.3 1909.88
  4949.8 1903.88  4963.1 1900.99  4976.9 1896.72  4995.8 1892.58  4998.6 1892.08
  5001.8 1892.58  5007.2    1893  5013.1  1894.4  5034.5  1901.6  5043.5 1903.54
  5064.6 1906.02  5085.7 1907.27    5122 1910.57  5173.4 1916.83  5209.7 1919.84
  5288.2 1923.48  5309.3 1925.59  5339.7 1930.31  5360.8 1931.39  5416.6 1936.03
#Mann= 3 ,-1 , 0
  4599.7      .1       0  4995.8     .07       0  5001.8      .1       0
Bank Sta=4995.8,5001.8
XS Rating Curve= 0 ,0
Exp/Cntr=0.3,0.1

Type RM Length L Ch R = 1 ,1388    ,269,269,269
BEGIN DESCRIPTION:
Mapping XS 0b5f6b00
END DESCRIPTION:
XS GIS Cut Line= 4
      2708915.47     10015296.54      2709238.38     10015452.79
       2709371.2     10015439.77      2709681.07     10015497.06
#Sta/Elev= 30
  4581.2 1934.38  4610.7 1932.28  4627.8 1928.91  4633.3 1929.52  4650.4 1925.77
  4655.9 1926.24    4673 1924.11  4784.5 1918.12  4819.6 1914.74  4836.6 1911.97
  4842.2 1912.13  4859.2 1909.44  4909.9 1905.35  4970.2 1897.22  4983.4 1893.61
  4990.2 1888.15  4997.3 1886.86    5000 1886.36  5003.3 1886.86  5015.3 1888.12
  5040.5 1888.18  5050.5  1889.4  5074.2 1894.52  5090.9 1899.55  5119.5 1905.44
  5177.5 1913.32  5230.5  1918.4  5288.5 1921.95  5341.4 1929.33  5388.5 1932.54
#Mann= 5 ,-1 , 0
  4581.2      .1       0  4997.3     .07       0  5003.3      .1       0
  5015.3     .16       0  5074.2      .1       0
Bank Sta=4997.3,5003.3
XS Rating Curve= 0 ,0
Exp/Cntr=0.3,0.1

Type RM Length L Ch R = 1 ,1119    ,357,357,357
BEGIN DESCRIPTION:
UNT 1033 IN HEWA 3.0
END DESCRIPTION:
XS GIS Cut Line= 2
      2708828.04     10015446.76      2709514.47     10015821.17
#Sta/Elev= 30
  4542.9 1937.45  4623.1  1933.3  4667.7 1926.36  4748.4 1921.69  4896.4 1905.64
  4967.6 1886.67  4976.2 1883.32  4983.8  1876.9  4989.4 1873.24  4998.8 1870.36
  5021.7  1874.5  5027.3 1874.62  5033.2 1876.03  5043.6 1878.39  5049.2 1877.35
  5071.1 1882.56  5081.6 1886.16  5100.8 1891.03  5109.1 1893.72  5114.7 1894.33
  5124.3 1897.04  5130.9  1899.9  5152.7 1902.64  5158.5 1904.34  5171.6 1906.11
  5212.5 1910.81    5278 1915.42  5294.2 1917.52  5321.7 1919.51  5324.8 1920.43
#Mann= 6 ,-1 , 0
  4542.9      .1       0  4983.8     .07       0  5033.2     .16       0
  5081.6      .1       0  5100.8     .16       0  5171.6      .1       0
Bank Sta=4989.4,5021.7
XS Rating Curve= 0 ,0
Exp/Cntr=0.3,0.1

Type RM Length L Ch R = 1 ,762     ,405,405,405
BEGIN DESCRIPTION:
UNT 1033 IN HEWA 2.0
END DESCRIPTION:
XS GIS Cut Line= 2
      2708591.91      10015752.3      2709418.26     10016113.39
#Sta/Elev= 30
    4509 1926.61  4545.1 1926.19  4668.9 1922.84  4750.3 1915.44  4820.5  1910.4
  4843.5  1906.7  4878.2 1896.22  4887.2 1896.18  4896.2 1894.82  4901.6  1892.4
  4919.6 1889.25  4941.8 1881.25  4953.9 1873.84  4977.3 1865.21  4985.4 1863.46
  5000.4 1860.41  5024.1 1863.34  5070.9 1863.37  5076.3 1864.41  5116.4 1872.97
    5160 1884.67  5222.2 1895.21    5269  1901.1  5274.4  1900.8  5297.8 1904.26
  5303.3 1903.75  5321.2 1905.97  5326.7 1905.48  5374.6 1908.66  5410.8  1909.3
#Mann= 5 ,-1 , 0
    4509     .16       0  4545.1      .1       0  4977.3     .07       0
  5076.3     .16       0  5374.6      .1       0
Bank Sta=4985.4,5070.9
XS Rating Curve= 0 ,0
Exp/Cntr=0.3,0.1

Type RM Length L Ch R = 1 ,576     ,219,219,219
BEGIN DESCRIPTION:
Mapping XS 4720ef9b
END DESCRIPTION:
XS GIS Cut Line= 4
      2708774.82     10015892.86      2708918.07     10016093.41
      2709043.07      10016145.5      2709431.11     10016153.31
#Sta/Elev= 30
    4727 1914.76  4788.4 1911.47  4802.6 1909.45  4840.3 1899.25  4851.1  1895.4
  4874.5 1891.96  4895.4 1885.08  4901.5 1881.06  4910.1 1877.58  4916.2 1873.29
    4931    1868  4937.1 1864.67  4945.7 1862.66  4951.9 1860.12  4960.5 1859.05
  4995.6 1857.78  5012.6 1858.74  5046.7  1857.3  5049.5  1856.8  5052.7  1857.3
  5065.6 1858.06  5089.5 1863.22  5154.3 1866.21  5174.3 1868.12  5204.3 1873.79
  5244.3  1883.2  5269.4 1886.45  5274.4 1884.76  5394.3 1897.02    5497 1904.78
#Mann= 5 ,-1 , 0
    4727      .1       0  4802.6     .16       0  4840.3      .1       0
  5046.7     .07       0  5052.7      .1       0
Bank Sta=4945.7,5089.5
XS Rating Curve= 0 ,0
Exp/Cntr=0.3,0.1

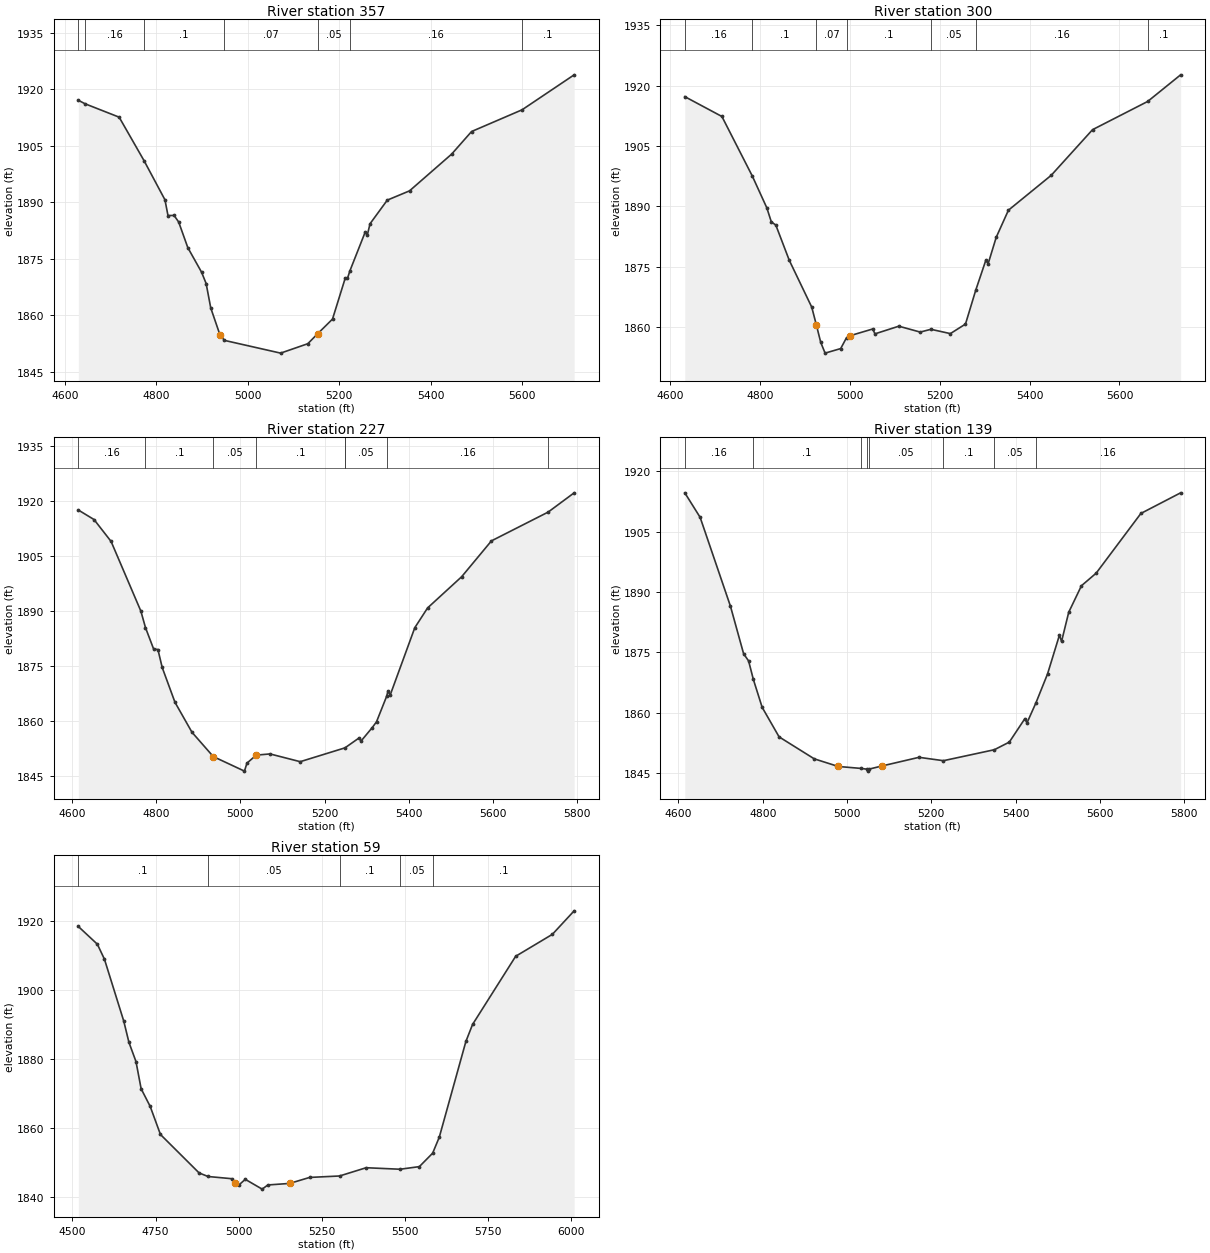
Type RM Length L Ch R = 1 ,357     ,57,57,57
BEGIN DESCRIPTION:
Mapping XS 3b8e2d96
END DESCRIPTION:
XS GIS Cut Line= 4
      2708734.82     10015894.66      2708749.14     10016221.51
      2708948.36     10016310.06       2709473.9     10016427.13
#Sta/Elev= 30
  4629.8 1917.03  4644.6 1916.09    4719 1912.54  4773.3 1901.02  4819.1 1890.61
  4825.7 1886.44  4839.1 1886.45  4849.1 1884.71  4869.1  1877.9  4899.1  1871.4
  4909.1 1868.39  4919.2  1861.9  4939.2  1854.8  4949.2 1853.29  5071.9 1849.91
  5131.3 1852.41  5153.2  1855.1  5185.3 1858.95  5212.9 1869.74    5218 1869.74
  5223.2 1871.72  5256.4 1881.94  5261.5 1881.33  5267.3 1884.25    5305 1890.52
  5353.6 1892.98  5445.7 1902.74  5489.2 1908.73  5599.5 1914.49  5713.4 1923.78
#Mann= 7 ,-1 , 0
  4629.8      .1       0  4644.6     .16       0  4773.3      .1       0
  4949.2     .07       0  5153.2     .05       0  5223.2     .16       0
  5599.5      .1       0
Bank Sta=4939.2,5153.2
XS Rating Curve= 0 ,0
Exp/Cntr=0.3,0.1

Type RM Length L Ch R = 1 ,300     ,73,73,73
BEGIN DESCRIPTION:
Mapping XS f7dca223
END DESCRIPTION:
XS GIS Cut Line= 5
      2708717.89     10015901.17      2708713.99     10016243.65
      2708781.69     10016290.52      2708857.22     10016325.68
      2709440.58     10016445.48
#Sta/Elev= 30
  4632.5 1917.28  4715.1 1912.35  4782.7 1897.57  4815.1 1889.65  4825.1 1886.16
  4835.1 1885.38  4865.1 1876.61  4915.1 1864.98  4925.1 1860.67  4935.1 1856.23
  4944.8 1853.56  4979.5 1854.69  4992.6 1857.41  5000.1 1857.88  5050.8 1859.56
  5055.8 1858.35  5108.9 1860.25  5156.5 1858.79  5180.4 1859.48  5223.6 1858.41
  5257.3 1860.78  5280.2 1869.22  5302.6 1876.64  5307.7 1875.75  5325.7 1882.33
  5352.9 1889.07  5448.2 1897.74  5540.1 1909.07  5662.8 1916.08  5736.2  1922.7
#Mann= 7 ,-1 , 0
  4632.5     .16       0  4782.7      .1       0  4925.1     .07       0
  4992.6      .1       0  5180.4     .05       0  5280.2     .16       0
  5662.8      .1       0
Bank Sta=4925.1,5000.1
XS Rating Curve= 0 ,0
Exp/Cntr=0.3,0.1

Type RM Length L Ch R = 1 ,227     ,168,168,168
BEGIN DESCRIPTION:
Mapping XS 945bf50a
END DESCRIPTION:
XS GIS Cut Line= 4
      2708697.05     10015916.87      2708642.37     10016270.99
      2708812.94     10016360.84      2709432.79     10016454.59
#Sta/Elev= 30
    4615 1917.56  4652.3 1914.96  4692.8 1908.98  4763.6 1889.93  4774.5 1885.44
    4794 1879.54  4804.1 1879.44  4814.2 1874.55  4844.6 1865.02    4885 1856.83
  4935.6 1850.19  5009.7 1846.21  5015.6 1848.39  5037.6 1850.58  5070.4 1850.91
  5142.1 1848.79  5248.5 1852.57  5281.8 1855.26  5286.9 1854.46  5313.3 1858.11
  5323.4 1859.68  5347.6 1866.69  5350.7 1868.14  5355.7 1866.93  5414.4 1885.41
  5444.8 1890.81  5525.7 1899.33  5596.5 1909.13  5731.3    1917    5793 1922.26
#Mann= 8 ,-1 , 0
    4615     .16       0  4774.5      .1       0  4935.6     .05       0
  5037.6      .1       0  5248.5      .1       0  5248.5     .05       0
  5347.6     .16       0  5731.3      .1       0
Bank Sta=4935.6,5037.6
XS Rating Curve= 0 ,0
Exp/Cntr=0.3,0.1

Type RM Length L Ch R = 1 ,139     ,80,80,80
BEGIN DESCRIPTION:
Mapping XS b1cc3fbc
END DESCRIPTION:
XS GIS Cut Line= 4
       2708675.9     10015952.75      2708563.91     10016239.25
      2708597.76     10016364.25      2709332.13     10016452.79
#Sta/Elev= 30
  4615.1 1914.66  4651.5 1908.57  4723.5 1886.48  4754.7 1874.68  4766.5 1872.91
  4777.8 1868.31  4798.7 1861.38  4838.9 1854.04  4922.4 1848.58  4979.2 1846.69
  5033.5  1846.2  5046.4 1846.03  5049.1 1845.53  5052.4 1846.03  5083.1 1846.81
    5171 1848.96  5228.9 1848.12  5349.9 1850.85  5385.3 1852.74  5422.2 1858.56
  5427.2  1857.5  5448.7 1862.54    5476 1869.66  5504.3 1879.32  5509.3 1877.74
  5526.3 1884.99  5556.5 1891.58  5591.4  1894.7  5697.6 1909.54  5791.9 1914.66
#Mann= 8 ,-1 , 0
  4615.1     .16       0  4777.8      .1       0  5033.5     .05       0
  5046.4     .07       0  5052.4     .05       0  5228.9      .1       0
  5349.9     .05       0  5448.7     .16       0
Bank Sta=4979.2,5083.1
XS Rating Curve= 0 ,0
Exp/Cntr=0.3,0.1

Type RM Length L Ch R = 1 ,59      ,0,0,0
BEGIN DESCRIPTION:
UNT 1033 IN HEWA 1.0
END DESCRIPTION:
XS GIS Cut Line= 4
      2708682.71     10015909.05      2708486.12     10016231.93
      2708530.39     10016457.19      2709413.99     10016471.51
#Sta/Elev= 30
  4517.6  1918.5  4574.8 1913.35  4596.1    1909  4654.2 1891.01  4669.7 1884.86
    4691 1879.24  4706.5 1871.34  4733.8 1866.19  4764.6 1858.05  4880.8 1846.88
  4907.6 1845.84    4979  1845.2  4989.9 1843.87  4999.4 1843.27  5019.7 1845.02
  5070.5 1842.17  5087.6 1843.38  5153.3 1843.83  5213.3 1845.57  5303.3 1845.99
  5383.3 1848.39  5485.3 1847.95  5543.3 1848.71  5583.3 1852.62  5603.3 1857.28
  5683.3  1885.1  5703.3 1890.02    5833 1909.84  5943.4 1916.22  6008.9 1923.05
#Mann= 5 ,-1 , 0
  4517.6      .1       0  4907.6     .05       0  5303.3      .1       0
  5485.3     .05       0  5583.3      .1       0
Bank Sta=4989.9,5153.3
XS Rating Curve= 0 ,0
Exp/Cntr=0.3,0.1

Chan Stop Cuts=-1
Use User Specified Reach Order=0
Composite Channel Slope=5