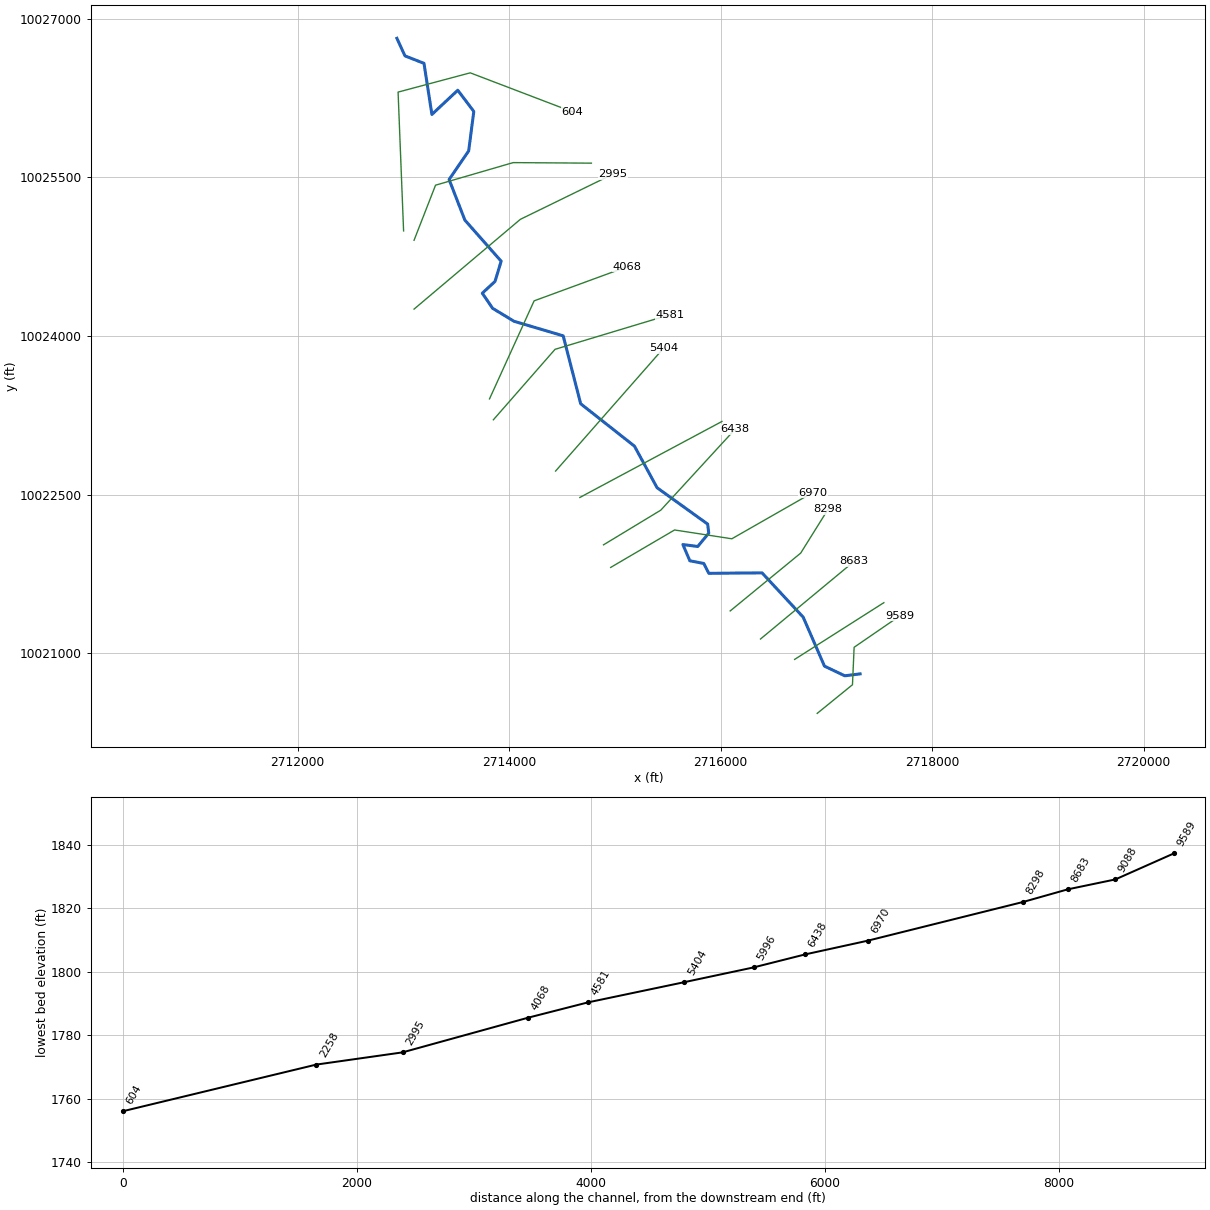
--- UNT 1034 IN HEWA.prj (project) ---

Proj Title=UNT 1034 IN HEWA Base Level Engineering
Current Plan=p01
Default Exp/Contr=0.3,0.1
English Units
Geom File=g01
Flow File=f01
Plan File=p01
BEGIN DESCRIPTION:
UNT 1034 IN HEWA
END DESCRIPTION:

--- UNT 1034 IN HEWA.p01 (plan) ---

Plan Title=Multiple Run
Short Identifier=Multiple
Geom File=g01
Flow File=f01
Subcritical Flow
K Sum by GR= 0
Std Step Tol= 0.01
Critical Tol= 0.01
Num of Std Step Trials= 20
Max Error Tol= 0.3
Flow Tol Ratio= 0.001
Split Flow NTrial= 30
Split Flow Tol= 0.02
Split Flow Ratio= 0.02
Log Output Level= 0
Friction Slope Method= 1
Unsteady Friction Slope Method= 2
Unsteady Bridges Friction Slope Method= 1
Parabolic Critical Depth
Global Vel Dist=  1 , 1 , 1
Global Log Level= 0
CheckData=True
Encroach Param= -1, 0, 0, 0
BEGIN DESCRIPTION:
Multiple Run
END DESCRIPTION:

--- UNT 1034 IN HEWA.f01 (steady flow) ---

Flow Title=Multiple
Number of Profiles=7
Profile Names=10-year,25-year,50-year,1pct_min,100-year,1pct_plu,500-year
River Rch & RM= UNT 1034 IN HEWA,Reach-1,9589
    1822    2723    3523    3322    4493    6076    7321
Boundary for River Rch & Prof#=UNT 1034 IN HEWA,Reach-1,1
Up Type=0
Dn Type=3
Dn Slope=0.005
Boundary for River Rch & Prof#=UNT 1034 IN HEWA,Reach-1,2
Up Type=0
Dn Type=3
Dn Slope=0.005
Boundary for River Rch & Prof#=UNT 1034 IN HEWA,Reach-1,3
Up Type=0
Dn Type=3
Dn Slope=0.005
Boundary for River Rch & Prof#=UNT 1034 IN HEWA,Reach-1,4
Up Type=0
Dn Type=3
Dn Slope=0.005
Boundary for River Rch & Prof#=UNT 1034 IN HEWA,Reach-1,5
Up Type=0
Dn Type=3
Dn Slope=0.005
Boundary for River Rch & Prof#=UNT 1034 IN HEWA,Reach-1,6
Up Type=0
Dn Type=3
Dn Slope=0.005
Boundary for River Rch & Prof#=UNT 1034 IN HEWA,Reach-1,7
Up Type=0
Dn Type=3
Dn Slope=0.005

--- UNT 1034 IN HEWA.g01 (geometry) ---

Geom Title=Existing Conditions

River Reach=UNT 1034 IN HEWA,Reach-1
Reach XY= 30
      2717318.47     10020803.73      2717173.87     10020785.51
      2716981.59     10020876.97      2716780.26     10021340.24
      2716391.25     10021759.02      2715888.06     10021754.64
      2715840.03     10021847.84      2715708.32     10021873.42
      2715642.62     10022026.91      2715783.31     10022008.55
      2715887.07     10022134.28      2715877.31     10022219.93
      2715398.58     10022564.26      2715184.92     10022957.08
      2714676.34     10023358.02      2714510.72     10024000.57
      2714045.71     10024138.20      2713843.28     10024260.89
      2713745.69     10024403.72      2713865.99     10024514.74
      2713924.28     10024706.22      2713581.06     10025094.80
      2713432.00     10025478.76      2713617.06     10025749.32
      2713665.58     10026122.46      2713513.81     10026323.00
      2713269.36     10026093.89      2713194.47     10026577.29
      2713014.52     10026647.75      2712938.47     10026813.73

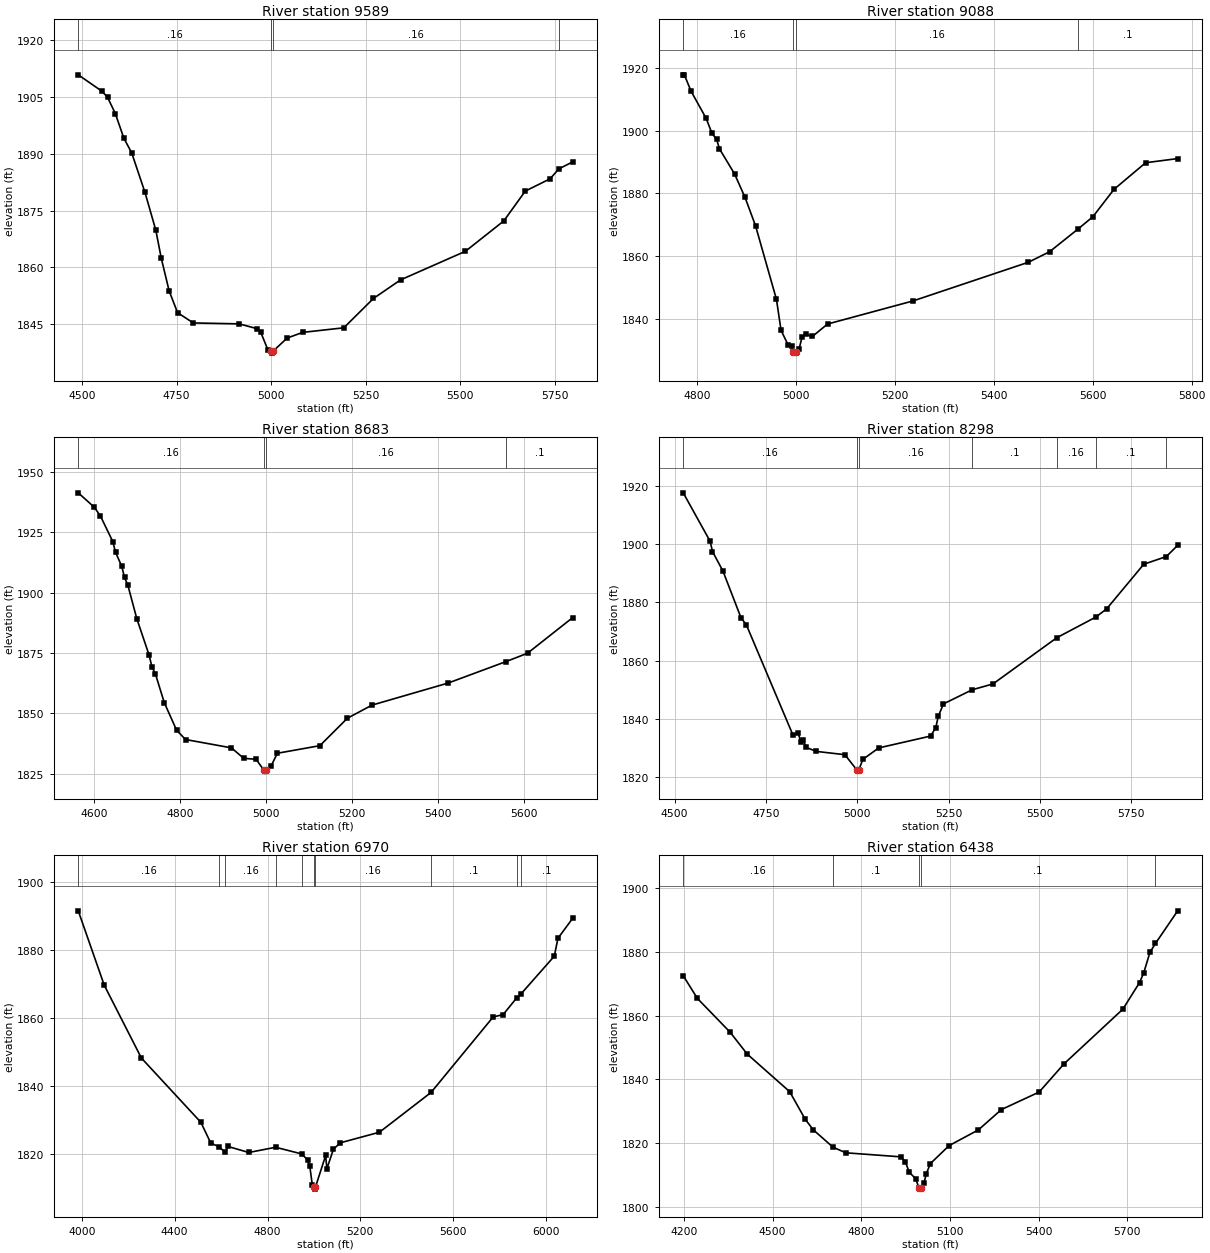
Type RM Length L Ch R = 1,9589,501,501,501
BEGIN DESCRIPTION:
UNT 1034 IN HEWA 16.0
END DESCRIPTION:
XS GIS Cut Line= 4
      2716913.07     10020430.24      2717246.41     10020701.08
      2717262.03     10021055.24      2717693.89     10021351.82
#Sta/Elev= 30
  4489.7 1910.90  4552.7 1906.54  4567.1 1904.98  4587.9 1900.62  4610.2 1894.18
  4631.0 1890.29  4666.2 1879.82  4694.9 1869.82  4709.3 1862.42  4730.1 1853.80
  4752.4 1848.05  4794.0 1845.35  4915.4 1845.10  4961.9 1843.85  4971.9 1843.01
  4991.9 1838.07  4998.9 1837.87  5001.7 1837.37  5004.9 1837.87  5042.0 1841.34
  5083.2 1842.85  5192.1 1844.06  5270.4 1851.81  5342.2 1856.72  5513.8 1864.28
  5615.3 1872.30  5672.1 1880.18  5737.8 1883.43  5760.7 1886.04  5797.6 1887.90
#Mann=4,-1,0
  4489.7    0.16       0  4998.9    0.07       0  5004.9    0.16       0
  5760.7     0.1       0
Bank Sta=4998.9,5004.9
Exp/Cntr=0.3,0.1

Type RM Length L Ch R = 1,9088,405,405,405
BEGIN DESCRIPTION:
UNT 1034 IN HEWA 15.0
END DESCRIPTION:
XS GIS Cut Line= 2
      2716699.55     10020940.67      2717543.25     10021477.10
#Sta/Elev= 30
  4772.0 1917.73  4774.3 1917.73  4787.8 1912.52  4818.1 1903.95  4830.1 1899.12
  4839.4 1897.21  4845.3 1894.17  4875.8 1886.19  4897.0 1878.70  4918.2 1869.70
  4960.5 1846.25  4969.8 1836.41  4984.0 1831.79  4991.0 1831.36  4993.9 1829.66
  4996.7 1829.16  4999.9 1829.66  5006.2 1830.45  5012.2 1834.23  5019.6 1835.13
  5033.3 1834.49  5063.8 1838.42  5236.6 1845.77  5469.9 1858.08  5512.6 1861.41
  5569.7 1868.58  5600.2 1872.55  5643.0 1881.28  5706.9 1889.75  5771.8 1891.08
#Mann=4,-1,0
  4772.0    0.16       0  4993.9    0.07       0  4999.9    0.16       0
  5569.7     0.1       0
Bank Sta=4993.9,4999.9
Exp/Cntr=0.3,0.1

Type RM Length L Ch R = 1,8683,385,385,385
BEGIN DESCRIPTION:
UNT 1034 IN HEWA 14.0
END DESCRIPTION:
XS GIS Cut Line= 2
      2716376.64     10021133.39      2717262.04     10021867.75
#Sta/Elev= 30
  4562.8 1941.35  4600.1 1935.38  4614.4 1931.74  4643.1 1921.16  4649.5 1916.73
  4663.9 1910.93  4670.4 1906.32  4678.2 1903.05  4699.0 1889.20  4727.7 1874.06
  4734.2 1869.22  4742.0 1866.49  4762.8 1854.47  4791.5 1843.03  4812.3 1839.15
  4919.1 1835.69  4947.8 1831.34  4976.4 1830.97  4994.2 1826.55  4997.0 1826.05
  5000.2 1826.55  5011.6 1828.23  5025.9 1833.45  5124.9 1836.60  5188.8 1847.95
  5246.0 1853.39  5423.1 1862.53  5558.3 1871.46  5608.0 1874.90  5713.1 1889.67
#Mann=4,-1,0
  4562.8    0.16       0  4994.2    0.07       0  5000.2    0.16       0
  5558.3     0.1       0
Bank Sta=4994.2,5000.2
Exp/Cntr=0.3,0.1

Type RM Length L Ch R = 1,8298,1328,1328,1328
BEGIN DESCRIPTION:
UNT 1034 IN HEWA 13.0
END DESCRIPTION:
XS GIS Cut Line= 3
      2716090.18     10021399.01      2716756.82     10021945.87
      2717017.24     10022362.54
#Sta/Elev= 30
  4523.6 1917.54  4597.3 1900.89  4603.7 1897.40  4632.4 1890.67  4681.9 1874.62
  4696.3 1872.27  4824.0 1834.41  4838.4 1835.18  4844.9 1832.17  4852.7 1832.88
  4859.2 1830.23  4887.9 1828.81  4966.1 1827.68  4998.3 1822.54  5001.0 1822.04
  5004.3 1822.54  5015.6 1826.10  5058.7 1830.00  5200.8 1834.07  5215.1 1837.00
  5221.6 1840.80  5236.0 1845.11  5314.4 1849.94  5371.6 1851.97  5546.5 1867.84
  5652.9 1874.89  5682.7 1877.72  5784.3 1893.03  5846.2 1895.68  5877.2 1899.53
#Mann=7,-1,0
  4523.6    0.16       0  4998.3    0.07       0  5004.3    0.16       0
  5314.4     0.1       0  5546.5    0.16       0  5652.9     0.1       0
  5846.2    0.16       0
Bank Sta=4998.3,5004.3
Exp/Cntr=0.3,0.1

Type RM Length L Ch R = 1,6970,532,532,532
BEGIN DESCRIPTION:
UNT 1034 IN HEWA 11.0
END DESCRIPTION:
XS GIS Cut Line= 4
      2714959.99     10021810.47      2715564.11     10022164.62
      2716105.78     10022081.28      2716871.38     10022518.77
#Sta/Elev= 30
  3984.7 1891.41  4096.5 1869.62  4256.7 1848.25  4512.7 1829.43  4555.7 1823.31
  4590.7 1822.28  4617.8 1820.59  4630.0 1822.33  4719.2 1820.57  4835.0 1822.10
  4947.7 1820.14  4972.7 1818.38  4982.2 1816.53  4992.9 1811.04  5000.0 1810.33
  5002.8 1809.83  5006.0 1810.33  5050.5 1819.70  5055.6 1815.77  5084.0 1821.54
  5113.8 1823.41  5282.2 1826.51  5504.8 1838.19  5771.9 1860.29  5815.1 1861.00
  5873.1 1865.86  5892.1 1867.06  6035.3 1878.11  6051.2 1883.37  6114.8 1889.24
#Mann=10,-1,0
  3984.7    0.16       0  4590.7     0.1       0  4617.8    0.16       0
  4835.0     0.1       0  4947.7    0.16       0  5000.0    0.07       0
  5006.0    0.16       0  5504.8     0.1       0  5873.1    0.16       0
  5892.1     0.1       0
Bank Sta=5000,5006
Exp/Cntr=0.3,0.1

Type RM Length L Ch R = 1,6438,442,442,442
BEGIN DESCRIPTION:
UNT 1034 IN HEWA 9.0
END DESCRIPTION:
XS GIS Cut Line= 3
      2714892.27     10022024.01      2715433.91     10022352.12
      2716137.05     10023117.77
#Sta/Elev= 30
  4197.8 1872.50  4245.7 1865.38  4356.3 1854.79  4414.4 1847.90  4558.0 1836.11
  4610.3 1827.47  4637.6 1824.16  4704.5 1818.68  4748.0 1816.93  4934.5 1815.66
  4948.7 1814.19  4962.9 1810.76  4983.8 1808.86  4995.0 1806.03  4997.8 1805.53
  5001.0 1806.03  5012.2 1807.39  5019.6 1810.22  5033.8 1813.54  5097.3 1819.19
  5196.5 1824.13  5274.2 1830.50  5401.8 1835.99  5486.3 1844.87  5684.9 1861.99
  5741.6 1870.35  5755.8 1873.44  5776.7 1879.84  5795.5 1882.65  5870.6 1892.87
#Mann=5,-1,0
  4197.8    0.16       0  4704.5     0.1       0  4995.0    0.07       0
  5001.0     0.1       0  5795.5    0.16       0
Bank Sta=4995,5001
Exp/Cntr=0.3,0.1

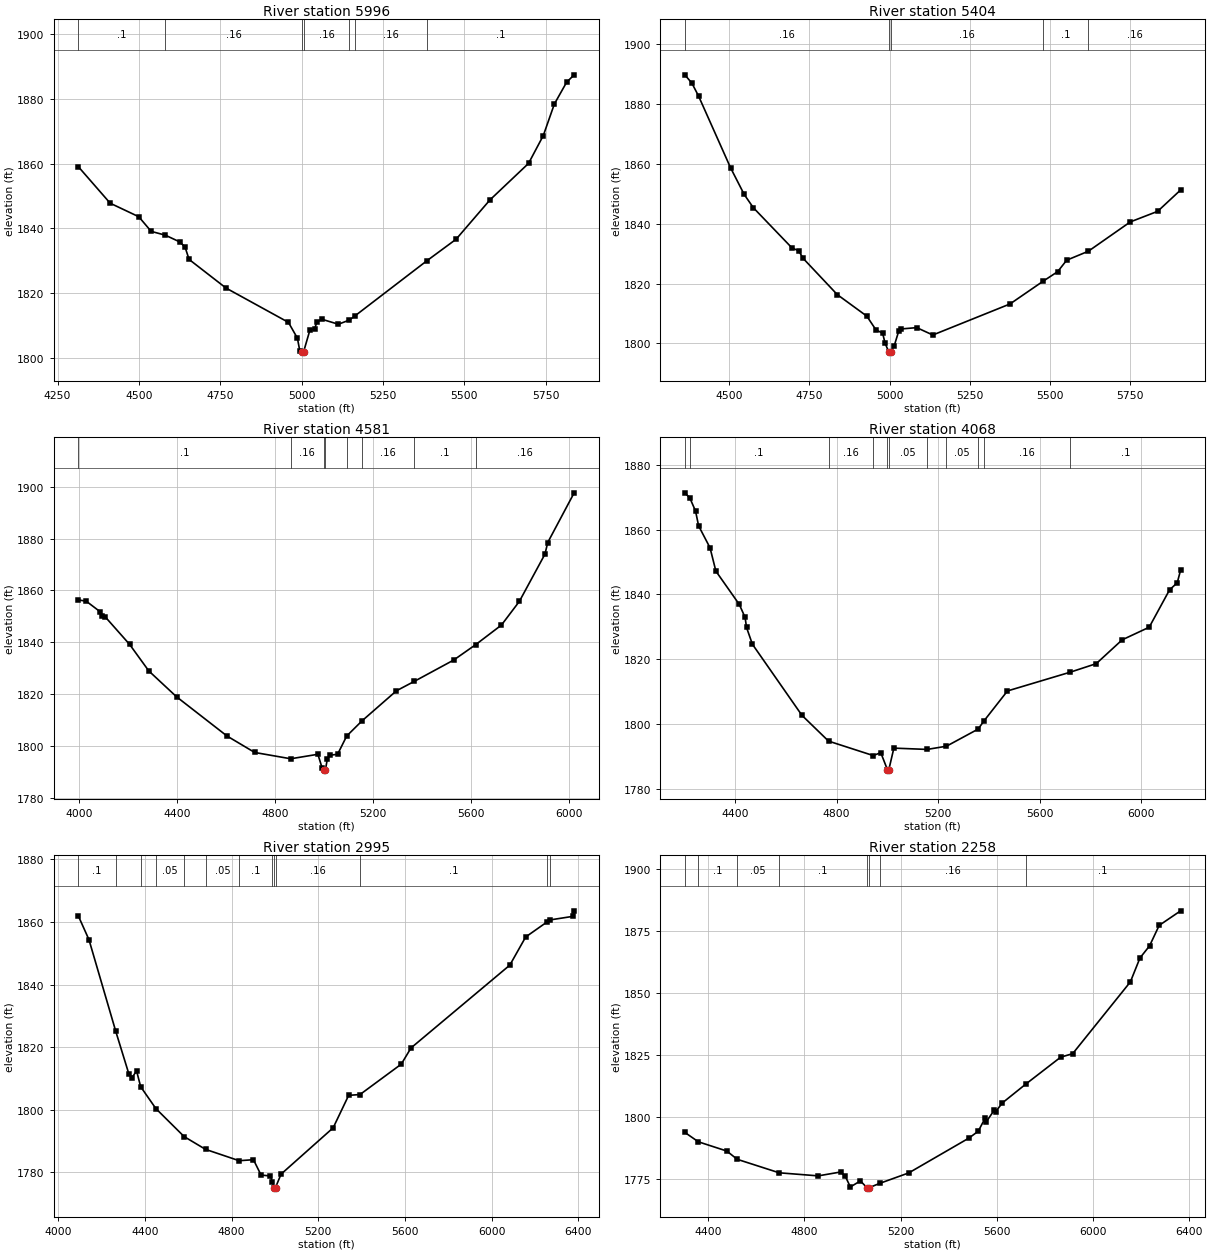
Type RM Length L Ch R = 1,5996,592,592,592
BEGIN DESCRIPTION:
UNT 1034 IN HEWA 8.0
END DESCRIPTION:
XS GIS Cut Line= 2
      2714668.30     10022471.92      2716012.05     10023190.67
#Sta/Elev= 30
  4313.9 1859.10  4411.8 1847.80  4499.6 1843.62  4537.8 1839.09  4581.3 1837.91
  4625.6 1835.83  4641.8 1834.25  4654.3 1830.41  4767.7 1821.56  4959.6 1810.94
  4987.2 1806.05  4994.5 1802.16  5000.5 1801.92  5003.3 1801.42  5006.5 1801.92
  5025.4 1808.47  5039.9 1808.93  5047.4 1811.09  5062.6 1811.89  5113.2 1810.36
  5146.7 1811.64  5163.6 1812.90  5384.7 1829.96  5474.9 1836.65  5578.9 1848.81
  5697.6 1860.12  5743.0 1868.74  5777.0 1878.50  5814.6 1885.22  5837.8 1887.52
#Mann=7,-1,0
  4313.9     0.1       0  4581.3    0.16       0  5000.5    0.07       0
  5006.5    0.16       0  5146.7     0.1       0  5163.6    0.16       0
  5384.7     0.1       0
Bank Sta=5000.5,5006.5
Exp/Cntr=0.3,0.1

Type RM Length L Ch R = 1,5404,823,823,823
BEGIN DESCRIPTION:
UNT 1034 IN HEWA 7.0
END DESCRIPTION:
XS GIS Cut Line= 2
      2714439.12     10022721.91      2715459.94     10023883.36
#Sta/Elev= 30
  4361.2 1889.66  4383.3 1886.89  4404.1 1882.58  4503.8 1858.66  4546.5 1849.72
  4574.9 1845.31  4695.4 1831.89  4716.3 1830.93  4730.5 1828.37  4836.8 1816.30
  4928.8 1809.12  4957.3 1804.54  4978.2 1803.42  4985.8 1800.07  4997.0 1797.27
  4999.7 1796.77  5003.0 1797.27  5014.2 1799.18  5028.5 1804.16  5035.1 1804.83
  5084.5 1805.28  5134.7 1802.82  5375.4 1813.18  5479.3 1820.82  5523.8 1823.94
  5552.2 1827.79  5619.7 1830.78  5750.6 1840.57  5835.9 1844.10  5907.5 1851.23
#Mann=5,-1,0
  4361.2    0.16       0  4997.0    0.07       0  5003.0    0.16       0
  5479.3     0.1       0  5619.7    0.16       0
Bank Sta=4997,5003
Exp/Cntr=0.3,0.1

Type RM Length L Ch R = 1,4581,513,513,513
BEGIN DESCRIPTION:
UNT 1034 IN HEWA 5.0
END DESCRIPTION:
XS GIS Cut Line= 3
      2713850.57     10023206.28      2714433.91     10023872.95
      2715522.47     10024201.08
#Sta/Elev= 30
  3998.2 1856.36  4030.5 1855.87  4087.4 1851.79  4094.1 1850.29  4108.3 1849.79
  4207.4 1839.22  4285.8 1828.99  4398.8 1819.05  4604.7 1803.93  4717.7 1797.59
  4864.7 1795.16  4975.5 1796.89  4993.3 1791.44  5000.3 1790.90  5003.0 1790.40
  5006.3 1790.90  5014.1 1795.13  5024.6 1796.53  5055.9 1796.89  5093.1 1803.93
  5155.8 1809.79  5296.1 1821.36  5368.0 1824.94  5529.5 1833.19  5619.3 1839.13
  5724.4 1846.68  5797.5 1855.81  5901.9 1874.00  5913.2 1878.48  6021.0 1897.62
#Mann=8,-1,0
  3998.2     0.1       0  4864.7    0.16       0  5000.3    0.07       0
  5006.3    0.16       0  5093.1     0.1       0  5155.8    0.16       0
  5368.0     0.1       0  5619.3    0.16       0
Bank Sta=5000.3,5006.3
Exp/Cntr=0.3,0.1

Type RM Length L Ch R = 1,4068,1073,1073,1073
BEGIN DESCRIPTION:
UNT 1034 IN HEWA 4.0
END DESCRIPTION:
XS GIS Cut Line= 3
      2713814.10     10023404.18      2714235.99     10024331.28
      2715114.83     10024653.70
#Sta/Elev= 30
  4201.5 1871.33  4221.2 1869.76  4243.9 1865.71  4255.9 1861.16  4301.0 1854.39
  4324.0 1847.20  4416.3 1836.94  4439.3 1832.91  4444.8 1829.86  4467.9 1824.68
  4663.3 1802.76  4768.2 1794.81  4944.3 1790.36  4974.1 1791.25  5000.0 1786.06
  5002.8 1785.56  5006.0 1786.06  5025.7 1792.65  5156.8 1792.25  5233.1 1793.24
  5357.7 1798.51  5381.7 1801.11  5473.5 1810.27  5720.8 1816.05  5823.5 1818.68
  5925.7 1826.02  6032.3 1829.91  6112.4 1841.40  6142.9 1843.62  6156.2 1847.54
#Mann=11,-1,0
  4201.5    0.16       0  4221.2     0.1       0  4768.2    0.16       0
  4944.3    0.05       0  5000.0   0.035       0  5006.0    0.05       0
  5156.8     0.1       0  5233.1    0.05       0  5357.7     0.1       0
  5381.7    0.16       0  5720.8     0.1       0
Bank Sta=5000,5006
Exp/Cntr=0.3,0.1

Type RM Length L Ch R = 1,2995,737,737,737
BEGIN DESCRIPTION:
UNT 1034 IN HEWA 3.0
END DESCRIPTION:
XS GIS Cut Line= 3
      2713100.58     10024253.17      2714105.78     10025102.12
      2714980.34     10025528.98
#Sta/Elev= 30
  4092.2 1861.91  4141.3 1854.32  4265.1 1825.01  4325.0 1811.54  4339.0 1810.13
  4361.0 1812.41  4380.0 1807.34  4450.1 1800.37  4580.7 1791.41  4679.6 1787.33
  4834.6 1783.71  4900.6 1784.03  4935.7 1779.13  4978.6 1778.83  4987.3 1777.01
  4996.4 1775.13  4999.2 1774.63  5002.4 1775.13  5028.0 1779.41  5268.6 1794.22
  5340.1 1804.59  5392.5 1804.85  5583.0 1814.56  5628.0 1819.74  6084.1 1846.19
  6157.3 1855.18  6257.4 1860.06  6267.4 1860.61  6377.0 1861.79  6381.1 1863.54
#Mann=13,-1,0
  4092.2     0.1       0  4265.1    0.05       0  4380.0     0.1       0
  4450.1    0.05       0  4580.7     0.1       0  4679.6    0.05       0
  4834.6     0.1       0  4987.3    0.16       0  4996.4    0.07       0
  5002.4    0.16       0  5392.5     0.1       0  6257.4    0.16       0
  6267.4     0.1       0
Bank Sta=4996.4,5002.4
Exp/Cntr=0.3,0.1

Type RM Length L Ch R = 1,2258,1654,1654,1654
BEGIN DESCRIPTION:
UNT 1034 IN HEWA 2.0
END DESCRIPTION:
XS GIS Cut Line= 4
      2713100.57     10024904.21      2713303.70     10025425.03
      2714038.07     10025638.58      2714777.63     10025633.37
#Sta/Elev= 30
  4302.2 1793.68  4358.8 1789.87  4477.0 1786.15  4520.2 1782.82  4694.9 1777.37
  4857.5 1776.13  4950.4 1777.69  4970.3 1775.93  4991.2 1771.65  5032.8 1774.10
  5061.1 1771.28  5063.8 1770.78  5067.1 1771.28  5114.0 1773.13  5234.3 1777.33
  5484.6 1791.38  5523.3 1794.14  5551.6 1799.34  5556.8 1797.97  5590.4 1802.70
  5595.6 1802.00  5623.6 1805.56  5721.3 1813.17  5866.4 1824.03  5916.4 1825.45
  6156.4 1854.40  6196.4 1864.07  6236.4 1868.96  6276.4 1877.22  6365.6 1883.09
#Mann=8,-1,0
  4302.2    0.05       0  4358.8     0.1       0  4520.2    0.05       0
  4694.9     0.1       0  5061.1    0.07       0  5067.1     0.1       0
  5114.0    0.16       0  5721.3     0.1       0
Bank Sta=5061.1,5067.1
Exp/Cntr=0.3,0.1

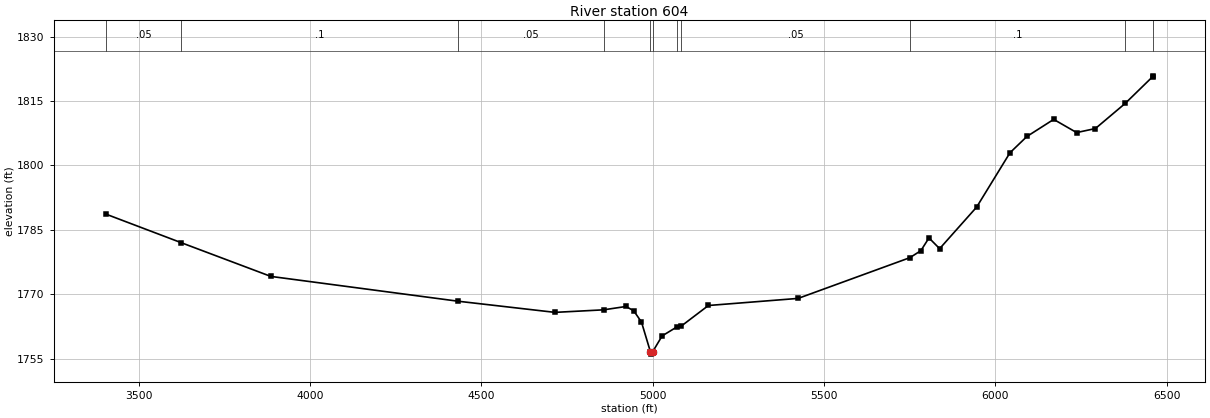
Type RM Length L Ch R = 1,604,0,0,0
BEGIN DESCRIPTION:
UNT 1034 IN HEWA 1.0
END DESCRIPTION:
XS GIS Cut Line= 4
      2713001.61     10024992.77      2712949.53     10026305.24
      2713631.82     10026487.53      2714599.31     10026118.23
#Sta/Elev= 30
  3404.8 1788.66  3623.9 1782.03  3886.1 1774.16  4432.9 1768.38  4715.0 1765.79
  4856.8 1766.38  4922.3 1767.16  4944.9 1766.15  4967.5 1763.53  4993.7 1756.57
  4996.4 1756.07  4999.7 1756.57  5027.7 1760.31  5072.2 1762.47  5083.6 1762.60
  5162.7 1767.39  5424.5 1769.04  5750.5 1778.52  5782.6 1780.15  5806.3 1783.12
  5837.4 1780.62  5945.4 1790.30  6042.6 1802.94  6092.0 1806.73  6170.2 1810.71
  6237.1 1807.64  6291.9 1808.58  6379.0 1814.44  6458.6 1820.63  6460.1 1820.85
#Mann=11,-1,0
  3404.8    0.05       0  3623.9     0.1       0  4432.9    0.05       0
  4856.8     0.1       0  4993.7    0.07       0  4999.7     0.1       0
  5072.2    0.16       0  5083.6    0.05       0  5750.5     0.1       0
  6379.0    0.16       0  6458.6     0.1       0
Bank Sta=4993.7,4999.7
Exp/Cntr=0.3,0.1

Chan Stop Cuts=-1