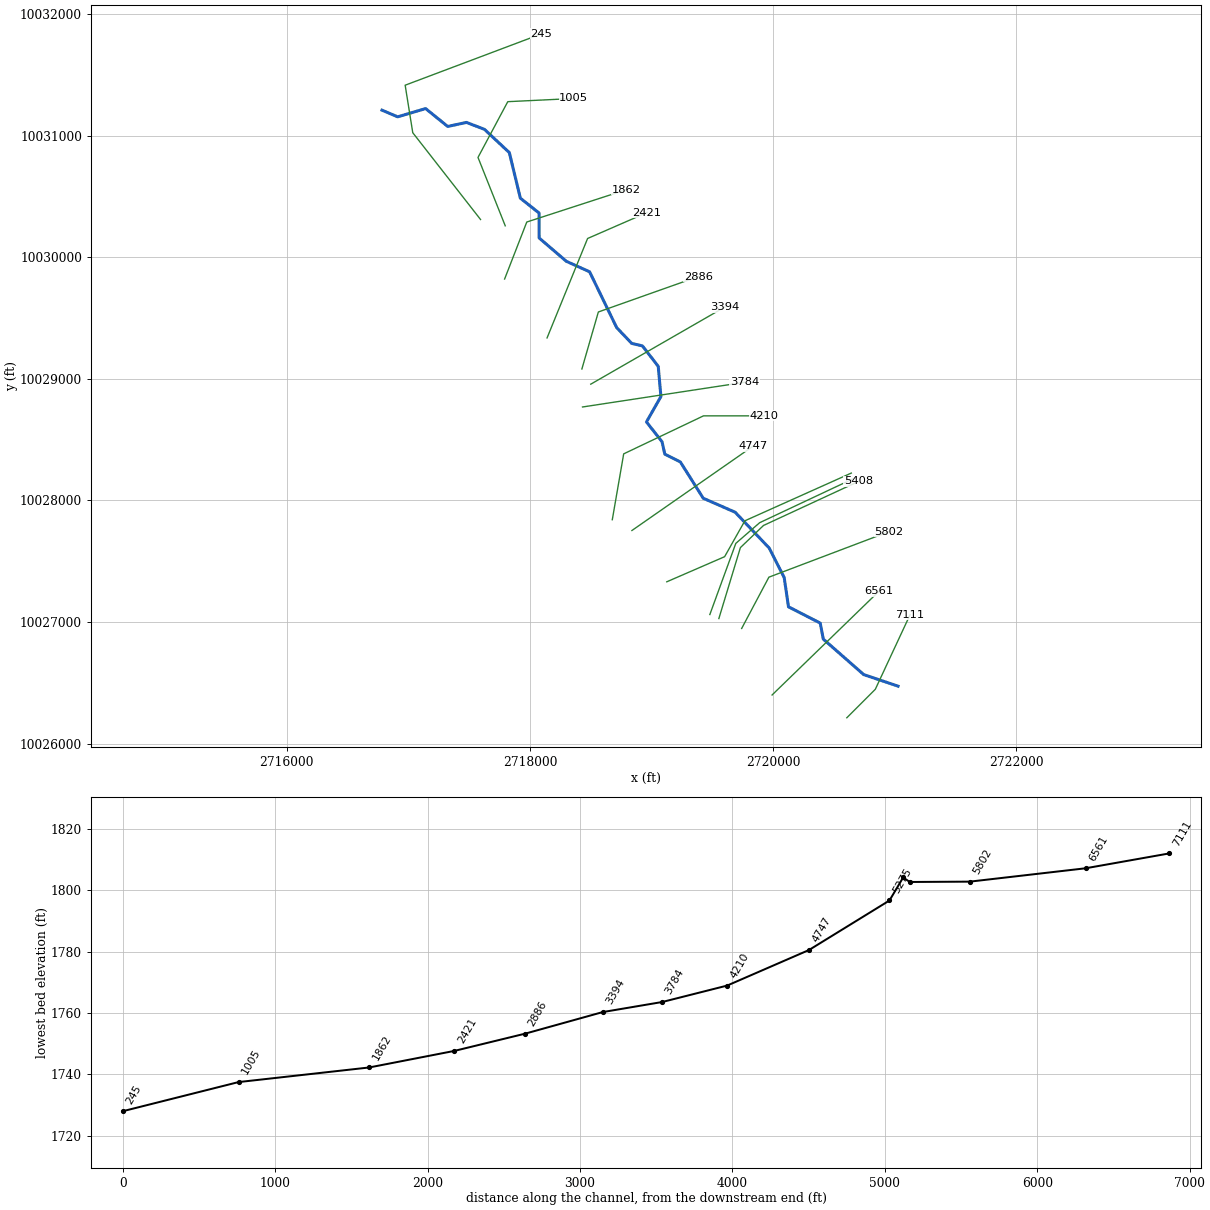
--- UNT 1035 IN HEWA.prj (project) ---

Proj Title=UNT 1035 IN HEWA Base Level Engineering
Current Plan=p01
Default Exp/Contr=0.3,0.1
English Units
Geom File=g01
Flow File=f01
Plan File=p01
BEGIN DESCRIPTION:
UNT 1035 IN HEWA
END DESCRIPTION:

--- UNT 1035 IN HEWA.p01 (plan) ---

Plan Title=Multiple Run
Short Identifier=Multiple
Geom File=g01
Flow File=f01
Subcritical Flow
K Sum by GR= 0
Std Step Tol= 0.01
Critical Tol= 0.01
Num of Std Step Trials= 20
Max Error Tol= 0.3
Flow Tol Ratio= 0.001
Split Flow NTrial= 30
Split Flow Tol= 0.02
Split Flow Ratio= 0.02
Log Output Level= 0
Friction Slope Method= 1
Unsteady Friction Slope Method= 2
Unsteady Bridges Friction Slope Method= 1
Parabolic Critical Depth
Global Vel Dist=  1 , 1 , 1
Global Log Level= 0
CheckData=True
Encroach Param= -1, 0, 0, 0
BEGIN DESCRIPTION:
Multiple Run
END DESCRIPTION:

--- UNT 1035 IN HEWA.f01 (steady flow) ---

Flow Title=Multiple
Number of Profiles=7
Profile Names=10-year,25-year,50-year,1pct_min,100-year,1pct_plu,500-year
River Rch & RM= UNT 1035 IN HEWA,Reach-1,7111
     966    1416    1809    1693    2290    3097    3682
River Rch & RM= UNT 1035 IN HEWA,Reach-1,5802
    1209    1784    2291    2150    2908    3933    4707
Boundary for River Rch & Prof#=UNT 1035 IN HEWA,Reach-1,1
Up Type=0
Dn Type=3
Dn Slope=0.005
Boundary for River Rch & Prof#=UNT 1035 IN HEWA,Reach-1,2
Up Type=0
Dn Type=3
Dn Slope=0.005
Boundary for River Rch & Prof#=UNT 1035 IN HEWA,Reach-1,3
Up Type=0
Dn Type=3
Dn Slope=0.005
Boundary for River Rch & Prof#=UNT 1035 IN HEWA,Reach-1,4
Up Type=0
Dn Type=3
Dn Slope=0.005
Boundary for River Rch & Prof#=UNT 1035 IN HEWA,Reach-1,5
Up Type=0
Dn Type=3
Dn Slope=0.005
Boundary for River Rch & Prof#=UNT 1035 IN HEWA,Reach-1,6
Up Type=0
Dn Type=3
Dn Slope=0.005
Boundary for River Rch & Prof#=UNT 1035 IN HEWA,Reach-1,7
Up Type=0
Dn Type=3
Dn Slope=0.005

--- UNT 1035 IN HEWA.g01 (geometry) ---

Geom Title=Existing Conditions

River Reach=UNT 1035 IN HEWA,Reach-1
Reach XY= 30
      2721026.96     10026472.34      2720744.80     10026567.65
      2720412.49     10026859.43      2720387.02     10026991.27
      2720126.27     10027124.81      2720090.90     10027365.60
      2719967.84     10027607.90      2719687.84     10027902.63
      2719425.32     10028017.55      2719237.08     10028316.08
      2719109.23     10028380.36      2719086.26     10028482.80
      2718958.42     10028644.96      2719077.27     10028853.76
      2719055.23     10029102.38      2718925.03     10029270.40
      2718837.28     10029290.72      2718713.34     10029420.95
      2718490.82     10029879.75      2718299.41     10029966.02
      2718076.23     10030157.54      2718075.84     10030362.60
      2717921.65     10030484.73      2717830.93     10030859.58
      2717627.09     10031050.42      2717478.38     10031107.86
      2717324.15     10031074.73      2717142.51     10031221.71
      2716912.83     10031153.90      2716783.59     10031208.70

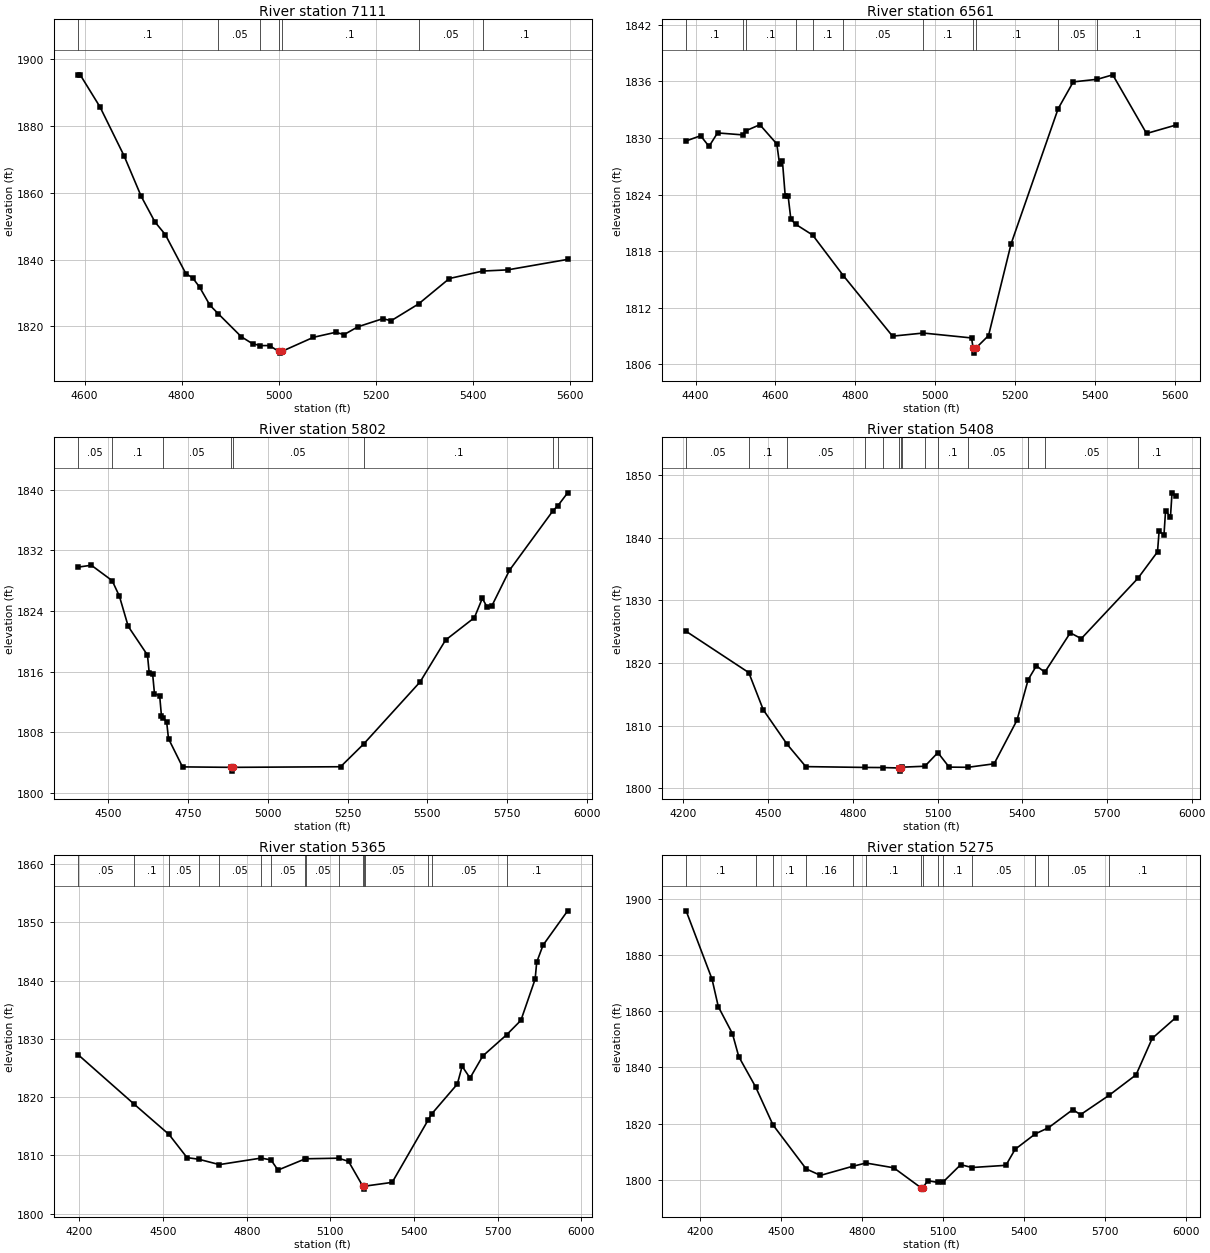
Type RM Length L Ch R = 1,7111,550,550,550
BEGIN DESCRIPTION:
UNT 1035 IN HEWA 15.0
END DESCRIPTION:
XS GIS Cut Line= 3
      2720605.80     10026212.38      2720840.16     10026446.74
      2721126.03     10027060.06
#Sta/Elev= 30
  4586.6 1895.21  4591.1 1895.21  4631.9 1885.60  4681.4 1871.01  4716.7 1858.89
  4745.0 1851.23  4766.2 1847.49  4808.6 1835.82  4822.8 1834.50  4836.9 1831.77
  4858.1 1826.37  4875.1 1823.84  4923.0 1816.91  4945.9 1814.85  4962.3 1814.29
  4980.9 1814.30  5000.0 1812.54  5002.7 1812.04  5006.0 1812.54  5071.3 1816.77
  5117.0 1818.26  5134.4 1817.58  5162.8 1819.91  5214.0 1822.33  5231.4 1821.73
  5287.7 1826.74  5351.2 1834.34  5420.0 1836.57  5471.1 1836.92  5594.7 1840.05
#Mann=7,-1,0
  4586.6     0.1       0  4875.1    0.05       0  4962.3     0.1       0
  5000.0    0.07       0  5006.0     0.1       0  5287.7    0.05       0
  5420.0     0.1       0
Bank Sta=5000,5006
Exp/Cntr=0.3,0.1

Type RM Length L Ch R = 1,6561,759,759,759
BEGIN DESCRIPTION:
UNT 1035 IN HEWA 14.0
END DESCRIPTION:
XS GIS Cut Line= 2
      2719991.16     10026399.83      2720871.42     10027254.05
#Sta/Elev= 30
  4376.1 1829.69  4412.4 1830.24  4433.5 1829.11  4454.8 1830.54  4518.4 1830.33
  4526.5 1830.78  4560.8 1831.41  4603.3 1829.37  4610.2 1827.23  4617.4 1827.54
  4624.4 1823.84  4631.6 1823.87  4638.5 1821.38  4650.3 1820.86  4693.1 1819.71
  4769.9 1815.41  4893.2 1808.99  4970.2 1809.32  5091.2 1808.80  5095.2 1807.69
  5097.9 1807.19  5101.2 1807.69  5133.7 1809.05  5190.3 1818.79  5308.0 1833.10
  5345.9 1835.95  5406.5 1836.23  5444.9 1836.70  5529.6 1830.48  5602.7 1831.37
#Mann=11,-1,0
  4376.1     0.1       0  4518.4    0.05       0  4526.5     0.1       0
  4650.3    0.05       0  4693.1     0.1       0  4769.9    0.05       0
  4970.2     0.1       0  5095.2    0.07       0  5101.2     0.1       0
  5308.0    0.05       0  5406.5     0.1       0
Bank Sta=5095.2,5101.2
Exp/Cntr=0.3,0.1

Type RM Length L Ch R = 1,5802,394,394,394
BEGIN DESCRIPTION:
UNT 1035 IN HEWA 13.0
END DESCRIPTION:
XS GIS Cut Line= 3
      2719741.22     10026946.78      2719965.16     10027368.61
      2720954.14     10027743.38
#Sta/Elev= 30
  4404.7 1829.80  4446.5 1830.05  4511.8 1828.01  4534.5 1825.95  4562.1 1821.97
  4622.4 1818.18  4628.1 1815.75  4638.7 1815.66  4644.4 1813.08  4660.7 1812.80
  4666.4 1810.09  4671.2 1809.92  4682.7 1809.30  4688.4 1807.13  4732.3 1803.40
  4883.9 1803.34  4886.7 1802.84  4889.9 1803.34  5228.0 1803.42  5300.0 1806.41
  5477.3 1814.63  5557.1 1820.16  5647.5 1823.12  5672.3 1825.67  5687.9 1824.49
  5702.5 1824.70  5757.4 1829.38  5894.4 1837.28  5909.1 1837.91  5939.9 1839.62
#Mann=8,-1,0
  4404.7    0.05       0  4511.8     0.1       0  4671.2    0.05       0
  4883.9    0.03       0  4889.9    0.05       0  5300.0     0.1       0
  5894.4    0.05       0  5909.1     0.1       0
Bank Sta=4883.9,4889.9
Exp/Cntr=0.3,0.1

Type RM Length L Ch R = 1,5408,43,43,43
BEGIN DESCRIPTION:
UNT 1035 IN HEWA 12.0
END DESCRIPTION:
XS GIS Cut Line= 4
      2719553.70     10027028.25      2719730.78     10027611.58
      2719920.88     10027793.87      2720702.11     10028155.84
#Sta/Elev= 30
  4209.7 1825.04  4431.6 1818.45  4483.1 1812.50  4567.6 1807.00  4633.5 1803.45
  4843.2 1803.32  4906.3 1803.30  4964.9 1803.23  4967.6 1802.73  4970.9 1803.23
  4974.4 1803.36  5055.2 1803.51  5101.3 1805.68  5141.2 1803.37  5207.9 1803.34
  5300.5 1803.90  5381.4 1810.85  5421.0 1817.32  5450.2 1819.54  5480.0 1818.52
  5570.2 1824.80  5609.1 1823.87  5809.7 1833.50  5879.1 1837.72  5884.7 1840.99
  5902.1 1840.47  5907.6 1844.26  5925.0 1843.30  5930.5 1847.14  5943.7 1846.60
#Mann=14,-1,0
  4209.7    0.05       0  4431.6     0.1       0  4567.6    0.05       0
  4843.2     0.1       0  4906.3    0.05       0  4964.9    0.07       0
  4970.9    0.05       0  4974.4     0.1       0  5055.2    0.05       0
  5101.3     0.1       0  5207.9    0.05       0  5421.0     0.1       0
  5480.0    0.05       0  5809.7     0.1       0
Bank Sta=4964.9,4970.9
Exp/Cntr=0.3,0.1

Type RM Length L Ch R = 1,5365,90,90,90
BEGIN DESCRIPTION:
UNT 1035 IN HEWA 11.0
END DESCRIPTION:
XS GIS Cut Line= 4
      2719479.56     10027061.38      2719693.11     10027646.48
      2719889.29     10027816.61      2720679.25     10028188.16
#Sta/Elev= 30
  4195.0 1827.30  4397.3 1818.75  4521.3 1813.59  4585.8 1809.62  4627.7 1809.34
  4701.8 1808.42  4851.5 1809.54  4886.9 1809.22  4911.9 1807.48  5009.6 1809.41
  5012.7 1809.42  5129.3 1809.52  5165.0 1808.97  5216.1 1804.71  5218.9 1804.21
  5222.1 1804.71  5222.8 1804.72  5321.4 1805.37  5449.8 1816.03  5462.4 1817.08
  5554.9 1822.24  5572.2 1825.30  5600.5 1823.28  5646.1 1827.06  5732.1 1830.72
  5782.9 1833.18  5834.0 1840.26  5839.5 1843.15  5862.3 1846.09  5950.5 1851.98
#Mann=16,-1,0
  4195.0    0.05       0  4397.3     0.1       0  4521.3    0.05       0
  4627.7    0.16       0  4701.8    0.05       0  4851.5     0.1       0
  4886.9    0.05       0  5009.6     0.1       0  5012.7    0.05       0
  5129.3     0.1       0  5216.1    0.03       0  5222.1     0.1       0
  5222.8    0.05       0  5449.8     0.1       0  5462.4    0.05       0
  5732.1     0.1       0
Bank Sta=5216.1,5222.1
Exp/Cntr=0.3,0.1

Type RM Length L Ch R = 1,5275,528,528,528
BEGIN DESCRIPTION:
UNT 1035 IN HEWA 10.0
END DESCRIPTION:
XS GIS Cut Line= 4
      2719125.39     10027330.50      2719601.09     10027537.10
      2719767.76     10027832.24      2720642.74     10028224.59
#Sta/Elev= 30
  4147.0 1895.74  4243.0 1871.47  4266.5 1861.61  4318.8 1852.04  4342.3 1843.85
  4404.9 1833.06  4469.2 1819.56  4592.3 1803.90  4645.5 1801.59  4764.3 1804.81
  4814.4 1805.99  4917.3 1804.29  5018.1 1797.20  5020.9 1796.70  5024.1 1797.20
  5044.3 1799.69  5079.8 1799.11  5099.8 1799.18  5165.7 1805.40  5207.6 1804.39
  5333.4 1805.17  5367.5 1810.87  5442.7 1816.38  5491.2 1818.54  5581.6 1825.00
  5610.3 1823.20  5716.1 1830.09  5816.3 1837.38  5876.2 1850.35  5963.5 1857.72
#Mann=14,-1,0
  4147.0     0.1       0  4404.9    0.05       0  4469.2     0.1       0
  4592.3    0.16       0  4764.3    0.05       0  4814.4     0.1       0
  5018.1    0.07       0  5024.1     0.1       0  5079.8    0.05       0
  5099.8     0.1       0  5207.6    0.05       0  5442.7     0.1       0
  5491.2    0.05       0  5716.1     0.1       0
Bank Sta=5018.1,5024.1
Exp/Cntr=0.3,0.1

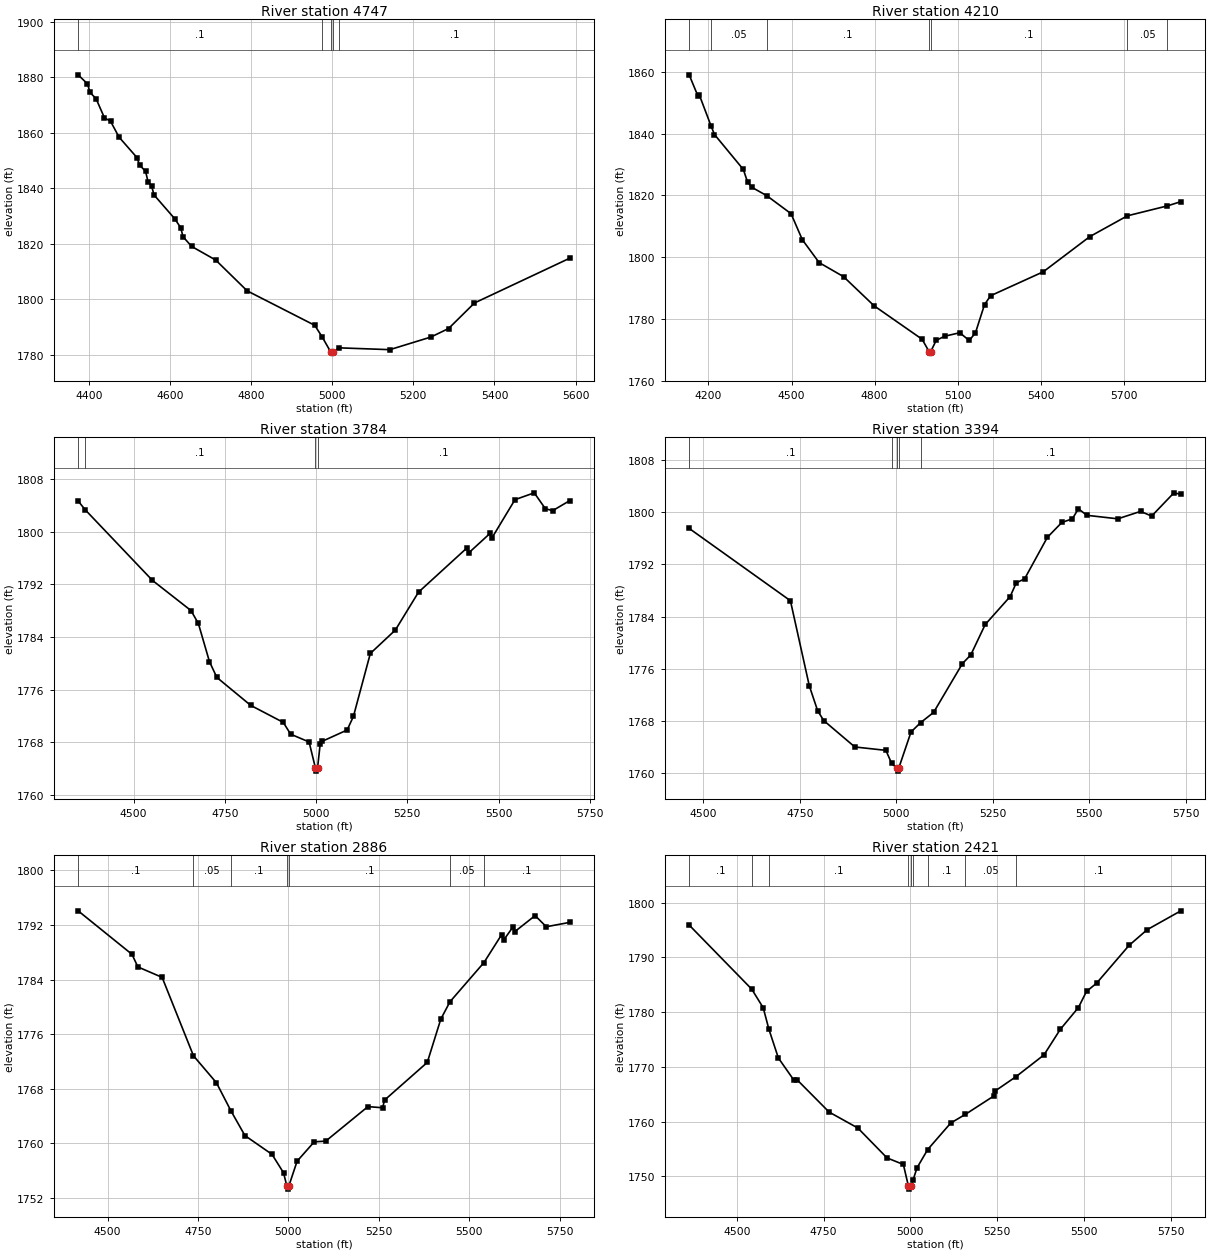
Type RM Length L Ch R = 1,4747,537,537,537
BEGIN DESCRIPTION:
UNT 1035 IN HEWA 9.0
END DESCRIPTION:
XS GIS Cut Line= 2
      2718838.95     10027752.39      2719833.57     10028444.98
#Sta/Elev= 30
  4373.6 1880.92  4396.7 1877.66  4402.8 1874.55  4417.7 1872.36  4438.6 1865.38
  4453.5 1864.19  4474.4 1858.46  4518.9 1851.03  4525.0 1848.39  4539.9 1846.12
  4545.9 1842.38  4554.7 1840.81  4560.8 1837.59  4611.4 1829.08  4626.3 1825.84
  4632.3 1822.52  4653.3 1819.05  4712.7 1814.13  4790.3 1803.02  4957.0 1790.58
  4975.6 1786.30  4995.9 1781.06  4998.6 1780.56  5001.9 1781.06  5017.9 1782.46
  5142.0 1781.81  5243.2 1786.36  5286.9 1789.44  5350.6 1798.64  5585.6 1814.80
#Mann=5,-1,0
  4373.6     0.1       0  4975.6    0.16       0  4995.9    0.07       0
  5001.9    0.16       0  5017.9     0.1       0
Bank Sta=4995.9,5001.9
Exp/Cntr=0.3,0.1

Type RM Length L Ch R = 1,4210,426,426,426
BEGIN DESCRIPTION:
UNT 1035 IN HEWA 8.0
END DESCRIPTION:
XS GIS Cut Line= 4
      2718677.49     10027840.97      2718771.23     10028382.59
      2719427.48     10028695.09      2719927.46     10028695.09
#Sta/Elev= 30
  4130.2 1858.98  4161.8 1852.12  4166.9 1852.47  4209.4 1842.41  4221.6 1839.68
  4325.8 1828.38  4341.1 1824.33  4356.3 1822.62  4410.6 1819.89  4498.4 1814.06
  4539.0 1805.66  4599.8 1798.25  4687.9 1793.71  4798.6 1784.26  4971.8 1773.46
  4997.0 1769.47  4999.8 1768.97  5003.0 1769.47  5022.7 1773.10  5053.4 1774.44
  5108.0 1775.56  5142.0 1773.06  5164.5 1775.50  5197.4 1784.69  5219.5 1787.54
  5409.7 1795.28  5577.7 1806.65  5713.5 1813.38  5858.5 1816.60  5906.7 1817.96
#Mann=7,-1,0
  4130.2     0.1       0  4209.4    0.05       0  4410.6     0.1       0
  4997.0    0.07       0  5003.0     0.1       0  5713.5    0.05       0
  5858.5     0.1       0
Bank Sta=4997,5003
Exp/Cntr=0.3,0.1

Type RM Length L Ch R = 1,3784,390,390,390
BEGIN DESCRIPTION:
UNT 1035 IN HEWA 7.0
END DESCRIPTION:
XS GIS Cut Line= 2
      2718432.68     10028768.00      2719764.71     10028970.93
#Sta/Elev= 30
  4347.8 1804.69  4366.9 1803.37  4551.4 1792.62  4657.1 1788.03  4677.3 1786.07
  4707.7 1780.27  4727.9 1777.87  4820.7 1773.62  4910.0 1771.03  4930.2 1769.24
  4980.8 1768.05  4998.0 1764.12  5000.8 1763.62  5004.0 1764.12  5011.1 1767.70
  5016.2 1768.14  5085.0 1769.87  5102.2 1771.93  5148.6 1781.51  5217.2 1785.07
  5280.7 1790.83  5412.9 1797.53  5417.9 1796.78  5476.4 1799.75  5481.5 1799.04
  5545.0 1804.89  5597.8 1805.93  5628.2 1803.52  5648.4 1803.22  5695.2 1804.75
#Mann=4,-1,0
  4347.8    0.05       0  4366.9     0.1       0  4998.0    0.07       0
  5004.0     0.1       0
Bank Sta=4998,5004
Exp/Cntr=0.3,0.1

Type RM Length L Ch R = 1,3394,508,508,508
BEGIN DESCRIPTION:
UNT 1035 IN HEWA 6.0
END DESCRIPTION:
XS GIS Cut Line= 2
      2718500.41     10028955.51      2719604.02     10029590.61
#Sta/Elev= 30
  4463.4 1797.50  4725.6 1786.43  4774.5 1773.40  4796.1 1769.59  4811.9 1768.08
  4892.4 1764.04  4972.8 1763.52  4987.9 1761.51  5000.4 1760.84  5003.2 1760.34
  5006.4 1760.84  5038.0 1766.34  5062.9 1767.77  5096.4 1769.33  5171.1 1776.81
  5192.7 1778.13  5230.1 1782.79  5294.7 1787.07  5310.5 1789.17  5332.1 1789.78
  5391.0 1796.13  5428.4 1798.41  5455.7 1798.97  5471.5 1800.51  5493.1 1799.51
  5573.5 1798.97  5632.5 1800.11  5661.1 1799.39  5718.8 1802.95  5736.7 1802.72
#Mann=5,-1,0
  4463.4     0.1       0  4987.9    0.16       0  5000.4    0.07       0
  5006.4    0.16       0  5062.9     0.1       0
Bank Sta=5000.4,5006.4
Exp/Cntr=0.3,0.1

Type RM Length L Ch R = 1,2886,465,465,465
BEGIN DESCRIPTION:
UNT 1035 IN HEWA 5.0
END DESCRIPTION:
XS GIS Cut Line= 3
      2718427.49     10029080.54      2718562.90     10029549.25
      2719384.63     10029840.50
#Sta/Elev= 30
  4418.6 1794.06  4567.6 1787.69  4583.8 1785.85  4650.9 1784.32  4737.6 1772.84
  4801.1 1768.89  4841.3 1764.77  4879.9 1761.16  4954.8 1758.41  4986.7 1755.71
  4995.6 1753.82  4998.4 1753.32  5001.6 1753.82  5024.2 1757.41  5071.5 1760.24
  5103.4 1760.35  5220.1 1765.40  5260.7 1765.23  5266.0 1766.35  5384.2 1771.87
  5421.6 1778.21  5447.0 1780.75  5541.0 1786.49  5589.7 1790.56  5595.1 1789.76
  5620.6 1791.65  5625.9 1791.00  5682.4 1793.36  5713.3 1791.73  5778.3 1792.37
#Mann=7,-1,0
  4418.6     0.1       0  4737.6    0.05       0  4841.3     0.1       0
  4995.6    0.07       0  5001.6     0.1       0  5447.0    0.05       0
  5541.0     0.1       0
Bank Sta=4995.6,5001.6
Exp/Cntr=0.3,0.1

Type RM Length L Ch R = 1,2421,559,559,559
BEGIN DESCRIPTION:
UNT 1035 IN HEWA 4.0
END DESCRIPTION:
XS GIS Cut Line= 3
      2718141.04     10029335.74      2718474.36     10030153.42
      2718963.73     10030366.87
#Sta/Elev= 30
  4362.4 1795.90  4542.7 1784.20  4575.8 1780.80  4592.2 1776.87  4619.4 1771.64
  4664.1 1767.59  4673.4 1767.65  4765.7 1761.76  4848.6 1758.84  4932.6 1753.39
  4979.7 1752.19  4994.4 1748.19  4997.1 1747.69  5000.4 1748.19  5007.3 1749.28
  5019.0 1751.58  5049.8 1754.92  5116.2 1759.76  5157.9 1761.32  5241.7 1764.75
  5244.2 1765.61  5304.2 1768.22  5385.0 1772.20  5431.8 1776.85  5484.1 1780.84
  5507.5 1783.79  5536.4 1785.28  5630.1 1792.19  5682.4 1795.06  5779.3 1798.50
#Mann=9,-1,0
  4362.4     0.1       0  4542.7    0.05       0  4592.2     0.1       0
  4994.4    0.07       0  5000.4     0.1       0  5007.3    0.05       0
  5049.8     0.1       0  5157.9    0.05       0  5304.2     0.1       0
Bank Sta=4994.4,5000.4
Exp/Cntr=0.3,0.1

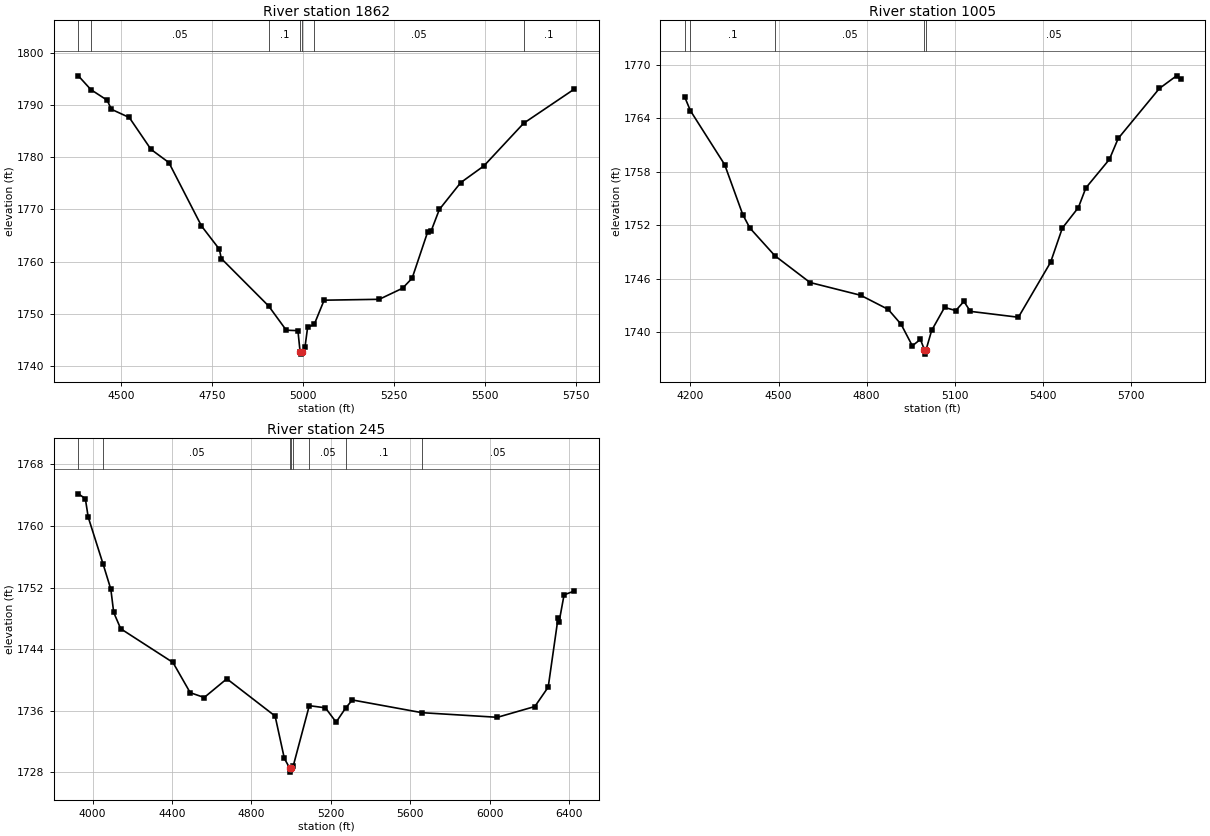
Type RM Length L Ch R = 1,1862,857,857,857
BEGIN DESCRIPTION:
UNT 1035 IN HEWA 3.0
END DESCRIPTION:
XS GIS Cut Line= 3
      2717792.06     10029820.06      2717974.36     10030288.84
      2718792.02     10030554.45
#Sta/Elev= 30
  4382.6 1795.59  4417.2 1792.94  4461.6 1790.93  4473.5 1789.18  4522.6 1787.61
  4582.3 1781.50  4631.4 1778.98  4721.0 1766.84  4770.1 1762.39  4775.5 1760.60
  4905.7 1751.50  4954.1 1746.87  4986.1 1746.79  4992.0 1742.79  4994.8 1742.29
  4998.0 1742.79  5005.6 1743.68  5012.8 1747.44  5030.9 1747.97  5058.1 1752.62
  5209.7 1752.79  5273.7 1754.91  5300.0 1756.83  5342.8 1765.72  5352.5 1765.92
  5374.8 1770.00  5433.4 1775.13  5497.3 1778.34  5606.6 1786.51  5745.3 1793.03
#Mann=7,-1,0
  4382.6     0.1       0  4417.2    0.05       0  4905.7     0.1       0
  4992.0    0.07       0  4998.0     0.1       0  5030.9    0.05       0
  5606.6     0.1       0
Bank Sta=4992,4998
Exp/Cntr=0.3,0.1

Type RM Length L Ch R = 1,1005,760,760,760
BEGIN DESCRIPTION:
UNT 1035 IN HEWA 2.0
END DESCRIPTION:
XS GIS Cut Line= 6
      2717797.28     10030257.57      2717573.32     10030820.09
      2717818.11     10031278.42      2718359.77     10031304.46
      2718370.19     10031304.46      2718360.69     10031309.21
#Sta/Elev= 30
  4180.9 1766.37  4199.9 1764.86  4316.7 1758.80  4378.2 1753.20  4402.4 1751.69
  4487.8 1748.57  4607.3 1745.57  4779.5 1744.14  4873.6 1742.55  4917.5 1740.88
  4955.7 1738.46  4983.3 1739.19  4996.6 1738.03  4999.3 1737.53  5002.6 1738.03
  5021.5 1740.19  5065.4 1742.77  5103.7 1742.42  5131.3 1743.45  5153.3 1742.33
  5316.9 1741.67  5426.5 1747.84  5466.5 1751.68  5521.1 1753.98  5546.6 1756.19
  5626.7 1759.39  5656.7 1761.74  5796.9 1767.35  5855.3 1768.77  5869.3 1768.38
#Mann=5,-1,0
  4180.9    0.05       0  4199.9     0.1       0  4487.8    0.05       0
  4996.6   0.035       0  5002.6    0.05       0
Bank Sta=4996.6,5002.6
Exp/Cntr=0.3,0.1

Type RM Length L Ch R = 1,245,0,0,0
BEGIN DESCRIPTION:
UNT 1035 IN HEWA 1.0
END DESCRIPTION:
XS GIS Cut Line= 4
      2717594.15     10030309.66      2717036.86     10031023.21
      2716974.36     10031413.84      2718093.77     10031835.57
#Sta/Elev= 30
  3928.1 1764.17  3963.3 1763.55  3977.8 1761.15  4052.9 1755.04  4091.8 1751.78
  4106.2 1748.77  4141.5 1746.65  4404.7 1742.27  4491.5 1738.35  4562.1 1737.72
  4676.0 1740.15  4919.2 1735.31  4965.7 1729.81  4993.1 1728.53  4995.8 1728.03
  4999.1 1728.53  5010.1 1728.79  5091.3 1736.66  5172.4 1736.38  5226.5 1734.52
  5274.5 1736.36  5308.3 1737.40  5658.4 1735.75  6038.7 1735.15  6227.3 1736.55
  6294.6 1739.07  6344.3 1748.06  6349.7 1747.58  6374.5 1751.05  6425.3 1751.54
#Mann=8,-1,0
  3928.1     0.1       0  4052.9    0.05       0  4993.1   0.033       0
  4999.1    0.05       0  5010.1     0.1       0  5091.3    0.05       0
  5274.5     0.1       0  5658.4    0.05       0
Bank Sta=4993.1,4999.1
Exp/Cntr=0.3,0.1

Chan Stop Cuts=-1