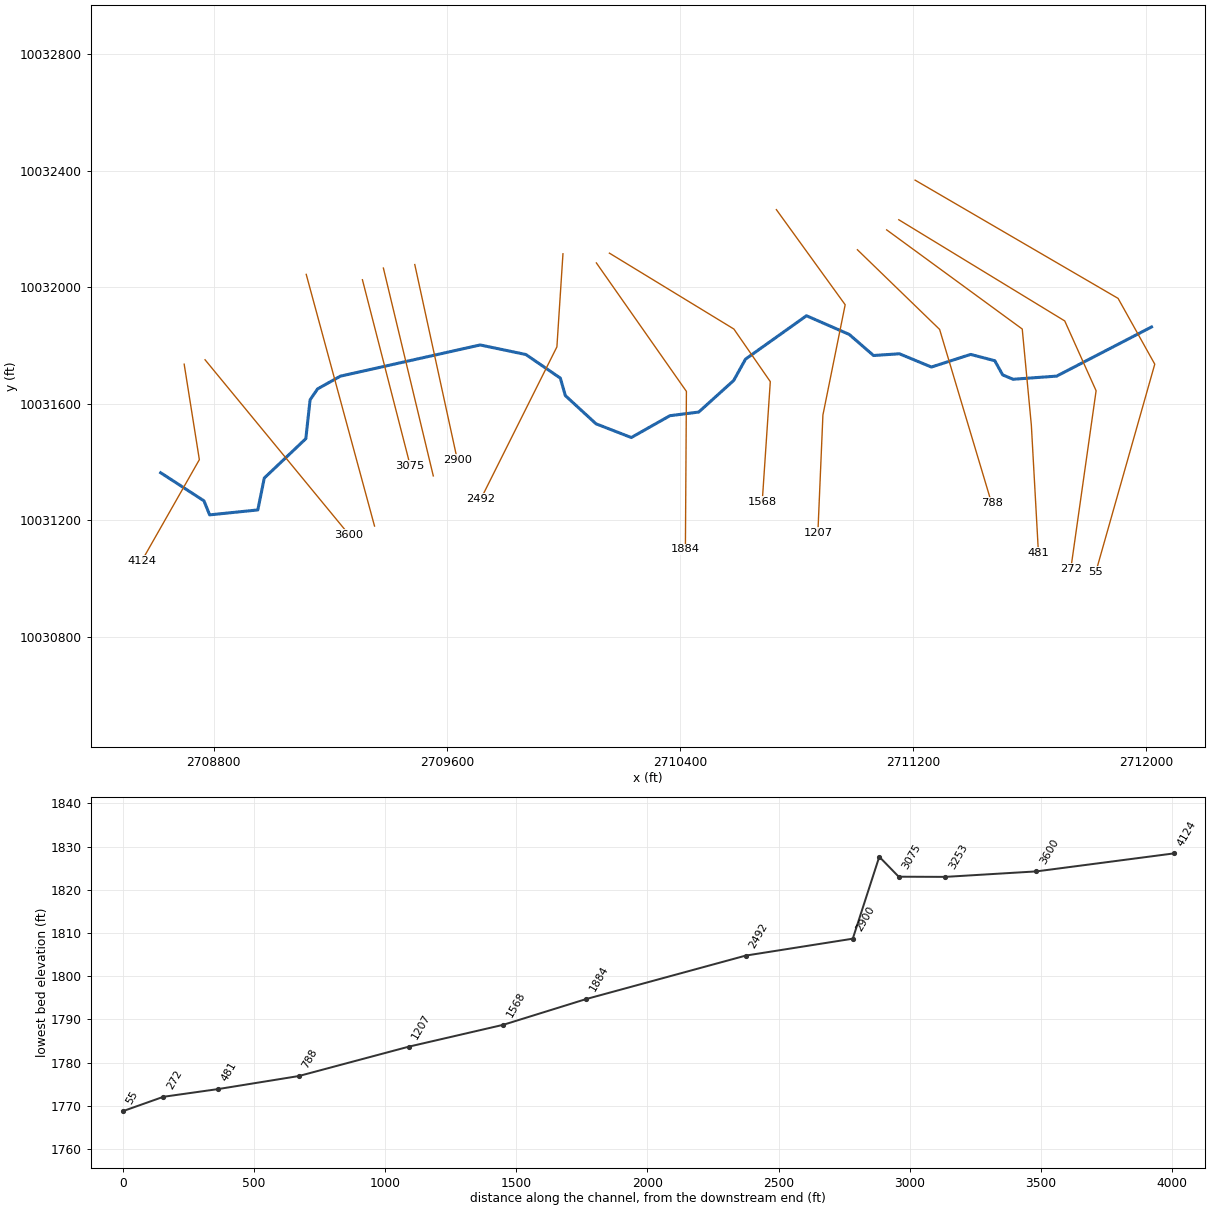
--- UNT 1037 IN HEWA.prj (project) ---

Proj Title=UNT 1037 IN HEWA Base Level Engineering
Current Plan=p01
Default Exp/Contr=0.3,0.1
English Units
Geom File=g01
Flow File=f01
Plan File=p01
Y Axis Title=Elevation
X Axis Title(PF)=Main Channel Distance
X Axis Title(XS)=Station
BEGIN DESCRIPTION:
UNT 1037 IN HEWA
END DESCRIPTION:
DSS Export Rating Curves= 0
DSS Export Rating Curve Sorted= 0
DSS Export Volume Flow Curves= 0
DXF OffsetX= 0
DXF OffsetY= 0
DXF ScaleX= 1
DXF ScaleY= 10

--- UNT 1037 IN HEWA.p01 (plan) ---

Plan Title=Multiple Run
Short Identifier=Multiple
Geom File=g01
Flow File=f01
Subcritical Flow
K Sum by GR= 0
Std Step Tol= 0.01
Critical Tol= 0.01
Num of Std Step Trials= 20
Max Error Tol= 0.3
Flow Tol Ratio= 0.001
Split Flow NTrial= 30
Split Flow Tol= 0.02
Split Flow Ratio= 0.02
Log Output Level= 0
Friction Slope Method= 1
Unsteady Friction Slope Method= 2
Unsteady Bridges Friction Slope Method= 1
Parabolic Critical Depth
Global Vel Dist=  1 , 1 , 1
Global Log Level= 0
CheckData=True
Encroach Param= -1, 0, 0, 0
BEGIN DESCRIPTION:
Multiple Run
END DESCRIPTION:

--- UNT 1037 IN HEWA.f01 (steady flow) ---

Flow Title=Multiple
Number of Profiles=7
Profile Names=10-year,25-year,50-year,1pct_min,100-year,1pct_plu,500-year
River Rch & RM= UNT 1037 IN HEWA,Reach-1,4124
    1351    1985    2539    2368    3202    4331    5089
Boundary for River Rch & Prof#=UNT 1037 IN HEWA,Reach-1,1
Up Type=0
Dn Type=3
Dn Slope=0.005
Boundary for River Rch & Prof#=UNT 1037 IN HEWA,Reach-1,2
Up Type=0
Dn Type=3
Dn Slope=0.005
Boundary for River Rch & Prof#=UNT 1037 IN HEWA,Reach-1,3
Up Type=0
Dn Type=3
Dn Slope=0.005
Boundary for River Rch & Prof#=UNT 1037 IN HEWA,Reach-1,4
Up Type=0
Dn Type=3
Dn Slope=0.005
Boundary for River Rch & Prof#=UNT 1037 IN HEWA,Reach-1,5
Up Type=0
Dn Type=3
Dn Slope=0.005
Boundary for River Rch & Prof#=UNT 1037 IN HEWA,Reach-1,6
Up Type=0
Dn Type=3
Dn Slope=0.005
Boundary for River Rch & Prof#=UNT 1037 IN HEWA,Reach-1,7
Up Type=0
Dn Type=3
Dn Slope=0.005

--- UNT 1037 IN HEWA.g01 (geometry) ---

Geom Title=Existing Conditions
Program Version=4.10

River Reach=UNT 1037 IN HEWA,Reach-1
Reach XY= 30
      2708618.17     10031363.38      2708766.61     10031267.03
      2708786.14     10031218.85       2708951.5     10031235.78
      2708973.64     10031345.16      2709116.26     10031480.31
      2709130.84     10031613.64      2709156.54     10031651.14
      2709235.05      10031694.9      2709714.36     10031801.91
      2709871.29     10031769.17      2709989.63     10031688.15
      2710006.87      10031628.1      2710112.05     10031531.33
      2710233.19     10031484.27      2710365.65     10031559.15
       2710464.6      10031571.7      2710584.44     10031679.99
      2710625.05     10031753.17      2710834.23     10031902.17
      2710981.05     10031838.09       2711064.4     10031765.74
      2711153.14     10031771.68      2711262.99     10031726.19
      2711397.63     10031769.47      2711480.57     10031747.84
      2711507.47     10031699.21      2711543.29     10031684.22
      2711692.84       10031695.      2712018.47     10031863.73

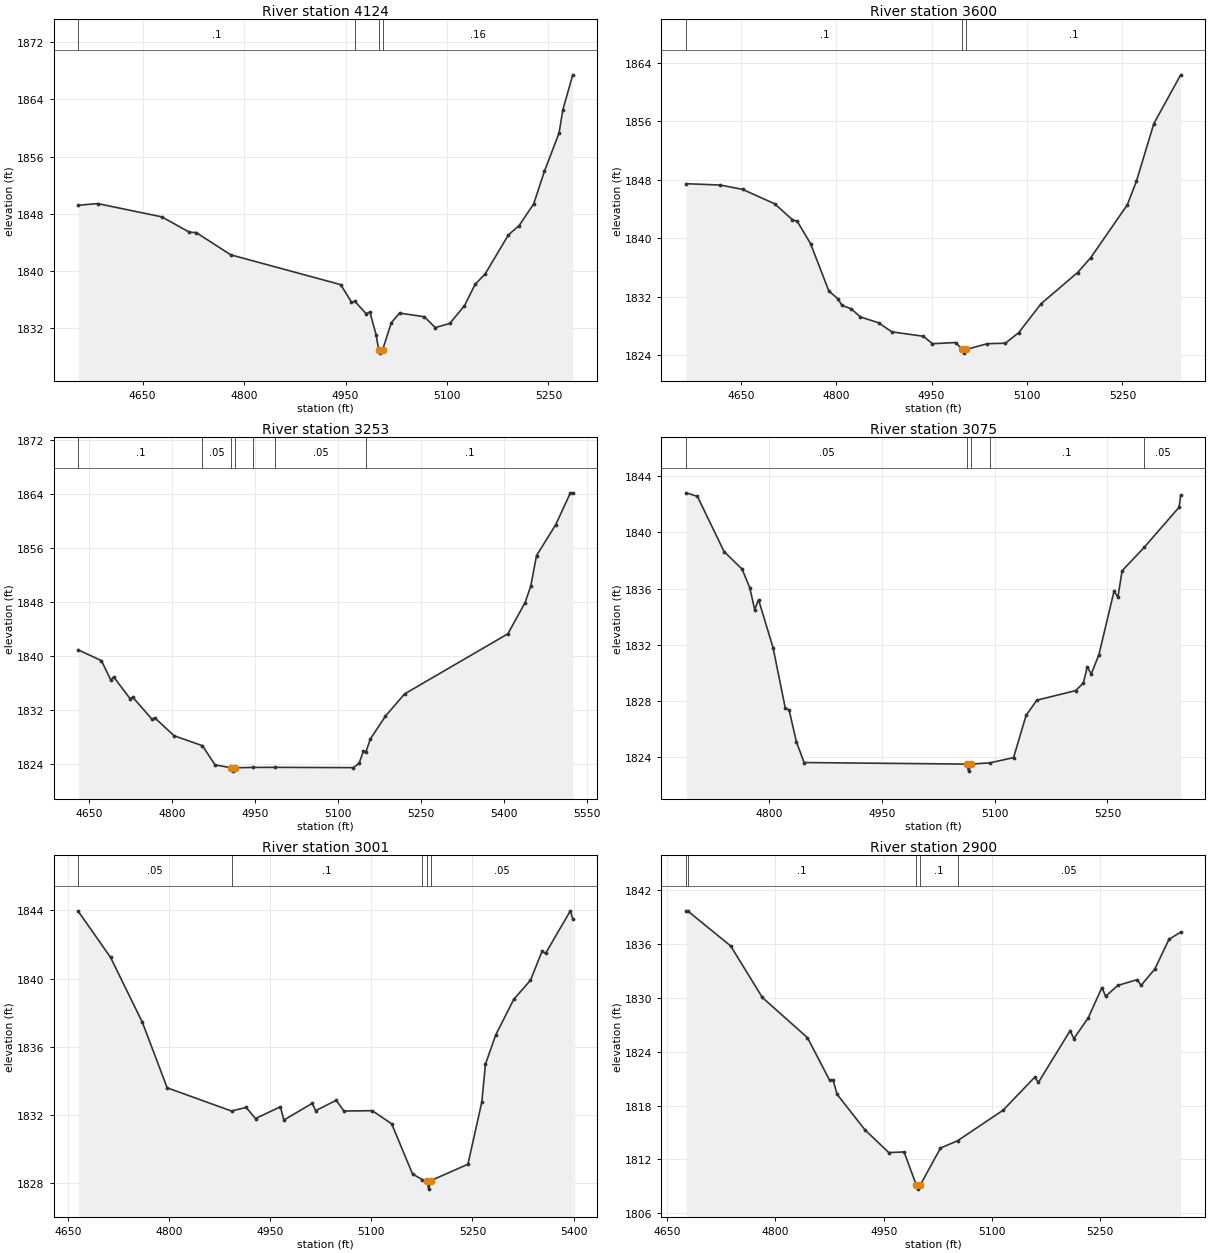
Type RM Length L Ch R = 1 ,4124    ,524,524,524
BEGIN DESCRIPTION:
UNT 1037 IN HEWA 7.0
END DESCRIPTION:
XS GIS Cut Line= 3
      2708698.78     10031735.94      2708750.86     10031408.26
       2708553.4     10031061.08
#Sta/Elev= 30
  4554.8 1849.16  4583.5  1849.4  4678.5 1847.53    4719 1845.39  4729.2 1845.33
  4780.3 1842.21  4942.8 1838.03  4958.7  1835.6    4964 1835.67  4980.3 1833.96
    4986 1834.18  4995.3 1830.96  4998.9 1828.92  5001.6 1828.42  5004.9 1828.92
  5017.8  1832.7  5029.9 1834.04  5066.7 1833.52  5082.6    1832  5104.2 1832.59
  5125.8 1835.06  5141.7 1838.08  5156.4 1839.52  5190.9 1845.02  5206.6  1846.3
  5228.2 1849.35    5244 1853.91  5265.7 1859.28  5271.4 1862.58    5286 1867.46
#Mann= 4 ,-1 , 0
  4554.8      .1       0    4964     .16       0  4998.9     .07       0
  5004.9     .16       0
Bank Sta=4998.9,5004.9
XS Rating Curve= 0 ,0
Exp/Cntr=0.3,0.1

Type RM Length L Ch R = 1 ,3600    ,347,347,347
BEGIN DESCRIPTION:
Mapping XS 40a4d77b
END DESCRIPTION:
XS GIS Cut Line= 2
      2708770.42     10031751.11      2709264.34     10031151.04
#Sta/Elev= 30
  4564.3 1847.44  4617.7 1847.26  4652.9 1846.67  4703.4 1844.69  4731.1 1842.53
    4739 1842.28  4759.8 1839.23  4788.5 1832.77  4802.8 1831.69  4809.3 1830.78
  4823.6 1830.33    4838 1829.22  4866.7 1828.41  4887.5 1827.17    4937 1826.57
  4951.3 1825.55  4987.9 1825.71  4998.3 1824.76    5001 1824.26  5004.3 1824.76
  5037.4 1825.55    5066 1825.62  5086.9 1827.06  5122.1 1831.02  5179.4 1835.28
  5200.3 1837.34  5257.6 1844.55    5272  1847.8  5299.3 1855.67  5341.5 1862.34
#Mann= 3 ,-1 , 0
  4564.3      .1       0  4998.3     .07       0  5004.3      .1       0
Bank Sta=4998.3,5004.3
XS Rating Curve= 0 ,0
Exp/Cntr=0.3,0.1

Type RM Length L Ch R = 1 ,3253    ,178,178,178
BEGIN DESCRIPTION:
Mapping XS cda7d063
END DESCRIPTION:
XS GIS Cut Line= 2
      2709117.62      10032044.1      2709351.98     10031180.43
#Sta/Elev= 30
    4630 1840.95  4671.8 1839.36  4688.9 1836.49  4694.1 1836.94  4723.6 1833.74
  4728.7 1833.94  4763.4 1830.68  4768.6 1830.88  4803.2 1828.24  4854.6 1826.76
  4877.6 1823.91  4907.1 1823.49  4909.9 1822.99  4913.1 1823.49  4947.1 1823.54
  4986.5 1823.55  5127.7 1823.51  5138.1 1824.12    5146 1825.94  5150.5 1825.85
  5158.8 1827.78  5185.8 1831.12  5220.4 1834.42  5407.5 1843.33  5438.6 1847.95
  5448.9  1850.4  5459.3 1854.91    5494 1859.48  5520.6 1864.21  5524.9 1864.21
#Mann= 7 ,-1 , 0
    4630      .1       0  4854.6     .05       0  4907.1    .033       0
  4913.1     .05       0  4947.1      .1       0  4986.5     .05       0
  5150.5      .1       0
Bank Sta=4907.1,4913.1
XS Rating Curve= 0 ,0
Exp/Cntr=0.3,0.1

Type RM Length L Ch R = 1 ,3075    ,74,74,74
BEGIN DESCRIPTION:
Mapping XS 1b6c0bb0
END DESCRIPTION:
XS GIS Cut Line= 2
      2709310.45     10032025.78      2709474.39     10031388.22
#Sta/Elev= 30
  4689.2  1842.8  4704.1 1842.55  4739.6 1838.63  4763.6 1837.38  4773.9 1836.05
  4780.4  1834.5  4785.5 1835.21  4804.9 1831.79  4821.1 1827.51  4826.2 1827.38
  4835.9 1825.11  4846.2 1823.64  5062.4 1823.53  5065.2 1823.03  5068.4 1823.53
  5093.8 1823.62    5125 1823.99  5141.7 1826.99    5156 1828.07  5207.6 1828.75
  5217.9 1829.29  5223.2 1830.44  5228.4 1829.93  5238.6  1831.3  5258.8 1835.82
  5263.9 1835.38  5269.5 1837.26  5298.8 1838.92  5345.4 1841.78  5347.5 1842.64
#Mann= 5 ,-1 , 0
  4689.2     .05       0  5062.4    .033       0  5068.4     .05       0
  5093.8      .1       0  5298.8     .05       0
Bank Sta=5062.4,5068.4
XS Rating Curve= 0 ,0
Exp/Cntr=0.3,0.1

Type RM Length L Ch R = 1 ,3001    ,101,101,101
BEGIN DESCRIPTION:
Mapping XS 9a328648
END DESCRIPTION:
XS GIS Cut Line= 2
      2709382.38     10032065.79      2709553.64     10031352.56
#Sta/Elev= 30
  4665.3 1843.94  4713.2 1841.24  4760.4 1837.43  4797.2 1833.59  4892.6 1832.23
  4914.2 1832.44  4928.3 1831.79  4965.1 1832.48  4970.3  1831.7  5012.3 1832.68
  5017.4 1832.25  5047.9 1832.86  5059.4 1832.23  5101.4 1832.25  5130.2 1831.48
  5161.1 1828.54  5175.9  1828.2  5182.3 1828.15  5185.1 1827.65  5188.3 1828.15
  5243.3 1829.11  5263.9 1832.76  5269.3 1834.98  5284.5 1836.69  5311.3 1838.78
  5335.9 1839.89  5353.3  1841.6  5358.4 1841.47  5395.2 1843.97  5398.8  1843.5
#Mann= 5 ,-1 , 0
  4665.3     .05       0  4892.6      .1       0  5175.9     .05       0
  5182.3     .07       0  5188.3     .05       0
Bank Sta=5182.3,5188.3
XS Rating Curve= 0 ,0
Exp/Cntr=0.3,0.1

Type RM Length L Ch R = 1 ,2900    ,408,408,408
BEGIN DESCRIPTION:
UNT 1037 IN HEWA 6.0
END DESCRIPTION:
XS GIS Cut Line= 2
      2709490.14     10032077.85      2709635.95     10031408.66
#Sta/Elev= 30
  4676.5 1839.68  4678.4 1839.68  4738.1 1835.77    4782 1830.03  4844.5 1825.55
    4875 1820.84  4880.2 1820.79  4885.4 1819.26  4924.1 1815.29  4957.1 1812.76
  4978.3 1812.83    4995 1809.19  4997.7 1808.69    5001 1809.19  5028.7 1813.26
  5052.4 1814.08  5115.3 1817.47  5159.2 1821.15  5164.4 1820.58  5208.3 1826.34
  5213.4 1825.45  5233.4 1827.77  5252.3 1831.14  5257.4 1830.17  5274.3 1831.37
  5301.3 1832.02  5306.4 1831.37  5325.5 1833.19  5345.3 1836.52  5361.4  1837.3
#Mann= 5 ,-1 , 0
  4676.5     .05       0  4678.4      .1       0    4995     .07       0
    5001      .1       0  5052.4     .05       0
Bank Sta=4995,5001
XS Rating Curve= 0 ,0
Exp/Cntr=0.3,0.1

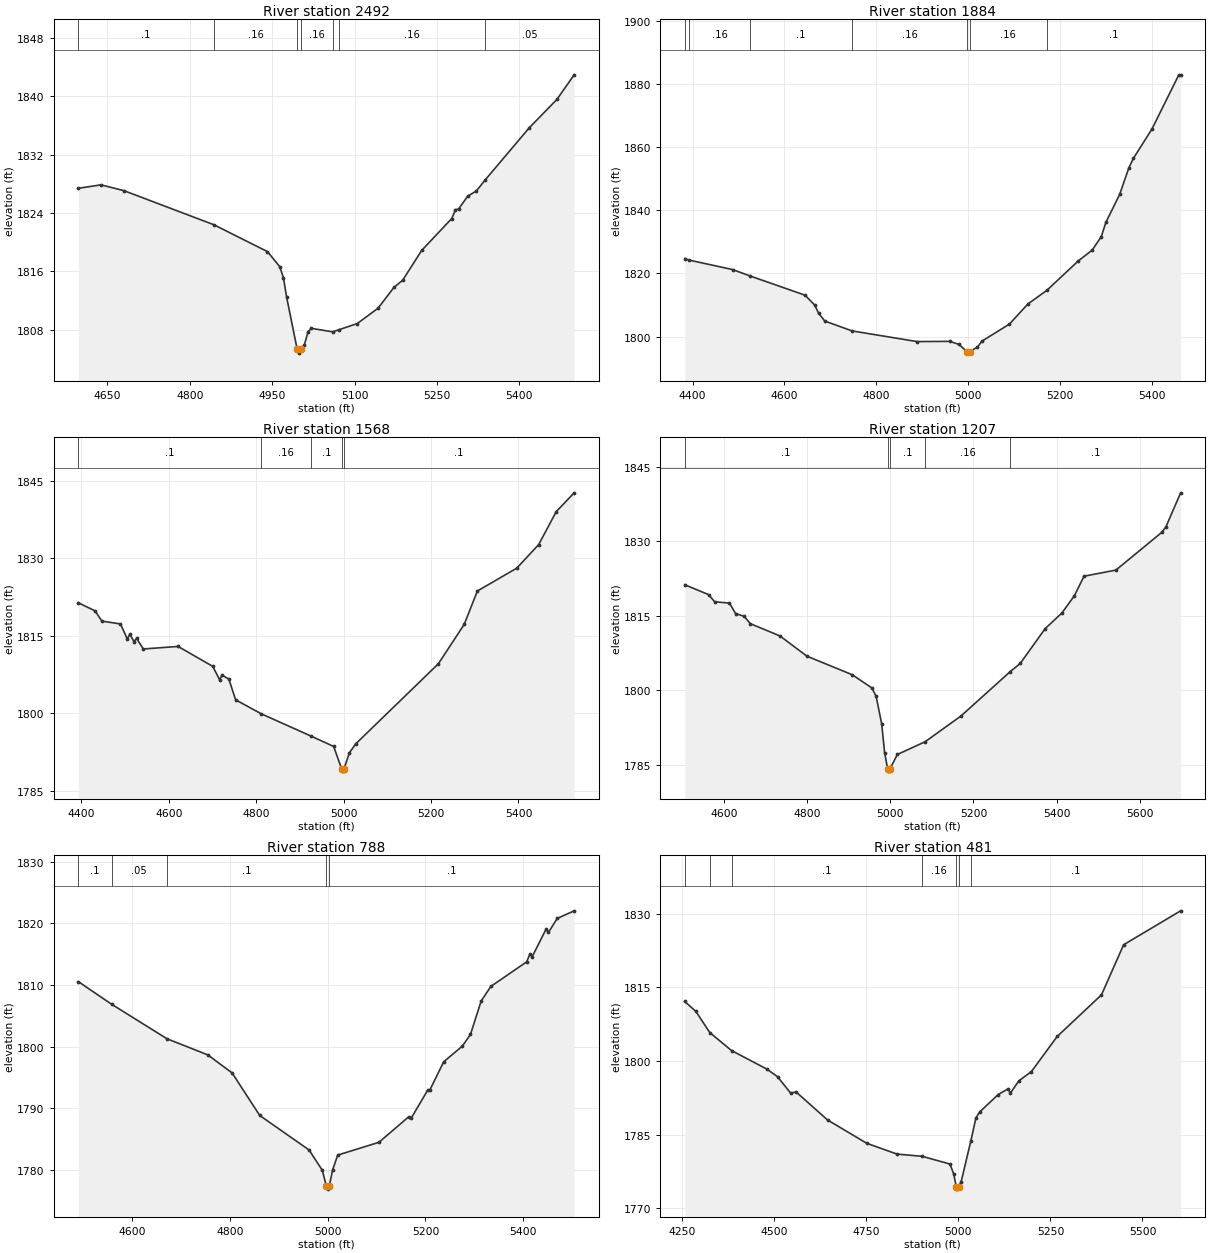
Type RM Length L Ch R = 1 ,2492    ,608,608,608
BEGIN DESCRIPTION:
UNT 1037 IN HEWA 5.0
END DESCRIPTION:
XS GIS Cut Line= 3
      2709998.66     10032114.81      2709977.83     10031795.35
      2709717.39     10031274.47
#Sta/Elev= 30
  4597.3 1827.39  4638.5 1827.86  4680.4 1827.06    4844 1822.39  4941.6  1818.7
    4964 1816.63  4970.7  1815.1  4976.3 1812.51  4995.7 1805.28  4998.4 1804.78
  5001.7 1805.28  5008.7 1805.92  5015.5 1807.71  5021.1 1808.18  5060.4  1807.7
  5071.3 1807.98  5104.9 1808.83  5142.9 1810.94    5172 1813.82  5187.6 1814.77
  5222.3 1818.87    5277 1823.24  5283.8 1824.45  5289.4 1824.54  5306.2 1826.32
  5321.7 1827.01    5338 1828.55    5418 1835.68  5468.3 1839.57  5499.8 1842.95
#Mann= 7 ,-1 , 0
  4597.3      .1       0    4844     .16       0  4995.7     .07       0
  5001.7     .16       0  5060.4      .1       0  5071.3     .16       0
    5338     .05       0
Bank Sta=4995.7,5001.7
XS Rating Curve= 0 ,0
Exp/Cntr=0.3,0.1

Type RM Length L Ch R = 1 ,1884    ,316,316,316
BEGIN DESCRIPTION:
UNT 1037 IN HEWA 4.0
END DESCRIPTION:
XS GIS Cut Line= 3
      2710113.26     10032083.51      2710422.27     10031642.57
       2710418.8     10031100.92
#Sta/Elev= 30
  4382.9 1824.71  4391.4 1824.26  4487.1 1821.23  4525.1  1819.2  4644.9  1813.1
  4665.8 1809.99  4674.5 1807.37  4687.9 1804.89  4747.4 1801.77    4889 1798.39
  4960.2 1798.46  4980.2 1797.49  4997.2 1795.23  4999.9 1794.73  5003.2 1795.23
  5020.2  1796.6  5030.2 1798.53  5090.2 1803.95  5130.2  1810.3  5171.9 1814.68
  5240.2 1823.99  5270.2 1827.37  5290.2 1831.68  5300.2 1836.22  5330.2 1845.06
  5350.2 1853.47  5360.2 1856.52  5400.2 1865.71  5459.1 1882.99    5463 1882.99
#Mann= 7 ,-1 , 0
  4382.9      .1       0  4391.4     .16       0  4525.1      .1       0
  4747.4     .16       0  4997.2     .07       0  5003.2     .16       0
  5171.9      .1       0
Bank Sta=4997.2,5003.2
XS Rating Curve= 0 ,0
Exp/Cntr=0.3,0.1

Type RM Length L Ch R = 1 ,1568    ,361,361,361
BEGIN DESCRIPTION:
Mapping XS dbef611a
END DESCRIPTION:
XS GIS Cut Line= 4
      2710158.04     10032117.03      2710585.16      10031856.6
      2710710.16     10031676.04      2710682.38     10031262.83
#Sta/Elev= 30
  4393.3 1821.36  4431.6  1819.8  4447.1 1817.81  4489.7 1817.27  4505.2 1814.37
    4511 1815.23  4520.6 1813.86  4526.5 1814.46    4542 1812.42  4621.4 1812.91
  4700.8 1809.05  4716.2 1806.49  4722.1 1807.35  4737.6 1806.59    4753 1802.58
  4811.6 1799.87  4925.6 1795.55  4977.3 1793.55  4995.2 1789.27    4998 1788.77
  5001.2 1789.27  5013.1  1792.3  5027.9 1794.07  5216.8 1809.56  5275.8 1817.17
  5305.9 1823.64  5396.1 1828.07  5446.2 1832.64  5486.3 1839.01  5527.3 1842.65
#Mann= 5 ,-1 , 0
  4393.3      .1       0  4811.6     .16       0  4925.6      .1       0
  4995.2     .07       0  5001.2      .1       0
Bank Sta=4995.2,5001.2
XS Rating Curve= 0 ,0
Exp/Cntr=0.3,0.1

Type RM Length L Ch R = 1 ,1207    ,419,419,419
BEGIN DESCRIPTION:
UNT 1037 IN HEWA 3.0
END DESCRIPTION:
XS GIS Cut Line= 4
      2710730.98     10032266.33       2710967.1     10031939.93
      2710890.71     10031561.46      2710873.48     10031158.28
#Sta/Elev= 30
  4505.9 1821.24    4563 1819.25  4577.7 1817.81  4613.3 1817.54    4628 1815.44
  4648.8 1814.87  4663.5  1813.4  4734.7 1810.93  4799.7 1806.85  4908.7 1803.11
  4955.9 1800.45  4966.1 1798.76  4979.5 1793.19  4986.5 1787.39  4993.7  1784.2
  4996.4  1783.7  4999.7  1784.2  5017.1 1787.05  5083.9 1789.62  5170.1  1794.8
  5288.8 1803.76  5312.6 1805.38  5372.6  1812.4  5412.7 1815.53  5442.7    1819
  5466.1 1822.96  5542.8 1824.19  5652.9 1831.78  5662.9 1832.87  5698.4 1839.75
#Mann= 5 ,-1 , 0
  4505.9      .1       0  4993.7     .07       0  4999.7      .1       0
  5083.9     .16       0  5288.8      .1       0
Bank Sta=4993.7,4999.7
XS Rating Curve= 0 ,0
Exp/Cntr=0.3,0.1

Type RM Length L Ch R = 1 ,788     ,307,307,307
BEGIN DESCRIPTION:
UNT 1037 IN HEWA 2.0
END DESCRIPTION:
XS GIS Cut Line= 3
      2711009.08     10032128.68       2711291.2     10031855.24
      2711469.16     10031260.59
#Sta/Elev= 30
  4490.5 1810.56  4558.4  1806.9  4671.6  1801.3  4755.1 1798.68  4804.8 1795.76
  4861.4 1788.85  4962.2 1783.26  4989.3 1779.96  4997.5 1777.41  5000.2 1776.91
  5003.5 1777.41  5010.2 1779.99  5020.7 1782.43    5105  1784.5    5166 1788.65
  5171.2 1788.44  5204.3 1792.91  5209.5 1793.05  5237.4 1797.56  5275.7 1800.11
  5292.1 1801.99    5314 1807.41  5333.8 1809.78  5406.9 1813.76  5413.3 1814.96
  5418.5 1814.63  5446.4 1819.03  5451.6 1818.55  5469.5 1820.81  5504.1 1822.04
#Mann= 5 ,-1 , 0
  4490.5      .1       0  4558.4     .05       0  4671.6      .1       0
  4997.5     .07       0  5003.5      .1       0
Bank Sta=4997.5,5003.5
XS Rating Curve= 0 ,0
Exp/Cntr=0.3,0.1

Type RM Length L Ch R = 1 ,481     ,209,209,209
BEGIN DESCRIPTION:
Mapping XS c9a2396e
END DESCRIPTION:
XS GIS Cut Line= 4
      2711109.48     10032196.86      2711574.74      10031856.6
      2711605.99     10031526.74      2711630.29     10031089.26
#Sta/Elev= 30
  4257.6 1812.12  4287.8 1810.09  4325.4 1805.79  4384.4 1802.13  4480.1 1798.36
  4509.4  1796.8  4544.9 1793.46  4559.6  1793.7  4645.3 1787.98  4751.9 1783.22
    4834 1781.03  4901.7 1780.59  4977.5 1779.01  4987.6 1776.96  4994.6  1774.4
  4997.4  1773.9  5000.6  1774.4  5007.6 1775.37  5034.3 1783.79  5047.8  1788.4
  5057.9 1789.61  5108.1 1793.15  5135.9 1794.37  5140.9  1793.4  5164.3 1795.95
  5198.4 1797.84  5268.5    1805  5388.7 1813.48  5448.8 1823.68  5603.5 1830.59
#Mann= 7 ,-1 , 0
  4257.6      .1       0  4325.4     .05       0  4384.4      .1       0
  4901.7     .16       0  4994.6     .07       0  5000.6     .16       0
  5034.3      .1       0
Bank Sta=4994.6,5000.6
XS Rating Curve= 0 ,0
Exp/Cntr=0.3,0.1

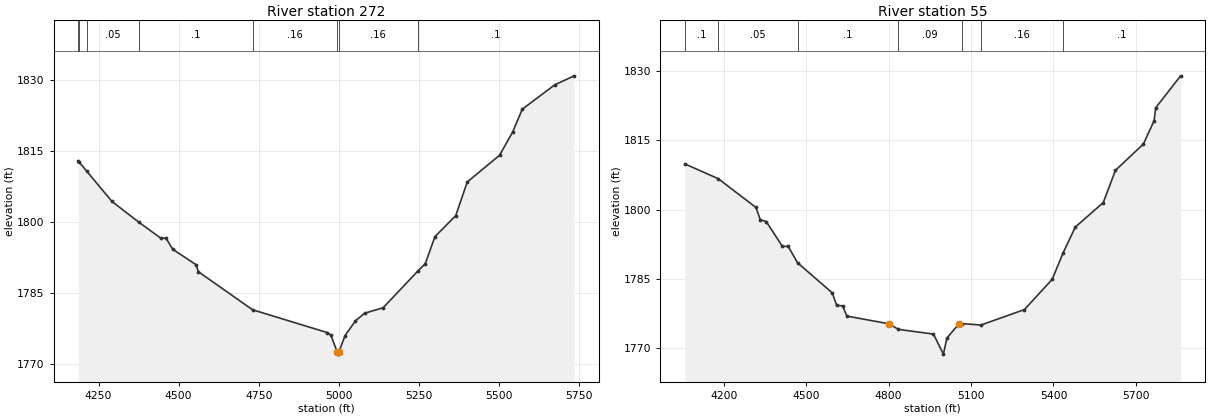
Type RM Length L Ch R = 1 ,272     ,155,155,155
BEGIN DESCRIPTION:
Mapping XS cf145a64
END DESCRIPTION:
XS GIS Cut Line= 4
      2711151.12      10032231.6      2711720.57     10031884.38
      2711828.21     10031644.79       2711741.4     10031033.64
#Sta/Elev= 30
    4187 1812.93  4189.2 1812.75  4213.2 1810.76  4291.9 1804.37    4376 1799.97
  4444.8 1796.59  4460.3 1796.64  4481.6 1794.25  4555.1 1790.97    4561 1789.55
  4730.6 1781.48  4964.3 1776.65  4975.3 1776.06  4994.2 1772.61  4996.9 1772.11
  5000.2 1772.61  5019.1 1776.03  5051.4 1779.12    5080 1780.75  5137.9 1781.91
  5245.5 1789.61  5269.2 1791.19  5299.5 1796.93  5364.4 1801.37  5400.5 1808.49
  5501.2 1814.13  5541.9 1819.03  5572.1 1823.86  5673.2    1829  5733.9 1830.91
#Mann= 8 ,-1 , 0
    4187     .05       0  4189.2      .1       0  4213.2     .05       0
    4376      .1       0  4730.6     .16       0  4994.2     .07       0
  5000.2     .16       0  5245.5      .1       0
Bank Sta=4994.2,5000.2
XS Rating Curve= 0 ,0
Exp/Cntr=0.3,0.1

Type RM Length L Ch R = 1 ,55      ,0,0,0
BEGIN DESCRIPTION:
UNT 1037 IN HEWA 1.0
END DESCRIPTION:
XS GIS Cut Line= 4
      2711207.02     10032367.56      2711903.67     10031961.73
      2712029.53     10031736.04      2711827.71     10031024.25
#Sta/Elev= 30
  4058.3 1809.85    4180 1806.66  4317.3 1800.44    4333  1797.8  4354.5 1797.41
  4413.3 1792.06  4434.8 1792.02  4468.6  1788.5  4595.2 1781.99    4611 1779.29
  4632.5  1779.2  4648.2 1776.99  4800.6 1775.33    4836 1774.11  4963.2  1773.1
  4999.4 1768.77  5012.3 1772.25  5056.9 1775.38    5066 1775.37  5135.9 1775.05
  5294.3 1778.39  5395.6 1784.94  5434.8  1790.6  5479.5 1796.21  5581.3  1801.5
  5625.6 1808.46  5727.4 1814.15  5766.5 1819.21  5771.7 1821.94  5862.8 1828.87
#Mann= 7 ,-1 , 0
  4058.3      .1       0    4180     .05       0  4468.6      .1       0
    4836     .09       0    5066      .1       0  5135.9     .16       0
  5434.8      .1       0
Bank Sta=4800.6,5056.9
XS Rating Curve= 0 ,0
Exp/Cntr=0.3,0.1

Chan Stop Cuts=-1
Use User Specified Reach Order=0
Composite Channel Slope=5