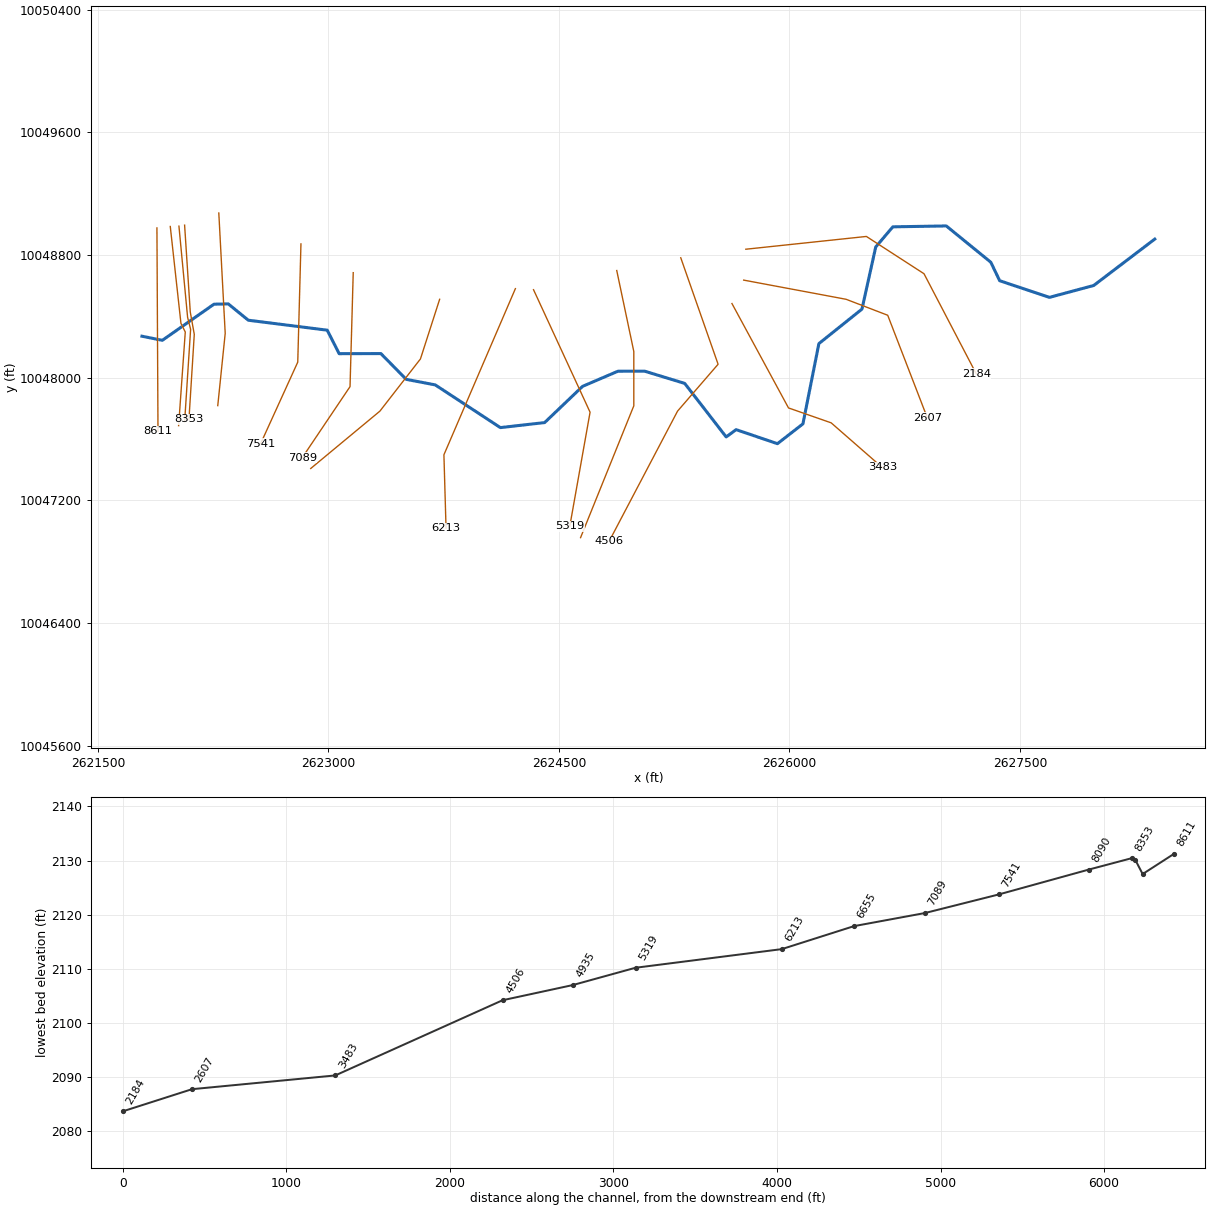
--- UNT 1039 IN HEWA.prj (project) ---

Proj Title=UNT 1039 IN HEWA Base Level Engineering
Current Plan=p01
Default Exp/Contr=0.3,0.1
English Units
Geom File=g01
Flow File=f01
Plan File=p01
BEGIN DESCRIPTION:
UNT 1039 IN HEWA
END DESCRIPTION:

--- UNT 1039 IN HEWA.p01 (plan) ---

Plan Title=Multiple Run
Short Identifier=Multiple
Geom File=g01
Flow File=f01
Subcritical Flow
K Sum by GR= 0
Std Step Tol= 0.01
Critical Tol= 0.01
Num of Std Step Trials= 20
Max Error Tol= 0.3
Flow Tol Ratio= 0.001
Split Flow NTrial= 30
Split Flow Tol= 0.02
Split Flow Ratio= 0.02
Log Output Level= 0
Friction Slope Method= 1
Unsteady Friction Slope Method= 2
Unsteady Bridges Friction Slope Method= 1
Parabolic Critical Depth
Global Vel Dist=  1 , 1 , 1
Global Log Level= 0
CheckData=True
Encroach Param= -1, 0, 0, 0
BEGIN DESCRIPTION:
Multiple Run
END DESCRIPTION:

--- UNT 1039 IN HEWA.f01 (steady flow) ---

Flow Title=Multiple
Number of Profiles=7
Profile Names=10-year,25-year,50-year,1pct_min,100-year,1pct_plu,500-year
River Rch & RM= UNT 1039 IN HEWA,Reach-1,8611
    1068    1543    1950    1794    2427    3282    3760
River Rch & RM= UNT 1039 IN HEWA,Reach-1,5319
    1662    2454    3146    2933    3966    5364    6309
Boundary for River Rch & Prof#=UNT 1039 IN HEWA,Reach-1,1
Up Type=0
Dn Type=3
Dn Slope=0.005
Boundary for River Rch & Prof#=UNT 1039 IN HEWA,Reach-1,2
Up Type=0
Dn Type=3
Dn Slope=0.005
Boundary for River Rch & Prof#=UNT 1039 IN HEWA,Reach-1,3
Up Type=0
Dn Type=3
Dn Slope=0.005
Boundary for River Rch & Prof#=UNT 1039 IN HEWA,Reach-1,4
Up Type=0
Dn Type=3
Dn Slope=0.005
Boundary for River Rch & Prof#=UNT 1039 IN HEWA,Reach-1,5
Up Type=0
Dn Type=3
Dn Slope=0.005
Boundary for River Rch & Prof#=UNT 1039 IN HEWA,Reach-1,6
Up Type=0
Dn Type=3
Dn Slope=0.005
Boundary for River Rch & Prof#=UNT 1039 IN HEWA,Reach-1,7
Up Type=0
Dn Type=3
Dn Slope=0.005

--- UNT 1039 IN HEWA.g01 (geometry) ---

Geom Title=Existing Conditions

River Reach=UNT 1039 IN HEWA,Reach-1
Reach XY= 30
      2621785.60     10048270.48      2621918.47     10048243.73
      2622254.77     10048479.24      2622347.53     10048481.21
      2622478.04     10048374.68      2622991.80     10048309.77
      2623069.41     10048156.44      2623340.99     10048157.23
      2623505.94     10047989.19      2623694.84     10047953.03
      2624118.91     10047674.50      2624406.93     10047707.37
      2624653.60     10047943.32      2624884.17     10048042.23
      2625057.87     10048042.54      2625318.80     10047962.68
      2625588.47     10047613.73      2625653.46     10047661.27
      2625922.33     10047569.75      2626088.16     10047698.85
      2626192.10     10048222.22      2626472.47     10048447.11
      2626562.12     10048852.25      2626673.51     10048983.58
      2627021.36     10048989.34      2627311.10     10048752.74
      2627368.95     10048632.24      2627692.55     10048523.68
      2627980.91     10048601.11      2628378.47     10048903.73

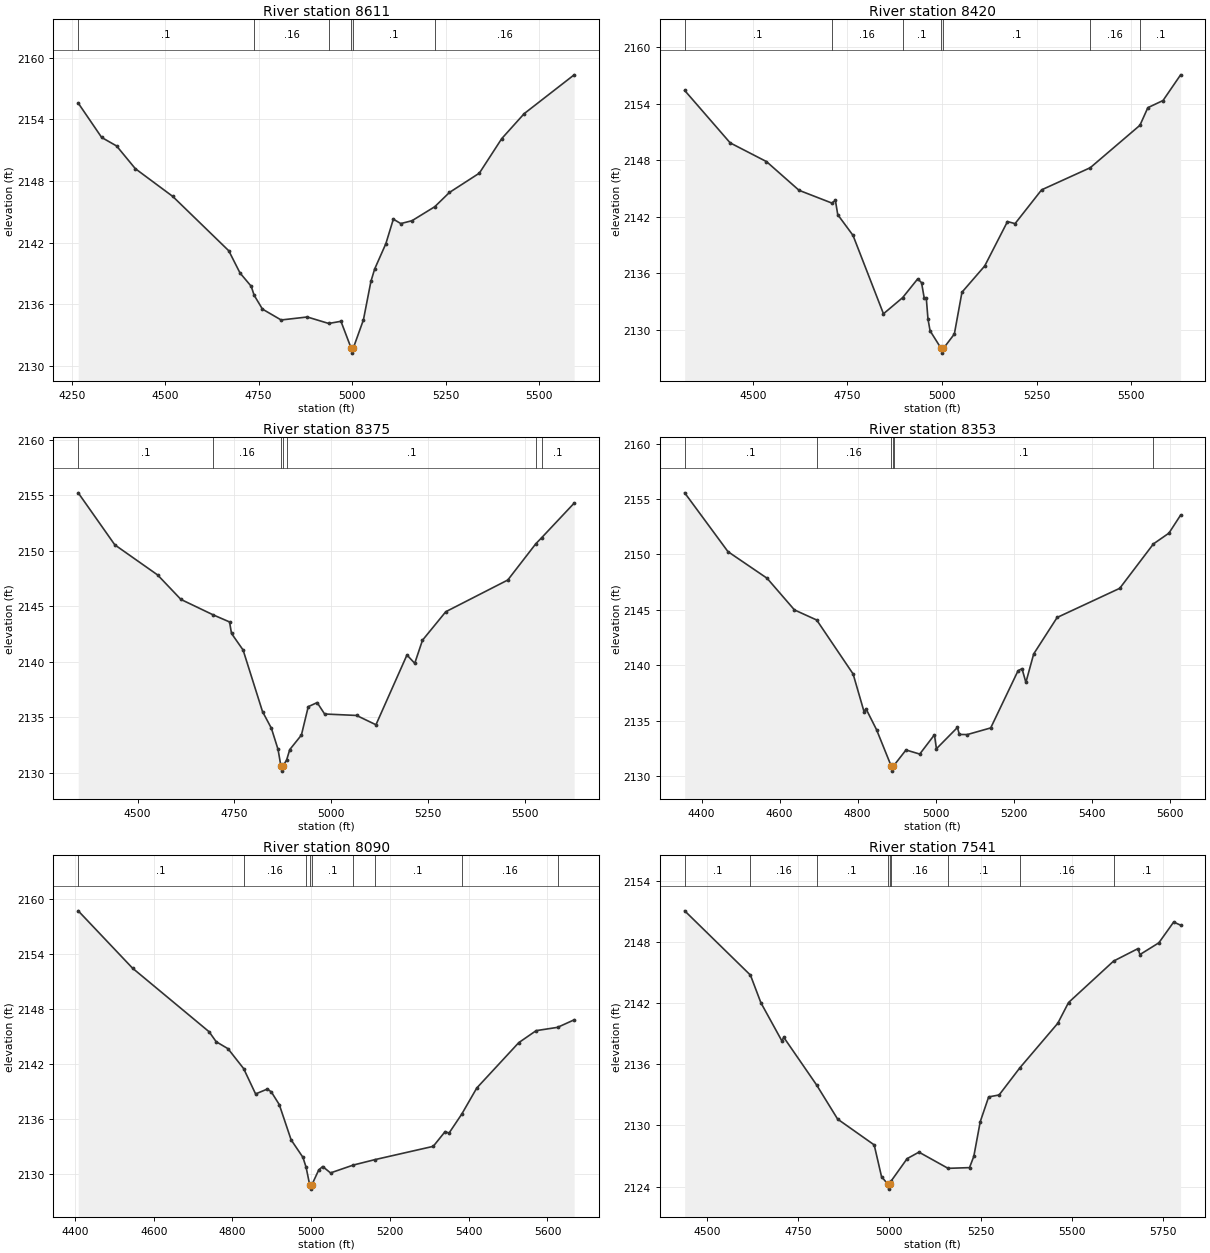
Type RM Length L Ch R = 1,8611,191,191,191
BEGIN DESCRIPTION:
UNT 1039 IN HEWA 15.0
END DESCRIPTION:
XS GIS Cut Line= 2
      2621883.22     10048976.47      2621890.16     10047650.09
#Sta/Elev= 30
  4267.6 2155.59  4330.3 2152.24  4370.3 2151.41  4420.3 2149.20  4520.3 2146.50
  4670.3 2141.20  4700.3 2139.04  4730.3 2137.74  4738.1 2136.87  4760.3 2135.52
  4810.3 2134.46  4880.3 2134.75  4937.5 2134.12  4970.3 2134.33  4997.4 2131.73
  5000.1 2131.23  5003.4 2131.73  5030.4 2134.47  5050.4 2138.21  5060.4 2139.42
  5090.4 2141.89  5110.4 2144.28  5130.4 2143.85  5160.4 2144.13  5221.1 2145.49
  5260.4 2146.88  5340.4 2148.76  5400.4 2152.13  5460.4 2154.56  5594.0 2158.34
#Mann=6,-1,0
  4267.6     0.1       0  4738.1    0.16       0  4937.5     0.1       0
  4997.4    0.07       0  5003.4     0.1       0  5221.1    0.16       0
Bank Sta=4997.4,5003.4
Exp/Cntr=0.3,0.1

Type RM Length L Ch R = 1,8420,45,45,45
BEGIN DESCRIPTION:
Mapping XS 4ac5e510
END DESCRIPTION:
XS GIS Cut Line= 4
      2621970.07     10048985.85      2622039.52     10048354.31
      2622067.73     10048297.88      2622024.43     10047687.35
#Sta/Elev= 30
  4320.2 2155.42  4440.4 2149.85  4536.4 2147.86  4622.4 2144.81  4708.8 2143.46
  4718.5 2143.73  4724.7 2142.22  4765.0 2140.02  4845.5 2131.69  4896.0 2133.40
  4936.0 2135.40  4946.1 2135.00  4953.3 2133.33  4958.7 2133.33  4963.1 2131.14
  4968.7 2129.88  4997.9 2128.01  5000.7 2127.51  5003.9 2128.01  5032.8 2129.54
  5052.9 2133.98  5113.0 2136.77  5173.2 2141.49  5193.2 2141.27  5263.4 2144.86
  5391.9 2147.21  5523.2 2151.72  5544.1 2153.59  5584.2 2154.35  5630.7 2157.08
#Mann=7,-1,0
  4320.2     0.1       0  4708.8    0.16       0  4896.0     0.1       0
  4997.9    0.07       0  5003.9     0.1       0  5391.9    0.16       0
  5523.2     0.1       0
Bank Sta=4997.9,5003.9
Exp/Cntr=0.3,0.1

Type RM Length L Ch R = 1,8375,22,22,22
BEGIN DESCRIPTION:
Mapping XS f98f16c2
END DESCRIPTION:
XS GIS Cut Line= 4
      2622026.50     10048987.94      2622082.92     10048393.37
      2622102.45     10048315.24      2622063.43     10047712.58
#Sta/Elev= 30
  4346.3 2155.22  4440.9 2150.53  4551.4 2147.82  4611.7 2145.61  4695.6 2144.21
  4737.4 2143.58  4742.5 2142.54  4772.4 2141.05  4822.6 2135.50  4845.6 2133.99
  4862.8 2132.08  4869.9 2130.63  4872.6 2130.13  4875.9 2130.63  4884.8 2131.12
  4893.0 2132.07  4923.1 2133.38  4940.8 2135.94  4963.8 2136.31  4983.1 2135.28
  5065.7 2135.15  5115.8 2134.31  5195.9 2140.60  5216.0 2139.85  5236.0 2141.93
  5296.2 2144.50  5456.5 2147.36  5529.2 2150.64  5544.2 2151.18  5628.0 2154.29
#Mann=7,-1,0
  4346.3     0.1       0  4695.6    0.16       0  4869.9    0.07       0
  4875.9    0.16       0  4884.8     0.1       0  5529.2    0.16       0
  5544.2     0.1       0
Bank Sta=4869.9,4875.9
Exp/Cntr=0.3,0.1

Type RM Length L Ch R = 1,8353,263,263,263
BEGIN DESCRIPTION:
Mapping XS 040e264f
END DESCRIPTION:
XS GIS Cut Line= 4
      2622063.39     10048994.50      2622100.28     10048428.09
      2622126.32     10048282.69      2622091.65     10047727.89
#Sta/Elev= 30
  4356.6 2155.56  4467.6 2150.25  4567.8 2147.85  4638.0 2144.99  4695.0 2144.08
  4788.3 2139.21  4816.3 2135.81  4821.3 2136.07  4848.4 2134.18  4885.5 2130.94
  4888.2 2130.44  4891.5 2130.94  4893.5 2130.98  4923.9 2132.35  4959.1 2131.98
  4996.8 2133.72  5001.9 2132.46  5055.7 2134.38  5060.7 2133.75  5080.9 2133.74
  5141.0 2134.34  5211.1 2139.50  5221.2 2139.69  5231.2 2138.45  5251.2 2141.02
  5311.3 2144.31  5471.7 2146.94  5558.1 2150.95  5597.8 2151.92  5627.8 2153.55
#Mann=6,-1,0
  4356.6     0.1       0  4695.0    0.16       0  4885.5    0.07       0
  4891.5    0.16       0  4893.5     0.1       0  5558.1    0.16       0
Bank Sta=4885.5,4891.5
Exp/Cntr=0.3,0.1

Type RM Length L Ch R = 1,8090,549,549,549
BEGIN DESCRIPTION:
UNT 1039 IN HEWA 14.0
END DESCRIPTION:
XS GIS Cut Line= 3
      2622286.00     10049073.64      2622327.66     10048288.94
      2622279.16     10047817.74
#Sta/Elev= 30
  4408.3 2158.71  4546.3 2152.45  4740.7 2145.51  4758.7 2144.42  4788.7 2143.66
  4828.4 2141.49  4858.8 2138.72  4888.9 2139.26  4898.9 2138.93  4918.9 2137.56
  4949.0 2133.71  4979.0 2131.80  4987.1 2130.71  4996.0 2128.83  4998.8 2128.33
  5002.0 2128.83  5019.1 2130.42  5029.1 2130.80  5049.1 2130.10  5107.1 2130.96
  5160.8 2131.54  5309.9 2133.00  5340.1 2134.61  5350.1 2134.45  5382.2 2136.51
  5420.5 2139.37  5527.1 2144.32  5571.3 2145.63  5625.6 2145.99  5667.8 2146.81
#Mann=9,-1,0
  4408.3     0.1       0  4828.4    0.16       0  4987.1     0.1       0
  4996.0    0.07       0  5002.0     0.1       0  5107.1    0.16       0
  5160.8     0.1       0  5382.2    0.16       0  5625.6     0.1       0
Bank Sta=4996,5002
Exp/Cntr=0.3,0.1

Type RM Length L Ch R = 1,7541,452,452,452
BEGIN DESCRIPTION:
UNT 1039 IN HEWA 13.0
END DESCRIPTION:
XS GIS Cut Line= 3
      2622820.72     10048872.29      2622799.88     10048101.44
      2622557.29     10047567.72
#Sta/Elev= 30
  4439.7 2151.06  4619.7 2144.75  4648.3 2142.04  4705.8 2138.29  4710.8 2138.65
  4800.6 2133.98  4858.4 2130.62  4958.4 2128.09  4978.5 2124.97  4995.5 2124.25
  4998.2 2123.75  5001.5 2124.25  5004.5 2124.53  5048.5 2126.74  5080.9 2127.38
  5160.6 2125.79  5219.3 2125.86  5231.1 2126.97  5248.6 2130.36  5271.7 2132.80
  5300.3 2132.99  5357.0 2135.65  5461.0 2140.03  5490.3 2142.06  5613.7 2146.13
  5680.3 2147.35  5685.8 2146.77  5737.5 2147.92  5778.1 2149.96  5797.1 2149.65
#Mann=9,-1,0
  4439.7     0.1       0  4619.7    0.16       0  4800.6     0.1       0
  4995.5    0.07       0  5001.5     0.1       0  5004.5    0.16       0
  5160.6     0.1       0  5357.0    0.16       0  5613.7     0.1       0
Bank Sta=4995.5,5001.5
Exp/Cntr=0.3,0.1

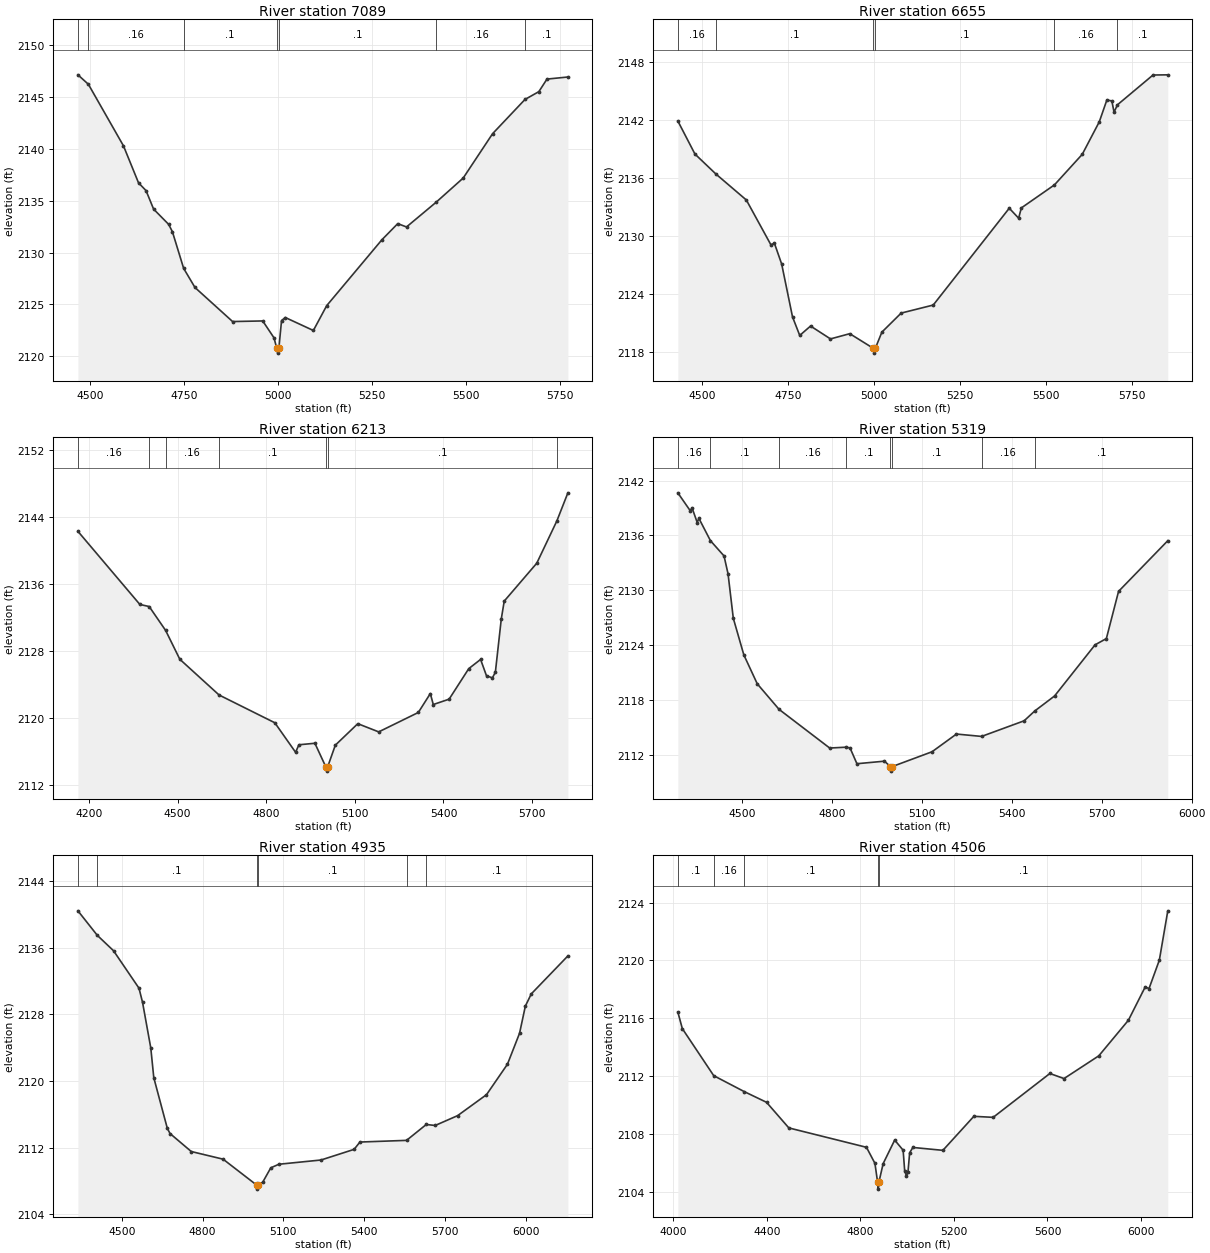
Type RM Length L Ch R = 1,7089,434,434,434
BEGIN DESCRIPTION:
UNT 1039 IN HEWA 12.0
END DESCRIPTION:
XS GIS Cut Line= 3
      2623161.00     10048684.81      2623140.16     10047941.71
      2622828.42     10047477.57
#Sta/Elev= 30
  4468.4 2147.11  4496.2 2146.20  4589.5 2140.27  4629.5 2136.71  4649.5 2135.96
  4669.6 2134.18  4709.6 2132.71  4719.6 2132.00  4749.5 2128.47  4779.6 2126.63
  4879.6 2123.35  4959.7 2123.41  4989.7 2121.78  4996.7 2120.81  4999.4 2120.31
  5002.7 2120.81  5009.7 2123.45  5019.7 2123.74  5094.3 2122.49  5129.7 2124.88
  5276.6 2131.23  5318.6 2132.78  5341.9 2132.46  5420.3 2134.83  5492.6 2137.17
  5570.7 2141.44  5656.9 2144.74  5693.7 2145.49  5715.3 2146.70  5770.9 2146.90
#Mann=7,-1,0
  4468.4     0.1       0  4496.2    0.16       0  4749.5     0.1       0
  4996.7    0.07       0  5002.7     0.1       0  5420.3    0.16       0
  5656.9     0.1       0
Bank Sta=4996.7,5002.7
Exp/Cntr=0.3,0.1

Type RM Length L Ch R = 1,6655,442,442,442
BEGIN DESCRIPTION:
UNT 1039 IN HEWA 11.0
END DESCRIPTION:
XS GIS Cut Line= 4
      2623723.50     10048511.17      2623598.50     10048122.27
      2623334.61     10047781.99      2622884.40     10047407.98
#Sta/Elev= 30
  4429.4 2141.89  4479.2 2138.47  4540.3 2136.40  4628.6 2133.72  4699.8 2129.10
  4710.3 2129.24  4731.3 2127.10  4762.8 2121.64  4783.8 2119.72  4815.3 2120.69
  4873.2 2119.36  4929.3 2119.90  4997.6 2118.39  5000.3 2117.89  5003.6 2118.39
  5022.6 2120.06  5078.7 2122.03  5171.9 2122.86  5392.9 2132.87  5420.2 2131.84
  5428.0 2132.90  5524.2 2135.28  5605.1 2138.44  5654.6 2141.80  5676.7 2144.06
  5691.1 2143.96  5697.6 2142.80  5707.4 2143.56  5810.8 2146.64  5853.8 2146.66
#Mann=6,-1,0
  4429.4    0.16       0  4540.3     0.1       0  4997.6    0.07       0
  5003.6     0.1       0  5524.2    0.16       0  5707.4     0.1       0
Bank Sta=4997.6,5003.6
Exp/Cntr=0.3,0.1

Type RM Length L Ch R = 1,6213,894,894,894
BEGIN DESCRIPTION:
UNT 1039 IN HEWA 10.0
END DESCRIPTION:
XS GIS Cut Line= 3
      2624216.54     10048580.57      2623751.27     10047497.27
      2623765.15     10047018.46
#Sta/Elev= 30
  4163.0 2142.30  4372.6 2133.56  4404.2 2133.31  4459.9 2130.45  4507.8 2127.01
  4640.6 2122.74  4829.3 2119.42  4899.6 2115.89  4910.8 2116.79  4964.9 2116.97
  5002.0 2114.14  5004.8 2113.64  5008.0 2114.14  5034.0 2116.74  5110.1 2119.31
  5180.8 2118.33  5314.9 2120.65  5355.5 2122.91  5365.5 2121.60  5419.1 2122.24
  5485.6 2125.89  5525.6 2126.99  5545.6 2125.03  5565.6 2124.79  5575.6 2125.46
  5595.6 2131.82  5605.6 2133.96  5715.7 2138.49  5783.8 2143.55  5821.0 2146.90
#Mann=7,-1,0
  4163.0    0.16       0  4404.2     0.1       0  4459.9    0.16       0
  4640.6     0.1       0  5002.0    0.07       0  5008.0     0.1       0
  5783.8    0.16       0
Bank Sta=5002,5008
Exp/Cntr=0.3,0.1

Type RM Length L Ch R = 1,5319,384,384,384
BEGIN DESCRIPTION:
UNT 1039 IN HEWA 9.0
END DESCRIPTION:
XS GIS Cut Line= 3
      2624334.61     10048573.66      2624702.66     10047775.05
      2624570.72     10047032.01
#Sta/Elev= 30
  4286.4 2140.67  4328.2 2138.69  4333.7 2139.04  4351.1 2137.42  4356.6 2137.88
  4395.2 2135.43  4440.5 2133.76  4453.9 2131.80  4471.4 2126.94  4506.5 2122.93
  4551.3 2119.76  4624.1 2116.96  4792.8 2112.73  4847.8 2112.82  4860.7 2112.74
  4883.7 2111.01  4975.5 2111.29  4995.5 2110.70  4998.2 2110.20  5001.5 2110.70
  5134.2 2112.32  5215.6 2114.26  5299.4 2114.00  5441.3 2115.71  5476.9 2116.79
  5542.9 2118.43  5677.9 2124.03  5715.5 2124.71  5756.2 2129.88  5920.4 2135.43
#Mann=8,-1,0
  4286.4    0.16       0  4395.2     0.1       0  4624.1    0.16       0
  4847.8     0.1       0  4995.5    0.07       0  5001.5     0.1       0
  5299.4    0.16       0  5476.9     0.1       0
Bank Sta=4995.5,5001.5
Exp/Cntr=0.3,0.1

Type RM Length L Ch R = 1,4935,429,429,429
BEGIN DESCRIPTION:
UNT 1039 IN HEWA 8.0
END DESCRIPTION:
XS GIS Cut Line= 4
      2624876.27     10048698.67      2624987.38     10048170.88
      2624987.38     10047816.71      2624640.80     10046957.19
#Sta/Elev= 30
  4336.5 2140.45  4408.6 2137.50  4468.9 2135.65  4563.4 2131.15  4576.6 2129.45
  4607.2 2123.97  4618.4 2120.39  4668.6 2114.31  4678.8 2113.68  4757.6 2111.52
  4875.9 2110.60  5000.0 2107.50  5002.8 2107.00  5006.0 2107.50  5023.0 2107.83
  5053.0 2109.56  5083.0 2109.99  5239.6 2110.50  5362.6 2111.78  5384.2 2112.66
  5557.4 2112.86  5630.7 2114.77  5663.7 2114.65  5747.0 2115.83  5854.4 2118.35
  5932.2 2122.01  5977.2 2125.73  5998.8 2129.00  6020.9 2130.47  6156.8 2135.03
#Mann=6,-1,0
  4336.5    0.16       0  4408.6     0.1       0  5000.0    0.07       0
  5006.0     0.1       0  5557.4    0.16       0  5630.7     0.1       0
Bank Sta=5000,5006
Exp/Cntr=0.3,0.1

Type RM Length L Ch R = 1,4506,1023,1023,1023
BEGIN DESCRIPTION:
UNT 1039 IN HEWA 7.0
END DESCRIPTION:
XS GIS Cut Line= 4
      2625292.95     10048781.96      2625536.00     10048087.55
      2625272.11     10047781.99      2624827.65     10046934.74
#Sta/Elev= 30
  4018.7 2116.44  4038.0 2115.29  4172.3 2112.04  4302.7 2110.94  4398.2 2110.20
  4493.6 2108.43  4825.8 2107.09  4862.0 2105.98  4873.2 2104.70  4876.0 2104.20
  4879.2 2104.70  4897.1 2105.96  4946.5 2107.59  4982.6 2106.89  4989.2 2105.48
  4996.9 2105.10  5003.5 2105.41  5010.5 2106.71  5024.3 2107.08  5152.7 2106.88
  5285.2 2109.23  5367.8 2109.16  5610.4 2112.19  5670.9 2111.84  5819.7 2113.41
  5946.4 2115.87  6018.2 2118.17  6034.6 2118.06  6078.7 2120.02  6114.9 2123.43
#Mann=5,-1,0
  4018.7     0.1       0  4172.3    0.16       0  4302.7     0.1       0
  4873.2    0.07       0  4879.2     0.1       0
Bank Sta=4873.2,4879.2
Exp/Cntr=0.3,0.1

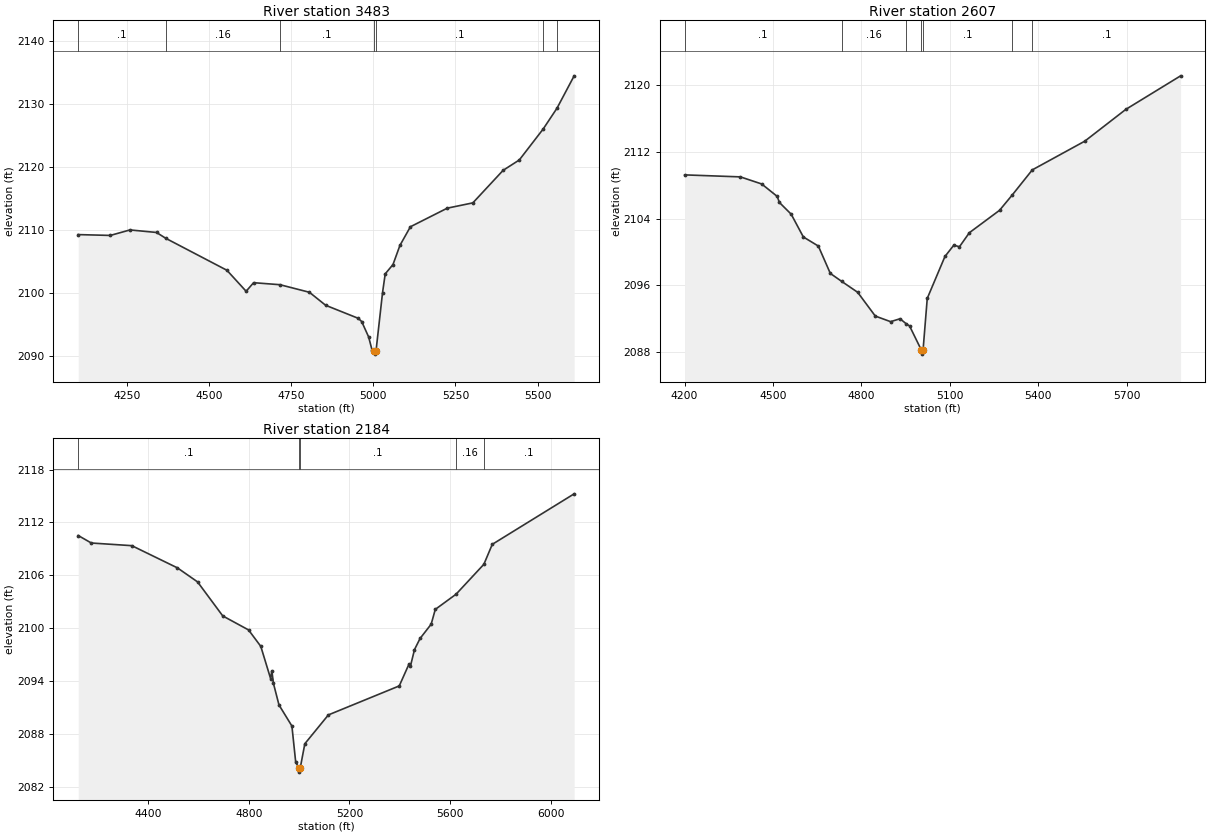
Type RM Length L Ch R = 1,3483,876,876,876
BEGIN DESCRIPTION:
UNT 1039 IN HEWA 5.0
END DESCRIPTION:
XS GIS Cut Line= 4
      2625626.30     10048483.34      2625994.33     10047802.83
      2626272.11     10047705.60      2626604.48     10047414.78
#Sta/Elev= 30
  4101.9 2109.25  4199.6 2109.12  4259.5 2109.99  4340.2 2109.59  4369.2 2108.64
  4554.5 2103.60  4613.0 2100.27  4635.8 2101.63  4716.1 2101.31  4805.7 2100.11
  4855.1 2098.05  4954.1 2095.99  4964.7 2095.48  4985.9 2093.04  4996.5 2090.92
  5002.4 2090.81  5005.2 2090.31  5008.4 2090.81  5028.3 2100.07  5036.4 2103.03
  5060.1 2104.51  5081.2 2107.54  5113.0 2110.49  5225.3 2113.44  5303.2 2114.28
  5395.2 2119.43  5444.6 2121.08  5517.3 2125.99  5559.4 2129.29  5611.5 2134.41
#Mann=7,-1,0
  4101.9     0.1       0  4369.2    0.16       0  4716.1     0.1       0
  5002.4    0.07       0  5008.4     0.1       0  5517.3    0.16       0
  5559.4     0.1       0
Bank Sta=5002.4,5008.4
Exp/Cntr=0.3,0.1

Type RM Length L Ch R = 1,2607,423,423,423
BEGIN DESCRIPTION:
UNT 1039 IN HEWA 3.0
END DESCRIPTION:
XS GIS Cut Line= 4
      2625702.62     10048636.17      2626369.33     10048511.16
      2626640.16     10048406.99      2626897.12     10047740.30
#Sta/Elev= 30
  4200.4 2109.25  4389.5 2109.01  4461.8 2108.16  4514.4 2106.67  4521.7 2105.95
  4561.8 2104.54  4603.1 2101.81  4654.0 2100.72  4694.7 2097.44  4733.5 2096.48
  4787.4 2095.18  4847.3 2092.33  4899.2 2091.66  4931.4 2092.01  4952.7 2091.39
  4963.5 2091.15  5003.4 2088.27  5006.1 2087.77  5009.4 2088.27  5023.6 2094.45
  5083.6 2099.47  5113.6 2100.82  5132.9 2100.64  5166.5 2102.32  5268.8 2105.00
  5312.7 2106.87  5380.1 2109.85  5558.2 2113.29  5697.5 2117.10  5883.4 2121.12
#Mann=7,-1,0
  4200.4     0.1       0  4733.5    0.16       0  4952.7     0.1       0
  5003.4    0.07       0  5009.4     0.1       0  5312.7    0.16       0
  5380.1     0.1       0
Bank Sta=5003.4,5009.4
Exp/Cntr=0.3,0.1

Type RM Length L Ch R = 1,2184,0,0,0
BEGIN DESCRIPTION:
UNT 1039 IN HEWA 2.0
END DESCRIPTION:
XS GIS Cut Line= 4
      2625716.54     10048837.55      2626501.27     10048920.88
      2626876.27     10048677.83      2627216.57     10048025.02
#Sta/Elev= 30
  4121.2 2110.52  4173.4 2109.67  4334.3 2109.37  4515.8 2106.85  4595.8 2105.26
  4696.0 2101.40  4798.6 2099.81  4847.2 2097.95  4886.2 2094.30  4891.2 2095.18
  4897.5 2093.75  4919.6 2091.30  4971.0 2088.91  4986.1 2084.81  4998.3 2084.18
  5001.1 2083.68  5004.3 2084.18  5022.4 2086.90  5116.0 2090.17  5397.9 2093.46
  5436.4 2095.92  5442.1 2095.67  5458.5 2097.58  5480.6 2098.84  5524.8 2100.46
  5541.2 2102.14  5623.7 2103.86  5734.5 2107.26  5767.8 2109.52  6093.4 2115.25
#Mann=5,-1,0
  4121.2     0.1       0  4998.3    0.07       0  5004.3     0.1       0
  5623.7    0.16       0  5734.5     0.1       0
Bank Sta=4998.3,5004.3
Exp/Cntr=0.3,0.1

Chan Stop Cuts=-1