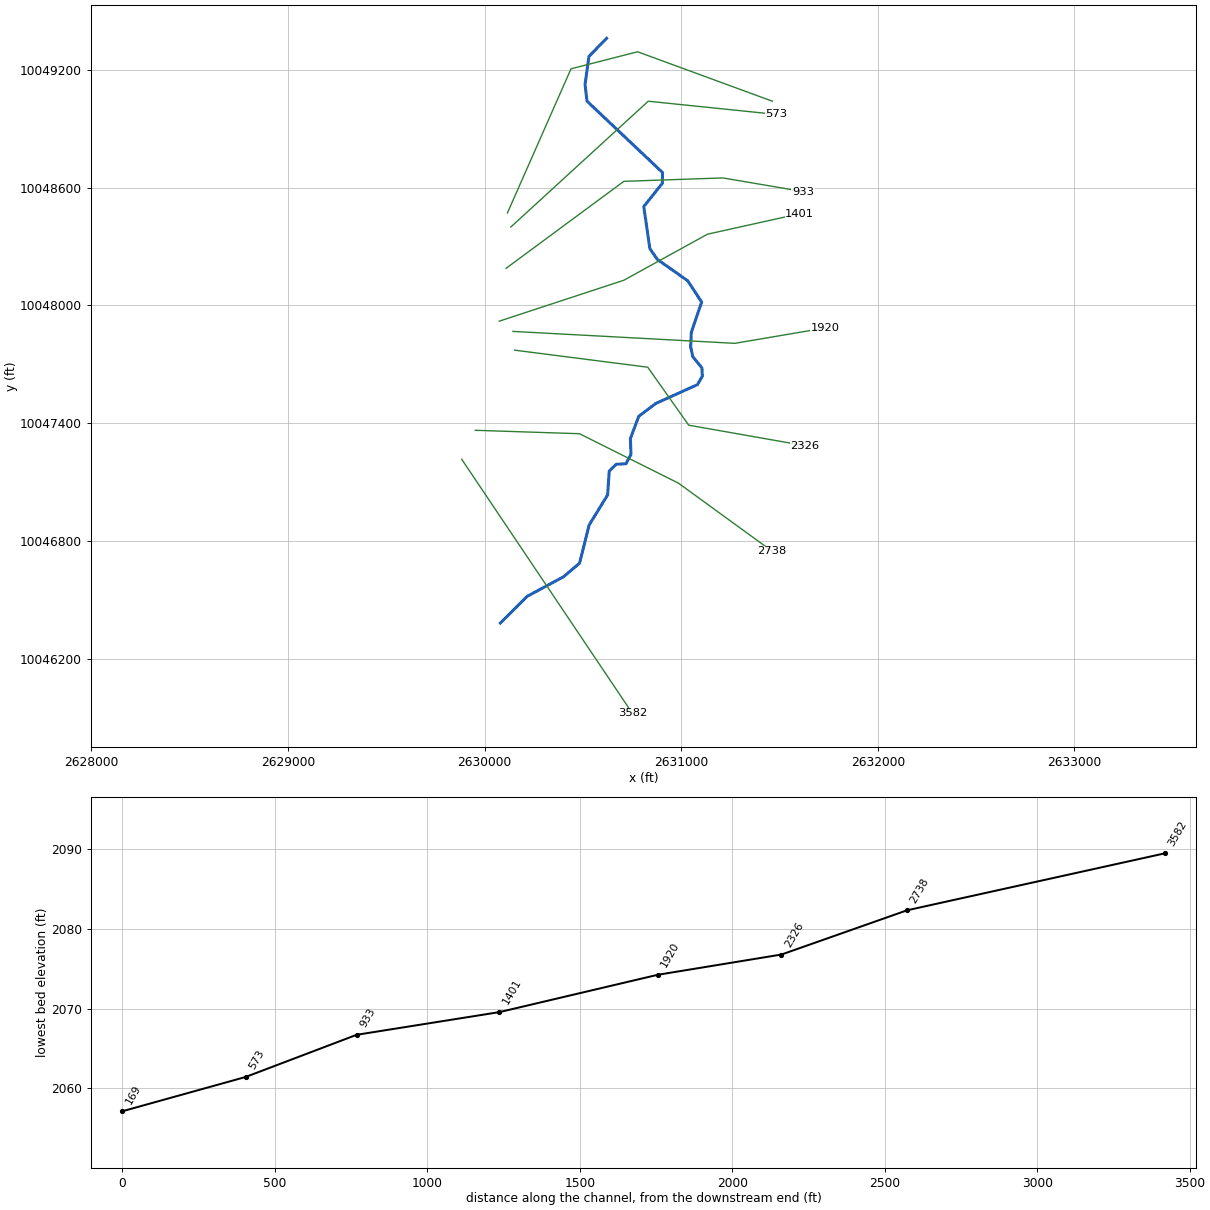
--- UNT 1040 IN HEWA.prj (project) ---

Proj Title=UNT 1040 IN HEWA Base Level Engineering
Current Plan=p01
Default Exp/Contr=0.3,0.1
English Units
Geom File=g01
Flow File=f01
Plan File=p01
Y Axis Title=Elevation
X Axis Title(PF)=Main Channel Distance
X Axis Title(XS)=Station
BEGIN DESCRIPTION:
UNT 1040 IN HEWA
END DESCRIPTION:
DSS Export Rating Curves= 0
DSS Export Rating Curve Sorted= 0
DSS Export Volume Flow Curves= 0
DXF OffsetX= 0
DXF OffsetY= 0
DXF ScaleX= 1
DXF ScaleY= 10

--- UNT 1040 IN HEWA.p01 (plan) ---

Plan Title=Multiple Run
Short Identifier=Multiple
Geom File=g01
Flow File=f01
Subcritical Flow
K Sum by GR= 0
Std Step Tol= 0.01
Critical Tol= 0.01
Num of Std Step Trials= 20
Max Error Tol= 0.3
Flow Tol Ratio= 0.001
Split Flow NTrial= 30
Split Flow Tol= 0.02
Split Flow Ratio= 0.02
Log Output Level= 0
Friction Slope Method= 1
Unsteady Friction Slope Method= 2
Unsteady Bridges Friction Slope Method= 1
Parabolic Critical Depth
Global Vel Dist=  1 , 1 , 1
Global Log Level= 0
CheckData=True
Encroach Param= -1, 0, 0, 0
BEGIN DESCRIPTION:
Multiple Run
END DESCRIPTION:

--- UNT 1040 IN HEWA.f01 (steady flow) ---

Flow Title=Multiple
Number of Profiles=7
Profile Names=10-year,25-year,50-year,1pct_min,100-year,1pct_plu,500-year
River Rch & RM= UNT 1040 IN HEWA,Reach-1,3582
    1087    1571    1985    1827    2470    3341    3827
Boundary for River Rch & Prof#=UNT 1040 IN HEWA,Reach-1,1
Up Type=0
Dn Type=3
Dn Slope=0.005
Boundary for River Rch & Prof#=UNT 1040 IN HEWA,Reach-1,2
Up Type=0
Dn Type=3
Dn Slope=0.005
Boundary for River Rch & Prof#=UNT 1040 IN HEWA,Reach-1,3
Up Type=0
Dn Type=3
Dn Slope=0.005
Boundary for River Rch & Prof#=UNT 1040 IN HEWA,Reach-1,4
Up Type=0
Dn Type=3
Dn Slope=0.005
Boundary for River Rch & Prof#=UNT 1040 IN HEWA,Reach-1,5
Up Type=0
Dn Type=3
Dn Slope=0.005
Boundary for River Rch & Prof#=UNT 1040 IN HEWA,Reach-1,6
Up Type=0
Dn Type=3
Dn Slope=0.005
Boundary for River Rch & Prof#=UNT 1040 IN HEWA,Reach-1,7
Up Type=0
Dn Type=3
Dn Slope=0.005

--- UNT 1040 IN HEWA.g01 (geometry) ---

Geom Title=Existing Conditions
Program Version=4.10

River Reach=UNT 1040 IN HEWA,Reach-1
Reach XY= 30
      2630080.12     10046382.86      2630216.05     10046518.67
      2630401.25     10046618.48      2630482.56     10046687.27
      2630531.81     10046882.35      2630625.54     10047035.02
      2630633.69     10047156.39      2630669.14     10047190.96
      2630718.47     10047193.73      2630744.35     10047240.91
      2630741.43     10047322.54      2630783.79     10047435.31
      2630869.85     10047500.34      2631082.22     10047596.34
      2631107.32     10047639.36      2631105.09     10047682.01
      2631058.69     10047738.82      2631047.96     10047788.63
      2631051.17     10047862.58      2631103.92     10048016.62
      2631032.97      10048125.2      2630878.32     10048234.07
       2630840.2      10048289.4      2630809.46     10048503.22
       2630904.1      10048621.6      2630904.47     10048676.47
      2630520.61     10049039.65      2630510.81     10049123.78
       2630530.6      10049267.5      2630620.39     10049359.34

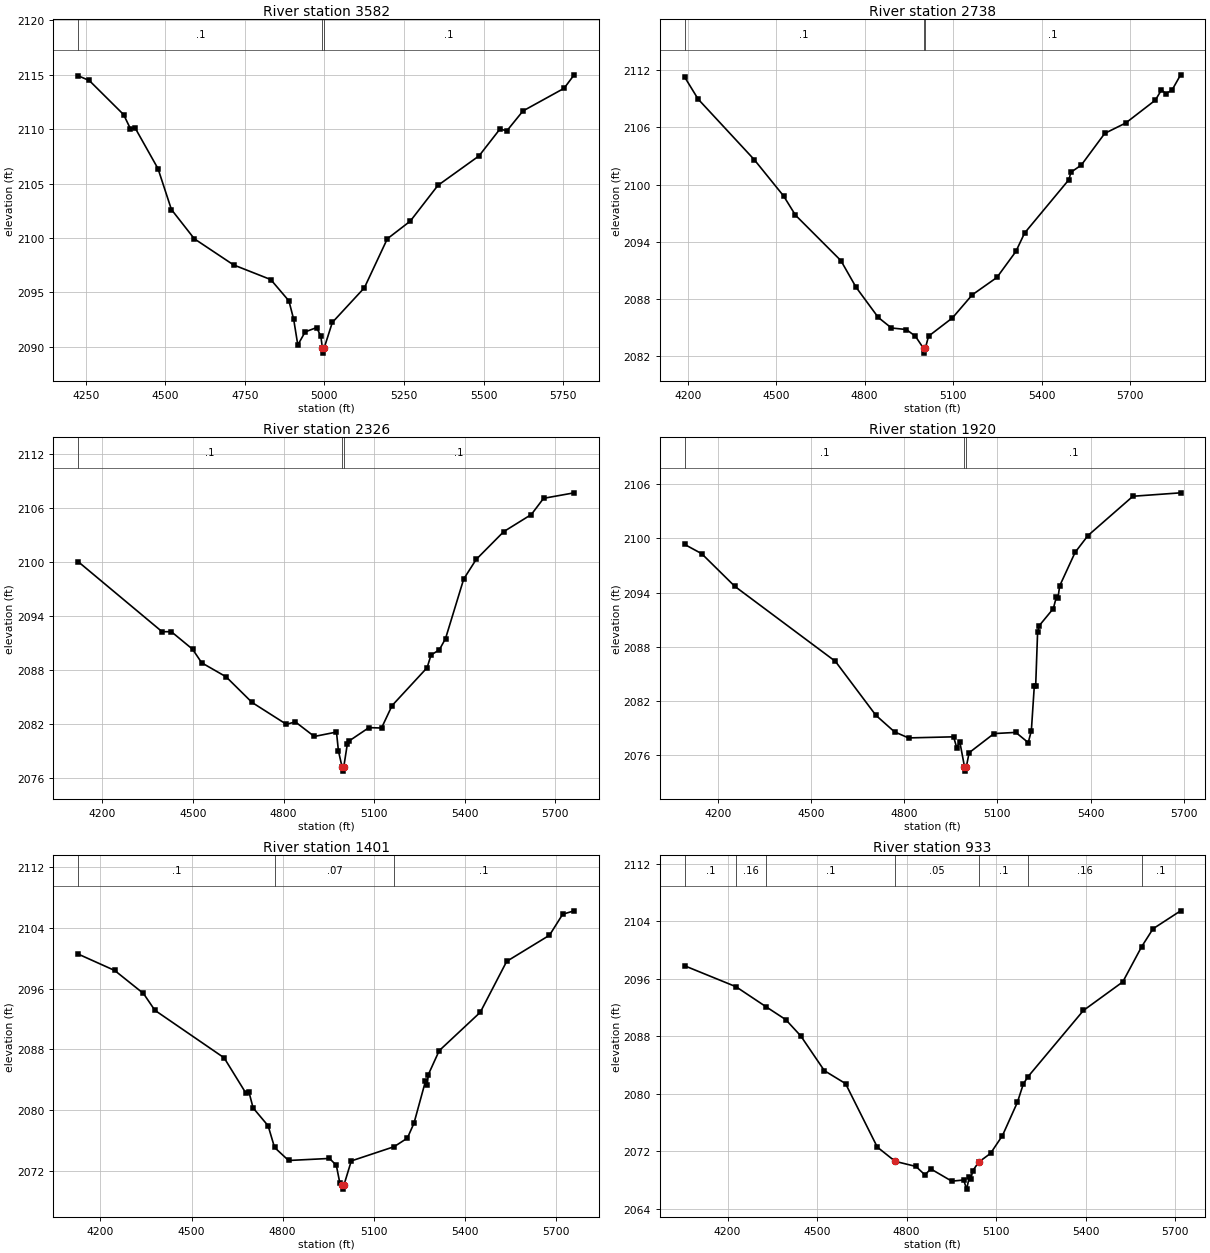
Type RM Length L Ch R = 1 ,3582    ,844,844,844
BEGIN DESCRIPTION:
UNT 1040 IN HEWA 8.0
END DESCRIPTION:
XS GIS Cut Line= 2
      2629883.48     10047216.45      2630751.54     10045923.04
#Sta/Elev= 30
  4226.7 2114.91  4261.3 2114.48  4369.4 2111.34  4390.4 2110.06  4405.4 2110.12
  4477.4 2106.37  4519.4 2102.62  4591.4 2099.93  4714.5 2097.53  4831.5 2096.18
  4888.5 2094.22  4903.5 2092.52  4916.4 2090.17  4939.5 2091.37  4975.5 2091.77
  4988.7 2090.98  4993.5 2089.92  4996.3 2089.42  4999.5 2089.92  5024.8 2092.24
  5125.6 2095.43  5197.6 2099.93  5269.6 2101.55  5356.6 2104.84  5485.7 2107.55
  5551.7 2110.03  5572.7 2109.84  5623.7 2111.68  5752.7 2113.76  5784.4    2115
#Mann= 3 ,-1 , 0
  4226.7      .1       0  4993.5     .07       0  4999.5      .1       0
Bank Sta=4993.5,4999.5
XS Rating Curve= 0 ,0
Exp/Cntr=0.3,0.1

Type RM Length L Ch R = 1 ,2738    ,412,412,412
BEGIN DESCRIPTION:
UNT 1040 IN HEWA 7.0
END DESCRIPTION:
XS GIS Cut Line= 4
      2629952.92     10047364.02      2630482.44     10047346.66
      2630985.91     10047094.93      2631462.66      10046748.2
#Sta/Elev= 30
  4189.5 2111.29  4235.1 2108.98  4425.2 2102.63  4525.2  2098.8  4565.3 2096.79
  4719.3 2092.02  4770.8 2089.22  4846.1 2086.05  4890.9 2084.94  4941.2 2084.78
    4972 2084.08  4999.7  2082.8  5002.4  2082.3  5005.7  2082.8  5016.7 2084.08
  5097.7    2086  5164.8 2088.42  5248.6 2090.25    5313 2092.98  5342.4 2094.91
  5493.1 2100.53  5499.3 2101.29  5534.8 2102.05  5614.4 2105.38  5685.5 2106.47
    5786 2108.87  5806.8 2109.95  5821.5 2109.56  5842.4 2109.92  5871.7 2111.53
#Mann= 3 ,-1 , 0
  4189.5      .1       0  4999.7     .07       0  5005.7      .1       0
Bank Sta=4999.7,5005.7
XS Rating Curve= 0 ,0
Exp/Cntr=0.3,0.1

Type RM Length L Ch R = 1 ,2326    ,406,406,406
BEGIN DESCRIPTION:
UNT 1040 IN HEWA 5.0
END DESCRIPTION:
XS GIS Cut Line= 4
      2630152.62       10047772.      2630829.66      10047685.2
      2631037.99     10047390.07      2631628.23     10047285.91
#Sta/Elev= 30
  4119.7 2100.02  4397.8 2092.24  4428.1 2092.25  4498.6  2090.3  4528.9 2088.79
  4609.5 2087.24  4695.6 2084.39  4809.5 2081.96  4839.1 2082.23    4902 2080.61
  4975.4  2081.1  4981.9    2079  4993.7 2077.26  4996.5 2076.76  4999.7 2077.26
  5011.5  2079.8  5017.6 2080.12  5082.9 2081.59  5124.7 2081.55  5159.6 2084.04
  5275.7 2088.25  5288.6 2089.65  5316.3 2090.24  5336.7 2091.48  5396.9 2098.09
  5438.2 2100.27  5529.6 2103.36    5621 2105.26  5661.6 2107.06  5762.9 2107.67
#Mann= 3 ,-1 , 0
  4119.7      .1       0  4993.7     .07       0  4999.7      .1       0
Bank Sta=4993.7,4999.7
XS Rating Curve= 0 ,0
Exp/Cntr=0.3,0.1

Type RM Length L Ch R = 1 ,1920    ,519,519,519
BEGIN DESCRIPTION:
UNT 1040 IN HEWA 4.0
END DESCRIPTION:
XS GIS Cut Line= 3
      2630143.88      10047867.5      2631272.37     10047806.73
      2631732.45     10047884.86
#Sta/Elev= 30
  4093.3 2099.33    4148 2098.31  4254.7 2094.69  4578.6 2086.38  4708.8 2080.41
  4768.9 2078.57  4814.1  2077.9  4959.1 2078.02  4969.2 2076.83  4979.2 2077.45
  4994.2 2074.72    4997 2074.22  5000.2 2074.72  5009.2 2076.26  5089.3 2078.38
  5159.4 2078.51  5199.5 2077.38  5209.5  2078.7    5219 2083.65  5223.4 2083.65
  5229.6  2089.6    5235 2090.34  5280.3 2092.23  5290.3 2093.55  5295.3 2093.41
  5300.6 2094.73  5350.5 2098.46  5391.9 2100.32  5536.5 2104.67  5690.1 2105.05
#Mann= 3 ,-1 , 0
  4093.3      .1       0  4994.2     .07       0  5000.2      .1       0
Bank Sta=4994.2,5000.2
XS Rating Curve= 0 ,0
Exp/Cntr=0.3,0.1

Type RM Length L Ch R = 1 ,1401    ,468,468,468
BEGIN DESCRIPTION:
UNT 1040 IN HEWA 3.0
END DESCRIPTION:
XS GIS Cut Line= 4
      2630074.44     10047919.58      2630708.13     10048127.91
      2631133.48     10048362.29      2631602.24     10048466.46
#Sta/Elev= 30
  4126.9 2100.57  4246.9 2098.41  4341.7 2095.37  4379.4 2093.15  4607.3 2086.88
  4678.5 2082.25    4689 2082.38  4702.7 2080.27  4752.2 2077.91  4773.3 2075.05
  4819.6 2073.33  4954.2  2073.6  4976.7  2072.7  4988.4 2070.34  4995.5 2070.05
  4998.3 2069.55  5001.5 2070.05    5026 2073.27    5167 2075.15  5210.6 2076.28
  5232.4 2078.25  5270.2 2083.79  5275.9 2083.26  5279.6 2084.66  5315.4 2087.82
  5450.7 2092.89  5537.7 2099.61  5678.6 2103.06  5722.1 2105.83  5759.8 2106.28
#Mann= 3 ,-1 , 0
  4126.9      .1       0  4773.3     .07       0    5167      .1       0
Bank Sta=4995.5,5001.5
XS Rating Curve= 0 ,0
Exp/Cntr=0.3,0.1

Type RM Length L Ch R = 1 ,933     ,364,364,364
BEGIN DESCRIPTION:
UNT 1040 IN HEWA 2.0
END DESCRIPTION:
XS GIS Cut Line= 4
      2630109.14     10048188.66      2630708.13     10048631.39
       2631211.6     10048648.75      2631619.62      10048579.3
#Sta/Elev= 30
  4056.1 2097.82    4228 2094.91  4330.2 2092.08    4395 2090.32  4445.1 2088.06
  4524.4 2083.21  4595.4 2081.41  4701.9 2072.56  4760.3 2070.63  4761.7 2070.58
  4831.3 2069.87  4861.3  2068.7  4881.3 2069.52  4951.4 2067.82  4991.4 2067.98
  5001.2 2066.71  5010.3 2068.39  5015.3 2068.06  5021.4 2069.24  5041.4 2070.46
  5081.4 2071.69  5121.5 2074.18  5171.5 2078.81  5191.5 2081.38  5207.1 2082.38
  5392.8  2091.6  5524.7 2095.58  5587.9 2100.48  5626.1 2102.98  5718.6 2105.48
#Mann= 7 ,-1 , 0
  4056.1      .1       0    4228     .16       0  4330.2      .1       0
  4760.3     .05       0  5041.4      .1       0  5207.1     .16       0
  5587.9      .1       0
Bank Sta=4761.7,5041.4
XS Rating Curve= 0 ,0
Exp/Cntr=0.3,0.1

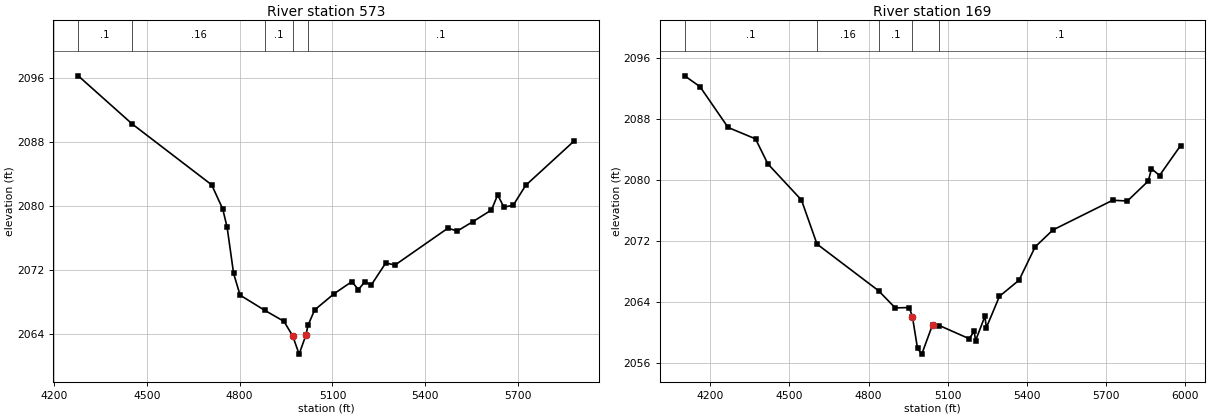
Type RM Length L Ch R = 1 ,573     ,404,404,404
BEGIN DESCRIPTION:
Mapping XS cafddeb4
END DESCRIPTION:
XS GIS Cut Line= 3
       2630133.4     10048399.04      2630832.17     10049039.22
      2631484.43     10048972.05
#Sta/Elev= 30
    4278 2096.25  4452.7 2090.22  4709.5 2082.61  4745.2 2079.59  4759.4 2077.31
  4780.4 2071.52  4801.3 2068.81  4881.9 2066.89  4943.2 2065.53  4971.5  2063.7
  4992.2 2061.43  5014.1  2063.8  5020.9 2065.03  5042.4 2066.96    5106 2069.01
  5162.7  2070.5  5183.7 2069.51  5205.2 2070.49  5225.3 2070.07  5272.2 2072.83
  5302.4 2072.58  5473.3 2077.19  5503.4 2076.83  5553.7    2078    5614 2079.46
  5634.1 2081.35  5654.2 2079.83  5684.4 2080.05  5724.6 2082.54  5881.4  2088.1
#Mann= 5 ,-1 , 0
    4278      .1       0  4452.7     .16       0  4881.9      .1       0
  4971.5     .07       0  5020.9      .1       0
Bank Sta=4971.5,5014.1
XS Rating Curve= 0 ,0
Exp/Cntr=0.3,0.1

Type RM Length L Ch R = 1 ,169     ,0,0,0
BEGIN DESCRIPTION:
UNT 1040 IN HEWA 1.0
END DESCRIPTION:
XS GIS Cut Line= 4
      2630116.01     10048470.61      2630439.38     10049204.16
      2630777.92     10049290.96      2631463.53     10049039.28
#Sta/Elev= 30
  4102.5  2093.6  4160.6 2092.18  4267.1 2086.84  4371.3 2085.34  4417.9 2082.07
  4545.5 2077.33  4604.5 2071.56  4837.9 2065.45  4901.2  2063.2  4954.8 2063.24
  4966.6 2062.01  4985.8  2057.9    5002 2057.14    5043    2061  5068.4 2060.89
    5182 2059.16  5200.9 2060.14  5206.1 2058.91  5241.7 2062.11  5246.9  2060.6
  5296.8 2064.72  5371.1 2066.83  5432.1 2071.19  5499.2  2073.4  5726.3  2077.3
    5782  2077.2  5861.4 2079.82  5873.5 2081.44    5904 2080.54    5984 2084.47
#Mann= 5 ,-1 , 0
  4102.5      .1       0  4604.5     .16       0  4837.9      .1       0
  4966.6     .07       0  5068.4      .1       0
Bank Sta=4966.6,5043
XS Rating Curve= 0 ,0
Exp/Cntr=0.3,0.1

Chan Stop Cuts=-1
Use User Specified Reach Order=0
Composite Channel Slope=5