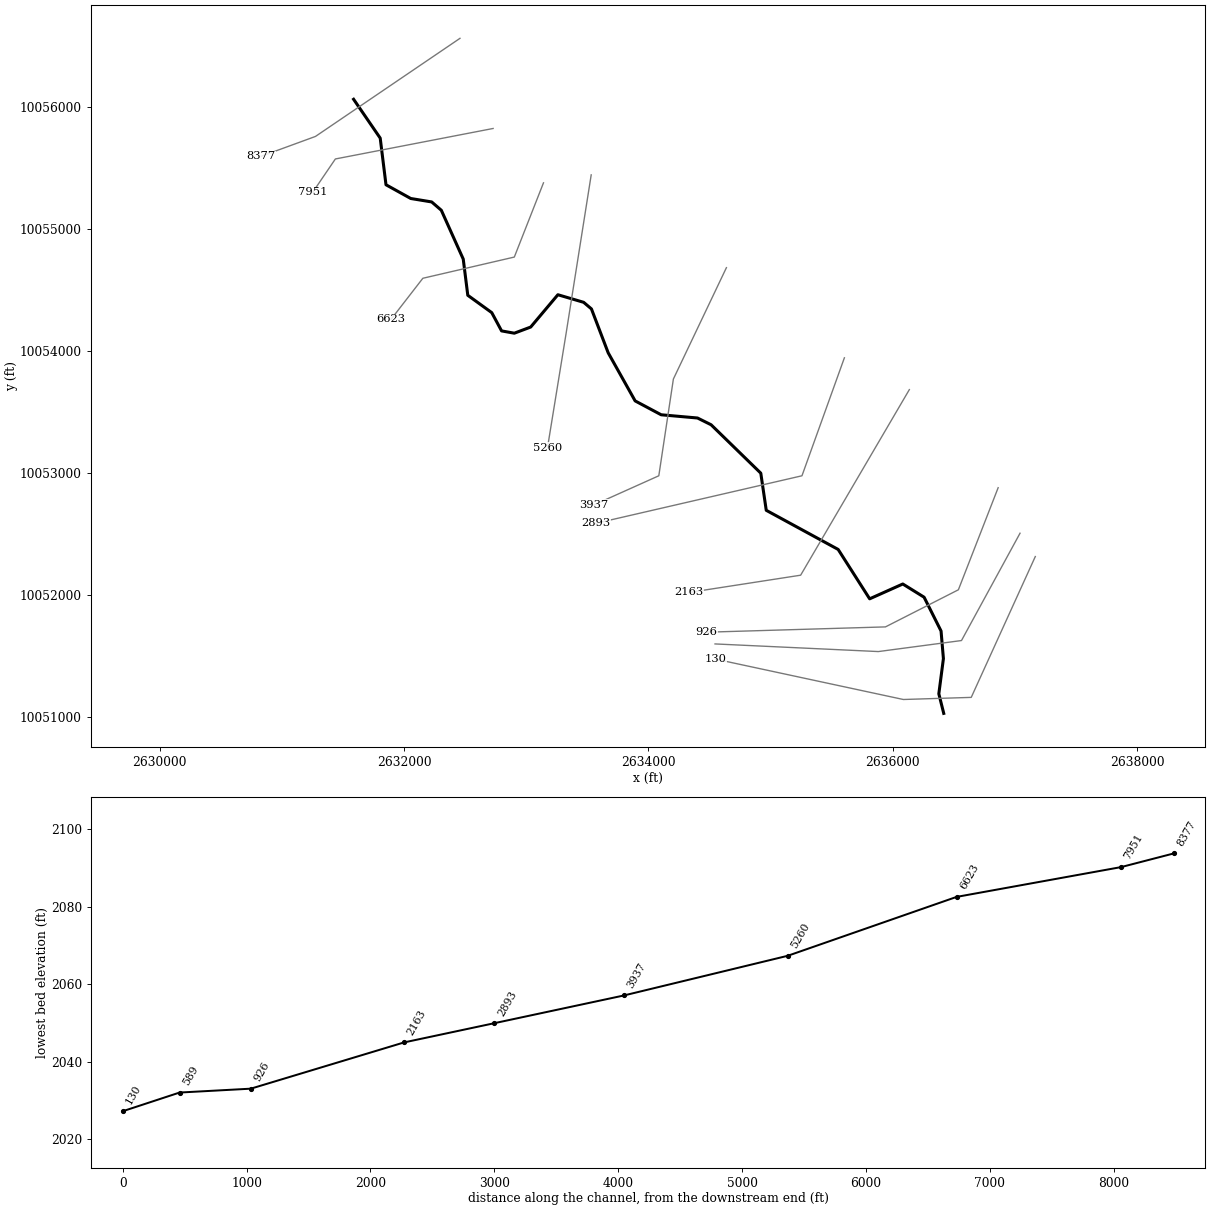
--- UNT 1041 IN HEWA.prj (project) ---

Proj Title=UNT 1041 IN HEWA Base Level Engineering
Current Plan=p01
Default Exp/Contr=0.3,0.1
English Units
Geom File=g01
Flow File=f01
Plan File=p01
Y Axis Title=Elevation
X Axis Title(PF)=Main Channel Distance
X Axis Title(XS)=Station
BEGIN DESCRIPTION:
UNT 1041 IN HEWA
END DESCRIPTION:
DSS Export Rating Curves= 0
DSS Export Rating Curve Sorted= 0
DSS Export Volume Flow Curves= 0
DXF OffsetX= 0
DXF OffsetY= 0
DXF ScaleX= 1
DXF ScaleY= 10

--- UNT 1041 IN HEWA.p01 (plan) ---

Plan Title=Multiple Run
Short Identifier=Multiple
Geom File=g01
Flow File=f01
Subcritical Flow
K Sum by GR= 0
Std Step Tol= 0.01
Critical Tol= 0.01
Num of Std Step Trials= 20
Max Error Tol= 0.3
Flow Tol Ratio= 0.001
Split Flow NTrial= 30
Split Flow Tol= 0.02
Split Flow Ratio= 0.02
Log Output Level= 0
Friction Slope Method= 1
Unsteady Friction Slope Method= 2
Unsteady Bridges Friction Slope Method= 1
Parabolic Critical Depth
Global Vel Dist=  1 , 1 , 1
Global Log Level= 0
CheckData=True
Encroach Param= -1, 0, 0, 0
BEGIN DESCRIPTION:
Multiple Run
END DESCRIPTION:

--- UNT 1041 IN HEWA.f01 (steady flow) ---

Flow Title=Multiple
Number of Profiles=7
Profile Names=10-year,25-year,50-year,1pct_min,100-year,1pct_plu,500-year
River Rch & RM= UNT 1041 IN HEWA,Reach-1,8377
    1066    1550    1967    1819    2460    3327    3849
River Rch & RM= UNT 1041 IN HEWA,Reach-1,7951
    1516    2234    2860    2663    3602    4871    5718
Boundary for River Rch & Prof#=UNT 1041 IN HEWA,Reach-1,1
Up Type=0
Dn Type=3
Dn Slope=0.005
Boundary for River Rch & Prof#=UNT 1041 IN HEWA,Reach-1,2
Up Type=0
Dn Type=3
Dn Slope=0.005
Boundary for River Rch & Prof#=UNT 1041 IN HEWA,Reach-1,3
Up Type=0
Dn Type=3
Dn Slope=0.005
Boundary for River Rch & Prof#=UNT 1041 IN HEWA,Reach-1,4
Up Type=0
Dn Type=3
Dn Slope=0.005
Boundary for River Rch & Prof#=UNT 1041 IN HEWA,Reach-1,5
Up Type=0
Dn Type=3
Dn Slope=0.005
Boundary for River Rch & Prof#=UNT 1041 IN HEWA,Reach-1,6
Up Type=0
Dn Type=3
Dn Slope=0.005
Boundary for River Rch & Prof#=UNT 1041 IN HEWA,Reach-1,7
Up Type=0
Dn Type=3
Dn Slope=0.005

--- UNT 1041 IN HEWA.g01 (geometry) ---

Geom Title=Existing Conditions
Program Version=4.10

River Reach=UNT 1041 IN HEWA,Reach-1
Reach XY= 30
      2631587.83     10056060.52      2631805.68     10055742.58
      2631853.01     10055360.75      2632055.66     10055248.34
        2632227.     10055220.14      2632305.85     10055152.07
      2632485.33     10054752.39      2632522.57     10054455.95
       2632718.7     10054314.03      2632799.17     10054164.47
      2632903.42     10054145.74      2633037.54     10054196.11
      2633259.99     10054460.58      2633471.01      10054398.5
       2633534.7     10054344.46      2633671.83     10053985.12
      2633892.44      10053591.5      2634105.48     10053477.92
      2634402.84     10053451.56      2634514.31     10053396.15
      2634920.95     10052999.97      2634965.71     10052695.88
      2635554.31     10052375.61      2635812.07     10051971.42
      2636083.42     10052092.75       2636257.7     10051984.69
      2636396.53     10051707.93      2636415.82     10051481.93
      2636378.28     10051193.82      2636418.47     10051033.73

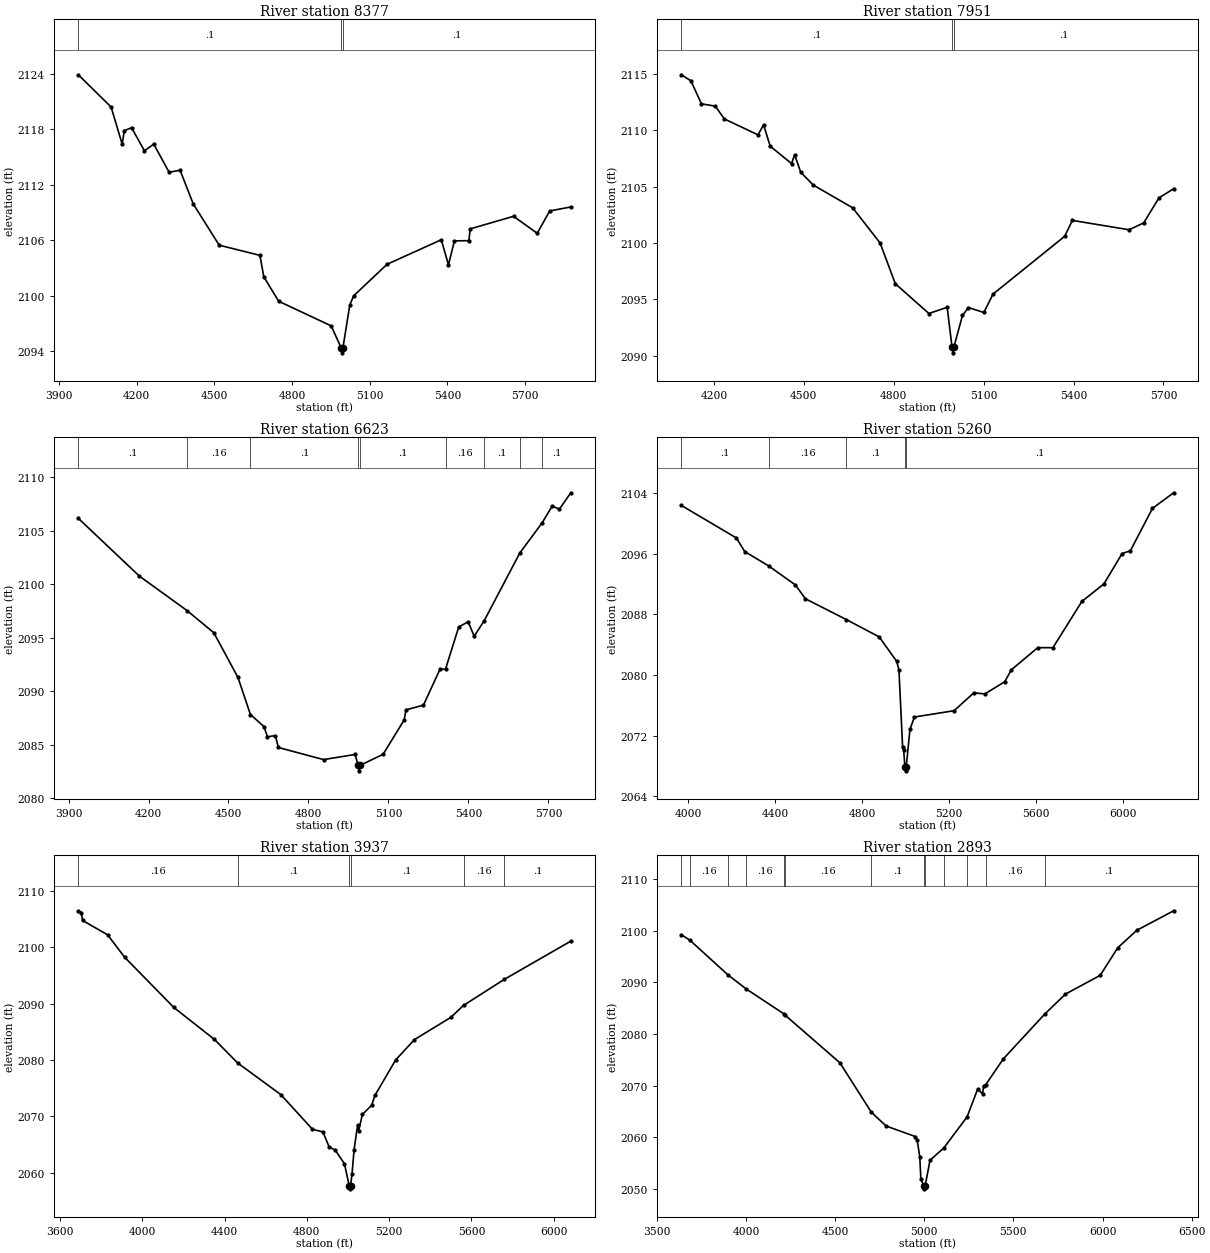
Type RM Length L Ch R = 1 ,8377    ,426,426,426
BEGIN DESCRIPTION:
UNT 1041 IN HEWA 19.0
END DESCRIPTION:
XS GIS Cut Line= 3
       2632458.6     10056559.36      2631275.84     10055756.39
      2630832.18     10055594.07
#Sta/Elev= 30
  3974.3 2123.91  4100.7 2120.42  4143.7 2116.39  4151.6 2117.86  4179.9 2118.18
  4229.5 2115.67  4265.4  2116.4    4325 2113.35  4367.2 2113.57  4418.1 2109.92
  4518.4 2105.45  4675.7 2104.35  4690.6 2102.03    4748 2099.38    4951 2096.71
    4990 2094.29  4992.8 2093.79    4996 2094.29  5022.9 2098.99  5037.8 2099.97
  5166.6 2103.38  5376.2 2106.04  5403.9 2103.32  5426.9 2105.92  5482.7 2105.94
    5488 2107.22  5655.2 2108.58  5746.7 2106.74  5795.1 2109.16  5876.3 2109.59
#Mann= 3 ,-1 , 0
  3974.3      .1       0    4990     .07       0    4996      .1       0
Bank Sta=4990,4996
XS Rating Curve= 0 ,0
Exp/Cntr=0.3,0.1

Type RM Length L Ch R = 1 ,7951    ,1328,1328,1328
BEGIN DESCRIPTION:
UNT 1041 IN HEWA 16.0
END DESCRIPTION:
XS GIS Cut Line= 3
      2632729.87      10055821.5       2631438.6     10055571.92
      2631254.15     10055300.67
#Sta/Elev= 30
    4091 2114.93    4123  2114.4  4158.5 2112.35  4204.5 2112.15    4235 2111.01
  4347.1  2109.6  4365.7 2110.49  4387.8  2108.6  4459.1 2107.05  4469.3 2107.84
  4489.7 2106.28  4531.3 2105.15  4662.8 2103.13  4754.5 2100.01  4805.4 2096.39
  4917.4 2093.75  4978.5  2094.3  4994.6 2090.76  4997.4 2090.26  5000.6 2090.76
  5029.5 2093.58  5049.4 2094.28  5100.8 2093.84  5131.3 2095.47  5370.5  2100.6
  5396.1 2102.01  5585.4 2101.18  5634.3 2101.79  5685.1 2104.01  5734.2 2104.82
#Mann= 3 ,-1 , 0
    4091      .1       0  4994.6     .07       0  5000.6      .1       0
Bank Sta=4994.6,5000.6
XS Rating Curve= 0 ,0
Exp/Cntr=0.3,0.1

Type RM Length L Ch R = 1 ,6623    ,1363,1363,1363
BEGIN DESCRIPTION:
UNT 1041 IN HEWA 13.0
END DESCRIPTION:
XS GIS Cut Line= 4
      2633142.15     10055376.59      2632903.44     10054768.97
      2632154.75     10054595.36      2631894.32     10054258.98
#Sta/Elev= 30
  3936.9 2106.15  4165.6 2100.76    4345 2097.53  4444.9 2095.47  4535.6 2091.29
  4582.2 2087.83  4632.9 2086.71  4646.2 2085.75  4675.6 2085.86  4687.2 2084.75
  4856.5 2083.62  4974.7  2084.1  4986.6 2083.07  4989.4 2082.57  4992.6 2083.07
  5080.1 2084.12  5159.4 2087.35  5165.4 2088.26  5231.3 2088.71  5292.9 2092.04
    5314 2092.07  5363.5 2096.01  5398.8 2096.49  5421.5 2095.14    5459 2096.59
  5592.7 2102.92  5675.9 2105.72  5713.9 2107.29  5741.1 2107.01  5783.7 2108.54
#Mann= 9 ,-1 , 0
  3936.9      .1       0    4345     .16       0  4582.2      .1       0
  4986.6     .07       0  4992.6      .1       0    5314     .16       0
    5459      .1       0  5592.7     .16       0  5675.9      .1       0
Bank Sta=4986.6,4992.6
XS Rating Curve= 0 ,0
Exp/Cntr=0.3,0.1

Type RM Length L Ch R = 1 ,5260    ,1323,1323,1323
BEGIN DESCRIPTION:
UNT 1041 IN HEWA 12.0
END DESCRIPTION:
XS GIS Cut Line= 3
      2633532.78     10055441.69      2633326.62     10054139.63
      2633174.89     10053207.58
#Sta/Elev= 30
  3968.8 2102.35  4222.5 2098.05  4260.3 2096.27  4371.8 2094.35  4493.2 2091.87
  4539.3 2090.05  4727.2 2087.31  4877.9 2085.03  4958.9  2081.8  4969.1 2080.68
  4985.9 2070.54    4991 2070.06  4996.4 2067.88  4999.2 2067.38  5002.4 2067.88
  5019.7 2072.83  5039.9 2074.47  5222.2  2075.3  5313.3 2077.66  5363.9 2077.51
  5455.2 2079.12  5485.6 2080.69  5607.1 2083.61  5676.6  2083.6  5809.8  2089.7
  5911.1 2092.01  5994.3    2096  6032.7 2096.38    6134 2101.96  6231.4 2104.01
#Mann= 5 ,-1 , 0
  3968.8      .1       0  4371.8     .16       0  4727.2      .1       0
  4996.4     .07       0  5002.4      .1       0
Bank Sta=4996.4,5002.4
XS Rating Curve= 0 ,0
Exp/Cntr=0.3,0.1

Type RM Length L Ch R = 1 ,3937    ,1044,1044,1044
BEGIN DESCRIPTION:
UNT 1041 IN HEWA 9.0
END DESCRIPTION:
XS GIS Cut Line= 4
      2634639.55     10054682.15      2634205.53     10053770.71
      2634086.17     10052978.61      2633554.45     10052739.88
#Sta/Elev= 30
  3689.4 2106.47  3703.9 2106.16  3709.8 2104.75  3831.6 2102.21  3913.8 2098.25
  4152.8 2089.34  4350.7 2083.65  4463.5 2079.48  4673.4 2073.86  4827.3 2067.71
  4877.9 2067.24  4908.2 2064.59  4938.6 2063.98  4982.6 2061.61  5006.3 2057.64
  5009.1 2057.14  5012.3 2057.64  5019.5 2059.76  5029.6 2064.08  5046.5 2068.38
  5051.6  2067.4    5070 2070.34  5115.5 2071.98  5130.7  2073.7  5231.8 2080.01
  5322.8 2083.61  5499.9 2087.56  5561.5 2089.68  5759.3 2094.29  6082.8 2101.08
#Mann= 6 ,-1 , 0
  3689.4     .16       0  4463.5      .1       0  5006.3     .07       0
  5012.3      .1       0  5561.5     .16       0  5759.3      .1       0
Bank Sta=5006.3,5012.3
XS Rating Curve= 0 ,0
Exp/Cntr=0.3,0.1

Type RM Length L Ch R = 1 ,2893    ,730,730,730
BEGIN DESCRIPTION:
UNT 1041 IN HEWA 6.0
END DESCRIPTION:
XS GIS Cut Line= 3
      2635605.27     10053944.33      2635258.04     10052978.61
      2633566.94     10052588.35
#Sta/Elev= 30
  3637.3 2099.19  3686.3 2098.11  3898.7 2091.43  4001.9 2088.68  4211.7  2083.9
  4220.4  2083.6  4527.3 2074.39  4703.2 2064.84  4786.3 2062.16  4950.5 2060.12
  4960.7 2059.46  4975.2 2056.12  4981.3 2051.85  4998.8  2050.5  5001.5    2050
  5004.8  2050.5  5032.6 2055.53  5109.6  2057.9  5240.4 2063.92  5299.4 2069.28
  5327.6  2068.4  5332.7 2069.95  5345.4 2070.18  5443.1 2075.13  5675.8 2083.82
    5792 2087.69    5987 2091.32  6085.3 2096.65  6192.3 2100.04  6399.1 2103.82
#Mann= 13 ,-1 , 0
  3637.3      .1       0  3686.3     .16       0  3898.7      .1       0
  4001.9     .16       0  4211.7      .1       0  4220.4     .16       0
  4703.2      .1       0  4998.8     .07       0  5004.8      .1       0
  5109.6     .16       0  5240.4      .1       0  5345.4     .16       0
  5675.8      .1       0
Bank Sta=4998.8,5004.8
XS Rating Curve= 0 ,0
Exp/Cntr=0.3,0.1

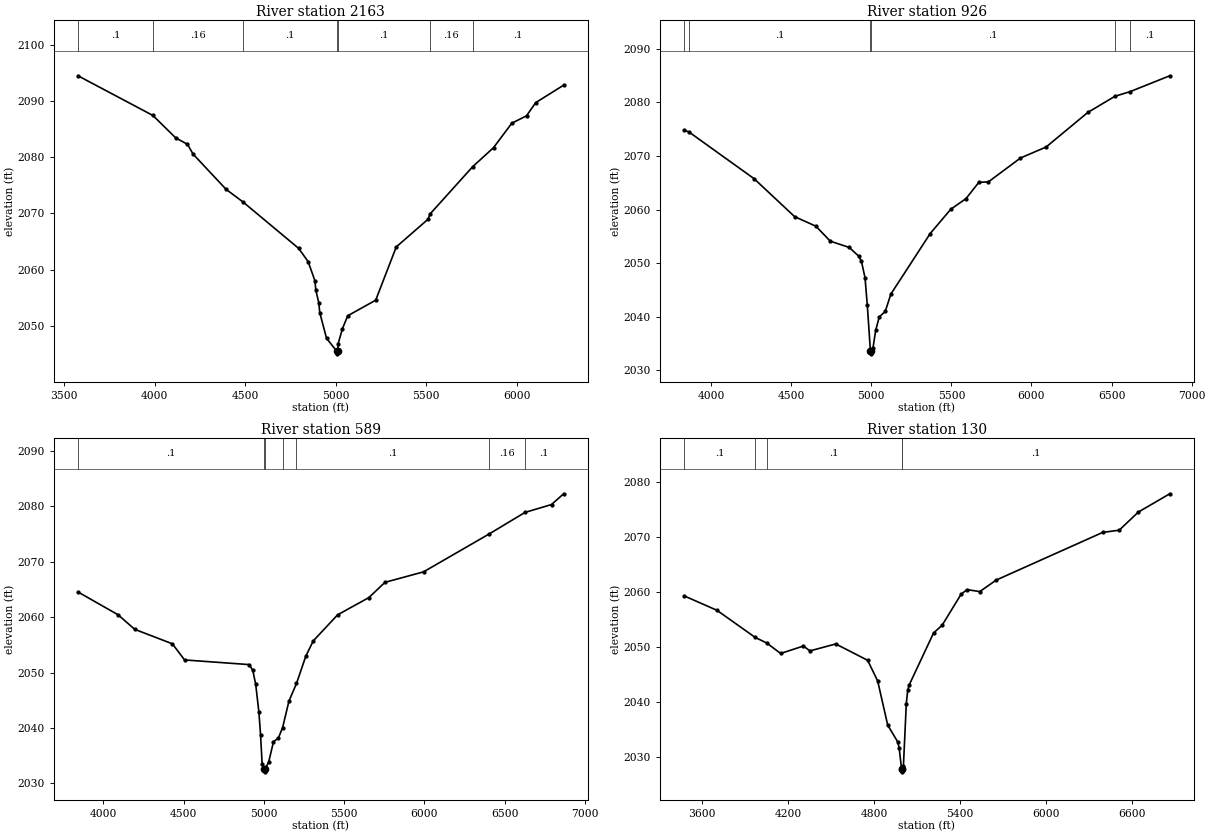
Type RM Length L Ch R = 1 ,2163    ,1237,1237,1237
BEGIN DESCRIPTION:
UNT 1041 IN HEWA 5.0
END DESCRIPTION:
XS GIS Cut Line= 3
      2636136.96     10053683.92      2635247.19     10052164.81
      2634335.75     10052023.75
#Sta/Elev= 30
  3577.3 2094.47  3991.2 2087.41  4117.4 2083.42  4181.9 2082.29  4213.2 2080.54
    4395 2074.29  4489.3 2072.02  4795.7  2063.8  4848.5 2061.44  4885.7 2058.06
  4891.5  2056.3  4907.2 2054.14    4913 2052.35  4950.1 2047.81  5005.8 2045.53
  5008.5 2045.03  5011.8 2045.53  5014.6 2046.85  5037.7 2049.47  5067.4  2051.8
  5221.9 2054.57  5335.5 2064.04  5510.9 2068.96  5522.3  2069.9  5757.2 2078.29
  5872.8 2081.69    5974 2086.04    6055 2087.35  6105.6 2089.69  6260.1  2092.8
#Mann= 7 ,-1 , 0
  3577.3      .1       0  3991.2     .16       0  4489.3      .1       0
  5005.8     .07       0  5011.8      .1       0  5522.3     .16       0
  5757.2      .1       0
Bank Sta=5005.8,5011.8
XS Rating Curve= 0 ,0
Exp/Cntr=0.3,0.1

Type RM Length L Ch R = 1 ,926     ,575,575,575
BEGIN DESCRIPTION:
UNT 1041 IN HEWA 3.0
END DESCRIPTION:
XS GIS Cut Line= 4
      2636863.96     10052880.99      2636538.43     10052045.45
      2635941.64     10051741.63      2634476.78     10051698.22
#Sta/Elev= 30
  3831.4 2074.81  3861.5 2074.46  4268.3 2065.75  4521.1 2058.68  4654.3 2056.89
  4743.9  2054.1  4862.7 2052.93  4921.9 2051.29  4938.5 2050.33  4960.7 2047.28
  4974.9 2042.18  4994.4  2033.6  4997.1  2033.1  5000.4  2033.6  5010.8 2034.28
  5027.5  2037.5  5049.7 2039.99  5087.2 2041.02    5122 2044.24  5367.7 2055.53
  5495.8 2060.05  5591.1 2062.04  5671.1 2065.07  5731.1 2065.16  5931.2 2069.61
  6091.3 2071.66  6351.4  2078.1  6521.2 2081.12  6615.2 2081.98  6863.3 2084.94
#Mann= 6 ,-1 , 0
  3831.4     .16       0  3861.5      .1       0  4994.4     .07       0
  5000.4      .1       0  6521.2     .16       0  6615.2      .1       0
Bank Sta=4994.4,5000.4
XS Rating Curve= 0 ,0
Exp/Cntr=0.3,0.1

Type RM Length L Ch R = 1 ,589     ,459,459,459
BEGIN DESCRIPTION:
Mapping XS 14992ca9
END DESCRIPTION:
XS GIS Cut Line= 4
      2637043.01     10052508.45      2636563.83     10051629.96
      2635883.28     10051539.68      2634546.43     10051602.18
#Sta/Elev= 30
  3842.2 2064.55  4092.2 2060.43  4195.6 2057.81  4430.1  2055.2    4506 2052.29
  4908.8 2051.45  4931.1  2050.4  4949.2 2047.91  4969.3 2042.83  4979.4 2038.81
  4989.5 2033.47  5001.5  2032.6  5004.2  2032.1  5007.5  2032.6  5029.9 2033.84
  5060.1 2037.54  5090.4 2038.19    5117 2040.09  5156.2 2044.85  5203.4 2048.05
  5261.9    2053  5307.9 2055.73  5459.6 2060.43  5654.3 2063.54  5754.5 2066.29
  5994.7 2068.18    6405 2075.04  6626.5  2078.9  6792.2 2080.33  6867.7 2082.27
#Mann= 7 ,-1 , 0
  3842.2      .1       0  5001.5     .07       0  5007.5      .1       0
    5117     .16       0  5203.4      .1       0    6405     .16       0
  6626.5      .1       0
Bank Sta=5001.5,5007.5
XS Rating Curve= 0 ,0
Exp/Cntr=0.3,0.1

Type RM Length L Ch R = 1 ,130     ,0,0,0
BEGIN DESCRIPTION:
UNT 1041 IN HEWA 1.0
END DESCRIPTION:
XS GIS Cut Line= 4
      2637167.98     10052317.42      2636643.69     10051164.68
      2636088.14     10051147.32      2634553.48     10051477.17
#Sta/Elev= 30
    3473 2059.26  3701.8 2056.64  3969.1 2051.71  4049.1  2050.7  4147.2 2048.79
  4305.8 2050.14  4351.9 2049.26  4531.7 2050.52  4754.6 2047.55  4824.6  2043.8
  4894.7 2035.78  4964.7 2032.72  4974.7 2031.65  4991.7 2027.78  4994.5 2027.28
  4997.7 2027.78  5004.7 2028.42  5024.7 2039.69  5034.7 2042.14  5044.7 2043.06
  5214.8  2052.5  5274.9 2053.92  5407.4 2059.55    5449  2060.4  5537.5 2060.03
  5652.8 2062.13  6395.4 2070.78    6512  2071.2    6645 2074.48  6864.9 2077.81
#Mann= 5 ,-1 , 0
    3473      .1       0  3969.1     .05       0  4049.1      .1       0
  4991.7     .07       0  4997.7      .1       0
Bank Sta=4991.7,4997.7
XS Rating Curve= 0 ,0
Exp/Cntr=0.3,0.1

Chan Stop Cuts=-1
Use User Specified Reach Order=0
Composite Channel Slope=5