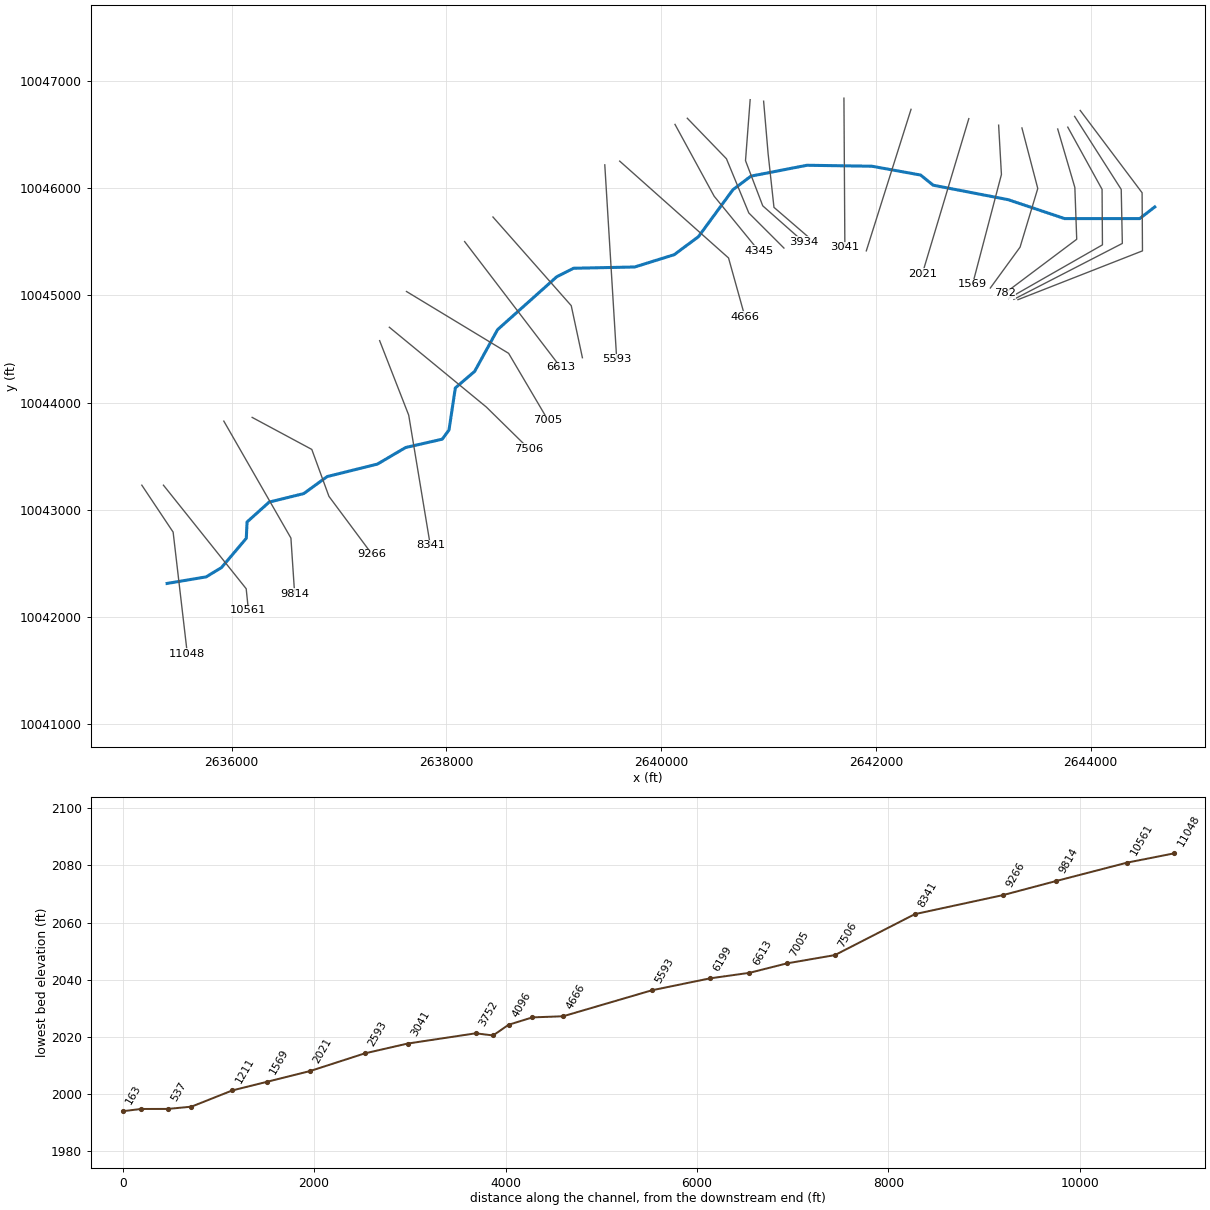
--- UNT 1043 IN HEWA.prj (project) ---

Proj Title=UNT 1043 IN HEWA Base Level Engineering
Current Plan=p01
Default Exp/Contr=0.3,0.1
English Units
Geom File=g01
Flow File=f01
Plan File=p01
Y Axis Title=Elevation
X Axis Title(PF)=Main Channel Distance
X Axis Title(XS)=Station
BEGIN DESCRIPTION:
UNT 1043 IN HEWA
END DESCRIPTION:
DSS Export Rating Curves= 0
DSS Export Rating Curve Sorted= 0
DSS Export Volume Flow Curves= 0
DXF OffsetX= 0
DXF OffsetY= 0
DXF ScaleX= 1
DXF ScaleY= 10

--- UNT 1043 IN HEWA.p01 (plan) ---

Plan Title=Multiple Run
Short Identifier=Multiple
Geom File=g01
Flow File=f01
Subcritical Flow
K Sum by GR= 0
Std Step Tol= 0.01
Critical Tol= 0.01
Num of Std Step Trials= 20
Max Error Tol= 0.3
Flow Tol Ratio= 0.001
Split Flow NTrial= 30
Split Flow Tol= 0.02
Split Flow Ratio= 0.02
Log Output Level= 0
Friction Slope Method= 1
Unsteady Friction Slope Method= 2
Unsteady Bridges Friction Slope Method= 1
Parabolic Critical Depth
Global Vel Dist=  1 , 1 , 1
Global Log Level= 0
CheckData=True
Encroach Param= -1, 0, 0, 0
BEGIN DESCRIPTION:
Multiple Run
END DESCRIPTION:

--- UNT 1043 IN HEWA.f01 (steady flow) ---

Flow Title=Multiple
Number of Profiles=7
Profile Names=10-year,25-year,50-year,1pct_min,100-year,1pct_plu,500-year
River Rch & RM= UNT 1043 IN HEWA,Reach-1,11048
     997    1433    1806    1658    2242    3033    3457
River Rch & RM= UNT 1043 IN HEWA,Reach-1,9814
    1564    2301    2943    2739    3705    5010    5871
River Rch & RM= UNT 1043 IN HEWA,Reach-1,4096
    1867    2771    3565    3335    4511    6100    7224
Boundary for River Rch & Prof#=UNT 1043 IN HEWA,Reach-1,1
Up Type=0
Dn Type=3
Dn Slope=0.005
Boundary for River Rch & Prof#=UNT 1043 IN HEWA,Reach-1,2
Up Type=0
Dn Type=3
Dn Slope=0.005
Boundary for River Rch & Prof#=UNT 1043 IN HEWA,Reach-1,3
Up Type=0
Dn Type=3
Dn Slope=0.005
Boundary for River Rch & Prof#=UNT 1043 IN HEWA,Reach-1,4
Up Type=0
Dn Type=3
Dn Slope=0.005
Boundary for River Rch & Prof#=UNT 1043 IN HEWA,Reach-1,5
Up Type=0
Dn Type=3
Dn Slope=0.005
Boundary for River Rch & Prof#=UNT 1043 IN HEWA,Reach-1,6
Up Type=0
Dn Type=3
Dn Slope=0.005
Boundary for River Rch & Prof#=UNT 1043 IN HEWA,Reach-1,7
Up Type=0
Dn Type=3
Dn Slope=0.005

--- UNT 1043 IN HEWA.g01 (geometry) ---

Geom Title=Existing Conditions
Program Version=4.10

River Reach=UNT 1043 IN HEWA,Reach-1
Reach XY= 30
      2635398.47     10042313.73       2635762.9     10042375.22
      2635905.14     10042461.69       2636136.2     10042734.71
      2636143.28     10042886.68      2636349.18       10043072.
       2636671.4     10043151.47      2636889.99     10043310.22
      2637357.41     10043426.29      2637619.73     10043580.68
      2637961.29     10043658.57      2638024.55     10043744.37
      2638083.35     10044136.54      2638263.43     10044290.88
      2638476.44     10044679.42      2639028.37     10045172.84
      2639184.23     10045251.88      2639754.13     10045263.72
       2640122.2     10045378.44      2640348.08     10045546.49
      2640668.47     10045983.73      2640836.19     10046110.42
      2641358.84     10046212.07      2641963.49     10046202.96
      2642417.45      10046120.9      2642533.93     10046026.23
      2643232.95      10045891.2      2643758.94     10045714.88
      2644458.12     10045714.76      2644598.47     10045823.73

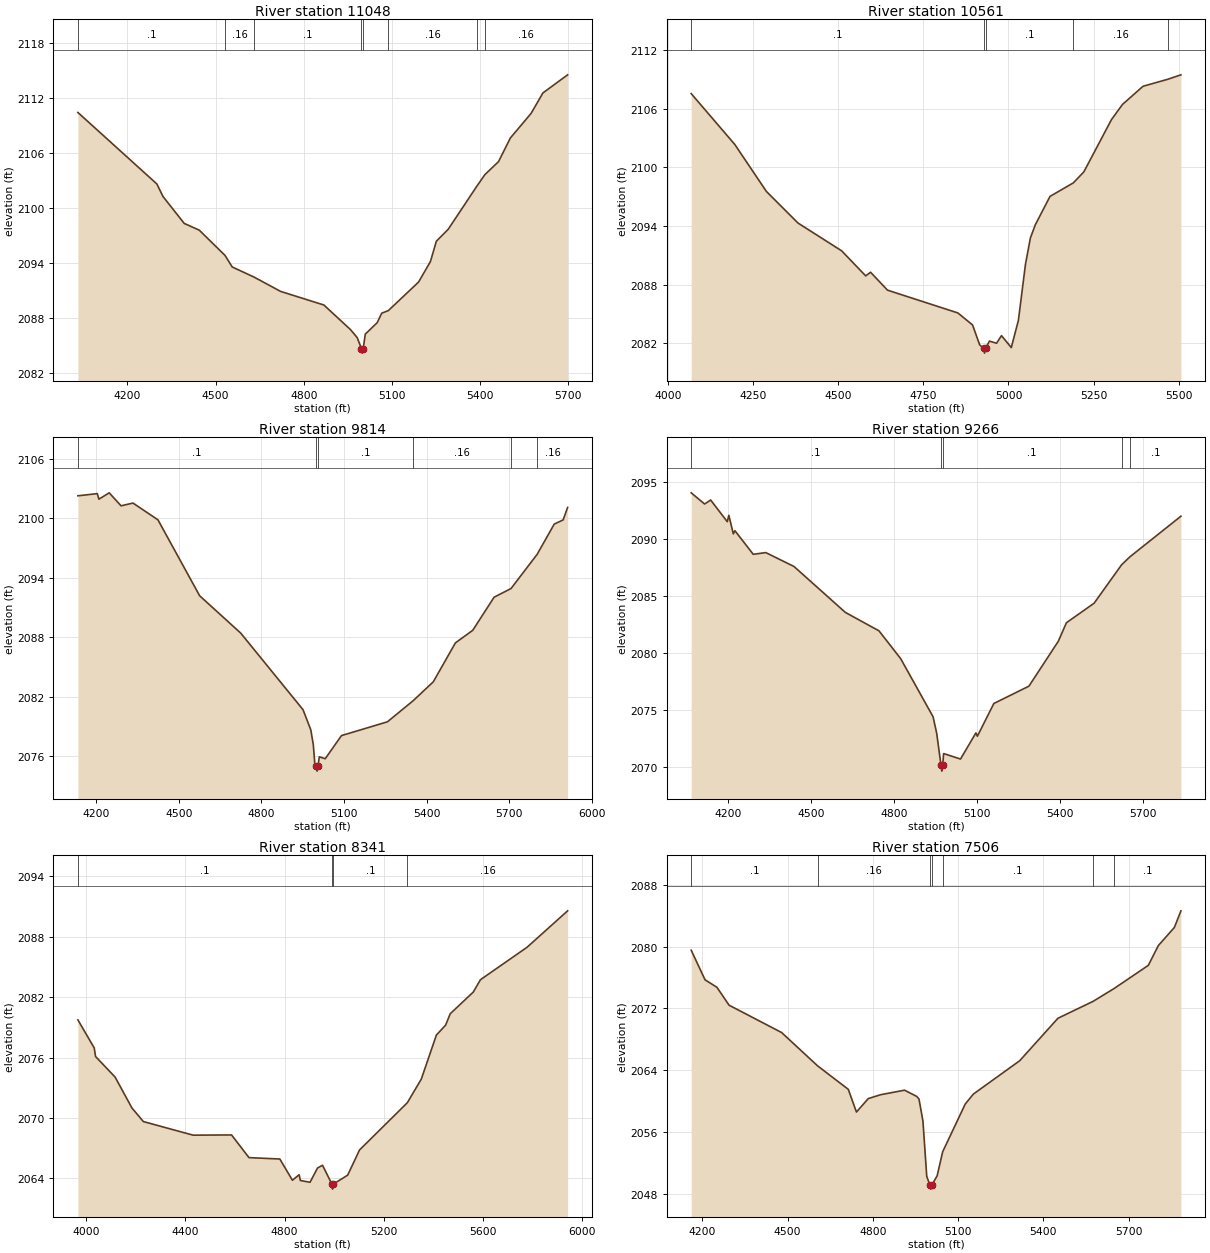
Type RM Length L Ch R = 1 ,11048   ,487,487,487
BEGIN DESCRIPTION:
UNT 1043 IN HEWA 24.0
END DESCRIPTION:
XS GIS Cut Line= 3
      2635162.97     10043229.79      2635454.66     10042792.26
      2635586.61     10041660.27
#Sta/Elev= 30
  4031.8 2110.41  4300.3 2102.63  4321.3 2101.26  4393.4 2098.33  4444.5  2097.6
  4532.1 2094.85  4556.6 2093.59  4630.2  2092.5  4721.2 2090.93  4868.3 2089.45
  4958.9 2086.77  4981.6  2085.9  4996.1 2084.71  4998.9 2084.21  5002.1 2084.71
  5009.2 2086.28  5049.5 2087.52  5065.1 2088.56  5087.6 2088.84  5190.4 2091.95
  5230.7 2094.18  5250.8 2096.39  5291.1 2097.69  5388.4 2102.38  5415.8 2103.64
  5462.3 2105.06  5502.5 2107.63    5573 2110.31  5613.3 2112.54  5697.3 2114.51
#Mann= 8 ,-1 , 0
  4031.8      .1       0  4532.1     .16       0  4630.2      .1       0
  4996.1     .07       0  5002.1      .1       0  5087.6     .16       0
  5388.4      .1       0  5415.8     .16       0
Bank Sta=4996.1,5002.1
XS Rating Curve= 0 ,0
Exp/Cntr=0.3,0.1

Type RM Length L Ch R = 1 ,10561   ,747,747,747
BEGIN DESCRIPTION:
UNT 1043 IN HEWA 23.0
END DESCRIPTION:
XS GIS Cut Line= 3
      2635364.38     10043229.76      2636135.21     10042264.49
      2636156.05     10042063.05
#Sta/Elev= 30
  4068.5 2107.53  4196.5 2102.33  4289.4 2097.52  4382.2 2094.29  4510.3 2091.45
  4580.8 2088.89  4595.2 2089.26  4644.8 2087.43  4851.4  2085.1  4894.6 2083.87
  4915.4 2081.84  4926.8 2081.49  4929.6 2080.99  4932.8 2081.49  4944.2 2082.22
    4965    2082  4979.5 2082.78  5008.3 2081.56  5029.1 2084.34  5049.9 2090.07
  5064.3 2092.76  5078.7 2094.11    5122 2097.02  5190.4  2098.4  5221.2 2099.52
  5302.4 2104.87  5334.7 2106.42    5395 2108.28  5468.2    2109  5506.3 2109.45
#Mann= 5 ,-1 , 0
  4068.5      .1       0  4926.8     .07       0  4932.8      .1       0
  5190.4     .16       0  5468.2      .1       0
Bank Sta=4926.8,4932.8
XS Rating Curve= 0 ,0
Exp/Cntr=0.3,0.1

Type RM Length L Ch R = 1 ,9814    ,548,548,548
BEGIN DESCRIPTION:
UNT 1043 IN HEWA 21.0
END DESCRIPTION:
XS GIS Cut Line= 3
      2635926.86     10043827.02      2636551.88     10042736.71
      2636586.51     10042217.32
#Sta/Elev= 30
  4134.2 2102.25  4204.6 2102.47  4210.4 2101.91  4247.8 2102.55  4290.9 2101.24
  4334.1 2101.52  4424.7 2099.83    4576 2092.18  4725.3 2088.41  4951.2  2080.7
  4979.4 2078.67  4988.6 2077.16  4994.4 2075.08  4999.5 2075.01  5002.2 2074.51
  5005.5 2075.01  5010.2 2075.95  5031.8 2075.76  5090.7 2078.09  5257.6 2079.48
  5350.7  2081.6    5424 2083.51  5504.2 2087.43  5567.2  2088.7  5644.5 2092.03
  5706.2 2092.91    5801 2096.36  5862.9  2099.4  5895.1 2099.82  5911.5 2101.08
#Mann= 6 ,-1 , 0
  4134.2      .1       0  4999.5     .07       0  5005.5      .1       0
  5350.7     .16       0  5706.2      .1       0    5801     .16       0
Bank Sta=4999.5,5005.5
XS Rating Curve= 0 ,0
Exp/Cntr=0.3,0.1

Type RM Length L Ch R = 1 ,9266    ,925,925,925
BEGIN DESCRIPTION:
UNT 1043 IN HEWA 20.0
END DESCRIPTION:
XS GIS Cut Line= 4
      2636190.76     10043861.71      2636746.33      10043563.1
      2636906.05      10043125.6      2637308.84     10042583.92
#Sta/Elev= 30
  4066.7 2094.04  4115.2 2093.06  4137.1 2093.41  4197.2 2091.51  4202.9 2092.07
  4219.1 2090.44  4224.8 2090.72  4291.2 2088.65  4336.6  2088.8  4438.7 2087.58
  4624.1 2083.56    4746 2081.94  4824.5  2079.5  4941.6 2074.41  4954.6 2072.98
  4970.5 2070.14  4973.3 2069.64  4976.5 2070.14  4979.8 2071.18  5040.9  2070.7
  5096.6 2072.99    5102  2072.7  5161.5 2075.57  5288.4 2077.09  5394.8 2081.03
    5424 2082.65  5524.1 2084.36  5623.6 2087.73  5653.7 2088.43  5838.2 2091.99
#Mann= 5 ,-1 , 0
  4066.7      .1       0  4970.5     .07       0  4976.5      .1       0
  5623.6     .16       0  5653.7      .1       0
Bank Sta=4970.5,4976.5
XS Rating Curve= 0 ,0
Exp/Cntr=0.3,0.1

Type RM Length L Ch R = 1 ,8341    ,835,835,835
BEGIN DESCRIPTION:
UNT 1043 IN HEWA 18.0
END DESCRIPTION:
XS GIS Cut Line= 3
      2637378.28     10044576.97       2637649.1     10043882.54
      2637850.37     10042667.97
#Sta/Elev= 30
  3965.8 2079.75  4031.7 2076.96  4037.1 2076.11  4115.9 2074.07  4183.9    2071
    4230 2069.65  4430.8  2068.3    4586 2068.32  4656.2 2066.07  4780.9 2065.93
  4831.6 2063.82  4858.6 2064.37  4863.6  2063.8  4902.6 2063.62    4933 2065.04
  4953.2 2065.31  4990.8 2063.44  4993.5 2062.94  4996.8 2063.44  5054.6 2064.33
  5102.5 2066.83  5295.3 2071.52  5351.6 2073.86  5412.6 2078.24  5449.9 2079.23
  5468.5 2080.36  5561.4 2082.51  5590.5 2083.74  5778.5 2086.96  5942.3 2090.58
#Mann= 4 ,-1 , 0
  3965.8      .1       0  4990.8     .07       0  4996.8      .1       0
  5295.3     .16       0
Bank Sta=4990.8,4996.8
XS Rating Curve= 0 ,0
Exp/Cntr=0.3,0.1

Type RM Length L Ch R = 1 ,7506    ,501,501,501
BEGIN DESCRIPTION:
UNT 1043 IN HEWA 16.0
END DESCRIPTION:
XS GIS Cut Line= 3
      2637468.54       10044702.      2638371.33     10043958.93
      2638767.18     10043570.02
#Sta/Elev= 30
  4160.3 2079.54  4209.1 2075.71  4250.9 2074.74  4293.8 2072.42  4478.8 2068.88
  4605.3 2064.57  4713.4 2061.53  4742.1 2058.59  4783.7 2060.33  4826.8 2060.83
  4911.4 2061.42  4954.5 2060.61  4962.3 2060.28  4976.2 2057.43  4989.6 2050.27
    5001 2049.11  5003.7 2048.61    5007 2049.11  5026.2 2050.33  5045.7 2053.45
  5125.2 2059.63  5153.9 2060.92  5316.8 2065.23  5451.5 2070.73  5575.3 2072.92
  5649.6 2074.59  5769.7 2077.58    5805 2080.14  5861.5 2082.49  5884.5 2084.64
#Mann= 7 ,-1 , 0
  4160.3      .1       0  4605.3     .16       0    5001     .07       0
    5007     .16       0  5045.7      .1       0  5575.3     .05       0
  5649.6      .1       0
Bank Sta=5001,5007
XS Rating Curve= 0 ,0
Exp/Cntr=0.3,0.1

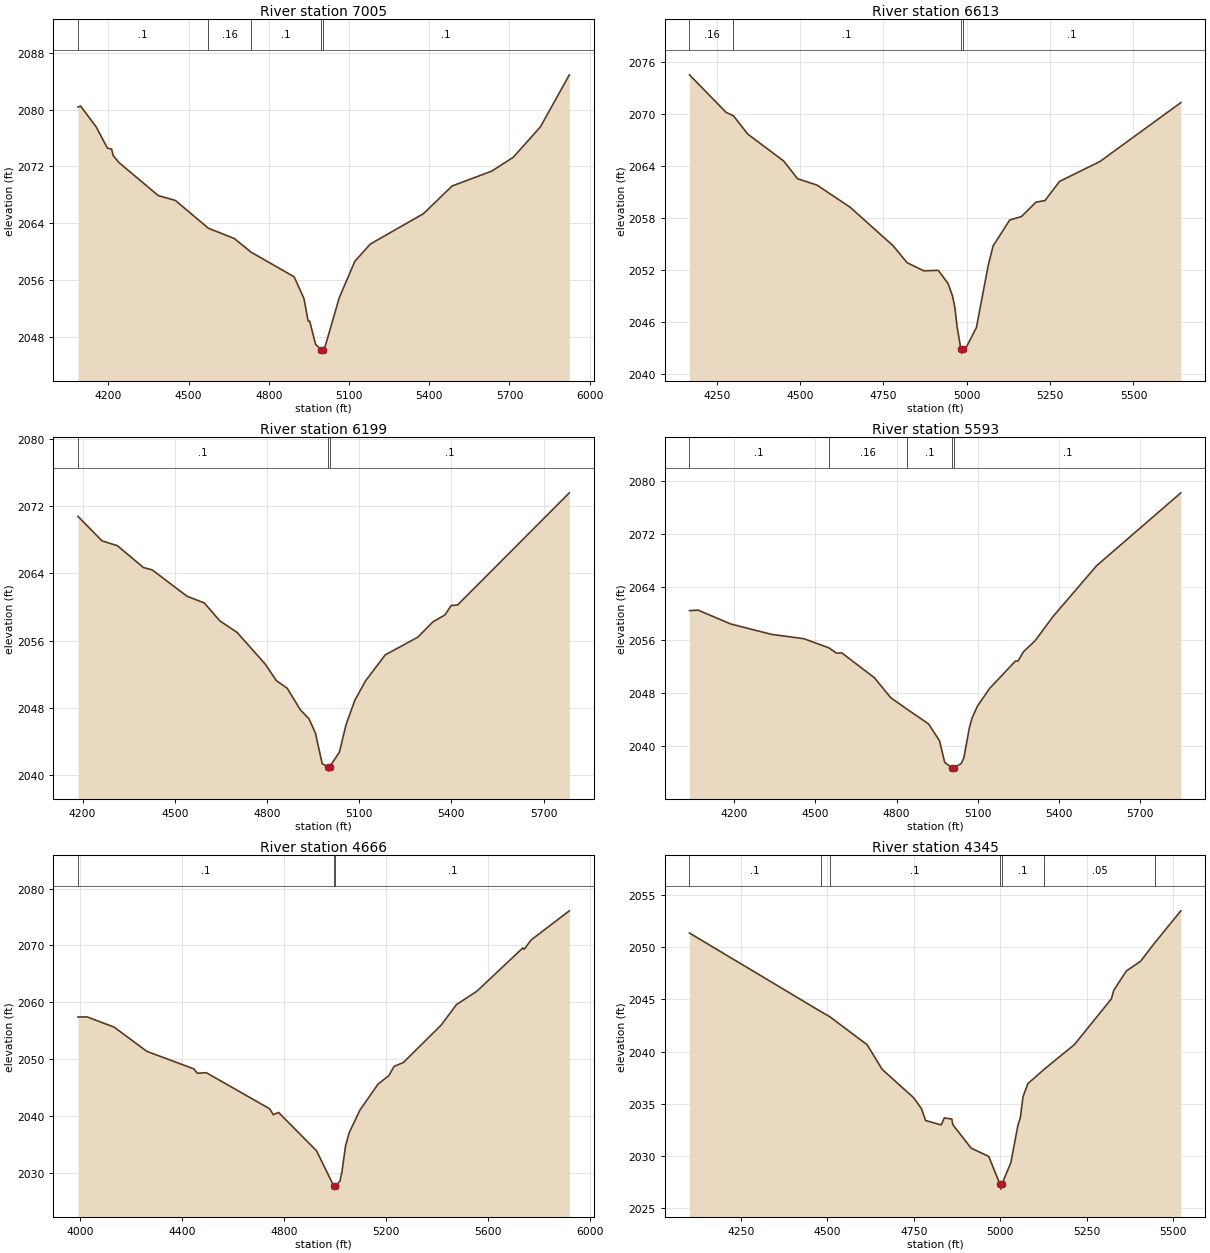
Type RM Length L Ch R = 1 ,7005    ,392,392,392
BEGIN DESCRIPTION:
UNT 1043 IN HEWA 15.0
END DESCRIPTION:
XS GIS Cut Line= 3
      2637628.24     10045035.34      2638579.66     10044458.93
       2638947.7     10043833.95
#Sta/Elev= 30
  4086.1 2080.34  4095.5 2080.51  4153.7 2077.59  4196.4 2074.55  4211.9 2074.44
  4217.7 2073.53  4239.1 2072.55  4386.4 2067.89  4450.4 2067.21  4573.9 2063.29
    4671 2061.84  4733.6 2059.92  4894.5 2056.46  4931.4 2053.39  4946.9 2050.23
  4952.7 2050.21    4975 2046.93  4995.3 2046.21  4998.1 2045.71  5001.3 2046.21
  5010.9  2046.7  5063.2  2053.5  5121.4 2058.63  5179.6 2061.07  5378.1 2065.34
  5485.4 2069.24  5633.8 2071.34  5713.9 2073.28  5815.4 2077.55  5923.8 2084.89
#Mann= 5 ,-1 , 0
  4086.1      .1       0  4573.9     .16       0  4733.6      .1       0
  4995.3     .07       0  5001.3      .1       0
Bank Sta=4995.3,5001.3
XS Rating Curve= 0 ,0
Exp/Cntr=0.3,0.1

Type RM Length L Ch R = 1 ,6613    ,414,414,414
BEGIN DESCRIPTION:
UNT 1043 IN HEWA 14.0
END DESCRIPTION:
XS GIS Cut Line= 2
      2638169.95     10045500.59      2639063.93     10044329.39
#Sta/Elev= 30
  4168.6 2074.56  4278.7 2070.21  4300.4 2069.83  4343.1 2067.72  4451.1  2064.6
  4492.8 2062.55  4550.9 2061.82  4650.7 2059.25  4779.5  2054.8  4821.1 2052.85
    4871 2051.91  4914.6 2051.97  4943.7 2050.46  4957.2 2049.02  4964.5 2047.65
  4970.8 2045.51  4982.3  2042.9  4985.1  2042.4  4988.3  2042.9  4999.8 2043.17
  5028.9 2045.35  5064.3 2052.52  5078.8 2054.77  5128.7 2057.78    5164 2058.18
  5207.6 2059.85  5234.7 2060.03  5278.3 2062.25  5398.9 2064.53    5642 2071.35
#Mann= 4 ,-1 , 0
  4168.6     .16       0  4300.4      .1       0  4982.3     .07       0
  4988.3      .1       0
Bank Sta=4982.3,4988.3
XS Rating Curve= 0 ,0
Exp/Cntr=0.3,0.1

Type RM Length L Ch R = 1 ,6199    ,606,606,606
BEGIN DESCRIPTION:
UNT 1043 IN HEWA 13.0
END DESCRIPTION:
XS GIS Cut Line= 3
      2638433.81     10045729.78      2639162.99     10044903.38
        2639267.     10044418.01
#Sta/Elev= 30
  4185.1 2070.78  4263.3 2067.86  4313.2 2067.29    4398 2064.69  4426.5 2064.41
  4539.9 2061.27  4596.3 2060.47  4646.5 2058.34  4702.5 2056.97  4794.6 2053.18
  4830.6 2051.22  4865.7 2050.32  4908.4 2047.76  4936.8 2046.67  4957.7 2044.96
  4979.5 2041.35  4997.4 2040.95  5000.1 2040.45  5003.4 2040.95  5035.5  2042.7
  5057.3 2045.99  5085.7 2048.88  5120.9 2051.21  5184.4 2054.28  5290.7  2056.4
  5340.1 2058.23  5378.9 2059.04  5399.3 2060.17  5419.8 2060.22  5783.6 2073.58
#Mann= 3 ,-1 , 0
  4185.1      .1       0  4997.4     .07       0  5003.4      .1       0
Bank Sta=4997.4,5003.4
XS Rating Curve= 0 ,0
Exp/Cntr=0.3,0.1

Type RM Length L Ch R = 1 ,5593    ,927,927,927
BEGIN DESCRIPTION:
UNT 1043 IN HEWA 12.0
END DESCRIPTION:
XS GIS Cut Line= 2
      2639475.49     10046215.91       2639586.6     10044403.41
#Sta/Elev= 30
  4034.8  2060.5    4067 2060.57  4187.3 2058.48  4337.5 2056.92  4457.8 2056.26
    4550 2054.88    4578 2054.09    4598 2054.11  4718.3 2050.37  4778.4 2047.36
  4837.4 2045.67  4918.6 2043.39  4958.7 2040.87    4978  2037.6  5005.8 2036.78
  5008.6 2036.28  5011.8 2036.78  5038.9 2037.42  5048.9 2038.31  5068.9 2042.78
  5078.9 2044.28    5099 2046.09  5144.9  2048.8  5239.2 2052.88  5249.3  2052.9
  5269.3 2054.31  5311.8 2055.94  5379.5 2059.67  5539.8 2067.29  5850.7 2078.27
#Mann= 5 ,-1 , 0
  4034.8      .1       0    4550     .16       0  4837.4      .1       0
  5005.8     .07       0  5011.8      .1       0
Bank Sta=5005.8,5011.8
XS Rating Curve= 0 ,0
Exp/Cntr=0.3,0.1

Type RM Length L Ch R = 1 ,4666    ,321,321,321
BEGIN DESCRIPTION:
UNT 1043 IN HEWA 11.0
END DESCRIPTION:
XS GIS Cut Line= 3
      2639614.35     10046250.62      2640628.27     10045347.82
      2640781.05      10044799.2
#Sta/Elev= 30
  3990.9 2057.44  4026.8 2057.45    4133 2055.65    4261  2051.4  4444.9 2048.33
  4459.1 2047.55  4494.3 2047.65  4742.6 2041.31  4756.8 2040.27  4777.7 2040.66
  4926.5 2033.93  4994.6 2027.69  4997.4 2027.19  5000.6 2027.69  5018.5 2028.61
    5026 2030.18  5040.2 2034.75  5054.2 2037.06  5096.3 2041.05  5167.3 2045.62
    5210 2047.14  5230.9 2048.76  5266.8 2049.43    5415    2056  5475.9 2059.64
  5554.7 2061.94  5736.1 2069.59  5741.3 2069.34    5768 2070.97    5918 2076.09
#Mann= 3 ,-1 , 0
  3990.9      .1       0  4994.6     .07       0  5000.6      .1       0
Bank Sta=4994.6,5000.6
XS Rating Curve= 0 ,0
Exp/Cntr=0.3,0.1

Type RM Length L Ch R = 1 ,4345    ,249,249,249
BEGIN DESCRIPTION:
UNT 1043 IN HEWA 10.0
END DESCRIPTION:
XS GIS Cut Line= 3
      2640129.49     10046593.02      2640494.06     10045923.78
      2640910.73     10045413.35
#Sta/Elev= 30
  4101.5 2051.38  4480.9 2043.85  4507.2 2043.35  4615.2 2040.66  4658.8 2038.29
  4749.8 2035.57  4772.6 2034.51  4784.2 2033.39  4829.5 2032.96  4838.3 2033.63
  4860.2 2033.53    4863 2032.99  4915.9 2030.74  4966.9 2029.94  4999.1  2027.3
  5001.8  2026.8  5005.1  2027.3  5030.8 2029.33  5051.6 2032.98  5058.1 2033.62
    5066 2035.67  5080.3 2036.93  5127.1  2038.3  5214.6 2040.67  5321.6 2045.06
  5328.4 2045.88  5364.7 2047.73  5406.3 2048.68  5446.5 2050.42  5522.5 2053.51
#Mann= 7 ,-1 , 0
  4101.5      .1       0  4480.9     .16       0  4507.2      .1       0
  4999.1     .07       0  5005.1      .1       0  5127.1     .05       0
  5446.5      .1       0
Bank Sta=4999.1,5005.1
XS Rating Curve= 0 ,0
Exp/Cntr=0.3,0.1

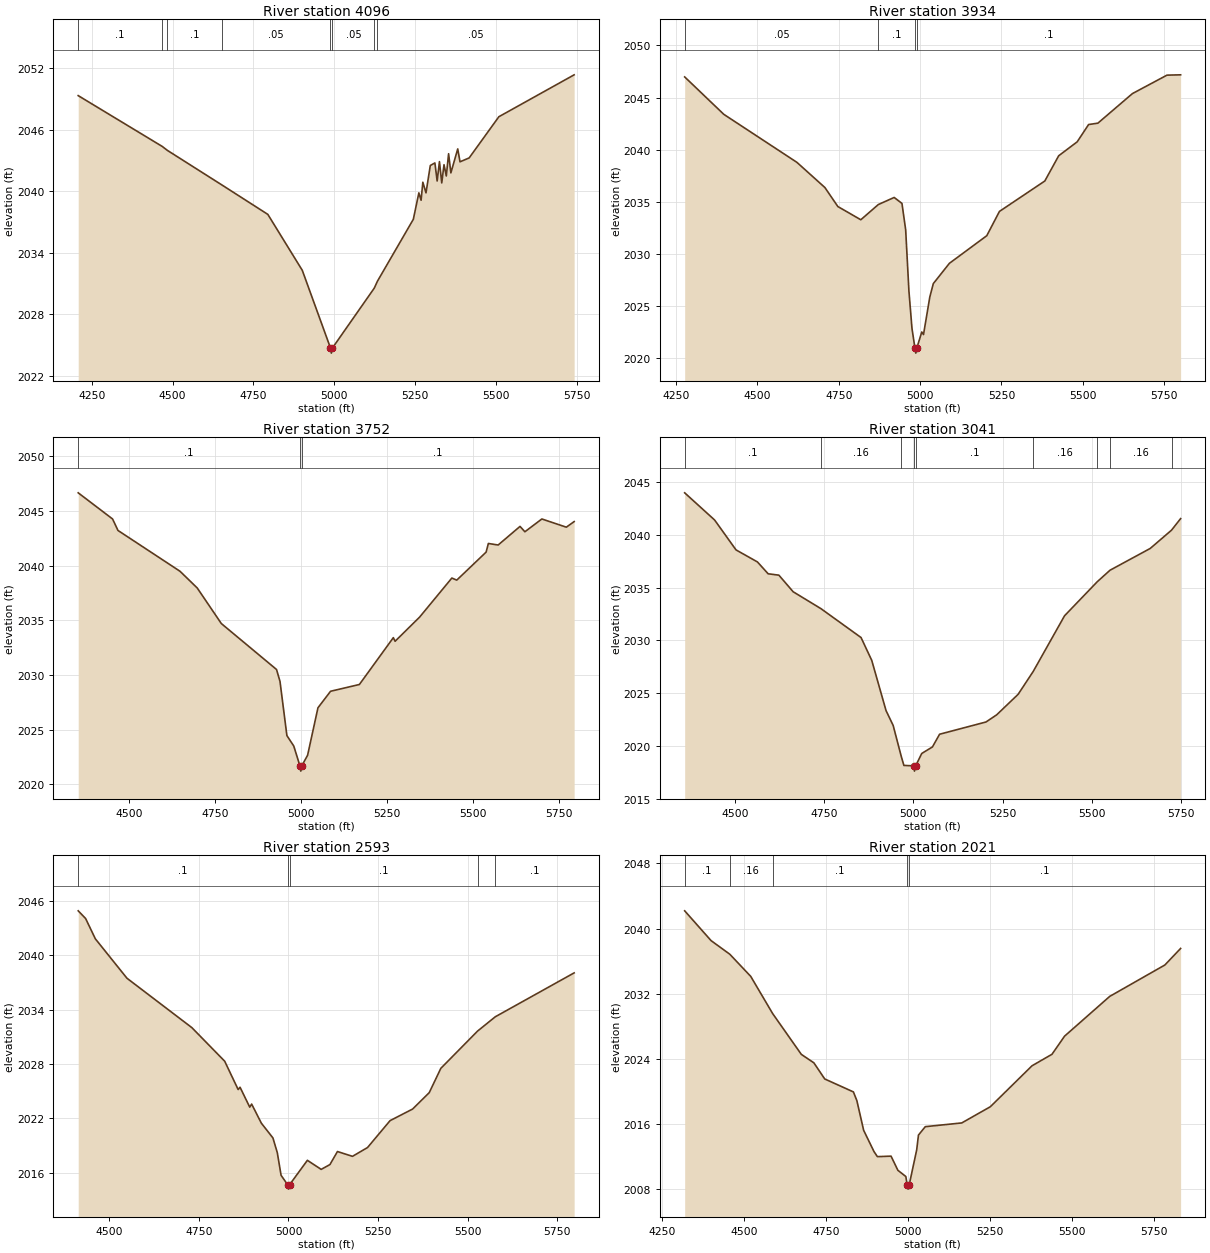
Type RM Length L Ch R = 1 ,4096    ,162,162,162
BEGIN DESCRIPTION:
UNT 1043 IN HEWA 9.0
END DESCRIPTION:
XS GIS Cut Line= 4
      2640244.09     10046650.32      2640608.64     10046272.74
      2640816.97     10045767.53      2641144.28     10045440.23
#Sta/Elev= 30
  4207.9 2049.34  4467.9 2044.38  4483.6    2044    4652 2040.63  4794.5 2037.75
  4901.1 2032.29  4988.3 2024.71    4991 2024.21  4994.3 2024.71  5123.7 2030.55
  5133.6 2031.23  5244.6 2037.27  5261.7 2039.85  5268.6 2039.13    5274 2040.89
  5283.8 2039.85  5297.1 2042.52  5311.3 2042.77  5318.3 2041.01  5325.4  2042.9
  5332.5 2040.82  5339.5  2042.6  5346.6  2041.5  5353.7 2043.67  5360.7  2041.8
    5382 2044.14    5389 2042.88  5417.3 2043.26  5509.2 2047.28  5742.1 2051.37
#Mann= 8 ,-1 , 0
  4207.9      .1       0  4467.9     .16       0  4483.6      .1       0
    4652     .05       0  4988.3     .04       0  4994.3     .05       0
  5123.7      .1       0  5133.6     .05       0
Bank Sta=4988.3,4994.3
XS Rating Curve= 0 ,0
Exp/Cntr=0.3,0.1

Type RM Length L Ch R = 1 ,3934    ,182,182,182
BEGIN DESCRIPTION:
UNT 1043 IN HEWA 7.0
END DESCRIPTION:
XS GIS Cut Line= 4
      2640829.66     10046823.53      2640786.26     10046254.94
      2640946.85     10045833.93      2641323.92      10045500.2
#Sta/Elev= 30
  4276.2 2046.98  4396.4 2043.39  4621.2 2038.78  4707.3 2036.36    4747 2034.54
  4817.6 2033.27  4871.4 2034.73  4920.1 2035.41  4944.1 2034.84  4955.5  2032.3
  4965.5 2026.42  4974.9 2022.83  4983.9 2020.97  4986.6 2020.47  4989.9 2020.97
    5005  2022.5  5010.3 2022.25  5029.7 2025.86  5040.4 2027.14  5089.9 2029.09
  5204.8 2031.74  5243.7 2034.07  5383.2 2036.99  5425.8 2039.41  5482.7 2040.75
  5517.8 2042.41  5546.3 2042.54  5652.5 2045.38  5758.7 2047.15  5800.6 2047.18
#Mann= 4 ,-1 , 0
  4276.2     .05       0  4871.4      .1       0  4983.9     .07       0
  4989.9      .1       0
Bank Sta=4983.9,4989.9
XS Rating Curve= 0 ,0
Exp/Cntr=0.3,0.1

Type RM Length L Ch R = 1 ,3752    ,711,711,711
BEGIN DESCRIPTION:
UNT 1043 IN HEWA 8.0
END DESCRIPTION:
XS GIS Cut Line= 4
      2640954.99     10046809.24      2640996.66     10046322.22
      2641051.35     10045819.62      2641392.49     10045525.35
#Sta/Elev= 30
  4350.6 2046.66  4450.7 2044.27  4466.5 2043.22  4647.2 2039.49  4697.4 2037.96
  4767.6 2034.71  4928.4 2030.51  4938.5 2029.42  4958.6 2024.47  4978.7 2023.51
  4996.3 2021.72  4999.1 2021.22  5002.3 2021.72  5018.9 2022.67  5049.1 2027.01
  5085.8 2028.52  5169.8 2029.14  5268.7 2033.42  5273.8 2033.09    5345 2035.29
  5439.2 2038.87  5453.5 2038.68    5539 2041.24  5545.6 2042.03  5574.1 2041.89
  5637.8 2043.59    5652  2043.1  5701.4 2044.27  5772.7 2043.52  5795.5 2044.03
#Mann= 3 ,-1 , 0
  4350.6      .1       0  4996.3     .07       0  5002.3      .1       0
Bank Sta=4996.3,5002.3
XS Rating Curve= 0 ,0
Exp/Cntr=0.3,0.1

Type RM Length L Ch R = 1 ,3041    ,448,448,448
BEGIN DESCRIPTION:
UNT 1043 IN HEWA 6.0
END DESCRIPTION:
XS GIS Cut Line= 2
      2641703.14     10046837.58      2641711.82      10045448.7
#Sta/Elev= 30
  4359.8 2043.96  4443.6 2041.39  4503.6 2038.56  4563.6 2037.42  4593.6  2036.3
  4623.6 2036.17  4663.6  2034.6  4741.5    2033  4853.7 2030.27  4883.7 2028.11
  4923.7 2023.36  4943.7 2021.95  4965.9 2019.08  4973.7 2018.17  5000.7 2018.13
  5003.4 2017.63  5006.7 2018.13  5023.7  2019.3  5053.7 2019.92  5073.7 2021.12
  5203.7 2022.28  5233.7 2022.96  5293.7  2024.9  5335.9 2027.06  5423.7 2032.33
  5515.6 2035.56  5551.1 2036.64  5663.7  2038.7  5723.3 2040.43  5748.7 2041.52
#Mann= 9 ,-1 , 0
  4359.8      .1       0  4741.5     .16       0  4965.9      .1       0
  5000.7     .07       0  5006.7      .1       0  5335.9     .16       0
  5515.6      .1       0  5551.1     .16       0  5723.3      .1       0
Bank Sta=5000.7,5006.7
XS Rating Curve= 0 ,0
Exp/Cntr=0.3,0.1

Type RM Length L Ch R = 1 ,2593    ,572,572,572
BEGIN DESCRIPTION:
UNT 1043 IN HEWA 5.0
END DESCRIPTION:
XS GIS Cut Line= 2
      2642328.14     10046733.45      2641911.46     10045413.98
#Sta/Elev= 30
  4413.4 2044.91  4434.1 2044.06  4461.2 2041.82  4549.4 2037.47  4730.4 2032.02
  4822.1 2028.31  4859.7 2025.18  4864.9 2025.44    4892 2023.24  4897.3 2023.58
  4924.4 2021.47  4956.7 2019.84  4968.9 2018.21  4979.4 2015.72  4997.4 2014.69
  5000.1 2014.19  5003.4 2014.69  5052.8 2017.37  5091.3 2016.37  5115.7  2016.9
  5136.7 2018.34  5178.6 2017.81  5220.6 2018.78  5283.5 2021.75  5346.4 2023.03
  5392.8 2024.84  5425.1 2027.52  5527.5 2031.63  5576.9 2033.21  5797.1 2038.06
#Mann= 5 ,-1 , 0
  4413.4      .1       0  4997.4     .07       0  5003.4      .1       0
  5527.5     .16       0  5576.9      .1       0
Bank Sta=4997.4,5003.4
XS Rating Curve= 0 ,0
Exp/Cntr=0.3,0.1

Type RM Length L Ch R = 1 ,2021    ,452,452,452
BEGIN DESCRIPTION:
UNT 1043 IN HEWA 4.0
END DESCRIPTION:
XS GIS Cut Line= 2
      2642866.33     10046646.63      2642432.57     10045197.87
#Sta/Elev= 30
  4319.2 2042.18  4399.7 2038.52  4456.8 2036.85  4520.6 2034.13  4587.5 2029.56
  4674.9 2024.55  4713.2 2023.51  4746.3 2021.53  4833.7 2019.94  4844.2 2018.88
    4865 2015.22  4896.4 2012.62  4906.8 2011.99  4948.5 2012.05  4969.4 2010.31
  4993.6 2009.55  4997.7  2008.5  5000.5    2008  5003.7  2008.5  5026.7 2012.82
  5032.1 2014.64  5052.9 2015.67  5164.2 2016.13  5251.3 2018.12  5378.4 2023.15
  5439.2 2024.56  5477.7 2026.79  5615.3 2031.67  5783.6 2035.53  5831.5 2037.56
#Mann= 5 ,-1 , 0
  4319.2      .1       0  4456.8     .16       0  4587.5      .1       0
  4997.7     .07       0  5003.7      .1       0
Bank Sta=4997.7,5003.7
XS Rating Curve= 0 ,0
Exp/Cntr=0.3,0.1

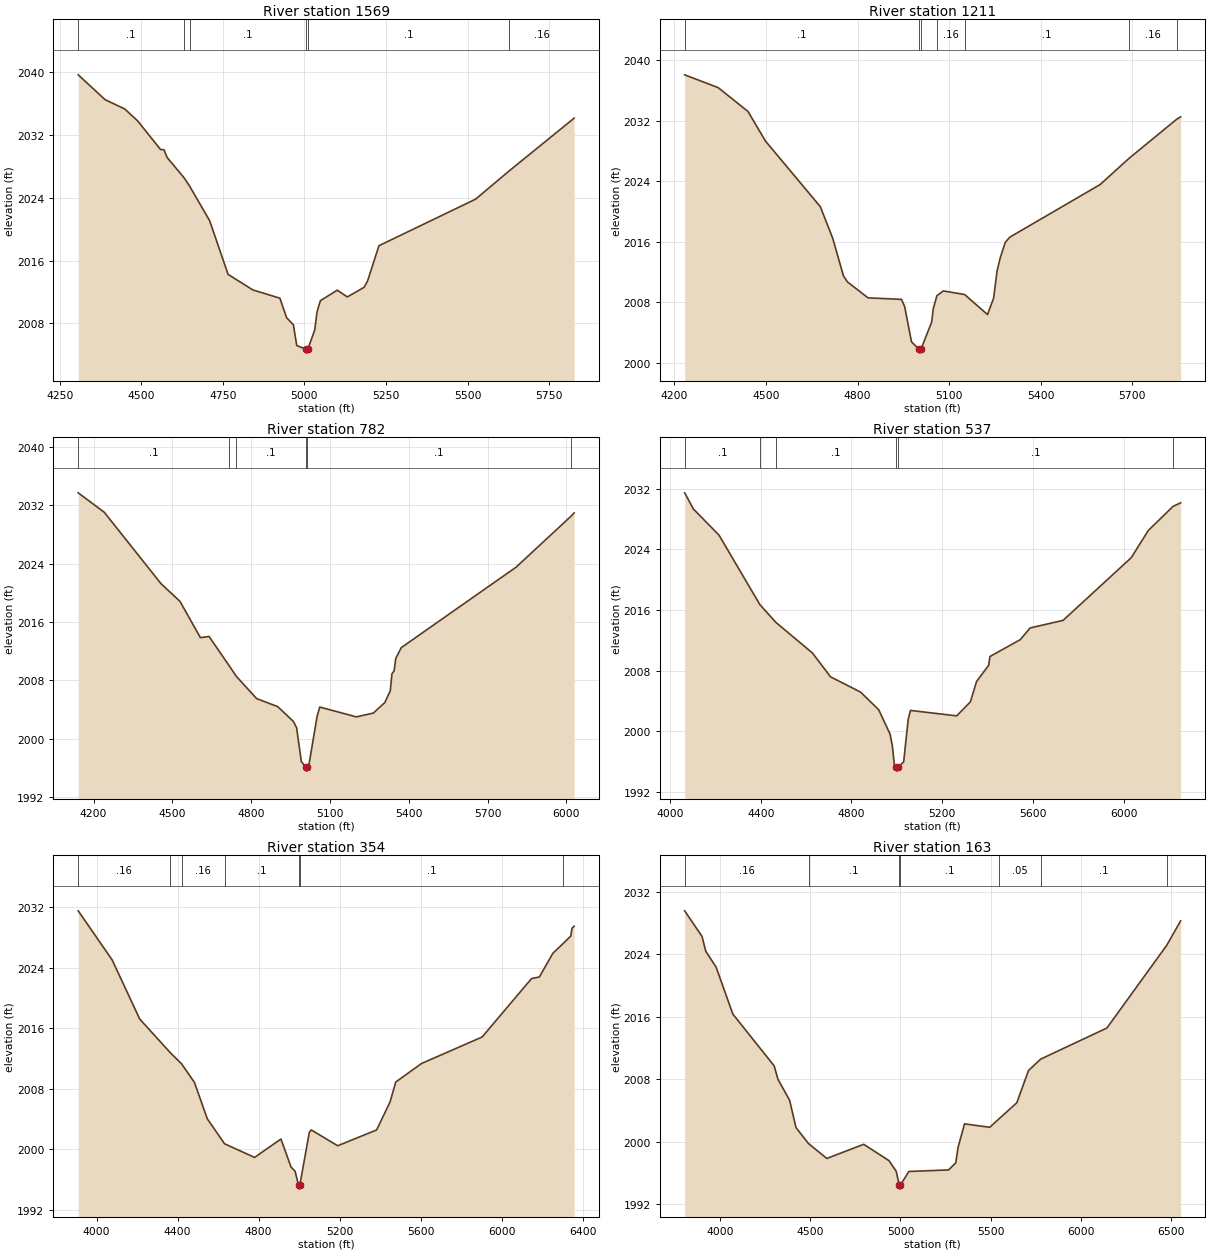
Type RM Length L Ch R = 1 ,1569    ,358,358,358
BEGIN DESCRIPTION:
UNT 1043 IN HEWA 3.0
END DESCRIPTION:
XS GIS Cut Line= 3
      2643144.11     10046585.86      2643170.15     10046125.82
      2642901.07     10045101.56
#Sta/Elev= 30
  4306.9 2039.67  4389.2 2036.51  4449.3 2035.33  4489.3 2033.79  4559.4 2030.15
  4569.5 2030.14  4579.5 2029.14  4631.8 2026.53  4648.1 2025.51  4709.7 2021.09
  4766.2 2014.25  4842.2 2012.27  4924.9 2011.22  4945.6 2008.73  4966.3 2007.83
  4976.6 2005.19  5004.6 2004.72  5007.4 2004.22  5010.6 2004.72  5031.8 2007.18
  5038.7 2009.46    5049  2010.9  5100.7 2012.24  5131.7 2011.38  5182.9  2012.6
  5193.8 2013.43  5228.4  2017.9  5524.6 2023.83  5626.7  2027.4  5826.7 2034.15
#Mann= 6 ,-1 , 0
  4306.9      .1       0  4631.8     .16       0  4648.1      .1       0
  5004.6     .07       0  5010.6      .1       0  5626.7     .16       0
Bank Sta=5004.6,5010.6
XS Rating Curve= 0 ,0
Exp/Cntr=0.3,0.1

Type RM Length L Ch R = 1 ,1211    ,429,429,429
BEGIN DESCRIPTION:
UNT 1043 IN HEWA 2.0
END DESCRIPTION:
XS GIS Cut Line= 4
      2643361.12     10046559.88       2643508.7     10045995.61
      2643343.77     10045448.73      2643066.71     10045067.78
#Sta/Elev= 30
  4233.5 2038.05  4343.2 2036.36  4440.9 2033.21  4498.3 2029.29  4678.3  2020.6
  4718.8 2016.42    4754 2011.45    4767 2010.66  4834.6 2008.55  4944.1 2008.35
  4954.5  2007.4    4977 2002.73  5001.8 2001.74  5004.5 2001.24  5007.8 2001.74
    5043 2005.34  5048.5 2007.15  5060.3 2008.84  5081.2 2009.47  5151.1 2008.99
  5226.1 2006.34  5246.1 2008.51  5257.4 2012.11  5267.8 2013.84  5284.3 2015.89
  5299.2 2016.58  5595.3 2023.54    5689 2026.97  5845.6 2032.16    5859 2032.49
#Mann= 7 ,-1 , 0
  4233.5      .1       0  5001.8     .07       0  5007.8      .1       0
  5060.3     .16       0  5151.1      .1       0    5689     .16       0
  5845.6      .1       0
Bank Sta=5001.8,5007.8
XS Rating Curve= 0 ,0
Exp/Cntr=0.3,0.1

Type RM Length L Ch R = 1 ,782     ,245,245,245
BEGIN DESCRIPTION:
Mapping XS 95e16df4
END DESCRIPTION:
XS GIS Cut Line= 4
      2643694.37     10046549.96      2643854.11     10046004.78
      2643871.47     10045522.14       2643202.4     10045019.48
#Sta/Elev= 30
  4141.5 2033.71  4240.8 2031.04  4456.9 2021.24  4528.9 2018.83  4606.5 2013.85
  4639.6 2014.01  4716.3 2009.99  4743.4 2008.54  4820.7 2005.49  4900.8 2004.39
  4960.8 2002.35  4972.9 2001.48  4990.8 1996.88  5007.8 1996.04  5010.6 1995.54
  5013.8 1996.04  5020.9 1996.63  5050.9 2003.06  5060.9 2004.33  5200.4 2002.98
    5265  2003.5  5308.7 2004.95  5329.5 2006.56  5335.8 2008.89  5344.1  2009.3
  5350.4 2011.01  5371.4 2012.48  5808.6 2023.52  6017.3  2030.5  6029.4 2030.96
#Mann= 6 ,-1 , 0
  4141.5      .1       0  4716.3     .16       0  4743.4      .1       0
  5007.8     .07       0  5013.8      .1       0  6017.3     .16       0
Bank Sta=5007.8,5013.8
XS Rating Curve= 0 ,0
Exp/Cntr=0.3,0.1

Type RM Length L Ch R = 1 ,537     ,282,282,282
BEGIN DESCRIPTION:
Mapping XS 47eab763
END DESCRIPTION:
XS GIS Cut Line= 4
      2643788.14     10046567.28      2644107.58     10045987.42
      2644111.05     10045470.06      2643236.03     10044970.05
#Sta/Elev= 30
  4064.4 2031.47  4102.7 2029.34  4215.8 2025.89  4396.3 2016.71  4467.2 2014.36
  4627.9 2010.34  4707.8 2007.19  4840.1 2005.18  4920.1 2002.85  4970.1 1999.65
  4980.1 1998.12  4990.1 1995.32  4997.1 1995.25  4999.9 1994.75  5003.1 1995.25
  5030.1 1995.96  5050.1 2001.55  5060.1 2002.76  5264.1 2002.04  5324.4 2003.89
  5351.7 2006.58    5405 2008.71  5410.7 2009.87  5544.6  2012.1  5587.8 2013.64
  5733.2 2014.64  6034.1 2022.92    6109  2026.5  6218.2 2029.68  6251.6 2030.15
#Mann= 6 ,-1 , 0
  4064.4      .1       0  4396.3     .16       0  4467.2      .1       0
  4997.1     .07       0  5003.1      .1       0  6218.2     .05       0
Bank Sta=4997.1,5003.1
XS Rating Curve= 0 ,0
Exp/Cntr=0.3,0.1

Type RM Length L Ch R = 1 ,354     ,191,191,191
BEGIN DESCRIPTION:
Mapping XS f3648246
END DESCRIPTION:
XS GIS Cut Line= 4
      2643851.97      10046667.5      2644285.99     10045986.95
      2644296.41     10045483.48      2643285.99     10044962.65
#Sta/Elev= 30
  3909.6  2031.5    4077 2025.02  4213.2  2017.2    4365 2012.73  4419.5 2011.29
  4483.2 2008.83  4546.7 2004.02  4631.9 2000.72    4780 1998.92    4910 2001.35
    4960 1997.65    4980 1997.09  4997.1 1995.23  4999.8 1994.73  5003.1 1995.23
  5050.1 2002.23  5060.1 2002.55  5190.1 2000.46  5382.3 2002.55  5448.7 2006.26
  5476.8 2008.88    5604 2011.33    5903 2014.83  6146.8 2022.55  6185.5 2022.76
    6252 2025.89    6304 2027.21  6340.6 2028.17  6346.3  2029.2  6357.1 2029.47
#Mann= 7 ,-1 , 0
  3909.6     .16       0    4365      .1       0  4419.5     .16       0
  4631.9      .1       0  4997.1     .07       0  5003.1      .1       0
    6304     .05       0
Bank Sta=4997.1,5003.1
XS Rating Curve= 0 ,0
Exp/Cntr=0.3,0.1

Type RM Length L Ch R = 1 ,163     ,0,0,0
BEGIN DESCRIPTION:
UNT 1043 IN HEWA 1.0
END DESCRIPTION:
XS GIS Cut Line= 4
      2643904.03     10046723.09      2644480.43      10045955.7
      2644483.91     10045414.04      2643324.15     10044959.16
#Sta/Elev= 30
  3804.8 2029.58  3900.8 2026.31  3921.6 2024.41  3979.1 2022.36  4071.6 2016.36
  4300.7 2009.72  4321.5 2008.01  4386.1 2005.32  4421.5 2001.82  4490.9 1999.77
  4592.3 1997.87  4796.5 1999.68  4936.5 1997.59  4976.5 1996.23  4993.5 1994.44
  4996.3 1993.94  4999.5 1994.44  5046.5  1996.2  5266.5  1996.4  5306.2 1997.29
  5319.1 1999.27    5355  2002.3  5494.7 2001.86  5547.3 2002.97  5644.6    2005
  5709.5 2009.13  5776.8 2010.59  6143.5 2014.57  6474.9 2025.16    6552 2028.29
#Mann= 7 ,-1 , 0
  3804.8     .16       0  4490.9      .1       0  4993.5     .07       0
  4999.5      .1       0  5547.3     .05       0  5776.8      .1       0
  6474.9     .05       0
Bank Sta=4993.5,4999.5
XS Rating Curve= 0 ,0
Exp/Cntr=0.3,0.1

Chan Stop Cuts=-1
Use User Specified Reach Order=0
Composite Channel Slope=5