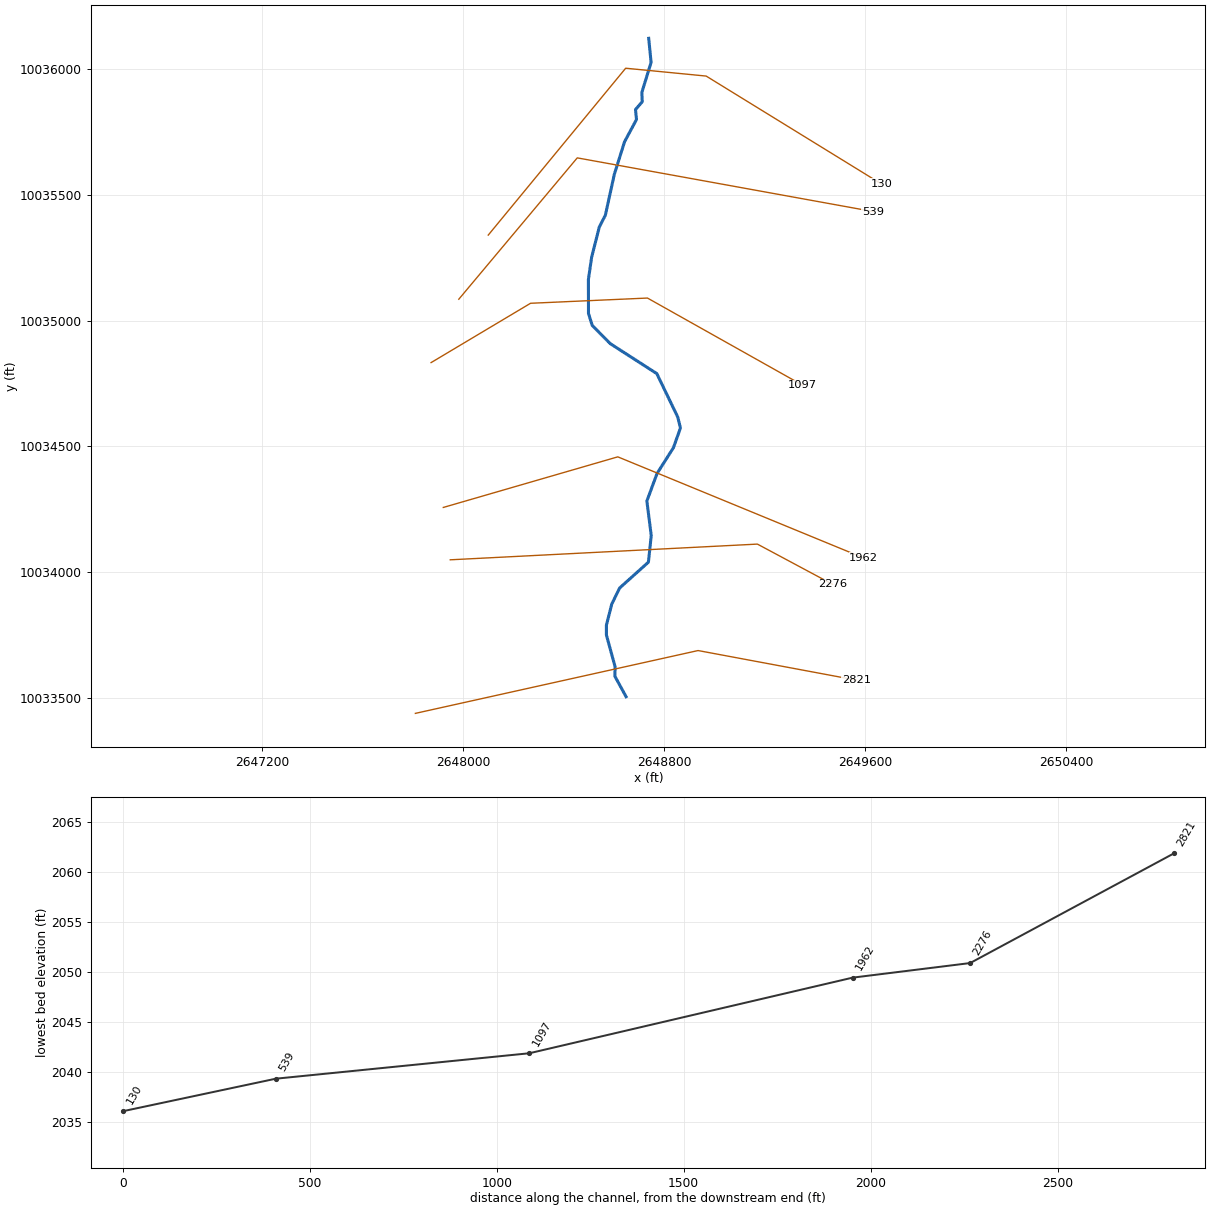
--- UNT 1044 IN HEWA.prj (project) ---

Proj Title=UNT 1044 IN HEWA Base Level Engineering
Current Plan=p01
Default Exp/Contr=0.3,0.1
English Units
Geom File=g01
Flow File=f01
Plan File=p01
Y Axis Title=Elevation
X Axis Title(PF)=Main Channel Distance
X Axis Title(XS)=Station
BEGIN DESCRIPTION:
UNT 1044 IN HEWA
END DESCRIPTION:
DSS Export Rating Curves= 0
DSS Export Rating Curve Sorted= 0
DSS Export Volume Flow Curves= 0
DXF OffsetX= 0
DXF OffsetY= 0
DXF ScaleX= 1
DXF ScaleY= 10

--- UNT 1044 IN HEWA.p01 (plan) ---

Plan Title=Multiple Run
Short Identifier=Multiple
Geom File=g01
Flow File=f01
Subcritical Flow
K Sum by GR= 0
Std Step Tol= 0.01
Critical Tol= 0.01
Num of Std Step Trials= 20
Max Error Tol= 0.3
Flow Tol Ratio= 0.001
Split Flow NTrial= 30
Split Flow Tol= 0.02
Split Flow Ratio= 0.02
Log Output Level= 0
Friction Slope Method= 1
Unsteady Friction Slope Method= 2
Unsteady Bridges Friction Slope Method= 1
Parabolic Critical Depth
Global Vel Dist=  1 , 1 , 1
Global Log Level= 0
CheckData=True
Encroach Param= -1, 0, 0, 0
BEGIN DESCRIPTION:
Multiple Run
END DESCRIPTION:

--- UNT 1044 IN HEWA.f01 (steady flow) ---

Flow Title=Multiple
Program Version=4.10
Number of Profiles= 7
Profile Names=10-year,25-year,50-year,1pct_min,100-year,1pct_plu,500-year
River Rch & RM=UNT 1044 IN HEWA,Reach-1         ,2821
    1502    2211    2829    2635    3563    4819    5655
Boundary for River Rch & Prof#=UNT 1044 IN HEWA,Reach-1         , 1
Up Type= 0
Dn Type= 3
Dn Slope=0.01
Boundary for River Rch & Prof#=UNT 1044 IN HEWA,Reach-1         , 2
Up Type= 0
Dn Type= 3
Dn Slope=0.01
Boundary for River Rch & Prof#=UNT 1044 IN HEWA,Reach-1         , 3
Up Type= 0
Dn Type= 3
Dn Slope=0.01
Boundary for River Rch & Prof#=UNT 1044 IN HEWA,Reach-1         , 4
Up Type= 0
Dn Type= 3
Dn Slope=0.01
Boundary for River Rch & Prof#=UNT 1044 IN HEWA,Reach-1         , 5
Up Type= 0
Dn Type= 3
Dn Slope=0.01
Boundary for River Rch & Prof#=UNT 1044 IN HEWA,Reach-1         , 6
Up Type= 0
Dn Type= 3
Dn Slope=0.01
Boundary for River Rch & Prof#=UNT 1044 IN HEWA,Reach-1         , 7
Up Type= 0
Dn Type= 3
Dn Slope=0.01
DSS Import GetInterval= 0
DSS Import GetPeak= 0
DSS Import FillOption= 0

--- UNT 1044 IN HEWA.g01 (geometry) ---

Geom Title=Existing Conditions
Program Version=4.10

River Reach=UNT 1044 IN HEWA,Reach-1
Reach XY= 30
      2648648.47     10033503.73      2648603.68     10033585.38
      2648604.88     10033622.52       2648570.2     10033749.15
      2648570.15      10033788.3      2648591.45     10033872.51
      2648623.06     10033936.62      2648737.27     10034039.11
      2648748.56     10034144.98      2648731.15     10034282.48
      2648771.81     10034392.35      2648836.76     10034494.49
      2648864.71       10034573.      2648854.12     10034616.48
      2648770.65     10034789.56      2648585.56     10034908.68
       2648513.8       10034981.      2648498.81     10035028.88
      2648498.45     10035163.73      2648511.36     10035252.53
       2648541.7     10035372.39      2648565.94     10035419.78
      2648601.62     10035582.43       2648642.3     10035712.17
      2648689.81     10035800.54      2648685.96     10035840.51
      2648712.69     10035871.26      2648711.15      10035908.3
      2648747.94     10036028.14      2648738.47     10036123.73

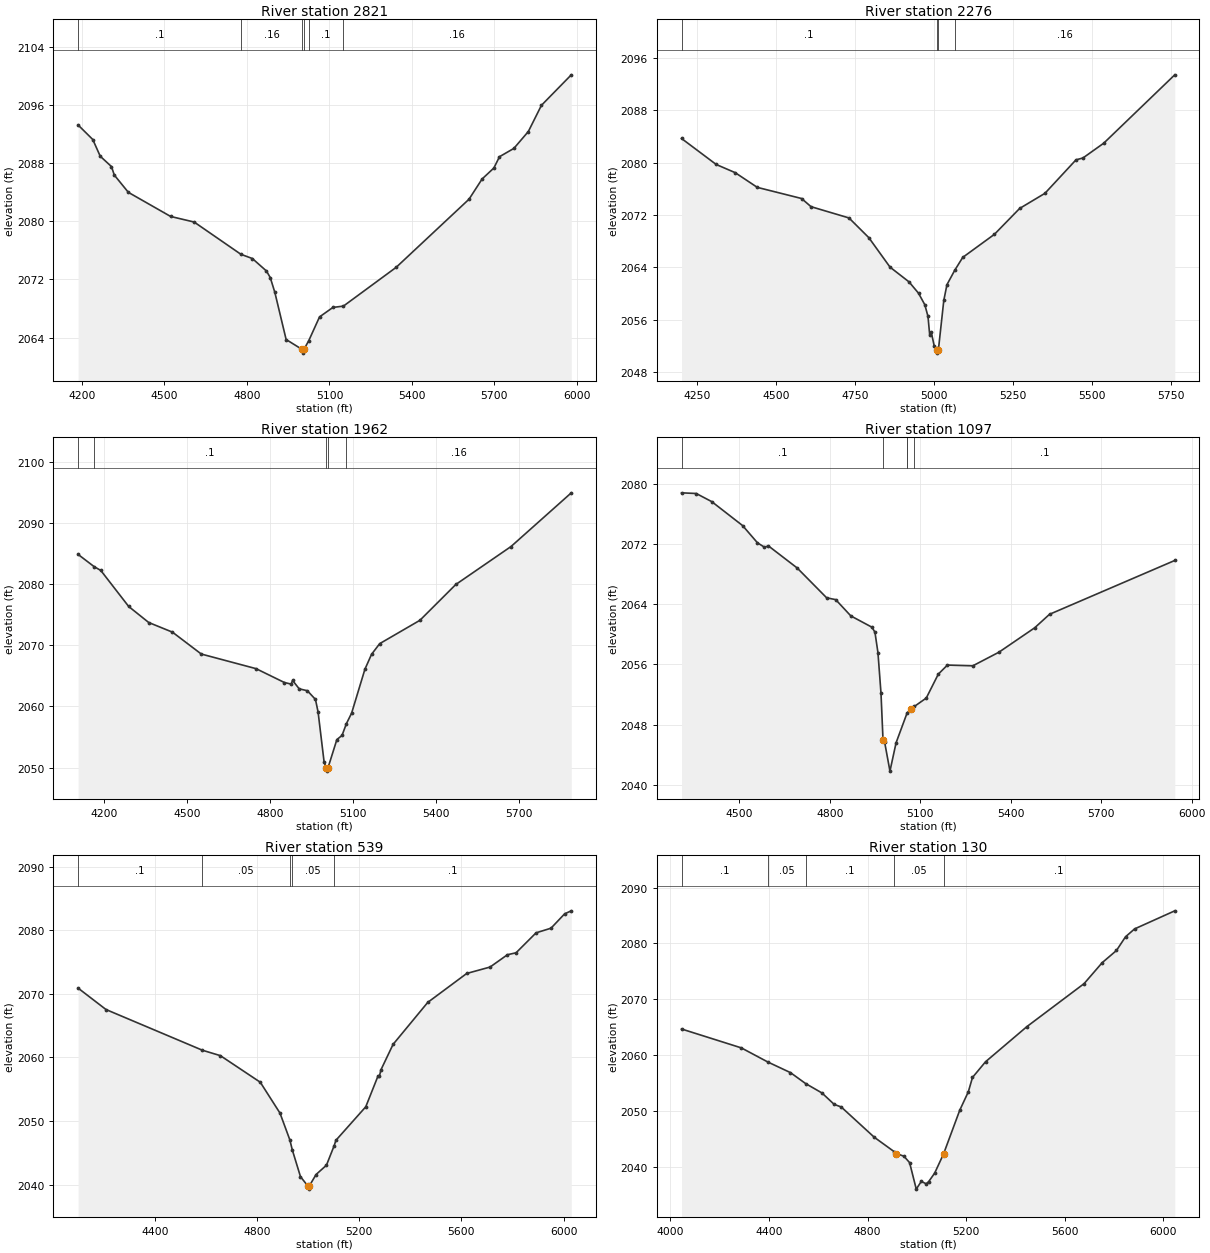
Type RM Length L Ch R = 1 ,2821    ,545,545,545
BEGIN DESCRIPTION:
UNT 1044 IN HEWA 6.0
END DESCRIPTION:
XS GIS Cut Line= 3
      2647809.89     10033437.44      2648934.91     10033687.45
      2649565.15     10033569.71
#Sta/Elev= 30
  4185.9 2093.22  4239.4 2091.22  4266.4 2088.93  4307.4  2087.5  4317.6 2086.34
  4368.8 2083.96  4522.5 2080.65  4608.1 2079.88    4778 2075.45  4819.6 2074.87
  4870.8 2073.16  4884.7 2072.26  4901.5 2070.21  4942.5 2063.74    5001 2062.37
  5003.7 2061.87    5007 2062.37  5024.4 2063.55    5064 2066.85  5112.7 2068.15
  5150.8 2068.33  5342.7 2073.66  5607.6 2083.02  5655.2  2085.8    5698 2087.31
  5718.4 2088.86  5770.7    2090  5823.3 2092.32  5870.9 2095.92  5979.5 2100.11
#Mann= 6 ,-1 , 0
  4185.9      .1       0    4778     .16       0    5001     .07       0
    5007     .16       0  5024.4      .1       0  5150.8     .16       0
Bank Sta=5001,5007
XS Rating Curve= 0 ,0
Exp/Cntr=0.3,0.1

Type RM Length L Ch R = 1 ,2276    ,314,314,314
BEGIN DESCRIPTION:
UNT 1044 IN HEWA 5.0
END DESCRIPTION:
XS GIS Cut Line= 3
      2647948.79     10034048.56      2649171.02     10034111.06
      2649469.66     10033951.32
#Sta/Elev= 30
  4199.9 2083.68  4309.7 2079.71  4369.8 2078.46  4439.9 2076.21  4580.1 2074.51
  4610.1 2073.26  4730.3 2071.54  4793.1 2068.53  4860.4 2064.02  4920.5 2061.77
  4950.6 2060.04  4970.6 2058.27  4980.6 2056.49  4986.1 2053.63  4991.1 2054.04
  5000.6 2051.93  5007.6 2051.38  5010.4 2050.88  5013.6 2051.38  5030.7 2058.94
  5040.7 2061.34  5065.1 2063.52  5090.7 2065.51  5190.9 2069.03    5271 2072.99
  5351.1  2075.3  5449.5 2080.42  5471.5  2080.7  5537.3 2082.96  5762.4 2093.41
#Mann= 4 ,-1 , 0
  4199.9      .1       0  5007.6     .07       0  5013.6      .1       0
  5065.1     .16       0
Bank Sta=5007.6,5013.6
XS Rating Curve= 0 ,0
Exp/Cntr=0.3,0.1

Type RM Length L Ch R = 1 ,1962    ,865,865,865
BEGIN DESCRIPTION:
UNT 1044 IN HEWA 4.0
END DESCRIPTION:
XS GIS Cut Line= 3
      2647921.06      10034256.9      2648615.47     10034458.28
      2649594.09     10034055.73
#Sta/Elev= 30
  4107.1 2084.87    4165 2082.87  4189.2 2082.24  4289.9 2076.35  4362.2 2073.73
    4448 2072.15  4552.1 2068.57  4749.9 2066.18  4852.4 2063.91  4876.4 2063.66
  4881.8 2064.25  4905.7 2062.88  4935.1 2062.57  4964.4 2061.15  4973.9 2059.08
  4995.6 2050.91  5003.4 2049.92  5006.1 2049.42  5009.4 2049.92  5041.7 2054.58
  5060.3 2055.26  5076.2 2057.19    5095 2058.91    5143 2066.09  5166.9 2068.52
  5196.3 2070.27  5341.6 2074.09  5471.3 2079.95  5670.7 2086.16  5888.3 2094.94
#Mann= 5 ,-1 , 0
  4107.1     .16       0    4165      .1       0  5003.4     .07       0
  5009.4      .1       0  5076.2     .16       0
Bank Sta=5003.4,5009.4
XS Rating Curve= 0 ,0
Exp/Cntr=0.3,0.1

Type RM Length L Ch R = 1 ,1097    ,678,678,678
BEGIN DESCRIPTION:
UNT 1044 IN HEWA 2.0
END DESCRIPTION:
XS GIS Cut Line= 4
      2647872.38     10034833.26      2648268.24     10035069.39
      2648733.52     10035090.22      2649351.58       10034743.
#Sta/Elev= 30
  4308.4 2078.79  4357.2  2078.7  4408.6 2077.62  4510.9 2074.44    4560 2072.16
  4583.3 2071.57  4596.6 2071.74  4691.9 2068.81  4789.6 2064.85  4819.6 2064.61
  4869.7 2062.45  4939.7 2060.95  4949.7 2060.29  4959.7 2057.58  4969.8 2052.18
  4976.5 2045.99  4981.5 2045.77  4999.5 2041.84  5019.8  2045.6  5056.6 2049.59
  5069.9 2050.04  5080.9 2050.44  5119.9 2051.54  5159.9 2054.72    5190 2055.92
  5274.2 2055.82  5360.9 2057.63  5479.5 2060.87  5528.6 2062.66    5944 2069.81
#Mann= 5 ,-1 , 0
  4308.4      .1       0  4976.5     .07       0  5056.6      .1       0
  5056.6     .05       0  5080.9      .1       0
Bank Sta=4976.5,5069.9
XS Rating Curve= 0 ,0
Exp/Cntr=0.3,0.1

Type RM Length L Ch R = 1 ,539     ,409,409,409
BEGIN DESCRIPTION:
Mapping XS 939f7e62
END DESCRIPTION:
XS GIS Cut Line= 3
      2647982.77     10035085.57      2648454.11     10035648.05
      2649631.24      10035434.5
#Sta/Elev= 30
  4099.8  2070.9  4209.1 2067.53  4586.3 2061.13  4656.6 2060.28  4812.8  2056.1
  4889.9 2051.25  4928.5 2047.04  4938.3 2045.44  4970.2 2041.25  4998.8 2039.79
  5001.6 2039.29  5004.8 2039.79  5031.2 2041.59  5071.8 2043.05  5102.3 2046.15
  5108.7 2046.96  5225.7 2052.24    5274 2057.12  5279.1 2057.06  5285.3 2058.07
  5332.5 2062.05  5468.2 2068.65  5620.7  2073.2  5712.1 2074.21  5780.2 2076.15
  5813.8 2076.45  5892.1 2079.59  5950.6 2080.32    6004 2082.58    6030 2083.05
#Mann= 5 ,-1 , 0
  4099.8      .1       0  4586.3     .05       0  4928.5      .1       0
  4938.3     .05       0  5102.3      .1       0
Bank Sta=4998.8,5004.8
XS Rating Curve= 0 ,0
Exp/Cntr=0.3,0.1

Type RM Length L Ch R = 1 ,130     ,0,0,0
BEGIN DESCRIPTION:
UNT 1044 IN HEWA 1.0
END DESCRIPTION:
XS GIS Cut Line= 4
      2648099.96     10035340.78      2648646.82     10036004.82
      2648967.13     10035973.57      2649664.23     10035544.39
#Sta/Elev= 30
  4045.7 2064.69  4288.2 2061.31  4395.8 2058.78  4487.6 2056.88  4548.8 2054.93
  4615.3 2053.24  4664.8  2051.2  4693.5 2050.73  4827.6 2045.31  4909.3  2042.7
  4917.6 2042.39  4947.8 2041.92  4970.8 2040.77  4997.8 2036.03  5018.1 2037.41
  5038.2 2036.98  5048.3 2037.38  5072.5  2038.9  5108.5 2042.33  5174.2 2050.15
    5209 2053.45  5225.9 2056.02  5278.7 2058.82  5446.7 2065.12  5678.6 2072.81
    5752 2076.56  5809.9 2078.74  5846.6 2081.19  5883.3  2082.6  6046.4 2085.84
#Mann= 5 ,-1 , 0
  4045.7      .1       0  4395.8     .05       0  4548.8      .1       0
  4909.3     .05       0  5108.5      .1       0
Bank Sta=4917.6,5108.5
XS Rating Curve= 0 ,0
Exp/Cntr=0.3,0.1

Chan Stop Cuts=-1
Use User Specified Reach Order=0
Composite Channel Slope=5