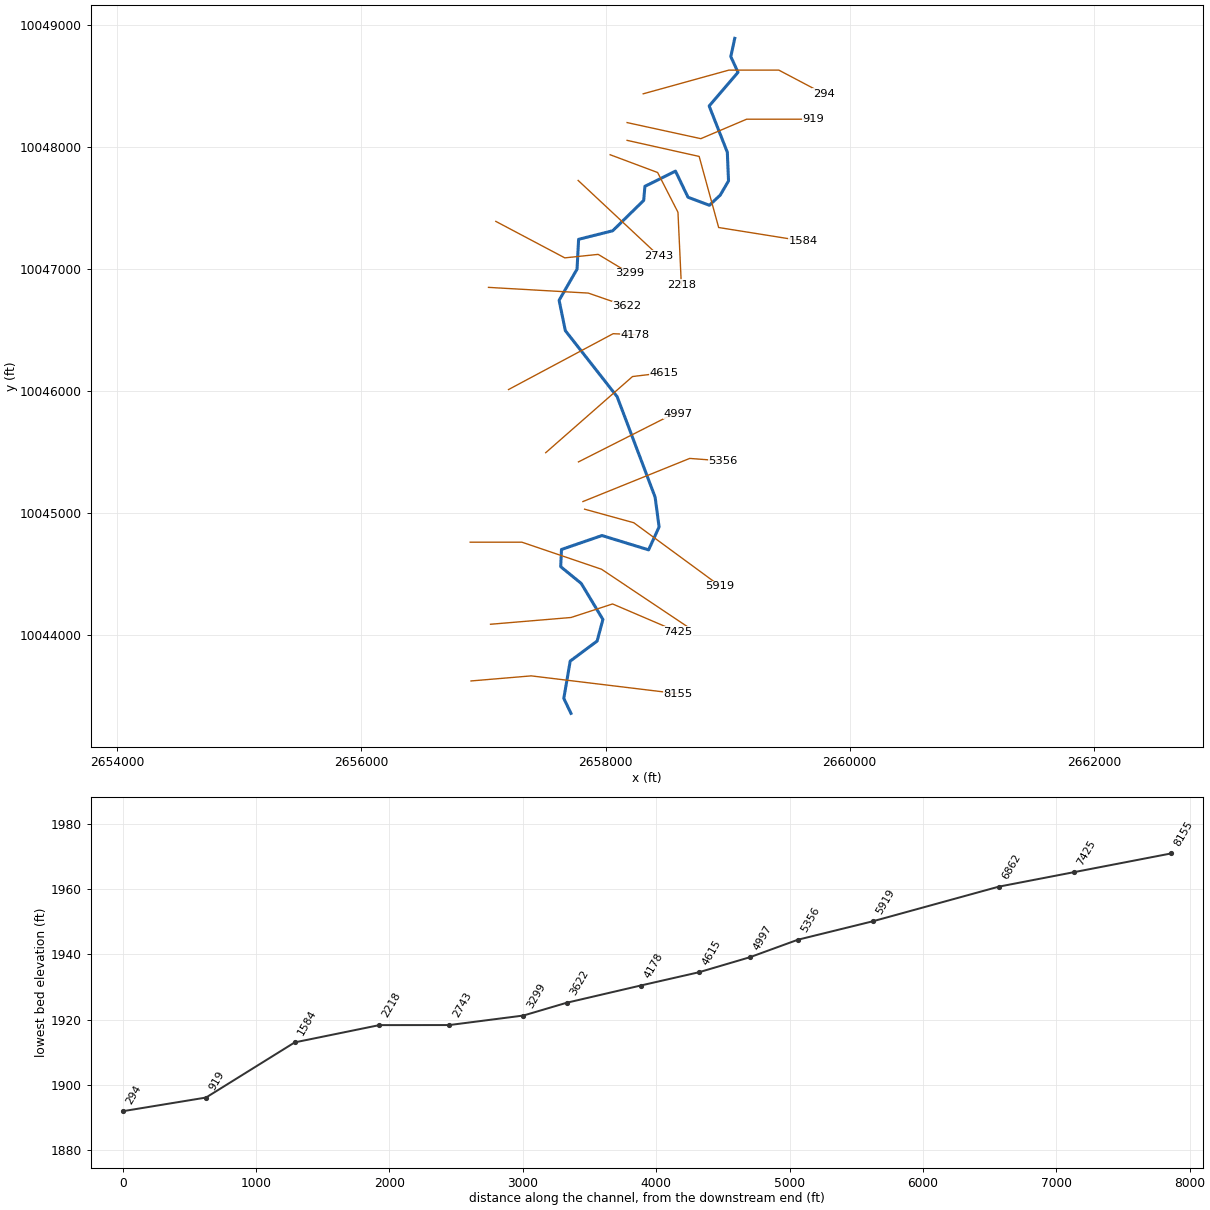
--- UNT 1047 IN HEWA.prj (project) ---

Proj Title=UNT 1047 IN HEWA Base Level Engineering
Current Plan=p01
Default Exp/Contr=0.3,0.1
English Units
Geom File=g01
Flow File=f01
Plan File=p01
BEGIN DESCRIPTION:
UNT 1047 IN HEWA
END DESCRIPTION:

--- UNT 1047 IN HEWA.p01 (plan) ---

Plan Title=Multiple Run
Short Identifier=Multiple
Geom File=g01
Flow File=f01
Subcritical Flow
K Sum by GR= 0
Std Step Tol= 0.01
Critical Tol= 0.01
Num of Std Step Trials= 20
Max Error Tol= 0.3
Flow Tol Ratio= 0.001
Split Flow NTrial= 30
Split Flow Tol= 0.02
Split Flow Ratio= 0.02
Log Output Level= 0
Friction Slope Method= 1
Unsteady Friction Slope Method= 2
Unsteady Bridges Friction Slope Method= 1
Parabolic Critical Depth
Global Vel Dist=  1 , 1 , 1
Global Log Level= 0
CheckData=True
Encroach Param= -1, 0, 0, 0
BEGIN DESCRIPTION:
Multiple Run
END DESCRIPTION:

--- UNT 1047 IN HEWA.f01 (steady flow) ---

Flow Title=Multiple
Number of Profiles=7
Profile Names=10-year,25-year,50-year,1pct_min,100-year,1pct_plu,500-year
River Rch & RM= UNT 1047 IN HEWA,Reach-1,8155
    1698    2518    3238    3031    4098    5543    6567
Boundary for River Rch & Prof#=UNT 1047 IN HEWA,Reach-1,1
Up Type=0
Dn Type=3
Dn Slope=0.005
Boundary for River Rch & Prof#=UNT 1047 IN HEWA,Reach-1,2
Up Type=0
Dn Type=3
Dn Slope=0.005
Boundary for River Rch & Prof#=UNT 1047 IN HEWA,Reach-1,3
Up Type=0
Dn Type=3
Dn Slope=0.005
Boundary for River Rch & Prof#=UNT 1047 IN HEWA,Reach-1,4
Up Type=0
Dn Type=3
Dn Slope=0.005
Boundary for River Rch & Prof#=UNT 1047 IN HEWA,Reach-1,5
Up Type=0
Dn Type=3
Dn Slope=0.005
Boundary for River Rch & Prof#=UNT 1047 IN HEWA,Reach-1,6
Up Type=0
Dn Type=3
Dn Slope=0.005
Boundary for River Rch & Prof#=UNT 1047 IN HEWA,Reach-1,7
Up Type=0
Dn Type=3
Dn Slope=0.005

--- UNT 1047 IN HEWA.g01 (geometry) ---

Geom Title=Existing Conditions

River Reach=UNT 1047 IN HEWA,Reach-1
Reach XY= 30
      2657716.73     10043353.73      2657658.03     10043476.64
      2657710.62     10043782.86      2657931.02     10043947.17
      2657978.39     10044124.64      2657800.80     10044420.07
      2657632.72     10044557.64      2657639.16     10044698.89
      2657970.62     10044813.12      2658352.75     10044695.87
      2658438.69     10044883.68      2658406.20     10045128.25
      2658095.21     10045952.38      2657670.73     10046494.65
      2657619.63     10046743.87      2657766.58     10046999.56
      2657779.30     10047244.22      2658058.65     10047314.49
      2658312.52     10047563.44      2658322.52     10047679.12
      2658573.18     10047803.85      2658675.65     10047589.46
      2658850.77     10047523.65      2658939.74     10047607.26
      2659007.56     10047723.75      2658997.65     10047958.99
      2658848.95     10048338.46      2659085.31     10048615.25
      2659026.08     10048743.51      2659058.47     10048893.73

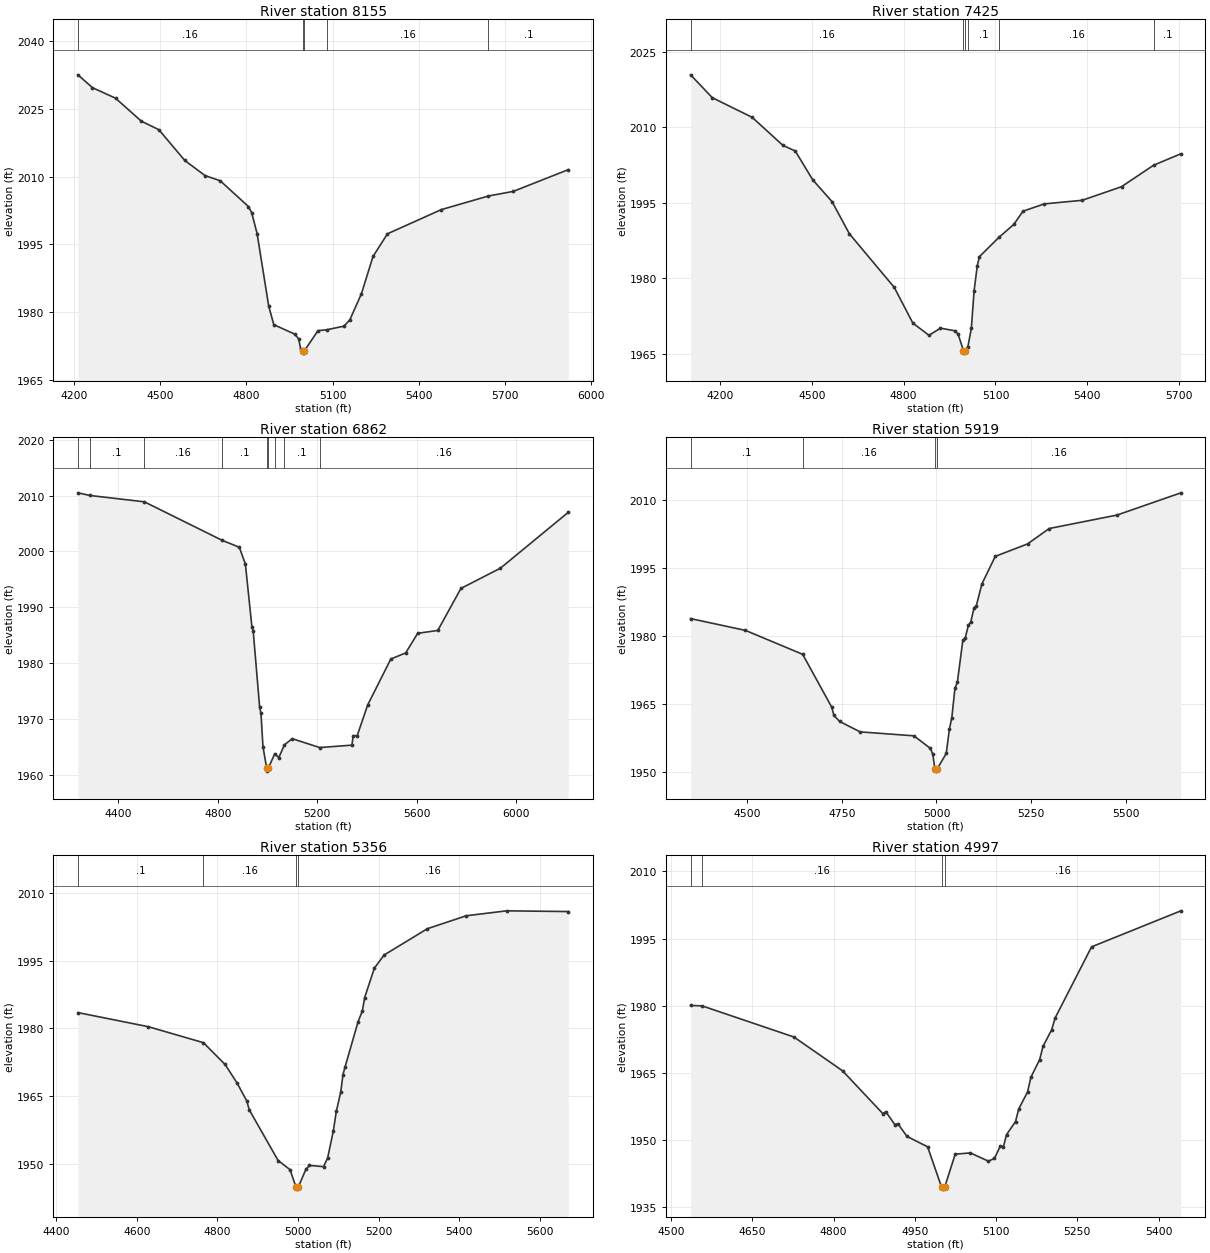
Type RM Length L Ch R = 1,8155,730,730,730
BEGIN DESCRIPTION:
UNT 1047 IN HEWA 18.0
END DESCRIPTION:
XS GIS Cut Line= 3
      2656898.04     10043619.83      2657391.07     10043661.49
      2658592.46     10043515.66
#Sta/Elev= 30
  4214.6 2032.53  4265.2 2029.68  4345.5 2027.35  4434.9 2022.27  4496.0 2020.37
  4586.3 2013.55  4656.6 2010.21  4709.4 2009.06  4807.5 2003.35  4818.9 2001.96
  4837.7 1997.34  4878.0 1981.28  4895.7 1977.18  4968.7 1975.07  4982.5 1973.99
  4988.8 1971.86  4995.9 1971.37  4998.6 1970.87  5001.9 1971.37  5049.3 1975.85
  5079.2 1976.04  5139.9 1976.85  5160.1 1978.25  5200.4 1984.03  5240.7 1992.29
  5291.0 1997.31  5478.3 2002.67  5641.8 2005.68  5728.7 2006.71  5919.6 2011.52
#Mann=5,-1,0
  4214.6    0.16       0  4995.9    0.07       0  5001.9    0.16       0
  5079.2    0.16       0  5641.8     0.1       0
Bank Sta=4995.9,5001.9
Exp/Cntr=0.3,0.1

Type RM Length L Ch R = 1,7425,563,563,563
BEGIN DESCRIPTION:
UNT 1047 IN HEWA 17.0
END DESCRIPTION:
XS GIS Cut Line= 4
      2657057.78     10044085.11      2657717.46     10044140.66
      2658057.74     10044251.77      2658592.43     10044022.62
#Sta/Elev= 30
  4104.1 2020.39  4175.0 2015.85  4305.5 2011.94  4405.9 2006.37  4446.0 2005.27
  4503.0 1999.55  4566.4 1995.19  4622.8 1988.83  4769.3 1978.19  4830.3 1971.08
  4882.9 1968.66  4920.4 1970.08  4967.0 1969.56  4977.6 1968.95  4995.6 1965.62
  4998.4 1965.12  5001.6 1965.62  5009.9 1966.37  5021.3 1970.05  5030.2 1977.46
  5040.7 1982.51  5047.9 1984.30  5112.2 1988.16  5160.1 1990.69  5190.1 1993.31
  5259.8 1994.76  5383.1 1995.47  5511.8 1998.17  5616.9 2002.45  5705.8 2004.71
#Mann=6,-1,0
  4104.1    0.16       0  4995.6    0.07       0  5001.6    0.16       0
  5009.9     0.1       0  5112.2    0.16       0  5616.9     0.1       0
Bank Sta=4995.6,5001.6
Exp/Cntr=0.3,0.1

Type RM Length L Ch R = 1,6862,943,943,943
BEGIN DESCRIPTION:
UNT 1047 IN HEWA 15.0
END DESCRIPTION:
XS GIS Cut Line= 4
      2656891.10     10044758.71      2657314.69     10044758.71
      2657967.46     10044536.49      2658681.67     10044058.04
#Sta/Elev= 30
  4237.5 2010.50  4285.1 2010.03  4504.7 2008.89  4817.7 2002.00  4886.9 2000.76
  4911.3 1997.74  4937.4 1986.54  4942.7 1985.78  4968.7 1972.08  4974.0 1971.01
  4982.0 1965.06  4997.1 1961.19  4999.8 1960.69  5003.1 1961.19  5029.6 1963.82
  5045.4 1963.10  5068.6 1965.40  5099.5 1966.50  5210.2 1964.91  5339.8 1965.34
  5345.1 1967.03  5361.2 1967.04  5403.3 1972.53  5496.3 1980.75  5556.3 1981.85
  5604.6 1985.36  5685.4 1985.87  5778.5 1993.39  5937.6 1997.02  6210.3 2007.01
#Mann=9,-1,0
  4237.5    0.16       0  4285.1     0.1       0  4504.7    0.16       0
  4817.7     0.1       0  4997.1    0.07       0  5003.1     0.1       0
  5029.6    0.16       0  5068.6     0.1       0  5210.2    0.16       0
Bank Sta=4997.1,5003.1
Exp/Cntr=0.3,0.1

Type RM Length L Ch R = 1,5919,563,563,563
BEGIN DESCRIPTION:
UNT 1047 IN HEWA 13.0
END DESCRIPTION:
XS GIS Cut Line= 3
      2657828.58     10045029.55      2658231.35     10044918.44
      2658938.94     10044398.15
#Sta/Elev= 30
  4350.1 1983.83  4495.2 1981.22  4646.4 1975.93  4723.4 1964.21  4728.9 1962.44
  4744.2 1961.08  4798.3 1958.78  4940.3 1957.91  4984.2 1955.12  4990.4 1953.82
  4995.9 1950.60  4998.6 1950.10  5001.9 1950.60  5025.9 1954.00  5034.4 1959.47
  5040.6 1961.89  5049.0 1968.47  5055.2 1969.70  5069.9 1979.08  5076.1 1979.53
  5084.5 1982.36  5090.7 1983.07  5099.2 1986.13  5105.4 1986.65  5120.0 1991.46
  5155.5 1997.59  5241.1 2000.35  5298.1 2003.75  5477.2 2006.72  5646.2 2011.64
#Mann=4,-1,0
  4350.1     0.1       0  4646.4    0.16       0  4995.9    0.07       0
  5001.9    0.16       0
Bank Sta=4995.9,5001.9
Exp/Cntr=0.3,0.1

Type RM Length L Ch R = 1,5356,359,359,359
BEGIN DESCRIPTION:
UNT 1047 IN HEWA 12.0
END DESCRIPTION:
XS GIS Cut Line= 3
      2657814.68     10045092.04      2658689.69     10045446.21
      2658960.52     10045425.38
#Sta/Elev= 30
  4454.3 1983.49  4628.8 1980.37  4765.3 1976.84  4819.2 1972.01  4848.7 1967.93
  4872.8 1963.97  4879.1 1961.97  4950.6 1950.77  4980.1 1948.75  4994.8 1944.94
  4997.5 1944.44  5000.8 1944.94  5019.4 1948.81  5028.3 1949.69  5063.2 1949.41
  5073.3 1951.31  5087.3 1957.21  5094.9 1961.66  5105.7 1965.85  5111.4 1969.78
  5116.8 1971.54  5148.8 1981.46  5159.6 1983.91  5165.1 1986.80  5189.2 1993.32
  5213.3 1996.22  5320.5 2002.04  5417.1 2004.91  5517.4 2006.00  5669.9 2005.84
#Mann=4,-1,0
  4454.3     0.1       0  4765.3    0.16       0  4994.8    0.07       0
  5000.8    0.16       0
Bank Sta=4994.8,5000.8
Exp/Cntr=0.3,0.1

Type RM Length L Ch R = 1,4997,382,382,382
BEGIN DESCRIPTION:
UNT 1047 IN HEWA 11.0
END DESCRIPTION:
XS GIS Cut Line= 3
      2657778.27     10045417.59      2658523.02     10045795.17
      2658590.71     10045813.40
#Sta/Elev= 30
  4536.0 1980.10  4557.3 1980.00  4726.8 1973.05  4816.5 1965.51  4890.9 1955.95
  4896.5 1956.36  4913.1 1953.49  4918.8 1953.69  4935.4 1950.87  4973.5 1948.54
  4999.2 1939.59  5002.0 1939.09  5005.2 1939.59  5024.5 1946.89  5052.4 1947.18
  5085.6 1945.34  5096.9 1945.93  5108.0 1948.77  5113.5 1948.56  5119.2 1951.25
  5135.8 1954.17  5141.7 1956.97  5158.1 1960.80  5164.1 1964.04  5180.4 1968.01
  5186.5 1970.94  5202.6 1974.69  5208.9 1977.29  5276.2 1993.18  5441.1 2001.22
#Mann=4,-1,0
  4536.0     0.1       0  4557.3    0.16       0  4999.2    0.07       0
  5005.2    0.16       0
Bank Sta=4999.2,5005.2
Exp/Cntr=0.3,0.1

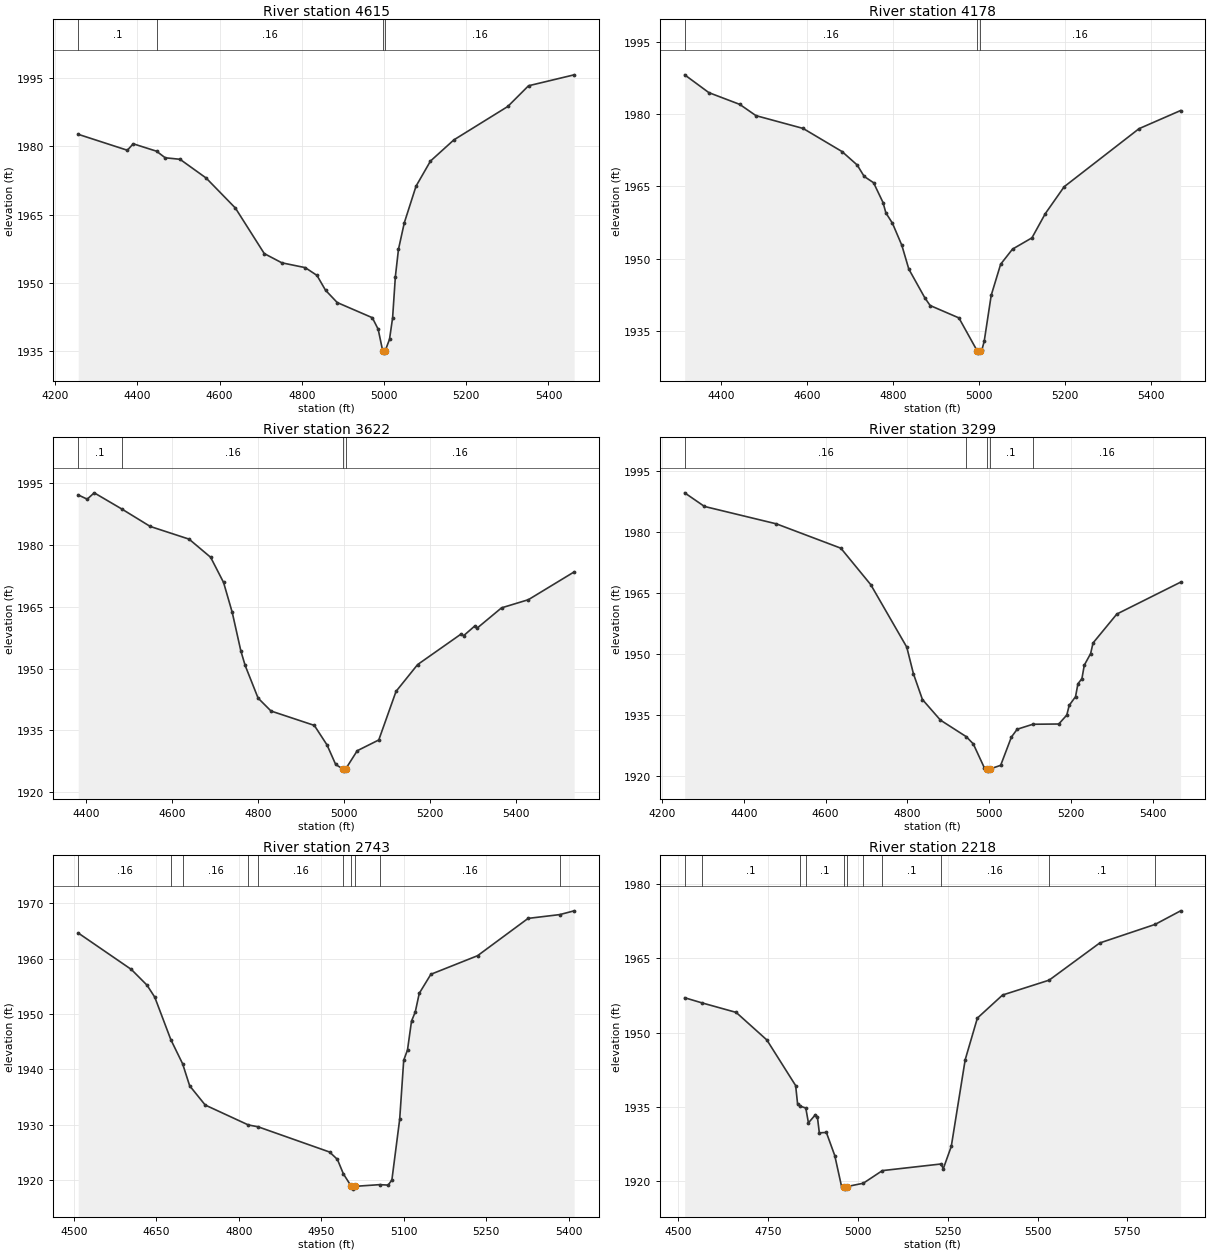
Type RM Length L Ch R = 1,4615,437,437,437
BEGIN DESCRIPTION:
UNT 1047 IN HEWA 10.0
END DESCRIPTION:
XS GIS Cut Line= 3
      2657509.97     10045493.06      2658220.94     10046118.09
      2658478.70     10046149.33
#Sta/Elev= 30
  4256.2 1982.68  4375.7 1979.17  4390.0 1980.59  4446.7 1978.96  4467.8 1977.51
  4503.8 1977.18  4567.4 1973.05  4638.6 1966.43  4708.8 1956.41  4751.5 1954.38
  4808.4 1953.32  4836.9 1951.61  4857.7 1948.35  4886.2 1945.63  4971.6 1942.29
  4985.8 1939.75  4996.8 1934.99  4999.6 1934.49  5002.8 1934.99  5013.4 1937.54
  5020.9 1942.25  5027.6 1951.31  5035.2 1957.36  5049.4 1963.20  5077.9 1971.26
  5113.0 1976.79  5169.9 1981.45  5301.1 1988.81  5351.5 1993.37  5462.5 1995.78
#Mann=4,-1,0
  4256.2     0.1       0  4446.7    0.16       0  4996.8    0.07       0
  5002.8    0.16       0
Bank Sta=4996.8,5002.8
Exp/Cntr=0.3,0.1

Type RM Length L Ch R = 1,4178,556,556,556
BEGIN DESCRIPTION:
UNT 1047 IN HEWA 9.0
END DESCRIPTION:
XS GIS Cut Line= 3
      2657205.35     10046011.34      2658062.08     10046469.65
      2658245.20     10046461.91
#Sta/Elev= 30
  4314.6 1988.11  4370.9 1984.42  4442.9 1981.98  4480.6 1979.65  4590.3 1977.00
  4681.1 1972.20  4716.3 1969.42  4732.6 1967.05  4754.5 1965.74  4776.5 1961.64
  4783.1 1959.50  4798.4 1957.35  4820.3 1952.77  4836.6 1947.83  4873.8 1941.89
  4886.2 1940.29  4953.2 1937.72  4995.6 1930.92  4998.3 1930.42  5001.6 1930.92
  5006.5 1931.02  5012.1 1932.87  5028.4 1942.40  5050.4 1948.85  5078.0 1951.98
  5123.3 1954.32  5154.4 1959.34  5198.3 1964.91  5372.7 1976.95  5469.5 1980.71
#Mann=3,-1,0
  4314.6    0.16       0  4995.6    0.07       0  5001.6    0.16       0
Bank Sta=4995.6,5001.6
Exp/Cntr=0.3,0.1

Type RM Length L Ch R = 1,3622,323,323,323
BEGIN DESCRIPTION:
UNT 1047 IN HEWA 8.0
END DESCRIPTION:
XS GIS Cut Line= 3
      2657041.29     10046849.86      2657858.96     10046802.99
      2658173.73     10046693.73
#Sta/Elev= 30
  4382.5 1992.22  4403.4 1991.19  4419.7 1992.73  4484.4 1988.76  4549.9 1984.56
  4640.1 1981.48  4690.2 1977.07  4720.2 1970.96  4740.3 1963.70  4760.3 1954.35
  4770.3 1950.81  4800.4 1942.87  4830.4 1939.73  4931.0 1936.24  4960.6 1931.48
  4980.7 1926.74  4997.7 1925.63  5000.4 1925.13  5003.7 1925.63  5030.7 1930.08
  5080.8 1932.70  5120.9 1944.50  5171.0 1951.01  5272.6 1958.47  5277.9 1958.03
  5303.8 1960.38  5309.0 1959.84  5366.0 1964.79  5428.3 1966.77  5534.7 1973.52
#Mann=4,-1,0
  4382.5     0.1       0  4484.4    0.16       0  4997.7    0.07       0
  5003.7    0.16       0
Bank Sta=4997.7,5003.7
Exp/Cntr=0.3,0.1

Type RM Length L Ch R = 1,3299,556,556,556
BEGIN DESCRIPTION:
UNT 1047 IN HEWA 7.0
END DESCRIPTION:
XS GIS Cut Line= 4
      2657101.10     10047391.55      2657666.25     10047092.05
      2657939.69     10047120.69      2658194.87     10046967.06
#Sta/Elev= 30
  4255.4 1989.74  4303.7 1986.39  4479.7 1982.10  4637.2 1976.11  4710.3 1967.13
  4798.3 1951.76  4814.6 1945.21  4836.6 1938.86  4880.6 1933.79  4943.8 1929.71
  4960.9 1927.94  4987.7 1922.11  4994.8 1921.73  4997.5 1921.23  5000.8 1921.73
  5027.9 1922.66  5054.1 1929.61  5068.2 1931.54  5106.7 1932.77  5169.9 1932.83
  5189.6 1935.04  5195.4 1937.42  5210.9 1939.56  5216.8 1942.74  5226.5 1944.00
  5232.3 1947.31  5247.8 1950.17  5253.7 1952.78  5311.9 1959.90  5467.8 1967.75
#Mann=5,-1,0
  4255.4    0.16       0  4943.8     0.1       0  4994.8    0.07       0
  5000.8     0.1       0  5106.7    0.16       0
Bank Sta=4994.8,5000.8
Exp/Cntr=0.3,0.1

Type RM Length L Ch R = 1,2743,525,525,525
BEGIN DESCRIPTION:
UNT 1047 IN HEWA 6.0
END DESCRIPTION:
XS GIS Cut Line= 2
      2657775.66     10047727.43      2658433.94     10047110.78
#Sta/Elev= 30
  4507.8 1964.64  4604.5 1958.04  4632.8 1955.22  4647.0 1953.04  4676.2 1945.36
  4697.7 1940.98  4710.5 1937.00  4738.8 1933.52  4817.2 1929.92  4835.1 1929.58
  4965.0 1925.02  4979.2 1923.69  4990.1 1921.07  5004.5 1918.81  5007.3 1918.31
  5010.5 1918.81  5056.0 1919.12  5071.5 1919.04  5078.3 1919.96  5092.5 1930.96
  5099.8 1941.62  5106.7 1943.49  5114.0 1948.70  5120.8 1950.35  5128.1 1953.73
  5149.2 1957.17  5234.1 1960.53  5326.0 1967.28  5383.7 1967.97  5409.8 1968.65
#Mann=10,-1,0
  4507.8    0.16       0  4676.2     0.1       0  4697.7    0.16       0
  4817.2     0.1       0  4835.1    0.16       0  4990.1     0.1       0
  5004.5    0.07       0  5010.5     0.1       0  5056.0    0.16       0
  5383.7     0.1       0
Bank Sta=5004.5,5010.5
Exp/Cntr=0.3,0.1

Type RM Length L Ch R = 1,2218,634,634,634
BEGIN DESCRIPTION:
UNT 1047 IN HEWA 5.0
END DESCRIPTION:
XS GIS Cut Line= 4
      2658037.76     10047938.41      2658426.66     10047792.57
      2658593.33     10047466.18      2658621.11     10046868.96
#Sta/Elev= 30
  4518.3 1957.05  4565.8 1956.02  4661.5 1954.08  4746.9 1948.50  4827.0 1939.26
  4832.4 1935.55  4840.5 1935.07  4855.2 1934.72  4862.6 1931.71  4882.2 1933.38
  4887.6 1932.87  4892.9 1929.69  4912.5 1929.77  4935.8 1925.09  4954.8 1918.81
  4962.5 1918.79  4965.3 1918.29  4968.5 1918.79  5015.1 1919.48  5068.3 1922.04
  5231.2 1923.38  5237.8 1922.44  5260.0 1926.95  5298.7 1944.50  5332.6 1952.93
  5402.7 1957.60  5532.2 1960.61  5673.0 1968.14  5827.0 1971.90  5898.0 1974.65
#Mann=11,-1,0
  4518.3    0.16       0  4565.8     0.1       0  4840.5    0.16       0
  4855.2     0.1       0  4962.5    0.07       0  4968.5     0.1       0
  5015.1    0.16       0  5068.3     0.1       0  5231.2    0.16       0
  5532.2     0.1       0  5827.0    0.16       0
Bank Sta=4962.5,4968.5
Exp/Cntr=0.3,0.1

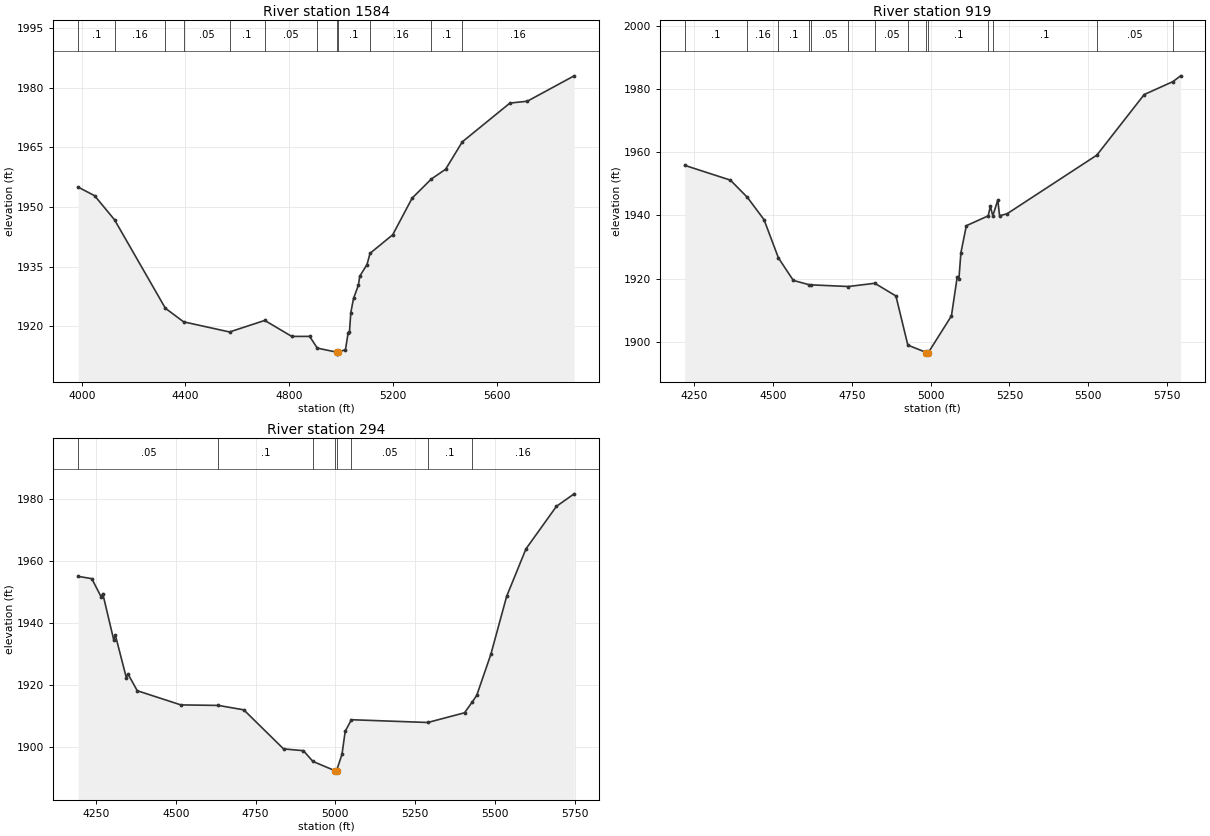
Type RM Length L Ch R = 1,1584,665,665,665
BEGIN DESCRIPTION:
UNT 1047 IN HEWA 4.0
END DESCRIPTION:
XS GIS Cut Line= 4
      2658176.66     10048056.46      2658766.94     10047924.51
      2658926.66     10047341.18      2659621.07     10047230.07
#Sta/Elev= 30
  3986.5 1954.97  4049.8 1952.81  4126.5 1946.77  4322.7 1924.53  4393.2 1921.11
  4570.2 1918.57  4706.1 1921.47  4810.2 1917.45  4879.2 1917.46  4908.7 1914.51
  4983.1 1913.50  4985.9 1913.00  4989.1 1913.50  5017.3 1914.12  5027.5 1918.30
  5032.7 1918.53  5038.0 1923.44  5048.4 1926.99  5067.2 1930.32  5072.4 1932.59
  5100.2 1935.48  5112.2 1938.34  5199.6 1943.00  5274.4 1952.20  5348.7 1957.02
  5403.6 1959.46  5468.0 1966.35  5651.7 1976.09  5718.8 1976.56  5899.4 1982.94
#Mann=12,-1,0
  3986.5     0.1       0  4126.5    0.16       0  4322.7     0.1       0
  4393.2    0.05       0  4570.2     0.1       0  4706.1    0.05       0
  4908.7     0.1       0  4983.1    0.07       0  4989.1     0.1       0
  5112.2    0.16       0  5348.7     0.1       0  5468.0    0.16       0
Bank Sta=4983.1,4989.1
Exp/Cntr=0.3,0.1

Type RM Length L Ch R = 1,919,625,625,625
BEGIN DESCRIPTION:
UNT 1047 IN HEWA 2.0
END DESCRIPTION:
XS GIS Cut Line= 4
      2658176.67     10048202.29      2658780.83     10048070.35
      2659155.83     10048230.07      2659703.93     10048230.07
#Sta/Elev= 30
  4219.2 1955.80  4364.3 1951.12  4418.4 1945.66  4471.0 1938.63  4516.8 1926.53
  4563.9 1919.43  4615.0 1918.03  4618.8 1918.02  4738.6 1917.49  4822.7 1918.51
  4889.7 1914.50  4927.5 1898.96  4986.6 1896.61  4989.4 1896.11  4992.6 1896.61
  5065.9 1908.20  5084.1 1920.43  5089.6 1919.84  5095.9 1928.14  5113.2 1936.71
  5182.5 1939.83  5189.5 1942.85  5197.2 1939.84  5213.1 1944.84  5218.6 1939.87
  5242.2 1940.47  5527.3 1959.02  5677.8 1978.19  5768.9 1982.27  5793.3 1984.10
#Mann=14,-1,0
  4219.2     0.1       0  4418.4    0.16       0  4516.8     0.1       0
  4615.0    0.16       0  4618.8    0.05       0  4738.6     0.1       0
  4822.7    0.05       0  4927.5     0.1       0  4986.6    0.07       0
  4992.6     0.1       0  5182.5    0.16       0  5197.2     0.1       0
  5527.3    0.05       0  5768.9     0.1       0
Bank Sta=4986.6,4992.6
Exp/Cntr=0.3,0.1

Type RM Length L Ch R = 1,294,0,0,0
BEGIN DESCRIPTION:
UNT 1047 IN HEWA 1.0
END DESCRIPTION:
XS GIS Cut Line= 4
      2658308.61     10048438.40      2659010.00     10048632.85
      2659419.72     10048632.85      2659787.49     10048438.55
#Sta/Elev= 30
  4194.6 1955.01  4237.2 1954.28  4266.3 1948.42  4271.5 1949.46  4305.8 1934.57
  4311.0 1936.06  4345.2 1922.41  4350.4 1923.58  4379.5 1918.16  4516.1 1913.59
  4633.9 1913.42  4713.3 1911.99  4837.8 1899.41  4900.1 1898.83  4929.6 1895.38
  4997.9 1892.42  5000.7 1891.92  5003.9 1892.42  5020.9 1897.67  5030.9 1905.08
  5050.4 1908.81  5289.6 1907.92  5404.7 1911.05  5429.5 1914.61  5443.1 1916.71
  5487.1 1929.87  5536.8 1948.63  5597.2 1963.88  5692.7 1977.60  5748.1 1981.62
#Mann=8,-1,0
  4194.6    0.05       0  4633.9     0.1       0  4929.6    0.16       0
  4997.9    0.07       0  5003.9    0.16       0  5050.4    0.05       0
  5289.6     0.1       0  5429.5    0.16       0
Bank Sta=4997.9,5003.9
Exp/Cntr=0.3,0.1

Chan Stop Cuts=-1