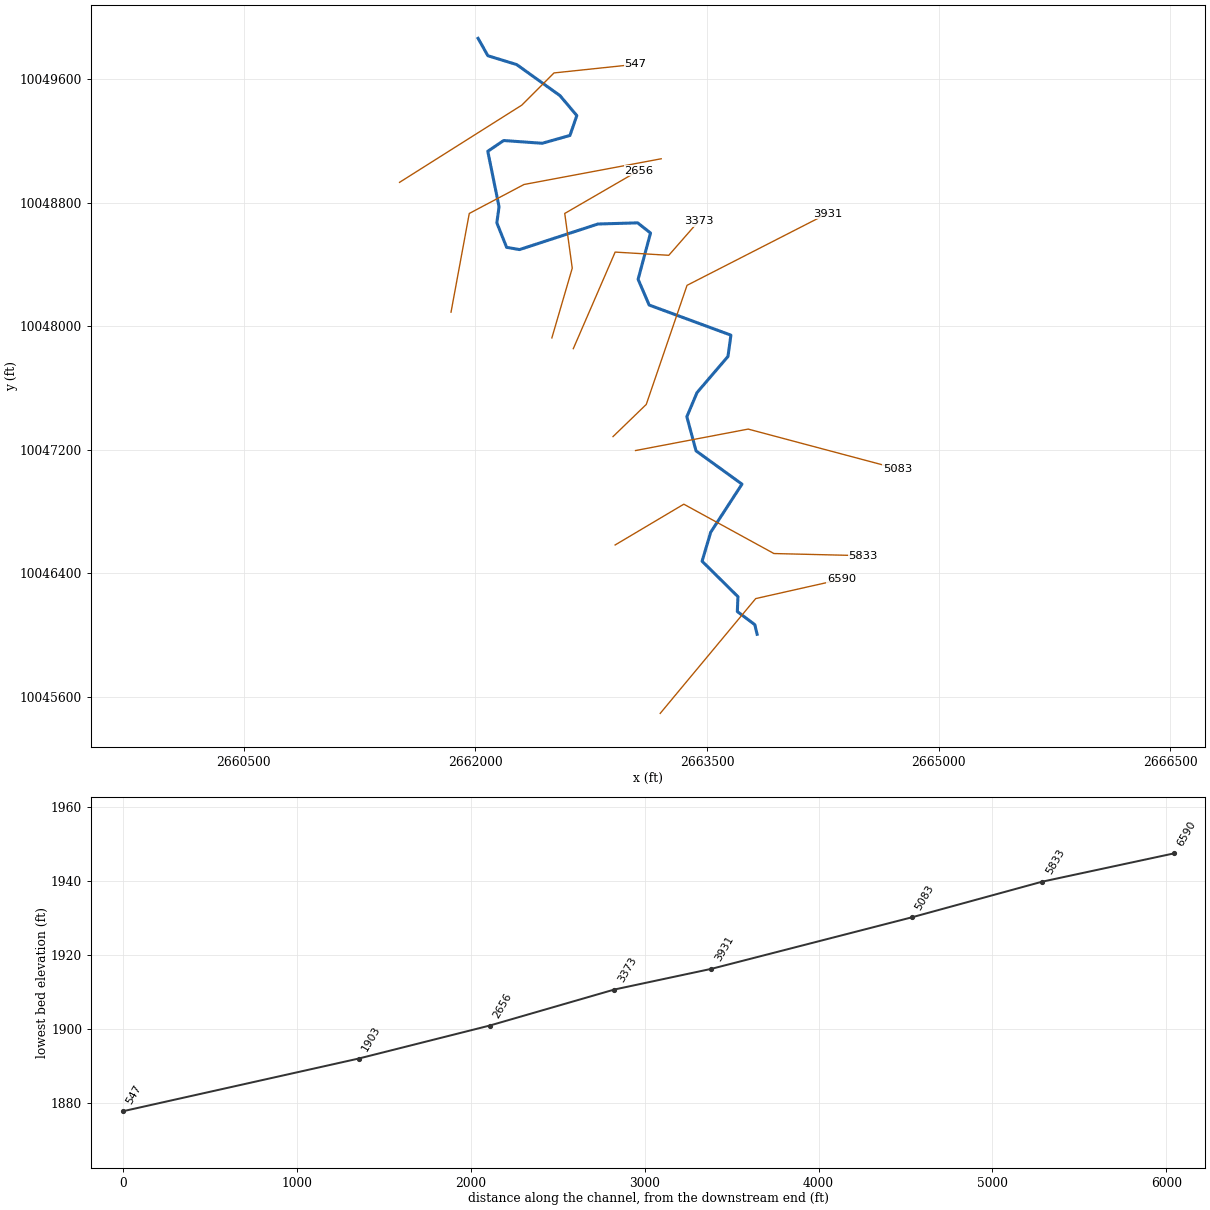
--- UNT 1048 IN HEWA.prj (project) ---

Proj Title=UNT 1048 IN HEWA Base Level Engineering
Current Plan=p01
Default Exp/Contr=0.3,0.1
English Units
Geom File=g01
Flow File=f01
Plan File=p01
Y Axis Title=Elevation
X Axis Title(PF)=Main Channel Distance
X Axis Title(XS)=Station
BEGIN DESCRIPTION:
UNT 1048 IN HEWA
END DESCRIPTION:
DSS Export Rating Curves= 0
DSS Export Rating Curve Sorted= 0
DSS Export Volume Flow Curves= 0
DXF OffsetX= 0
DXF OffsetY= 0
DXF ScaleX= 1
DXF ScaleY= 10

--- UNT 1048 IN HEWA.p01 (plan) ---

Plan Title=Multiple Run
Short Identifier=Multiple
Geom File=g01
Flow File=f01
Subcritical Flow
K Sum by GR= 0
Std Step Tol= 0.01
Critical Tol= 0.01
Num of Std Step Trials= 20
Max Error Tol= 0.3
Flow Tol Ratio= 0.001
Split Flow NTrial= 30
Split Flow Tol= 0.02
Split Flow Ratio= 0.02
Log Output Level= 0
Friction Slope Method= 1
Unsteady Friction Slope Method= 2
Unsteady Bridges Friction Slope Method= 1
Parabolic Critical Depth
Global Vel Dist=  1 , 1 , 1
Global Log Level= 0
CheckData=True
Encroach Param= -1, 0, 0, 0
BEGIN DESCRIPTION:
Multiple Run
END DESCRIPTION:

--- UNT 1048 IN HEWA.f01 (steady flow) ---

Flow Title=Multiple
Number of Profiles=7
Profile Names=10-year,25-year,50-year,1pct_min,100-year,1pct_plu,500-year
River Rch & RM= UNT 1048 IN HEWA,Reach-1,6590
    1123    1635    2078    1926    2604    3522    4088
River Rch & RM= UNT 1048 IN HEWA,Reach-1,5083
    1489    2198    2818    2632    3560    4814    5679
Boundary for River Rch & Prof#=UNT 1048 IN HEWA,Reach-1,1
Up Type=0
Dn Type=3
Dn Slope=0.005
Boundary for River Rch & Prof#=UNT 1048 IN HEWA,Reach-1,2
Up Type=0
Dn Type=3
Dn Slope=0.005
Boundary for River Rch & Prof#=UNT 1048 IN HEWA,Reach-1,3
Up Type=0
Dn Type=3
Dn Slope=0.005
Boundary for River Rch & Prof#=UNT 1048 IN HEWA,Reach-1,4
Up Type=0
Dn Type=3
Dn Slope=0.005
Boundary for River Rch & Prof#=UNT 1048 IN HEWA,Reach-1,5
Up Type=0
Dn Type=3
Dn Slope=0.005
Boundary for River Rch & Prof#=UNT 1048 IN HEWA,Reach-1,6
Up Type=0
Dn Type=3
Dn Slope=0.005
Boundary for River Rch & Prof#=UNT 1048 IN HEWA,Reach-1,7
Up Type=0
Dn Type=3
Dn Slope=0.005

--- UNT 1048 IN HEWA.g01 (geometry) ---

Geom Title=Existing Conditions
Program Version=4.10

River Reach=UNT 1048 IN HEWA,Reach-1
Reach XY= 30
      2663824.78     10046005.99      2663809.77     10046068.23
      2663696.72     10046153.08      2663700.63     10046249.48
      2663468.58     10046479.02      2663524.17     10046666.08
      2663726.75     10046977.86      2663429.51     10047193.25
      2663369.84     10047414.13      2663435.67     10047570.24
      2663636.22     10047804.67      2663655.06     10047942.37
      2663126.07     10048137.24      2663054.37     10048303.71
      2663134.73     10048603.48      2663051.39     10048669.27
      2662794.27     10048661.79      2662287.14     10048496.34
      2662203.18      10048510.7      2662139.86     10048669.53
      2662154.27     10048772.92      2662081.34     10049132.51
      2662183.91     10049202.16      2662433.72     10049184.41
      2662613.18     10049235.08       2662657.7     10049363.79
      2662548.57     10049492.89      2662268.57      10049693.8
      2662081.77     10049751.16      2662018.47     10049863.73

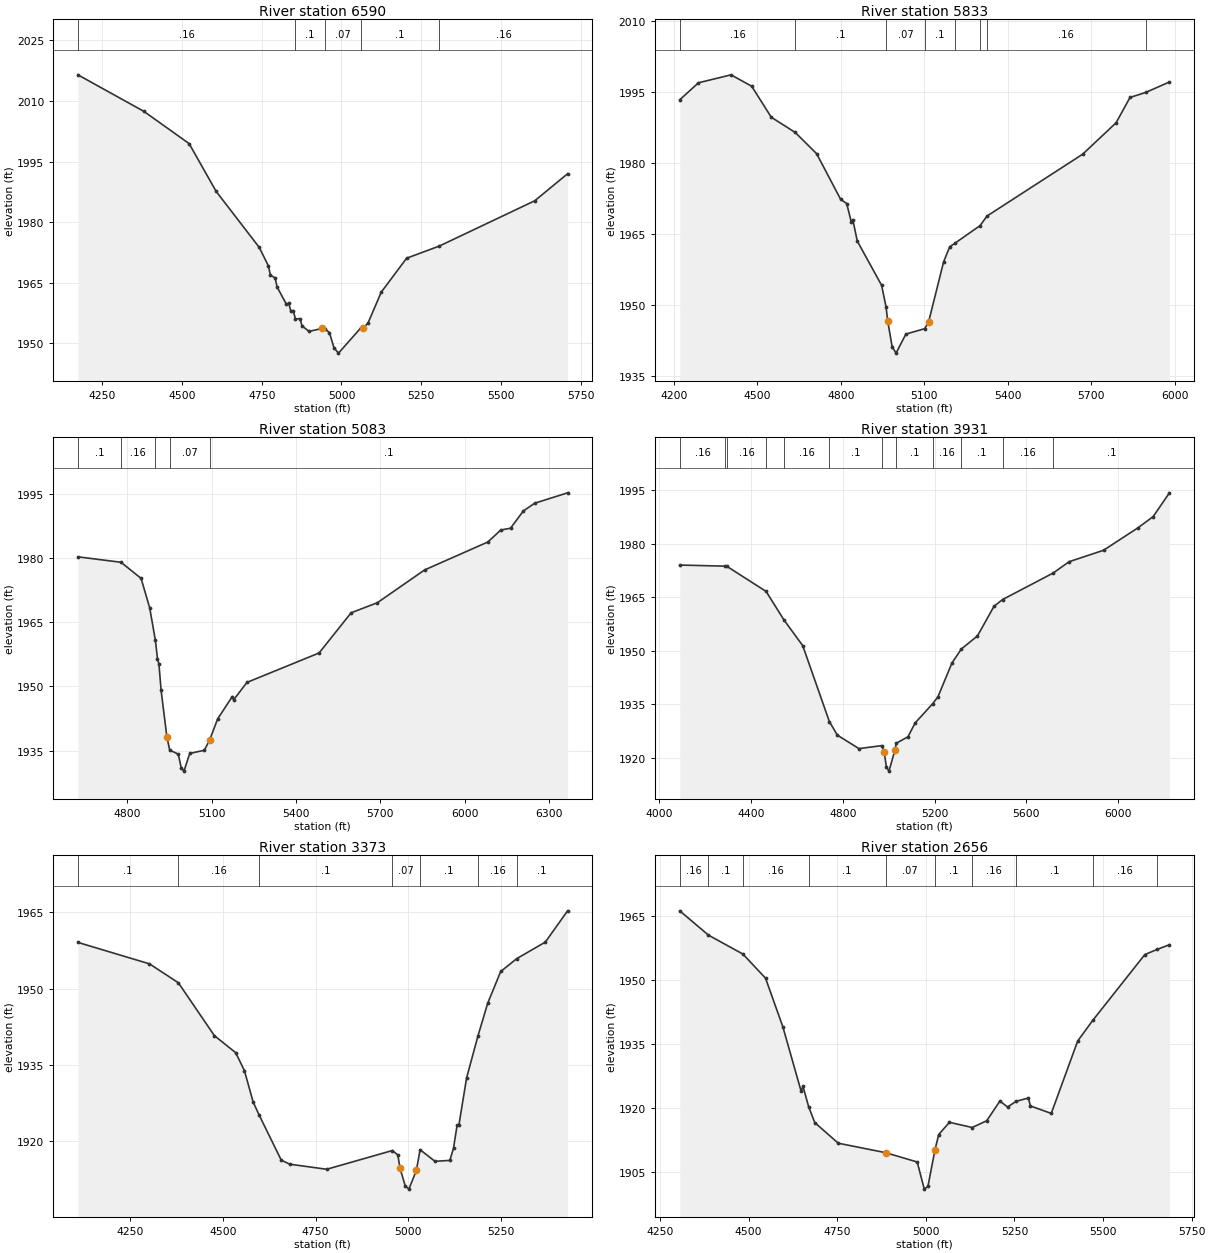
Type RM Length L Ch R = 1 ,6590    ,757,757,757
BEGIN DESCRIPTION:
UNT 1048 IN HEWA 11.0
END DESCRIPTION:
XS GIS Cut Line= 3
      2663197.51     10045493.98      2663815.55     10046237.01
      2664371.09     10046362.01
#Sta/Elev= 30
  4173.4 2016.48  4380.3 2007.43  4522.3 1999.44  4606.9 1987.62  4742.3 1973.72
  4770.9 1969.14  4777.4 1966.78  4791.8 1966.22  4798.3  1963.9  4826.9 1959.72
  4834.7 1959.88  4841.2 1957.96    4849 1958.07  4855.5 1956.01  4869.9 1956.08
  4876.4 1954.29  4898.5 1952.92  4940.5 1953.68    4948 1953.56  4962.3 1952.64
  4976.6 1948.87  4990.7 1947.54  5061.2 1953.82  5069.1 1953.81  5083.4    1955
    5125 1962.66  5204.4 1971.05  5306.9 1974.06  5606.3 1985.28  5709.3 1991.98
#Mann= 5 ,-1 , 0
  4173.4     .16       0  4855.5      .1       0    4948     .07       0
  5061.2      .1       0  5306.9     .16       0
Bank Sta=4940.5,5069.1
XS Rating Curve= 0 ,0
Exp/Cntr=0.3,0.1

Type RM Length L Ch R = 1 ,5833    ,750,750,750
BEGIN DESCRIPTION:
UNT 1048 IN HEWA 10.0
END DESCRIPTION:
XS GIS Cut Line= 4
      2662905.82     10046584.23      2663350.28     10046848.12
      2663933.61     10046528.68      2664509.98     10046514.79
#Sta/Elev= 30
  4221.9 1993.41  4289.2    1997  4406.1 1998.68  4480.2 1996.27  4550.6 1989.72
  4636.7  1986.5  4713.4 1982.02  4799.7 1972.37  4821.5 1971.49  4837.6 1967.64
  4843.3 1968.09  4859.4 1963.55  4946.7 1954.22  4962.8 1949.62  4968.5 1946.71
  4984.6 1941.25  4998.7 1939.88  5033.9  1943.9  5101.6 1945.05  5115.5 1946.46
  5169.5 1959.17  5191.3 1962.34    5210  1963.1  5300.6 1966.83  5325.2 1968.84
  5668.8 1981.91  5788.8 1988.55  5838.8  1993.9  5894.9 1994.95  5980.4 1997.17
#Mann= 8 ,-1 , 0
  4221.9     .16       0  4636.7      .1       0  4962.8     .07       0
  5101.6      .1       0    5210     .16       0  5300.6      .1       0
  5325.2     .16       0  5894.9      .1       0
Bank Sta=4968.5,5115.5
XS Rating Curve= 0 ,0
Exp/Cntr=0.3,0.1

Type RM Length L Ch R = 1 ,5083    ,1152,1152,1152
BEGIN DESCRIPTION:
UNT 1048 IN HEWA 8.0
END DESCRIPTION:
XS GIS Cut Line= 3
      2663037.75     10047195.34      2663766.94     10047334.24
      2664732.23     10047077.29
#Sta/Elev= 30
  4624.5 1980.26  4777.9 1978.99  4849.2 1975.22  4879.7 1968.37  4900.1 1960.72
  4907.5 1956.46  4912.6 1955.26  4920.4 1949.05  4940.8 1938.25    4951 1935.11
  4981.5 1934.18  4991.7 1931.02  5001.6 1930.21  5022.2 1934.34  5074.2 1935.09
  5093.5 1937.58  5121.3 1942.39  5173.5 1947.64  5178.5 1946.89  5225.6 1950.93
  5482.2 1957.81    5596 1967.19  5689.2 1969.54  5857.3  1977.2  6082.4 1983.73
  6127.9 1986.52  6162.9 1986.95  6208.2 1990.96  6248.3 1992.77  6365.7 1995.21
#Mann= 5 ,-1 , 0
  4624.5      .1       0  4777.9     .16       0  4900.1      .1       0
    4951     .07       0  5093.5      .1       0
Bank Sta=4940.8,5093.5
XS Rating Curve= 0 ,0
Exp/Cntr=0.3,0.1

Type RM Length L Ch R = 1 ,3931    ,558,558,558
BEGIN DESCRIPTION:
UNT 1048 IN HEWA 6.0
END DESCRIPTION:
XS GIS Cut Line= 4
      2662891.95     10047285.63      2663107.22     10047493.96
      2663371.11     10048264.79      2664279.56     10048729.42
#Sta/Elev= 30
  4088.8    1974  4287.9 1973.69  4294.1 1973.65  4465.3  1966.6  4542.3 1958.69
  4624.9 1951.41  4741.1 1930.12    4776 1926.33  4869.9 1922.56  4969.5  1923.4
    4980 1921.48  4989.8 1917.41  5000.9 1916.25  5026.4 1922.06  5032.9 1924.07
  5083.7 1925.87    5115 1929.76  5191.6 1935.16  5214.4 1937.08  5275.4 1946.56
  5316.6 1950.49  5386.5 1954.13  5458.7 1962.44  5496.2 1964.34  5716.2 1971.75
  5786.3 1974.94  5936.2 1978.14    6086 1984.42  6152.7 1987.59  6223.5 1994.24
#Mann= 12 ,-1 , 0
  4088.8     .16       0  4287.9      .1       0  4294.1     .16       0
  4465.3      .1       0  4542.3     .16       0  4741.1      .1       0
  4969.5     .07       0  5032.9      .1       0  5191.6     .16       0
  5316.6      .1       0  5496.2     .16       0  5716.2      .1       0
Bank Sta=4980,5026.4
XS Rating Curve= 0 ,0
Exp/Cntr=0.3,0.1

Type RM Length L Ch R = 1 ,3373    ,717,717,717
BEGIN DESCRIPTION:
UNT 1048 IN HEWA 4.0
END DESCRIPTION:
XS GIS Cut Line= 4
      2662635.01     10047855.09      2662905.83     10048480.07
      2663253.05     10048459.24      2663446.34     10048680.13
#Sta/Elev= 30
  4108.2 1959.08  4301.5 1954.87  4379.5 1951.16  4476.7 1940.78  4534.5 1937.42
    4558 1933.88  4581.5 1927.74    4598 1925.14  4657.4 1916.33  4680.8 1915.53
  4780.2 1914.54  4957.6 1918.22  4972.3 1917.35    4978 1914.78  4992.3 1911.27
  5002.1 1910.64  5022.4 1914.34  5032.4 1918.38  5072.5  1916.1  5112.6 1916.28
  5122.6 1918.66  5132.4 1923.23  5137.2 1923.23    5158 1932.49  5188.5 1940.68
    5215 1947.15  5250.1 1953.37  5293.7 1955.91  5370.6 1959.14  5430.7 1965.28
#Mann= 7 ,-1 , 0
  4108.2      .1       0  4379.5     .16       0    4598      .1       0
  4957.6     .07       0  5032.4      .1       0  5188.5     .16       0
  5293.7      .1       0
Bank Sta=4978,5022.4
XS Rating Curve= 0 ,0
Exp/Cntr=0.3,0.1

Type RM Length L Ch R = 1 ,2656    ,753,753,753
BEGIN DESCRIPTION:
UNT 1048 IN HEWA 3.0
END DESCRIPTION:
XS GIS Cut Line= 4
      2662496.11     10047924.52      2662628.05      10048375.9
      2662579.44     10048730.07      2663058.59     10049007.84
#Sta/Elev= 30
  4305.7 1966.22  4386.7 1960.51  4483.7 1956.08  4547.7 1950.41  4596.6 1938.98
  4648.1 1923.87  4653.3 1925.01  4669.5 1920.19  4686.7 1916.49  4752.9 1911.65
  4886.6 1909.43  4975.7 1907.24  4995.6 1900.87  5005.9 1901.51  5025.7 1910.05
  5036.2 1913.67  5066.5 1916.56  5130.8 1915.34  5171.7 1916.92    5209 1921.55
  5230.5 1920.16  5254.9 1921.49  5289.3 1922.27  5295.1  1920.4  5353.9 1918.65
  5428.5 1935.66  5471.2 1940.52  5617.8 1955.94  5653.6 1957.19  5687.3 1958.26
#Mann= 10 ,-1 , 0
  4305.7     .16       0  4386.7      .1       0  4483.7     .16       0
  4669.5      .1       0  4886.6     .07       0  5025.7      .1       0
  5130.8     .16       0  5254.9      .1       0  5471.2     .16       0
  5653.6      .1       0
Bank Sta=4886.6,5025.7
XS Rating Curve= 0 ,0
Exp/Cntr=0.3,0.1

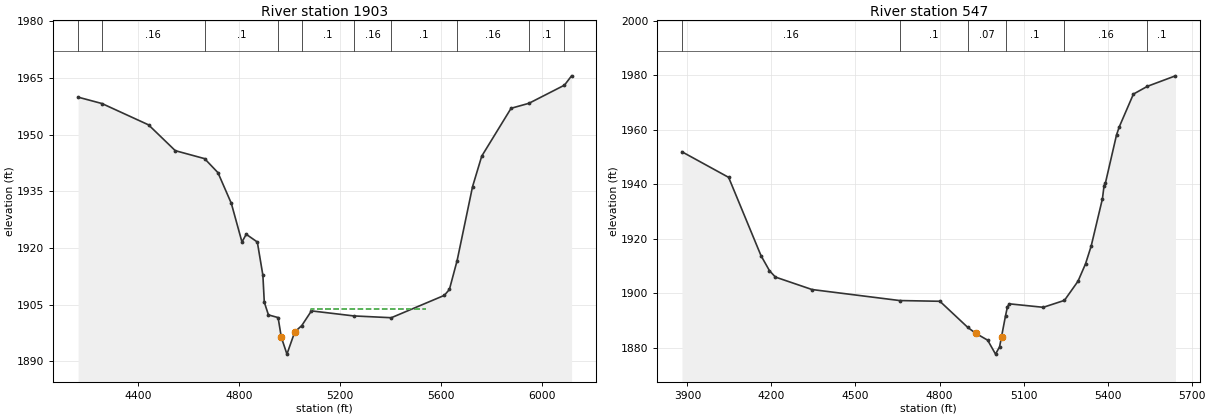
Type RM Length L Ch R = 1 ,1903    ,1356,1356,1356
BEGIN DESCRIPTION:
UNT 1048 IN HEWA 2.0
END DESCRIPTION:
XS GIS Cut Line= 4
      2661843.34     10048091.22      2661961.39     10048730.07
      2662315.55     10048917.57      2663203.97     10049084.15
#Sta/Elev= 30
  4163.6 1959.92  4258.1 1958.23  4442.6 1952.59  4548.5 1945.76  4664.6 1943.65
  4717.5 1939.94  4770.4 1931.83  4812.6 1921.59  4829.4 1923.64  4873.4 1921.59
  4895.4  1912.8    4901 1905.68  4917.4 1902.31  4955.7  1901.6  4968.4  1896.4
  4990.7 1891.93  5021.7 1897.81  5049.4 1899.48  5087.7 1903.37  5255.2 1902.04
    5404 1901.56  5613.8 1907.47  5634.1 1909.04  5664.7  1916.7  5725.7 1936.23
  5762.1 1944.31  5878.3 1956.97    5949 1958.29  6089.7 1963.09  6117.9 1965.56
#Mann= 10 ,-1 , 0
  4163.6      .1       0  4258.1     .16       0  4664.6      .1       0
  4955.7     .07       0  5049.4      .1       0  5255.2     .16       0
    5404      .1       0  5664.7     .16       0    5949      .1       0
  6089.7     .16       0
#XS Ineff= 1 ,-1
 5086.65 5542.61 1903.82
Permanent Ineff=
       F
Bank Sta=4968.4,5021.7
XS Rating Curve= 0 ,0
Exp/Cntr=0.3,0.1

Type RM Length L Ch R = 1 ,547     ,0,0,0
BEGIN DESCRIPTION:
UNT 1048 IN HEWA 1.0
END DESCRIPTION:
XS GIS Cut Line= 4
      2661510.01     10048931.47      2662301.66     10049431.46
        2662510.     10049639.79      2663037.73     10049695.34
#Sta/Elev= 30
  3880.6 1951.88  4047.1  1942.5  4162.6  1913.8    4193 1908.24  4214.2 1905.91
  4344.8 1901.34  4657.7  1897.3  4801.3 1897.03  4901.1 1887.42  4929.4 1885.26
  4971.8 1882.76  4999.9 1877.64  5014.3 1880.31  5021.3 1884.02  5035.5 1891.69
  5042.5 1895.03  5049.6 1896.09  5170.3 1894.82  5245.9 1897.36  5294.3 1904.39
  5321.2 1910.77  5341.3 1917.28  5381.5 1934.64  5387.3 1939.43  5392.3 1940.47
  5431.8 1958.06  5441.8 1961.08  5492.1 1973.05  5542.2 1975.91  5642.2 1979.75
#Mann= 6 ,-1 , 0
  3880.6     .16       0  4657.7      .1       0  4901.1     .07       0
  5035.5      .1       0  5245.9     .16       0  5542.2      .1       0
Bank Sta=4929.4,5021.3
XS Rating Curve= 0 ,0
Exp/Cntr=0.3,0.1

Chan Stop Cuts=-1
Use User Specified Reach Order=0
Composite Channel Slope=5