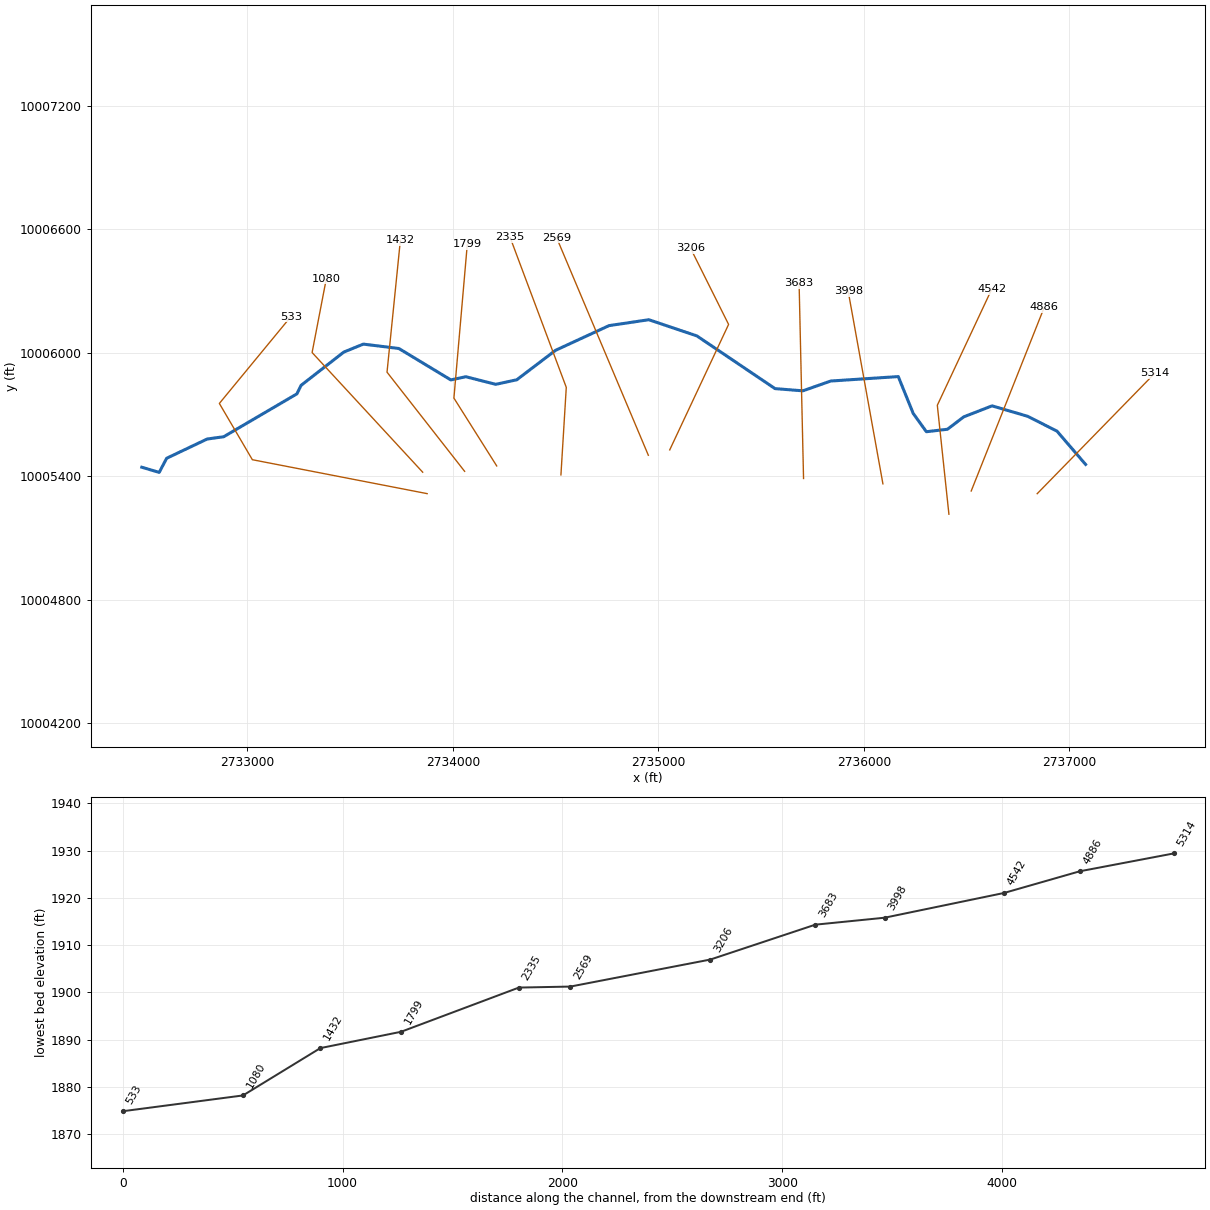
--- UNT 1050 IN HEWA.prj (project) ---

Proj Title=UNT 1050 IN HEWA Base Level Engineering
Current Plan=p01
Default Exp/Contr=0.3,0.1
English Units
Geom File=g01
Flow File=f01
Plan File=p01
Y Axis Title=Elevation
X Axis Title(PF)=Main Channel Distance
X Axis Title(XS)=Station
BEGIN DESCRIPTION:
UNT 1050 IN HEWA
END DESCRIPTION:
DSS Export Rating Curves= 0
DSS Export Rating Curve Sorted= 0
DSS Export Volume Flow Curves= 0
DXF OffsetX= 0
DXF OffsetY= 0
DXF ScaleX= 1
DXF ScaleY= 10

--- UNT 1050 IN HEWA.p01 (plan) ---

Plan Title=Multiple Run
Short Identifier=Multiple
Geom File=g01
Flow File=f01
Subcritical Flow
K Sum by GR= 0
Std Step Tol= 0.01
Critical Tol= 0.01
Num of Std Step Trials= 20
Max Error Tol= 0.3
Flow Tol Ratio= 0.001
Split Flow NTrial= 30
Split Flow Tol= 0.02
Split Flow Ratio= 0.02
Log Output Level= 0
Friction Slope Method= 1
Unsteady Friction Slope Method= 2
Unsteady Bridges Friction Slope Method= 1
Parabolic Critical Depth
Global Vel Dist=  1 , 1 , 1
Global Log Level= 0
CheckData=True
Encroach Param= -1, 0, 0, 0
BEGIN DESCRIPTION:
Multiple Run
END DESCRIPTION:

--- UNT 1050 IN HEWA.f01 (steady flow) ---

Flow Title=Multiple
Program Version=4.10
Number of Profiles= 7
Profile Names=10-year,25-year,50-year,1pct_min,100-year,1pct_plu,500-year
River Rch & RM=UNT 1050 IN HEWA,Reach-1         ,5314
     984    1423    1803    1671    2259    3055    3562
Boundary for River Rch & Prof#=UNT 1050 IN HEWA,Reach-1         , 1
Up Type= 0
Dn Type= 3
Dn Slope=0.013
Boundary for River Rch & Prof#=UNT 1050 IN HEWA,Reach-1         , 2
Up Type= 0
Dn Type= 3
Dn Slope=0.013
Boundary for River Rch & Prof#=UNT 1050 IN HEWA,Reach-1         , 3
Up Type= 0
Dn Type= 3
Dn Slope=0.013
Boundary for River Rch & Prof#=UNT 1050 IN HEWA,Reach-1         , 4
Up Type= 0
Dn Type= 3
Dn Slope=0.013
Boundary for River Rch & Prof#=UNT 1050 IN HEWA,Reach-1         , 5
Up Type= 0
Dn Type= 3
Dn Slope=0.013
Boundary for River Rch & Prof#=UNT 1050 IN HEWA,Reach-1         , 6
Up Type= 0
Dn Type= 3
Dn Slope=0.013
Boundary for River Rch & Prof#=UNT 1050 IN HEWA,Reach-1         , 7
Up Type= 0
Dn Type= 3
Dn Slope=0.013
DSS Import GetInterval= 0
DSS Import GetPeak= 0
DSS Import FillOption= 0

--- UNT 1050 IN HEWA.g01 (geometry) ---

Geom Title=Existing Conditions
Program Version=4.10

River Reach=UNT 1050 IN HEWA,Reach-1
Reach XY= 30
      2737079.18     10005456.57      2736940.02     10005618.36
      2736797.14     10005690.52      2736624.02     10005741.25
      2736486.18     10005687.79      2736406.92     10005627.53
      2736304.27     10005615.56      2736240.25     10005704.43
      2736167.55     10005883.55      2735838.96     10005861.92
       2735703.2     10005814.27      2735567.89       10005825.
       2735187.4     10006081.24      2734953.54     10006159.87
      2734759.64     10006131.12      2734499.59     10006011.19
      2734311.03     10005868.07      2734208.57     10005845.83
      2734063.18     10005882.79      2733990.02     10005867.33
      2733736.96      10006020.1      2733564.19     10006041.34
      2733468.86     10006002.51       2733261.4     10005841.07
      2733240.67     10005799.42      2732884.78     10005591.25
      2732803.95     10005579.95      2732606.96     10005486.48
      2732570.81     10005417.87      2732486.12      10005442.9

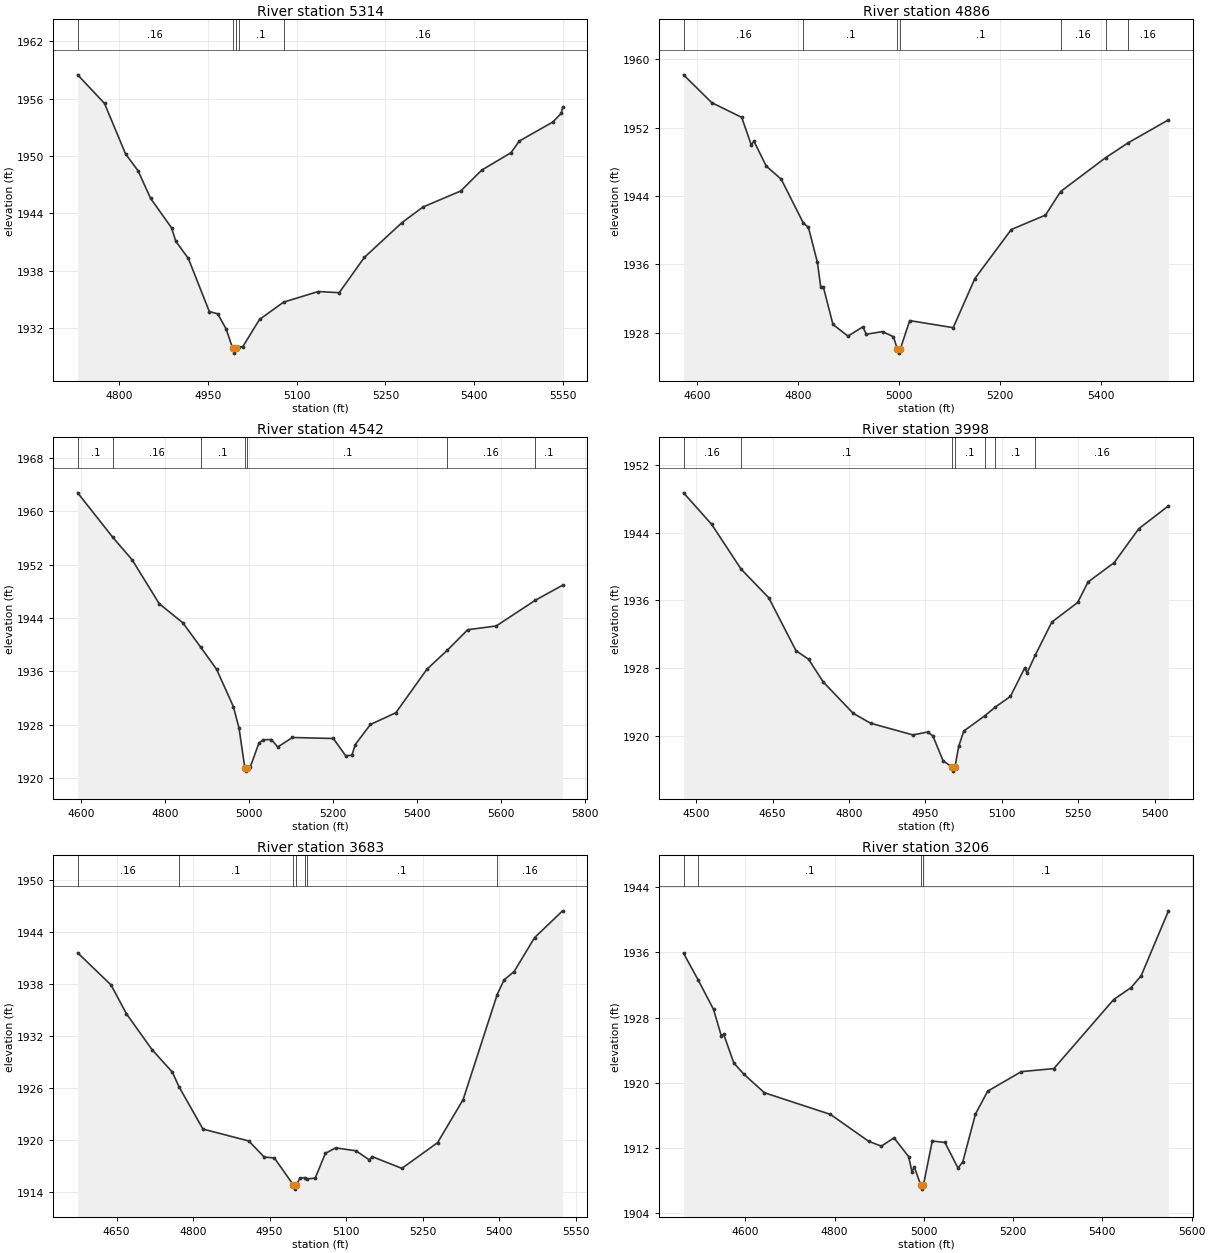
Type RM Length L Ch R = 1 ,5314    ,428,428,428
BEGIN DESCRIPTION:
UNT 1050 IN HEWA 12.0
END DESCRIPTION:
XS GIS Cut Line= 2
      2736843.67      10005314.4      2737415.83     10005899.56
#Sta/Elev= 30
  4730.6  1958.5  4775.9 1955.51  4811.4 1950.24  4832.5 1948.47  4853.8 1945.57
  4889.1  1942.5  4896.2  1941.1  4917.4  1939.3  4952.8 1933.75    4967 1933.51
  4981.1 1931.93  4992.2  1929.9    4995  1929.4  4998.2  1929.9  5002.2 1930.04
  5009.4 1930.09  5037.5 1932.92  5078.1 1934.73  5136.5 1935.84    5172 1935.72
  5214.4 1939.41    5278 1943.05  5313.4 1944.68    5377 1946.35  5412.4 1948.53
  5461.9 1950.36    5476 1951.58  5532.6 1953.57  5546.7 1954.48    5549  1955.1
#Mann= 5 ,-1 , 0
  4730.6     .16       0  4992.2     .07       0  4998.2     .16       0
  5002.2      .1       0  5078.1     .16       0
Bank Sta=4992.2,4998.2
XS Rating Curve= 0 ,0
Exp/Cntr=0.3,0.1

Type RM Length L Ch R = 1 ,4886    ,344,344,344
BEGIN DESCRIPTION:
UNT 1050 IN HEWA 11.0
END DESCRIPTION:
XS GIS Cut Line= 2
      2736522.52     10005327.44      2736877.86     10006220.12
#Sta/Elev= 30
    4573  1958.2  4628.9 1954.94  4688.2 1953.22  4707.1 1950.01  4712.5 1950.43
  4736.8 1947.52  4766.5 1945.98  4810.1 1940.87  4820.4 1940.34  4838.1 1936.27
  4844.7  1933.4  4850.1 1933.33    4869 1928.98  4898.7 1927.61  4928.3  1928.7
    4935 1927.83  4967.2 1928.14  4988.8 1927.54  4996.5 1926.12  4999.3 1925.62
  5002.5 1926.12  5021.1 1929.43  5107.2  1928.6  5150.2 1934.35  5222.3 1940.09
  5290.1 1941.78  5320.1 1944.54    5409 1948.49  5453.8 1950.24  5533.8 1952.93
#Mann= 7 ,-1 , 0
    4573     .16       0  4810.1      .1       0  4996.5     .07       0
  5002.5      .1       0  5320.1     .16       0    5409      .1       0
  5453.8     .16       0
Bank Sta=4996.5,5002.5
XS Rating Curve= 0 ,0
Exp/Cntr=0.3,0.1

Type RM Length L Ch R = 1 ,4542    ,544,544,544
BEGIN DESCRIPTION:
UNT 1050 IN HEWA 10.0
END DESCRIPTION:
XS GIS Cut Line= 3
      2736414.02     10005214.61       2736357.6     10005744.12
      2736622.37     10006308.38
#Sta/Elev= 30
  4591.7 1962.74  4675.6 1956.06  4721.6  1952.7  4786.3 1946.11  4842.2 1943.28
  4884.9 1939.62  4922.7 1936.31  4962.9  1930.7  4976.2 1927.53  4990.1 1921.54
  4992.8 1921.04  4996.1 1921.54  5003.1 1921.65  5023.3 1925.19  5033.3 1925.74
  5053.4 1925.77  5068.6 1924.66  5103.7 1926.08  5201.1 1925.93  5230.5 1923.34
  5245.3 1923.42  5253.3 1925.02  5289.5 1928.03  5350.1 1929.79    5424  1936.3
    5473 1939.17  5521.4 1942.23  5589.3 1942.79  5682.4 1946.64  5747.5  1948.9
#Mann= 7 ,-1 , 0
  4591.7      .1       0  4675.6     .16       0  4884.9      .1       0
  4990.1     .07       0  4996.1      .1       0    5473     .16       0
  5682.4      .1       0
Bank Sta=4990.1,4996.1
XS Rating Curve= 0 ,0
Exp/Cntr=0.3,0.1

Type RM Length L Ch R = 1 ,3998    ,315,315,315
BEGIN DESCRIPTION:
UNT 1050 IN HEWA 9.0
END DESCRIPTION:
XS GIS Cut Line= 2
      2736092.84     10005362.16      2735923.65     10006299.21
#Sta/Elev= 30
  4475.1  1948.7  4530.2 1944.98  4588.1 1939.68  4642.4 1936.29  4695.9 1930.04
  4720.6 1929.02  4749.5 1926.33  4808.1 1922.64  4842.5 1921.46  4925.4 1920.08
  4954.3 1920.42  4964.5 1919.98  4984.8 1917.02  5002.1  1916.3  5004.9  1915.8
  5008.1  1916.3  5015.3 1918.73  5025.4 1920.54  5066.3 1922.33  5087.6 1923.39
  5116.9 1924.63  5144.6 1927.95  5149.7 1927.42  5165.5 1929.49  5198.2 1933.42
    5249 1935.74  5269.3 1938.16  5320.5 1940.44    5369 1944.46  5427.3 1947.16
#Mann= 7 ,-1 , 0
  4475.1     .16       0  4588.1      .1       0  5002.1     .07       0
  5008.1      .1       0  5066.3     .16       0  5087.6      .1       0
  5165.5     .16       0
Bank Sta=5002.1,5008.1
XS Rating Curve= 0 ,0
Exp/Cntr=0.3,0.1

Type RM Length L Ch R = 1 ,3683    ,477,477,477
BEGIN DESCRIPTION:
UNT 1050 IN HEWA 8.0
END DESCRIPTION:
XS GIS Cut Line= 2
      2735706.55     10005388.17      2735684.85     10006338.72
#Sta/Elev= 30
  4573.8 1941.63  4639.4 1937.91  4669.4 1934.59  4719.4 1930.46  4759.4 1927.85
  4772.3 1926.18  4819.4 1921.27  4909.4 1919.89  4939.5 1918.04  4959.5 1917.93
  4996.5 1914.83  4999.2 1914.33  5002.5 1914.83  5009.5 1915.58  5018.7 1915.66
    5024 1915.51  5039.5  1915.6  5059.5 1918.46  5079.5  1919.1  5119.5 1918.76
  5145.9  1917.7  5150.9 1918.09  5209.5 1916.73  5279.5  1919.7  5329.6 1924.68
  5396.3  1936.8  5409.6 1938.48  5429.6 1939.47  5469.6 1943.38  5524.6 1946.48
#Mann= 7 ,-1 , 0
  4573.8     .16       0  4772.3      .1       0  4996.5     .07       0
  5002.5      .1       0  5018.7     .16       0    5024      .1       0
  5396.3     .16       0
Bank Sta=4996.5,5002.5
XS Rating Curve= 0 ,0
Exp/Cntr=0.3,0.1

Type RM Length L Ch R = 1 ,3206    ,637,637,637
BEGIN DESCRIPTION:
UNT 1050 IN HEWA 7.0
END DESCRIPTION:
XS GIS Cut Line= 3
      2735055.31     10005527.24      2735341.79     10006137.09
      2735157.31     10006506.06
#Sta/Elev= 30
  4461.8  1935.9    4495 1932.58  4528.9 1929.02  4546.2  1925.8  4551.7 1925.96
  4574.5 1922.43  4597.3 1921.04  4642.9 1918.79  4790.8 1916.13  4876.5 1912.83
  4904.9 1912.23  4933.2 1913.26  4966.1 1910.94  4973.3 1909.11  4978.8 1909.67
  4993.1 1907.46  4995.8 1906.96  4999.1 1907.46  5018.9 1912.86  5047.2 1912.69
  5076.6 1909.55  5087.3 1910.31  5115.7 1916.18    5143 1918.98  5218.5 1921.38
  5291.2 1921.75  5425.3 1930.22  5464.4  1931.7  5486.8 1933.14  5548.1 1941.11
#Mann= 4 ,-1 , 0
  4461.8     .16       0    4495      .1       0  4993.1     .07       0
  4999.1      .1       0
Bank Sta=4993.1,4999.1
XS Rating Curve= 0 ,0
Exp/Cntr=0.3,0.1

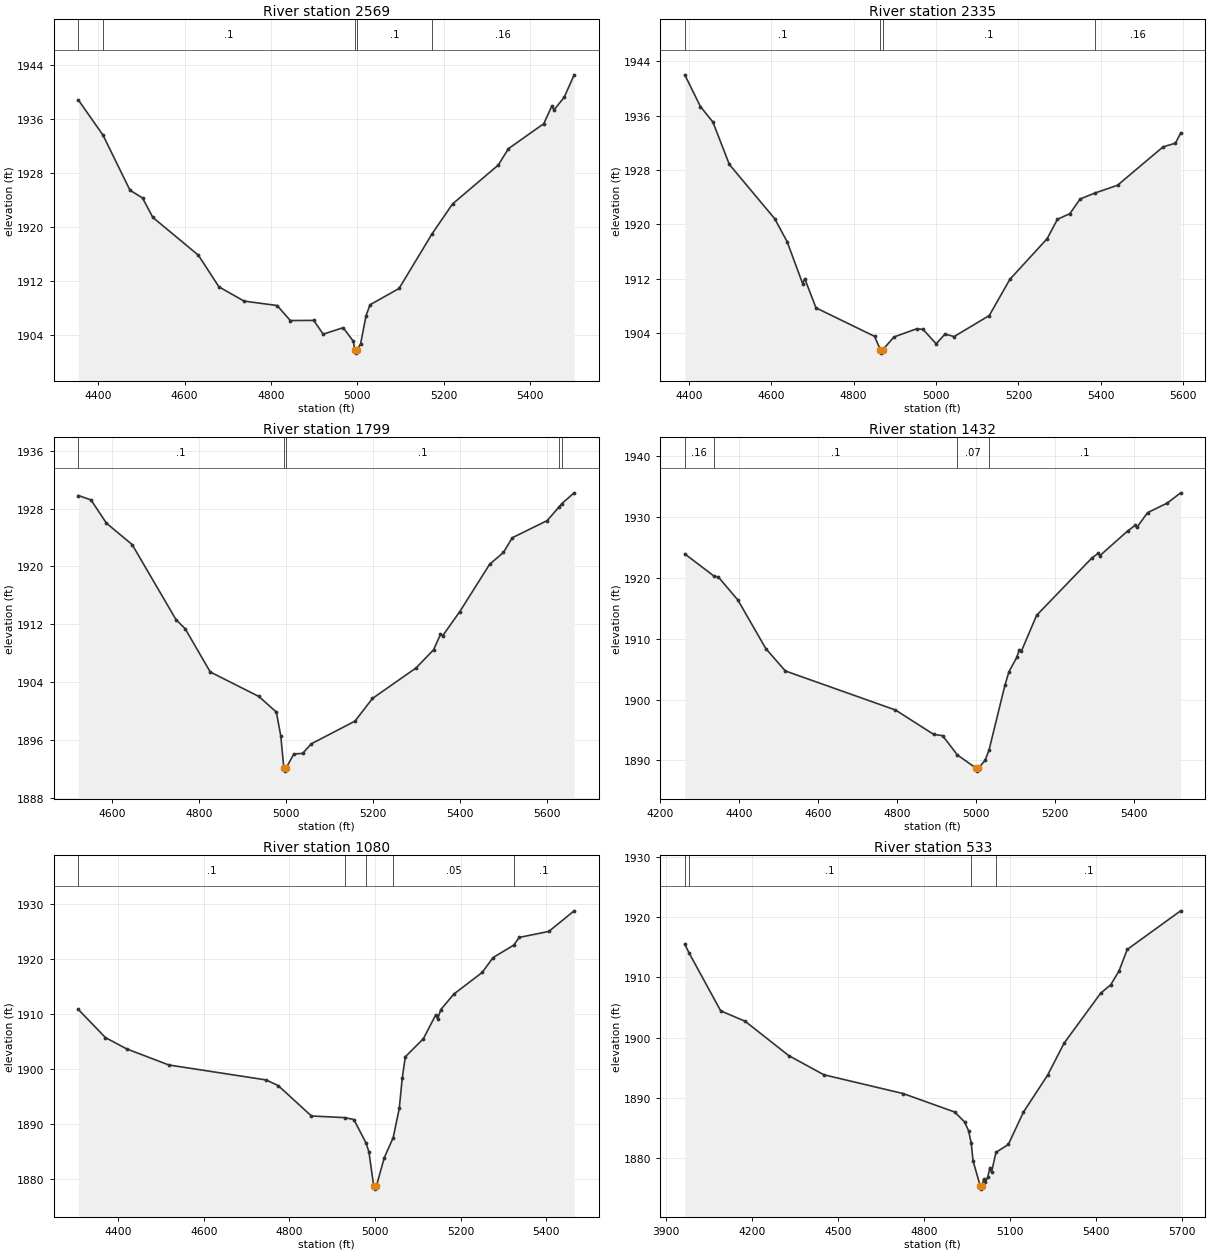
Type RM Length L Ch R = 1 ,2569    ,234,234,234
BEGIN DESCRIPTION:
UNT 1050 IN HEWA 6.0
END DESCRIPTION:
XS GIS Cut Line= 2
      2734951.18     10005501.21      2734504.45     10006559.49
#Sta/Elev= 30
  4353.9 1938.84    4411 1933.62  4473.6 1925.43  4502.7 1924.28  4526.4  1921.4
  4632.1 1915.78  4679.6 1911.09  4737.8 1908.97  4814.4 1908.31  4845.1 1906.08
  4899.4  1906.1  4921.1 1904.06  4967.5 1905.02  4991.2 1902.99    4994 1901.74
  4996.8 1901.24    5000 1901.74  5007.9 1902.64  5020.4 1906.78  5029.6 1908.42
  5096.9 1910.84  5173.7 1918.99  5220.9  1923.4  5326.6 1929.16  5350.3  1931.6
  5432.3 1935.32  5450.6  1937.9    5456 1937.36  5479.7 1939.26  5502.6 1942.57
#Mann= 5 ,-1 , 0
  4353.9     .16       0    4411      .1       0    4994     .07       0
    5000      .1       0  5173.7     .16       0
Bank Sta=4994,5000
XS Rating Curve= 0 ,0
Exp/Cntr=0.3,0.1

Type RM Length L Ch R = 1 ,2335    ,536,536,536
BEGIN DESCRIPTION:
UNT 1050 IN HEWA 5.0
END DESCRIPTION:
XS GIS Cut Line= 3
      2734525.82     10005405.75      2734551.86      10005831.1
       2734278.7     10006559.53
#Sta/Elev= 30
  4389.9 1942.03  4427.9 1937.35    4458 1935.09  4498.1 1928.83  4608.3 1920.83
  4638.3 1917.46  4676.1 1911.27  4681.1 1912.01  4708.5  1907.7  4850.9  1903.5
  4864.7 1901.53  4867.4 1901.03  4870.7 1901.53  4897.9 1903.41  4953.1 1904.62
  4968.4 1904.53  5000.4  1902.4  5021.8 1903.84  5043.9 1903.47  5129.3 1906.57
  5179.2 1911.89  5269.9  1917.9  5294.9 1920.75  5325.1 1921.58    5350 1923.74
  5386.1 1924.62  5440.8 1925.76  5551.2 1931.41  5581.4 1931.96    5594 1933.45
#Mann= 4 ,-1 , 0
  4389.9      .1       0  4864.7     .07       0  4870.7      .1       0
  5386.1     .16       0
Bank Sta=4864.7,4870.7
XS Rating Curve= 0 ,0
Exp/Cntr=0.3,0.1

Type RM Length L Ch R = 1 ,1799    ,367,367,367
BEGIN DESCRIPTION:
UNT 1050 IN HEWA 4.0
END DESCRIPTION:
XS GIS Cut Line= 3
      2734213.34     10005449.13      2734004.98     10005779.02
      2734070.08     10006525.51
#Sta/Elev= 30
  4522.1 1929.82  4551.2 1929.21  4586.7 1925.99  4645.8 1923.03  4746.5 1912.65
  4767.7 1911.38  4825.3  1905.4  4937.1 1902.01  4977.2 1899.85  4987.3 1896.58
  4994.3 1892.18  4997.1 1891.68  5000.3 1892.18  5017.4 1894.06  5037.5 1894.13
  5057.5 1895.46  5157.9  1898.6  5198.1 1901.74  5298.5 1905.97  5338.6 1908.48
  5354.4 1910.61  5359.5 1910.42  5398.8 1913.76  5467.2 1920.29  5499.2 1921.95
  5519.3 1923.97  5599.6 1926.35  5626.4  1928.2  5632.9 1928.68  5661.6 1930.19
#Mann= 5 ,-1 , 0
  4522.1      .1       0  4994.3     .07       0  5000.3      .1       0
  5626.4     .16       0  5632.9      .1       0
Bank Sta=4994.3,5000.3
XS Rating Curve= 0 ,0
Exp/Cntr=0.3,0.1

Type RM Length L Ch R = 1 ,1432    ,352,352,352
BEGIN DESCRIPTION:
UNT 1050 IN HEWA 3.0
END DESCRIPTION:
XS GIS Cut Line= 3
      2734057.04     10005423.15      2733679.46     10005904.89
      2733744.56     10006547.22
#Sta/Elev= 30
  4261.8 1923.95  4335.7 1920.31  4346.9 1920.15  4396.6 1916.35  4467.2 1908.39
  4516.9  1904.7  4796.2 1898.28  4892.8 1894.28  4915.8 1894.06  4953.1  1890.9
  5000.4 1888.73  5003.1 1888.23  5006.4 1888.73  5023.5 1889.99  5033.5 1891.69
  5073.7 1902.32  5083.8 1904.54  5103.9 1906.95  5110.4 1908.22  5115.4 1907.93
  5154.2 1913.85  5294.9 1923.31  5310.1 1924.02  5315.1 1923.68  5385.3 1927.73
  5404.9 1928.68  5409.9 1928.43  5435.6 1930.73  5485.8 1932.31  5519.5 1933.99
#Mann= 4 ,-1 , 0
  4261.8     .16       0  4335.7      .1       0  4953.1     .07       0
  5033.5      .1       0
Bank Sta=5000.4,5006.4
XS Rating Curve= 0 ,0
Exp/Cntr=0.3,0.1

Type RM Length L Ch R = 1 ,1080    ,547,547,547
BEGIN DESCRIPTION:
UNT 1050 IN HEWA 2.0
END DESCRIPTION:
XS GIS Cut Line= 3
      2733853.05      10005418.8      2733314.88     10006000.37
      2733384.14     10006359.69
#Sta/Elev= 30
  4306.8 1910.86    4370 1905.76  4419.8 1903.69  4518.5 1900.77  4745.3 1898.06
  4773.6 1897.04  4851.3 1891.51  4929.5 1891.21  4950.5 1890.86  4978.9  1886.6
  4985.7 1884.97  4996.9 1878.72  4999.6 1878.22  5002.9 1878.72  5021.4 1883.91
  5042.4 1887.59  5056.6 1892.92  5063.4 1898.35  5070.7 1902.27  5112.8 1905.54
  5141.4 1909.83  5146.5 1909.16  5153.5 1910.84  5184.1 1913.66  5250.2 1917.58
  5275.7 1920.29  5323.9 1922.54  5336.8 1923.95  5405.9 1925.04  5465.1 1928.78
#Mann= 5 ,-1 , 0
  4306.8      .1       0  4929.5     .05       0  4978.9    .035       0
  5042.4     .05       0  5323.9      .1       0
Bank Sta=4996.9,5002.9
XS Rating Curve= 0 ,0
Exp/Cntr=0.3,0.1

Type RM Length L Ch R = 1 ,533     ,0,0,0
BEGIN DESCRIPTION:
UNT 1050 IN HEWA 1.0
END DESCRIPTION:
XS GIS Cut Line= 4
      2733874.77     10005314.61      2733024.08     10005479.54
      2732863.49     10005752.98      2733210.74     10006174.02
#Sta/Elev= 30
  3965.4  1915.5  3980.7 1914.03  4090.5 1904.46  4175.5 1902.74  4328.3 1897.02
  4450.6 1893.85  4726.6 1890.74  4906.4 1887.68  4941.2 1886.04  4955.1 1884.57
  4964.4 1882.54  4970.8 1879.56  4996.1 1875.38  4998.9 1874.88  5002.1 1875.38
  5007.9 1876.55  5013.7    1876  5022.3 1876.89  5029.4 1878.45  5035.2 1877.68
  5050.8 1880.98  5093.8 1882.29  5146.6 1887.66  5230.9 1893.79  5288.3 1899.09
    5416 1907.39  5451.1 1908.79  5479.8 1911.06  5508.5 1914.64  5694.8 1921.05
#Mann= 4 ,-1 , 0
  3965.4     .16       0  3980.7      .1       0  4964.4     .05       0
  5050.8      .1       0
Bank Sta=4996.1,5002.1
XS Rating Curve= 0 ,0
Exp/Cntr=0.3,0.1

Chan Stop Cuts=-1
Use User Specified Reach Order=0
Composite Channel Slope=5