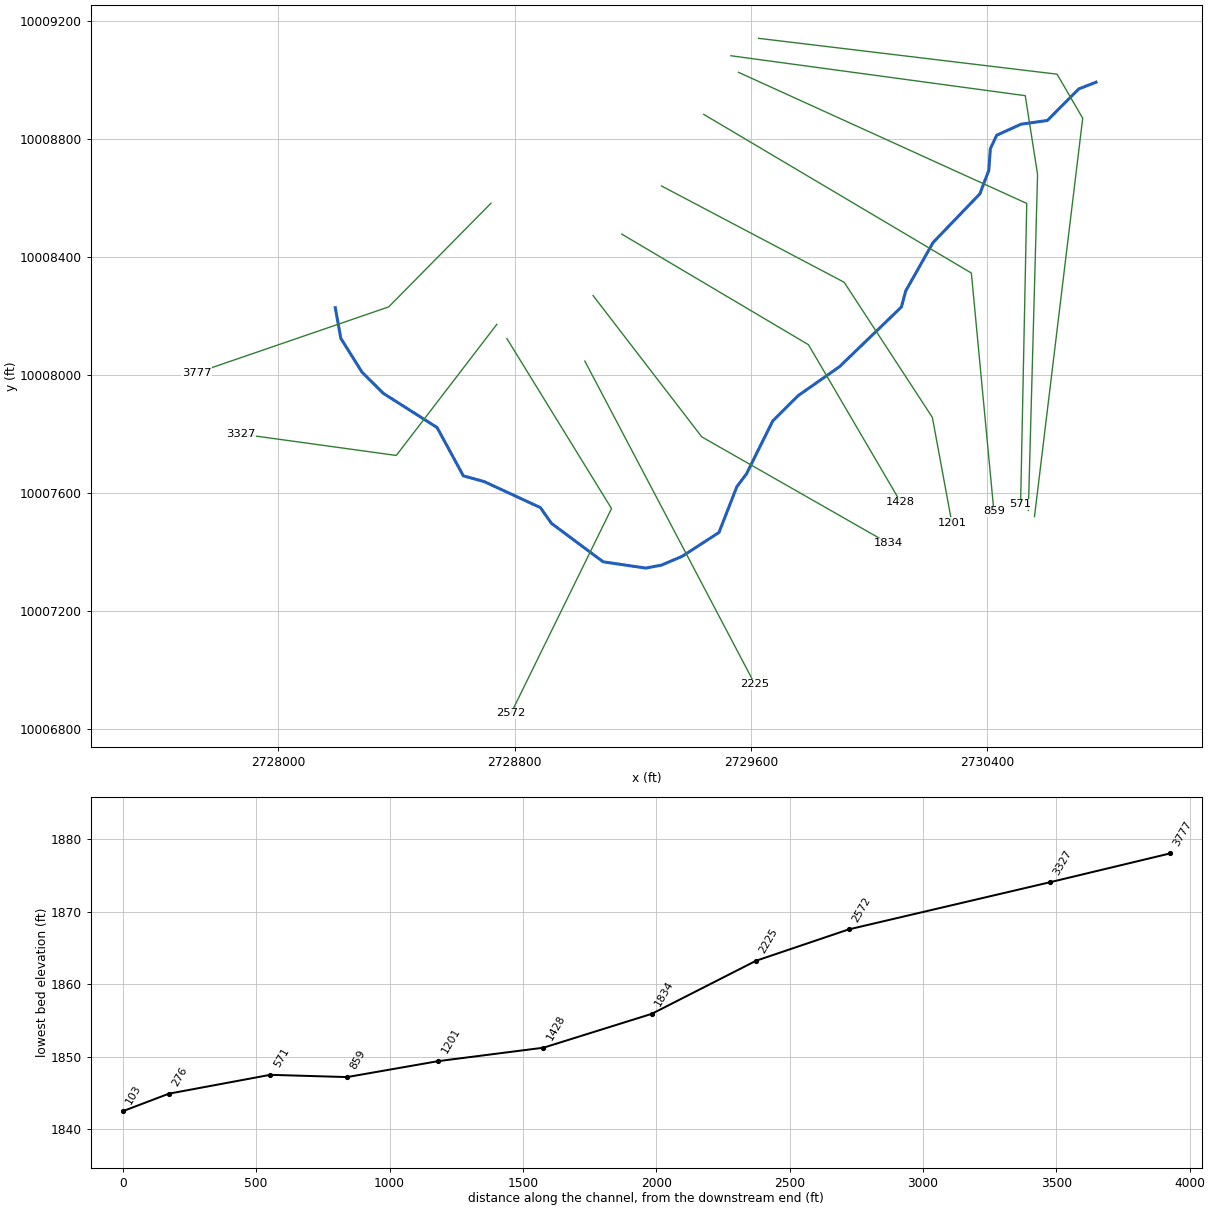
--- UNT 1051 IN HEWA.prj (project) ---

Proj Title=UNT 1051 IN HEWA Base Level Engineering
Current Plan=p01
Default Exp/Contr=0.3,0.1
English Units
Geom File=g01
Flow File=f01
Plan File=p01
Y Axis Title=Elevation
X Axis Title(PF)=Main Channel Distance
X Axis Title(XS)=Station
BEGIN DESCRIPTION:
UNT 1051 IN HEWA
END DESCRIPTION:
DSS Export Rating Curves= 0
DSS Export Rating Curve Sorted= 0
DSS Export Volume Flow Curves= 0
DXF OffsetX= 0
DXF OffsetY= 0
DXF ScaleX= 1
DXF ScaleY= 10

--- UNT 1051 IN HEWA.p01 (plan) ---

Plan Title=Multiple Run
Short Identifier=Multiple
Geom File=g01
Flow File=f01
Subcritical Flow
K Sum by GR= 0
Std Step Tol= 0.01
Critical Tol= 0.01
Num of Std Step Trials= 20
Max Error Tol= 0.3
Flow Tol Ratio= 0.001
Split Flow NTrial= 30
Split Flow Tol= 0.02
Split Flow Ratio= 0.02
Log Output Level= 0
Friction Slope Method= 1
Unsteady Friction Slope Method= 2
Unsteady Bridges Friction Slope Method= 1
Parabolic Critical Depth
Global Vel Dist=  1 , 1 , 1
Global Log Level= 0
CheckData=True
Encroach Param= -1, 0, 0, 0
BEGIN DESCRIPTION:
Multiple Run
END DESCRIPTION:

--- UNT 1051 IN HEWA.f01 (steady flow) ---

Flow Title=Multiple
Program Version=4.10
Number of Profiles= 7
Profile Names=10-year,25-year,50-year,1pct_min,100-year,1pct_plu,500-year
River Rch & RM=UNT 1051 IN HEWA,Reach-1         ,3777
     644     915    1146    1051    1421    1922    2193
River Rch & RM=UNT 1051 IN HEWA,Reach-1         ,2572
    1013    1475    1877    1746    2361    3193    3754
Boundary for River Rch & Prof#=UNT 1051 IN HEWA,Reach-1         , 1
Up Type= 0
Dn Type= 3
Dn Slope=0.005
Boundary for River Rch & Prof#=UNT 1051 IN HEWA,Reach-1         , 2
Up Type= 0
Dn Type= 3
Dn Slope=0.005
Boundary for River Rch & Prof#=UNT 1051 IN HEWA,Reach-1         , 3
Up Type= 0
Dn Type= 3
Dn Slope=0.005
Boundary for River Rch & Prof#=UNT 1051 IN HEWA,Reach-1         , 4
Up Type= 0
Dn Type= 3
Dn Slope=0.005
Boundary for River Rch & Prof#=UNT 1051 IN HEWA,Reach-1         , 5
Up Type= 0
Dn Type= 3
Dn Slope=0.005
Boundary for River Rch & Prof#=UNT 1051 IN HEWA,Reach-1         , 6
Up Type= 0
Dn Type= 3
Dn Slope=0.005
Boundary for River Rch & Prof#=UNT 1051 IN HEWA,Reach-1         , 7
Up Type= 0
Dn Type= 3
Dn Slope=0.005
DSS Import GetInterval= 0
DSS Import GetPeak= 0
DSS Import FillOption= 0

--- UNT 1051 IN HEWA.g01 (geometry) ---

Geom Title=Existing Conditions
Program Version=4.10

River Reach=UNT 1051 IN HEWA,Reach-1
Reach XY= 30
      2728193.06     10008229.14      2728211.99     10008125.19
      2728283.48     10008010.86      2728355.63     10007938.82
      2728537.73     10007822.91       2728626.7     10007658.92
      2728696.77     10007639.78      2728887.47     10007551.35
      2728924.88     10007497.95      2729100.03     10007367.49
      2729244.03     10007346.28      2729297.29     10007356.32
      2729367.45     10007386.18      2729491.93     10007466.92
      2729552.48     10007622.07      2729584.86     10007665.23
      2729673.98     10007845.22      2729760.18     10007931.05
      2729899.99     10008029.13      2730109.63     10008231.58
      2730124.21     10008286.07      2730216.72     10008450.12
      2730375.17     10008615.18      2730405.43     10008694.99
      2730410.59     10008767.94      2730432.02     10008813.78
      2730514.46     10008851.33      2730603.48     10008863.88
      2730710.16       10008971.      2730768.47     10008993.73

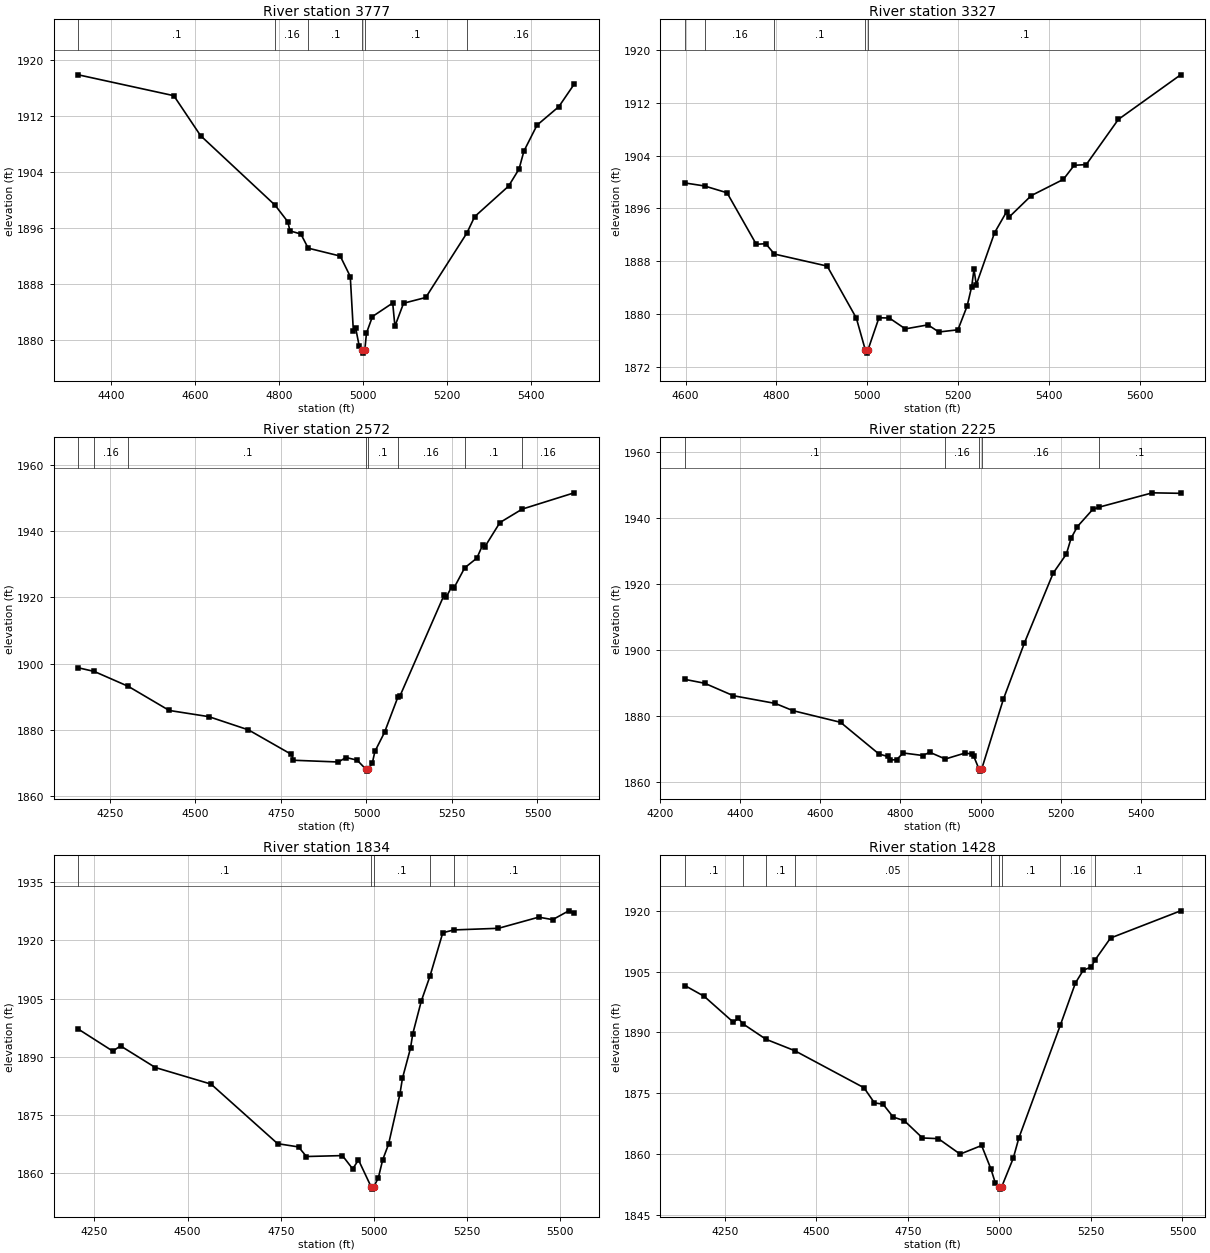
Type RM Length L Ch R = 1 ,3777    ,450,450,450
BEGIN DESCRIPTION:
UNT 1051 IN HEWA 7.0
END DESCRIPTION:
XS GIS Cut Line= 3
      2728720.31     10008583.41      2728373.96     10008231.86
      2727724.42     10008008.41
#Sta/Elev= 30
  4322.9 1917.83  4550.2 1914.85  4613.9 1909.14  4791.3  1899.2  4821.5 1896.84
  4826.8 1895.53  4852.7 1895.08  4870.1 1893.06  4946.4 1891.93  4970.3 1889.01
  4977.6 1881.28  4982.9 1881.72  4991.4 1879.12    4999 1878.56  5001.7 1878.06
    5005 1878.56  5008.9 1880.93  5023.1 1883.29  5071.3 1885.22  5076.6 1881.91
  5097.2 1885.19    5150 1886.01  5247.9 1895.22  5266.4 1897.56  5347.1 1901.92
  5372.1 1904.37  5383.7 1906.93  5414.9 1910.64  5466.8 1913.28  5503.3 1916.49
#Mann= 6 ,-1 , 0
  4322.9      .1       0  4791.3     .16       0  4870.1      .1       0
    4999     .07       0    5005      .1       0  5247.9     .16       0
Bank Sta=4999,5005
XS Rating Curve= 0 ,0
Exp/Cntr=0.3,0.1

Type RM Length L Ch R = 1 ,3327    ,755,755,755
BEGIN DESCRIPTION:
UNT 1051 IN HEWA 6.0
END DESCRIPTION:
XS GIS Cut Line= 3
      2728739.96     10008172.66      2728399.66     10007728.19
      2727872.65       10007801.
#Sta/Elev= 30
  4598.2 1899.86  4641.7  1899.4  4691.2 1898.37  4755.6 1890.57  4776.4 1890.66
  4795.5 1889.09  4911.7 1887.27  4975.9  1879.4  4995.6 1874.59  4998.4 1874.09
  5001.6 1874.59  5025.7 1879.44  5048.5 1879.41  5083.8 1877.76  5133.7 1878.37
  5157.6 1877.29  5199.6 1877.62  5219.8  1881.2  5229.9 1884.16    5235 1886.79
    5240 1884.45  5280.3 1892.32  5306.8  1895.5  5311.9 1894.66  5361.1 1897.94
  5431.8  1900.4  5455.6 1902.53  5482.2 1902.64  5552.9 1909.48    5690 1916.23
#Mann= 5 ,-1 , 0
  4598.2      .1       0  4641.7     .16       0  4795.5      .1       0
  4995.6     .07       0  5001.6      .1       0
Bank Sta=4995.6,5001.6
XS Rating Curve= 0 ,0
Exp/Cntr=0.3,0.1

Type RM Length L Ch R = 1 ,2572    ,347,347,347
BEGIN DESCRIPTION:
UNT 1051 IN HEWA 5.0
END DESCRIPTION:
XS GIS Cut Line= 3
      2728774.06     10008124.54      2729128.25     10007548.12
      2728787.96     10006853.65
#Sta/Elev= 30
  4157.4 1898.73  4203.8 1897.63  4303.6 1893.13  4423.1 1885.87    4539    1884
    4655 1880.01  4780.4 1872.63  4786.4 1870.86  4917.7 1870.33  4940.2 1871.68
  4972.5  1870.9  4999.1 1868.08  5001.9 1867.58  5005.1 1868.08    5017 1869.98
  5024.6 1873.51  5052.7 1879.25  5091.5 1889.81  5097.7 1890.17  5227.1  1920.7
  5232.7 1919.98  5249.6  1923.2  5255.2 1922.67  5287.2 1928.86  5322.7 1931.78
  5339.6  1935.7  5345.2 1935.05  5390.2 1942.51  5455.3 1946.56  5607.3 1951.47
#Mann= 8 ,-1 , 0
  4157.4      .1       0  4203.8     .16       0  4303.6      .1       0
  4999.1     .07       0  5005.1      .1       0  5091.5     .16       0
  5287.2      .1       0  5455.3     .16       0
Bank Sta=4999.1,5005.1
XS Rating Curve= 0 ,0
Exp/Cntr=0.3,0.1

Type RM Length L Ch R = 1 ,2225    ,391,391,391
BEGIN DESCRIPTION:
UNT 1051 IN HEWA 4.0
END DESCRIPTION:
XS GIS Cut Line= 2
      2729037.99     10008048.07      2729613.91     10006951.74
#Sta/Elev= 30
  4261.4 1891.06    4311 1889.88  4382.8  1886.1  4487.4 1883.77  4531.5 1881.58
  4650.4 1878.05  4746.3 1868.45  4768.4  1867.7  4774.6 1866.62  4790.4 1866.73
  4806.8 1868.76  4856.5 1867.98  4872.9 1868.99  4912.1 1866.93  4961.1 1868.73
  4977.5 1868.47  4983.2 1867.73  4996.6 1863.76  4999.3 1863.26  5002.6 1863.76
    5057 1885.01  5109.8 1902.14  5181.6 1923.27  5214.4 1929.01  5226.4 1933.87
  5242.1 1937.36  5280.5 1942.57  5296.5 1943.24  5429.2 1947.57  5499.8 1947.42
#Mann= 5 ,-1 , 0
  4261.4      .1       0  4912.1     .16       0  4996.6     .07       0
  5002.6     .16       0  5296.5      .1       0
Bank Sta=4996.6,5002.6
XS Rating Curve= 0 ,0
Exp/Cntr=0.3,0.1

Type RM Length L Ch R = 1 ,1834    ,406,406,406
BEGIN DESCRIPTION:
UNT 1051 IN HEWA 3.0
END DESCRIPTION:
XS GIS Cut Line= 3
      2729065.75     10008270.33       2729433.8     10007791.17
      2730064.59     10007430.73
#Sta/Elev= 30
  4206.9 1897.15  4299.4 1891.48  4320.2 1892.83  4413.6 1887.26  4563.1 1882.99
  4741.7 1867.65  4797.8 1866.81  4819.1 1864.34  4915.6 1864.58  4943.2 1861.16
  4958.8 1863.45  4993.2 1856.44    4996 1855.94  4999.2 1856.44    5012 1858.83
  5023.8 1863.51  5039.4 1867.48  5069.9 1880.39  5076.8  1884.5  5098.4 1892.25
  5104.4 1895.93  5127.4  1904.4  5150.6 1910.78    5185 1921.97  5214.6  1922.7
  5334.5 1923.12  5442.5 1925.99  5479.9 1925.35  5523.1 1927.62  5537.6 1926.96
#Mann= 5 ,-1 , 0
  4206.9      .1       0  4993.2     .07       0  4999.2      .1       0
  5150.6     .16       0  5214.6      .1       0
Bank Sta=4993.2,4999.2
XS Rating Curve= 0 ,0
Exp/Cntr=0.3,0.1

Type RM Length L Ch R = 1 ,1428    ,394,394,394
BEGIN DESCRIPTION:
UNT 1051 IN HEWA 2.0
END DESCRIPTION:
XS GIS Cut Line= 3
      2729162.99     10008478.66      2729794.91     10008103.67
      2730107.39     10007568.99
#Sta/Elev= 30
  4140.8 1901.58  4193.7 1898.91  4273.5  1892.5  4286.7 1893.44  4300.7 1892.04
  4362.6 1888.29  4440.9 1885.48  4630.1 1876.32  4658.8 1872.57  4682.1 1872.27
    4710 1869.07  4740.2 1868.18  4789.9 1863.91  4833.2 1863.74  4892.7 1859.92
  4951.4 1862.05  4976.9 1856.23  4988.6 1852.85  4999.9 1851.77  5002.7 1851.27
  5005.9 1851.77  5037.7 1858.87  5053.1  1863.9  5166.8 1891.88  5207.6  1902.2
  5229.1 1905.36  5250.6 1906.13  5260.5  1907.8  5303.5 1913.31  5494.9 1920.03
#Mann= 9 ,-1 , 0
  4140.8      .1       0  4300.7     .05       0  4362.6      .1       0
  4440.9     .05       0  4976.9      .1       0  4999.9     .07       0
  5005.9      .1       0  5166.8     .16       0  5260.5      .1       0
Bank Sta=4999.9,5005.9
XS Rating Curve= 0 ,0
Exp/Cntr=0.3,0.1

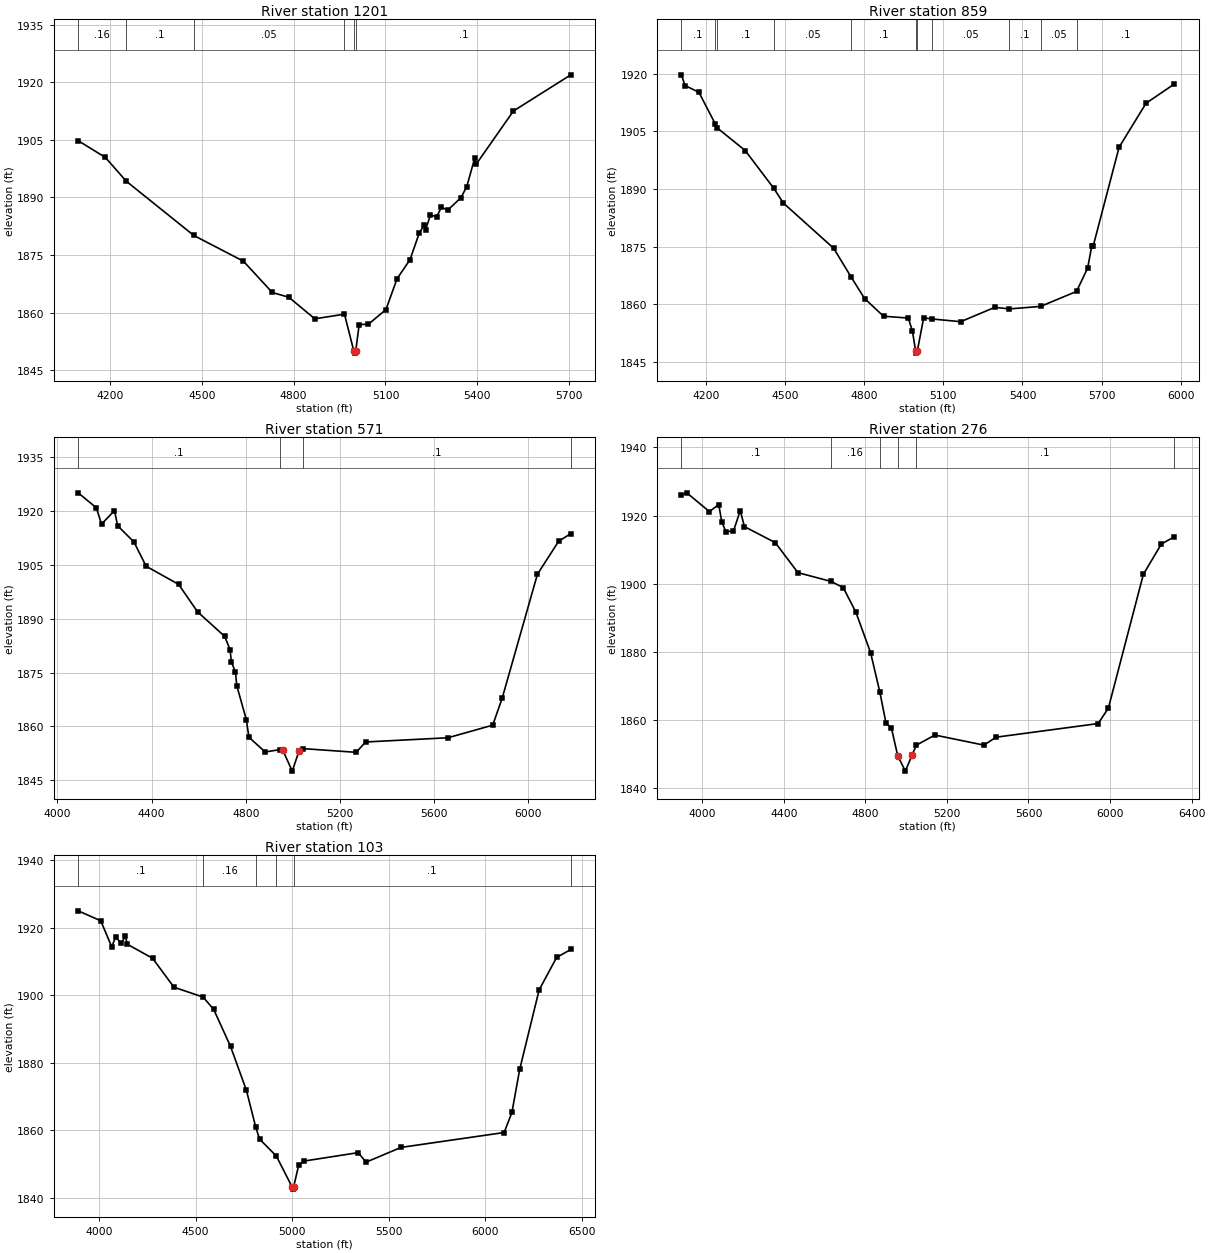
Type RM Length L Ch R = 1 ,1201    ,342,342,342
BEGIN DESCRIPTION:
Mapping XS b6c22ae5
END DESCRIPTION:
XS GIS Cut Line= 4
      2729297.72     10008641.79      2729915.81     10008315.38
      2730214.42     10007857.05       2730280.4     10007499.39
#Sta/Elev= 30
    4096 1904.75  4184.9 1900.38  4253.2 1894.19  4473.9 1880.06    4636 1873.36
  4730.1 1865.22  4784.4 1863.97  4869.2 1858.36  4966.1 1859.57  4996.8 1849.92
  4999.6 1849.42  5002.8 1849.92  5014.1 1856.86  5044.4 1856.95  5101.7 1860.77
  5137.9  1868.8  5180.1 1873.73  5210.4 1880.66  5225.5 1882.68  5231.5 1881.57
  5246.6 1885.33  5267.7    1885  5282.8 1887.37  5303.9  1886.7  5346.2 1889.86
  5365.7 1892.77  5391.5 1900.17  5396.6 1898.64  5518.2 1912.48  5705.7  1921.9
#Mann= 6 ,-1 , 0
    4096     .16       0  4253.2      .1       0  4473.9     .05       0
  4966.1      .1       0  4996.8     .07       0  5002.8      .1       0
Bank Sta=4996.8,5002.8
XS Rating Curve= 0 ,0
Exp/Cntr=0.3,0.1

Type RM Length L Ch R = 1 ,859     ,288,288,288
BEGIN DESCRIPTION:
Mapping XS 6358918b
END DESCRIPTION:
XS GIS Cut Line= 3
       2729440.1     10008884.84      2730346.37     10008346.63
       2730422.7     10007538.16
#Sta/Elev= 30
  4108.1 1919.73  4121.9 1916.94  4174.5 1915.18  4235.8 1907.03    4244 1905.89
  4349.8 1900.01  4458.2 1890.15    4494 1886.35    4685 1874.53  4750.1 1867.16
  4801.9 1861.45  4873.8 1856.83  4967.4 1856.36    4983 1853.06  4995.6 1847.72
  4998.4 1847.22  5001.6 1847.72  5025.9 1856.43  5055.8 1856.13  5166.1 1855.41
  5295.6 1859.16  5350.1 1858.74  5468.5 1859.39  5604.8 1863.29  5647.2 1869.43
  5662.7 1875.24  5667.7 1875.04  5766.1 1900.87  5868.2 1912.33  5974.2 1917.28
#Mann= 11 ,-1 , 0
  4108.1      .1       0  4235.8     .05       0    4244      .1       0
  4458.2     .05       0  4750.1      .1       0  4995.6     .07       0
  5001.6      .1       0  5055.8     .05       0  5350.1      .1       0
  5468.5     .05       0  5604.8      .1       0
Bank Sta=4995.6,5001.6
XS Rating Curve= 0 ,0
Exp/Cntr=0.3,0.1

Type RM Length L Ch R = 1 ,571     ,380,380,380
BEGIN DESCRIPTION:
Mapping XS d50c662b
END DESCRIPTION:
XS GIS Cut Line= 3
      2729558.19     10009027.18      2730533.87     10008582.74
      2730513.03     10007561.88
#Sta/Elev= 30
  4088.1 1925.09  4165.3 1920.92  4187.3 1916.36  4242.2 1920.14    4256  1915.9
  4325.1 1911.39  4376.7 1904.64    4515 1899.57  4595.2 1891.94  4710.4 1885.09
  4733.5 1881.39  4738.9 1878.02  4756.5  1875.1    4762 1871.35  4802.6 1861.85
  4813.6 1856.98  4882.7 1852.87  4945.5 1853.52  4957.4 1853.37  4997.7 1847.53
  5026.5 1853.15  5044.1  1853.8  5269.3 1852.77  5309.3 1855.65  5659.3 1856.83
  5849.4 1860.34  5889.4  1867.8  6039.4  1902.4  6129.4 1911.58  6181.3 1913.72
#Mann= 4 ,-1 , 0
  4088.1      .1       0  4945.5     .07       0  5044.1      .1       0
  6181.3      .1       0
Bank Sta=4957.4,5026.5
XS Rating Curve= 0 ,0
Exp/Cntr=0.3,0.1

Type RM Length L Ch R = 1 ,276     ,173,173,173
BEGIN DESCRIPTION:
Mapping XS 21c8617b
END DESCRIPTION:
XS GIS Cut Line= 4
      2729532.33     10009083.42      2730528.83     10008948.01
       2730570.5     10008680.65      2730539.25     10007541.72
#Sta/Elev= 30
  3898.1 1926.01  3924.5 1926.67  4035.5 1921.16  4081.2 1923.22    4096 1918.17
  4116.2 1915.28  4153.6 1915.46  4186.9 1921.47    4207 1916.75  4358.4 1912.05
  4469.4 1903.23  4630.9 1900.66  4691.5 1898.85  4753.5 1891.64  4825.9 1879.71
  4871.5 1868.06  4901.1 1859.11  4928.3  1857.5  4958.7 1849.48  4996.2 1844.93
  5029.5 1849.68  5049.8 1852.53  5140.9 1855.53  5381.3 1852.57  5441.4  1854.9
  5941.6  1858.9  5991.6 1863.41  6163.3 1902.74  6251.7 1911.64  6313.7 1913.72
#Mann= 6 ,-1 , 0
  3898.1      .1       0  4630.9     .16       0  4871.5      .1       0
  4958.7     .07       0  5049.8      .1       0  6313.7      .1       0
Bank Sta=4958.7,5029.5
XS Rating Curve= 0 ,0
Exp/Cntr=0.3,0.1

Type RM Length L Ch R = 1 ,103     ,0,0,0
BEGIN DESCRIPTION:
UNT 1051 IN HEWA 1.0
END DESCRIPTION:
XS GIS Cut Line= 4
      2729626.05     10009142.46      2730636.47     10009020.93
      2730723.28     10008871.62      2730560.09     10007520.96
#Sta/Elev= 30
  3891.8 1925.02  4008.4 1922.08  4065.5 1914.37  4085.5 1917.17  4115.8 1915.43
    4136 1917.55    4146 1915.12    4277 1910.96  4387.8 1902.37  4538.8 1899.45
  4593.6 1895.78  4680.8 1884.81  4762.9 1871.81  4810.8 1860.97  4830.9 1857.35
  4917.7 1852.33  5000.8 1843.01  5003.5 1842.51  5006.8 1843.01  5033.5 1849.62
  5062.6 1850.84    5342 1853.33  5382.3  1850.5  5563.6 1854.88  6097.4 1859.29
  6137.7 1865.25    6178 1878.03  6278.7 1901.59  6369.4 1911.21  6442.7 1913.56
#Mann= 6 ,-1 , 0
  3891.8      .1       0  4538.8     .16       0  4810.8      .1       0
  4917.7     .09       0  5006.8      .1       0  6442.7      .1       0
Bank Sta=5000.8,5006.8
XS Rating Curve= 0 ,0
Exp/Cntr=0.3,0.1

Chan Stop Cuts=-1
Use User Specified Reach Order=0
Composite Channel Slope=5