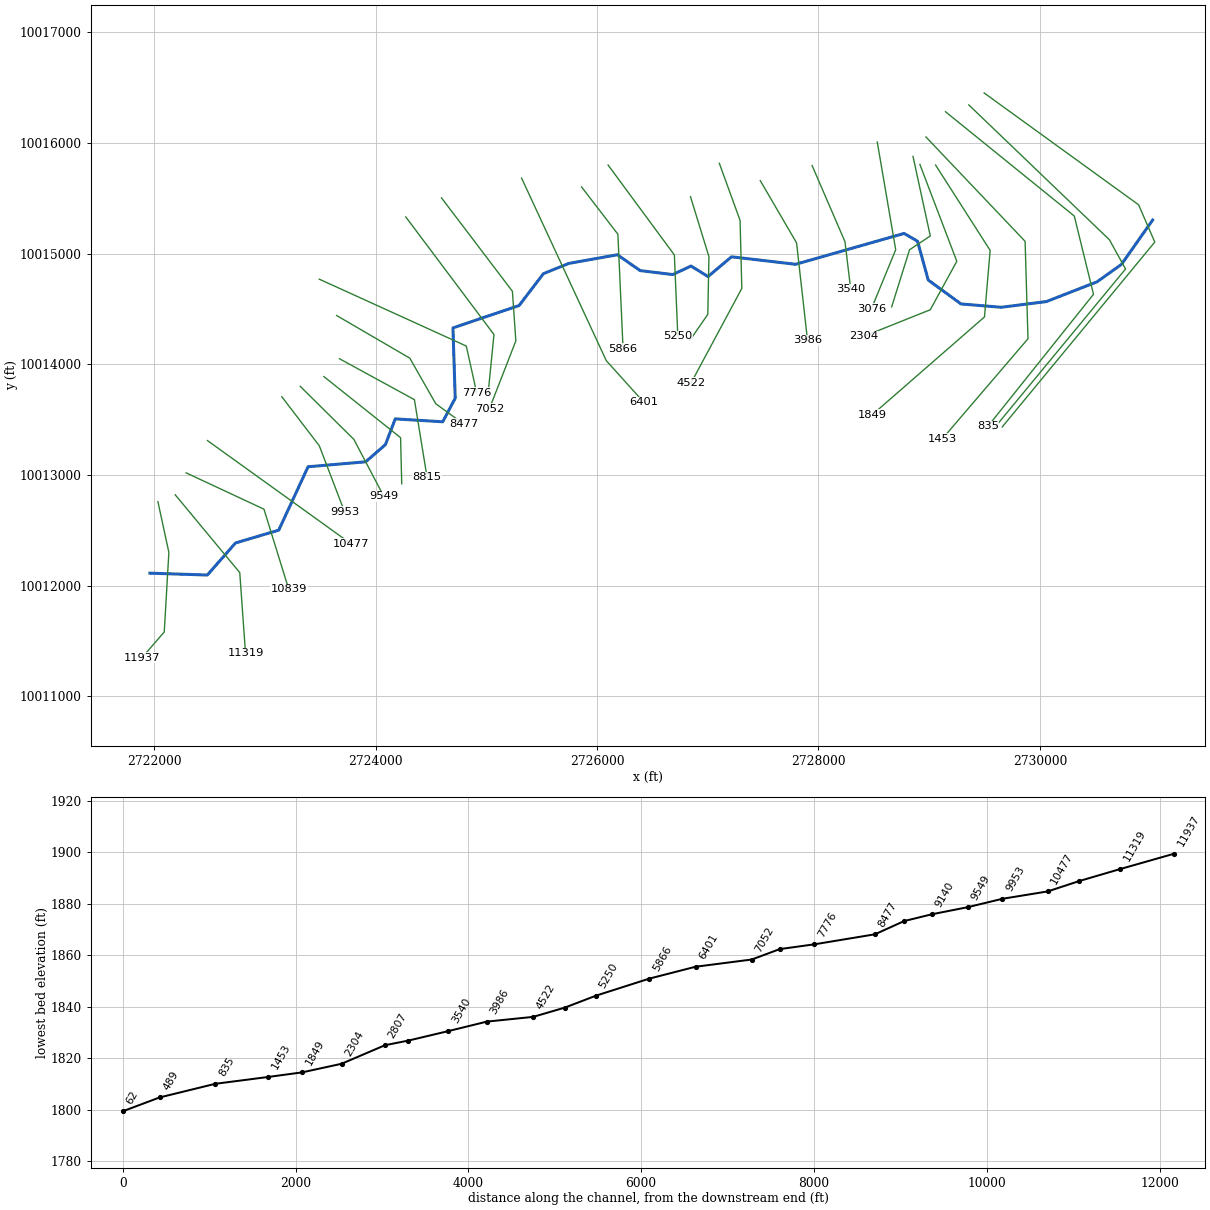
--- UNT 1052 IN HEWA.prj (project) ---

Proj Title=UNT 1052 IN HEWA Base Level Engineering
Current Plan=p01
Default Exp/Contr=0.3,0.1
English Units
Geom File=g01
Flow File=f01
Plan File=p01
Y Axis Title=Elevation
X Axis Title(PF)=Main Channel Distance
X Axis Title(XS)=Station
BEGIN DESCRIPTION:
UNT 1052 IN HEWA
END DESCRIPTION:
DSS Export Rating Curves= 0
DSS Export Rating Curve Sorted= 0
DSS Export Volume Flow Curves= 0
DXF OffsetX= 0
DXF OffsetY= 0
DXF ScaleX= 1
DXF ScaleY= 10

--- UNT 1052 IN HEWA.p01 (plan) ---

Plan Title=Multiple Run
Short Identifier=Multiple
Geom File=g01
Flow File=f01
Subcritical Flow
K Sum by GR= 0
Std Step Tol= 0.01
Critical Tol= 0.01
Num of Std Step Trials= 20
Max Error Tol= 0.3
Flow Tol Ratio= 0.001
Split Flow NTrial= 30
Split Flow Tol= 0.02
Split Flow Ratio= 0.02
Log Output Level= 0
Friction Slope Method= 1
Unsteady Friction Slope Method= 2
Unsteady Bridges Friction Slope Method= 1
Parabolic Critical Depth
Global Vel Dist=  1 , 1 , 1
Global Log Level= 0
CheckData=True
Encroach Param= -1, 0, 0, 0
BEGIN DESCRIPTION:
Multiple Run
END DESCRIPTION:

--- UNT 1052 IN HEWA.f01 (steady flow) ---

Flow Title=Multiple
Number of Profiles=7
Profile Names=10-year,25-year,50-year,1pct_min,100-year,1pct_plu,500-year
River Rch & RM= UNT 1052 IN HEWA,Reach-1,11937
    1336    1975    2539    2384    3224    4360    5219
River Rch & RM= UNT 1052 IN HEWA,Reach-1,7052
    1651    2460    3178    2996    4051    5479    6614
Boundary for River Rch & Prof#=UNT 1052 IN HEWA,Reach-1,1
Up Type=0
Dn Type=3
Dn Slope=0.005
Boundary for River Rch & Prof#=UNT 1052 IN HEWA,Reach-1,2
Up Type=0
Dn Type=3
Dn Slope=0.005
Boundary for River Rch & Prof#=UNT 1052 IN HEWA,Reach-1,3
Up Type=0
Dn Type=3
Dn Slope=0.005
Boundary for River Rch & Prof#=UNT 1052 IN HEWA,Reach-1,4
Up Type=0
Dn Type=3
Dn Slope=0.005
Boundary for River Rch & Prof#=UNT 1052 IN HEWA,Reach-1,5
Up Type=0
Dn Type=3
Dn Slope=0.005
Boundary for River Rch & Prof#=UNT 1052 IN HEWA,Reach-1,6
Up Type=0
Dn Type=3
Dn Slope=0.005
Boundary for River Rch & Prof#=UNT 1052 IN HEWA,Reach-1,7
Up Type=0
Dn Type=3
Dn Slope=0.005

--- UNT 1052 IN HEWA.g01 (geometry) ---

Geom Title=Existing Conditions
Program Version=4.10

River Reach=UNT 1052 IN HEWA,Reach-1
Reach XY= 30
      2721958.47     10012113.73      2722477.48      10012096.7
       2722732.1     10012386.33       2723123.1     10012502.32
      2723387.96     10013075.13      2723908.34     10013119.83
      2724086.59     10013274.56      2724175.69     10013507.63
      2724604.83     10013481.48      2724717.58     10013694.26
       2724697.1     10014329.58      2725294.93     10014531.87
      2725514.51     10014819.73      2725744.95     10014912.53
      2726183.15     10014990.65      2726388.23     10014847.43
      2726683.37     10014811.62       2726848.3     10014888.66
      2727002.06     10014793.74      2727214.16       10014972.
      2727793.12     10014904.44      2728773.83     10015183.27
      2728895.23     10015112.39      2728991.79     10014761.99
      2729288.26     10014546.02      2729651.42       10014516.
      2730058.66     10014567.24      2730517.41     10014746.02
       2730737.6     10014903.44      2731019.29     10015304.05

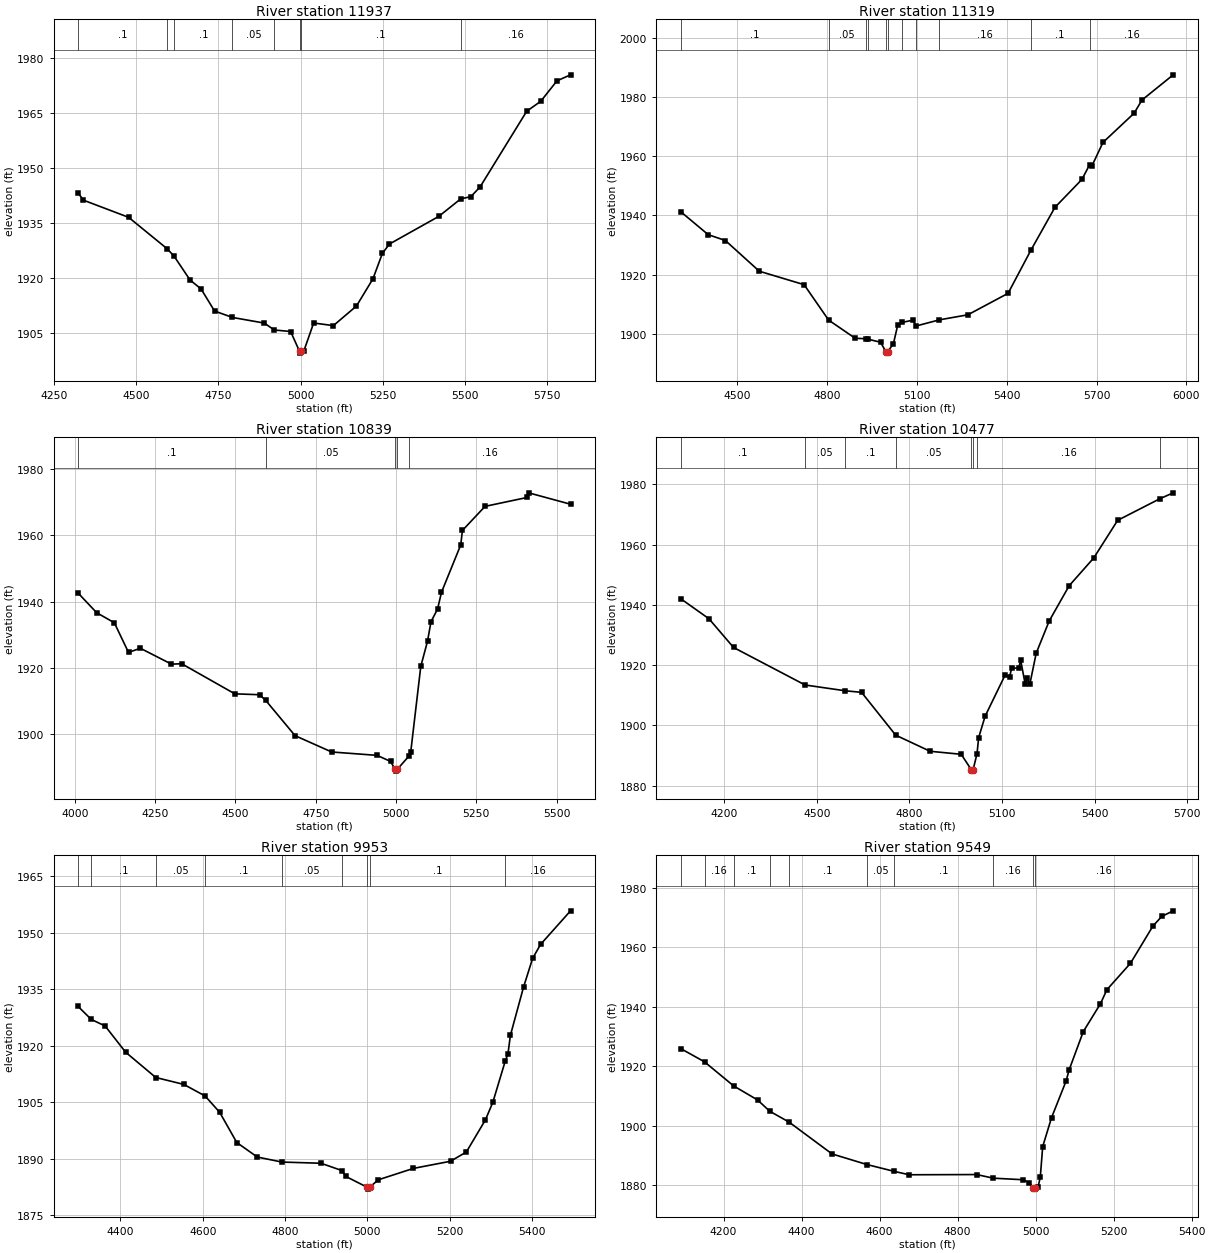
Type RM Length L Ch R = 1 ,11937   ,618,618,618
BEGIN DESCRIPTION:
UNT 1052 IN HEWA 25.0
END DESCRIPTION:
XS GIS Cut Line= 4
      2722031.17     10012759.48      2722130.14     10012301.11
      2722088.47     10011582.36      2721885.69     10011348.39
#Sta/Elev= 30
    4323  1943.1  4339.1 1941.17  4476.6 1936.49  4594.5 1927.86  4615.5 1925.81
  4663.5 1919.38  4697.2 1916.93  4738.1 1910.92  4792.4 1909.17  4889.5 1907.63
  4919.9 1905.74  4969.6 1905.33  4996.7 1899.93  4999.4 1899.43  5002.7 1899.93
  5009.7 1899.99  5039.7 1907.65  5099.8 1906.94  5169.9 1912.28    5220 1919.68
  5248.9 1926.65  5270.1 1929.19  5420.4 1936.74  5487.5 1941.54  5518.1 1942.12
  5546.6 1944.84  5688.1 1965.44  5730.9 1968.16  5780.2 1973.74  5821.5 1975.38
#Mann= 8 ,-1 , 0
    4323      .1       0  4594.5     .05       0  4615.5      .1       0
  4792.4     .05       0  4919.9      .1       0  4996.7     .07       0
  5002.7      .1       0  5487.5     .16       0
Bank Sta=4996.7,5002.7
XS Rating Curve= 0 ,0
Exp/Cntr=0.3,0.1

Type RM Length L Ch R = 1 ,11319   ,480,480,480
BEGIN DESCRIPTION:
UNT 1052 IN HEWA 24.0
END DESCRIPTION:
XS GIS Cut Line= 3
      2722187.41     10012821.97      2722770.76     10012118.82
      2722822.85     10011389.61
#Sta/Elev= 30
  4311.1 1941.21  4402.6 1933.49  4459.9 1931.52  4573.2 1921.16  4722.9 1916.62
  4804.7 1904.68  4893.5 1898.54  4929.5 1898.38  4934.9 1898.26  4978.2 1897.21
    4996 1894.03  4998.8 1893.53    5002 1894.03  5021.2 1896.69  5035.5 1902.96
  5051.5 1903.92    5085 1904.62    5098 1902.71  5174.9 1904.76  5269.9 1906.46
  5404.2  1913.7    5480 1928.17  5560.7  1942.7  5650.9 1952.13  5676.7  1957.1
  5684.9 1956.81  5721.1  1964.6  5825.2 1974.46  5851.4  1978.9  5955.8 1987.41
#Mann= 11 ,-1 , 0
  4311.1      .1       0  4804.7     .05       0  4929.5      .1       0
  4934.9     .05       0    4996    .035       0    5002     .05       0
  5051.5     .16       0    5098      .1       0  5174.9     .16       0
    5480      .1       0  5676.7     .16       0
Bank Sta=4996,5002
XS Rating Curve= 0 ,0
Exp/Cntr=0.3,0.1

Type RM Length L Ch R = 1 ,10839   ,362,362,362
BEGIN DESCRIPTION:
UNT 1052 IN HEWA 23.0
END DESCRIPTION:
XS GIS Cut Line= 3
      2722286.41     10013019.85      2722989.51     10012691.74
      2723213.32     10011968.26
#Sta/Elev= 30
  4010.1 1942.56  4067.5 1936.66  4122.7 1933.61  4166.9 1924.65  4203.7 1925.91
  4300.7 1921.11  4332.4 1921.24  4497.9 1912.15    4575 1911.88  4594.2 1910.16
  4685.5 1899.52  4799.5 1894.59  4940.9 1893.57  4982.8 1891.74  4997.4 1889.31
  5000.2 1888.81  5003.4 1889.31  5041.3 1893.48  5045.6  1894.5    5077 1920.45
  5097.9 1928.01  5108.8 1933.93  5129.3 1937.76  5141.4  1942.8  5201.4 1957.11
  5206.6 1961.48  5277.1 1968.75  5407.6 1971.43  5412.8 1972.84  5543.3  1969.4
#Mann= 5 ,-1 , 0
  4010.1      .1       0  4594.2     .05       0  4997.4    .035       0
  5003.4     .05       0  5041.3     .16       0
Bank Sta=4997.4,5003.4
XS Rating Curve= 0 ,0
Exp/Cntr=0.3,0.1

Type RM Length L Ch R = 1 ,10477   ,524,524,524
BEGIN DESCRIPTION:
UNT 1052 IN HEWA 22.0
END DESCRIPTION:
XS GIS Cut Line= 2
       2722479.1     10013311.52      2723774.68     10012380.17
#Sta/Elev= 30
  4059.2 1942.03  4150.2 1935.42    4230 1925.87  4461.9 1913.41  4592.6 1911.48
  4644.9 1910.97  4755.5 1896.75  4867.1  1891.4  4967.8  1890.4  5000.4 1885.31
  5003.2 1884.81  5006.4 1885.31    5019 1890.58  5024.3 1895.91  5045.2 1903.03
  5110.2 1916.75  5124.9 1916.19  5131.1 1918.93  5154.4 1919.12  5160.6 1921.59
  5175.3  1913.6  5181.4 1915.77    5190 1913.61  5210.9    1924    5253 1934.68
  5317.7 1946.38  5397.5 1955.62  5474.8 1968.09  5612.2 1975.29  5654.8 1977.22
#Mann= 8 ,-1 , 0
  4059.2      .1       0  4461.9     .05       0  4592.6      .1       0
  4755.5     .05       0  5000.4    .035       0  5006.4     .05       0
    5019     .16       0  5612.2      .1       0
Bank Sta=5000.4,5006.4
XS Rating Curve= 0 ,0
Exp/Cntr=0.3,0.1

Type RM Length L Ch R = 1 ,9953    ,404,404,404
BEGIN DESCRIPTION:
UNT 1052 IN HEWA 21.0
END DESCRIPTION:
XS GIS Cut Line= 3
      2723150.98     10013707.35      2723489.51     10013264.65
      2723718.11     10012667.19
#Sta/Elev= 30
  4297.2 1930.38  4329.2 1926.94  4362.8 1925.21  4412.6 1918.26  4485.9 1911.55
    4554 1909.72  4605.7 1906.66  4641.2 1902.33  4682.8 1894.31  4732.7 1890.46
  4792.5 1889.13  4887.6 1888.81  4938.4 1886.87    4948 1885.31  4999.8 1882.45
  5002.5 1881.95  5005.8 1882.45  5026.8 1884.42  5112.3 1887.45  5202.4 1889.34
  5240.9 1891.79  5287.2  1900.3  5305.2 1904.94  5335.5 1915.93    5342 1917.78
    5348 1922.73  5380.1 1935.58  5402.1 1943.16  5421.4 1946.85  5494.2 1955.75
#Mann= 9 ,-1 , 0
  4297.2     .16       0  4329.2      .1       0  4485.9     .05       0
  4605.7      .1       0  4792.5     .05       0  4938.4      .1       0
  4999.8     .07       0  5005.8      .1       0  5335.5     .16       0
Bank Sta=4999.8,5005.8
XS Rating Curve= 0 ,0
Exp/Cntr=0.3,0.1

Type RM Length L Ch R = 1 ,9549    ,409,409,409
BEGIN DESCRIPTION:
UNT 1052 IN HEWA 20.0
END DESCRIPTION:
XS GIS Cut Line= 3
      2723317.65      10013801.1      2723802.01     10013321.95
      2724072.22     10012807.51
#Sta/Elev= 30
  4090.3 1925.91    4151 1921.48  4225.9 1913.36    4287 1908.66  4318.4 1904.85
  4367.8 1901.22  4477.9 1890.51  4567.1 1886.95  4637.6 1884.63  4675.9  1883.5
  4848.7 1883.57  4891.6 1882.35  4967.8 1881.83  4984.2 1880.83  4992.5 1879.17
  4995.3 1878.67  4998.5 1879.17  5006.2  1879.4  5011.9 1882.68  5018.1 1892.98
  5040.7 1902.68    5078 1915.01  5085.9 1918.79  5122.1 1931.63  5166.2 1941.02
  5182.6 1945.72  5243.1 1954.62  5300.5  1967.1  5323.1 1970.36  5352.7 1972.26
#Mann= 10 ,-1 , 0
  4090.3      .1       0    4151     .16       0  4225.9      .1       0
  4318.4     .16       0  4367.8      .1       0  4567.1     .05       0
  4637.6      .1       0  4891.6     .16       0  4992.5     .07       0
  4998.5     .16       0
Bank Sta=4992.5,4998.5
XS Rating Curve= 0 ,0
Exp/Cntr=0.3,0.1

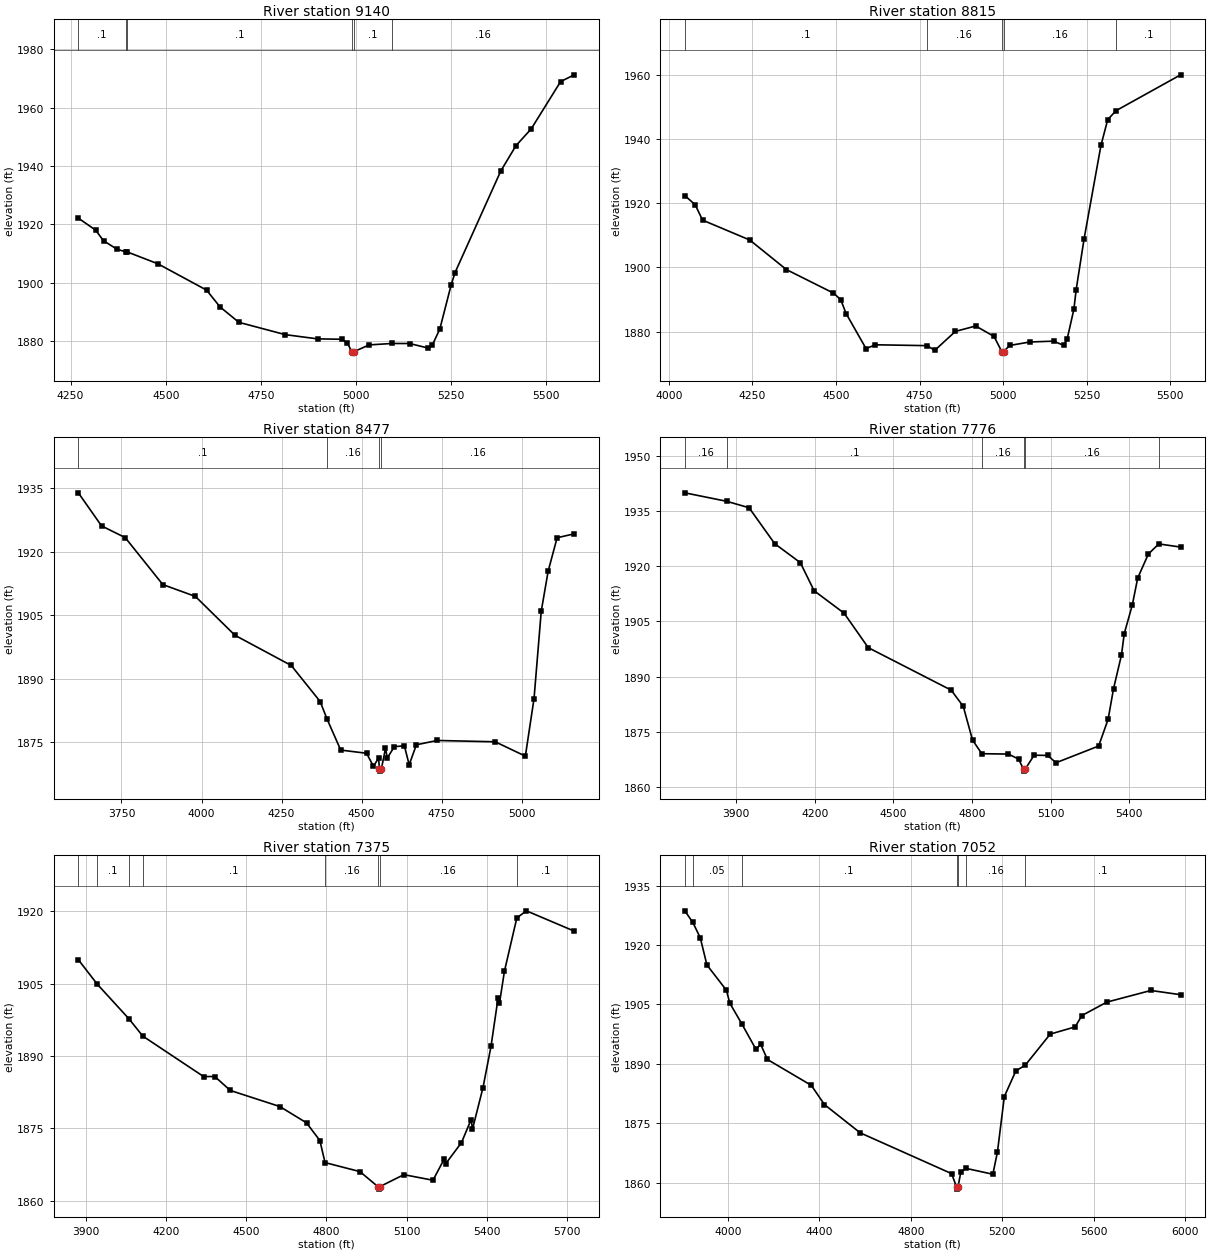
Type RM Length L Ch R = 1 ,9140    ,325,325,325
BEGIN DESCRIPTION:
UNT 1052 IN HEWA 19.0
END DESCRIPTION:
XS GIS Cut Line= 3
      2723531.22     10013889.62      2724223.89     10013337.57
       2724234.3     10012920.95
#Sta/Elev= 30
  4270.4 1922.14  4315.8 1918.05  4336.6  1914.4  4371.8 1911.53  4394.8 1910.61
  4399.3 1910.56  4479.1 1906.54  4607.3 1897.52  4642.5 1891.79  4692.1  1886.5
  4813.8 1882.29  4898.7 1880.84  4962.8  1880.7  4977.2 1879.44  4988.6 1876.46
  4991.4 1875.96  4994.6 1876.46  5034.1 1878.77  5093.9 1879.26  5140.5 1879.25
    5190 1877.67    5200 1878.63    5220  1884.2    5250 1899.42    5260 1903.53
  5380.1 1938.27  5420.1 1946.95  5460.1 1952.69  5537.3 1968.86  5572.9 1971.18
#Mann= 6 ,-1 , 0
  4270.4      .1       0  4394.8     .16       0  4399.3      .1       0
  4988.6     .07       0  4994.6      .1       0  5093.9     .16       0
Bank Sta=4988.6,4994.6
XS Rating Curve= 0 ,0
Exp/Cntr=0.3,0.1

Type RM Length L Ch R = 1 ,8815    ,338,338,338
BEGIN DESCRIPTION:
UNT 1052 IN HEWA 18.0
END DESCRIPTION:
XS GIS Cut Line= 3
      2723671.79     10014051.12      2724348.89     10013681.32
      2724463.42     10012978.49
#Sta/Elev= 30
  4047.5 1922.37  4078.5 1919.53  4100.7 1914.72  4241.7 1908.54  4351.4 1899.33
  4492.2    1892    4514 1889.96  4530.1 1885.63  4589.9 1874.68  4617.4 1875.89
  4771.8 1875.62  4795.7 1874.18  4857.1 1880.05  4917.9 1881.74  4972.7  1878.5
  4995.9 1873.79  4998.7 1873.29  5001.9 1873.79  5019.2 1875.67    5080 1876.76
  5150.9 1877.02  5181.3 1875.71  5191.4 1877.59  5211.7 1886.95  5218.6  1893.1
  5242.1  1908.8  5292.8 1938.05    5313 1946.05    5338 1948.83  5531.1 1959.99
#Mann= 5 ,-1 , 0
  4047.5      .1       0  4771.8     .16       0  4995.9     .07       0
  5001.9     .16       0    5338      .1       0
Bank Sta=4995.9,5001.9
XS Rating Curve= 0 ,0
Exp/Cntr=0.3,0.1

Type RM Length L Ch R = 1 ,8477    ,701,701,701
BEGIN DESCRIPTION:
UNT 1052 IN HEWA 17.0
END DESCRIPTION:
XS GIS Cut Line= 4
       2723645.8     10014441.71      2724307.22     10014056.32
      2724541.59     10013644.86      2724791.56     10013462.59
#Sta/Elev= 30
  3615.3 1933.88  3687.8 1926.07  3761.7  1923.3  3879.1 1912.21  3980.9 1909.41
  4104.5 1900.23  4280.3  1893.1  4370.5 1884.59  4391.6 1880.52  4434.7 1873.12
  4515.4 1872.37    4537 1869.27  4552.9 1871.26  4555.6 1868.65  4558.4 1868.15
  4561.6 1868.65  4574.5 1873.51  4580.2 1871.27  4602.4 1873.94  4633.5 1874.12
  4648.5 1869.66    4671 1874.37  4735.8 1875.39  4917.1 1875.08  5011.3 1871.69
  5038.4 1885.28  5060.9 1905.91  5082.4 1915.34  5110.4 1923.27  5163.7 1924.19
#Mann= 4 ,-1 , 0
  3615.3      .1       0  4391.6     .16       0  4555.6     .07       0
  4561.6     .16       0
Bank Sta=4555.6,4561.6
XS Rating Curve= 0 ,0
Exp/Cntr=0.3,0.1

Type RM Length L Ch R = 1 ,7776    ,401,401,401
BEGIN DESCRIPTION:
UNT 1052 IN HEWA 16.0
END DESCRIPTION:
XS GIS Cut Line= 3
      2723489.48     10014769.87      2724817.64      10014165.7
      2724911.39      10013743.8
#Sta/Elev= 30
  3704.2 1939.97  3864.3 1937.66  3949.4 1935.91  4047.1 1926.14  4144.8 1920.98
  4197.5 1913.33  4311.8 1907.23    4404 1897.85  4720.3 1886.29  4766.4 1881.88
  4801.7 1872.71  4837.2    1869  4938.8  1868.9  4977.5 1867.52  4996.4 1864.76
  4999.2 1864.26  5002.4 1864.76  5036.6 1868.59  5088.2 1868.53  5120.3 1866.54
  5282.8 1871.09    5319 1878.38  5339.5 1886.66  5369.8 1895.83  5380.5 1901.68
  5411.2 1909.46  5431.7 1916.77  5472.6 1923.34  5512.3 1926.07  5595.5 1925.21
#Mann= 6 ,-1 , 0
  3704.2     .16       0  3864.3      .1       0  4837.2     .16       0
  4996.4     .07       0  5002.4     .16       0  5512.3      .1       0
Bank Sta=4996.4,5002.4
XS Rating Curve= 0 ,0
Exp/Cntr=0.3,0.1

Type RM Length L Ch R = 1 ,7375    ,323,323,323
BEGIN DESCRIPTION:
UNT 1052 IN HEWA 15.0
END DESCRIPTION:
XS GIS Cut Line= 3
      2724270.77     10015332.35      2725067.64     10014269.86
      2725015.55     10013743.84
#Sta/Elev= 30
  3870.9 1909.95  3941.9 1904.87    4061 1897.66  4112.2 1894.12    4340 1885.73
  4381.7 1885.74    4440 1882.85  4625.4 1879.52  4725.4 1876.14  4775.4 1872.47
  4794.7  1867.9  4925.4 1866.03  4993.2  1862.9    4996  1862.4  4999.2  1862.9
    5090  1865.4    5199 1864.24  5240.8 1868.63  5245.9 1867.62  5305.7 1872.04
  5341.8 1876.83  5346.8 1874.81    5386 1883.39  5416.2 1891.98  5442.8 1902.05
  5447.8 1900.88  5466.4 1907.53  5512.9 1918.61  5548.8 1920.08  5727.6 1915.88
#Mann= 8 ,-1 , 0
  3870.9     .05       0  3941.9      .1       0    4061     .16       0
  4112.2      .1       0  4794.7     .16       0  4993.2     .07       0
  4999.2     .16       0  5512.9      .1       0
Bank Sta=4993.2,4999.2
XS Rating Curve= 0 ,0
Exp/Cntr=0.3,0.1

Type RM Length L Ch R = 1 ,7052    ,651,651,651
BEGIN DESCRIPTION:
UNT 1052 IN HEWA 14.0
END DESCRIPTION:
XS GIS Cut Line= 4
      2724593.69     10015504.22       2725234.3     10014660.49
      2725265.55     10014212.57      2725026.12     10013598.37
#Sta/Elev= 30
  3811.7 1928.63  3846.9 1925.69  3879.4 1921.81  3908.5 1914.95  3993.8 1908.57
  4008.3 1905.33  4060.3 1900.16  4122.7 1893.67  4143.6 1894.91  4172.6 1891.11
  4364.8 1884.56  4422.2 1879.71  4578.3 1872.58  4978.1 1862.27  4999.9 1858.86
  5002.7 1858.36  5005.9 1858.86  5018.2 1862.61  5041.1  1863.6  5158.5 1862.12
  5178.6 1867.79  5208.6 1881.73  5258.8  1888.2  5300.4 1889.68  5409.2  1897.5
    5518 1899.32  5547.8 1902.19  5656.6 1905.58  5849.5 1908.52  5979.3 1907.45
#Mann= 7 ,-1 , 0
  3811.7      .1       0  3846.9     .05       0  4060.3      .1       0
  4999.9     .07       0  5005.9      .1       0  5041.1     .16       0
  5300.4      .1       0
Bank Sta=4999.9,5005.9
XS Rating Curve= 0 ,0
Exp/Cntr=0.3,0.1

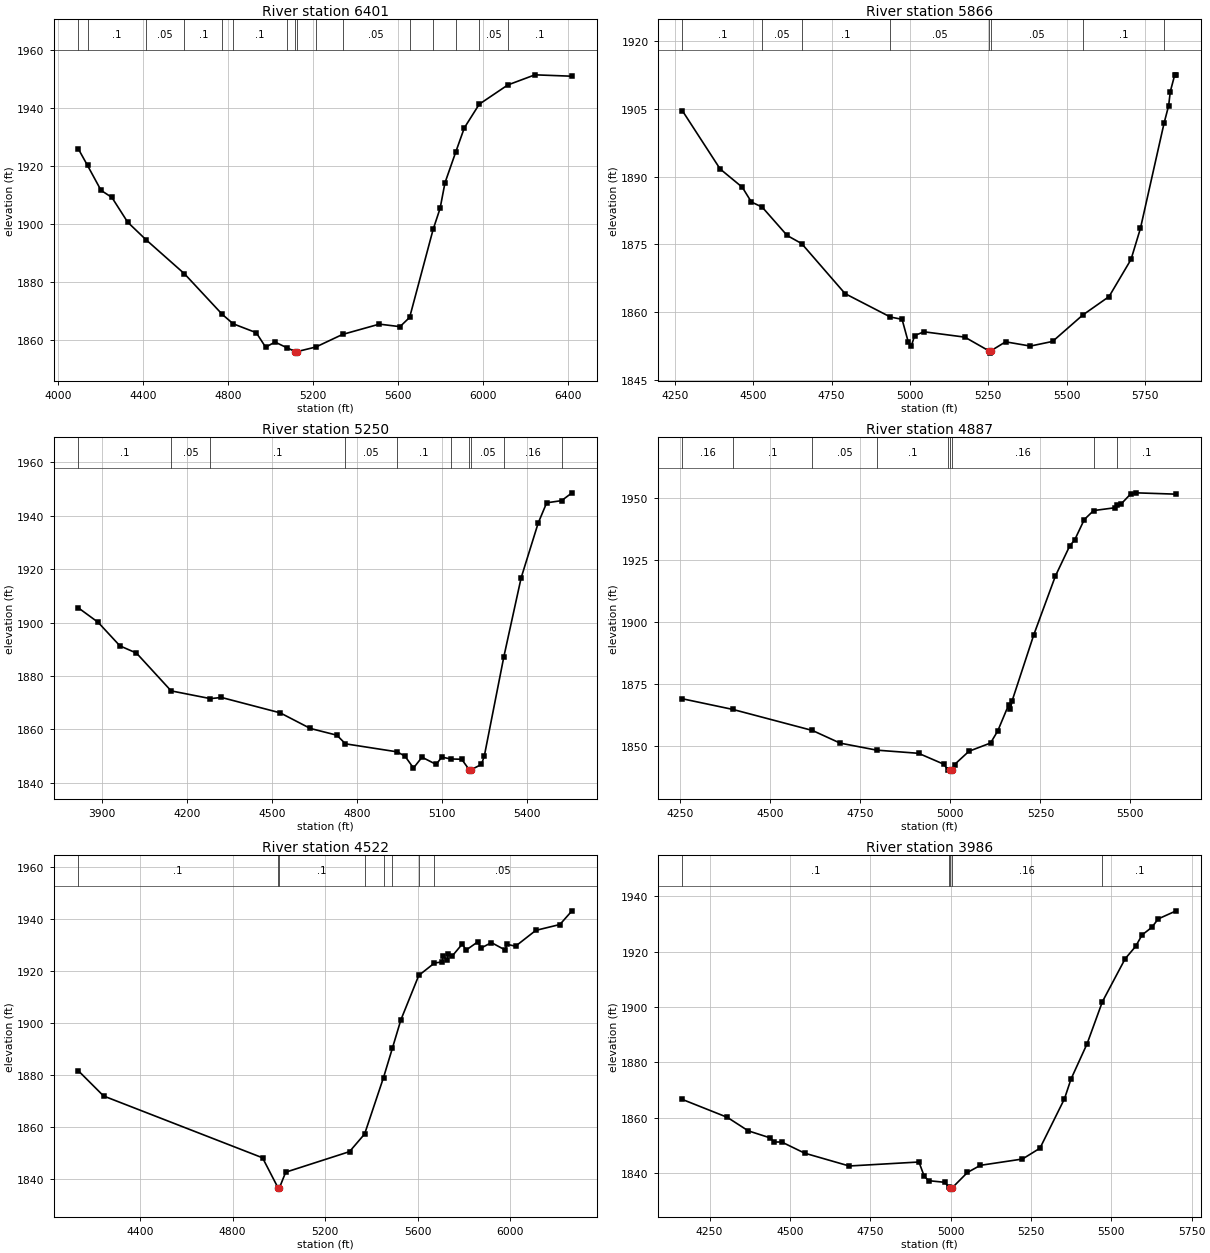
Type RM Length L Ch R = 1 ,6401    ,535,535,535
BEGIN DESCRIPTION:
UNT 1052 IN HEWA 13.0
END DESCRIPTION:
XS GIS Cut Line= 3
      2725317.13     10015683.31      2726082.92     10014033.23
      2726420.23     10013659.45
#Sta/Elev= 30
  4095.3 1925.98    4139 1920.21  4202.5 1911.64  4253.8 1909.18    4328 1900.66
  4413.4 1894.67  4595.1 1882.88  4772.4 1868.93  4823.9 1865.66  4932.7 1862.59
  4976.8  1857.6  5020.9 1859.36  5076.1 1857.43  5117.1 1856.05  5119.9 1855.55
  5123.1 1856.05  5213.1 1857.66  5338.5 1861.99  5511.7 1865.54  5608.8 1864.67
  5654.2 1867.86  5764.6 1898.15  5797.5 1905.44  5820.4 1914.22  5870.9  1924.8
  5911.4 1933.16  5981.7 1941.32    6116 1947.95  6243.7 1951.44  6417.9 1950.96
#Mann= 16 ,-1 , 0
  4095.3     .05       0    4139      .1       0  4413.4     .05       0
  4595.1      .1       0  4772.4     .05       0  4823.9      .1       0
  5076.1     .05       0  5117.1     .07       0  5123.1     .05       0
  5213.1      .1       0  5338.5     .05       0  5654.2      .1       0
  5764.6     .16       0  5870.9      .1       0  5981.7     .05       0
    6116      .1       0
Bank Sta=5117.1,5123.1
XS Rating Curve= 0 ,0
Exp/Cntr=0.3,0.1

Type RM Length L Ch R = 1 ,5866    ,616,616,616
BEGIN DESCRIPTION:
UNT 1052 IN HEWA 12.0
END DESCRIPTION:
XS GIS Cut Line= 3
      2725859.31     10015603.19      2726187.43     10015176.11
       2726234.3     10014139.64
#Sta/Elev= 30
  4273.7 1904.54  4394.1 1891.67  4464.8 1887.63  4493.8 1884.37  4528.4 1883.23
    4608 1876.96  4654.3 1875.17  4792.9  1864.1  4937.7 1858.92  4974.8 1858.42
  4994.8 1853.34  5004.8 1852.61  5014.9 1854.83  5044.9 1855.66    5175 1854.48
  5252.1 1851.44  5254.9 1850.94  5258.1 1851.44  5305.2 1853.44  5384.4  1852.5
  5455.3 1853.53  5551.4 1859.36  5635.5 1863.45  5705.6 1871.66  5735.6 1878.52
    5811 1901.78  5825.7 1905.68    5831  1908.8  5845.2  1912.5  5849.8  1912.5
#Mann= 8 ,-1 , 0
  4273.7      .1       0  4528.4     .05       0  4654.3      .1       0
  4937.7     .05       0  5252.1    .035       0  5258.1     .05       0
  5551.4      .1       0    5811     .16       0
Bank Sta=5252.1,5258.1
XS Rating Curve= 0 ,0
Exp/Cntr=0.3,0.1

Type RM Length L Ch R = 1 ,5250    ,363,363,363
BEGIN DESCRIPTION:
UNT 1052 IN HEWA 11.0
END DESCRIPTION:
XS GIS Cut Line= 3
      2726098.89      10015801.1      2726697.84     10014988.61
      2726729.09     10014254.27
#Sta/Elev= 30
  3815.8 1905.52  3885.9 1900.09  3963.1 1891.25  4021.6 1888.54    4144 1874.39
  4282.8 1871.49  4321.9 1871.92  4529.1 1866.17  4635.6 1860.32  4729.6 1857.79
  4759.8 1854.56  4942.6 1851.55  4970.2 1849.94  5000.2 1845.49  5030.3 1849.54
  5080.3 1846.85  5100.3 1849.59  5131.3 1848.89  5170.4 1848.77  5197.4 1844.83
  5200.2 1844.33  5203.4 1844.83  5240.4 1846.85  5250.5 1850.03  5319.6 1887.26
  5380.6 1916.76  5440.6  1937.2  5470.7 1944.84  5523.4 1945.65  5560.2 1948.58
#Mann= 10 ,-1 , 0
  3815.8      .1       0    4144     .05       0  4282.8      .1       0
  4759.8     .05       0  4942.6      .1       0  5131.3     .05       0
  5197.4     .07       0  5203.4     .05       0  5319.6     .16       0
  5523.4      .1       0
Bank Sta=5197.4,5203.4
XS Rating Curve= 0 ,0
Exp/Cntr=0.3,0.1

Type RM Length L Ch R = 1 ,4887    ,365,365,365
BEGIN DESCRIPTION:
UNT 1052 IN HEWA 10.0
END DESCRIPTION:
XS GIS Cut Line= 4
      2726843.68     10015514.65      2727010.34     10014972.99
      2726999.93     10014452.15      2726838.79     10014218.24
#Sta/Elev= 30
  4255.6  1868.9  4395.6  1864.6  4616.9 1856.09  4693.8 1850.98  4795.2 1848.15
  4911.6 1846.87  4981.6 1842.47    4993 1840.22  4998.6 1840.17  5001.4 1839.67
  5004.6 1840.17  5011.6 1842.34  5051.6  1847.7  5111.6 1851.03  5131.6 1855.92
  5161.5 1866.33  5166.5 1864.63  5171.6 1868.13  5231.7 1894.77  5291.7 1918.48
  5331.7 1930.73  5345.3 1933.09    5372 1941.33  5397.9 1944.95  5458.6 1946.12
  5463.8 1947.25  5473.4 1947.47  5500.5 1951.62  5515.4 1952.12  5627.3 1951.58
#Mann= 9 ,-1 , 0
  4255.6     .16       0  4395.6      .1       0  4616.9     .05       0
  4795.2      .1       0    4993     .16       0  4998.6     .07       0
  5004.6     .16       0  5397.9     .05       0  5463.8      .1       0
Bank Sta=4998.6,5004.6
XS Rating Curve= 0 ,0
Exp/Cntr=0.3,0.1

Type RM Length L Ch R = 1 ,4522    ,536,536,536
BEGIN DESCRIPTION:
UNT 1052 IN HEWA 9.0
END DESCRIPTION:
XS GIS Cut Line= 4
      2727104.11      10015816.7      2727291.59     10015301.11
      2727307.22     10014686.53      2726848.87     10013832.33
#Sta/Elev= 30
  4133.2 1881.71  4242.8 1871.95  4929.3 1848.15  4996.3 1836.58    4999 1836.08
  5002.3 1836.58  5029.3  1842.6    5305 1850.52  5370.3 1857.32  5451.9 1879.07
  5489.9 1890.27  5526.7 1901.23  5604.2 1918.39  5671.8 1923.16  5704.5 1923.58
  5710.2 1925.87  5726.4  1924.2  5732.1 1926.75  5748.4 1925.83  5792.2 1930.51
  5808.5 1928.14    5858 1931.25  5874.2 1928.98  5918.1 1931.03  5978.2 1928.14
  5983.8 1930.42    6022 1929.63  6109.7 1935.74  6213.7    1938    6266 1943.27
#Mann= 8 ,-1 , 0
  4133.2      .1       0  4996.3     .07       0  5002.3      .1       0
  5370.3     .16       0  5451.9      .1       0  5489.9     .16       0
  5604.2      .1       0  5671.8     .05       0
Bank Sta=4996.3,5002.3
XS Rating Curve= 0 ,0
Exp/Cntr=0.3,0.1

Type RM Length L Ch R = 1 ,3986    ,446,446,446
BEGIN DESCRIPTION:
UNT 1052 IN HEWA 8.0
END DESCRIPTION:
XS GIS Cut Line= 3
      2727473.86     10015660.52      2727802.01     10015097.99
      2727900.91     10014218.28
#Sta/Elev= 30
  4165.4 1866.64    4305 1860.19  4370.1 1855.31  4438.1 1852.77  4451.1 1851.27
  4474.3 1851.27  4545.6 1847.24  4684.5  1842.6  4901.4 1844.04  4917.9 1838.87
  4931.6 1837.29  4981.9  1836.7  4994.3 1834.97  4999.1 1834.74  5001.8 1834.24
  5005.1 1834.74  5052.4 1840.27  5092.6 1842.84  5223.5 1845.12    5278 1849.03
  5354.3  1866.9  5374.4 1873.96  5424.7 1886.79  5472.2 1901.96  5543.1 1917.49
  5575.7 1921.96  5595.8 1926.11    5626 1928.84  5646.1  1931.9  5701.9 1934.81
#Mann= 5 ,-1 , 0
  4165.4      .1       0  4994.3     .16       0  4999.1     .07       0
  5005.1     .16       0  5472.2      .1       0
Bank Sta=4999.1,5005.1
XS Rating Curve= 0 ,0
Exp/Cntr=0.3,0.1

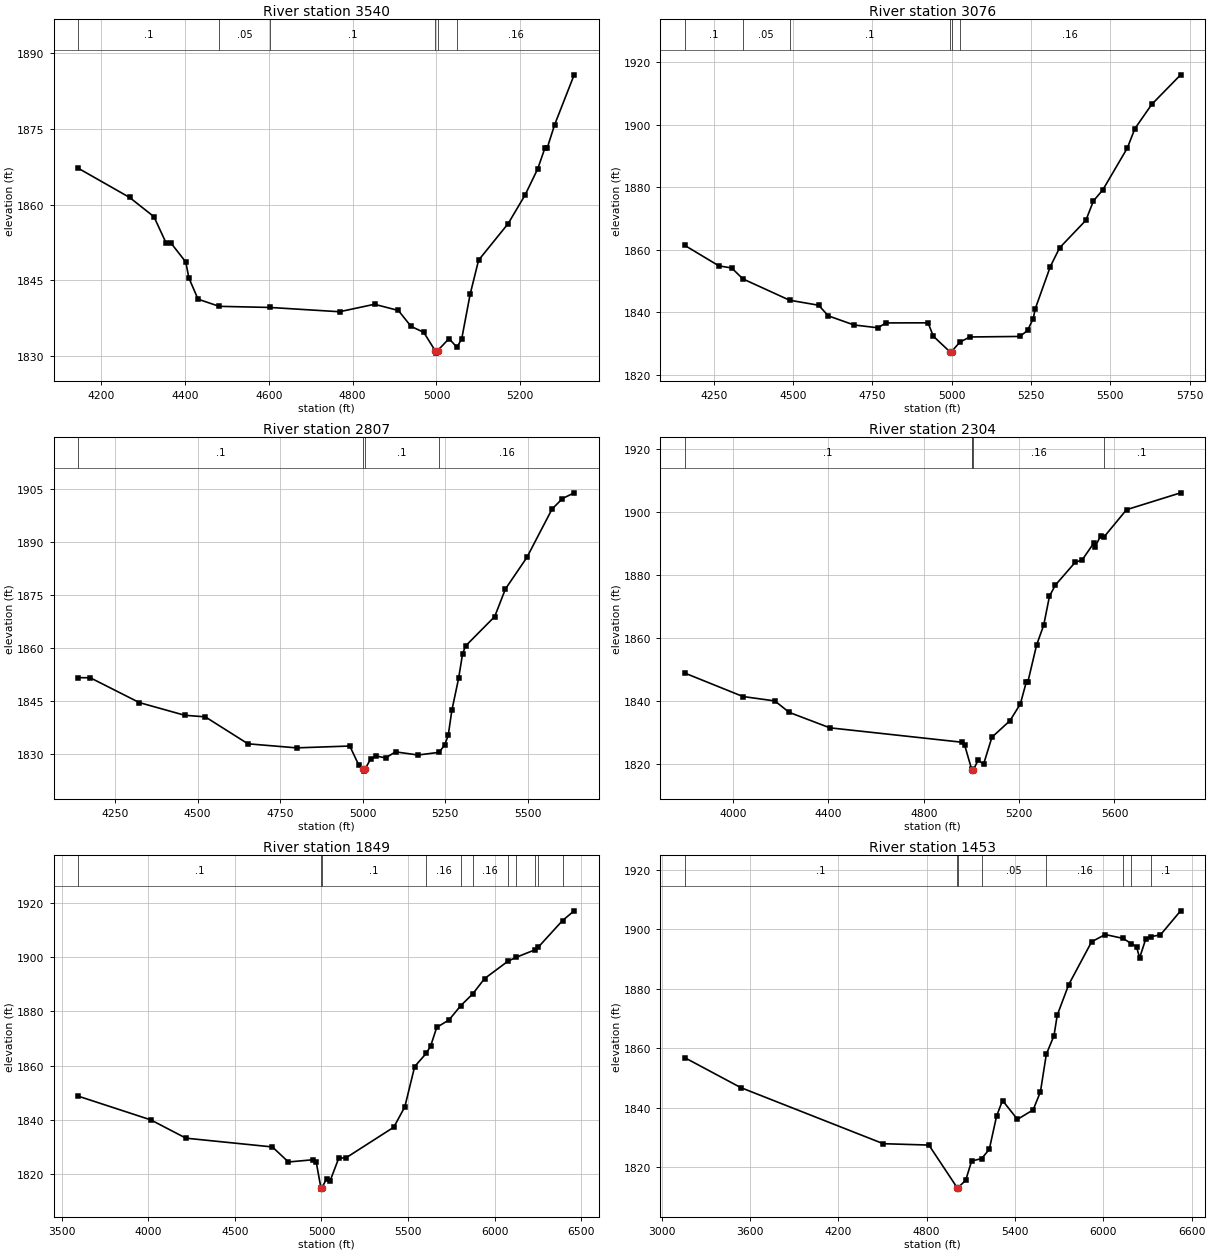
Type RM Length L Ch R = 1 ,3540    ,464,464,464
BEGIN DESCRIPTION:
UNT 1052 IN HEWA 7.0
END DESCRIPTION:
XS GIS Cut Line= 3
      2727942.64      10015795.9      2728239.51      10015108.4
      2728291.44     10014677.37
#Sta/Elev= 30
  4145.5 1867.18  4267.7 1861.41  4325.9 1857.59  4354.8  1852.4  4365.7 1852.46
  4401.8 1848.62  4409.3 1845.45  4431.1 1841.25  4481.6 1839.83  4602.8 1839.61
  4768.7 1838.76  4852.2 1840.24  4909.1 1839.01  4939.3 1835.86  4969.6 1834.68
  4996.8 1831.06  4999.5 1830.56  5002.8 1831.06    5030 1833.44  5048.8 1831.71
  5060.2 1833.38  5080.4 1842.25  5100.5 1848.98    5171 1856.22  5211.3 1861.87
  5241.5 1867.06  5259.2  1871.3  5264.3 1871.22  5281.8 1875.79  5328.5  1885.7
#Mann= 6 ,-1 , 0
  4145.5      .1       0  4481.6     .05       0  4602.8      .1       0
  4996.8     .07       0  5002.8      .1       0  5048.8     .16       0
Bank Sta=4996.8,5002.8
XS Rating Curve= 0 ,0
Exp/Cntr=0.3,0.1

Type RM Length L Ch R = 1 ,3076    ,269,269,269
BEGIN DESCRIPTION:
UNT 1052 IN HEWA 6.0
END DESCRIPTION:
XS GIS Cut Line= 3
      2728531.18     10016009.45      2728697.84     10015035.49
      2728479.11     10014504.28
#Sta/Elev= 30
    4159 1861.34  4266.3  1854.8  4306.8 1854.11  4342.1 1850.62  4489.1  1843.8
  4580.8 1842.19  4611.2 1838.79  4692.4 1835.87  4766.9 1834.98  4793.8 1836.53
  4925.7 1836.56  4942.1 1832.29  4993.7 1827.36  4996.5 1826.86  4999.7 1827.36
    5026 1830.39  5057.2 1832.03  5215.2  1832.2  5239.2 1834.13  5257.2 1837.93
  5263.1 1840.95    5311 1854.58  5340.4 1860.59    5423 1869.37    5447 1875.61
  5476.3  1879.1  5553.6  1892.5  5577.5 1898.73  5630.8 1906.51  5721.6 1915.94
#Mann= 6 ,-1 , 0
    4159      .1       0  4342.1     .05       0  4489.1      .1       0
  4993.7     .07       0  4999.7      .1       0    5026     .16       0
Bank Sta=4993.7,4999.7
XS Rating Curve= 0 ,0
Exp/Cntr=0.3,0.1

Type RM Length L Ch R = 1 ,2807    ,503,503,503
BEGIN DESCRIPTION:
UNT 1052 IN HEWA 5.0
END DESCRIPTION:
XS GIS Cut Line= 4
       2728854.1     10015879.23      2729010.34     10015160.49
      2728822.84     10015035.49      2728661.38     10014519.85
#Sta/Elev= 30
  4139.1 1851.53  4175.4 1851.48  4324.1 1844.46  4461.2 1840.88  4523.4 1840.44
  4652.6 1832.81    4800 1831.66    4961 1832.18  4988.5 1826.73  5000.5 1825.58
  5003.3 1825.08  5006.5 1825.58  5024.6 1828.56  5039.6 1829.39  5069.2 1828.82
  5099.6 1830.53  5167.4 1829.64  5231.7  1830.4  5248.5 1832.57    5259 1835.18
    5270 1842.28  5290.4 1851.29  5302.4 1858.23  5311.4 1860.47  5399.8 1868.81
  5432.2 1876.61  5497.1 1885.52  5573.4 1899.22  5604.9 1902.19  5640.3 1903.81
#Mann= 4 ,-1 , 0
  4139.1      .1       0  5000.5     .07       0  5006.5      .1       0
  5231.7     .16       0
Bank Sta=5000.5,5006.5
XS Rating Curve= 0 ,0
Exp/Cntr=0.3,0.1

Type RM Length L Ch R = 1 ,2304    ,455,455,455
BEGIN DESCRIPTION:
UNT 1052 IN HEWA 4.0
END DESCRIPTION:
XS GIS Cut Line= 4
      2728916.58     10015806.35      2729249.93     10014931.32
      2729010.34     10014493.82      2728412.38     10014254.64
#Sta/Elev= 30
  3798.2 1848.99    4042 1841.55  4175.5 1840.15  4236.6  1836.5  4406.5 1831.61
  4960.9 1827.03  4971.2 1826.26  5001.2 1818.42  5002.5 1818.36  5005.2 1817.86
  5008.5 1818.36  5028.3 1821.31  5051.1 1820.05  5086.1 1828.63  5161.9 1833.88
  5205.5 1839.23  5230.6 1846.27  5237.1 1846.27  5273.5 1857.93  5303.2 1864.19
  5327.4 1873.38  5351.6 1876.88  5435.1 1884.15  5464.7 1884.94  5513.2 1890.27
  5518.6 1889.07  5542.8 1892.67  5554.7 1892.08  5650.5 1900.87  5877.4 1906.23
#Mann= 5 ,-1 , 0
  3798.2      .1       0  5001.2     .16       0  5002.5     .07       0
  5008.5     .16       0  5554.7      .1       0
Bank Sta=5002.5,5008.5
XS Rating Curve= 0 ,0
Exp/Cntr=0.3,0.1

Type RM Length L Ch R = 1 ,1849    ,396,396,396
BEGIN DESCRIPTION:
UNT 1052 IN HEWA 3.0
END DESCRIPTION:
XS GIS Cut Line= 4
      2729058.06     10015801.15      2729551.14     10015030.28
      2729499.93     10014428.72      2728486.93     10013545.93
#Sta/Elev= 30
  3596.3 1848.73  4014.6 1840.01  4217.6 1833.28  4716.7 1830.05    4809 1824.52
  4949.5 1825.33  4969.6 1824.49  4996.7 1815.03  4999.4 1814.53  5002.7 1815.03
  5029.8  1818.4  5049.9 1817.58    5100 1825.96  5141.2 1826.03  5417.5 1837.32
  5481.1  1844.8  5538.1 1859.64  5604.8  1864.5  5630.2 1867.18  5665.3 1874.04
  5736.5 1876.81  5804.7 1882.08  5872.9 1886.35  5941.6    1892  6076.8 1898.41
    6125 1899.86  6234.4 1902.64  6251.1 1903.54    6392 1913.38  6458.8 1916.94
#Mann= 11 ,-1 , 0
  3596.3      .1       0  4996.7     .07       0  5002.7      .1       0
  5604.8     .16       0  5804.7      .1       0  5872.9     .16       0
  6076.8      .1       0    6125     .16       0  6234.4      .1       0
  6251.1     .16       0    6392      .1       0
Bank Sta=4996.7,5002.7
XS Rating Curve= 0 ,0
Exp/Cntr=0.3,0.1

Type RM Length L Ch R = 1 ,1453    ,610,610,610
BEGIN DESCRIPTION:
UNT 1052 IN HEWA 2.0
END DESCRIPTION:
XS GIS Cut Line= 4
      2728971.27      10016054.6      2729867.11     10015111.88
      2729893.16     10014231.67      2729120.59     10013328.89
#Sta/Elev= 30
  3156.3 1856.88  3536.9 1846.83    4505 1827.99  4815.1 1827.53  5006.9 1813.23
  5009.7 1812.73  5012.9 1813.23  5065.2 1815.71  5105.2 1822.16  5173.2 1822.99
  5225.3 1826.08  5275.3 1837.32  5315.3  1842.5    5417 1836.17  5523.5 1839.36
  5572.9 1845.41  5613.1 1858.07  5665.1 1864.27  5687.1 1871.16    5765 1881.41
  5920.9 1895.83  6013.1 1898.26  6134.3 1896.96  6190.6  1895.2    6226 1894.14
  6246.9 1890.41  6289.7 1896.92  6321.6 1897.53  6388.5 1898.14  6525.6 1906.22
#Mann= 8 ,-1 , 0
  3156.3      .1       0  5006.9     .07       0  5012.9      .1       0
  5173.2     .05       0  5613.1     .16       0  6134.3      .1       0
  6190.6     .16       0  6321.6      .1       0
Bank Sta=5006.9,5012.9
XS Rating Curve= 0 ,0
Exp/Cntr=0.3,0.1

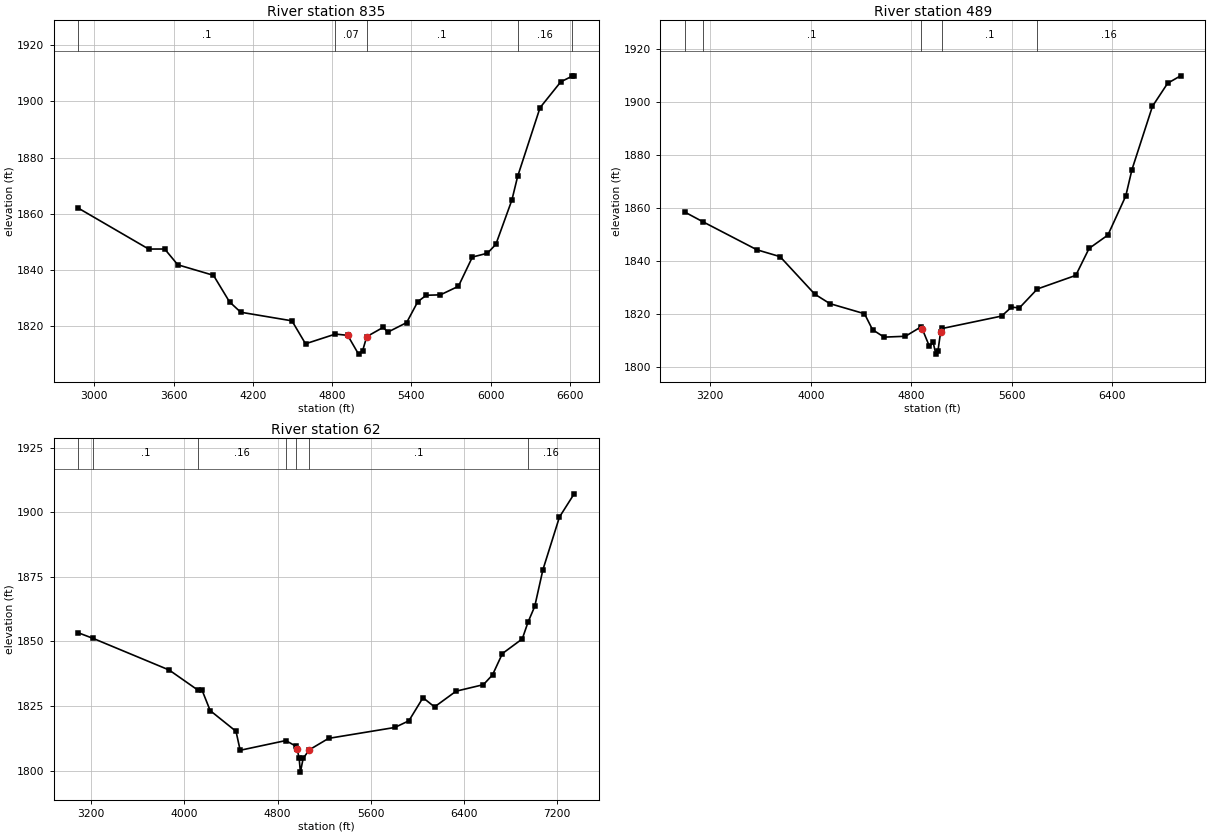
Type RM Length L Ch R = 1 ,835     ,645,645,645
BEGIN DESCRIPTION:
Mapping XS 835130dc
END DESCRIPTION:
XS GIS Cut Line= 4
      2729148.27     10016282.43      2730311.45     10015340.61
      2730485.06     10014633.14      2729530.17     10013439.53
#Sta/Elev= 30
    2879 1862.02  3411.3 1847.47  3532.7 1847.48  3631.9 1841.87  3902.1 1838.12
  4023.5 1828.68  4108.3 1824.99    4496 1821.93    4599 1813.76  4825.5 1817.22
  4918.2 1816.76  5000.3 1810.08  5031.4  1811.3  5062.3  1816.3  5186.7  1819.6
  5221.9  1817.9  5364.3 1821.29  5449.2 1828.77  5513.2 1831.02  5620.5 1831.18
  5756.5 1834.22  5862.2 1844.62  5975.8 1845.98  6039.9 1849.13  6161.5 1864.94
  6204.7 1873.29  6374.4 1897.76  6531.3 1906.96  6614.8 1908.91  6632.7  1909.1
#Mann= 5 ,-1 , 0
    2879      .1       0  4825.5     .07       0  5062.3      .1       0
  6204.7     .16       0  6614.8      .1       0
Bank Sta=4918.2,5062.3
XS Rating Curve= 0 ,0
Exp/Cntr=0.3,0.1

Type RM Length L Ch R = 1 ,489     ,427,427,427
BEGIN DESCRIPTION:
Mapping XS 2f5c1d13
END DESCRIPTION:
XS GIS Cut Line= 4
      2729358.15     10016344.64      2730629.01     10015125.87
      2730774.84     10014861.98      2729576.94     10013410.61
#Sta/Elev= 30
  2998.4 1858.34  3140.6 1854.73  3572.1 1844.12  3756.1 1841.54  4031.9 1827.41
    4152 1823.83  4427.8 1820.01  4491.7    1814  4583.5 1811.19  4753.3 1811.51
  4876.7 1815.03  4887.1 1814.31  4944.5 1807.69  4974.1 1809.17  4995.6 1804.78
  5011.9 1805.91  5033.7 1813.22  5047.3 1814.46  5518.6 1819.13  5596.8 1822.48
  5660.6 1822.23  5802.6 1829.34  6108.7 1834.47  6214.3 1844.63  6364.2 1849.68
  6506.2 1864.41  6555.7 1874.39  6718.5 1898.22  6839.7 1906.93  6942.6 1909.71
#Mann= 5 ,-1 , 0
  2998.4      .1       0  3140.6      .1       0  4876.7     .07       0
  5047.3      .1       0  5802.6     .16       0
Bank Sta=4887.1,5033.7
XS Rating Curve= 0 ,0
Exp/Cntr=0.3,0.1

Type RM Length L Ch R = 1 ,62      ,0,0,0
BEGIN DESCRIPTION:
UNT 1052 IN HEWA 1.0
END DESCRIPTION:
XS GIS Cut Line= 4
      2729497.05     10016452.27       2730892.9     10015441.84
      2731038.73     10015105.03      2729660.29     10013434.93
#Sta/Elev= 30
  3089.3 1853.35  3217.9 1851.15  3868.9 1838.94  4120.2 1831.01  4149.6 1831.32
  4220.8 1823.23  4442.7  1815.2  4478.3 1807.86  4869.8 1811.62  4961.2 1809.33
  4966.7 1808.51  4984.7 1804.73  4995.4  1799.4  5019.1 1804.74    5072 1808.05
  5237.2 1812.47  5805.3 1816.69  5926.4 1819.27  6047.6 1828.22  6146.6 1824.65
  6331.6 1830.74  6566.2 1833.27  6644.3 1837.05    6729 1845.31  6899.7 1850.99
  6949.2 1857.49  7006.5 1863.56  7076.8 1877.77  7218.9 1898.18    7345 1907.16
#Mann= 7 ,-1 , 0
  3089.3     .05       0  3217.9      .1       0  4120.2     .16       0
  4869.8      .1       0  4961.2     .07       0    5072      .1       0
  6949.2     .16       0
Bank Sta=4966.7,5072
XS Rating Curve= 0 ,0
Exp/Cntr=0.3,0.1

Chan Stop Cuts=-1
Use User Specified Reach Order=0
Composite Channel Slope=5