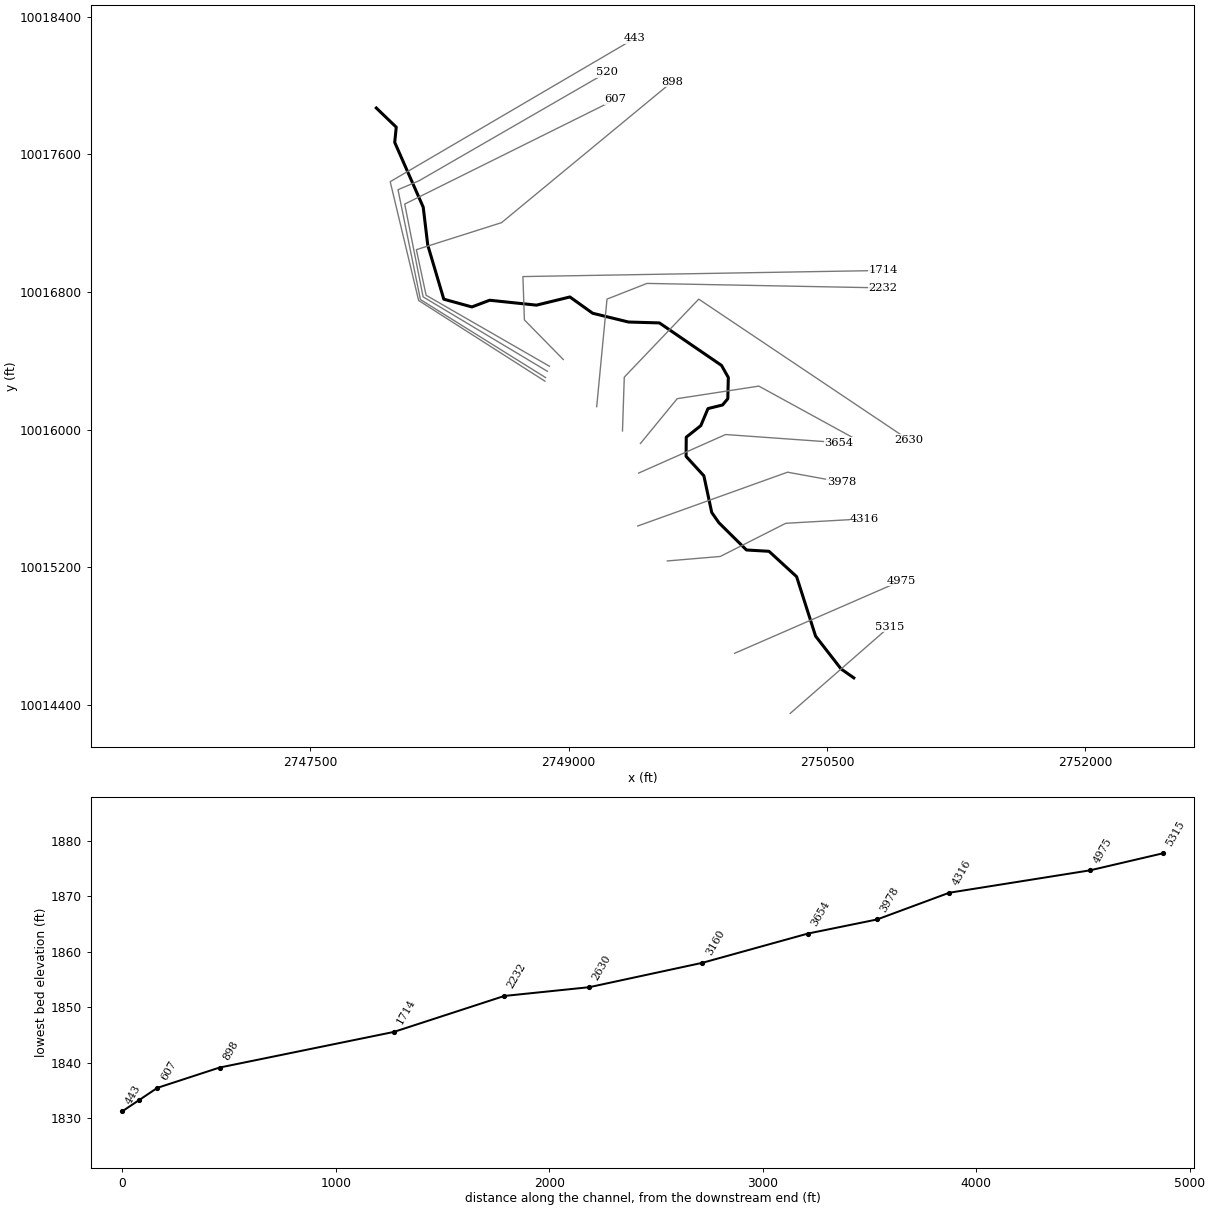
--- UNT 1054 IN HEWA.prj (project) ---

Proj Title=UNT 1054 IN HEWA Base Level Engineering
Current Plan=p01
Default Exp/Contr=0.3,0.1
English Units
Geom File=g01
Flow File=f01
Plan File=p01
Y Axis Title=Elevation
X Axis Title(PF)=Main Channel Distance
X Axis Title(XS)=Station
BEGIN DESCRIPTION:
UNT 1054 IN HEWA
END DESCRIPTION:
DSS Export Rating Curves= 0
DSS Export Rating Curve Sorted= 0
DSS Export Volume Flow Curves= 0
DXF OffsetX= 0
DXF OffsetY= 0
DXF ScaleX= 1
DXF ScaleY= 10

--- UNT 1054 IN HEWA.p01 (plan) ---

Plan Title=Multiple Run
Short Identifier=Multiple
Geom File=g01
Flow File=f01
Subcritical Flow
K Sum by GR= 0
Std Step Tol= 0.01
Critical Tol= 0.01
Num of Std Step Trials= 20
Max Error Tol= 0.3
Flow Tol Ratio= 0.001
Split Flow NTrial= 30
Split Flow Tol= 0.02
Split Flow Ratio= 0.02
Log Output Level= 0
Friction Slope Method= 1
Unsteady Friction Slope Method= 2
Unsteady Bridges Friction Slope Method= 1
Parabolic Critical Depth
Global Vel Dist=  1 , 1 , 1
Global Log Level= 0
CheckData=True
Encroach Param= -1, 0, 0, 0
BEGIN DESCRIPTION:
Multiple Run
END DESCRIPTION:

--- UNT 1054 IN HEWA.f01 (steady flow) ---

Flow Title=Multiple
Number of Profiles=7
Profile Names=10-year,25-year,50-year,1pct_min,100-year,1pct_plu,500-year
River Rch & RM= UNT 1054 IN HEWA,Reach-1,5315
     685     976    1225    1126    1523    2060    2362
River Rch & RM= UNT 1054 IN HEWA,Reach-1,520
    1050    1536    1960    1830    2475    3347    3963
Boundary for River Rch & Prof#=UNT 1054 IN HEWA,Reach-1,1
Up Type=0
Dn Type=3
Dn Slope=0.005
Boundary for River Rch & Prof#=UNT 1054 IN HEWA,Reach-1,2
Up Type=0
Dn Type=3
Dn Slope=0.005
Boundary for River Rch & Prof#=UNT 1054 IN HEWA,Reach-1,3
Up Type=0
Dn Type=3
Dn Slope=0.005
Boundary for River Rch & Prof#=UNT 1054 IN HEWA,Reach-1,4
Up Type=0
Dn Type=3
Dn Slope=0.005
Boundary for River Rch & Prof#=UNT 1054 IN HEWA,Reach-1,5
Up Type=0
Dn Type=3
Dn Slope=0.005
Boundary for River Rch & Prof#=UNT 1054 IN HEWA,Reach-1,6
Up Type=0
Dn Type=3
Dn Slope=0.005
Boundary for River Rch & Prof#=UNT 1054 IN HEWA,Reach-1,7
Up Type=0
Dn Type=3
Dn Slope=0.005

--- UNT 1054 IN HEWA.g01 (geometry) ---

Geom Title=Existing Conditions

River Reach=UNT 1054 IN HEWA,Reach-1
Reach XY= 30
      2750655.86     10014558.63      2750582.02     10014610.36
      2750433.83     10014801.22      2750323.72     10015146.59
      2750163.50     10015293.83      2750032.58     10015301.55
      2749872.61     10015459.71      2749830.93     10015519.30
      2749785.29     10015732.39      2749682.02     10015845.27
      2749682.93     10015956.62      2749767.69     10016024.08
      2749809.15     10016122.91      2749893.71     10016143.79
      2749924.29     10016180.50      2749927.20     10016303.56
      2749887.79     10016373.61      2749527.13     10016620.53
      2749347.64     10016625.71      2749139.63     10016676.68
      2749007.49     10016771.23      2748813.46     10016723.74
      2748541.46     10016752.25      2748438.48     10016713.35
      2748275.28     10016758.40      2748182.23     10017072.43
      2748155.87     10017292.97      2747990.39     10017669.24
      2747999.24     10017757.69      2747883.46     10017868.99

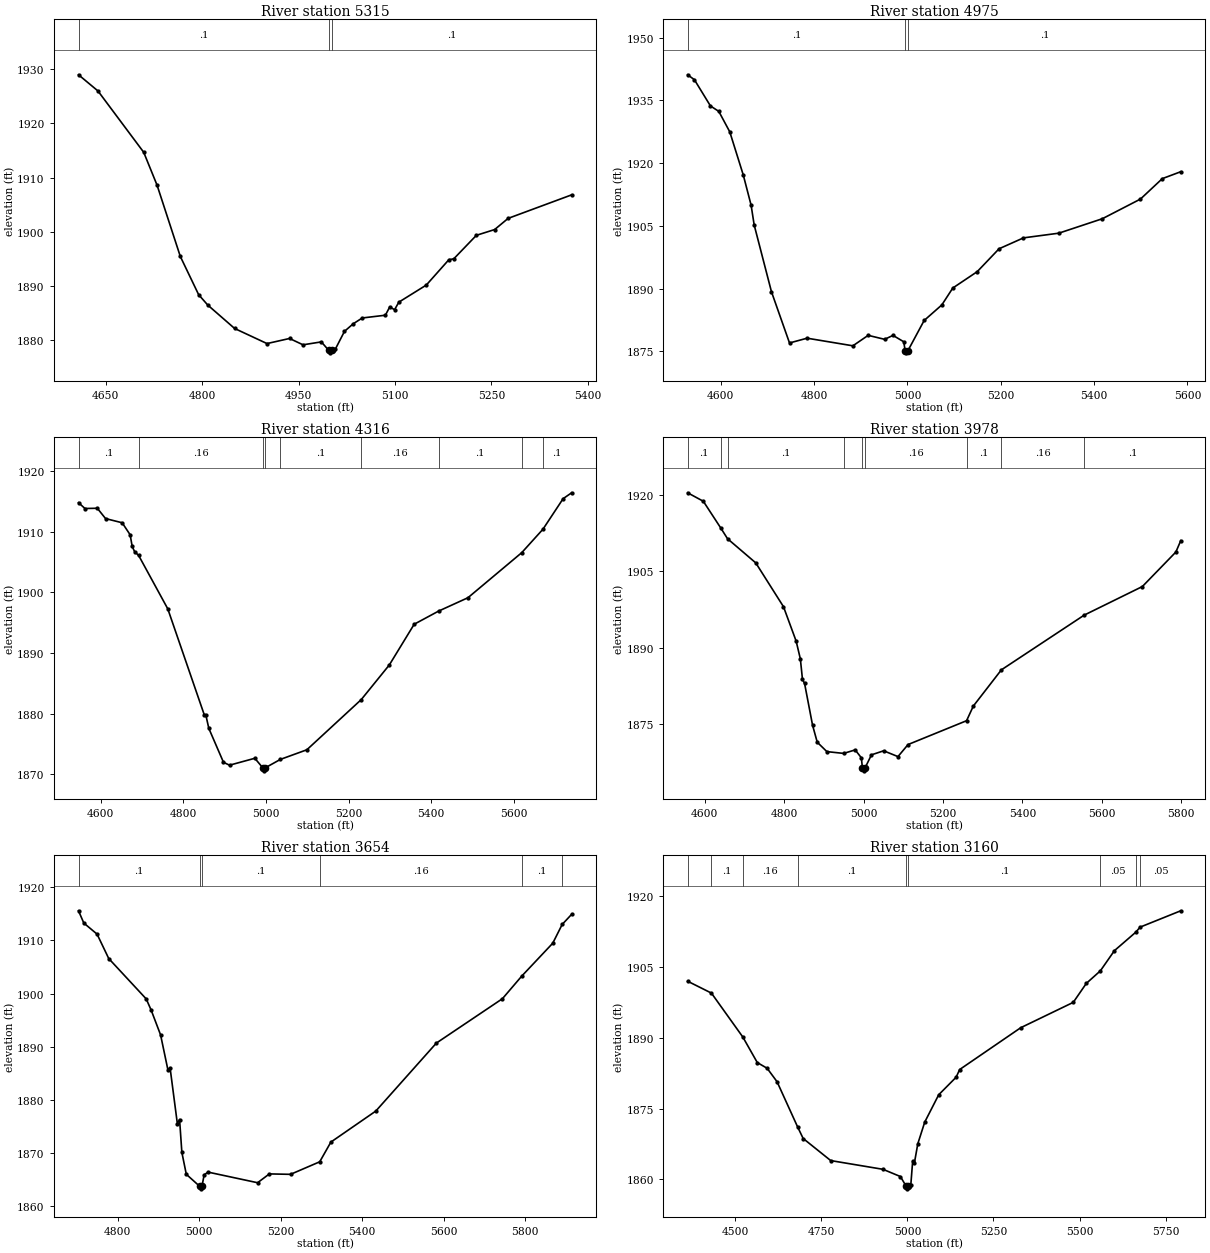
Type RM Length L Ch R = 1,5315,340,340,340
BEGIN DESCRIPTION:
UNT 1054 IN HEWA 10.0
END DESCRIPTION:
XS GIS Cut Line= 2
      2750286.74     10014352.40      2750864.13     10014856.98
#Sta/Elev= 30
  4607.9 1928.97  4638.1 1925.99  4709.3 1914.67  4730.1 1908.59  4766.2 1895.46
  4794.7 1888.41  4808.9 1886.49  4850.7 1882.17  4901.0 1879.39  4936.1 1880.33
  4957.0 1879.16  4985.5 1879.70  4996.7 1878.18  4999.5 1877.68  5002.7 1878.18
  5007.3 1878.37  5021.5 1881.65  5035.2 1883.05  5049.1 1884.11  5085.1 1884.62
  5091.8 1886.14  5099.4 1885.64  5106.0 1887.03  5148.7 1890.18  5183.8 1894.86
  5191.4 1895.02  5226.6 1899.36  5255.0 1900.42  5275.9 1902.48  5374.7 1906.82
#Mann=3,-1,0
  4607.9     0.1       0  4996.7    0.07       0  5002.7     0.1       0
Bank Sta=4996.7,5002.7
Exp/Cntr=0.3,0.1

Type RM Length L Ch R = 1,4975,659,659,659
BEGIN DESCRIPTION:
UNT 1054 IN HEWA 9.0
END DESCRIPTION:
XS GIS Cut Line= 2
      2749963.79     10014701.35      2750932.61     10015123.25
#Sta/Elev= 30
  4529.0 1941.09  4543.5 1939.91  4577.9 1933.64  4595.8 1932.34  4619.3 1927.45
  4648.2 1917.15  4665.0 1909.93  4671.6 1905.19  4708.6 1889.24  4747.3 1876.99
  4785.0 1878.13  4883.1 1876.31  4915.9 1878.81  4951.1 1877.86  4969.1 1878.80
  4992.2 1877.27  4995.0 1875.13  4997.7 1874.63  5001.0 1875.13  5035.8 1882.36
  5073.7 1886.08  5097.2 1890.12  5149.5 1894.03  5196.3 1899.50  5248.7 1902.11
  5324.4 1903.23  5417.6 1906.68  5499.3 1911.38  5546.2 1916.27  5585.7 1917.92
#Mann=3,-1,0
  4529.0     0.1       0  4995.0    0.07       0  5001.0     0.1       0
Bank Sta=4995,5001
Exp/Cntr=0.3,0.1

Type RM Length L Ch R = 1,4316,338,338,338
BEGIN DESCRIPTION:
UNT 1054 IN HEWA 8.0
END DESCRIPTION:
XS GIS Cut Line= 4
      2749573.16     10015237.81      2749880.48     10015263.86
      2750260.69     10015456.57      2750719.07     10015482.61
#Sta/Elev= 30
  4546.0 1914.78  4561.6 1913.82  4591.5 1913.86  4611.5 1912.16  4651.7 1911.47
  4671.0 1909.49  4676.0 1907.56  4681.8 1906.72  4691.6 1906.08  4762.1 1897.29
  4850.9 1879.74  4854.4 1879.74  4861.5 1877.59  4897.0 1872.00  4911.6 1871.53
  4972.8 1872.67  4992.1 1871.10  4994.9 1870.60  4998.1 1871.10  5034.9 1872.49
  5098.8 1874.07  5230.5 1882.34  5298.5 1888.05  5358.6 1894.75  5417.8 1896.92
  5488.8 1899.12  5619.1 1906.55  5670.4 1910.41  5719.2 1915.44  5739.8 1916.41
#Mann=9,-1,0
  4546.0     0.1       0  4691.6    0.16       0  4992.1    0.07       0
  4998.1    0.16       0  5034.9     0.1       0  5230.5    0.16       0
  5417.8     0.1       0  5619.1    0.16       0  5670.4     0.1       0
Bank Sta=4992.1,4998.1
Exp/Cntr=0.3,0.1

Type RM Length L Ch R = 1,3978,324,324,324
BEGIN DESCRIPTION:
UNT 1054 IN HEWA 7.0
END DESCRIPTION:
XS GIS Cut Line= 3
      2749401.30     10015440.93      2750271.11     10015753.44
      2750583.55     10015696.16
#Sta/Elev= 30
  4556.9 1920.48  4596.4 1918.81  4640.1 1913.58  4657.4 1911.44  4728.5 1906.69
  4798.3 1898.07  4830.2 1891.30  4840.8 1887.80  4846.1 1883.78  4851.4 1882.98
  4871.5 1874.77  4883.3 1871.42  4907.6 1869.57  4949.8 1869.22  4978.9 1869.91
  4994.4 1868.35  4997.2 1866.29  4999.9 1865.79  5003.2 1866.29  5019.9 1868.94
  5050.6 1869.73  5086.6 1868.59  5112.0 1870.96  5259.4 1875.65  5276.4 1878.53
  5347.0 1885.65  5555.7 1896.42  5702.1 1902.04  5786.5 1908.83  5798.8 1911.06
#Mann=9,-1,0
  4556.9     0.1       0  4640.1    0.05       0  4657.4     0.1       0
  4949.8    0.16       0  4997.2    0.07       0  5003.2    0.16       0
  5259.4     0.1       0  5347.0    0.16       0  5555.7     0.1       0
Bank Sta=4997.2,5003.2
Exp/Cntr=0.3,0.1

Type RM Length L Ch R = 1,3654,494,494,494
BEGIN DESCRIPTION:
UNT 1054 IN HEWA 6.0
END DESCRIPTION:
XS GIS Cut Line= 3
      2749406.55     10015748.24      2749911.73     10015972.19
      2750567.96     10015925.32
#Sta/Elev= 30
  4703.6 1915.59  4716.6 1913.28  4749.1 1911.20  4777.8 1906.60  4869.8 1899.00
  4881.9 1896.90  4905.1 1892.22  4922.9 1885.70  4928.4 1886.02  4946.2 1875.53
  4951.7 1876.30  4957.3 1870.11  4968.2 1865.99  5000.7 1863.75  5003.5 1863.25
  5006.7 1863.75  5012.0 1865.88  5021.5 1866.40  5143.2 1864.40  5172.1 1866.06
  5224.1 1865.98  5295.7 1868.34  5323.1 1872.05  5433.4 1877.89  5582.1 1890.69
  5744.2 1899.04  5791.7 1903.30  5867.8 1909.49  5890.9 1913.02  5914.1 1914.92
#Mann=6,-1,0
  4703.6     0.1       0  5000.7    0.07       0  5006.7     0.1       0
  5295.7    0.16       0  5791.7     0.1       0  5890.9    0.05       0
Bank Sta=5000.7,5006.7
Exp/Cntr=0.3,0.1

Type RM Length L Ch R = 1,3160,530,530,530
BEGIN DESCRIPTION:
UNT 1054 IN HEWA 5.0
END DESCRIPTION:
XS GIS Cut Line= 4
      2749416.97     10015920.15      2749630.48     10016180.52
      2750104.44     10016253.44      2750644.75     10015957.31
#Sta/Elev= 30
  4361.6 1902.00  4430.7 1899.48  4522.0 1890.16  4563.9 1884.76  4592.6 1883.54
  4621.3 1880.70  4681.2 1871.09  4697.2 1868.66  4777.2 1863.98  4929.0 1862.13
  4979.6 1860.60  4996.8 1858.49  4999.6 1857.99  5002.8 1858.49  5009.9 1858.85
  5015.2 1863.82  5020.2 1863.44  5030.2 1867.55  5050.4 1872.15  5090.9 1877.93
  5141.5 1881.65  5151.8 1883.28  5329.1 1892.14  5481.8 1897.52  5519.7 1901.54
  5560.5 1904.20  5601.2 1908.47  5663.7 1912.41  5675.8 1913.46  5794.0 1916.93
#Mann=9,-1,0
  4361.6    0.16       0  4430.7     0.1       0  4522.0    0.16       0
  4681.2     0.1       0  4996.8    0.07       0  5002.8     0.1       0
  5560.5    0.05       0  5663.7     0.1       0  5675.8    0.05       0
Bank Sta=4996.8,5002.8
Exp/Cntr=0.3,0.1

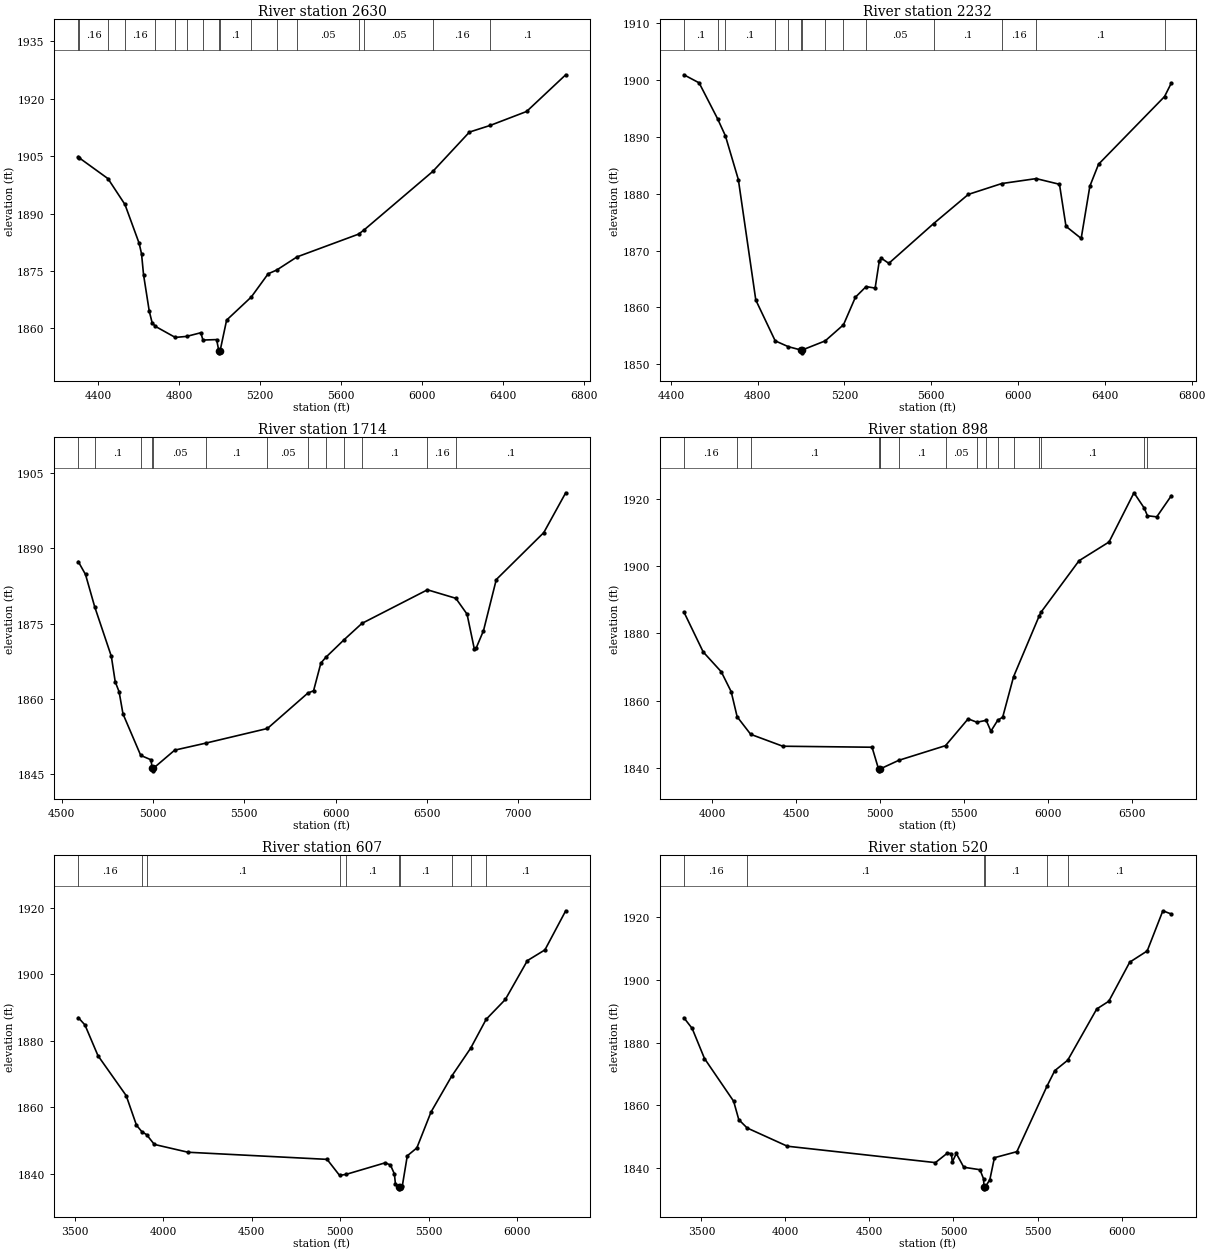
Type RM Length L Ch R = 1,2630,398,398,398
BEGIN DESCRIPTION:
UNT 1054 IN HEWA 4.0
END DESCRIPTION:
XS GIS Cut Line= 4
      2749312.78     10015993.07      2749323.19     10016305.52
      2749755.48     10016758.65      2750973.87     10015941.18
#Sta/Elev= 30
  4301.8 1904.87  4308.0 1904.49  4448.6 1899.11  4532.4 1892.36  4602.6 1882.19
  4614.4 1879.43  4624.1 1874.04  4652.4 1864.48  4666.5 1861.48  4682.5 1860.52
  4780.7 1857.63  4836.5 1857.89  4906.8 1858.85  4917.4 1856.94  4984.8 1857.06
  4995.9 1854.10  4998.7 1853.60  5001.9 1854.10  5034.2 1862.15  5156.0 1868.19
  5239.2 1874.25  5281.4 1875.23  5381.6 1878.66  5685.5 1884.61  5713.4 1885.74
  6052.6 1901.03  6232.7 1911.27  6336.2 1913.03  6514.8 1916.65  6707.9 1926.24
#Mann=17,-1,0
  4301.8     0.1       0  4308.0    0.16       0  4448.6     0.1       0
  4532.4    0.16       0  4682.5     0.1       0  4780.7    0.05       0
  4836.5    0.16       0  4917.4     0.1       0  4995.9    0.07       0
  5001.9     0.1       0  5156.0    0.05       0  5281.4     0.1       0
  5381.6    0.05       0  5685.5     0.1       0  5713.4    0.05       0
  6052.6    0.16       0  6336.2     0.1       0
Bank Sta=4995.9,5001.9
Exp/Cntr=0.3,0.1

Type RM Length L Ch R = 1,2232,518,518,518
BEGIN DESCRIPTION:
Mapping XS 877caa68
END DESCRIPTION:
XS GIS Cut Line= 4
      2749163.05     10016133.86      2749222.95     10016758.84
      2749454.72     10016849.99      2750823.98     10016823.96
#Sta/Elev= 30
  4460.1 1900.95  4530.3 1899.53  4615.4 1893.21  4651.3 1890.22  4711.1 1882.51
  4791.5 1861.31  4880.9 1854.13  4941.6 1853.10  4999.4 1852.52  5002.2 1852.02
  5005.4 1852.52  5111.2 1854.12  5195.6 1856.96  5250.6 1861.81  5299.8 1863.68
  5341.4 1863.41  5360.7 1868.21  5370.7 1868.65  5404.5 1867.77  5611.0 1874.77
  5770.8 1879.90  5924.9 1881.81  6083.5 1882.68  6190.9 1881.68  6220.9 1874.28
  6290.9 1872.15  6330.9 1881.35  6370.9 1885.21  6675.1 1897.12  6706.5 1899.51
#Mann=14,-1,0
  4460.1     0.1       0  4615.4    0.16       0  4651.3     0.1       0
  4880.9    0.05       0  4941.6     0.1       0  4999.4    0.07       0
  5005.4     0.1       0  5111.2    0.05       0  5195.6     0.1       0
  5299.8    0.05       0  5611.0     0.1       0  5924.9    0.16       0
  6083.5     0.1       0  6675.1    0.16       0
Bank Sta=4999.4,5005.4
Exp/Cntr=0.3,0.1

Type RM Length L Ch R = 1,1714,816,816,816
BEGIN DESCRIPTION:
UNT 1054 IN HEWA 3.0
END DESCRIPTION:
XS GIS Cut Line= 4
      2748969.02     10016407.96      2748743.33     10016637.99
      2748734.65     10016889.73      2750828.40     10016925.32
#Sta/Elev= 30
  4591.5 1887.39  4631.3 1884.81  4681.5 1878.36  4772.7 1868.44  4794.0 1863.34
  4815.2 1861.36  4836.5 1856.92  4933.5 1848.63  4989.5 1847.75  4996.6 1846.04
  4999.3 1845.54  5002.6 1846.04  5119.6 1849.68  5290.8 1851.09  5627.1 1854.01
  5848.4 1861.09  5879.6 1861.55  5919.6 1867.09  5947.0 1868.25  6045.6 1871.72
  6144.2 1875.02  6502.9 1881.74  6658.3 1880.04  6719.7 1876.87  6759.7 1869.87
  6769.7 1870.10  6809.7 1873.57  6879.7 1883.79  7139.7 1893.18  7259.7 1901.14
#Mann=13,-1,0
  4591.5    0.16       0  4681.5     0.1       0  4933.5    0.05       0
  4996.6   0.035       0  5002.6    0.05       0  5290.8     0.1       0
  5627.1    0.05       0  5848.4     0.1       0  5947.0    0.05       0
  6045.6    0.16       0  6144.2     0.1       0  6502.9    0.16       0
  6658.3     0.1       0
Bank Sta=4996.6,5002.6
Exp/Cntr=0.3,0.1

Type RM Length L Ch R = 1,898,291,291,291
BEGIN DESCRIPTION:
UNT 1054 IN HEWA 2.0
END DESCRIPTION:
XS GIS Cut Line= 5
      2748888.73     10016368.89      2748172.58     10016781.22
      2748116.16     10017045.98      2748610.53     10017202.85
      2749602.71     10018022.54
#Sta/Elev= 30
  3831.8 1886.38  3946.7 1874.49  4054.5 1868.58  4113.4 1862.68  4149.0 1855.20
  4229.6 1849.99  4420.6 1846.45  4952.3 1846.15  4991.2 1839.63  4994.0 1839.13
  4997.2 1839.63  4997.6 1839.63  5111.5 1842.26  5389.6 1846.62  5524.4 1854.59
  5576.6 1853.58  5631.9 1854.15  5659.9 1850.92  5700.1 1854.13  5730.2 1855.11
  5794.9 1867.12  5947.2 1885.15  5957.9 1886.27  6184.8 1901.61  6363.4 1907.18
  6511.8 1921.81  6573.2 1917.24  6592.0 1914.98  6647.4 1914.65  6734.5 1920.95
#Mann=16,-1,0
  3831.8    0.16       0  4149.0    0.05       0  4229.6     0.1       0
  4991.2    0.07       0  4997.2     0.1       0  4997.6    0.16       0
  5111.5     0.1       0  5389.6    0.05       0  5576.6     0.1       0
  5631.9    0.16       0  5700.1     0.1       0  5794.9    0.05       0
  5947.2    0.16       0  5957.9     0.1       0  6573.2    0.05       0
  6592.0     0.1       0
Bank Sta=4991.2,4997.2
Exp/Cntr=0.3,0.1

Type RM Length L Ch R = 1,607,87,87,87
BEGIN DESCRIPTION:
Mapping XS e970a8b1
END DESCRIPTION:
XS GIS Cut Line= 4
      2748876.55     10016339.60      2748155.24     10016771.86
      2748048.47     10017310.93      2749272.65     10017919.12
#Sta/Elev= 30
  3518.4 1886.97  3556.3 1884.76  3630.2 1875.50  3789.6 1863.51  3847.9 1854.60
  3879.3 1852.60  3904.7 1851.79  3949.0 1848.83  4139.6 1846.48  4926.0 1844.34
  4996.6 1839.52  5033.0 1839.82  5255.0 1843.31  5284.5 1842.63  5306.9 1839.94
  5312.5 1836.97  5331.9 1835.98  5334.6 1835.48  5337.9 1835.98  5351.7 1836.40
  5379.7 1845.41  5433.7 1847.78  5514.1 1858.59  5630.7 1869.34  5738.5 1877.79
  5825.7 1886.44  5934.2 1892.40  6059.0 1904.09  6158.2 1907.31  6275.8 1919.07
#Mann=10,-1,0
  3518.4    0.16       0  3879.3    0.05       0  3904.7     0.1       0
  4996.6    0.16       0  5033.0     0.1       0  5331.9    0.07       0
  5337.9     0.1       0  5630.7    0.05       0  5738.5    0.16       0
  5825.7     0.1       0
Bank Sta=5331.9,5337.9
Exp/Cntr=0.3,0.1

Type RM Length L Ch R = 1,520,77,77,77
BEGIN DESCRIPTION:
Mapping XS 645fed2f
END DESCRIPTION:
XS GIS Cut Line= 5
      2748866.21     10016303.09      2748139.61     10016756.24
      2748009.40     10017394.26      2748131.80     10017446.34
      2749222.97     10018076.57
#Sta/Elev= 30
  3395.9 1887.91  3445.3 1884.49  3518.5 1874.89  3691.9 1861.24  3722.6 1855.35
  3772.3 1852.69  4011.6 1846.86  4892.6 1841.62  4964.0 1844.67  4987.7 1844.48
  4993.1 1841.80  5016.7 1844.55  5061.3 1840.14  5157.5 1839.35  5179.0 1836.44
  5181.8 1833.74  5184.5 1833.24  5187.8 1833.74  5216.3 1836.15  5243.7 1843.19
  5377.2 1845.12  5556.3 1866.04  5602.6 1871.00  5679.9 1874.35  5852.5 1890.72
  5924.2 1893.19  6048.8 1905.68  6152.7 1909.26  6245.9 1922.10  6296.5 1921.05
#Mann=6,-1,0
  3395.9    0.16       0  3772.3     0.1       0  5181.8    0.07       0
  5187.8     0.1       0  5556.3    0.05       0  5679.9     0.1       0
Bank Sta=5181.8,5187.8
Exp/Cntr=0.3,0.1

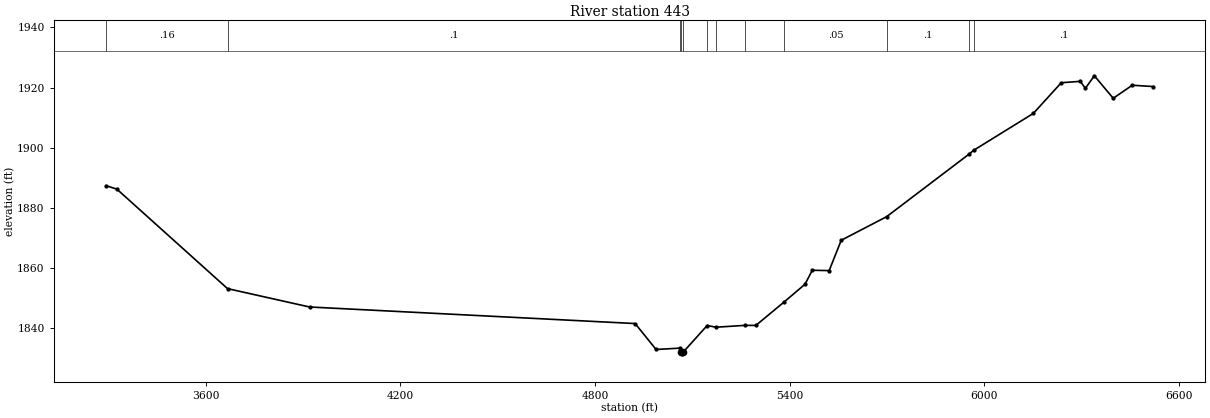
Type RM Length L Ch R = 1,443,0,0,0
BEGIN DESCRIPTION:
UNT 1054 IN HEWA 1.0
END DESCRIPTION:
XS GIS Cut Line= 4
      2748862.71     10016282.07      2748129.18     10016750.84
      2747964.25     10017440.94      2749384.60     10018273.63
#Sta/Elev= 30
  3293.5 1887.29  3326.3 1886.15  3667.4 1853.00  3920.1 1846.88  4923.8 1841.36
  4988.2 1832.72  5062.7 1833.18  5065.3 1831.77  5068.1 1831.27  5071.3 1831.77
  5145.7 1840.71  5173.1 1840.14  5262.8 1840.76  5295.8 1840.74  5383.1 1848.57
  5447.4 1854.47  5469.6 1859.12  5521.7 1859.00  5558.9 1869.11  5698.7 1876.96
  5953.5 1897.86  5967.0 1899.08  6151.1 1911.38  6237.0 1921.59  6295.6 1922.06
  6311.3 1919.73  6339.0 1923.91  6397.2 1916.41  6455.9 1920.76  6520.0 1920.33
#Mann=12,-1,0
  3293.5    0.16       0  3667.4     0.1       0  5062.7    0.16       0
  5065.3    0.07       0  5071.3    0.16       0  5145.7     0.1       0
  5173.1    0.05       0  5262.8     0.1       0  5383.1    0.05       0
  5698.7     0.1       0  5953.5    0.16       0  5967.0     0.1       0
Bank Sta=5065.3,5071.3
Exp/Cntr=0.3,0.1

Chan Stop Cuts=-1