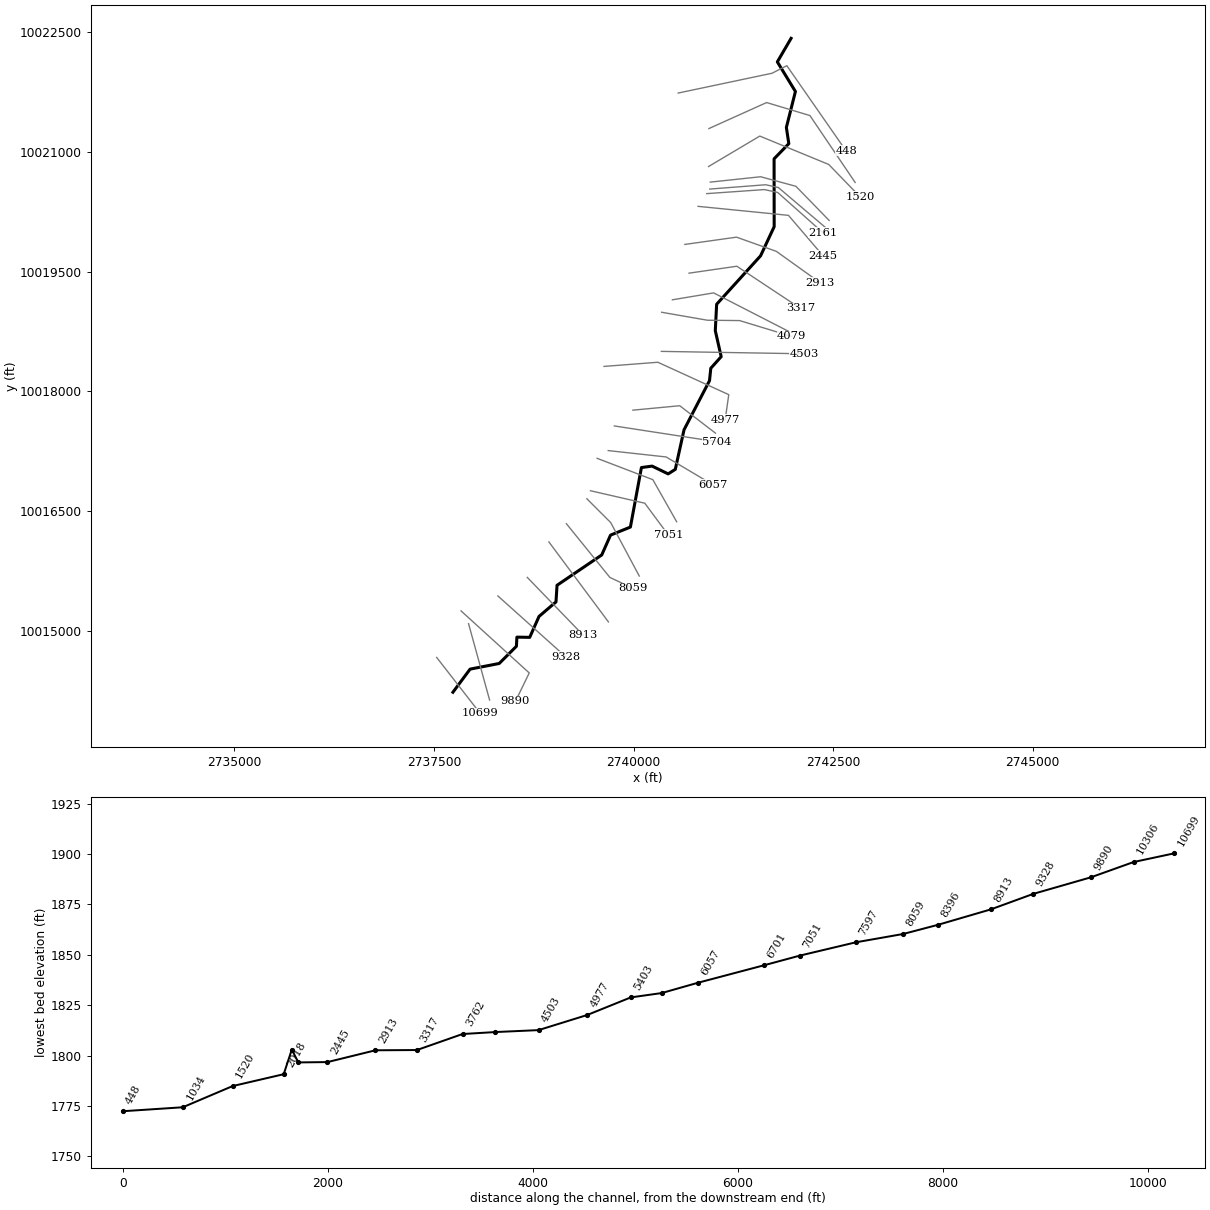
--- UNT 1055 IN HEWA.prj (project) ---

Proj Title=UNT 1055 IN HEWA Base Level Engineering
Current Plan=p01
Default Exp/Contr=0.3,0.1
English Units
Geom File=g01
Flow File=f01
Plan File=p01
Y Axis Title=Elevation
X Axis Title(PF)=Main Channel Distance
X Axis Title(XS)=Station
BEGIN DESCRIPTION:
UNT 1055 IN HEWA
END DESCRIPTION:
DSS Export Rating Curves= 0
DSS Export Rating Curve Sorted= 0
DSS Export Volume Flow Curves= 0
DXF OffsetX= 0
DXF OffsetY= 0
DXF ScaleX= 1
DXF ScaleY= 10

--- UNT 1055 IN HEWA.p01 (plan) ---

Plan Title=Multiple Run
Short Identifier=Multiple
Geom File=g01
Flow File=f01
Subcritical Flow
K Sum by GR= 0
Std Step Tol= 0.01
Critical Tol= 0.01
Num of Std Step Trials= 20
Max Error Tol= 0.3
Flow Tol Ratio= 0.001
Split Flow NTrial= 30
Split Flow Tol= 0.02
Split Flow Ratio= 0.02
Log Output Level= 0
Friction Slope Method= 1
Unsteady Friction Slope Method= 2
Unsteady Bridges Friction Slope Method= 1
Parabolic Critical Depth
Global Vel Dist=  1 , 1 , 1
Global Log Level= 0
CheckData=True
Encroach Param= -1, 0, 0, 0
BEGIN DESCRIPTION:
Multiple Run
END DESCRIPTION:

--- UNT 1055 IN HEWA.f01 (steady flow) ---

Flow Title=Multiple
Number of Profiles=7
Profile Names=10-year,25-year,50-year,1pct_min,100-year,1pct_plu,500-year
River Rch & RM= UNT 1055 IN HEWA,Reach-1,10699
     868    1259    1597    1483    2006    2712    3177
River Rch & RM= UNT 1055 IN HEWA,Reach-1,4503
    1456    2166    2796    2637    3566    4823    5829
Boundary for River Rch & Prof#=UNT 1055 IN HEWA,Reach-1,1
Up Type=0
Dn Type=3
Dn Slope=0.005
Boundary for River Rch & Prof#=UNT 1055 IN HEWA,Reach-1,2
Up Type=0
Dn Type=3
Dn Slope=0.005
Boundary for River Rch & Prof#=UNT 1055 IN HEWA,Reach-1,3
Up Type=0
Dn Type=3
Dn Slope=0.005
Boundary for River Rch & Prof#=UNT 1055 IN HEWA,Reach-1,4
Up Type=0
Dn Type=3
Dn Slope=0.005
Boundary for River Rch & Prof#=UNT 1055 IN HEWA,Reach-1,5
Up Type=0
Dn Type=3
Dn Slope=0.005
Boundary for River Rch & Prof#=UNT 1055 IN HEWA,Reach-1,6
Up Type=0
Dn Type=3
Dn Slope=0.005
Boundary for River Rch & Prof#=UNT 1055 IN HEWA,Reach-1,7
Up Type=0
Dn Type=3
Dn Slope=0.005

--- UNT 1055 IN HEWA.g01 (geometry) ---

Geom Title=Existing Conditions
Program Version=4.10

River Reach=UNT 1055 IN HEWA,Reach-1
Reach XY= 30
      2737737.32     10014226.17      2737952.09     10014515.74
      2738317.26     10014586.65      2738532.77     10014802.33
      2738538.66      10014916.9      2738699.29     10014914.24
      2738815.85      10015176.2      2739028.56     10015358.74
      2739041.73     10015567.12      2739601.74     10015947.24
      2739712.03     10016196.13      2739960.97     10016297.05
      2740099.11     10017043.28      2740232.71      10017061.5
      2740433.98     10016963.93      2740523.46     10017020.65
      2740632.91     10017516.61      2740952.09     10018132.75
      2740968.39     10018288.65      2741098.47     10018433.73
      2741024.63     10018759.92      2741041.53     10019091.05
       2741592.1     10019698.25      2741762.46     10020063.88
      2741761.25     10020914.48      2741945.85     10021104.94
      2741915.21     10021308.13      2742028.63      10021758.9
      2741802.09     10022130.14      2741974.22     10022425.37

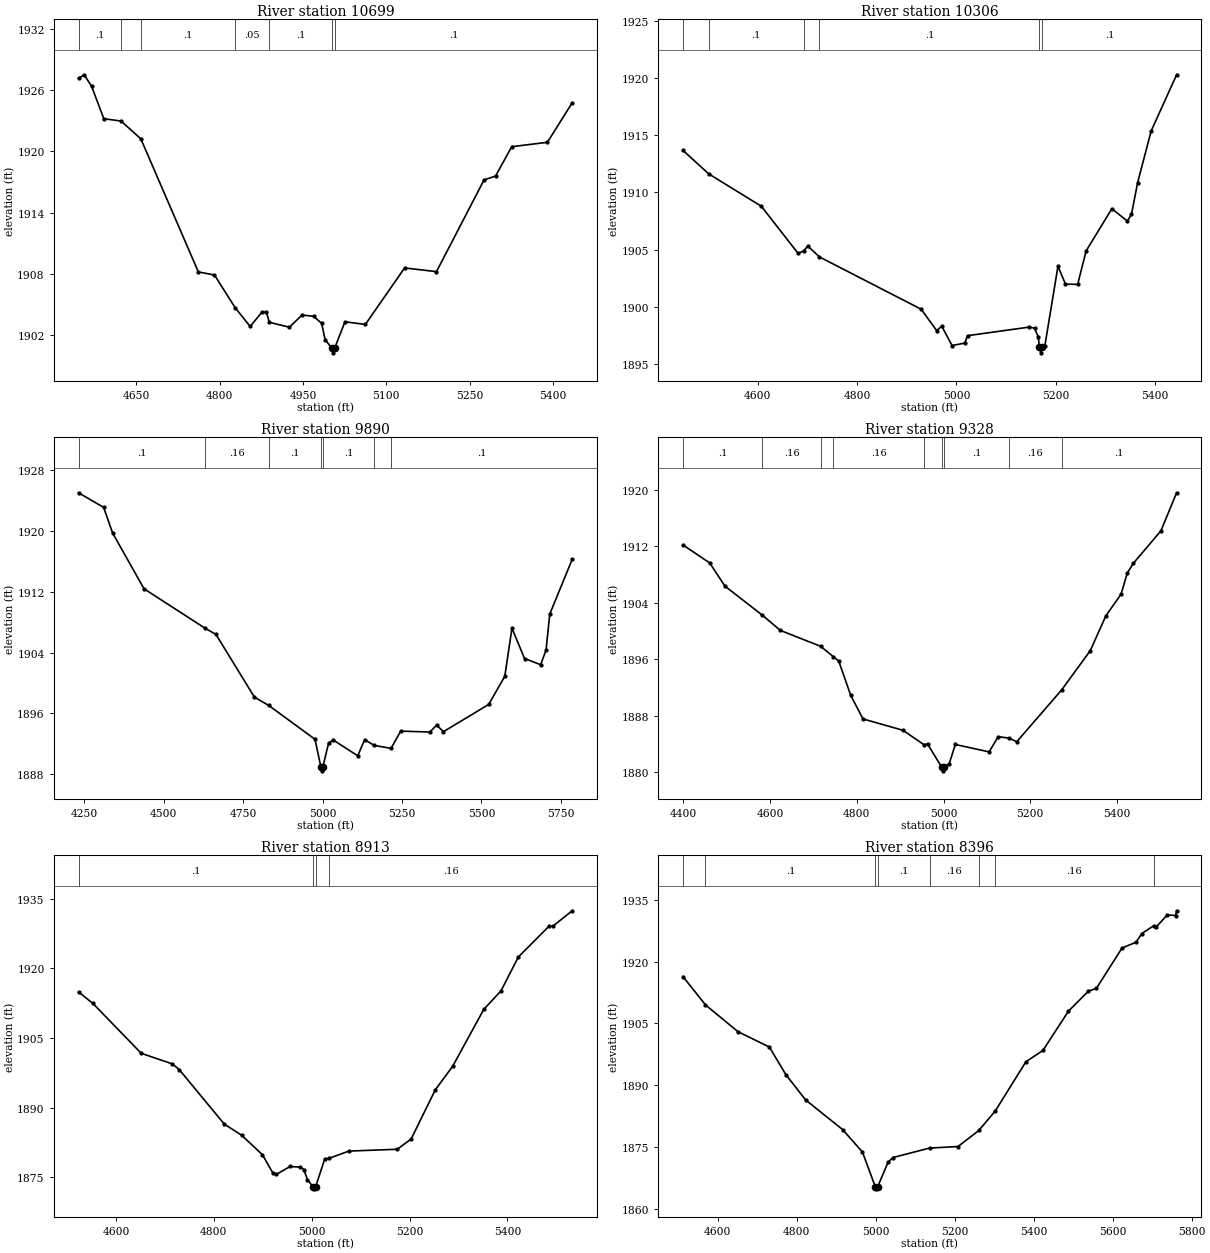
Type RM Length L Ch R = 1 ,10699   ,393,393,393
BEGIN DESCRIPTION:
UNT 1055 IN HEWA 23.0
END DESCRIPTION:
XS GIS Cut Line= 2
       2737533.7     10014662.28      2738078.83     10013960.92
#Sta/Elev= 30
  4546.2 1927.14  4556.4 1927.49  4569.7 1926.36  4591.7 1923.19  4622.7 1922.96
  4658.3 1921.22  4761.8 1908.19  4790.8 1907.89  4827.9  1904.7    4855 1902.85
  4875.9 1904.23    4884 1904.29  4889.5 1903.26  4925.6 1902.78  4948.3 1903.97
  4969.1 1903.85  4983.6 1903.16  4989.9 1901.56  5001.4 1900.77  5004.1 1900.27
  5007.4 1900.77  5025.6 1903.31  5062.3 1903.05  5132.9 1908.58  5190.3 1908.22
  5275.9  1917.2  5296.7 1917.58  5325.6 1920.45  5389.9 1920.88  5434.5 1924.75
#Mann= 7 ,-1 , 0
  4546.2      .1       0  4622.7     .05       0  4658.3      .1       0
  4827.9     .05       0  4889.5      .1       0  5001.4     .07       0
  5007.4      .1       0
Bank Sta=5001.4,5007.4
XS Rating Curve= 0 ,0
Exp/Cntr=0.3,0.1

Type RM Length L Ch R = 1 ,10306   ,416,416,416
BEGIN DESCRIPTION:
UNT 1055 IN HEWA 22.0
END DESCRIPTION:
XS GIS Cut Line= 2
        2737933.     10015085.93      2738196.72     10014128.17
#Sta/Elev= 30
  4449.7 1913.68  4501.7 1911.62  4607.6 1908.79  4681.4 1904.68  4692.7 1904.89
  4700.9 1905.32  4724.3 1904.37  4929.1  1899.8  4960.2 1897.94  4970.6 1898.31
  4991.3 1896.63  5016.9 1896.84  5022.4 1897.49  5146.9 1898.24  5157.3 1898.13
  5164.8 1897.38    5167 1896.49  5169.7 1895.99    5173 1896.49    5178  1896.6
  5204.4 1903.56  5219.5 1901.99    5244 1901.97    5261 1904.89  5312.8 1908.58
    5344  1907.5  5352.3 1908.09  5364.7 1910.86  5391.9 1915.37  5443.1 1920.28
#Mann= 6 ,-1 , 0
  4449.7     .16       0  4501.7      .1       0  4692.7     .16       0
  4724.3      .1       0    5167     .07       0    5173      .1       0
Bank Sta=5167,5173
XS Rating Curve= 0 ,0
Exp/Cntr=0.3,0.1

Type RM Length L Ch R = 1 ,9890    ,562,562,562
BEGIN DESCRIPTION:
UNT 1055 IN HEWA 21.0
END DESCRIPTION:
XS GIS Cut Line= 3
      2737839.24     10015245.64      2738693.42     10014467.85
       2738519.8      10014110.2
#Sta/Elev= 30
  4232.6 1925.03  4311.5 1923.11  4339.8 1919.73  4438.6 1912.39    4630 1907.21
  4664.9 1906.38  4785.9 1898.12  4830.9 1897.03  4976.4 1892.57    4995 1888.92
  4997.8 1888.42    5001 1888.92    5019 1892.04  5033.2 1892.49  5110.9  1890.4
  5132.5 1892.52  5162.5 1891.77  5215.6 1891.38  5245.9 1893.65  5337.9 1893.53
  5358.8 1894.44  5380.5 1893.58  5522.7 1897.16  5573.4 1900.87  5595.9  1907.2
  5635.5 1903.21  5686.2 1902.39  5703.2 1904.33  5714.8 1909.05  5785.4 1916.27
#Mann= 7 ,-1 , 0
  4232.6      .1       0    4630     .16       0  4830.9      .1       0
    4995     .07       0    5001      .1       0  5162.5     .16       0
  5215.6      .1       0
Bank Sta=4995,5001
XS Rating Curve= 0 ,0
Exp/Cntr=0.3,0.1

Type RM Length L Ch R = 1 ,9328    ,415,415,415
BEGIN DESCRIPTION:
UNT 1055 IN HEWA 20.0
END DESCRIPTION:
XS GIS Cut Line= 2
      2738301.04     10015433.14      2739148.24     10014672.74
#Sta/Elev= 30
  4399.1 1912.17  4460.8 1909.63    4496 1906.34  4582.3 1902.23  4623.8 1900.08
  4716.5 1897.83  4745.9 1896.37  4758.4 1895.74    4786 1890.89  4814.4 1887.55
  4906.4 1885.95  4954.6 1883.92  4963.2    1884  4996.1 1880.71  4998.8 1880.21
  5002.1 1880.71  5013.3 1881.24  5027.2 1883.94  5105.2 1882.89  5126.1 1885.04
  5151.3 1884.84  5168.8 1884.32  5272.4 1891.66  5338.4 1897.21  5374.3 1902.13
  5409.5 1905.21  5423.7 1908.18  5437.9 1909.58  5501.4 1914.17  5537.5 1919.55
#Mann= 9 ,-1 , 0
  4399.1      .1       0  4582.3     .16       0  4716.5      .1       0
  4745.9     .16       0  4954.6      .1       0  4996.1     .07       0
  5002.1      .1       0  5151.3     .16       0  5272.4      .1       0
Bank Sta=4996.1,5002.1
XS Rating Curve= 0 ,0
Exp/Cntr=0.3,0.1

Type RM Length L Ch R = 1 ,8913    ,517,517,517
BEGIN DESCRIPTION:
UNT 1055 IN HEWA 19.0
END DESCRIPTION:
XS GIS Cut Line= 2
      2738669.08      10015665.8       2739370.5     10014940.07
#Sta/Elev= 30
  4523.3 1914.88  4552.7 1912.42  4651.5 1901.68  4715.3 1899.39  4729.4 1898.15
  4821.3 1886.44  4856.8 1884.04  4899.2 1879.85  4920.3 1875.97  4927.5 1875.59
  4955.8 1877.31  4976.9 1877.17  4984.1 1876.64  4991.1 1874.51  5002.2    1873
    5005  1872.5  5008.2    1873  5026.6 1878.92  5035.3 1879.06    5076 1880.63
    5175 1881.02  5203.3 1883.23  5252.7 1893.82  5288.2 1898.89  5351.7 1911.12
  5387.2 1915.15  5422.5 1922.43    5486 1929.13  5493.2 1929.06  5532.6 1932.37
#Mann= 4 ,-1 , 0
  4523.3      .1       0  5002.2     .07       0  5008.2      .1       0
  5035.3     .16       0
Bank Sta=5002.2,5008.2
XS Rating Curve= 0 ,0
Exp/Cntr=0.3,0.1

Type RM Length L Ch R = 1 ,8396    ,337,337,337
BEGIN DESCRIPTION:
UNT 1055 IN HEWA 18.0
END DESCRIPTION:
XS GIS Cut Line= 2
      2738939.93     10016110.24      2739685.73     10015107.73
#Sta/Elev= 30
  4512.4 1916.39  4569.5 1909.49  4651.9 1902.98  4731.1 1899.27  4772.8 1892.58
  4822.9 1886.42  4916.8  1879.2  4966.8 1873.76  4999.3 1865.33    5002 1864.83
  5005.3 1865.33  5031.5 1871.28    5044 1872.43  5136.5 1874.73  5208.7  1875.1
  5261.3    1879  5303.1 1883.76  5380.5 1895.69  5423.6 1898.44  5488.2 1907.98
  5538.3 1912.79  5559.1 1913.54  5623.8 1923.31  5659.3 1924.71  5673.9 1926.83
  5703.5 1928.68  5709.3 1928.32  5738.5 1931.35  5759.4 1931.19  5761.9 1932.35
#Mann= 8 ,-1 , 0
  4512.4     .05       0  4569.5      .1       0  4999.3     .07       0
  5005.3      .1       0  5136.5     .16       0  5261.3      .1       0
  5303.1     .16       0  5703.5      .1       0
Bank Sta=4999.3,5005.3
XS Rating Curve= 0 ,0
Exp/Cntr=0.3,0.1

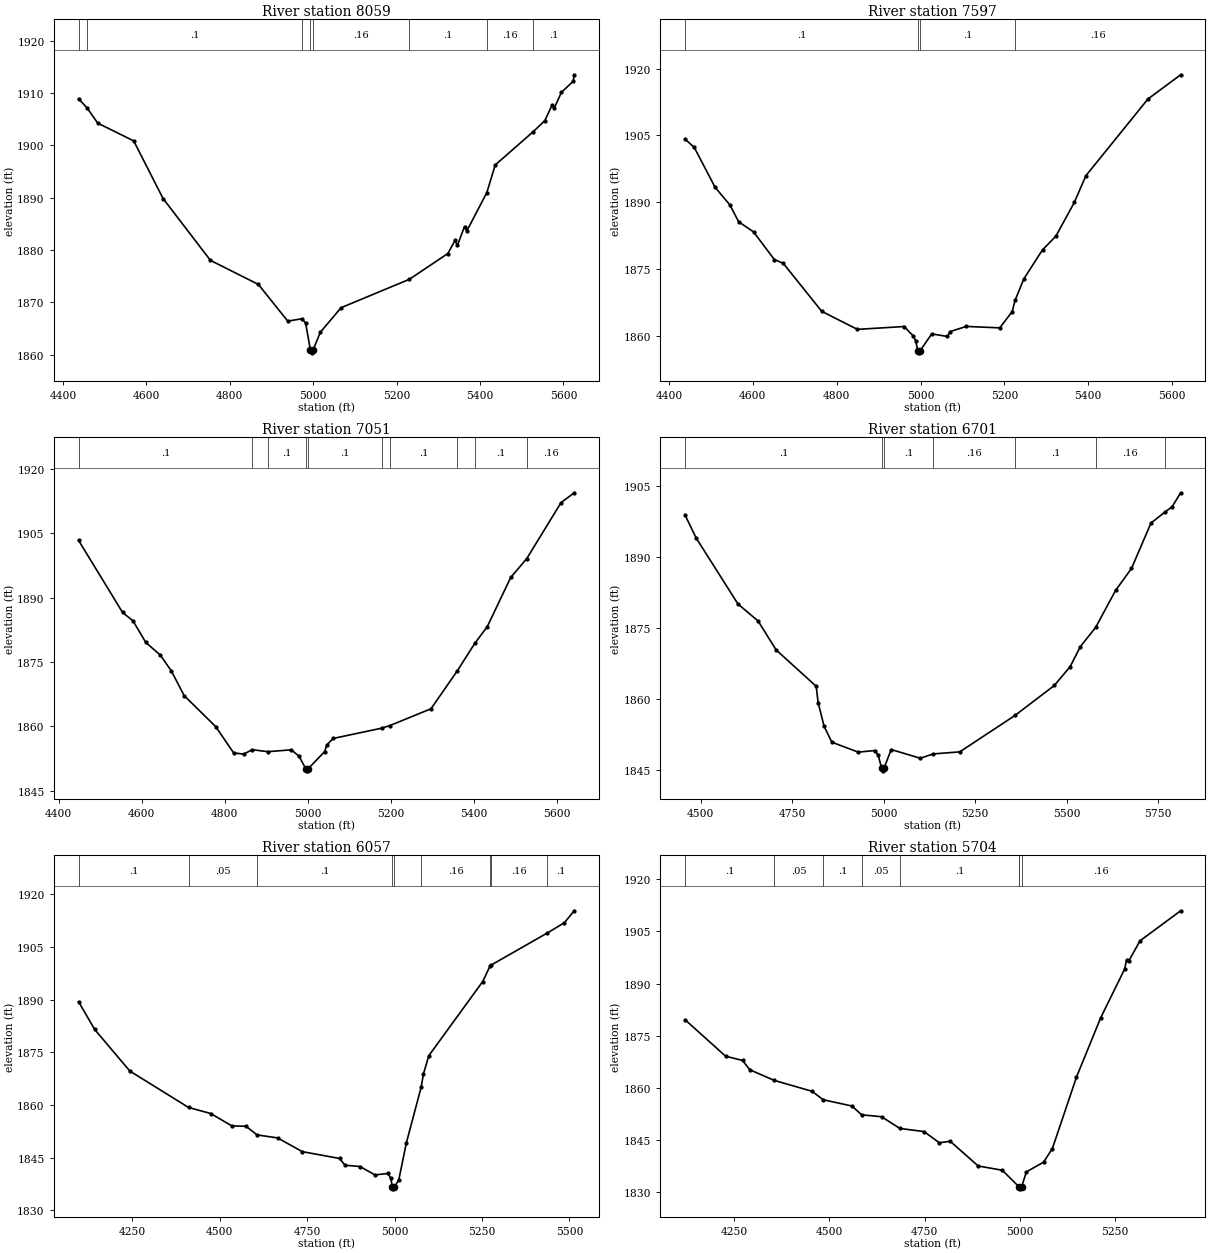
Type RM Length L Ch R = 1 ,8059    ,462,462,462
BEGIN DESCRIPTION:
UNT 1055 IN HEWA 17.0
END DESCRIPTION:
XS GIS Cut Line= 3
      2739158.68      10016339.4      2739703.83     10015665.77
      2739994.47     10015527.37
#Sta/Elev= 30
  4437.3  1908.9  4457.2  1907.2  4483.2 1904.26  4569.4 1900.86  4639.8 1889.84
  4753.4 1878.01  4868.4 1873.41  4938.8 1866.39  4973.7 1866.85  4981.9 1865.94
  4993.3 1860.82  4996.1 1860.32  4999.3 1860.82  5017.1 1864.27  5066.7 1868.95
  5230.3 1874.38  5322.9 1879.32  5340.1 1881.83  5345.7 1880.87  5362.8 1884.48
  5368.4 1883.65  5416.4 1890.99  5436.5 1896.26  5527.9 1902.65  5555.5 1904.74
  5572.7 1907.69  5578.2 1907.17  5595.4 1910.16  5623.7 1912.29  5625.8 1913.51
#Mann= 8 ,-1 , 0
  4437.3     .05       0  4457.2      .1       0  4973.7     .16       0
  4993.3     .07       0  4999.3     .16       0  5230.3      .1       0
  5416.4     .16       0  5527.9      .1       0
Bank Sta=4993.3,4999.3
XS Rating Curve= 0 ,0
Exp/Cntr=0.3,0.1

Type RM Length L Ch R = 1 ,7597    ,546,546,546
BEGIN DESCRIPTION:
UNT 1055 IN HEWA 16.0
END DESCRIPTION:
XS GIS Cut Line= 3
      2739415.66     10016651.86      2739714.25     10016353.27
       2740071.9     10015683.11
#Sta/Elev= 30
  4438.4 1904.18  4460.3 1902.31  4509.8 1893.38  4545.1 1889.42  4566.3  1885.6
  4601.7 1883.35  4651.2 1877.14  4672.4  1876.3  4764.3 1865.51  4849.2 1861.46
  4960.9  1862.1  4982.8 1859.95  4988.5 1858.91  4993.2 1856.69  4995.9 1856.19
  4999.2 1856.69  5026.7 1860.45  5064.2 1859.86  5070.6 1860.97  5108.9 1862.12
  5188.9  1861.8  5218.6 1865.46  5225.4 1867.97  5246.3  1872.8  5290.9 1879.33
  5322.7 1882.38  5366.7 1889.96  5394.3 1895.96  5542.3 1913.19  5620.3 1918.63
#Mann= 4 ,-1 , 0
  4438.4      .1       0  4993.2     .07       0  4999.2      .1       0
  5225.4     .16       0
Bank Sta=4993.2,4999.2
XS Rating Curve= 0 ,0
Exp/Cntr=0.3,0.1

Type RM Length L Ch R = 1 ,7051    ,350,350,350
BEGIN DESCRIPTION:
UNT 1055 IN HEWA 15.0
END DESCRIPTION:
XS GIS Cut Line= 3
      2739460.81     10016752.57      2740141.33     10016596.32
      2740435.84     10016197.87
#Sta/Elev= 30
  4447.9  1903.3  4553.8 1886.51  4578.9 1884.56  4609.7 1879.52  4644.7 1876.57
  4671.2 1872.89    4702 1867.14  4778.4 1859.87  4821.3 1853.77  4845.6 1853.49
    4866 1854.52  4903.5 1854.06  4960.1 1854.49    4979 1852.98  4994.9 1850.09
  4997.6 1849.59  5000.9 1850.09  5040.6 1854.08  5045.8 1855.64  5061.1 1857.14
  5177.5 1859.53    5198 1860.16  5296.7 1864.06  5360.4 1872.95  5402.3 1879.33
  5432.4 1883.23  5488.8 1894.68  5527.5 1899.09  5609.8  1912.1  5641.6 1914.42
#Mann= 10 ,-1 , 0
  4447.9      .1       0    4866     .16       0  4903.5      .1       0
  4994.9     .07       0  5000.9      .1       0  5177.5     .16       0
    5198      .1       0  5360.4     .16       0  5402.3      .1       0
  5527.5     .16       0
Bank Sta=4994.9,5000.9
XS Rating Curve= 0 ,0
Exp/Cntr=0.3,0.1

Type RM Length L Ch R = 1 ,6701    ,644,644,644
BEGIN DESCRIPTION:
UNT 1055 IN HEWA 14.0
END DESCRIPTION:
XS GIS Cut Line= 3
       2739544.1     10017158.83      2740242.03     10016891.46
      2740540.65     10016363.67
#Sta/Elev= 30
  4457.8  1898.8  4487.6 1894.02  4602.4 1880.01  4657.2 1876.44  4706.5 1870.33
  4815.9 1862.65  4821.3  1859.2  4837.3 1854.25  4858.7 1850.84  4930.8 1848.74
  4976.5 1849.08  4985.5 1848.06  4994.9 1845.29  4997.7 1844.79  5000.9 1845.29
  5020.9 1849.29  5100.3 1847.45  5135.2 1848.36  5208.2  1848.8  5358.9 1856.48
  5466.6 1862.82  5509.9 1866.82  5537.3 1870.99  5579.6 1875.11    5634 1882.91
  5677.3 1887.53  5730.7 1897.14  5768.1 1899.41  5788.6  1900.6  5811.6 1903.52
#Mann= 7 ,-1 , 0
  4457.8      .1       0  4994.9     .07       0  5000.9      .1       0
  5135.2     .16       0  5358.9      .1       0  5579.6     .16       0
  5768.1      .1       0
Bank Sta=4994.9,5000.9
XS Rating Curve= 0 ,0
Exp/Cntr=0.3,0.1

Type RM Length L Ch R = 1 ,6057    ,353,353,353
BEGIN DESCRIPTION:
UNT 1055 IN HEWA 13.0
END DESCRIPTION:
XS GIS Cut Line= 3
      2739683.04     10017256.04      2740408.69     10017176.18
      2740998.95     10016825.51
#Sta/Elev= 30
  4096.9 1889.38  4142.6 1881.53  4243.2 1869.67    4411 1859.31  4474.6 1857.57
    4535 1854.04  4575.2 1853.95  4607.1 1851.48  4665.7 1850.63  4736.2 1846.72
  4842.8 1844.78  4858.4 1842.86  4901.3 1842.48  4944.1 1840.09  4981.1 1840.51
  4989.5 1839.09  4993.7 1836.63  4996.5 1836.13  4999.7 1836.63  5012.3 1838.76
  5033.8 1849.22  5076.1 1865.07  5082.6 1868.83    5098 1874.04  5251.9 1895.14
  5273.2  1899.6  5276.5 1899.86  5434.5 1908.85  5485.7 1911.91  5513.5  1915.3
#Mann= 9 ,-1 , 0
  4096.9      .1       0    4411     .05       0  4607.1      .1       0
  4993.7     .07       0  4999.7      .1       0  5076.1     .16       0
  5273.2      .1       0  5276.5     .16       0  5434.5      .1       0
Bank Sta=4993.7,4999.7
XS Rating Curve= 0 ,0
Exp/Cntr=0.3,0.1

Type RM Length L Ch R = 1 ,5704    ,301,301,301
BEGIN DESCRIPTION:
UNT 1055 IN HEWA 12.0
END DESCRIPTION:
XS GIS Cut Line= 2
       2739759.4     10017565.07      2741043.75     10017367.21
#Sta/Elev= 30
  4121.9 1879.61  4228.2 1869.14  4272.7 1867.92  4291.4 1865.25  4355.8 1862.19
  4454.8 1859.06  4484.3 1856.62  4559.3 1854.83  4584.8  1852.3    4637 1851.75
  4685.2 1848.38  4748.3 1847.49  4788.7 1844.27  4817.2 1844.69  4890.5  1837.6
  4953.7 1836.37  4997.9 1831.57  4998.2 1831.53    5001 1831.03  5004.2 1831.53
  5016.9 1835.91  5061.9 1838.69  5085.1 1842.62  5148.3 1863.15  5211.5 1880.12
  5274.4 1894.16  5279.8 1896.84  5284.8 1896.38  5314.9  1902.3  5421.4 1910.93
#Mann= 8 ,-1 , 0
  4121.9      .1       0  4355.8     .05       0  4484.3      .1       0
  4584.8     .05       0  4685.2      .1       0  4997.9     .16       0
  4998.2     .07       0  5004.2     .16       0
Bank Sta=4998.2,5004.2
XS Rating Curve= 0 ,0
Exp/Cntr=0.3,0.1

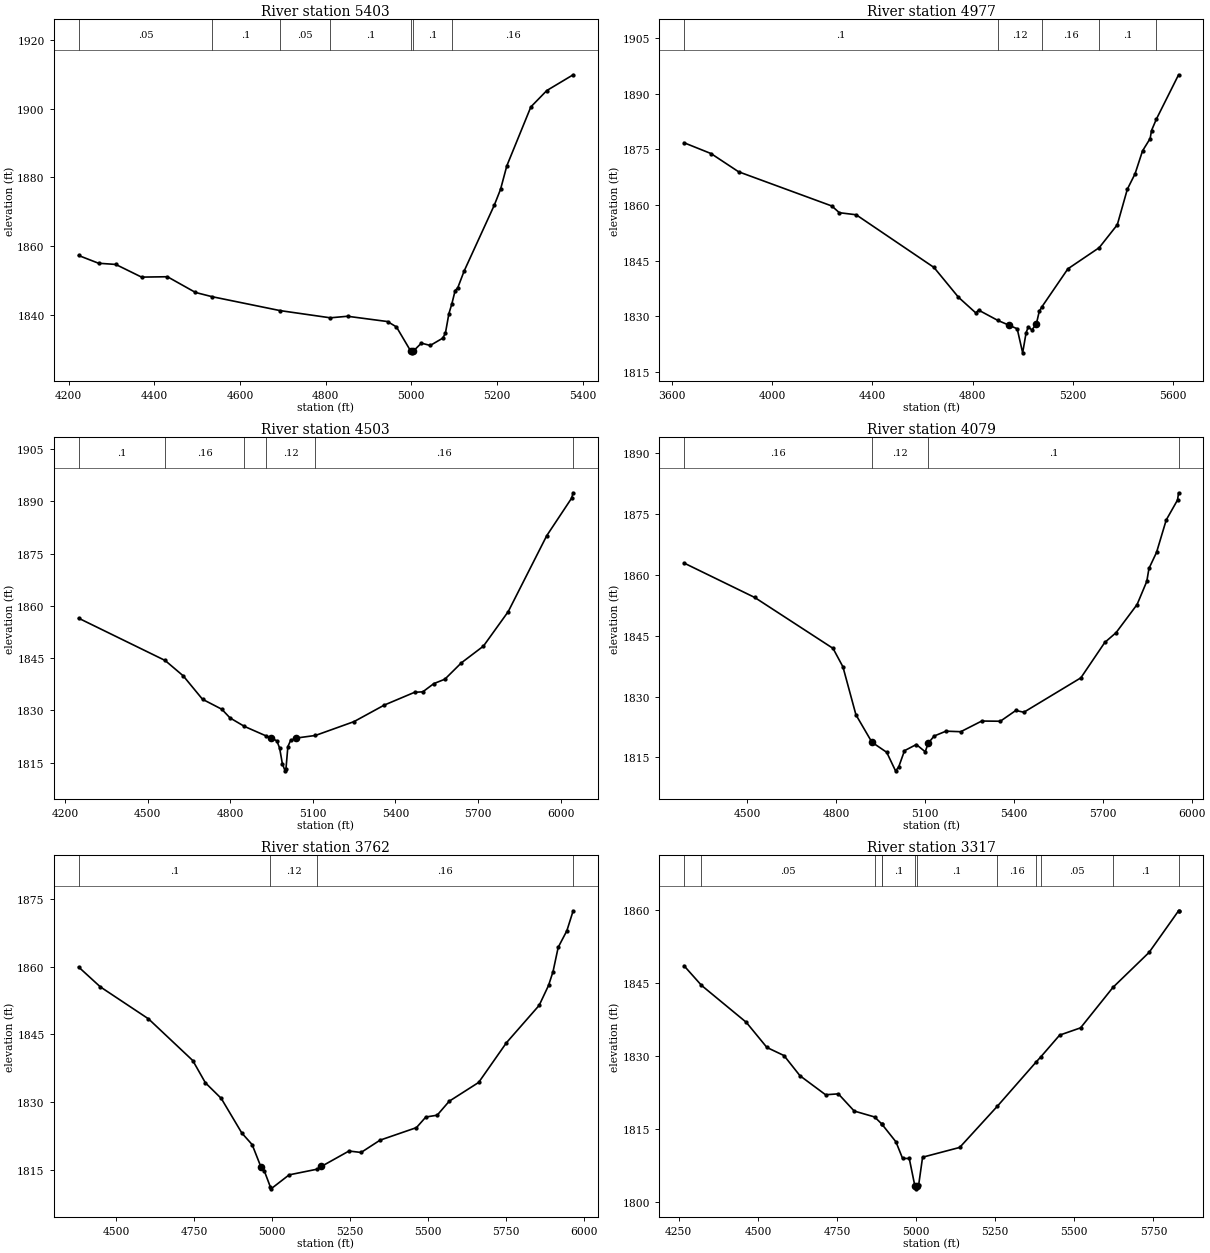
Type RM Length L Ch R = 1 ,5403    ,426,426,426
BEGIN DESCRIPTION:
UNT 1055 IN HEWA 11.0
END DESCRIPTION:
XS GIS Cut Line= 3
      2739992.08     10017762.99      2740578.83     10017818.55
      2741026.75      10017474.8
#Sta/Elev= 30
  4223.5 1857.23  4270.1 1854.97  4310.3 1854.62  4370.5 1850.93  4430.8 1851.04
  4496.3 1846.46  4535.4 1845.22  4693.6 1841.18  4810.9 1839.08    4851 1839.53
  4944.4 1837.99  4965.2 1836.42  4998.5 1829.38  5001.2 1828.88  5004.5 1829.38
  5023.3  1831.7  5044.1 1831.03  5073.1 1833.15  5079.4  1834.6  5087.6 1840.31
  5094.3 1843.08  5102.1 1846.99  5108.4 1847.87    5123 1852.67  5193.6 1871.92
  5208.1 1876.51  5222.7 1883.33  5278.8  1900.5    5316 1905.26  5377.5 1909.85
#Mann= 7 ,-1 , 0
  4223.5     .05       0  4535.4      .1       0  4693.6     .05       0
  4810.9      .1       0  4998.5     .07       0  5004.5      .1       0
  5094.3     .16       0
Bank Sta=4998.5,5004.5
XS Rating Curve= 0 ,0
Exp/Cntr=0.3,0.1

Type RM Length L Ch R = 1 ,4977    ,474,474,474
BEGIN DESCRIPTION:
UNT 1055 IN HEWA 10.0
END DESCRIPTION:
XS GIS Cut Line= 4
      2739630.95      10018311.6      2740304.53     10018363.68
      2741193.42     10017957.43      2741148.28     10017641.45
#Sta/Elev= 30
  3649.3 1876.78  3757.1 1873.86    3867 1868.95  4238.6 1859.73  4268.7 1857.92
  4335.8 1857.36  4646.1 1843.16  4743.7 1835.13  4812.7 1830.91    4824 1831.66
    4901 1828.87  4944.9  1827.6  4977.9 1826.63  4999.7 1820.14  5013.4 1825.55
  5021.9 1827.11  5036.4 1826.32    5054 1827.86  5065.9 1831.33  5076.9 1832.59
  5180.1 1842.79  5304.9 1848.49  5377.1 1854.67  5417.1 1864.25  5447.9 1868.41
  5477.7 1874.59    5508 1877.91  5513.5 1880.07  5532.7 1883.12  5621.4  1895.1
#Mann= 5 ,-1 , 0
  3649.3      .1       0    4901     .12       0  5076.9     .16       0
  5304.9      .1       0  5532.7     .16       0
Bank Sta=4944.9,5054
XS Rating Curve= 0 ,0
Exp/Cntr=0.3,0.1

Type RM Length L Ch R = 1 ,4503    ,424,424,424
BEGIN DESCRIPTION:
UNT 1055 IN HEWA 9.0
END DESCRIPTION:
XS GIS Cut Line= 2
      2740348.42     10018500.03      2742144.37     10018469.66
#Sta/Elev= 30
  4249.6 1856.49  4563.7 1844.36  4629.7 1839.93  4699.7 1833.21  4769.7 1830.35
  4799.7 1827.85  4851.9 1825.42  4929.7 1822.72  4949.7 1822.09  4969.7 1821.26
  4979.7 1819.21  4989.7 1814.69  4999.5 1812.66  5002.7 1813.16  5009.7 1819.62
  5019.8 1821.41  5039.8 1822.07  5109.8 1822.82  5249.8 1826.79  5359.8 1831.54
  5469.8 1835.21  5499.8 1835.35  5539.8 1837.71  5579.8 1838.97  5639.8 1843.67
  5719.9 1848.47  5809.9 1858.37  5949.9 1880.19  6039.9 1890.92  6045.8  1892.5
#Mann= 6 ,-1 , 0
  4249.6      .1       0  4563.7     .16       0  4851.9      .1       0
  4929.7     .12       0  5109.8     .16       0  6045.8      .1       0
Bank Sta=4949.7,5039.8
XS Rating Curve= 0 ,0
Exp/Cntr=0.3,0.1

Type RM Length L Ch R = 1 ,4079    ,317,317,317
BEGIN DESCRIPTION:
UNT 1055 IN HEWA 8.0
END DESCRIPTION:
XS GIS Cut Line= 4
      2740352.75     10018990.49      2740925.71     10018890.65
      2741329.35     10018886.31      2741984.09     10018686.86
#Sta/Elev= 30
  4286.3 1862.93    4525 1854.44  4789.5 1841.88  4822.9 1837.33  4866.8  1825.5
  4920.7 1818.75  4970.7 1816.26  5000.4 1811.69  5010.7 1812.56  5030.7 1816.66
  5070.7 1818.18  5100.7 1816.39  5110.7 1818.49  5130.7 1820.27  5170.7 1821.47
  5220.7 1821.34  5291.5 1823.97  5354.3 1823.92  5406.5 1826.57  5433.7 1826.14
  5626.1 1834.62  5706.9 1843.35    5745 1845.76  5815.9 1852.69  5848.7 1858.41
    5856 1861.59  5881.6 1865.55  5914.4 1873.56  5952.5 1878.47    5956 1880.25
#Mann= 4 ,-1 , 0
  4286.3     .16       0  4920.7     .12       0  5110.7      .1       0
    5956      .1       0
Bank Sta=4920.7,5110.7
XS Rating Curve= 0 ,0
Exp/Cntr=0.3,0.1

Type RM Length L Ch R = 1 ,3762    ,445,445,445
BEGIN DESCRIPTION:
UNT 1055 IN HEWA 7.0
END DESCRIPTION:
XS GIS Cut Line= 3
      2740487.37     10019146.73      2741003.83     10019233.53
      2741948.72     10018748.09
#Sta/Elev= 30
    4379 1859.94  4448.7 1855.53  4603.2 1848.43  4745.2 1839.18  4785.7 1834.24
  4836.4 1830.79  4902.5  1823.1  4935.6 1820.53  4964.1 1815.52  4974.3 1814.75
  4993.5 1811.22  4996.2 1810.72  5054.1 1813.82    5144 1815.08  5157.4 1815.68
  5246.1 1819.11  5284.9 1818.79  5345.8 1821.52  5462.4  1824.3  5492.5 1826.65
  5528.9 1827.06  5567.6 1830.16    5662 1834.33  5751.1 1843.14    5856 1851.43
    5886 1855.84  5900.4  1858.9    5917  1864.3  5944.8 1867.98    5965 1872.41
#Mann= 4 ,-1 , 0
    4379      .1       0  4993.5     .12       0    5144     .16       0
    5965     .05       0
Bank Sta=4964.1,5157.4
XS Rating Curve= 0 ,0
Exp/Cntr=0.3,0.1

Type RM Length L Ch R = 1 ,3317    ,404,404,404
BEGIN DESCRIPTION:
UNT 1055 IN HEWA 6.0
END DESCRIPTION:
XS GIS Cut Line= 3
      2740695.68     10019480.93      2741294.63     10019567.74
      2742092.89     10019038.45
#Sta/Elev= 30
  4266.5 1848.64  4321.8  1844.6  4463.3 1837.01  4528.5 1831.84  4582.6 1830.17
  4633.1 1826.02  4713.9 1822.12  4754.3  1822.3  4804.4 1818.77    4869 1817.55
  4890.8 1816.16  4892.7 1816.01  4936.3 1812.44  4957.3 1809.03  4978.4 1809.02
  4996.4 1803.28  4999.2 1802.78  5002.4 1803.28  5008.3 1803.66  5020.5 1809.28
  5137.8 1811.29  5256.8 1819.76  5378.7  1828.8    5395 1829.97  5453.6 1834.37
  5519.8 1835.87  5622.5 1844.21  5736.4 1851.38  5829.3 1859.91  5829.5 1859.93
#Mann= 12 ,-1 , 0
  4266.5      .1       0  4321.8     .05       0    4869      .1       0
  4890.8     .05       0  4892.7      .1       0  4996.4     .07       0
  5002.4      .1       0  5256.8     .16       0  5378.7      .1       0
    5395     .05       0  5622.5      .1       0  5829.3     .05       0
Bank Sta=4996.4,5002.4
XS Rating Curve= 0 ,0
Exp/Cntr=0.3,0.1

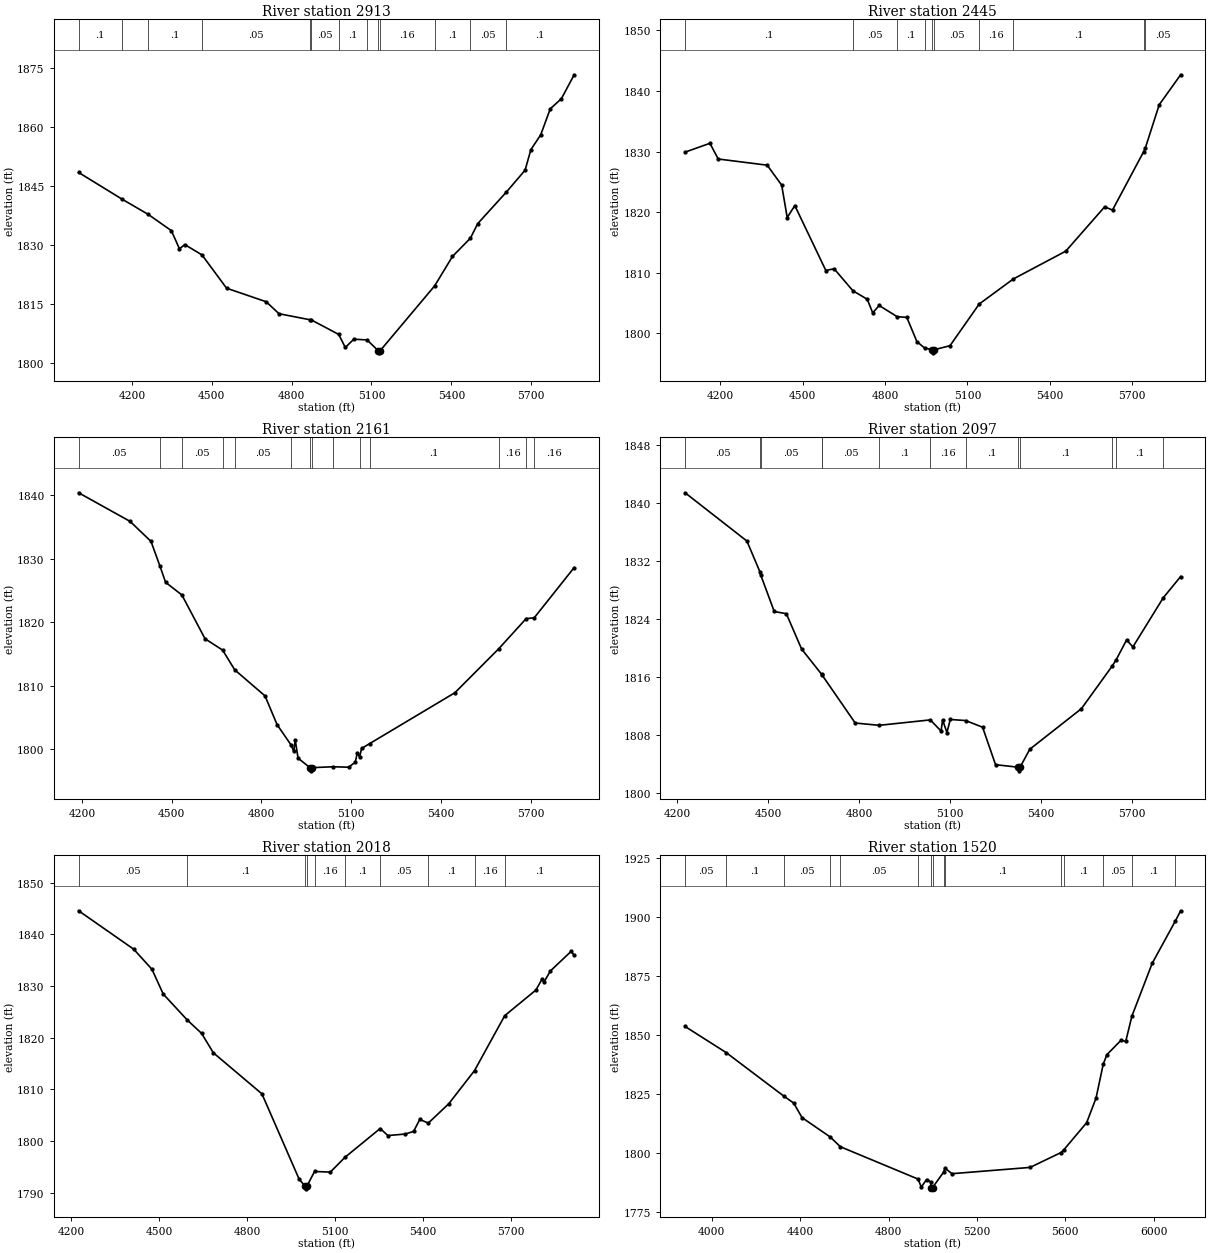
Type RM Length L Ch R = 1 ,2913    ,468,468,468
BEGIN DESCRIPTION:
UNT 1055 IN HEWA 5.0
END DESCRIPTION:
XS GIS Cut Line= 4
      2740643.56     10019841.17      2741290.29     10019932.32
      2741789.42     10019754.37      2742340.61     10019359.42
#Sta/Elev= 30
  4000.2  1848.5  4162.5 1841.75  4261.5 1837.85  4348.5 1833.71  4378.8  1829.1
    4399 1830.17  4463.6 1827.54  4555.8 1819.09  4704.5 1815.65  4752.8  1812.6
  4870.6 1811.05  4872.6 1811.08    4977 1807.34  5001.7 1804.02  5033.6 1806.13
  5083.4 1805.94  5126.1 1803.16  5128.9 1802.66  5132.1 1803.16  5337.5  1819.7
  5404.3 1827.17  5471.6 1831.79  5498.8 1835.48    5606 1843.47    5677 1849.09
  5698.7 1854.31  5735.6 1858.06  5771.5 1864.68  5813.3 1867.25  5861.3 1873.33
#Mann= 13 ,-1 , 0
  4000.2      .1       0  4162.5     .05       0  4261.5      .1       0
  4463.6     .05       0  4870.6      .1       0  4872.6     .05       0
    4977      .1       0  5083.4     .16       0  5126.1     .07       0
  5132.1     .16       0  5337.5      .1       0  5471.6     .05       0
    5606      .1       0
Bank Sta=5126.1,5132.1
XS Rating Curve= 0 ,0
Exp/Cntr=0.3,0.1

Type RM Length L Ch R = 1 ,2445    ,284,284,284
BEGIN DESCRIPTION:
UNT 1055 IN HEWA 4.0
END DESCRIPTION:
XS GIS Cut Line= 3
       2740808.5     10020318.61      2741941.33     10020205.76
      2742374.09     10019699.44
#Sta/Elev= 30
  4071.8 1829.91  4162.2 1831.37  4192.4 1828.78  4370.7 1827.76  4423.5 1824.47
  4443.6 1819.13  4471.4  1821.1  4584.3 1810.39  4614.4 1810.68  4682.8 1807.05
    4735 1805.65  4755.1  1803.4  4778.5 1804.62  4844.1 1802.77  4879.2 1802.66
  4915.9 1798.66  4943.7 1797.62  4971.8 1797.31  4974.6 1796.81  4977.8 1797.31
  5036.5 1797.99  5142.8 1804.86  5266.9 1808.99    5458 1813.58  5599.6 1820.89
  5628.2 1820.36  5741.9 1830.01  5748.3 1830.67  5798.3 1837.73  5876.3 1842.67
#Mann= 10 ,-1 , 0
  4071.8      .1       0  4682.8     .05       0  4844.1      .1       0
  4943.7     .05       0  4971.8    .033       0  4977.8     .05       0
  5142.8     .16       0  5266.9      .1       0  5741.9     .16       0
  5748.3     .05       0
Bank Sta=4971.8,4977.8
XS Rating Curve= 0 ,0
Exp/Cntr=0.3,0.1

Type RM Length L Ch R = 1 ,2161    ,64,64,64
BEGIN DESCRIPTION:
Mapping XS ffa91c8a
END DESCRIPTION:
XS GIS Cut Line= 5
      2740917.23     10020478.19      2741502.95     10020519.21
      2741639.12     10020529.05      2741806.47     10020492.95
      2742374.59     10019987.05
#Sta/Elev= 30
  4189.3 1840.33    4361 1835.84  4431.1 1832.69  4461.3 1828.77  4479.8 1826.26
  4534.3 1824.27  4611.6 1817.39  4670.4 1815.61  4710.6 1812.52  4812.1 1808.41
  4852.2 1803.91  4899.7 1800.66  4907.9 1799.71    4913 1801.46  4922.5 1798.63
  4962.2 1797.14    4965 1796.64  4968.2 1797.14  5039.7 1797.28    5092 1797.21
  5113.6 1798.02  5120.5  1799.5    5128 1798.83  5134.7 1800.16  5161.6 1800.92
  5446.6 1808.92  5593.2 1815.84  5684.5 1820.56  5711.3 1820.68  5844.9 1828.58
#Mann= 14 ,-1 , 0
  4189.3     .05       0  4461.3      .1       0  4534.3     .05       0
  4670.4      .1       0  4710.6     .05       0  4899.7      .1       0
  4962.2     .07       0  4968.2      .1       0  5039.7     .16       0
    5128     .05       0  5161.6      .1       0  5593.2     .16       0
  5684.5      .1       0  5711.3     .16       0
Bank Sta=4962.2,4968.2
XS Rating Curve= 0 ,0
Exp/Cntr=0.3,0.1

Type RM Length L Ch R = 1 ,2097    ,79,79,79
BEGIN DESCRIPTION:
Mapping XS 0a8e285d
END DESCRIPTION:
XS GIS Cut Line= 4
      2740954.97     10020535.25      2741655.96     10020589.51
      2741814.38     10020554.79      2742402.46     10020055.68
#Sta/Elev= 30
  4225.1 1841.36  4429.2  1834.7  4472.9 1830.38  4475.1 1829.99  4519.5 1824.98
  4559.6 1824.67  4609.7 1819.81  4676.4 1816.29  4678.2 1816.17  4786.9 1809.59
    4866 1809.27  5034.9 1810.02  5070.5 1808.48  5075.6    1810  5089.9 1808.28
    5101 1810.08  5151.6 1809.93  5207.6 1809.01  5250.4 1803.84  5325.4 1803.49
  5328.1 1802.99  5331.4 1803.49  5363.5 1805.97  5533.8 1811.56  5635.8 1817.46
  5648.4 1818.29  5683.2 1821.05    5704 1820.09  5804.3 1826.87  5861.7  1829.8
#Mann= 13 ,-1 , 0
  4225.1     .05       0  4472.9      .1       0  4475.1     .05       0
  4676.4      .1       0  4678.2     .05       0    4866      .1       0
  5034.9     .16       0  5151.6      .1       0  5325.4     .07       0
  5331.4      .1       0  5635.8     .16       0  5648.4      .1       0
  5804.3     .16       0
Bank Sta=5325.4,5331.4
XS Rating Curve= 0 ,0
Exp/Cntr=0.3,0.1

Type RM Length L Ch R = 1 ,2018    ,498,498,498
BEGIN DESCRIPTION:
UNT 1055 IN HEWA 3.0
END DESCRIPTION:
XS GIS Cut Line= 4
      2740961.56     10020622.57      2741593.18     10020689.83
      2742034.52     10020570.07      2742451.24     10020141.86
#Sta/Elev= 30
  4224.6 1844.54  4412.6 1837.11  4474.8 1833.22  4513.1 1828.45  4594.9 1823.44
  4643.9 1820.85  4684.1 1817.09  4849.7 1809.16  4976.3 1792.71    4997  1791.3
  4999.7  1790.8    5003  1791.3  5029.2 1794.16  5082.9 1794.03  5132.7 1796.88
    5253 1802.46  5279.3  1801.1  5338.6 1801.39  5366.9  1801.9    5388 1804.21
  5417.2 1803.51    5487 1807.25  5574.7 1813.65  5677.8 1824.27  5784.1 1829.22
  5805.2 1831.34  5812.4 1830.83  5833.5 1832.91  5904.2  1836.7  5914.6 1835.95
#Mann= 10 ,-1 , 0
  4224.6     .05       0  4594.9      .1       0    4997     .07       0
    5003      .1       0  5029.2     .16       0  5132.7      .1       0
    5253     .05       0  5417.2      .1       0  5574.7     .16       0
  5677.8      .1       0
Bank Sta=4997,5003
XS Rating Curve= 0 ,0
Exp/Cntr=0.3,0.1

Type RM Length L Ch R = 1 ,1520    ,486,486,486
BEGIN DESCRIPTION:
UNT 1055 IN HEWA 2.0
END DESCRIPTION:
XS GIS Cut Line= 4
      2740939.81      10020817.8      2741582.18     10021199.75
      2742445.89     10020843.85       2742836.5     10020440.22
#Sta/Elev= 30
  3879.1 1853.72    4065 1842.66  4326.3 1824.19    4371 1821.25  4408.1 1815.13
  4537.1 1806.82  4581.8 1802.77  4933.8 1789.05  4948.2 1785.68  4972.1 1788.85
  4990.2 1787.91  4993.1 1785.42  4995.8 1784.92  4999.1 1785.42  5050.2 1792.11
  5055.2 1793.68  5087.5 1791.34  5440.9    1794    5581 1800.31  5593.6 1801.47
  5696.9 1812.96  5739.4  1823.4    5772 1837.81  5788.8 1841.81  5852.6  1847.9
  5873.7 1847.36  5901.6 1858.08  5993.8 1880.54    6099 1898.52  6122.3 1902.75
#Mann= 15 ,-1 , 0
  3879.1     .05       0    4065      .1       0  4326.3     .05       0
  4537.1      .1       0  4581.8     .05       0  4933.8      .1       0
  4993.1     .07       0  4999.1      .1       0  5050.2     .16       0
  5055.2      .1       0    5581     .16       0  5593.6      .1       0
    5772     .05       0  5901.6      .1       0    6099     .16       0
Bank Sta=4993.1,4999.1
XS Rating Curve= 0 ,0
Exp/Cntr=0.3,0.1

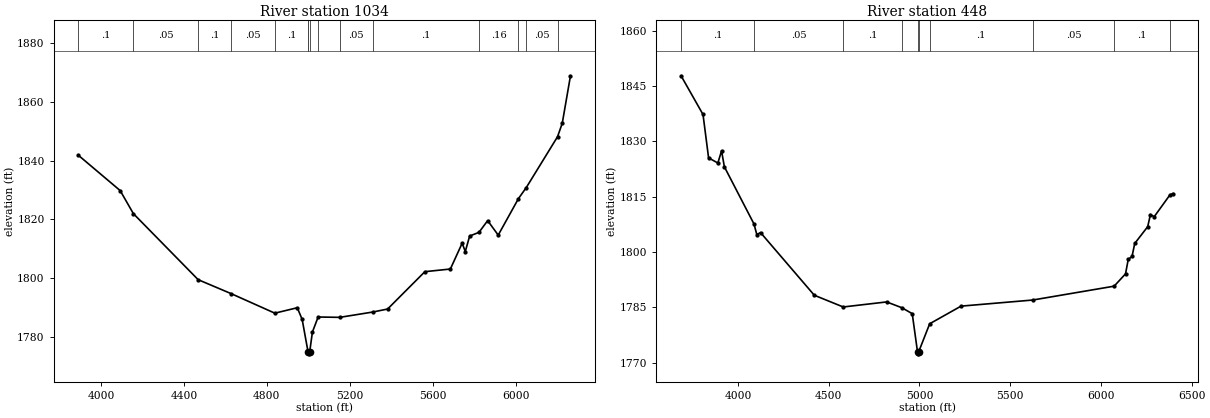
Type RM Length L Ch R = 1 ,1034    ,586,586,586
BEGIN DESCRIPTION:
Mapping XS 3d784618
END DESCRIPTION:
XS GIS Cut Line= 4
      2740944.71     10021293.98      2741667.63     10021620.14
      2742210.44     10021457.05      2742777.08     10020618.04
#Sta/Elev= 30
  3891.7 1841.76  4092.8 1829.81  4156.5 1821.98  4468.9 1799.57  4628.8 1794.81
  4838.5 1788.21  4946.7 1790.05  4970.3  1786.1  4998.1  1775.3  5000.3 1774.91
    5003 1774.41  5006.3 1774.91  5019.8 1781.82  5047.3 1786.91  5151.6 1786.79
  5309.5 1788.58  5382.2 1789.61    5562 1802.29  5684.9 1803.19  5741.8 1811.96
  5756.8 1809.11  5777.8 1814.38  5822.9 1815.64  5864.7 1819.61  5915.6  1814.7
  6013.3  1827.1  6051.1 1830.85  6201.7 1848.09  6224.4 1852.66    6264 1868.76
#Mann= 15 ,-1 , 0
  3891.7      .1       0  4156.5     .05       0  4468.9      .1       0
  4628.8     .05       0  4838.5      .1       0  4998.1     .16       0
  5000.3     .07       0  5006.3     .16       0  5047.3      .1       0
  5151.6     .05       0  5309.5      .1       0  5822.9     .16       0
  6013.3      .1       0  6051.1     .05       0  6201.7      .1       0
Bank Sta=5000.3,5006.3
XS Rating Curve= 0 ,0
Exp/Cntr=0.3,0.1

Type RM Length L Ch R = 1 ,448     ,0,0,0
BEGIN DESCRIPTION:
UNT 1055 IN HEWA 1.0
END DESCRIPTION:
XS GIS Cut Line= 4
      2740560.08     10021739.41      2741735.78     10021987.69
      2741920.78     10022082.63      2742663.17     10021014.07
#Sta/Elev= 30
  3686.9  1847.8  3807.9 1837.31  3838.6 1825.55  3889.7 1824.16  3910.1 1827.46
  3925.5 1823.14  4088.6 1807.65  4104.3 1804.77  4124.7 1805.31  4421.1 1788.32
  4580.3 1785.14  4819.7 1786.51  4903.2 1784.94  4960.6 1783.33  4989.7 1772.94
  4992.5 1772.44  4995.7 1772.94  5056.7 1780.59  5229.5 1785.37  5623.9 1787.02
    6073 1790.78  6135.7 1794.12  6150.6 1798.04  6171.5 1798.83  6186.4 1802.36
  6257.9 1806.91  6272.8  1810.2  6293.7 1809.61  6380.8 1815.55  6397.6 1815.89
#Mann= 10 ,-1 , 0
  3686.9      .1       0  4088.6     .05       0  4580.3      .1       0
  4903.2     .05       0  4989.7     .04       0  4995.7     .05       0
  5056.7      .1       0  5623.9     .05       0    6073      .1       0
  6380.8     .16       0
Bank Sta=4989.7,4995.7
XS Rating Curve= 0 ,0
Exp/Cntr=0.3,0.1

Chan Stop Cuts=-1
Use User Specified Reach Order=0
Composite Channel Slope=5