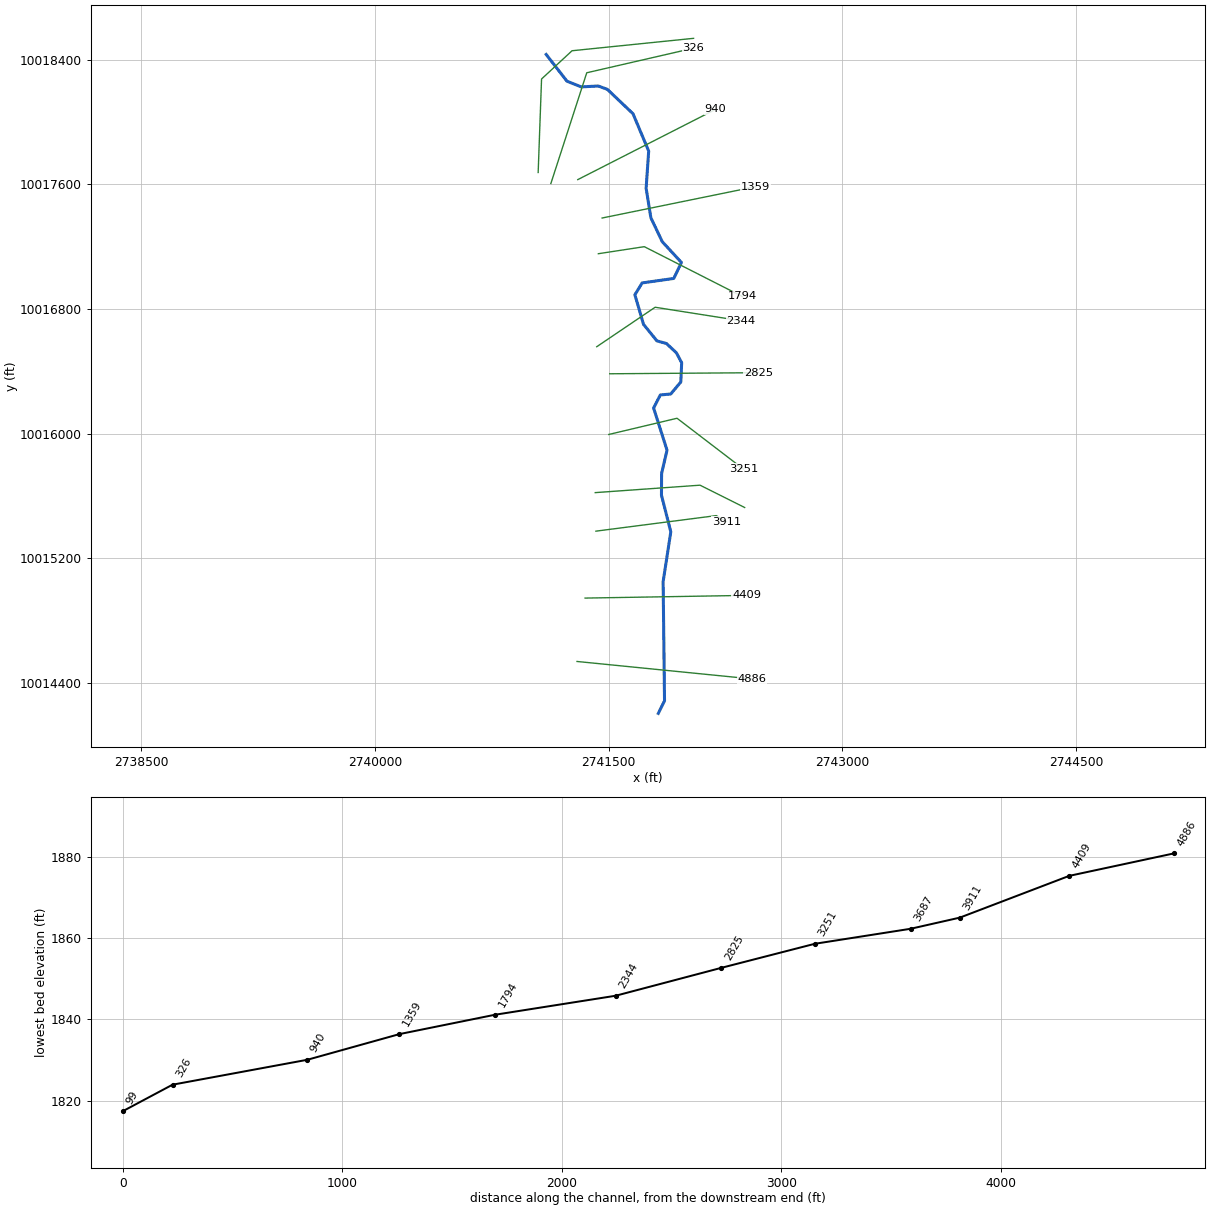
--- UNT 1056 IN HEWA.prj (project) ---

Proj Title=UNT 1056 IN HEWA Base Level Engineering
Current Plan=p01
Default Exp/Contr=0.3,0.1
English Units
Geom File=g01
Flow File=f01
Plan File=p01
Y Axis Title=Elevation
X Axis Title(PF)=Main Channel Distance
X Axis Title(XS)=Station
BEGIN DESCRIPTION:
UNT 1056 IN HEWA
END DESCRIPTION:
DSS Export Rating Curves= 0
DSS Export Rating Curve Sorted= 0
DSS Export Volume Flow Curves= 0
DXF OffsetX= 0
DXF OffsetY= 0
DXF ScaleX= 1
DXF ScaleY= 10

--- UNT 1056 IN HEWA.p01 (plan) ---

Plan Title=Multiple Run
Short Identifier=Multiple
Geom File=g01
Flow File=f01
Subcritical Flow
K Sum by GR= 0
Std Step Tol= 0.01
Critical Tol= 0.01
Num of Std Step Trials= 20
Max Error Tol= 0.3
Flow Tol Ratio= 0.001
Split Flow NTrial= 30
Split Flow Tol= 0.02
Split Flow Ratio= 0.02
Log Output Level= 0
Friction Slope Method= 1
Unsteady Friction Slope Method= 2
Unsteady Bridges Friction Slope Method= 1
Parabolic Critical Depth
Global Vel Dist=  1 , 1 , 1
Global Log Level= 0
CheckData=True
Encroach Param= -1, 0, 0, 0
BEGIN DESCRIPTION:
Multiple Run
END DESCRIPTION:

--- UNT 1056 IN HEWA.f01 (steady flow) ---

Flow Title=Multiple
Program Version=4.10
Number of Profiles= 7
Profile Names=10-year,25-year,50-year,1pct_min,100-year,1pct_plu,500-year
River Rch & RM=UNT 1056 IN HEWA,Reach-1         ,4886
     700    1002    1262    1164    1574    2128    2457
Boundary for River Rch & Prof#=UNT 1056 IN HEWA,Reach-1         , 1
Up Type= 0
Dn Type= 3
Dn Slope=0.01
Boundary for River Rch & Prof#=UNT 1056 IN HEWA,Reach-1         , 2
Up Type= 0
Dn Type= 3
Dn Slope=0.01
Boundary for River Rch & Prof#=UNT 1056 IN HEWA,Reach-1         , 3
Up Type= 0
Dn Type= 3
Dn Slope=0.01
Boundary for River Rch & Prof#=UNT 1056 IN HEWA,Reach-1         , 4
Up Type= 0
Dn Type= 3
Dn Slope=0.01
Boundary for River Rch & Prof#=UNT 1056 IN HEWA,Reach-1         , 5
Up Type= 0
Dn Type= 3
Dn Slope=0.01
Boundary for River Rch & Prof#=UNT 1056 IN HEWA,Reach-1         , 6
Up Type= 0
Dn Type= 3
Dn Slope=0.01
Boundary for River Rch & Prof#=UNT 1056 IN HEWA,Reach-1         , 7
Up Type= 0
Dn Type= 3
Dn Slope=0.01
DSS Import GetInterval= 0
DSS Import GetPeak= 0
DSS Import FillOption= 0

--- UNT 1056 IN HEWA.g01 (geometry) ---

Geom Title=Existing Conditions
Program Version=4.10

River Reach=UNT 1056 IN HEWA,Reach-1
Reach XY= 30
      2741818.47     10014203.21      2741858.44     10014283.76
      2741849.47     10015048.71      2741898.74     10015368.63
       2741838.8     10015603.88      2741839.67     10015743.28
      2741874.45       10015893.      2741788.32     10016163.65
       2741831.4     10016247.43      2741898.47     10016253.73
      2741963.01     10016331.01       2741968.5     10016454.41
      2741934.64     10016518.21      2741870.86     10016577.78
      2741809.42     10016594.77      2741723.55     10016700.84
      2741668.18     10016890.71      2741714.78     10016966.78
      2741917.86     10016995.57        2741967.      10017098.1
      2741844.08     10017231.25      2741770.89     10017384.74
       2741740.3     10017574.15      2741756.76     10017813.32
      2741656.21      10018052.8       2741491.4     10018209.57
      2741433.01     10018231.05      2741324.14     10018225.43
      2741232.34     10018261.71      2741098.47     10018433.73

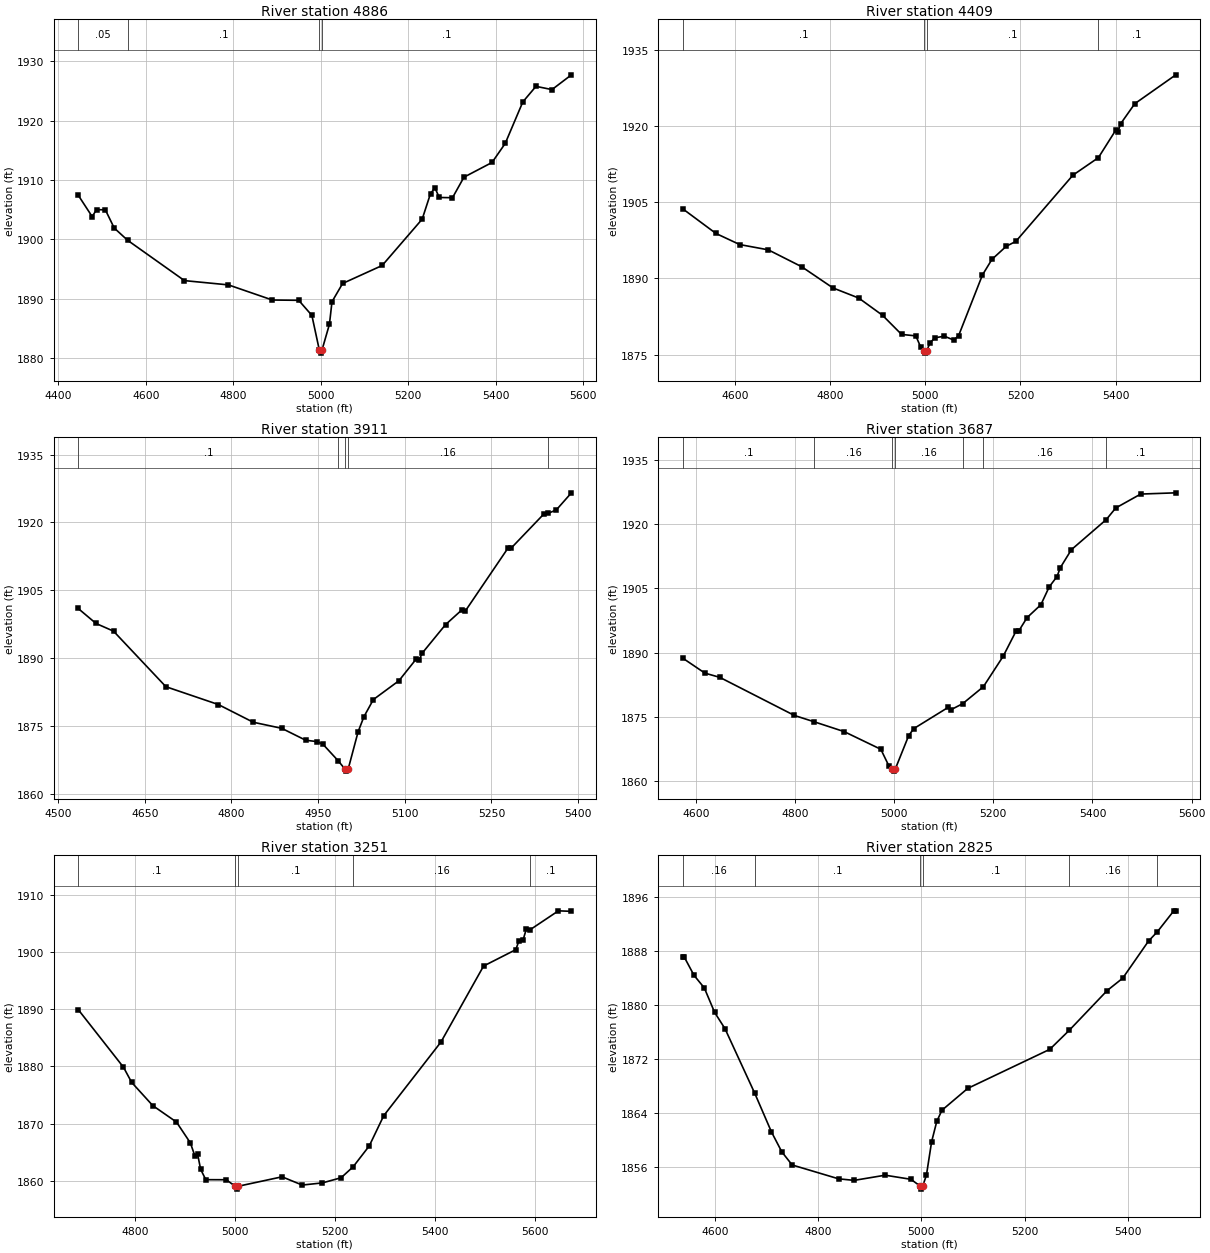
Type RM Length L Ch R = 1 ,4886    ,477,477,477
BEGIN DESCRIPTION:
UNT 1056 IN HEWA 11.0
END DESCRIPTION:
XS GIS Cut Line= 2
      2741296.71     10014536.43      2742419.13     10014424.45
#Sta/Elev= 30
  4445.4 1907.43  4477.3 1903.82  4487.4 1904.99  4507.5 1904.96  4527.8 1901.89
  4558.5 1899.82  4688.4 1893.03  4788.9 1892.31  4889.4 1889.76  4949.7 1889.71
  4979.8 1887.17  4996.9 1881.31  4999.6 1880.81  5002.9 1881.31    5020 1885.69
  5025.8 1889.47  5050.1 1892.55  5140.6 1895.58  5232.1 1903.39  5251.1 1907.69
  5261.2 1908.66  5271.2 1907.04  5301.4    1907  5327.6 1910.46  5391.8 1912.94
    5422 1916.15  5462.2 1923.14  5492.3 1925.77  5528.9 1925.22  5573.4 1927.71
#Mann= 4 ,-1 , 0
  4445.4     .05       0  4558.5      .1       0  4996.9     .07       0
  5002.9      .1       0
Bank Sta=4996.9,5002.9
XS Rating Curve= 0 ,0
Exp/Cntr=0.3,0.1

Type RM Length L Ch R = 1 ,4409    ,498,498,498
BEGIN DESCRIPTION:
UNT 1056 IN HEWA 10.0
END DESCRIPTION:
XS GIS Cut Line= 2
      2741348.41     10014943.43      2742384.67     10014960.77
#Sta/Elev= 30
  4490.1 1903.75  4560.2 1898.87  4610.2 1896.68  4670.2 1895.64  4740.2 1892.32
  4806.1 1888.13  4860.2 1886.14  4910.2 1882.74  4950.2 1878.97  4980.2 1878.68
  4990.2 1876.53  4997.2 1875.78    5000 1875.28  5003.2 1875.78  5010.2 1877.32
  5020.2  1878.3  5040.2 1878.62  5060.2 1877.84  5070.2 1878.75  5120.2 1890.69
  5140.2 1893.77  5170.2 1896.34  5190.3  1897.3  5310.3 1910.36  5363.8 1913.81
  5399.9 1919.17  5404.9 1918.88  5410.3 1920.46  5440.3 1924.45  5526.5 1930.14
#Mann= 4 ,-1 , 0
  4490.1      .1       0  4997.2     .07       0  5003.2      .1       0
  5363.8      .1       0
Bank Sta=4997.2,5003.2
XS Rating Curve= 0 ,0
Exp/Cntr=0.3,0.1

Type RM Length L Ch R = 1 ,3911    ,224,224,224
BEGIN DESCRIPTION:
UNT 1056 IN HEWA 9.0
END DESCRIPTION:
XS GIS Cut Line= 3
      2741417.92     10015373.12      2742190.47     10015472.94
      2742254.54      10015434.5
#Sta/Elev= 30
  4534.7 1900.98  4565.5 1897.67  4595.8 1895.97  4686.5 1883.68  4777.2 1879.74
  4837.7 1875.82  4886.9 1874.48  4928.5 1871.84  4948.7 1871.53  4958.7  1870.9
  4984.9 1867.27  4996.1 1865.51  4998.8 1865.01  5002.1 1865.51  5019.2 1873.73
  5029.3 1877.06  5045.6 1880.84  5089.8    1885  5119.9 1889.83  5124.9  1889.6
  5130.2 1891.12  5170.5 1897.41  5199.2 1900.72  5204.3 1900.34  5278.6 1914.34
  5283.6 1914.27  5340.9 1921.91  5348.1 1922.02  5362.3 1922.79  5388.4 1926.56
#Mann= 5 ,-1 , 0
  4534.7      .1       0  4984.9     .16       0  4996.1     .07       0
  5002.1     .16       0  5348.1      .1       0
Bank Sta=4996.1,5002.1
XS Rating Curve= 0 ,0
Exp/Cntr=0.3,0.1

Type RM Length L Ch R = 1 ,3687    ,436,436,436
BEGIN DESCRIPTION:
UNT 1056 IN HEWA 8.0
END DESCRIPTION:
XS GIS Cut Line= 3
      2741413.57     10015620.51       2742086.3     10015668.26
      2742372.76     10015525.03
#Sta/Elev= 30
  4573.4 1888.72  4618.4 1885.19  4648.5  1884.2  4798.9 1875.29  4839.3 1873.79
  4899.1 1871.52  4973.2 1867.38  4989.3 1863.53  4996.4 1862.77  4999.1 1862.27
  5002.4 1862.77  5029.4 1870.58  5039.5  1872.2    5109 1877.18    5114 1876.59
  5138.3 1878.05    5180 1882.01  5219.9 1889.13  5246.4 1895.13  5251.8 1895.13
  5268.1 1898.17    5296 1901.19  5312.8 1905.37  5328.5 1907.78  5335.2 1909.86
  5357.5 1914.06  5427.8  1921.1    5447 1923.82  5497.3 1927.07  5568.1 1927.36
#Mann= 7 ,-1 , 0
  4573.4      .1       0  4839.3     .16       0  4996.4     .07       0
  5002.4     .16       0  5138.3      .1       0    5180     .16       0
  5427.8      .1       0
Bank Sta=4996.4,5002.4
XS Rating Curve= 0 ,0
Exp/Cntr=0.3,0.1

Type RM Length L Ch R = 1 ,3251    ,426,426,426
BEGIN DESCRIPTION:
UNT 1056 IN HEWA 7.0
END DESCRIPTION:
XS GIS Cut Line= 3
      2741500.39     10015993.78      2741938.73     10016097.94
      2742363.79     10015772.64
#Sta/Elev= 30
  4686.6 1889.93  4777.1 1879.86  4793.5 1877.21  4835.7 1873.16    4883 1870.29
  4910.8 1866.65  4920.1  1864.3  4925.2  1864.7  4931.3 1862.04  4941.6 1860.23
  4982.7 1860.22  5000.3 1859.08    5003 1858.58  5006.3 1859.08    5094 1860.73
  5134.4 1859.29  5174.8 1859.67  5212.1 1860.57  5236.2 1862.49  5268.3 1866.12
  5297.3 1871.41  5411.6 1884.26  5496.8 1897.53  5561.2 1900.39  5567.5 1901.93
  5575.7 1902.07    5582 1903.91  5589.5 1903.85  5646.4 1907.17  5672.4 1907.08
#Mann= 5 ,-1 , 0
  4686.6      .1       0  5000.3     .07       0  5006.3      .1       0
  5236.2     .16       0  5589.5      .1       0
Bank Sta=5000.3,5006.3
XS Rating Curve= 0 ,0
Exp/Cntr=0.3,0.1

Type RM Length L Ch R = 1 ,2825    ,481,481,481
BEGIN DESCRIPTION:
UNT 1056 IN HEWA 6.0
END DESCRIPTION:
XS GIS Cut Line= 2
      2741506.39     10016383.53      2742461.26     10016390.48
#Sta/Elev= 30
  4537.7 1887.09  4541.3 1887.09  4559.8 1884.43  4579.8 1882.55  4599.8 1878.91
  4619.8  1876.5  4677.6 1866.87  4709.8 1861.15  4729.8  1858.2  4749.8 1856.25
  4839.8 1854.19  4869.8 1853.96  4929.8 1854.73  4979.8 1854.12  4996.8 1853.16
  4999.5 1852.66  5002.8 1853.16  5009.8 1854.74  5019.8 1859.69  5029.8 1862.72
  5039.8 1864.38  5089.8 1867.63  5248.6 1873.43  5286.2 1876.25  5359.8 1882.17
  5389.8    1884  5439.8 1889.52  5457.1 1890.92  5488.7 1894.01  5492.6 1894.01
#Mann= 6 ,-1 , 0
  4537.7     .16       0  4677.6      .1       0  4996.8     .07       0
  5002.8      .1       0  5286.2     .16       0  5457.1      .1       0
Bank Sta=4996.8,5002.8
XS Rating Curve= 0 ,0
Exp/Cntr=0.3,0.1

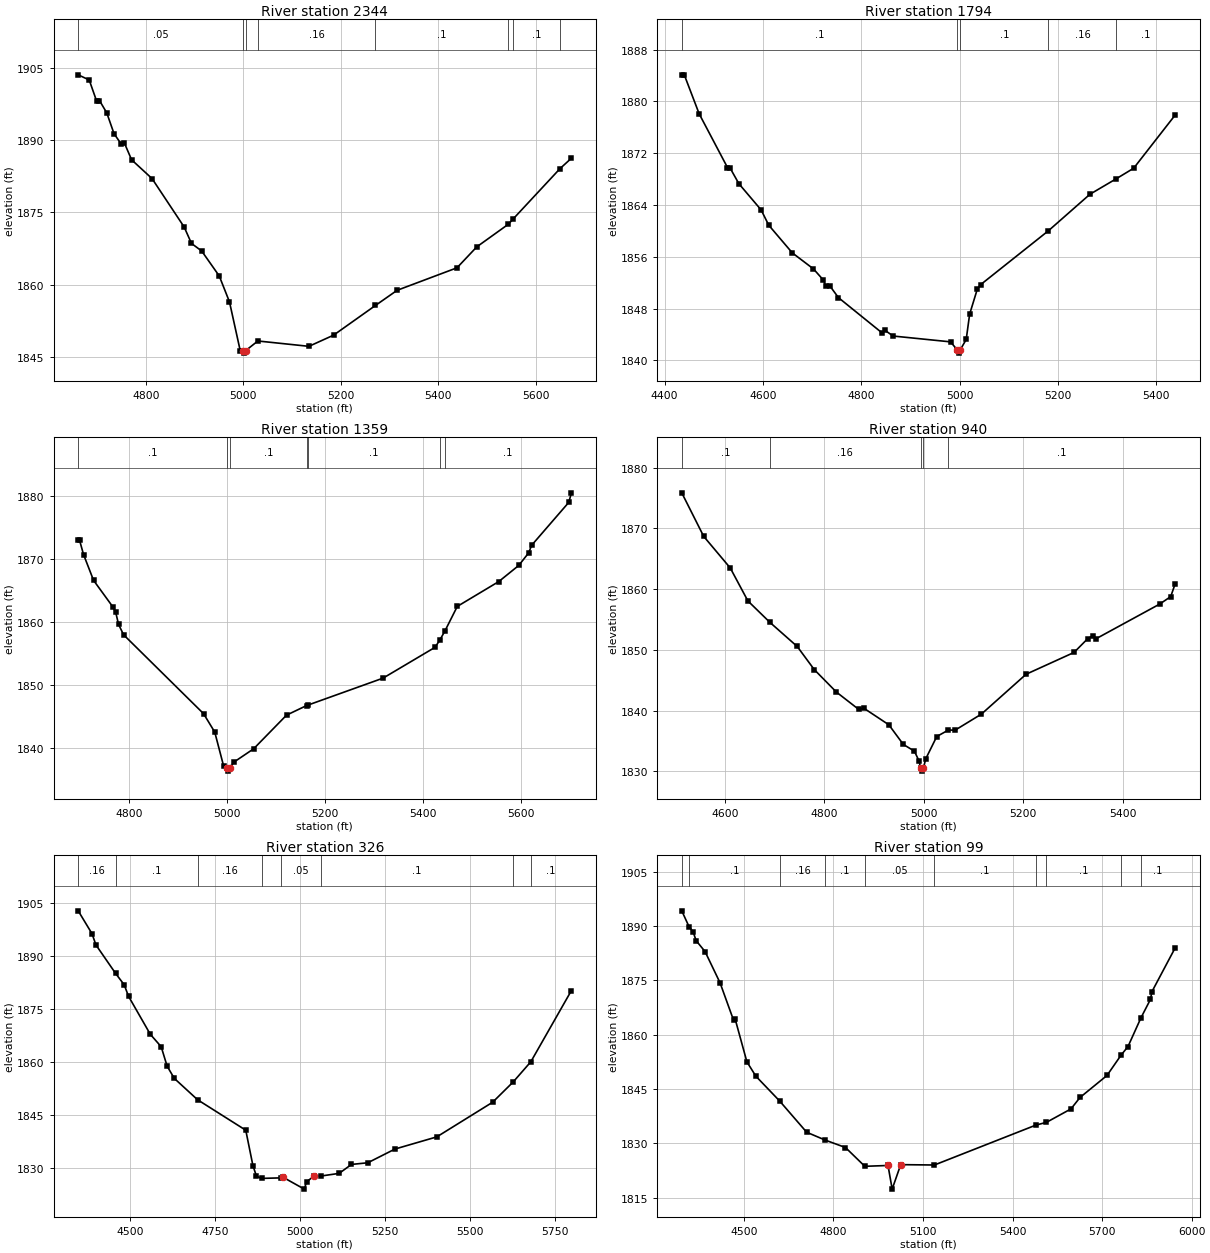
Type RM Length L Ch R = 1 ,2344    ,550,550,550
BEGIN DESCRIPTION:
UNT 1056 IN HEWA 5.0
END DESCRIPTION:
XS GIS Cut Line= 3
      2741423.14     10016557.17       2741798.1     10016810.62
      2742350.23      10016723.8
#Sta/Elev= 30
  4661.3 1903.56  4683.9 1902.49  4698.9 1898.16  4704.9 1898.23  4719.9 1895.66
  4734.8 1891.34  4749.8 1889.16  4755.8 1889.46  4770.8 1885.93  4812.8 1882.02
  4878.7 1871.96  4893.6 1868.57  4914.6 1866.99  4950.6 1861.81  4971.6 1856.42
  4993.6 1846.31  4998.5  1846.3  5001.3  1845.8  5004.5  1846.3  5029.8 1848.32
  5134.5 1847.21  5185.1 1849.53  5270.9 1855.69  5315.4 1858.84  5438.2 1863.51
  5478.7 1867.85  5543.6 1872.56  5553.4 1873.65  5649.6 1884.11  5672.8 1886.25
#Mann= 8 ,-1 , 0
  4661.3     .05       0  4998.5    .035       0  5004.5     .05       0
  5029.8     .16       0  5270.9      .1       0  5543.6     .16       0
  5553.4      .1       0  5649.6     .16       0
Bank Sta=4998.5,5004.5
XS Rating Curve= 0 ,0
Exp/Cntr=0.3,0.1

Type RM Length L Ch R = 1 ,1794    ,435,435,435
BEGIN DESCRIPTION:
UNT 1056 IN HEWA 4.0
END DESCRIPTION:
XS GIS Cut Line= 3
       2741433.5     10017154.36      2741728.66     10017199.51
      2742357.14     10016880.06
#Sta/Elev= 30
  4434.8 1884.09  4439.9 1884.09  4470.2 1878.07  4527.8 1869.78  4532.9 1869.73
  4551.1 1867.27  4596.3 1863.23  4611.8 1860.87  4659.7  1856.6  4702.8 1854.12
  4723.1 1852.39  4728.2 1851.42  4736.9 1851.42  4753.6 1849.69  4842.6 1844.23
  4848.2 1844.65  4864.8 1843.76  4981.7 1842.86  4995.4 1841.62  4998.1 1841.12
  5001.4 1841.62  5013.6 1843.23  5020.6 1847.14  5036.1 1850.98  5042.9 1851.69
    5181 1860.02  5265.4 1865.65  5319.1 1868.05  5354.4 1869.67  5438.4 1877.84
#Mann= 5 ,-1 , 0
  4434.8      .1       0  4995.4     .07       0  5001.4      .1       0
    5181     .16       0  5319.1      .1       0
Bank Sta=4995.4,5001.4
XS Rating Curve= 0 ,0
Exp/Cntr=0.3,0.1

Type RM Length L Ch R = 1 ,1359    ,419,419,419
BEGIN DESCRIPTION:
UNT 1056 IN HEWA 3.0
END DESCRIPTION:
XS GIS Cut Line= 2
      2741457.82     10017383.53      2742443.67     10017584.87
#Sta/Elev= 30
  4696.3 1872.95  4699.2 1872.95  4707.2 1870.72  4727.6 1866.63  4767.8 1862.33
  4772.9 1861.53  4778.6 1859.65  4788.8    1858  4952.1 1845.47  4974.9 1842.55
  4992.9 1837.19  5000.2 1836.86  5002.9 1836.36  5006.2 1836.86  5013.4 1837.76
  5054.2  1839.9  5121.3 1845.24  5162.5 1846.77  5164.4 1846.82  5318.2 1851.11
  5424.3    1856  5433.9 1857.13  5444.6 1858.61  5469.7 1862.49  5554.3 1866.43
  5595.1 1868.99  5615.5    1871  5621.2 1872.17  5697.2    1879  5702.5 1880.51
#Mann= 7 ,-1 , 0
  4696.3      .1       0  5000.2     .07       0  5006.2      .1       0
  5162.5     .16       0  5164.4      .1       0  5433.9     .05       0
  5444.6      .1       0
Bank Sta=5000.2,5006.2
XS Rating Curve= 0 ,0
Exp/Cntr=0.3,0.1

Type RM Length L Ch R = 1 ,940     ,614,614,614
BEGIN DESCRIPTION:
UNT 1056 IN HEWA 2.0
END DESCRIPTION:
XS GIS Cut Line= 2
      2741301.59     10017630.07      2742185.19     10018080.53
#Sta/Elev= 30
  4513.3 1875.87  4557.4  1868.7  4610.8  1863.5  4646.3 1858.07  4690.7 1854.53
  4745.5 1850.57  4779.7 1846.77  4824.2 1843.07    4869 1840.22  4879.6  1840.4
  4929.7 1837.68  4958.8 1834.45  4981.2 1833.33  4990.8 1831.65  4993.4 1830.55
  4996.2 1830.05  4999.4 1830.55  5003.7 1832.04  5026.1 1835.75  5049.4 1836.81
  5063.1  1836.8  5115.9 1839.44  5205.7    1846  5302.1 1849.59  5329.9 1851.88
  5340.4 1852.33  5346.5 1851.85  5474.3 1857.55  5496.5 1858.78  5505.1 1860.79
#Mann= 5 ,-1 , 0
  4513.3      .1       0  4690.7     .16       0  4993.4     .07       0
  4999.4     .16       0  5049.4      .1       0
Bank Sta=4993.4,4999.4
XS Rating Curve= 0 ,0
Exp/Cntr=0.3,0.1

Type RM Length L Ch R = 1 ,326     ,227,227,227
BEGIN DESCRIPTION:
Mapping XS 5c05392b
END DESCRIPTION:
XS GIS Cut Line= 3
      2741128.77     10017605.03      2741359.11     10018316.01
      2742044.04     10018473.66
#Sta/Elev= 30
    4348 1902.79  4388.7 1896.29  4400.1 1893.13    4458 1885.05  4483.3 1881.82
    4496 1878.57    4560  1867.8    4592 1864.28  4609.4 1858.78  4630.5 1855.31
    4699 1849.25  4840.7 1840.62  4861.7 1830.61  4872.2 1827.58  4887.2 1826.96
  4943.9 1827.11  4949.2 1827.34  5012.9 1823.92  5019.4 1825.99  5039.9  1827.5
  5061.4 1827.63  5115.2 1828.38  5151.6 1830.92  5199.5 1831.39  5279.4 1835.28
  5402.5 1838.73  5566.7 1848.55    5627 1854.29  5678.9 1860.01  5798.2 1880.19
#Mann= 8 ,-1 , 0
    4348     .16       0    4458      .1       0    4699     .16       0
  4887.2      .1       0  4943.9     .05       0  5061.4      .1       0
    5627     .05       0  5678.9      .1       0
Bank Sta=4949.2,5039.9
XS Rating Curve= 0 ,0
Exp/Cntr=0.3,0.1

Type RM Length L Ch R = 1 ,99      ,0,0,0
BEGIN DESCRIPTION:
UNT 1056 IN HEWA 1.0
END DESCRIPTION:
XS GIS Cut Line= 4
      2741047.16     10017675.75      2741068.93     10018276.11
       2741264.8     10018457.48      2742044.94     10018537.12
#Sta/Elev= 30
  4292.2 1894.23  4316.5 1889.86  4330.2 1888.44  4340.2 1886.01  4370.2 1882.98
  4420.3 1874.38  4465.8 1863.99  4470.8 1864.41  4510.3 1852.54  4540.3 1848.58
  4619.7 1841.75  4710.5  1833.1  4773.2 1830.91  4840.5 1828.88  4905.3 1823.69
    4983 1823.92  4996.9 1817.39  5025.5 1824.15  5138.4 1824.05  5477.7 1835.05
  5513.7 1835.83  5595.8 1839.54    5626 1842.69  5716.4 1848.77    5764 1854.43
  5786.8 1856.76  5830.2 1864.69  5861.8 1869.75  5867.2 1871.95  5944.1  1883.9
#Mann= 10 ,-1 , 0
  4292.2     .16       0  4316.5      .1       0  4619.7     .16       0
  4773.2      .1       0  4905.3     .05       0  5138.4      .1       0
  5477.7     .05       0  5513.7      .1       0    5764     .05       0
  5830.2      .1       0
Bank Sta=4983,5025.5
XS Rating Curve= 0 ,0
Exp/Cntr=0.3,0.1

Chan Stop Cuts=-1
Use User Specified Reach Order=0
Composite Channel Slope=5