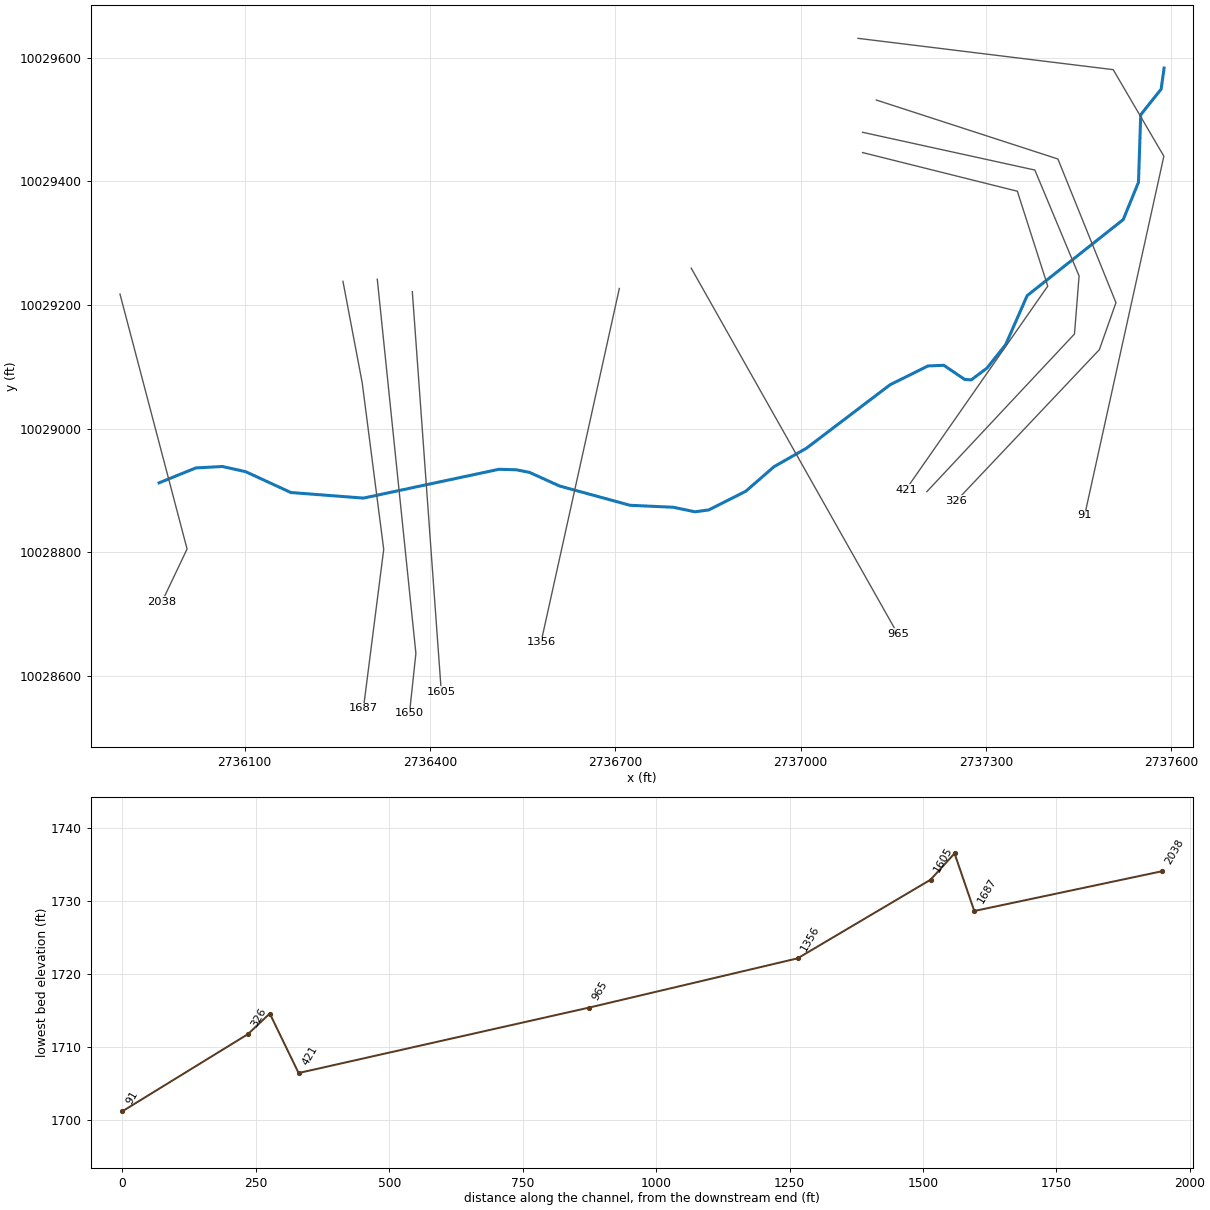
--- UNT 1057 IN HEWA.prj (project) ---

Proj Title=UNT 1057 IN HEWA Base Level Engineering
Current Plan=p01
Default Exp/Contr=0.3,0.1
English Units
Geom File=g01
Flow File=f01
Plan File=p01
Y Axis Title=Elevation
X Axis Title(PF)=Main Channel Distance
X Axis Title(XS)=Station
BEGIN DESCRIPTION:
UNT 1057 IN HEWA
END DESCRIPTION:
DSS Export Rating Curves= 0
DSS Export Rating Curve Sorted= 0
DSS Export Volume Flow Curves= 0
DXF OffsetX= 0
DXF OffsetY= 0
DXF ScaleX= 1
DXF ScaleY= 10

--- UNT 1057 IN HEWA.p01 (plan) ---

Plan Title=Multiple Run
Short Identifier=Multiple
Geom File=g01
Flow File=f01
Subcritical Flow
K Sum by GR= 0
Std Step Tol= 0.01
Critical Tol= 0.01
Num of Std Step Trials= 20
Max Error Tol= 0.3
Flow Tol Ratio= 0.001
Split Flow NTrial= 30
Split Flow Tol= 0.02
Split Flow Ratio= 0.02
Log Output Level= 0
Friction Slope Method= 1
Unsteady Friction Slope Method= 2
Unsteady Bridges Friction Slope Method= 1
Parabolic Critical Depth
Global Vel Dist=  1 , 1 , 1
Global Log Level= 0
CheckData=True
Encroach Param= -1, 0, 0, 0
BEGIN DESCRIPTION:
Multiple Run
END DESCRIPTION:

--- UNT 1057 IN HEWA.f01 (steady flow) ---

Flow Title=Multiple
Program Version=4.10
Number of Profiles= 7
Profile Names=10-year,25-year,50-year,1pct_min,100-year,1pct_plu,500-year
River Rch & RM=UNT 1057 IN HEWA,Reach-1         ,2038
     465     649     803     729     986    1334    1490
Boundary for River Rch & Prof#=UNT 1057 IN HEWA,Reach-1         , 1
Up Type= 0
Dn Type= 3
Dn Slope=0.005
Boundary for River Rch & Prof#=UNT 1057 IN HEWA,Reach-1         , 2
Up Type= 0
Dn Type= 3
Dn Slope=0.005
Boundary for River Rch & Prof#=UNT 1057 IN HEWA,Reach-1         , 3
Up Type= 0
Dn Type= 3
Dn Slope=0.005
Boundary for River Rch & Prof#=UNT 1057 IN HEWA,Reach-1         , 4
Up Type= 0
Dn Type= 3
Dn Slope=0.005
Boundary for River Rch & Prof#=UNT 1057 IN HEWA,Reach-1         , 5
Up Type= 0
Dn Type= 3
Dn Slope=0.005
Boundary for River Rch & Prof#=UNT 1057 IN HEWA,Reach-1         , 6
Up Type= 0
Dn Type= 3
Dn Slope=0.005
Boundary for River Rch & Prof#=UNT 1057 IN HEWA,Reach-1         , 7
Up Type= 0
Dn Type= 3
Dn Slope=0.005
DSS Import GetInterval= 0
DSS Import GetPeak= 0
DSS Import FillOption= 0

--- UNT 1057 IN HEWA.g01 (geometry) ---

Geom Title=Existing Conditions
Program Version=4.10

River Reach=UNT 1057 IN HEWA,Reach-1
Reach XY= 30
      2735961.65     10028912.05      2736021.22     10028936.18
      2736064.17     10028938.52      2736101.77     10028930.12
       2736175.1     10028896.36       2736292.6     10028887.33
      2736511.91       10028934.      2736539.58     10028933.21
      2736561.22       10028929.       2736609.8     10028906.95
      2736724.03     10028875.69      2736793.95     10028872.51
      2736828.95     10028865.13      2736851.33     10028868.12
       2736911.3     10028898.39      2736957.01     10028938.16
      2737009.65     10028968.18      2737144.89     10029070.85
      2737206.25     10029101.33      2737231.95     10029102.36
      2737265.61      10029079.5      2737276.29     10029078.75
      2737301.88     10029097.94      2737332.05     10029135.97
      2737366.82     10029215.23      2737522.34     10029338.36
      2737547.01     10029398.84      2737550.63     10029508.12
      2737583.62     10029549.46      2737588.47     10029583.73

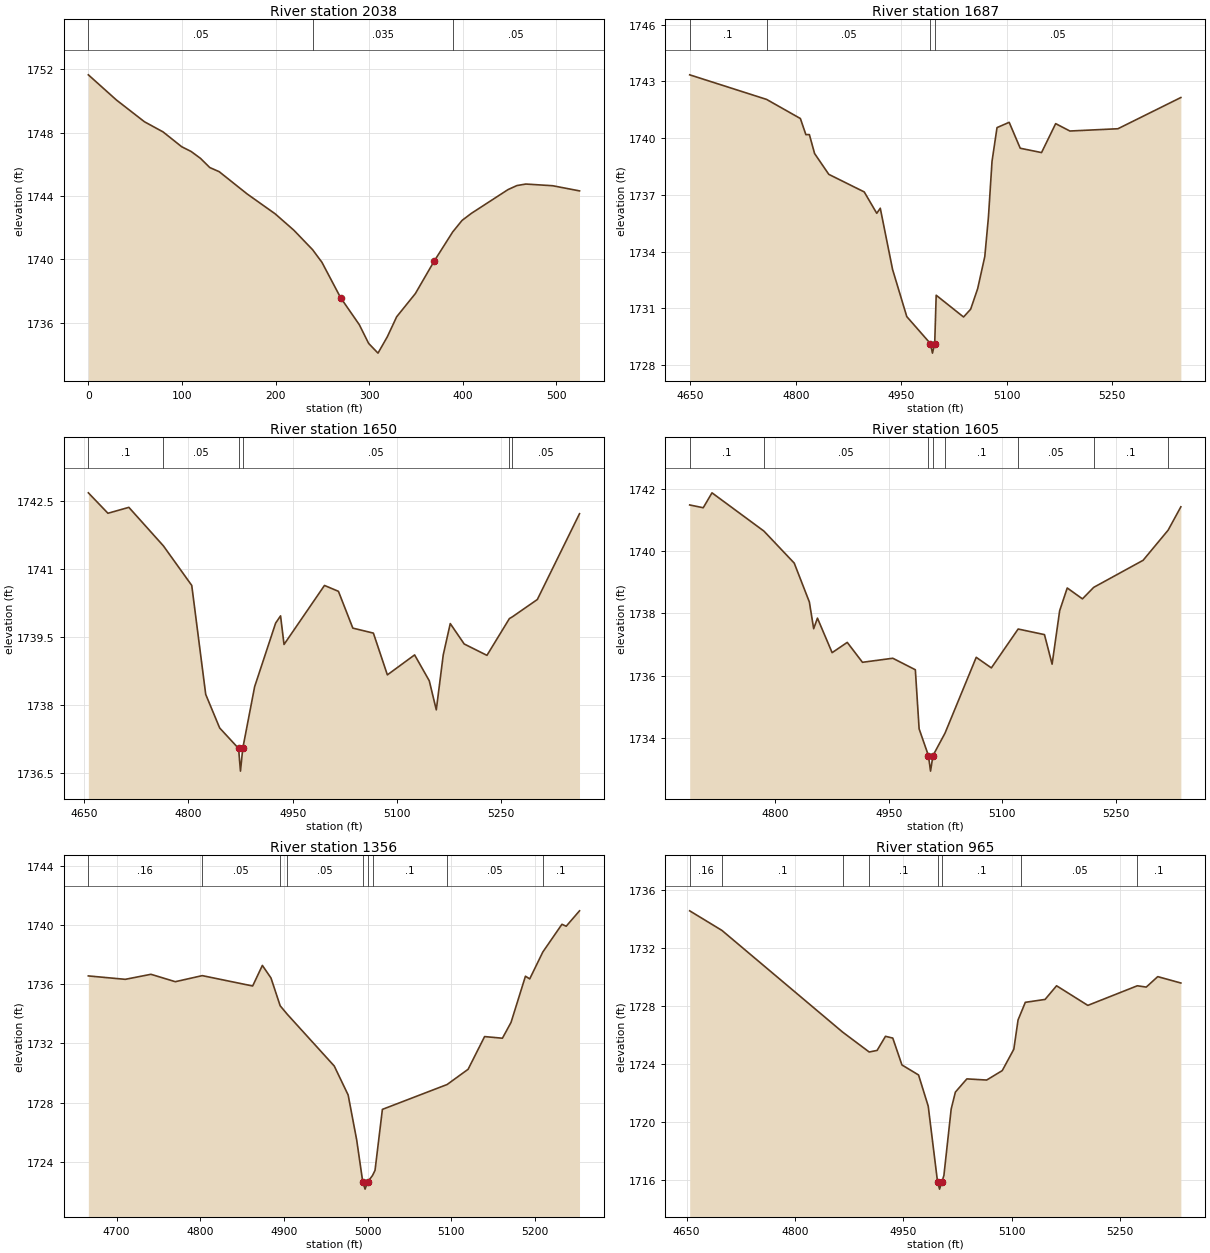
Type RM Length L Ch R = 1 ,2038    ,351,351,351
BEGIN DESCRIPTION:
UNT 1057 IN HEWA 4.0
END DESCRIPTION:
XS GIS Cut Line= 3
     2735898.399    10029217.708     2736007.002    10028804.874
     2735966.354    10028719.417
#Sta/Elev= 30
       01751.64929.943771750.06359.887541748.68979.850041748.04599.812561747.107
109.79381746.812119.77511746.378129.75631745.796139.73761745.538169.68141744.129
199.62511742.874219.5876 1741.84239.55011740.613249.53141739.818  269.491737.583
289.4564 1735.88299.43771734.697309.41891734.085319.40021735.119329.3814 1736.38
 349.3441737.844  369.311739.878 389.2691741.737399.25021742.462409.23151742.908
448.29521744.405457.84581744.661467.39631744.756496.04811744.649524.69981744.324
#Mann= 3 ,-1 , 0
       0     .05       0239.5501    .035       0 389.269     .05       0
Bank Sta=269.49,369.31
XS Rating Curve= 0 ,0
Exp/Cntr=0.3,0.1

Type RM Length L Ch R = 1 ,1687    ,37,37,37
BEGIN DESCRIPTION:
Mapping XS 7a0eb4d9
END DESCRIPTION:
XS GIS Cut Line= 4
      2736259.31     10029238.35      2736290.57      10029073.4
      2736325.29     10028804.31       2736292.5     10028547.19
#Sta/Elev= 30
  4649.1 1743.35  4758.5 1742.05  4806.5 1741.04  4814.3 1740.19  4819.3 1740.19
  4826.7 1739.19  4846.9 1738.09  4897.3 1737.16  4915.1 1736.03  4920.1  1736.3
  4937.6 1733.06  4957.8 1730.57  4991.5 1729.14  4994.3 1728.64  4997.5 1729.14
  4999.6  1731.7  5038.5 1730.55  5048.6 1730.96  5058.6 1732.05  5068.7 1733.74
  5073.9 1735.83    5079 1738.78  5086.1 1740.56  5103.4 1740.84  5119.1 1739.47
  5149.4 1739.24  5169.5 1740.77  5189.7 1740.38    5258  1740.5  5347.5 1742.15
#Mann= 4 ,-1 , 0
  4649.1      .1       0  4758.5     .05       0  4991.5    .035       0
  4997.5     .05       0
Bank Sta=4991.5,4997.5
XS Rating Curve= 0 ,0
Exp/Cntr=0.3,0.1

Type RM Length L Ch R = 1 ,1650    ,45,45,45
BEGIN DESCRIPTION:
Mapping XS f9938f18
END DESCRIPTION:
XS GIS Cut Line= 3
      2736314.87     10029241.77      2736377.37      10028635.9
      2736366.96     10028538.74
#Sta/Elev= 30
    4656 1742.67  4684.2 1742.22  4714.3 1742.35  4764.1  1741.5  4804.8 1740.63
  4824.9 1738.23    4845 1737.49  4872.2 1737.04  4874.9 1736.54  4878.2 1737.04
  4895.3  1738.4  4925.5  1739.8  4932.6 1739.96  4937.6 1739.33  4995.8 1740.63
  5015.9  1740.5  5036.6 1739.69  5066.2 1739.58  5086.3 1738.66  5125.5  1739.1
  5146.6 1738.53  5156.7 1737.89  5166.7  1739.1  5176.8 1739.79  5196.9 1739.34
  5229.6 1739.09  5261.9  1739.9  5266.3 1739.94  5302.1 1740.32  5362.8 1742.21
#Mann= 6 ,-1 , 0
    4656      .1       0  4764.1     .05       0  4872.2    .035       0
  4878.2     .05       0  5261.9      .1       0  5266.3     .05       0
Bank Sta=4872.2,4878.2
XS Rating Curve= 0 ,0
Exp/Cntr=0.3,0.1

Type RM Length L Ch R = 1 ,1605    ,249,249,249
BEGIN DESCRIPTION:
Mapping XS 6daed476
END DESCRIPTION:
XS GIS Cut Line= 2
      2736371.59     10029221.54      2736418.46     10028573.93
#Sta/Elev= 30
  4686.6 1741.49  4704.5  1741.4  4716.1 1741.88  4784.7 1740.65  4824.8 1739.62
  4844.8 1738.37  4850.5 1737.51  4855.5 1737.85  4874.9 1736.74  4894.9 1737.07
    4915 1736.43  4955.1 1736.56  4984.9 1736.19  4989.9 1734.29  5002.2 1733.43
    5005 1732.93  5008.2 1733.43  5024.1 1734.15  5065.4 1736.59  5085.4 1736.25
  5120.8  1737.5  5155.6 1737.32  5165.7 1736.37  5175.7 1738.09  5185.7 1738.82
  5205.8 1738.47  5220.7 1738.84    5286 1739.71  5319.1 1740.68  5335.9 1741.43
#Mann= 8 ,-1 , 0
  4686.6      .1       0  4784.7     .05       0  5002.2    .035       0
  5008.2     .05       0  5024.1      .1       0  5120.8     .05       0
  5220.7      .1       0  5319.1     .05       0
Bank Sta=5002.2,5008.2
XS Rating Curve= 0 ,0
Exp/Cntr=0.3,0.1

Type RM Length L Ch R = 1 ,1356    ,391,391,391
BEGIN DESCRIPTION:
UNT 1057 IN HEWA 3.0
END DESCRIPTION:
XS GIS Cut Line= 2
      2736706.66     10029226.77      2736579.92     10028653.82
#Sta/Elev= 30
  4666.3 1736.56  4710.4 1736.33  4741.1 1736.67  4770.2 1736.17  4802.4 1736.58
  4862.6 1735.88  4874.2 1737.27  4884.5 1736.42  4895.5 1734.54  4904.1 1733.96
  4960.1 1730.47  4976.7 1728.51  4986.9 1725.47  4994.1 1722.65  4996.9 1722.15
  5000.1 1722.65  5005.8 1723.07  5008.8 1723.42  5017.6 1727.54  5094.9 1729.22
    5120 1730.25  5139.7 1732.46    5161 1732.35  5171.3 1733.42  5188.5 1736.54
  5193.6 1736.36  5209.3 1738.18  5232.1 1740.05  5237.2 1739.92  5253.1 1740.96
#Mann= 9 ,-1 , 0
  4666.3     .16       0  4802.4     .05       0  4895.5      .1       0
  4904.1     .05       0  4994.1    .035       0  5000.1     .05       0
  5005.8      .1       0  5094.9     .05       0  5209.3      .1       0
Bank Sta=4994.1,5000.1
XS Rating Curve= 0 ,0
Exp/Cntr=0.3,0.1

Type RM Length L Ch R = 1 ,965     ,544,544,544
BEGIN DESCRIPTION:
UNT 1057 IN HEWA 2.0
END DESCRIPTION:
XS GIS Cut Line= 2
        2736823.     10029259.69      2737157.25      10028667.4
#Sta/Elev= 30
  4654.3 1734.55    4699  1733.2  4866.1  1726.2  4902.9 1724.83  4913.8 1724.94
  4925.4 1725.91  4935.5 1725.79  4948.2 1723.94  4971.2 1723.25  4984.6  1721.1
  4997.5 1715.89  5000.3 1715.39  5003.5 1715.89  5006.3 1716.33  5016.4 1720.91
  5022.2 1722.07  5038.1 1722.98  5065.5  1722.9  5087.1 1723.55  5103.1 1725.02
    5109 1727.04  5113.5 1727.58    5119 1728.25  5146.4 1728.45  5162.3 1729.39
  5205.6 1728.04  5274.1 1729.39  5286.5  1729.3  5302.4 1730.02  5334.4 1729.58
#Mann= 8 ,-1 , 0
  4654.3     .16       0    4699      .1       0  4866.1     .16       0
  4902.9      .1       0  4997.5     .07       0  5003.5      .1       0
  5113.5     .05       0  5274.1      .1       0
Bank Sta=4997.5,5003.5
XS Rating Curve= 0 ,0
Exp/Cntr=0.3,0.1

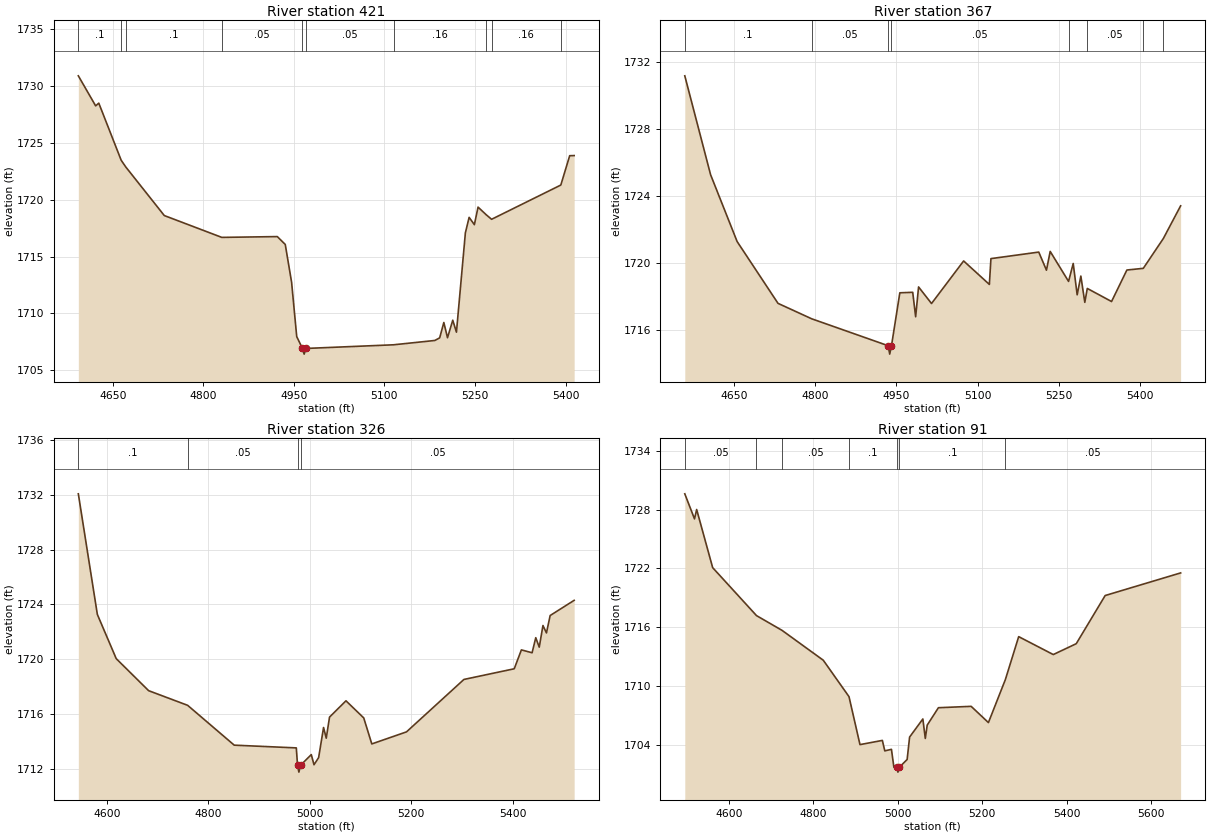
Type RM Length L Ch R = 1 ,421     ,54,54,54
BEGIN DESCRIPTION:
Mapping XS e8264c17
END DESCRIPTION:
XS GIS Cut Line= 4
      2737100.34     10029446.88      2737350.92     10029384.24
      2737400.14     10029230.61      2737170.43     10028900.96
#Sta/Elev= 30
  4592.9 1730.88  4621.6 1728.24  4626.8 1728.48  4663.9 1723.46  4671.5 1722.87
  4735.3  1718.6  4830.6 1716.68  4922.5 1716.75  4935.7 1716.06  4946.2 1712.74
  4954.7 1707.96  4964.2 1706.92    4967 1706.42  4970.2 1706.92  5115.1 1707.24
  5183.5 1707.62  5191.5 1707.85  5198.4  1709.2  5204.5 1707.86  5213.2  1709.4
  5219.3 1708.35  5234.1 1717.08  5240.3 1718.44    5249  1717.8  5255.1 1719.34
  5268.6 1718.67  5277.5 1718.27  5392.2 1721.28  5406.9 1723.86  5414.3 1723.87
#Mann= 10 ,-1 , 0
  4592.9      .1       0  4663.9     .16       0  4671.5      .1       0
  4830.6     .05       0  4964.2     .04       0  4970.2     .05       0
  5115.1     .16       0  5268.6     .05       0  5277.5     .16       0
  5392.2     .05       0
Bank Sta=4964.2,4970.2
XS Rating Curve= 0 ,0
Exp/Cntr=0.3,0.1

Type RM Length L Ch R = 1 ,367     ,41,41,41
BEGIN DESCRIPTION:
Mapping XS f355c98f
END DESCRIPTION:
XS GIS Cut Line= 5
      2737100.36     10029479.69      2737379.26     10029418.54
      2737450.85     10029247.02       2737443.4     10029153.05
      2737204.38     10028897.71
#Sta/Elev= 30
  4559.3 1731.19  4606.9 1725.29  4655.9  1721.3  4731.4 1717.61  4793.5 1716.69
  4934.9 1715.08  4937.6 1714.58  4940.9 1715.08  4956.3 1718.24  4980.1 1718.27
  4985.5 1716.81  4990.9 1718.59  5014.8  1717.6  5074.1 1720.14  5121.6 1718.74
  5124.5 1720.28  5212.8 1720.67    5227 1719.59  5233.9 1720.71  5267.8 1718.92
  5276.4 1719.99  5283.7 1718.12  5290.5 1719.24  5297.8 1717.67  5302.4  1718.5
  5347.2 1717.72  5375.5  1719.6  5405.8  1719.7  5442.8 1721.48  5474.7 1723.43
#Mann= 8 ,-1 , 0
  4559.3      .1       0  4793.5     .05       0  4934.9     .04       0
  4940.9     .05       0  5267.8     .16       0  5302.4     .05       0
  5405.8     .16       0  5442.8     .05       0
Bank Sta=4934.9,4940.9
XS Rating Curve= 0 ,0
Exp/Cntr=0.3,0.1

Type RM Length L Ch R = 1 ,326     ,235,235,235
BEGIN DESCRIPTION:
Mapping XS 76c5a2f7
END DESCRIPTION:
XS GIS Cut Line= 5
       2737122.7      10029531.9      2737416.55     10029436.44
      2737510.51     10029203.77      2737483.67      10029127.7
      2737252.25     10028882.94
#Sta/Elev= 30
  4543.9 1732.08  4581.4 1723.27  4618.6 1720.04  4682.5  1717.7  4759.4 1716.63
  4851.2 1713.72  4973.6 1713.52    4976 1712.25  4978.7 1711.75    4982 1712.25
  5003.1 1713.03  5008.5 1712.29  5017.6 1712.81  5027.3 1715.01  5032.6 1714.23
  5039.1 1715.77  5071.5 1716.96  5106.5 1715.71  5122.4 1713.81  5190.8 1714.69
    5304 1718.52  5403.2  1719.3  5417.3 1720.68  5438.4 1720.47  5445.6 1721.57
  5452.5 1720.88  5459.8 1722.46  5466.7 1721.92    5474 1723.19  5521.3  1724.3
#Mann= 4 ,-1 , 0
  4543.9      .1       0  4759.4     .05       0    4976     .04       0
    4982     .05       0
Bank Sta=4976,4982
XS Rating Curve= 0 ,0
Exp/Cntr=0.3,0.1

Type RM Length L Ch R = 1 ,91      ,0,0,0
BEGIN DESCRIPTION:
UNT 1057 IN HEWA 1.0
END DESCRIPTION:
XS GIS Cut Line= 4
      2737092.94     10029631.82      2737506.04     10029581.12
      2737588.07     10029440.92       2737459.8     10028859.23
#Sta/Elev= 30
  4495.7 1729.61  4518.7 1727.05  4523.8 1728.01  4561.7 1722.07  4665.5 1717.17
  4726.1 1715.66  4823.7 1712.61  4884.6 1708.89  4910.6 1703.99  4963.6 1704.42
  4969.4 1703.35  4985.1 1703.51  4990.9 1701.69  4997.8 1701.68  5000.5 1701.18
  5003.8 1701.68  5022.3 1702.47  5028.1 1704.76  5059.5 1706.61  5065.3 1704.62
  5069.8 1705.98  5096.4 1707.76  5173.9  1707.9  5214.8 1706.24  5254.9 1710.63
  5286.5 1715.02  5368.4 1713.19  5422.8  1714.3  5491.3 1719.22    5670 1721.53
#Mann= 7 ,-1 , 0
  4495.7     .05       0  4665.5      .1       0  4726.1     .05       0
  4884.6      .1       0  4997.8     .07       0  5003.8      .1       0
  5254.9     .05       0
Bank Sta=4997.8,5003.8
XS Rating Curve= 0 ,0
Exp/Cntr=0.3,0.1

Chan Stop Cuts=-1
Use User Specified Reach Order=0
Composite Channel Slope=5