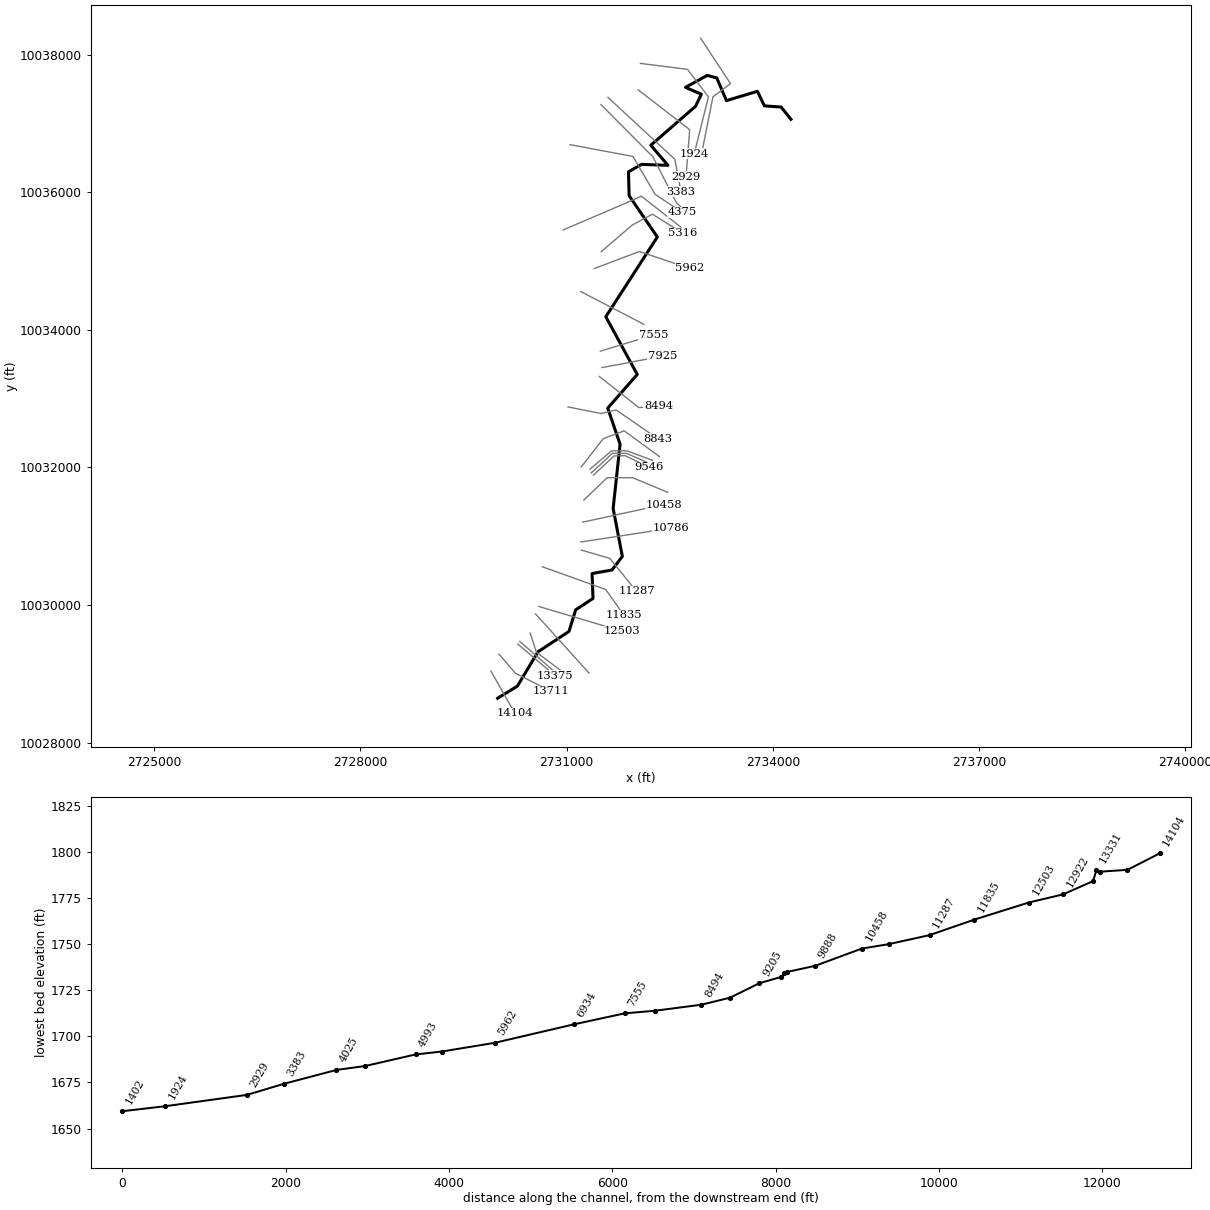
--- UNT 1058 IN HEWA.prj (project) ---

Proj Title=UNT 1058 IN HEWA Base Level Engineering
Current Plan=p01
Default Exp/Contr=0.3,0.1
English Units
Geom File=g01
Flow File=f01
Plan File=p01
Y Axis Title=Elevation
X Axis Title(PF)=Main Channel Distance
X Axis Title(XS)=Station
BEGIN DESCRIPTION:
UNT 1058 IN HEWA
END DESCRIPTION:
DSS Export Rating Curves= 0
DSS Export Rating Curve Sorted= 0
DSS Export Volume Flow Curves= 0
DXF OffsetX= 0
DXF OffsetY= 0
DXF ScaleX= 1
DXF ScaleY= 10

--- UNT 1058 IN HEWA.p01 (plan) ---

Plan Title=Multiple Run
Short Identifier=Multiple
Geom File=g01
Flow File=f01
Subcritical Flow
K Sum by GR= 0
Std Step Tol= 0.01
Critical Tol= 0.01
Num of Std Step Trials= 20
Max Error Tol= 0.3
Flow Tol Ratio= 0.001
Split Flow NTrial= 30
Split Flow Tol= 0.02
Split Flow Ratio= 0.02
Log Output Level= 0
Friction Slope Method= 1
Unsteady Friction Slope Method= 2
Unsteady Bridges Friction Slope Method= 1
Parabolic Critical Depth
Global Vel Dist=  1 , 1 , 1
Global Log Level= 0
CheckData=True
Encroach Param= -1, 0, 0, 0
BEGIN DESCRIPTION:
Multiple Run
END DESCRIPTION:

--- UNT 1058 IN HEWA.f01 (steady flow) ---

Flow Title=Multiple
Program Version=4.10
Number of Profiles= 7
Profile Names=10-year,25-year,50-year,1pct_min,100-year,1pct_plu,500-year
River Rch & RM=UNT 1058 IN HEWA,Reach-1         ,14104
     903    1313    1669    1552    2099    2839    3338
River Rch & RM=UNT 1058 IN HEWA,Reach-1         ,8843
    1509    2249    2907    2745    3712    5020    6083
River Rch & RM=UNT 1058 IN HEWA,Reach-1         ,4375
    1705    2551    3305    3126    4228    5718    6954
Boundary for River Rch & Prof#=UNT 1058 IN HEWA,Reach-1         , 1
Up Type= 0
Dn Type= 3
Dn Slope=0.006
Boundary for River Rch & Prof#=UNT 1058 IN HEWA,Reach-1         , 2
Up Type= 0
Dn Type= 3
Dn Slope=0.006
Boundary for River Rch & Prof#=UNT 1058 IN HEWA,Reach-1         , 3
Up Type= 0
Dn Type= 3
Dn Slope=0.006
Boundary for River Rch & Prof#=UNT 1058 IN HEWA,Reach-1         , 4
Up Type= 0
Dn Type= 3
Dn Slope=0.006
Boundary for River Rch & Prof#=UNT 1058 IN HEWA,Reach-1         , 5
Up Type= 0
Dn Type= 3
Dn Slope=0.006
Boundary for River Rch & Prof#=UNT 1058 IN HEWA,Reach-1         , 6
Up Type= 0
Dn Type= 3
Dn Slope=0.006
Boundary for River Rch & Prof#=UNT 1058 IN HEWA,Reach-1         , 7
Up Type= 0
Dn Type= 3
Dn Slope=0.006
DSS Import GetInterval= 0
DSS Import GetPeak= 0
DSS Import FillOption= 0

--- UNT 1058 IN HEWA.g01 (geometry) ---

Geom Title=Existing Conditions
Program Version=4.10

River Reach=UNT 1058 IN HEWA,Reach-1
Reach XY= 30
      2729998.47     10028643.73      2730285.23     10028820.18
      2730585.97     10029319.99      2731035.97     10029615.26
        2731133.     10029929.82      2731385.39     10030095.17
      2731372.09      10030457.4      2731661.05     10030508.93
      2731812.09     10030706.78      2731678.23     10031403.74
        2731779.     10032338.93      2731599.62     10032863.41
      2732028.83      10033353.6      2731571.51     10034192.67
      2732320.99     10035352.18      2731910.62     10035952.71
      2731901.35     10036300.34      2732090.95     10036408.35
      2732475.52       10036395.      2732226.01     10036687.31
      2732877.46     10037253.58      2732960.82     10037429.55
      2732730.22      10037528.5      2733047.45     10037703.09
      2733185.67     10037665.68      2733325.84     10037335.83
      2733777.41     10037471.58      2733877.86      10037259.6
      2734121.56     10037242.25      2734263.92     10037063.85

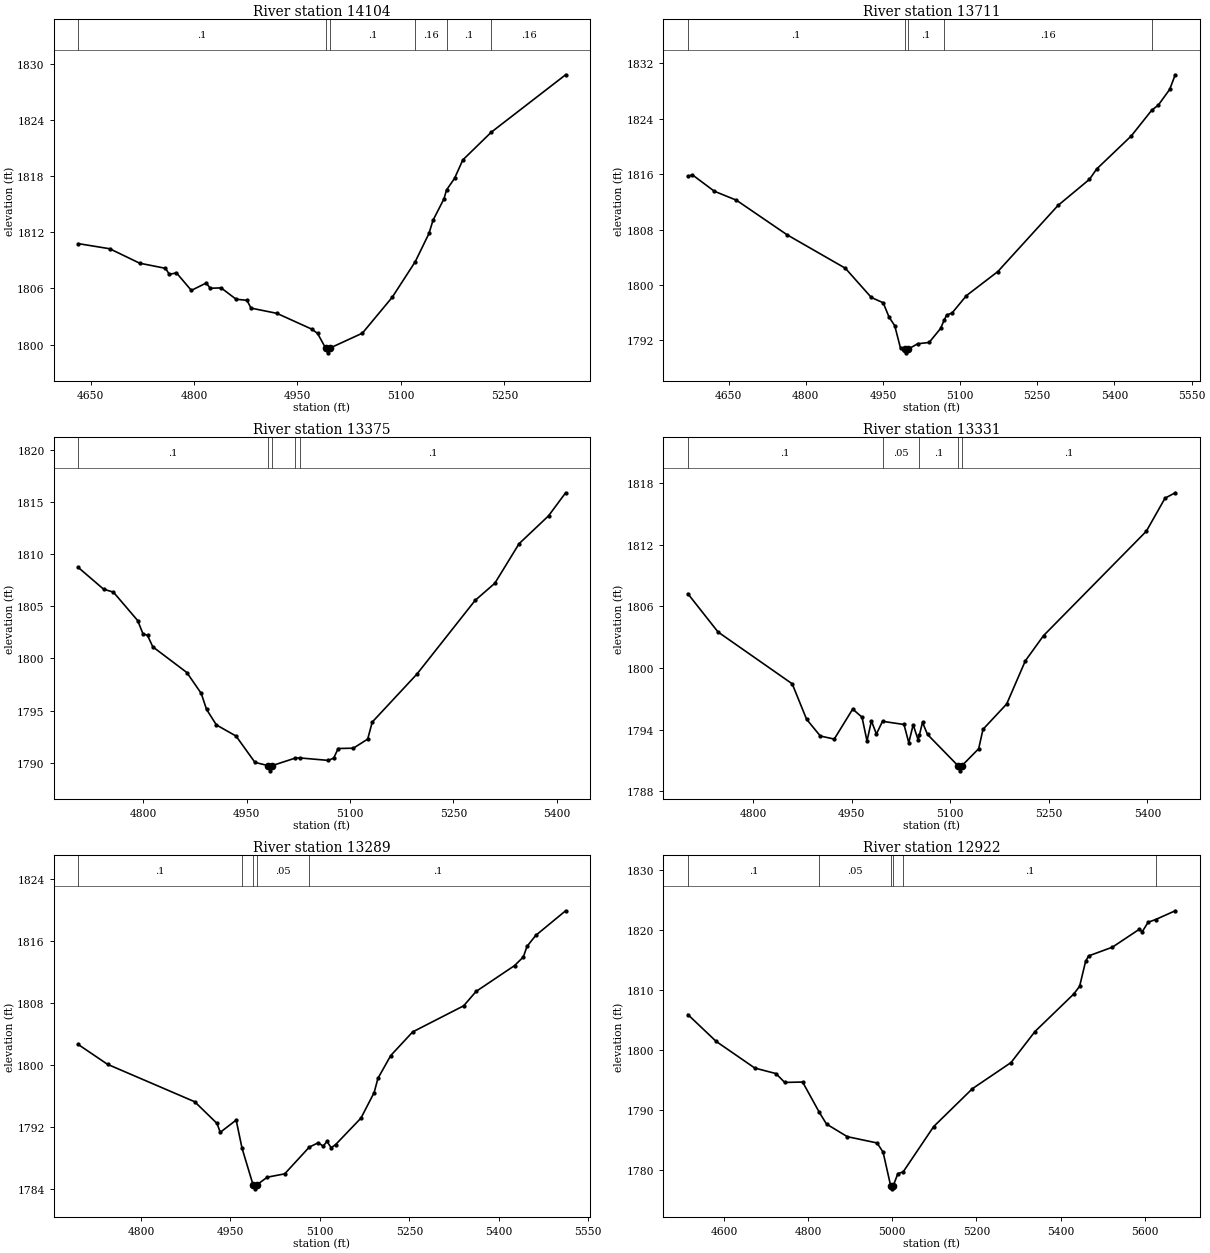
Type RM Length L Ch R = 1 ,14104   ,393,393,393
BEGIN DESCRIPTION:
UNT 1058 IN HEWA 28.0
END DESCRIPTION:
XS GIS Cut Line= 2
      2729900.75     10029038.27      2730249.69     10028423.72
#Sta/Elev= 30
  4632.1 1810.79  4677.8 1810.24  4721.1  1808.7  4758.6 1808.15  4764.3  1807.5
  4774.5 1807.67  4796.1 1805.79  4817.7 1806.58  4823.5 1806.02  4839.3 1806.06
    4861 1804.85  4876.8 1804.73  4882.6  1803.9  4920.1 1803.34  4970.8 1801.65
  4979.2 1801.19  4990.8 1799.62  4993.6 1799.12  4996.8 1799.62  5044.1 1801.22
  5087.4 1805.06  5120.7 1808.85  5140.7 1811.88  5146.5 1813.28  5162.4 1815.57
  5166.2 1816.53  5177.8 1817.77  5189.7 1819.73  5231.1  1822.7  5338.8 1828.83
#Mann= 6 ,-1 , 0
  4632.1      .1       0  4990.8     .07       0  4996.8      .1       0
  5120.7     .16       0  5166.2      .1       0  5231.1     .16       0
Bank Sta=4990.8,4996.8
XS Rating Curve= 0 ,0
Exp/Cntr=0.3,0.1

Type RM Length L Ch R = 1 ,13711   ,336,336,336
BEGIN DESCRIPTION:
Mapping XS 81387d46
END DESCRIPTION:
XS GIS Cut Line= 3
      2730017.97     10029285.62      2730257.52     10029007.01
       2730774.6     10028744.58
#Sta/Elev= 30
  4570.8  1815.7  4579.6 1815.92  4622.3 1813.55  4665.1 1812.26  4763.9 1807.25
  4876.9 1802.43  4927.4 1798.21  4950.5 1797.44  4961.9 1795.37  4972.9 1794.13
  4984.2 1790.87  4992.2 1790.71    4995 1790.21  4998.2 1790.71  5017.5 1791.52
  5039.8 1791.71    5062 1793.73  5068.9 1794.92  5073.9 1795.68  5084.3 1795.96
  5112.2 1798.47  5173.3 1801.95  5290.3  1811.5  5351.4 1815.27  5365.4 1816.76
  5432.7 1821.54  5472.6 1825.27    5485 1825.97  5507.3 1828.26  5518.1 1830.37
#Mann= 5 ,-1 , 0
  4570.8      .1       0  4992.2     .07       0  4998.2      .1       0
  5068.9     .16       0  5472.6      .1       0
Bank Sta=4992.2,4998.2
XS Rating Curve= 0 ,0
Exp/Cntr=0.3,0.1

Type RM Length L Ch R = 1 ,13375   ,44,44,44
BEGIN DESCRIPTION:
Mapping XS c8df630a
END DESCRIPTION:
XS GIS Cut Line= 2
      2730292.74     10029430.35      2730833.09     10028973.33
#Sta/Elev= 30
  4705.3 1808.72  4742.2 1806.63  4756.4 1806.35  4791.6 1803.63  4799.3 1802.36
  4805.9 1802.21  4813.6 1801.11    4863 1798.65  4883.9 1796.65  4891.6 1795.12
  4905.9 1793.63  4934.5 1792.56  4961.9 1790.04  4980.9 1789.73  4983.7 1789.23
  4986.9 1789.73  5019.4 1790.43  5026.6 1790.47  5068.5 1790.23  5076.2 1790.45
  5082.8 1791.37  5104.8  1791.4  5125.6 1792.27  5132.2  1793.9  5197.1  1798.5
  5281.6 1805.56  5310.2  1807.2  5345.4 1810.99  5388.2 1813.66    5413 1815.87
#Mann= 5 ,-1 , 0
  4705.3      .1       0  4980.9     .07       0  4986.9      .1       0
  5019.4     .05       0  5026.6      .1       0
Bank Sta=4980.9,4986.9
XS Rating Curve= 0 ,0
Exp/Cntr=0.3,0.1

Type RM Length L Ch R = 1 ,13331   ,42,42,42
BEGIN DESCRIPTION:
Mapping XS b3b2b040
END DESCRIPTION:
XS GIS Cut Line= 2
      2730320.65     10029470.58      2730879.47     10028982.28
#Sta/Elev= 30
  4700.4 1807.24  4746.4 1803.51  4859.3 1798.47  4881.2 1795.02  4902.1 1793.39
  4923.3 1793.09  4951.4 1796.01  4965.6 1795.22  4973.2  1792.9  4979.9 1794.86
  4987.5 1793.58  4996.8 1794.82  5029.5 1794.51  5036.8 1792.74  5043.5 1794.48
  5051.1    1793  5052.9 1793.47  5057.7 1794.72  5065.3 1793.54  5111.7  1790.5
  5114.4    1790  5117.7  1790.5  5143.2 1792.15  5149.8 1794.04  5185.9 1796.51
  5214.3 1800.71    5242 1803.16  5398.5 1813.32    5427 1816.54  5442.5 1817.06
#Mann= 5 ,-1 , 0
  4700.4      .1       0  4996.8     .05       0  5052.9      .1       0
  5111.7    .035       0  5117.7      .1       0
Bank Sta=5111.7,5117.7
XS Rating Curve= 0 ,0
Exp/Cntr=0.3,0.1

Type RM Length L Ch R = 1 ,13289   ,367,367,367
BEGIN DESCRIPTION:
UNT 1058 IN HEWA 27.0
END DESCRIPTION:
XS GIS Cut Line= 3
      2730472.46     10029590.45      2730560.99     10029314.45
      2730983.17     10028998.46
#Sta/Elev= 30
  4694.7 1802.66  4743.8 1800.11    4890 1795.29  4927.4  1792.5  4932.8 1791.35
  4959.5 1792.93  4969.4  1789.3  4987.9 1784.58  4990.6 1784.08  4993.9 1784.58
  5011.7 1785.58  5040.9 1786.01  5082.1 1789.45  5097.1 1790.01  5105.5 1789.57
  5111.7  1790.2  5118.8 1789.37  5126.3 1789.78  5168.8 1793.19  5190.9 1796.48
  5197.2  1798.3  5218.7 1801.24  5255.5 1804.28    5341 1807.64  5361.8 1809.49
  5426.4 1812.82    5441 1813.93  5447.2 1815.29  5461.8  1816.7  5511.9 1819.87
#Mann= 5 ,-1 , 0
  4694.7      .1       0  4969.4     .05       0  4987.9    .035       0
  4993.9     .05       0  5082.1      .1       0
Bank Sta=4987.9,4993.9
XS Rating Curve= 0 ,0
Exp/Cntr=0.3,0.1

Type RM Length L Ch R = 1 ,12922   ,419,419,419
BEGIN DESCRIPTION:
UNT 1058 IN HEWA 26.0
END DESCRIPTION:
XS GIS Cut Line= 2
      2730549.64      10029870.2      2731326.56     10029010.82
#Sta/Elev= 30
  4514.1 1805.95  4581.5 1801.47  4673.4 1797.03  4723.4 1796.12  4744.4 1794.64
  4786.9 1794.71  4826.6 1789.66  4843.7 1787.71  4893.1 1785.61    4964 1784.56
  4978.2 1783.02  4996.2 1777.42  4998.9 1776.92  5002.2 1777.42  5013.4 1779.47
  5025.8 1779.73  5098.5  1787.3  5190.5  1793.6  5282.4 1797.96  5339.2 1803.12
  5431.1 1809.35  5445.3 1810.65  5459.5 1814.79  5466.5 1815.71    5523 1817.16
  5587.2 1820.15    5594 1819.73  5608.2 1821.32  5625.9 1821.77  5672.6 1823.23
#Mann= 6 ,-1 , 0
  4514.1      .1       0  4826.6     .05       0  4996.2    .035       0
  5002.2     .05       0  5025.8      .1       0  5625.9     .05       0
Bank Sta=4996.2,5002.2
XS Rating Curve= 0 ,0
Exp/Cntr=0.3,0.1

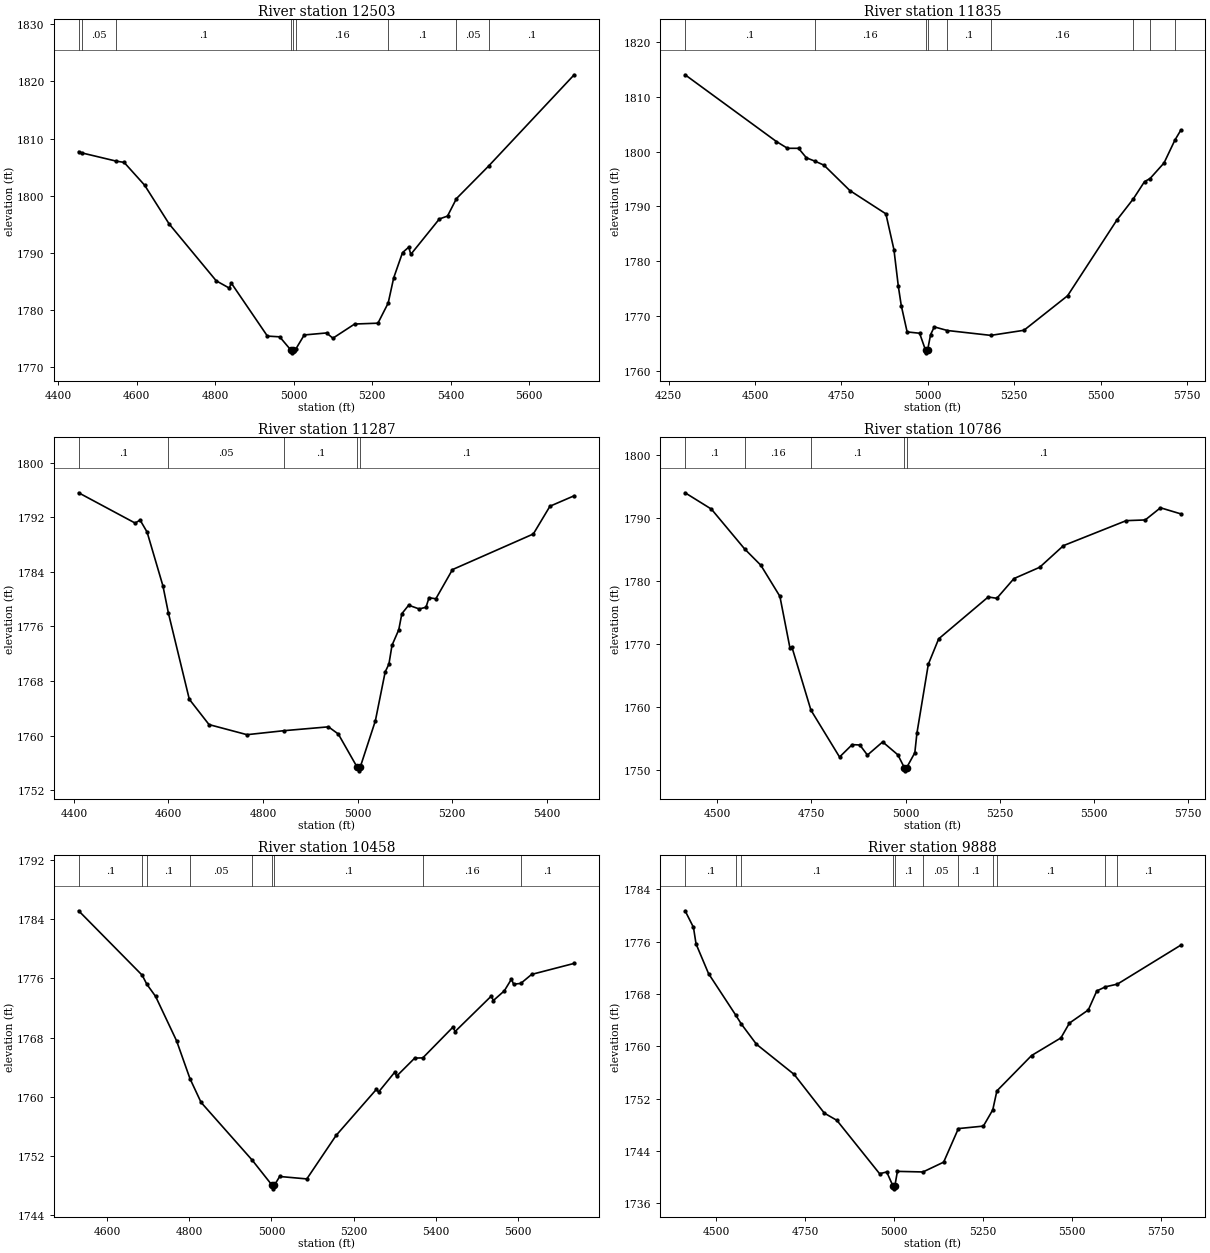
Type RM Length L Ch R = 1 ,12503   ,668,668,668
BEGIN DESCRIPTION:
UNT 1058 IN HEWA 25.0
END DESCRIPTION:
XS GIS Cut Line= 2
      2730597.38     10029978.73      2731807.85     10029618.62
#Sta/Elev= 30
  4451.7 1807.71  4461.1 1807.47    4547 1806.06  4567.6 1805.83  4619.8 1801.85
  4682.4 1795.06  4802.4 1785.11  4835.6 1783.84  4840.8 1784.71  4932.8 1775.44
  4964.1 1775.31  4992.4 1773.01  4995.1 1772.51  4998.4 1773.01  5005.2 1773.18
  5026.7 1775.64  5083.5 1775.99  5099.7 1775.07  5155.1 1777.55  5214.5  1777.7
  5240.6 1781.22  5254.6 1785.62  5277.1 1790.04    5293    1791  5298.3 1789.74
    5371 1795.93  5391.8 1796.44  5414.6  1799.5  5496.4 1805.18  5714.6 1821.16
#Mann= 9 ,-1 , 0
  4451.7      .1       0  4461.1     .05       0    4547      .1       0
  4992.4     .07       0  4998.4      .1       0  5005.2     .16       0
  5240.6      .1       0  5414.6     .05       0  5496.4      .1       0
Bank Sta=4992.4,4998.4
XS Rating Curve= 0 ,0
Exp/Cntr=0.3,0.1

Type RM Length L Ch R = 1 ,11835   ,548,548,548
BEGIN DESCRIPTION:
UNT 1058 IN HEWA 24.0
END DESCRIPTION:
XS GIS Cut Line= 3
      2730649.44     10030555.99      2731569.59     10030226.13
      2731833.93     10029853.45
#Sta/Elev= 30
  4297.4 1814.03  4561.9 1801.83  4593.8  1800.6  4625.7  1800.6  4648.6 1798.86
  4673.6 1798.24  4699.4 1797.52  4774.4 1792.88  4878.6 1788.63  4901.9  1782.1
  4914.7 1775.36  4923.1 1771.88  4940.1 1767.06  4976.2 1766.82  4993.3 1763.74
  4996.1 1763.24  4999.3 1763.74  5008.1 1766.58  5018.7 1767.98  5056.6 1767.32
  5182.2 1766.43  5278.2 1767.36  5404.6 1773.67  5547.5 1787.52  5594.9 1791.37
  5627.3 1794.52  5643.2 1795.07  5683.8 1797.93  5715.2  1802.1  5731.8 1803.86
#Mann= 9 ,-1 , 0
  4297.4      .1       0  4673.6     .16       0  4993.3     .07       0
  4999.3     .16       0  5056.6      .1       0  5182.2     .16       0
  5594.9      .1       0  5643.2     .05       0  5715.2      .1       0
Bank Sta=4993.3,4999.3
XS Rating Curve= 0 ,0
Exp/Cntr=0.3,0.1

Type RM Length L Ch R = 1 ,11287   ,501,501,501
BEGIN DESCRIPTION:
UNT 1058 IN HEWA 23.0
END DESCRIPTION:
XS GIS Cut Line= 3
       2731213.7     10030799.04      2731630.35     10030677.52
      2732016.61     10030200.12
#Sta/Elev= 30
    4410 1795.59  4529.5 1791.15    4540 1791.59  4554.8 1789.83  4588.3 1781.94
    4600 1777.92  4644.1 1765.32  4685.8 1761.61  4766.1 1760.13  4844.8 1760.72
  4938.4 1761.28  4959.2 1760.23  4999.4 1755.33  5002.1 1754.83  5005.4 1755.33
  5037.6 1762.16  5058.4 1769.34  5066.3 1770.48  5072.8 1773.23  5087.1 1775.51
  5093.6 1777.86    5108 1779.11  5130.3 1778.56  5144.7 1778.81  5151.1 1780.21
  5165.5 1780.05  5200.7 1784.33  5371.7 1789.55  5406.9 1793.62  5458.1 1795.15
#Mann= 5 ,-1 , 0
    4410      .1       0    4600     .05       0  4844.8      .1       0
  4999.4     .07       0  5005.4      .1       0
Bank Sta=4999.4,5005.4
XS Rating Curve= 0 ,0
Exp/Cntr=0.3,0.1

Type RM Length L Ch R = 1 ,10786   ,328,328,328
BEGIN DESCRIPTION:
UNT 1058 IN HEWA 22.0
END DESCRIPTION:
XS GIS Cut Line= 2
      2731209.38     10030916.24      2732511.46     10031115.89
#Sta/Elev= 30
    4414 1794.05  4483.9 1791.46  4572.4 1785.13  4615.4 1782.55    4666 1777.62
  4692.8 1769.41  4697.9 1769.59  4748.5 1759.57  4824.6 1752.13  4858.2  1754.1
  4878.5 1754.04  4898.7 1752.44  4939.2 1754.53  4979.6 1752.48  4996.9 1750.44
  4999.6 1749.94  5002.9 1750.44  5024.7 1752.81  5030.2 1755.89  5060.6 1766.86
  5088.1 1770.88  5219.8 1777.52  5242.7 1777.31  5288.2 1780.44  5356.6 1782.23
  5419.9 1785.67  5586.6 1789.63  5637.2 1789.74  5677.7 1791.67  5731.3 1790.71
#Mann= 5 ,-1 , 0
    4414      .1       0  4572.4     .16       0  4748.5      .1       0
  4996.9     .07       0  5002.9      .1       0
Bank Sta=4996.9,5002.9
XS Rating Curve= 0 ,0
Exp/Cntr=0.3,0.1

Type RM Length L Ch R = 1 ,10458   ,570,570,570
BEGIN DESCRIPTION:
UNT 1058 IN HEWA 21.0
END DESCRIPTION:
XS GIS Cut Line= 2
      2731235.36     10031204.85      2732414.73     10031460.67
#Sta/Elev= 30
  4530.4 1785.14  4685.2 1776.43  4696.5 1775.21  4717.8 1773.57  4768.9 1767.57
  4801.5 1762.46  4828.5 1759.25  4953.4 1751.42  5001.3 1748.06    5004 1747.56
  5007.3 1748.06    5020 1749.23  5086.1  1748.9  5157.3 1754.77  5255.6 1761.01
  5260.8 1760.64  5299.7 1763.29  5304.8 1762.79  5348.9 1765.23  5368.6 1765.26
  5442.1 1769.42  5447.2 1768.82  5535.3 1773.61  5540.4 1773.01  5567.1 1774.32
  5584.5 1775.91  5589.6 1775.22  5607.1 1775.32  5633.6 1776.54  5737.2 1778.03
#Mann= 9 ,-1 , 0
  4530.4      .1       0  4685.2     .16       0  4696.5      .1       0
  4801.5     .05       0  4953.4      .1       0  5001.3     .07       0
  5007.3      .1       0  5368.6     .16       0  5607.1      .1       0
Bank Sta=5001.3,5007.3
XS Rating Curve= 0 ,0
Exp/Cntr=0.3,0.1

Type RM Length L Ch R = 1 ,9888    ,342,342,342
BEGIN DESCRIPTION:
UNT 1058 IN HEWA 20.0
END DESCRIPTION:
XS GIS Cut Line= 4
      2731252.73     10031526.02      2731591.29     10031851.56
      2731960.21     10031851.56      2732472.41     10031638.87
#Sta/Elev= 30
  4413.2 1780.73  4436.7  1778.2    4444 1775.66  4479.2 1771.12  4555.6 1764.78
  4571.3 1763.42  4613.8 1760.33  4719.8 1755.72  4804.7  1749.8  4839.9  1748.7
  4960.1 1740.54  4980.1 1740.81  4997.1 1738.73  4999.8 1738.23  5003.1 1738.73
  5010.1  1740.9    5082 1740.81  5140.1 1742.31  5181.5 1747.44  5251.8 1747.82
  5278.2  1750.3  5289.8  1753.2  5387.4 1758.61  5469.8  1761.3  5493.7 1763.56
  5546.8 1765.57  5570.7 1768.48  5595.1 1769.11  5628.6 1769.52  5806.4 1775.46
#Mann= 11 ,-1 , 0
  4413.2      .1       0  4555.6     .05       0  4571.3      .1       0
  4997.1     .07       0  5003.1      .1       0    5082     .05       0
  5181.5      .1       0  5278.2     .05       0  5289.8      .1       0
  5595.1     .05       0  5628.6      .1       0
Bank Sta=4997.1,5003.1
XS Rating Curve= 0 ,0
Exp/Cntr=0.3,0.1

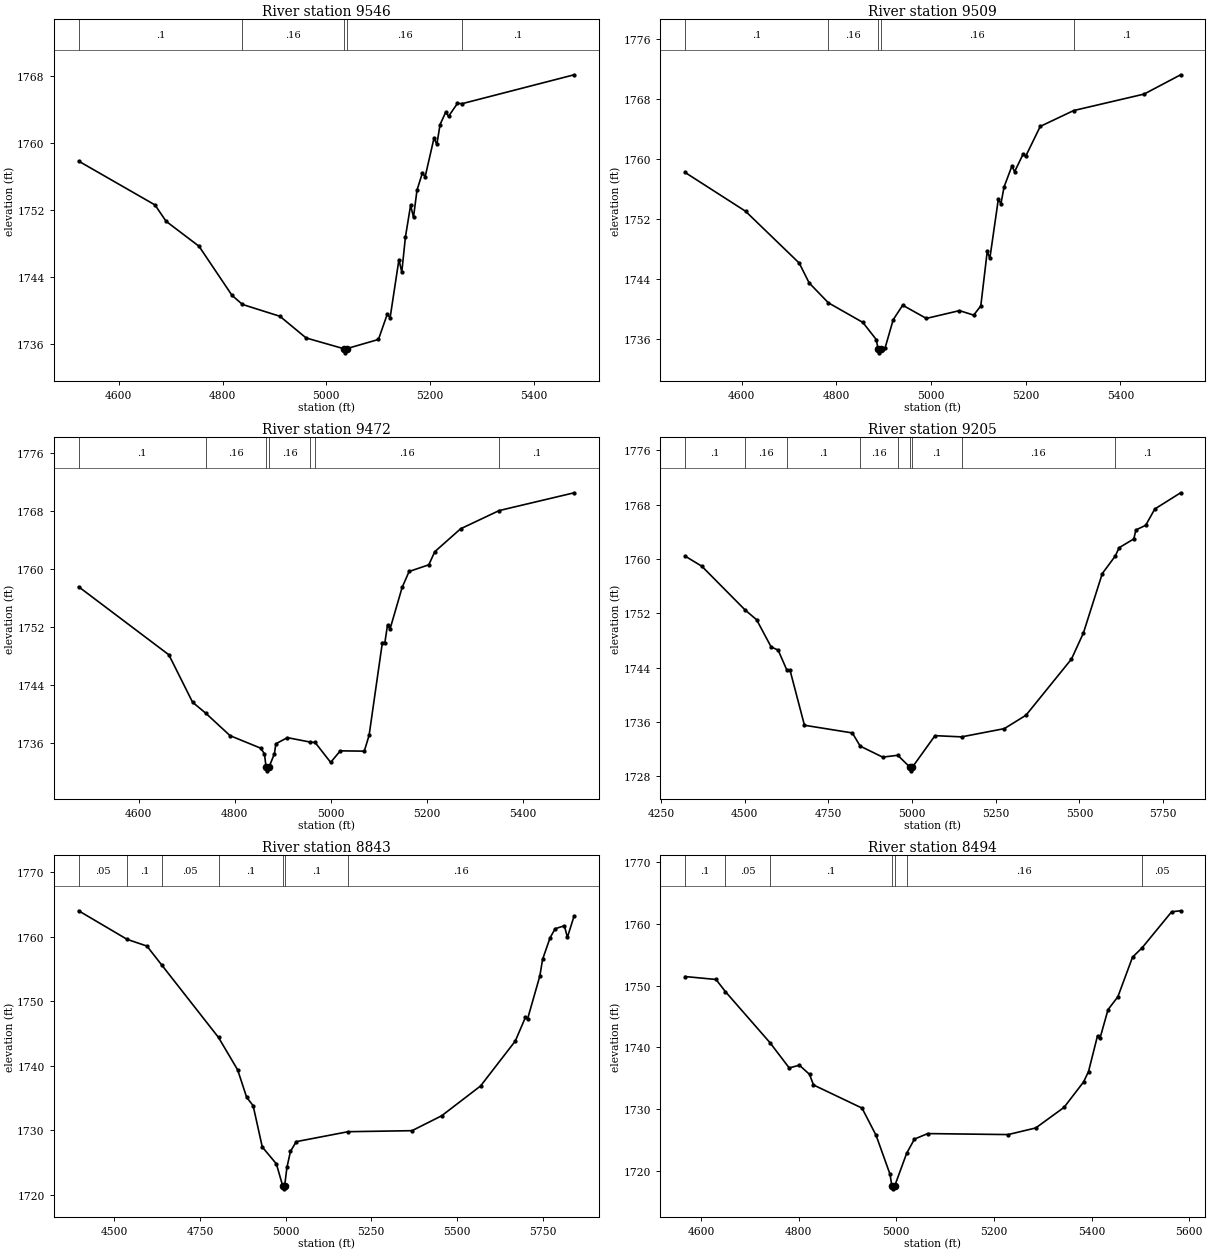
Type RM Length L Ch R = 1 ,9546    ,37,37,37
BEGIN DESCRIPTION:
Mapping XS a4f721df
END DESCRIPTION:
XS GIS Cut Line= 4
      2731392.91     10031891.27      2731692.96      10032167.9
       2731852.5     10032172.29      2732200.82     10032002.52
#Sta/Elev= 30
  4522.6 1757.85  4669.7 1752.61  4691.2 1750.65  4754.7 1747.66  4818.2 1741.79
  4838.4  1740.7  4910.7 1739.28  4961.1 1736.69  5033.3 1735.41    5036 1734.91
  5039.3 1735.41  5100.5 1736.51  5117.4 1739.51    5123 1739.11    5140 1746.06
  5145.5 1744.57  5152.6  1748.8  5162.5 1752.56  5168.1 1751.13  5174.8 1754.37
  5185.1 1756.41  5190.6 1755.99  5207.6  1760.6  5213.1 1759.85  5219.3 1762.23
  5230.1 1763.69  5235.7 1763.21  5252.7 1764.75  5262.2 1764.73  5477.8 1768.18
#Mann= 5 ,-1 , 0
  4522.6      .1       0  4838.4     .16       0  5033.3     .07       0
  5039.3     .16       0  5262.2      .1       0
Bank Sta=5033.3,5039.3
XS Rating Curve= 0 ,0
Exp/Cntr=0.3,0.1

Type RM Length L Ch R = 1 ,9509    ,37,37,37
BEGIN DESCRIPTION:
Mapping XS 0b754f82
END DESCRIPTION:
XS GIS Cut Line= 4
      2731360.41     10031921.46      2731668.98      10032206.6
      2731873.41     10032205.29      2732260.12     10032036.03
#Sta/Elev= 30
  4480.6 1758.18  4608.2 1753.02  4721.6 1746.12  4742.6 1743.48  4783.2 1740.83
    4856 1738.22  4884.4 1735.94  4888.2 1734.67  4890.9 1734.17  4894.2 1734.67
    4903 1734.82  4920.2 1738.58  4940.2 1740.51  4990.2 1738.75  5060.2 1739.79
  5090.2 1739.19  5105.2 1740.42  5118.8 1747.68  5124.3 1746.75  5142.2  1754.6
  5147.7 1754.01  5154.4 1756.26  5171.1 1759.06  5176.5 1758.27  5194.5 1760.61
  5199.9 1760.32  5230.8 1764.31  5301.4 1766.42  5450.1 1768.61  5527.3 1771.18
#Mann= 5 ,-1 , 0
  4480.6      .1       0  4783.2     .16       0  4888.2     .07       0
  4894.2     .16       0  5301.4      .1       0
Bank Sta=4888.2,4894.2
XS Rating Curve= 0 ,0
Exp/Cntr=0.3,0.1

Type RM Length L Ch R = 1 ,9472    ,267,267,267
BEGIN DESCRIPTION:
UNT 1058 IN HEWA 19.0
END DESCRIPTION:
XS GIS Cut Line= 4
      2731341.71     10031976.19      2731656.37     10032242.55
      2731878.84     10032242.55      2732250.57     10032104.98
#Sta/Elev= 30
  4474.9 1757.53  4662.6 1748.17    4712 1741.64  4738.9 1740.16    4790 1737.04
  4853.7 1735.32  4861.5 1734.54    4865  1732.7  4867.8  1732.2    4871  1732.7
  4882.3 1734.56  4885.3 1735.92  4909.3 1736.77  4956.4 1736.16    4967  1736.1
  4999.3 1733.36  5019.3 1734.95  5069.3 1734.91  5079.3 1737.09  5106.9 1749.85
  5112.1 1749.85  5117.6 1752.25  5122.9 1751.72    5148 1757.43  5162.5 1759.63
  5203.5 1760.55  5215.9 1762.35  5269.6  1765.5  5349.8 1768.01    5506 1770.46
#Mann= 7 ,-1 , 0
  4474.9      .1       0  4738.9     .16       0    4865     .07       0
    4871     .16       0  4956.4      .1       0    4967     .16       0
  5349.8      .1       0
Bank Sta=4865,4871
XS Rating Curve= 0 ,0
Exp/Cntr=0.3,0.1

Type RM Length L Ch R = 1 ,9205    ,362,362,362
BEGIN DESCRIPTION:
UNT 1058 IN HEWA 18.0
END DESCRIPTION:
XS GIS Cut Line= 4
      2731213.98     10032007.81      2731535.16     10032420.14
      2731838.98     10032532.98      2732351.13     10032159.72
#Sta/Elev= 30
  4321.7 1760.43  4371.6 1758.94  4501.4 1752.48  4535.4 1751.06  4578.8 1747.05
  4599.6  1746.6  4625.1 1743.72  4634.9 1743.68  4678.3 1735.53  4821.3  1734.4
  4844.8 1732.46  4911.9 1730.84  4957.1 1731.11  4994.2 1729.32    4997 1728.82
  5000.2 1729.32  5068.3    1734  5147.6 1733.82  5275.3 1735.03  5340.2 1737.01
  5476.1 1745.28  5511.7 1749.11  5568.1 1757.86  5606.9 1760.44  5618.3 1761.66
  5662.3 1762.96  5668.5 1764.27  5697.9 1764.97  5724.9 1767.36  5802.2 1769.75
#Mann= 9 ,-1 , 0
  4321.7      .1       0  4501.4     .16       0  4625.1      .1       0
  4844.8     .16       0  4957.1      .1       0  4994.2     .07       0
  5000.2      .1       0  5147.6     .16       0  5606.9      .1       0
Bank Sta=4994.2,5000.2
XS Rating Curve= 0 ,0
Exp/Cntr=0.3,0.1

Type RM Length L Ch R = 1 ,8843    ,349,349,349
BEGIN DESCRIPTION:
UNT 1058 IN HEWA 17.0
END DESCRIPTION:
XS GIS Cut Line= 4
      2731022.98     10032880.21      2731504.77     10032784.72
      2731721.79      10032836.8      2732324.31     10032420.67
#Sta/Elev= 30
  4395.8 1764.04  4537.3 1759.61  4595.1 1758.57  4638.7 1755.61  4804.2 1744.39
  4860.1 1739.36  4886.3 1735.11  4905.2 1733.82  4931.9 1727.41    4973  1724.8
  4991.3 1721.42  4994.1 1720.92  4997.3 1721.42  5003.9 1724.25  5014.2 1726.73
  5031.2 1728.24  5182.4 1729.78  5369.1 1729.94  5455.6 1732.25  5569.1 1736.87
  5670.5 1743.84  5700.3 1747.54  5706.4 1747.27  5742.2 1753.93  5750.2 1756.51
  5771.9 1759.83  5786.7 1761.25  5813.8 1761.72  5822.6 1759.92  5842.4 1763.26
#Mann= 7 ,-1 , 0
  4395.8     .05       0  4537.3      .1       0  4638.7     .05       0
  4804.2      .1       0  4991.3     .07       0  4997.3      .1       0
  5182.4     .16       0
Bank Sta=4991.3,4997.3
XS Rating Curve= 0 ,0
Exp/Cntr=0.3,0.1

Type RM Length L Ch R = 1 ,8494    ,569,569,569
BEGIN DESCRIPTION:
UNT 1058 IN HEWA 16.0
END DESCRIPTION:
XS GIS Cut Line= 3
      2731478.74     10033322.91      2732051.65     10032871.53
      2732336.86     10032888.81
#Sta/Elev= 30
  4567.3 1751.45  4630.6 1750.98  4649.9 1749.01    4741 1740.78  4780.6 1736.68
  4801.4 1737.12  4822.2 1735.64  4830.3 1733.93  4929.7 1730.19  4958.5 1725.79
  4987.1 1719.49  4990.8 1717.64  4993.6 1717.14  4996.8 1717.64  5021.1 1722.87
  5037.1 1725.18  5064.3 1726.07    5229 1725.91  5285.6 1726.98  5343.6 1730.31
  5383.6 1734.42  5393.7  1736.1  5412.2  1741.9  5417.2 1741.48  5433.7 1746.11
  5453.8 1748.18  5483.8 1754.57  5503.7 1756.12    5564 1761.92  5582.4 1762.08
#Mann= 7 ,-1 , 0
  4567.3      .1       0  4649.9     .05       0    4741      .1       0
  4990.8     .07       0  4996.8      .1       0  5021.1     .16       0
  5503.7     .05       0
Bank Sta=4990.8,4996.8
XS Rating Curve= 0 ,0
Exp/Cntr=0.3,0.1

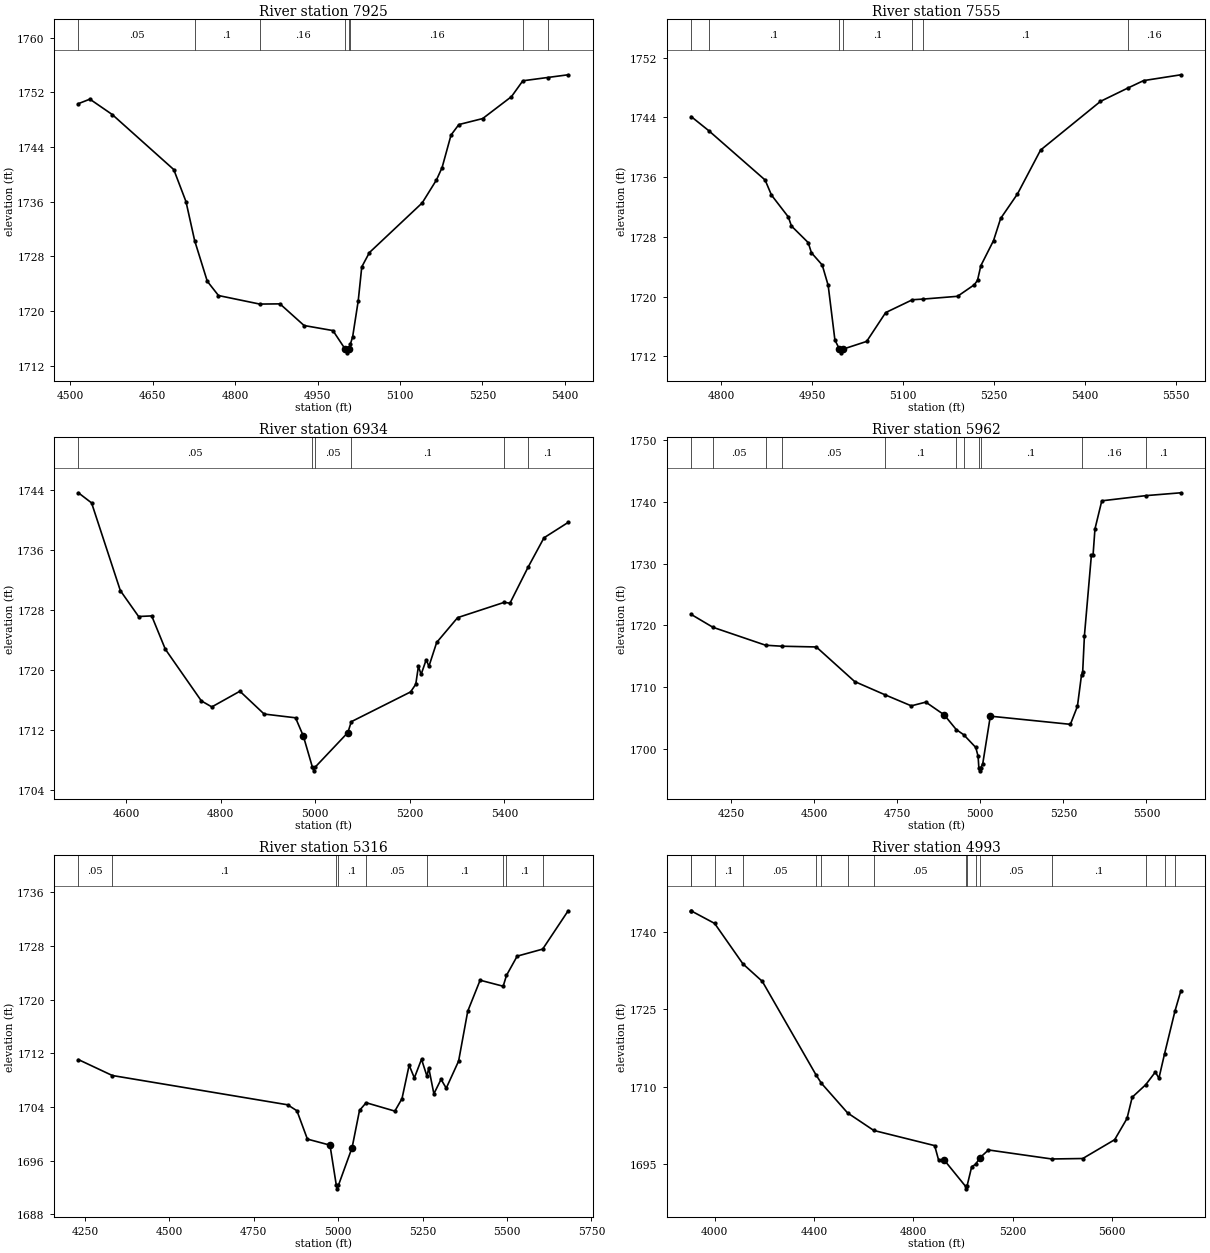
Type RM Length L Ch R = 1 ,7925    ,370,370,370
BEGIN DESCRIPTION:
UNT 1058 IN HEWA 15.0
END DESCRIPTION:
XS GIS Cut Line= 2
      2731517.79     10033453.12      2732394.02     10033617.96
#Sta/Elev= 30
  4514.5 1750.35  4535.5 1751.01  4576.2 1748.76  4688.2  1740.7  4710.4 1736.02
  4726.2  1730.3  4749.2 1724.35  4769.6 1722.26  4844.6 1721.01  4881.5 1721.04
  4925.4 1717.87  4977.9 1717.13  5000.6 1714.37  5003.4 1713.87  5006.6 1714.37
  5009.5 1715.11  5013.8 1716.21    5024 1721.51  5030.4 1726.45  5044.3 1728.55
  5140.4 1735.82  5166.4 1739.19  5176.6 1740.99  5192.9 1745.76  5207.1 1747.29
  5250.5 1748.17  5302.9 1751.38  5323.6  1753.7  5368.5 1754.18  5406.1 1754.58
#Mann= 8 ,-1 , 0
  4514.5     .05       0  4726.2      .1       0  4844.6     .16       0
  5000.6     .07       0  5006.6     .16       0  5009.5     .16       0
  5323.6      .1       0  5368.5     .05       0
Bank Sta=5000.6,5006.6
XS Rating Curve= 0 ,0
Exp/Cntr=0.3,0.1

Type RM Length L Ch R = 1 ,7555    ,621,621,621
BEGIN DESCRIPTION:
UNT 1058 IN HEWA 14.0
END DESCRIPTION:
XS GIS Cut Line= 2
      2731491.74     10033691.83      2732263.89     10033926.08
#Sta/Elev= 30
  4750.7  1744.1  4779.7 1742.21  4872.6  1735.6  4883.1 1733.58  4910.8 1730.66
    4916 1729.44  4943.6 1727.22  4948.9 1725.86  4966.7 1724.22  4976.5 1721.49
  4987.6 1714.17  4995.1 1712.96  4997.8 1712.46  5001.1 1712.96  5039.9 1713.99
  5071.2 1717.85  5115.3 1719.57  5133.5 1719.66  5189.6 1720.03  5217.3 1721.58
  5222.5 1722.17    5228 1724.13  5248.9 1727.49  5260.6 1730.45  5288.3 1733.73
  5326.4 1739.61  5425.1 1746.13  5469.8  1747.9  5496.1 1748.91  5557.6 1749.69
#Mann= 7 ,-1 , 0
  4750.7     .05       0  4779.7      .1       0  4995.1     .07       0
  5001.1      .1       0  5115.3     .05       0  5133.5      .1       0
  5469.8     .16       0
Bank Sta=4995.1,5001.1
XS Rating Curve= 0 ,0
Exp/Cntr=0.3,0.1

Type RM Length L Ch R = 1 ,6934    ,972,972,972
BEGIN DESCRIPTION:
UNT 1058 IN HEWA 13.0
END DESCRIPTION:
XS GIS Cut Line= 2
      2731205.26     10034559.91      2732124.49     10034082.95
#Sta/Elev= 30
    4499 1743.58    4527 1742.23  4587.8 1730.54  4626.4 1727.09  4654.1 1727.17
  4682.9 1722.73  4759.1 1715.84  4781.2 1715.04  4840.6 1717.13  4891.8 1714.09
  4958.2 1713.59  4974.7 1711.16  4993.8 1707.02  4996.6 1706.52  4999.8 1707.02
  5068.8 1711.62  5076.1 1713.07  5201.5 1717.04  5212.4 1718.06    5218 1720.45
  5223.7 1719.37  5234.5 1721.33  5240.2 1720.45  5256.6 1723.63  5300.9 1726.94
  5399.6 1728.98  5411.5 1728.86  5449.6 1733.63  5483.5 1737.58  5534.6 1739.63
#Mann= 6 ,-1 , 0
    4499     .05       0  4993.8    .035       0  4999.8     .05       0
  5076.1      .1       0  5399.6     .05       0  5449.6      .1       0
Bank Sta=4974.7,5068.8
XS Rating Curve= 0 ,0
Exp/Cntr=0.3,0.1

Type RM Length L Ch R = 1 ,5962    ,646,646,646
BEGIN DESCRIPTION:
UNT 1058 IN HEWA 12.0
END DESCRIPTION:
XS GIS Cut Line= 3
      2731404.92     10034894.08      2732060.33     10035141.49
      2732793.69     10034894.15
#Sta/Elev= 30
  4129.4 1721.78  4195.1 1719.69  4353.7 1716.79  4402.6 1716.63  4506.3 1716.51
  4621.7 1710.92  4713.8 1708.76  4792.2 1706.99  4835.9 1707.59  4891.3 1705.53
  4927.6 1703.15  4950.2 1702.31  4986.3 1700.26  4993.3 1698.84  4995.6 1696.98
  4998.3 1696.48  5001.6 1696.98  5007.4 1697.65  5030.1 1705.32  5271.2    1704
  5292.3 1706.91  5304.7 1712.02  5308.1 1712.42  5313.4 1718.34  5334.3 1731.32
  5339.5 1731.44  5345.1 1735.59  5365.7 1740.14  5498.5 1740.98  5603.9 1741.44
#Mann= 11 ,-1 , 0
  4129.4      .1       0  4195.1     .05       0  4353.7      .1       0
  4402.6     .05       0  4713.8      .1       0  4927.6     .05       0
  4950.2      .1       0  4995.6     .07       0  5001.6      .1       0
  5304.7     .16       0  5498.5      .1       0
Bank Sta=4891.3,5030.1
XS Rating Curve= 0 ,0
Exp/Cntr=0.3,0.1

Type RM Length L Ch R = 1 ,5316    ,323,323,323
BEGIN DESCRIPTION:
UNT 1058 IN HEWA 11.0
END DESCRIPTION:
XS GIS Cut Line= 4
      2731503.91     10035137.59      2731951.82       10035523.
       2732248.7     10035684.46      2732691.18     10035408.56
#Sta/Elev= 30
  4230.6 1711.07  4331.2 1708.69  4850.3 1704.32  4877.8 1703.43  4908.8  1699.2
  4975.7  1698.3  4994.5 1692.28  4997.3 1691.78  5000.5 1692.28  5041.2 1697.94
  5063.1 1703.48  5082.7 1704.63  5167.7 1703.38  5188.9 1705.24  5210.1 1710.23
  5225.5 1708.33  5246.7 1711.12    5263 1708.56    5268 1709.85  5283.3 1705.96
  5304.5 1708.12  5319.9  1706.8  5356.5 1710.84  5383.6 1718.29  5420.2 1722.91
  5488.5 1722.01  5498.3 1723.63  5529.9  1726.5  5605.4 1727.55  5680.9 1733.27
#Mann= 9 ,-1 , 0
  4230.6     .05       0  4331.2      .1       0  4994.5     .07       0
  5000.5      .1       0  5082.7     .05       0    5263      .1       0
  5488.5     .05       0  5498.3      .1       0  5605.4     .05       0
Bank Sta=4975.7,5041.2
XS Rating Curve= 0 ,0
Exp/Cntr=0.3,0.1

Type RM Length L Ch R = 1 ,4993    ,618,618,618
BEGIN DESCRIPTION:
UNT 1058 IN HEWA 10.0
END DESCRIPTION:
XS GIS Cut Line= 4
       2730951.8     10035455.28      2731852.86     10035840.71
      2732087.24     10035947.48       2732664.4     10035495.11
#Sta/Elev= 30
  3905.3  1744.1    3906 1744.07  3999.9 1741.65  4113.7 1733.81  4191.8 1730.41
  4408.6 1712.22  4429.7 1710.65    4535  1704.9  4640.4  1701.5  4885.3 1698.56
  4900.8 1695.82  4923.9 1695.75  5009.4 1690.68  5012.1 1690.18  5015.4 1690.68
  5034.3 1694.48    5050 1694.93  5066.9 1696.18  5101.7 1697.72  5356.6 1695.97
  5481.2 1696.06  5609.6 1699.71  5659.3 1703.83  5680.1 1707.94  5734.3 1710.36
  5773.2 1712.82  5787.7 1711.64  5810.6 1716.42  5852.2 1724.65  5876.2 1728.63
#Mann= 16 ,-1 , 0
  3905.3      .1       0    3906     .05       0  3999.9      .1       0
  4113.7     .05       0  4408.6     .16       0  4429.7      .1       0
    4535     .16       0  4640.4     .05       0  5009.4     .04       0
  5015.4     .05       0    5050      .1       0  5066.9     .05       0
  5356.6      .1       0  5734.3     .05       0  5810.6      .1       0
  5852.2     .05       0
Bank Sta=4923.9,5066.9
XS Rating Curve= 0 ,0
Exp/Cntr=0.3,0.1

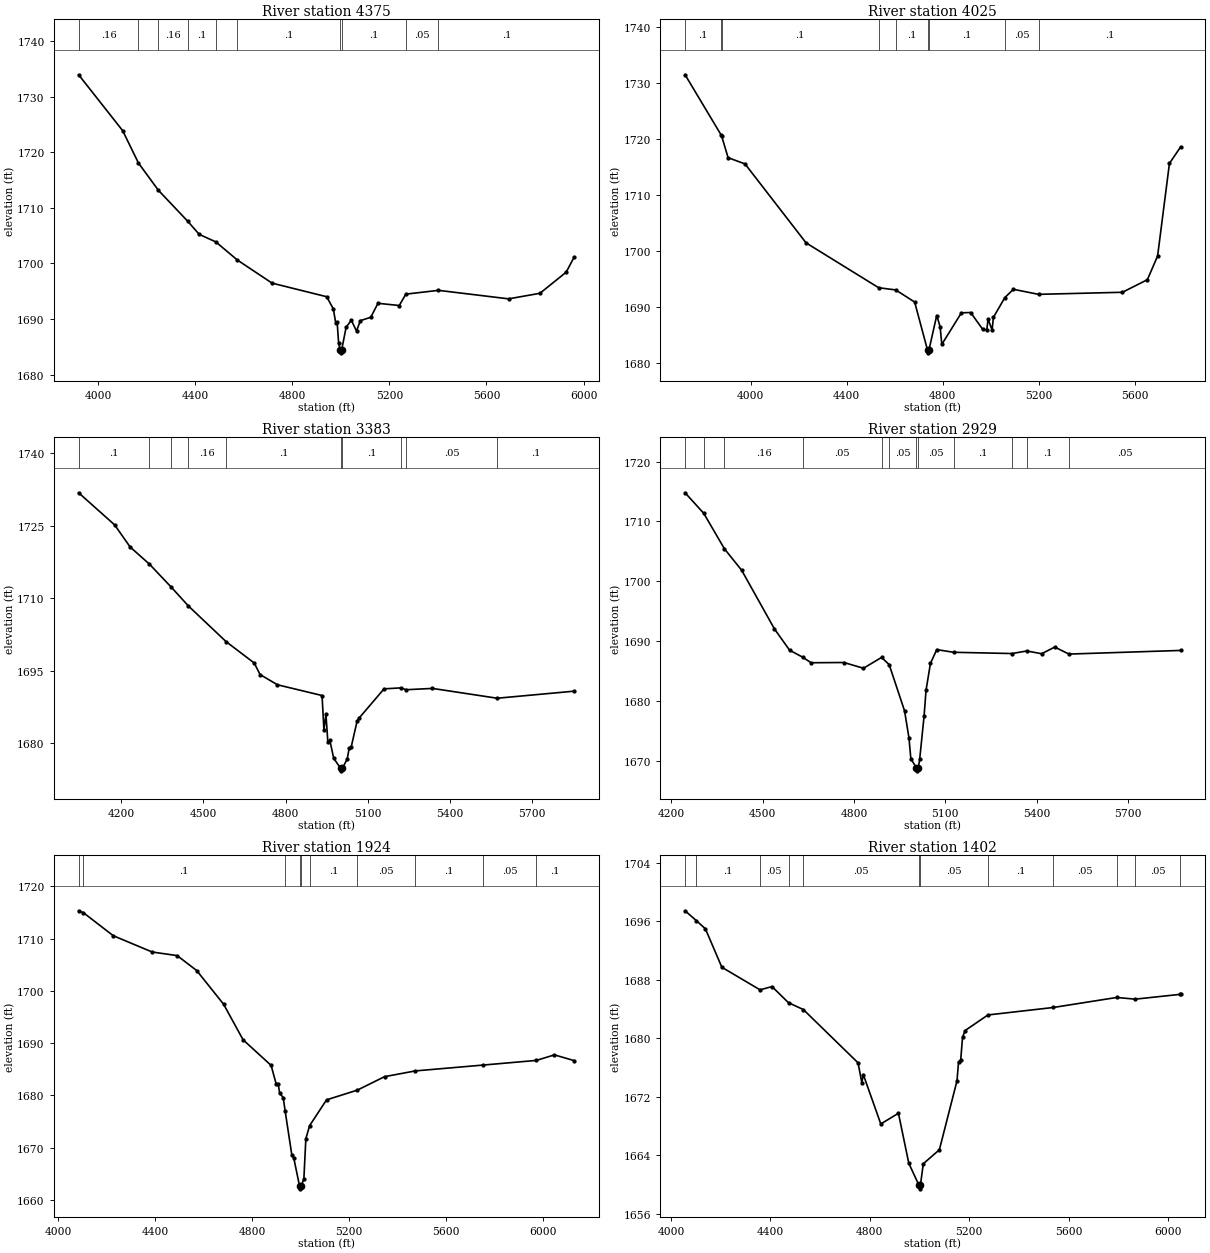
Type RM Length L Ch R = 1 ,4375    ,350,350,350
BEGIN DESCRIPTION:
UNT 1058 IN HEWA 9.0
END DESCRIPTION:
XS GIS Cut Line= 4
      2731049.91     10036695.75      2731966.58     10036523.87
       2732289.5     10035971.79      2732680.98     10035710.51
#Sta/Elev= 30
  3918.6 1733.97  4100.3  1723.9  4165.1 1718.09  4247.5 1713.17  4367.5 1707.64
  4415.7 1705.24  4484.3 1703.88  4572.9 1700.62  4716.1 1696.46  4941.2 1694.01
  4968.5 1691.84  4978.4 1689.32  4984.2 1689.52  4990.4 1685.66  4996.9 1684.41
  4999.6 1683.91  5002.9 1684.41  5021.4 1688.53  5042.8 1689.77  5064.3 1687.83
    5080 1689.71    5123 1690.31  5152.6 1692.83  5240.4 1692.43  5267.6 1694.48
  5402.1 1695.16  5691.2 1693.63  5820.4 1694.63  5928.5 1698.43  5961.5 1701.15
#Mann= 10 ,-1 , 0
  3918.6     .16       0  4165.1      .1       0  4247.5     .16       0
  4367.5      .1       0  4484.3     .16       0  4572.9      .1       0
  4996.9     .07       0  5002.9      .1       0  5267.6     .05       0
  5402.1      .1       0
Bank Sta=4996.9,5002.9
XS Rating Curve= 0 ,0
Exp/Cntr=0.3,0.1

Type RM Length L Ch R = 1 ,4025    ,642,642,642
BEGIN DESCRIPTION:
UNT 1058 IN HEWA 8.0
END DESCRIPTION:
XS GIS Cut Line= 4
      2731500.31     10037278.89      2732257.83     10036516.83
      2732598.03     10035850.03      2732778.37     10035687.73
#Sta/Elev= 30
  3726.2 1731.52  3875.3 1720.84  3879.1 1720.49  3905.3  1716.7    3976 1715.58
  4230.6 1701.46  4533.2 1693.44  4604.3 1693.05  4683.1 1690.88  4736.7  1682.3
  4739.5  1681.8  4742.7  1682.3  4775.1 1688.47  4789.2 1686.49  4796.3 1683.31
  4878.1 1688.96  4916.5 1689.01  4967.1 1685.99  4983.7  1685.9  4989.3 1687.82
  5005.9 1685.88  5011.5 1688.15  5058.9 1691.67  5094.8 1693.16  5199.5 1692.26
  5549.3 1692.63  5653.3 1694.88  5695.9 1699.12  5745.2 1715.67  5791.9 1718.63
#Mann= 9 ,-1 , 0
  3726.2      .1       0  3875.3     .16       0  3879.1      .1       0
  4533.2     .16       0  4604.3      .1       0  4736.7     .07       0
  4742.7      .1       0  5058.9     .05       0  5199.5      .1       0
Bank Sta=4736.7,4742.7
XS Rating Curve= 0 ,0
Exp/Cntr=0.3,0.1

Type RM Length L Ch R = 1 ,3383    ,454,454,454
BEGIN DESCRIPTION:
UNT 1058 IN HEWA 6.0
END DESCRIPTION:
XS GIS Cut Line= 3
      2731602.01     10037383.23      2732575.95      10036482.2
      2732665.24     10036008.04
#Sta/Elev= 30
  4044.5 1731.83  4175.9 1725.19  4232.5 1720.62    4303 1717.07  4382.3 1712.33
  4445.4 1708.41  4582.9 1701.04  4685.5 1696.62  4707.1 1694.22  4770.6 1692.11
  4933.3 1689.89  4940.1  1682.8  4947.5 1685.99  4954.3 1680.36  4961.7 1680.61
  4975.8 1676.91  5001.2 1674.81  5003.9 1674.31  5007.2 1674.81  5025.2 1676.76
  5032.5 1679.07  5039.3 1679.14  5060.9 1684.52  5067.7 1685.17  5159.6 1691.27
  5221.1 1691.47  5239.9 1691.09  5336.5 1691.36  5572.8 1689.33  5853.8 1690.79
#Mann= 10 ,-1 , 0
  4044.5      .1       0    4303     .05       0  4382.3      .1       0
  4445.4     .16       0  4582.9      .1       0  5001.2     .07       0
  5007.2      .1       0  5221.1     .16       0  5239.9     .05       0
  5572.8      .1       0
Bank Sta=5001.2,5007.2
XS Rating Curve= 0 ,0
Exp/Cntr=0.3,0.1

Type RM Length L Ch R = 1 ,2929    ,1005,1005,1005
BEGIN DESCRIPTION:
UNT 1058 IN HEWA 5.0
END DESCRIPTION:
XS GIS Cut Line= 3
      2732044.71     10037490.88      2732791.23     10036913.63
      2732738.28     10036231.35
#Sta/Elev= 30
  4245.1 1714.79  4306.4 1711.35  4374.3 1705.42  4430.8 1701.84  4538.6 1692.02
  4588.4 1688.46  4632.4 1687.26    4659 1686.36  4766.8  1686.4  4831.1 1685.44
  4890.5 1687.25  4915.5 1686.05    4966 1678.33  4980.5 1673.82  4986.8 1670.29
  5005.3 1668.78    5008 1668.28  5011.3 1668.78  5015.8 1670.23  5030.3 1677.47
  5036.6 1681.74  5051.1 1686.25  5071.9 1688.56  5127.1 1688.11  5319.1  1687.9
  5367.7 1688.33  5416.4 1687.87  5459.5 1688.98  5506.1 1687.81  5873.1 1688.42
#Mann= 12 ,-1 , 0
  4245.1     .05       0  4306.4      .1       0  4374.3     .16       0
  4632.4     .05       0  4890.5      .1       0  4915.5     .05       0
  5005.3    .035       0  5011.3     .05       0  5127.1      .1       0
  5319.1     .05       0  5367.7      .1       0  5506.1     .05       0
Bank Sta=5005.3,5011.3
XS Rating Curve= 0 ,0
Exp/Cntr=0.3,0.1

Type RM Length L Ch R = 1 ,1924    ,522,522,522
BEGIN DESCRIPTION:
UNT 1058 IN HEWA 4.0
END DESCRIPTION:
XS GIS Cut Line= 4
      2732075.13     10037877.16      2732760.85     10037790.36
      2733064.67     10037391.06      2732858.06     10036564.63
#Sta/Elev= 30
  4084.9 1715.34  4104.1 1714.99    4228 1710.56  4388.3 1707.45  4491.5 1706.76
  4572.1  1703.9    4683 1697.46  4763.6 1690.64  4879.1 1685.75  4899.9 1682.21
  4908.2 1682.25  4914.4 1680.42    4929  1679.6  4936.8  1677.1  4964.3 1668.69
  4972.6 1668.02  4996.7 1662.62  4999.5 1662.12  5002.7 1662.62  5014.3 1664.01
  5022.5 1671.71    5038 1674.21  5107.8 1679.15  5235.3 1681.02  5347.2 1683.59
  5474.2 1684.69  5751.5  1685.8  5973.7  1686.7  6048.2 1687.76  6129.7 1686.66
#Mann= 10 ,-1 , 0
  4084.9     .05       0  4104.1      .1       0  4936.8     .05       0
  4996.7    .035       0  5002.7     .05       0    5038      .1       0
  5235.3     .05       0  5474.2      .1       0  5751.5     .05       0
  5973.7      .1       0
Bank Sta=4996.7,5002.7
XS Rating Curve= 0 ,0
Exp/Cntr=0.3,0.1

Type RM Length L Ch R = 1 ,1402    ,318,318,318
BEGIN DESCRIPTION:
UNT 1058 IN HEWA 3.0
END DESCRIPTION:
XS GIS Cut Line= 4
      2732951.84     10038241.73      2733385.85     10037582.03
      2733129.77     10037391.06      2732957.03     10036522.99
#Sta/Elev= 30
  4056.8 1697.43  4101.9 1696.09  4138.4 1694.97  4204.7 1689.71  4358.5 1686.62
  4406.5 1687.07    4473 1684.86  4532.6 1683.93  4752.9 1676.64    4768 1673.92
    4774 1675.04  4844.3 1668.29  4915.4 1669.75    4957 1662.92  4997.8 1659.92
  5000.6 1659.42  5003.8 1659.92  5015.4 1662.85  5080.1 1664.76    5151 1674.19
  5157.2 1676.74  5165.9 1677.05  5173.4 1680.15  5183.6 1681.06  5275.6 1683.19
  5538.5 1684.21  5793.6 1685.58  5868.2 1685.35  6047.6    1686    6051 1686.01
#Mann= 12 ,-1 , 0
  4056.8     .16       0  4101.9      .1       0  4358.5     .05       0
    4473      .1       0  4532.6     .05       0  4997.8     .04       0
  5003.8     .05       0  5275.6      .1       0  5538.5     .05       0
  5793.6      .1       0  5868.2     .05       0  6047.6      .1       0
Bank Sta=4997.8,5003.8
XS Rating Curve= 0 ,0
Exp/Cntr=0.3,0.1