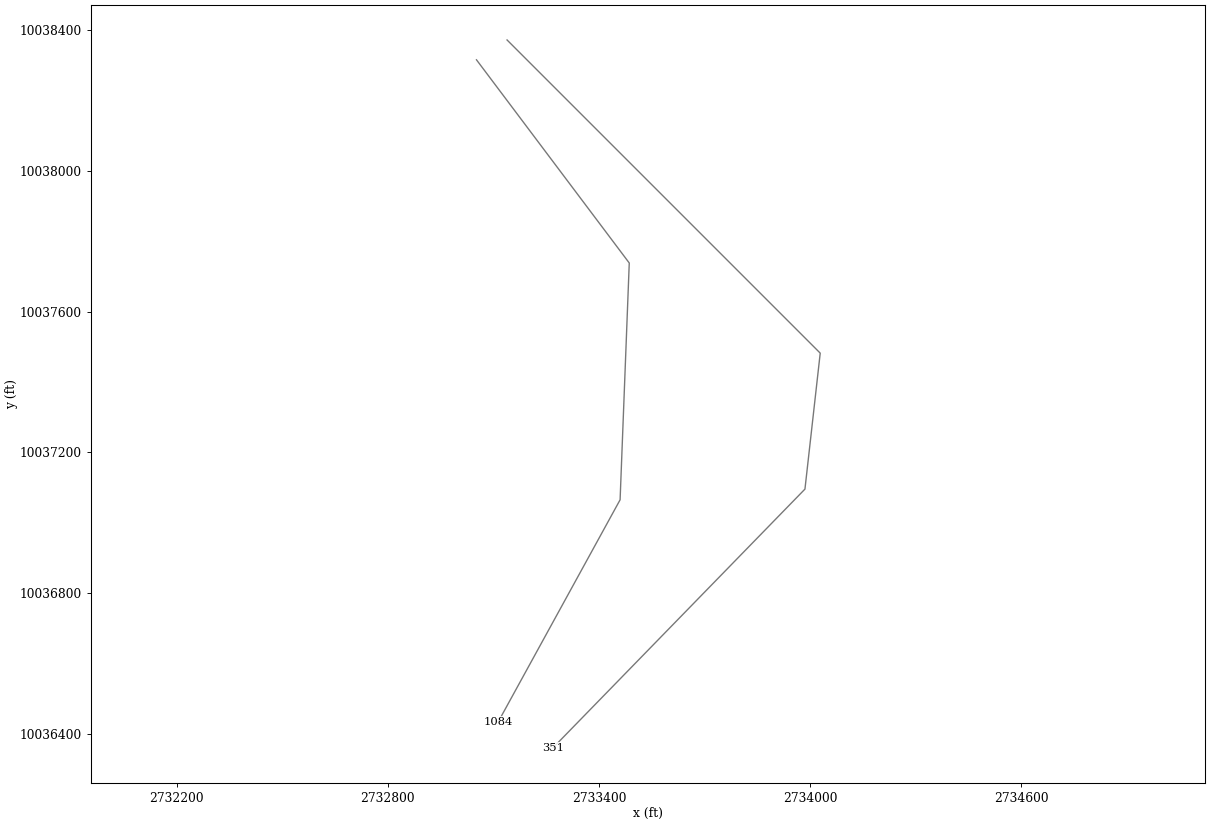
HEC-RAS study UNT 1058 IN HEWA.prj: UNT 1058 IN HEWA Base Level Engineering

--- UNT 1058 IN HEWA.g01 (geometry) --- (continued)

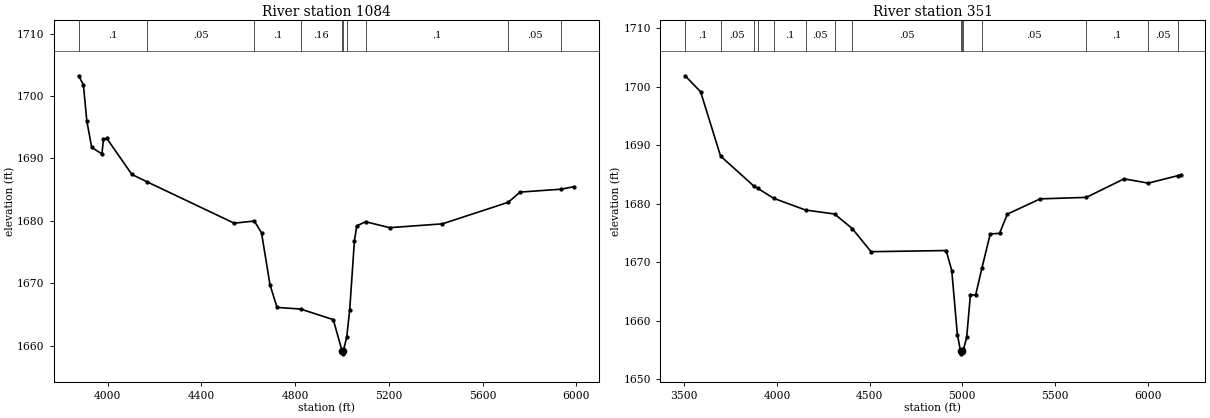
Type RM Length L Ch R = 1 ,1084    ,733,733,733
BEGIN DESCRIPTION:
UNT 1058 IN HEWA 2.0
END DESCRIPTION:
XS GIS Cut Line= 4
      2733051.63     10038315.56      2733485.68     10037738.28
      2733459.64     10037065.54      2733113.36     10036434.61
#Sta/Elev= 30
  3875.8 1703.25  3896.2  1701.8  3910.7 1696.01  3931.6 1691.77  3975.3 1690.73
  3981.6 1693.04  3996.1 1693.21  4103.3 1687.43  4168.2 1686.25  4539.7 1679.63
  4625.8 1679.97  4656.4 1678.09  4692.7 1669.75  4722.7 1666.13    4823 1665.87
  4962.9 1664.17  4999.9 1659.19  5002.6 1658.69  5005.9 1659.19  5020.3  1661.4
  5032.9 1665.77  5052.9 1676.75  5062.9  1679.2    5101 1679.86    5203 1678.91
  5428.5 1679.52  5709.6 1682.98  5760.2 1684.61  5936.5 1685.08    5991 1685.49
#Mann= 10 ,-1 , 0
  3875.8      .1       0  4168.2     .05       0  4625.8      .1       0
    4823     .16       0  4999.9     .07       0  5005.9     .16       0
  5020.3     .05       0    5101      .1       0  5709.6     .05       0
  5936.5      .1       0
Bank Sta=4999.9,5005.9
XS Rating Curve= 0 ,0
Exp/Cntr=0.3,0.1

Type RM Length L Ch R = 1 ,351     ,0,0,0
BEGIN DESCRIPTION:
UNT 1058 IN HEWA 1.0
END DESCRIPTION:
XS GIS Cut Line= 4
      2733138.47     10038371.94      2734028.21      10037482.2
      2733984.81     10037095.92      2733269.56     10036361.58
#Sta/Elev= 30
    3505 1701.88  3588.6 1699.15  3696.2 1688.15    3877 1682.98  3896.9 1682.62
  3982.8 1680.92  4155.2 1678.91  4311.1 1678.24  4406.6 1675.74  4507.8 1671.79
  4912.7 1671.99  4942.9 1668.57  4973.1 1657.62  4990.2 1654.82  4992.9 1654.32
  4996.2 1654.82  5005.9 1655.08  5023.4 1657.14  5043.5 1664.44  5071.6 1664.37
  5105.4 1668.97  5150.6 1674.84  5200.4 1674.92  5242.9 1678.22  5419.8 1680.83
  5668.3 1681.08  5872.2 1684.25  6002.7 1683.52  6162.6  1684.8  6177.1 1684.93
#Mann= 15 ,-1 , 0
    3505      .1       0  3696.2     .05       0    3877      .1       0
  3896.9     .05       0  3982.8      .1       0  4155.2     .05       0
  4311.1      .1       0  4406.6     .05       0  4990.2    .035       0
  4996.2     .05       0  5005.9     .16       0  5105.4     .05       0
  5668.3      .1       0  6002.7     .05       0  6162.6      .1       0
Bank Sta=4990.2,4996.2
XS Rating Curve= 0 ,0
Exp/Cntr=0.3,0.1

Chan Stop Cuts=-1
Use User Specified Reach Order=0
Composite Channel Slope=5