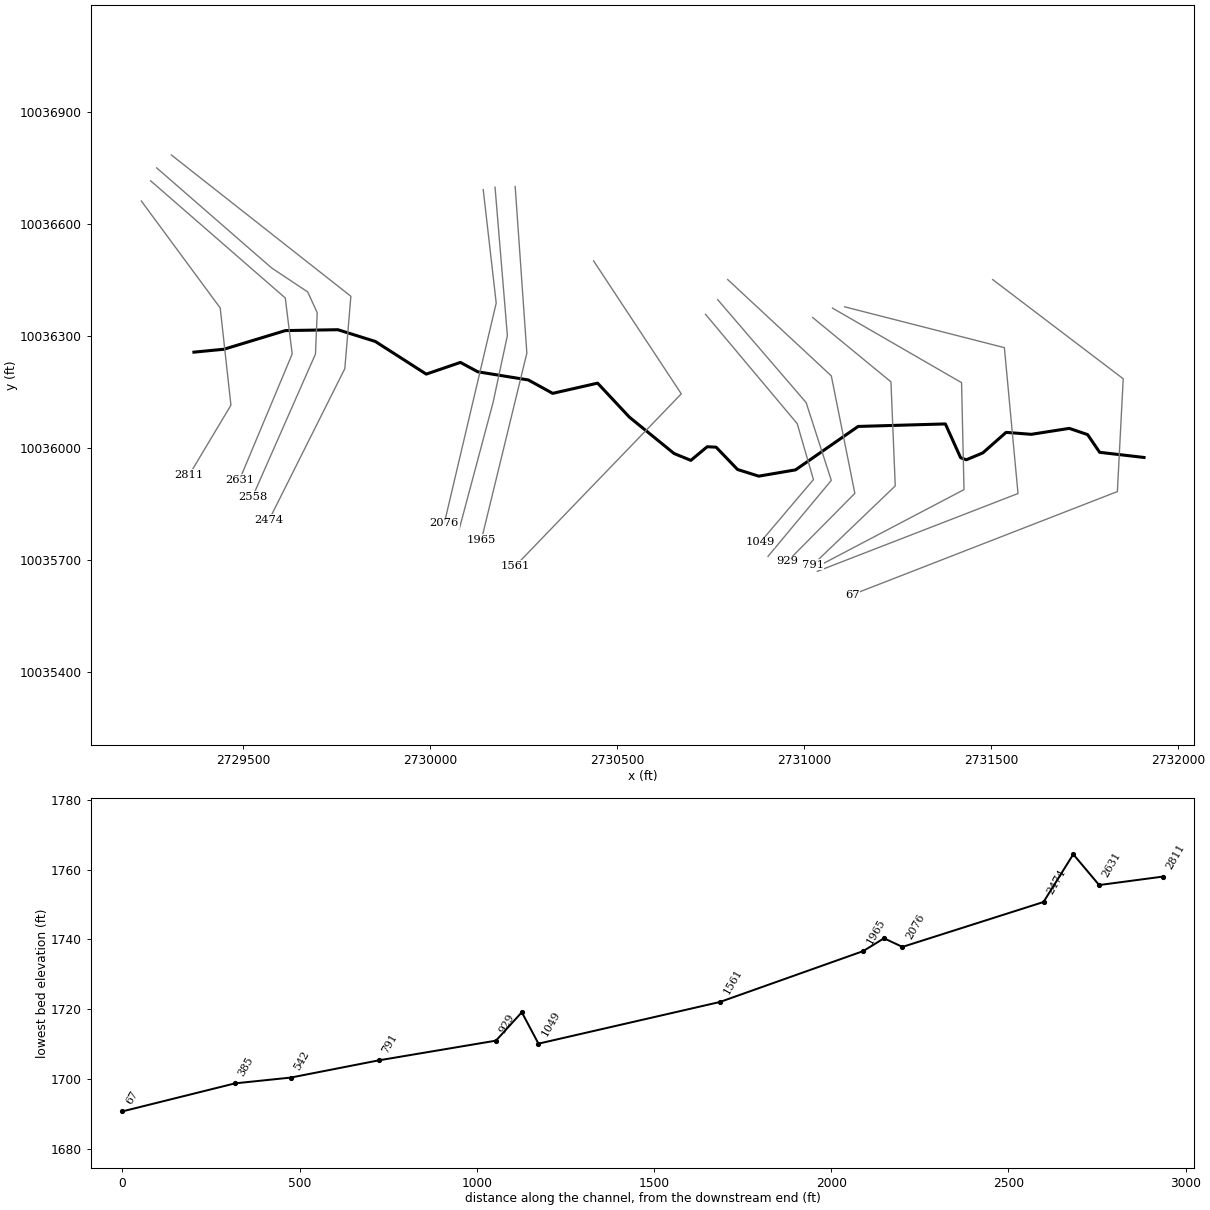
--- UNT 1059 IN HEWA.prj (project) ---

Proj Title=UNT 1059 IN HEWA Base Level Engineering
Current Plan=p01
Default Exp/Contr=0.3,0.1
English Units
Geom File=g01
Flow File=f01
Plan File=p01
Y Axis Title=Elevation
X Axis Title(PF)=Main Channel Distance
X Axis Title(XS)=Station
BEGIN DESCRIPTION:
UNT 1059 IN HEWA
END DESCRIPTION:
DSS Export Rating Curves= 0
DSS Export Rating Curve Sorted= 0
DSS Export Volume Flow Curves= 0
DXF OffsetX= 0
DXF OffsetY= 0
DXF ScaleX= 1
DXF ScaleY= 10

--- UNT 1059 IN HEWA.p01 (plan) ---

Plan Title=Multiple Run
Short Identifier=Multiple
Geom File=g01
Flow File=f01
Subcritical Flow
K Sum by GR= 0
Std Step Tol= 0.01
Critical Tol= 0.01
Num of Std Step Trials= 20
Max Error Tol= 0.3
Flow Tol Ratio= 0.001
Split Flow NTrial= 30
Split Flow Tol= 0.02
Split Flow Ratio= 0.02
Log Output Level= 0
Friction Slope Method= 1
Unsteady Friction Slope Method= 2
Unsteady Bridges Friction Slope Method= 1
Parabolic Critical Depth
Global Vel Dist=  1 , 1 , 1
Global Log Level= 0
CheckData=True
Encroach Param= -1, 0, 0, 0
BEGIN DESCRIPTION:
Multiple Run
END DESCRIPTION:

--- UNT 1059 IN HEWA.f01 (steady flow) ---

Flow Title=Multiple
Number of Profiles=7
Profile Names=10-year,25-year,50-year,1pct_min,100-year,1pct_plu,500-year
River Rch & RM= UNT 1059 IN HEWA,Reach-1,2811
     356     498     618     566     765    1035    1172
Boundary for River Rch & Prof#=UNT 1059 IN HEWA,Reach-1,1
Up Type=0
Dn Type=3
Dn Slope=0.005
Boundary for River Rch & Prof#=UNT 1059 IN HEWA,Reach-1,2
Up Type=0
Dn Type=3
Dn Slope=0.005
Boundary for River Rch & Prof#=UNT 1059 IN HEWA,Reach-1,3
Up Type=0
Dn Type=3
Dn Slope=0.005
Boundary for River Rch & Prof#=UNT 1059 IN HEWA,Reach-1,4
Up Type=0
Dn Type=3
Dn Slope=0.005
Boundary for River Rch & Prof#=UNT 1059 IN HEWA,Reach-1,5
Up Type=0
Dn Type=3
Dn Slope=0.005
Boundary for River Rch & Prof#=UNT 1059 IN HEWA,Reach-1,6
Up Type=0
Dn Type=3
Dn Slope=0.005
Boundary for River Rch & Prof#=UNT 1059 IN HEWA,Reach-1,7
Up Type=0
Dn Type=3
Dn Slope=0.005

--- UNT 1059 IN HEWA.g01 (geometry) ---

Geom Title=Existing Conditions
Program Version=4.10

River Reach=UNT 1059 IN HEWA,Reach-1
Reach XY= 30
      2729368.55     10036255.76      2729448.81     10036263.54
      2729613.08      10036313.5      2729753.34     10036315.82
      2729853.47     10036284.38      2729989.59      10036196.9
      2730080.95     10036228.26      2730127.45     10036203.13
      2730262.41     10036181.33      2730327.59      10036145.4
       2730447.7     10036172.74      2730532.67     10036081.73
      2730652.17     10035984.28        2730697.     10035965.98
      2730740.67     10036002.41      2730764.47      10036001.3
      2730821.84     10035941.49      2730878.57     10035923.68
      2730976.81     10035940.48      2731144.18     10036056.82
      2731377.45     10036063.53      2731418.13     10035973.13
      2731433.56     10035967.57       2731477.4     10035985.88
      2731539.73     10036040.92      2731607.07     10036035.69
      2731708.68     10036051.62      2731757.59     10036034.94
      2731789.94     10035987.46      2731908.47     10035973.73

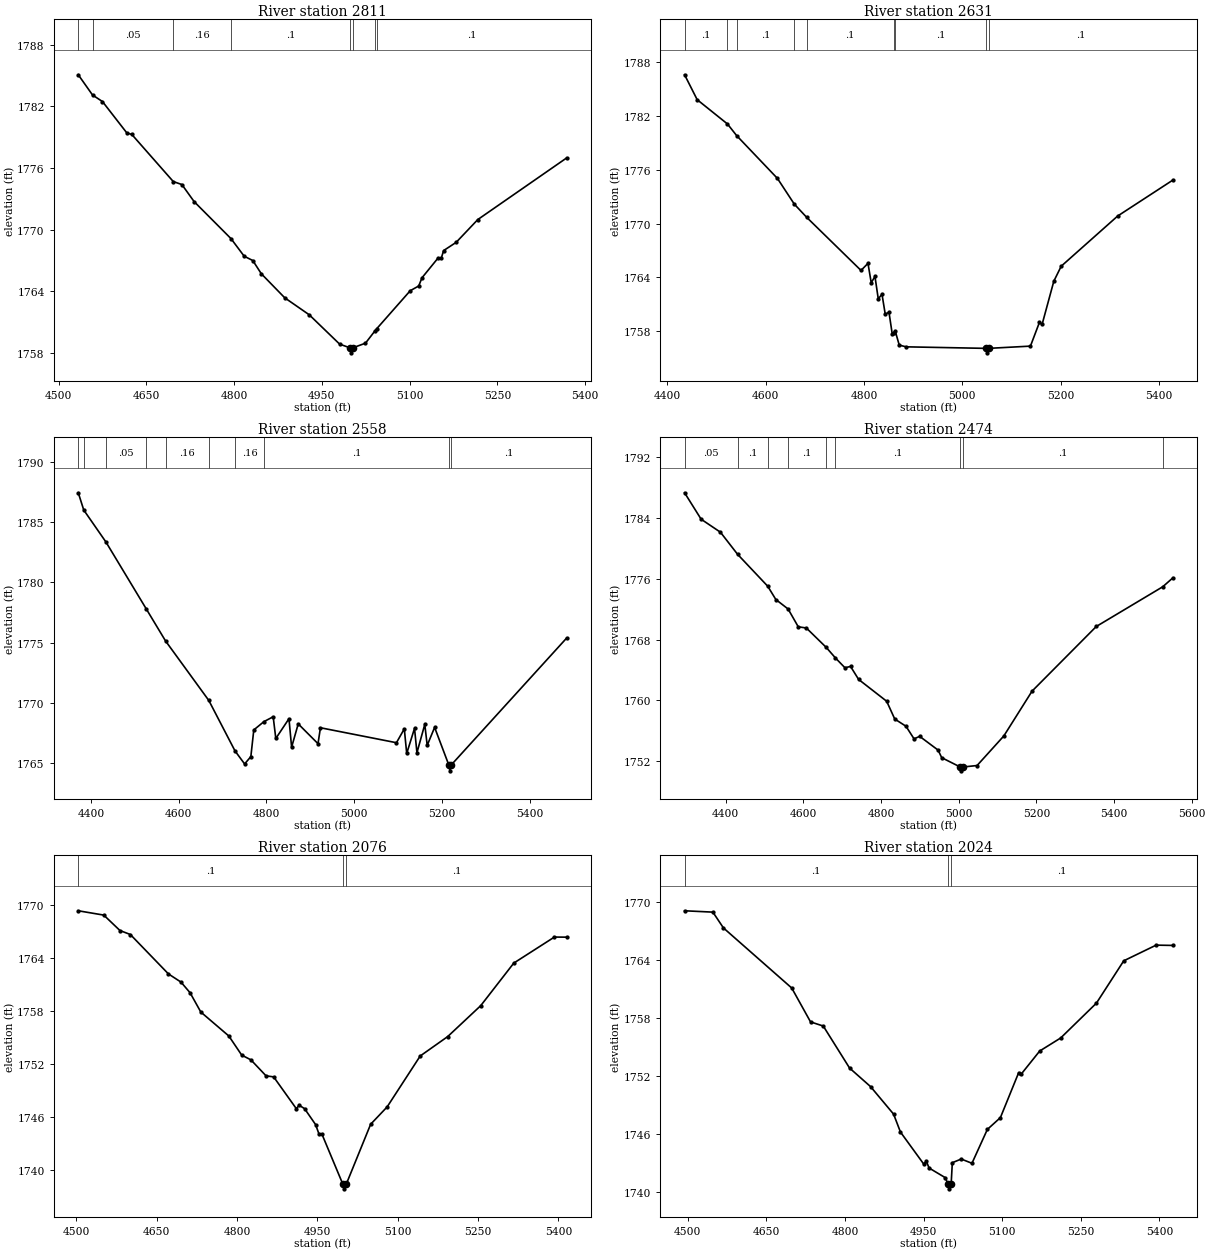
Type RM Length L Ch R = 1 ,2811    ,180,180,180
BEGIN DESCRIPTION:
UNT 1059 IN HEWA 6.0
END DESCRIPTION:
XS GIS Cut Line= 4
      2729227.86     10036660.59       2729438.8     10036374.13
      2729467.45     10036113.71       2729356.2     10035927.44
#Sta/Elev= 30
  4533.7 1785.07  4558.1  1783.1  4575.1 1782.46  4616.8  1779.4  4625.2 1779.26
  4696.1 1774.67  4710.8 1774.38  4731.7 1772.72  4794.8 1769.11  4817.3  1767.4
    4832 1766.98  4846.6 1765.69  4886.6 1763.35  4928.6 1761.69  4980.4 1758.84
  4997.5 1758.49  5000.3 1757.99  5003.5 1758.49  5024.6 1758.93  5040.7 1760.12
  5043.7 1760.33  5101.1 1764.04  5115.6  1764.5  5121.2  1765.3  5148.9 1767.24
  5154.3 1767.24  5158.2 1767.95  5179.6 1768.75  5216.6 1770.97  5368.4 1776.97
#Mann= 8 ,-1 , 0
  4533.7      .1       0  4558.1     .05       0  4696.1     .16       0
  4794.8      .1       0  4997.5     .07       0  5003.5      .1       0
  5040.7     .05       0  5043.7      .1       0
Bank Sta=4997.5,5003.5
XS Rating Curve= 0 ,0
Exp/Cntr=0.3,0.1

Type RM Length L Ch R = 1 ,2631    ,73,73,73
BEGIN DESCRIPTION:
Mapping XS 82a25175
END DESCRIPTION:
XS GIS Cut Line= 4
      2729252.91     10036714.51      2729612.76     10036400.79
      2729631.22     10036250.84       2729490.5     10035914.04
#Sta/Elev= 30
  4435.1 1786.61  4460.7 1783.83  4522.3 1781.12    4541 1779.82    4624 1775.04
  4658.3 1772.17  4683.6 1770.69    4794 1764.77  4808.2 1765.56  4814.8 1763.39
  4822.4  1764.1  4829.1  1761.6  4836.7 1762.11  4843.3 1759.88  4850.9 1760.11
  4857.6 1757.65  4860.2 1757.82  4863.5 1758.03  4871.8 1756.43    4886 1756.24
  5047.6 1756.07  5050.3 1755.57  5053.6 1756.07  5138.7 1756.32    5157 1758.97
  5162.5 1758.76  5186.3 1763.57  5201.3 1765.24  5316.1 1770.84  5428.6 1774.86
#Mann= 9 ,-1 , 0
  4435.1      .1       0  4522.3     .05       0    4541      .1       0
  4658.3     .16       0  4683.6      .1       0  4860.2     .16       0
  4863.5      .1       0  5047.6     .07       0  5053.6      .1       0
Bank Sta=5047.6,5053.6
XS Rating Curve= 0 ,0
Exp/Cntr=0.3,0.1

Type RM Length L Ch R = 1 ,2558    ,84,84,84
BEGIN DESCRIPTION:
Mapping XS e6f7fd74
END DESCRIPTION:
XS GIS Cut Line= 6
      2729269.02     10036749.14      2729575.85     10036481.53
      2729672.74     10036416.94      2729698.12     10036361.57
       2729693.5     10036250.84      2729525.28     10035868.31
#Sta/Elev= 30
    4371 1787.41  4383.5 1785.98  4433.9 1783.34  4526.1 1777.78    4570 1775.13
  4668.6  1770.2  4728.3 1766.02  4750.2 1764.94  4764.4 1765.55  4771.1 1767.76
  4794.3 1768.45  4815.3 1768.85  4821.3 1767.05  4851.3 1768.69  4857.3 1766.33
  4872.4 1768.26  4917.5 1766.62    4923 1767.94  5096.3  1766.7  5114.2 1767.85
  5119.7 1765.81  5137.5 1767.89    5143 1765.87  5160.9 1768.22  5166.4 1766.48
  5183.3 1767.97  5215.5 1764.87  5218.3 1764.37  5221.5 1764.87  5484.2 1775.37
#Mann= 10 ,-1 , 0
    4371     .05       0  4383.5      .1       0  4433.9     .05       0
  4526.1      .1       0    4570     .16       0  4668.6      .1       0
  4728.3     .16       0  4794.3      .1       0  5215.5     .07       0
  5221.5      .1       0
Bank Sta=5215.5,5221.5
XS Rating Curve= 0 ,0
Exp/Cntr=0.3,0.1

Type RM Length L Ch R = 1 ,2474    ,398,398,398
BEGIN DESCRIPTION:
UNT 1059 IN HEWA 5.0
END DESCRIPTION:
XS GIS Cut Line= 4
      2729308.29      10036783.7      2729788.09      10036405.4
      2729771.94     10036211.62      2729569.73      10035807.2
#Sta/Elev= 30
  4294.2 1787.32  4336.8 1783.84  4386.5 1782.13  4430.7 1779.22  4508.3 1775.02
  4529.2 1773.27  4560.8 1772.02  4586.9 1769.68  4607.8 1769.52  4658.9 1766.97
  4682.8 1765.57  4707.1 1764.29  4721.6 1764.46  4742.4 1762.75  4814.6 1759.88
  4835.4 1757.54  4864.3 1756.59  4885.1 1754.93  4899.6 1755.26    4947 1753.45
  4956.4 1752.45  5004.2 1751.22    5007 1750.72  5010.2 1751.22  5047.4 1751.42
  5116.3 1755.31    5189 1761.21  5354.4 1769.72  5525.6 1774.95  5551.8 1776.13
#Mann= 9 ,-1 , 0
  4294.2     .05       0  4430.7      .1       0  4508.3     .16       0
  4560.8      .1       0  4658.9     .16       0  4682.8      .1       0
  5004.2     .07       0  5010.2      .1       0  5525.6     .16       0
Bank Sta=5004.2,5010.2
XS Rating Curve= 0 ,0
Exp/Cntr=0.3,0.1

Type RM Length L Ch R = 1 ,2076    ,52,52,52
BEGIN DESCRIPTION:
Mapping XS d00b5453
END DESCRIPTION:
XS GIS Cut Line= 3
      2730141.92     10036690.99      2730176.65     10036387.15
      2730037.97     10035797.76
#Sta/Elev= 30
    4504  1769.4  4551.6 1768.91  4581.8 1767.16  4601.2 1766.71  4672.3 1762.24
  4695.6 1761.32  4712.6 1760.11  4732.7 1757.92  4784.9 1755.21    4809 1753.04
  4826.2  1752.5  4854.4 1750.69  4868.6 1750.57    4911 1746.96  4916.1 1747.36
  4926.3 1746.97  4946.9 1745.16  4953.4 1744.06  4958.5 1744.11  4997.9 1738.38
  5000.6 1737.88  5003.9 1738.38  5049.6  1745.2  5080.4 1747.17  5142.1 1752.94
  5193.4 1755.14  5255.1 1758.65  5316.7 1763.47  5392.5 1766.42  5415.3 1766.41
#Mann= 3 ,-1 , 0
    4504      .1       0  4997.9     .07       0  5003.9      .1       0
Bank Sta=4997.9,5003.9
XS Rating Curve= 0 ,0
Exp/Cntr=0.3,0.1

Type RM Length L Ch R = 1 ,2024    ,59,59,59
BEGIN DESCRIPTION:
Mapping XS 22436e5a
END DESCRIPTION:
XS GIS Cut Line= 4
      2730173.52     10036697.56      2730206.51     10036300.02
      2730168.31      10036121.2      2730078.04     10035782.69
#Sta/Elev= 30
  4493.9 1769.07  4547.9 1768.93    4568  1767.3  4698.4 1761.09  4734.3 1757.59
  4758.6 1757.16  4808.8 1752.82  4848.9  1750.9  4892.8 1748.06  4905.9 1746.21
  4950.2 1742.91  4955.4 1743.18  4960.6 1742.49  4991.3  1741.5  4996.7 1740.84
  4999.5 1740.34  5002.7 1740.84  5004.9 1743.04  5021.9 1743.42  5042.4 1742.98
  5071.8 1746.48  5096.7  1747.7  5131.6 1752.35  5136.8 1752.22  5171.7 1754.58
  5211.8 1755.93    5280 1759.53  5332.1  1763.9  5393.9 1765.52    5426 1765.49
#Mann= 3 ,-1 , 0
  4493.9      .1       0  4996.7     .07       0  5002.7      .1       0
Bank Sta=4996.7,5002.7
XS Rating Curve= 0 ,0
Exp/Cntr=0.3,0.1

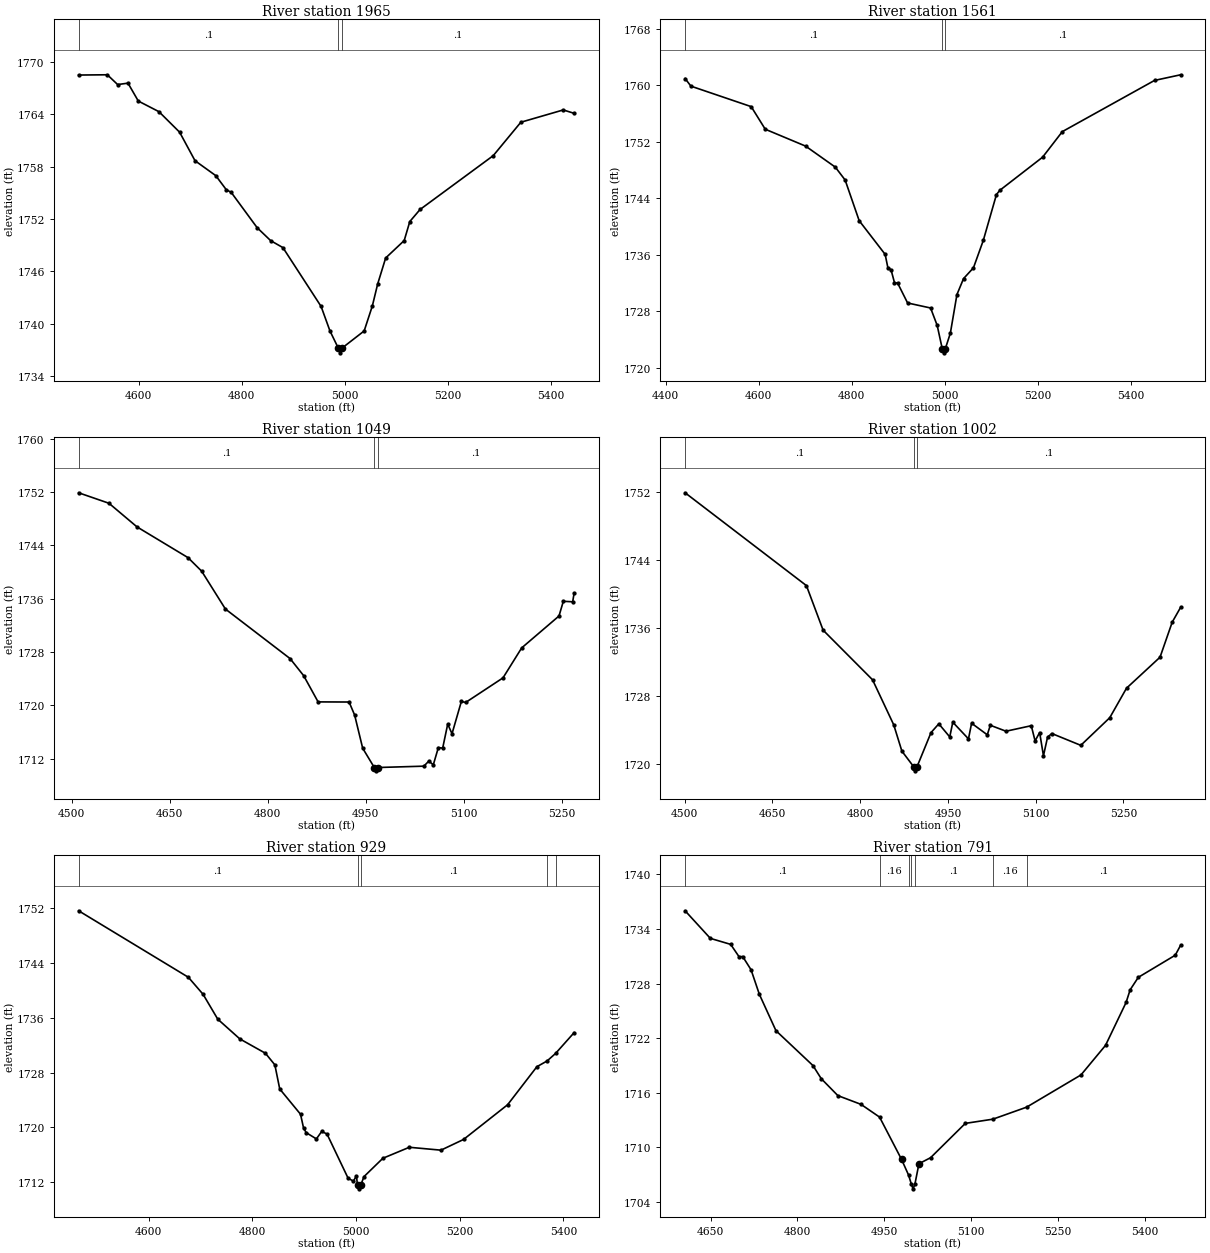
Type RM Length L Ch R = 1 ,1965    ,404,404,404
BEGIN DESCRIPTION:
Mapping XS c24e59aa
END DESCRIPTION:
XS GIS Cut Line= 3
      2730227.34     10036699.29      2730258.59     10036253.14
      2730137.06     10035753.14
#Sta/Elev= 30
  4483.6 1768.51  4539.3 1768.54  4559.3 1767.42  4579.4 1767.58  4599.4 1765.53
  4639.5 1764.31  4679.6 1761.96  4709.5 1758.69  4749.8 1756.98  4769.9 1755.39
  4779.9 1755.05    4830 1751.02  4856.3 1749.53  4880.1 1748.73  4954.2 1741.99
  4971.4 1739.18  4987.9 1737.17  4990.6 1736.67  4993.9 1737.17  5037.8 1739.18
  5053.7 1742.05    5064 1744.56  5079.5 1747.54  5115.5 1749.54  5126.4 1751.72
  5146.3  1753.1  5288.3 1759.27  5341.9  1763.1  5424.2 1764.51  5445.4 1764.12
#Mann= 3 ,-1 , 0
  4483.6      .1       0  4987.9     .07       0  4993.9      .1       0
Bank Sta=4987.9,4993.9
XS Rating Curve= 0 ,0
Exp/Cntr=0.3,0.1

Type RM Length L Ch R = 1 ,1561    ,512,512,512
BEGIN DESCRIPTION:
UNT 1059 IN HEWA 4.0
END DESCRIPTION:
XS GIS Cut Line= 3
      2730437.07     10036499.99      2730671.44      10036144.1
      2730228.74     10035684.03
#Sta/Elev= 30
    4442 1760.97  4454.5 1759.89    4584 1756.99  4614.2 1753.79  4700.9  1751.4
  4764.8 1748.42  4785.8  1746.6    4816 1740.84  4871.8 1736.07  4877.6 1734.19
  4884.5 1733.87  4891.8 1732.08  4898.7 1731.99    4920 1729.19  4969.4 1728.48
  4983.6 1726.01  4994.7 1722.63  4997.5 1722.13  5000.7 1722.63  5011.9 1724.92
    5026 1730.38  5040.2 1732.64  5061.5 1734.17  5082.6 1738.04  5110.9 1744.54
  5118.1 1745.14    5210 1749.83  5252.4 1753.45  5450.5  1760.7  5506.6  1761.5
#Mann= 3 ,-1 , 0
    4442      .1       0  4994.7     .07       0  5000.7      .1       0
Bank Sta=4994.7,5000.7
XS Rating Curve= 0 ,0
Exp/Cntr=0.3,0.1

Type RM Length L Ch R = 1 ,1049    ,47,47,47
BEGIN DESCRIPTION:
Mapping XS 279262d7
END DESCRIPTION:
XS GIS Cut Line= 4
      2730736.13     10036357.18      2730981.34     10036064.23
      2731024.74     10035914.49      2730882.46     10035746.34
#Sta/Elev= 30
  4510.8 1751.87  4557.2  1750.3  4600.1 1746.76  4678.2 1742.15    4699 1740.13
  4735.4 1734.45  4834.3 1727.03  4855.1 1724.47  4877.2 1720.54  4924.6 1720.52
  4933.1 1718.57  4945.4  1713.6  4963.2 1710.71    4966 1710.21  4969.2 1710.71
    5039 1710.91  5046.5 1711.66  5053.5 1711.12  5061.2  1713.7  5067.8 1713.61
  5075.5 1717.21  5082.1 1715.77  5096.4 1720.61  5102.9 1720.45  5160.1 1724.14
  5188.7 1728.63  5245.8 1733.41  5252.4 1735.61  5266.7 1735.54    5269 1736.86
#Mann= 3 ,-1 , 0
  4510.8      .1       0  4963.2     .07       0  4969.2      .1       0
Bank Sta=4963.2,4969.2
XS Rating Curve= 0 ,0
Exp/Cntr=0.3,0.1

Type RM Length L Ch R = 1 ,1002    ,73,73,73
BEGIN DESCRIPTION:
Mapping XS 5d3d00cf
END DESCRIPTION:
XS GIS Cut Line= 4
      2730768.69     10036396.24      2731005.21     10036120.66
      2731072.48     10035912.32      2730903.29     10035708.87
#Sta/Elev= 30
    4501  1751.9  4708.3 1740.98  4736.8 1735.74  4821.3  1729.9  4857.5  1724.6
  4871.4 1721.51  4891.4 1719.69  4894.1 1719.19  4897.4 1719.69  4921.2 1723.69
  4934.5 1724.72  4953.2 1723.18  4958.4 1724.91  4985.2 1722.95  4990.5 1724.79
  5017.3 1723.43  5022.5 1724.55  5049.3 1723.85  5092.5  1724.5    5099 1722.71
  5106.8  1723.7  5113.3 1720.96  5120.3 1723.15  5127.6 1723.58  5177.1 1722.19
  5226.6 1725.44  5255.2 1728.91  5312.5 1732.56  5333.3 1736.68  5347.7 1738.43
#Mann= 3 ,-1 , 0
    4501      .1       0  4891.4     .07       0  4897.4      .1       0
Bank Sta=4891.4,4897.4
XS Rating Curve= 0 ,0
Exp/Cntr=0.3,0.1

Type RM Length L Ch R = 1 ,929     ,330,330,330
BEGIN DESCRIPTION:
UNT 1059 IN HEWA 3.0
END DESCRIPTION:
XS GIS Cut Line= 4
      2730795.54     10036450.12      2731072.48     10036192.27
      2731135.42      10035877.6      2730955.27     10035695.28
#Sta/Elev= 30
    4465 1751.55  4676.6 1741.87    4705 1739.39  4733.3 1735.77  4775.8  1732.9
  4825.2 1730.81  4843.4 1729.12  4852.8 1725.61  4892.9 1721.93  4898.7 1719.94
  4903.8 1719.25  4923.5 1718.34  4933.7 1719.42  4943.9 1719.06  4984.7 1712.61
  4994.9 1712.19  5000.7 1712.97  5002.8 1711.57  5005.5 1711.07  5008.8 1711.57
  5015.3 1712.85  5051.7 1715.52  5102.7 1717.12  5163.7  1716.7  5207.3 1718.26
  5292.2 1723.31  5348.7 1728.85  5368.3 1729.68  5384.7 1730.78  5420.6 1733.82
#Mann= 5 ,-1 , 0
    4465      .1       0  5002.8     .07       0  5008.8      .1       0
  5368.3     .05       0  5384.7      .1       0
Bank Sta=5002.8,5008.8
XS Rating Curve= 0 ,0
Exp/Cntr=0.3,0.1

Type RM Length L Ch R = 1 ,791     ,249,249,249
BEGIN DESCRIPTION:
Mapping XS e3dacd6d
END DESCRIPTION:
XS GIS Cut Line= 4
      2731022.51     10036348.61      2731231.92     10036176.22
      2731243.44     10035897.56      2731023.01     10035685.94
#Sta/Elev= 30
    4606 1735.99  4649.6 1732.96  4684.7  1732.3  4699.1 1730.95  4705.5 1730.96
  4719.9 1729.51  4734.2 1726.82  4762.9 1722.82  4826.8 1718.99  4841.1 1717.55
  4869.8 1715.69  4909.7 1714.73  4941.8 1713.33  4979.8 1708.68  4991.9 1706.96
  4996.8 1705.95  4999.6 1705.45  5002.8 1705.95  5009.8 1708.21  5029.9 1708.87
  5089.9 1712.64  5137.4  1713.1  5195.7 1714.42  5289.6 1717.96    5332 1721.21
  5367.5 1725.92  5374.5 1727.31  5388.6 1728.68  5452.4 1731.11  5461.7 1732.21
#Mann= 7 ,-1 , 0
    4606      .1       0  4941.8     .16       0  4991.9      .1       0
  4996.8     .07       0  5002.8      .1       0  5137.4     .16       0
  5195.7      .1       0
Bank Sta=4979.8,5009.8
XS Rating Curve= 0 ,0
Exp/Cntr=0.3,0.1

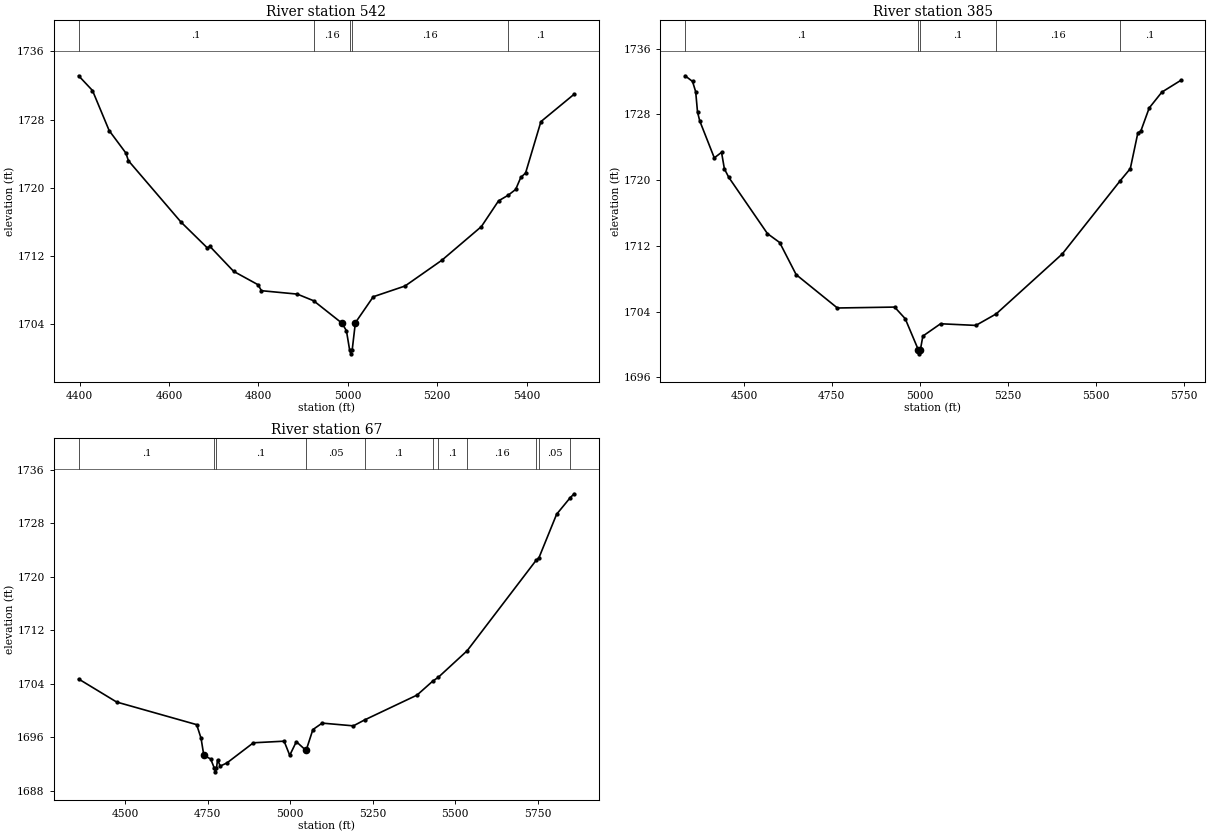
Type RM Length L Ch R = 1 ,542     ,157,157,157
BEGIN DESCRIPTION:
Mapping XS e5ef5b8a
END DESCRIPTION:
XS GIS Cut Line= 4
      2731075.68     10036373.69      2731420.72     10036174.05
      2731427.23     10035887.59      2731052.65     10035690.56
#Sta/Elev= 30
  4397.8 1733.14  4428.8 1731.41  4466.1 1726.71  4503.4 1724.08  4509.2 1723.17
  4626.8 1715.97  4685.7 1712.94  4691.4 1713.12  4744.5 1710.19  4799.1 1708.62
  4806.7 1707.92  4886.8 1707.52  4923.4 1706.74  4986.8 1704.11  4996.8 1703.22
  5003.8 1701.01  5006.6 1700.51  5009.8 1701.01  5016.8 1704.16  5056.8 1707.21
  5127.9 1708.47  5210.4  1711.5  5298.6 1715.44    5337 1718.46  5358.5 1719.12
  5375.3  1719.8  5386.8 1721.21  5397.5 1721.73  5431.8 1727.76  5506.2 1730.98
#Mann= 5 ,-1 , 0
  4397.8      .1       0  4923.4     .16       0  5003.8     .07       0
  5009.8     .16       0  5358.5      .1       0
Bank Sta=4986.8,5016.8
XS Rating Curve= 0 ,0
Exp/Cntr=0.3,0.1

Type RM Length L Ch R = 1 ,385     ,318,318,318
BEGIN DESCRIPTION:
UNT 1059 IN HEWA 2.0
END DESCRIPTION:
XS GIS Cut Line= 4
      2731108.07     10036377.17      2731535.16     10036267.79
      2731571.61     10035877.17      2731035.14     10035668.83
#Sta/Elev= 30
  4332.8  1732.7  4353.9 1732.01  4362.9 1730.76  4368.1 1728.29  4374.5  1727.2
  4415.8 1722.71  4436.4 1723.38  4444.5 1721.37  4457.1 1720.33  4566.9 1713.49
  4601.6 1712.41  4648.5  1708.5  4765.7 1704.44  4928.4 1704.55  4958.5 1703.14
  4995.7 1699.36  4998.5 1698.86  5001.7 1699.36  5008.7 1701.02    5059 1702.52
  5159.4 1702.32  5217.1 1703.72  5405.1 1711.02  5568.3 1719.85  5598.4  1721.4
  5619.9 1725.75  5628.3 1725.97  5652.1 1728.78  5688.1 1730.71  5741.5 1732.13
#Mann= 5 ,-1 , 0
  4332.8      .1       0  4995.7     .07       0  5001.7      .1       0
  5217.1     .16       0  5568.3      .1       0
Bank Sta=4995.7,5001.7
XS Rating Curve= 0 ,0
Exp/Cntr=0.3,0.1

Type RM Length L Ch R = 1 ,67      ,0,0,0
BEGIN DESCRIPTION:
UNT 1059 IN HEWA 1.0
END DESCRIPTION:
XS GIS Cut Line= 4
      2731503.94     10036450.06      2731852.86     10036184.46
      2731837.24     10035882.38      2731128.93     10035606.34
#Sta/Elev= 30
  4359.5 1704.71  4474.6 1701.27  4717.1 1697.89  4730.4 1695.85  4738.7 1693.31
  4759.5 1692.76    4771 1691.34  4773.8 1690.84    4777 1691.34  4780.3 1692.63
  4788.6  1691.7  4808.8 1692.17  4888.9 1695.18    4982 1695.42    4999 1693.31
    5019 1695.34  5048.6 1694.03  5069.1 1697.15  5097.3 1698.12  5191.8 1697.71
  5226.1  1698.6  5384.8 1702.31  5432.2 1704.39    5449 1704.96  5536.3 1708.92
  5745.7 1722.46  5753.9 1722.81  5807.5 1729.32  5848.6 1731.79  5860.7 1732.38
#Mann= 11 ,-1 , 0
  4359.5      .1       0    4771     .07       0    4777      .1       0
  5048.6     .05       0  5226.1      .1       0  5432.2     .16       0
    5449      .1       0  5536.3     .16       0  5745.7      .1       0
  5753.9     .05       0  5848.6      .1       0
Bank Sta=4738.7,5048.6
XS Rating Curve= 0 ,0
Exp/Cntr=0.3,0.1

Chan Stop Cuts=-1
Use User Specified Reach Order=0
Composite Channel Slope=5