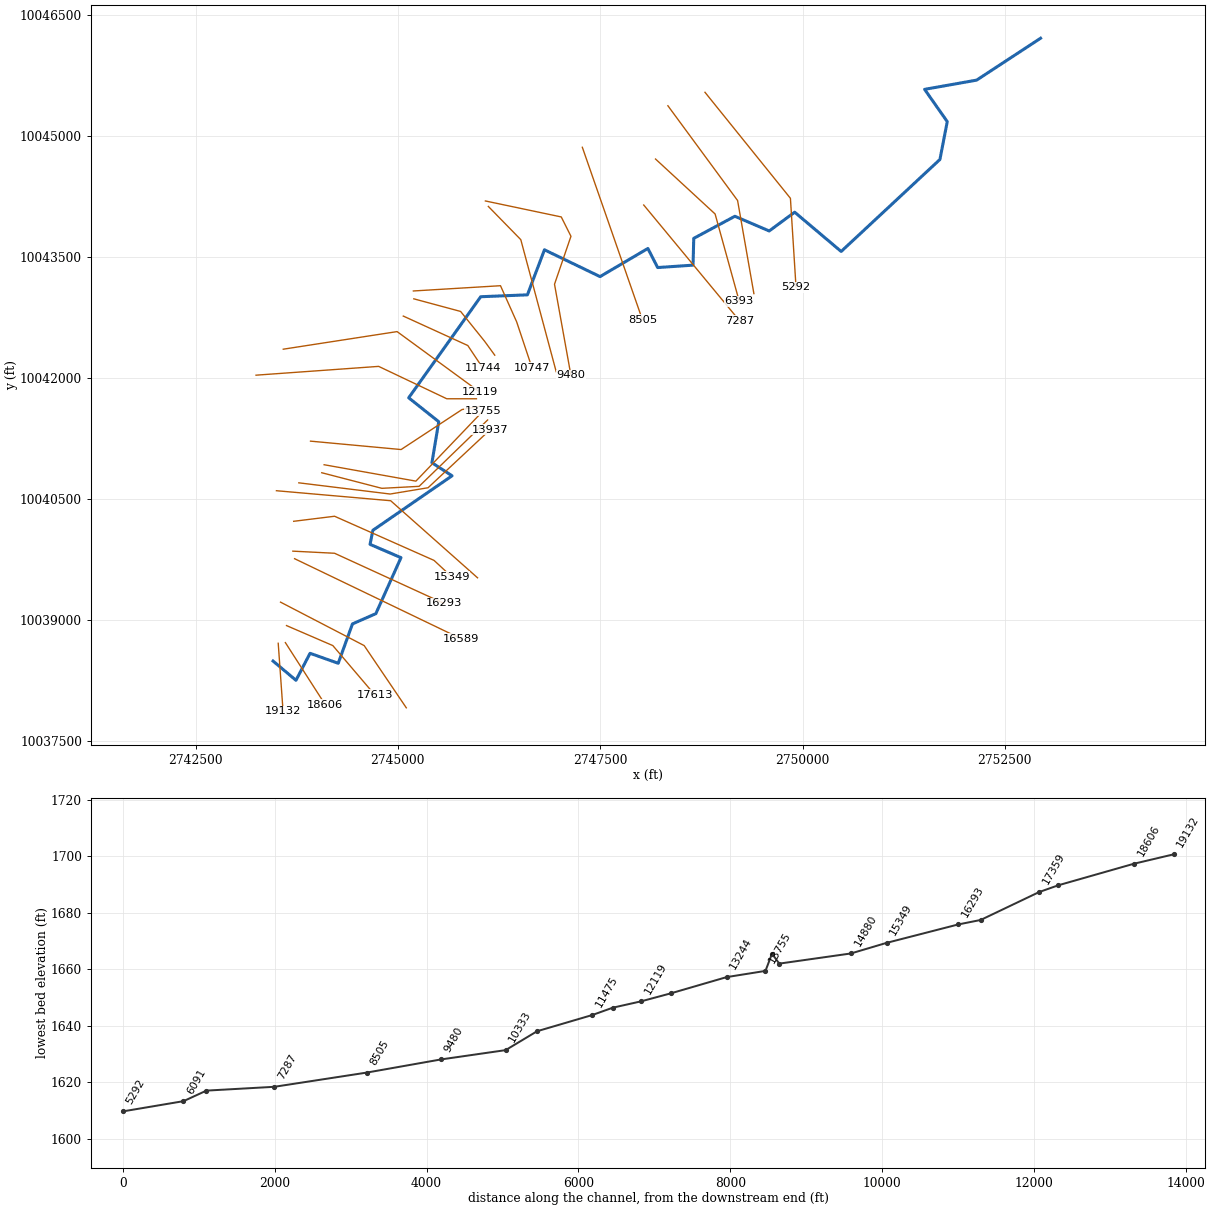
--- UNT 1060 IN HEWA.prj (project) ---

Proj Title=UNT 1060 IN HEWA Base Level Engineering
Current Plan=p01
Default Exp/Contr=0.3,0.1
English Units
Geom File=g01
Flow File=f01
Plan File=p01
Y Axis Title=Elevation
X Axis Title(PF)=Main Channel Distance
X Axis Title(XS)=Station
BEGIN DESCRIPTION:
UNT 1060 IN HEWA
END DESCRIPTION:
DSS Export Rating Curves= 0
DSS Export Rating Curve Sorted= 0
DSS Export Volume Flow Curves= 0
DXF OffsetX= 0
DXF OffsetY= 0
DXF ScaleX= 1
DXF ScaleY= 10

--- UNT 1060 IN HEWA.p01 (plan) ---

Plan Title=Multiple Run
Short Identifier=Multiple
Geom File=g01
Flow File=f01
Subcritical Flow
K Sum by GR= 0
Std Step Tol= 0.01
Critical Tol= 0.01
Num of Std Step Trials= 20
Max Error Tol= 0.3
Flow Tol Ratio= 0.001
Split Flow NTrial= 30
Split Flow Tol= 0.02
Split Flow Ratio= 0.02
Log Output Level= 0
Friction Slope Method= 1
Unsteady Friction Slope Method= 2
Unsteady Bridges Friction Slope Method= 1
Parabolic Critical Depth
Global Vel Dist=  1 , 1 , 1
Global Log Level= 0
CheckData=True
Encroach Param= -1, 0, 0, 0
BEGIN DESCRIPTION:
Multiple Run
END DESCRIPTION:

--- UNT 1060 IN HEWA.f01 (steady flow) ---

Flow Title=Multiple
Program Version=4.10
Number of Profiles= 7
Profile Names=10-year,25-year,50-year,1pct_min,100-year,1pct_plu,500-year
River Rch & RM=UNT 1060 IN HEWA,Reach-1         ,19132
     776    1121    1420    1318    1782    2410    2816
River Rch & RM=UNT 1060 IN HEWA,Reach-1         ,17613
    1087    1594    2038    1905    2576    3483    4135
River Rch & RM=UNT 1060 IN HEWA,Reach-1         ,10333
    1910    2880    3750    3564    4820    6519    8006
River Rch & RM=UNT 1060 IN HEWA,Reach-1         ,9480
    1910    2880    3750    3564    4820    6519    8006
River Rch & RM=UNT 1060 IN HEWA,Reach-1         ,7287
    2512    3825    5014    4791    6479    8762   10880
River Rch & RM=UNT 1060 IN HEWA,Reach-1         ,4587
    2512    3825    5014    4791    6479    8762   10880
Boundary for River Rch & Prof#=UNT 1060 IN HEWA,Reach-1         , 1
Up Type= 0
Dn Type= 3
Dn Slope=0.005
Boundary for River Rch & Prof#=UNT 1060 IN HEWA,Reach-1         , 2
Up Type= 0
Dn Type= 3
Dn Slope=0.005
Boundary for River Rch & Prof#=UNT 1060 IN HEWA,Reach-1         , 3
Up Type= 0
Dn Type= 3
Dn Slope=0.005
Boundary for River Rch & Prof#=UNT 1060 IN HEWA,Reach-1         , 4
Up Type= 0
Dn Type= 3
Dn Slope=0.005
Boundary for River Rch & Prof#=UNT 1060 IN HEWA,Reach-1         , 5
Up Type= 0
Dn Type= 3
Dn Slope=0.005
Boundary for River Rch & Prof#=UNT 1060 IN HEWA,Reach-1         , 6
Up Type= 0
Dn Type= 3
Dn Slope=0.005
Boundary for River Rch & Prof#=UNT 1060 IN HEWA,Reach-1         , 7
Up Type= 0
Dn Type= 3
Dn Slope=0.005
DSS Import GetInterval= 0
DSS Import GetPeak= 0
DSS Import FillOption= 0

--- UNT 1060 IN HEWA.g01 (geometry) ---

Geom Title=Existing Conditions
Program Version=4.10

River Reach=UNT 1060 IN HEWA,Reach-1
Reach XY= 30
      2743457.64      10038493.6      2743741.18     10038255.42
      2743914.88     10038589.42      2744263.32     10038465.96
      2744439.03     10038953.55      2744727.98      10039080.6
      2745038.47     10039774.13      2744656.29      10039938.7
      2744690.91     10040112.72      2745669.53     10040787.89
      2745421.11     10040949.65      2745505.21     10041457.24
      2745134.07     10041753.98      2746023.62      10043005.6
      2746600.86     10043029.07      2746811.09     10043586.73
       2747498.1     10043254.86      2748089.27      10043603.4
      2748209.94     10043366.88      2748647.32     10043396.68
      2748655.94     10043728.45      2749163.91     10044001.94
      2749588.11     10043820.08      2749902.72     10044052.42
      2750477.42     10043566.21      2751697.69      10044705.6
      2751788.19     10045174.37      2751508.45     10045573.85
      2752151.35     10045688.16      2752941.39     10046206.91

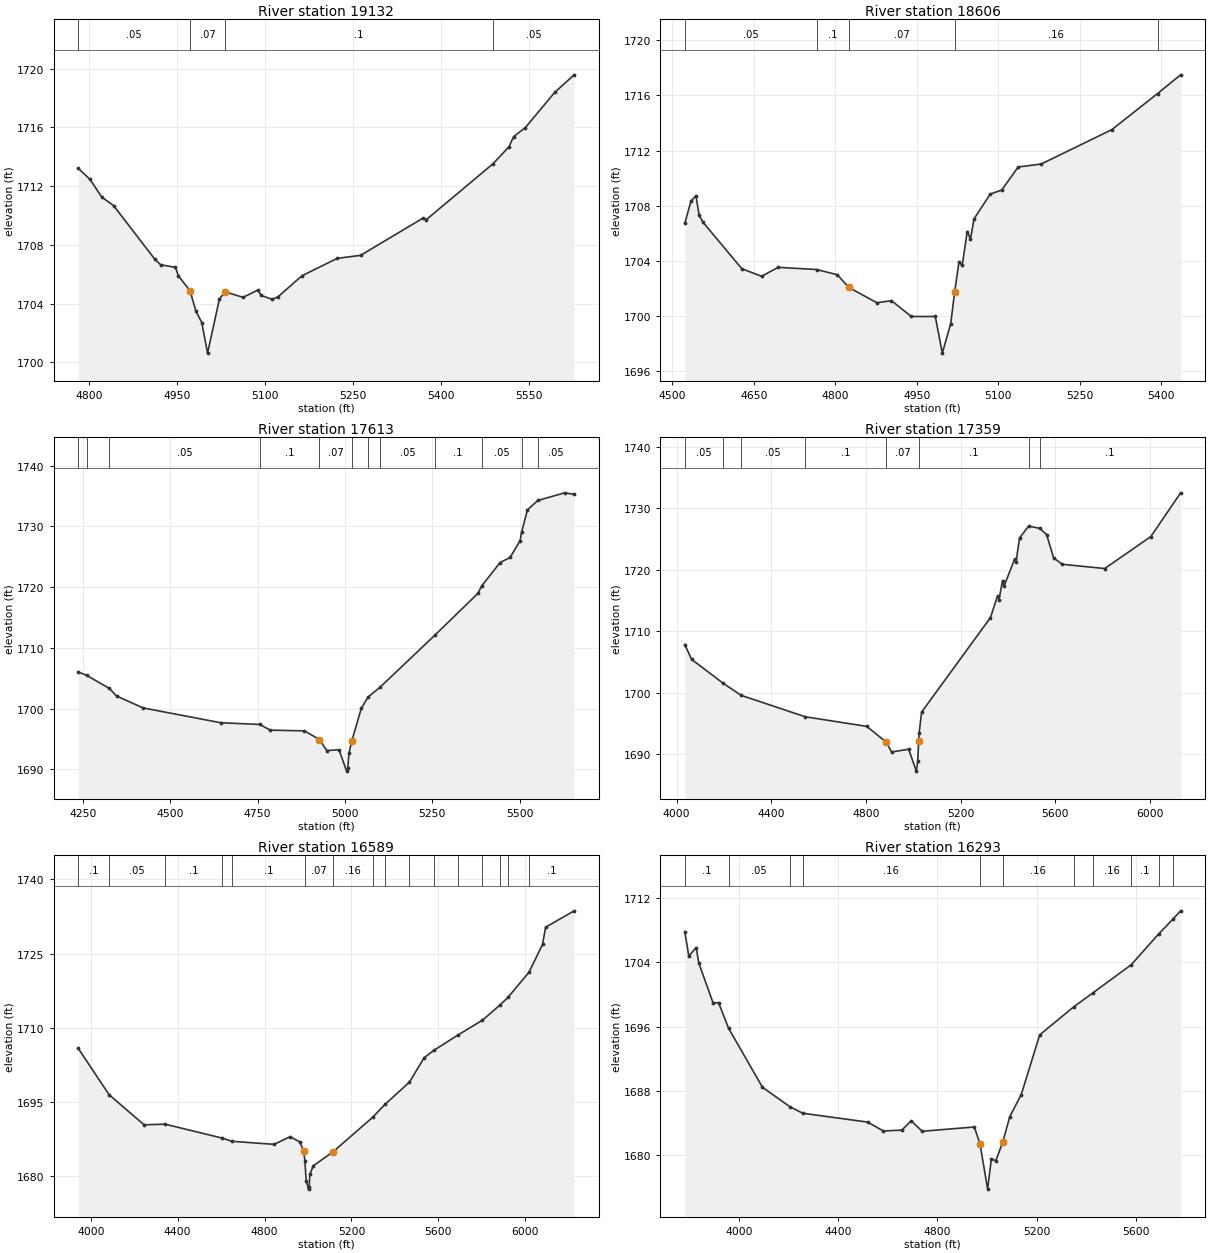
Type RM Length L Ch R = 1 ,19132   ,526,526,526
BEGIN DESCRIPTION:
UNT 1060 IN HEWA 31.0
END DESCRIPTION:
XS GIS Cut Line= 2
      2743521.74     10038713.59      2743581.53      10037870.8
#Sta/Elev= 30
  4781.6 1713.21  4801.3 1712.47  4821.6 1711.25  4841.6 1710.68  4911.8 1707.03
  4921.8 1706.65  4947.1 1706.47  4952.1 1705.89  4971.9 1704.88    4982 1703.49
    4992 1702.71  5001.8 1700.63  5022.1 1704.33  5032.1  1704.8  5062.2 1704.43
  5087.9 1704.93  5092.9 1704.56  5112.3 1704.29  5122.3 1704.48  5162.4 1705.89
  5222.6 1707.08  5262.7 1707.29  5369.6 1709.84  5374.6 1709.72  5488.1 1713.52
  5515.4 1714.68  5523.3 1715.37  5543.4 1715.99  5593.5 1718.39  5626.5 1719.58
#Mann= 4 ,-1 , 0
  4781.6     .05       0  4971.9     .07       0  5032.1      .1       0
  5488.1     .05       0
Bank Sta=4971.9,5032.1
XS Rating Curve= 0 ,0
Exp/Cntr=0.3,0.1

Type RM Length L Ch R = 1 ,18606   ,993,993,993
BEGIN DESCRIPTION:
Mapping XS d9e386d6
END DESCRIPTION:
XS GIS Cut Line= 2
      2743609.98     10038722.15      2744102.54     10037953.41
#Sta/Elev= 30
    4523 1706.71  4534.2 1708.31  4543.5 1708.73  4549.4  1707.3  4556.8 1706.78
    4628 1703.42  4664.4 1702.87  4694.8 1703.52  4766.2 1703.36  4803.9 1702.98
    4825 1702.06  4876.6 1700.95  4903.6  1701.1    4940 1699.95  4984.3 1699.95
  4997.2 1697.29  5012.7 1699.44  5019.9 1701.73  5027.9 1703.92  5033.8 1703.66
  5043.1 1706.12    5049 1705.57  5055.6 1707.04  5085.4 1708.84  5106.5 1709.13
    5137 1710.81  5179.2 1711.02  5309.4 1713.52  5393.5 1716.14    5436  1717.5
#Mann= 5 ,-1 , 0
    4523     .05       0  4766.2      .1       0    4825     .07       0
  5019.9     .16       0  5393.5      .1       0
Bank Sta=4825,5019.9
XS Rating Curve= 0 ,0
Exp/Cntr=0.3,0.1

Type RM Length L Ch R = 1 ,17613   ,254,254,254
BEGIN DESCRIPTION:
UNT 1060 IN HEWA 30.0
END DESCRIPTION:
XS GIS Cut Line= 3
      2743624.26      10038932.8      2744196.52     10038685.11
       2744711.8     10038078.73
#Sta/Elev= 30
  4236.6 1706.02  4260.2 1705.47  4325.2 1703.32  4346.1 1702.06    4422  1700.1
  4644.3 1697.66  4755.8 1697.38    4786 1696.44    4884 1696.32  4926.8 1694.89
  4947.7 1693.08  4982.8 1693.21  5004.6 1689.69  5007.8 1690.19  5011.4 1692.67
  5019.1  1694.6  5046.5 1700.01    5066 1701.89  5100.7 1703.53  5256.4 1712.04
  5380.4 1718.96  5391.3 1720.21  5444.1 1724.05  5472.7 1724.89  5501.2 1727.66
  5505.4 1729.02  5522.1 1732.73  5551.9 1734.27  5628.6 1735.53  5655.9 1735.28
#Mann= 12 ,-1 , 0
  4236.6     .05       0  4260.2      .1       0  4325.2     .05       0
  4755.8      .1       0  4926.8     .07       0  5019.1     .05       0
    5066      .1       0  5100.7     .05       0  5256.4      .1       0
  5391.3     .05       0  5505.4      .1       0  5551.9     .05       0
Bank Sta=4926.8,5019.1
XS Rating Curve= 0 ,0
Exp/Cntr=0.3,0.1

Type RM Length L Ch R = 1 ,17359   ,770,770,770
BEGIN DESCRIPTION:
UNT 1060 IN HEWA 29.0
END DESCRIPTION:
XS GIS Cut Line= 3
      2743550.22     10039223.22      2744583.73     10038685.11
      2745104.13     10037914.47
#Sta/Elev= 30
  4034.6 1707.85  4063.4 1705.44  4196.2 1701.57    4273 1699.59  4543.8 1696.11
  4803.6 1694.55  4886.3 1691.97  4908.4 1690.39  4980.4 1690.84    5013 1687.28
  5018.9 1688.85 5022.73 1692.24  5024.8  1693.5  5035.4 1696.88  5326.3 1712.23
  5356.2 1715.77  5362.3 1715.14  5377.2 1718.25  5383.3 1717.31  5428.2 1721.73
  5434.2 1721.28  5449.2 1725.16  5487.7 1727.11  5534.4 1726.72  5563.5 1725.71
    5593 1721.94    5629 1720.89  5808.9  1720.2  6003.7 1725.39  6129.7  1732.5
#Mann= 8 ,-1 , 0
  4034.6     .05       0  4196.2      .1       0    4273     .05       0
  4543.8      .1       0  4886.3     .07       0  5024.8      .1       0
  5487.7     .05       0  5534.4      .1       0
Bank Sta=4886.3,5022.73
XS Rating Curve= 0 ,0
Exp/Cntr=0.3,0.1

Type RM Length L Ch R = 1 ,16589   ,296,296,296
BEGIN DESCRIPTION:
UNT 1060 IN HEWA 28.0
END DESCRIPTION:
XS GIS Cut Line= 2
      2743723.92     10039761.32       2745779.5     10038770.54
#Sta/Elev= 30
  3942.9 1705.82  4084.8 1696.47  4245.2 1690.41  4342.4 1690.53  4604.1 1687.73
  4650.1 1687.07  4844.3 1686.46  4917.7 1688.01    4963 1686.91    4980 1685.05
  4985.6 1683.19  4991.4 1679.13  5002.3 1677.41  5005.5 1677.91  5008.2  1680.4
  5024.7 1682.14  5113.6 1684.89  5297.4 1691.92    5355 1694.56  5466.8 1699.03
  5533.9 1703.93  5578.8 1705.43  5690.6 1708.56  5802.5 1711.53  5882.6 1714.57
    5920 1716.14  6016.8 1721.21  6079.3 1726.84  6093.4 1730.32  6224.8 1733.63
#Mann= 16 ,-1 , 0
  3942.9      .1       0  4084.8     .05       0  4342.4      .1       0
  4604.1     .05       0  4650.1      .1       0  4985.6     .07       0
  5113.6     .16       0  5297.4      .1       0    5355     .16       0
  5466.8      .1       0  5578.8     .16       0  5690.6      .1       0
  5802.5     .16       0  5882.6      .1       0    5920     .16       0
  6016.8      .1       0
Bank Sta=4980,5113.6
XS Rating Curve= 0 ,0
Exp/Cntr=0.3,0.1

Type RM Length L Ch R = 1 ,16293   ,944,944,944
BEGIN DESCRIPTION:
UNT 1060 IN HEWA 27.0
END DESCRIPTION:
XS GIS Cut Line= 3
       2743702.4     10039854.59      2744218.02     10039828.55
      2745565.24     10039209.55
#Sta/Elev= 30
  3781.7 1707.82  3797.8 1704.78  3827.8 1705.84  3837.8 1703.94  3895.4 1698.98
  3917.9 1698.98  3957.9 1695.83  4094.6 1688.48  4204.5 1686.08  4256.9 1685.25
  4518.6 1684.15    4582 1683.05  4656.5 1683.15  4694.6 1684.31  4738.7 1683.01
  4948.8 1683.54  4971.7 1681.47  5002.5 1675.82  5017.7  1679.6  5035.2 1679.33
  5063.7 1681.68  5092.1 1684.84  5138.1 1687.57  5212.5 1694.99  5350.4 1698.49
  5426.3 1700.19  5581.5  1703.7  5692.3 1707.54  5750.9 1709.41  5780.6  1710.4
#Mann= 11 ,-1 , 0
  3781.7      .1       0  3957.9     .05       0  4204.5      .1       0
  4256.9     .16       0  4971.7     .05       0  5063.7     .16       0
  5350.4      .1       0  5426.3     .16       0  5581.5      .1       0
  5692.3     .16       0  5750.9      .1       0
Bank Sta=4971.7,5063.7
XS Rating Curve= 0 ,0
Exp/Cntr=0.3,0.1

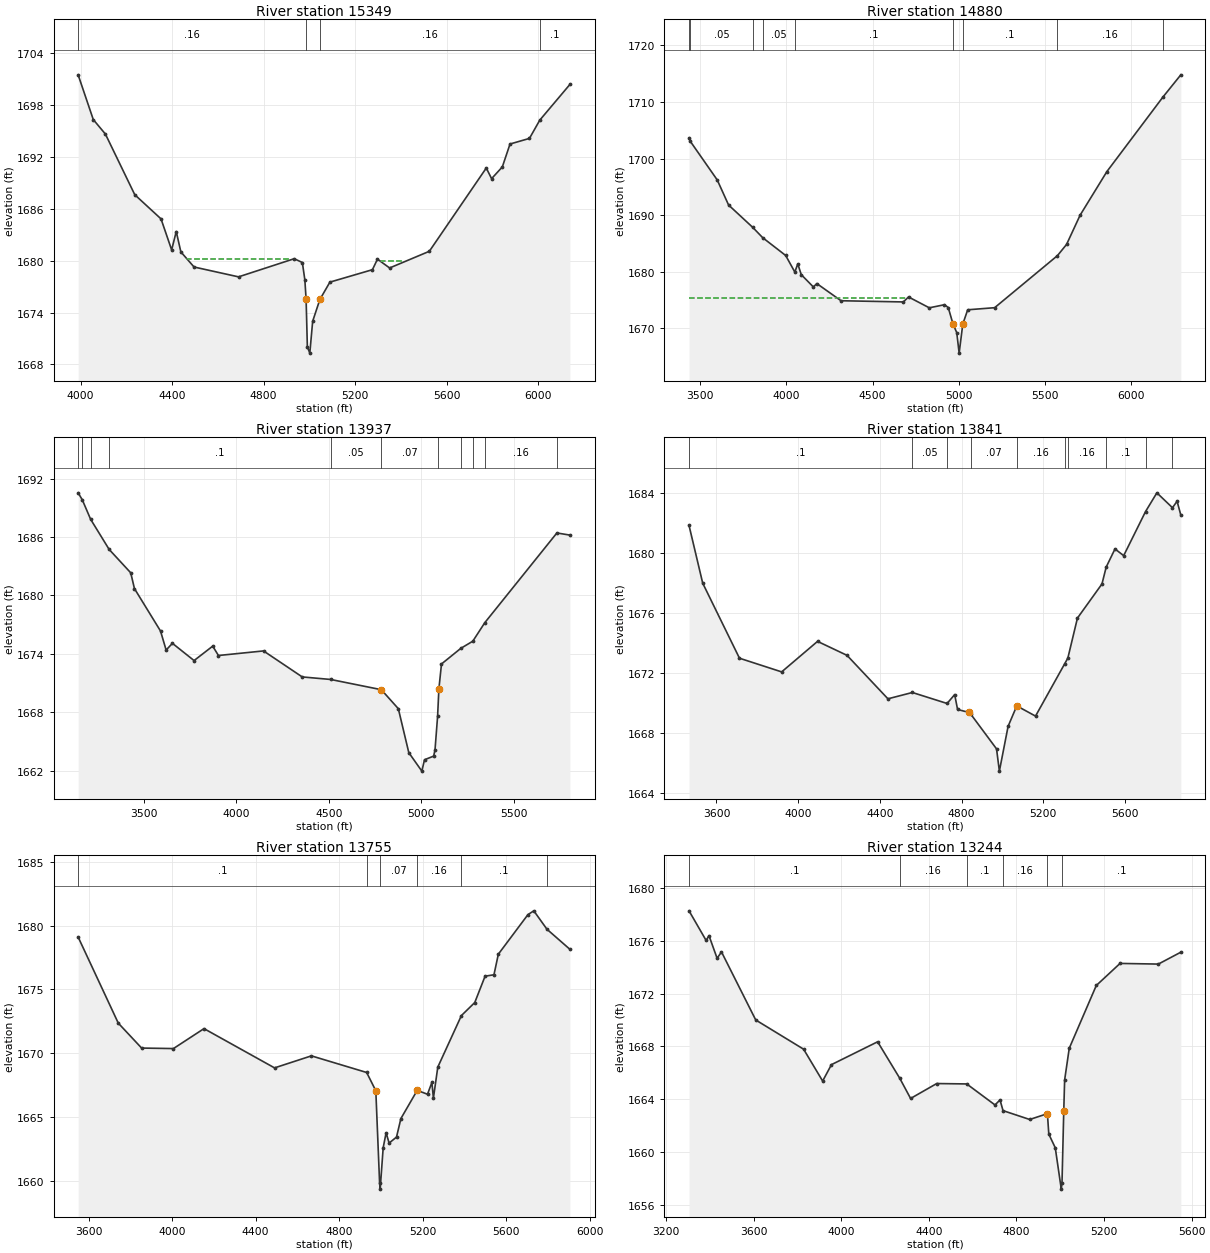
Type RM Length L Ch R = 1 ,15349   ,469,469,469
BEGIN DESCRIPTION:
UNT 1060 IN HEWA 26.0
END DESCRIPTION:
XS GIS Cut Line= 4
      2743712.78     10040224.38      2744218.02     10040286.88
      2745447.18     10039740.01      2745663.71     10039538.95
#Sta/Elev= 30
  3989.3 1701.52  4055.5 1696.34  4108.6 1694.66  4236.9 1687.64  4351.7 1684.84
  4398.1 1681.25  4418.2 1683.38  4438.4 1681.02  4496.1 1679.27  4690.5 1678.13
  4933.9 1680.23  4969.5 1679.79  4980.4 1677.79  4985.9 1675.53  4991.4 1670.02
  5002.1  1669.3  5014.6 1672.99  5046.1 1675.51  5089.9 1677.52  5275.8 1678.96
  5297.9 1680.18    5351 1679.16  5524.6 1681.09  5773.5 1690.73  5796.8  1689.5
  5843.7 1690.86  5877.3 1693.51  5962.3 1694.16  6007.3 1696.27  6139.2 1700.41
#Mann= 4 ,-1 , 0
  3989.3     .16       0  4985.9    .035       0  5046.1     .16       0
  6007.3      .1       0
#XS Ineff= 2 ,-1
 4459.66 4916.48 1680.17 5313.64  5410.8 1680.02
Permanent Ineff=
       T       T
Bank Sta=4985.9,5046.1
XS Rating Curve= 0 ,0
Exp/Cntr=0.3,0.1

Type RM Length L Ch R = 1 ,14880   ,943,943,943
BEGIN DESCRIPTION:
UNT 1060 IN HEWA 25.0
END DESCRIPTION:
XS GIS Cut Line= 3
      2743499.89     10040602.97      2744911.12     10040479.18
      2745984.54     10039524.48
#Sta/Elev= 30
  3434.7 1703.66  3441.7 1703.06  3598.3 1696.21  3664.2 1691.77  3804.4 1687.81
  3861.7    1686  3995.4 1682.84  4048.5 1679.91  4065.7 1681.36  4085.8 1679.45
    4156 1677.27  4176.1 1677.87  4316.7 1674.83    4678 1674.62  4708.2  1675.5
  4828.6 1673.58  4916.8 1674.13  4938.5 1673.63 4966.76 1670.66  4987.9 1669.19
  5001.8 1665.56    5023  1670.7  5051.4 1673.23  5207.8  1673.6    5572 1682.81
  5625.1  1684.8  5703.7 1689.98  5859.2  1697.7  6184.4 1710.89  6287.9 1714.81
#Mann= 9 ,-1 , 0
  3434.7      .1       0  3441.7     .05       0  3804.4      .1       0
  3861.7     .05       0  4048.5      .1       0 4966.76     .05       0
    5023      .1       0    5572     .16       0  6184.4      .1       0
#XS Ineff= 2 , 0
         4697.83 1675.34
Permanent Ineff=
       T       T
Bank Sta=4966.76,5023
XS Rating Curve= 0 ,0
Exp/Cntr=0.3,0.1

Type RM Length L Ch R = 1 ,13937   ,96,96,96
BEGIN DESCRIPTION:
Mapping XS e1b7f459
END DESCRIPTION:
XS GIS Cut Line= 4
      2743776.22     10040700.88      2744904.66       10040562.
      2745373.41     10040640.12      2746137.33     10041356.29
#Sta/Elev= 30
  3144.3 1690.54  3166.6 1689.83    3212 1687.82    3312 1684.73  3428.7 1682.33
  3448.8 1680.71  3589.9 1676.35  3620.1  1674.4  3654.2 1675.09  3771.2 1673.32
    3872  1674.8    3903 1673.84  4146.7 1674.31  4356.1 1671.64  4509.8 1671.38
  4783.8 1670.33  4875.7 1668.38  4932.3 1663.87  5002.9 1661.97  5017.3 1663.14
  5066.7 1663.51    5074 1664.13  5088.1 1667.61    5095 1670.41  5109.1 1672.97
  5213.3 1674.57  5278.5 1675.31  5343.3 1677.21  5733.1 1686.42  5803.6  1686.2
#Mann= 11 ,-1 , 0
  3144.3     .05       0  3166.6      .1       0    3212     .05       0
    3312      .1       0  4509.8     .05       0  4783.8     .07       0
  5088.1      .1       0  5213.3     .16       0  5278.5      .1       0
  5343.3     .16       0  5733.1      .1       0
Bank Sta=4783.8,5095
XS Rating Curve= 0 ,0
Exp/Cntr=0.3,0.1

Type RM Length L Ch R = 1 ,13841   ,86,86,86
BEGIN DESCRIPTION:
UNT 1060 IN HEWA 24.0
END DESCRIPTION:
XS GIS Cut Line= 4
      2744059.43      10040825.8      2744802.18     10040632.68
       2745262.7     10040657.44      2746109.06     10041479.06
#Sta/Elev= 30
  3465.6 1681.81  3532.6 1677.97  3712.6 1672.98  3919.2 1672.07  4094.9  1674.1
  4239.3 1673.17  4439.6 1670.28  4559.2  1670.7  4729.2 1669.97  4766.4 1670.56
  4780.6 1669.57  4837.2 1669.37  4844.1 1669.28  4971.4 1666.95  4985.3 1665.47
    5028 1668.45  5070.5 1669.81  5162.3 1669.13  5305.1 1672.61  5320.6 1672.99
  5367.6 1675.65  5487.7 1677.92  5508.3 1679.04  5551.5 1680.25  5593.9  1679.8
  5700.9 1682.73  5756.5 1683.98  5832.9 1682.99  5855.5 1683.42  5873.8  1682.5
#Mann= 10 ,-1 , 0
  3465.6      .1       0  4559.2     .05       0  4729.2      .1       0
  4844.1     .07       0  5070.5     .16       0  5305.1      .1       0
  5320.6     .16       0  5508.3      .1       0  5700.9     .16       0
  5832.9      .1       0
Bank Sta=4837.2,5070.5
XS Rating Curve= 0 ,0
Exp/Cntr=0.3,0.1

Type RM Length L Ch R = 1 ,13755   ,511,511,511
BEGIN DESCRIPTION:
Mapping XS 40f61b58
END DESCRIPTION:
XS GIS Cut Line= 3
      2744089.14     10040924.84      2745223.08     10040721.82
      2746054.23     10041592.54
#Sta/Elev= 30
    3550  1679.1  3742.3 1672.37  3854.1 1670.42  4006.5 1670.38  4152.9 1671.94
  4490.8 1668.87  4667.3 1669.81  4932.1 1668.51  4975.9 1667.08    4994 1659.89
  4996.8 1659.39  5011.2 1662.63  5025.3  1663.8  5039.5 1662.99    5075 1663.46
  5096.1 1664.91  5174.1 1667.11  5223.5 1666.81  5244.5 1667.73  5251.8 1666.51
  5272.8 1668.93  5385.9 1672.96  5449.9 1673.98  5499.3 1676.04  5541.8 1676.15
  5562.8 1677.76  5704.4 1680.85  5732.7 1681.15  5795.7 1679.71  5905.7 1678.14
#Mann= 6 ,-1 , 0
    3550      .1       0  4932.1     .16       0    4994     .07       0
  5174.1     .16       0  5385.9      .1       0  5795.7     .16       0
Bank Sta=4975.9,5174.1
XS Rating Curve= 0 ,0
Exp/Cntr=0.3,0.1

Type RM Length L Ch R = 1 ,13244   ,735,735,735
BEGIN DESCRIPTION:
UNT 1060 IN HEWA 23.0
END DESCRIPTION:
XS GIS Cut Line= 4
       2743920.8     10041216.99      2745039.87     10041113.01
      2745792.54     10041608.19      2746010.42      10041647.8
#Sta/Elev= 30
  3304.9 1678.26  3382.9 1676.02  3396.1 1676.38  3433.1 1674.67  3453.2 1675.15
  3609.6    1670  3828.2 1667.79  3915.2 1665.38  3955.4 1666.62  4166.3 1668.35
  4267.4 1665.59  4316.9 1664.06  4436.2 1665.19  4573.3 1665.16  4702.4 1663.57
  4725.4 1663.95  4739.1 1663.14  4860.9 1662.47  4941.8 1662.91  4948.2 1661.36
  4977.7 1660.33  5005.2  1657.2  5008.5  1657.7 5016.48  1663.1  5020.5 1665.46
  5041.6 1667.86  5165.1 1672.61  5273.6 1674.28  5448.6 1674.23  5551.2 1675.13
#Mann= 6 ,-1 , 0
  3304.9      .1       0  4267.4     .16       0  4573.3      .1       0
  4739.1     .16       0  4941.8     .07       0  5008.5      .1       0
Bank Sta=4941.8,5016.48
XS Rating Curve= 0 ,0
Exp/Cntr=0.3,0.1

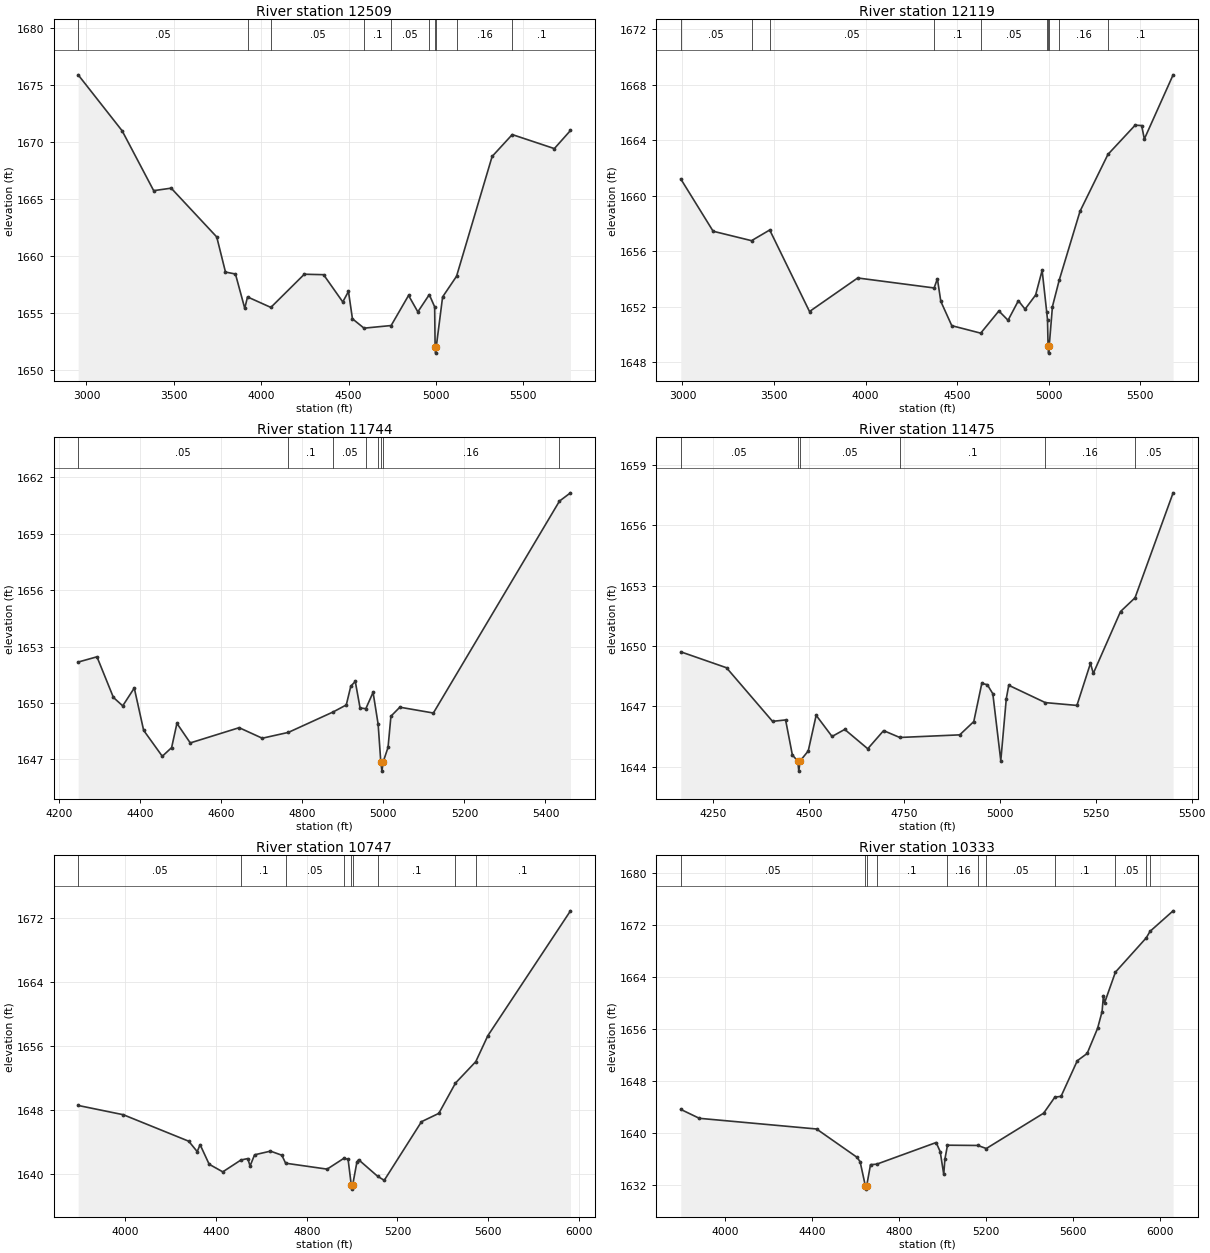
Type RM Length L Ch R = 1 ,12509   ,390,390,390
BEGIN DESCRIPTION:
UNT 1060 IN HEWA 22.0
END DESCRIPTION:
XS GIS Cut Line= 4
      2743247.31     10042034.04      2744762.57     10042142.98
      2745604.37     10041741.89      2745970.83     10041741.89
#Sta/Elev= 30
  2952.4 1675.87  3204.2 1670.96  3384.7 1665.71  3484.9 1665.93  3745.6 1661.65
  3795.7 1658.57  3852.7  1658.4    3906 1655.39  3921.8 1656.39  4055.4 1655.47
  4246.9 1658.38  4357.2 1658.34    4467 1655.95  4499.7 1656.87  4522.4 1654.47
  4588.7 1653.65  4743.9 1653.88  4843.6 1656.52  4896.7 1655.08  4962.2 1656.59
    4993 1655.52  4995.7 1651.96  4998.5 1651.46  5001.7 1651.96  5038.5 1656.39
  5118.2  1658.2  5321.9 1668.71  5437.1 1670.63  5678.1  1669.4  5770.5 1670.99
#Mann= 10 ,-1 , 0
  2952.4     .05       0  3921.8      .1       0  4055.4     .05       0
  4588.7      .1       0  4743.9     .05       0  4962.2      .1       0
  4995.7     .07       0  5001.7      .1       0  5118.2     .16       0
  5437.1      .1       0
Bank Sta=4995.7,5001.7
XS Rating Curve= 0 ,0
Exp/Cntr=0.3,0.1

Type RM Length L Ch R = 1 ,12119   ,375,375,375
BEGIN DESCRIPTION:
UNT 1060 IN HEWA 21.0
END DESCRIPTION:
XS GIS Cut Line= 3
      2743583.99      10042355.9      2744990.35     10042573.79
      2746010.42     10041826.07
#Sta/Elev= 30
  2990.7  1661.2  3167.3 1657.43    3377 1656.75  3476.2 1657.52  3693.5 1651.64
  3956.6 1654.06  4373.8 1653.34  4391.7    1654  4410.4 1652.37  4470.2 1650.62
  4628.2 1650.08  4727.3 1651.68  4777.4 1651.01  4833.8 1652.42  4870.3 1651.81
  4927.9 1652.83  4963.5 1654.61  4988.2 1651.64  4992.8 1651.06    4996 1649.14
  4998.7 1648.64    5002 1649.14  5019.8    1652  5056.5 1653.89  5170.3 1658.87
  5322.7 1662.97  5471.4 1665.08  5506.9 1665.05  5521.5 1664.08  5678.6 1668.71
#Mann= 10 ,-1 , 0
  2990.7     .05       0    3377      .1       0  3476.2     .05       0
  4373.8      .1       0  4628.2     .05       0  4988.2      .1       0
    4996     .07       0    5002      .1       0  5056.5     .16       0
  5322.7      .1       0
Bank Sta=4996,5002
XS Rating Curve= 0 ,0
Exp/Cntr=0.3,0.1

Type RM Length L Ch R = 1 ,11744   ,269,269,269
BEGIN DESCRIPTION:
UNT 1060 IN HEWA 20.0
END DESCRIPTION:
XS GIS Cut Line= 3
      2745066.97     10042766.05      2745863.85     10042401.46
      2746051.32     10042120.25
#Sta/Elev= 30
  4247.4 1652.18  4293.8 1652.46  4334.3  1650.3  4357.3 1649.85  4385.8  1650.8
  4408.9 1648.55  4454.9 1647.17  4477.9 1647.63    4491 1648.92  4523.9 1647.88
  4644.5 1648.69  4701.5 1648.13  4765.9 1648.44  4876.6 1649.53  4908.7  1649.9
  4919.9  1650.9  4930.9 1651.15  4942.7 1649.74  4956.9  1649.7  4974.8 1650.57
  4987.3 1648.87  4993.8 1646.88  4996.6 1646.38  4999.8 1646.88  5011.7 1647.64
  5018.8  1649.3  5040.8 1649.78  5123.5 1649.47  5434.5 1660.74  5461.7 1661.18
#Mann= 8 ,-1 , 0
  4247.4     .05       0  4765.9      .1       0  4876.6     .05       0
  4956.9      .1       0  4987.3     .16       0  4993.8     .07       0
  4999.8     .16       0  5434.5      .1       0
Bank Sta=4993.8,4999.8
XS Rating Curve= 0 ,0
Exp/Cntr=0.3,0.1

Type RM Length L Ch R = 1 ,11475   ,728,728,728
BEGIN DESCRIPTION:
UNT 1060 IN HEWA 19.0
END DESCRIPTION:
XS GIS Cut Line= 4
      2745197.18     10042979.59      2745775.31     10042823.34
      2746072.18     10042453.55      2746197.17     10042281.68
#Sta/Elev= 30
    4166 1649.71  4285.4 1648.92  4405.6 1646.26  4439.7 1646.33  4457.4 1644.59
  4471.4 1644.29  4474.2 1643.79  4477.4 1644.29  4498.8 1644.79  4519.5 1646.56
    4561 1645.51  4594.1 1645.86  4654.2  1644.9  4695.6  1645.8  4737.8 1645.46
  4894.4 1645.59  4931.1 1646.25    4952 1648.14  4966.4 1648.08  4980.8 1647.63
  5001.6 1644.31    5016 1647.39  5022.4 1648.05  5117.9 1647.19  5200.4 1647.05
  5235.8 1649.14  5243.2 1648.64  5314.3 1651.71  5352.1 1652.39  5451.6  1657.6
#Mann= 6 ,-1 , 0
    4166     .05       0  4471.4     .07       0  4477.4     .05       0
  4737.8      .1       0  5117.9     .16       0  5352.1     .05       0
Bank Sta=4471.4,4477.4
XS Rating Curve= 0 ,0
Exp/Cntr=0.3,0.1

Type RM Length L Ch R = 1 ,10747   ,414,414,414
BEGIN DESCRIPTION:
UNT 1060 IN HEWA 18.0
END DESCRIPTION:
XS GIS Cut Line= 4
      2745191.59     10043076.87      2746268.01     10043141.98
      2746467.67     10042694.93      2746658.64     10042122.02
#Sta/Elev= 30
  3791.4 1648.51  3990.7 1647.35  4279.2 1644.04  4316.6 1642.74  4329.3 1643.61
  4369.3 1641.16  4429.4 1640.21  4509.5 1641.69  4539.6 1641.87  4549.7 1640.94
  4569.7 1642.34  4639.8  1642.8  4689.9 1642.29  4706.6 1641.29  4889.8 1640.55
  4962.3 1641.88  4982.1  1641.8  4996.3 1638.55    4999 1638.05  5002.3 1638.55
  5021.2 1641.45  5028.5 1641.73  5112.7 1639.65  5141.7 1639.15    5306 1646.48
  5382.4 1647.52    5456 1651.31  5545.5 1653.99  5598.5 1657.22  5963.3 1672.84
#Mann= 9 ,-1 , 0
  3791.4     .05       0  4509.5      .1       0  4706.6     .05       0
  4962.3     .16       0  4996.3     .07       0  5002.3     .16       0
  5112.7      .1       0    5456     .05       0  5545.5      .1       0
Bank Sta=4996.3,5002.3
XS Rating Curve= 0 ,0
Exp/Cntr=0.3,0.1

Type RM Length L Ch R = 1 ,10333   ,853,853,853
BEGIN DESCRIPTION:
UNT 1060 IN HEWA 17.0
END DESCRIPTION:
XS GIS Cut Line= 3
      2746117.83     10044123.96      2746518.89     10043712.48
      2746956.18     10042077.86
#Sta/Elev= 30
  3794.2 1643.62  3879.6 1642.25  4419.3 1640.61  4605.6 1636.26  4619.9 1635.57
    4644 1631.87  4646.8 1631.37    4650 1631.87  4667.7 1635.13  4696.1  1635.2
    4970 1638.53  4988.6 1637.12  5004.9 1633.63  5010.1 1635.96  5022.1 1638.12
  5161.8 1638.08  5200.9 1637.61  5464.8 1643.04  5516.6 1645.51  5544.9 1645.62
  5619.8  1651.1    5665 1652.21  5713.2 1656.08  5733.9 1658.66    5740  1661.1
  5745.2 1659.99  5795.3 1664.71    5937 1669.97  5954.8 1670.98  6060.9 1674.13
#Mann= 11 ,-1 , 0
  3794.2     .05       0    4644     .07       0    4650     .05       0
  4696.1      .1       0  5022.1     .16       0  5161.8      .1       0
  5200.9     .05       0  5516.6      .1       0  5795.3     .05       0
    5937      .1       0  5954.8     .05       0
Bank Sta=4644,4650
XS Rating Curve= 0 ,0
Exp/Cntr=0.3,0.1

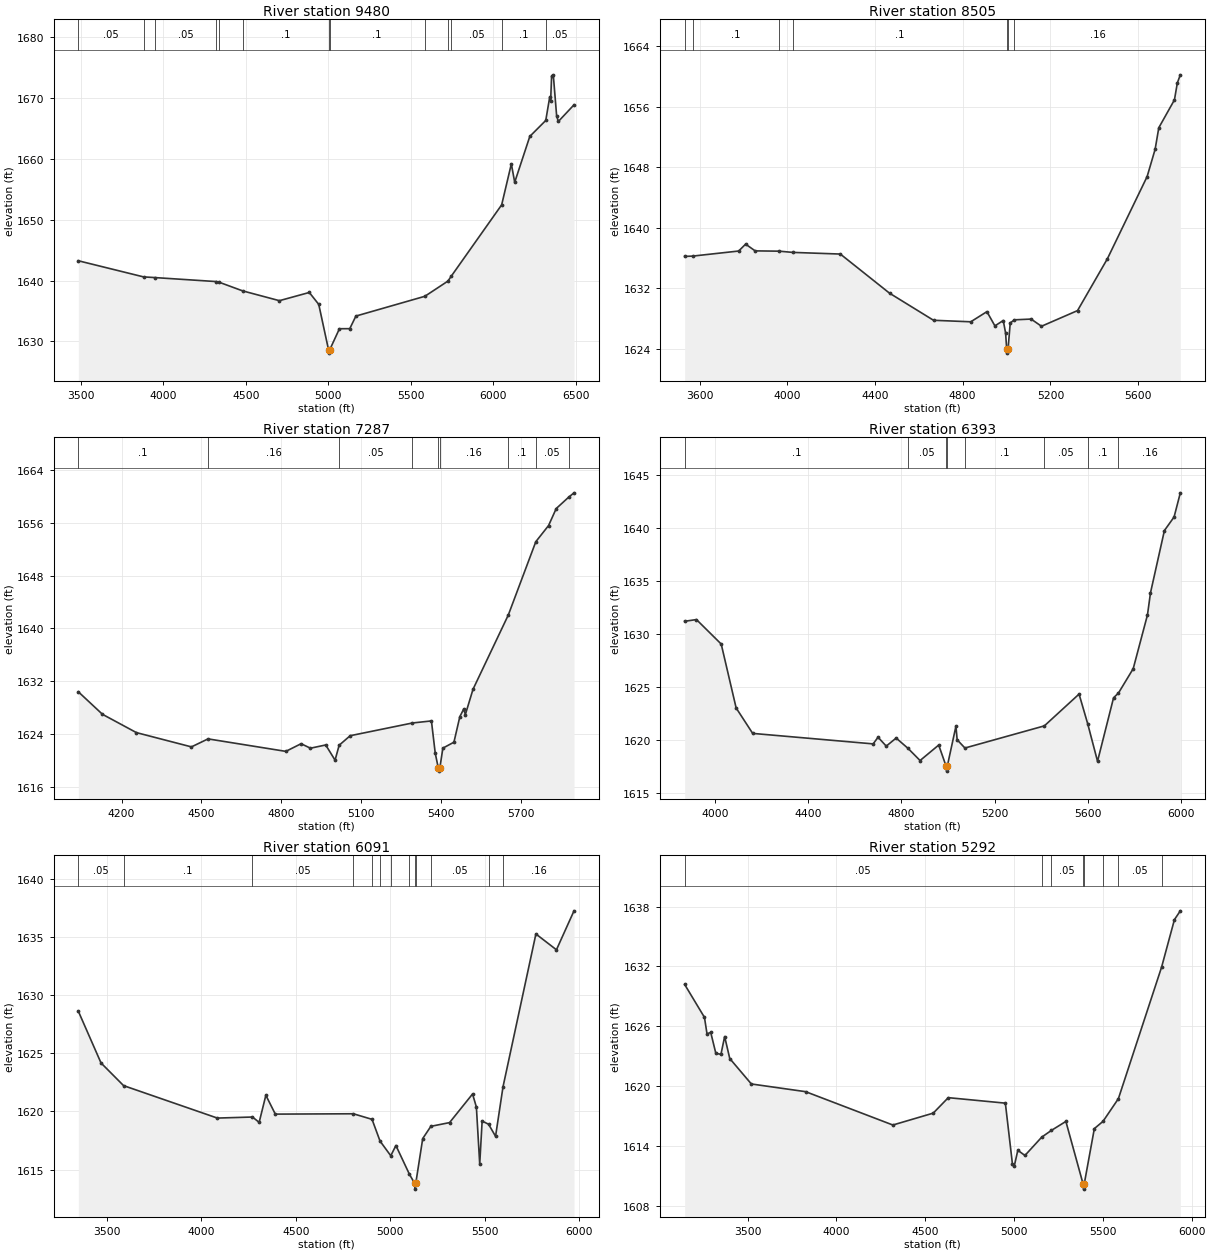
Type RM Length L Ch R = 1 ,9480    ,975,975,975
BEGIN DESCRIPTION:
UNT 1060 IN HEWA 16.0
END DESCRIPTION:
XS GIS Cut Line= 5
      2746081.44     10044191.64      2747018.89     10043993.73
      2747138.68     10043754.15      2746935.56      10043160.4
      2747138.68     10042030.21
#Sta/Elev= 30
  3485.9 1643.25  3880.8  1640.6  3947.7 1640.49  4321.5 1639.83  4339.9 1639.71
  4481.1  1638.3  4703.5 1636.69  4884.6 1638.04  4941.9 1636.08  5001.5 1628.57
  5004.3 1628.07  5007.5 1628.57  5067.1 1632.08  5129.7 1632.09  5166.8 1634.16
  5584.4 1637.41  5724.2 1639.91  5743.2 1640.67  6049.6 1652.44  6108.2 1659.17
  6128.5 1656.15    6220 1663.69  6316.6 1666.31    6341 1670.23  6346.1 1669.49
    6352 1673.61  6362.2 1673.81  6382.5 1667.06  6392.7 1666.14  6487.7 1668.88
#Mann= 13 ,-1 , 0
  3485.9     .05       0  3880.8      .1       0  3947.7     .05       0
  4321.5      .1       0  4339.9     .05       0  4481.1      .1       0
  5001.5     .07       0  5007.5      .1       0  5584.4     .05       0
  5724.2      .1       0  5743.2     .05       0  6049.6      .1       0
  6316.6     .05       0
Bank Sta=5001.5,5007.5
XS Rating Curve= 0 ,0
Exp/Cntr=0.3,0.1

Type RM Length L Ch R = 1 ,8505    ,1218,1218,1218
BEGIN DESCRIPTION:
UNT 1060 IN HEWA 15.0
END DESCRIPTION:
XS GIS Cut Line= 2
      2747279.28     10044856.43       2748021.5     10042720.94
#Sta/Elev= 30
  3531.9 1636.21  3568.5 1636.25  3778.3 1636.92    3810 1637.83  3853.5 1636.94
  3964.1  1636.9  4024.1 1636.74    4242 1636.52  4466.4 1631.35    4667 1627.77
  4836.9 1627.57  4910.5 1628.91    4947 1627.03  4985.1 1627.74  4995.7 1626.09
  5000.9 1623.93  5003.6 1623.43  5006.9 1623.93  5016.9 1627.42  5036.2 1627.83
  5112.2 1627.93  5159.4 1626.98  5323.9 1629.05  5459.9 1635.89  5641.3 1646.76
  5677.7 1650.36  5694.5 1653.21  5765.8 1656.89  5779.2 1659.15  5792.7  1660.2
#Mann= 7 ,-1 , 0
  3531.9     .05       0  3568.5      .1       0  3964.1     .05       0
  4024.1      .1       0  5000.9     .07       0  5006.9      .1       0
  5036.2     .16       0
Bank Sta=5000.9,5006.9
XS Rating Curve= 0 ,0
Exp/Cntr=0.3,0.1

Type RM Length L Ch R = 1 ,7287    ,894,894,894
BEGIN DESCRIPTION:
UNT 1060 IN HEWA 14.0
END DESCRIPTION:
XS GIS Cut Line= 2
      2748037.93     10044141.44      2749224.44     10042705.14
#Sta/Elev= 30
  4037.5 1630.41  4128.3    1627  4255.9 1624.23  4462.6 1622.07  4525.1 1623.28
  4817.4 1621.39  4874.8 1622.55  4909.9 1621.87  4967.3 1622.36  5002.4 1620.06
  5017.8 1622.32  5059.2 1623.76  5293.4 1625.69  5364.6    1626  5378.9 1621.12
  5390.3  1618.9    5393  1618.4  5396.3  1618.9  5407.6 1621.88  5449.2 1622.78
  5471.4 1626.65  5485.8 1627.79  5492.2 1626.97  5520.9 1630.79  5653.6 1642.04
  5756.9 1653.13  5804.9 1655.58  5833.6 1658.15  5880.1 1659.86  5900.5 1660.53
#Mann= 9 ,-1 , 0
  4037.5      .1       0  4525.1     .16       0  5017.8     .05       0
  5293.4     .16       0  5390.3     .07       0  5396.3     .16       0
  5653.6      .1       0  5756.9     .05       0  5880.1      .1       0
Bank Sta=5390.3,5396.3
XS Rating Curve= 0 ,0
Exp/Cntr=0.3,0.1

Type RM Length L Ch R = 1 ,6393    ,302,302,302
BEGIN DESCRIPTION:
UNT 1060 IN HEWA 13.0
END DESCRIPTION:
XS GIS Cut Line= 3
      2748183.75     10044710.91      2748919.84     10044030.37
      2749218.21     10042947.92
#Sta/Elev= 30
  3870.9 1631.19  3921.6 1631.35  4027.7 1629.04  4091.7 1623.01  4162.6 1620.61
  4679.2 1619.62  4700.1 1620.25  4735.3 1619.41  4777.8 1620.17  4828.6  1619.2
  4880.3 1618.05  4960.2 1619.51  4991.4 1617.55  4994.1 1617.05  4997.4 1617.55
  5034.1 1621.29  5039.3 1620.01  5072.6 1619.23  5413.2 1621.32    5562 1624.32
  5598.9 1621.53  5641.2 1617.98  5709.9 1623.97    5731 1624.42  5794.2 1626.72
  5855.3 1631.79  5868.2 1633.87  5927.9 1639.75  5969.4 1641.03  5996.2 1643.31
#Mann= 8 ,-1 , 0
  3870.9      .1       0  4828.6     .05       0  4991.4     .04       0
  4997.4     .05       0  5072.6      .1       0  5413.2     .05       0
  5598.9      .1       0    5731     .16       0
Bank Sta=4991.4,4997.4
XS Rating Curve= 0 ,0
Exp/Cntr=0.3,0.1

Type RM Length L Ch R = 1 ,6091    ,799,799,799
BEGIN DESCRIPTION:
UNT 1060 IN HEWA 12.0
END DESCRIPTION:
XS GIS Cut Line= 3
      2748336.53     10045370.62      2749197.62     10044197.04
        2749399.     10043044.29
#Sta/Elev= 30
    3348 1628.62  3468.2 1624.17  3587.7 1622.22  4084.4 1619.43  4270.6 1619.52
  4305.9 1619.06  4341.4 1621.39  4391.5 1619.77  4804.8  1619.8  4903.9 1619.32
  4946.3 1617.45  5003.1 1616.19  5030.3 1617.07  5102.2 1614.59  5129.5 1613.82
  5132.3 1613.32  5135.5 1613.82  5172.4 1617.67  5215.5 1618.72  5314.5 1619.04
  5436.3  1621.5  5456.6 1620.38  5474.3 1615.48  5487.1 1619.17  5521.2  1618.9
  5558.2 1617.86  5597.7 1622.12  5771.9 1635.26  5880.7  1633.9  5973.8 1637.25
#Mann= 13 ,-1 , 0
    3348     .05       0  3587.7      .1       0  4270.6     .05       0
  4804.8      .1       0  4903.9     .05       0  4946.3      .1       0
  5003.1     .05       0  5102.2      .1       0  5129.5     .07       0
  5135.5      .1       0  5215.5     .05       0  5521.2      .1       0
  5597.7     .16       0
Bank Sta=5129.5,5135.5
XS Rating Curve= 0 ,0
Exp/Cntr=0.3,0.1

Type RM Length L Ch R = 1 ,5292    ,705,705,705
BEGIN DESCRIPTION:
UNT 1060 IN HEWA 11.0
END DESCRIPTION:
XS GIS Cut Line= 3
      2748794.83     10045537.32      2749850.39     10044224.81
      2749919.84      10043120.6
#Sta/Elev= 30
  3145.7  1630.2  3257.3  1626.9  3271.7 1625.24  3292.5  1625.4  3321.3  1623.3
  3350.1  1623.2  3370.9 1624.98  3399.7 1622.78  3521.3 1620.23  3826.8 1619.46
    4318 1616.12  4545.2 1617.31    4630 1618.86  4951.3 1618.31  4991.4 1612.18
  5001.4    1612  5021.5 1613.59  5061.5 1613.07  5156.3 1614.91  5210.5 1615.58
    5292 1616.48  5389.2  1610.2  5391.9  1609.7  5395.2  1610.2  5452.3 1615.76
  5501.2 1616.49  5587.7 1618.76  5831.2 1631.95  5903.2 1636.69  5936.4 1637.57
#Mann= 8 ,-1 , 0
  3145.7     .05       0  5156.3      .1       0  5210.5     .05       0
  5389.2    .035       0  5395.2     .05       0  5501.2      .1       0
  5587.7     .05       0  5831.2      .1       0
Bank Sta=5389.2,5395.2
XS Rating Curve= 0 ,0
Exp/Cntr=0.3,0.1