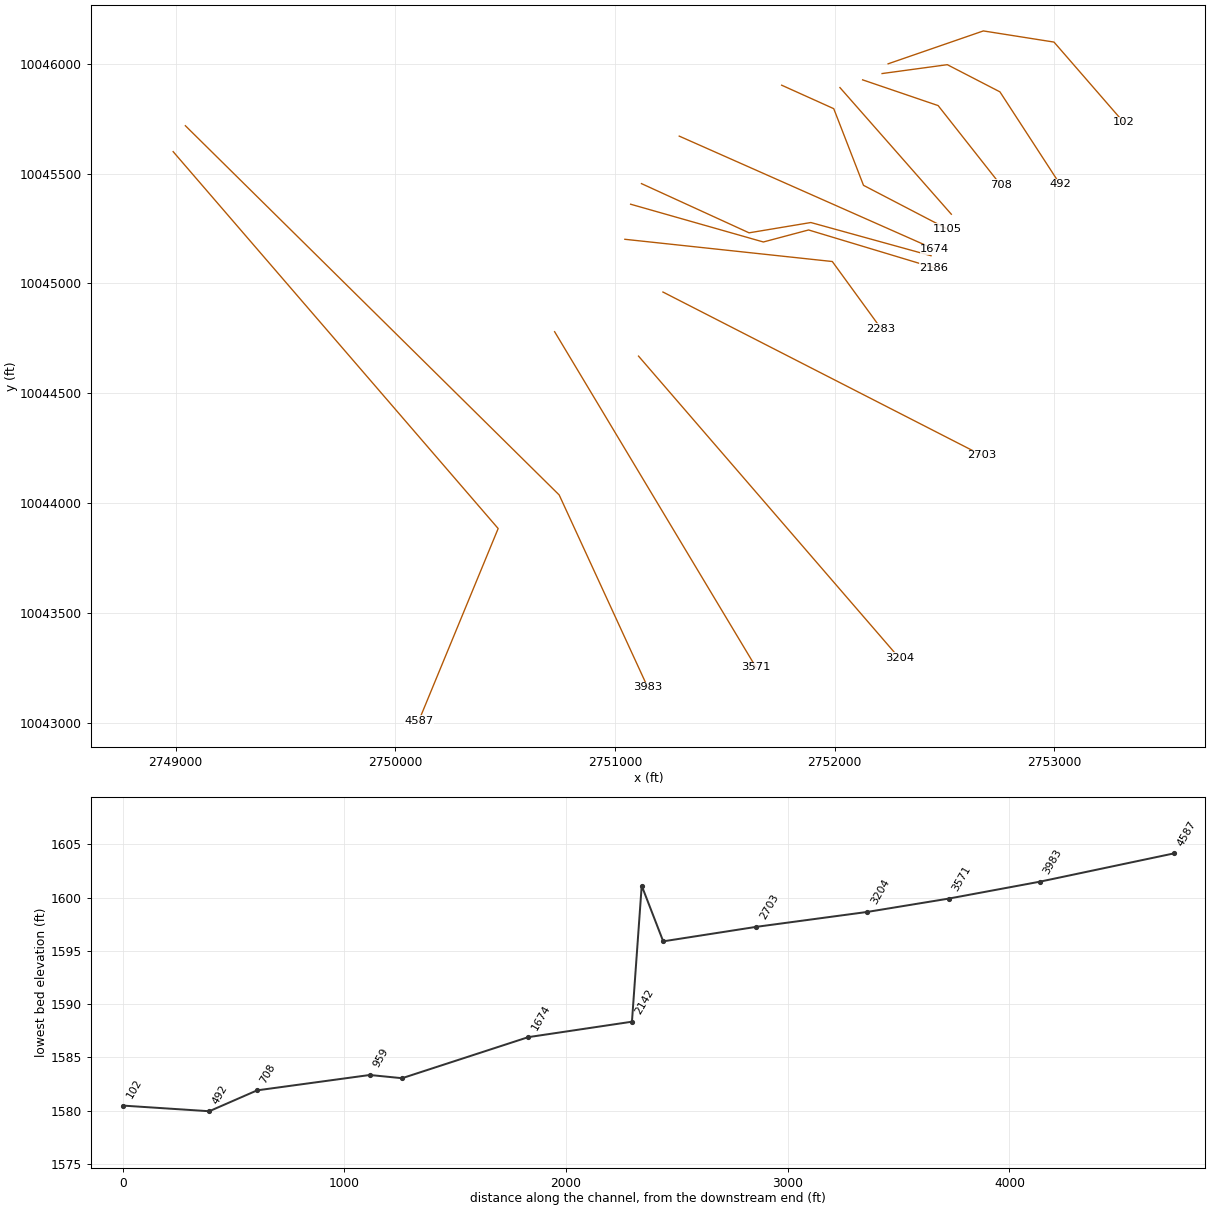
HEC-RAS study UNT 1060 IN HEWA.prj: UNT 1060 IN HEWA Base Level Engineering

--- UNT 1060 IN HEWA.g01 (geometry) --- (continued)

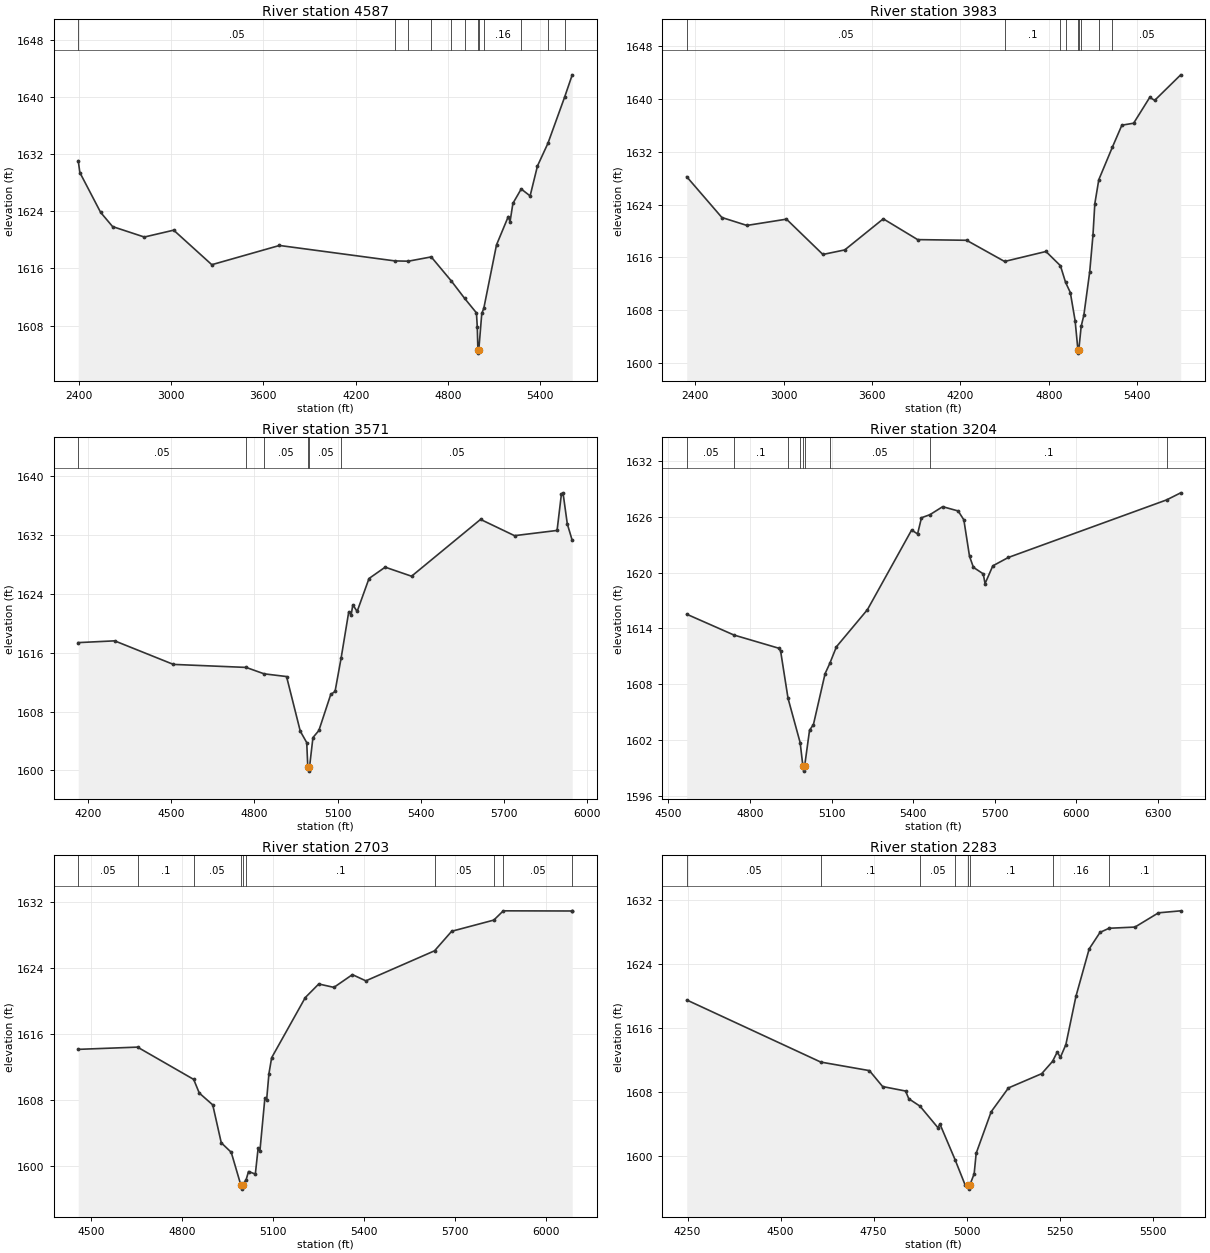
Type RM Length L Ch R = 1 ,4587    ,604,604,604
BEGIN DESCRIPTION:
UNT 1060 IN HEWA 10.0
END DESCRIPTION:
XS GIS Cut Line= 3
      2748989.28     10045599.82      2750468.45     10043884.54
      2750107.33     10043009.51
#Sta/Elev= 30
  2396.4 1631.05  2406.9  1629.4  2541.9 1623.83  2619.8 1621.84    2826 1620.38
  3016.9 1621.34  3264.8 1616.51  3704.7  1619.2  4455.1 1617.04  4542.3    1617
  4691.3  1617.6  4822.4 1614.22    4908 1611.81  4985.2 1609.77  4990.6 1607.82
  4994.6 1604.64  4997.4 1604.14  5000.6 1604.64  5019.9 1609.69  5033.2 1610.43
  5115.6 1619.28  5192.3 1623.25  5203.6 1622.51  5222.2 1625.09  5276.2  1627.1
  5334.1 1626.13  5381.9 1630.32  5449.7 1633.48  5558.1 1639.93    5608 1643.07
#Mann= 12 ,-1 , 0
  2396.4     .05       0  4455.1      .1       0  4542.3     .05       0
  4691.3      .1       0  4822.4     .05       0    4908      .1       0
  4994.6     .07       0  5000.6      .1       0  5033.2     .16       0
  5276.2      .1       0  5449.7     .16       0  5558.1      .1       0
Bank Sta=4994.6,5000.6
XS Rating Curve= 0 ,0
Exp/Cntr=0.3,0.1

Type RM Length L Ch R = 1 ,3983    ,412,412,412
BEGIN DESCRIPTION:
UNT 1060 IN HEWA 9.0
END DESCRIPTION:
XS GIS Cut Line= 3
      2749044.82     10045717.89      2750746.23     10044037.31
      2751148.99     10043162.34
#Sta/Elev= 30
  2340.8 1628.22  2579.7 1622.04  2749.4 1620.84  3018.1 1621.79  3265.6 1616.44
  3414.1 1617.13  3675.7 1621.84    3909 1618.69  4241.4 1618.59  4499.4 1615.38
  4780.3 1616.89  4878.6 1614.74  4913.5 1612.22  4945.9 1610.67  4978.4  1606.4
  4997.4 1601.99  5000.2 1601.49  5003.4 1601.99  5019.6 1605.56  5037.8 1607.25
  5077.5 1613.81  5099.5 1619.33  5112.2 1624.13  5139.2 1627.77    5232 1632.73
  5295.9 1636.03  5375.8 1636.33  5484.8 1640.23  5519.1  1639.8  5695.5 1643.66
#Mann= 9 ,-1 , 0
  2340.8     .05       0  4499.4      .1       0  4878.6     .05       0
  4913.5      .1       0  4997.4     .07       0  5003.4      .1       0
  5019.6     .16       0  5139.2      .1       0    5232     .05       0
Bank Sta=4997.4,5003.4
XS Rating Curve= 0 ,0
Exp/Cntr=0.3,0.1

Type RM Length L Ch R = 1 ,3571    ,367,367,367
BEGIN DESCRIPTION:
UNT 1060 IN HEWA 8.0
END DESCRIPTION:
XS GIS Cut Line= 2
      2750725.38     10044780.39      2751642.06      10043252.6
#Sta/Elev= 30
  4164.4 1617.36  4295.7  1617.6  4507.5  1614.4  4769.9 1613.99  4834.7 1613.12
  4915.7 1612.75  4965.2 1605.33  4988.5 1603.77  4992.4  1600.4  4995.1  1599.9
  4998.4  1600.4  5010.9 1604.46  5032.3 1605.42  5075.1 1610.32  5090.6 1610.72
  5112.7  1615.3  5140.1 1621.56  5148.9 1621.17  5154.8  1622.5  5170.3 1621.59
  5213.1 1626.07  5271.4 1627.61  5366.6 1626.38  5615.4  1634.1  5737.9 1631.89
  5891.4  1632.6    5907 1637.53  5912.8 1637.71  5928.3 1633.48  5946.1 1631.24
#Mann= 6 ,-1 , 0
  4164.4     .05       0  4769.9      .1       0  4834.7     .05       0
  4992.4     .07       0  4998.4     .05       0  5112.7     .05       0
Bank Sta=4992.4,4998.4
XS Rating Curve= 0 ,0
Exp/Cntr=0.3,0.1

Type RM Length L Ch R = 1 ,3204    ,501,501,501
BEGIN DESCRIPTION:
UNT 1060 IN HEWA 7.0
END DESCRIPTION:
XS GIS Cut Line= 2
      2751107.31     10044669.29      2752294.15     10043295.06
#Sta/Elev= 30
  4567.6 1615.52  4741.4 1613.28  4905.3 1611.87  4912.7 1611.57    4940 1606.48
  4984.6 1601.71  4994.8 1599.15  4997.5 1598.65  5000.8 1599.15  5019.1 1603.05
  5033.4 1603.66  5076.2 1609.13  5093.5 1610.23  5117.9 1612.02  5231.9 1616.01
  5394.3 1624.57  5416.2 1624.15  5430.5 1625.89  5461.5 1626.22  5508.4 1627.08
  5565.4 1626.62  5586.3 1625.66  5607.1 1621.75  5621.4 1620.56  5657.5 1619.86
  5664.2 1618.81  5692.7 1620.72  5749.7 1621.62  6331.6 1627.81  6383.4 1628.57
#Mann= 9 ,-1 , 0
  4567.6     .05       0  4741.4      .1       0    4940     .05       0
  4984.6      .1       0  4994.8     .07       0  5000.8      .1       0
  5093.5     .05       0  5461.5      .1       0  6331.6     .05       0
Bank Sta=4994.8,5000.8
XS Rating Curve= 0 ,0
Exp/Cntr=0.3,0.1

Type RM Length L Ch R = 1 ,2703    ,420,420,420
BEGIN DESCRIPTION:
UNT 1060 IN HEWA 6.0
END DESCRIPTION:
XS GIS Cut Line= 2
      2751218.46     10044960.92      2752669.01     10044218.29
#Sta/Elev= 30
  4457.9 1614.14  4653.5 1614.41  4838.7 1610.51  4857.2 1608.86  4901.6 1607.43
  4929.7 1602.85  4962.6  1601.7  4994.2 1597.75  4996.9 1597.25  5000.2 1597.75
  5011.8  1598.4  5019.6 1599.38  5042.1 1599.07  5051.4 1602.23  5057.1 1601.82
  5073.6 1608.26  5079.3 1608.02    5087 1611.21  5095.9 1613.13  5206.9  1620.4
  5251.3 1622.04  5301.3 1621.63  5362.3 1623.17  5406.7 1622.42  5633.3 1626.05
  5689.8 1628.41  5828.7 1629.76  5860.1 1630.88  6086.8 1630.86  6087.5 1630.84
#Mann= 10 ,-1 , 0
  4457.9     .05       0  4653.5      .1       0  4838.7     .05       0
  4994.2     .04       0  5000.2     .05       0  5011.8      .1       0
  5633.3     .05       0  5828.7      .1       0  5860.1     .05       0
  6086.8      .1       0
Bank Sta=4994.2,5000.2
XS Rating Curve= 0 ,0
Exp/Cntr=0.3,0.1

Type RM Length L Ch R = 1 ,2283    ,97,97,97
BEGIN DESCRIPTION:
UNT 1060 IN HEWA 5.0
END DESCRIPTION:
XS GIS Cut Line= 3
      2751045.06       10045201.      2751989.28     10045099.81
      2752211.48      10044794.3
#Sta/Elev= 30
  4247.8 1619.53  4607.9 1611.77  4738.7  1610.7  4774.2 1608.71  4835.9 1608.15
  4844.6 1607.18  4874.6 1606.26    4923 1603.56  4928.1 1604.03  4968.8 1599.58
  4995.5 1596.46  5002.5 1596.39  5005.3 1595.89  5008.5 1596.39  5020.2 1597.81
  5025.6 1600.37  5065.9 1605.56  5112.4 1608.54  5201.7 1610.32  5230.7 1611.85
  5243.4 1613.02  5251.9 1612.36  5266.6 1613.95  5293.6 1619.97  5329.2 1625.91
  5358.5 1627.98  5382.6 1628.49  5452.3 1628.64  5515.4 1630.42  5575.2 1630.67
#Mann= 8 ,-1 , 0
  4247.8     .05       0  4607.9      .1       0  4874.6     .05       0
  4968.8      .1       0  5002.5     .07       0  5008.5      .1       0
  5230.7     .16       0  5382.6      .1       0
Bank Sta=5002.5,5008.5
XS Rating Curve= 0 ,0
Exp/Cntr=0.3,0.1

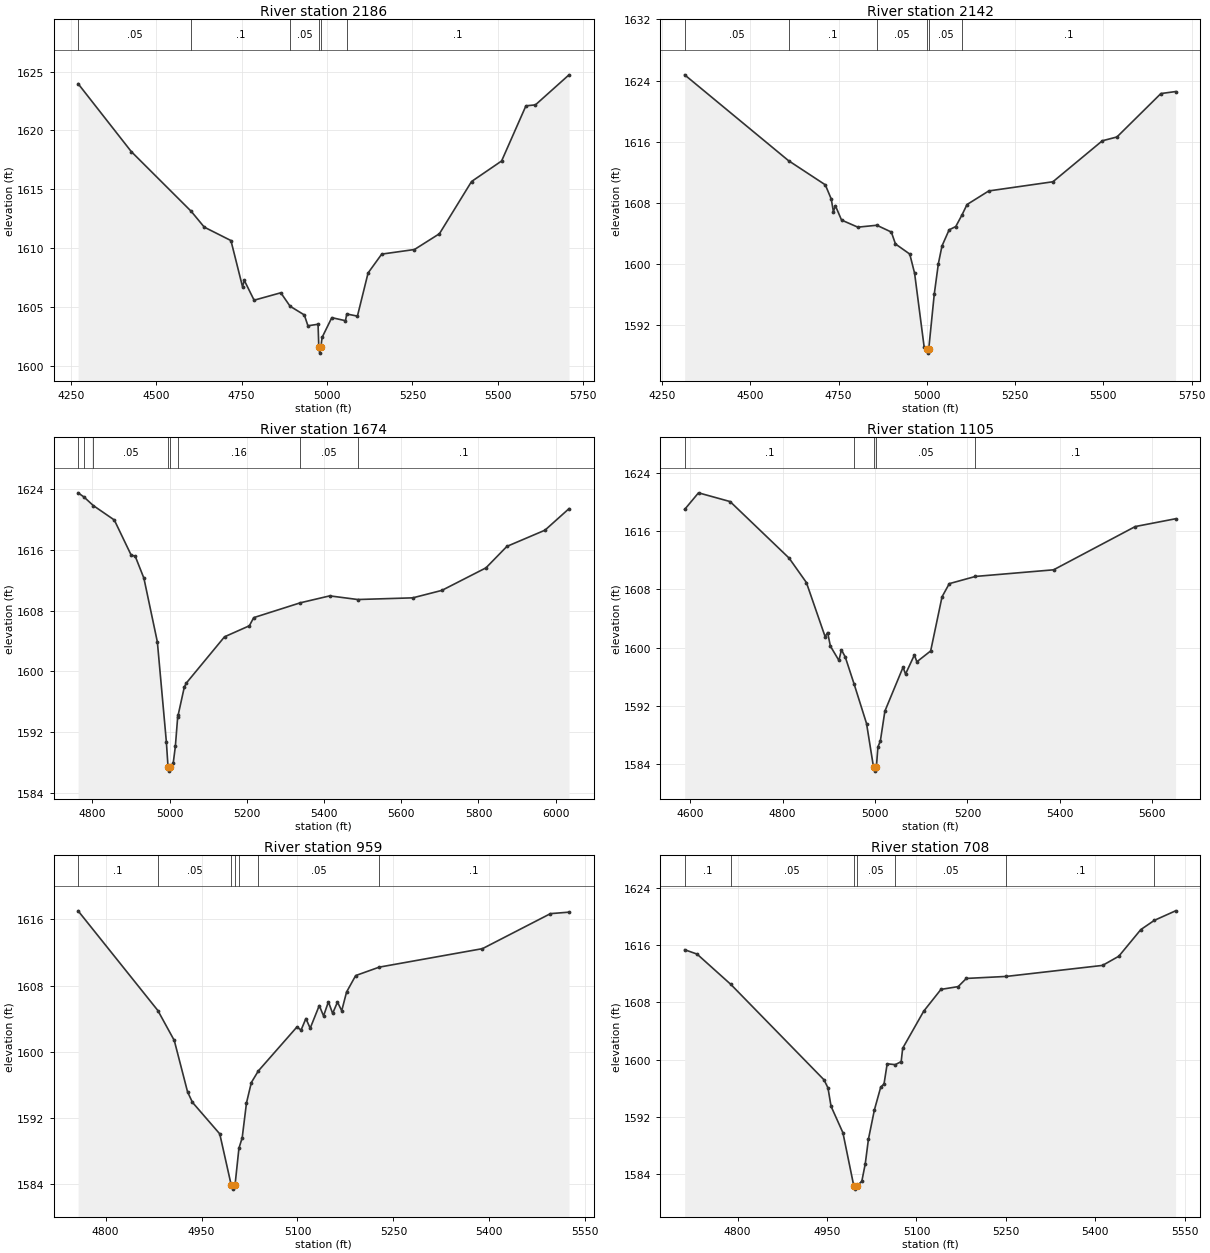
Type RM Length L Ch R = 1 ,2186    ,44,44,44
BEGIN DESCRIPTION:
Mapping XS 75f04e2d
END DESCRIPTION:
XS GIS Cut Line= 4
      2751071.35      10045360.6       2751675.5     10045188.73
      2751881.23     10045243.42       2752451.5     10045071.56
#Sta/Elev= 30
  4271.7 1623.97  4427.3 1618.21  4602.7 1613.14  4640.9  1611.8    4719 1610.66
  4752.9 1606.74  4758.1 1607.28  4786.8  1605.6  4864.9 1606.23    4892 1605.09
  4933.7 1604.35  4944.3 1603.43  4973.9 1603.56  4976.1 1601.61  4978.8 1601.11
  4982.1 1601.61  4985.7 1602.44  5014.1 1604.12  5054.2 1603.86  5057.9 1604.43
  5089.1 1604.25  5120.3 1607.91  5160.2 1609.51    5256  1609.9  5329.1 1611.24
  5423.1 1615.67    5511 1617.41  5582.2 1622.09    5610 1622.17  5708.3 1624.72
#Mann= 6 ,-1 , 0
  4271.7     .05       0  4602.7      .1       0    4892     .05       0
  4976.1     .04       0  4982.1     .05       0  5057.9      .1       0
Bank Sta=4976.1,4982.1
XS Rating Curve= 0 ,0
Exp/Cntr=0.3,0.1

Type RM Length L Ch R = 1 ,2142    ,468,468,468
BEGIN DESCRIPTION:
Mapping XS 39781539
END DESCRIPTION:
XS GIS Cut Line= 4
      2751120.79     10045454.37      2751610.39      10045230.4
      2751891.64     10045277.27      2752438.54     10045126.23
#Sta/Elev= 30
  4313.6 1624.76  4607.9 1613.53  4712.1 1610.37  4728.9 1608.52  4735.1 1606.85
  4740.6 1607.65  4758.1 1605.76  4804.2 1604.83  4858.1 1605.08  4899.2 1604.19
  4910.9 1602.63  4951.4 1601.31  4965.1  1598.8    4992 1589.21  4999.1 1588.85
  5001.9 1588.35  5005.1 1588.85  5020.8 1596.06  5032.5 1600.07  5042.7 1602.37
  5062.9 1604.48  5081.7 1604.91  5099.6 1606.45  5113.6 1607.79  5175.3 1609.57
    5357 1610.77  5496.9 1616.13  5538.4 1616.63  5662.9 1622.31  5704.5 1622.57
#Mann= 6 ,-1 , 0
  4313.6     .05       0  4607.9      .1       0  4858.1     .05       0
  4999.1     .04       0  5005.1     .05       0  5099.6      .1       0
Bank Sta=4999.1,5005.1
XS Rating Curve= 0 ,0
Exp/Cntr=0.3,0.1

Type RM Length L Ch R = 1 ,1674    ,569,569,569
BEGIN DESCRIPTION:
UNT 1060 IN HEWA 4.0
END DESCRIPTION:
XS GIS Cut Line= 2
      2751292.67     10045670.51      2752455.14     10045155.59
#Sta/Elev= 30
  4763.1 1623.47  4778.4 1622.92  4802.4  1621.8  4856.9  1619.9  4900.7 1615.27
  4910.9 1615.16  4933.5 1612.26  4968.4 1603.88  4991.7 1590.76  4996.1  1587.4
  4998.9  1586.9  5002.1  1587.4  5009.5 1587.96    5015 1590.14    5021 1593.99
  5022.5 1594.32  5038.2 1597.95  5043.7 1598.49  5142.3 1604.55  5206.7    1606
  5217.9 1607.07  5338.7 1609.02  5414.8 1609.93  5487.4 1609.45  5629.8 1609.67
  5705.2 1610.65  5819.4 1613.61  5873.6 1616.43  5972.2 1618.56  6034.5 1621.39
#Mann= 8 ,-1 , 0
  4763.1     .05       0  4778.4      .1       0  4802.4     .05       0
  4996.1     .04       0  5002.1     .05       0  5022.5     .16       0
  5338.7     .05       0  5487.4      .1       0
Bank Sta=4996.1,5002.1
XS Rating Curve= 0 ,0
Exp/Cntr=0.3,0.1

Type RM Length L Ch R = 1 ,1105    ,146,146,146
BEGIN DESCRIPTION:
UNT 1060 IN HEWA 3.0
END DESCRIPTION:
XS GIS Cut Line= 4
      2751758.79     10045902.29      2751995.81      10045795.5
      2752131.23     10045446.55      2752511.34     10045248.68
#Sta/Elev= 30
  4587.8 1618.98  4617.8 1621.26  4686.2 1620.06  4813.9  1612.3  4851.4 1608.94
  4891.9 1601.51  4897.3 1602.08  4903.3 1600.22  4921.8 1598.24  4927.2 1599.71
  4935.5 1598.72  4954.7    1595  4981.6 1589.58  4996.8 1583.55  4999.6 1583.05
  5002.8 1583.55  5006.2 1586.37  5011.5 1587.19  5021.3 1591.29  5060.6 1597.31
    5066 1596.38  5085.2    1599  5090.5 1598.06  5120.4 1599.55    5145 1606.98
  5160.7 1608.79  5217.3 1609.78  5386.5 1610.69  5563.3 1616.63  5650.6  1617.7
#Mann= 5 ,-1 , 0
  4587.8      .1       0  4954.7     .05       0  4996.8    .035       0
  5002.8     .05       0  5217.3      .1       0
Bank Sta=4996.8,5002.8
XS Rating Curve= 0 ,0
Exp/Cntr=0.3,0.1

Type RM Length L Ch R = 1 ,959     ,508,508,508
BEGIN DESCRIPTION:
UNT 1060 IN HEWA 2.0
END DESCRIPTION:
XS GIS Cut Line= 2
      2752024.02     10045891.47      2752530.96     10045315.08
#Sta/Elev= 30
    4757 1617.05  4881.7 1604.98  4907.4 1601.35  4928.2 1595.12  4935.8 1593.86
  4978.5 1590.04  4996.4 1583.85  4999.1 1583.35  5002.4 1583.85  5008.5  1588.3
  5013.6 1589.57  5020.3 1593.79  5027.9 1596.26  5038.8 1597.66    5099 1602.97
  5105.7 1602.62  5113.2 1604.01  5119.9 1602.83  5134.1 1605.58  5140.8 1604.32
  5148.4 1606.03    5155 1604.63  5162.6    1606  5169.2 1604.95  5176.8 1607.22
    5191 1609.21  5227.8 1610.23  5389.3 1612.47  5495.6 1616.71  5524.6 1616.89
#Mann= 7 ,-1 , 0
    4757      .1       0  4881.7     .05       0  4996.4    .035       0
  5002.4     .05       0  5008.5      .1       0  5038.8     .05       0
  5227.8      .1       0
Bank Sta=4996.4,5002.4
XS Rating Curve= 0 ,0
Exp/Cntr=0.3,0.1

Type RM Length L Ch R = 1 ,708     ,216,216,216
BEGIN DESCRIPTION:
Mapping XS 83d11788
END DESCRIPTION:
XS GIS Cut Line= 3
      2752127.26     10045926.66      2752470.99     10045809.48
      2752755.68      10045448.1
#Sta/Elev= 30
  4711.3 1615.34  4732.1 1614.73  4788.7  1610.5    4945 1597.17  4951.6 1596.05
  4956.8 1593.48  4976.7 1589.78  4994.8 1582.41  4997.6 1581.91  5000.8 1582.41
  5008.4 1583.01  5014.2 1585.47  5019.5 1588.89  5029.5 1592.98  5040.1 1596.16
  5045.6 1596.58  5050.9 1599.41  5064.5 1599.29  5074.4 1599.72  5076.9 1601.58
  5112.2 1606.76  5141.1  1609.8    5170 1610.19  5183.6 1611.33  5250.6 1611.61
  5412.1 1613.15  5439.3 1614.43  5476.2 1618.15  5498.9 1619.44  5534.5 1620.77
#Mann= 7 ,-1 , 0
  4711.3      .1       0  4788.7     .05       0  4994.8    .035       0
  5000.8     .05       0  5064.5     .05       0  5250.6      .1       0
  5498.9     .05       0
Bank Sta=4994.8,5000.8
XS Rating Curve= 0 ,0
Exp/Cntr=0.3,0.1

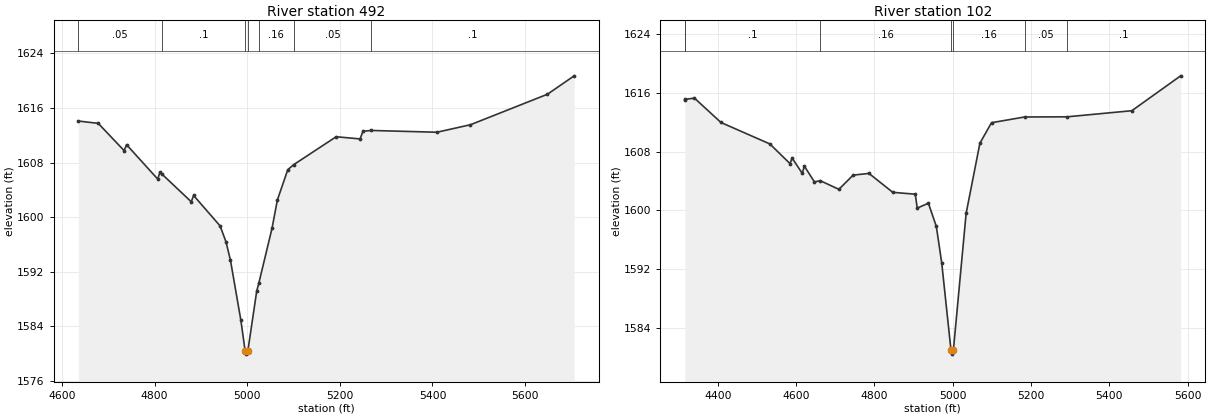
Type RM Length L Ch R = 1 ,492     ,390,390,390
BEGIN DESCRIPTION:
Mapping XS 8ab0334c
END DESCRIPTION:
XS GIS Cut Line= 4
      2752215.81     10045955.32      2752512.65     10045995.68
      2752752.24     10045871.98       2753025.7     10045451.37
#Sta/Elev= 30
  4635.1 1614.08  4678.1 1613.74  4734.1 1609.74  4739.2 1610.62  4806.6 1605.58
  4811.6 1606.63  4815.4 1606.33    4879 1602.26  4884.1 1603.18  4941.2 1598.73
    4954  1596.4  4963.7 1593.68  4986.2 1584.89  4995.3 1580.45    4998 1579.95
  5001.3 1580.45  5020.4 1589.19    5025 1590.36  5053.5 1598.39    5065 1602.52
  5087.5 1606.96  5100.4  1607.7    5192 1611.78  5243.6 1611.46  5249.9 1612.59
    5268  1612.7  5409.7 1612.44  5482.1 1613.54  5648.2    1618    5706  1620.7
#Mann= 7 ,-1 , 0
  4635.1     .05       0  4815.4      .1       0  4995.3     .07       0
  5001.3      .1       0    5025     .16       0  5100.4     .05       0
    5268      .1       0
Bank Sta=4995.3,5001.3
XS Rating Curve= 0 ,0
Exp/Cntr=0.3,0.1

Type RM Length L Ch R = 1 ,102     ,0,0,0
BEGIN DESCRIPTION:
UNT 1060 IN HEWA 1.0
END DESCRIPTION:
XS GIS Cut Line= 4
      2752243.17      10045999.6      2752676.72     10046149.33
      2752998.33     10046098.55      2753314.76     10045734.13
#Sta/Elev= 30
  4315.5 1615.03  4316.8  1615.1  4340.2 1615.26  4407.9 1611.95  4532.7 1609.04
  4584.4 1606.36  4589.7 1607.12  4615.6 1605.04  4620.9 1606.03  4646.8 1603.87
  4661.4 1604.05  4709.2 1602.87  4745.6  1604.8  4786.1 1605.03    4847 1602.46
  4904.4 1602.21  4909.4 1600.32  4937.9 1600.98  4958.2 1597.83  4971.9 1592.91
  4995.7 1580.98  4998.4 1580.48  5001.7 1580.98  5034.3 1599.59  5069.5 1609.13
  5099.2 1611.92  5183.8  1612.7    5292 1612.72  5457.8 1613.55  5582.4 1618.29
#Mann= 7 ,-1 , 0
  4315.5     .05       0  4316.8      .1       0  4661.4     .16       0
  4995.7     .07       0  5001.7     .16       0  5183.8     .05       0
    5292      .1       0
Bank Sta=4995.7,5001.7
XS Rating Curve= 0 ,0
Exp/Cntr=0.3,0.1

Chan Stop Cuts=-1
Use User Specified Reach Order=0
Composite Channel Slope=5