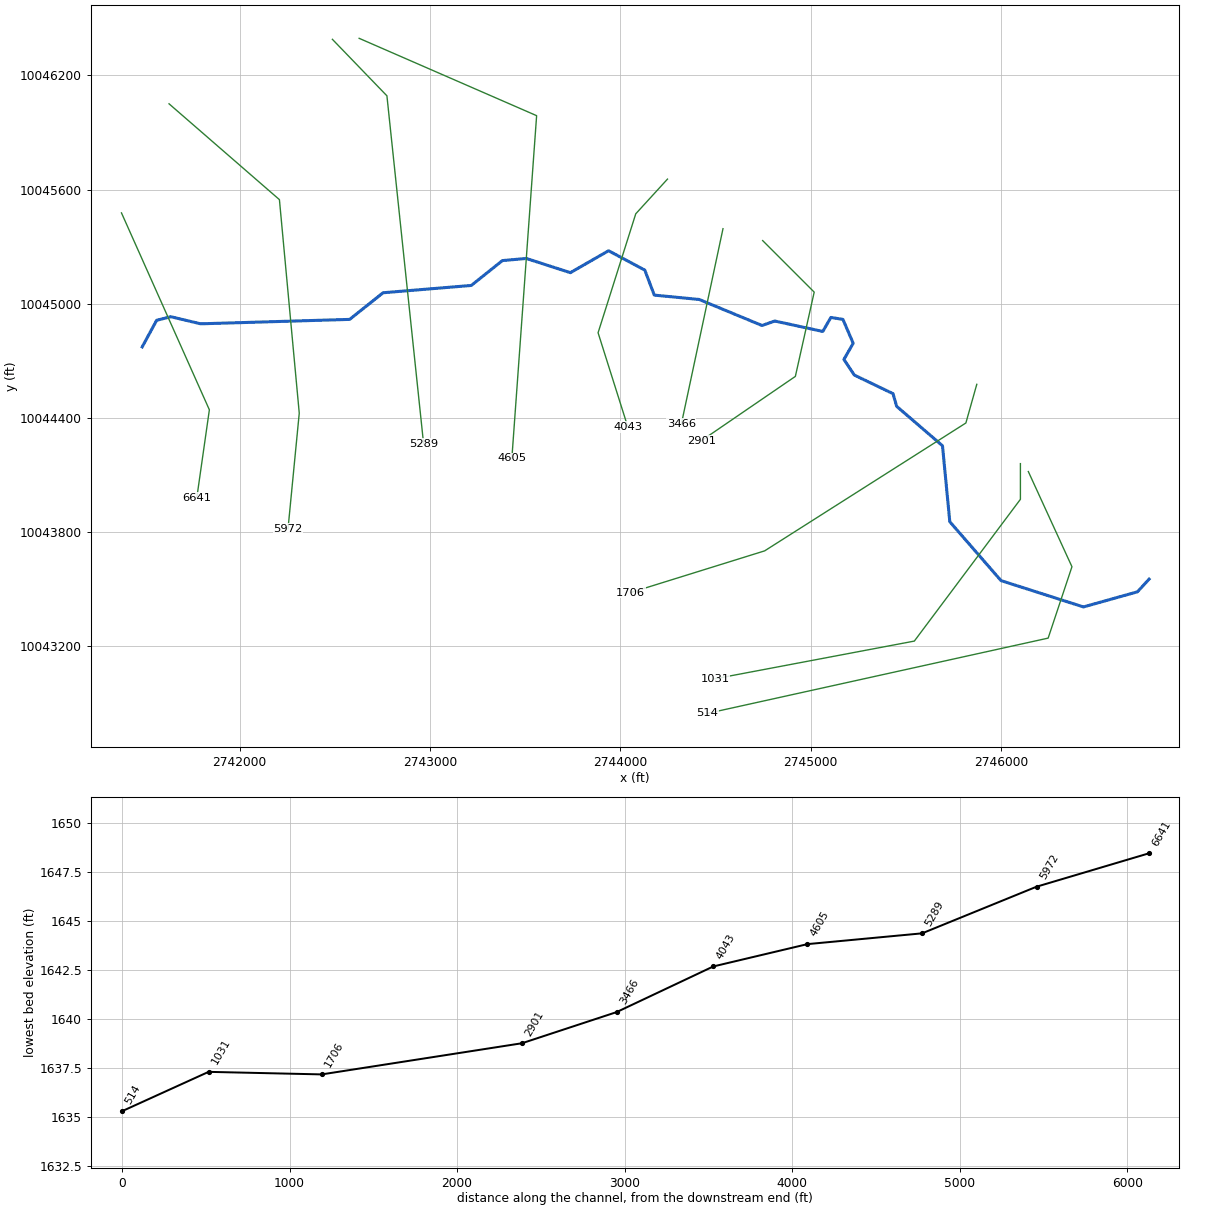
--- UNT 1061 IN HEWA.prj (project) ---

Proj Title=UNT 1061 IN HEWA Base Level Engineering
Current Plan=p01
Default Exp/Contr=0.3,0.1
English Units
Geom File=g01
Flow File=f01
Plan File=p01
Y Axis Title=Elevation
X Axis Title(PF)=Main Channel Distance
X Axis Title(XS)=Station
BEGIN DESCRIPTION:
UNT 1061 IN HEWA
END DESCRIPTION:
DSS Export Rating Curves= 0
DSS Export Rating Curve Sorted= 0
DSS Export Volume Flow Curves= 0
DXF OffsetX= 0
DXF OffsetY= 0
DXF ScaleX= 1
DXF ScaleY= 10

--- UNT 1061 IN HEWA.p01 (plan) ---

Plan Title=Multiple Run
Short Identifier=Multiple
Geom File=g01
Flow File=f01
Subcritical Flow
K Sum by GR= 0
Std Step Tol= 0.01
Critical Tol= 0.01
Num of Std Step Trials= 20
Max Error Tol= 0.3
Flow Tol Ratio= 0.001
Split Flow NTrial= 30
Split Flow Tol= 0.02
Split Flow Ratio= 0.02
Log Output Level= 0
Friction Slope Method= 1
Unsteady Friction Slope Method= 2
Unsteady Bridges Friction Slope Method= 1
Parabolic Critical Depth
Global Vel Dist=  1 , 1 , 1
Global Log Level= 0
CheckData=True
Encroach Param= -1, 0, 0, 0
BEGIN DESCRIPTION:
Multiple Run
END DESCRIPTION:

--- UNT 1061 IN HEWA.f01 (steady flow) ---

Flow Title=Multiple
Program Version=4.10
Number of Profiles= 7
Profile Names=10-year,25-year,50-year,1pct_min,100-year,1pct_plu,500-year
River Rch & RM=UNT 1061 IN HEWA,Reach-1         ,6641
     892    1288    1628    1504    2035    2751    3194
Boundary for River Rch & Prof#=UNT 1061 IN HEWA,Reach-1         , 1
Up Type= 0
Dn Type= 3
Dn Slope=0.004
Boundary for River Rch & Prof#=UNT 1061 IN HEWA,Reach-1         , 2
Up Type= 0
Dn Type= 3
Dn Slope=0.004
Boundary for River Rch & Prof#=UNT 1061 IN HEWA,Reach-1         , 3
Up Type= 0
Dn Type= 3
Dn Slope=0.004
Boundary for River Rch & Prof#=UNT 1061 IN HEWA,Reach-1         , 4
Up Type= 0
Dn Type= 3
Dn Slope=0.004
Boundary for River Rch & Prof#=UNT 1061 IN HEWA,Reach-1         , 5
Up Type= 0
Dn Type= 3
Dn Slope=0.004
Boundary for River Rch & Prof#=UNT 1061 IN HEWA,Reach-1         , 6
Up Type= 0
Dn Type= 3
Dn Slope=0.004
Boundary for River Rch & Prof#=UNT 1061 IN HEWA,Reach-1         , 7
Up Type= 0
Dn Type= 3
Dn Slope=0.004
DSS Import GetInterval= 0
DSS Import GetPeak= 0
DSS Import FillOption= 0

--- UNT 1061 IN HEWA.g01 (geometry) ---

Geom Title=Existing Conditions
Program Version=4.10

River Reach=UNT 1061 IN HEWA,Reach-1
Reach XY= 30
      2741488.47     10044773.73      2741564.19     10044913.32
      2741638.53     10044932.27      2741795.45     10044894.97
      2742578.45     10044918.18      2742753.92     10045058.13
      2743217.31     10045096.51      2743380.84     10045227.14
      2743506.24     10045238.28      2743737.87     10045163.69
      2743938.69     10045278.78      2744128.98     10045177.08
      2744178.82     10045045.73      2744414.53     10045022.86
      2744744.51      10044886.2      2744811.94     10044909.58
      2745064.05     10044854.79      2745106.46     10044928.35
      2745169.83     10044918.15      2745223.72     10044792.91
      2745175.04     10044707.99       2745229.5     10044625.74
      2745432.91     10044527.96      2745452.23     10044461.27
      2745692.84     10044254.34      2745731.29     10043855.15
      2746000.37     10043545.79       2746433.4     10043407.56
       2746717.2     10043486.97      2746778.47     10043553.73

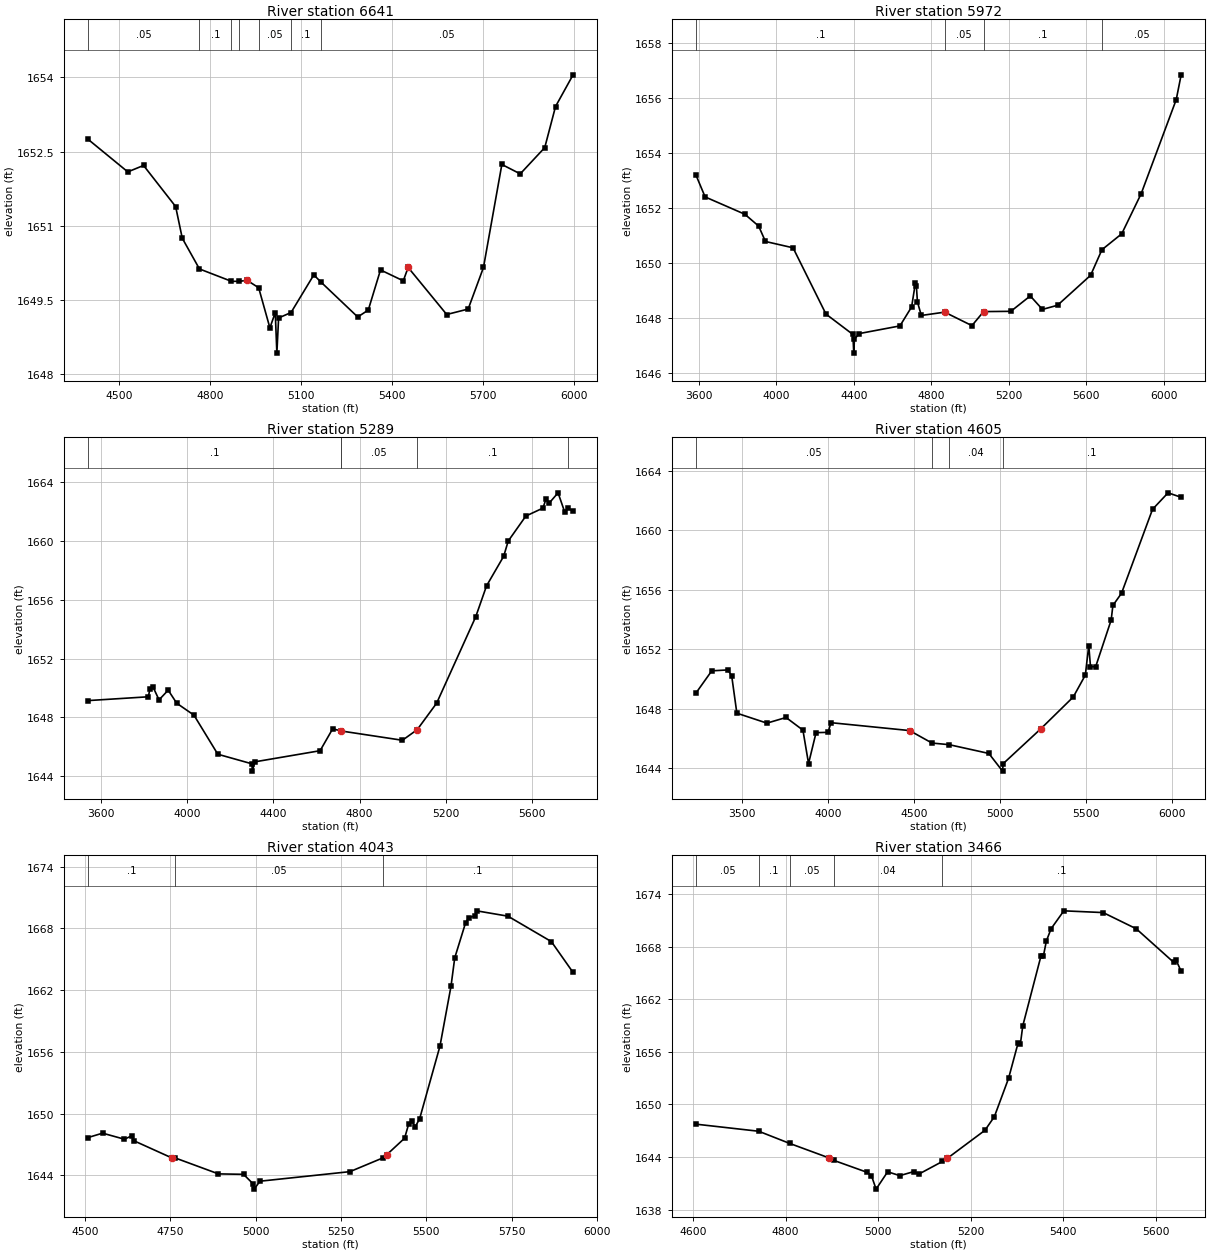
Type RM Length L Ch R = 1 ,6641    ,669,669,669
BEGIN DESCRIPTION:
UNT 1061 IN HEWA 7.0
END DESCRIPTION:
XS GIS Cut Line= 3
      2741379.47     10045477.85      2741841.28     10044443.13
      2741775.31     10043981.32
#Sta/Elev= 30
  4396.6 1652.75  4528.1 1652.09    4580 1652.22  4685.8 1651.39  4707.7 1650.75
  4764.3 1650.13  4869.9 1649.88  4895.8 1649.88  4921.5  1649.9  4959.6 1649.75
  4996.6 1648.94  5014.3 1649.25  5019.6 1648.43  5025.3 1649.14  5066.3 1649.25
  5141.4 1650.01  5164.1 1649.87  5286.2 1649.16    5321  1649.3  5361.3 1650.11
  5436.4 1649.89  5452.4 1650.16  5579.6 1649.21  5650.3 1649.32  5700.8 1650.16
  5761.4 1652.24    5822 1652.05  5902.8 1652.58  5938.4 1653.41  5996.2 1654.05
#Mann= 7 ,-1 , 0
  4396.6     .05       0  4764.3      .1       0  4869.9     .05       0
  4895.8      .1       0  4959.6     .05       0  5066.3      .1       0
  5164.1     .05       0
Bank Sta=4921.5,5452.4
XS Rating Curve= 0 ,0
Exp/Cntr=0.3,0.1

Type RM Length L Ch R = 1 ,5972    ,683,683,683
BEGIN DESCRIPTION:
Mapping XS 2d0b40fa
END DESCRIPTION:
XS GIS Cut Line= 4
      2741629.46     10046050.79      2742209.34      10045547.3
       2742313.5     10044425.77       2742254.5     10043818.44
#Sta/Elev= 30
  3585.8  1653.2  3632.8 1652.41  3837.9 1651.78  3909.1 1651.35  3944.2 1650.79
  4086.7 1650.56  4256.7 1648.15  4395.5 1647.41  4400.2 1646.73  4403.5 1647.23
  4427.6 1647.44  4638.5 1647.72  4698.8 1648.41  4718.3 1649.28  4723.4 1649.17
  4728.9 1648.59    4749  1648.1  4869.5 1648.22  5010.1 1647.73  5070.4 1648.24
    5211 1648.25  5311.4 1648.81  5374.2 1648.32    5452 1648.47  5622.8 1649.56
  5681.3 1650.49  5783.6 1651.07    5884 1652.53  6064.9 1655.95  6090.3 1656.85
#Mann= 4 ,-1 , 0
  3585.8      .1       0  4869.5     .05       0  5070.4      .1       0
  5681.3     .05       0
Bank Sta=4869.5,5070.4
XS Rating Curve= 0 ,0
Exp/Cntr=0.3,0.1

Type RM Length L Ch R = 1 ,5289    ,684,684,684
BEGIN DESCRIPTION:
Mapping XS d3f72195
END DESCRIPTION:
XS GIS Cut Line= 3
      2742487.64     10046389.57       2742774.1     10046092.69
      2742966.81     10044264.56
#Sta/Elev= 30
  3539.7 1649.15  3820.3 1649.41  3827.2 1649.96  3841.3 1650.09  3869.6  1649.2
  3912.1 1649.86  3951.8 1648.97  4031.6 1648.16  4142.3  1645.5  4300.1 1644.85
  4302.9 1644.35  4313.2 1644.98  4616.9 1645.74  4675.2 1647.23  4715.4 1647.08
  4998.7 1646.45  5067.3 1647.17  5157.8 1648.98  5338.8 1654.85  5389.1 1656.96
  5468.5 1658.97  5489.7 1660.01  5571.5 1661.71  5650.6 1662.25  5664.4 1662.84
  5680.7 1662.61  5720.9 1663.29  5751.1 1662.01  5768.4 1662.25  5790.5 1662.02
#Mann= 5 ,-1 , 0
  3539.7      .1       0  4715.4     .05       0  4715.4     .05       0
  5067.3      .1       0  5768.4     .05       0
Bank Sta=4715.4,5067.3
XS Rating Curve= 0 ,0
Exp/Cntr=0.3,0.1

Type RM Length L Ch R = 1 ,4605    ,562,562,562
BEGIN DESCRIPTION:
UNT 1061 IN HEWA 6.0
END DESCRIPTION:
XS GIS Cut Line= 3
      2742628.25     10046394.78      2743560.56     10045988.52
      2743430.43     10044187.59
#Sta/Elev= 30
  3230.8 1649.06  3322.4 1650.55  3416.1 1650.61  3438.3 1650.22  3468.4  1647.7
  3643.3 1647.03  3754.6 1647.41  3852.8 1646.56  3885.5 1644.31  3929.2 1646.39
  3998.5 1646.41  4016.4 1647.06  4473.2 1646.53  4603.7 1645.69  4703.8 1645.58
  4934.4 1644.99  5014.3  1643.8  5017.6  1644.3  5235.1 1646.63  5425.6 1648.79
  5495.8 1650.26  5515.9 1652.25  5525.9 1650.83    5556 1650.83  5646.2 1653.97
  5656.2 1654.95  5706.4 1655.77  5886.8 1661.42  5977.1 1662.53  6053.4 1662.23
#Mann= 4 ,-1 , 0
  3230.8     .05       0  4603.7      .1       0  4703.8     .04       0
  5017.6      .1       0
Bank Sta=4473.2,5235.1
XS Rating Curve= 0 ,0
Exp/Cntr=0.3,0.1

Type RM Length L Ch R = 1 ,4043    ,577,577,577
BEGIN DESCRIPTION:
UNT 1061 IN HEWA 5.0
END DESCRIPTION:
XS GIS Cut Line= 4
      2744248.07      10045655.2      2744081.39      10045472.9
      2743883.47      10044847.9      2744039.73     10044353.09
#Sta/Elev= 30
  4508.5 1647.67  4551.4  1648.1  4615.6 1647.51  4636.6 1647.84    4644 1647.35
    4754  1645.7  4765.1 1645.68    4891 1644.14  4964.4  1644.1  4992.9 1643.16
  4995.6 1642.66  5012.6 1643.43  5276.3 1644.36  5373.1  1645.7    5384    1646
  5436.4 1647.61  5448.2 1648.98  5457.4 1649.24  5467.9 1648.73  5480.6 1649.52
    5540 1656.56  5572.3 1662.37  5583.3 1665.14  5615.1 1668.55  5625.2 1669.06
  5642.2  1669.2  5647.5 1669.71  5739.2 1669.19  5866.4 1666.72    5930 1663.72
#Mann= 3 ,-1 , 0
  4508.5      .1       0  4765.1     .05       0  5373.1      .1       0
Bank Sta=4754,5384
XS Rating Curve= 0 ,0
Exp/Cntr=0.3,0.1

Type RM Length L Ch R = 1 ,3466    ,565,565,565
BEGIN DESCRIPTION:
UNT 1061 IN HEWA 4.0
END DESCRIPTION:
XS GIS Cut Line= 2
      2744539.73     10045394.78      2744320.98     10044368.74
#Sta/Elev= 30
  4606.1 1647.75  4741.8 1646.94  4808.7 1645.55  4893.5  1643.9  4903.7 1643.62
  4976.1 1642.25  4985.5 1641.86  4995.5 1640.33  5020.5 1642.31  5046.8 1641.87
  5077.5 1642.34  5087.7 1642.04  5138.9 1643.49  5149.1 1643.83  5230.9 1647.05
  5251.3 1648.61    5282 1652.99  5302.4 1656.99  5307.6 1656.93  5312.7 1658.98
    5352 1666.95  5357.1 1666.91  5363.8 1668.69    5374 1670.08  5401.5 1672.12
  5486.5 1671.92  5558.1 1670.07    5639 1666.24  5644.1 1666.51  5655.2 1665.21
#Mann= 5 ,-1 , 0
  4606.1     .05       0  4741.8      .1       0  4808.7     .05       0
  4903.7     .04       0  5138.9      .1       0
Bank Sta=4893.5,5149.1
XS Rating Curve= 0 ,0
Exp/Cntr=0.3,0.1

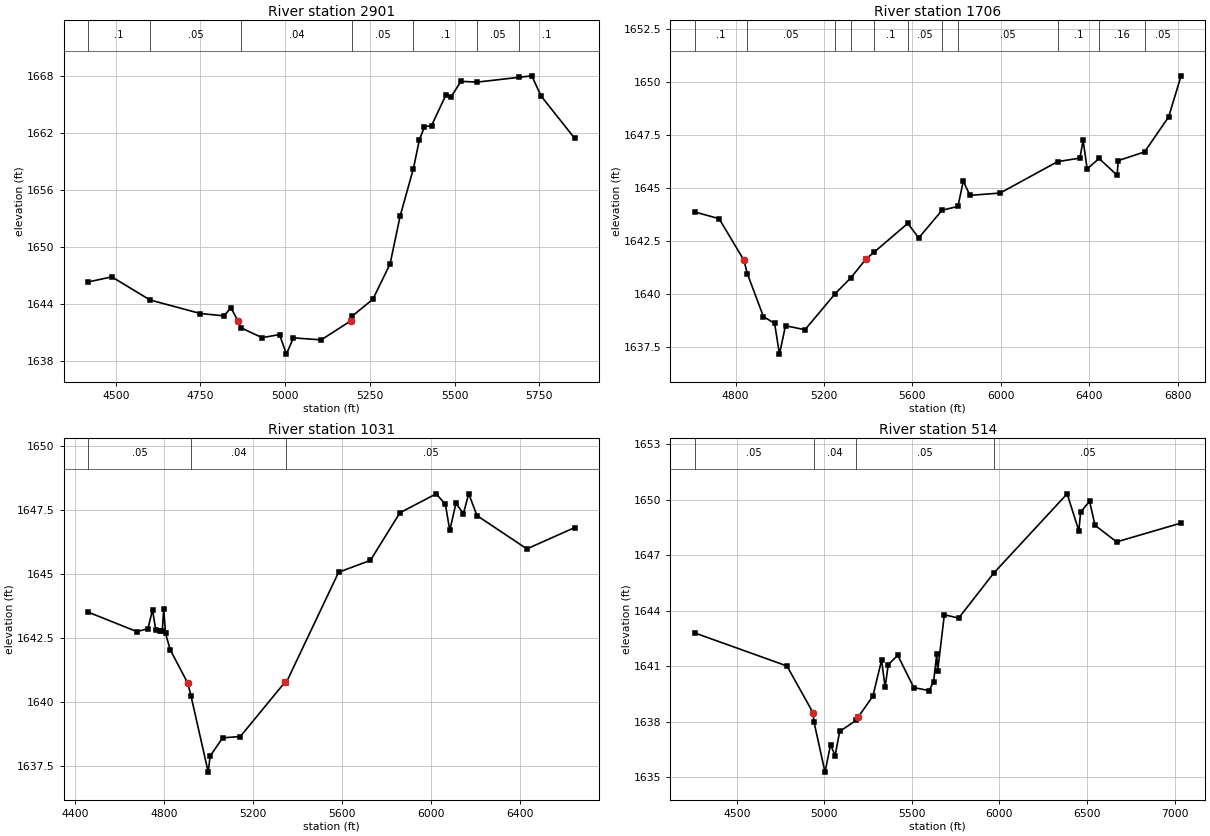
Type RM Length L Ch R = 1 ,2901    ,1195,1195,1195
BEGIN DESCRIPTION:
Mapping XS 4033a1d6
END DESCRIPTION:
XS GIS Cut Line= 4
      2744748.07     10045332.25      2745018.89     10045061.44
      2744919.93     10044618.73       2744425.1     10044280.16
#Sta/Elev= 30
  4418.4 1646.33  4488.3 1646.87  4600.9 1644.44    4750 1643.01  4819.5 1642.77
    4840 1643.61  4860.5 1642.27  4868.9 1641.52  4932.3 1640.47  4983.5  1640.8
  5003.7 1638.74  5024.5 1640.45  5106.4 1640.24  5193.3 1642.23  5198.7 1642.76
  5258.9 1644.51  5309.7 1648.22  5339.6 1653.28  5378.6 1658.25  5396.4  1661.3
  5411.3 1662.65  5432.3 1662.79  5474.9 1666.02  5489.2 1665.77    5519 1667.44
  5567.1 1667.36    5690 1667.86  5728.2 1668.02  5755.3 1665.91  5854.6 1661.45
#Mann= 7 ,-1 , 0
  4418.4      .1       0  4600.9     .05       0  4868.9     .04       0
  5198.7     .05       0  5378.6      .1       0  5567.1     .05       0
    5690      .1       0
Bank Sta=4860.5,5193.3
XS Rating Curve= 0 ,0
Exp/Cntr=0.3,0.1

Type RM Length L Ch R = 1 ,1706    ,675,675,675
BEGIN DESCRIPTION:
UNT 1061 IN HEWA 3.0
END DESCRIPTION:
XS GIS Cut Line= 4
      2745873.07     10044577.11      2745815.77     10044373.94
      2744758.47     10043702.06      2744055.33      10043483.3
#Sta/Elev= 30
  4614.8 1643.86  4725.6 1643.54    4838 1641.58  4853.3 1640.95  4926.1 1638.92
  4976.7  1638.6  4998.7 1637.15    5026 1638.49  5114.1  1638.3  5250.5    1640
  5322.3 1640.76  5390.2 1641.64  5427.8 1641.97  5579.2 1643.32  5628.4 1642.63
  5734.2 1643.94  5805.9 1644.12  5829.8 1645.31  5860.3 1644.64  5996.6 1644.75
  6256.2 1646.23  6357.6  1646.4  6371.9 1647.24  6390.2 1645.89    6444 1646.38
  6525.6 1645.59  6530.8 1646.28  6649.8 1646.69  6758.6 1648.34    6815 1650.28
#Mann= 11 ,-1 , 0
  4614.8      .1       0  4853.3     .05       0  5250.5      .1       0
  5322.3     .05       0  5427.8      .1       0  5579.2     .05       0
  5734.2      .1       0  5805.9     .05       0  6256.2      .1       0
    6444     .16       0  6649.8     .05       0
Bank Sta=4838,5390.2
XS Rating Curve= 0 ,0
Exp/Cntr=0.3,0.1

Type RM Length L Ch R = 1 ,1031    ,517,517,517
BEGIN DESCRIPTION:
UNT 1061 IN HEWA 2.0
END DESCRIPTION:
XS GIS Cut Line= 4
      2746102.22     10044160.43      2746102.22      10043972.9
      2745544.93      10043228.1      2744498.02     10043030.18
#Sta/Elev= 30
  4460.2 1643.53  4678.5 1642.77  4728.5 1642.88  4749.3 1643.62  4763.9 1642.82
  4784.8 1642.78  4793.1 1642.79  4799.3 1643.64  4807.7  1642.7  4828.5 1642.06
  4907.7 1640.75  4921.5 1640.27  4999.2 1637.28  5007.8 1637.91    5064 1638.62
  5143.2 1638.67  5343.3 1640.79  5349.5 1640.78  5584.5 1645.09    5727 1645.55
  5859.3 1647.41  6022.1 1648.15  6063.5 1647.74  6083.2 1646.72  6110.8 1647.78
  6144.3 1647.38  6168.2 1648.15  6205.3  1647.3  6429.2    1646  6643.4 1646.83
#Mann= 3 ,-1 , 0
  4460.2     .05       0  4921.5     .04       0  5349.5     .05       0
Bank Sta=4907.7,5343.3
XS Rating Curve= 0 ,0
Exp/Cntr=0.3,0.1

Type RM Length L Ch R = 1 ,514     ,0,0,0
BEGIN DESCRIPTION:
UNT 1061 IN HEWA 1.0
END DESCRIPTION:
XS GIS Cut Line= 4
       2746143.9     10044118.71      2746373.06     10043618.73
      2746248.06     10043243.73       2744458.3     10042848.32
#Sta/Elev= 30
  4259.4  1642.8  4786.9 1641.01  4935.2 1638.49  4941.2 1637.99  5004.2 1635.27
    5036 1636.76  5061.7 1636.16  5088.1 1637.47    5183 1638.08  5194.1 1638.25
  5277.6 1639.38  5327.2 1641.32  5347.6 1639.85    5365 1641.08  5419.3 1641.59
  5511.5 1639.84  5598.6 1639.68  5624.2 1640.16  5642.3 1641.65  5647.4 1640.73
  5685.6 1643.78  5767.5  1643.6  5968.4 1646.04  6386.9 1650.32  6453.7 1648.32
  6463.9 1649.33  6515.1 1649.92  6545.9 1648.62  6669.4 1647.72  7037.6 1648.74
#Mann= 4 ,-1 , 0
  4259.4     .05       0  4941.2     .04       0    5183     .05       0
  5968.4     .05       0
Bank Sta=4935.2,5194.1
XS Rating Curve= 0 ,0
Exp/Cntr=0.3,0.1

Chan Stop Cuts=-1
Use User Specified Reach Order=0
Composite Channel Slope=5