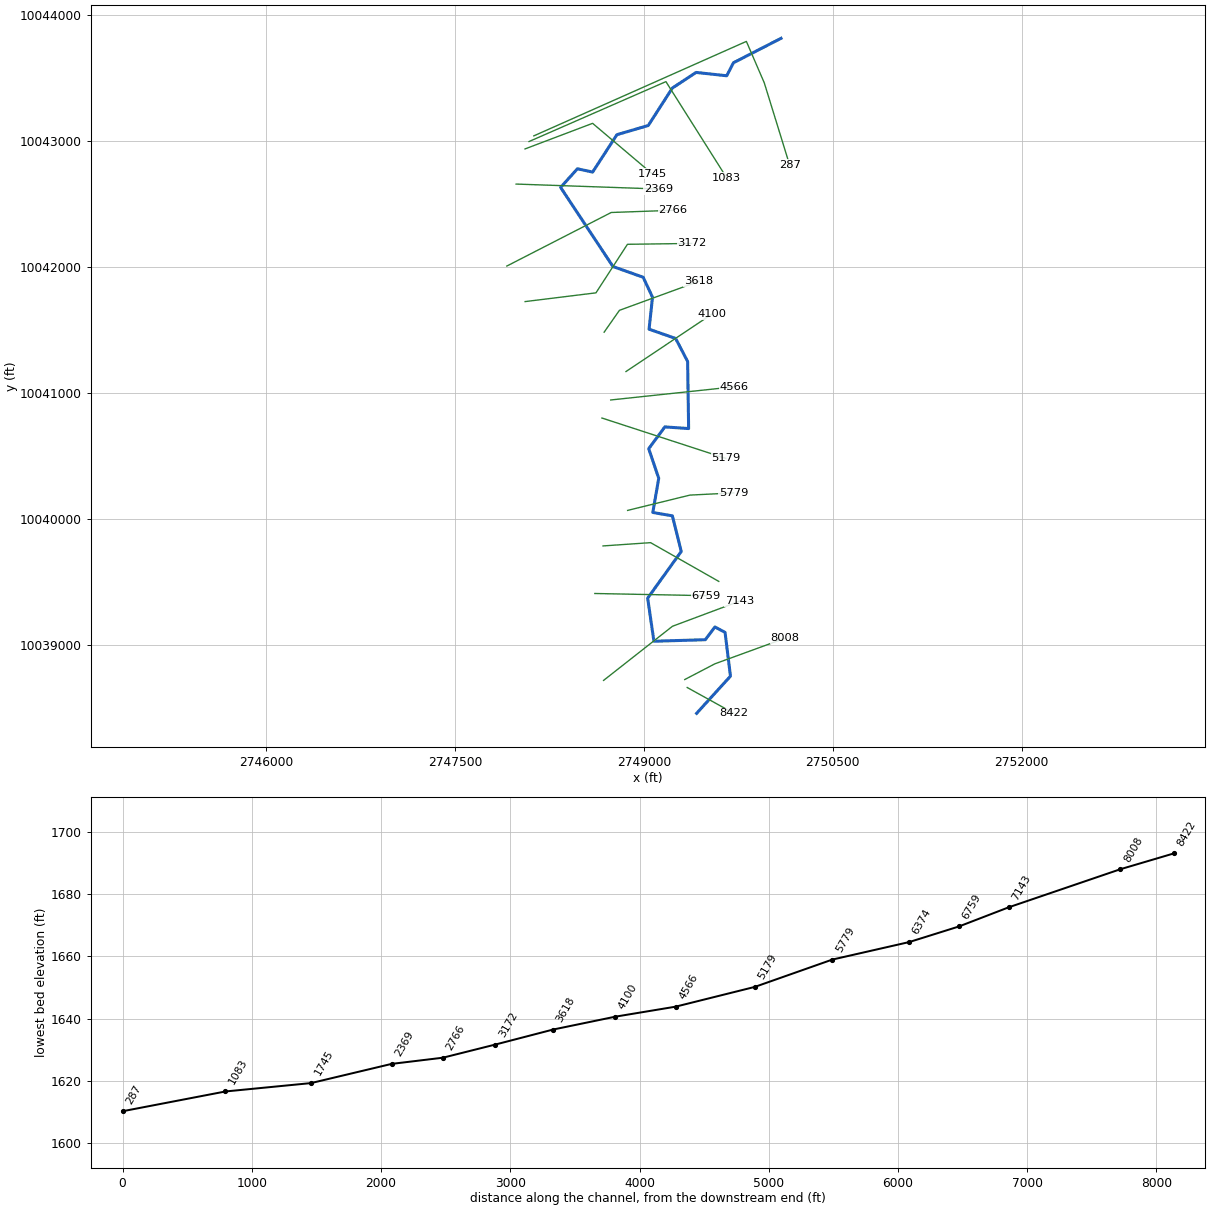
--- UNT 1062 IN HEWA.prj (project) ---

Proj Title=UNT 1062 IN HEWA Base Level Engineering
Current Plan=p01
Default Exp/Contr=0.3,0.1
English Units
Geom File=g01
Flow File=f01
Plan File=p01
BEGIN DESCRIPTION:
UNT 1062 IN HEWA
END DESCRIPTION:

--- UNT 1062 IN HEWA.p01 (plan) ---

Plan Title=Multiple Run
Short Identifier=Multiple
Geom File=g01
Flow File=f01
Subcritical Flow
K Sum by GR= 0
Std Step Tol= 0.01
Critical Tol= 0.01
Num of Std Step Trials= 20
Max Error Tol= 0.3
Flow Tol Ratio= 0.001
Split Flow NTrial= 30
Split Flow Tol= 0.02
Split Flow Ratio= 0.02
Log Output Level= 0
Friction Slope Method= 1
Unsteady Friction Slope Method= 2
Unsteady Bridges Friction Slope Method= 1
Parabolic Critical Depth
Global Vel Dist=  1 , 1 , 1
Global Log Level= 0
CheckData=True
Encroach Param= -1, 0, 0, 0
BEGIN DESCRIPTION:
Multiple Run
END DESCRIPTION:

--- UNT 1062 IN HEWA.f01 (steady flow) ---

Flow Title=Multiple
Number of Profiles=7
Profile Names=10-year,25-year,50-year,1pct_min,100-year,1pct_plu,500-year
River Rch & RM= UNT 1062 IN HEWA,Reach-1,8422
     828    1205    1533    1429    1933    2614    3084
River Rch & RM= UNT 1062 IN HEWA,Reach-1,7143
     967    1413    1803    1683    2277    3079    3646
Boundary for River Rch & Prof#=UNT 1062 IN HEWA,Reach-1,1
Up Type=0
Dn Type=3
Dn Slope=0.005
Boundary for River Rch & Prof#=UNT 1062 IN HEWA,Reach-1,2
Up Type=0
Dn Type=3
Dn Slope=0.005
Boundary for River Rch & Prof#=UNT 1062 IN HEWA,Reach-1,3
Up Type=0
Dn Type=3
Dn Slope=0.005
Boundary for River Rch & Prof#=UNT 1062 IN HEWA,Reach-1,4
Up Type=0
Dn Type=3
Dn Slope=0.005
Boundary for River Rch & Prof#=UNT 1062 IN HEWA,Reach-1,5
Up Type=0
Dn Type=3
Dn Slope=0.005
Boundary for River Rch & Prof#=UNT 1062 IN HEWA,Reach-1,6
Up Type=0
Dn Type=3
Dn Slope=0.005
Boundary for River Rch & Prof#=UNT 1062 IN HEWA,Reach-1,7
Up Type=0
Dn Type=3
Dn Slope=0.005

--- UNT 1062 IN HEWA.g01 (geometry) ---

Geom Title=Existing Conditions

River Reach=UNT 1062 IN HEWA,Reach-1
Reach XY= 30
      2749418.09     10038453.84      2749687.05     10038749.22
      2749644.20     10039096.91      2749563.99     10039139.91
      2749486.91     10039038.71      2749079.27     10039026.59
      2749029.79     10039368.78      2749296.30     10039739.24
      2749225.93     10040022.32      2749070.53     10040048.98
      2749117.57     10040320.67      2749038.03     10040555.29
      2749165.92     10040728.35      2749354.99     10040715.37
      2749346.99     10041247.97      2749252.02     10041430.43
      2749040.79     10041504.34      2749068.15     10041758.48
      2748993.85     10041916.75      2748754.34     10042001.69
      2748338.62     10042629.92      2748471.81     10042778.02
      2748592.80     10042751.90      2748785.44     10043048.73
      2749034.41     10043121.60      2749225.46     10043418.76
      2749414.01     10043542.93      2749657.43     10043516.58
      2749710.88     10043619.80      2750088.47     10043813.73

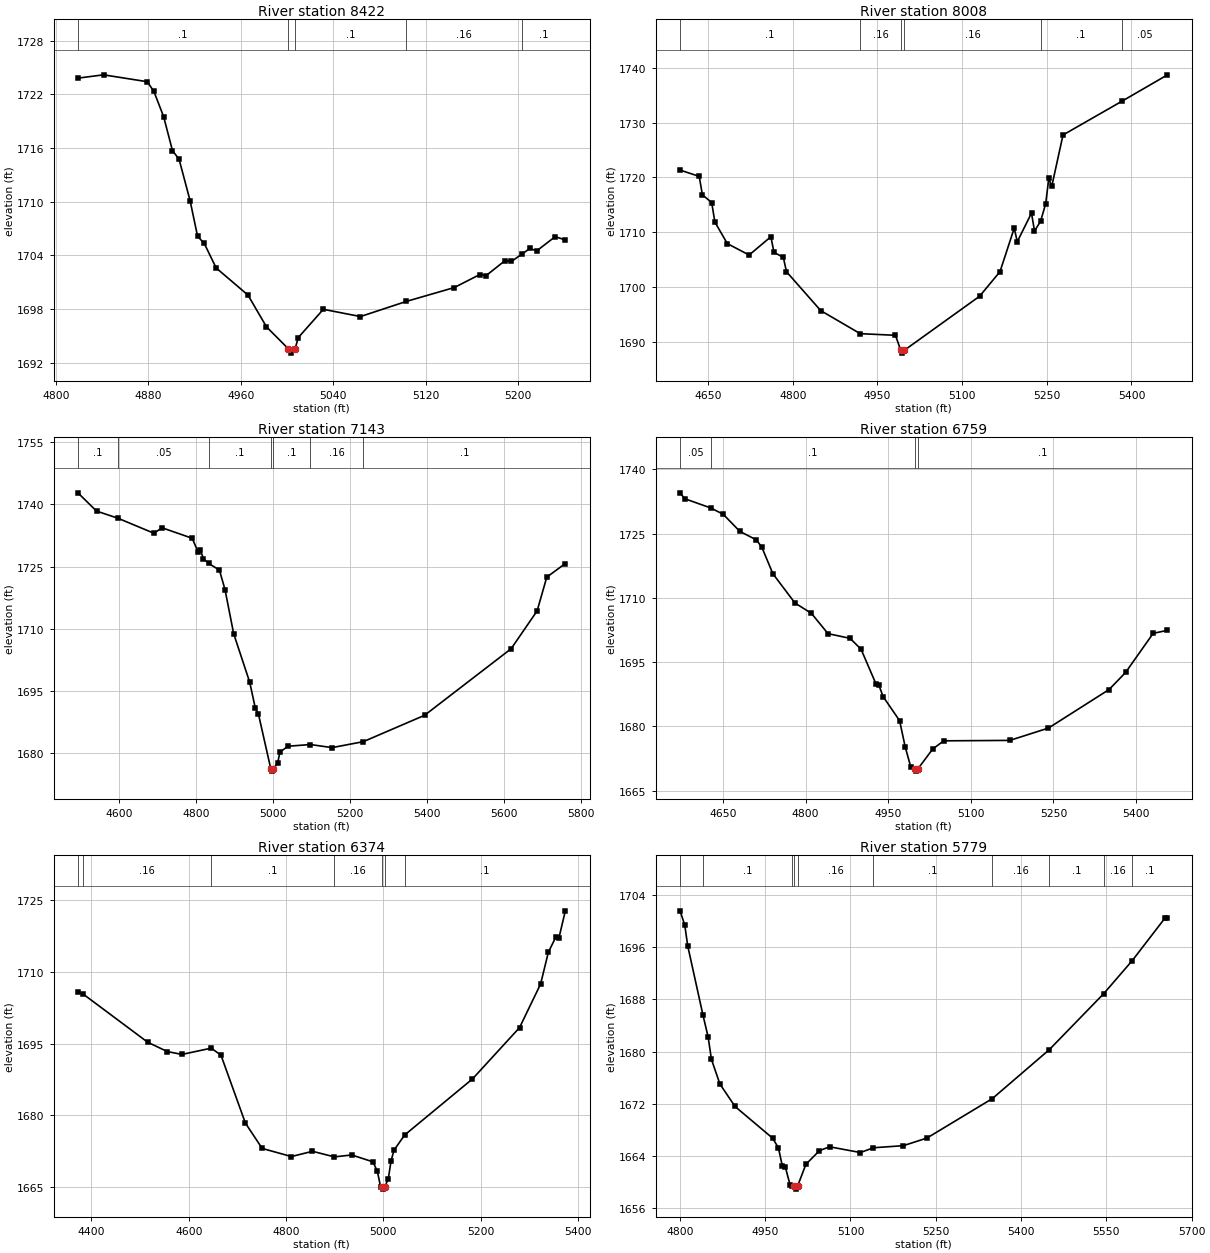
Type RM Length L Ch R = 1,8422,414,414,414
BEGIN DESCRIPTION:
UNT 1062 IN HEWA 14.0
END DESCRIPTION:
XS GIS Cut Line= 2
      2749343.59     10038659.25      2749712.54     10038455.24
#Sta/Elev= 30
  4819.1 1723.80  4841.3 1724.17  4879.1 1723.40  4884.8 1722.32  4893.2 1719.51
  4900.9 1715.69  4906.6 1714.73  4916.1 1710.11  4922.6 1706.12  4928.4 1705.31
  4938.7 1702.57  4966.2 1699.54  4982.2 1695.99  5001.0 1693.55  5003.7 1693.05
  5007.0 1693.55  5009.7 1694.79  5031.4 1697.95  5063.5 1697.14  5103.1 1698.83
  5144.6 1700.38  5166.6 1701.83  5172.3 1701.73  5188.4 1703.38  5194.1 1703.30
  5203.0 1704.11  5210.1 1704.76  5215.9 1704.48  5231.9 1706.07  5240.7 1705.71
#Mann=5,-1,0
  4819.1     0.1       0  5001.0    0.07       0  5007.0     0.1       0
  5103.1    0.16       0  5203.0     0.1       0
Bank Sta=5001,5007
Exp/Cntr=0.3,0.1

Type RM Length L Ch R = 1,8008,865,865,865
BEGIN DESCRIPTION:
UNT 1062 IN HEWA 13.0
END DESCRIPTION:
XS GIS Cut Line= 3
      2749324.33     10038722.57      2749563.95     10038847.59
      2750121.21     10039050.70
#Sta/Elev= 30
  4600.4 1721.35  4634.3 1720.20  4639.9 1716.84  4656.4 1715.43  4662.0 1711.88
  4684.1 1707.94  4722.7 1705.86  4761.2 1709.19  4766.8 1706.34  4783.3 1705.43
  4788.9 1702.81  4849.6 1695.72  4919.5 1691.52  4981.9 1691.22  4991.4 1688.47
  4994.1 1687.97  4997.4 1688.47  5130.9 1698.34  5167.1 1702.83  5192.3 1710.76
  5197.7 1708.29  5222.9 1713.51  5228.2 1710.24  5239.0 1712.02  5248.0 1715.21
  5253.5 1719.82  5258.8 1718.39  5278.7 1727.75  5383.0 1733.90  5463.8 1738.72
#Mann=6,-1,0
  4600.4     0.1       0  4919.5    0.16       0  4991.4    0.07       0
  4997.4    0.16       0  5239.0     0.1       0  5383.0    0.05       0
Bank Sta=4991.4,4997.4
Exp/Cntr=0.3,0.1

Type RM Length L Ch R = 1,7143,384,384,384
BEGIN DESCRIPTION:
UNT 1062 IN HEWA 12.0
END DESCRIPTION:
XS GIS Cut Line= 3
      2748679.55     10038715.64      2749226.44     10039145.34
      2749760.32     10039345.00
#Sta/Elev= 30
  4494.1 1742.81  4542.4 1738.41  4597.9 1736.69  4691.6 1733.06  4712.4 1734.39
  4791.0 1731.85  4805.5 1728.65  4811.8 1729.14  4819.9 1726.93  4833.8 1725.78
  4861.5 1724.18  4876.0 1719.49  4898.5 1708.85  4940.2 1697.14  4954.6 1690.95
  4962.7 1689.52  4995.0 1676.22  4997.7 1675.72  5001.0 1676.22  5012.4 1677.60
  5018.8 1680.33  5039.6 1681.72  5097.6 1682.13  5154.0 1681.39  5235.0 1682.82
  5394.2 1689.18  5618.8 1705.22  5686.4 1714.35  5711.4 1722.48  5759.6 1725.77
#Mann=7,-1,0
  4494.1     0.1       0  4597.9    0.05       0  4833.8     0.1       0
  4995.0    0.07       0  5001.0     0.1       0  5097.6    0.16       0
  5235.0     0.1       0
Bank Sta=4995,5001
Exp/Cntr=0.3,0.1

Type RM Length L Ch R = 1,6759,385,385,385
BEGIN DESCRIPTION:
UNT 1062 IN HEWA 11.0
END DESCRIPTION:
XS GIS Cut Line= 2
      2748610.13     10039405.75      2749494.46     10039388.41
#Sta/Elev= 30
  4572.4 1734.52  4580.7 1733.15  4628.2 1730.98  4650.7 1729.51  4680.8 1725.53
  4710.8 1723.54  4720.8 1721.82  4740.8 1715.64  4780.8 1708.82  4810.8 1706.39
  4840.8 1701.66  4880.8 1700.57  4900.8 1698.03  4928.2 1689.83  4933.2 1689.62
  4940.8 1686.98  4970.8 1681.35  4980.8 1675.29  4990.8 1670.65  4997.8 1670.08
  5000.6 1669.58  5003.8 1670.08  5030.8 1674.73  5050.8 1676.65  5170.8 1676.75
  5240.9 1679.63  5350.9 1688.62  5380.9 1692.61  5430.9 1701.73  5456.9 1702.44
#Mann=4,-1,0
  4572.4    0.05       0  4628.2     0.1       0  4997.8    0.07       0
  5003.8     0.1       0
Bank Sta=4997.8,5003.8
Exp/Cntr=0.3,0.1

Type RM Length L Ch R = 1,6374,595,595,595
BEGIN DESCRIPTION:
UNT 1062 IN HEWA 10.0
END DESCRIPTION:
XS GIS Cut Line= 3
      2748675.26     10039783.36      2749052.83     10039809.40
      2749594.40     10039501.79
#Sta/Elev= 30
  4372.4 1705.68  4382.7 1705.38  4515.9 1695.27  4556.0 1693.33  4586.1 1692.73
  4646.3 1694.04  4666.3 1692.57  4716.4 1678.39  4750.9 1673.08  4811.0 1671.38
  4854.3 1672.48  4899.2 1671.31  4935.0 1671.71  4978.3 1670.28  4987.4 1668.34
  4994.1 1665.11  4996.9 1665.07  4999.6 1664.57  5002.9 1665.07  5010.0 1666.73
  5015.8 1670.54  5021.9 1672.74  5043.6 1675.88  5183.0 1687.61  5279.6 1698.33
  5322.9 1707.45  5338.8 1714.09  5354.6 1717.35  5360.4 1717.01  5373.7 1722.75
#Mann=7,-1,0
  4372.4     0.1       0  4382.7    0.16       0  4646.3     0.1       0
  4899.2    0.16       0  4996.9    0.07       0  5002.9    0.16       0
  5043.6     0.1       0
Bank Sta=4996.9,5002.9
Exp/Cntr=0.3,0.1

Type RM Length L Ch R = 1,5779,600,600,600
BEGIN DESCRIPTION:
UNT 1062 IN HEWA 9.0
END DESCRIPTION:
XS GIS Cut Line= 3
      2748870.52     10040065.47      2749365.33     10040187.00
      2749712.58     10040204.37
#Sta/Elev= 30
  4800.3 1701.53  4808.5 1699.35  4813.8 1696.14  4840.5 1685.59  4849.7 1682.20
  4855.4 1678.81  4870.3 1675.03  4896.9 1671.59  4962.9 1666.75  4973.2 1665.27
  4980.0 1662.54  4985.2 1662.40  4993.8 1659.55  4997.6 1659.49  5001.1 1659.44
  5003.9 1658.94  5007.1 1659.44  5021.6 1662.74  5045.3 1664.82  5063.1 1665.42
  5117.4 1664.54  5140.3 1665.27  5193.0 1665.59  5234.5 1666.76  5349.4 1672.79
  5449.6 1680.28  5545.5 1688.87  5595.3 1693.89  5652.9 1700.40  5657.5 1700.40
#Mann=10,-1,0
  4800.3    0.16       0  4840.5     0.1       0  4997.6    0.16       0
  5001.1    0.07       0  5007.1    0.16       0  5140.3     0.1       0
  5349.4    0.16       0  5449.6     0.1       0  5545.5    0.16       0
  5595.3     0.1       0
Bank Sta=5001.1,5007.1
Exp/Cntr=0.3,0.1

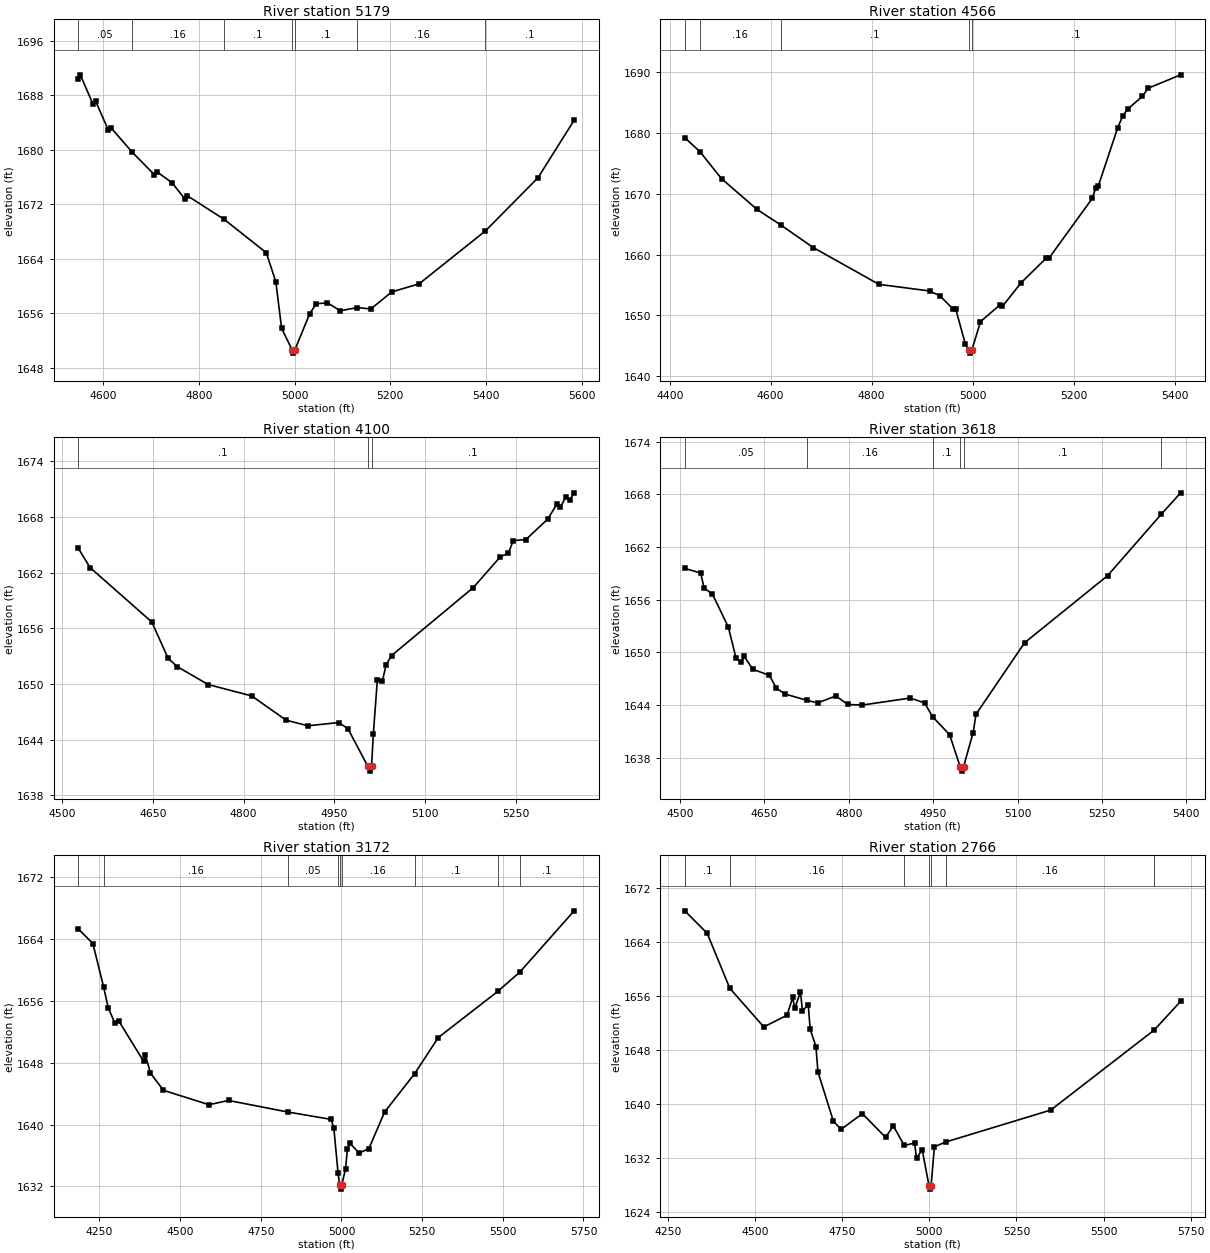
Type RM Length L Ch R = 1,5179,613,613,613
BEGIN DESCRIPTION:
UNT 1062 IN HEWA 8.0
END DESCRIPTION:
XS GIS Cut Line= 2
      2748666.51     10040798.99      2749650.35     10040478.27
#Sta/Elev= 30
  4548.8 1690.40  4552.9 1690.99  4579.5 1686.67  4584.8 1687.14  4611.4 1682.89
  4616.7 1683.24  4661.3 1679.64  4707.2 1676.36  4712.4 1676.79  4744.3 1675.16
  4771.0 1672.79  4776.2 1673.25  4852.7 1669.81  4941.1 1664.89  4961.1 1660.60
  4973.0 1653.79  4994.9 1650.66  4997.6 1650.16  5000.9 1650.66  5031.5 1655.92
  5045.2 1657.40  5068.7 1657.54  5095.3 1656.38  5131.4 1656.84  5159.2 1656.64
  5203.0 1659.14  5260.1 1660.33  5398.2 1668.08  5508.0 1675.88  5583.6 1684.34
#Mann=7,-1,0
  4548.8    0.05       0  4661.3    0.16       0  4852.7     0.1       0
  4994.9    0.07       0  5000.9     0.1       0  5131.4    0.16       0
  5398.2     0.1       0
Bank Sta=4994.9,5000.9
Exp/Cntr=0.3,0.1

Type RM Length L Ch R = 1,4566,466,466,466
BEGIN DESCRIPTION:
UNT 1062 IN HEWA 7.0
END DESCRIPTION:
XS GIS Cut Line= 2
      2748736.03     10040942.22      2749712.59     10041046.38
#Sta/Elev= 30
  4429.9 1679.25  4459.6 1676.97  4502.7 1672.51  4573.1 1667.44  4619.8 1664.90
  4684.3 1661.18  4814.5 1655.12  4915.1 1654.03  4935.2 1653.24  4961.5 1651.04
  4966.6 1651.06  4985.5 1645.32  4992.5 1644.31  4995.3 1643.81  4998.5 1644.31
  5015.6 1648.99  5053.9 1651.73  5059.0 1651.50  5096.1 1655.39  5146.3 1659.48
  5151.4 1659.45  5236.9 1669.25  5243.8 1670.98  5248.8 1671.26  5287.2 1680.84
  5297.2 1682.81  5307.3 1683.97  5336.2 1686.03  5347.5 1687.38  5412.0 1689.59
#Mann=5,-1,0
  4429.9    0.05       0  4459.6    0.16       0  4619.8     0.1       0
  4992.5    0.07       0  4998.5     0.1       0
Bank Sta=4992.5,4998.5
Exp/Cntr=0.3,0.1

Type RM Length L Ch R = 1,4100,482,482,482
BEGIN DESCRIPTION:
UNT 1062 IN HEWA 6.0
END DESCRIPTION:
XS GIS Cut Line= 2
      2748857.48     10041167.89      2749538.93     10041623.63
#Sta/Elev= 30
  4526.7 1664.62  4546.1 1662.55  4648.2 1656.68  4675.2 1652.76  4690.2 1651.87
  4741.2 1649.94  4813.3 1648.71  4870.4 1646.09  4906.4 1645.49  4957.4 1645.84
  4972.5 1645.17  5005.5 1641.10  5008.2 1640.60  5011.5 1641.10  5014.5 1644.65
  5021.1 1650.44  5029.5 1650.34  5035.5 1652.05  5044.5 1653.06  5179.7 1660.39
  5224.7 1663.73  5237.7 1664.08  5245.7 1665.46  5266.7 1665.57  5302.8 1667.78
  5317.8 1669.37  5323.8 1669.05  5332.8 1670.20  5338.8 1669.79  5346.5 1670.61
#Mann=3,-1,0
  4526.7     0.1       0  5005.5    0.07       0  5011.5     0.1       0
Bank Sta=5005.5,5011.5
Exp/Cntr=0.3,0.1

Type RM Length L Ch R = 1,3618,446,446,446
BEGIN DESCRIPTION:
UNT 1062 IN HEWA 5.0
END DESCRIPTION:
XS GIS Cut Line= 3
      2748683.91     10041480.42      2748805.43     10041654.02
      2749434.15     10041883.82
#Sta/Elev= 30
  4508.6 1659.57  4536.8 1659.05  4542.9 1657.34  4557.7 1656.64  4585.9 1652.90
  4599.6 1649.36  4608.3 1648.86  4614.4 1649.53  4629.2 1648.08  4658.9 1647.38
  4671.3 1645.93  4685.9 1645.27  4725.6 1644.53  4745.0 1644.24  4777.0 1645.03
  4798.3 1644.06  4823.3 1643.99  4909.5 1644.79  4934.7 1644.24  4949.2 1642.65
  4979.3 1640.61  4998.1 1636.96  5000.9 1636.46  5004.1 1636.96  5021.0 1640.84
  5026.3 1642.95  5112.6 1651.10  5260.0 1658.74  5355.4 1665.74  5389.9 1668.19
#Mann=6,-1,0
  4508.6    0.05       0  4725.6    0.16       0  4949.2     0.1       0
  4998.1    0.07       0  5004.1     0.1       0  5355.4    0.05       0
Bank Sta=4998.1,5004.1
Exp/Cntr=0.3,0.1

Type RM Length L Ch R = 1,3172,406,406,406
BEGIN DESCRIPTION:
UNT 1062 IN HEWA 4.0
END DESCRIPTION:
XS GIS Cut Line= 4
      2748056.60     10041723.46      2748619.07     10041792.90
      2748869.07     10042178.32      2749379.49     10042185.26
#Sta/Elev= 30
  4184.5 1665.28  4229.6 1663.39  4262.6 1657.82  4277.1 1655.09  4297.2 1653.17
  4310.7 1653.33  4386.8 1648.17  4391.9 1649.05  4408.0 1646.64  4448.4 1644.42
  4589.4 1642.56  4649.9 1643.11  4833.4 1641.62  4967.1 1640.67  4976.3 1639.58
  4989.4 1633.74  4994.4 1632.15  4997.1 1631.65  5000.4 1632.15  5012.5 1634.22
  5018.5 1636.86  5026.4 1637.56  5054.8 1636.31  5085.1 1636.90  5133.7 1641.62
  5226.9 1646.58  5300.0 1651.24  5484.1 1657.20  5552.2 1659.68  5721.1 1667.62
#Mann=9,-1,0
  4184.5     0.1       0  4262.6    0.16       0  4833.4    0.05       0
  4989.4    0.16       0  4994.4    0.07       0  5000.4    0.16       0
  5226.9     0.1       0  5484.1    0.05       0  5552.2     0.1       0
Bank Sta=4994.4,5000.4
Exp/Cntr=0.3,0.1

Type RM Length L Ch R = 1,2766,397,397,397
BEGIN DESCRIPTION:
UNT 1062 IN HEWA 3.0
END DESCRIPTION:
XS GIS Cut Line= 3
      2747911.33     10042005.58      2748740.33     10042430.93
      2749230.77     10042448.29
#Sta/Elev= 30
  4298.7 1668.60  4362.9 1665.28  4427.8 1657.14  4525.3 1651.42  4591.9 1653.15
  4608.4 1655.80  4614.0 1654.15  4630.6 1656.61  4636.2 1653.78  4652.8 1654.72
  4658.4 1651.09  4675.0 1648.49  4680.6 1644.78  4725.0 1637.47  4747.2 1636.27
  4808.2 1638.59  4874.7 1635.08  4896.9 1636.77  4928.5 1633.88  4957.9 1634.24
  4963.5 1632.05  4980.1 1633.19  4999.3 1627.92  5002.0 1627.42  5005.3 1627.92
  5014.8 1633.69  5048.2 1634.41  5348.7 1639.12  5645.4 1650.96  5721.2 1655.21
#Mann=7,-1,0
  4298.7     0.1       0  4427.8    0.16       0  4928.5    0.05       0
  4999.3    0.04       0  5005.3    0.05       0  5048.2    0.16       0
  5645.4     0.1       0
Bank Sta=4999.3,5005.3
Exp/Cntr=0.3,0.1

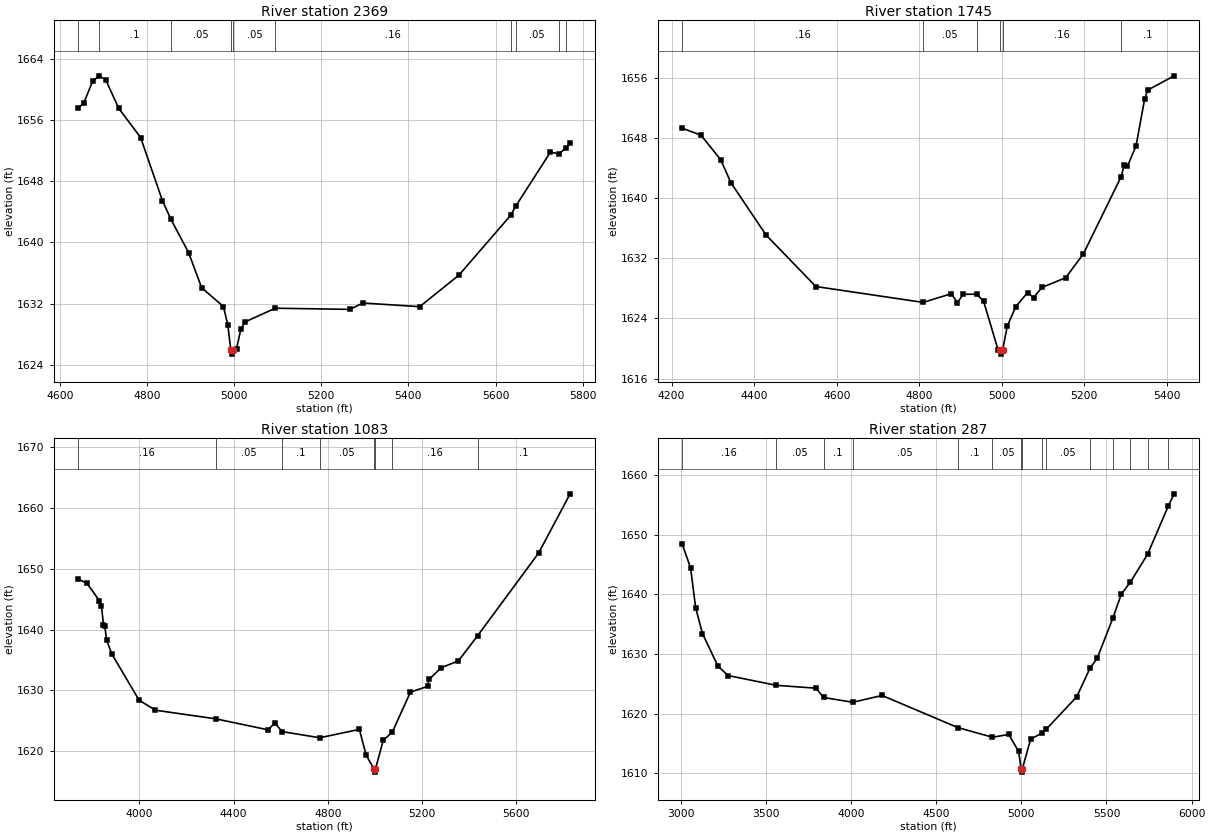
Type RM Length L Ch R = 1,2369,624,624,624
BEGIN DESCRIPTION:
UNT 1062 IN HEWA 2.0
END DESCRIPTION:
XS GIS Cut Line= 2
      2747985.14     10042656.62      2749113.57     10042617.56
#Sta/Elev= 30
  4642.1 1657.49  4655.4 1658.25  4675.4 1661.03  4690.3 1661.74  4705.5 1661.20
  4735.5 1657.48  4785.5 1653.69  4835.5 1645.46  4855.2 1643.00  4895.6 1638.67
  4925.6 1634.09  4975.6 1631.63  4985.6 1629.23  4992.6 1625.93  4995.4 1625.43
  4998.6 1625.93  5005.6 1626.13  5015.6 1628.71  5025.7 1629.65  5094.7 1631.42
  5265.8 1631.27  5295.8 1632.10  5425.9 1631.62  5515.9 1635.73  5634.6 1643.53
  5646.2 1644.72  5726.1 1651.80  5745.0 1651.55  5761.8 1652.33  5771.2 1652.94
#Mann=10,-1,0
  4642.1    0.16       0  4690.3     0.1       0  4855.2    0.05       0
  4992.6    0.04       0  4998.6    0.05       0  5094.7    0.16       0
  5634.6     0.1       0  5646.2    0.05       0  5745.0     0.1       0
  5761.8    0.05       0
Bank Sta=4992.6,4998.6
Exp/Cntr=0.3,0.1

Type RM Length L Ch R = 1,1745,662,662,662
BEGIN DESCRIPTION:
Mapping XS 6e8983bb
END DESCRIPTION:
XS GIS Cut Line= 3
      2748055.94     10042935.70      2748592.41     10043138.83
      2749064.38     10042739.46
#Sta/Elev= 30
  4225.5 1649.27  4271.0 1648.36  4318.9 1645.09  4343.8 1642.02  4428.9 1635.08
  4549.5 1628.24  4809.5 1626.13  4877.9 1627.29  4892.2 1626.09  4906.5 1627.21
  4939.4 1627.22  4955.9 1626.28  4991.0 1619.82  4995.8 1619.76  4998.5 1619.26
  5001.8 1619.76  5013.1 1622.97  5033.9 1625.57  5062.5 1627.44  5076.8 1626.78
  5097.6 1628.13  5154.8 1629.41  5197.7 1632.59  5289.0 1642.82  5296.5 1644.40
  5304.2 1644.20  5325.1 1646.91  5345.9 1653.11  5353.7 1654.34  5417.4 1656.23
#Mann=6,-1,0
  4225.5    0.16       0  4809.5    0.05       0  4939.4    0.16       0
  4995.8    0.07       0  5001.8    0.16       0  5289.0     0.1       0
Bank Sta=4995.8,5001.8
Exp/Cntr=0.3,0.1

Type RM Length L Ch R = 1,1083,796,796,796
BEGIN DESCRIPTION:
Mapping XS fc6db6e4
END DESCRIPTION:
XS GIS Cut Line= 3
      2748087.83     10042994.29      2749174.63     10043469.98
      2749656.45     10042707.39
#Sta/Elev= 30
  3739.8 1648.31  3777.3 1647.61  3829.5 1644.78  3838.7 1643.86  3847.4 1640.81
  3852.9 1640.59  3860.6 1638.28  3882.4 1636.02  3998.6 1628.39  4068.0 1626.75
  4323.8 1625.33  4545.9 1623.53  4574.7 1624.65  4605.9 1623.23  4765.6 1622.22
  4933.5 1623.60  4962.3 1619.38  4995.7 1617.07  4998.5 1616.57  5001.7 1617.07
  5035.2 1621.83  5073.1 1623.13  5150.5 1629.73  5223.4 1630.67  5229.3 1631.80
  5281.1 1633.74  5354.0 1634.86  5435.2 1638.98  5694.0 1652.56  5828.2 1662.32
#Mann=8,-1,0
  3739.8    0.16       0  4323.8    0.05       0  4605.9     0.1       0
  4765.6    0.05       0  4995.7    0.07       0  5001.7    0.05       0
  5073.1    0.16       0  5435.2     0.1       0
Bank Sta=4995.7,5001.7
Exp/Cntr=0.3,0.1

Type RM Length L Ch R = 1,287,0,0,0
BEGIN DESCRIPTION:
UNT 1062 IN HEWA 1.0
END DESCRIPTION:
XS GIS Cut Line= 4
      2748126.00     10043039.42      2749813.52     10043789.43
      2749955.88     10043459.57      2750156.98     10042807.73
#Sta/Elev= 30
  3009.0 1648.48  3058.7 1644.46  3088.3 1637.78  3128.5 1633.44  3219.6 1627.97
  3279.0 1626.41  3561.7 1624.77  3794.7 1624.29  3839.9 1622.73  4010.8 1621.93
  4182.6 1623.07  4626.5 1617.70  4830.3 1616.07  4926.5 1616.53  4984.4 1613.68
  4999.5 1610.72  5002.2 1610.22  5005.5 1610.72  5055.0 1615.76  5121.6 1616.76
  5145.2 1617.38  5325.7 1622.86  5403.1 1627.63  5445.1 1629.27  5538.1 1636.07
  5587.3 1640.07  5639.7 1642.03  5741.3 1646.74  5863.0 1654.82  5897.1 1656.87
#Mann=15,-1,0
  3009.0    0.16       0  3561.7    0.05       0  3839.9     0.1       0
  4010.8    0.05       0  4626.5     0.1       0  4830.3    0.05       0
  4999.5   0.035       0  5005.5    0.05       0  5121.6     0.1       0
  5145.2    0.05       0  5403.1     0.1       0  5538.1    0.16       0
  5639.7     0.1       0  5741.3    0.05       0  5863.0     0.1       0
Bank Sta=4999.5,5005.5
Exp/Cntr=0.3,0.1

Chan Stop Cuts=-1