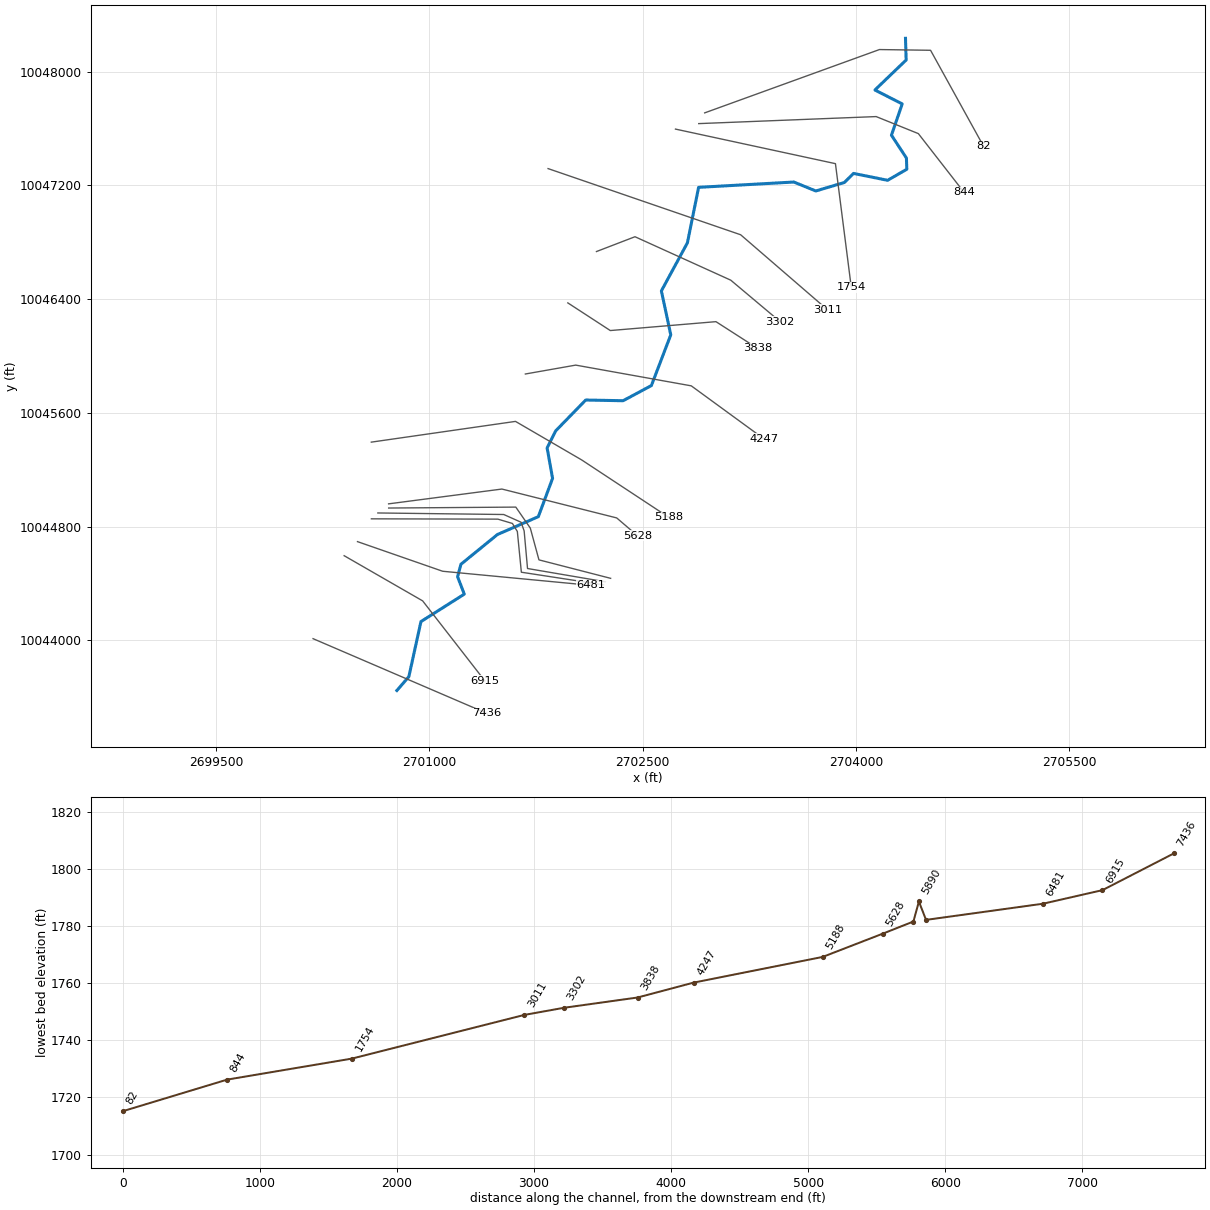
--- UNT 1063 IN HEWA.prj (project) ---

Proj Title=UNT 1063 IN HEWA Base Level Engineering
Current Plan=p01
Default Exp/Contr=0.3,0.1
English Units
Geom File=g01
Flow File=f01
Plan File=p01
Y Axis Title=Elevation
X Axis Title(PF)=Main Channel Distance
X Axis Title(XS)=Station
BEGIN DESCRIPTION:
UNT 1063 IN HEWA
END DESCRIPTION:
DSS Export Rating Curves= 0
DSS Export Rating Curve Sorted= 0
DSS Export Volume Flow Curves= 0
DXF OffsetX= 0
DXF OffsetY= 0
DXF ScaleX= 1
DXF ScaleY= 10

--- UNT 1063 IN HEWA.p01 (plan) ---

Plan Title=Multiple Run
Short Identifier=Multiple
Geom File=g01
Flow File=f01
Subcritical Flow
K Sum by GR= 0
Std Step Tol= 0.01
Critical Tol= 0.01
Num of Std Step Trials= 20
Max Error Tol= 0.3
Flow Tol Ratio= 0.001
Split Flow NTrial= 30
Split Flow Tol= 0.02
Split Flow Ratio= 0.02
Log Output Level= 0
Friction Slope Method= 1
Unsteady Friction Slope Method= 2
Unsteady Bridges Friction Slope Method= 1
Parabolic Critical Depth
Global Vel Dist=  1 , 1 , 1
Global Log Level= 0
CheckData=True
Encroach Param= -1, 0, 0, 0
BEGIN DESCRIPTION:
Multiple Run
END DESCRIPTION:

--- UNT 1063 IN HEWA.f01 (steady flow) ---

Flow Title=Multiple
Program Version=4.10
Number of Profiles= 7
Profile Names=10-year,25-year,50-year,1pct_min,100-year,1pct_plu,500-year
River Rch & RM=UNT 1063 IN HEWA,Reach-1         ,7436
    1430    2134    2759    2604    3521    4762    5730
River Rch & RM=UNT 1063 IN HEWA,Reach-1         ,5628
    1902    2872    3742    3552    4804    6496    7916
Boundary for River Rch & Prof#=UNT 1063 IN HEWA,Reach-1         , 1
Up Type= 0
Dn Type= 3
Dn Slope=0.015
Boundary for River Rch & Prof#=UNT 1063 IN HEWA,Reach-1         , 2
Up Type= 0
Dn Type= 3
Dn Slope=0.015
Boundary for River Rch & Prof#=UNT 1063 IN HEWA,Reach-1         , 3
Up Type= 0
Dn Type= 3
Dn Slope=0.015
Boundary for River Rch & Prof#=UNT 1063 IN HEWA,Reach-1         , 4
Up Type= 0
Dn Type= 3
Dn Slope=0.015
Boundary for River Rch & Prof#=UNT 1063 IN HEWA,Reach-1         , 5
Up Type= 0
Dn Type= 3
Dn Slope=0.015
Boundary for River Rch & Prof#=UNT 1063 IN HEWA,Reach-1         , 6
Up Type= 0
Dn Type= 3
Dn Slope=0.015
Boundary for River Rch & Prof#=UNT 1063 IN HEWA,Reach-1         , 7
Up Type= 0
Dn Type= 3
Dn Slope=0.015
DSS Import GetInterval= 0
DSS Import GetPeak= 0
DSS Import FillOption= 0

--- UNT 1063 IN HEWA.g01 (geometry) ---

Geom Title=Existing Conditions
Program Version=4.10

River Reach=UNT 1063 IN HEWA,Reach-1
Reach XY= 30
      2700771.77     10043647.63      2700855.96     10043744.72
      2700941.03      10044132.2      2701245.83     10044325.14
      2701198.57     10044447.96      2701222.26     10044535.34
      2701478.89     10044744.41      2701766.47     10044869.99
      2701866.76     10045139.48      2701828.25     10045353.55
      2701888.95     10045473.75      2702099.77     10045690.28
      2702362.59     10045685.32      2702561.65     10045792.01
      2702697.87     10046148.41      2702631.75     10046457.71
      2702814.72     10046795.28      2702893.59     10047185.94
       2703563.3     10047223.21      2703717.85     10047160.36
      2703918.54     10047220.06      2703983.06     10047283.77
      2704222.68      10047235.4      2704357.75     10047313.15
      2704354.92     10047392.08      2704249.59      10047552.7
       2704325.4     10047772.59      2704133.39     10047870.39
        2704353.     10048081.31      2704348.47     10048233.73

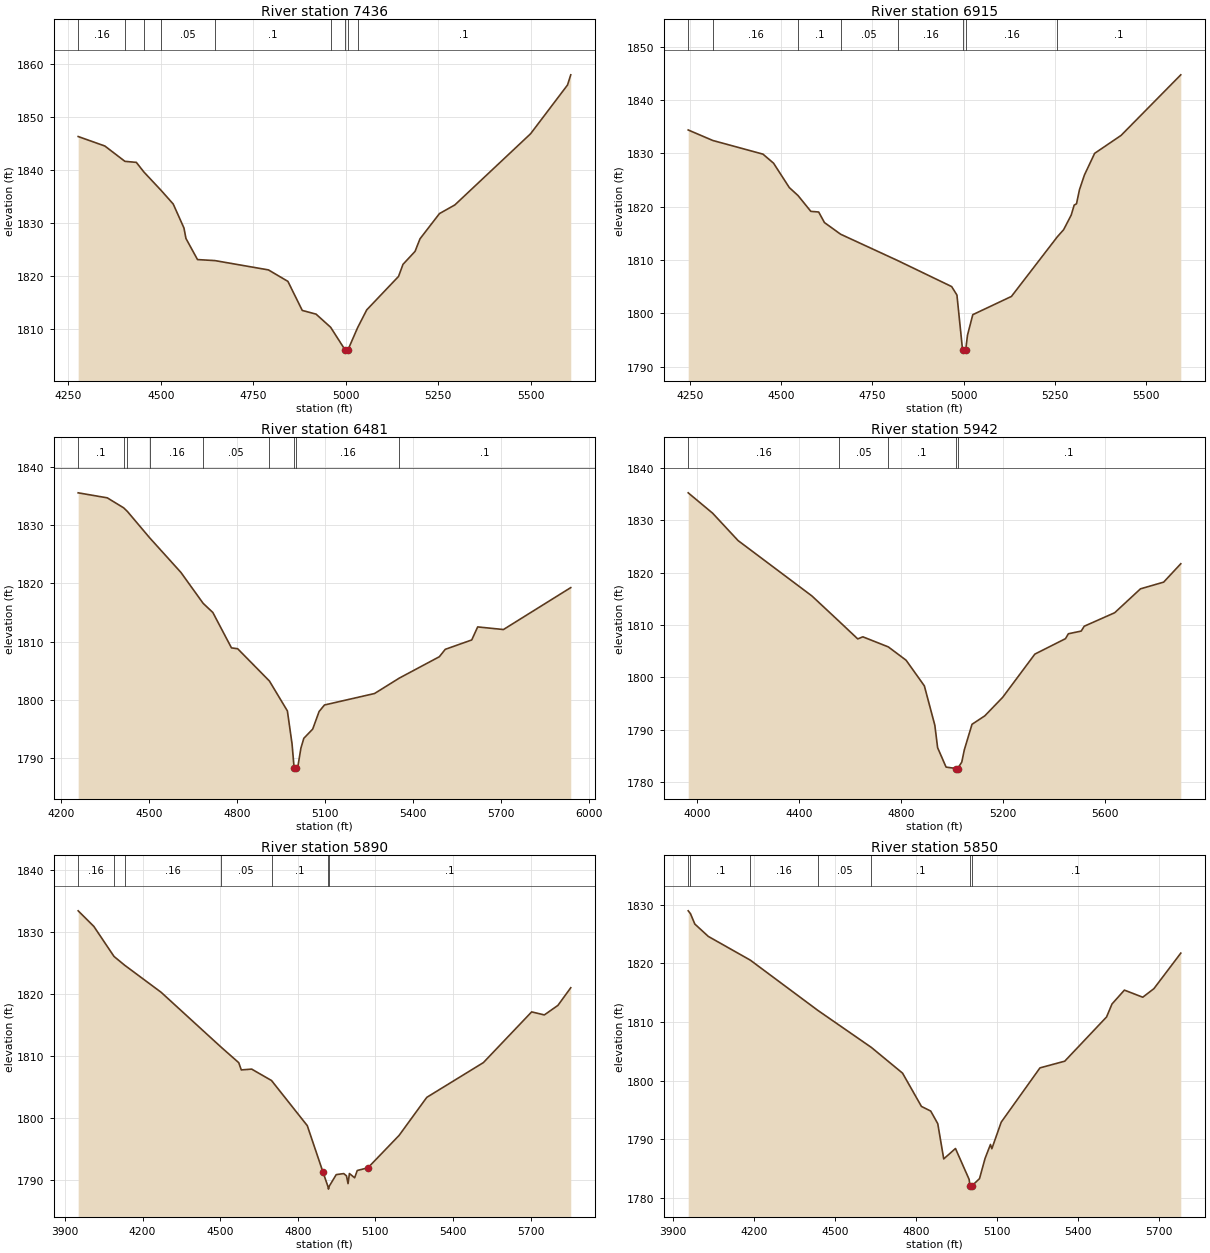
Type RM Length L Ch R = 1 ,7436    ,521,521,521
BEGIN DESCRIPTION:
UNT 1063 IN HEWA 13.0
END DESCRIPTION:
XS GIS Cut Line= 2
      2700182.29     10044012.17      2701404.86     10043486.73
#Sta/Elev= 30
    4277  1846.3    4349 1844.51  4403.3 1841.61  4434.2 1841.41  4454.6 1839.59
  4501.6 1836.08  4533.8 1833.54  4562.8 1829.01  4568.2 1827.03  4599.4 1823.04
  4646.4 1822.85    4791 1821.09  4843.6 1818.92  4882.4 1813.43  4919.7 1812.73
  4959.1 1810.24  4999.1 1805.86  5001.8 1805.36  5005.1 1805.86  5031.9 1810.17
  5056.5 1813.53  5142.5 1819.86  5154.5 1822.14  5187.1 1824.59  5200.4 1826.96
    5253 1831.73  5294.6 1833.37  5499.3 1846.83    5599 1856.04  5607.7 1857.96
#Mann= 9 ,-1 , 0
    4277     .16       0  4403.3      .1       0  4454.6     .16       0
  4501.6     .05       0  4646.4      .1       0  4959.1     .16       0
  4999.1     .07       0  5005.1     .16       0  5031.9      .1       0
Bank Sta=4999.1,5005.1
XS Rating Curve= 0 ,0
Exp/Cntr=0.3,0.1

Type RM Length L Ch R = 1 ,6915    ,434,434,434
BEGIN DESCRIPTION:
UNT 1063 IN HEWA 12.0
END DESCRIPTION:
XS GIS Cut Line= 3
      2700400.96     10044595.54      2700953.09     10044277.81
      2701390.57     10043715.33
#Sta/Elev= 30
  4245.5 1834.35  4312.9 1832.38  4450.3 1829.82  4479.4 1828.12  4522.5 1823.55
  4546.5 1822.05  4581.5 1819.09    4603 1818.97  4618.8 1816.99  4663.2  1814.8
  4819.3 1809.87  4967.3 1804.99  4981.8  1803.4  4996.3 1793.71  4999.6 1793.01
  5002.3 1792.51  5005.6 1793.01  5010.7 1795.87  5025.2 1799.72  5131.1 1803.14
  5256.7 1814.31  5274.1 1815.65  5294.9  1818.4    5303 1820.26  5309.4 1820.51
  5317.5 1823.15  5331.1 1825.91  5359.1 1829.97  5431.5 1833.33  5595.1 1844.69
#Mann= 8 ,-1 , 0
  4245.5      .1       0  4312.9     .16       0  4546.5      .1       0
  4663.2     .05       0  4819.3     .16       0  4999.6     .07       0
  5005.6     .16       0  5256.7      .1       0
Bank Sta=4999.6,5005.6
XS Rating Curve= 0 ,0
Exp/Cntr=0.3,0.1

Type RM Length L Ch R = 1 ,6481    ,853,853,853
BEGIN DESCRIPTION:
UNT 1063 IN HEWA 11.0
END DESCRIPTION:
XS GIS Cut Line= 3
      2700494.75     10044694.48      2701093.71     10044486.15
      2702134.47     10044387.27
#Sta/Elev= 30
    4259 1835.56  4358.2  1834.7  4414.2 1832.98  4426.9 1832.36    4503 1827.82
  4609.2  1821.9  4685.3 1816.57  4718.2 1815.01  4781.7 1808.93  4802.9 1808.78
  4911.1 1803.24  4972.4  1798.1  4988.3 1792.44  4995.4 1788.26  4998.1 1787.76
  5001.4 1788.26  5008.4 1788.63  5018.5 1791.71  5028.5  1793.4  5058.7 1794.98
  5080.5    1798  5098.8 1799.12  5269.6 1801.09  5354.1 1803.74  5490.6 1807.41
  5510.7 1808.68    5601 1810.29  5621.2 1812.53  5709.1 1812.08  5938.6 1819.28
#Mann= 9 ,-1 , 0
    4259      .1       0  4414.2     .16       0  4426.9      .1       0
    4503     .16       0  4685.3     .05       0  4911.1     .16       0
  4995.4     .07       0  5001.4     .16       0  5354.1      .1       0
Bank Sta=4995.4,5001.4
XS Rating Curve= 0 ,0
Exp/Cntr=0.3,0.1

Type RM Length L Ch R = 1 ,5942    ,52,52,52
BEGIN DESCRIPTION:
Mapping XS ee2e175d
END DESCRIPTION:
XS GIS Cut Line= 6
      2700592.48      10044854.8      2701482.21     10044852.63
      2701584.21     10044822.25      2701618.93     10044765.83
      2701647.14     10044479.37      2702225.02     10044390.63
#Sta/Elev= 30
  3963.6 1835.24  4059.6 1831.35  4159.6 1826.12  4449.6 1815.55    4555 1810.77
  4629.6 1807.35  4649.6 1807.75  4749.5 1805.83  4819.6 1803.28  4891.2 1798.39
  4932.4 1790.87  4943.3 1786.59  4976.5 1782.88  5016.1 1782.61  5018.8 1782.11
  5022.1 1782.61  5038.2 1783.83  5048.2 1786.17  5078.4 1791.05  5128.6 1792.66
  5198.9  1796.2  5325.3 1804.45  5445.7  1807.4  5456.8 1808.33  5507.4 1808.85
  5519.2 1809.77  5638.9 1812.35  5740.1 1816.91  5831.2 1818.19  5898.5  1821.7
#Mann= 5 ,-1 , 0
  3963.6     .16       0    4555     .05       0  4749.5      .1       0
  5016.1     .07       0  5022.1      .1       0
Bank Sta=5016.1,5022.1
XS Rating Curve= 0 ,0
Exp/Cntr=0.3,0.1

Type RM Length L Ch R = 1 ,5890    ,40,40,40
BEGIN DESCRIPTION:
Mapping XS cea39331
END DESCRIPTION:
XS GIS Cut Line= 6
      2700637.99     10044896.04      2701523.45     10044885.19
      2701644.97     10044830.93      2701666.68     10044770.17
      2701690.55     10044505.41      2702237.38      10044412.1
#Sta/Elev= 30
  3951.3 1833.48  4011.8 1830.97  4089.9 1826.11  4130.9  1824.7  4271.8 1820.33
  4501.8 1811.54  4571.8 1808.96  4581.8 1807.79  4621.8 1807.92  4698.5 1806.08
  4836.8 1798.79  4896.7 1791.38    4916 1789.04  4918.7 1788.54    4922 1789.04
  4948.6 1790.88  4977.6 1791.05  4988.2 1790.69  4994.3 1789.43  4999.6 1791.06
  5019.8 1790.37  5029.9 1791.55    5071 1791.98  5191.5 1797.21  5298.6 1803.36
  5517.3 1808.97  5703.9 1817.16  5752.9 1816.67  5805.4 1818.21    5855 1821.06
#Mann= 7 ,-1 , 0
  3951.3     .16       0  4089.9      .1       0  4130.9     .16       0
  4501.8     .05       0  4698.5      .1       0    4916     .07       0
    4922      .1       0
Bank Sta=4896.7,5071
XS Rating Curve= 0 ,0
Exp/Cntr=0.3,0.1

Type RM Length L Ch R = 1 ,5850    ,222,222,222
BEGIN DESCRIPTION:
Mapping XS f529e3fc
END DESCRIPTION:
XS GIS Cut Line= 5
      2700713.97     10044930.76      2701608.08     10044937.27
      2701710.08      10044789.7      2701770.84     10044566.18
      2702274.94     10044436.37
#Sta/Elev= 30
  3955.6 1828.96    3964 1828.48  3980.1 1826.71  4030.1  1824.6  4185.7 1820.56
  4435.7 1812.01  4634.6 1805.68  4750.1  1801.3  4820.1 1795.63  4854.5 1794.84
  4880.6 1792.69  4902.7 1786.69  4946.2 1788.46  4996.9 1783.19  4999.9 1782.04
  5002.7 1781.54  5005.9 1782.04  5035.3 1783.33    5056 1786.79  5075.9 1789.15
    5081 1788.42  5115.7 1792.95  5259.4  1802.2  5351.2 1803.34  5506.1 1810.87
  5526.4 1813.09  5572.3 1815.45  5640.4 1814.24  5681.7  1815.7  5781.3 1821.75
#Mann= 7 ,-1 , 0
  3955.6     .16       0    3964      .1       0  4185.7     .16       0
  4435.7     .05       0  4634.6      .1       0  4999.9     .07       0
  5005.9      .1       0
Bank Sta=4999.9,5005.9
XS Rating Curve= 0 ,0
Exp/Cntr=0.3,0.1

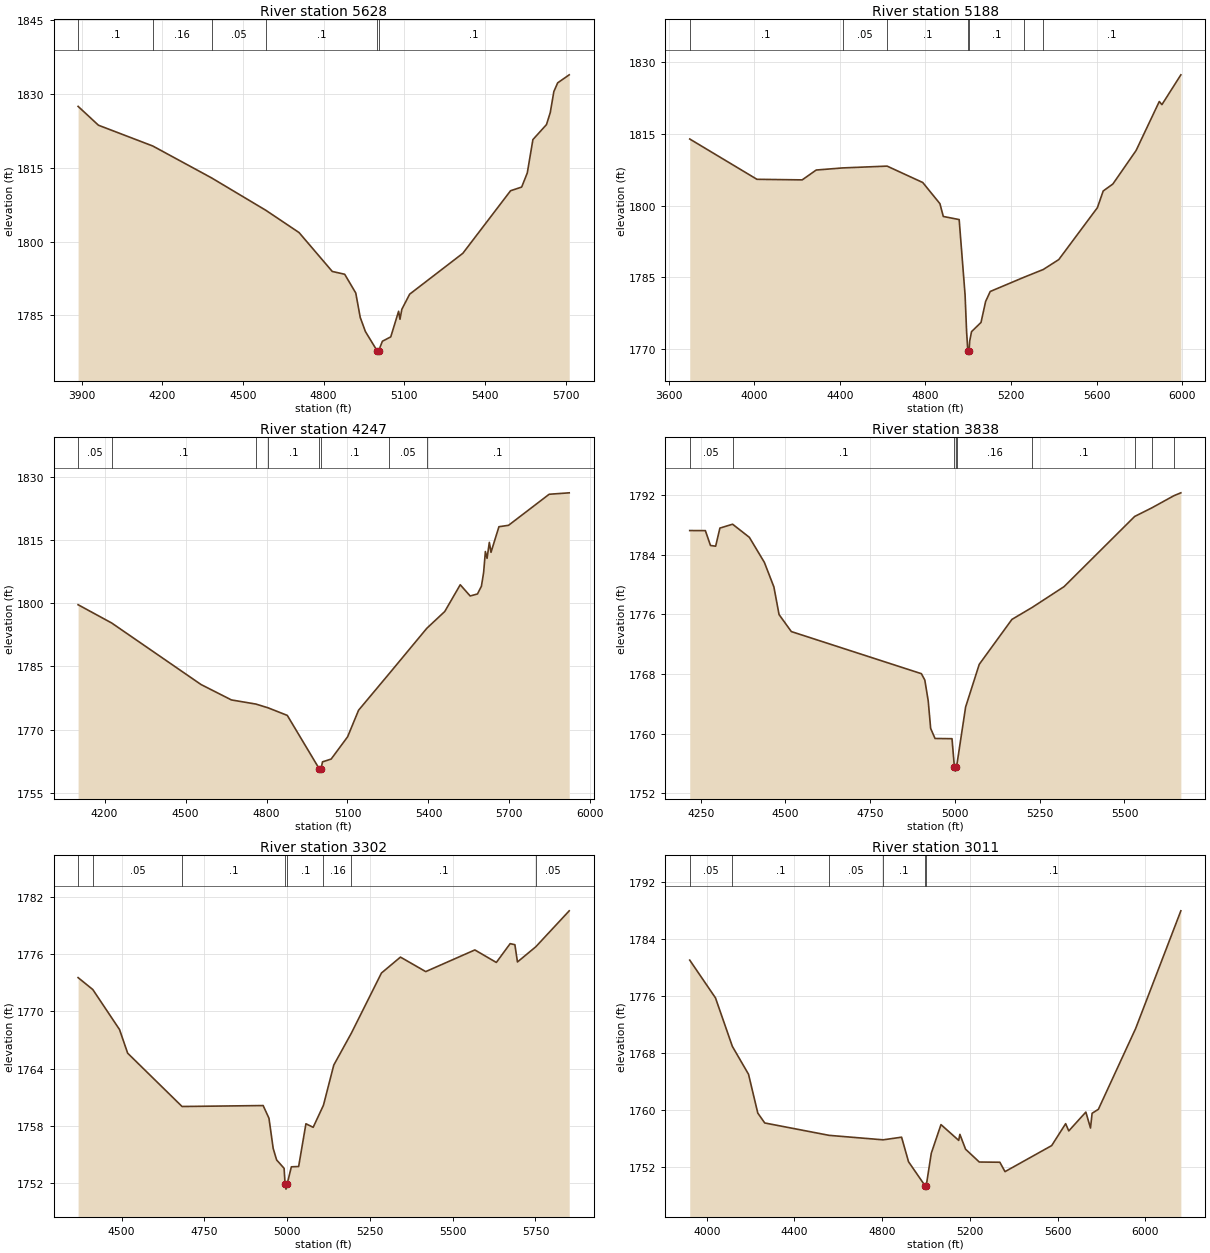
Type RM Length L Ch R = 1 ,5628    ,440,440,440
BEGIN DESCRIPTION:
UNT 1063 IN HEWA 9.0
END DESCRIPTION:
XS GIS Cut Line= 4
      2700713.52     10044960.11      2701510.38     10045064.27
      2702317.67     10044861.15      2702462.01     10044737.43
#Sta/Elev= 30
  3886.8 1827.47  3962.4 1823.64  4164.7 1819.41  4382.9 1812.94  4585.2 1806.34
  4708.5 1801.82  4831.9 1793.92  4878.1 1793.35  4919.3 1789.54  4935.9 1784.58
  4955.2  1781.7  4998.5 1777.82  5001.2 1777.32  5004.5 1777.82  5018.4 1779.74
  5049.4 1780.62  5078.6 1785.83  5083.7  1784.2  5090.6 1786.23  5119.7  1789.3
  5317.5 1797.61  5494.9 1810.32  5536.2 1811.07  5557.1 1813.94    5578 1820.72
  5628.4 1823.76  5642.5  1826.2  5655.9 1830.48  5670.1 1832.25    5713 1833.88
#Mann= 6 ,-1 , 0
  3886.8      .1       0  4164.7     .16       0  4382.9     .05       0
  4585.2      .1       0  4998.5     .07       0  5004.5      .1       0
Bank Sta=4998.5,5004.5
XS Rating Curve= 0 ,0
Exp/Cntr=0.3,0.1

Type RM Length L Ch R = 1 ,5188    ,941,941,941
BEGIN DESCRIPTION:
UNT 1063 IN HEWA 8.0
END DESCRIPTION:
XS GIS Cut Line= 4
      2700591.97     10045394.13      2701605.86     10045539.96
      2702071.14     10045269.13      2702682.26     10044866.35
#Sta/Elev= 30
  3699.2 1813.93  4013.2  1805.5  4224.6 1805.38  4290.1 1807.44  4413.2 1807.88
  4621.3 1808.26  4787.9 1804.83  4868.1 1800.41  4883.9 1797.73    4958 1797.08
  4985.6 1781.36  4992.7 1773.69  4998.4 1769.65  5001.1 1769.15  5004.4 1769.65
  5007.1 1771.66  5015.8 1773.64  5060.1 1775.57  5081.6 1779.95  5103.1 1782.04
    5261 1785.02    5351 1786.64  5423.3 1788.71  5603.9 1799.57    5631 1803.06
  5676.2 1804.52  5784.6 1811.52    5893 1821.77  5905.4 1821.12  5993.8 1827.35
#Mann= 7 ,-1 , 0
  3699.2      .1       0  4413.2     .05       0  4621.3      .1       0
  4998.4     .07       0  5004.4      .1       0    5261     .16       0
    5351      .1       0
Bank Sta=4998.4,5004.4
XS Rating Curve= 0 ,0
Exp/Cntr=0.3,0.1

Type RM Length L Ch R = 1 ,4247    ,409,409,409
BEGIN DESCRIPTION:
UNT 1063 IN HEWA 6.0
END DESCRIPTION:
XS GIS Cut Line= 4
      2701675.32      10045873.3      2702029.48      10045935.8
      2702841.98     10045789.96      2703354.67     10045415.84
#Sta/Elev= 30
  4101.8 1799.65  4226.4 1795.31  4557.5 1780.71    4670 1777.06  4760.7 1776.08
  4805.8 1775.19    4877 1773.39  4995.9 1760.67  4998.6 1760.17  5001.9 1760.67
  5007.4 1762.37  5039.5 1763.03  5100.5 1768.32  5141.1 1774.62  5254.9 1783.33
  5394.1 1794.07  5460.4 1798.04  5517.8 1804.39  5554.6 1801.73  5581.6  1802.2
  5596.3 1804.05  5604.4 1807.26    5611 1812.27  5617.2 1810.66  5625.6 1814.45
  5631.8 1812.09  5661.2 1818.16  5696.7 1818.49  5847.3 1825.86  5921.6  1826.2
#Mann= 8 ,-1 , 0
  4101.8     .05       0  4226.4      .1       0  4760.7     .16       0
  4805.8      .1       0  4995.9     .07       0  5001.9      .1       0
  5254.9     .05       0  5394.1      .1       0
Bank Sta=4995.9,5001.9
XS Rating Curve= 0 ,0
Exp/Cntr=0.3,0.1

Type RM Length L Ch R = 1 ,3838    ,536,536,536
BEGIN DESCRIPTION:
UNT 1063 IN HEWA 5.0
END DESCRIPTION:
XS GIS Cut Line= 4
      2701973.92      10046373.3      2702272.53     10046178.85
      2703015.59     10046241.35       2703307.3     10046053.83
#Sta/Elev= 30
  4217.6 1787.23  4263.7 1787.22  4278.8 1785.23    4294 1785.13  4306.6 1787.56
    4344 1788.08  4393.5 1786.32  4437.8 1782.96  4465.9 1779.66  4481.1 1775.96
  4517.3 1773.68    4901 1768.03  4911.1 1767.17  4921.1 1764.39  4928.3 1760.69
  4941.2 1759.34  4991.3 1759.31  4998.4 1755.46  5001.1 1754.96  5004.4 1755.46
  5005.2 1755.68  5031.5 1763.57  5071.6 1769.28    5168 1775.31  5228.2 1776.93
    5322 1779.71  5530.1 1789.12  5580.6 1790.27  5646.1 1791.91  5666.4 1792.29
#Mann= 9 ,-1 , 0
  4217.6     .05       0    4344      .1       0  4998.4     .07       0
  5004.4      .1       0  5005.2     .16       0  5228.2      .1       0
  5530.1     .05       0  5580.6      .1       0  5646.1     .05       0
Bank Sta=4998.4,5004.4
XS Rating Curve= 0 ,0
Exp/Cntr=0.3,0.1

Type RM Length L Ch R = 1 ,3302    ,291,291,291
BEGIN DESCRIPTION:
UNT 1063 IN HEWA 4.0
END DESCRIPTION:
XS GIS Cut Line= 4
      2702175.28      10046734.4      2702446.14     10046838.58
      2703119.75     10046533.02      2703466.94     10046241.38
#Sta/Elev= 30
  4368.6 1773.54    4413 1772.29  4493.7  1768.1  4518.3 1765.62  4682.6 1760.03
  4927.5 1760.13  4945.1  1758.8  4957.8 1755.64  4968.2 1754.43  4990.8 1753.55
  4993.8 1751.87  4996.5 1751.37  4999.8 1751.87  5012.7 1753.71  5034.7 1753.74
  5056.7 1758.22  5078.6 1757.85  5109.6 1760.16  5140.8 1764.37  5193.8 1767.71
  5284.8 1774.02  5342.2 1775.69  5418.5 1774.17  5566.9 1776.44  5631.8 1775.13
  5673.5  1777.1  5687.8 1776.99  5695.6 1775.18  5750.9 1776.77  5851.9 1780.54
#Mann= 8 ,-1 , 0
  4368.6      .1       0    4413     .05       0  4682.6      .1       0
  4993.8     .07       0  4999.8      .1       0  5109.6     .16       0
  5193.8      .1       0  5750.9     .05       0
Bank Sta=4993.8,4999.8
XS Rating Curve= 0 ,0
Exp/Cntr=0.3,0.1

Type RM Length L Ch R = 1 ,3011    ,1257,1257,1257
BEGIN DESCRIPTION:
UNT 1063 IN HEWA 3.0
END DESCRIPTION:
XS GIS Cut Line= 3
      2701835.03     10047317.74       2703189.2     10046852.46
      2703800.28     10046324.71
#Sta/Elev= 30
  3922.4 1781.05  4039.8 1775.74  4116.8 1768.92  4190.4 1765.01  4232.7 1759.55
  4264.4 1758.16  4557.7 1756.42  4804.1 1755.79  4888.3 1756.16    4920 1752.71
  4994.9 1749.36  4997.6 1748.86  5000.9 1749.36  5023.8 1753.91    5068 1757.93
  5148.8 1755.71  5154.1 1756.56  5180.1 1754.47  5242.6 1752.67  5336.3 1752.64
  5359.9 1751.32  5572.7 1754.98  5636.4 1758.06  5650.6 1757.04  5728.5 1759.69
  5749.7 1757.45    5757 1759.52  5785.6 1760.08  5955.6 1771.44  6161.7 1787.98
#Mann= 6 ,-1 , 0
  3922.4     .05       0  4116.8      .1       0  4557.7     .05       0
  4804.1      .1       0  4994.9     .07       0  5000.9      .1       0
Bank Sta=4994.9,5000.9
XS Rating Curve= 0 ,0
Exp/Cntr=0.3,0.1

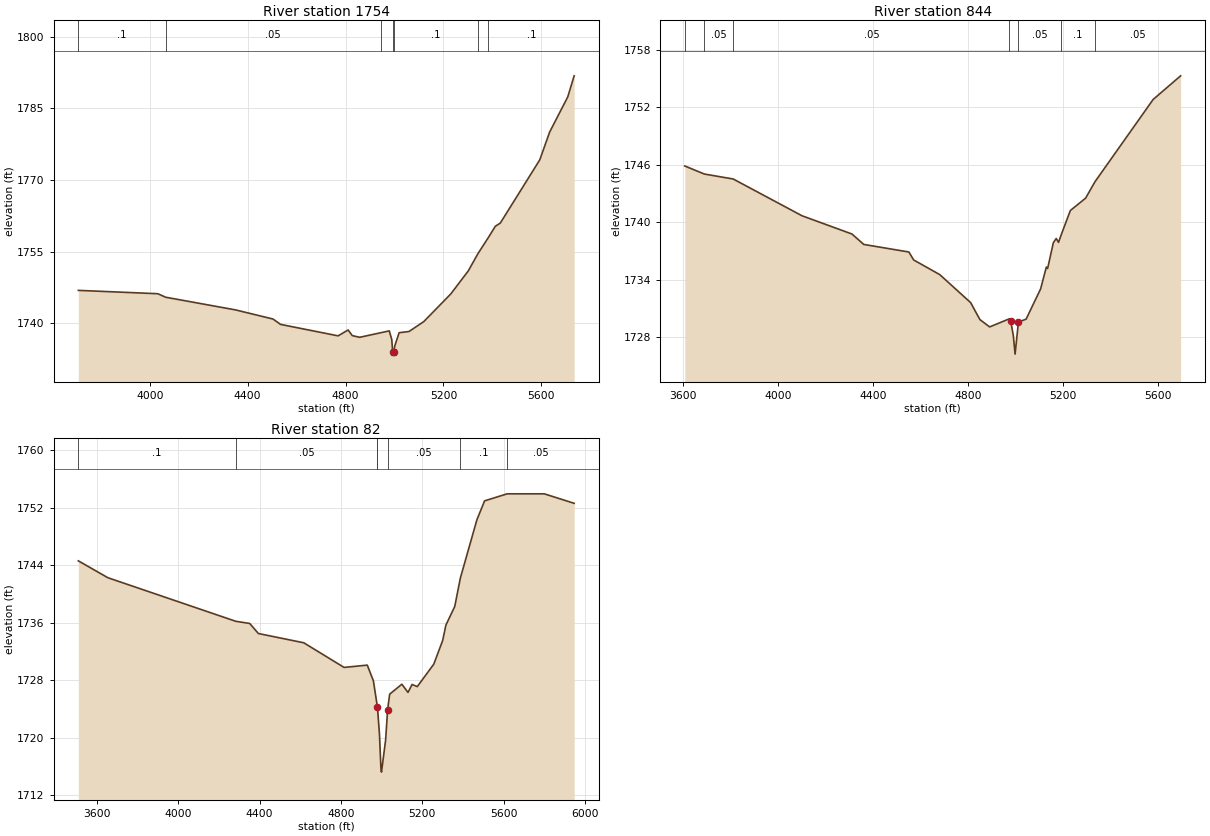
Type RM Length L Ch R = 1 ,1754    ,910,910,910
BEGIN DESCRIPTION:
UNT 1063 IN HEWA 2.0
END DESCRIPTION:
XS GIS Cut Line= 3
       2702730.9     10047595.51      2703855.86     10047352.46
      2703966.98     10046484.37
#Sta/Elev= 30
  3708.2 1746.92  4033.1 1746.22  4064.9 1745.49  4350.2 1742.84  4503.7 1740.93
  4534.4 1739.81  4769.7 1737.41  4810.6 1738.64  4827.7 1737.46  4857.9 1737.11
  4943.6 1738.06  4978.8 1738.45  4988.9 1736.66  4992.8 1734.09  4995.6 1733.59
  4998.8 1734.09  5000.9 1735.24  5019.1 1738.07  5059.5 1738.32    5120  1740.4
  5229.9 1746.16  5301.4 1750.97  5340.6 1754.55  5384.1    1758  5412.3 1760.33
  5432.5 1760.99  5593.8 1774.21  5634.1 1780.01  5708.2 1787.38  5734.3 1791.78
#Mann= 7 ,-1 , 0
  3708.2      .1       0  4064.9     .05       0  4943.6      .1       0
  4992.8     .07       0  4998.8      .1       0  5340.6     .16       0
  5384.1      .1       0
Bank Sta=4992.8,4998.8
XS Rating Curve= 0 ,0
Exp/Cntr=0.3,0.1

Type RM Length L Ch R = 1 ,844     ,762,762,762
BEGIN DESCRIPTION:
Mapping XS d92cd0e9
END DESCRIPTION:
XS GIS Cut Line= 4
      2702894.57     10047634.04        2704142.     10047683.52
      2704438.87     10047563.72       2704759.2     10047152.25
#Sta/Elev= 30
  3606.8 1745.88  3689.1 1745.04  3810.9 1744.52  4101.1 1740.68  4311.3 1738.78
  4361.3 1737.69  4551.4  1736.9  4571.5 1736.07  4681.5 1734.54  4811.6 1731.62
  4850.9 1729.84  4891.9 1729.08  4975.2 1729.93  4980.8 1729.66  4991.6 1728.18
    4999 1726.24  5013.2 1729.59  5045.5 1729.89  5106.7 1733.05  5130.8 1735.33
  5136.2 1735.18  5160.3 1737.87  5172.4 1738.31  5182.2 1737.91  5194.1 1738.74
    5232 1741.23  5296.3 1742.52  5335.7 1744.23  5580.9 1752.82  5696.8 1755.29
#Mann= 7 ,-1 , 0
  3606.8      .1       0  3689.1     .05       0  3810.9     .05       0
  4975.2     .04       0  5013.2     .05       0  5194.1      .1       0
  5335.7     .05       0
Bank Sta=4980.8,5013.2
XS Rating Curve= 0 ,0
Exp/Cntr=0.3,0.1

Type RM Length L Ch R = 1 ,82      ,0,0,0
BEGIN DESCRIPTION:
UNT 1063 IN HEWA 1.0
END DESCRIPTION:
XS GIS Cut Line= 4
       2702936.3     10047709.57      2704165.43     10048154.87
      2704524.81     10048149.66      2704897.22     10047475.16
#Sta/Elev= 30
  3508.9  1744.6    3654 1742.25    4283 1736.18  4351.4 1735.88    4394 1734.48
    4617 1733.19  4815.2 1729.76  4929.3 1730.08  4959.3 1727.89  4979.3  1724.2
  4989.3 1720.37  4996.3 1715.68    4999 1715.18  5019.3 1719.64  5029.3  1723.9
  5039.3 1726.04  5099.3 1727.42  5129.3 1726.28  5149.3 1727.38    5175 1727.09
  5256.1 1730.21  5299.7  1733.5  5315.7 1735.65  5359.2 1738.25  5386.8 1742.21
  5468.1 1750.32  5505.9 1752.95  5616.8 1753.93  5799.2 1753.93  5946.1 1752.61
#Mann= 7 ,-1 , 0
  3508.9      .1       0    4283     .05       0  4979.3      .1       0
  4979.3     .07       0  5029.3     .05       0  5386.8      .1       0
  5616.8     .05       0
Bank Sta=4979.3,5029.3
XS Rating Curve= 0 ,0
Exp/Cntr=0.3,0.1

Chan Stop Cuts=-1
Use User Specified Reach Order=0
Composite Channel Slope=5