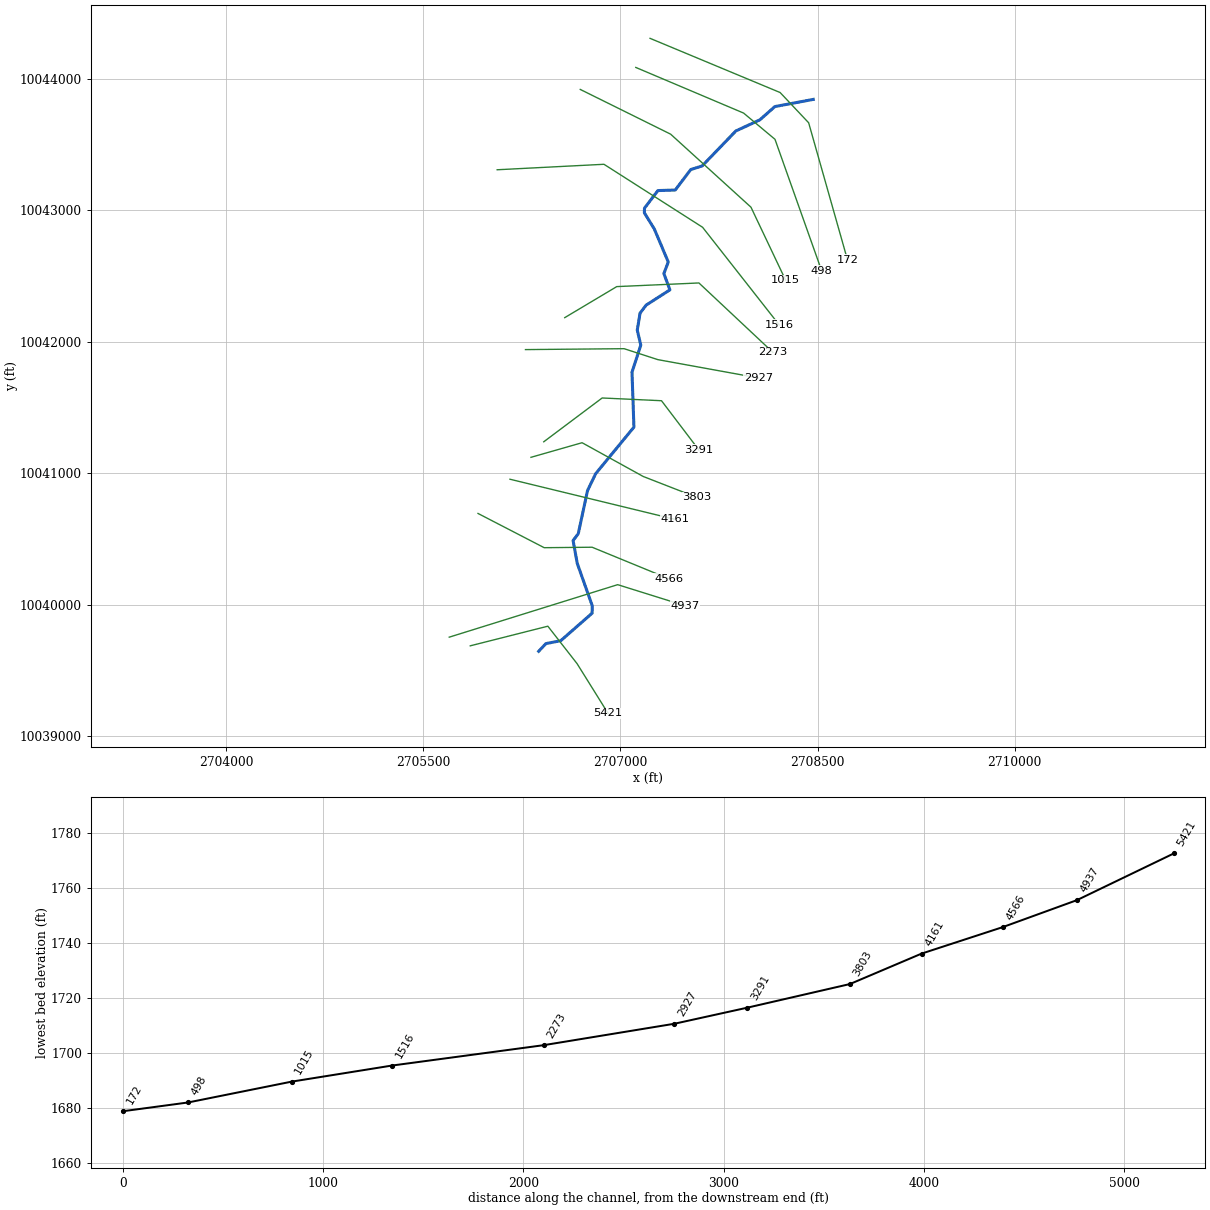
--- UNT 1064 IN HEWA.prj (project) ---

Proj Title=UNT 1064 IN HEWA Base Level Engineering
Current Plan=p01
Default Exp/Contr=0.3,0.1
English Units
Geom File=g01
Flow File=f01
Plan File=p01
BEGIN DESCRIPTION:
UNT 1064 IN HEWA
END DESCRIPTION:

--- UNT 1064 IN HEWA.p01 (plan) ---

Plan Title=Multiple Run
Short Identifier=Multiple
Geom File=g01
Flow File=f01
Subcritical Flow
K Sum by GR= 0
Std Step Tol= 0.01
Critical Tol= 0.01
Num of Std Step Trials= 20
Max Error Tol= 0.3
Flow Tol Ratio= 0.001
Split Flow NTrial= 30
Split Flow Tol= 0.02
Split Flow Ratio= 0.02
Log Output Level= 0
Friction Slope Method= 1
Unsteady Friction Slope Method= 2
Unsteady Bridges Friction Slope Method= 1
Parabolic Critical Depth
Global Vel Dist=  1 , 1 , 1
Global Log Level= 0
CheckData=True
Encroach Param= -1, 0, 0, 0
BEGIN DESCRIPTION:
Multiple Run
END DESCRIPTION:

--- UNT 1064 IN HEWA.f01 (steady flow) ---

Flow Title=Multiple
Number of Profiles=7
Profile Names=10-year,25-year,50-year,1pct_min,100-year,1pct_plu,500-year
River Rch & RM= UNT 1064 IN HEWA,Reach-1,5421
    1478    2203    2847    2684    3630    4909    5896
River Rch & RM= UNT 1064 IN HEWA,Reach-1,4937
    2256    3434    4499    4293    5806    7852    9667
Boundary for River Rch & Prof#=UNT 1064 IN HEWA,Reach-1,1
Up Type=0
Dn Type=3
Dn Slope=0.005
Boundary for River Rch & Prof#=UNT 1064 IN HEWA,Reach-1,2
Up Type=0
Dn Type=3
Dn Slope=0.005
Boundary for River Rch & Prof#=UNT 1064 IN HEWA,Reach-1,3
Up Type=0
Dn Type=3
Dn Slope=0.005
Boundary for River Rch & Prof#=UNT 1064 IN HEWA,Reach-1,4
Up Type=0
Dn Type=3
Dn Slope=0.005
Boundary for River Rch & Prof#=UNT 1064 IN HEWA,Reach-1,5
Up Type=0
Dn Type=3
Dn Slope=0.005
Boundary for River Rch & Prof#=UNT 1064 IN HEWA,Reach-1,6
Up Type=0
Dn Type=3
Dn Slope=0.005
Boundary for River Rch & Prof#=UNT 1064 IN HEWA,Reach-1,7
Up Type=0
Dn Type=3
Dn Slope=0.005

--- UNT 1064 IN HEWA.g01 (geometry) ---

Geom Title=Existing Conditions

River Reach=UNT 1064 IN HEWA,Reach-1
Reach XY= 30
      2706378.54     10039645.51      2706433.46     10039703.78
      2706546.75     10039726.32      2706785.14     10039935.22
      2706785.96     10039992.40      2706671.76     10040315.10
      2706640.29     10040487.92      2706679.80     10040540.40
      2706750.16     10040868.03      2706812.34     10040996.84
      2707103.17     10041350.53      2707088.41     10041768.65
      2707155.39     10041974.76      2707128.48     10042088.79
      2707149.84     10042218.21      2707195.85     10042278.84
      2707376.94     10042395.00      2707330.89     10042519.20
      2707364.43     10042606.66      2707258.12     10042858.59
      2707182.57     10042981.03      2707183.46     10043016.10
      2707285.61     10043150.30      2707417.54     10043154.42
      2707535.39     10043310.11      2707622.13     10043337.66
      2707878.47     10043603.73      2708061.29     10043688.43
      2708175.49     10043789.41      2708467.41     10043843.86

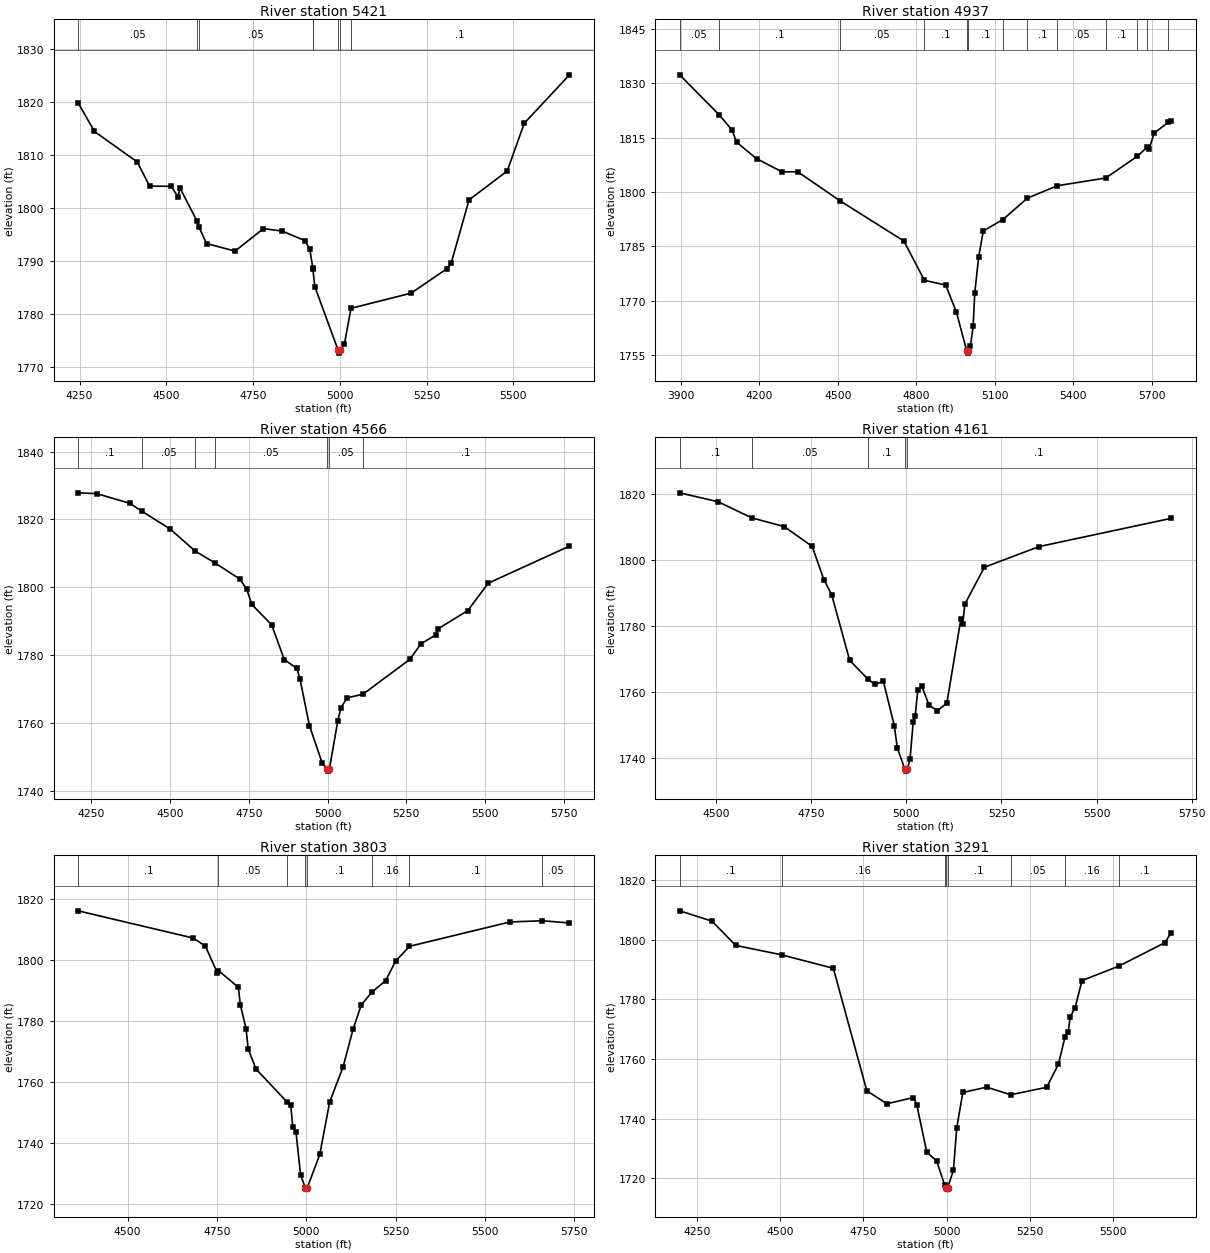
Type RM Length L Ch R = 1,5421,484,484,484
BEGIN DESCRIPTION:
UNT 1064 IN HEWA 12.0
END DESCRIPTION:
XS GIS Cut Line= 4
      2705858.04     10039687.10      2706448.31     10039836.41
      2706670.53     10039551.68      2706906.63     10039173.23
#Sta/Elev= 30
  4245.9 1819.87  4293.0 1814.46  4416.1 1808.71  4452.0 1804.13  4514.5 1804.09
  4534.0 1802.08  4539.2 1803.82  4588.1 1797.57  4594.0 1796.42  4616.0 1793.27
  4698.1 1791.85  4780.1 1796.10  4834.3 1795.63  4899.1 1793.84  4913.6 1792.24
  4922.2 1788.67  4922.5 1788.49  4928.0 1785.14  4995.6 1773.06  4998.4 1772.56
  5001.6 1773.06  5013.1 1774.20  5032.4 1781.03  5205.7 1783.90  5307.8 1788.48
  5320.7 1789.51  5372.6 1801.53  5482.4 1806.98  5531.8 1816.02  5662.0 1825.17
#Mann=8,-1,0
  4245.9    0.05       0  4588.1     0.1       0  4594.0    0.05       0
  4922.2     0.1       0  4922.5    0.05       0  4995.6   0.035       0
  5001.6    0.05       0  5032.4     0.1       0
Bank Sta=4995.6,5001.6
Exp/Cntr=0.3,0.1

Type RM Length L Ch R = 1,4937,371,371,371
BEGIN DESCRIPTION:
UNT 1064 IN HEWA 11.0
END DESCRIPTION:
XS GIS Cut Line= 3
      2705698.29     10039753.06      2706979.56     10040152.38
      2707490.00     10039992.65
#Sta/Elev= 30
  3896.1 1832.36  4046.0 1821.40  4095.3 1817.21  4113.9 1813.74  4189.6 1809.23
  4287.0 1805.59  4346.7 1805.61  4508.4 1797.61  4752.7 1786.48  4830.8 1775.65
  4912.3 1774.35  4953.0 1766.89  4993.1 1756.06  4995.8 1755.56  4999.1 1756.06
  5006.6 1757.45  5017.0 1762.92  5023.3 1772.19  5038.0 1782.03  5055.8 1789.27
  5130.1 1792.39  5224.5 1798.34  5339.1 1801.76  5523.4 1803.88  5643.9 1809.87
  5682.7 1812.46  5689.2 1811.91  5708.5 1816.26  5762.2 1819.27  5773.0 1819.72
#Mann=13,-1,0
  3896.1    0.05       0  4046.0     0.1       0  4508.4    0.05       0
  4830.8     0.1       0  4993.1    0.07       0  4999.1     0.1       0
  5130.1    0.05       0  5224.5     0.1       0  5339.1    0.05       0
  5523.4     0.1       0  5643.9    0.05       0  5682.7     0.1       0
  5762.2    0.05       0
Bank Sta=4993.1,4999.1
Exp/Cntr=0.3,0.1

Type RM Length L Ch R = 1,4566,405,405,405
BEGIN DESCRIPTION:
UNT 1064 IN HEWA 10.0
END DESCRIPTION:
XS GIS Cut Line= 4
      2705917.06     10040694.05      2706420.53     10040433.63
      2706785.12     10040437.10      2707367.01     10040198.11
#Sta/Elev= 30
  4207.5 1827.83  4266.8 1827.59  4371.9 1824.73  4410.0 1822.41  4499.1 1817.20
  4579.2 1810.65  4641.3 1807.18  4720.5 1802.44  4742.7 1799.45  4759.2 1794.90
  4822.3 1788.87  4862.3 1778.61  4902.3 1776.06  4912.3 1772.84  4942.3 1759.11
  4982.3 1748.21  4999.3 1746.23  5002.0 1745.73  5005.3 1746.23  5032.3 1760.60
  5042.3 1764.50  5062.3 1767.38  5111.9 1768.41  5261.2 1778.71  5295.9 1783.27
  5343.9 1785.92  5349.3 1787.63  5445.2 1793.10  5510.1 1801.18  5768.0 1812.11
#Mann=7,-1,0
  4207.5     0.1       0  4410.0    0.05       0  4579.2     0.1       0
  4641.3    0.05       0  4999.3   0.035       0  5005.3    0.05       0
  5111.9     0.1       0
Bank Sta=4999.3,5005.3
Exp/Cntr=0.3,0.1

Type RM Length L Ch R = 1,4161,358,358,358
BEGIN DESCRIPTION:
UNT 1064 IN HEWA 9.0
END DESCRIPTION:
XS GIS Cut Line= 2
      2706160.10     10040954.47      2707415.24     10040649.35
#Sta/Elev= 30
  4404.1 1820.44  4505.3 1817.73  4594.1 1812.83  4678.8 1810.22  4752.3 1804.22
  4783.2 1794.14  4803.8 1789.51  4850.9 1769.69  4898.9 1763.99  4917.0 1762.41
  4939.6 1763.29  4968.4 1749.83  4976.2 1743.12  4996.3 1736.60  4999.1 1736.10
  5002.3 1736.60  5009.6 1739.68  5017.9 1750.90  5023.1 1752.73  5030.2 1760.77
  5040.5 1761.84  5059.7 1756.08  5081.6 1754.40  5106.5 1756.74  5143.2 1782.13
  5148.3 1780.79  5153.7 1786.70  5205.1 1797.89  5349.2 1804.16  5695.8 1812.70
#Mann=5,-1,0
  4404.1     0.1       0  4594.1    0.05       0  4898.9     0.1       0
  4996.3    0.07       0  5002.3     0.1       0
Bank Sta=4996.3,5002.3
Exp/Cntr=0.3,0.1

Type RM Length L Ch R = 1,3803,512,512,512
BEGIN DESCRIPTION:
UNT 1064 IN HEWA 8.0
END DESCRIPTION:
XS GIS Cut Line= 4
      2706319.82     10041121.12      2706708.73     10041232.24
      2707174.01     10040975.29      2707583.60     10040815.62
#Sta/Elev= 30
  4361.4 1816.07  4684.0 1807.15  4717.8 1804.51  4751.6 1795.66  4754.4 1796.53
  4810.0 1791.05  4815.7 1785.29  4831.8 1777.35  4837.5 1770.88  4859.3 1764.33
  4945.8 1753.58  4956.7 1752.39  4962.4 1745.37  4971.2 1743.83  4984.2 1729.72
  4997.2 1725.52  5000.0 1725.02  5003.2 1725.52  5038.0 1736.40  5065.5 1753.46
  5103.3 1765.04  5131.1 1777.29  5154.0 1785.26  5184.2 1789.50  5222.5 1793.24
  5250.0 1799.58  5289.1 1804.46  5570.5 1812.43  5660.5 1812.82  5737.0 1812.11
#Mann=8,-1,0
  4361.4     0.1       0  4754.4    0.05       0  4945.8     0.1       0
  4997.2    0.07       0  5003.2     0.1       0  5184.2    0.16       0
  5289.1     0.1       0  5660.5    0.05       0
Bank Sta=4997.2,5003.2
Exp/Cntr=0.3,0.1

Type RM Length L Ch R = 1,3291,364,364,364
BEGIN DESCRIPTION:
UNT 1064 IN HEWA 7.0
END DESCRIPTION:
XS GIS Cut Line= 4
      2706417.09     10041239.20      2706861.51     10041572.52
      2707312.90     10041551.68      2707596.87     10041177.67
#Sta/Elev= 30
  4197.5 1809.66  4294.8 1806.20  4365.7 1798.08  4504.7 1794.90  4659.4 1790.40
  4760.0 1749.39  4820.1 1745.03  4900.1 1747.10  4910.2 1744.67  4940.2 1728.86
  4970.2 1725.80  4994.3 1717.67  4997.2 1716.93  5000.0 1716.43  5003.2 1716.93
  5020.3 1722.75  5030.3 1736.94  5048.7 1748.82  5120.4 1750.59  5192.3 1748.04
  5300.8 1750.55  5336.1 1758.33  5356.0 1767.52  5365.2 1768.96  5371.5 1774.17
  5386.1 1777.23  5406.9 1786.30  5517.5 1791.13  5656.5 1799.02  5674.5 1802.32
#Mann=8,-1,0
  4197.5     0.1       0  4504.7    0.16       0  4994.3     0.1       0
  4997.2    0.07       0  5003.2     0.1       0  5192.3    0.05       0
  5356.0    0.16       0  5517.5     0.1       0
Bank Sta=4997.2,5003.2
Exp/Cntr=0.3,0.1

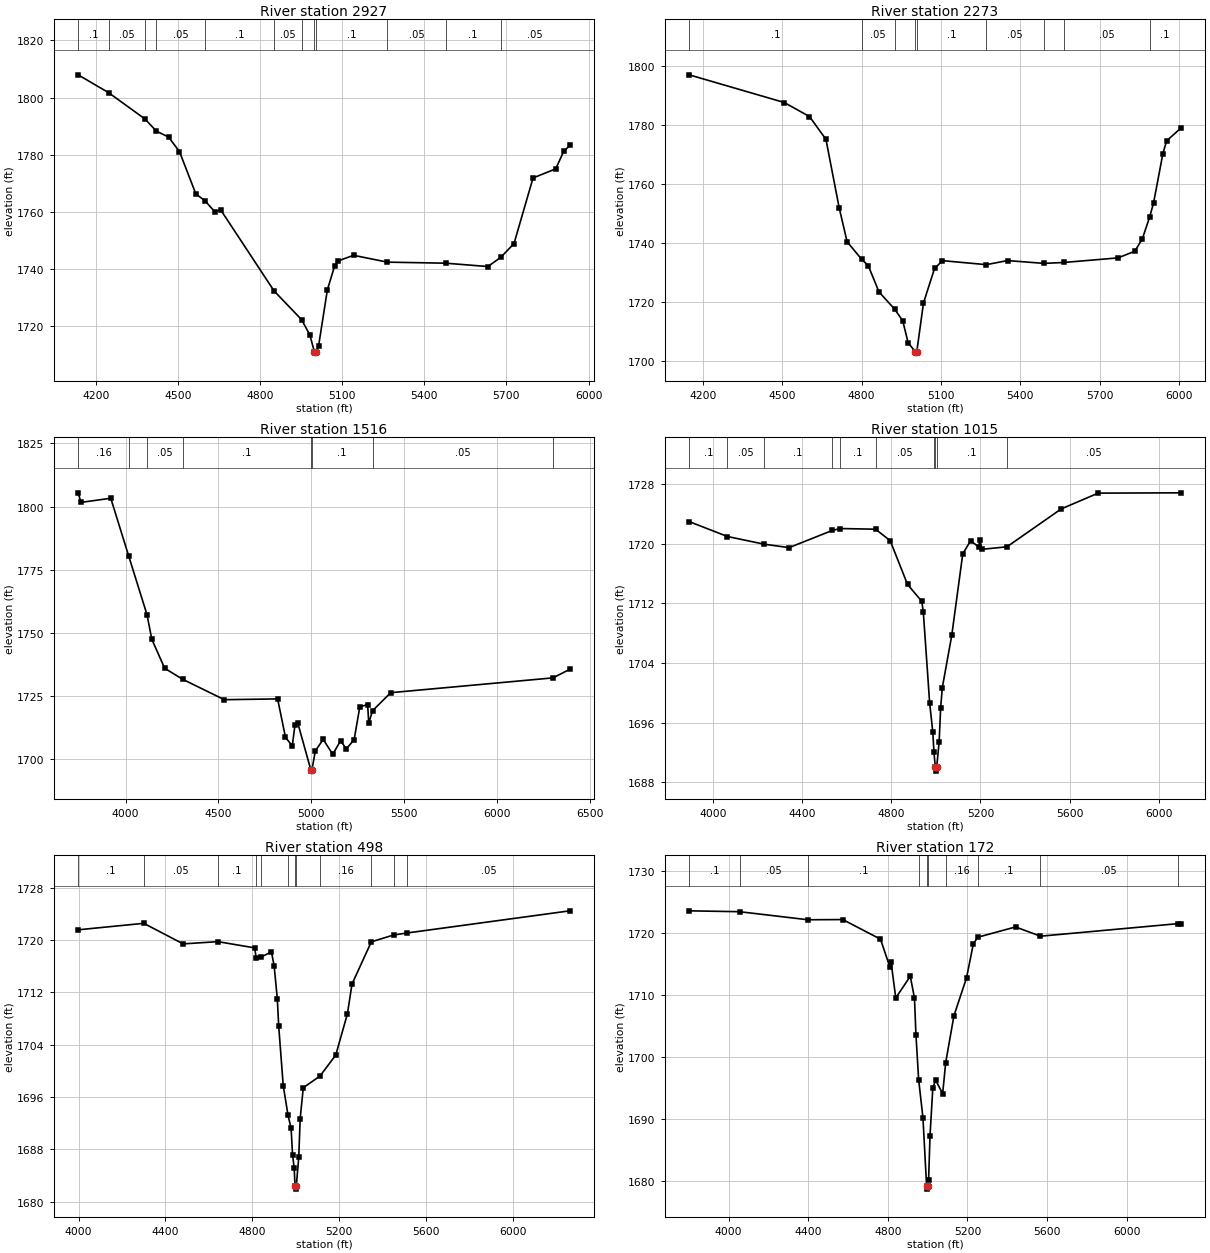
Type RM Length L Ch R = 1,2927,654,654,654
BEGIN DESCRIPTION:
UNT 1064 IN HEWA 6.0
END DESCRIPTION:
XS GIS Cut Line= 4
      2706278.19     10041940.57      2707028.17     10041947.52
      2707285.12     10041864.18      2708048.96     10041725.30
#Sta/Elev= 30
  4135.0 1807.98  4246.0 1801.76  4379.4 1792.52  4420.9 1788.26  4465.3 1786.21
  4505.3 1781.12  4565.3 1766.26  4598.6 1763.92  4635.3 1759.94  4655.3 1760.81
  4850.9 1732.36  4951.2 1722.32  4981.8 1716.95  4998.0 1711.08  5000.7 1710.58
  5004.0 1711.08  5013.7 1713.16  5045.7 1732.72  5072.4 1741.13  5085.1 1742.86
  5141.6 1744.81  5265.3 1742.42  5477.8 1742.06  5632.0 1740.88  5679.4 1744.11
  5727.7 1748.93  5797.2 1771.89  5880.2 1775.07  5909.0 1781.16  5931.5 1783.25
#Mann=12,-1,0
  4135.0     0.1       0  4246.0    0.05       0  4379.4     0.1       0
  4420.9    0.05       0  4598.6     0.1       0  4850.9    0.05       0
  4951.2     0.1       0  4998.0    0.07       0  5004.0     0.1       0
  5265.3    0.05       0  5477.8     0.1       0  5679.4    0.05       0
Bank Sta=4998,5004
Exp/Cntr=0.3,0.1

Type RM Length L Ch R = 1,2273,757,757,757
BEGIN DESCRIPTION:
UNT 1064 IN HEWA 5.0
END DESCRIPTION:
XS GIS Cut Line= 4
      2706576.82     10042183.65      2706972.62     10042419.74
      2707597.62     10042447.52      2708160.10     10041919.75
#Sta/Elev= 30
  4148.7 1797.10  4507.9 1787.72  4603.3 1782.96  4665.5 1775.24  4715.5 1752.04
  4745.6 1740.50  4800.5 1734.57  4825.6 1732.40  4865.7 1723.55  4925.2 1717.66
  4955.8 1713.71  4975.8 1706.37  5002.8 1703.27  5005.6 1702.77  5008.8 1703.27
  5034.1 1719.78  5075.9 1731.46  5105.9 1734.11  5271.5 1732.76  5351.6 1734.14
  5489.1 1733.19  5563.4 1733.49  5769.2 1735.05  5832.7 1737.32  5861.1 1741.53
  5888.6 1748.88  5903.5 1753.68  5938.7 1770.41  5952.9 1774.73  6006.5 1779.04
#Mann=9,-1,0
  4148.7     0.1       0  4800.5    0.05       0  4925.2     0.1       0
  5002.8    0.07       0  5008.8     0.1       0  5271.5    0.05       0
  5489.1     0.1       0  5563.4    0.05       0  5888.6     0.1       0
Bank Sta=5002.8,5008.8
Exp/Cntr=0.3,0.1

Type RM Length L Ch R = 1,1516,501,501,501
BEGIN DESCRIPTION:
UNT 1064 IN HEWA 3.0
END DESCRIPTION:
XS GIS Cut Line= 4
      2706062.94     10043308.63      2706875.40     10043350.29
      2707625.40     10042871.13      2708208.49     10042128.38
#Sta/Elev= 30
  3744.6 1805.48  3760.1 1801.70  3920.4 1803.33  4016.9 1780.49  4115.5 1757.25
  4141.4 1747.54  4210.7 1736.07  4306.8 1731.73  4531.9 1723.62  4819.0 1723.94
  4861.3 1708.73  4897.7 1705.35  4912.9 1713.80  4928.1 1714.24  4997.8 1695.86
  5000.6 1695.36  5003.8 1695.86  5022.0 1703.36  5064.3 1707.91  5115.9 1702.02
  5158.2 1707.42  5188.6 1704.14  5231.0 1707.79  5261.4 1720.75  5303.7 1721.72
  5309.6 1714.41  5330.0 1719.25  5428.0 1726.40  6301.8 1732.26  6392.4 1735.64
#Mann=8,-1,0
  3744.6    0.16       0  4016.9     0.1       0  4115.5    0.05       0
  4306.8     0.1       0  4997.8    0.07       0  5003.8     0.1       0
  5330.0    0.05       0  6301.8     0.1       0
Bank Sta=4997.8,5003.8
Exp/Cntr=0.3,0.1

Type RM Length L Ch R = 1,1015,517,517,517
BEGIN DESCRIPTION:
UNT 1064 IN HEWA 2.0
END DESCRIPTION:
XS GIS Cut Line= 4
      2706694.88     10043919.72      2707382.34     10043579.46
      2707993.45     10043023.91      2708257.26     10042468.53
#Sta/Elev= 30
  3892.0 1722.98  4064.1 1720.98  4228.7 1719.95  4340.9 1719.49  4534.3 1721.79
  4570.9 1722.05  4728.9 1721.96  4794.8 1720.42  4872.5 1714.55  4936.7 1712.28
  4943.5 1710.82  4971.9 1698.65  4986.1 1694.72  4991.2 1692.06  4997.3 1690.01
  5000.0 1689.51  5003.3 1690.01  5014.4 1693.39  5021.2 1697.95  5028.6 1700.69
  5071.2 1707.73  5120.5 1718.64  5155.7 1720.42  5191.5 1719.59  5198.2 1720.56
  5205.7 1719.26  5319.0 1719.60  5562.6 1724.68  5728.7 1726.80  6099.8 1726.84
#Mann=10,-1,0
  3892.0     0.1       0  4064.1    0.05       0  4228.7     0.1       0
  4534.3    0.05       0  4570.9     0.1       0  4728.9    0.05       0
  4991.2     0.1       0  4997.3    0.07       0  5003.3     0.1       0
  5319.0    0.05       0
Bank Sta=4997.3,5003.3
Exp/Cntr=0.3,0.1

Type RM Length L Ch R = 1,498,326,326,326
BEGIN DESCRIPTION:
Mapping XS b4b4c83a
END DESCRIPTION:
XS GIS Cut Line= 4
      2707117.27     10044087.04      2707937.56     10043739.83
      2708176.27     10043540.18      2708531.96     10042538.18
#Sta/Elev= 30
  3997.9 1721.55  4300.2 1722.54  4481.7 1719.40  4642.0 1719.74  4811.3 1718.79
  4818.3 1717.22  4841.9 1717.40  4888.6 1718.19  4901.1 1716.00  4915.5 1711.05
  4922.0 1706.83  4942.8 1697.76  4965.0 1693.20  4979.2 1691.22  4985.7 1687.20
  4993.5 1685.10  4997.1 1682.43  4999.8 1681.93  5003.1 1682.43  5014.4 1686.82
  5020.9 1692.68  5035.2 1697.42  5112.3 1699.21  5184.8 1702.41  5238.5 1708.70
  5259.7 1713.26  5348.7 1719.71  5451.5 1720.76  5514.6 1721.07  6263.1 1724.45
#Mann=12,-1,0
  3997.9     0.1       0  4300.2    0.05       0  4642.0     0.1       0
  4818.3    0.05       0  4841.9     0.1       0  4965.0    0.05       0
  4997.1    0.04       0  5003.1    0.05       0  5112.3    0.16       0
  5348.7    0.05       0  5451.5     0.1       0  5514.6    0.05       0
Bank Sta=4997.1,5003.1
Exp/Cntr=0.3,0.1

Type RM Length L Ch R = 1,172,0,0,0
BEGIN DESCRIPTION:
UNT 1064 IN HEWA 1.0
END DESCRIPTION:
XS GIS Cut Line= 4
      2707225.76     10044308.40      2708215.33     10043896.08
      2708432.35     10043666.05      2708727.50     10042624.33
#Sta/Elev= 30
  3801.7 1723.62  4054.7 1723.48  4398.3 1722.18  4573.8 1722.21  4763.1 1719.05
  4810.8 1714.53  4816.2 1715.42  4840.0 1709.57  4913.0 1713.07  4934.1 1709.54
  4941.4 1703.66  4955.0 1696.39  4976.5 1690.29  4995.0 1679.24  4997.7 1678.74
  5001.0 1679.24  5004.9 1680.15  5012.2 1687.36  5026.3 1695.12  5040.5 1696.29
  5075.7 1694.15  5091.0 1699.16  5132.3 1706.69  5195.8 1712.83  5229.8 1718.28
  5252.0 1719.36  5441.8 1721.02  5567.4 1719.53  6257.8 1721.55  6272.7 1721.46
#Mann=10,-1,0
  3801.7     0.1       0  4054.7    0.05       0  4398.3     0.1       0
  4955.0    0.05       0  4995.0    0.04       0  5001.0    0.05       0
  5091.0    0.16       0  5252.0     0.1       0  5567.4    0.05       0
  6257.8     0.1       0
Bank Sta=4995,5001
Exp/Cntr=0.3,0.1

Chan Stop Cuts=-1