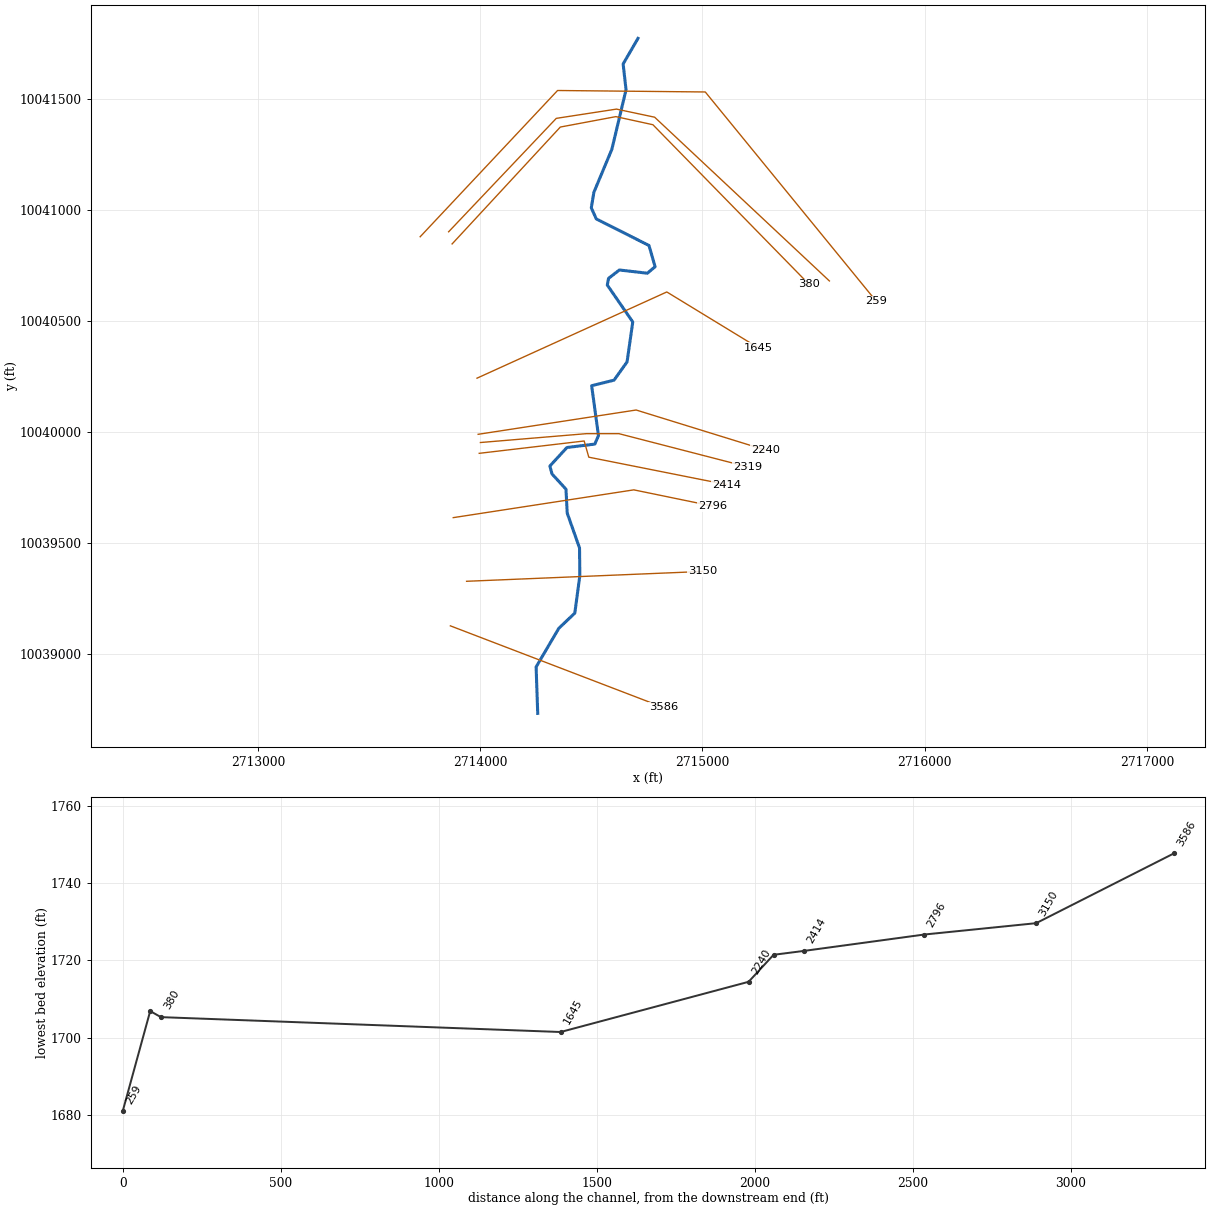
--- UNT 1065 IN HEWA.prj (project) ---

Proj Title=UNT 1065 IN HEWA Base Level Engineering
Current Plan=p01
Default Exp/Contr=0.3,0.1
English Units
Geom File=g01
Flow File=f01
Plan File=p01
BEGIN DESCRIPTION:
UNT 1065 IN HEWA
END DESCRIPTION:

--- UNT 1065 IN HEWA.p01 (plan) ---

Plan Title=Multiple Run
Short Identifier=Multiple
Geom File=g01
Flow File=f01
Subcritical Flow
K Sum by GR= 0
Std Step Tol= 0.01
Critical Tol= 0.01
Num of Std Step Trials= 20
Max Error Tol= 0.3
Flow Tol Ratio= 0.001
Split Flow NTrial= 30
Split Flow Tol= 0.02
Split Flow Ratio= 0.02
Log Output Level= 0
Friction Slope Method= 1
Unsteady Friction Slope Method= 2
Unsteady Bridges Friction Slope Method= 1
Parabolic Critical Depth
Global Vel Dist=  1 , 1 , 1
Global Log Level= 0
CheckData=True
Encroach Param= -1, 0, 0, 0
BEGIN DESCRIPTION:
Multiple Run
END DESCRIPTION:

--- UNT 1065 IN HEWA.f01 (steady flow) ---

Flow Title=Multiple
Number of Profiles=7
Profile Names=10-year,25-year,50-year,1pct_min,100-year,1pct_plu,500-year
River Rch & RM= UNT 1065 IN HEWA,Reach-1,3586
     930    1346    1706    1581    2139    2892    3351
Boundary for River Rch & Prof#=UNT 1065 IN HEWA,Reach-1,1
Up Type=0
Dn Type=3
Dn Slope=0.005
Boundary for River Rch & Prof#=UNT 1065 IN HEWA,Reach-1,2
Up Type=0
Dn Type=3
Dn Slope=0.005
Boundary for River Rch & Prof#=UNT 1065 IN HEWA,Reach-1,3
Up Type=0
Dn Type=3
Dn Slope=0.005
Boundary for River Rch & Prof#=UNT 1065 IN HEWA,Reach-1,4
Up Type=0
Dn Type=3
Dn Slope=0.005
Boundary for River Rch & Prof#=UNT 1065 IN HEWA,Reach-1,5
Up Type=0
Dn Type=3
Dn Slope=0.005
Boundary for River Rch & Prof#=UNT 1065 IN HEWA,Reach-1,6
Up Type=0
Dn Type=3
Dn Slope=0.005
Boundary for River Rch & Prof#=UNT 1065 IN HEWA,Reach-1,7
Up Type=0
Dn Type=3
Dn Slope=0.005

--- UNT 1065 IN HEWA.g01 (geometry) ---

Geom Title=Existing Conditions

River Reach=UNT 1065 IN HEWA,Reach-1
Reach XY= 30
      2714258.47     10038733.73      2714251.22     10038942.59
      2714353.38     10039116.49      2714425.36     10039184.97
      2714447.99     10039353.19      2714446.65     10039478.14
      2714391.22     10039634.88      2714385.62     10039742.64
      2714322.82     10039811.13      2714313.08     10039846.78
      2714389.89     10039930.18      2714515.37     10039945.62
      2714531.86     10039983.54      2714501.16     10040208.33
      2714601.85     10040233.25      2714660.59     10040315.56
      2714686.20     10040495.37      2714571.52     10040661.29
      2714577.15     10040691.30      2714625.92     10040729.13
      2714751.65     10040714.59      2714786.71     10040743.83
      2714759.25     10040839.35      2714522.13     10040958.91
      2714499.55     10041008.74      2714511.14     10041078.58
      2714592.16     10041272.28      2714655.92     10041540.10
      2714642.90     10041656.37      2714709.81     10041771.63

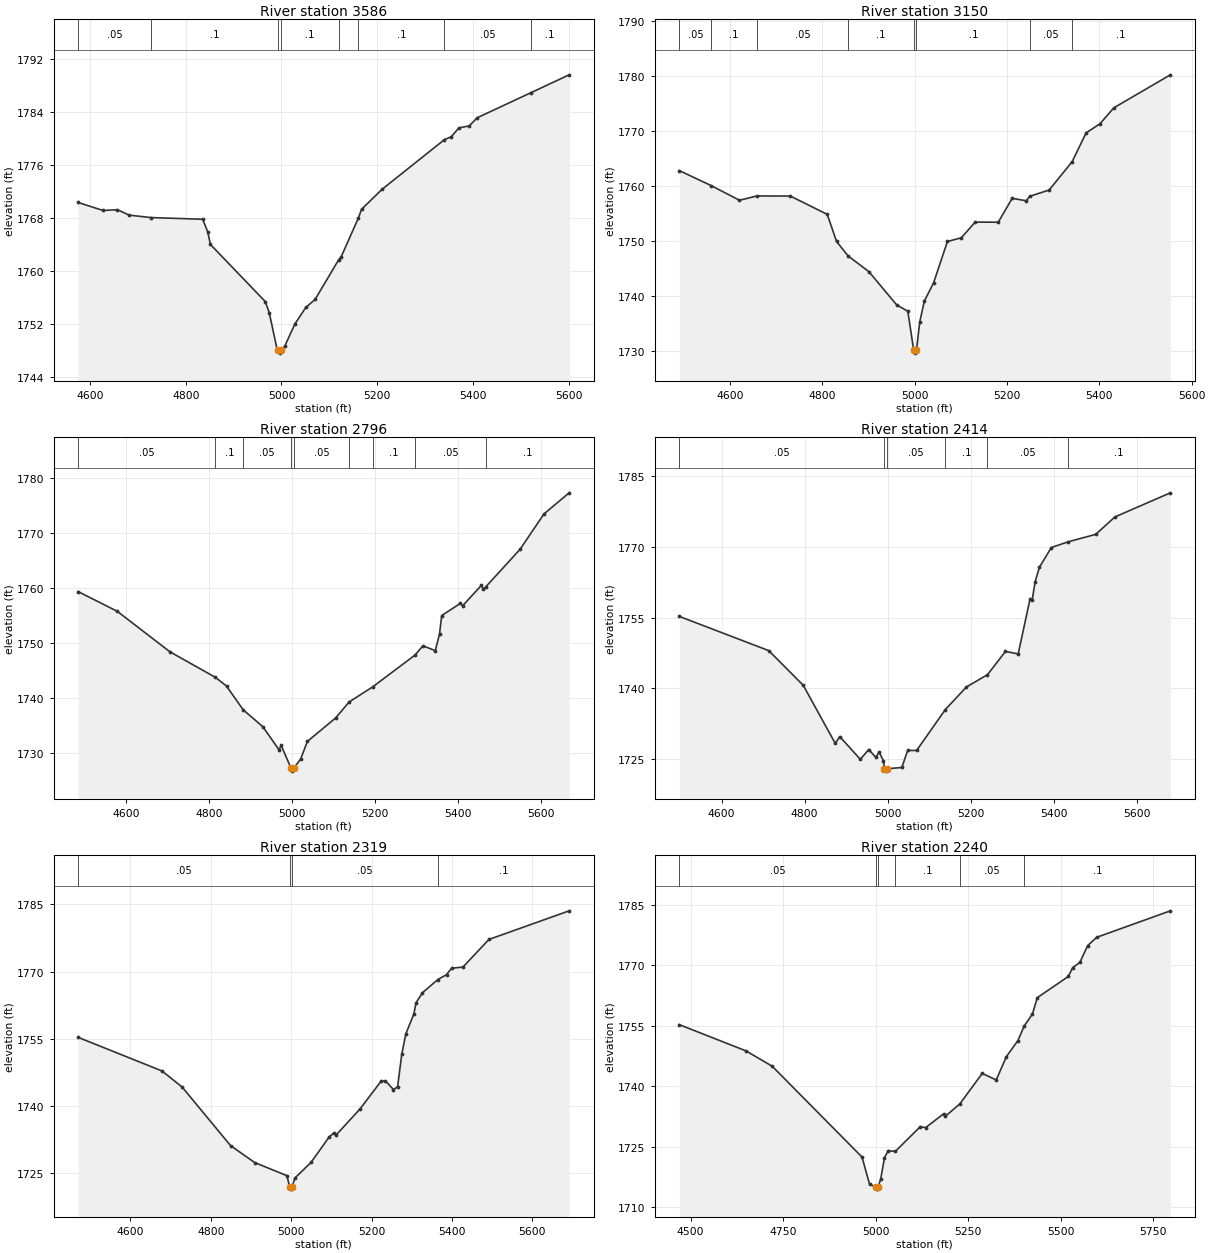
Type RM Length L Ch R = 1,3586,436,436,436
BEGIN DESCRIPTION:
UNT 1065 IN HEWA 7.0
END DESCRIPTION:
XS GIS Cut Line= 2
      2713865.37     10039127.66      2714823.64     10038760.49
#Sta/Elev= 30
  4575.0 1770.35  4627.2 1769.14  4657.2 1769.26  4681.9 1768.44  4728.0 1768.07
  4835.3 1767.82  4846.0 1765.91  4851.4 1764.03  4966.2 1755.41  4974.5 1753.73
  4990.9 1748.19  4993.3 1748.14  4996.0 1747.64  4999.3 1748.14  5006.7 1748.66
  5028.1 1752.04  5051.0 1754.54  5070.3 1755.73  5119.5 1761.71  5124.5 1762.11
  5160.7 1768.00  5167.3 1769.31  5209.8 1772.31  5340.5 1779.82  5354.6 1780.25
  5370.8 1781.59  5392.2 1781.89  5409.4 1783.13  5522.0 1786.92  5601.2 1789.59
#Mann=8,-1,0
  4575.0    0.05       0  4728.0     0.1       0  4993.3    0.07       0
  4999.3     0.1       0  5119.5    0.16       0  5160.7     0.1       0
  5340.5    0.05       0  5522.0     0.1       0
Bank Sta=4993.3,4999.3
Exp/Cntr=0.3,0.1

Type RM Length L Ch R = 1,3150,354,354,354
BEGIN DESCRIPTION:
UNT 1065 IN HEWA 6.0
END DESCRIPTION:
XS GIS Cut Line= 2
      2713938.32     10039328.16      2715000.80     10039372.43
#Sta/Elev= 30
  4490.5 1762.79  4560.1 1760.03  4620.8 1757.40  4658.7 1758.18  4730.9 1758.16
  4810.9 1754.83  4830.9 1749.93  4855.8 1747.30  4901.0 1744.43  4961.1 1738.40
  4985.4 1737.23  4998.1 1730.13  5000.8 1729.63  5004.1 1730.13  5011.1 1735.29
  5021.1 1739.09  5041.1 1742.39  5071.1 1749.91  5101.2 1750.58  5131.2 1753.43
  5181.2 1753.41  5211.3 1757.75  5241.3 1757.31  5250.1 1758.14  5291.3 1759.25
  5341.1 1764.39  5371.4 1769.63  5401.4 1771.29  5431.5 1774.19  5553.9 1780.18
#Mann=8,-1,0
  4490.5    0.05       0  4560.1     0.1       0  4658.7    0.05       0
  4855.8     0.1       0  4998.1    0.07       0  5004.1     0.1       0
  5250.1    0.05       0  5341.1     0.1       0
Bank Sta=4998.1,5004.1
Exp/Cntr=0.3,0.1

Type RM Length L Ch R = 1,2796,382,382,382
BEGIN DESCRIPTION:
UNT 1065 IN HEWA 5.0
END DESCRIPTION:
XS GIS Cut Line= 3
      2713878.40     10039614.61      2714690.93     10039739.62
      2715044.33     10039666.86
#Sta/Elev= 30
  4484.2 1759.38  4578.7 1755.78  4705.2 1748.43  4815.1 1743.76  4841.8 1742.18
  4881.6 1737.88  4929.4 1734.77  4968.3 1730.57  4973.3 1731.40  4997.3 1727.20
  5000.0 1726.70  5003.3 1727.20  5020.5 1728.93  5036.5 1732.11  5104.8 1736.39
  5137.1 1739.29  5193.4 1742.01  5296.0 1747.83  5314.9 1749.51  5344.6 1748.63
  5354.8 1751.63  5360.1 1755.02  5405.3 1757.24  5410.4 1756.79  5455.6 1760.50
  5460.7 1759.77  5466.5 1760.26  5548.8 1767.07  5606.6 1773.52  5667.1 1777.35
#Mann=9,-1,0
  4484.2    0.05       0  4815.1     0.1       0  4881.6    0.05       0
  4997.3    0.07       0  5003.3    0.05       0  5137.1    0.05       0
  5193.4     0.1       0  5296.0    0.05       0  5466.5     0.1       0
Bank Sta=4997.3,5003.3
Exp/Cntr=0.3,0.1

Type RM Length L Ch R = 1,2414,95,95,95
BEGIN DESCRIPTION:
Mapping XS 74e9145a
END DESCRIPTION:
XS GIS Cut Line= 4
      2713995.30     10039904.03      2714467.49     10039959.59
      2714488.32     10039886.67      2715108.10     10039763.41
#Sta/Elev= 30
  4498.1 1755.25  4713.6 1748.00  4796.7 1740.65  4873.8 1728.34  4884.8 1729.77
  4934.3 1724.96  4954.4 1727.04  4971.5 1725.40  4979.6 1726.47  4990.0 1724.65
  4992.3 1722.96  4995.0 1722.46  4998.3 1722.96  5034.3 1723.23  5048.3 1726.85
  5069.9 1726.84  5139.1 1735.51  5189.9 1740.30  5240.6 1742.89  5284.0 1747.83
  5314.6 1747.30  5343.3 1759.00  5348.4 1758.74  5355.4 1762.59  5365.6 1765.64
  5394.4 1769.84  5434.3 1771.04  5501.7 1772.65  5547.7 1776.33  5681.3 1781.44
#Mann=6,-1,0
  4498.1    0.05       0  4992.3    0.04       0  4998.3    0.05       0
  5139.1     0.1       0  5240.6    0.05       0  5434.3     0.1       0
Bank Sta=4992.3,4998.3
Exp/Cntr=0.3,0.1

Type RM Length L Ch R = 1,2319,79,79,79
BEGIN DESCRIPTION:
Mapping XS 3ffe027b
END DESCRIPTION:
XS GIS Cut Line= 4
      2714000.49     10039952.64      2714477.90     10039992.57
      2714623.74     10039992.57      2715201.85     10039843.27
#Sta/Elev= 30
  4469.6 1755.34  4678.3 1747.84  4728.5 1744.25  4848.9 1731.19  4909.1 1727.40
  4989.2 1724.47  4996.2 1721.97  4999.0 1721.47  5002.2 1721.97  5009.2 1723.95
  5049.2 1727.42  5094.4 1733.11  5107.2 1734.08  5112.4 1733.62  5171.7 1739.41
  5223.3 1745.52  5234.3 1745.65  5254.3 1743.68  5264.7 1744.30  5275.0 1751.55
  5285.3 1756.14  5305.3 1760.58  5310.5 1763.03  5326.6 1765.30  5364.9 1768.24
  5386.6 1769.34  5398.9 1770.76  5427.3 1771.02  5491.9 1777.18  5691.6 1783.57
#Mann=4,-1,0
  4469.6    0.05       0  4996.2    0.04       0  5002.2    0.05       0
  5364.9     0.1       0
Bank Sta=4996.2,5002.2
Exp/Cntr=0.3,0.1

Type RM Length L Ch R = 1,2240,595,595,595
BEGIN DESCRIPTION:
UNT 1065 IN HEWA 4.0
END DESCRIPTION:
XS GIS Cut Line= 3
      2713990.37     10039989.61      2714701.35     10040098.99
      2715282.04     10039919.32
#Sta/Elev= 30
  4469.3 1755.27  4649.5 1748.77  4720.3 1744.97  4963.1 1722.45  4983.4 1715.74
  5000.6 1715.00  5003.4 1714.50  5006.6 1715.00  5013.7 1717.06  5023.8 1722.29
  5034.0 1724.05  5052.9 1723.83  5120.6 1729.99  5135.1 1729.75  5183.8 1733.19
  5187.8 1732.52  5227.3 1735.61  5288.0 1743.18  5325.9 1741.56  5353.1 1747.32
  5384.5 1751.33  5401.6 1754.97  5423.7 1757.90  5436.9 1761.97  5520.6 1767.21
  5532.1 1769.36  5552.0 1770.73  5572.9 1774.86  5597.3 1776.92  5796.5 1783.49
#Mann=6,-1,0
  4469.3    0.05       0  5000.6   0.035       0  5006.6    0.05       0
  5052.9     0.1       0  5227.3    0.05       0  5401.6     0.1       0
Bank Sta=5000.6,5006.6
Exp/Cntr=0.3,0.1

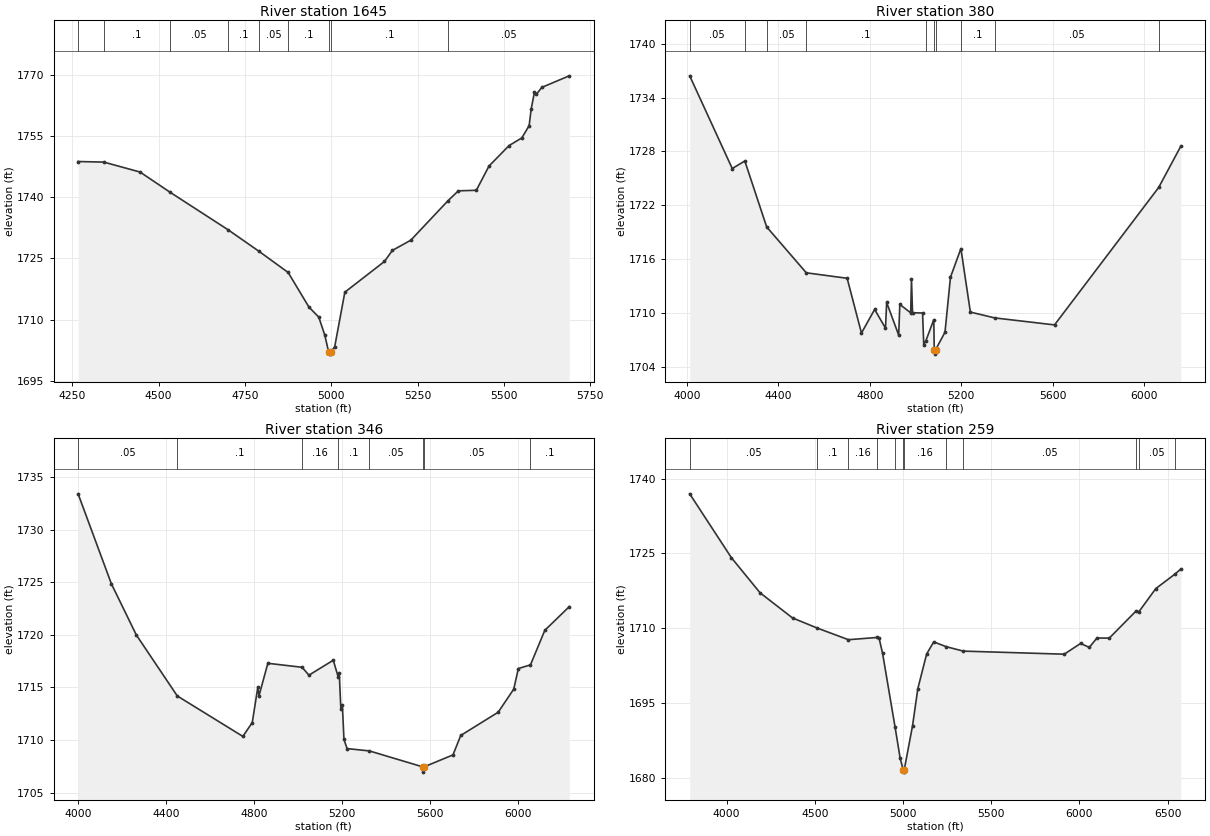
Type RM Length L Ch R = 1,1645,1265,1265,1265
BEGIN DESCRIPTION:
UNT 1065 IN HEWA 3.0
END DESCRIPTION:
XS GIS Cut Line= 3
      2713985.20     10040242.22      2714839.37     10040630.24
      2715252.57     10040378.16
#Sta/Elev= 30
  4266.8 1748.71  4341.2 1748.57  4446.1 1746.14  4533.6 1741.16  4700.5 1732.03
  4789.8 1726.77  4875.0 1721.54  4935.1 1713.08  4963.7 1710.60  4981.3 1706.15
  4992.3 1702.04  4995.0 1701.54  4998.3 1702.04  5009.8 1703.34  5039.2 1716.71
  5153.8 1724.23  5176.8 1726.94  5230.1 1729.44  5338.2 1739.14  5367.9 1741.53
  5419.9 1741.67  5456.6 1747.60  5514.7 1752.62  5551.5 1754.48  5572.8 1757.49
  5578.8 1761.58  5588.3 1765.74  5594.1 1765.22  5609.6 1766.87  5689.0 1769.70
#Mann=9,-1,0
  4266.8    0.05       0  4341.2     0.1       0  4533.6    0.05       0
  4700.5     0.1       0  4789.8    0.05       0  4875.0     0.1       0
  4992.3    0.07       0  4998.3     0.1       0  5338.2    0.05       0
Bank Sta=4992.3,4998.3
Exp/Cntr=0.3,0.1

Type RM Length L Ch R = 1,380,34,34,34
BEGIN DESCRIPTION:
Mapping XS 6a702405
END DESCRIPTION:
XS GIS Cut Line= 5
      2713873.23     10040846.39      2714360.20     10041372.43
      2714610.20     10041419.30      2714776.87     10041382.85
      2715480.01     10040664.09
#Sta/Elev= 30
  4012.3 1736.42  4198.3 1726.08  4253.3 1726.92  4348.8 1719.57  4522.1 1714.45
  4700.7 1713.84  4763.2 1707.73  4820.8 1710.36  4868.3 1708.28  4873.4 1711.14
  4926.0 1707.50  4931.0 1710.92  4978.5 1709.99  4981.9 1713.75  4986.5 1709.99
  5030.4 1709.97  5035.5 1706.45  5044.7 1706.86  5079.4 1709.22  5081.5 1705.88
  5084.2 1705.38  5087.5 1705.88  5128.4 1707.82  5152.4 1713.96  5198.0 1717.15
  5239.4 1710.07  5345.7 1709.42  5607.2 1708.64  6062.7 1723.97  6159.6 1728.58
#Mann=10,-1,0
  4012.3    0.05       0  4253.3     0.1       0  4348.8    0.05       0
  4522.1     0.1       0  5044.7    0.16       0  5081.5    0.07       0
  5087.5    0.16       0  5198.0     0.1       0  5345.7    0.05       0
  6062.7     0.1       0
Bank Sta=5081.5,5087.5
Exp/Cntr=0.3,0.1

Type RM Length L Ch R = 1,346,87,87,87
BEGIN DESCRIPTION:
UNT 1065 IN HEWA 2.0
END DESCRIPTION:
XS GIS Cut Line= 5
      2713857.60     10040901.07      2714341.98     10041411.49
      2714612.81     10041453.16      2714784.68     10041416.70
      2715571.15     10040679.72
#Sta/Elev= 30
  4000.5 1733.43  4151.6 1724.87  4264.9 1720.00  4451.1 1714.19  4749.0 1710.34
  4791.7 1711.66  4817.3 1715.07  4822.3 1714.21  4862.5 1717.30  5017.9 1716.92
  5049.1 1716.17  5159.7 1717.59  5182.5 1715.97  5186.8 1716.39  5194.1 1712.97
  5200.9 1713.36  5208.2 1710.05  5222.4 1709.18  5323.5 1708.96  5566.2 1707.44
  5568.9 1706.94  5572.2 1707.44  5703.5 1708.58  5738.7 1710.43  5908.7 1712.64
  5979.5 1714.84  6000.5 1716.80  6055.5 1717.15  6120.7 1720.44  6231.7 1722.69
#Mann=8,-1,0
  4000.5    0.05       0  4451.1     0.1       0  5017.9    0.16       0
  5182.5     0.1       0  5323.5    0.05       0  5566.2    0.07       0
  5572.2    0.05       0  6055.5     0.1       0
Bank Sta=5566.2,5572.2
Exp/Cntr=0.3,0.1

Type RM Length L Ch R = 1,259,0,0,0
BEGIN DESCRIPTION:
UNT 1065 IN HEWA 1.0
END DESCRIPTION:
XS GIS Cut Line= 4
      2713729.57     10040878.77      2714347.80     10041536.89
      2715012.54     10041530.25      2715782.57     10040587.62
#Sta/Elev= 30
  3790.4 1736.97  4026.7 1724.15  4189.3 1717.10  4373.5 1712.05  4513.4 1710.02
  4690.4 1707.68  4853.9 1708.13  4864.0 1708.02  4884.0 1704.95  4954.9 1690.13
  4984.0 1683.83  5001.0 1681.59  5003.8 1681.09  5007.0 1681.59  5054.0 1690.41
  5084.0 1697.86  5134.0 1704.82  5174.1 1707.24  5244.0 1706.29  5341.3 1705.39
  5914.1 1704.77  6006.7 1706.93  6056.2 1706.13  6099.3 1708.01  6169.7 1708.01
  6320.9 1713.43  6338.3 1713.34  6433.1 1717.94  6544.0 1720.91  6575.3 1721.89
#Mann=12,-1,0
  3790.4    0.05       0  4513.4     0.1       0  4690.4    0.16       0
  4853.9     0.1       0  4954.9    0.16       0  5001.0    0.07       0
  5007.0    0.16       0  5244.0     0.1       0  5341.3    0.05       0
  6320.9     0.1       0  6338.3    0.05       0  6544.0     0.1       0
Bank Sta=5001,5007
Exp/Cntr=0.3,0.1

Chan Stop Cuts=-1