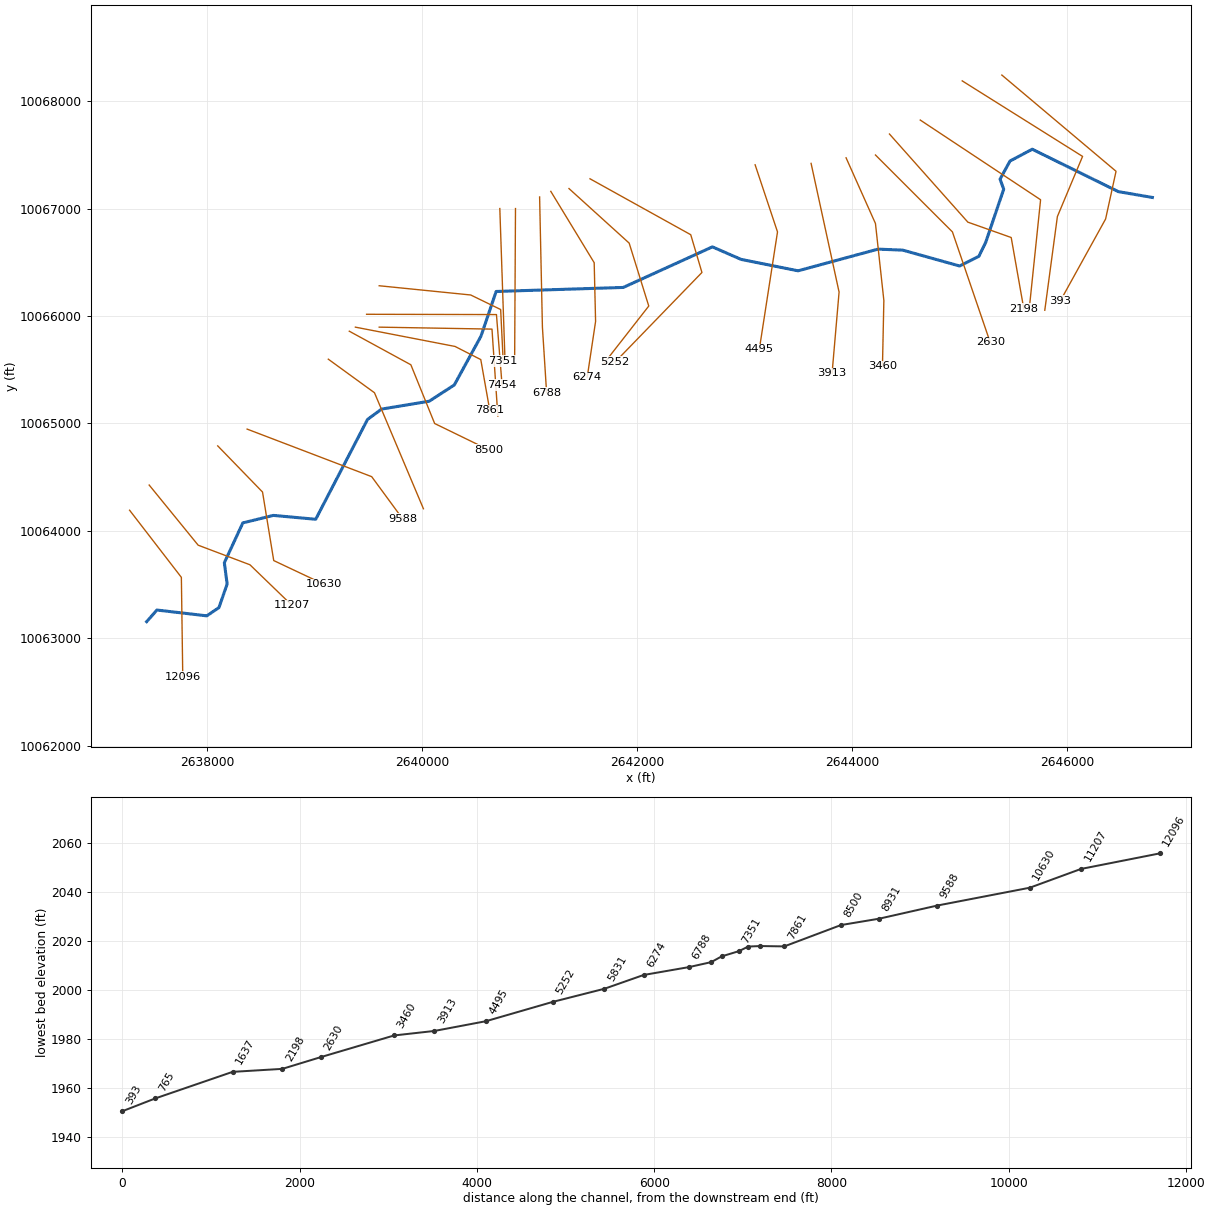
--- UNT 1066 IN HEWA.prj (project) ---

Proj Title=UNT 1066 IN HEWA Base Level Engineering
Current Plan=p01
Default Exp/Contr=0.3,0.1
English Units
Geom File=g01
Flow File=f01
Plan File=p01
BEGIN DESCRIPTION:
UNT 1066 IN HEWA
END DESCRIPTION:

--- UNT 1066 IN HEWA.p01 (plan) ---

Plan Title=Multiple Run
Short Identifier=Multiple
Geom File=g01
Flow File=f01
Subcritical Flow
K Sum by GR= 0
Std Step Tol= 0.01
Critical Tol= 0.01
Num of Std Step Trials= 20
Max Error Tol= 0.3
Flow Tol Ratio= 0.001
Split Flow NTrial= 30
Split Flow Tol= 0.02
Split Flow Ratio= 0.02
Log Output Level= 0
Friction Slope Method= 1
Unsteady Friction Slope Method= 2
Unsteady Bridges Friction Slope Method= 1
Parabolic Critical Depth
Global Vel Dist=  1 , 1 , 1
Global Log Level= 0
CheckData=True
Encroach Param= -1, 0, 0, 0
BEGIN DESCRIPTION:
Multiple Run
END DESCRIPTION:

--- UNT 1066 IN HEWA.f01 (steady flow) ---

Flow Title=Multiple
Number of Profiles=7
Profile Names=10-year,25-year,50-year,1pct_min,100-year,1pct_plu,500-year
River Rch & RM= UNT 1066 IN HEWA,Reach-1,12096
    1013    1469    1861    1719    2325    3144    3628
River Rch & RM= UNT 1066 IN HEWA,Reach-1,11207
    1505    2223    2850    2659    3596    4864    5732
River Rch & RM= UNT 1066 IN HEWA,Reach-1,4495
    2127    3197    4146    3909    5287    7150    8605
Boundary for River Rch & Prof#=UNT 1066 IN HEWA,Reach-1,1
Up Type=0
Dn Type=3
Dn Slope=0.005
Boundary for River Rch & Prof#=UNT 1066 IN HEWA,Reach-1,2
Up Type=0
Dn Type=3
Dn Slope=0.005
Boundary for River Rch & Prof#=UNT 1066 IN HEWA,Reach-1,3
Up Type=0
Dn Type=3
Dn Slope=0.005
Boundary for River Rch & Prof#=UNT 1066 IN HEWA,Reach-1,4
Up Type=0
Dn Type=3
Dn Slope=0.005
Boundary for River Rch & Prof#=UNT 1066 IN HEWA,Reach-1,5
Up Type=0
Dn Type=3
Dn Slope=0.005
Boundary for River Rch & Prof#=UNT 1066 IN HEWA,Reach-1,6
Up Type=0
Dn Type=3
Dn Slope=0.005
Boundary for River Rch & Prof#=UNT 1066 IN HEWA,Reach-1,7
Up Type=0
Dn Type=3
Dn Slope=0.005

--- UNT 1066 IN HEWA.g01 (geometry) ---

Geom Title=Existing Conditions

River Reach=UNT 1066 IN HEWA,Reach-1
Reach XY= 30
      2637438.47     10063153.73      2637533.98     10063262.10
      2637997.78     10063208.11      2638111.11     10063284.57
      2638187.43     10063504.27      2638161.39     10063702.48
      2638333.61     10064073.55      2638616.88     10064143.20
      2639011.49     10064107.24      2639493.60     10065036.60
      2639624.41     10065132.99      2640067.49     10065206.37
      2640300.84     10065357.31      2640549.14     10065811.60
      2640690.46     10066228.22      2641872.69     10066265.61
      2642702.72     10066643.39      2642969.74     10066526.81
      2643499.65     10066420.51      2644243.39     10066622.32
      2644473.23     10066613.16      2645002.77     10066465.41
      2645182.00     10066555.58      2645245.34     10066685.02
      2645413.11     10067180.59      2645379.18     10067273.73
      2645471.71     10067442.51      2645678.66     10067552.60
      2646480.09     10067157.65      2646796.72     10067103.46

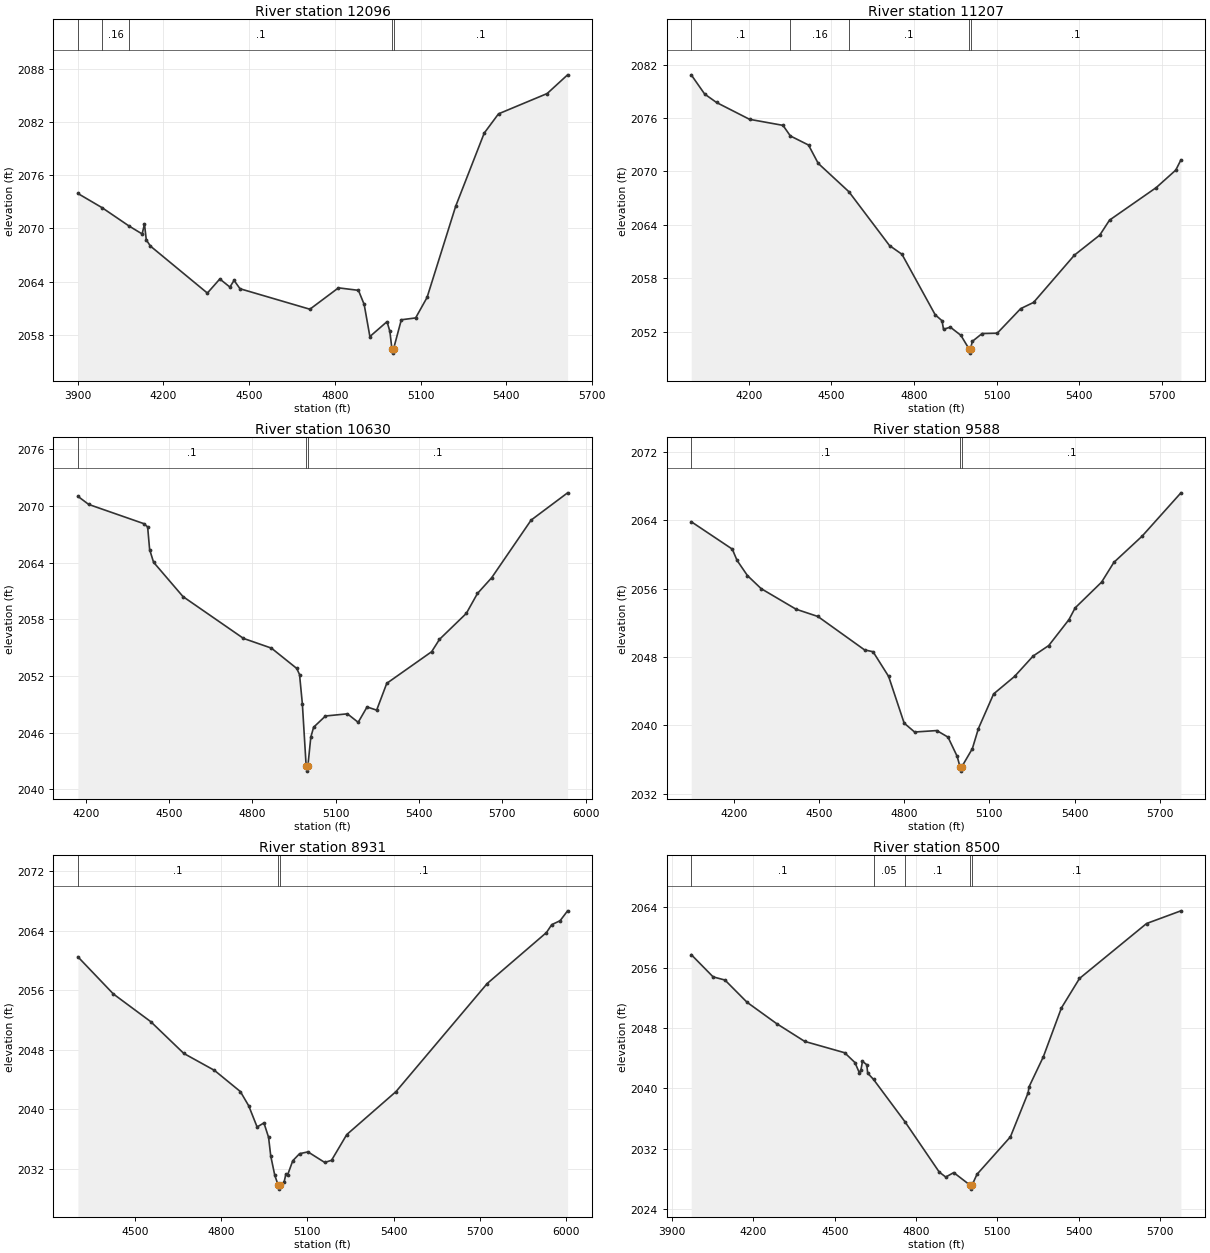
Type RM Length L Ch R = 1,12096,889,889,889
BEGIN DESCRIPTION:
UNT 1066 IN HEWA 27.0
END DESCRIPTION:
XS GIS Cut Line= 3
      2637279.77     10064191.42      2637761.52     10063566.45
      2637774.54     10062641.94
#Sta/Elev= 30
  3900.7 2073.94  3985.3 2072.34  4081.2 2070.24  4125.5 2069.38  4133.7 2070.50
  4140.0 2068.71  4154.5 2068.01  4353.8 2062.71  4397.3 2064.30  4432.6 2063.39
  4447.2 2064.14  4468.0 2063.20  4712.5 2060.89  4812.5 2063.30  4882.5 2063.02
  4902.5 2061.43  4922.5 2057.81  4982.5 2059.49  4992.5 2058.38  4999.5 2056.44
  5002.3 2055.94  5005.5 2056.44  5032.5 2059.70  5082.6 2059.91  5122.6 2062.22
  5222.6 2072.49  5322.6 2080.75  5372.6 2082.92  5542.9 2085.21  5614.4 2087.32
#Mann=5,-1,0
  3900.7     0.1       0  3985.3    0.16       0  4081.2     0.1       0
  4999.5    0.07       0  5005.5     0.1       0
Bank Sta=4999.5,5005.5
Exp/Cntr=0.3,0.1

Type RM Length L Ch R = 1,11207,577,577,577
BEGIN DESCRIPTION:
UNT 1066 IN HEWA 26.0
END DESCRIPTION:
XS GIS Cut Line= 4
      2637462.02     10064425.85      2637917.77     10063865.93
      2638399.54     10063683.64      2638788.76     10063307.39
#Sta/Elev= 30
  3990.7 2080.86  4039.5 2078.70  4082.6 2077.75  4202.5 2075.86  4323.9 2075.18
  4350.7 2073.99  4416.6 2072.97  4451.8 2070.91  4563.3 2067.72  4710.8 2061.67
  4756.0 2060.69  4876.7 2053.89  4901.5 2053.22  4906.9 2052.26  4931.7 2052.50
  4970.0 2051.58  4999.1 2050.08  5001.8 2049.58  5005.1 2050.08  5011.5 2050.90
  5047.0 2051.78  5102.0 2051.82  5187.1 2054.58  5234.0 2055.28  5382.5 2060.60
  5474.5 2062.85  5509.8 2064.53  5679.6 2068.19  5750.3 2070.15  5769.1 2071.30
#Mann=5,-1,0
  3990.7     0.1       0  4350.7    0.16       0  4563.3     0.1       0
  4999.1    0.07       0  5005.1     0.1       0
Bank Sta=4999.1,5005.1
Exp/Cntr=0.3,0.1

Type RM Length L Ch R = 1,10630,1042,1042,1042
BEGIN DESCRIPTION:
UNT 1066 IN HEWA 24.0
END DESCRIPTION:
XS GIS Cut Line= 4
      2638100.06     10064790.41      2638516.73     10064360.73
      2638620.89     10063722.70      2639089.65     10063501.35
#Sta/Elev= 30
  4172.0 2071.02  4210.9 2070.16  4408.9 2068.13  4423.1 2067.78  4430.3 2065.38
  4444.4 2064.04  4550.4 2060.40  4768.2 2055.97  4868.8 2054.94  4960.0 2052.79
  4970.1 2052.14  4980.3 2049.03  4994.0 2042.41  4996.8 2041.91  5000.0 2042.41
  5010.7 2045.51  5020.8 2046.56  5063.5 2047.75  5142.4 2047.98  5181.3 2047.08
  5213.3 2048.71  5247.8 2048.37  5284.2 2051.21  5445.8 2054.56  5474.1 2055.87
  5570.7 2058.62  5610.8 2060.73  5661.8 2062.39  5804.0 2068.50  5935.4 2071.39
#Mann=3,-1,0
  4172.0     0.1       0  4994.0    0.07       0  5000.0     0.1       0
Bank Sta=4994,5000
Exp/Cntr=0.3,0.1

Type RM Length L Ch R = 1,9588,657,657,657
BEGIN DESCRIPTION:
UNT 1066 IN HEWA 22.0
END DESCRIPTION:
XS GIS Cut Line= 3
      2638373.50     10064946.66      2639532.35     10064503.95
      2639818.79     10064113.36
#Sta/Elev= 30
  4049.7 2063.84  4194.2 2060.63  4211.1 2059.31  4247.7 2057.53  4296.0 2056.00
  4419.0 2053.59  4495.8 2052.74  4660.1 2048.83  4690.2 2048.61  4745.0 2045.72
  4799.7 2040.25  4836.5 2039.21  4914.7 2039.38  4954.2 2038.61  4986.3 2036.37
  4996.5 2035.13  4999.3 2034.63  5002.5 2035.13  5039.9 2037.26  5061.3 2039.62
  5114.8 2043.67  5188.6 2045.72  5254.1 2048.11  5309.1 2049.34  5380.1 2052.37
  5402.1 2053.75  5495.1 2056.76  5538.5 2059.08  5637.7 2062.14  5774.6 2067.22
#Mann=3,-1,0
  4049.7     0.1       0  4996.5    0.07       0  5002.5     0.1       0
Bank Sta=4996.5,5002.5
Exp/Cntr=0.3,0.1

Type RM Length L Ch R = 1,8931,431,431,431
BEGIN DESCRIPTION:
UNT 1066 IN HEWA 20.0
END DESCRIPTION:
XS GIS Cut Line= 3
      2639128.69     10065597.71      2639558.39     10065285.20
      2640013.81     10064205.22
#Sta/Elev= 30
  4301.7 2060.51  4425.1 2055.51  4555.0 2051.79  4670.1 2047.51  4776.7 2045.23
  4866.8 2042.38  4895.9 2040.46  4925.1 2037.61  4948.8 2038.16  4964.9 2036.23
  4972.5 2033.71  4986.6 2031.10  4998.7 2029.75  5001.4 2029.25  5004.7 2029.75
  5019.1 2030.22  5025.4 2031.31  5030.8 2031.12  5049.1 2033.07  5072.8 2034.02
  5102.0 2034.26  5160.3 2032.84  5184.0 2033.13  5236.9 2036.59  5408.3 2042.38
  5725.5 2056.92  5931.6 2063.78  5949.9 2064.84  5979.0 2065.37  6005.1 2066.70
#Mann=3,-1,0
  4301.7     0.1       0  4998.7    0.07       0  5004.7     0.1       0
Bank Sta=4998.7,5004.7
Exp/Cntr=0.3,0.1

Type RM Length L Ch R = 1,8500,639,639,639
BEGIN DESCRIPTION:
UNT 1066 IN HEWA 19.0
END DESCRIPTION:
XS GIS Cut Line= 4
      2639323.98     10065858.14      2639896.93     10065545.62
      2640118.29     10064998.75      2640624.77     10064752.00
#Sta/Elev= 30
  3970.9 2057.71  4051.6 2054.76  4095.3 2054.34  4176.9 2051.39  4286.1 2048.56
  4389.5 2046.21  4536.7 2044.71  4574.7 2043.41  4590.8 2042.06  4596.5 2042.38
  4602.5 2043.57  4618.3 2043.12  4621.6 2042.01  4643.3 2041.17  4759.1 2035.57
  4885.4 2028.91  4909.5 2028.24  4939.0 2028.83  5000.2 2027.14  5002.9 2026.64
  5006.2 2027.14  5024.7 2028.60  5148.1 2033.57  5213.5 2039.42  5216.4 2040.17
  5269.3 2044.16  5336.1 2050.64  5402.8 2054.55  5650.2 2061.83  5776.9 2063.51
#Mann=5,-1,0
  3970.9     0.1       0  4643.3    0.05       0  4759.1     0.1       0
  5000.2    0.07       0  5006.2     0.1       0
Bank Sta=5000.2,5006.2
Exp/Cntr=0.3,0.1

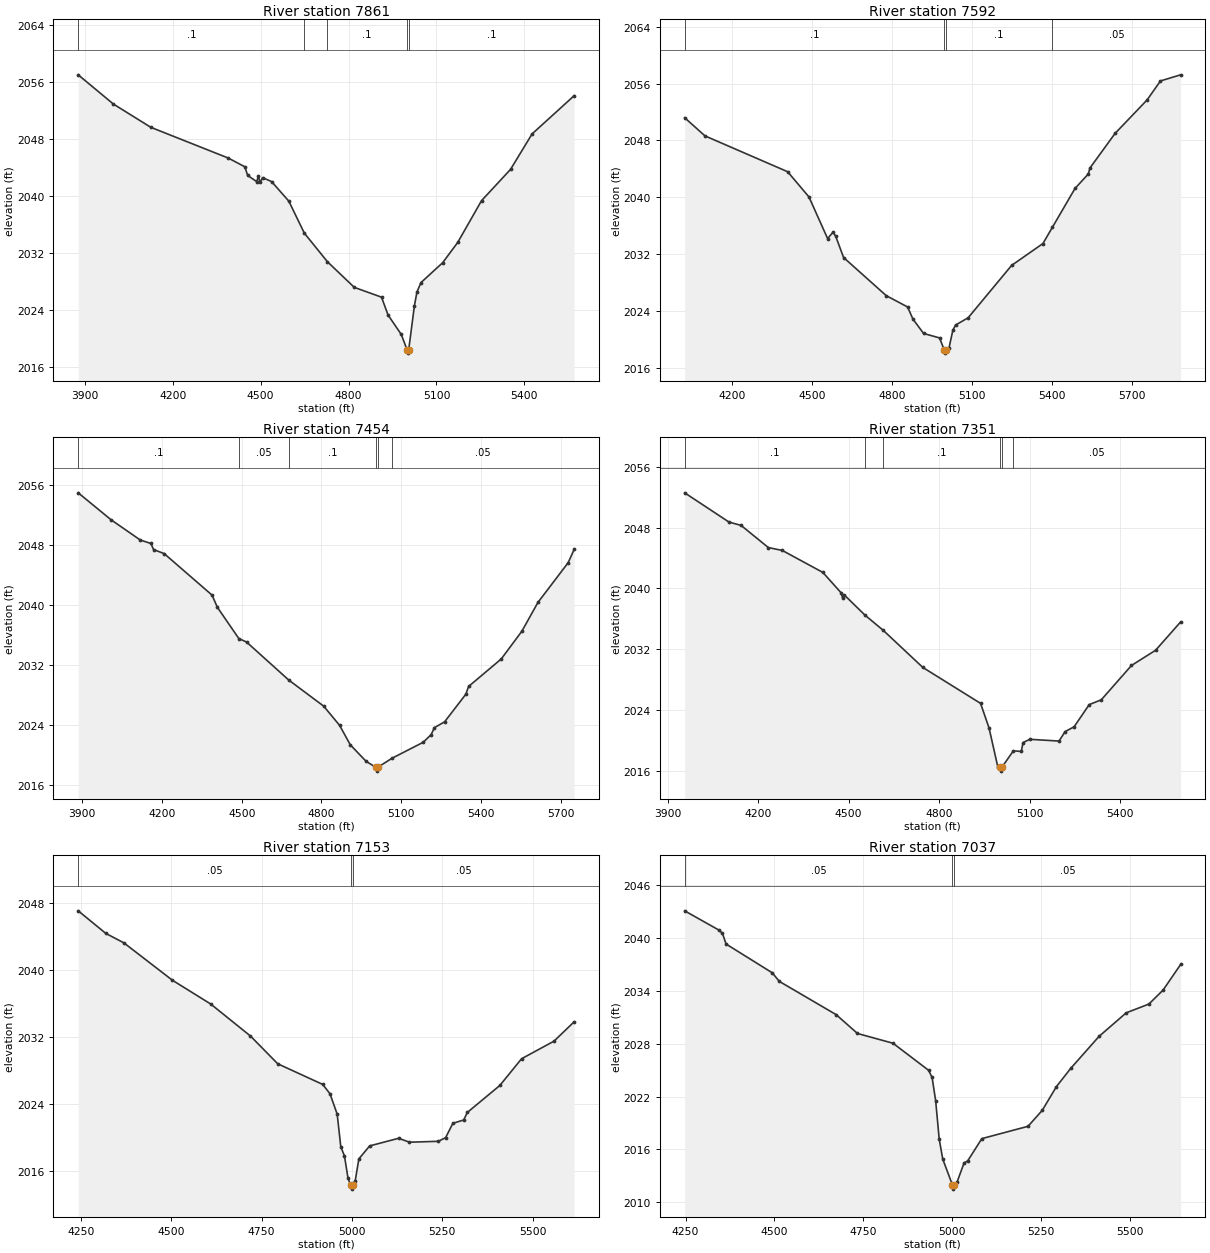
Type RM Length L Ch R = 1,7861,269,269,269
BEGIN DESCRIPTION:
Mapping XS 6688d98a
END DESCRIPTION:
XS GIS Cut Line= 4
      2639380.80     10065895.98      2640307.93     10065716.28
      2640547.51     10065593.89      2640630.85     10065122.52
#Sta/Elev= 30
  3877.6 2057.00  3997.5 2052.90  4125.3 2049.63  4389.2 2045.32  4446.0 2044.09
  4455.8 2042.87  4486.4 2042.01  4492.6 2042.77  4497.7 2041.89  4506.8 2042.56
  4537.3 2042.01  4596.1 2039.27  4649.1 2034.77  4728.0 2030.75  4819.7 2027.15
  4912.4 2025.78  4934.9 2023.26  4979.8 2020.55  4999.3 2018.42  5002.0 2017.92
  5005.3 2018.42  5024.7 2024.58  5033.4 2026.52  5047.2 2027.83  5120.9 2030.61
  5172.4 2033.46  5253.7 2039.33  5352.6 2043.72  5426.3 2048.71  5569.7 2054.07
#Mann=5,-1,0
  3877.6     0.1       0  4649.1    0.05       0  4728.0     0.1       0
  4999.3    0.07       0  5005.3     0.1       0
Bank Sta=4999.3,5005.3
Exp/Cntr=0.3,0.1

Type RM Length L Ch R = 1,7592,138,138,138
BEGIN DESCRIPTION:
UNT 1066 IN HEWA 17.0
END DESCRIPTION:
XS GIS Cut Line= 3
      2639602.21     10065895.97      2640651.68     10065877.74
      2640706.34     10065068.32
#Sta/Elev= 30
  4022.8 2051.20  4099.1 2048.64  4409.1 2043.60  4489.1 2040.05  4559.1 2034.19
  4579.1 2035.07  4589.1 2034.55  4619.1 2031.52  4779.2 2026.15  4859.2 2024.56
  4879.2 2022.86  4919.2 2020.83  4979.2 2020.20  4996.2 2018.56  4999.0 2018.06
  5002.2 2018.56  5014.8 2018.83  5029.2 2021.30  5039.2 2022.01  5086.5 2023.04
  5249.6 2030.41  5367.1 2033.49  5402.7 2035.78  5487.4 2041.24  5537.5 2043.29
  5543.4 2044.12  5637.7 2048.99  5758.0 2053.71  5808.1 2056.38  5883.7 2057.24
#Mann=4,-1,0
  4022.8     0.1       0  4996.2    0.07       0  5002.2     0.1       0
  5402.7    0.05       0
Bank Sta=4996.2,5002.2
Exp/Cntr=0.3,0.1

Type RM Length L Ch R = 1,7454,103,103,103
BEGIN DESCRIPTION:
Mapping XS 6a724205
END DESCRIPTION:
XS GIS Cut Line= 3
      2639485.03     10066015.76      2640693.35     10066013.16
      2640745.36     10065357.84
#Sta/Elev= 30
  3885.0 2054.90  4008.4 2051.32  4118.4 2048.62  4158.4 2048.16  4168.4 2047.35
  4208.4 2046.81  4388.4 2041.29  4408.4 2039.67  4489.2 2035.51  4518.4 2035.04
  4677.1 2029.98  4808.4 2026.51  4868.4 2023.95  4908.4 2021.37  4968.4 2019.15
  5005.4 2018.36  5008.2 2017.86  5011.4 2018.36  5066.3 2019.59  5183.0 2021.70
  5213.1 2022.73  5224.7 2023.64  5263.3 2024.42  5343.1 2028.09  5353.6 2029.13
  5476.5 2032.79  5554.2 2036.49  5614.4 2040.31  5728.3 2045.61  5750.7 2047.37
#Mann=6,-1,0
  3885.0     0.1       0  4489.2    0.05       0  4677.1     0.1       0
  5005.4    0.07       0  5011.4     0.1       0  5066.3    0.05       0
Bank Sta=5005.4,5011.4
Exp/Cntr=0.3,0.1

Type RM Length L Ch R = 1,7351,198,198,198
BEGIN DESCRIPTION:
Mapping XS b6192bf5
END DESCRIPTION:
XS GIS Cut Line= 4
      2639602.22     10066281.39      2640453.76     10066195.45
      2640732.41     10066060.03      2640755.85     10065580.88
#Sta/Elev= 30
  3955.9 2052.56  4102.9 2048.72  4143.1 2048.28  4233.5 2045.37  4279.9 2044.99
  4414.5 2042.10  4474.8 2039.43  4480.1 2038.71  4485.1 2039.16  4553.6 2036.51
  4615.1 2034.48  4746.1 2029.62  4937.6 2024.90  4965.7 2021.67  4994.9 2016.54
  5002.3 2016.50  5005.1 2016.00  5008.3 2016.50  5046.4 2018.67  5072.7 2018.58
  5078.5 2019.75  5101.1 2020.18  5198.0 2019.95  5218.0 2021.19  5248.0 2021.83
  5298.1 2024.74  5338.1 2025.37  5438.3 2029.88  5518.3 2031.88  5601.3 2035.60
#Mann=6,-1,0
  3955.9     0.1       0  4553.6    0.05       0  4615.1     0.1       0
  5002.3    0.07       0  5008.3     0.1       0  5046.4    0.05       0
Bank Sta=5002.3,5008.3
Exp/Cntr=0.3,0.1

Type RM Length L Ch R = 1,7153,116,116,116
BEGIN DESCRIPTION:
Mapping XS 801ba387
END DESCRIPTION:
XS GIS Cut Line= 2
      2640724.60     10067000.11      2640771.46     10065628.21
#Sta/Elev= 30
  4242.5 2047.10  4318.9 2044.40  4368.9 2043.27  4503.2 2038.80  4609.1 2035.96
  4719.2 2032.13  4794.7 2028.81  4919.3 2026.34  4939.3 2025.23  4959.3 2022.79
  4969.3 2018.88  4979.3 2017.81  4989.3 2015.13  4996.3 2014.32  4999.1 2013.82
  5002.3 2014.32  5009.3 2014.84  5019.3 2017.44  5049.3 2018.99  5129.4 2019.90
  5159.4 2019.43  5239.5 2019.54  5259.5 2019.98  5279.5 2021.69  5309.5 2022.09
  5319.5 2022.99  5409.6 2026.22  5469.6 2029.41  5559.6 2031.52  5615.2 2033.83
#Mann=3,-1,0
  4242.5    0.05       0  4996.3    0.04       0  5002.3    0.05       0
Bank Sta=4996.3,5002.3
Exp/Cntr=0.3,0.1

Type RM Length L Ch R = 1,7037,249,249,249
BEGIN DESCRIPTION:
Mapping XS 0746011b
END DESCRIPTION:
XS GIS Cut Line= 2
      2640870.43     10067000.17      2640862.62     10065604.29
#Sta/Elev= 30
  4247.6 2043.12  4344.0 2040.93  4354.0 2040.56  4364.0 2039.35  4494.0 2036.08
  4514.0 2035.10  4674.0 2031.32  4734.0 2029.18  4834.0 2028.07  4934.0 2025.00
  4944.0 2024.19  4954.0 2021.54  4964.0 2017.18  4974.0 2014.90  5001.0 2011.99
  5003.8 2011.49  5007.0 2011.99  5014.0 2012.26  5034.0 2014.47  5044.0 2014.69
  5084.0 2017.23  5214.0 2018.63  5254.0 2020.44  5294.1 2023.15  5334.1 2025.21
  5414.1 2028.86  5490.5 2031.53  5554.1 2032.52  5594.1 2034.11  5643.5 2037.02
#Mann=3,-1,0
  4247.6    0.05       0  5001.0    0.04       0  5007.0    0.05       0
Bank Sta=5001,5007
Exp/Cntr=0.3,0.1

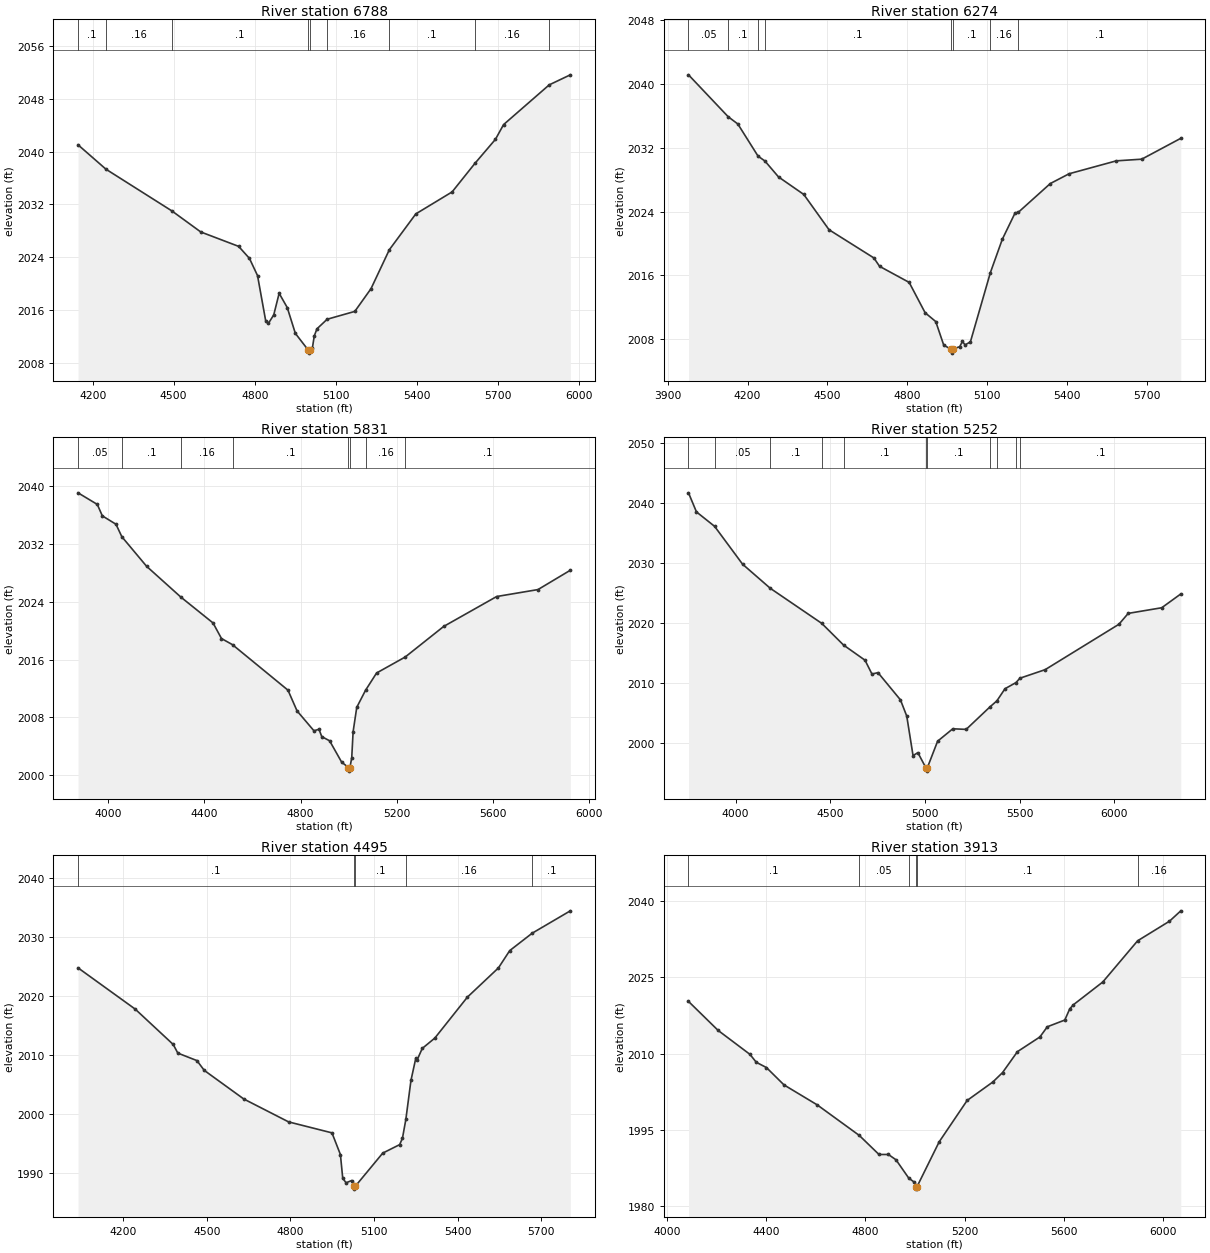
Type RM Length L Ch R = 1,6788,514,514,514
BEGIN DESCRIPTION:
UNT 1066 IN HEWA 15.0
END DESCRIPTION:
XS GIS Cut Line= 3
      2641094.85     10067108.17      2641120.89     10065897.18
      2641159.84     10065286.99
#Sta/Elev= 30
  4145.9 2041.02  4249.5 2037.32  4493.3 2031.01  4600.4 2027.82  4740.5 2025.64
  4780.5 2023.82  4810.5 2021.21  4840.5 2014.41  4850.5 2013.96  4870.5 2015.26
  4890.5 2018.53  4920.5 2016.37  4950.5 2012.46  4997.5 2009.97  5000.3 2009.47
  5003.5 2009.97  5013.7 2010.27  5020.5 2012.07  5030.5 2013.15  5068.2 2014.60
  5170.6 2015.79  5230.6 2019.23  5298.5 2025.13  5396.6 2030.56  5531.0 2033.89
  5615.4 2038.21  5691.3 2041.85  5721.4 2044.08  5890.4 2050.10  5968.6 2051.62
#Mann=9,-1,0
  4145.9     0.1       0  4249.5    0.16       0  4493.3     0.1       0
  4997.5    0.07       0  5003.5     0.1       0  5068.2    0.16       0
  5298.5     0.1       0  5615.4    0.16       0  5890.4     0.1       0
Bank Sta=4997.5,5003.5
Exp/Cntr=0.3,0.1

Type RM Length L Ch R = 1,6274,443,443,443
BEGIN DESCRIPTION:
UNT 1066 IN HEWA 14.0
END DESCRIPTION:
XS GIS Cut Line= 4
      2641199.04     10067160.17      2641602.66     10066496.14
      2641615.68     10065949.27      2641537.58     10065428.60
#Sta/Elev= 30
  3977.9 2041.17  4127.3 2035.90  4163.3 2035.00  4239.4 2030.96  4265.2 2030.35
  4316.3 2028.35  4411.3 2026.15  4506.2 2021.72  4674.8 2018.18  4696.1 2017.13
  4807.4 2015.11  4867.4 2011.30  4907.4 2010.19  4937.4 2007.23  4964.4 2006.73
  4967.2 2006.23  4970.4 2006.73  4997.5 2007.04  5007.5 2007.70  5017.5 2007.27
  5037.5 2007.63  5112.7 2016.34  5157.5 2020.52  5205.7 2023.84  5217.7 2023.91
  5337.9 2027.52  5408.7 2028.75  5586.1 2030.37  5681.7 2030.58  5828.5 2033.20
#Mann=8,-1,0
  3977.9    0.05       0  4127.3     0.1       0  4239.4    0.16       0
  4265.2     0.1       0  4964.4    0.07       0  4970.4     0.1       0
  5112.7    0.16       0  5217.7     0.1       0
Bank Sta=4964.4,4970.4
Exp/Cntr=0.3,0.1

Type RM Length L Ch R = 1,5831,579,579,579
BEGIN DESCRIPTION:
UNT 1066 IN HEWA 13.0
END DESCRIPTION:
XS GIS Cut Line= 4
      2641368.25     10067186.28      2641928.18     10066678.43
      2642110.48     10066092.50      2641693.85     10065558.70
#Sta/Elev= 30
  3874.9 2039.02  3955.0 2037.42  3975.9 2035.84  4032.7 2034.68  4057.0 2032.96
  4159.8 2028.88  4302.1 2024.63  4436.2 2021.05  4471.3 2018.90  4517.1 2018.05
  4747.7 2011.77  4785.4 2008.91  4855.7 2006.16  4876.6 2006.37  4888.3 2005.35
  4920.8 2004.78  4970.9 2001.83  4999.3 2001.09  5002.0 2000.59  5005.3 2001.09
  5012.8 2002.43  5018.5 2006.03  5033.7 2009.40  5070.1 2011.75  5116.1 2014.14
  5235.2 2016.35  5395.1 2020.57  5615.3 2024.70  5787.1 2025.66  5921.6 2028.33
#Mann=8,-1,0
  3874.9    0.05       0  4057.0     0.1       0  4302.1    0.16       0
  4517.1     0.1       0  4999.3    0.07       0  5005.3     0.1       0
  5070.1    0.16       0  5235.2     0.1       0
Bank Sta=4999.3,5005.3
Exp/Cntr=0.3,0.1

Type RM Length L Ch R = 1,5252,757,757,757
BEGIN DESCRIPTION:
UNT 1066 IN HEWA 12.0
END DESCRIPTION:
XS GIS Cut Line= 4
      2641563.64     10067277.37      2642501.10     10066756.56
      2642605.27     10066405.00      2641798.00     10065571.69
#Sta/Elev= 30
  3751.5 2041.66  3793.5 2038.48  3889.4 2036.07  4037.1 2029.76  4183.4 2025.74
  4454.9 2019.90  4570.2 2016.28  4683.6 2013.75  4720.1 2011.45  4752.1 2011.68
  4870.6 2007.14  4903.9 2004.43  4937.1 1997.85  4962.5 1998.34  5005.8 1995.76
  5008.6 1995.26  5011.8 1995.76  5066.8 2000.25  5147.0 2002.32  5217.6 2002.22
  5342.5 2005.95  5379.8 2006.98  5422.6 2009.00  5480.5 2010.02  5501.3 2010.75
  5634.8 2012.18  6023.8 2019.74  6073.2 2021.56  6250.1 2022.50  6350.8 2024.80
#Mann=11,-1,0
  3751.5     0.1       0  3889.4    0.05       0  4183.4     0.1       0
  4454.9    0.16       0  4570.2     0.1       0  5005.8    0.07       0
  5011.8     0.1       0  5342.5    0.16       0  5379.8     0.1       0
  5480.5    0.16       0  5501.3     0.1       0
Bank Sta=5005.8,5011.8
Exp/Cntr=0.3,0.1

Type RM Length L Ch R = 1,4495,582,582,582
BEGIN DESCRIPTION:
UNT 1066 IN HEWA 10.0
END DESCRIPTION:
XS GIS Cut Line= 3
      2643100.05     10067407.62      2643308.39     10066782.60
      2643139.12     10065688.84
#Sta/Elev= 30
  4038.2 2024.81  4243.3 2017.82  4379.6 2011.83  4396.1 2010.37  4464.6 2009.10
  4491.0 2007.44  4632.6 2002.60  4793.3 1998.72  4948.9 1996.86  4979.2 1993.19
  4987.5 1989.19  4999.4 1988.40  5019.7 1988.79  5026.8 1987.83  5029.6 1987.33
  5032.8 1987.83  5131.0 1993.43  5191.8 1994.87  5201.8 1995.97  5213.9 1999.14
  5232.2 2005.74  5249.8 2009.56  5254.9 2009.27  5272.7 2011.16  5317.9 2012.92
  5434.6 2019.85  5545.9 2024.80  5586.4 2027.73  5667.0 2030.68  5803.8 2034.47
#Mann=5,-1,0
  4038.2     0.1       0  5026.8    0.07       0  5032.8     0.1       0
  5213.9    0.16       0  5667.0     0.1       0
Bank Sta=5026.8,5032.8
Exp/Cntr=0.3,0.1

Type RM Length L Ch R = 1,3913,453,453,453
BEGIN DESCRIPTION:
UNT 1066 IN HEWA 9.0
END DESCRIPTION:
XS GIS Cut Line= 3
      2643620.90     10067420.61      2643881.31     10066222.70
      2643816.25     10065468.08
#Sta/Elev= 30
  4087.5 2020.29  4207.1 2014.57  4335.0 2009.87  4360.6 2008.31  4401.5 2007.27
  4472.1 2003.86  4606.2 1999.92  4775.5 1993.91  4854.9 1990.16  4892.8 1990.16
  4923.5 1989.11  4974.9 1985.50  4997.1 1984.71  5002.3 1983.84  5005.1 1983.34
  5008.3 1983.84  5097.4 1992.65  5210.0 2000.79  5313.4 2004.42  5352.5 2006.27
  5412.7 2010.40  5503.1 2013.29  5533.2 2015.30  5603.4 2016.62  5623.5 2018.83
  5638.1 2019.63  5756.5 2024.11  5896.8 2032.22  6025.0 2036.07  6070.8 2038.12
#Mann=6,-1,0
  4087.5     0.1       0  4775.5    0.05       0  4974.9     0.1       0
  5002.3    0.07       0  5008.3     0.1       0  5896.8    0.16       0
Bank Sta=5002.3,5008.3
Exp/Cntr=0.3,0.1

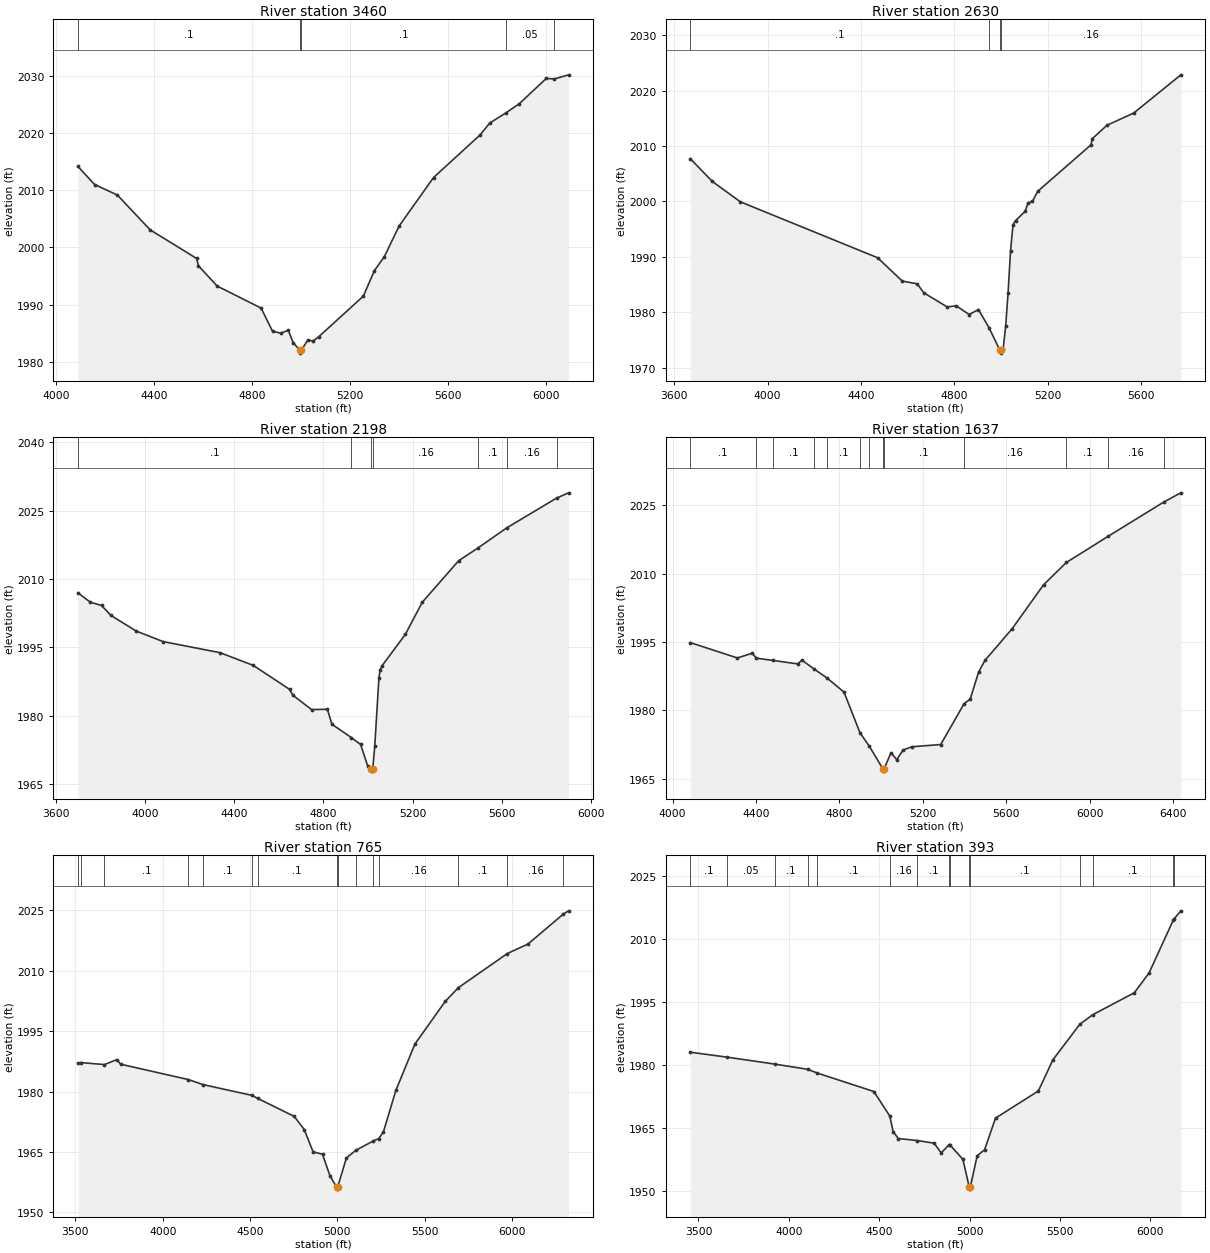
Type RM Length L Ch R = 1,3460,830,830,830
BEGIN DESCRIPTION:
UNT 1066 IN HEWA 8.0
END DESCRIPTION:
XS GIS Cut Line= 4
      2643946.42     10067472.68      2644219.85     10066860.73
      2644297.98     10066144.58      2644284.95     10065532.58
#Sta/Elev= 30
  4089.5 2014.13  4157.7 2010.97  4250.5 2009.14  4384.1 2003.06  4574.1 1998.05
  4581.2 1996.78  4657.9 1993.23  4837.2 1989.38  4883.9 1985.32  4917.7 1985.00
  4947.9 1985.51  4968.0 1983.34  4995.2 1982.01  4997.9 1981.51  5001.2 1982.01
  5028.3 1983.82  5048.5 1983.61  5071.7 1984.35  5254.4 1991.47  5299.9 1995.95
  5340.2 1998.37  5400.5 2003.73  5541.0 2012.20  5731.1 2019.65  5771.1 2021.75
  5837.1 2023.51  5891.1 2025.10  6001.1 2029.52  6034.1 2029.43  6092.3 2030.15
#Mann=5,-1,0
  4089.5     0.1       0  4995.2    0.07       0  5001.2     0.1       0
  5837.1    0.05       0  6034.1    0.16       0
Bank Sta=4995.2,5001.2
Exp/Cntr=0.3,0.1

Type RM Length L Ch R = 1,2630,432,432,432
BEGIN DESCRIPTION:
UNT 1066 IN HEWA 6.0
END DESCRIPTION:
XS GIS Cut Line= 3
      2644219.83     10067498.76      2644936.00     10066782.60
      2645287.57     10065753.93
#Sta/Elev= 30
  3669.0 2007.71  3763.5 2003.60  3883.7 1999.92  4470.6 1989.84  4576.7 1985.62
  4640.3 1985.13  4668.6 1983.51  4768.6 1980.96  4807.4 1981.16  4862.5 1979.59
  4902.5 1980.49  4947.4 1977.23  4994.6 1973.12  4997.4 1972.62  5000.6 1973.12
  5008.2 1973.35  5019.1 1977.51  5029.4 1983.54  5039.8 1991.04  5050.5 1995.82
  5061.1 1996.53  5102.5 1998.21  5113.9 1999.65  5133.8 2000.01  5156.2 2001.82
  5384.3 2010.21  5389.6 2011.30  5452.2 2013.73  5566.9 2015.94  5768.9 2022.84
#Mann=4,-1,0
  3669.0     0.1       0  4947.4    0.16       0  4994.6    0.07       0
  5000.6    0.16       0
Bank Sta=4994.6,5000.6
Exp/Cntr=0.3,0.1

Type RM Length L Ch R = 1,2198,561,561,561
BEGIN DESCRIPTION:
UNT 1066 IN HEWA 5.0
END DESCRIPTION:
XS GIS Cut Line= 4
      2644350.05     10067694.06      2645079.23     10066873.75
      2645482.87     10066730.52      2645599.85     10066067.61
#Sta/Elev= 30
  3700.5 2006.99  3756.0 2004.92  3806.1 2004.22  3848.1 2002.03  3961.7 1998.59
  4082.1 1996.28  4337.1 1993.85  4486.0 1991.06  4649.1 1985.79  4663.3 1984.52
  4747.7 1981.35  4818.5 1981.42  4838.7 1978.14  4925.7 1975.21  4967.4 1973.69
  4998.9 1968.99  5015.6 1968.34  5018.3 1967.84  5021.6 1968.34  5030.7 1973.27
  5049.4 1988.28  5054.7 1990.00  5062.5 1990.92  5167.6 1997.84  5243.4 2004.90
  5406.7 2014.03  5493.9 2016.85  5621.7 2021.23  5845.4 2027.78  5899.5 2028.94
#Mann=7,-1,0
  3700.5     0.1       0  4925.7    0.16       0  5015.6    0.07       0
  5021.6    0.16       0  5493.9     0.1       0  5621.7    0.16       0
  5845.4     0.1       0
Bank Sta=5015.6,5021.6
Exp/Cntr=0.3,0.1

Type RM Length L Ch R = 1,1637,872,872,872
BEGIN DESCRIPTION:
UNT 1066 IN HEWA 4.0
END DESCRIPTION:
XS GIS Cut Line= 3
      2644636.52     10067824.26      2645756.31     10067082.08
      2645652.14     10066079.49
#Sta/Elev= 30
  4085.0 1994.85  4310.7 1991.48  4382.9 1992.52  4401.1 1991.43  4480.5 1990.94
  4599.5 1990.17  4620.6 1990.98  4678.2 1989.07  4742.0 1987.02  4822.1 1983.96
  4898.5 1975.05  4944.1 1972.03  5008.1 1967.12  5010.9 1966.62  5014.1 1967.12
  5047.1 1970.66  5074.8 1969.15  5104.9 1971.25  5147.0 1971.97  5285.3 1972.46
  5397.8 1981.45  5426.7 1982.42  5467.0 1988.37  5497.1 1990.92  5627.8 1997.90
  5778.6 2007.56  5887.8 2012.45  6088.2 2018.20  6356.4 2025.77  6436.4 2027.74
#Mann=13,-1,0
  4085.0     0.1       0  4401.1    0.05       0  4480.5     0.1       0
  4678.2    0.05       0  4742.0     0.1       0  4898.5    0.05       0
  4944.1     0.1       0  5008.1    0.07       0  5014.1     0.1       0
  5397.8    0.16       0  5887.8     0.1       0  6088.2    0.16       0
  6356.4     0.1       0
Bank Sta=5008.1,5014.1
Exp/Cntr=0.3,0.1

Type RM Length L Ch R = 1,765,372,372,372
BEGIN DESCRIPTION:
UNT 1066 IN HEWA 2.0
END DESCRIPTION:
XS GIS Cut Line= 4
      2645027.14     10068188.85      2646146.93     10067485.73
      2645912.56     10066925.83      2645795.38     10066053.48
#Sta/Elev= 30
  3514.7 1987.00  3529.5 1987.20  3666.4 1986.69  3737.7 1987.94  3758.9 1986.79
  4147.0 1982.97  4230.2 1981.73  4512.0 1979.03  4543.3 1978.31  4753.1 1973.82
  4810.9 1970.54  4860.8 1965.04  4915.0 1964.41  4958.4 1959.00  4995.8 1956.26
  4998.6 1955.76  5001.8 1956.26  5051.8 1963.50  5106.2 1965.41  5204.9 1967.70
  5236.8 1968.31  5263.8 1969.99  5335.2 1980.29  5443.9 1991.78  5617.6 2002.38
  5693.2 2005.80  5973.6 2014.28  6091.8 2016.64  6294.8 2024.10  6324.1 2024.88
#Mann=15,-1,0
  3514.7     0.1       0  3529.5    0.05       0  3666.4     0.1       0
  4147.0    0.05       0  4230.2     0.1       0  4512.0    0.05       0
  4543.3     0.1       0  4995.8    0.07       0  5001.8     0.1       0
  5106.2    0.16       0  5204.9     0.1       0  5236.8    0.16       0
  5693.2     0.1       0  5973.6    0.16       0  6294.8     0.1       0
Bank Sta=4995.8,5001.8
Exp/Cntr=0.3,0.1

Type RM Length L Ch R = 1,393,0,0,0
BEGIN DESCRIPTION:
UNT 1066 IN HEWA 1.0
END DESCRIPTION:
XS GIS Cut Line= 4
      2645395.87     10068243.04      2646458.40     10067347.18
      2646361.18     10066902.73      2645940.33     10066140.90
#Sta/Elev= 30
  3454.6 1983.06  3658.1 1981.89  3921.7 1980.24  4105.4 1978.99  4157.2 1978.11
  4470.7 1973.72  4558.9 1967.89  4577.3 1964.21  4605.9 1962.54  4712.1 1962.07
  4804.8 1961.43  4843.2 1959.12  4887.6 1961.11  4890.8 1961.07  4963.4 1957.60
  4998.5 1951.02  5001.2 1950.52  5004.5 1951.02  5042.4 1958.44  5083.4 1959.88
  5144.0 1967.40  5380.6 1973.83  5462.0 1981.29  5610.7 1989.71  5681.6 1991.96
  5912.2 1997.19  5993.6 2001.89  6127.4 2014.44  6129.6 2014.63  6169.7 2016.66
#Mann=15,-1,0
  3454.6     0.1       0  3658.1    0.05       0  3921.7     0.1       0
  4105.4    0.05       0  4157.2     0.1       0  4558.9    0.16       0
  4712.1     0.1       0  4887.6    0.16       0  4890.8     0.1       0
  4998.5    0.07       0  5004.5     0.1       0  5610.7    0.16       0
  5681.6     0.1       0  6127.4    0.16       0  6129.6     0.1       0
Bank Sta=4998.5,5004.5
Exp/Cntr=0.3,0.1

Chan Stop Cuts=-1