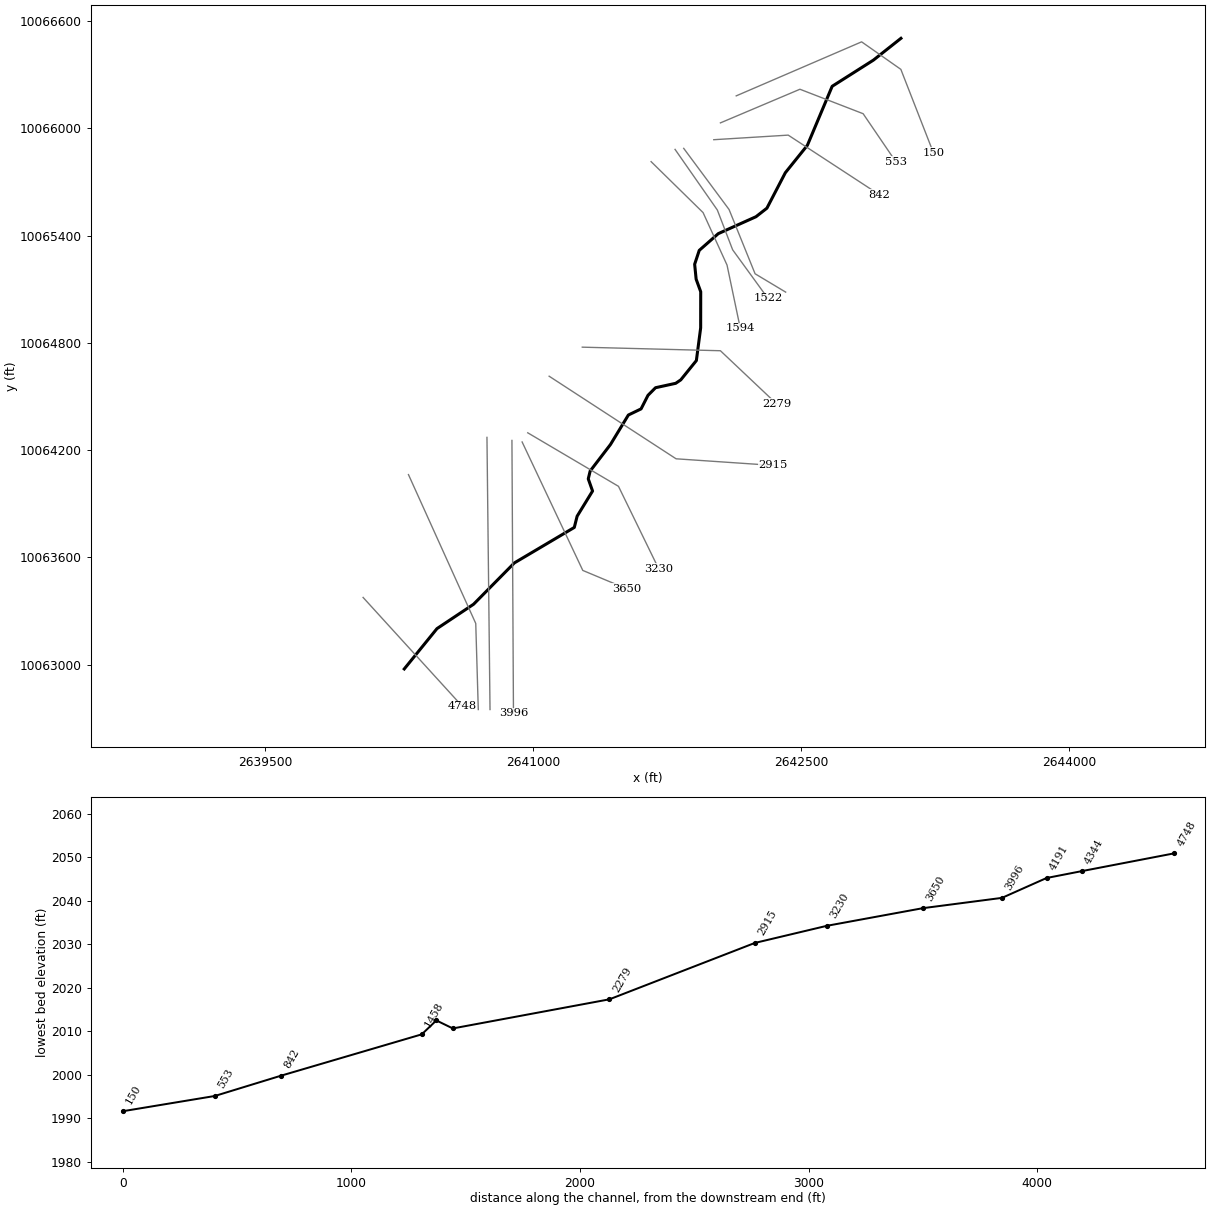
--- UNT 1067 IN HEWA.prj (project) ---

Proj Title=UNT 1067 IN HEWA Base Level Engineering
Current Plan=p01
Default Exp/Contr=0.3,0.1
English Units
Geom File=g01
Flow File=f01
Plan File=p01
BEGIN DESCRIPTION:
UNT 1067 IN HEWA
END DESCRIPTION:

--- UNT 1067 IN HEWA.p01 (plan) ---

Plan Title=Multiple Run
Short Identifier=Multiple
Geom File=g01
Flow File=f01
Subcritical Flow
K Sum by GR= 0
Std Step Tol= 0.01
Critical Tol= 0.01
Num of Std Step Trials= 20
Max Error Tol= 0.3
Flow Tol Ratio= 0.001
Split Flow NTrial= 30
Split Flow Tol= 0.02
Split Flow Ratio= 0.02
Log Output Level= 0
Friction Slope Method= 1
Unsteady Friction Slope Method= 2
Unsteady Bridges Friction Slope Method= 1
Parabolic Critical Depth
Global Vel Dist=  1 , 1 , 1
Global Log Level= 0
CheckData=True
Encroach Param= -1, 0, 0, 0
BEGIN DESCRIPTION:
Multiple Run
END DESCRIPTION:

--- UNT 1067 IN HEWA.f01 (steady flow) ---

Flow Title=Multiple
Number of Profiles=7
Profile Names=10-year,25-year,50-year,1pct_min,100-year,1pct_plu,500-year
River Rch & RM= UNT 1067 IN HEWA,Reach-1,4748
     830    1190    1496    1373    1856    2510    2857
Boundary for River Rch & Prof#=UNT 1067 IN HEWA,Reach-1,1
Up Type=0
Dn Type=3
Dn Slope=0.005
Boundary for River Rch & Prof#=UNT 1067 IN HEWA,Reach-1,2
Up Type=0
Dn Type=3
Dn Slope=0.005
Boundary for River Rch & Prof#=UNT 1067 IN HEWA,Reach-1,3
Up Type=0
Dn Type=3
Dn Slope=0.005
Boundary for River Rch & Prof#=UNT 1067 IN HEWA,Reach-1,4
Up Type=0
Dn Type=3
Dn Slope=0.005
Boundary for River Rch & Prof#=UNT 1067 IN HEWA,Reach-1,5
Up Type=0
Dn Type=3
Dn Slope=0.005
Boundary for River Rch & Prof#=UNT 1067 IN HEWA,Reach-1,6
Up Type=0
Dn Type=3
Dn Slope=0.005
Boundary for River Rch & Prof#=UNT 1067 IN HEWA,Reach-1,7
Up Type=0
Dn Type=3
Dn Slope=0.005

--- UNT 1067 IN HEWA.g01 (geometry) ---

Geom Title=Existing Conditions

River Reach=UNT 1067 IN HEWA,Reach-1
Reach XY= 30
      2640279.71     10062975.70      2640462.75     10063201.27
      2640667.39     10063337.56      2640895.70     10063568.85
      2641231.06     10063767.38      2641246.83     10063830.07
      2641333.23     10063971.04      2641309.18     10064039.06
      2641319.82     10064083.02      2641433.30     10064231.15
      2641533.55     10064396.28      2641604.67     10064430.65
      2641643.35     10064506.54      2641685.56     10064549.05
      2641798.47     10064573.73      2641826.80     10064593.04
      2641913.97     10064700.88      2641938.04     10064883.99
      2641938.33     10065086.03      2641912.70     10065156.31
      2641904.42     10065239.90      2641930.12     10065317.45
      2642036.65     10065411.08      2642247.54     10065505.74
      2642308.62     10065553.50      2642411.74     10065751.89
      2642535.01     10065905.16      2642673.72     10066235.39
      2642904.59     10066381.91      2643058.47     10066503.73

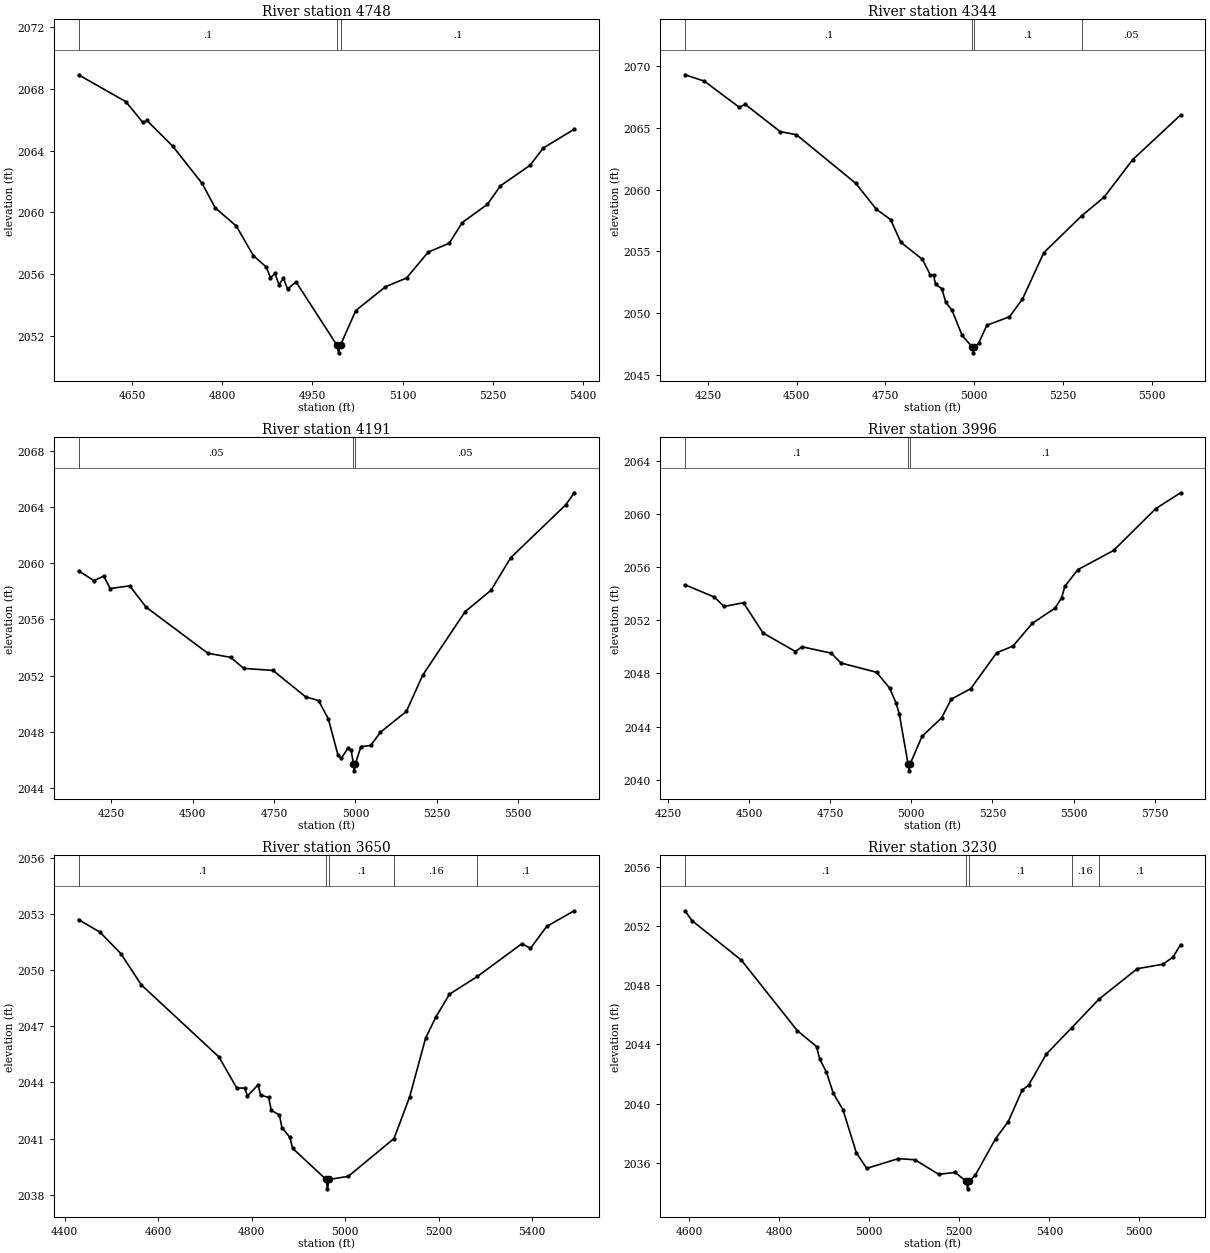
Type RM Length L Ch R = 1,4748,404,404,404
BEGIN DESCRIPTION:
UNT 1067 IN HEWA 10.0
END DESCRIPTION:
XS GIS Cut Line= 2
      2640049.48     10063375.69      2640604.54     10062766.55
#Sta/Elev= 30
  4561.1 2068.92  4639.7 2067.18  4668.1 2065.83  4674.8 2065.96  4717.4 2064.31
  4766.7 2061.88  4788.4 2060.30  4823.5 2059.12  4851.9 2057.20  4873.5 2056.46
  4880.2 2055.77  4887.7 2056.05  4894.4 2055.33  4901.9 2055.74  4908.6 2055.05
  4922.8 2055.50  4990.7 2051.41  4993.5 2050.91  4996.7 2051.41  5022.1 2053.65
  5071.5 2055.19  5106.6 2055.76  5142.4 2057.43  5177.5 2058.01  5199.1 2059.35
  5241.0 2060.53  5262.7 2061.73  5312.0 2063.06  5333.6 2064.17  5385.2 2065.39
#Mann=3,-1,0
  4561.1     0.1       0  4990.7    0.07       0  4996.7     0.1       0
Bank Sta=4990.7,4996.7
Exp/Cntr=0.3,0.1

Type RM Length L Ch R = 1,4344,153,153,153
BEGIN DESCRIPTION:
Mapping XS 7dea069b
END DESCRIPTION:
XS GIS Cut Line= 3
      2640303.28     10064062.96      2640679.70     10063230.27
      2640693.95     10062748.50
#Sta/Elev= 30
  4185.4 2069.26  4239.7 2068.75  4338.2 2066.64  4355.2 2066.87  4453.2 2064.68
  4499.4 2064.42  4666.7 2060.49  4723.9 2058.42  4764.6 2057.57  4793.2 2055.74
  4854.0 2054.37  4875.9 2053.13  4885.6 2053.07  4891.1 2052.34  4908.8 2052.00
  4919.8 2050.90  4937.4 2050.25  4966.0 2048.22  4993.6 2047.32  4996.4 2046.82
  4999.6 2047.32  5012.2 2047.58  5035.3 2049.04  5099.2 2049.73  5135.8 2051.16
  5195.8 2054.90  5302.2 2057.87  5365.9 2059.39  5445.9 2062.40  5581.2 2066.02
#Mann=4,-1,0
  4185.4     0.1       0  4993.6    0.07       0  4999.6     0.1       0
  5302.2    0.05       0
Bank Sta=4993.6,4999.6
Exp/Cntr=0.3,0.1

Type RM Length L Ch R = 1,4191,195,195,195
BEGIN DESCRIPTION:
Mapping XS 4bb2c0fe
END DESCRIPTION:
XS GIS Cut Line= 2
      2640742.44     10064271.16      2640759.55     10062748.56
#Sta/Elev= 30
  4149.4 2059.46  4196.8 2058.76  4226.8 2059.08  4246.8 2058.20  4306.8 2058.39
  4356.8 2056.88  4546.9 2053.60  4616.9 2053.31  4656.9 2052.53  4746.9 2052.38
  4846.9 2050.51  4886.9 2050.24  4916.9 2048.94  4946.9 2046.34  4956.9 2046.14
  4976.9 2046.86  4986.9 2046.75  4993.9 2045.75  4996.6 2045.25  4999.9 2045.75
  5016.9 2046.97  5046.9 2047.05  5076.9 2047.99  5156.9 2049.48  5206.9 2052.05
  5336.9 2056.55  5416.9 2058.08  5476.9 2060.38  5646.9 2064.16  5672.1 2065.00
#Mann=3,-1,0
  4149.4    0.05       0  4993.9    0.04       0  4999.9    0.05       0
Bank Sta=4993.9,4999.9
Exp/Cntr=0.3,0.1

Type RM Length L Ch R = 1,3996,346,346,346
BEGIN DESCRIPTION:
UNT 1067 IN HEWA 9.0
END DESCRIPTION:
XS GIS Cut Line= 2
      2640882.17     10064254.08      2640890.72     10062727.10
#Sta/Elev= 30
  4302.8 2054.67  4393.1 2053.75  4423.1 2053.04  4483.1 2053.32  4543.1 2051.05
  4643.2 2049.65  4663.2 2050.01  4753.2 2049.53  4783.2 2048.79  4893.2 2048.09
  4933.2 2046.90  4953.2 2045.78  4963.2 2044.94  4990.2 2041.18  4992.9 2040.68
  4996.2 2041.18  5033.2 2043.28  5093.2 2044.66  5123.2 2046.07  5183.2 2046.86
  5263.2 2049.56  5313.2 2050.06  5373.2 2051.78  5443.2 2052.92  5463.2 2053.70
  5473.2 2054.56  5513.2 2055.81  5623.2 2057.25  5753.2 2060.40  5829.8 2061.59
#Mann=3,-1,0
  4302.8     0.1       0  4990.2    0.07       0  4996.2     0.1       0
Bank Sta=4990.2,4996.2
Exp/Cntr=0.3,0.1

Type RM Length L Ch R = 1,3650,420,420,420
BEGIN DESCRIPTION:
UNT 1067 IN HEWA 8.0
END DESCRIPTION:
XS GIS Cut Line= 3
      2640939.19     10064245.54      2641278.57     10063526.85
      2641523.67     10063424.25
#Sta/Elev= 30
  4429.4 2052.71  4475.6 2052.03  4519.9 2050.89  4564.1 2049.21  4730.0 2045.36
  4768.0 2043.70  4785.2 2043.70  4790.8 2043.27  4813.5 2043.87  4819.1 2043.32
  4836.3 2043.20  4841.8 2042.51  4859.1 2042.26  4864.6 2041.59  4881.8 2041.06
  4887.4 2040.48  4959.2 2038.81  4962.0 2038.31  4965.2 2038.81  5006.7 2038.98
  5104.4 2041.00  5137.8 2043.22  5172.3 2046.39  5194.5 2047.52  5223.1 2048.72
  5283.0 2049.67  5378.0 2051.42  5396.4 2051.17  5431.0 2052.34  5489.9 2053.18
#Mann=5,-1,0
  4429.4     0.1       0  4959.2    0.07       0  4965.2     0.1       0
  5104.4    0.16       0  5283.0     0.1       0
Bank Sta=4959.2,4965.2
Exp/Cntr=0.3,0.1

Type RM Length L Ch R = 1,3230,315,315,315
BEGIN DESCRIPTION:
UNT 1067 IN HEWA 7.0
END DESCRIPTION:
XS GIS Cut Line= 3
      2640970.60     10064296.82      2641478.19     10063997.39
      2641702.64     10063537.13
#Sta/Elev= 30
  4590.4 2053.02  4605.8 2052.36  4715.6 2049.69  4840.0 2044.93  4882.9 2043.85
  4889.8 2043.01  4904.4 2042.15  4920.0 2040.70  4941.5 2039.59  4971.1 2036.69
  4994.2 2035.63  5064.4 2036.29  5101.5 2036.21  5154.2 2035.23  5190.6 2035.36
  5215.7 2034.75  5218.4 2034.25  5221.7 2034.75  5235.6 2035.18  5280.7 2037.64
  5308.8 2038.79  5339.6 2040.91  5353.9 2041.25  5393.4 2043.35  5449.4 2045.11
  5510.2 2047.05  5595.4 2049.11  5652.3 2049.41  5674.9 2049.89  5691.8 2050.74
#Mann=5,-1,0
  4590.4     0.1       0  5215.7    0.07       0  5221.7     0.1       0
  5449.4    0.16       0  5510.2     0.1       0
Bank Sta=5215.7,5221.7
Exp/Cntr=0.3,0.1

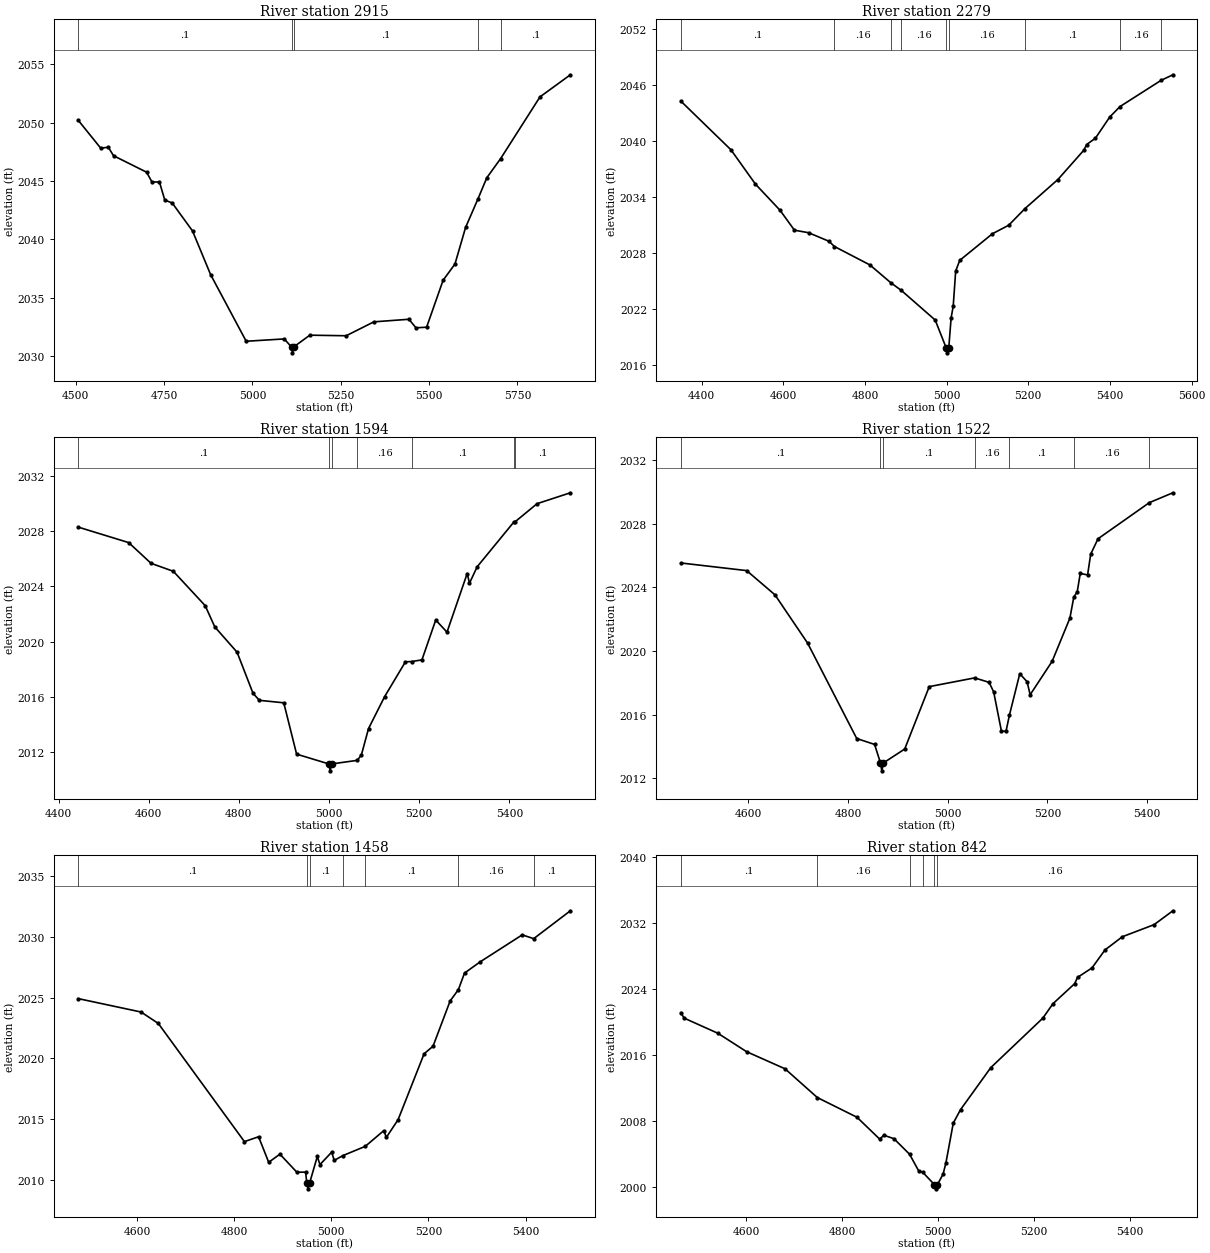
Type RM Length L Ch R = 1,2915,636,636,636
BEGIN DESCRIPTION:
UNT 1067 IN HEWA 6.0
END DESCRIPTION:
XS GIS Cut Line= 3
      2641090.34     10064613.38      2641800.44     10064151.39
      2642344.32     10064114.37
#Sta/Elev= 30
  4507.4 2050.18  4570.9 2047.80  4592.0 2047.89  4607.1 2047.16  4700.7 2045.75
  4715.8 2044.91  4736.9 2044.92  4752.0 2043.37  4773.1 2043.12  4830.5 2040.73
  4881.8 2036.99  4982.4 2031.30  5090.0 2031.50  5110.6 2030.81  5113.4 2030.31
  5116.6 2030.81  5162.5 2031.82  5265.2 2031.77  5343.7 2032.96  5442.8 2033.18
  5462.8 2032.45  5492.9 2032.50  5539.5 2036.51  5573.1 2037.90  5603.2 2041.03
  5637.5 2043.42  5663.3 2045.28  5702.5 2046.92  5813.7 2052.19  5899.7 2054.08
#Mann=5,-1,0
  4507.4     0.1       0  5110.6    0.07       0  5116.6     0.1       0
  5637.5    0.16       0  5702.5     0.1       0
Bank Sta=5110.6,5116.6
Exp/Cntr=0.3,0.1

Type RM Length L Ch R = 1,2279,685,685,685
BEGIN DESCRIPTION:
UNT 1067 IN HEWA 5.0
END DESCRIPTION:
XS GIS Cut Line= 3
      2641275.73     10064775.92      2642048.54     10064755.96
      2642362.26     10064459.36
#Sta/Elev= 30
  4349.2 2044.31  4472.0 2039.09  4532.0 2035.41  4592.0 2032.62  4627.4 2030.48
  4662.0 2030.21  4712.1 2029.29  4725.4 2028.73  4812.1 2026.76  4863.1 2024.86
  4889.3 2024.02  4972.1 2020.85  4999.2 2017.84  5001.9 2017.34  5005.2 2017.84
  5011.1 2021.12  5016.1 2022.31  5022.2 2026.11  5032.2 2027.25  5112.2 2030.10
  5152.0 2031.01  5191.8 2032.79  5272.5 2035.91  5336.0 2039.05  5342.9 2039.66
  5364.3 2040.33  5399.5 2042.61  5424.7 2043.73  5525.0 2046.53  5554.0 2047.13
#Mann=9,-1,0
  4349.2     0.1       0  4725.4    0.16       0  4863.1     0.1       0
  4889.3    0.16       0  4999.2    0.07       0  5005.2    0.16       0
  5191.8     0.1       0  5424.7    0.16       0  5525.0     0.1       0
Bank Sta=4999.2,5005.2
Exp/Cntr=0.3,0.1

Type RM Length L Ch R = 1,1594,72,72,72
BEGIN DESCRIPTION:
UNT 1067 IN HEWA 4.0
END DESCRIPTION:
XS GIS Cut Line= 4
      2641660.72     10065813.94      2641951.58     10065528.79
      2642085.61     10065235.06      2642159.76     10064881.44
#Sta/Elev= 30
  4443.9 2028.30  4555.6 2027.18  4605.1 2025.68  4654.6 2025.10  4725.3 2022.61
  4746.6 2021.07  4796.0 2019.24  4831.4 2016.26  4845.5 2015.75  4899.6 2015.57
  4928.1 2011.85  4999.7 2011.14  5002.5 2010.64  5005.7 2011.14  5062.7 2011.40
  5071.8 2011.79  5087.6 2013.70  5123.4 2016.02  5169.5 2018.54  5183.3 2018.56
  5206.1 2018.68  5236.7 2021.57  5261.7 2020.69  5306.5 2024.94  5311.6 2024.24
  5328.7 2025.43  5409.5 2028.65  5411.7 2028.66  5461.5 2030.00  5535.4 2030.79
#Mann=7,-1,0
  4443.9     0.1       0  4999.7    0.07       0  5005.7     0.1       0
  5062.7    0.16       0  5183.3     0.1       0  5409.5    0.16       0
  5411.7     0.1       0
Bank Sta=4999.7,5005.7
Exp/Cntr=0.3,0.1

Type RM Length L Ch R = 1,1522,64,64,64
BEGIN DESCRIPTION:
Mapping XS 06d8b3cf
END DESCRIPTION:
XS GIS Cut Line= 4
      2641794.76     10065882.38      2642031.43     10065543.05
      2642116.98     10065320.61      2642313.59     10065049.91
#Sta/Elev= 30
  4465.0 2025.54  4597.0 2025.06  4653.7 2023.54  4719.1 2020.51  4817.7 2014.51
  4853.5 2014.14  4865.3 2012.98  4868.0 2012.48  4871.3 2012.98  4913.9 2013.85
  4963.1 2017.77  5054.1 2018.32  5083.1 2018.04  5092.3 2017.44  5107.8 2014.98
  5117.0 2014.96  5123.8 2015.97  5144.6 2018.58  5159.3 2018.08  5165.4 2017.26
  5209.5 2019.36  5245.1 2022.07  5252.9 2023.39  5259.8 2023.73  5265.9 2024.88
  5280.6 2024.79  5286.8 2026.09  5301.5 2027.06  5404.4 2029.33  5451.6 2029.95
#Mann=7,-1,0
  4465.0     0.1       0  4865.3    0.07       0  4871.3     0.1       0
  5054.1    0.16       0  5123.8     0.1       0  5252.9    0.16       0
  5404.4     0.1       0
Bank Sta=4865.3,4871.3
Exp/Cntr=0.3,0.1

Type RM Length L Ch R = 1,1458,616,616,616
BEGIN DESCRIPTION:
Mapping XS af572874
END DESCRIPTION:
XS GIS Cut Line= 4
      2641843.23     10065888.09      2642097.02     10065545.90
      2642242.46     10065186.58      2642413.56     10065083.92
#Sta/Elev= 30
  4479.2 2024.91  4608.4 2023.81  4643.9 2022.87  4821.2 2013.16  4850.4 2013.56
  4871.2 2011.46  4894.3 2012.13  4929.1 2010.65  4947.2 2010.65  4949.6 2009.78
  4952.3 2009.28  4955.6 2009.78  4971.3 2011.94  4976.7 2011.27  5000.8 2012.29
  5006.2 2011.62  5023.9 2012.01  5070.0 2012.77  5108.1 2014.06  5113.5 2013.51
  5137.6 2014.96  5191.2 2020.38  5209.6 2021.00  5244.8 2024.72  5261.8 2025.65
  5274.4 2027.01  5306.9 2027.94  5393.2 2030.15  5416.9 2029.84  5492.4 2032.13
#Mann=7,-1,0
  4479.2     0.1       0  4949.6    0.07       0  4955.6     0.1       0
  5023.9    0.16       0  5070.0     0.1       0  5261.8    0.16       0
  5416.9     0.1       0
Bank Sta=4949.6,4955.6
Exp/Cntr=0.3,0.1

Type RM Length L Ch R = 1,842,289,289,289
BEGIN DESCRIPTION:
UNT 1067 IN HEWA 3.0
END DESCRIPTION:
XS GIS Cut Line= 3
      2642011.44     10065936.59      2642427.83     10065962.25
      2642938.20     10065628.66
#Sta/Elev= 30
  4463.2 2021.11  4470.2 2020.46  4540.4 2018.63  4600.5 2016.39  4680.6 2014.32
  4748.1 2010.83  4830.9 2008.44  4878.2 2005.79  4887.0 2006.26  4908.0 2005.84
  4940.5 2003.96  4959.4 2001.96  4967.9 2001.78  4992.6 2000.26  4995.3 1999.76
  4998.6 2000.26  5010.7 2001.56  5016.6 2002.95  5031.8 2007.73  5046.9 2009.36
  5110.1 2014.46  5218.7 2020.46  5239.8 2022.21  5285.1 2024.64  5291.1 2025.40
  5321.3 2026.55  5348.4 2028.73  5384.6 2030.33  5451.0 2031.80  5490.1 2033.48
#Mann=6,-1,0
  4463.2     0.1       0  4748.1    0.16       0  4940.5     0.1       0
  4967.9    0.16       0  4992.6    0.07       0  4998.6    0.16       0
Bank Sta=4992.6,4998.6
Exp/Cntr=0.3,0.1

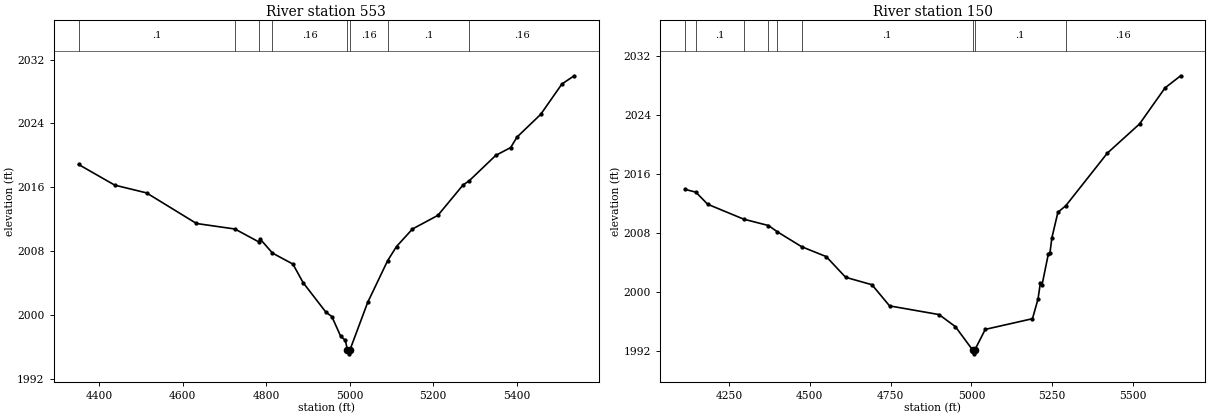
Type RM Length L Ch R = 1,553,403,403,403
BEGIN DESCRIPTION:
UNT 1067 IN HEWA 2.0
END DESCRIPTION:
XS GIS Cut Line= 4
      2642048.56     10066030.71      2642493.42     10066218.91
      2642847.03     10066082.03      2643029.54     10065813.97
#Sta/Elev= 30
  4350.8 2018.86  4437.6 2016.26  4513.6 2015.29  4633.2 2011.45  4725.1 2010.76
  4781.7 2009.16  4786.2 2009.47  4815.1 2007.74  4864.0 2006.36  4888.6 2004.02
  4943.1 2000.32  4957.2 1999.78  4978.6 1997.28  4989.4 1996.81  4994.6 1995.60
  4997.4 1995.10  5000.6 1995.60  5043.0 2001.55  5090.9 2006.80  5112.0 2008.56
  5150.2 2010.76  5211.1 2012.47  5271.4 2016.29  5285.5 2016.78  5349.5 2019.99
  5385.4 2020.98  5400.3 2022.28  5457.2 2025.14  5508.0 2028.95  5537.3 2029.98
#Mann=8,-1,0
  4350.8     0.1       0  4725.1    0.16       0  4781.7     0.1       0
  4815.1    0.16       0  4994.6    0.07       0  5000.6    0.16       0
  5090.9     0.1       0  5285.5    0.16       0
Bank Sta=4994.6,5000.6
Exp/Cntr=0.3,0.1

Type RM Length L Ch R = 1,150,0,0,0
BEGIN DESCRIPTION:
UNT 1067 IN HEWA 1.0
END DESCRIPTION:
XS GIS Cut Line= 4
      2642136.95     10066181.84      2642838.48     10066484.13
      2643058.06     10066330.13      2643240.57     10065862.47
#Sta/Elev= 30
  4113.5 2013.92  4147.2 2013.54  4183.7 2011.90  4295.5 2009.87  4371.9 2009.01
  4399.3 2008.16  4474.8 2006.13  4550.7 2004.79  4610.8 2001.98  4692.3 2000.97
  4746.7 1998.10  4899.9 1996.92  4950.5 1995.28  5004.2 1992.09  5006.9 1991.59
  5010.2 1992.09  5042.9 1994.91  5189.0 1996.36  5206.1 1999.01  5213.5 2001.22
  5218.8 2000.98  5238.0 2005.12  5243.3 2005.34  5249.1 2007.35  5267.8 2010.81
  5292.2 2011.70  5420.8 2018.84  5520.4 2022.80  5599.2 2027.69  5647.6 2029.34
#Mann=9,-1,0
  4113.5    0.16       0  4147.2     0.1       0  4295.5    0.16       0
  4371.9     0.1       0  4399.3    0.16       0  4474.8     0.1       0
  5004.2    0.07       0  5010.2     0.1       0  5292.2    0.16       0
Bank Sta=5004.2,5010.2
Exp/Cntr=0.3,0.1

Chan Stop Cuts=-1