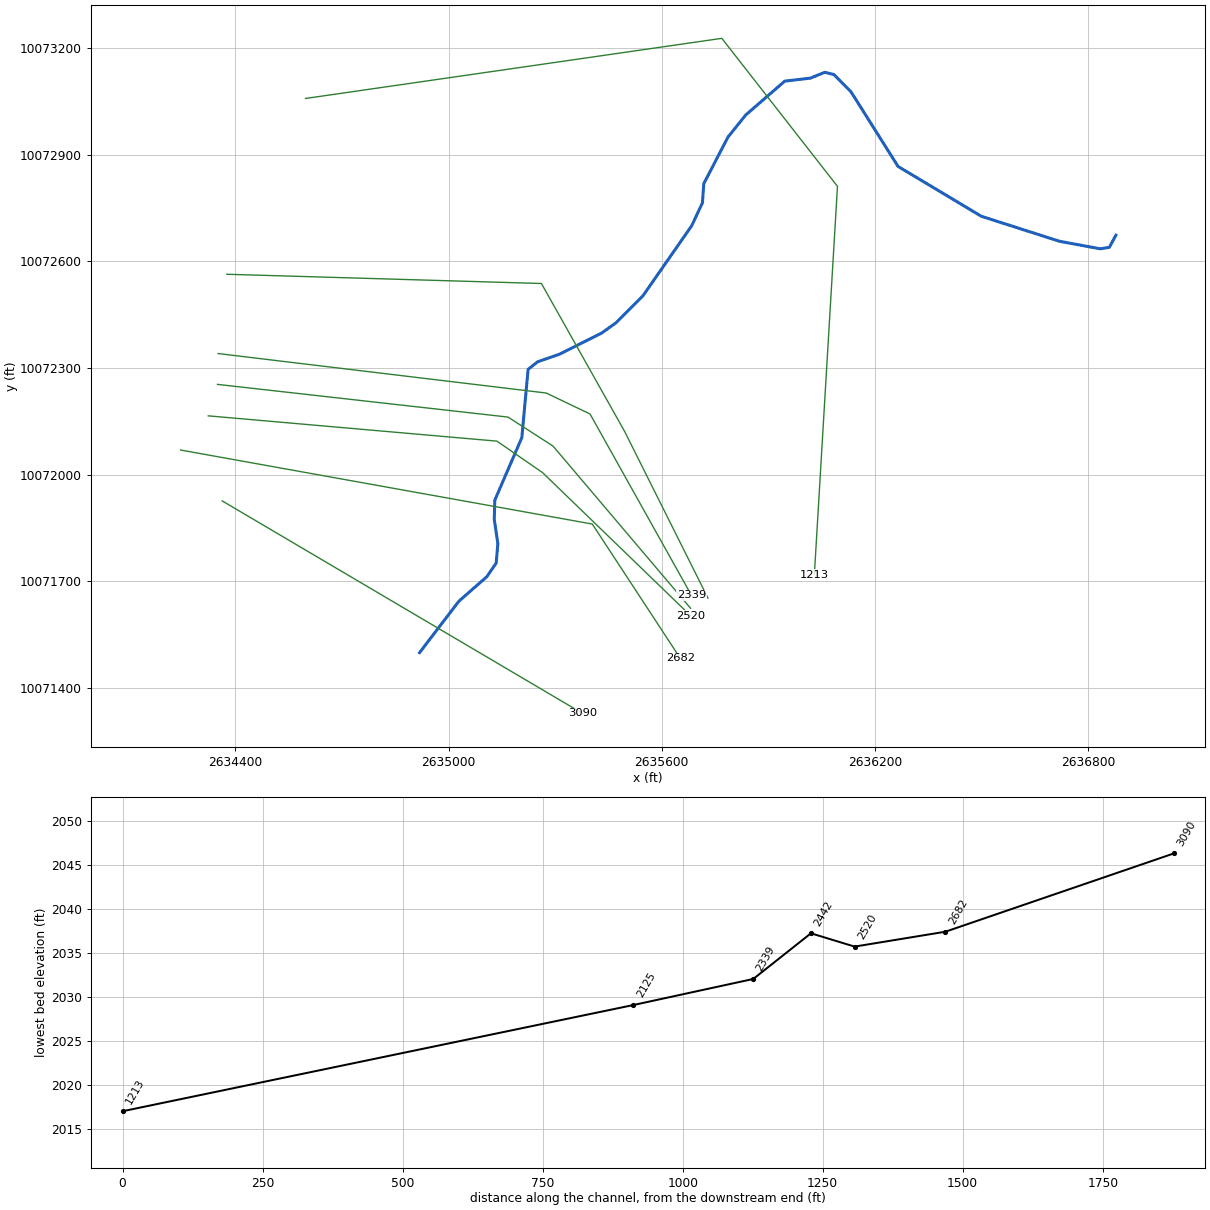
--- UNT 1068 IN HEWA.prj (project) ---

Proj Title=UNT 1068 IN HEWA Base Level Engineering
Current Plan=p01
Default Exp/Contr=0.3,0.1
English Units
Geom File=g01
Flow File=f01
Plan File=p01
BEGIN DESCRIPTION:
UNT 1068 IN HEWA
END DESCRIPTION:

--- UNT 1068 IN HEWA.p01 (plan) ---

Plan Title=Multiple Run
Short Identifier=Multiple
Geom File=g01
Flow File=f01
Subcritical Flow
K Sum by GR= 0
Std Step Tol= 0.01
Critical Tol= 0.01
Num of Std Step Trials= 20
Max Error Tol= 0.3
Flow Tol Ratio= 0.001
Split Flow NTrial= 30
Split Flow Tol= 0.02
Split Flow Ratio= 0.02
Log Output Level= 0
Friction Slope Method= 1
Unsteady Friction Slope Method= 2
Unsteady Bridges Friction Slope Method= 1
Parabolic Critical Depth
Global Vel Dist=  1 , 1 , 1
Global Log Level= 0
CheckData=True
Encroach Param= -1, 0, 0, 0
BEGIN DESCRIPTION:
Multiple Run
END DESCRIPTION:

--- UNT 1068 IN HEWA.f01 (steady flow) ---

Flow Title=Multiple
Number of Profiles=7
Profile Names=10-year,25-year,50-year,1pct_min,100-year,1pct_plu,500-year
River Rch & RM= UNT 1068 IN HEWA,Reach-1,3090
     633     896    1117    1018    1377    1862    2090
Boundary for River Rch & Prof#=UNT 1068 IN HEWA,Reach-1,1
Up Type=0
Dn Type=3
Dn Slope=0.005
Boundary for River Rch & Prof#=UNT 1068 IN HEWA,Reach-1,2
Up Type=0
Dn Type=3
Dn Slope=0.005
Boundary for River Rch & Prof#=UNT 1068 IN HEWA,Reach-1,3
Up Type=0
Dn Type=3
Dn Slope=0.005
Boundary for River Rch & Prof#=UNT 1068 IN HEWA,Reach-1,4
Up Type=0
Dn Type=3
Dn Slope=0.005
Boundary for River Rch & Prof#=UNT 1068 IN HEWA,Reach-1,5
Up Type=0
Dn Type=3
Dn Slope=0.005
Boundary for River Rch & Prof#=UNT 1068 IN HEWA,Reach-1,6
Up Type=0
Dn Type=3
Dn Slope=0.005
Boundary for River Rch & Prof#=UNT 1068 IN HEWA,Reach-1,7
Up Type=0
Dn Type=3
Dn Slope=0.005

--- UNT 1068 IN HEWA.g01 (geometry) ---

Geom Title=Existing Conditions

River Reach=UNT 1068 IN HEWA,Reach-1
Reach XY= 30
      2634918.47     10071498.75      2635029.14     10071643.51
      2635107.66     10071712.33      2635134.21     10071750.80
      2635138.87     10071805.73      2635128.78     10071873.97
      2635130.28     10071927.91      2635206.34     10072103.76
      2635224.05     10072296.16      2635251.16     10072317.68
      2635311.25     10072338.31      2635431.24     10072398.43
      2635472.18     10072427.75      2635547.56     10072503.61
      2635684.67     10072700.59      2635714.73     10072764.91
      2635718.53     10072818.77      2635786.51     10072949.83
      2635836.55     10073012.12      2635946.57     10073107.49
      2636018.58     10073115.84      2636059.11     10073132.28
      2636085.08     10073125.90      2636133.36     10073076.75
      2636265.36     10072867.34      2636499.84     10072727.04
      2636719.71     10072656.71      2636834.47     10072635.45
      2636860.16     10072639.65      2636878.47     10072673.73

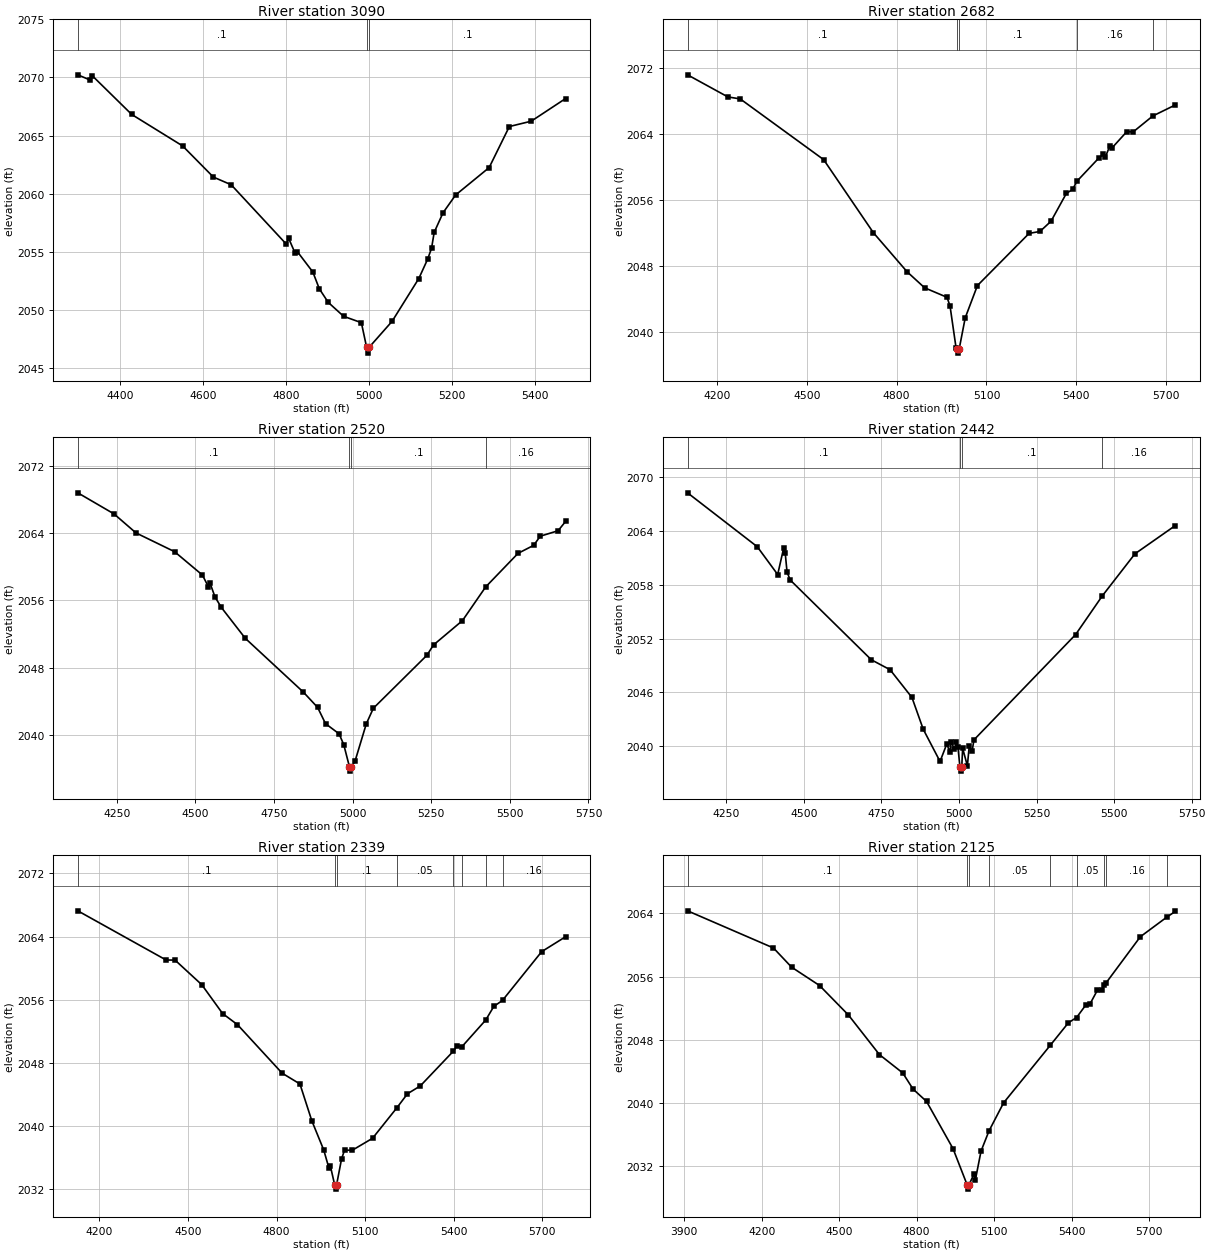
Type RM Length L Ch R = 1,3090,408,408,408
BEGIN DESCRIPTION:
UNT 1068 IN HEWA 6.0
END DESCRIPTION:
XS GIS Cut Line= 2
      2634363.11     10071925.81      2635377.11     10071327.81
#Sta/Elev= 30
  4297.5 2070.23  4326.1 2069.80  4331.9 2070.17  4427.6 2066.82  4550.5 2064.11
  4624.7 2061.43  4667.6 2060.77  4800.4 2055.67  4806.2 2056.17  4821.8 2054.89
  4827.6 2055.00  4864.7 2053.26  4880.4 2051.81  4901.8 2050.65  4938.9 2049.45
  4981.8 2048.90  4994.5 2046.78  4997.2 2046.28  5000.5 2046.78  5056.0 2049.02
  5120.4 2052.70  5141.8 2054.37  5151.2 2055.31  5157.5 2056.67  5178.9 2058.36
  5209.3 2059.89  5290.2 2062.25  5338.9 2065.78  5391.7 2066.24  5474.7 2068.19
#Mann=3,-1,0
  4297.5     0.1       0  4994.5    0.07       0  5000.5     0.1       0
Bank Sta=4994.5,5000.5
Exp/Cntr=0.3,0.1

Type RM Length L Ch R = 1,2682,162,162,162
BEGIN DESCRIPTION:
UNT 1068 IN HEWA 5.0
END DESCRIPTION:
XS GIS Cut Line= 3
      2634245.86     10072069.07      2635404.75     10071860.73
      2635652.14     10071483.12
#Sta/Elev= 30
  4101.9 2071.12  4236.6 2068.44  4277.8 2068.20  4556.3 2060.84  4722.4 2051.98
  4834.8 2047.25  4893.5 2045.30  4968.2 2044.15  4978.3 2043.11  4998.7 2037.97
  5002.9 2037.88  5005.6 2037.38  5008.9 2037.88  5029.1 2041.66  5069.8 2045.57
  5242.5 2051.90  5278.7 2052.13  5315.6 2053.37  5366.9 2056.75  5387.9 2057.23
  5401.6 2058.20  5475.4 2061.04  5490.5 2061.48  5496.5 2061.11  5511.6 2062.47
  5517.6 2062.19  5568.8 2064.24  5589.9 2064.20  5655.4 2066.13  5730.8 2067.47
#Mann=5,-1,0
  4101.9     0.1       0  5002.9    0.07       0  5008.9     0.1       0
  5401.6    0.16       0  5655.4     0.1       0
Bank Sta=5002.9,5008.9
Exp/Cntr=0.3,0.1

Type RM Length L Ch R = 1,2520,78,78,78
BEGIN DESCRIPTION:
Mapping XS ec672095
END DESCRIPTION:
XS GIS Cut Line= 4
      2634323.74     10072165.28      2635136.24     10072094.10
      2635264.71     10072005.56      2635681.41     10071602.75
#Sta/Elev= 30
  4126.1 2068.80  4241.3 2066.29  4311.1 2064.03  4433.7 2061.80  4522.3 2059.02
  4541.1 2057.64  4546.2 2058.09  4562.5 2056.40  4582.6 2055.16  4658.7 2051.49
  4843.6 2045.08  4888.7 2043.27  4913.8 2041.34  4956.9 2040.13  4971.8 2038.84
  4990.0 2036.19  4992.7 2035.69  4996.0 2036.19  5007.6 2036.87  5043.5 2041.32
  5065.9 2043.17  5236.1 2049.47  5257.2 2050.70  5349.3 2053.60  5423.0 2057.60
  5526.0 2061.60  5575.6 2062.55  5596.7 2063.64  5653.3 2064.29  5677.3 2065.40
#Mann=4,-1,0
  4126.1     0.1       0  4990.0    0.07       0  4996.0     0.1       0
  5423.0    0.16       0
Bank Sta=4990,4996
Exp/Cntr=0.3,0.1

Type RM Length L Ch R = 1,2442,103,103,103
BEGIN DESCRIPTION:
Mapping XS 5b77b286
END DESCRIPTION:
XS GIS Cut Line= 4
      2634349.74     10072253.83      2635167.49     10072161.81
      2635294.22     10072080.21      2635681.39     10071623.60
#Sta/Elev= 30
  4125.2 2068.27  4350.0 2062.25  4415.7 2059.15  4434.9 2062.09  4440.0 2061.54
  4445.9 2059.42  4456.0 2058.54  4717.6 2049.63  4778.0 2048.52  4848.5 2045.42
  4884.9 2041.87  4939.0 2038.28  4961.2 2040.27  4969.7 2039.32  4975.6 2040.45
  4984.9 2039.66  4990.8 2040.40  4996.8 2039.87  5003.0 2037.70  5005.8 2037.20
  5009.0 2037.70  5011.9 2039.74  5027.1 2037.80  5033.1 2039.97  5042.3 2039.41
  5048.3 2040.69  5376.1 2052.45  5461.9 2056.76  5567.2 2061.46  5697.5 2064.62
#Mann=4,-1,0
  4125.2     0.1       0  5003.0    0.07       0  5009.0     0.1       0
  5461.9    0.16       0
Bank Sta=5003,5009
Exp/Cntr=0.3,0.1

Type RM Length L Ch R = 1,2339,214,214,214
BEGIN DESCRIPTION:
Mapping XS 3e1f9c4f
END DESCRIPTION:
XS GIS Cut Line= 4
      2634351.53     10072340.63      2635275.13     10072229.52
      2635398.39     10072170.49      2635684.05     10071659.77
#Sta/Elev= 30
  4127.0 2067.26  4426.1 2061.03  4456.3 2061.02  4546.9 2057.90  4617.4 2054.25
  4667.8 2052.84  4818.9 2046.70  4879.3 2045.33  4919.6 2040.66  4959.9 2036.97
  4977.6 2034.66  4982.6 2034.90  4997.2 2032.51  4999.9 2032.01  5003.2 2032.51
  5020.3 2035.84  5030.4 2036.95  5056.4 2036.93  5125.2 2038.45  5207.8 2042.32
  5243.5 2044.09  5286.9 2045.08  5398.6 2049.47  5411.4 2050.16  5427.2 2050.02
  5508.6 2053.43  5535.9 2055.15  5565.4 2055.92  5698.0 2062.09  5779.1 2063.98
#Mann=8,-1,0
  4127.0     0.1       0  4997.2    0.07       0  5003.2     0.1       0
  5207.8    0.05       0  5398.6     0.1       0  5427.2    0.05       0
  5508.6     0.1       0  5565.4    0.16       0
Bank Sta=4997.2,5003.2
Exp/Cntr=0.3,0.1

Type RM Length L Ch R = 1,2125,912,912,912
BEGIN DESCRIPTION:
UNT 1068 IN HEWA 4.0
END DESCRIPTION:
XS GIS Cut Line= 4
      2634376.07     10072563.85      2635261.52     10072537.81
      2635495.89     10072121.14      2635730.28     10071652.36
#Sta/Elev= 30
  3913.3 2064.33  4245.8 2059.62  4315.9 2057.19  4424.2 2054.86  4536.0 2051.12
  4656.0 2046.10  4746.1 2043.78  4786.1 2041.73  4838.2 2040.17  4940.8 2034.18
  4995.9 2029.55  4998.6 2029.05  5001.9 2029.55  5021.8 2030.96  5027.5 2030.26
  5049.2 2033.87  5080.0 2036.43  5136.5 2039.99  5317.1 2047.28  5387.6 2050.15
  5418.8 2050.80  5454.7 2052.39  5471.5 2052.56  5499.4 2054.26  5516.2 2054.31
  5526.4 2054.92  5532.6 2055.17  5665.6 2061.04  5768.6 2063.54  5801.3 2064.26
#Mann=9,-1,0
  3913.3     0.1       0  4995.9    0.07       0  5001.9     0.1       0
  5080.0    0.05       0  5317.1     0.1       0  5418.8    0.05       0
  5526.4     0.1       0  5532.6    0.16       0  5768.6     0.1       0
Bank Sta=4995.9,5001.9
Exp/Cntr=0.3,0.1

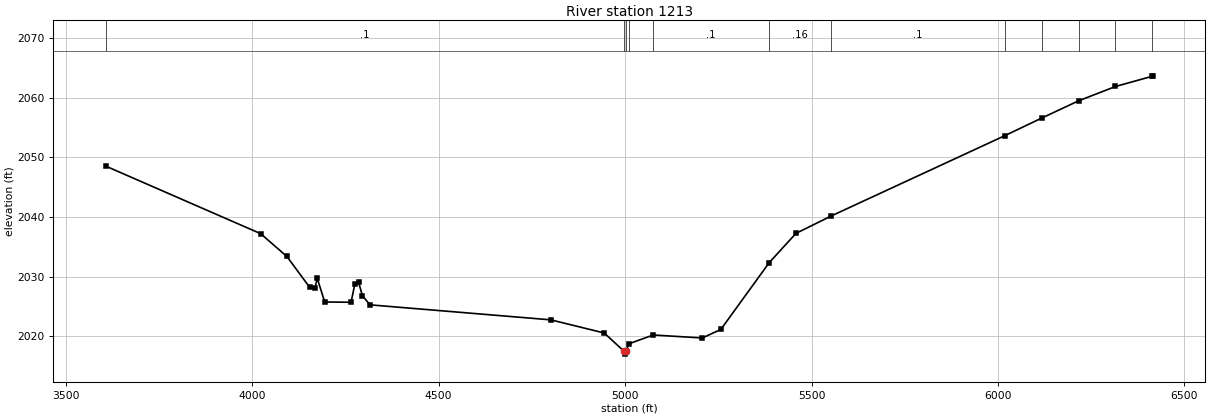
Type RM Length L Ch R = 1,1213,0,0,0
BEGIN DESCRIPTION:
UNT 1068 IN HEWA 1.0
END DESCRIPTION:
XS GIS Cut Line= 4
      2634597.50     10073058.65      2635769.33     10073227.91
      2636094.85     10072811.25      2636029.78     10071718.12
#Sta/Elev= 30
  3607.9 2048.52  4023.1 2037.19  4093.5 2033.36  4154.5 2028.19  4168.9 2028.08
  4174.7 2029.72  4194.9 2025.73  4265.6 2025.68  4275.7 2028.77  4285.8 2029.03
  4295.9 2026.79  4316.1 2025.25  4801.1 2022.73  4944.0 2020.53  4997.2 2017.48
  5000.0 2016.98  5003.2 2017.48  5009.7 2018.70  5075.7 2020.19  5207.2 2019.69
  5256.9 2021.12  5386.7 2032.34  5458.4 2037.24  5552.6 2040.15  6018.6 2053.64
  6117.4 2056.59  6216.2 2059.48  6315.0 2061.88  6413.7 2063.60  6415.7 2063.67
#Mann=12,-1,0
  3607.9     0.1       0  4997.2    0.07       0  5003.2     0.1       0
  5009.7    0.05       0  5075.7     0.1       0  5386.7    0.16       0
  5552.6     0.1       0  6018.6    0.16       0  6117.4    0.05       0
  6216.2    0.16       0  6315.0     0.1       0  6413.7    0.05       0
Bank Sta=4997.2,5003.2
Exp/Cntr=0.3,0.1

Chan Stop Cuts=-1