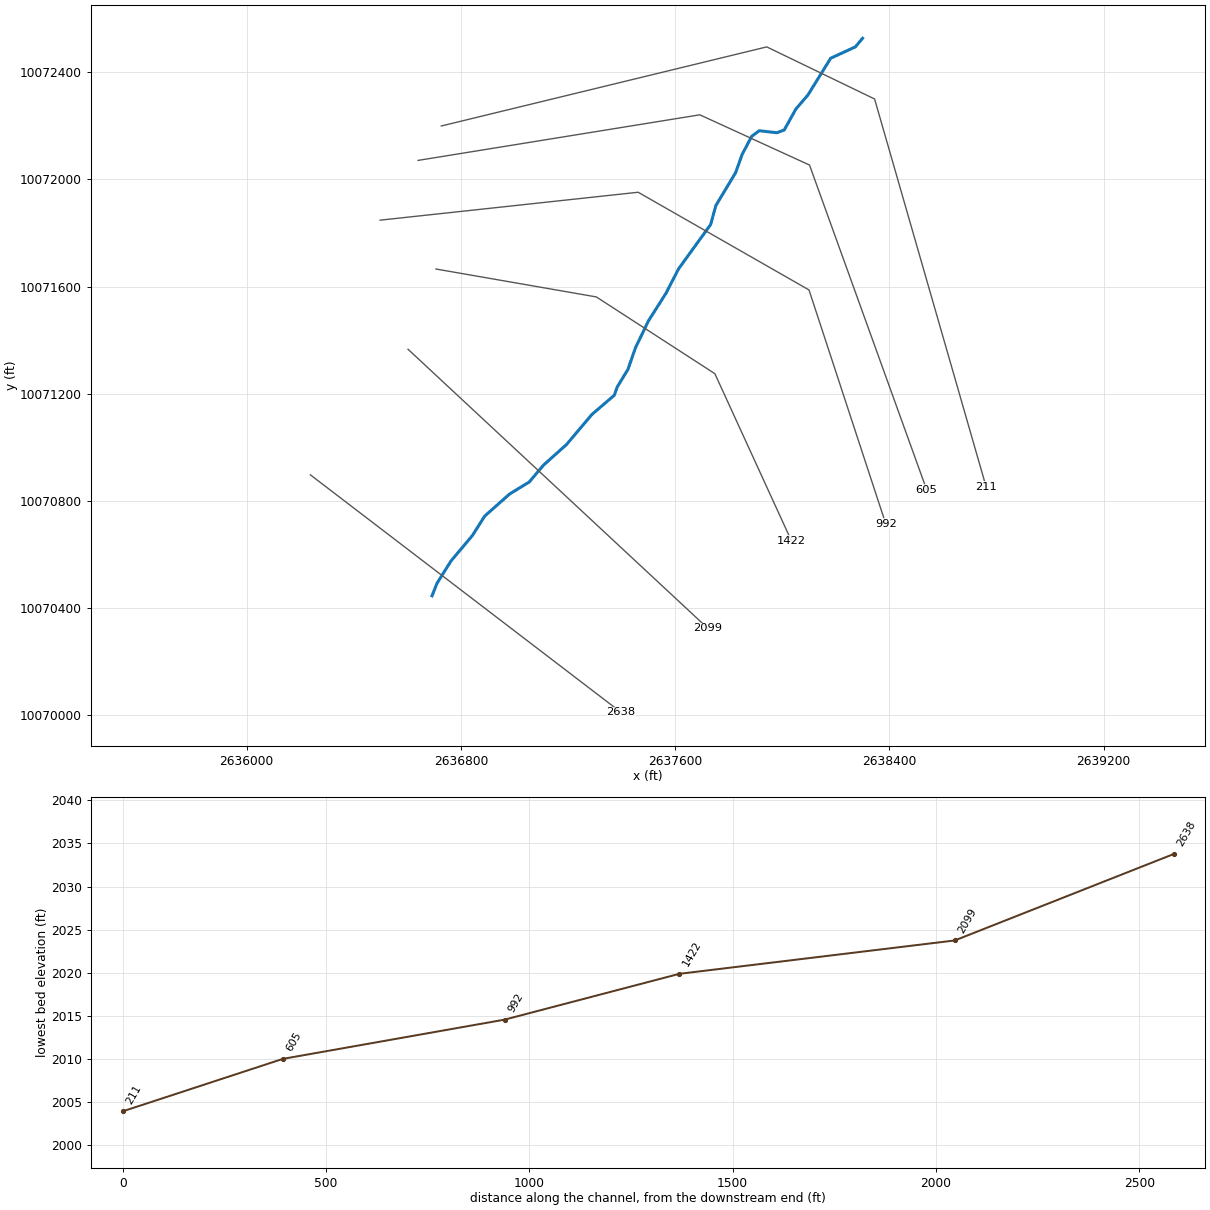
--- UNT 1069 IN HEWA.prj (project) ---

Proj Title=UNT 1069 IN HEWA Base Level Engineering
Current Plan=p01
Default Exp/Contr=0.3,0.1
English Units
Geom File=g01
Flow File=f01
Plan File=p01
Y Axis Title=Elevation
X Axis Title(PF)=Main Channel Distance
X Axis Title(XS)=Station
BEGIN DESCRIPTION:
UNT 1069 IN HEWA
END DESCRIPTION:
DSS Export Rating Curves= 0
DSS Export Rating Curve Sorted= 0
DSS Export Volume Flow Curves= 0
DXF OffsetX= 0
DXF OffsetY= 0
DXF ScaleX= 1
DXF ScaleY= 10

--- UNT 1069 IN HEWA.p01 (plan) ---

Plan Title=Multiple Run
Short Identifier=Multiple
Geom File=g01
Flow File=f01
Subcritical Flow
K Sum by GR= 0
Std Step Tol= 0.01
Critical Tol= 0.01
Num of Std Step Trials= 20
Max Error Tol= 0.3
Flow Tol Ratio= 0.001
Split Flow NTrial= 30
Split Flow Tol= 0.02
Split Flow Ratio= 0.02
Log Output Level= 0
Friction Slope Method= 1
Unsteady Friction Slope Method= 2
Unsteady Bridges Friction Slope Method= 1
Parabolic Critical Depth
Global Vel Dist=  1 , 1 , 1
Global Log Level= 0
CheckData=True
Encroach Param= -1, 0, 0, 0
BEGIN DESCRIPTION:
Multiple Run
END DESCRIPTION:

--- UNT 1069 IN HEWA.f01 (steady flow) ---

Flow Title=Multiple
Number of Profiles=7
Profile Names=10-year,25-year,50-year,1pct_min,100-year,1pct_plu,500-year
River Rch & RM= UNT 1069 IN HEWA,Reach-1,2638
     893    1285    1619    1489    2013    2723    3112
Boundary for River Rch & Prof#=UNT 1069 IN HEWA,Reach-1,1
Up Type=0
Dn Type=3
Dn Slope=0.005
Boundary for River Rch & Prof#=UNT 1069 IN HEWA,Reach-1,2
Up Type=0
Dn Type=3
Dn Slope=0.005
Boundary for River Rch & Prof#=UNT 1069 IN HEWA,Reach-1,3
Up Type=0
Dn Type=3
Dn Slope=0.005
Boundary for River Rch & Prof#=UNT 1069 IN HEWA,Reach-1,4
Up Type=0
Dn Type=3
Dn Slope=0.005
Boundary for River Rch & Prof#=UNT 1069 IN HEWA,Reach-1,5
Up Type=0
Dn Type=3
Dn Slope=0.005
Boundary for River Rch & Prof#=UNT 1069 IN HEWA,Reach-1,6
Up Type=0
Dn Type=3
Dn Slope=0.005
Boundary for River Rch & Prof#=UNT 1069 IN HEWA,Reach-1,7
Up Type=0
Dn Type=3
Dn Slope=0.005

--- UNT 1069 IN HEWA.g01 (geometry) ---

Geom Title=Existing Conditions
Program Version=4.10

River Reach=UNT 1069 IN HEWA,Reach-1
Reach XY= 30
       2636692.4     10070445.99      2636710.87     10070492.73
      2636763.54     10070576.35      2636843.19     10070670.94
      2636889.09     10070743.46      2636982.24      10070825.9
      2637055.19     10070870.45      2637108.69     10070933.65
      2637194.61     10071010.49      2637289.52     10071122.81
      2637372.68     10071194.03      2637384.32     10071225.92
      2637423.96     10071290.87      2637452.28     10071372.15
      2637500.98     10071472.69      2637565.93     10071574.78
      2637613.25     10071666.47      2637732.69     10071831.41
      2637752.19     10071902.19       2637825.9      10072024.8
      2637850.37     10072092.98      2637885.96     10072160.57
      2637914.09     10072181.43      2637980.36     10072173.96
      2638007.64     10072184.38      2638051.13     10072262.59
        2638096.     10072314.75      2638181.07     10072452.02
      2638273.55     10072494.58      2638300.14     10072526.51

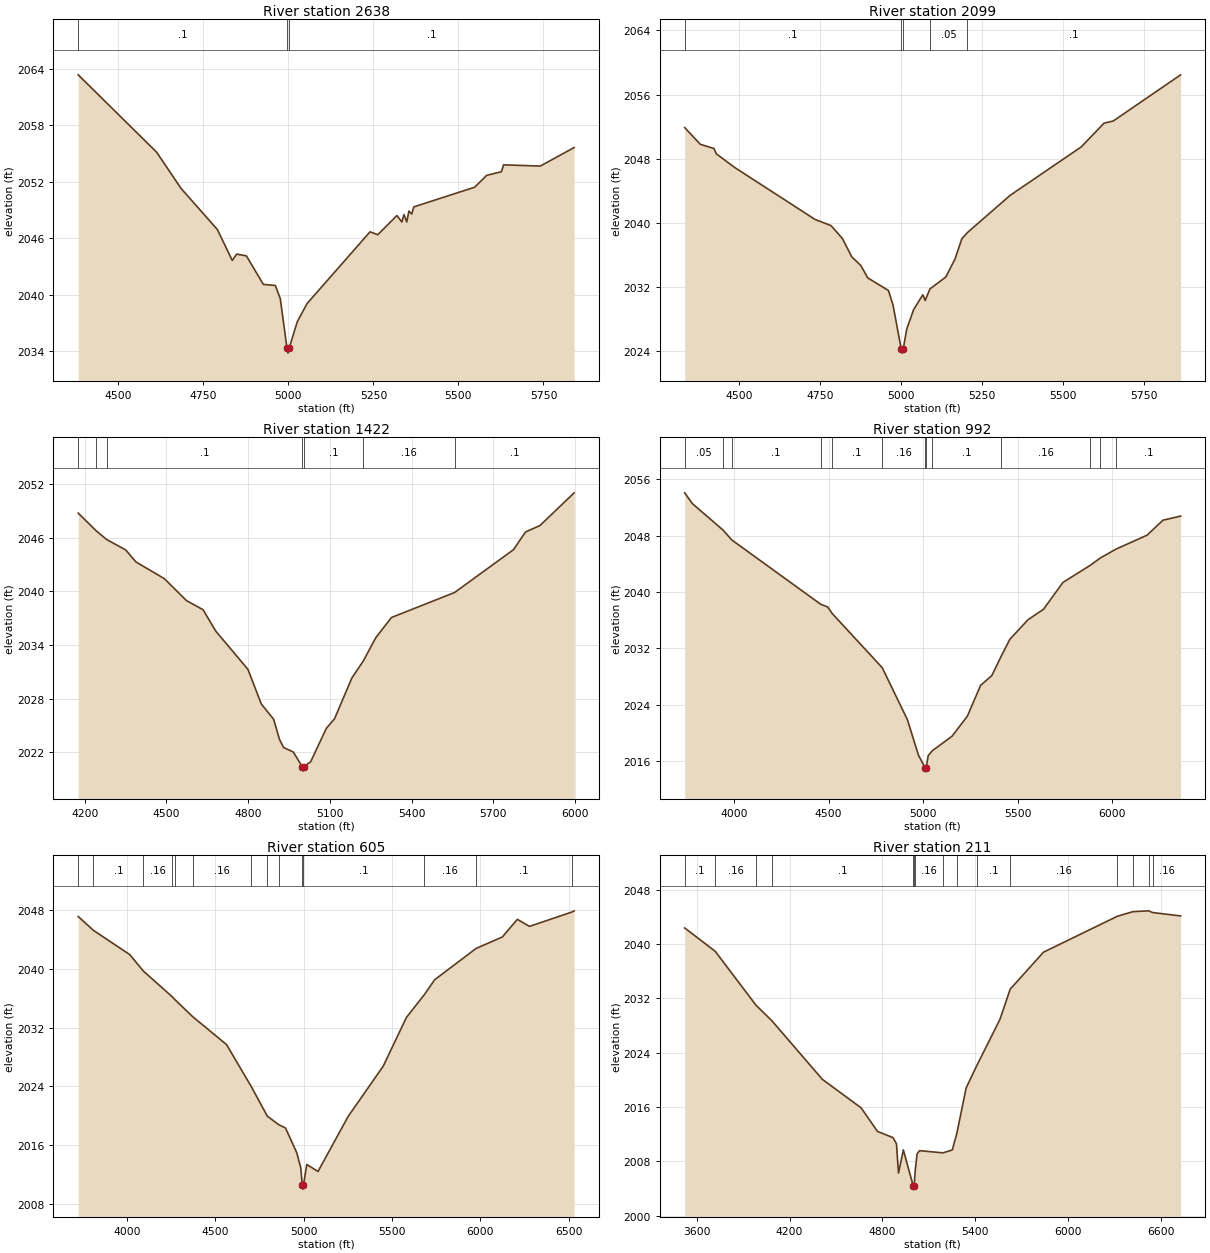
Type RM Length L Ch R = 1 ,2638    ,539,539,539
BEGIN DESCRIPTION:
UNT 1069 IN HEWA 6.0
END DESCRIPTION:
XS GIS Cut Line= 2
       2636238.1     10070897.17      2637396.96     10070011.75
#Sta/Elev= 30
  4381.9 2063.37  4612.6 2055.14  4684.4 2051.29  4791.2 2046.92  4834.8 2043.64
    4848 2044.31  4876.5 2044.12  4926.3 2041.09  4961.7 2040.97  4976.2 2039.56
    4996 2034.28  4998.7 2033.78    5002 2034.28  5026.1 2037.12  5055.1 2039.06
  5240.1 2046.68  5262.9 2046.37  5319.1 2048.41  5333.6 2047.73  5339.9 2048.51
  5348.1 2047.73  5354.4 2048.89  5362.6 2048.57  5368.9 2049.33  5547.6 2051.42
    5583 2052.68  5626.5 2053.07  5632.8  2053.8  5740.8 2053.67  5840.3 2055.64
#Mann= 3 ,-1 , 0
  4381.9      .1       0    4996     .07       0    5002      .1       0
Bank Sta=4996,5002
XS Rating Curve= 0 ,0
Exp/Cntr=0.3,0.1

Type RM Length L Ch R = 1 ,2099    ,677,677,677
BEGIN DESCRIPTION:
UNT 1069 IN HEWA 5.0
END DESCRIPTION:
XS GIS Cut Line= 2
      2636602.69     10071365.91      2637722.42      10070324.3
#Sta/Elev= 30
  4332.6 2051.88  4380.9 2049.79  4422.9 2049.27  4430.3  2048.6  4486.9  2046.9
  4734.6 2040.42    4784 2039.65  4819.2 2038.03  4847.5 2035.77  4875.8 2034.67
  4897.3 2033.12  4960.9 2031.56    4975 2029.76  5000.4 2024.24  5003.1 2023.74
  5006.4 2024.24  5017.5 2026.76  5038.5 2029.16  5066.9 2031.02  5074.2 2030.31
  5088.8 2031.75  5137.7 2033.23  5166.1 2035.47  5187.3 2038.01  5204.2 2038.77
  5336.1 2043.42  5555.5 2049.47  5625.8 2052.43  5654.2  2052.7  5861.9 2058.46
#Mann= 5 ,-1 , 0
  4332.6      .1       0  5000.4     .07       0  5006.4      .1       0
  5088.8     .05       0  5204.2      .1       0
Bank Sta=5000.4,5006.4
XS Rating Curve= 0 ,0
Exp/Cntr=0.3,0.1

Type RM Length L Ch R = 1 ,1422    ,430,430,430
BEGIN DESCRIPTION:
UNT 1069 IN HEWA 3.0
END DESCRIPTION:
XS GIS Cut Line= 4
      2636706.79     10071665.42      2637305.79     10071561.25
       2637748.5     10071274.79       2638034.2     10070651.44
#Sta/Elev= 30
  4176.1 2048.76  4241.4  2046.8  4280.1 2045.81  4350.4 2044.64  4388.1 2043.29
  4492.5 2041.42  4573.7 2038.96  4634.6 2037.94  4681.1 2035.55  4799.2 2031.27
  4848.4 2027.39  4893.8 2025.67    4915 2023.44  4930.1 2022.52  4965.9 2022.01
  4998.7 2020.37  5001.4 2019.87  5004.7 2020.37  5029.7 2020.92  5087.1 2024.66
  5117.4 2025.74  5180.8 2030.29    5223 2032.21  5268.5  2034.8  5326.2 2037.07
  5558.1 2039.87  5774.2 2044.66  5818.6 2046.65  5871.7 2047.37  5997.1 2051.03
#Mann= 7 ,-1 , 0
  4176.1      .1       0  4241.4     .16       0  4280.1      .1       0
  4998.7     .07       0  5004.7      .1       0    5223     .16       0
  5558.1      .1       0
Bank Sta=4998.7,5004.7
XS Rating Curve= 0 ,0
Exp/Cntr=0.3,0.1

Type RM Length L Ch R = 1 ,992     ,545,545,545
BEGIN DESCRIPTION:
UNT 1069 IN HEWA 2.0
END DESCRIPTION:
XS GIS Cut Line= 4
      2636498.51     10071847.71      2637462.04     10071951.87
      2638100.06     10071587.29      2638386.51      10070714.9
#Sta/Elev= 30
  3739.3 2054.08  3779.5 2052.56  3942.7 2048.78  3987.8  2047.4  4458.6 2038.25
  4495.9 2037.86  4519.2 2036.94  4783.9 2029.24  4916.9 2021.86  4975.9 2016.78
  5010.3 2015.05  5013.1 2014.55  5016.3 2015.05  5026.8 2016.74  5048.3 2017.44
    5153 2019.51  5233.6 2022.34  5304.1 2026.74  5363.2 2028.12  5413.1 2030.88
  5458.5 2033.27    5554 2036.04  5636.5 2037.54  5739.6 2041.36  5884.1 2043.79
  5937.3 2044.83  6020.3 2046.09  6183.8 2048.06    6268 2050.19  6361.5 2050.78
#Mann= 13 ,-1 , 0
  3739.3     .05       0  3942.7     .16       0  3987.8      .1       0
  4458.6     .05       0  4519.2      .1       0  4783.9     .16       0
  5010.3     .07       0  5016.3     .16       0  5048.3      .1       0
  5413.1     .16       0  5884.1      .1       0  5937.3     .16       0
  6020.3      .1       0
Bank Sta=5010.3,5016.3
XS Rating Curve= 0 ,0
Exp/Cntr=0.3,0.1

Type RM Length L Ch R = 1 ,605     ,394,394,394
BEGIN DESCRIPTION:
Mapping XS d6e31a46
END DESCRIPTION:
XS GIS Cut Line= 4
      2636640.15     10072070.73      2637692.26     10072240.87
      2638101.98     10072053.37      2638539.47     10070841.59
#Sta/Elev= 30
  3725.1 2047.17  3810.6 2045.29  4017.2 2041.96    4094 2039.72  4254.3 2036.28
  4273.9 2035.79  4372.6 2033.51  4564.2  2029.7  4704.1 2023.97  4794.6 2019.95
  4859.2 2018.78  4897.2 2018.34  4960.7 2014.99  4983.7 2012.91  4992.7  2010.5
  4995.4    2010  4998.7  2010.5  5017.7 2013.36  5081.3 2012.41  5251.7 2019.91
  5450.2 2026.77  5581.3 2033.41  5683.2 2036.53  5740.8 2038.54  5974.9 2042.81
  6123.5 2044.37  6208.6 2046.78  6277.1 2045.82  6515.3 2047.76  6529.8 2047.94
#Mann= 14 ,-1 , 0
  3725.1     .16       0  3810.6      .1       0    4094     .16       0
  4254.3      .1       0  4273.9     .05       0  4372.6     .16       0
  4704.1      .1       0  4794.6     .16       0  4859.2      .1       0
  4992.7     .07       0  4998.7      .1       0  5683.2     .16       0
  5974.9      .1       0  6515.3     .16       0
Bank Sta=4992.7,4998.7
XS Rating Curve= 0 ,0
Exp/Cntr=0.3,0.1

Type RM Length L Ch R = 1 ,211     ,0,0,0
BEGIN DESCRIPTION:
UNT 1069 IN HEWA 1.0
END DESCRIPTION:
XS GIS Cut Line= 4
        2636727.     10072199.21      2637942.26     10072494.35
      2638345.03      10072299.9       2638761.7       10070852.
#Sta/Elev= 30
  3522.6 2042.35  3719.8 2038.92  3983.4 2030.98  4086.2 2028.69  4412.3 2020.07
  4662.9 2015.87  4768.7  2012.4  4868.9 2011.49  4891.1 2010.57  4904.4 2006.26
  4935.5 2009.68  4999.2 2004.41  5001.9 2003.91  5005.2 2004.41  5013.2 2006.86
  5024.4 2009.11  5040.1 2009.57    5192 2009.25  5251.9 2009.68  5281.6 2012.17
  5341.3 2018.81  5408.7 2022.03  5559.8  2028.9  5625.9 2033.34  5840.8 2038.78
  6318.3 2044.07  6419.4 2044.75  6520.5 2044.87  6545.7 2044.62  6727.1 2044.12
#Mann= 15 ,-1 , 0
  3522.6      .1       0  3719.8     .16       0  3983.4     .05       0
  4086.2      .1       0  4999.2     .07       0  5005.2      .1       0
  5013.2     .16       0    5192      .1       0  5281.6     .16       0
  5408.7      .1       0  5625.9     .16       0  6318.3      .1       0
  6419.4     .05       0  6520.5      .1       0  6545.7     .16       0
Bank Sta=4999.2,5005.2
XS Rating Curve= 0 ,0
Exp/Cntr=0.3,0.1

Chan Stop Cuts=-1
Use User Specified Reach Order=0
Composite Channel Slope=5