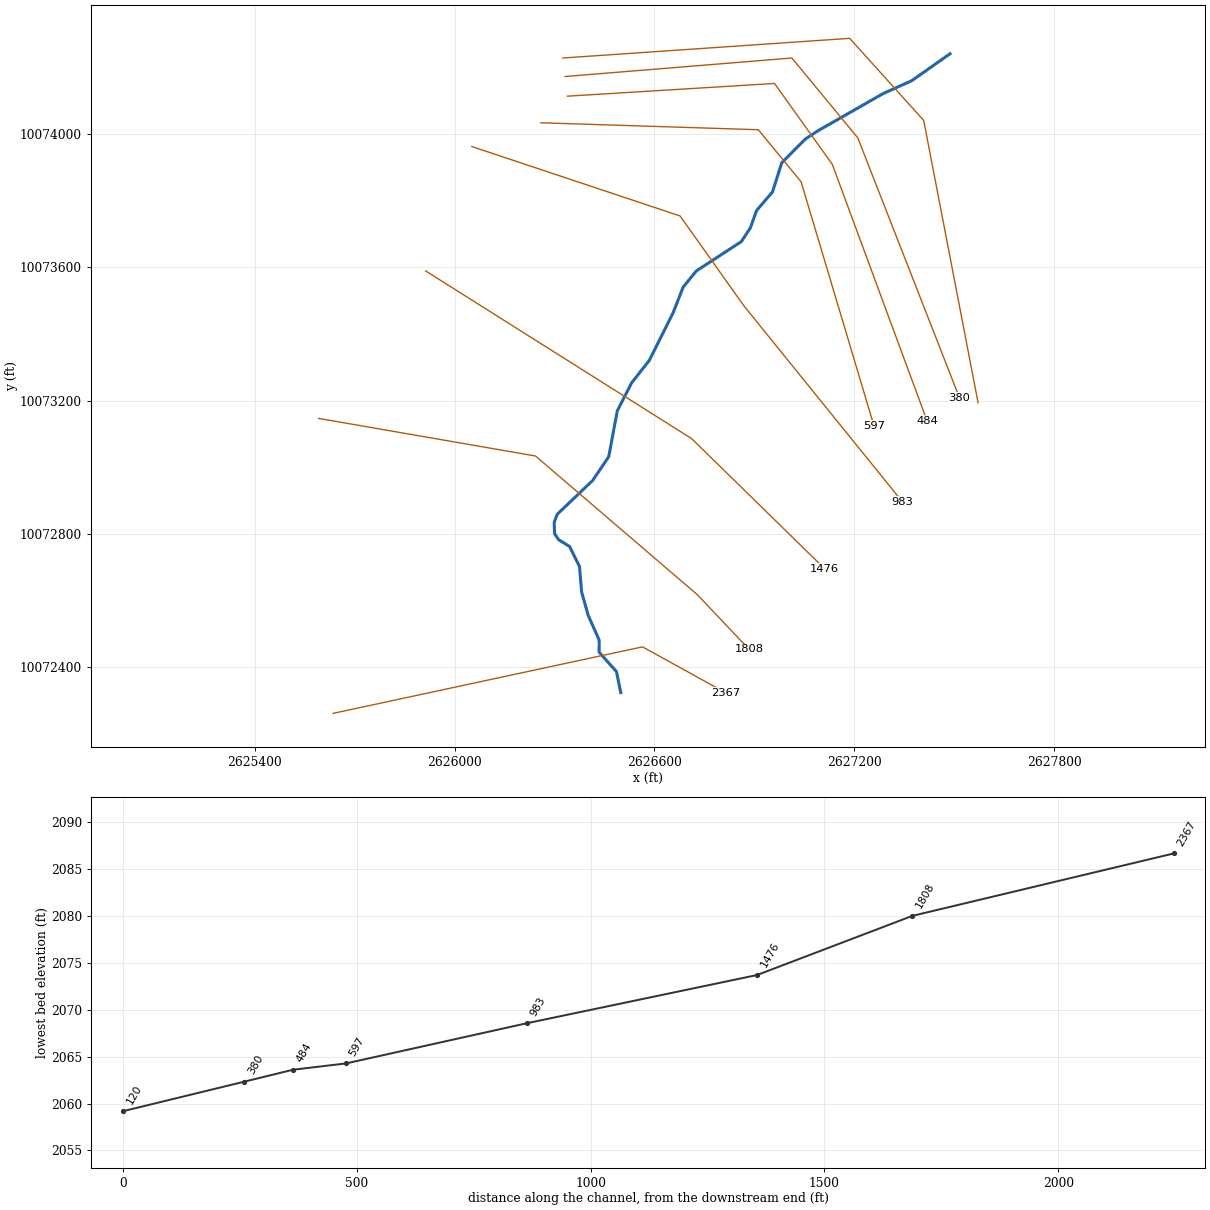
--- UNT 1070 IN HEWA.prj (project) ---

Proj Title=UNT 1070 IN HEWA Base Level Engineering
Current Plan=p01
Default Exp/Contr=0.3,0.1
English Units
Geom File=g01
Flow File=f01
Plan File=p01
Y Axis Title=Elevation
X Axis Title(PF)=Main Channel Distance
X Axis Title(XS)=Station
BEGIN DESCRIPTION:
UNT 1070 IN HEWA
END DESCRIPTION:
DSS Export Rating Curves= 0
DSS Export Rating Curve Sorted= 0
DSS Export Volume Flow Curves= 0
DXF OffsetX= 0
DXF OffsetY= 0
DXF ScaleX= 1
DXF ScaleY= 10

--- UNT 1070 IN HEWA.p01 (plan) ---

Plan Title=Multiple Run
Short Identifier=Multiple
Geom File=g01
Flow File=f01
Subcritical Flow
K Sum by GR= 0
Std Step Tol= 0.01
Critical Tol= 0.01
Num of Std Step Trials= 20
Max Error Tol= 0.3
Flow Tol Ratio= 0.001
Split Flow NTrial= 30
Split Flow Tol= 0.02
Split Flow Ratio= 0.02
Log Output Level= 0
Friction Slope Method= 1
Unsteady Friction Slope Method= 2
Unsteady Bridges Friction Slope Method= 1
Parabolic Critical Depth
Global Vel Dist=  1 , 1 , 1
Global Log Level= 0
CheckData=True
Encroach Param= -1, 0, 0, 0
BEGIN DESCRIPTION:
Multiple Run
END DESCRIPTION:

--- UNT 1070 IN HEWA.f01 (steady flow) ---

Flow Title=Multiple
Number of Profiles=7
Profile Names=10-year,25-year,50-year,1pct_min,100-year,1pct_plu,500-year
River Rch & RM= UNT 1070 IN HEWA,Reach-1,2367
     723    1027    1283    1170    1582    2139    2403
Boundary for River Rch & Prof#=UNT 1070 IN HEWA,Reach-1,1
Up Type=0
Dn Type=3
Dn Slope=0.005
Boundary for River Rch & Prof#=UNT 1070 IN HEWA,Reach-1,2
Up Type=0
Dn Type=3
Dn Slope=0.005
Boundary for River Rch & Prof#=UNT 1070 IN HEWA,Reach-1,3
Up Type=0
Dn Type=3
Dn Slope=0.005
Boundary for River Rch & Prof#=UNT 1070 IN HEWA,Reach-1,4
Up Type=0
Dn Type=3
Dn Slope=0.005
Boundary for River Rch & Prof#=UNT 1070 IN HEWA,Reach-1,5
Up Type=0
Dn Type=3
Dn Slope=0.005
Boundary for River Rch & Prof#=UNT 1070 IN HEWA,Reach-1,6
Up Type=0
Dn Type=3
Dn Slope=0.005
Boundary for River Rch & Prof#=UNT 1070 IN HEWA,Reach-1,7
Up Type=0
Dn Type=3
Dn Slope=0.005

--- UNT 1070 IN HEWA.g01 (geometry) ---

Geom Title=Existing Conditions
Program Version=4.10

River Reach=UNT 1070 IN HEWA,Reach-1
Reach XY= 30
      2626498.83     10072323.37      2626485.81     10072386.24
      2626433.69     10072444.82      2626434.23     10072480.27
      2626401.24     10072554.82      2626381.42     10072624.95
      2626374.82     10072702.29      2626345.23     10072761.63
      2626312.53     10072782.18      2626300.38     10072799.35
      2626298.88     10072833.96      2626308.18     10072858.66
      2626414.25     10072959.77      2626462.72      10073031.4
      2626488.34     10073168.79      2626531.08     10073252.65
      2626584.61     10073320.62      2626656.48     10073464.56
      2626685.94     10073540.14      2626725.58     10073588.94
      2626860.98     10073677.27      2626888.11     10073718.83
       2626906.3     10073769.99      2626954.24     10073826.15
      2626982.12     10073913.68      2627052.96     10073985.04
      2627090.87     10074009.79      2627287.46     10074121.94
      2627372.08     10074159.83      2627487.27     10074241.06

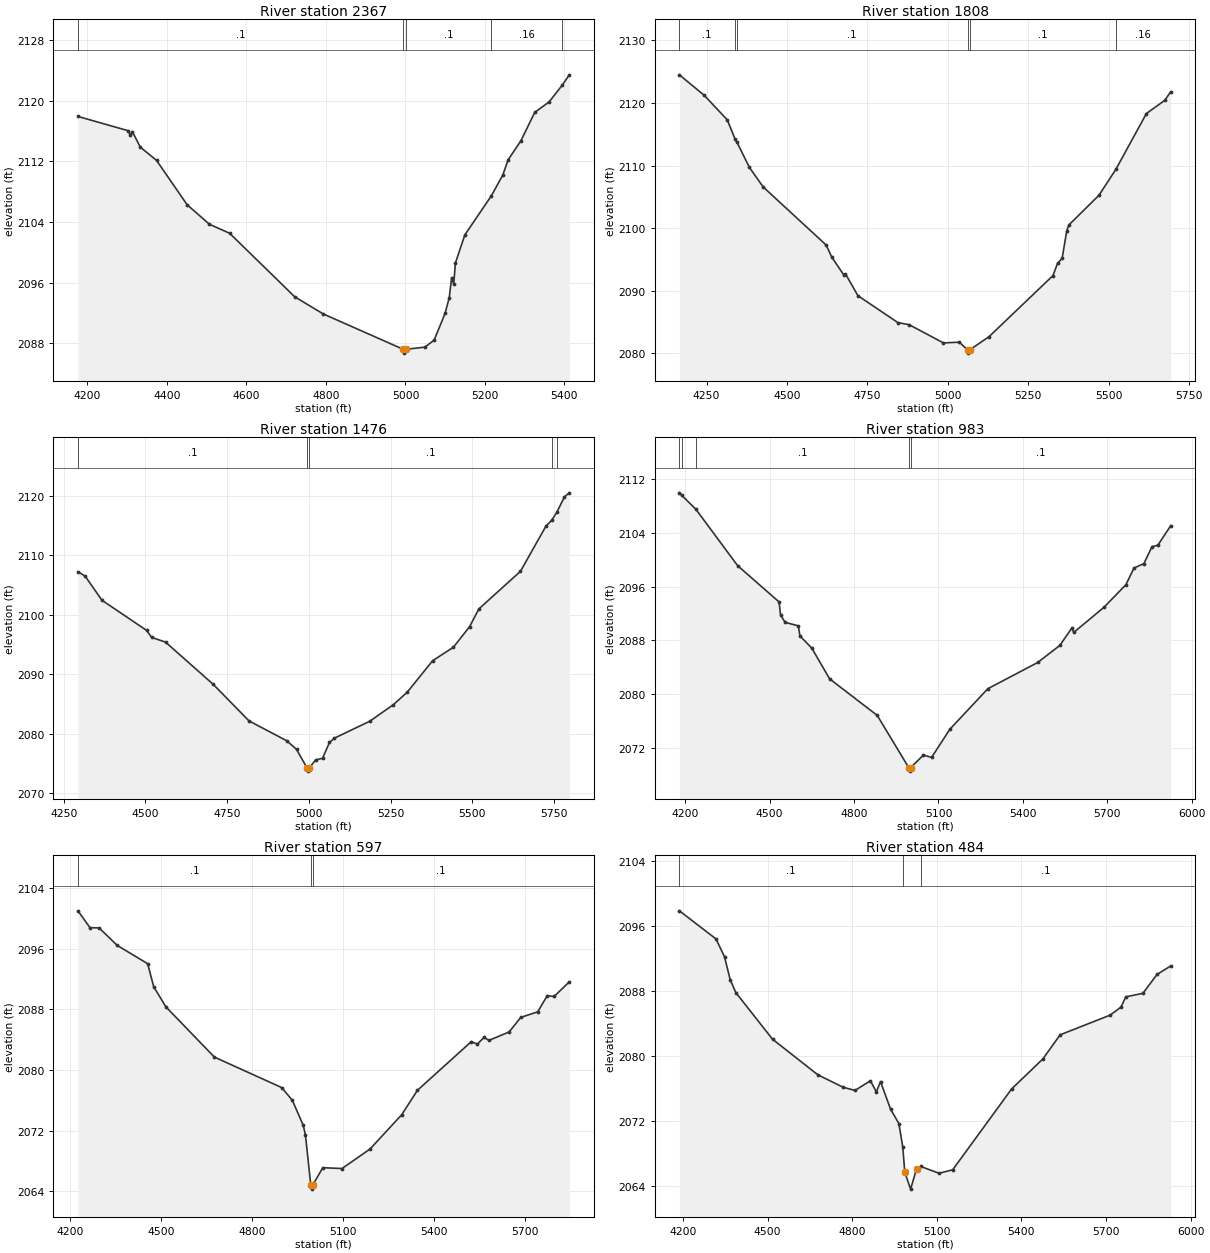
Type RM Length L Ch R = 1 ,2367    ,559,559,559
BEGIN DESCRIPTION:
UNT 1070 IN HEWA 5.0
END DESCRIPTION:
XS GIS Cut Line= 3
      2625635.27     10072260.92      2626564.09     10072460.57
      2626814.65     10072322.33
#Sta/Elev= 30
  4176.1 2117.95  4302.1 2116.07  4307.8  2115.5    4313 2115.94  4332.8  2113.9
  4373.7 2112.15  4450.8 2106.28  4506.7 2103.71  4557.8 2102.51  4721.5 2094.12
  4793.1 2091.86  4994.6 2087.18  4997.4 2086.68  5000.6 2087.18  5048.8 2087.47
  5072.1 2088.39  5099.9 2091.95  5110.2 2094.02  5116.3 2096.67  5121.4 2095.79
  5125.8  2098.6  5149.4  2102.3  5216.1 2107.46  5245.3 2110.25  5258.3 2112.22
  5290.4 2114.73  5325.3 2118.49  5361.5 2119.87  5394.7  2122.1  5412.3 2123.45
#Mann= 5 ,-1 , 0
  4176.1      .1       0  4994.6     .07       0  5000.6      .1       0
  5216.1     .16       0  5394.7      .1       0
Bank Sta=4994.6,5000.6
XS Rating Curve= 0 ,0
Exp/Cntr=0.3,0.1

Type RM Length L Ch R = 1 ,1808    ,332,332,332
BEGIN DESCRIPTION:
UNT 1070 IN HEWA 4.0
END DESCRIPTION:
XS GIS Cut Line= 4
      2625591.89     10073146.33      2626242.91     10073033.49
      2626729.02     10072616.82      2626884.33     10072452.88
#Sta/Elev= 30
  4165.7 2124.49  4243.4 2121.19  4314.5 2117.29  4338.2 2114.29  4344.4 2113.74
  4383.1 2109.71  4426.1 2106.57    4622 2097.28  4639.2 2095.36  4676.7  2092.5
  4681.8 2092.69  4720.4  2089.2  4844.7  2084.9  4879.8 2084.56  4986.3 2081.65
  5035.7 2081.77  5061.2 2080.52    5064 2080.02  5067.2 2080.52  5127.9 2082.65
  5326.5 2092.41  5340.8 2094.36  5355.1 2095.17  5369.3 2099.55  5375.9 2100.49
  5469.9 2105.27  5522.1  2109.4    5617 2118.31  5673.7  2120.4  5692.5 2121.79
#Mann= 6 ,-1 , 0
  4165.7      .1       0  4338.2     .16       0  4344.4      .1       0
  5061.2     .07       0  5067.2      .1       0  5522.1     .16       0
Bank Sta=5061.2,5067.2
XS Rating Curve= 0 ,0
Exp/Cntr=0.3,0.1

Type RM Length L Ch R = 1 ,1476    ,493,493,493
BEGIN DESCRIPTION:
UNT 1070 IN HEWA 3.0
END DESCRIPTION:
XS GIS Cut Line= 3
      2625913.07     10073589.03      2626711.66     10073085.57
      2627110.93     10072694.98
#Sta/Elev= 30
  4293.7 2107.18  4315.4 2106.47  4367.2  2102.4  4503.7 2097.34    4519 2096.17
  4561.4 2095.38  4707.4 2088.28  4816.8 2082.14  4932.2 2078.81  4962.1 2077.36
  4994.5 2074.21  4997.3 2073.71  5000.5 2074.21  5020.4  2075.6  5041.6 2075.86
  5062.8 2078.54  5078.1 2079.25  5186.7 2082.11    5258 2084.86  5300.5 2086.96
  5378.2 2092.25  5441.9 2094.52  5491.4 2097.98  5519.6 2100.95  5646.9 2107.27
  5724.7 2114.85  5742.8 2115.87  5758.2  2117.2  5781.2 2119.75  5796.3 2120.45
#Mann= 5 ,-1 , 0
  4293.7      .1       0  4994.5     .07       0  5000.5      .1       0
  5742.8     .16       0  5758.2      .1       0
Bank Sta=4994.5,5000.5
XS Rating Curve= 0 ,0
Exp/Cntr=0.3,0.1

Type RM Length L Ch R = 1 ,983     ,386,386,386
BEGIN DESCRIPTION:
UNT 1070 IN HEWA 2.0
END DESCRIPTION:
XS GIS Cut Line= 4
      2626051.96      10073962.3      2626676.94     10073753.97
      2626867.91     10073484.88      2627344.43     10072895.72
#Sta/Elev= 30
  4179.1 2109.93  4187.1 2109.57  4237.6 2107.49  4386.2  2099.1  4533.4 2093.71
  4538.7 2091.78  4554.9 2090.68  4601.9 2090.15  4607.6 2088.66  4649.8 2086.84
    4713 2082.28  4882.4 2076.84  4994.6 2069.06  4997.3 2068.56  5000.6 2069.06
  5046.6 2070.95  5075.5  2070.6  5140.8  2074.8  5275.4 2080.81  5452.9 2084.71
  5531.2 2087.24  5574.4 2089.84  5580.9 2089.18  5687.9  2092.9  5766.2 2096.27
    5795 2098.75  5830.2 2099.41  5858.9 2101.92  5879.8 2102.14  5925.6 2105.05
#Mann= 5 ,-1 , 0
  4179.1      .1       0  4187.1     .16       0  4237.6      .1       0
  4994.6     .07       0  5000.6      .1       0
Bank Sta=4994.6,5000.6
XS Rating Curve= 0 ,0
Exp/Cntr=0.3,0.1

Type RM Length L Ch R = 1 ,597     ,113,113,113
BEGIN DESCRIPTION:
Mapping XS 1010ae04
END DESCRIPTION:
XS GIS Cut Line= 4
       2626258.9     10074033.71      2626911.66     10074012.88
      2627040.13     10073856.63      2627258.89     10073123.97
#Sta/Elev= 30
  4226.4 2101.02    4266 2098.79    4296 2098.77    4356 2096.45  4456.1 2094.04
  4476.1    2091  4516.1 2088.35  4676.2 2081.71  4897.9 2077.69  4933.1 2076.01
    4969 2072.71  4976.2 2071.48    4994 2064.78  4996.7 2064.28    5000 2064.78
  5033.5 2067.11  5096.9    2067  5189.2 2069.57  5293.5 2074.09  5345.7 2077.33
  5523.1 2083.75  5543.3 2083.42  5564.9 2084.31  5581.6 2083.92  5647.9 2085.03
  5686.3 2086.95  5742.3 2087.69  5773.6 2089.82  5796.1 2089.71  5846.4 2091.65
#Mann= 3 ,-1 , 0
  4226.4      .1       0    4994     .07       0    5000      .1       0
Bank Sta=4994,5000
XS Rating Curve= 0 ,0
Exp/Cntr=0.3,0.1

Type RM Length L Ch R = 1 ,484     ,104,104,104
BEGIN DESCRIPTION:
Mapping XS fe643835
END DESCRIPTION:
XS GIS Cut Line= 4
      2626338.79     10074113.58      2626960.27     10074151.77
      2627133.88     10073908.72      2627418.44     10073138.33
#Sta/Elev= 30
  4186.9 2097.84  4316.8 2094.38  4346.9 2092.19  4366.9 2089.39  4386.9 2087.79
  4517.2 2082.05  4677.5 2077.68  4767.7 2076.14  4809.6 2075.75  4864.6 2076.94
  4885.4 2075.56  4900.2 2076.84  4935.8 2073.45  4965.3 2071.68  4979.2 2068.78
  4986.2  2065.7  5006.9 2063.61  5028.3 2066.14  5042.7  2066.4  5107.9 2065.56
  5156.2 2065.99  5365.4 2075.94    5476 2079.62  5537.3 2082.59  5714.5 2085.01
  5753.2    2086    5770 2087.26  5830.8 2087.69    5881 2090.02  5929.5 2091.06
#Mann= 3 ,-1 , 0
  4186.9      .1       0  4979.2     .07       0  5042.7      .1       0
Bank Sta=4986.2,5028.3
XS Rating Curve= 0 ,0
Exp/Cntr=0.3,0.1

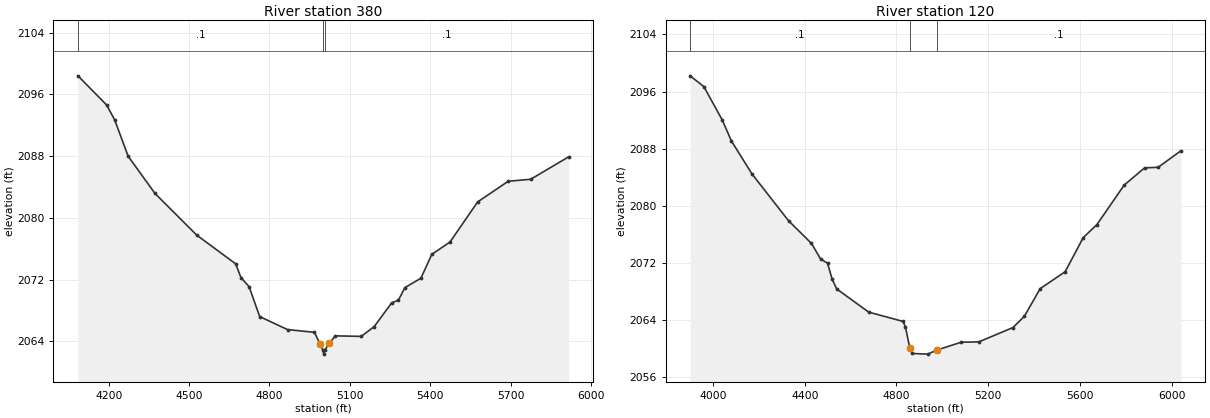
Type RM Length L Ch R = 1 ,380     ,260,260,260
BEGIN DESCRIPTION:
Mapping XS 5b957b36
END DESCRIPTION:
XS GIS Cut Line= 4
      2626331.82     10074172.61      2627012.36     10074228.16
      2627210.27     10073988.58      2627515.56     10073208.01
#Sta/Elev= 30
  4085.2 2098.42  4192.2 2094.64  4222.3 2092.71  4272.5    2088  4372.8 2083.17
  4528.8 2077.76  4673.8 2074.05  4693.9 2072.25    4724 2071.09  4763.5 2067.21
  4867.5 2065.52  4967.8 2065.17  4988.7 2063.66    5000 2062.84  5002.7 2062.34
    5006 2062.84  5023.8 2063.76    5046 2064.71  5142.7 2064.64  5191.3 2065.92
  5256.7 2069.01  5281.2 2069.33  5305.6 2070.96  5365.3 2072.18  5406.1 2075.28
  5473.9 2076.87  5577.1 2082.07  5691.1 2084.75  5775.2 2085.01  5916.9 2087.92
#Mann= 3 ,-1 , 0
  4085.2      .1       0    5000     .07       0    5006      .1       0
Bank Sta=4988.7,5023.8
XS Rating Curve= 0 ,0
Exp/Cntr=0.3,0.1

Type RM Length L Ch R = 1 ,120     ,0,0,0
BEGIN DESCRIPTION:
UNT 1070 IN HEWA 1.0
END DESCRIPTION:
XS GIS Cut Line= 4
      2626324.88     10074228.16      2627185.97     10074287.19
      2627408.19     10074040.66      2627571.38     10073193.45
#Sta/Elev= 30
    39002098.202 3959.912096.687 4039.79 2092.02 4079.732089.081  4169.62084.443
 4329.362077.876 4429.212074.707 4469.152072.514 4499.112071.939 4519.082069.716
 4539.052068.325 4678.842065.071 4828.622063.768 4838.612063.043 4858.582059.981
 4868.562059.273 4936.672059.182 4975.422059.743 5081.982060.848 5159.492060.904
 5307.962062.908 5357.46 2064.47 5426.752068.363 5535.632070.735 5614.82 2075.53
 5674.212077.345    57932082.875 5882.082085.296 5941.482085.376 6040.462087.695
#Mann= 3 , 0 , 0
    3900      .1       0 4858.58     .07       0 4975.42      .1       0
Bank Sta=4858.58,4975.42
XS Rating Curve= 0 ,0
Exp/Cntr=0.3,0.1

Chan Stop Cuts=-1
Use User Specified Reach Order=0
Composite Channel Slope=5