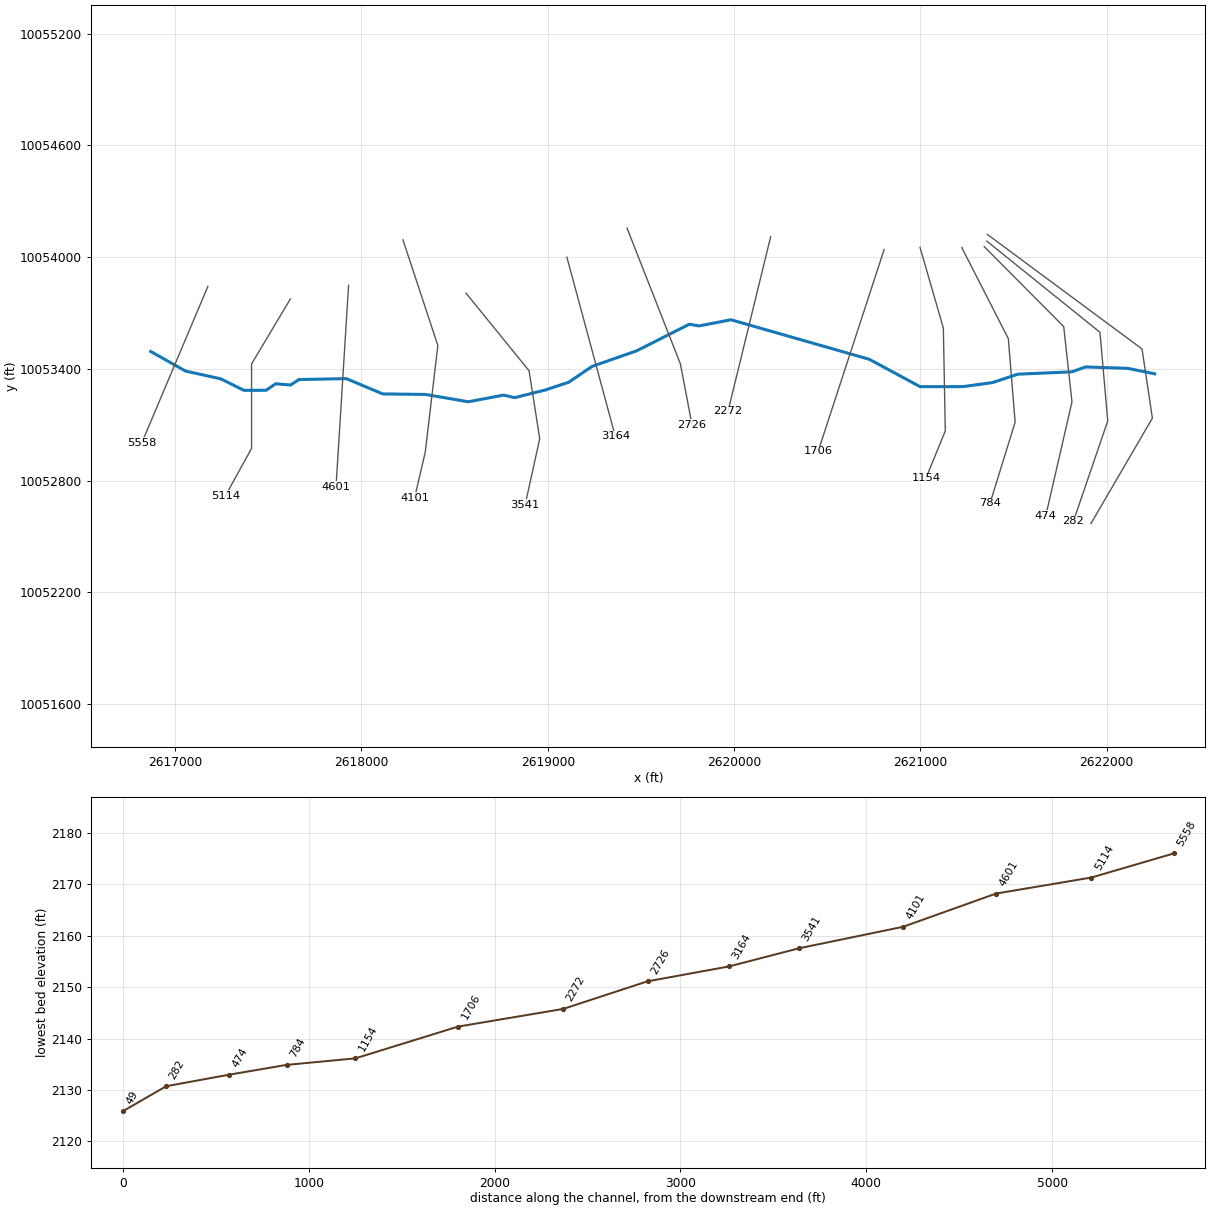
--- UNT 1071 IN HEWA.prj (project) ---

Proj Title=UNT 1071 IN HEWA Base Level Engineering
Current Plan=p01
Default Exp/Contr=0.3,0.1
English Units
Geom File=g01
Flow File=f01
Plan File=p01
Y Axis Title=Elevation
X Axis Title(PF)=Main Channel Distance
X Axis Title(XS)=Station
BEGIN DESCRIPTION:
UNT 1071 IN HEWA
END DESCRIPTION:
DSS Export Rating Curves= 0
DSS Export Rating Curve Sorted= 0
DSS Export Volume Flow Curves= 0
DXF OffsetX= 0
DXF OffsetY= 0
DXF ScaleX= 1
DXF ScaleY= 10

--- UNT 1071 IN HEWA.p01 (plan) ---

Plan Title=Multiple Run
Short Identifier=Multiple
Geom File=g01
Flow File=f01
Subcritical Flow
K Sum by GR= 0
Std Step Tol= 0.01
Critical Tol= 0.01
Num of Std Step Trials= 20
Max Error Tol= 0.3
Flow Tol Ratio= 0.001
Split Flow NTrial= 30
Split Flow Tol= 0.02
Split Flow Ratio= 0.02
Log Output Level= 0
Friction Slope Method= 1
Unsteady Friction Slope Method= 2
Unsteady Bridges Friction Slope Method= 1
Parabolic Critical Depth
Global Vel Dist=  1 , 1 , 1
Global Log Level= 0
CheckData=True
Encroach Param= -1, 0, 0, 0
BEGIN DESCRIPTION:
Multiple Run
END DESCRIPTION:

--- UNT 1071 IN HEWA.f01 (steady flow) ---

Flow Title=Multiple
Program Version=4.10
Number of Profiles= 7
Profile Names=10-year,25-year,50-year,1pct_min,100-year,1pct_plu,500-year
River Rch & RM=UNT 1071 IN HEWA,Reach-1         ,5558
     918    1318    1657    1519    2055    2779    3158
River Rch & RM=UNT 1071 IN HEWA,Reach-1         ,5114
    1291    1885    2398    2220    3003    4061    4712
Boundary for River Rch & Prof#=UNT 1071 IN HEWA,Reach-1         , 1
Up Type= 0
Dn Type= 3
Dn Slope=0.02
Boundary for River Rch & Prof#=UNT 1071 IN HEWA,Reach-1         , 2
Up Type= 0
Dn Type= 3
Dn Slope=0.02
Boundary for River Rch & Prof#=UNT 1071 IN HEWA,Reach-1         , 3
Up Type= 0
Dn Type= 3
Dn Slope=0.02
Boundary for River Rch & Prof#=UNT 1071 IN HEWA,Reach-1         , 4
Up Type= 0
Dn Type= 3
Dn Slope=0.02
Boundary for River Rch & Prof#=UNT 1071 IN HEWA,Reach-1         , 5
Up Type= 0
Dn Type= 3
Dn Slope=0.02
Boundary for River Rch & Prof#=UNT 1071 IN HEWA,Reach-1         , 6
Up Type= 0
Dn Type= 3
Dn Slope=0.02
Boundary for River Rch & Prof#=UNT 1071 IN HEWA,Reach-1         , 7
Up Type= 0
Dn Type= 3
Dn Slope=0.02
DSS Import GetInterval= 0
DSS Import GetPeak= 0
DSS Import FillOption= 0

--- UNT 1071 IN HEWA.g01 (geometry) ---

Geom Title=Existing Conditions
Program Version=4.10

River Reach=UNT 1071 IN HEWA,Reach-1
Reach XY= 30
      2616868.47     10053493.73       2617055.7     10053388.43
      2617243.84     10053347.05      2617368.69     10053285.06
      2617488.02     10053285.25       2617539.5     10053320.45
      2617619.02     10053313.49      2617664.11     10053342.93
       2617918.6     10053347.97      2618113.98     10053265.77
      2618343.05     10053263.12      2618573.37     10053223.72
      2618763.44     10053259.41      2618822.69     10053245.74
      2618987.11     10053287.02       2619111.4     10053328.02
      2619238.47     10053413.73      2619477.03     10053497.15
      2619760.09     10053639.97       2619812.4     10053630.82
      2619983.46     10053664.05      2620727.36     10053451.05
      2620998.67     10053304.71      2621228.13     10053305.02
      2621387.29     10053326.57      2621524.06     10053371.88
      2621813.23     10053384.36      2621886.74     10053410.58
       2622113.3     10053403.17      2622258.47     10053373.73

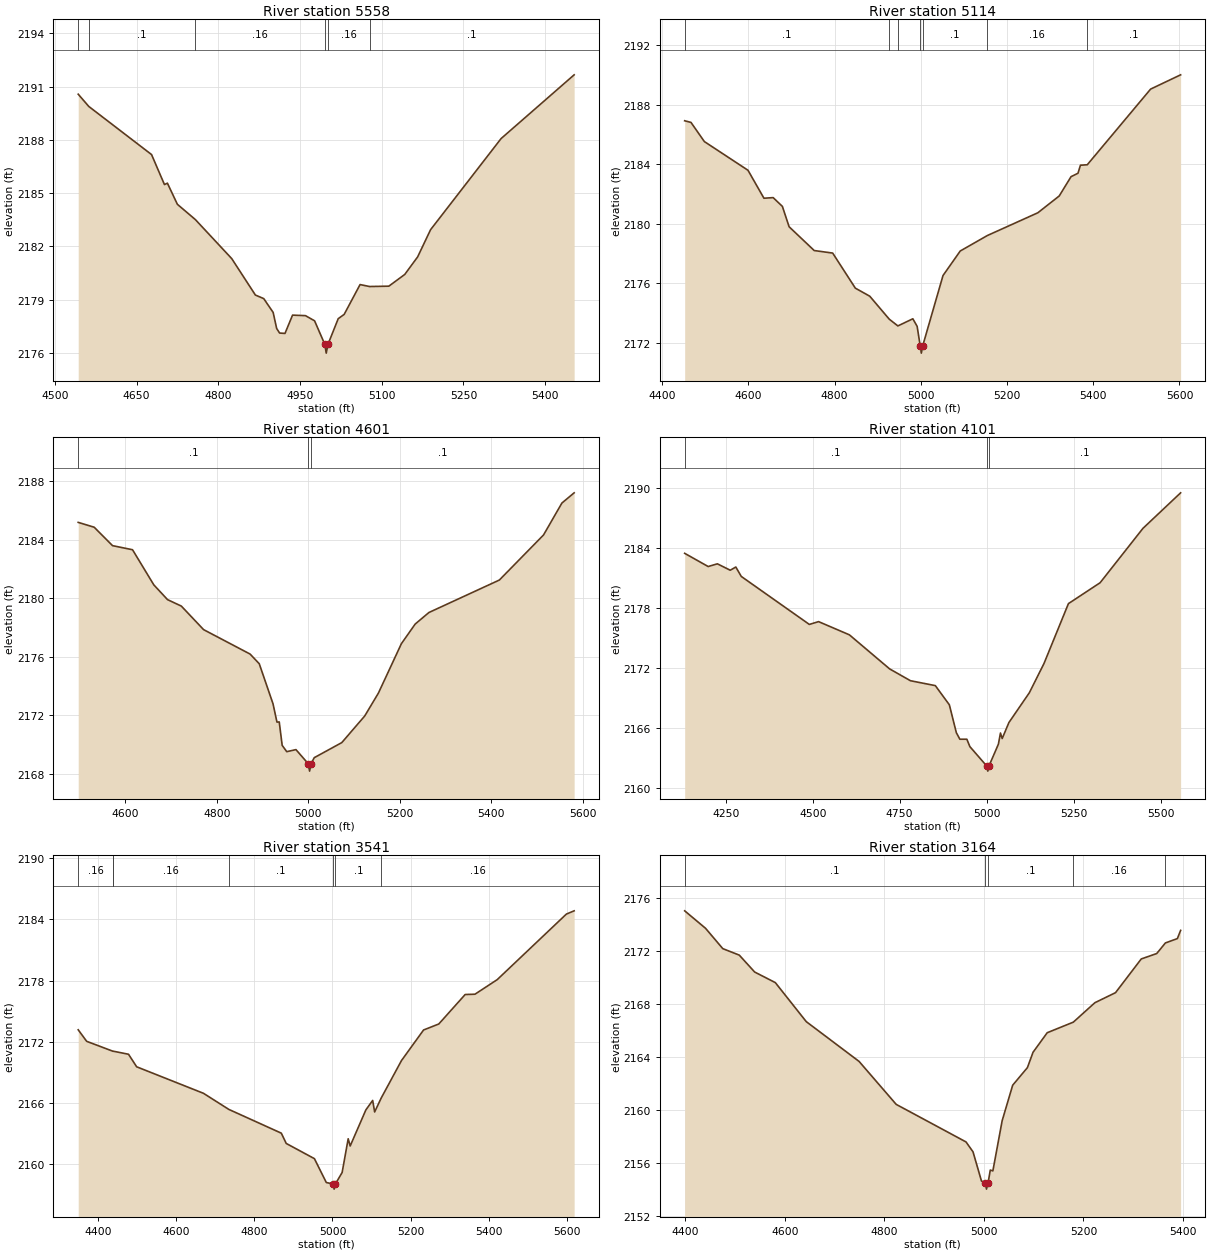
Type RM Length L Ch R = 1 ,5558    ,444,444,444
BEGIN DESCRIPTION:
UNT 1071 IN HEWA 12.0
END DESCRIPTION:
XS GIS Cut Line= 2
      2617175.56     10053843.33      2616821.42     10053004.85
#Sta/Elev= 30
  4542.9 2190.57  4562.3 2189.88  4677.5 2187.17  4701.2 2185.48  4706.6 2185.56
  4724.9 2184.37  4757.9 2183.51  4824.7 2181.31  4868.1 2179.26  4883.4 2179.06
  4900.7 2178.28  4907.1 2177.38  4912.5 2177.12  4922.4  2177.1  4936.3 2178.13
    4960  2178.1  4976.7 2177.81  4995.4 2176.49  4998.1 2175.99  5001.4 2176.49
  5020.1 2177.93    5031 2178.17  5060.2 2179.85  5077.7 2179.74    5113 2179.76
  5142.2 2180.42  5165.9 2181.41  5189.6 2182.94    5319 2188.07  5453.1 2191.66
#Mann= 6 ,-1 , 0
  4542.9     .16       0  4562.3      .1       0  4757.9     .16       0
  4995.4     .07       0  5001.4     .16       0  5077.7      .1       0
Bank Sta=4995.4,5001.4
XS Rating Curve= 0 ,0
Exp/Cntr=0.3,0.1

Type RM Length L Ch R = 1 ,5114    ,513,513,513
BEGIN DESCRIPTION:
UNT 1071 IN HEWA 11.0
END DESCRIPTION:
XS GIS Cut Line= 4
      2617618.29     10053775.66      2617409.95      10053426.7
      2617409.95     10052973.57      2617269.44     10052718.57
#Sta/Elev= 30
    4452 2186.93  4466.6 2186.82  4497.7 2185.53  4598.9  2183.6  4635.9 2181.72
  4657.3 2181.76  4678.7 2181.17  4694.3  2179.8  4752.6  2178.2  4795.4 2178.03
    4848 2175.67  4881.4 2175.13  4926.8 2173.58  4946.7 2173.13  4981.4 2173.61
  4991.4  2173.1  4998.4  2171.8  5001.1  2171.3  5004.4  2171.8  5051.4 2176.52
  5091.4 2178.17  5154.3 2179.21  5271.4 2180.74    5321 2181.87  5348.5 2183.17
  5364.6  2183.4  5370.3 2183.94  5386.1 2183.97  5533.1 2189.06  5602.7 2190.02
#Mann= 7 ,-1 , 0
    4452      .1       0  4926.8     .16       0  4946.7      .1       0
  4998.4     .07       0  5004.4      .1       0  5154.3     .16       0
  5386.1      .1       0
Bank Sta=4998.4,5004.4
XS Rating Curve= 0 ,0
Exp/Cntr=0.3,0.1

Type RM Length L Ch R = 1 ,4601    ,500,500,500
BEGIN DESCRIPTION:
UNT 1071 IN HEWA 10.0
END DESCRIPTION:
XS GIS Cut Line= 2
      2617930.79     10053848.57      2617863.19     10052766.98
#Sta/Elev= 30
  4497.4 2185.18  4532.3 2184.85  4572.4 2183.59  4616.1 2183.31  4662.6 2180.91
  4692.6  2179.9  4722.7 2179.46  4771.4 2177.85    4873 2176.18    4893 2175.52
  4923.1 2172.78  4931.7 2171.53  4936.7 2171.54  4943.1 2169.94  4953.1 2169.51
  4973.2 2169.65  5000.2 2168.68    5003 2168.18  5006.2 2168.68  5013.2  2169.1
  5073.4 2170.13  5123.5 2171.95  5153.5 2173.52  5203.6 2176.89  5233.7 2178.23
  5263.7 2179.02  5417.7 2181.24  5514.2 2184.32  5554.3  2186.5  5581.1  2187.2
#Mann= 3 ,-1 , 0
  4497.4      .1       0  5000.2     .07       0  5006.2      .1       0
Bank Sta=5000.2,5006.2
XS Rating Curve= 0 ,0
Exp/Cntr=0.3,0.1

Type RM Length L Ch R = 1 ,4101    ,560,560,560
BEGIN DESCRIPTION:
UNT 1071 IN HEWA 9.0
END DESCRIPTION:
XS GIS Cut Line= 4
      2618222.47     10054093.33      2618409.95     10053525.66
      2618342.25     10052952.74      2618285.05     10052708.38
#Sta/Elev= 30
    4132  2183.5  4199.5 2182.18    4226 2182.45    4263 2181.81    4279 2182.13
  4294.7 2181.19  4490.4 2176.39  4516.9 2176.67  4605.5 2175.35  4721.3 2171.94
  4781.1 2170.76  4852.6 2170.27  4892.9 2168.35    4913 2165.56  4923.1 2164.91
  4943.2 2164.91  4951.9 2164.17  5000.6 2162.22  5003.4 2161.72  5006.6 2162.22
  5033.9 2164.42  5039.8 2165.53  5044.8 2164.98  5064.1 2166.58  5122.7 2169.55
  5164.8 2172.47  5235.2 2178.47  5326.3 2180.56  5449.5    2186  5557.7 2189.55
#Mann= 3 ,-1 , 0
    4132      .1       0  5000.6     .07       0  5006.6      .1       0
Bank Sta=5000.6,5006.6
XS Rating Curve= 0 ,0
Exp/Cntr=0.3,0.1

Type RM Length L Ch R = 1 ,3541    ,377,377,377
BEGIN DESCRIPTION:
UNT 1071 IN HEWA 8.0
END DESCRIPTION:
XS GIS Cut Line= 4
      2618560.98     10053806.92      2618899.54     10053390.24
      2618956.83     10053025.66      2618878.71     10052671.51
#Sta/Elev= 30
  4349.6 2173.17  4371.2 2172.04  4438.8 2171.06  4439.3 2171.07  4478.3 2170.77
  4499.1 2169.54    4670 2166.94  4734.9 2165.36  4869.1 2163.03  4881.7 2162.02
  4953.8 2160.53  4984.2 2158.19  5001.4 2158.04  5004.2 2157.54  5007.4 2158.04
  5024.7 2159.17  5040.2 2162.48  5045.3 2161.77  5085.4 2165.31  5102.8 2166.24
  5107.9 2165.11  5124.6 2166.47  5176.5 2170.15    5233 2173.15    5272 2173.74
  5339.4 2176.63  5364.5 2176.66  5421.4 2178.09  5598.3 2184.52  5618.2 2184.84
#Mann= 7 ,-1 , 0
  4349.6     .16       0  4438.8      .1       0  4439.3     .16       0
  4734.9      .1       0  5001.4     .07       0  5007.4      .1       0
  5124.6     .16       0
Bank Sta=5001.4,5007.4
XS Rating Curve= 0 ,0
Exp/Cntr=0.3,0.1

Type RM Length L Ch R = 1 ,3164    ,438,438,438
BEGIN DESCRIPTION:
UNT 1071 IN HEWA 7.0
END DESCRIPTION:
XS GIS Cut Line= 2
      2619102.67     10053999.59      2619362.72     10053037.42
#Sta/Elev= 30
  4398.6 2175.06  4440.5 2173.74  4475.2  2172.2  4508.3 2171.71  4539.3 2170.43
  4580.8 2169.63  4642.9 2166.68  4749.1 2163.67  4823.7 2160.42    4964 2157.58
  4978.1 2156.83  4995.1 2154.62  5002.5 2154.51  5005.2 2154.01  5008.5 2154.51
  5012.8 2155.45    5018 2155.39  5036.6 2159.18  5057.8 2161.87  5087.4  2163.2
  5098.7 2164.36  5127.2 2165.84  5179.7 2166.64    5223 2168.11  5264.5 2168.87
  5316.2 2171.42  5347.3 2171.83  5364.7 2172.63  5388.8 2172.96  5395.3 2173.58
#Mann= 5 ,-1 , 0
  4398.6      .1       0  5002.5     .07       0  5008.5      .1       0
  5179.7     .16       0  5364.7      .1       0
Bank Sta=5002.5,5008.5
XS Rating Curve= 0 ,0
Exp/Cntr=0.3,0.1

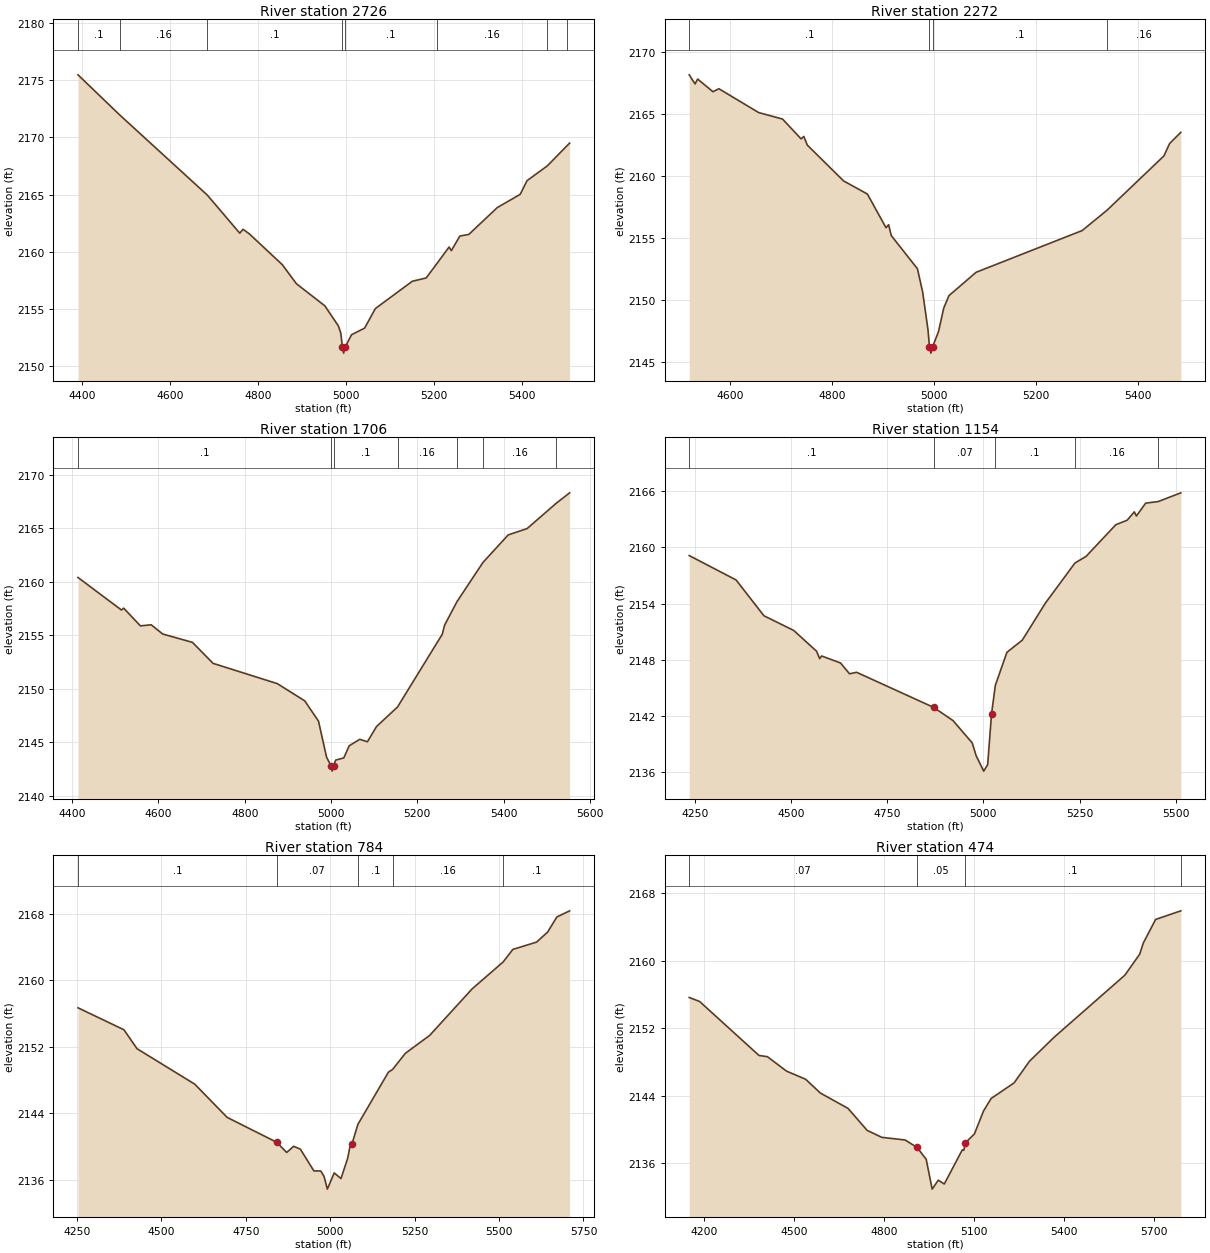
Type RM Length L Ch R = 1 ,2726    ,454,454,454
BEGIN DESCRIPTION:
UNT 1071 IN HEWA 6.0
END DESCRIPTION:
XS GIS Cut Line= 3
      2619425.59     10054155.85      2619712.04      10053426.7
      2619774.51      10053098.7
#Sta/Elev= 30
  4391.4 2175.48  4485.9 2171.98  4685.4 2164.95    4759 2161.62  4766.4 2161.96
  4780.5 2161.57  4855.8 2158.86  4887.9 2157.19  4952.4 2155.26  4983.2  2153.5
  4988.6 2152.88  4992.3 2151.62  4995.1 2151.12  4998.3 2151.62    5013 2152.73
  5042.8 2153.31  5067.2 2155.02  5151.2 2157.41  5182.7  2157.7  5207.5 2158.98
  5234.8 2160.41  5239.9 2160.09  5259.3 2161.37  5279.6 2161.51  5344.3 2163.86
  5396.4 2165.02    5412 2166.22    5458 2167.51  5501.9 2169.24  5508.7  2169.5
#Mann= 8 ,-1 , 0
  4391.4      .1       0  4485.9     .16       0  4685.4      .1       0
  4992.3     .07       0  4998.3      .1       0  5207.5     .16       0
    5458      .1       0  5501.9     .16       0
Bank Sta=4992.3,4998.3
XS Rating Curve= 0 ,0
Exp/Cntr=0.3,0.1

Type RM Length L Ch R = 1 ,2272    ,566,566,566
BEGIN DESCRIPTION:
UNT 1071 IN HEWA 5.0
END DESCRIPTION:
XS GIS Cut Line= 2
      2620196.42       10054109.      2619967.25     10053171.51
#Sta/Elev= 30
  4519.8 2168.16  4531.3 2167.43  4536.4 2167.82  4566.4  2166.8  4578.1 2167.04
  4656.2 2165.12    4703  2164.6  4739.5    2163  4744.7  2163.2  4751.7  2162.5
  4822.8 2159.62  4869.6 2158.56  4906.1 2155.85  4911.3 2156.09  4916.4 2155.22
  4967.9 2152.54  4978.2 2150.64  4988.5 2147.65  4991.5 2146.25  4994.3 2145.75
  4997.5 2146.25  5009.1 2147.47  5019.4 2149.37  5029.7 2150.38    5083 2152.26
  5291.2 2155.62  5340.1 2157.26  5451.7 2161.63  5462.9 2162.63  5484.9 2163.53
#Mann= 4 ,-1 , 0
  4519.8      .1       0  4991.5     .07       0  4997.5      .1       0
  5340.1     .16       0
Bank Sta=4991.5,4997.5
XS Rating Curve= 0 ,0
Exp/Cntr=0.3,0.1

Type RM Length L Ch R = 1 ,1706    ,552,552,552
BEGIN DESCRIPTION:
UNT 1071 IN HEWA 4.0
END DESCRIPTION:
XS GIS Cut Line= 2
      2620805.78     10054041.25      2620451.75     10052958.35
#Sta/Elev= 30
  4413.6 2160.39  4514.3 2157.35  4519.5 2157.52  4558.3 2155.87  4583.3 2155.97
  4609.9 2155.11  4678.9 2154.33  4726.6 2152.37  4875.4 2150.48  4939.1 2148.87
    4971 2146.97  4989.6 2143.62  4999.9 2142.81  5002.6 2142.31  5005.9 2142.81
  5010.7 2143.34  5029.5 2143.54  5042.2 2144.68  5066.6 2145.28  5084.3 2145.05
  5105.4 2146.47  5154.1  2148.3  5257.8 2155.09  5263.2 2155.94    5292 2158.14
  5352.1 2161.79  5410.5 2164.36  5454.3 2164.95  5521.7 2167.31  5552.9 2168.29
#Mann= 7 ,-1 , 0
  4413.6      .1       0  4999.9     .07       0  5005.9      .1       0
  5154.1     .16       0    5292      .1       0  5352.1     .16       0
  5521.7      .1       0
Bank Sta=4999.9,5005.9
XS Rating Curve= 0 ,0
Exp/Cntr=0.3,0.1

Type RM Length L Ch R = 1 ,1154    ,370,370,370
BEGIN DESCRIPTION:
UNT 1071 IN HEWA 3.0
END DESCRIPTION:
XS GIS Cut Line= 4
      2620998.49     10054051.72       2621123.5     10053619.41
      2621133.91     10053067.32      2621029.73     10052812.07
#Sta/Elev= 30
  4235.4 2159.13  4357.2 2156.53  4429.6 2152.71  4507.2 2151.14  4566.4 2148.93
  4574.5 2148.14  4579.7 2148.42  4628.9 2147.67  4652.1 2146.52  4670.5 2146.68
  4871.1 2142.93  4921.1 2141.53  4971.1 2139.15  4981.1  2137.8  5000.9 2136.14
  5011.2 2136.83  5021.2 2142.22  5031.2  2145.3  5061.2 2148.81  5101.2 2150.11
  5161.2 2154.06  5238.2 2158.34  5266.9 2159.04  5344.4 2162.42  5373.8  2162.9
  5392.4 2163.79  5397.8 2163.35  5421.9 2164.72  5454.5 2164.89  5513.3 2165.82
#Mann= 5 ,-1 , 0
  4235.4      .1       0  4871.1     .07       0  5031.2      .1       0
  5238.2     .16       0  5454.5      .1       0
Bank Sta=4871.1,5021.2
XS Rating Curve= 0 ,0
Exp/Cntr=0.3,0.1

Type RM Length L Ch R = 1 ,784     ,310,310,310
BEGIN DESCRIPTION:
UNT 1071 IN HEWA 2.0
END DESCRIPTION:
XS GIS Cut Line= 4
      2621222.46     10054051.69      2621472.45     10053562.11
      2621508.91      10053114.2      2621373.82     10052677.74
#Sta/Elev= 30
    4253 2156.67  4389.1 2154.03  4427.9 2151.75  4598.8 2147.49  4694.6  2143.5
  4841.2 2140.51  4871.3 2139.28  4891.4 2140.02  4911.5 2139.68  4951.6 2137.06
  4971.7 2137.06  4981.7 2136.41  4991.5 2134.87  5011.8 2136.82  5031.9 2136.14
  5051.9 2138.61  5059.3 2140.17  5064.3 2140.28    5082 2142.66  5172.3 2148.93
  5184.7 2149.26  5222.5  2151.2  5294.5 2153.35  5420.1 2158.94  5512.3 2162.19
  5540.8 2163.69  5611.2 2164.57  5643.9 2165.78  5671.2 2167.59    5709 2168.33
#Mann= 5 ,-1 , 0
    4253      .1       0  4841.2     .07       0    5082      .1       0
  5184.7     .16       0  5512.3      .1       0
Bank Sta=4841.2,5064.3
XS Rating Curve= 0 ,0
Exp/Cntr=0.3,0.1

Type RM Length L Ch R = 1 ,474     ,338,338,338
BEGIN DESCRIPTION:
Mapping XS 3714e4a5
END DESCRIPTION:
XS GIS Cut Line= 4
       2621342.6     10054056.86      2621769.71     10053627.15
      2621813.98      10053223.5      2621673.42     10052611.78
#Sta/Elev= 30
  4149.1 2155.65  4183.7 2155.18  4381.7 2148.79    4410 2148.64  4473.7 2146.93
  4537.3 2145.97  4586.8 2144.33  4678.7 2142.52  4742.4 2139.92  4791.5 2139.09
  4869.1 2138.78  4909.3 2137.89  4939.5 2136.49  4959.4 2132.96  4979.7 2134.02
  4999.8 2133.57  5059.9 2137.61  5064.9 2137.56  5070.3 2138.45  5100.4  2139.5
  5130.6 2142.21    5156 2143.69  5232.6 2145.54  5283.9  2148.1    5366 2150.94
    5602 2158.29  5651.4 2160.77  5663.6  2162.1  5704.6 2164.89  5788.7 2165.91
#Mann= 4 ,-1 , 0
  4149.1     .07       0  4909.3     .05       0  5070.3      .1       0
  5788.7      .1       0
Bank Sta=4909.3,5070.3
XS Rating Curve= 0 ,0
Exp/Cntr=0.3,0.1

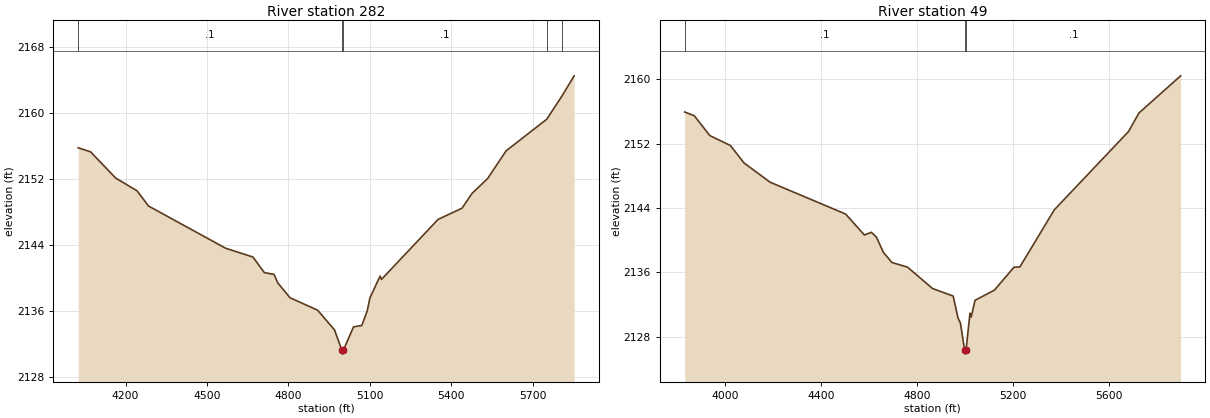
Type RM Length L Ch R = 1 ,282     ,233,233,233
BEGIN DESCRIPTION:
Mapping XS b92a1797
END DESCRIPTION:
XS GIS Cut Line= 4
      2621356.69     10054086.18      2621964.34     10053596.59
        2622006.     10053120.89      2621821.99     10052582.74
#Sta/Elev= 30
  4025.8 2155.76  4071.3 2155.27    4164 2152.08  4242.4 2150.54  4284.9 2148.69
  4568.8 2143.57  4669.5  2142.5  4711.1 2140.62  4747.2 2140.39  4760.7 2139.37
  4806.1 2137.56  4907.6 2136.05  4969.6 2133.67  4996.7 2131.22  4999.5 2130.72
  5002.7 2131.22  5039.9 2134.03    5070 2134.19  5090.1 2135.94  5100.1 2137.53
  5137.6 2140.19  5142.6 2139.78  5351.3 2147.07  5439.2 2148.42  5476.6 2150.23
  5533.9 2152.03  5601.8 2155.39  5751.4 2159.22  5807.3 2162.03  5852.4 2164.49
#Mann= 5 ,-1 , 0
  4025.8      .1       0  4996.7     .07       0  5002.7      .1       0
  5751.4     .16       0  5807.3      .1       0
Bank Sta=4996.7,5002.7
XS Rating Curve= 0 ,0
Exp/Cntr=0.3,0.1

Type RM Length L Ch R = 1 ,49      ,0,0,0
BEGIN DESCRIPTION:
UNT 1071 IN HEWA 1.0
END DESCRIPTION:
XS GIS Cut Line= 4
      2621360.13     10054121.79      2622190.03     10053507.18
      2622245.59     10053135.65      2621915.75     10052569.72
#Sta/Elev= 30
  3833.2 2155.91  3873.3 2155.44    3938 2152.98  4023.6 2151.75    4080 2149.59
  4188.5  2147.2  4503.1 2143.24  4580.8 2140.65  4610.1 2140.98  4630.9 2140.39
  4660.2 2138.48  4695.6 2137.23  4760.3 2136.66  4864.6    2134  4950.3 2133.07
  4970.5 2130.33  4980.6 2129.71  4997.8 2126.36  5000.6 2125.86  5003.8 2126.36
  5020.2 2130.94  5025.2 2130.46  5041.3 2132.54  5122.2 2133.81  5203.1 2136.64
  5227.8 2136.68  5371.1 2143.77  5680.3  2153.5  5723.3 2155.79  5896.6  2160.4
#Mann= 3 ,-1 , 0
  3833.2      .1       0  4997.8     .07       0  5003.8      .1       0
Bank Sta=4997.8,5003.8
XS Rating Curve= 0 ,0
Exp/Cntr=0.3,0.1

Chan Stop Cuts=-1
Use User Specified Reach Order=0
Composite Channel Slope=5