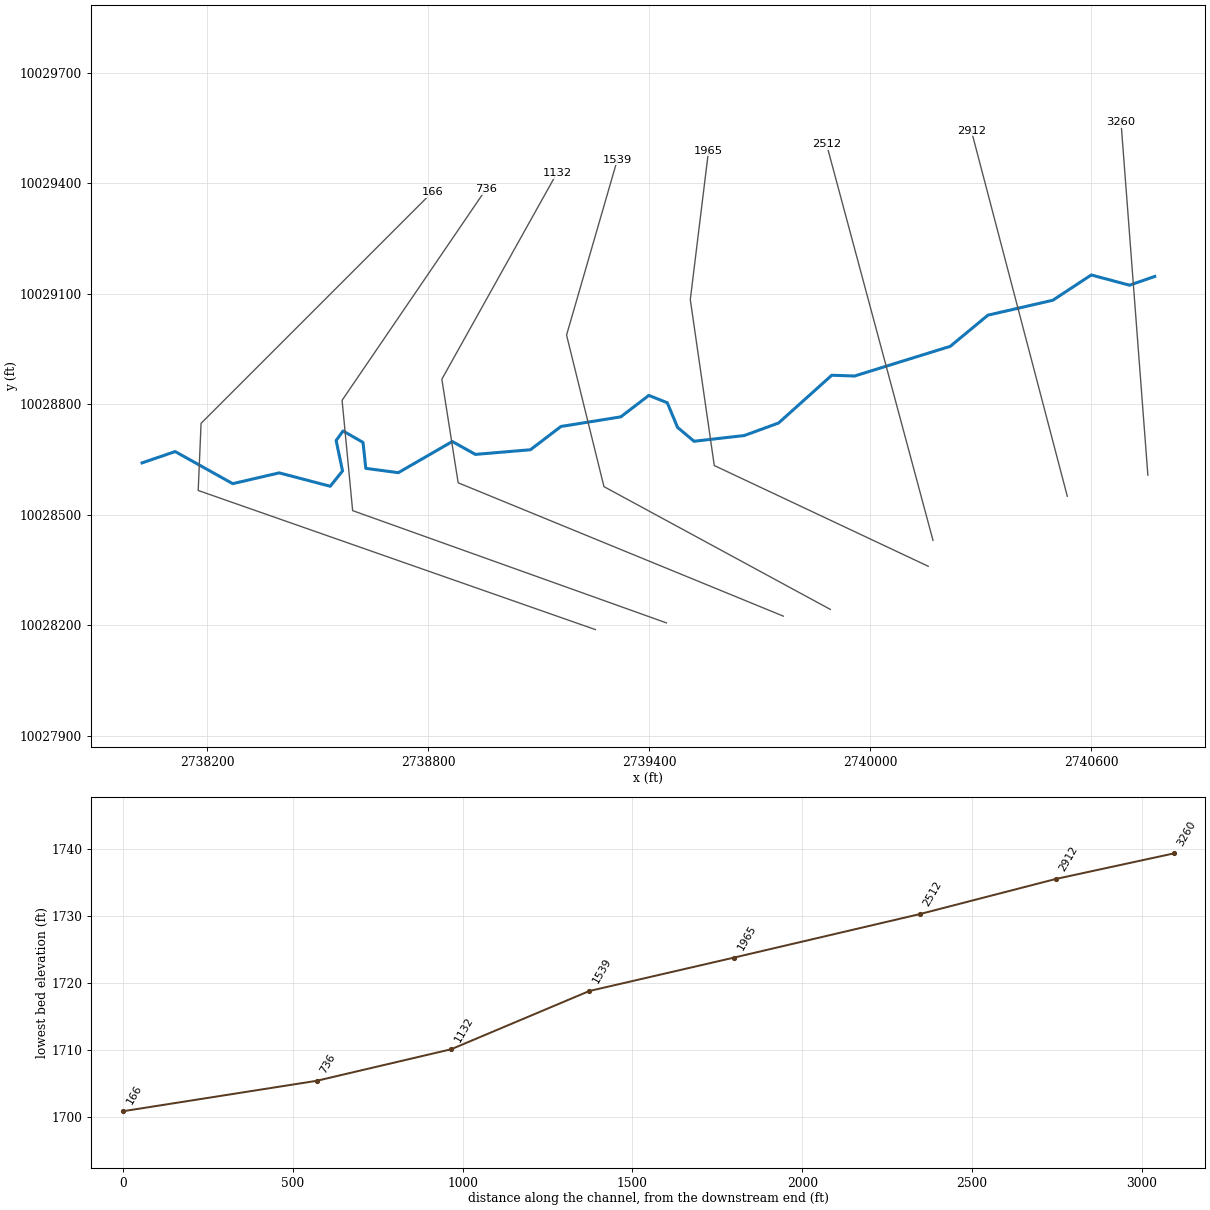
--- UNT 1072 IN HEWA.prj (project) ---

Proj Title=UNT 1072 IN HEWA Base Level Engineering
Current Plan=p01
Default Exp/Contr=0.3,0.1
English Units
Geom File=g01
Flow File=f01
Plan File=p01
Y Axis Title=Elevation
X Axis Title(PF)=Main Channel Distance
X Axis Title(XS)=Station
BEGIN DESCRIPTION:
UNT 1072 IN HEWA
END DESCRIPTION:
DSS Export Rating Curves= 0
DSS Export Rating Curve Sorted= 0
DSS Export Volume Flow Curves= 0
DXF OffsetX= 0
DXF OffsetY= 0
DXF ScaleX= 1
DXF ScaleY= 10

--- UNT 1072 IN HEWA.p01 (plan) ---

Plan Title=Multiple Run
Short Identifier=Multiple
Geom File=g01
Flow File=f01
Subcritical Flow
K Sum by GR= 0
Std Step Tol= 0.01
Critical Tol= 0.01
Num of Std Step Trials= 20
Max Error Tol= 0.3
Flow Tol Ratio= 0.001
Split Flow NTrial= 30
Split Flow Tol= 0.02
Split Flow Ratio= 0.02
Log Output Level= 0
Friction Slope Method= 1
Unsteady Friction Slope Method= 2
Unsteady Bridges Friction Slope Method= 1
Parabolic Critical Depth
Global Vel Dist=  1 , 1 , 1
Global Log Level= 0
CheckData=True
Encroach Param= -1, 0, 0, 0
BEGIN DESCRIPTION:
Multiple Run
END DESCRIPTION:

--- UNT 1072 IN HEWA.f01 (steady flow) ---

Flow Title=Multiple
Number of Profiles=7
Profile Names=10-year,25-year,50-year,1pct_min,100-year,1pct_plu,500-year
River Rch & RM= UNT 1072 IN HEWA,Reach-1,3260
     737    1063    1345    1247    1686    2280    2661
Boundary for River Rch & Prof#=UNT 1072 IN HEWA,Reach-1,1
Up Type=0
Dn Type=3
Dn Slope=0.005
Boundary for River Rch & Prof#=UNT 1072 IN HEWA,Reach-1,2
Up Type=0
Dn Type=3
Dn Slope=0.005
Boundary for River Rch & Prof#=UNT 1072 IN HEWA,Reach-1,3
Up Type=0
Dn Type=3
Dn Slope=0.005
Boundary for River Rch & Prof#=UNT 1072 IN HEWA,Reach-1,4
Up Type=0
Dn Type=3
Dn Slope=0.005
Boundary for River Rch & Prof#=UNT 1072 IN HEWA,Reach-1,5
Up Type=0
Dn Type=3
Dn Slope=0.005
Boundary for River Rch & Prof#=UNT 1072 IN HEWA,Reach-1,6
Up Type=0
Dn Type=3
Dn Slope=0.005
Boundary for River Rch & Prof#=UNT 1072 IN HEWA,Reach-1,7
Up Type=0
Dn Type=3
Dn Slope=0.005

--- UNT 1072 IN HEWA.g01 (geometry) ---

Geom Title=Existing Conditions

River Reach=UNT 1072 IN HEWA,Reach-1
Reach XY= 30
      2740772.18     10029147.16      2740703.60     10029123.38
      2740599.79     10029151.19      2740495.39     10029082.53
      2740319.18     10029042.00      2740216.95     10028957.39
      2739957.20     10028876.86      2739895.32     10028878.96
      2739750.91     10028749.32      2739657.83     10028715.25
      2739521.38     10028699.72      2739476.63     10028737.40
      2739448.67     10028804.35      2739398.68     10028824.22
      2739322.46     10028765.92      2739160.09     10028739.86
      2739077.24     10028676.68      2738927.75     10028664.04
      2738865.17     10028699.02      2738718.55     10028614.43
      2738630.32     10028626.12      2738622.79     10028696.55
      2738568.46     10028727.75      2738549.79     10028701.66
      2738567.12     10028619.06      2738533.79     10028577.54
      2738395.22     10028613.90      2738269.05     10028584.58
      2738112.79     10028671.75      2738022.88     10028640.98

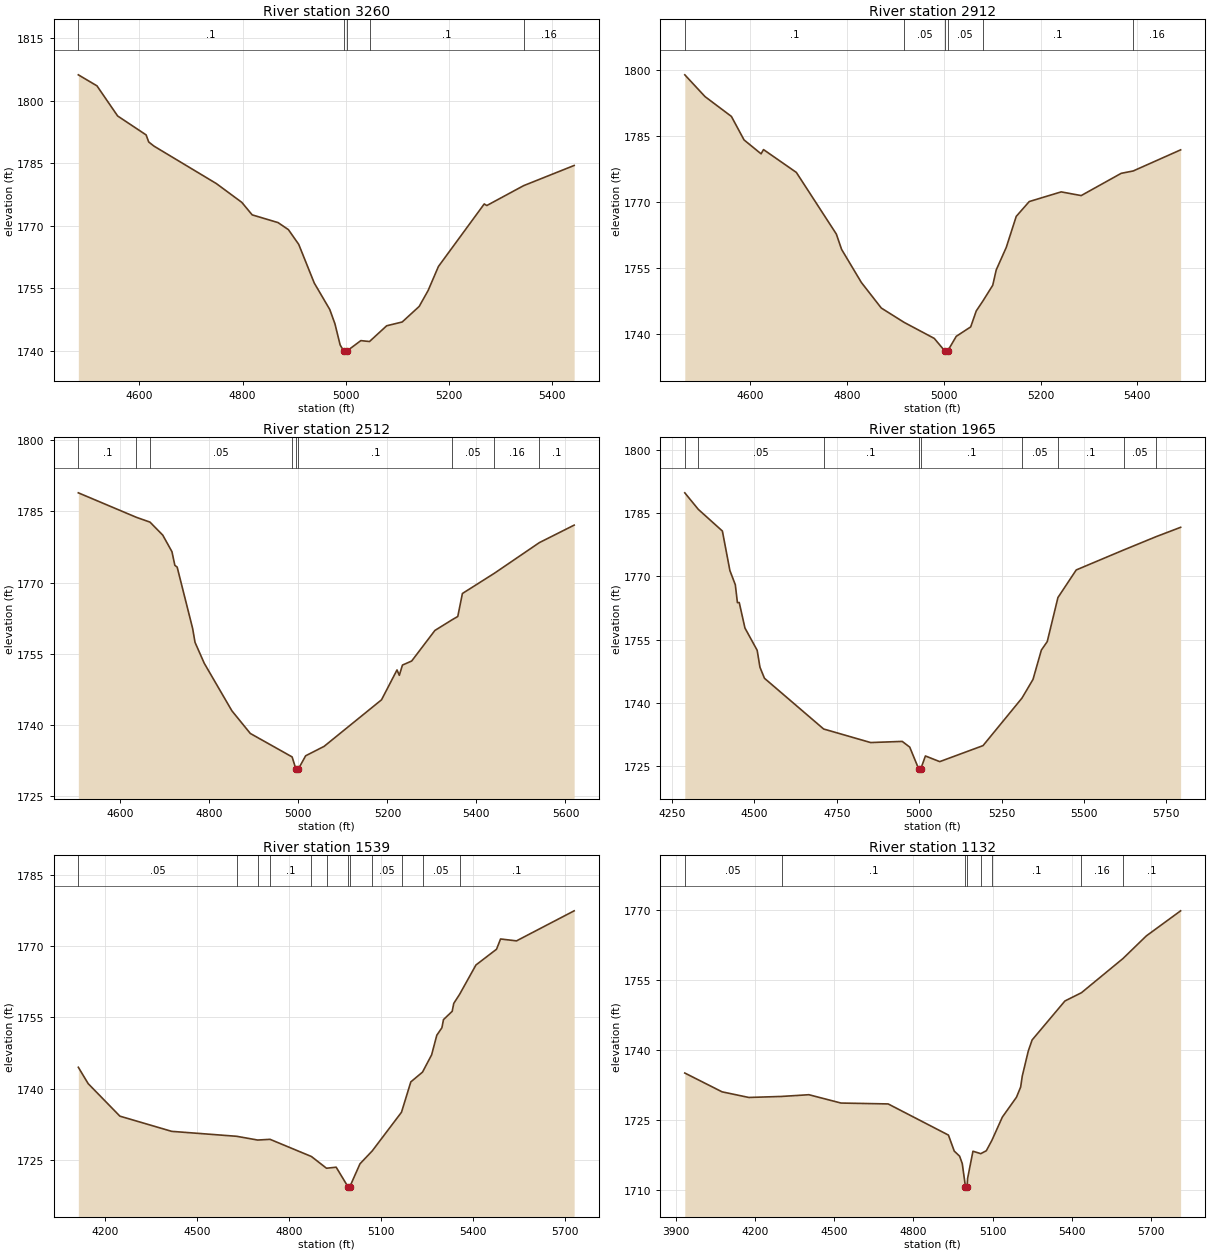
Type RM Length L Ch R = 1,3260,348,348,348
BEGIN DESCRIPTION:
UNT 1072 IN HEWA 5.0
END DESCRIPTION:
XS GIS Cut Line= 2
      2740753.43     10028607.72      2740680.51     10029566.05
#Sta/Elev= 30
  4481.7 1806.16  4517.8 1803.52  4557.9 1796.29  4613.1 1791.75  4618.1 1790.06
  4628.1 1789.08  4749.2 1780.08  4798.6 1775.57  4818.7 1772.57  4868.8 1770.72
  4888.9 1769.03  4908.9 1765.50  4939.0 1756.23  4969.1 1749.87  4979.1 1746.45
  4989.2 1741.37  4996.2 1739.91  4999.0 1739.41  5002.2 1739.91  5029.3 1742.41
  5046.1 1742.19  5079.4 1745.97  5109.5 1746.88  5142.4 1750.61  5159.7 1754.42
  5179.7 1760.19  5268.5 1775.19  5273.5 1774.81  5344.9 1779.58  5442.8 1784.42
#Mann=5,-1,0
  4481.7     0.1       0  4996.2    0.07       0  5002.2    0.05       0
  5046.1     0.1       0  5344.9    0.16       0
Bank Sta=4996.2,5002.2
Exp/Cntr=0.3,0.1

Type RM Length L Ch R = 1,2912,400,400,400
BEGIN DESCRIPTION:
Mapping XS 3551a89e
END DESCRIPTION:
XS GIS Cut Line= 2
      2740534.67     10028550.51      2740274.25     10029542.70
#Sta/Elev= 30
  4464.1 1798.89  4505.9 1793.94  4560.5 1789.43  4586.7 1784.08  4621.9 1780.92
  4627.0 1781.88  4694.9 1776.69  4777.6 1762.67  4788.5 1759.18  4829.3 1751.67
  4870.6 1745.84  4918.1 1742.56  4980.1 1738.94  5002.0 1736.08  5004.8 1735.58
  5008.0 1736.08  5025.7 1739.40  5055.6 1741.55  5067.1 1745.18  5080.8 1747.43
  5101.2 1751.02  5108.4 1754.51  5129.1 1759.61  5149.8 1766.69  5176.7 1770.06
  5242.8 1772.26  5284.2 1771.42  5366.9 1776.48  5391.8 1777.02  5489.9 1781.82
#Mann=6,-1,0
  4464.1     0.1       0  4918.1    0.05       0  5002.0   0.035       0
  5008.0    0.05       0  5080.8     0.1       0  5391.8    0.16       0
Bank Sta=5002,5008
Exp/Cntr=0.3,0.1

Type RM Length L Ch R = 1,2512,547,547,547
BEGIN DESCRIPTION:
UNT 1072 IN HEWA 4.0
END DESCRIPTION:
XS GIS Cut Line= 2
      2740170.10     10028430.64      2739881.04     10029506.17
#Sta/Elev= 30
  4505.8 1788.91  4636.3 1783.75  4666.7 1782.75  4695.4 1780.01  4716.1 1776.52
  4722.6 1773.65  4727.8 1773.27  4762.6 1760.34  4767.9 1757.44  4788.6 1753.04
  4850.7 1743.03  4892.1 1738.26  4986.0 1733.32  4994.3 1730.83  4997.0 1730.33
  5000.3 1730.83  5016.4 1733.56  5057.8 1735.54  5186.8 1745.34  5221.6 1751.63
  5226.8 1750.50  5233.8 1752.65  5254.6 1753.51  5306.7 1759.94  5345.2 1762.18
  5358.1 1762.88  5368.5 1767.72  5440.5 1771.99  5541.2 1778.42  5619.5 1782.11
#Mann=9,-1,0
  4505.8     0.1       0  4636.3    0.16       0  4666.7    0.05       0
  4986.0     0.1       0  4994.3    0.07       0  5000.3     0.1       0
  5345.2    0.05       0  5440.5    0.16       0  5541.2     0.1       0
Bank Sta=4994.3,5000.3
Exp/Cntr=0.3,0.1

Type RM Length L Ch R = 1,1965,426,426,426
BEGIN DESCRIPTION:
UNT 1072 IN HEWA 3.0
END DESCRIPTION:
XS GIS Cut Line= 4
      2740157.07     10028360.37      2739576.34     10028633.80
      2739511.24     10029084.32      2739560.72     10029488.02
#Sta/Elev= 30
  4289.3 1789.75  4330.3 1785.83  4403.3 1780.70  4426.1 1771.33  4442.5 1767.98
  4448.9 1763.74  4454.4 1763.76  4471.7 1757.73  4508.8 1752.44  4517.3 1748.42
  4530.9 1745.82  4710.4 1733.80  4852.9 1730.59  4948.8 1730.86  4971.5 1729.51
  4998.8 1724.32  5001.6 1723.82  5004.8 1724.32  5019.1 1727.41  5062.5 1726.07
  5193.8 1729.86  5311.9 1741.12  5345.4 1745.55  5370.7 1752.49  5388.6 1754.51
  5421.0 1764.94  5476.5 1771.48  5620.3 1776.21  5719.9 1779.40  5793.1 1781.58
#Mann=9,-1,0
  4289.3     0.1       0  4330.3    0.05       0  4710.4     0.1       0
  4998.8    0.07       0  5004.8     0.1       0  5311.9    0.05       0
  5421.0     0.1       0  5620.3    0.05       0  5719.9     0.1       0
Bank Sta=4998.8,5004.8
Exp/Cntr=0.3,0.1

Type RM Length L Ch R = 1,1539,407,407,407
BEGIN DESCRIPTION:
UNT 1072 IN HEWA 2.0
END DESCRIPTION:
XS GIS Cut Line= 4
      2739891.41     10028243.20      2739276.86     10028576.51
      2739175.30     10028987.97      2739313.33     10029464.56
#Sta/Elev= 30
  4112.2 1744.49  4144.4 1741.04  4248.0 1734.19  4417.2 1730.99  4629.4 1729.95
  4697.8 1729.16  4738.3 1729.31  4873.4 1725.69  4922.6 1723.22  4954.2 1723.44
  4992.7 1719.32  4995.5 1718.82  4998.7 1719.32  5032.0 1724.16  5071.8 1726.86
  5167.5 1735.02  5197.9 1741.41  5236.1 1743.47  5265.8 1747.10  5282.8 1751.25
  5299.4 1752.81  5304.6 1754.53  5333.0 1756.28  5338.2 1757.95  5357.4 1759.88
  5410.6 1766.04  5477.8 1769.36  5491.0 1771.52  5543.0 1771.12  5731.3 1777.45
#Mann=12,-1,0
  4112.2    0.05       0  4629.4     0.1       0  4697.8    0.16       0
  4738.3     0.1       0  4873.4    0.16       0  4922.6     0.1       0
  4992.7    0.07       0  4998.7     0.1       0  5071.8    0.05       0
  5167.5     0.1       0  5236.1    0.05       0  5357.4     0.1       0
Bank Sta=4992.7,4998.7
Exp/Cntr=0.3,0.1

Type RM Length L Ch R = 1,1132,396,396,396
BEGIN DESCRIPTION:
Mapping XS 141b396a
END DESCRIPTION:
XS GIS Cut Line= 4
      2739763.82     10028224.96      2738881.03     10028586.93
      2738836.76     10028868.18      2739149.24     10029428.04
#Sta/Elev= 30
  3933.0 1735.04  4074.3 1731.00  4175.7 1729.79  4300.3 1730.01  4403.5 1730.38
  4525.3 1728.59  4704.1 1728.40  4932.6 1721.71  4954.7 1718.27  4975.0 1717.18
  4985.1 1715.58  4997.2 1710.60  4999.9 1710.10  5003.2 1710.60  5005.4 1712.43
  5025.6 1718.24  5055.3 1717.72  5076.2 1718.34  5097.4 1720.58  5137.0 1725.57
  5190.5 1729.83  5206.5 1732.04  5212.6 1734.39  5235.5 1739.79  5249.9 1742.14
  5374.4 1750.52  5437.0 1752.29  5594.6 1759.64  5682.9 1764.49  5813.0 1769.88
#Mann=8,-1,0
  3933.0    0.05       0  4300.3     0.1       0  4997.2    0.07       0
  5003.2     0.1       0  5055.3    0.16       0  5097.4     0.1       0
  5437.0    0.16       0  5594.6     0.1       0
Bank Sta=4997.2,5003.2
Exp/Cntr=0.3,0.1

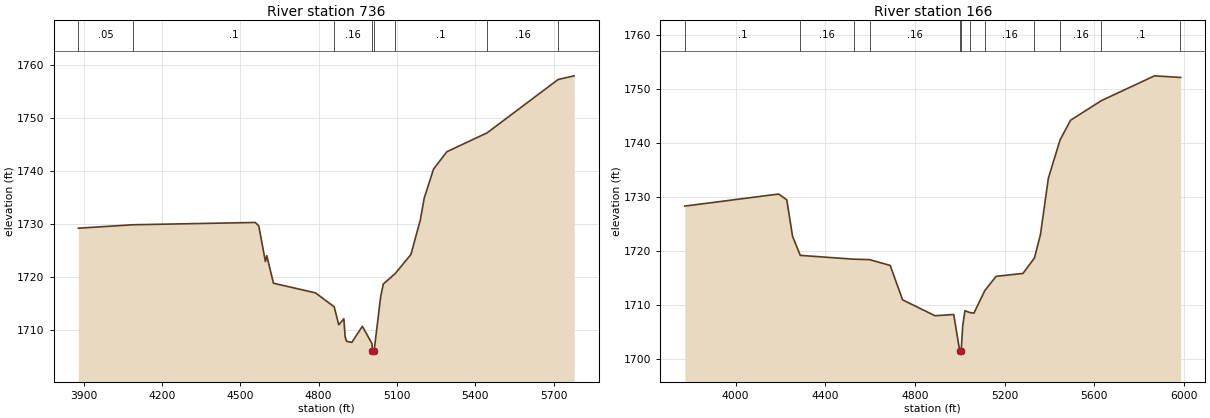
Type RM Length L Ch R = 1,736,570,570,570
BEGIN DESCRIPTION:
Mapping XS ecf58065
END DESCRIPTION:
XS GIS Cut Line= 4
      2739446.14     10028206.72      2738594.57     10028511.41
      2738565.93     10028810.89      2738956.55     10029383.81
#Sta/Elev= 30
  3879.7 1729.16  4089.5 1729.81  4557.0 1730.24  4570.7 1729.59  4596.1 1722.86
  4601.4 1723.98  4626.9 1718.77  4787.8 1716.95  4859.6 1714.31  4876.9 1710.92
  4896.4 1712.06  4901.4 1708.68  4907.0 1707.79  4927.1 1707.60  4967.3 1710.64
  5004.1 1707.38  5006.1 1705.88  5008.9 1705.38  5012.1 1705.88  5037.6 1716.29
  5047.7 1718.63  5092.4 1720.55  5153.3 1724.20  5189.2 1730.69  5204.1 1734.82
  5240.0 1740.33  5290.9 1743.60  5445.3 1747.17  5717.1 1757.24  5778.4 1757.93
#Mann=8,-1,0
  3879.7    0.05       0  4089.5     0.1       0  4859.6    0.16       0
  5006.1    0.07       0  5012.1    0.16       0  5092.4     0.1       0
  5445.3    0.16       0  5717.1     0.1       0
Bank Sta=5006.1,5012.1
Exp/Cntr=0.3,0.1

Type RM Length L Ch R = 1,166,0,0,0
BEGIN DESCRIPTION:
UNT 1072 IN HEWA 1.0
END DESCRIPTION:
XS GIS Cut Line= 4
      2739253.43     10028188.49      2738175.30     10028566.10
      2738183.11     10028748.39      2738810.74     10029376.01
#Sta/Elev= 30
  3773.2 1728.32  4191.7 1730.56  4228.2 1729.49  4254.0 1722.73  4288.3 1719.17
  4526.4 1718.46  4597.5 1718.38  4689.7 1717.30  4745.0 1710.91  4889.5 1707.96
  4973.2 1708.19  5000.3 1701.33  5003.0 1700.83  5006.3 1701.33  5013.3 1706.07
  5023.3 1708.90  5044.4 1708.56  5063.3 1708.44  5111.9 1712.63  5162.1 1715.27
  5282.3 1715.82  5333.2 1718.68  5360.1 1723.02  5395.5 1733.50  5447.8 1740.63
  5494.5 1744.26  5631.9 1747.90  5869.2 1752.51  5984.3 1752.21  5985.6 1752.21
#Mann=12,-1,0
  3773.2     0.1       0  4288.3    0.16       0  4526.4     0.1       0
  4597.5    0.16       0  5000.3    0.07       0  5006.3    0.16       0
  5044.4     0.1       0  5111.9    0.16       0  5333.2     0.1       0
  5447.8    0.16       0  5631.9     0.1       0  5984.3    0.16       0
Bank Sta=5000.3,5006.3
Exp/Cntr=0.3,0.1

Chan Stop Cuts=-1