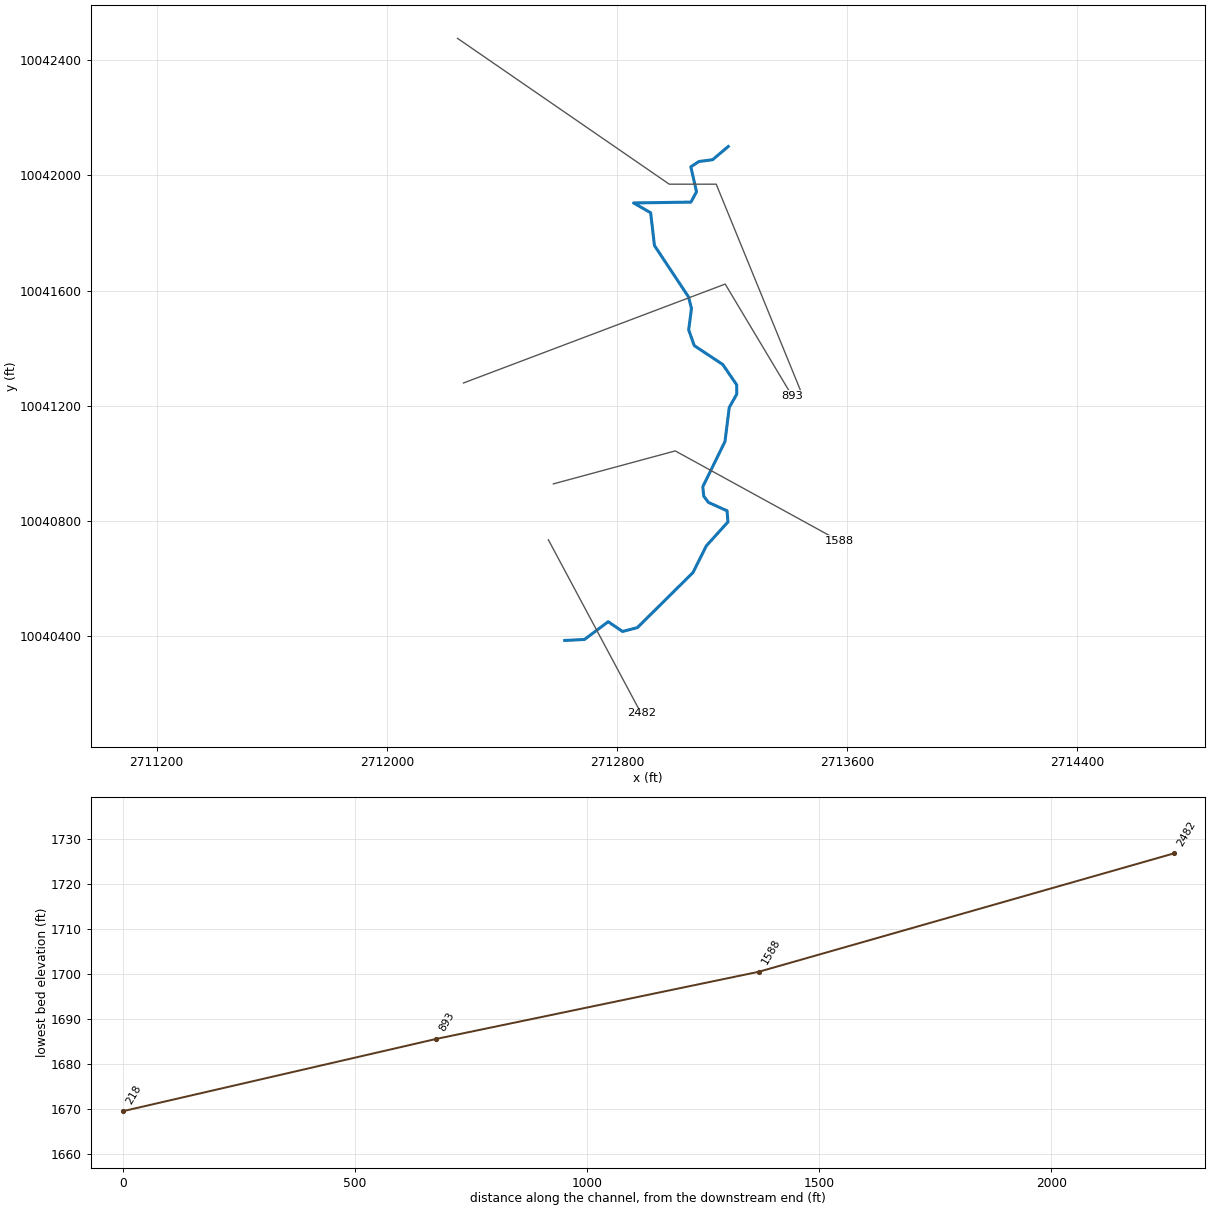
--- UNT 1073 IN HEWA.prj (project) ---

Proj Title=UNT 1073 IN HEWA Base Level Engineering
Current Plan=p01
Default Exp/Contr=0.3,0.1
English Units
Geom File=g01
Flow File=f01
Plan File=p01
BEGIN DESCRIPTION:
UNT 1073 IN HEWA
END DESCRIPTION:

--- UNT 1073 IN HEWA.p01 (plan) ---

Plan Title=Multiple Run
Short Identifier=Multiple
Geom File=g01
Flow File=f01
Subcritical Flow
K Sum by GR= 0
Std Step Tol= 0.01
Critical Tol= 0.01
Num of Std Step Trials= 20
Max Error Tol= 0.3
Flow Tol Ratio= 0.001
Split Flow NTrial= 30
Split Flow Tol= 0.02
Split Flow Ratio= 0.02
Log Output Level= 0
Friction Slope Method= 1
Unsteady Friction Slope Method= 2
Unsteady Bridges Friction Slope Method= 1
Parabolic Critical Depth
Global Vel Dist=  1 , 1 , 1
Global Log Level= 0
CheckData=True
Encroach Param= -1, 0, 0, 0
BEGIN DESCRIPTION:
Multiple Run
END DESCRIPTION:

--- UNT 1073 IN HEWA.f01 (steady flow) ---

Flow Title=Multiple
Number of Profiles=7
Profile Names=10-year,25-year,50-year,1pct_min,100-year,1pct_plu,500-year
River Rch & RM= UNT 1073 IN HEWA,Reach-1,2482
    1426    2140    2779    2637    3567    4824    5865
Boundary for River Rch & Prof#=UNT 1073 IN HEWA,Reach-1,1
Up Type=0
Dn Type=3
Dn Slope=0.005
Boundary for River Rch & Prof#=UNT 1073 IN HEWA,Reach-1,2
Up Type=0
Dn Type=3
Dn Slope=0.005
Boundary for River Rch & Prof#=UNT 1073 IN HEWA,Reach-1,3
Up Type=0
Dn Type=3
Dn Slope=0.005
Boundary for River Rch & Prof#=UNT 1073 IN HEWA,Reach-1,4
Up Type=0
Dn Type=3
Dn Slope=0.005
Boundary for River Rch & Prof#=UNT 1073 IN HEWA,Reach-1,5
Up Type=0
Dn Type=3
Dn Slope=0.005
Boundary for River Rch & Prof#=UNT 1073 IN HEWA,Reach-1,6
Up Type=0
Dn Type=3
Dn Slope=0.005
Boundary for River Rch & Prof#=UNT 1073 IN HEWA,Reach-1,7
Up Type=0
Dn Type=3
Dn Slope=0.005

--- UNT 1073 IN HEWA.g01 (geometry) ---

Geom Title=Existing Conditions

River Reach=UNT 1073 IN HEWA,Reach-1
Reach XY= 30
      2712618.47     10040383.73      2712687.05     10040387.24
      2712769.41     10040448.87      2712819.37     10040415.03
      2712870.82     10040428.33      2713064.25     10040619.95
      2713110.75     10040712.87      2713185.68     10040795.57
      2713182.70     10040834.37      2713118.07     10040863.55
      2713101.64     10040885.05      2713098.40     10040918.25
      2713175.36     10041075.02      2713190.24     10041193.66
      2713216.33     10041239.93      2713215.94     10041272.43
      2713167.70     10041342.94      2713068.49     10041408.63
      2713049.27     10041463.44      2713058.94     10041537.81
      2713048.56     10041578.05      2712930.27     10041756.33
      2712917.04     10041870.37      2712857.65     10041904.43
      2713056.94     10041907.32      2713076.53     10041943.18
      2713056.69     10042030.04      2713084.74     10042048.35
      2713132.64     10042054.82      2713186.84     10042100.74

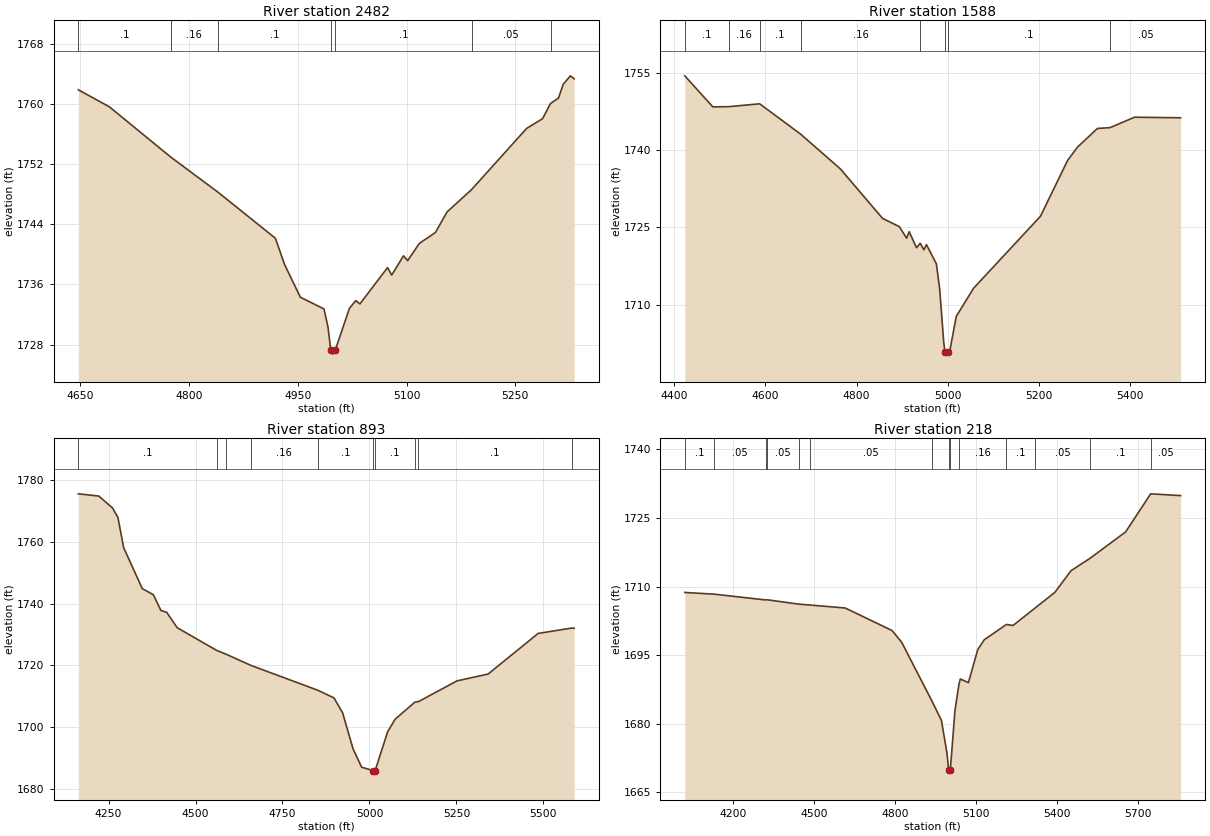
Type RM Length L Ch R = 1,2482,894,894,894
BEGIN DESCRIPTION:
UNT 1073 IN HEWA 4.0
END DESCRIPTION:
XS GIS Cut Line= 2
      2712561.58     10040733.56      2712884.00     10040130.32
#Sta/Elev= 30
  4647.2 1761.93  4690.2 1759.65  4774.4 1752.99  4839.6 1748.31  4919.1 1742.15
  4931.6 1738.68  4953.5 1734.30  4986.1 1732.74  4991.7 1730.28  4995.5 1727.22
  4998.3 1726.72  5001.5 1727.22  5021.2 1732.82  5030.0 1733.85  5035.6 1733.40
  5073.8 1738.25  5079.5 1737.25  5095.8 1739.82  5101.5 1739.17  5117.7 1741.47
  5139.7 1742.91  5156.0 1745.67  5189.6 1748.63  5265.7 1756.79  5287.6 1758.08
  5298.6 1760.11  5309.6 1760.83  5316.0 1762.64  5325.9 1763.79  5331.2 1763.40
#Mann=7,-1,0
  4647.2     0.1       0  4774.4    0.16       0  4839.6     0.1       0
  4995.5    0.07       0  5001.5     0.1       0  5189.6    0.05       0
  5298.6     0.1       0
Bank Sta=4995.5,5001.5
Exp/Cntr=0.3,0.1

Type RM Length L Ch R = 1,1588,695,695,695
BEGIN DESCRIPTION:
UNT 1073 IN HEWA 3.0
END DESCRIPTION:
XS GIS Cut Line= 3
      2712578.97     10040927.99      2713002.57     10041042.57
      2713572.03     10040730.06
#Sta/Elev= 30
  4423.0 1754.42  4484.6 1748.39  4519.6 1748.44  4587.4 1748.99  4677.2 1743.11
  4764.3 1736.38  4857.1 1726.76  4893.8 1725.16  4909.9 1722.92  4915.6 1724.17
  4931.7 1721.05  4939.7 1721.93  4947.8 1720.66  4953.5 1721.66  4975.3 1717.93
  4982.6 1712.96  4991.4 1702.69  4994.1 1700.92  4996.9 1700.42  5000.1 1700.92
  5005.4 1701.37  5018.9 1707.74  5056.8 1713.19  5203.7 1727.17  5263.4 1738.02
  5285.2 1740.60  5328.8 1744.21  5356.5 1744.37  5410.3 1746.39  5511.4 1746.28
#Mann=8,-1,0
  4423.0     0.1       0  4519.6    0.16       0  4587.4     0.1       0
  4677.2    0.16       0  4939.7     0.1       0  4994.1    0.07       0
  5000.1     0.1       0  5356.5    0.05       0
Bank Sta=4994.1,5000.1
Exp/Cntr=0.3,0.1

Type RM Length L Ch R = 1,893,675,675,675
BEGIN DESCRIPTION:
UNT 1073 IN HEWA 2.0
END DESCRIPTION:
XS GIS Cut Line= 3
      2712266.49     10041278.69      2713176.18     10041622.43
      2713408.80     10041233.56
#Sta/Elev= 30
  4163.0 1775.56  4221.8 1774.84  4261.3 1770.99  4276.8 1767.92  4293.4 1758.11
  4346.8 1744.90  4378.9 1742.88  4400.3 1737.82  4417.0 1737.22  4447.2 1732.24
  4560.5 1724.90  4588.2 1723.63  4659.7 1720.01  4851.1 1712.01  4898.0 1709.52
  4922.9 1704.68  4953.0 1692.99  4977.6 1687.09  5010.4 1685.99  5013.2 1685.49
  5016.4 1685.99  5052.4 1698.55  5073.8 1702.61  5131.1 1708.18  5140.8 1708.30
  5251.7 1715.02  5341.2 1717.23  5485.1 1730.38  5582.6 1732.14  5588.6 1732.06
#Mann=10,-1,0
  4163.0     0.1       0  4560.5    0.16       0  4588.2     0.1       0
  4659.7    0.16       0  4851.1     0.1       0  5010.4    0.07       0
  5016.4     0.1       0  5131.1    0.05       0  5140.8     0.1       0
  5582.6    0.05       0
Bank Sta=5010.4,5016.4
Exp/Cntr=0.3,0.1

Type RM Length L Ch R = 1,218,0,0,0
BEGIN DESCRIPTION:
UNT 1073 IN HEWA 1.0
END DESCRIPTION:
XS GIS Cut Line= 4
      2712245.66     10042476.57      2712981.73     10041969.65
      2713144.93     10041969.65      2713439.79     10041248.11
#Sta/Elev= 30
  4020.6 1708.73  4130.2 1708.35  4319.9 1707.09  4325.4 1707.13  4442.7 1706.17
  4483.0 1705.98  4614.6 1705.33  4787.7 1700.42  4823.6 1697.87  4937.2 1684.83
  4971.1 1680.75  4991.1 1673.80  4998.1 1669.93  5000.8 1669.43  5004.1 1669.93
  5021.1 1682.84  5035.9 1688.60  5041.1 1689.80  5071.1 1689.01  5105.5 1696.21
  5129.5 1698.37  5211.6 1701.72  5236.4 1701.51  5316.0 1705.23  5391.3 1708.75
  5451.2 1713.49  5522.3 1716.23  5653.2 1721.96  5746.1 1730.30  5857.0 1729.91
#Mann=14,-1,0
  4020.6     0.1       0  4130.2    0.05       0  4319.9    0.16       0
  4325.4    0.05       0  4442.7     0.1       0  4483.0    0.05       0
  4937.2     0.1       0  4998.1    0.07       0  5004.1     0.1       0
  5035.9    0.16       0  5211.6     0.1       0  5316.0    0.05       0
  5522.3     0.1       0  5746.1    0.05       0
Bank Sta=4998.1,5004.1
Exp/Cntr=0.3,0.1

Chan Stop Cuts=-1