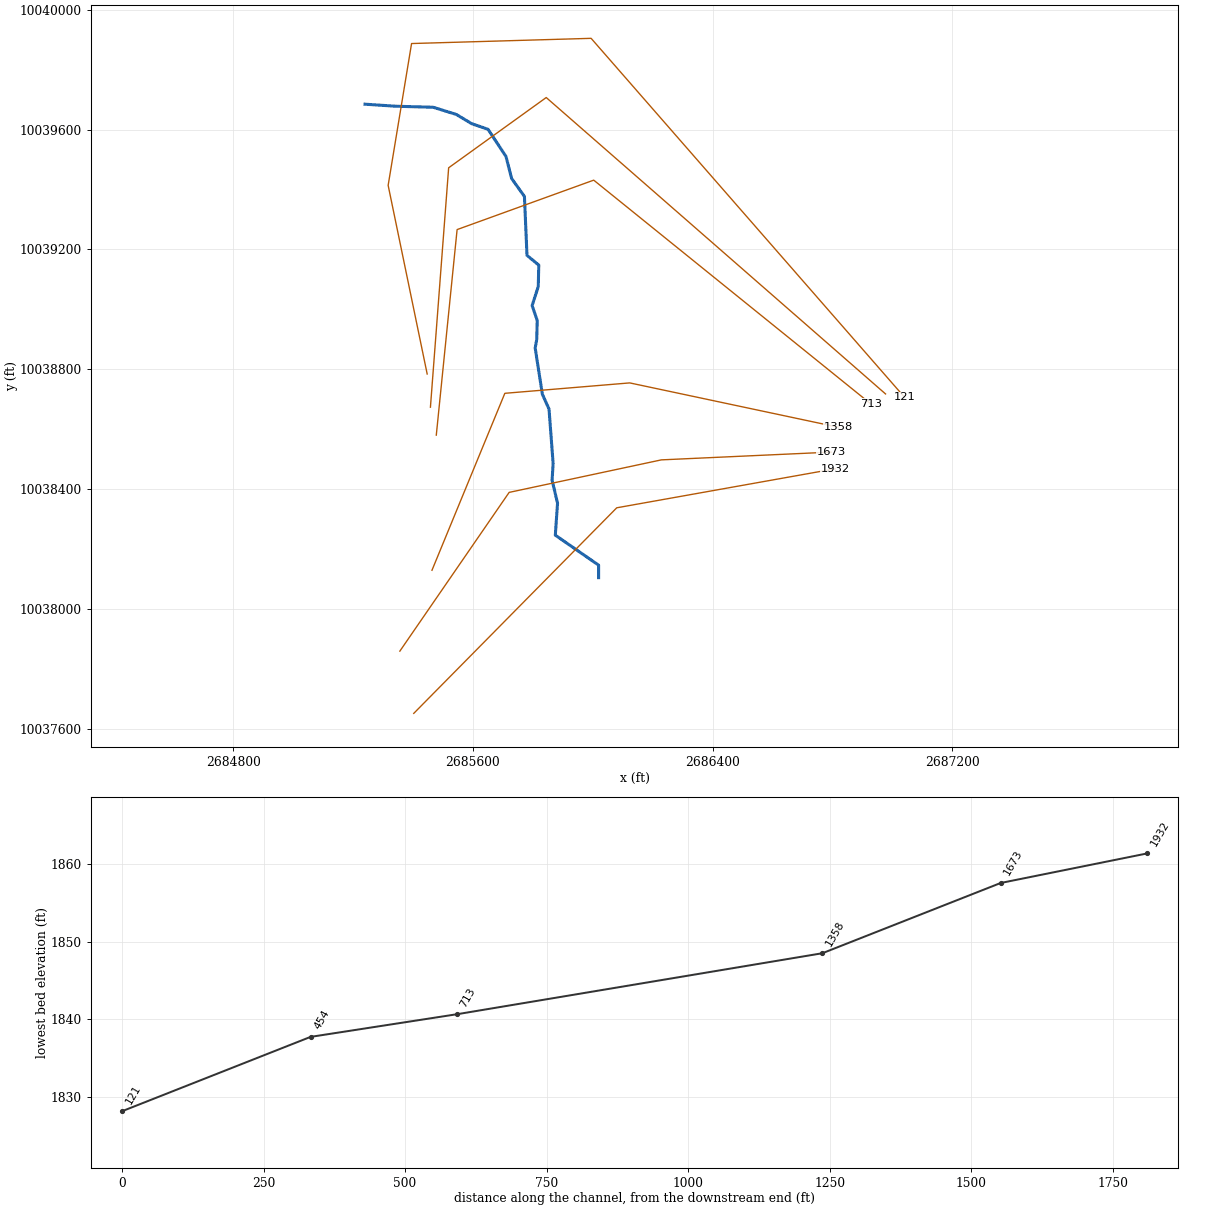
--- UNT 1074 IN HEWA.prj (project) ---

Proj Title=UNT 1074 IN HEWA Base Level Engineering
Current Plan=p01
Default Exp/Contr=0.3,0.1
English Units
Geom File=g01
Flow File=f01
Plan File=p01
Y Axis Title=Elevation
X Axis Title(PF)=Main Channel Distance
X Axis Title(XS)=Station
BEGIN DESCRIPTION:
UNT 1074 IN HEWA
END DESCRIPTION:
DSS Export Rating Curves= 0
DSS Export Rating Curve Sorted= 0
DSS Export Volume Flow Curves= 0
DXF OffsetX= 0
DXF OffsetY= 0
DXF ScaleX= 1
DXF ScaleY= 10

--- UNT 1074 IN HEWA.p01 (plan) ---

Plan Title=Multiple Run
Short Identifier=Multiple
Geom File=g01
Flow File=f01
Subcritical Flow
K Sum by GR= 0
Std Step Tol= 0.01
Critical Tol= 0.01
Num of Std Step Trials= 20
Max Error Tol= 0.3
Flow Tol Ratio= 0.001
Split Flow NTrial= 30
Split Flow Tol= 0.02
Split Flow Ratio= 0.02
Log Output Level= 0
Friction Slope Method= 1
Unsteady Friction Slope Method= 2
Unsteady Bridges Friction Slope Method= 1
Parabolic Critical Depth
Global Vel Dist=  1 , 1 , 1
Global Log Level= 0
CheckData=True
Encroach Param= -1, 0, 0, 0
BEGIN DESCRIPTION:
Multiple Run
END DESCRIPTION:

--- UNT 1074 IN HEWA.f01 (steady flow) ---

Flow Title=Multiple
Number of Profiles=7
Profile Names=10-year,25-year,50-year,1pct_min,100-year,1pct_plu,500-year
River Rch & RM= UNT 1074 IN HEWA,Reach-1,1932
     159     202     236     202     273     370     364
Boundary for River Rch & Prof#=UNT 1074 IN HEWA,Reach-1,1
Up Type=0
Dn Type=3
Dn Slope=0.005
Boundary for River Rch & Prof#=UNT 1074 IN HEWA,Reach-1,2
Up Type=0
Dn Type=3
Dn Slope=0.005
Boundary for River Rch & Prof#=UNT 1074 IN HEWA,Reach-1,3
Up Type=0
Dn Type=3
Dn Slope=0.005
Boundary for River Rch & Prof#=UNT 1074 IN HEWA,Reach-1,4
Up Type=0
Dn Type=3
Dn Slope=0.005
Boundary for River Rch & Prof#=UNT 1074 IN HEWA,Reach-1,5
Up Type=0
Dn Type=3
Dn Slope=0.005
Boundary for River Rch & Prof#=UNT 1074 IN HEWA,Reach-1,6
Up Type=0
Dn Type=3
Dn Slope=0.005
Boundary for River Rch & Prof#=UNT 1074 IN HEWA,Reach-1,7
Up Type=0
Dn Type=3
Dn Slope=0.005

--- UNT 1074 IN HEWA.g01 (geometry) ---

Geom Title=Existing Conditions
Program Version=4.10

River Reach=UNT 1074 IN HEWA,Reach-1
Reach XY= 24
      2686019.44     10038105.13      2686019.44      10038146.8
      2685874.99      10038246.8      2685882.45     10038353.76
      2685864.26     10038429.86      2685867.68     10038486.27
        2685854.     10038667.48      2685831.78     10038717.05
      2685807.84      10038870.9      2685812.97     10038899.96
      2685814.68     10038963.21      2685797.59     10039012.79
       2685818.1     10039076.04      2685819.81     10039147.84
      2685780.49     10039180.32      2685771.95      10039376.9
      2685729.21     10039436.74      2685710.41     10039510.24
      2685650.57     10039600.84      2685595.87     10039619.65
      2685544.59     10039650.42      2685467.66     10039674.35
      2685342.87     10039677.77      2685240.03     10039684.59

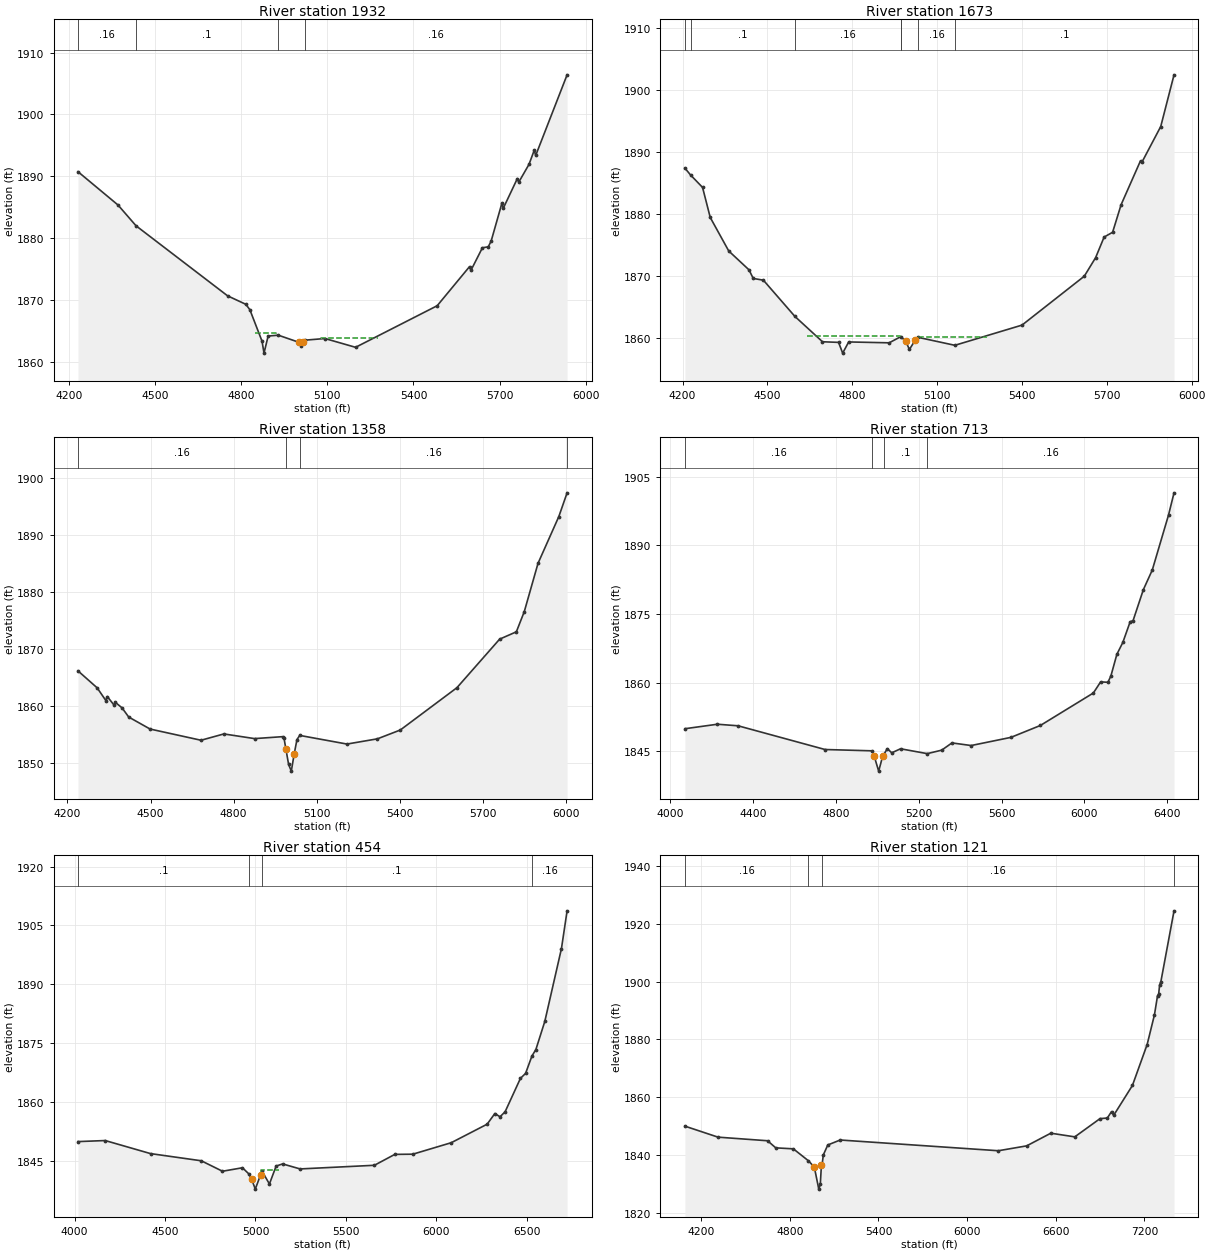
Type RM Length L Ch R = 1 ,1932    ,259,259,259
BEGIN DESCRIPTION:
UNT 1074 IN HEWA 2.0
END DESCRIPTION:
XS GIS Cut Line= 3
      2685402.76     10037652.34      2686079.88     10038338.14
        2686809.     10038468.34
#Sta/Elev= 30
  4230.9 1890.75  4370.3 1885.37  4433.2 1882.01  4752.2 1870.69  4815.8 1869.32
  4829.9 1868.44  4872.3 1863.35  4879.1 1861.43  4893.5 1864.19  4928.9 1864.33
  4999.6  1863.2  5006.6 1862.62  5013.8 1863.23  5020.8 1863.52  5091.5 1863.79
  5198.2 1862.37  5482.6 1869.09  5595.3 1875.41  5600.4 1874.82  5640.2 1878.46
  5660.5 1878.61  5670.6 1879.53  5708.1 1885.65  5713.2 1884.87  5761.9 1889.64
    5767 1889.07  5802.7 1891.95  5820.8 1894.22  5825.9 1893.38  5935.3 1906.41
#Mann= 4 ,-1 , 0
  4230.9     .16       0  4433.2      .1       0  4928.9     .09       0
  5020.8     .16       0
#XS Ineff= 2 ,-1
  4846.6 4921.84 1864.62 5077.53 5276.05 1863.89
Permanent Ineff=
       F       F
Bank Sta=4999.6,5013.8
XS Rating Curve= 0 ,0
Exp/Cntr=0.3,0.1

Type RM Length L Ch R = 1 ,1673    ,315,315,315
BEGIN DESCRIPTION:
Mapping XS 97269a87
END DESCRIPTION:
XS GIS Cut Line= 4
      2685356.37     10037859.99      2685720.98     10038389.54
      2686228.79     10038498.04      2686795.39     10038523.99
#Sta/Elev= 30
  4208.3 1887.38    4228 1886.29  4270.6 1884.28  4297.8 1879.44  4363.2 1874.05
  4434.9 1871.01  4449.8 1869.63  4485.7 1869.35  4597.1 1863.52  4694.7 1859.44
  4751.5 1859.34  4766.1 1857.61  4787.3 1859.41  4930.5 1859.27  4971.4 1860.26
  4988.8 1859.55    5002  1858.2  5022.5 1859.69  5032.7 1860.15  5162.7 1858.87
  5400.2 1862.12  5620.4 1869.99  5660.5 1872.98  5690.5 1876.29  5720.5 1877.06
  5750.6  1881.5  5819.2 1888.57  5824.2 1888.34  5890.7 1894.08  5937.7  1902.4
#Mann= 7 ,-1 , 0
  4208.3     .16       0    4228      .1       0  4597.1     .16       0
  4971.4     .05       0  4971.4     .09       0  5032.7     .16       0
  5162.7      .1       0
#XS Ineff= 2 ,-1
 4639.77 4970.11 1860.36 5032.64  5275.8 1860.16
Permanent Ineff=
       F       F
Bank Sta=4988.8,5022.5
XS Rating Curve= 0 ,0
Exp/Cntr=0.3,0.1

Type RM Length L Ch R = 1 ,1358    ,645,645,645
BEGIN DESCRIPTION:
Mapping XS 15b3d8ef
END DESCRIPTION:
XS GIS Cut Line= 4
      2685463.55     10038129.79      2685706.61     10038720.09
      2686123.28     10038754.81      2686817.69     10038607.25
#Sta/Elev= 30
  4238.1 1866.17  4307.2 1863.19  4338.6 1860.96    4344 1861.65    4368 1860.17
  4373.4 1860.62  4397.3 1859.66  4421.3 1858.05  4498.5 1855.94  4682.4 1853.97
    4765 1855.08  4875.7 1854.26  4977.1  1854.6  4982.1 1854.36  4988.7 1852.49
  4998.8 1849.71  5008.5 1848.54  5018.8 1851.53  5028.9 1854.08  5038.9 1854.82
  5209.5  1853.3  5319.5 1854.22  5402.1 1855.77  5606.6 1863.21  5760.9 1871.75
  5821.3 1873.04  5849.9 1876.59  5899.5 1885.08  5974.6  1893.3  6004.5 1897.48
#Mann= 4 ,-1 , 0
  4238.1     .16       0  4988.7     .09       0  5038.9     .16       0
  6004.5      .1       0
Bank Sta=4988.7,5018.8
XS Rating Curve= 0 ,0
Exp/Cntr=0.3,0.1

Type RM Length L Ch R = 1 ,713     ,259,259,259
BEGIN DESCRIPTION:
Mapping XS b787aeb7
END DESCRIPTION:
XS GIS Cut Line= 4
      2685477.93     10038580.55      2685547.37     10039266.27
       2686003.1      10039431.2      2686927.54      10038684.7
#Sta/Elev= 30
  4070.6 1849.93  4227.2 1850.91  4327.1 1850.57  4747.2 1845.39  4975.9  1845.1
  4984.3 1843.99  5006.3 1840.67  5026.5 1844.08  5031.9 1844.37  5048.1 1845.58
  5069.4 1844.67  5111.9 1845.55  5240.9 1844.49  5310.7 1845.25  5360.2 1846.83
    5453 1846.26  5644.9 1848.04  5787.2 1850.64  6043.1 1857.73  6078.3 1860.16
  6113.5 1860.07  6127.9 1861.47  6156.6 1866.17  6185.4 1868.77  6220.6 1873.26
    6235 1873.55  6284.6  1880.3  6327.7 1884.59  6406.1 1896.59  6432.7 1901.44
#Mann= 4 ,-1 , 0
  4070.6     .16       0  4975.9     .09       0  5031.9      .1       0
  5240.9     .16       0
Bank Sta=4984.3,5026.5
XS Rating Curve= 0 ,0
Exp/Cntr=0.3,0.1

Type RM Length L Ch R = 1 ,454     ,333,333,333
BEGIN DESCRIPTION:
Mapping XS bb178d95
END DESCRIPTION:
XS GIS Cut Line= 4
      2685458.39     10038673.81      2685519.16     10039472.43
      2685844.68     10039706.81      2686976.65     10038717.96
#Sta/Elev= 30
  4018.5 1849.86  4168.9 1850.13  4419.6  1846.8  4700.4 1844.97  4817.6  1842.3
  4928.1 1843.19  4963.7 1841.61  4978.4 1840.33  4999.1 1837.74  5028.1 1841.38
  5034.9 1842.41  5077.3 1839.06  5114.3 1843.62  5150.2 1844.17  5246.8 1842.89
  5657.8 1843.82  5770.7  1846.6  5870.4 1846.65    6083 1849.58  6281.4  1854.3
  6324.1 1857.02  6352.6 1856.19  6380.8 1857.47  6465.6 1865.99    6494 1867.25
  6529.2 1871.69    6551 1873.34  6600.4 1880.52  6692.4 1899.08  6723.6 1908.71
#Mann= 4 ,-1 , 0
  4018.5      .1       0  4963.7     .07       0  5034.9      .1       0
  6529.2     .16       0
#XS Ineff= 1 ,-1
 5032.95 5128.41 1842.62
Permanent Ineff=
       F
Bank Sta=4978.4,5028.1
XS Rating Curve= 0 ,0
Exp/Cntr=0.3,0.1

Type RM Length L Ch R = 1 ,121     ,0,0,0
BEGIN DESCRIPTION:
UNT 1074 IN HEWA 1.0
END DESCRIPTION:
XS GIS Cut Line= 5
      2685447.55     10038784.48      2685317.33     10039413.84
      2685395.46     10039886.93      2685994.42     10039904.29
      2687039.42     10038707.53
#Sta/Elev= 30
  4090.3 1849.96  4314.2 1846.15  4649.7  1844.9    4705 1842.44  4824.1  1842.1
  4925.5 1837.99    4966 1835.79  4996.2 1828.14  5006.5 1829.85  5013.9 1836.37
  5018.9 1836.69  5026.8 1839.98  5057.2 1843.44  5141.1 1845.16  6211.5 1841.44
  6403.2 1843.13  6566.5 1847.52  6728.8 1846.25  6899.7 1852.57    6949 1852.77
  6977.5 1855.01  6991.8 1853.69  7118.9 1864.06  7218.6 1878.25    7268 1888.54
  7288.9 1895.17  7296.5 1895.72  7303.1 1898.94  7310.7 1899.82  7400.5 1924.57
#Mann= 4 ,-1 , 0
  4090.3     .16       0  4925.5     .07       0  5018.9     .16       0
  7400.5      .1       0
Bank Sta=4966,5013.9
XS Rating Curve= 0 ,0
Exp/Cntr=0.3,0.1

Chan Stop Cuts=-1
Use User Specified Reach Order=0
Composite Channel Slope=5