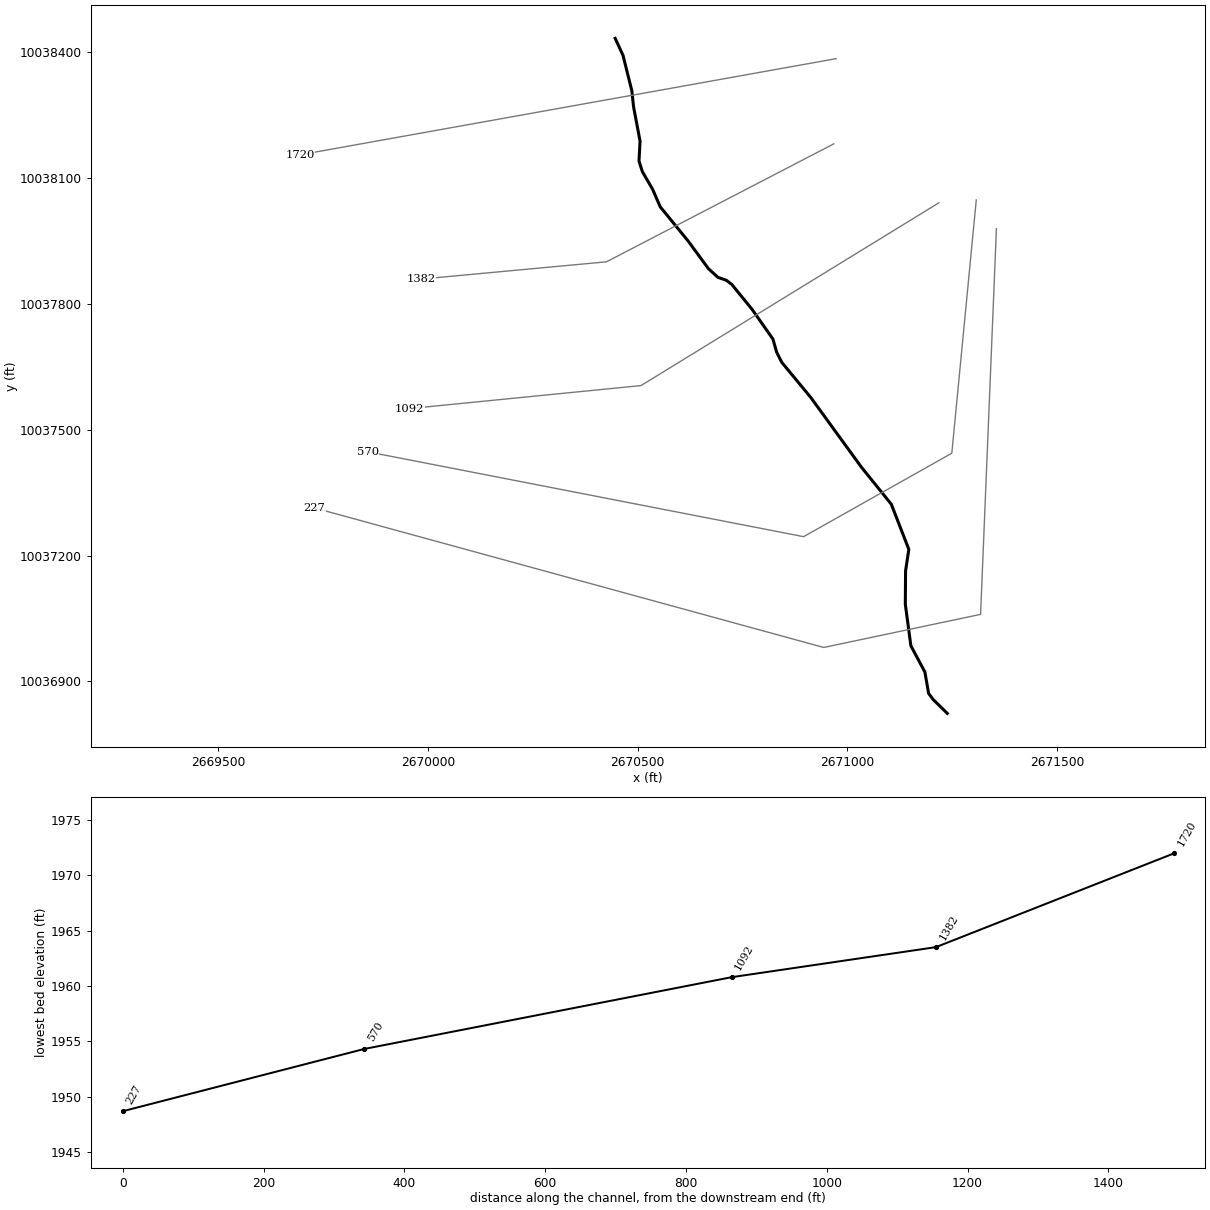
--- UNT 1075 IN HEWA.prj (project) ---

Proj Title=UNT 1075 IN HEWA Base Level Engineering
Current Plan=p01
Default Exp/Contr=0.3,0.1
English Units
Geom File=g01
Flow File=f01
Plan File=p01
BEGIN DESCRIPTION:
UNT 1075 IN HEWA
END DESCRIPTION:

--- UNT 1075 IN HEWA.p01 (plan) ---

Plan Title=Multiple Run
Short Identifier=Multiple
Geom File=g01
Flow File=f01
Subcritical Flow
K Sum by GR= 0
Std Step Tol= 0.01
Critical Tol= 0.01
Num of Std Step Trials= 20
Max Error Tol= 0.3
Flow Tol Ratio= 0.001
Split Flow NTrial= 30
Split Flow Tol= 0.02
Split Flow Ratio= 0.02
Log Output Level= 0
Friction Slope Method= 1
Unsteady Friction Slope Method= 2
Unsteady Bridges Friction Slope Method= 1
Parabolic Critical Depth
Global Vel Dist=  1 , 1 , 1
Global Log Level= 0
CheckData=True
Encroach Param= -1, 0, 0, 0
BEGIN DESCRIPTION:
Multiple Run
END DESCRIPTION:

--- UNT 1075 IN HEWA.f01 (steady flow) ---

Flow Title=Multiple
Number of Profiles=7
Profile Names=10-year,25-year,50-year,1pct_min,100-year,1pct_plu,500-year
River Rch & RM= UNT 1075 IN HEWA,Reach-1,1720
     744    1057    1321    1206    1631    2206    2482
Boundary for River Rch & Prof#=UNT 1075 IN HEWA,Reach-1,1
Up Type=0
Dn Type=3
Dn Slope=0.005
Boundary for River Rch & Prof#=UNT 1075 IN HEWA,Reach-1,2
Up Type=0
Dn Type=3
Dn Slope=0.005
Boundary for River Rch & Prof#=UNT 1075 IN HEWA,Reach-1,3
Up Type=0
Dn Type=3
Dn Slope=0.005
Boundary for River Rch & Prof#=UNT 1075 IN HEWA,Reach-1,4
Up Type=0
Dn Type=3
Dn Slope=0.005
Boundary for River Rch & Prof#=UNT 1075 IN HEWA,Reach-1,5
Up Type=0
Dn Type=3
Dn Slope=0.005
Boundary for River Rch & Prof#=UNT 1075 IN HEWA,Reach-1,6
Up Type=0
Dn Type=3
Dn Slope=0.005
Boundary for River Rch & Prof#=UNT 1075 IN HEWA,Reach-1,7
Up Type=0
Dn Type=3
Dn Slope=0.005

--- UNT 1075 IN HEWA.g01 (geometry) ---

Geom Title=Existing Conditions

River Reach=UNT 1075 IN HEWA,Reach-1
Reach XY= 29
      2670446.74     10038433.02      2670465.43     10038392.48
      2670486.49     10038307.91      2670490.61     10038269.60
      2670506.07     10038187.91      2670503.51     10038140.43
      2670511.60     10038115.13      2670536.16     10038072.81
      2670554.12     10038031.36      2670620.62     10037949.89
      2670669.14     10037883.78      2670691.77     10037863.15
      2670711.79     10037856.22      2670724.70     10037846.36
      2670773.49     10037786.45      2670822.80     10037716.10
      2670831.64     10037685.05      2670843.52     10037661.11
      2670913.42     10037576.35      2671033.45     10037411.08
      2671105.06     10037322.32      2671146.80     10037214.77
      2671139.08     10037163.62      2671138.44     10037083.75
      2671151.66     10036985.05      2671185.06     10036922.32
      2671194.01     10036871.31      2671204.80     10036856.77
      2671238.47     10036823.73

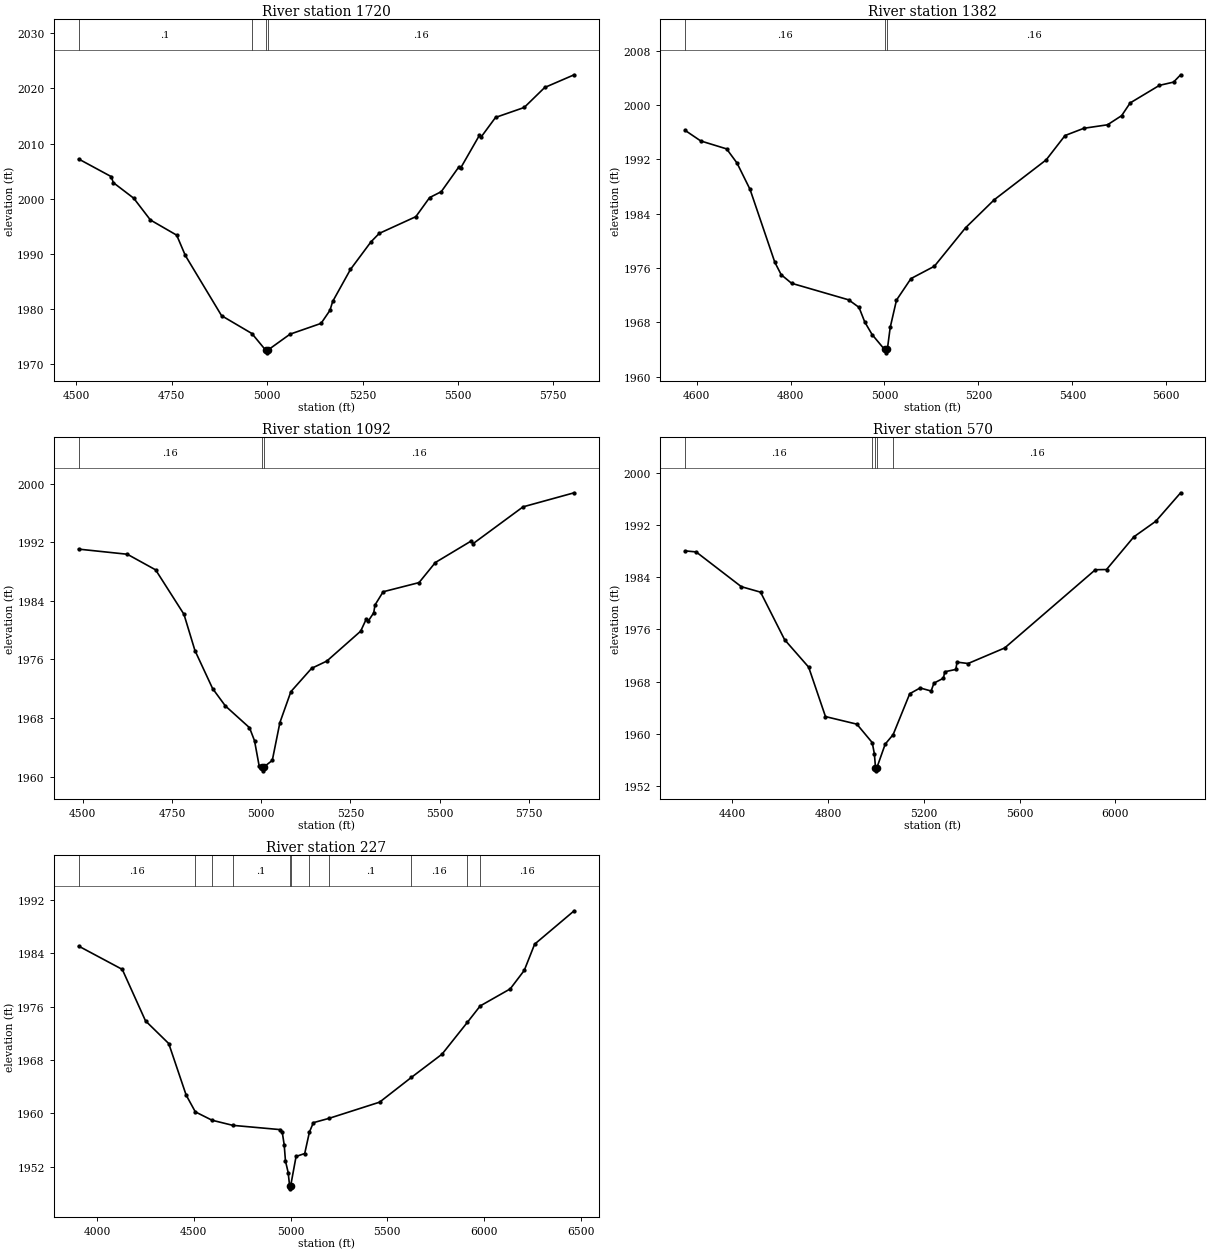
Type RM Length L Ch R = 1,1720,338,338,338
BEGIN DESCRIPTION:
UNT 1075 IN HEWA 3.0
END DESCRIPTION:
XS GIS Cut Line= 2
      2670973.56     10038384.59      2669695.75     10038155.41
#Sta/Elev= 30
  4506.3 2007.19  4591.9 2003.98  4597.0 2002.90  4650.7 2000.06  4694.3 1996.11
  4763.2 1993.35  4785.8 1989.66  4880.8 1978.72  4960.2 1975.48  4996.1 1972.47
  4998.9 1971.97  5002.1 1972.47  5060.1 1975.36  5141.4 1977.32  5164.7 1979.69
  5171.8 1981.30  5218.4 1987.12  5272.1 1992.13  5293.8 1993.67  5389.7 1996.71
  5425.8 2000.18  5456.3 2001.25  5502.2 2005.73  5507.3 2005.57  5556.0 2011.46
  5561.1 2011.22  5598.5 2014.74  5673.6 2016.55  5727.3 2020.18  5804.5 2022.49
#Mann=4,-1,0
  4506.3     0.1       0  4960.2    0.16       0  4996.1    0.07       0
  5002.1    0.16       0
Bank Sta=4996.1,5002.1
Exp/Cntr=0.3,0.1

Type RM Length L Ch R = 1,1382,290,290,290
BEGIN DESCRIPTION:
Mapping XS 136bbfba
END DESCRIPTION:
XS GIS Cut Line= 3
      2670967.96     10038181.50      2670425.97     10037900.22
      2669983.41     10037859.05
#Sta/Elev= 30
  4575.5 1996.29  4608.8 1994.73  4663.9 1993.56  4686.0 1991.48  4713.8 1987.59
  4766.5 1976.86  4780.1 1975.02  4802.2 1973.76  4923.7 1971.32  4945.8 1970.21
  4958.0 1968.06  4973.6 1966.21  5000.1 1964.01  5002.8 1963.51  5006.1 1964.01
  5012.2 1967.25  5025.6 1971.28  5056.4 1974.45  5106.3 1976.27  5172.7 1981.94
  5233.8 1986.07  5344.3 1991.94  5384.5 1995.53  5424.7 1996.60  5474.9 1997.11
  5505.0 1998.46  5523.1 2000.33  5585.4 2002.92  5615.5 2003.40  5630.6 2004.48
#Mann=3,-1,0
  4575.5    0.16       0  5000.1    0.07       0  5006.1    0.16       0
Bank Sta=5000.1,5006.1
Exp/Cntr=0.3,0.1

Type RM Length L Ch R = 1,1092,522,522,522
BEGIN DESCRIPTION:
Mapping XS 48dcac98
END DESCRIPTION:
XS GIS Cut Line= 3
      2671218.40     10038040.86      2670508.31     10037605.20
      2669956.01     10037550.31
#Sta/Elev= 30
  4488.7 1991.06  4625.1 1990.36  4704.4 1988.23  4783.7 1982.17  4814.5 1977.22
  4864.0 1972.03  4899.7 1969.66  4967.3 1966.69  4981.4 1964.91  4994.5 1961.44
  5001.0 1961.30  5003.8 1960.80  5007.0 1961.30  5031.2 1962.23  5052.5 1967.39
  5083.3 1971.61  5141.3 1974.79  5183.9 1975.78  5278.7 1979.86  5294.1 1981.48
  5300.0 1981.24  5315.4 1982.38  5318.8 1983.43  5341.7 1985.24  5442.2 1986.49
  5487.9 1989.23  5588.7 1992.18  5593.7 1991.81  5733.6 1996.83  5876.8 1998.75
#Mann=3,-1,0
  4488.7    0.16       0  5001.0    0.07       0  5007.0    0.16       0
Bank Sta=5001,5007
Exp/Cntr=0.3,0.1

Type RM Length L Ch R = 1,570,343,343,343
BEGIN DESCRIPTION:
UNT 1075 IN HEWA 2.0
END DESCRIPTION:
XS GIS Cut Line= 4
      2671307.60     10038047.69      2671249.28     10037443.97
      2670895.95     10037245.00      2669856.51     10037447.40
#Sta/Elev= 30
  4202.2 1988.05  4248.3 1987.89  4437.2 1982.56  4517.6 1981.72  4618.1 1974.43
  4718.6 1970.22  4788.9 1962.64  4920.0 1961.48  4984.3 1958.65  4993.3 1956.92
  4997.9 1954.82  5000.7 1954.32  5003.9 1954.82  5038.5 1958.42  5071.6 1959.87
  5141.1 1966.15  5184.5 1967.03  5230.4 1966.56  5242.2 1967.77  5282.0 1968.53
  5287.1 1969.51  5333.6 1969.87  5338.7 1970.99  5384.9 1970.78  5537.7 1973.16
  5916.8 1985.16  5963.4 1985.19  6077.6 1990.20  6169.3 1992.59  6273.2 1996.96
#Mann=5,-1,0
  4202.2    0.16       0  4984.3     0.1       0  4997.9    0.07       0
  5003.9     0.1       0  5071.6    0.16       0
Bank Sta=4997.9,5003.9
Exp/Cntr=0.3,0.1

Type RM Length L Ch R = 1,227,0,0,0
BEGIN DESCRIPTION:
UNT 1075 IN HEWA 1.0
END DESCRIPTION:
XS GIS Cut Line= 4
      2671355.63     10037979.11      2671317.89     10037059.76
      2670943.97     10036980.86      2669729.62     10037313.60
#Sta/Elev= 30
  3904.7 1985.06  4130.3 1981.57  4250.4 1973.86  4370.5 1970.46  4460.5 1962.74
  4507.9 1960.23  4594.0 1958.98  4701.6 1958.21  4946.9 1957.57  4957.1 1957.19
  4967.3 1955.29  4973.8 1952.87  4987.8 1951.14  4995.0 1949.20  4997.7 1948.70
  5001.0 1949.20  5028.6 1953.55  5073.3 1953.99  5097.7 1957.21  5118.0 1958.61
  5200.4 1959.27  5460.1 1961.68  5624.5 1965.39  5783.0 1968.87  5914.0 1973.64
  5980.5 1976.10  6135.5 1978.65  6208.1 1981.42  6261.8 1985.35  6466.1 1990.35
#Mann=11,-1,0
  3904.7    0.16       0  4507.9     0.1       0  4594.0    0.16       0
  4701.6     0.1       0  4995.0    0.07       0  5001.0     0.1       0
  5097.7    0.16       0  5200.4     0.1       0  5624.5    0.16       0
  5914.0     0.1       0  5980.5    0.16       0
Bank Sta=4995,5001
Exp/Cntr=0.3,0.1

Chan Stop Cuts=-1