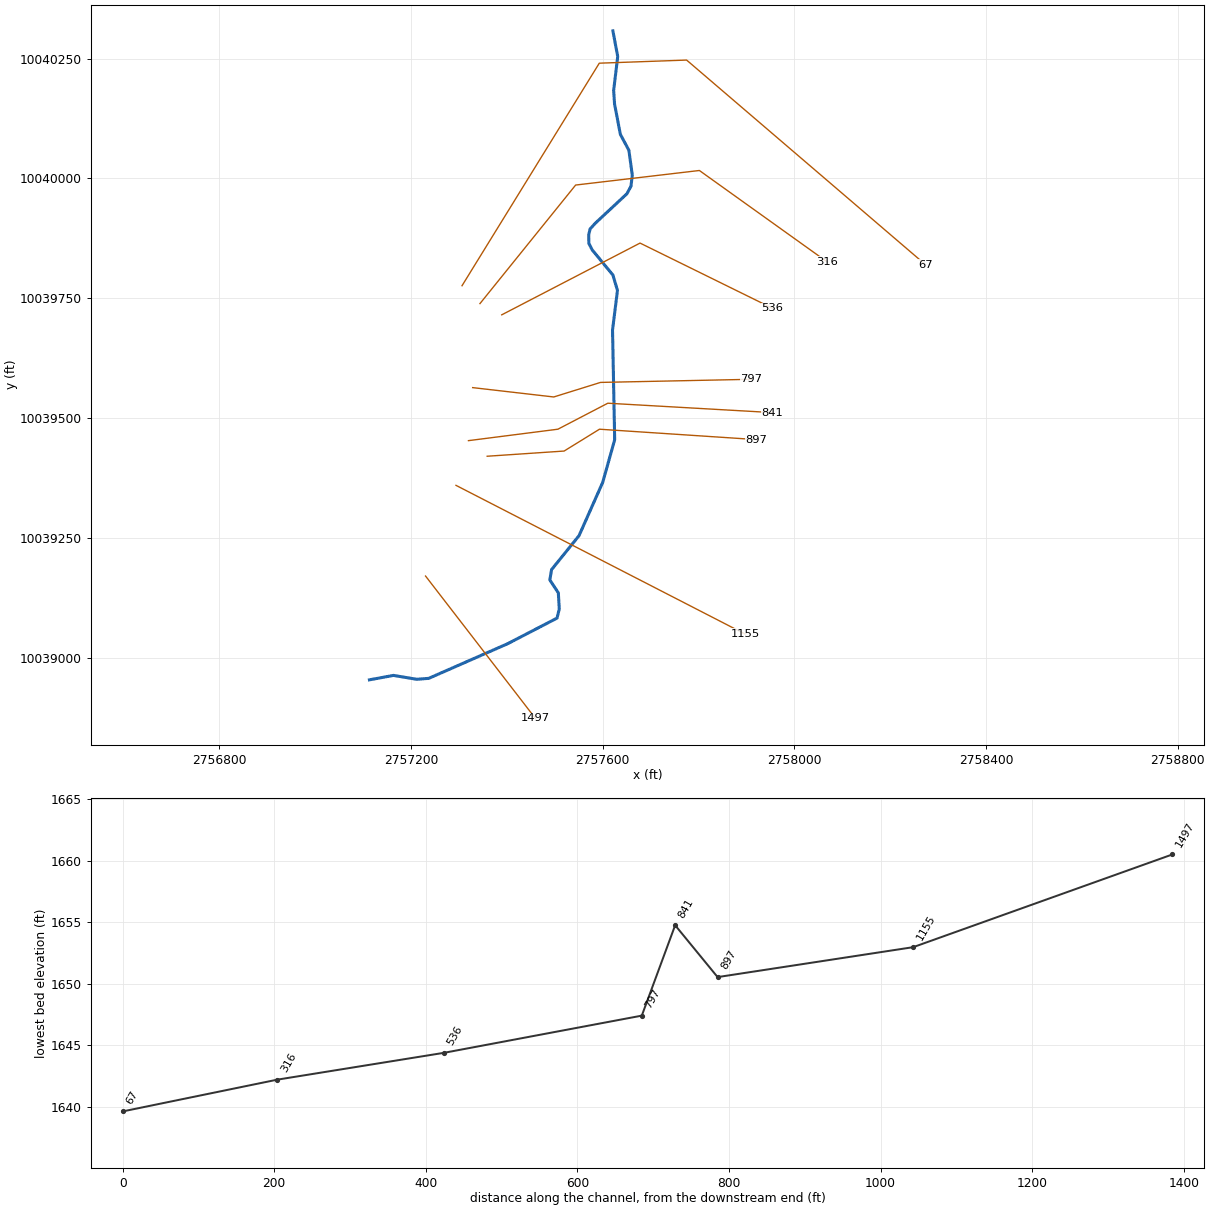
--- UNT 1076 IN HEWA.prj (project) ---

Proj Title=UNT 1076 IN HEWA Base Level Engineering
Current Plan=p01
Default Exp/Contr=0.3,0.1
English Units
Geom File=g01
Flow File=f01
Plan File=p01
Y Axis Title=Elevation
X Axis Title(PF)=Main Channel Distance
X Axis Title(XS)=Station
BEGIN DESCRIPTION:
UNT 1076 IN HEWA
END DESCRIPTION:
DSS Export Rating Curves= 0
DSS Export Rating Curve Sorted= 0
DSS Export Volume Flow Curves= 0
DXF OffsetX= 0
DXF OffsetY= 0
DXF ScaleX= 1
DXF ScaleY= 10

--- UNT 1076 IN HEWA.p01 (plan) ---

Plan Title=Multiple Run
Short Identifier=Multiple
Geom File=g01
Flow File=f01
Subcritical Flow
K Sum by GR= 0
Std Step Tol= 0.01
Critical Tol= 0.01
Num of Std Step Trials= 20
Max Error Tol= 0.3
Flow Tol Ratio= 0.001
Split Flow NTrial= 30
Split Flow Tol= 0.02
Split Flow Ratio= 0.02
Log Output Level= 0
Friction Slope Method= 1
Unsteady Friction Slope Method= 2
Unsteady Bridges Friction Slope Method= 1
Parabolic Critical Depth
Global Vel Dist=  1 , 1 , 1
Global Log Level= 0
CheckData=True
Encroach Param= -1, 0, 0, 0
BEGIN DESCRIPTION:
Multiple Run
END DESCRIPTION:

--- UNT 1076 IN HEWA.f01 (steady flow) ---

Flow Title=Multiple
Number of Profiles=7
Profile Names=10-year,25-year,50-year,1pct_min,100-year,1pct_plu,500-year
River Rch & RM= UNT 1076 IN HEWA,Reach-1,1497
     563     800    1002     921    1246    1685    1931
Boundary for River Rch & Prof#=UNT 1076 IN HEWA,Reach-1,1
Up Type=0
Dn Type=3
Dn Slope=0.005
Boundary for River Rch & Prof#=UNT 1076 IN HEWA,Reach-1,2
Up Type=0
Dn Type=3
Dn Slope=0.005
Boundary for River Rch & Prof#=UNT 1076 IN HEWA,Reach-1,3
Up Type=0
Dn Type=3
Dn Slope=0.005
Boundary for River Rch & Prof#=UNT 1076 IN HEWA,Reach-1,4
Up Type=0
Dn Type=3
Dn Slope=0.005
Boundary for River Rch & Prof#=UNT 1076 IN HEWA,Reach-1,5
Up Type=0
Dn Type=3
Dn Slope=0.005
Boundary for River Rch & Prof#=UNT 1076 IN HEWA,Reach-1,6
Up Type=0
Dn Type=3
Dn Slope=0.005
Boundary for River Rch & Prof#=UNT 1076 IN HEWA,Reach-1,7
Up Type=0
Dn Type=3
Dn Slope=0.005

--- UNT 1076 IN HEWA.g01 (geometry) ---

Geom Title=Existing Conditions
Program Version=4.10

River Reach=UNT 1076 IN HEWA,Reach-1
Reach XY= 30
       2757113.5     10038953.58      2757163.65     10038962.84
      2757212.21     10038954.67      2757237.23     10038956.66
      2757401.92     10039028.95      2757504.95     10039082.37
      2757509.67     10039101.43       2757507.7     10039135.01
      2757489.92     10039162.14      2757493.57     10039183.54
      2757550.89     10039254.48      2757600.25      10039365.5
       2757625.3     10039454.65      2757620.81     10039683.78
       2757631.1     10039766.38       2757621.6     10039798.38
      2757578.43     10039850.82      2757571.32     10039864.62
       2757571.1     10039882.42        2757574.      10039894.6
      2757584.28     10039906.01      2757650.81     10039968.02
       2757659.3     10039983.75      2757662.06     10040006.78
      2757654.93     10040058.79      2757637.16     10040091.99
      2757625.03     10040155.48      2757623.12     10040183.59
      2757631.65     10040254.38      2757621.54     10040307.98

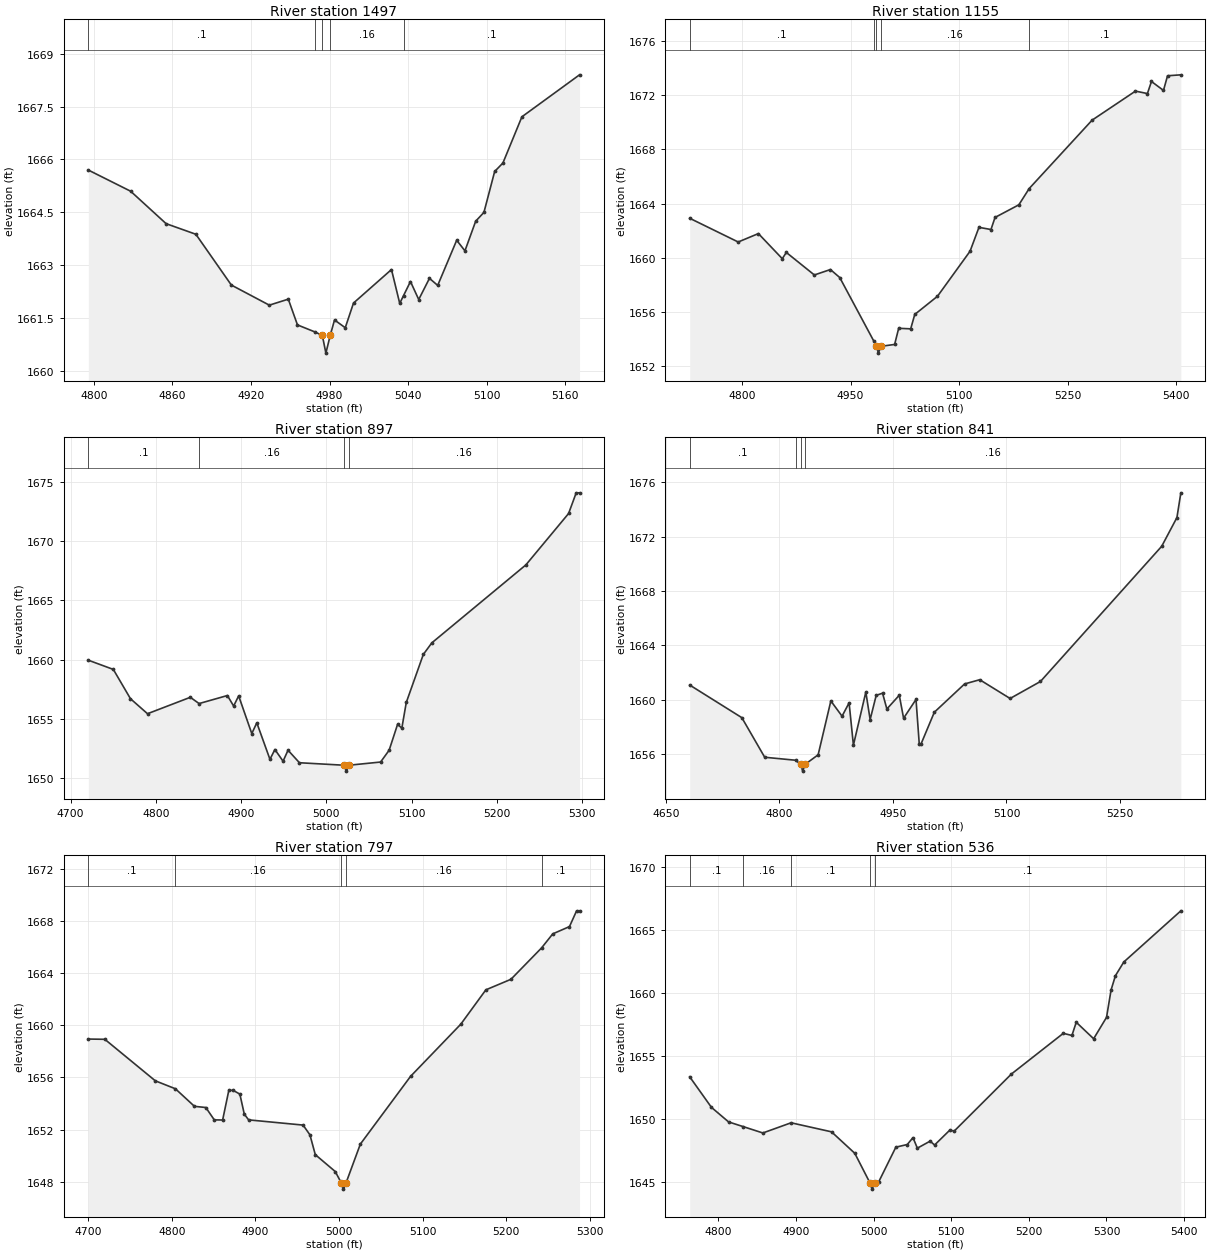
Type RM Length L Ch R = 1 ,1497    ,342,342,342
BEGIN DESCRIPTION:
UNT 1076 IN HEWA 3.0
END DESCRIPTION:
XS GIS Cut Line= 2
      2757230.58     10039170.16      2757459.79     10038873.23
#Sta/Elev= 30
  4795.8  1665.7  4828.1  1665.1  4855.2 1664.18  4877.9 1663.88    4905 1662.44
    4934 1661.87  4948.5 1662.04  4955.5 1661.31  4968.9 1661.11  4974.5 1661.01
  4977.2 1660.51  4980.5 1661.01  4983.8 1661.45    4992 1661.23  4998.3 1661.93
  5027.3 1662.88  5033.6 1661.92  5036.5 1662.14  5041.8 1662.54  5048.1 1662.03
  5056.3 1662.63  5062.6 1662.43  5077.1 1663.71  5083.4 1663.41  5091.6 1664.25
  5097.9  1664.5  5106.1 1665.66  5112.4  1665.9  5126.9 1667.21  5170.9  1668.4
#Mann= 5 ,-1 , 0
  4795.8      .1       0  4968.9     .16       0  4974.5     .07       0
  4980.5     .16       0  5036.5      .1       0
Bank Sta=4974.5,4980.5
XS Rating Curve= 0 ,0
Exp/Cntr=0.3,0.1

Type RM Length L Ch R = 1 ,1155    ,258,258,258
BEGIN DESCRIPTION:
Mapping XS cef75d93
END DESCRIPTION:
XS GIS Cut Line= 2
       2757294.1     10039359.48      2757897.46     10039049.12
#Sta/Elev= 30
  4727.7 1662.92  4794.7 1661.17  4822.6 1661.79  4855.6 1659.94  4861.2  1660.4
  4899.9 1658.74  4922.1 1659.14    4935 1658.55  4981.9 1653.88  4985.6 1653.48
  4988.4 1652.98  4991.6 1653.48  5010.8 1653.62  5016.4 1654.81    5033 1654.77
  5038.6 1655.83    5070 1657.17    5115 1660.49  5127.3 1662.25  5143.9 1662.09
  5149.5 1662.98  5182.4 1663.91  5196.7 1665.11  5283.6 1670.15  5343.5 1672.29
    5360 1672.11  5365.6    1673  5382.2 1672.34  5387.8 1673.42  5406.2 1673.49
#Mann= 5 ,-1 , 0
  4727.7      .1       0  4981.9     .16       0  4985.6     .07       0
  4991.6     .16       0  5196.7      .1       0
Bank Sta=4985.6,4991.6
XS Rating Curve= 0 ,0
Exp/Cntr=0.3,0.1

Type RM Length L Ch R = 1 ,897     ,56,56,56
BEGIN DESCRIPTION:
Mapping XS 59389190
END DESCRIPTION:
XS GIS Cut Line= 4
      2757359.19     10039420.22      2757519.82     10039431.08
       2757593.6     10039476.65      2757921.26     10039454.95
#Sta/Elev= 30
  4720.9 1659.94  4750.2 1659.16  4770.3 1656.68  4790.3 1655.41  4840.5  1656.8
  4850.8 1656.27    4884 1656.95  4891.3 1656.06  4897.2 1656.92  4912.6 1653.73
  4918.5 1654.64  4933.9 1651.55  4939.7 1652.38  4949.3 1651.39  4955.1 1652.32
  4968.5 1651.26  5020.6 1651.05  5023.4 1650.55  5026.6 1651.05  5063.7 1651.32
  5073.7 1652.32  5083.6 1654.51  5088.6 1654.19  5093.8 1656.36  5113.8 1660.43
  5123.8 1661.41  5234.1 1668.01  5284.2 1672.36  5293.1 1674.11    5297 1674.11
#Mann= 4 ,-1 , 0
  4720.9      .1       0  4850.8     .16       0  5020.6     .07       0
  5026.6     .16       0
Bank Sta=5020.6,5026.6
XS Rating Curve= 0 ,0
Exp/Cntr=0.3,0.1

Type RM Length L Ch R = 1 ,841     ,44,44,44
BEGIN DESCRIPTION:
UNT 1076 IN HEWA 2.0
END DESCRIPTION:
XS GIS Cut Line= 4
      2757320.15     10039452.78       2757506.8     10039476.65
      2757610.97      10039530.9      2757953.69     10039511.38
#Sta/Elev= 30
  4681.5 1661.09  4750.4 1658.69  4780.6 1655.78  4821.5 1655.56    4828 1655.26
  4830.8 1654.76    4834 1655.26  4851.2 1655.96    4868 1659.92  4882.8  1658.8
  4892.1 1659.78  4897.8 1656.67  4914.2 1660.57  4919.9 1658.55  4927.9 1660.33
  4936.3 1660.49    4942 1659.33  4958.4 1660.34  4964.1 1658.65  4980.5 1660.03
  4984.8 1656.75  4987.1 1656.75  5004.7 1659.09  5044.7 1661.17  5064.7 1661.48
  5104.8  1660.1  5144.9 1661.35  5305.1 1671.29  5325.2  1673.4  5330.4 1675.22
#Mann= 4 ,-1 , 0
  4681.5      .1       0  4821.5     .16       0    4828     .07       0
    4834     .16       0
Bank Sta=4828,4834
XS Rating Curve= 0 ,0
Exp/Cntr=0.3,0.1

Type RM Length L Ch R = 1 ,797     ,261,261,261
BEGIN DESCRIPTION:
Mapping XS 9712d683
END DESCRIPTION:
XS GIS Cut Line= 4
      2757328.89     10039563.45      2757498.12     10039543.92
      2757595.78     10039574.31      2757910.48     10039580.82
#Sta/Elev= 30
  4700.2 1658.95  4719.9 1658.93  4780.3 1655.74  4804.3 1655.13  4827.1 1653.78
  4840.7 1653.69  4850.8 1652.74  4860.8 1652.73  4868.2 1655.01  4873.3 1655.01
  4881.4 1654.72  4886.7 1653.18  4891.9 1652.74    4957 1652.34  4965.2 1651.59
  4971.6 1650.07  4995.5 1648.77  5002.5 1647.92  5005.3 1647.42  5008.5 1647.92
  5025.5 1650.88  5085.5 1656.08  5145.6 1660.09  5175.6 1662.73  5205.6 1663.54
  5242.2 1665.95  5255.6 1667.03  5275.6 1667.59  5284.1  1668.8  5287.6  1668.8
#Mann= 5 ,-1 , 0
  4700.2      .1       0  4804.3     .16       0  5002.5     .07       0
  5008.5     .16       0  5242.2      .1       0
Bank Sta=5002.5,5008.5
XS Rating Curve= 0 ,0
Exp/Cntr=0.3,0.1

Type RM Length L Ch R = 1 ,536     ,220,220,220
BEGIN DESCRIPTION:
Mapping XS 26452f39
END DESCRIPTION:
XS GIS Cut Line= 3
       2757389.6     10039715.36      2757678.24     10039865.11
      2757954.42     10039729.17
#Sta/Elev= 30
  4762.9 1653.34  4790.9 1650.91    4813 1649.75  4831.6 1649.38  4857.2 1648.87
  4893.6 1649.68  4945.7 1648.96  4975.7 1647.25  4995.2  1644.9    4998  1644.4
  5001.2  1644.9  5006.5 1644.98  5028.6 1647.74  5043.3 1647.95  5050.7  1648.5
  5056.3 1647.66  5072.8 1648.22  5078.5 1647.91  5098.2  1649.1  5103.8 1649.02
  5177.5 1653.56  5244.4  1656.8  5255.5 1656.63  5261.1 1657.68  5283.5 1656.37
  5300.1 1658.07    5306 1660.26  5311.6 1661.39  5322.4 1662.48  5395.9 1666.55
#Mann= 5 ,-1 , 0
  4762.9      .1       0  4831.6     .16       0  4893.6      .1       0
  4995.2     .07       0  5001.2      .1       0
Bank Sta=4995.2,5001.2
XS Rating Curve= 0 ,0
Exp/Cntr=0.3,0.1

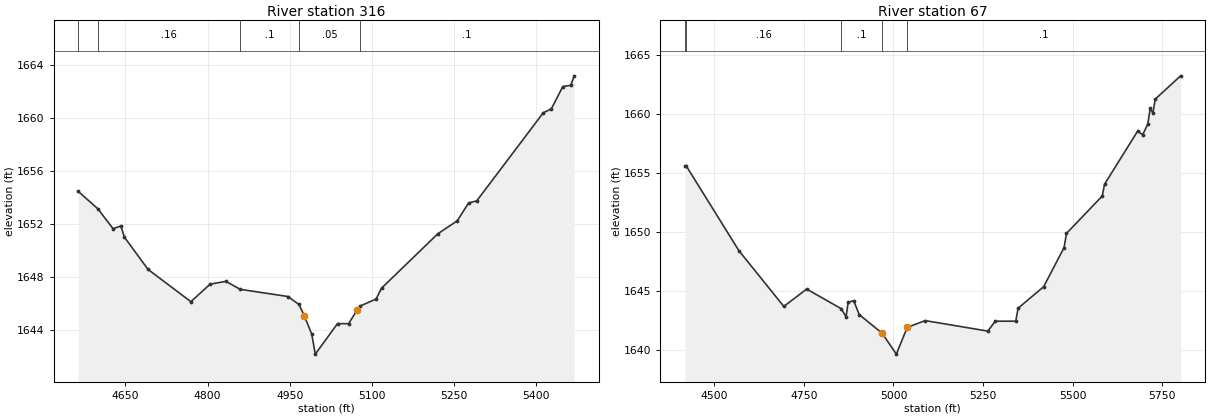
Type RM Length L Ch R = 1 ,316     ,204,204,204
BEGIN DESCRIPTION:
Mapping XS 750b1fce
END DESCRIPTION:
XS GIS Cut Line= 4
      2757344.13     10039738.79      2757543.81     10039986.22
      2757802.06      10040016.6        2758069.     10039825.62
#Sta/Elev= 30
  4563.8 1654.47  4599.4 1653.17  4627.2 1651.67  4641.6 1651.87    4648 1651.03
  4691.2  1648.6  4769.5 1646.17  4804.7 1647.49  4833.5  1647.7  4859.7  1647.1
  4946.8 1646.56    4967 1645.96  4977.1 1645.09  4990.5 1643.71  4996.9 1642.22
  5037.5 1644.52  5057.6 1644.51  5073.6 1645.55  5078.6 1645.84    5108 1646.37
    5118 1647.19  5220.7 1651.28  5256.3 1652.26  5277.2 1653.61  5291.9 1653.76
  5413.6  1660.4  5428.3 1660.69  5449.2 1662.37  5463.9 1662.47    5470 1663.18
#Mann= 5 ,-1 , 0
  4563.8      .1       0  4599.4     .16       0  4859.7      .1       0
    4967     .05       0  5078.6      .1       0
Bank Sta=4977.1,5073.6
XS Rating Curve= 0 ,0
Exp/Cntr=0.3,0.1

Type RM Length L Ch R = 1 ,67      ,0,0,0
BEGIN DESCRIPTION:
UNT 1076 IN HEWA 1.0
END DESCRIPTION:
XS GIS Cut Line= 4
      2757306.68     10039776.09      2757593.16     10040240.54
      2757775.45     10040247.05      2758274.05     10039819.99
#Sta/Elev= 30
  4417.3 1655.58  4421.7 1655.56  4568.4  1648.4  4693.8 1643.68  4757.6 1645.15
  4854.1 1643.49  4867.6  1642.8  4873.5 1644.02  4888.9 1644.17  4904.3 1642.99
  4968.3 1641.41  5008.1 1639.64  5038.3  1641.9  5088.4 1642.48  5263.5 1641.59
  5284.4 1642.43  5341.5 1642.43  5348.1 1643.53  5419.4 1645.35  5476.5 1648.67
  5483.1 1649.86    5583 1653.03  5589.5 1654.03  5681.7 1658.52    5696 1658.22
  5710.3 1659.13  5716.9 1660.45  5724.5 1660.06  5731.1 1661.24  5801.9 1663.21
#Mann= 5 ,-1 , 0
  4417.3      .1       0  4421.7     .16       0  4854.1      .1       0
  4968.3     .05       0  5038.3      .1       0
Bank Sta=4968.3,5038.3
XS Rating Curve= 0 ,0
Exp/Cntr=0.3,0.1

Chan Stop Cuts=-1
Use User Specified Reach Order=0
Composite Channel Slope=5