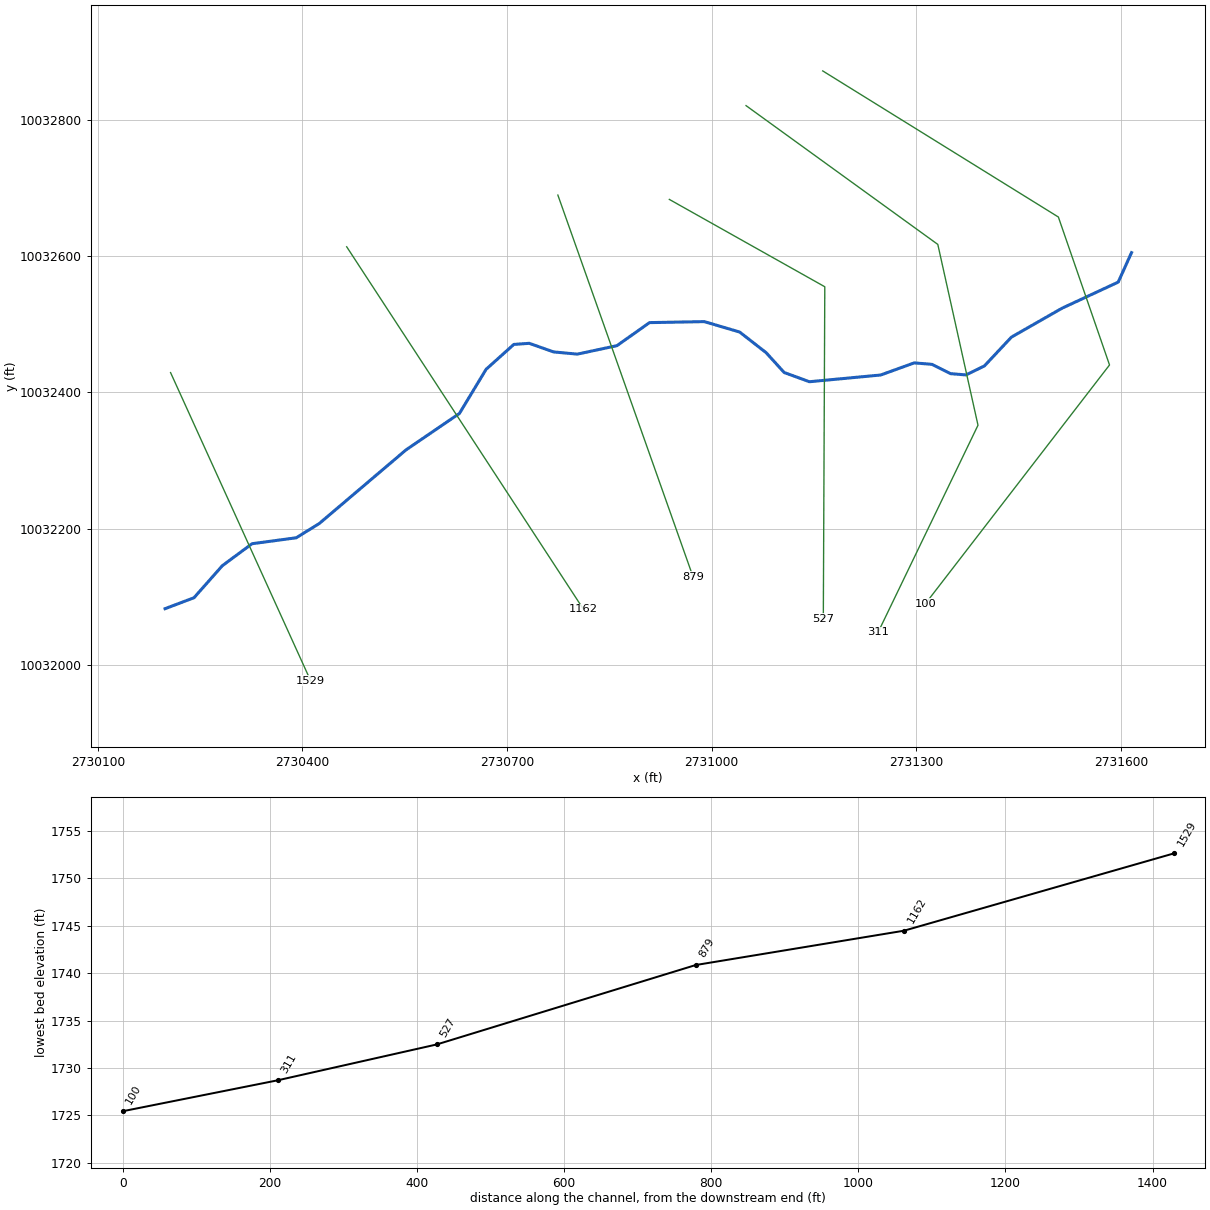
--- UNT 1077 IN HEWA.prj (project) ---

Proj Title=UNT 1077 IN HEWA Base Level Engineering
Current Plan=p01
Default Exp/Contr=0.3,0.1
English Units
Geom File=g01
Flow File=f01
Plan File=p01
Y Axis Title=Elevation
X Axis Title(PF)=Main Channel Distance
X Axis Title(XS)=Station
BEGIN DESCRIPTION:
UNT 1077 IN HEWA
END DESCRIPTION:
DSS Export Rating Curves= 0
DSS Export Rating Curve Sorted= 0
DSS Export Volume Flow Curves= 0
DXF OffsetX= 0
DXF OffsetY= 0
DXF ScaleX= 1
DXF ScaleY= 10

--- UNT 1077 IN HEWA.p01 (plan) ---

Plan Title=Multiple Run
Short Identifier=Multiple
Geom File=g01
Flow File=f01
Subcritical Flow
K Sum by GR= 0
Std Step Tol= 0.01
Critical Tol= 0.01
Num of Std Step Trials= 20
Max Error Tol= 0.3
Flow Tol Ratio= 0.001
Split Flow NTrial= 30
Split Flow Tol= 0.02
Split Flow Ratio= 0.02
Log Output Level= 0
Friction Slope Method= 1
Unsteady Friction Slope Method= 2
Unsteady Bridges Friction Slope Method= 1
Parabolic Critical Depth
Global Vel Dist=  1 , 1 , 1
Global Log Level= 0
CheckData=True
Encroach Param= -1, 0, 0, 0
BEGIN DESCRIPTION:
Multiple Run
END DESCRIPTION:

--- UNT 1077 IN HEWA.f01 (steady flow) ---

Flow Title=Multiple
Program Version=4.10
Number of Profiles= 7
Profile Names=10-year,25-year,50-year,1pct_min,100-year,1pct_plu,500-year
River Rch & RM=UNT 1077 IN HEWA,Reach-1         ,1529
     666     954    1201    1109    1500    2029    2347
Boundary for River Rch & Prof#=UNT 1077 IN HEWA,Reach-1         , 1
Up Type= 0
Dn Type= 3
Dn Slope=0.01
Boundary for River Rch & Prof#=UNT 1077 IN HEWA,Reach-1         , 2
Up Type= 0
Dn Type= 3
Dn Slope=0.01
Boundary for River Rch & Prof#=UNT 1077 IN HEWA,Reach-1         , 3
Up Type= 0
Dn Type= 3
Dn Slope=0.01
Boundary for River Rch & Prof#=UNT 1077 IN HEWA,Reach-1         , 4
Up Type= 0
Dn Type= 3
Dn Slope=0.01
Boundary for River Rch & Prof#=UNT 1077 IN HEWA,Reach-1         , 5
Up Type= 0
Dn Type= 3
Dn Slope=0.01
Boundary for River Rch & Prof#=UNT 1077 IN HEWA,Reach-1         , 6
Up Type= 0
Dn Type= 3
Dn Slope=0.01
Boundary for River Rch & Prof#=UNT 1077 IN HEWA,Reach-1         , 7
Up Type= 0
Dn Type= 3
Dn Slope=0.01
DSS Import GetInterval= 0
DSS Import GetPeak= 0
DSS Import FillOption= 0

--- UNT 1077 IN HEWA.g01 (geometry) ---

Geom Title=Existing Conditions
Program Version=4.10

River Reach=UNT 1077 IN HEWA,Reach-1
Reach XY= 30
      2730198.58     10032082.79        2730241.     10032098.84
      2730282.65      10032145.9      2730326.12     10032178.05
       2730390.9     10032186.76      2730424.75     10032207.71
      2730551.85     10032315.64      2730630.18     10032369.06
      2730669.25     10032433.77      2730709.91     10032470.28
      2730732.54     10032471.89      2730768.17      10032459.3
        2730803.     10032456.05      2730861.12     10032468.48
      2730908.88     10032502.26      2730989.23     10032503.72
      2731041.05     10032488.43      2731079.92     10032458.12
      2731106.28     10032429.12      2731143.32     10032415.57
      2731247.81     10032425.44      2731296.97     10032443.21
      2731322.85     10032441.09      2731350.26     10032427.43
      2731372.88     10032425.54      2731399.95     10032438.79
      2731439.52     10032481.01      2731513.68     10032523.36
      2731596.08     10032561.65      2731615.57     10032604.88

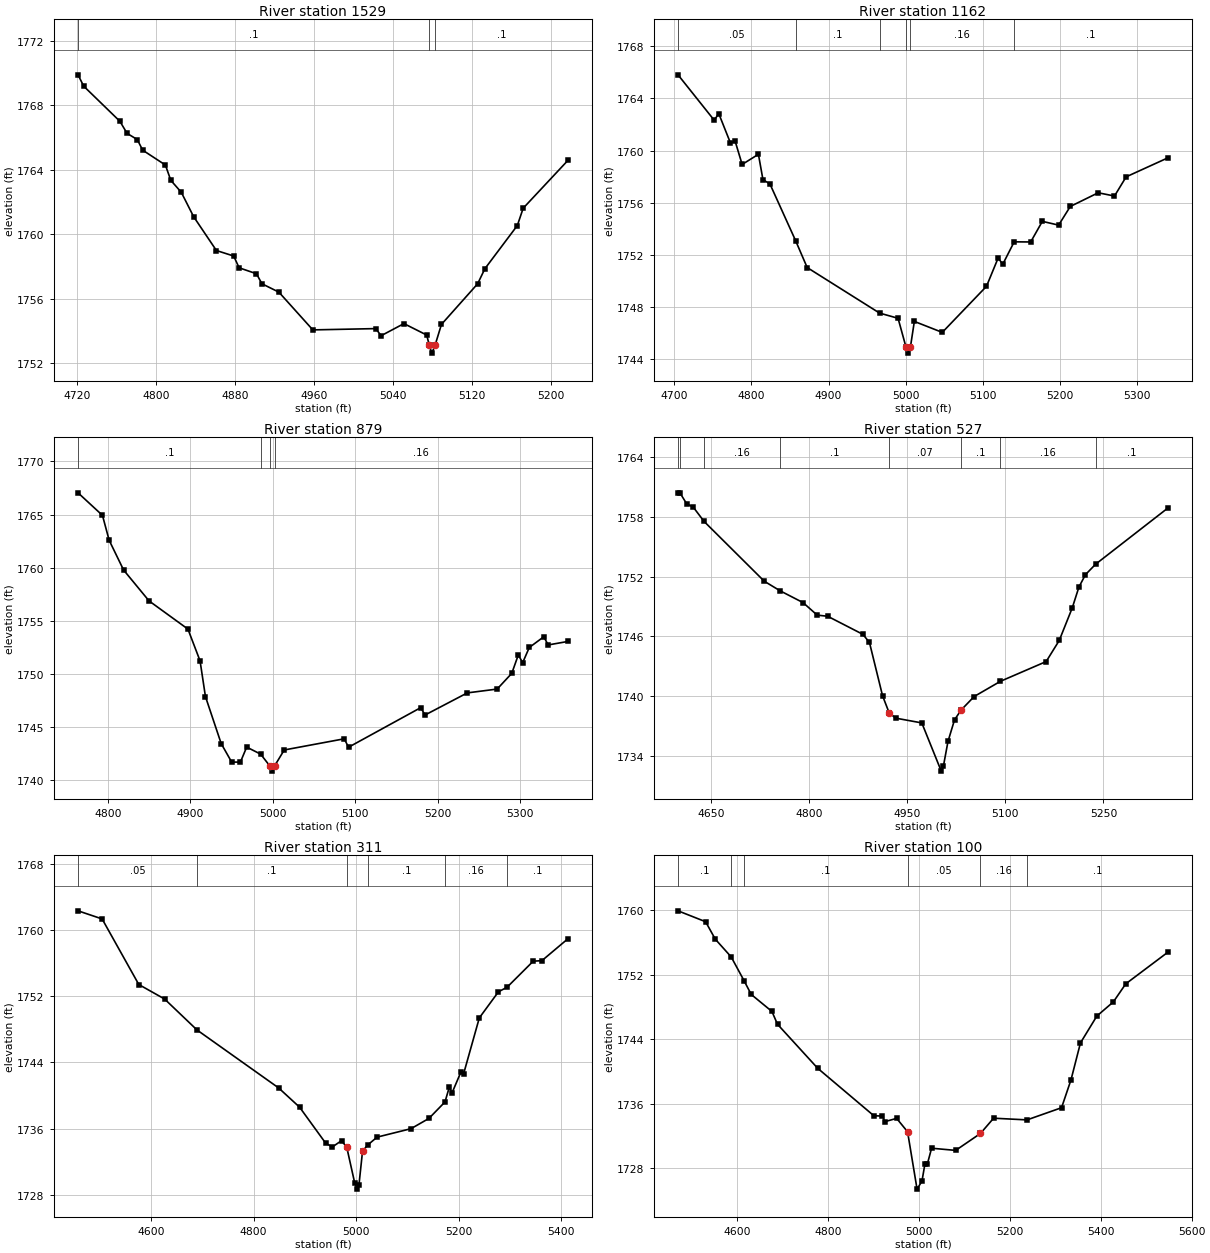
Type RM Length L Ch R = 1 ,1529    ,367,367,367
BEGIN DESCRIPTION:
UNT 1077 IN HEWA 3.0
END DESCRIPTION:
XS GIS Cut Line= 2
      2730206.66     10032428.96      2730412.07     10031977.05
#Sta/Elev= 30
  4721.1 1769.89  4726.8 1769.19  4763.5 1767.01  4770.8 1766.26  4781.1 1765.88
  4786.6 1765.22  4809.6  1764.3  4815.1 1763.35  4825.7 1762.61  4838.2  1761.1
  4861.3    1759  4878.8 1758.66  4884.3 1757.93  4901.9 1757.56  4907.4 1756.94
  4924.6 1756.42    4959 1754.08  5022.7 1754.16  5028.2 1753.72  5051.3 1754.47
  5074.4 1753.76  5076.9 1753.14  5079.6 1752.64  5082.9 1753.14  5089.3 1754.42
    5126 1756.94  5133.3 1757.87  5166.2 1760.55  5172.1 1761.62  5217.5 1764.59
#Mann= 3 ,-1 , 0
  4721.1      .1       0  5076.9     .07       0  5082.9      .1       0
Bank Sta=5076.9,5082.9
XS Rating Curve= 0 ,0
Exp/Cntr=0.3,0.1

Type RM Length L Ch R = 1 ,1162    ,283,283,283
BEGIN DESCRIPTION:
Mapping XS 829e42d1
END DESCRIPTION:
XS GIS Cut Line= 2
      2730464.89     10032613.46       2730812.1     10032081.79
#Sta/Elev= 30
  4704.9 1765.81  4751.8 1762.33  4757.7 1762.84  4772.9 1760.58  4778.8 1760.75
    4788 1758.94  4809.1 1759.72    4815 1757.77    4824 1757.45  4857.3  1753.1
  4872.3 1751.04  4966.1 1747.55  4990.1 1747.15  5000.2 1744.98  5002.9 1744.48
  5006.2 1744.98  5011.2 1746.91  5047.4 1746.07  5104.7  1749.6  5119.8 1751.77
  5125.8 1751.29  5140.6 1753.01    5162    1753  5177.1 1754.58  5198.2 1754.29
  5213.3 1755.72  5249.5 1756.77  5270.6 1756.52  5285.7 1757.99  5339.9 1759.45
#Mann= 6 ,-1 , 0
  4704.9     .05       0  4857.3      .1       0  4966.1     .16       0
  5000.2     .07       0  5006.2     .16       0  5140.6      .1       0
Bank Sta=5000.2,5006.2
XS Rating Curve= 0 ,0
Exp/Cntr=0.3,0.1

Type RM Length L Ch R = 1 ,879     ,352,352,352
BEGIN DESCRIPTION:
Mapping XS 6222a762
END DESCRIPTION:
XS GIS Cut Line= 2
      2730774.51     10032689.27       2730972.7     10032129.52
#Sta/Elev= 30
    4764 1767.04  4793.6 1764.92  4801.7 1762.58  4819.2 1759.78  4850.1 1756.87
  4897.2 1754.22  4911.9 1751.23  4918.4 1747.88  4937.5 1743.45  4950.2 1741.71
  4960.8 1741.71  4968.4 1743.12  4985.3 1742.46  4996.3 1741.36    4999 1740.86
  5002.3 1741.36  5013.9 1742.85  5086.6  1743.9  5091.9 1743.11  5179.3 1746.83
  5184.6 1746.14  5235.8 1748.22    5272 1748.58  5289.7 1750.06  5297.6 1751.79
  5302.9 1751.06  5310.9 1752.49  5328.5  1753.5  5333.8 1752.73  5357.8 1753.06
#Mann= 4 ,-1 , 0
    4764      .1       0  4985.3     .16       0  4996.3     .07       0
  5002.3     .16       0
Bank Sta=4996.3,5002.3
XS Rating Curve= 0 ,0
Exp/Cntr=0.3,0.1

Type RM Length L Ch R = 1 ,527     ,216,216,216
BEGIN DESCRIPTION:
UNT 1077 IN HEWA 2.0
END DESCRIPTION:
XS GIS Cut Line= 3
      2730937.98     10032682.89      2731165.86     10032554.84
      2731163.69     10032067.63
#Sta/Elev= 30
  4599.9 1760.42  4602.8 1760.42    4613 1759.33  4623.2 1758.98  4639.7 1757.55
  4731.6 1751.55  4755.7 1750.59  4790.9  1749.4  4812.6 1748.14  4828.5 1748.03
  4882.4 1746.21  4892.4  1745.4  4912.4 1740.05  4922.4 1738.35  4932.4  1737.8
  4972.4 1737.32  5002.1 1732.48  5005.4 1732.98  5012.4 1735.46  5022.4 1737.63
  5032.4 1738.61  5052.4 1739.97  5092.6  1741.5  5162.4 1743.48  5182.4  1745.6
  5202.4 1748.89  5212.4 1750.95  5222.4  1752.2  5237.9 1753.25  5348.5  1758.9
#Mann= 8 ,-1 , 0
  4599.9     .05       0  4602.8      .1       0  4639.7     .16       0
  4755.7      .1       0  4922.4     .07       0  5032.4      .1       0
  5092.6     .16       0  5237.9      .1       0
Bank Sta=4922.4,5032.4
XS Rating Curve= 0 ,0
Exp/Cntr=0.3,0.1

Type RM Length L Ch R = 1 ,311     ,211,211,211
BEGIN DESCRIPTION:
Mapping XS b5f9ba5d
END DESCRIPTION:
XS GIS Cut Line= 4
      2731050.39     10032820.44      2731331.56     10032616.92
      2731390.48     10032351.79      2731243.87      10032047.9
#Sta/Elev= 30
  4457.4 1762.31  4504.4 1761.33    4576 1753.41  4626.3 1751.66  4689.6 1747.92
  4848.7 1740.93  4889.7  1738.6  4940.9 1734.23  4953.9  1733.8  4971.7 1734.56
  4981.9 1733.73  4997.5 1729.39  5002.3  1728.7  5005.6  1729.2  5012.6 1733.28
  5022.9 1734.04    5041 1734.98  5107.2    1736  5142.2 1737.24  5173.5 1739.23
  5181.9 1741.01  5187.4 1740.34  5204.5 1742.83    5210 1742.66  5240.5 1749.38
  5277.8 1752.53  5294.8 1753.09  5345.7 1756.23  5362.6 1756.29  5413.5 1758.94
#Mann= 6 ,-1 , 0
  4457.4     .05       0  4689.6      .1       0  4981.9     .07       0
  5022.9      .1       0  5173.5     .16       0  5294.8      .1       0
Bank Sta=4981.9,5012.6
XS Rating Curve= 0 ,0
Exp/Cntr=0.3,0.1

Type RM Length L Ch R = 1 ,100     ,0,0,0
BEGIN DESCRIPTION:
UNT 1077 IN HEWA 1.0
END DESCRIPTION:
XS GIS Cut Line= 4
      2731162.84     10032871.34      2731508.32     10032657.09
      2731583.31     10032440.17      2731313.15     10032089.76
#Sta/Elev= 30
  4469.3 1759.92    4530 1758.57  4551.3 1756.41  4586.3 1754.21  4614.5 1751.28
  4630.4 1749.56    4676 1747.45  4688.3 1745.86  4776.9  1740.4  4900.5 1734.52
  4919.3 1734.49  4924.6 1733.79  4950.5  1734.2  4974.6 1732.54  4995.5 1725.43
  5006.3 1726.42  5012.8 1728.55  5018.1 1728.53  5027.5  1730.5  5080.5 1730.23
  5135.1 1732.33    5164 1734.22  5237.5 1734.01  5313.6 1735.52  5334.4 1738.98
  5355.2 1743.55  5391.3 1746.88  5427.7 1748.64  5454.9 1750.87  5547.8  1754.8
#Mann= 6 ,-1 , 0
  4469.3      .1       0  4586.3     .05       0  4614.5      .1       0
  4974.6     .05       0  5135.1     .16       0  5237.5      .1       0
Bank Sta=4974.6,5135.1
XS Rating Curve= 0 ,0
Exp/Cntr=0.3,0.1

Chan Stop Cuts=-1
Use User Specified Reach Order=0
Composite Channel Slope=5