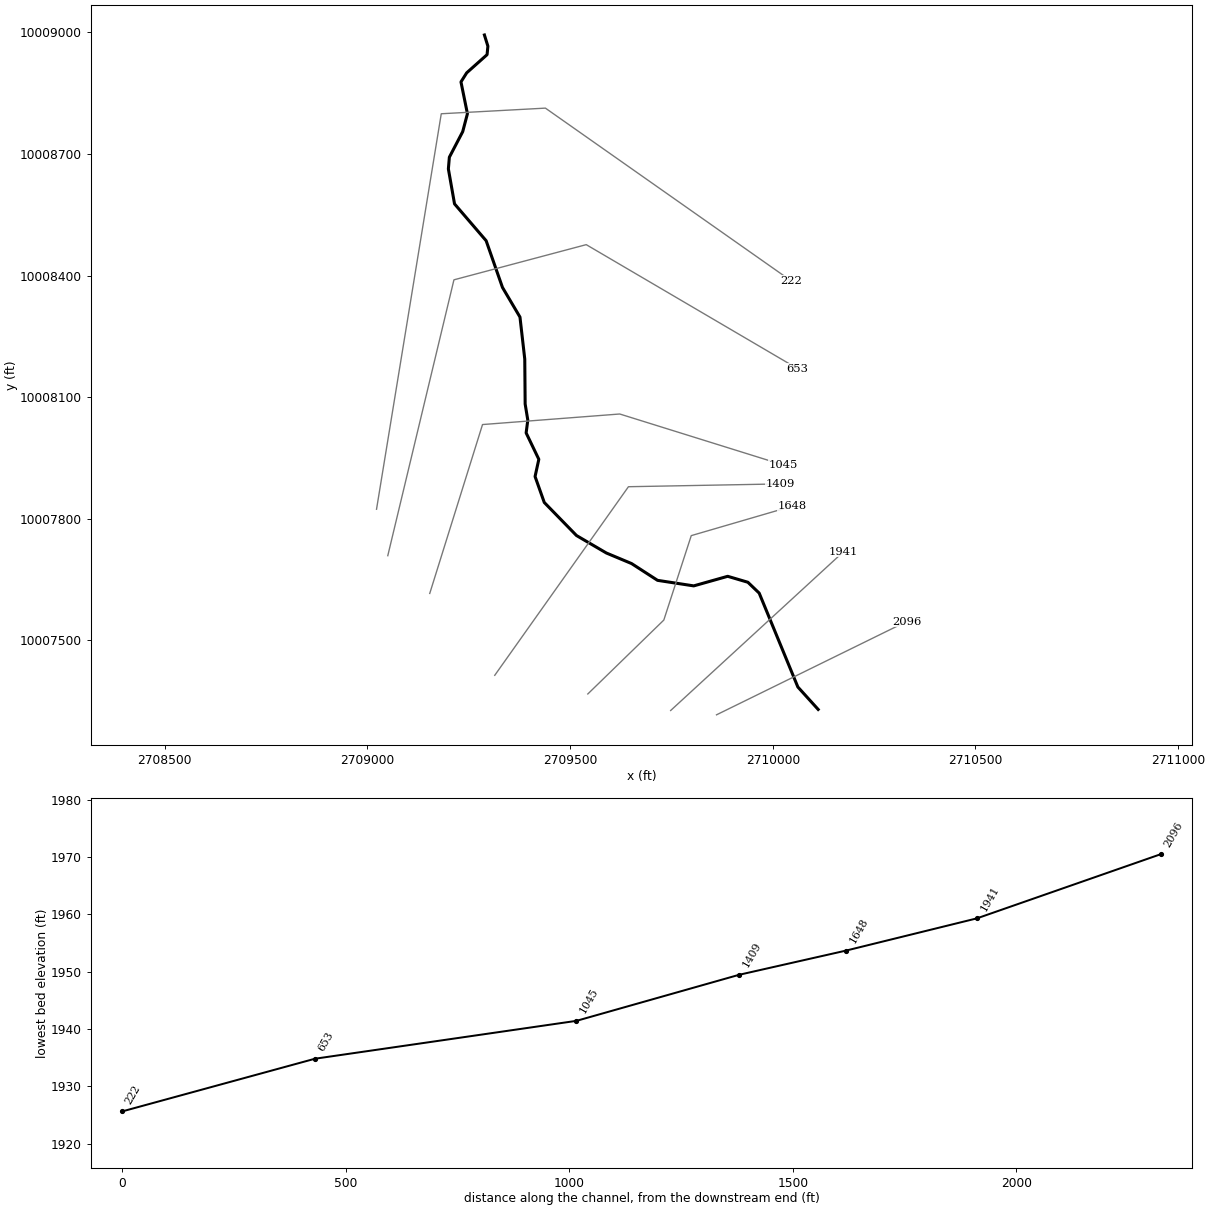
--- UNT 1078 IN HEWA.prj (project) ---

Proj Title=UNT 1078 IN HEWA Base Level Engineering
Current Plan=p01
Default Exp/Contr=0.3,0.1
English Units
Geom File=g01
Flow File=f01
Plan File=p01
Y Axis Title=Elevation
X Axis Title(PF)=Main Channel Distance
X Axis Title(XS)=Station
BEGIN DESCRIPTION:
UNT 1078 IN HEWA
END DESCRIPTION:
DSS Export Rating Curves= 0
DSS Export Rating Curve Sorted= 0
DSS Export Volume Flow Curves= 0
DXF OffsetX= 0
DXF OffsetY= 0
DXF ScaleX= 1
DXF ScaleY= 10

--- UNT 1078 IN HEWA.p01 (plan) ---

Plan Title=Multiple Run
Short Identifier=Multiple
Geom File=g01
Flow File=f01
Subcritical Flow
K Sum by GR= 0
Std Step Tol= 0.01
Critical Tol= 0.01
Num of Std Step Trials= 20
Max Error Tol= 0.3
Flow Tol Ratio= 0.001
Split Flow NTrial= 30
Split Flow Tol= 0.02
Split Flow Ratio= 0.02
Log Output Level= 0
Friction Slope Method= 1
Unsteady Friction Slope Method= 2
Unsteady Bridges Friction Slope Method= 1
Parabolic Critical Depth
Global Vel Dist=  1 , 1 , 1
Global Log Level= 0
CheckData=True
Encroach Param= -1, 0, 0, 0
BEGIN DESCRIPTION:
Multiple Run
END DESCRIPTION:

--- UNT 1078 IN HEWA.f01 (steady flow) ---

Flow Title=Multiple
Program Version=4.10
Number of Profiles= 7
Profile Names=10-year,25-year,50-year,1pct_min,100-year,1pct_plu,500-year
River Rch & RM=UNT 1078 IN HEWA,Reach-1         ,2096
     497     687     844     759    1027    1389    1514
Boundary for River Rch & Prof#=UNT 1078 IN HEWA,Reach-1         , 1
Up Type= 0
Dn Type= 3
Dn Slope=0.015
Boundary for River Rch & Prof#=UNT 1078 IN HEWA,Reach-1         , 2
Up Type= 0
Dn Type= 3
Dn Slope=0.015
Boundary for River Rch & Prof#=UNT 1078 IN HEWA,Reach-1         , 3
Up Type= 0
Dn Type= 3
Dn Slope=0.015
Boundary for River Rch & Prof#=UNT 1078 IN HEWA,Reach-1         , 4
Up Type= 0
Dn Type= 3
Dn Slope=0.015
Boundary for River Rch & Prof#=UNT 1078 IN HEWA,Reach-1         , 5
Up Type= 0
Dn Type= 3
Dn Slope=0.015
Boundary for River Rch & Prof#=UNT 1078 IN HEWA,Reach-1         , 6
Up Type= 0
Dn Type= 3
Dn Slope=0.015
Boundary for River Rch & Prof#=UNT 1078 IN HEWA,Reach-1         , 7
Up Type= 0
Dn Type= 3
Dn Slope=0.015
DSS Import GetInterval= 0
DSS Import GetPeak= 0
DSS Import FillOption= 0

--- UNT 1078 IN HEWA.g01 (geometry) ---

Geom Title=Existing Conditions
Program Version=4.10

River Reach=UNT 1078 IN HEWA,Reach-1
Reach XY= 30
      2710111.91     10007329.73      2710061.78     10007385.08
      2709966.37     10007616.78      2709938.45     10007643.54
      2709888.65      10007658.2      2709804.87     10007634.59
      2709715.58     10007648.25      2709651.49     10007689.67
       2709589.3      10007715.7      2709515.64     10007758.82
      2709436.15     10007840.37      2709413.44     10007904.41
      2709422.71     10007946.84      2709391.41       10008012.
      2709395.51     10008043.58      2709388.99     10008083.19
      2709388.01     10008194.19      2709376.19     10008297.79
      2709333.02      10008370.9      2709292.74     10008486.11
      2709214.75       10008577.      2709199.56     10008663.26
      2709201.99     10008692.17      2709234.94     10008755.28
      2709246.57     10008799.46      2709230.63     10008877.96
      2709244.78     10008900.37      2709295.03     10008945.17
      2709297.05     10008966.07      2709288.47     10008993.73

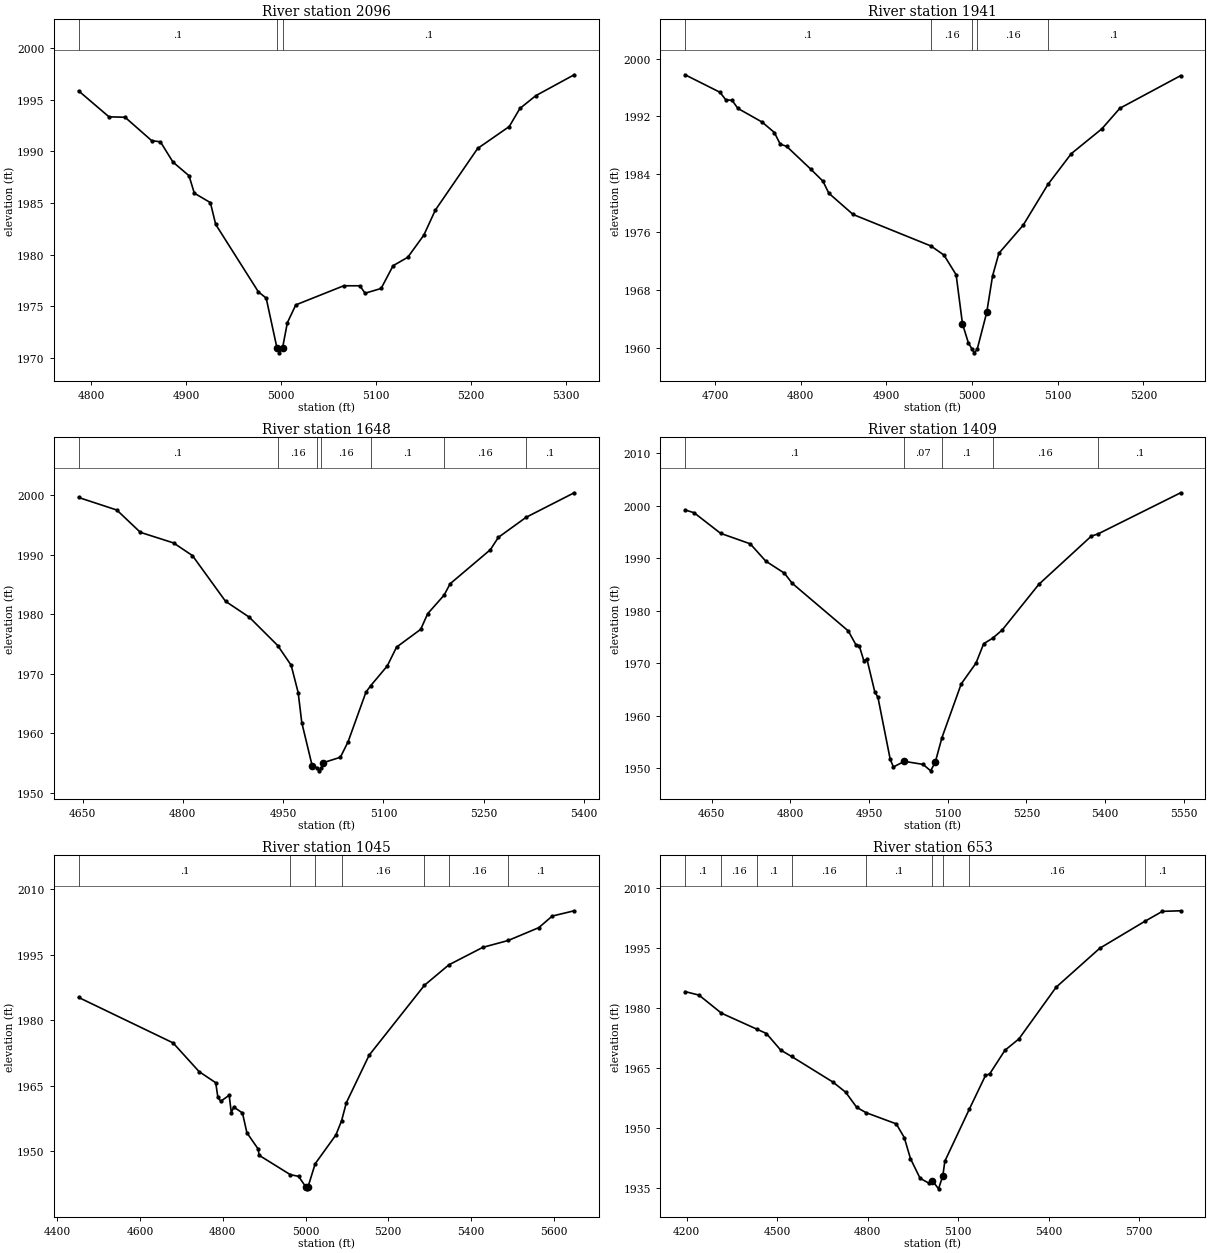
Type RM Length L Ch R = 1 ,2096    ,411,411,411
BEGIN DESCRIPTION:
UNT 1078 IN HEWA 4.0
END DESCRIPTION:
XS GIS Cut Line= 2
      2709861.08     10007316.46      2710329.78     10007546.48
#Sta/Elev= 30
  4786.9 1995.85  4818.9 1993.34  4835.8  1993.3  4863.8 1991.04  4873.1 1990.92
  4886.3 1988.96  4903.2 1987.64  4908.8 1985.95  4925.7 1985.04  4931.3 1982.93
  4976.3  1976.4  4984.5  1975.8  4995.8    1971  4998.5  1970.5  5001.8    1971
  5006.8 1973.41  5015.7 1975.14  5066.2 1976.99  5083.2 1976.99  5088.7 1976.27
  5105.6 1976.73  5118.2 1978.93  5133.7 1979.75  5150.6 1981.89  5162.7 1984.31
  5207.3 1990.28  5240.6  1992.4  5251.8 1994.15  5268.6 1995.39    5309 1997.41
#Mann= 3 ,-1 , 0
  4786.9      .1       0  4995.8     .07       0  5001.8      .1       0
Bank Sta=4995.8,5001.8
XS Rating Curve= 0 ,0
Exp/Cntr=0.3,0.1

Type RM Length L Ch R = 1 ,1941    ,293,293,293
BEGIN DESCRIPTION:
Mapping XS 8a3c06b0
END DESCRIPTION:
XS GIS Cut Line= 2
      2709747.98     10007327.13      2710173.84     10007718.37
#Sta/Elev= 30
  4665.2 1997.77  4705.9 1995.35  4712.7  1994.3    4720 1994.24  4726.8 1993.12
  4755.2 1991.22  4769.4 1989.78  4776.2 1988.17  4783.6 1987.88  4811.9 1984.71
  4826.1 1983.05  4832.9 1981.39  4861.2 1978.45  4952.1 1974.09  4967.3 1972.83
  4981.5 1970.11  4988.9 1963.32  4995.7 1960.72  5000.1 1959.81  5002.8 1959.31
  5006.1 1959.81  5017.2  1964.9    5024 1969.94  5031.4 1973.08  5059.7 1976.96
  5088.6  1982.6  5115.9 1986.86  5151.6  1990.3  5172.6 1993.14  5243.5 1997.65
#Mann= 5 ,-1 , 0
  4665.2      .1       0  4952.1     .16       0  5000.1     .07       0
  5006.1     .16       0  5088.6      .1       0
Bank Sta=4988.9,5017.2
XS Rating Curve= 0 ,0
Exp/Cntr=0.3,0.1

Type RM Length L Ch R = 1 ,1648    ,239,239,239
BEGIN DESCRIPTION:
UNT 1078 IN HEWA 3.0
END DESCRIPTION:
XS GIS Cut Line= 4
      2709543.58     10007367.95      2709731.07     10007550.24
      2709798.78     10007758.57       2710048.8     10007831.49
#Sta/Elev= 30
  4644.2 1999.64  4701.3 1997.53  4736.5 1993.78  4786.1    1992  4814.4 1989.87
  4863.9 1982.18  4899.3 1979.52  4941.9 1974.75    4962 1971.43  4972.5 1966.83
  4977.9 1961.78  4993.5  1954.5    5001 1954.18  5003.8 1953.68    5007 1954.18
  5009.9 1955.05  5035.6 1955.96  5047.1 1958.56  5073.8  1966.9  5080.9 1967.99
  5105.7 1971.31  5119.6 1974.48  5155.7 1977.47  5166.2 1980.11  5190.7 1983.22
  5199.7 1985.13  5259.9 1990.86  5271.8 1992.93  5313.4 1996.31  5385.2 2000.43
#Mann= 7 ,-1 , 0
  4644.2      .1       0  4941.9     .16       0    5001     .07       0
    5007     .16       0  5080.9      .1       0  5190.7     .16       0
  5313.4      .1       0
Bank Sta=4993.5,5009.9
XS Rating Curve= 0 ,0
Exp/Cntr=0.3,0.1

Type RM Length L Ch R = 1 ,1409    ,364,364,364
BEGIN DESCRIPTION:
Mapping XS a8135fd1
END DESCRIPTION:
XS GIS Cut Line= 3
      2709313.99     10007413.98      2709643.83     10007879.23
      2710018.85     10007886.18
#Sta/Elev= 30
    4599 1999.19  4616.2 1998.65  4666.7 1994.73  4723.3 1992.73  4752.8 1989.44
  4788.5 1987.13  4803.3 1985.21  4910.3 1976.13  4925.1 1973.45  4931.2  1973.3
  4939.9 1970.48    4946 1970.71  4960.8 1964.55  4966.9 1963.47  4990.3 1951.67
  4996.4  1950.2  5017.3 1951.27    5053 1950.69  5067.5 1949.46  5076.4 1951.15
    5089 1955.78  5125.8 1966.03  5153.9 1969.98  5168.7  1973.7  5185.8 1974.74
    5204 1976.31    5274 1985.02    5374  1994.2  5386.9 1994.62  5544.4 2002.46
#Mann= 5 ,-1 , 0
    4599      .1       0  5017.3     .07       0    5089      .1       0
  5185.8     .16       0  5386.9      .1       0
Bank Sta=5017.3,5076.4
XS Rating Curve= 0 ,0
Exp/Cntr=0.3,0.1

Type RM Length L Ch R = 1 ,1045    ,585,585,585
BEGIN DESCRIPTION:
UNT 1078 IN HEWA 2.0
END DESCRIPTION:
XS GIS Cut Line= 4
      2709153.58      10007615.9       2709283.8      10008032.6
      2709622.35     10008058.64      2710024.72     10007933.17
#Sta/Elev= 30
  4451.7 1985.22  4679.9 1974.82  4742.8 1968.25    4783  1965.7  4788.2 1962.39
  4795.2 1961.45  4815.5 1962.84  4820.7 1958.86  4826.6 1960.13  4847.6 1958.79
  4858.4 1954.24  4885.7 1950.52  4887.7 1949.11  4963.2 1944.67  4983.2 1944.28
  5000.3 1941.92    5003 1941.42  5006.3 1941.92  5023.3 1947.15  5073.5 1953.76
  5087.2    1957  5098.6 1961.11  5153.7 1971.99  5287.4    1988  5346.5 1992.68
  5428.5 1996.68  5489.8 1998.25  5563.8 2001.19  5596.3 2003.84  5649.3 2005.05
#Mann= 7 ,-1 , 0
  4451.7      .1       0  4963.2     .05       0  5023.3      .1       0
  5087.2     .16       0  5287.4      .1       0  5346.5     .16       0
  5489.8      .1       0
Bank Sta=5000.3,5006.3
XS Rating Curve= 0 ,0
Exp/Cntr=0.3,0.1

Type RM Length L Ch R = 1 ,653     ,431,431,431
BEGIN DESCRIPTION:
Mapping XS 5aa3c5cd
END DESCRIPTION:
XS GIS Cut Line= 4
      2709050.08     10007709.07      2709213.28     10008389.65
      2709539.67     10008476.45      2710060.53     10008170.88
#Sta/Elev= 30
  4195.2  1984.1  4241.1 1983.23  4315.6 1978.71  4432.1 1974.74  4464.6 1973.63
  4511.8 1969.49  4547.9 1967.89    4685 1961.49    4727 1958.96  4763.8 1955.17
  4794.9 1953.84  4894.6 1951.05  4921.1 1947.64  4941.8 1942.35  4973.7 1937.44
  5003.5  1936.2  5014.3 1936.85  5034.7 1934.81  5048.8 1938.03  5055.7 1941.73
  5136.6  1954.7  5190.2 1963.14  5204.2 1963.54  5254.6 1969.43    5301 1972.28
  5424.3  1985.2  5568.9 1994.94  5717.7 2001.65  5776.1 2004.15  5836.7  2004.3
#Mann= 9 ,-1 , 0
  4195.2      .1       0  4315.6     .16       0  4432.1      .1       0
  4547.9     .16       0  4794.9      .1       0  5014.3     .05       0
  5048.8      .1       0  5136.6     .16       0  5717.7      .1       0
Bank Sta=5014.3,5048.8
XS Rating Curve= 0 ,0
Exp/Cntr=0.3,0.1

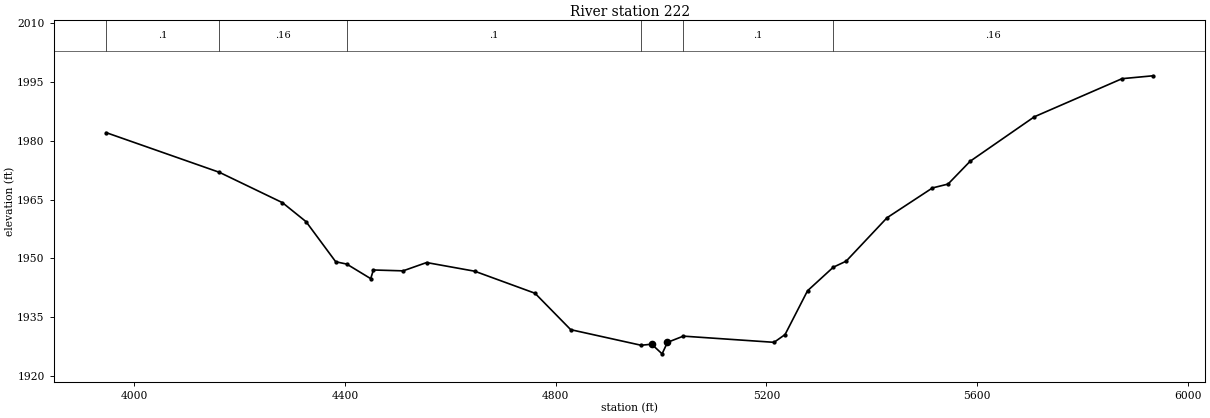
Type RM Length L Ch R = 1 ,222     ,0,0,0
BEGIN DESCRIPTION:
UNT 1078 IN HEWA 1.0
END DESCRIPTION:
XS GIS Cut Line= 4
       2709022.3     10007823.66      2709182.03     10008799.37
      2709438.97     10008813.26      2710045.03     10008387.28
#Sta/Elev= 30
  3946.9  1982.1  4161.9 1971.96  4281.4 1964.22  4326.2 1959.37  4382.5 1949.13
  4403.4 1948.54  4448.9 1944.82    4454 1947.03  4510.3 1946.81    4555 1948.93
  4646.2 1946.72  4760.7 1941.09  4828.5 1931.79  4962.1 1927.81  4982.1 1928.08
  5001.9 1925.62  5012.1 1928.55  5042.2 1930.14  5214.4 1928.56  5235.3 1930.55
  5277.9 1941.72  5326.8 1947.74  5351.2 1949.28  5428.8 1960.37    5515 1967.98
  5544.6 1968.97  5586.5 1974.79  5708.4 1986.15  5874.8 1995.88  5933.7 1996.62
#Mann= 6 ,-1 , 0
  3946.9      .1       0  4161.9     .16       0  4403.4      .1       0
  4962.1     .05       0  5042.2      .1       0  5326.8     .16       0
Bank Sta=4982.1,5012.1
XS Rating Curve= 0 ,0
Exp/Cntr=0.3,0.1

Chan Stop Cuts=-1
Use User Specified Reach Order=0
Composite Channel Slope=5