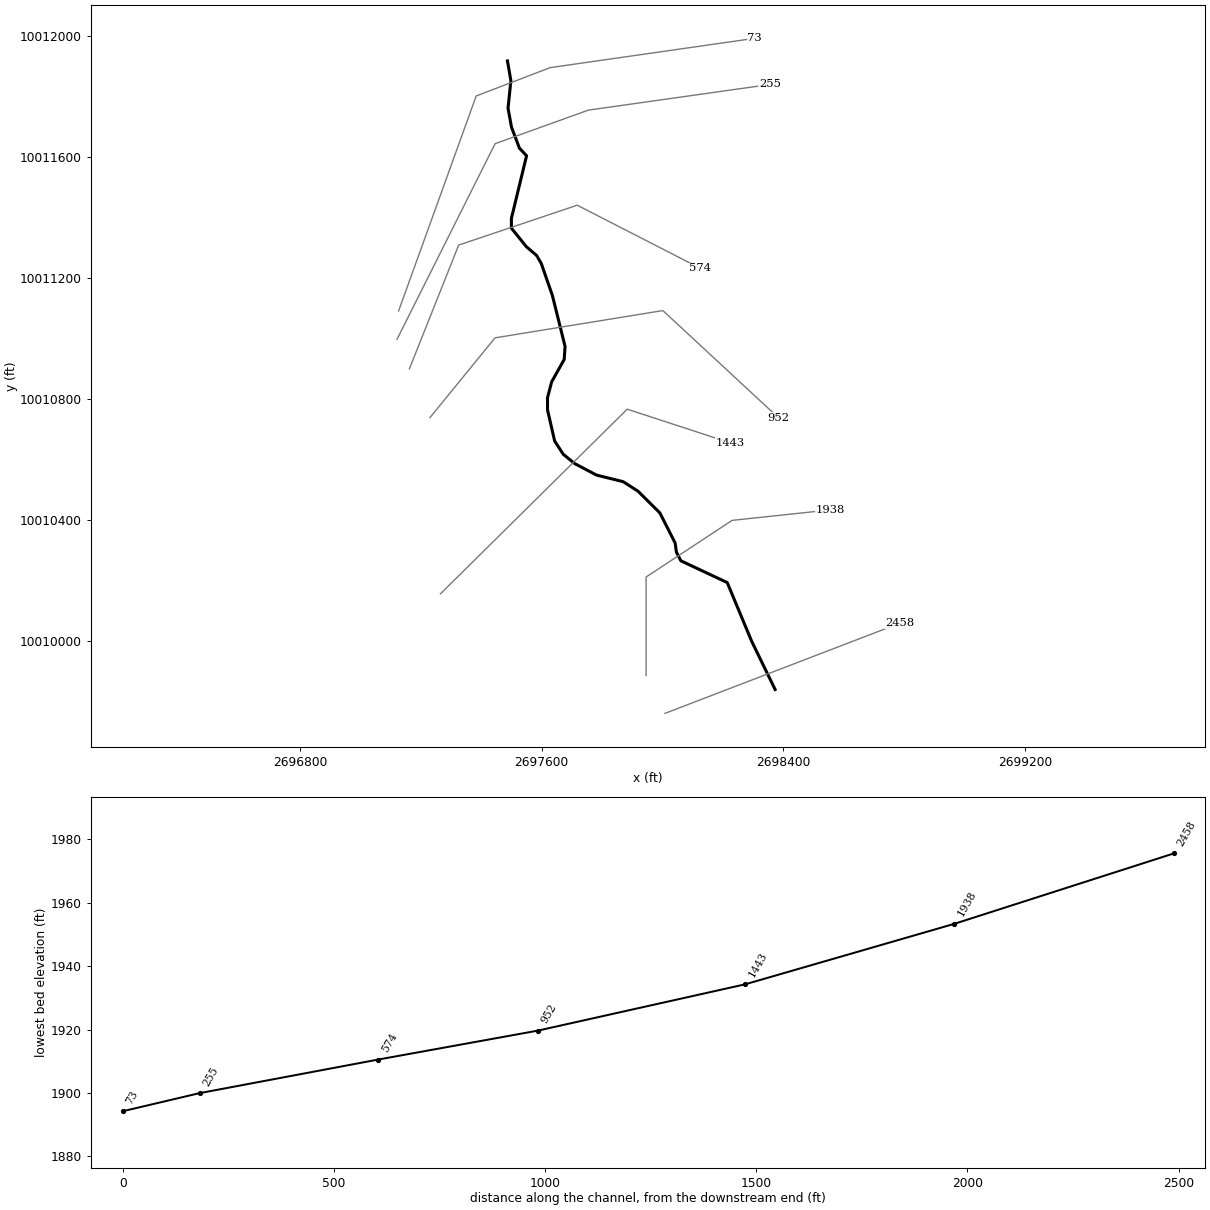
--- UNT 1079 IN HEWA.prj (project) ---

Proj Title=UNT 1079 IN HEWA Base Level Engineering
Current Plan=p01
Default Exp/Contr=0.3,0.1
English Units
Geom File=g01
Flow File=f01
Plan File=p01
Y Axis Title=Elevation
X Axis Title(PF)=Main Channel Distance
X Axis Title(XS)=Station
BEGIN DESCRIPTION:
UNT 1079 IN HEWA
END DESCRIPTION:
DSS Export Rating Curves= 0
DSS Export Rating Curve Sorted= 0
DSS Export Volume Flow Curves= 0
DXF OffsetX= 0
DXF OffsetY= 0
DXF ScaleX= 1
DXF ScaleY= 10

--- UNT 1079 IN HEWA.p01 (plan) ---

Plan Title=Multiple Run
Short Identifier=Multiple
Geom File=g01
Flow File=f01
Subcritical Flow
K Sum by GR= 0
Std Step Tol= 0.01
Critical Tol= 0.01
Num of Std Step Trials= 20
Max Error Tol= 0.3
Flow Tol Ratio= 0.001
Split Flow NTrial= 30
Split Flow Tol= 0.02
Split Flow Ratio= 0.02
Log Output Level= 0
Friction Slope Method= 1
Unsteady Friction Slope Method= 2
Unsteady Bridges Friction Slope Method= 1
Parabolic Critical Depth
Global Vel Dist=  1 , 1 , 1
Global Log Level= 0
CheckData=True
Encroach Param= -1, 0, 0, 0
BEGIN DESCRIPTION:
Multiple Run
END DESCRIPTION:

--- UNT 1079 IN HEWA.f01 (steady flow) ---

Flow Title=Multiple
Program Version=4.10
Number of Profiles= 7
Profile Names=10-year,25-year,50-year,1pct_min,100-year,1pct_plu,500-year
River Rch & RM=UNT 1079 IN HEWA,Reach-1         ,2458
     736    1048    1313    1203    1627    2201    2493
Boundary for River Rch & Prof#=UNT 1079 IN HEWA,Reach-1         , 1
Up Type= 0
Dn Type= 3
Dn Slope=0.01
Boundary for River Rch & Prof#=UNT 1079 IN HEWA,Reach-1         , 2
Up Type= 0
Dn Type= 3
Dn Slope=0.01
Boundary for River Rch & Prof#=UNT 1079 IN HEWA,Reach-1         , 3
Up Type= 0
Dn Type= 3
Dn Slope=0.01
Boundary for River Rch & Prof#=UNT 1079 IN HEWA,Reach-1         , 4
Up Type= 0
Dn Type= 3
Dn Slope=0.01
Boundary for River Rch & Prof#=UNT 1079 IN HEWA,Reach-1         , 5
Up Type= 0
Dn Type= 3
Dn Slope=0.01
Boundary for River Rch & Prof#=UNT 1079 IN HEWA,Reach-1         , 6
Up Type= 0
Dn Type= 3
Dn Slope=0.01
Boundary for River Rch & Prof#=UNT 1079 IN HEWA,Reach-1         , 7
Up Type= 0
Dn Type= 3
Dn Slope=0.01
DSS Import GetInterval= 0
DSS Import GetPeak= 0
DSS Import FillOption= 0

--- UNT 1079 IN HEWA.g01 (geometry) ---

Geom Title=Existing Conditions
Program Version=4.10

River Reach=UNT 1079 IN HEWA,Reach-1
Reach XY= 30
      2698372.77     10009838.35      2698294.98     10009998.43
      2698214.27     10010192.28      2698060.78     10010264.41
      2698046.11     10010293.15      2698041.85     10010323.31
      2697991.43     10010422.71      2697919.21     10010494.52
      2697869.87     10010526.22      2697781.55      10010548.1
      2697709.31     10010586.17      2697671.55      10010616.9
      2697643.01      10010660.8       2697619.5     10010763.56
      2697619.36     10010803.96      2697633.05     10010856.53
      2697674.61     10010930.78       2697677.5       10010974.
      2697635.57     10011142.53      2697598.62     10011248.86
      2697583.05     10011275.27      2697549.29     10011304.24
      2697499.88     10011365.35      2697499.85     10011397.69
      2697550.05     10011604.97      2697526.45     10011630.28
      2697500.21     10011699.47      2697488.72     10011762.62
      2697498.15     10011853.59      2697486.84      10011918.9

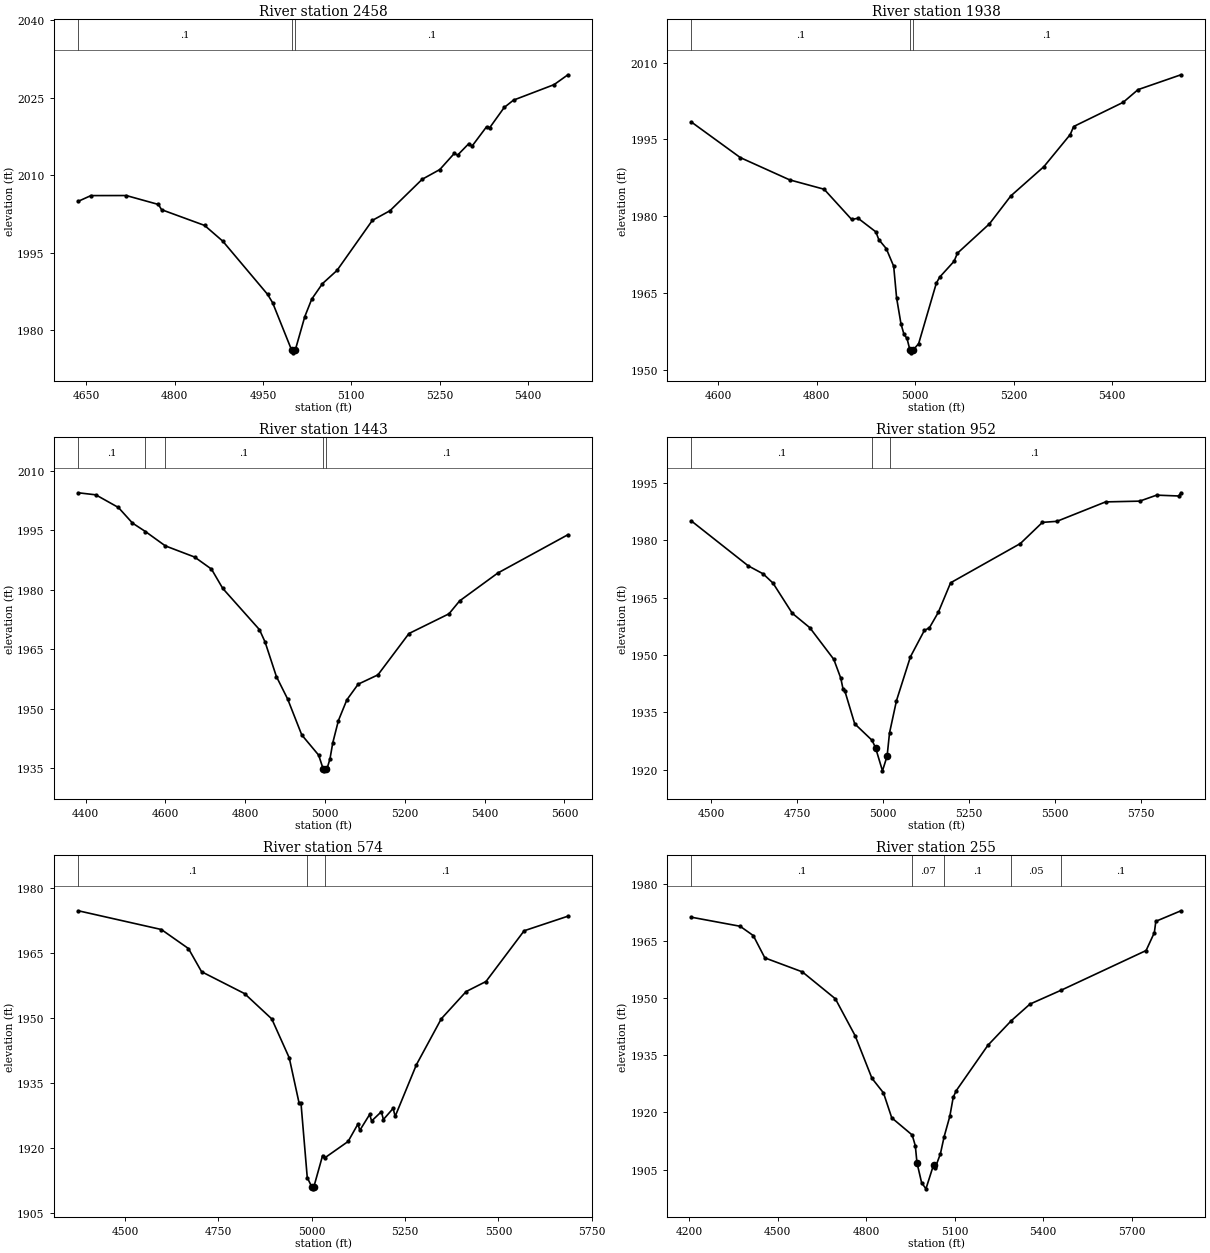
Type RM Length L Ch R = 1 ,2458    ,520,520,520
BEGIN DESCRIPTION:
UNT 1079 IN HEWA 5.0
END DESCRIPTION:
XS GIS Cut Line= 2
       2698008.2     10009759.28      2698784.74     10010057.41
#Sta/Elev= 30
  4636.2 2004.96  4657.6 2006.06  4717.6 2006.07  4772.3 2004.34  4777.6 2003.33
  4850.7 2000.28  4881.6 1997.23  4957.8 1986.91  4966.3  1985.3  4998.7 1976.09
  5001.5 1975.59  5004.7 1976.09    5021 1982.62  5032.8 1986.01    5051    1989
  5075.7 1991.56  5135.7 2001.25  5165.7 2003.13  5220.4 2009.22  5250.4 2011.11
  5275.1 2014.25  5280.5 2013.89  5299.8 2016.15  5305.1 2015.64  5329.8  2019.4
  5335.1 2019.21  5359.8 2023.14  5375.6 2024.56  5444.5 2027.56    5468 2029.47
#Mann= 3 ,-1 , 0
  4636.2      .1       0  4998.7     .07       0  5004.7      .1       0
Bank Sta=4998.7,5004.7
XS Rating Curve= 0 ,0
Exp/Cntr=0.3,0.1

Type RM Length L Ch R = 1 ,1938    ,495,495,495
BEGIN DESCRIPTION:
UNT 1079 IN HEWA 4.0
END DESCRIPTION:
XS GIS Cut Line= 4
       2697945.7     10009884.28       2697945.7     10010210.67
      2698230.42     10010398.17      2698555.09      10010432.7
#Sta/Elev= 30
  4545.9 1998.41  4645.4 1991.46  4745.4 1987.12  4815.4 1985.29  4871.3 1979.39
  4884.3 1979.63  4920.4 1976.97  4926.4 1975.46  4941.5 1973.71  4956.6 1970.26
  4962.5  1964.1  4971.4 1959.02  4977.6 1956.94  4983.6 1956.18  4989.7 1953.86
  4992.4 1953.36  4995.7 1953.86  5007.3 1955.16  5043.2 1966.97  5049.9 1968.13
  5079.2 1971.23    5086 1972.81    5151 1978.54  5194.5    1984  5261.5  1989.7
    5315 1995.97  5321.9 1997.53  5422.4 2002.25  5452.6 2004.73  5539.7 2007.63
#Mann= 3 ,-1 , 0
  4545.9      .1       0  4989.7     .07       0  4995.7      .1       0
Bank Sta=4989.7,4995.7
XS Rating Curve= 0 ,0
Exp/Cntr=0.3,0.1

Type RM Length L Ch R = 1 ,1443    ,491,491,491
BEGIN DESCRIPTION:
UNT 1079 IN HEWA 3.0
END DESCRIPTION:
XS GIS Cut Line= 3
      2697265.14     10010155.11       2697883.2     10010766.22
      2698223.45     10010655.12
#Sta/Elev= 30
  4381.7 2004.49  4425.5 2003.97  4482.1 2000.78  4517.4 1996.84  4549.8 1994.71
  4599.8 1991.08    4673 1988.27  4715.4 1985.22  4743.7 1980.34  4835.7 1969.93
  4849.8  1966.8  4878.1  1958.1  4906.4  1952.4  4941.7 1943.35  4984.1 1938.24
  4995.3 1934.78    4998 1934.28  5001.3 1934.78  5005.3 1934.93  5012.4 1937.28
  5019.4 1941.34  5033.6 1946.98  5054.8 1952.22  5083.1 1956.16  5132.6 1958.51
  5210.4 1968.95  5310.7 1973.93  5337.4 1977.19    5433 1984.22  5608.8  1993.9
#Mann= 5 ,-1 , 0
  4381.7      .1       0  4549.8     .05       0  4599.8      .1       0
  4995.3     .07       0  5001.3      .1       0
Bank Sta=4995.3,5001.3
XS Rating Curve= 0 ,0
Exp/Cntr=0.3,0.1

Type RM Length L Ch R = 1 ,952     ,378,378,378
BEGIN DESCRIPTION:
UNT 1079 IN HEWA 2.0
END DESCRIPTION:
XS GIS Cut Line= 4
      2697230.41     10010738.43       2697445.7     10011002.33
      2698001.25     10011092.61      2698383.05     10010738.58
#Sta/Elev= 30
  4442.8 1985.12  4608.4 1973.35  4651.5 1971.27  4680.2 1968.85  4736.2 1960.95
  4787.3 1957.16  4857.1 1948.87  4877.4 1943.94    4884 1941.11  4889.1 1940.63
  4917.9 1931.99  4968.5 1927.65  4978.7 1925.67  4998.7 1919.66  5012.2 1923.52
  5019.2 1929.58  5039.5 1938.06    5080 1949.53  5120.5 1956.43  5135.4 1957.15
    5161 1961.16  5196.9 1968.92  5399.9 1979.21    5464 1984.75  5506.1 1985.02
  5647.7 1990.11  5746.9 1990.31  5796.2 1991.88  5860.3 1991.66  5866.9  1992.5
#Mann= 3 ,-1 , 0
  4442.8      .1       0  4968.5     .07       0  5019.2      .1       0
Bank Sta=4978.7,5012.2
XS Rating Curve= 0 ,0
Exp/Cntr=0.3,0.1

Type RM Length L Ch R = 1 ,574     ,423,423,423
BEGIN DESCRIPTION:
Mapping XS db76611d
END DESCRIPTION:
XS GIS Cut Line= 4
       2697162.2     10010899.75      2697325.39     10011309.46
      2697717.75      10011441.4      2698123.72     10011233.21
#Sta/Elev= 30
  4374.9 1974.81  4597.2 1970.48  4669.8 1966.08    4705 1960.72  4820.2 1955.66
    4893 1949.81  4939.8 1940.81    4966 1930.41  4971.3 1930.26    4988 1913.15
  4999.8 1911.03  5002.6 1910.53  5005.8 1911.03  5029.1 1918.23  5034.3 1917.65
  5097.4 1921.48  5123.6 1925.49  5128.9 1924.07  5155.1 1927.72  5160.4 1926.21
  5186.6 1928.37  5191.9 1926.55  5218.1 1929.14  5223.4 1927.27  5280.4 1939.23
    5347 1949.84  5413.6 1956.14  5466.7 1958.46  5568.9 1970.19  5686.1 1973.56
#Mann= 3 ,-1 , 0
  4374.9      .1       0    4988     .07       0  5034.3      .1       0
Bank Sta=4999.8,5005.8
XS Rating Curve= 0 ,0
Exp/Cntr=0.3,0.1

Type RM Length L Ch R = 1 ,255     ,182,182,182
BEGIN DESCRIPTION:
Mapping XS a5a1bafe
END DESCRIPTION:
XS GIS Cut Line= 4
      2697121.24     10010997.49      2697445.89     10011645.05
      2697754.92     10011756.17      2698355.37     10011840.96
#Sta/Elev= 30
  4207.5 1971.33  4372.7 1968.95  4417.4  1966.5  4456.5 1960.64  4583.6 1956.96
  4695.5 1949.89  4762.6 1940.17  4819.5 1928.99  4858.6 1925.15  4886.6  1918.6
  4955.9 1914.08  4966.5 1911.25  4972.1 1906.79  4987.8 1901.55  5002.5 1899.93
  5028.2 1906.21  5033.5 1905.37  5051.5 1909.13  5064.2 1913.65  5083.4 1918.99
  5094.9 1923.97  5104.7 1925.68  5212.5 1937.67  5291.5 1944.11    5355 1948.49
  5461.6 1952.17  5748.6 1962.57  5776.6 1967.28  5781.6 1970.25  5866.7 1973.02
#Mann= 5 ,-1 , 0
  4207.5      .1       0  4955.9     .07       0  5064.2      .1       0
  5291.5     .05       0  5461.6      .1       0
Bank Sta=4972.1,5028.2
XS Rating Curve= 0 ,0
Exp/Cntr=0.3,0.1

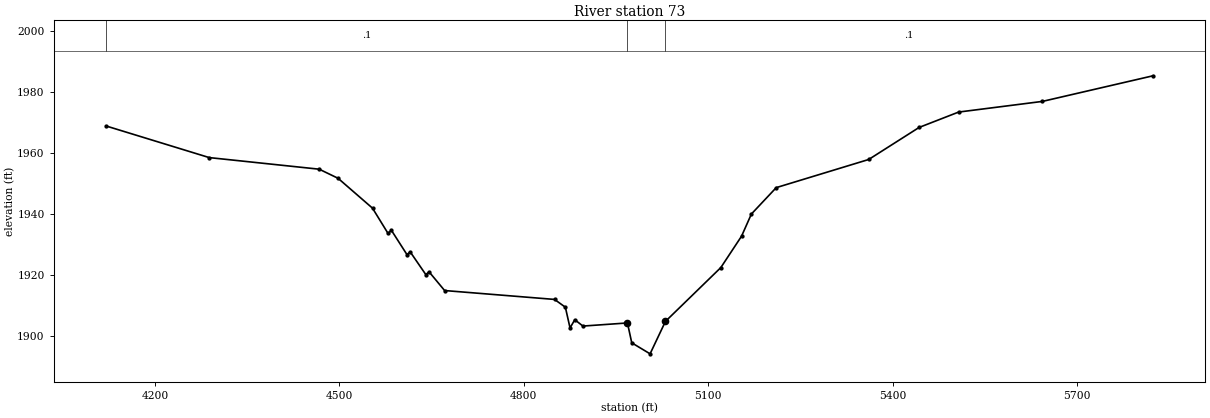
Type RM Length L Ch R = 1 ,73      ,0,0,0
BEGIN DESCRIPTION:
UNT 1079 IN HEWA 1.0
END DESCRIPTION:
XS GIS Cut Line= 4
      2697126.43     10011091.19      2697383.39     10011803.04
      2697628.18     10011896.79      2698305.23     10011993.76
#Sta/Elev= 30
  4120.8 1968.87  4288.5 1958.52  4467.3 1954.72  4497.9 1951.75    4554 1941.95
  4579.3 1933.66  4584.6 1934.74    4610 1926.75  4615.3 1927.63  4640.7 1920.19
    4646 1921.09  4671.3 1914.96  4850.1 1912.05  4867.7  1909.5  4875.3 1902.71
    4883 1905.39  4896.3 1903.32  4968.7 1904.34  4975.7 1897.83  5005.5 1894.22
  5030.5 1904.85  5120.6 1922.49  5154.3 1932.77  5170.3 1940.03  5210.7 1948.68
  5361.1  1957.9  5443.1  1968.4  5507.4 1973.44  5643.6 1976.93  5823.7 1985.33
#Mann= 3 , 0 , 0
  4120.8      .1       0  4968.7     .07       0  5030.5      .1       0
Bank Sta=4968.7,5030.5
XS Rating Curve= 0 ,0
Exp/Cntr=0.3,0.1

Chan Stop Cuts=-1
Use User Specified Reach Order=0
Composite Channel Slope=5