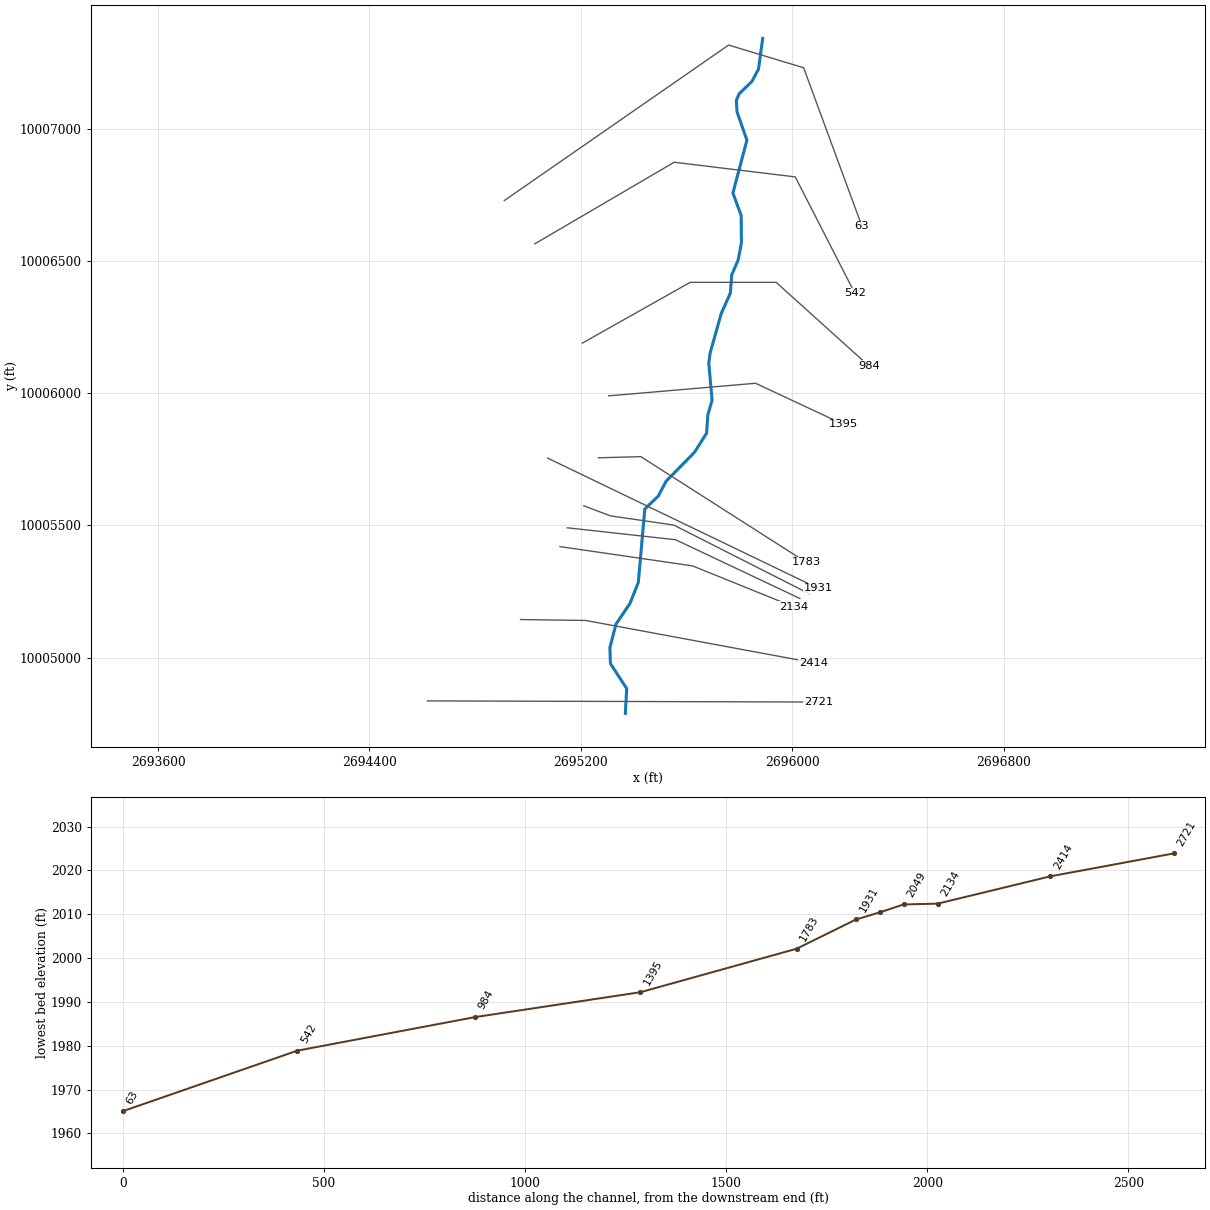
--- UNT 1080 IN HEWA.prj (project) ---

Proj Title=UNT 1080 IN HEWA Base Level Engineering
Current Plan=p01
Default Exp/Contr=0.3,0.1
English Units
Geom File=g01
Flow File=f01
Plan File=p01
Y Axis Title=Elevation
X Axis Title(PF)=Main Channel Distance
X Axis Title(XS)=Station
BEGIN DESCRIPTION:
UNT 1080 IN HEWA
END DESCRIPTION:
DSS Export Rating Curves= 0
DSS Export Rating Curve Sorted= 0
DSS Export Volume Flow Curves= 0
DXF OffsetX= 0
DXF OffsetY= 0
DXF ScaleX= 1
DXF ScaleY= 10

--- UNT 1080 IN HEWA.p01 (plan) ---

Plan Title=Multiple Run
Short Identifier=Multiple
Geom File=g01
Flow File=f01
Subcritical Flow
K Sum by GR= 0
Std Step Tol= 0.01
Critical Tol= 0.01
Num of Std Step Trials= 20
Max Error Tol= 0.3
Flow Tol Ratio= 0.001
Split Flow NTrial= 30
Split Flow Tol= 0.02
Split Flow Ratio= 0.02
Log Output Level= 0
Friction Slope Method= 1
Unsteady Friction Slope Method= 2
Unsteady Bridges Friction Slope Method= 1
Parabolic Critical Depth
Global Vel Dist=  1 , 1 , 1
Global Log Level= 0
CheckData=True
Encroach Param= -1, 0, 0, 0
BEGIN DESCRIPTION:
Multiple Run
END DESCRIPTION:

--- UNT 1080 IN HEWA.f01 (steady flow) ---

Flow Title=Multiple
Program Version=4.10
Number of Profiles= 7
Profile Names=10-year,25-year,50-year,1pct_min,100-year,1pct_plu,500-year
River Rch & RM=UNT 1080 IN HEWA,Reach-1         ,2721
     419     568     690     613     829    1121    1191
Boundary for River Rch & Prof#=UNT 1080 IN HEWA,Reach-1         , 1
Up Type= 0
Dn Type= 3
Dn Slope=0.01
Boundary for River Rch & Prof#=UNT 1080 IN HEWA,Reach-1         , 2
Up Type= 0
Dn Type= 3
Dn Slope=0.01
Boundary for River Rch & Prof#=UNT 1080 IN HEWA,Reach-1         , 3
Up Type= 0
Dn Type= 3
Dn Slope=0.01
Boundary for River Rch & Prof#=UNT 1080 IN HEWA,Reach-1         , 4
Up Type= 0
Dn Type= 3
Dn Slope=0.01
Boundary for River Rch & Prof#=UNT 1080 IN HEWA,Reach-1         , 5
Up Type= 0
Dn Type= 3
Dn Slope=0.01
Boundary for River Rch & Prof#=UNT 1080 IN HEWA,Reach-1         , 6
Up Type= 0
Dn Type= 3
Dn Slope=0.01
Boundary for River Rch & Prof#=UNT 1080 IN HEWA,Reach-1         , 7
Up Type= 0
Dn Type= 3
Dn Slope=0.01
DSS Import GetInterval= 0
DSS Import GetPeak= 0
DSS Import FillOption= 0

--- UNT 1080 IN HEWA.g01 (geometry) ---

Geom Title=Existing Conditions
Program Version=4.10

River Reach=UNT 1080 IN HEWA,Reach-1
Reach XY= 30
      2695368.47     10004788.73      2695373.63     10004882.73
      2695312.04     10004977.37      2695310.05     10005037.81
      2695333.03     10005126.55      2695385.97     10005204.77
      2695417.59     10005284.21      2695442.17     10005562.11
      2695493.19     10005611.17      2695522.89     10005667.62
      2695630.48      10005777.1      2695676.06     10005849.44
      2695680.73     10005918.15      2695696.85     10005974.04
      2695684.34     10006113.82      2695689.47     10006153.21
       2695731.6     10006302.43      2695765.94     10006379.48
      2695771.07     10006447.95      2695795.49     10006504.98
      2695807.84     10006569.12      2695806.97     10006673.22
      2695775.57     10006758.01      2695828.69     10006958.59
      2695791.23     10007065.16      2695788.61     10007108.49
      2695798.91     10007133.51      2695847.53      10007180.5
      2695872.32     10007226.77      2695888.47     10007343.73

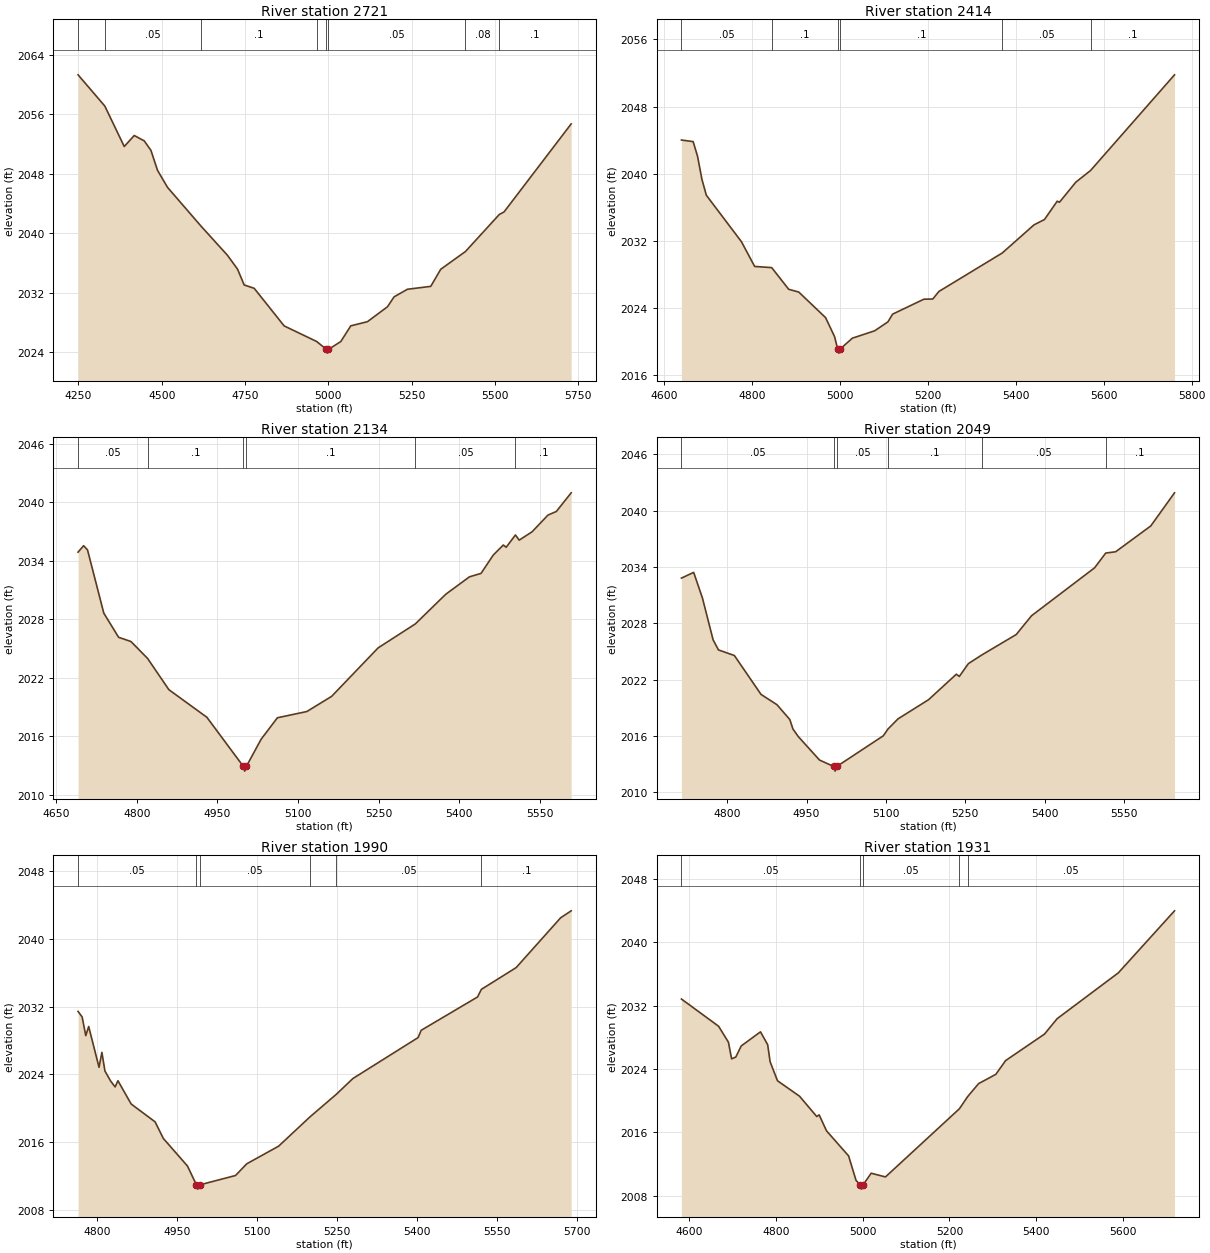
Type RM Length L Ch R = 1 ,2721    ,307,307,307
BEGIN DESCRIPTION:
UNT 1080 IN HEWA 6.0
END DESCRIPTION:
XS GIS Cut Line= 2
      2694619.84     10004835.95      2696099.94     10004831.61
#Sta/Elev= 30
  4248.9 2061.32  4329.2 2057.12  4387.5 2051.68  4417.5 2053.16  4447.5 2052.44
  4467.5 2051.17  4487.5 2048.47  4517.5 2046.18  4618.2 2040.96  4697.5 2037.04
  4727.5 2035.19  4747.5 2033.06  4777.5 2032.61  4867.5 2027.55  4964.9 2025.46
  4994.5 2024.39  4997.3 2023.89  5000.5 2024.39  5037.5 2025.45  5067.5 2027.56
  5117.5 2028.12  5177.5 2030.12  5197.5 2031.46  5237.5 2032.48  5307.5 2032.87
  5337.5 2035.17  5411.8 2037.56  5513.3 2042.54  5527.5 2042.88    5729 2054.72
#Mann= 8 ,-1 , 0
  4248.9      .1       0  4329.2     .05       0  4618.2      .1       0
  4964.9     .05       0  4994.5     .04       0  5000.5     .05       0
  5411.8     .08       0  5513.3      .1       0
Bank Sta=4994.5,5000.5
XS Rating Curve= 0 ,0
Exp/Cntr=0.3,0.1

Type RM Length L Ch R = 1 ,2414    ,280,280,280
BEGIN DESCRIPTION:
UNT 1080 IN HEWA 5.0
END DESCRIPTION:
XS GIS Cut Line= 3
      2694971.75     10005143.88      2695218.29     10005140.41
      2696079.43     10004980.68
#Sta/Elev= 30
  4638.6 2044.03  4665.3 2043.84  4675.3  2042.1  4685.3 2039.35  4695.3 2037.46
  4775.3 2031.92  4805.3 2028.98  4844.1 2028.84  4882.8 2026.26  4905.7 2025.93
  4966.7 2022.89  4987.1 2020.64  4994.2 2019.16    4997 2018.66  5000.2 2019.16
  5027.7 2020.44  5078.6 2021.32  5108.8 2022.39  5119.3  2023.3  5190.5 2025.08
  5210.8  2025.1  5224.7    2026  5368.9 2030.58  5441.2 2033.93  5465.1 2034.57
    5494 2036.75  5499.1 2036.62  5536.3 2039.01  5569.9  2040.4    5761 2051.79
#Mann= 6 ,-1 , 0
  4638.6     .05       0  4844.1      .1       0  4994.2     .07       0
  5000.2      .1       0  5368.9     .05       0  5569.9      .1       0
Bank Sta=4994.2,5000.2
XS Rating Curve= 0 ,0
Exp/Cntr=0.3,0.1

Type RM Length L Ch R = 1 ,2134    ,85,85,85
BEGIN DESCRIPTION:
Mapping XS d7524b45
END DESCRIPTION:
XS GIS Cut Line= 3
      2695121.08     10005419.92      2695622.81       10005347.
      2696004.09     10005192.76
#Sta/Elev= 30
  4690.4 2034.88  4700.8 2035.54    4708 2035.11  4738.3 2028.63  4765.9 2026.15
  4788.8 2025.72  4819.9 2023.98  4859.5 2020.78  4930.3 2017.95    4998 2012.93
  5000.8 2012.43    5004 2012.93  5031.3  2015.7  5061.6  2017.9  5116.5 2018.54
  5162.7  2020.1  5249.1 2025.06  5318.4 2027.52  5375.1 2030.56  5419.3 2032.35
  5440.8  2032.7  5463.6 2034.58  5482.3 2035.61  5487.7 2035.38  5504.9 2036.64
  5511.9 2036.11    5536 2036.97  5565.5 2038.68  5581.1 2039.05  5608.7 2040.96
#Mann= 6 ,-1 , 0
  4690.4     .05       0  4819.9      .1       0    4998     .07       0
    5004      .1       0  5318.4     .05       0  5504.9      .1       0
Bank Sta=4998,5004
XS Rating Curve= 0 ,0
Exp/Cntr=0.3,0.1

Type RM Length L Ch R = 1 ,2049    ,59,59,59
BEGIN DESCRIPTION:
Mapping XS 91166454
END DESCRIPTION:
XS GIS Cut Line= 3
      2695148.88      10005491.1      2695558.57     10005445.96
      2696029.06     10005223.74
#Sta/Elev= 30
  4713.3 2032.81  4736.5 2033.42  4753.1 2030.68  4773.2 2026.24  4783.3 2025.16
  4813.5 2024.56  4863.8 2020.42    4894 2019.32  4918.3 2017.74  4924.2 2016.73
  4934.2 2015.93  4974.5 2013.42  5001.2 2012.74    5004 2012.24  5007.2 2012.74
  5095.2 2016.01  5103.8 2016.72  5122.9 2017.81  5180.6 2019.85  5233.2 2022.57
  5238.8 2022.33    5256  2023.7  5281.4 2024.62  5346.5  2026.8  5375.4  2028.8
  5494.7 2033.91  5515.7 2035.48  5534.5 2035.62  5600.9 2038.37  5645.8  2041.9
#Mann= 6 ,-1 , 0
  4713.3     .05       0  5001.2     .04       0  5007.2     .05       0
  5103.8      .1       0  5281.4     .05       0  5515.7      .1       0
Bank Sta=5001.2,5007.2
XS Rating Curve= 0 ,0
Exp/Cntr=0.3,0.1

Type RM Length L Ch R = 1 ,1990    ,59,59,59
BEGIN DESCRIPTION:
Mapping XS a4bb5008
END DESCRIPTION:
XS GIS Cut Line= 4
      2695211.32     10005574.44      2695312.04     10005536.24
      2695551.63     10005501.52      2696064.52     10005241.61
#Sta/Elev= 30
    4765 2031.44  4772.6 2030.79  4779.5 2028.58  4784.9 2029.66  4804.3 2024.84
  4809.7  2026.6  4815.4  2024.4  4826.1 2023.21  4834.5 2022.52  4839.8 2023.25
  4864.6  2020.5  4909.5 2018.39  4924.9 2016.43  4970.2 2013.17    4987 2010.94
  4989.8 2010.44    4993 2010.94  5060.3 2012.05  5081.3 2013.43  5141.2 2015.52
  5199.8 2018.97  5249.4 2021.65  5280.4 2023.51  5402.7 2028.35  5408.5 2029.21
  5514.2 2033.15  5521.4 2034.05  5586.6 2036.62  5670.1 2042.51  5689.8 2043.33
#Mann= 6 ,-1 , 0
    4765     .05       0    4987     .04       0    4993     .05       0
  5199.8      .1       0  5249.4     .05       0  5521.4      .1       0
Bank Sta=4987,4993
XS Rating Curve= 0 ,0
Exp/Cntr=0.3,0.1

Type RM Length L Ch R = 1 ,1931    ,148,148,148
BEGIN DESCRIPTION:
Mapping XS d95f60d5
END DESCRIPTION:
XS GIS Cut Line= 2
      2695074.24     10005754.97      2696098.55     10005261.91
#Sta/Elev= 30
    4582 2032.84  4667.7  2029.4  4690.4 2027.38  4697.7 2025.28  4707.4 2025.51
  4719.9 2026.91  4764.3 2028.69  4780.9 2027.06  4786.5 2024.91  4803.5 2022.51
  4854.3 2020.56    4894 2017.99  4899.5  2018.2  4916.6 2016.18  4967.4 2013.02
  4984.5 2009.94  4994.3 2009.32  4997.1 2008.82  5000.3 2009.32  5019.5 2010.83
  5052.4 2010.36    5223 2018.98  5241.9 2020.51  5267.1 2022.15  5306.8 2023.32
  5329.4 2025.06  5419.1 2028.41  5448.1 2030.35  5589.4 2036.15  5718.8 2043.98
#Mann= 5 ,-1 , 0
    4582     .05       0  4994.3     .04       0  5000.3     .05       0
    5223      .1       0  5241.9     .05       0
Bank Sta=4994.3,5000.3
XS Rating Curve= 0 ,0
Exp/Cntr=0.3,0.1

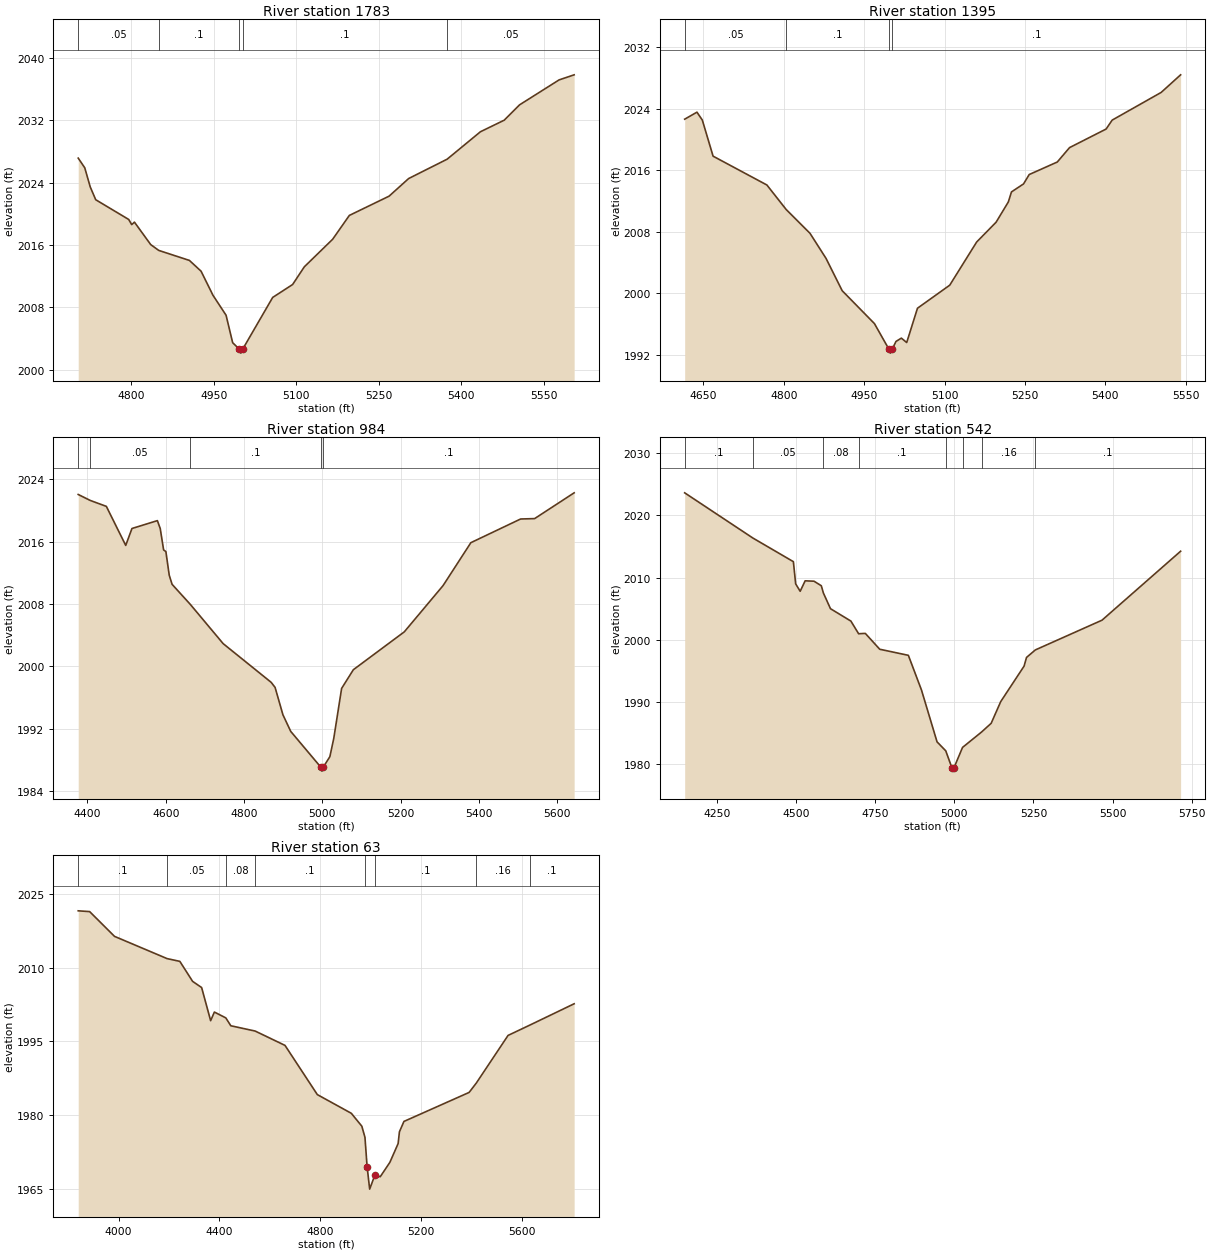
Type RM Length L Ch R = 1 ,1783    ,388,388,388
BEGIN DESCRIPTION:
UNT 1080 IN HEWA 4.0
END DESCRIPTION:
XS GIS Cut Line= 3
       2695266.6     10005756.09      2695427.18     10005760.43
      2696052.18     10005361.13
#Sta/Elev= 30
  4703.1 2027.14    4715  2025.9    4725 2023.44    4735  2021.8    4795 2019.27
  4800.4 2018.61  4805.4 2018.93    4835 2016.05  4849.7  2015.3  4905.4 2014.02
  4926.6 2012.64  4948.3 2009.55  4972.1 2006.99  4984.1 2003.47  4996.3 2002.63
  4999.1 2002.13  5002.3 2002.63  5056.9 2009.27  5093.2 2010.93  5114.5  2013.2
    5166 2016.73  5196.4 2019.79  5268.7 2022.26  5304.3 2024.52  5374.3    2027
  5434.9 2030.52  5478.1    2032  5506.1 2033.97    5578 2037.17  5605.4 2037.82
#Mann= 5 ,-1 , 0
  4703.1     .05       0  4849.7      .1       0  4996.3     .07       0
  5002.3      .1       0  5374.3     .05       0
Bank Sta=4996.3,5002.3
XS Rating Curve= 0 ,0
Exp/Cntr=0.3,0.1

Type RM Length L Ch R = 1 ,1395    ,411,411,411
BEGIN DESCRIPTION:
UNT 1080 IN HEWA 3.0
END DESCRIPTION:
XS GIS Cut Line= 3
      2695305.66     10005990.47      2695861.21     10006038.21
       2696194.4     10005882.43
#Sta/Elev= 30
    4615 2022.65  4637.9 2023.56  4647.9 2022.54    4668 2017.84  4768.4 2014.09
  4804.3 2010.91  4848.7 2007.82  4878.8 2004.54  4908.9 2000.34  4969.1 1996.06
  4996.2 1992.72    4999 1992.22  5002.2 1992.72  5009.3 1993.74  5019.3 1994.17
  5029.3  1993.6  5049.4 1998.06  5109.6 2001.06  5159.8 2006.67  5196.1 2009.25
  5218.9 2011.88  5224.8 2013.19  5247.3 2014.23  5257.9 2015.45  5310.3 2017.08
  5333.1 2018.95  5401.4 2021.37  5412.7 2022.53  5504.1 2026.13  5540.4 2028.42
#Mann= 4 ,-1 , 0
    4615     .05       0  4804.3      .1       0  4996.2     .07       0
  5002.2      .1       0
Bank Sta=4996.2,5002.2
XS Rating Curve= 0 ,0
Exp/Cntr=0.3,0.1

Type RM Length L Ch R = 1 ,984     ,442,442,442
BEGIN DESCRIPTION:
UNT 1080 IN HEWA 2.0
END DESCRIPTION:
XS GIS Cut Line= 4
      2695205.86     10006190.14      2695613.81     10006420.16
      2695939.33     10006420.16      2696290.88     10006103.33
#Sta/Elev= 30
  4376.5 2022.06  4406.9  2021.3  4448.4 2020.53  4497.9 2015.52  4513.8 2017.69
  4578.8  2018.7  4586.1 2017.68  4594.7 2014.94  4600.5 2014.73  4609.1 2011.68
  4616.4 2010.52  4663.2 2007.93  4746.8 2002.91  4869.5 1997.94  4879.5 1997.29
  4899.5 1993.78  4919.5 1991.64  4996.5 1987.04  4999.2 1986.54  5002.5 1987.04
  5019.5  1988.4  5029.5 1990.76  5049.5 1997.16  5079.5 1999.56  5209.6 2004.42
  5308.7 2010.36  5379.7 2015.87  5506.8 2018.91  5542.6 2018.96  5643.6 2022.27
#Mann= 5 ,-1 , 0
  4376.5      .1       0  4406.9     .05       0  4663.2      .1       0
  4996.5     .07       0  5002.5      .1       0
Bank Sta=4996.5,5002.5
XS Rating Curve= 0 ,0
Exp/Cntr=0.3,0.1

Type RM Length L Ch R = 1 ,542     ,434,434,434
BEGIN DESCRIPTION:
Mapping XS 7adf23fe
END DESCRIPTION:
XS GIS Cut Line= 4
      2695025.56     10006565.74      2695553.36     10006874.78
       2696011.7     10006819.22      2696237.26     10006378.51
#Sta/Elev= 30
  4146.9 2023.63  4362.6 2016.36  4490.7 2012.56  4497.9 2008.99  4512.2  2007.8
  4527.9 2009.48  4555.9 2009.42    4579 2008.69  4585.6 2007.52    4608    2005
  4672.5 2003.01    4697 2000.97  4718.1 2001.03  4763.7 1998.48  4854.3  1997.5
  4895.8 1991.92    4945 1983.59  4972.6 1982.14  4992.3 1979.38  4995.1 1978.88
  4998.3 1979.38  5025.6 1982.69  5085.6 1985.16  5116.2 1986.57  5146.4 1990.06
  5220.2 1995.76    5228 1997.16  5255.9 1998.37  5466.7 2003.15  5715.3 2014.24
#Mann= 8 ,-1 , 0
  4146.9      .1       0  4362.6     .05       0  4585.6     .08       0
    4697      .1       0  4972.6     .07       0  5025.6      .1       0
  5085.6     .16       0  5255.9      .1       0
Bank Sta=4992.3,4998.3
XS Rating Curve= 0 ,0
Exp/Cntr=0.3,0.1

Type RM Length L Ch R = 1 ,63      ,0,0,0
BEGIN DESCRIPTION:
UNT 1080 IN HEWA 1.0
END DESCRIPTION:
XS GIS Cut Line= 4
       2694910.5     10006729.79      2695759.43     10007318.32
      2696043.29     10007232.38      2696264.07     10006632.38
#Sta/Elev= 30
  3839.4  2021.5  3884.9 2021.34  3983.5 2016.32  4192.3 2011.81  4242.9 2011.25
  4293.6 2007.19  4329.4 2005.94  4365.2 1999.22    4380 2000.97  4425.3 1999.79
  4445.3 1998.19  4541.8 1997.12  4660.4 1994.21  4788.7 1984.23  4923.6 1980.44
  4965.4 1977.82  4977.8 1975.57  4986.3 1969.63  4996.5 1965.06  5017.7 1967.97
  5038.4 1967.57  5076.6 1970.48  5109.5  1974.3  5114.7 1976.69  5132.6 1978.79
  5391.3 1984.67  5419.7 1986.56  5545.9 1996.23  5634.2 1998.37  5808.3 2002.65
#Mann= 8 ,-1 , 0
  3839.4      .1       0  4192.3     .05       0  4425.3     .08       0
  4541.8      .1       0  4977.8     .07       0  5017.7      .1       0
  5419.7     .16       0  5634.2      .1       0
Bank Sta=4986.3,5017.7
XS Rating Curve= 0 ,0
Exp/Cntr=0.3,0.1

Chan Stop Cuts=-1
Use User Specified Reach Order=0
Composite Channel Slope=5