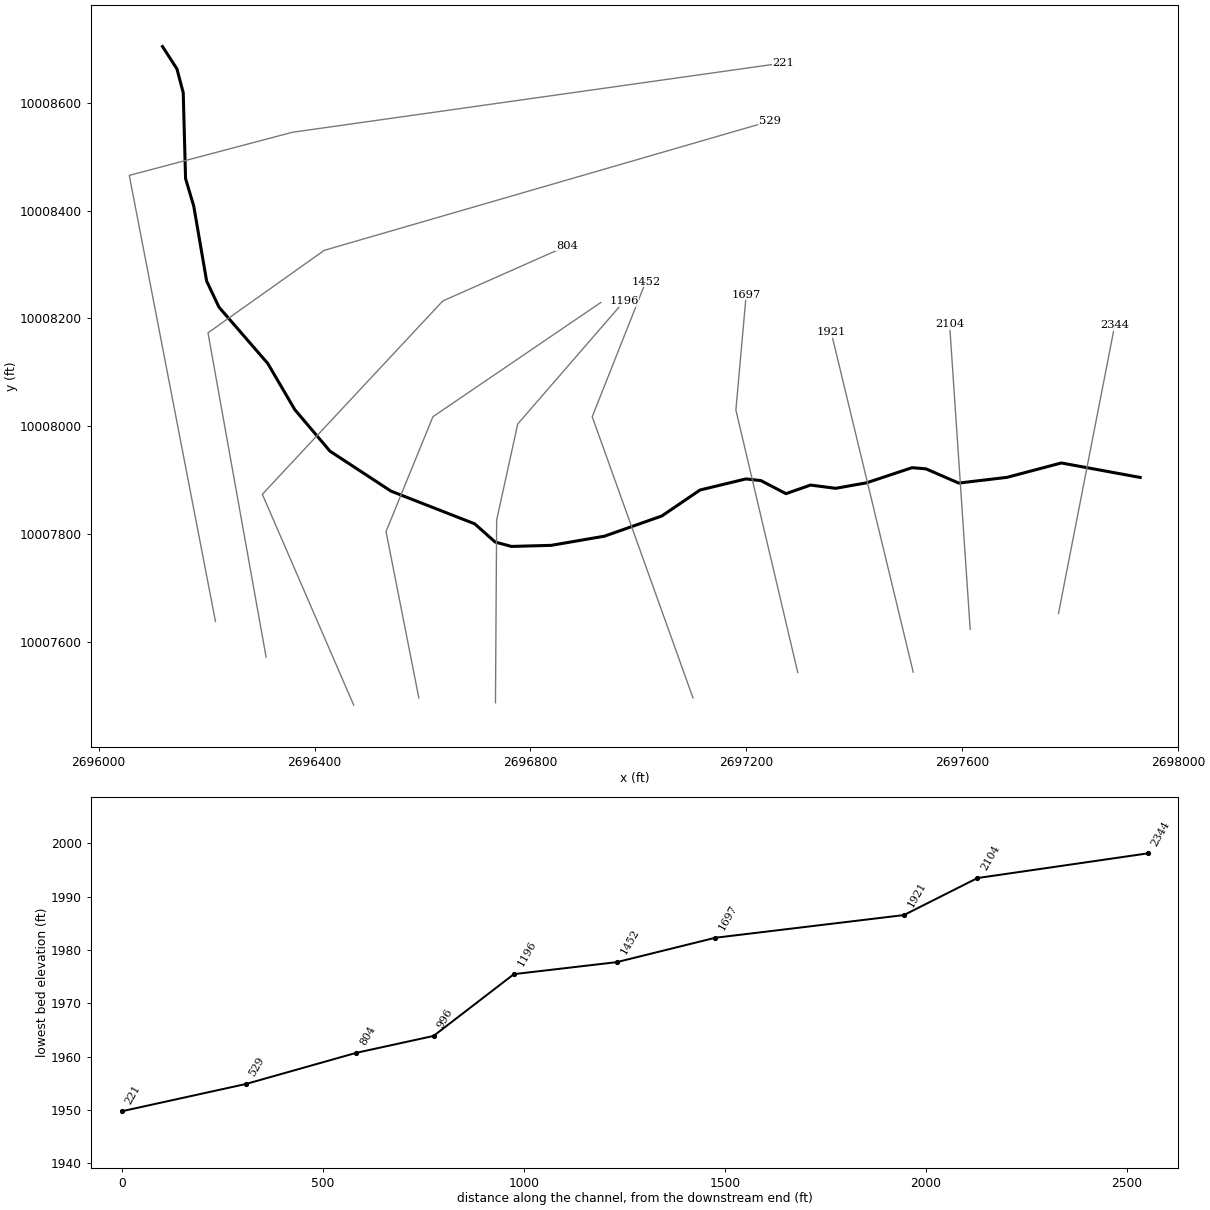
--- UNT 1081 IN HEWA.prj (project) ---

Proj Title=UNT 1081 IN HEWA Base Level Engineering
Current Plan=p01
Default Exp/Contr=0.3,0.1
English Units
Geom File=g01
Flow File=f01
Plan File=p01
Y Axis Title=Elevation
X Axis Title(PF)=Main Channel Distance
X Axis Title(XS)=Station
BEGIN DESCRIPTION:
UNT 1081 IN HEWA
END DESCRIPTION:
DSS Export Rating Curves= 0
DSS Export Rating Curve Sorted= 0
DSS Export Volume Flow Curves= 0
DXF OffsetX= 0
DXF OffsetY= 0
DXF ScaleX= 1
DXF ScaleY= 10

--- UNT 1081 IN HEWA.p01 (plan) ---

Plan Title=Multiple Run
Short Identifier=Multiple
Geom File=g01
Flow File=f01
Subcritical Flow
K Sum by GR= 0
Std Step Tol= 0.01
Critical Tol= 0.01
Num of Std Step Trials= 20
Max Error Tol= 0.3
Flow Tol Ratio= 0.001
Split Flow NTrial= 30
Split Flow Tol= 0.02
Split Flow Ratio= 0.02
Log Output Level= 0
Friction Slope Method= 1
Unsteady Friction Slope Method= 2
Unsteady Bridges Friction Slope Method= 1
Parabolic Critical Depth
Global Vel Dist=  1 , 1 , 1
Global Log Level= 0
CheckData=True
Encroach Param= -1, 0, 0, 0
BEGIN DESCRIPTION:
Multiple Run
END DESCRIPTION:

--- UNT 1081 IN HEWA.f01 (steady flow) ---

Flow Title=Multiple
Number of Profiles=7
Profile Names=10-year,25-year,50-year,1pct_min,100-year,1pct_plu,500-year
River Rch & RM= UNT 1081 IN HEWA,Reach-1,2344
     499     688     844     758    1025    1387    1507
Boundary for River Rch & Prof#=UNT 1081 IN HEWA,Reach-1,1
Up Type=0
Dn Type=3
Dn Slope=0.005
Boundary for River Rch & Prof#=UNT 1081 IN HEWA,Reach-1,2
Up Type=0
Dn Type=3
Dn Slope=0.005
Boundary for River Rch & Prof#=UNT 1081 IN HEWA,Reach-1,3
Up Type=0
Dn Type=3
Dn Slope=0.005
Boundary for River Rch & Prof#=UNT 1081 IN HEWA,Reach-1,4
Up Type=0
Dn Type=3
Dn Slope=0.005
Boundary for River Rch & Prof#=UNT 1081 IN HEWA,Reach-1,5
Up Type=0
Dn Type=3
Dn Slope=0.005
Boundary for River Rch & Prof#=UNT 1081 IN HEWA,Reach-1,6
Up Type=0
Dn Type=3
Dn Slope=0.005
Boundary for River Rch & Prof#=UNT 1081 IN HEWA,Reach-1,7
Up Type=0
Dn Type=3
Dn Slope=0.005

--- UNT 1081 IN HEWA.g01 (geometry) ---

Geom Title=Existing Conditions
Program Version=4.10

River Reach=UNT 1081 IN HEWA,Reach-1
Reach XY= 30
      2697929.54      10007905.5      2697783.43     10007932.34
      2697682.95     10007905.72      2697593.38     10007895.08
      2697532.79     10007921.41      2697506.89     10007923.58
      2697422.66     10007895.57      2697365.42     10007885.38
      2697318.89     10007891.39      2697273.44     10007875.47
       2697226.8     10007899.72      2697199.03     10007902.77
      2697114.12     10007882.21      2697043.31      10007834.1
       2696937.2     10007796.73      2696838.41     10007779.73
       2696764.8     10007777.72      2696734.66     10007785.85
      2696696.73     10007819.58       2696541.7     10007880.15
      2696428.58     10007954.24      2696363.51     10008031.09
      2696313.48     10008116.58      2696223.03     10008220.91
      2696200.13     10008269.42      2696176.28     10008408.24
      2696161.12     10008459.17       2696156.8     10008618.22
      2696145.12     10008662.34      2696118.47     10008703.73

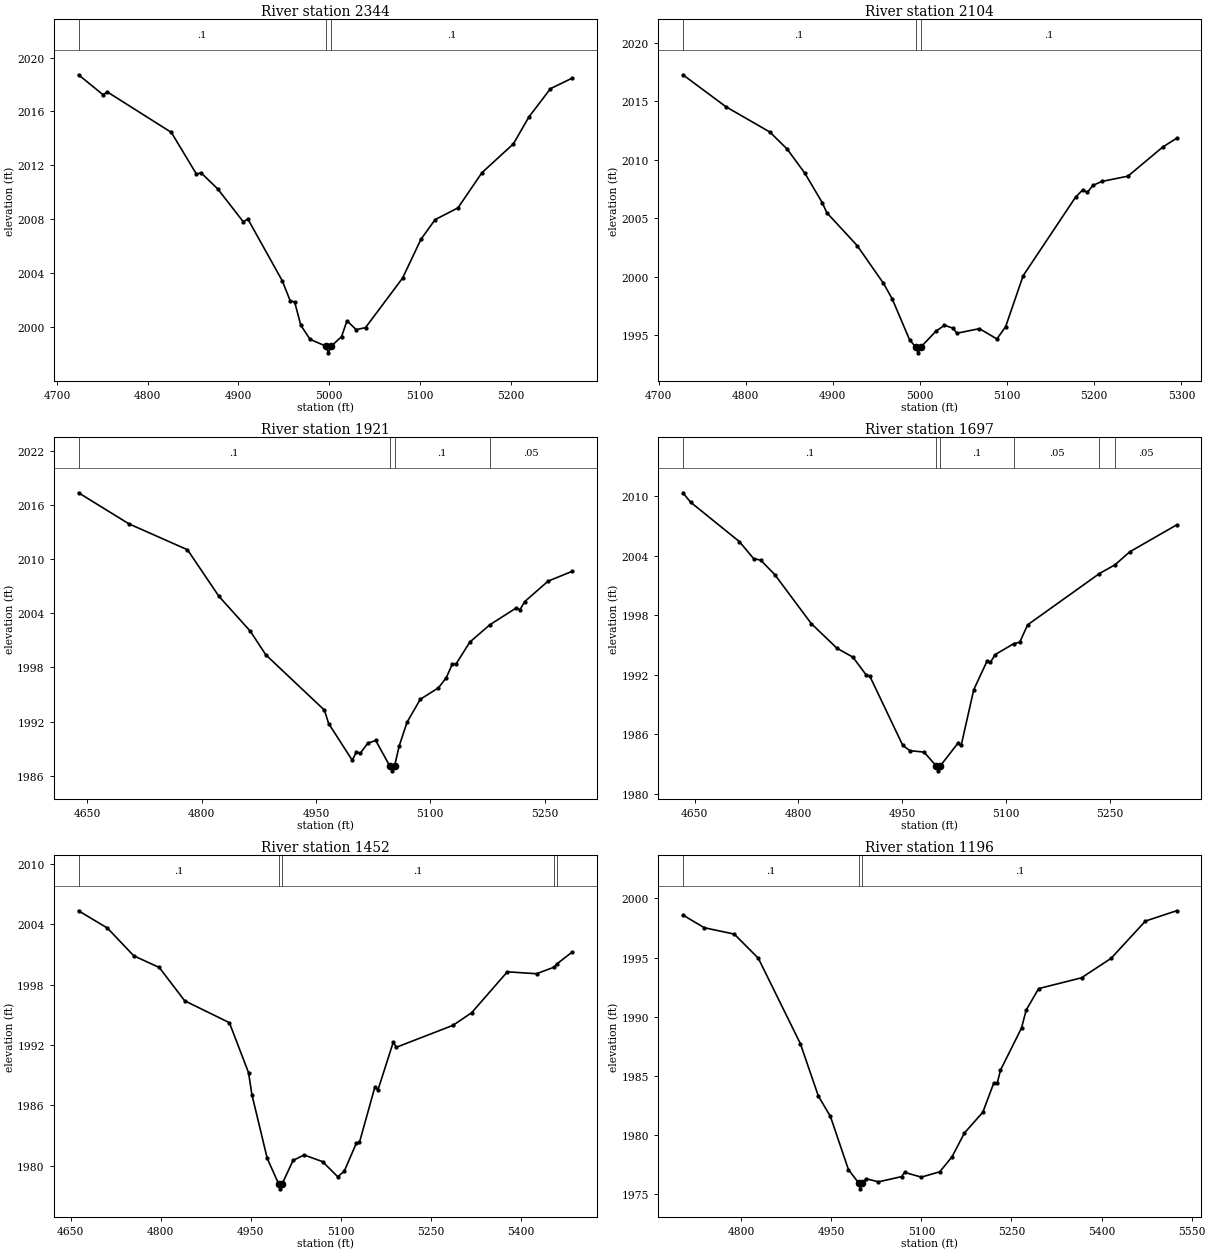
Type RM Length L Ch R = 1 ,2344    ,423,423,423
BEGIN DESCRIPTION:
UNT 1081 IN HEWA 5.0
END DESCRIPTION:
XS GIS Cut Line= 2
      2697778.16     10007653.38      2697882.32     10008187.21
#Sta/Elev= 30
  4723.8 2018.72  4750.6 2017.25  4755.7 2017.44    4826 2014.45  4853.7 2011.36
  4858.8 2011.45    4877 2010.27  4905.3 2007.82  4910.4 2008.02  4948.3 2003.44
  4956.9 2001.98    4962 2001.85  4968.7 2000.15  4978.9  1999.1  4996.3  1998.6
    4999  1998.1  5002.3  1998.6  5013.6  1999.3  5019.6 2000.47  5029.8 1999.82
    5040 1999.97  5080.8 2003.64  5101.1 2006.52  5116.7 2007.98  5141.9 2008.85
  5168.3 2011.46    5203  2013.6  5219.9 2015.58  5243.8 2017.69  5267.7 2018.47
#Mann= 3 ,-1 , 0
  4723.8      .1       0  4996.3     .07       0  5002.3      .1       0
Bank Sta=4996.3,5002.3
XS Rating Curve= 0 ,0
Exp/Cntr=0.3,0.1

Type RM Length L Ch R = 1 ,2104    ,183,183,183
BEGIN DESCRIPTION:
Mapping XS 3069e5a8
END DESCRIPTION:
XS GIS Cut Line= 2
       2697614.6     10007624.17      2697576.46     10008189.38
#Sta/Elev= 30
  4727.9 2017.28  4777.6 2014.53  4827.7 2012.38  4847.7 2010.91  4867.8 2008.86
  4887.8 2006.34  4893.1 2005.47  4927.9 2002.66    4958 1999.44    4968 1998.12
  4988.1 1994.59  4995.1 1993.98  4997.8 1993.48  5001.1 1993.98  5018.1 1995.32
  5028.1 1995.84  5037.5  1995.6  5042.5 1995.16  5068.2 1995.55  5088.3 1994.67
  5098.3 1995.72  5118.4 2000.08  5178.5  2006.8  5186.9 2007.44  5191.9 2007.21
  5198.5 2007.81  5208.6 2008.15  5238.6  2008.6  5278.7  2011.1  5294.4 2011.84
#Mann= 3 ,-1 , 0
  4727.9      .1       0  4995.1     .07       0  5001.1      .1       0
Bank Sta=4995.1,5001.1
XS Rating Curve= 0 ,0
Exp/Cntr=0.3,0.1

Type RM Length L Ch R = 1 ,1921    ,469,469,469
BEGIN DESCRIPTION:
UNT 1081 IN HEWA 4.0
END DESCRIPTION:
XS GIS Cut Line= 2
      2697509.07     10007544.86      2697357.16     10008174.19
#Sta/Elev= 30
  4638.6 2017.33  4704.7 2013.89  4781.5 2011.02  4822.6 2005.88  4863.8 2002.01
  4884.3 1999.38  4961.1 1993.26  4966.6 1991.78  4997.5 1987.72    5003  1988.6
  5008.2  1988.5  5018.1 1989.61  5028.4  1989.9    5047 1987.04  5049.8 1986.54
    5053 1987.04  5059.2 1989.31  5069.5 1991.93  5086.8 1994.46  5110.6 1995.73
  5120.9 1996.85  5128.7 1998.35  5133.8 1998.38  5151.8  2000.8  5178.3 2002.73
  5212.4 2004.56  5217.6 2004.39  5223.8 2005.28  5254.3 2007.54    5286 2008.63
#Mann= 4 ,-1 , 0
  4638.6      .1       0    5047     .07       0    5053      .1       0
  5178.3     .05       0
Bank Sta=5047,5053
XS Rating Curve= 0 ,0
Exp/Cntr=0.3,0.1

Type RM Length L Ch R = 1 ,1697    ,245,245,245
BEGIN DESCRIPTION:
Mapping XS 5a321baf
END DESCRIPTION:
XS GIS Cut Line= 3
      2697295.16     10007544.25      2697180.57     10008030.39
      2697199.67     10008243.97
#Sta/Elev= 30
    4633 2010.36  4644.1 2009.41  4714.7 2005.43  4735.2 2003.72  4745.5 2003.56
    4766 2002.09  4818.6 1997.16  4855.8 1994.67    4879 1993.76  4898.2 1991.96
  4903.3 1991.85    4951 1984.86  4961.2 1984.33  4981.8 1984.18  4999.3 1982.79
  5002.1 1982.29  5005.3 1982.79  5030.4 1985.05  5035.5 1984.87  5053.7 1990.49
  5072.7 1993.34  5077.8 1993.24  5084.5 1994.02  5111.3 1995.12  5120.2 1995.28
  5131.6 1997.03  5235.5 2002.21    5258 2003.09  5279.3  2004.4  5346.9 2007.11
#Mann= 6 ,-1 , 0
    4633      .1       0  4999.3     .07       0  5005.3      .1       0
  5111.3     .05       0  5235.5      .1       0    5258     .05       0
Bank Sta=4999.3,5005.3
XS Rating Curve= 0 ,0
Exp/Cntr=0.3,0.1

Type RM Length L Ch R = 1 ,1452    ,256,256,256
BEGIN DESCRIPTION:
UNT 1081 IN HEWA 3.0
END DESCRIPTION:
XS GIS Cut Line= 3
      2697101.07     10007497.16      2696914.45     10008017.96
      2697013.67     10008268.18
#Sta/Elev= 30
    4663 2005.33  4711.2 2003.61    4755 2000.86  4797.5  1999.7  4839.9 1996.39
  4914.3 1994.22  4946.2 1989.26  4951.9 1987.06  4977.3 1980.76  4996.3 1978.22
    4999 1977.72  5002.3 1978.22  5020.5 1980.55  5038.9 1981.08  5069.6 1980.42
  5094.9 1978.92  5105.7 1979.47  5125.8 1982.25  5131.1 1982.35  5156.6  1987.8
  5161.9 1987.55  5187.3 1992.27  5192.6 1991.78    5287 1993.96    5318 1995.21
  5377.4 1999.27    5426 1999.08  5455.8 1999.74  5460.1 2000.06  5485.4 2001.23
#Mann= 5 ,-1 , 0
    4663      .1       0  4996.3     .07       0  5002.3      .1       0
  5455.8     .05       0  5460.1      .1       0
Bank Sta=4996.3,5002.3
XS Rating Curve= 0 ,0
Exp/Cntr=0.3,0.1

Type RM Length L Ch R = 1 ,1196    ,200,200,200
BEGIN DESCRIPTION:
Mapping XS 988aac20
END DESCRIPTION:
XS GIS Cut Line= 4
      2696735.22     10007488.09      2696737.39      10007826.6
      2696776.45     10008004.55      2696973.72     10008232.16
#Sta/Elev= 30
  4702.9 1998.59  4738.5 1997.52  4788.5 1996.98  4828.5 1994.94  4898.5 1987.73
  4928.5  1983.3  4948.5 1981.59  4978.5  1977.1  4995.5 1975.97  4998.3 1975.47
  5001.5 1975.97  5008.5 1976.32  5028.5 1976.06  5066.9  1976.5    5072 1976.86
  5099.9 1976.46  5130.6 1976.91  5151.1 1978.18  5171.6 1980.18  5202.3 1981.94
  5220.6 1984.41  5226.4 1984.41  5231.7 1985.49  5266.8 1989.06  5274.5 1990.57
  5295.3 1992.38  5366.6 1993.29    5416 1994.94    5473 1998.08  5524.8 1998.95
#Mann= 3 ,-1 , 0
  4702.9      .1       0  4995.5     .07       0  5001.5      .1       0
Bank Sta=4995.5,5001.5
XS Rating Curve= 0 ,0
Exp/Cntr=0.3,0.1

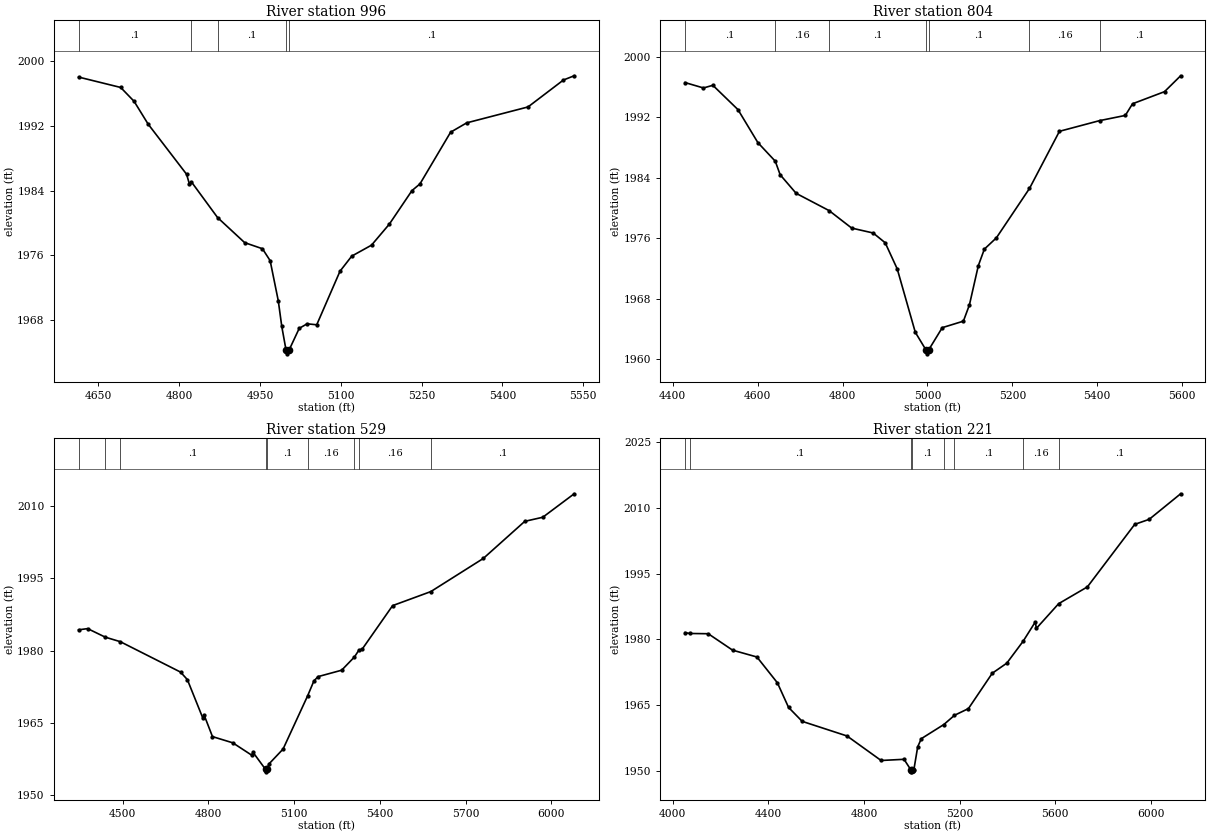
Type RM Length L Ch R = 1 ,996     ,192,192,192
BEGIN DESCRIPTION:
UNT 1081 IN HEWA 2.0
END DESCRIPTION:
XS GIS Cut Line= 4
      2696593.27      10007497.1       2696532.5     10007805.28
      2696619.31     10008017.96      2696930.38     10008229.66
#Sta/Elev= 30
  4613.2 1997.98  4691.3  1996.7  4716.2 1994.99  4742.3 1992.18  4813.6 1986.01
  4818.8 1984.83  4822.7 1985.06  4871.2 1980.67  4921.5 1977.58  4954.5 1976.83
  4968.8 1975.36  4983.9 1970.42  4990.4 1967.25  4998.2 1964.38    5001 1963.88
  5004.2 1964.38  5022.8 1967.02  5037.4 1967.58  5055.3 1967.46  5098.5 1974.06
  5120.3 1975.92    5157 1977.27  5190.1 1979.86  5232.1 1983.99    5247 1984.82
  5303.9 1991.19  5333.8 1992.34  5447.6  1994.3  5513.4 1997.62  5533.3 1998.14
#Mann= 5 ,-1 , 0
  4613.2      .1       0  4822.7     .16       0  4871.2      .1       0
  4998.2     .07       0  5004.2      .1       0
Bank Sta=4998.2,5004.2
XS Rating Curve= 0 ,0
Exp/Cntr=0.3,0.1

Type RM Length L Ch R = 1 ,804     ,275,275,275
BEGIN DESCRIPTION:
Mapping XS a1196104
END DESCRIPTION:
XS GIS Cut Line= 4
      2696472.65     10007483.68      2696303.36     10007874.35
      2696637.57     10008232.42       2696867.6     10008334.41
#Sta/Elev= 30
  4429.1 1996.57  4472.3 1995.86  4494.5 1996.21  4553.6    1993  4600.6 1988.63
  4641.5 1986.18    4653 1984.39  4690.7 1981.93  4768.3 1979.65  4821.5 1977.34
  4872.1 1976.69  4900.4  1975.4  4928.8 1971.94  4971.3 1963.57  4996.6 1961.22
  4999.4 1960.72  5002.6 1961.22  5034.8 1964.18  5084.6 1965.04  5098.8 1967.19
  5119.8 1972.38    5134 1974.56  5162.3 1976.05  5240.3 1982.58  5310.8 1990.13
  5405.3 1991.54    5466 1992.23    5483 1993.77  5558.3 1995.37  5596.3 1997.47
#Mann= 7 ,-1 , 0
  4429.1      .1       0  4641.5     .16       0  4768.3      .1       0
  4996.6     .07       0  5002.6      .1       0  5240.3     .16       0
  5405.3      .1       0
Bank Sta=4996.6,5002.6
XS Rating Curve= 0 ,0
Exp/Cntr=0.3,0.1

Type RM Length L Ch R = 1 ,529     ,308,308,308
BEGIN DESCRIPTION:
Mapping XS 4ba23a32
END DESCRIPTION:
XS GIS Cut Line= 4
      2696310.31     10007572.69      2696202.67     10008173.39
      2696417.95     10008326.17      2697243.88     10008565.62
#Sta/Elev= 30
  4345.7 1984.34  4377.2 1984.59  4439.2 1982.81  4491.5 1981.88  4702.3 1975.57
  4726.2 1974.01    4780 1966.07    4785 1966.64  4814.1 1962.18  4885.2 1960.89
  4951.3 1958.33    4956 1958.92  4999.9 1955.37  5002.6 1954.87  5005.9 1955.37
  5011.5 1956.49  5061.2  1959.6  5147.4 1970.68    5169 1973.73  5183.7 1974.63
  5266.2 1975.96  5310.8  1978.7  5326.1 1980.08  5338.6 1980.38  5444.5 1989.36
  5578.1 1992.27  5761.9 1999.15    5907 2006.85  5970.1  2007.7  6079.9 2012.57
#Mann= 9 ,-1 , 0
  4345.7      .1       0  4439.2     .16       0  4491.5      .1       0
  4999.9     .07       0  5005.9      .1       0  5147.4     .16       0
  5310.8      .1       0  5326.1     .16       0  5578.1      .1       0
Bank Sta=4999.9,5005.9
XS Rating Curve= 0 ,0
Exp/Cntr=0.3,0.1

Type RM Length L Ch R = 1 ,221     ,0,0,0
BEGIN DESCRIPTION:
UNT 1081 IN HEWA 1.0
END DESCRIPTION:
XS GIS Cut Line= 4
      2696216.56     10007638.69      2696056.84     10008465.06
      2696358.92     10008544.92      2697268.67     10008673.39
#Sta/Elev= 30
  4051.4 1981.53  4070.1 1981.34  4148.2 1981.28  4250.1 1977.53  4351.9 1975.97
  4437.5 1970.08  4484.2 1964.47  4541.1 1961.29  4728.8 1957.95  4871.3 1952.36
  4967.2 1952.63  4995.2 1950.27  4997.9 1949.77  5001.2 1950.27  5008.5 1950.29
  5024.4 1955.48  5039.6 1957.34  5133.9 1960.57  5178.3 1962.67  5236.6  1964.2
  5336.4 1972.27    5397 1974.56  5465.6 1979.58    5516 1983.94    5521 1982.51
  5614.1 1988.14  5734.3 1991.97  5932.2 2006.23  5992.8 2007.38  6124.3 2013.21
#Mann= 8 ,-1 , 0
  4051.4     .16       0  4070.1      .1       0  4995.2     .07       0
  5001.2      .1       0  5133.9     .16       0  5178.3      .1       0
  5465.6     .16       0  5614.1      .1       0
Bank Sta=4995.2,5001.2
XS Rating Curve= 0 ,0
Exp/Cntr=0.3,0.1

Chan Stop Cuts=-1
Use User Specified Reach Order=0
Composite Channel Slope=5