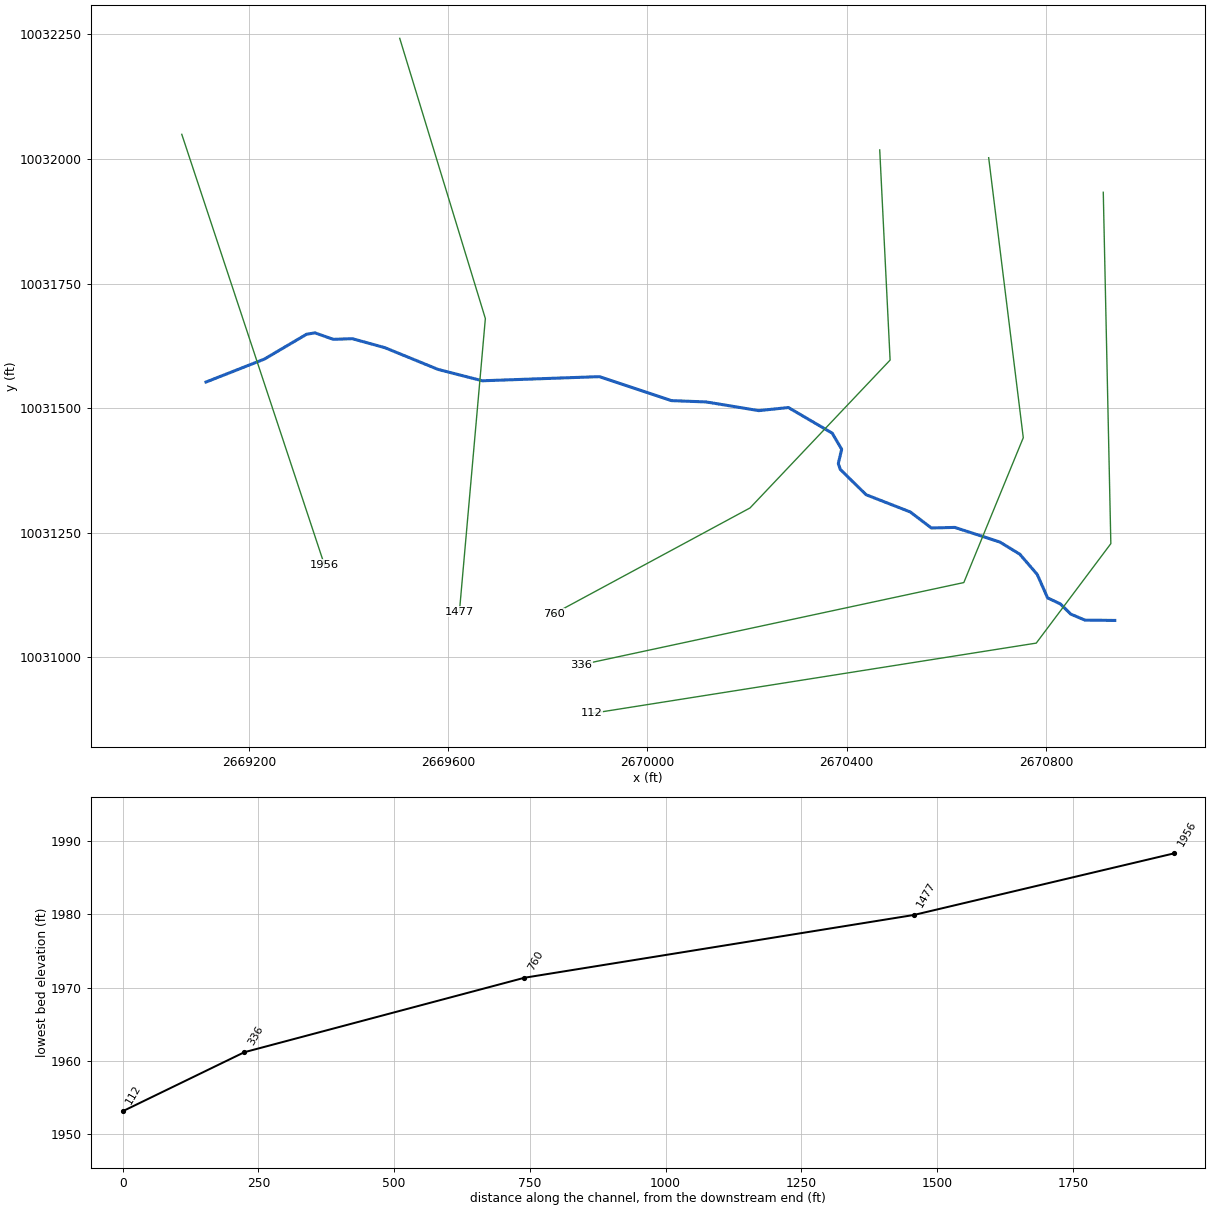
--- UNT 1082 IN HEWA.prj (project) ---

Proj Title=UNT 1082 IN HEWA Base Level Engineering
Current Plan=p01
Default Exp/Contr=0.3,0.1
English Units
Geom File=g01
Flow File=f01
Plan File=p01
Y Axis Title=Elevation
X Axis Title(PF)=Main Channel Distance
X Axis Title(XS)=Station
BEGIN DESCRIPTION:
UNT 1082 IN HEWA
END DESCRIPTION:
DSS Export Rating Curves= 0
DSS Export Rating Curve Sorted= 0
DSS Export Volume Flow Curves= 0
DXF OffsetX= 0
DXF OffsetY= 0
DXF ScaleX= 1
DXF ScaleY= 10

--- UNT 1082 IN HEWA.p01 (plan) ---

Plan Title=Multiple Run
Short Identifier=Multiple
Geom File=g01
Flow File=f01
Subcritical Flow
K Sum by GR= 0
Std Step Tol= 0.01
Critical Tol= 0.01
Num of Std Step Trials= 20
Max Error Tol= 0.3
Flow Tol Ratio= 0.001
Split Flow NTrial= 30
Split Flow Tol= 0.02
Split Flow Ratio= 0.02
Log Output Level= 0
Friction Slope Method= 1
Unsteady Friction Slope Method= 2
Unsteady Bridges Friction Slope Method= 1
Parabolic Critical Depth
Global Vel Dist=  1 , 1 , 1
Global Log Level= 0
CheckData=True
Encroach Param= -1, 0, 0, 0
BEGIN DESCRIPTION:
Multiple Run
END DESCRIPTION:

--- UNT 1082 IN HEWA.f01 (steady flow) ---

Flow Title=Multiple
Number of Profiles=7
Profile Names=10-year,25-year,50-year,1pct_min,100-year,1pct_plu,500-year
River Rch & RM= UNT 1082 IN HEWA,Reach-1,1956
     731    1037    1295    1182    1599    2162    2432
Boundary for River Rch & Prof#=UNT 1082 IN HEWA,Reach-1,1
Up Type=0
Dn Type=3
Dn Slope=0.005
Boundary for River Rch & Prof#=UNT 1082 IN HEWA,Reach-1,2
Up Type=0
Dn Type=3
Dn Slope=0.005
Boundary for River Rch & Prof#=UNT 1082 IN HEWA,Reach-1,3
Up Type=0
Dn Type=3
Dn Slope=0.005
Boundary for River Rch & Prof#=UNT 1082 IN HEWA,Reach-1,4
Up Type=0
Dn Type=3
Dn Slope=0.005
Boundary for River Rch & Prof#=UNT 1082 IN HEWA,Reach-1,5
Up Type=0
Dn Type=3
Dn Slope=0.005
Boundary for River Rch & Prof#=UNT 1082 IN HEWA,Reach-1,6
Up Type=0
Dn Type=3
Dn Slope=0.005
Boundary for River Rch & Prof#=UNT 1082 IN HEWA,Reach-1,7
Up Type=0
Dn Type=3
Dn Slope=0.005

--- UNT 1082 IN HEWA.g01 (geometry) ---

Geom Title=Existing Conditions
Program Version=4.10

River Reach=UNT 1082 IN HEWA,Reach-1
Reach XY= 30
      2669114.05     10031552.25      2669231.29     10031598.32
      2669315.99     10031648.22      2669332.91       10031651.
      2669369.62     10031637.99       2669407.7     10031639.35
      2669473.21     10031621.29      2669580.01     10031577.62
      2669668.94     10031554.83      2669903.76     10031563.13
      2670048.47     10031515.01      2670118.41     10031512.31
      2670223.78     10031494.89      2670283.26     10031501.12
      2670371.13     10031449.73      2670390.22     10031417.31
      2670383.43     10031388.67      2670387.34       10031377.
      2670439.27      10031326.1      2670527.69     10031291.58
      2670570.32     10031259.31      2670617.23     10031260.48
      2670707.65     10031231.15      2670747.72     10031206.73
      2670782.77     10031166.05      2670803.59       10031119.
      2670829.21     10031106.92      2670850.01     10031086.45
      2670878.54     10031074.36      2670938.47     10031073.73

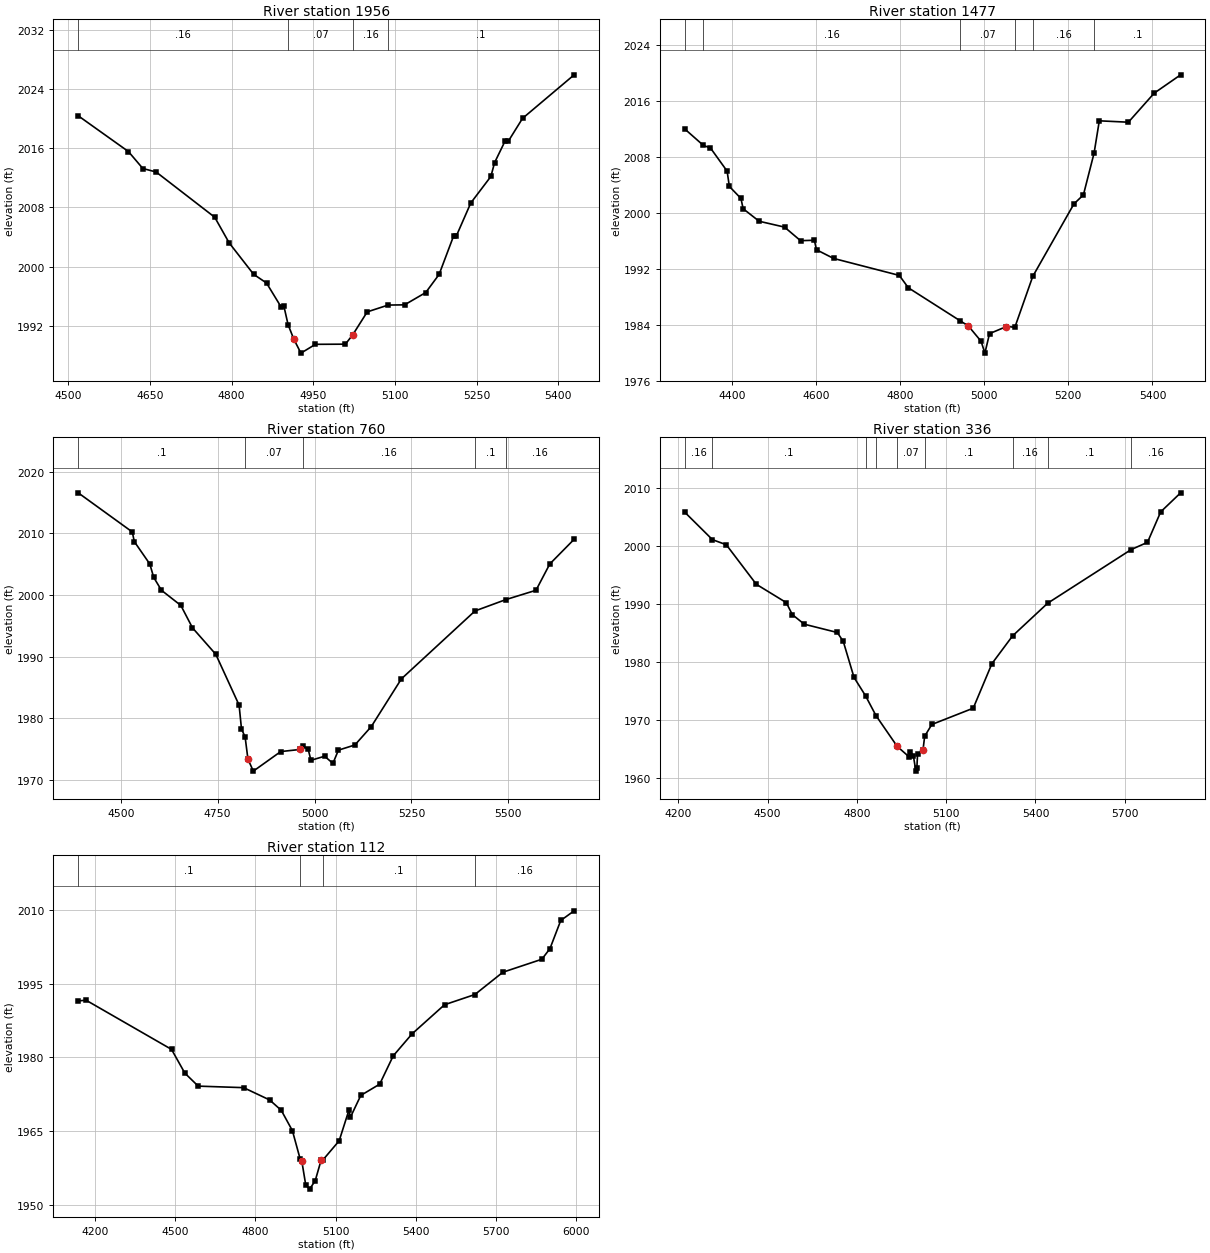
Type RM Length L Ch R = 1 ,1956    ,479,479,479
BEGIN DESCRIPTION:
UNT 1082 IN HEWA 4.0
END DESCRIPTION:
XS GIS Cut Line= 2
      2669065.54     10032049.55        2669352.     10031184.97
#Sta/Elev= 30
  4518.2 2020.38  4610.4 2015.55  4636.9 2013.26  4661.3 2012.79  4768.9 2006.68
  4795.4 2003.22  4840.4 1998.97    4864  1997.8  4890.5  1994.6  4895.7 1994.75
  4903.6 1992.18  4914.1 1990.22  4927.2 1988.33  4953.9 1989.52  5008.9 1989.54
  5022.5 1990.82    5049  1993.9  5087.4 1994.82  5117.6 1994.85  5156.4 1996.51
    5181 1998.96  5207.5 2004.13  5212.7 2004.16  5239.2 2008.61  5276.1 2012.19
  5282.8 2014.04  5302.6 2017.04  5307.8 2016.91  5334.2 2020.03    5429 2025.91
#Mann= 4 ,-1 , 0
  4518.2     .16       0  4903.6     .07       0  5022.5     .16       0
  5087.4      .1       0
Bank Sta=4914.1,5022.5
XS Rating Curve= 0 ,0
Exp/Cntr=0.3,0.1

Type RM Length L Ch R = 1 ,1477    ,717,717,717
BEGIN DESCRIPTION:
UNT 1082 IN HEWA 3.0
END DESCRIPTION:
XS GIS Cut Line= 3
      2669503.04     10032242.25      2669674.93     10031679.72
      2669622.85     10031091.22
#Sta/Elev= 30
  4287.9 2012.01  4332.6 2009.64  4349.1 2009.29  4388.8 2005.97  4394.1 2003.78
  4421.6 2002.07  4426.9 2000.59  4464.9  1998.8  4525.3 1997.96  4563.3 1996.02
  4596.1 1996.08  4601.3 1994.72  4641.9 1993.48  4798.1 1991.05  4819.6 1989.28
  4942.4 1984.57  4962.4 1983.81  4992.5 1981.63  5001.6 1979.93  5012.6 1982.72
  5052.8 1983.73  5072.9 1983.64  5115.4 1990.91  5213.4 2001.29  5235.8 2002.57
  5261.2 2008.56  5273.6 2013.17  5342.7 2012.97  5404.1 2017.13  5466.9 2019.75
#Mann= 6 ,-1 , 0
  4287.9      .1       0  4332.6     .16       0  4942.4     .07       0
  5072.9      .1       0  5115.4     .16       0  5261.2      .1       0
Bank Sta=4962.4,5052.8
XS Rating Curve= 0 ,0
Exp/Cntr=0.3,0.1

Type RM Length L Ch R = 1 ,760     ,516,516,516
BEGIN DESCRIPTION:
UNT 1082 IN HEWA 2.0
END DESCRIPTION:
XS GIS Cut Line= 4
       2670466.6     10032018.22      2670487.43     10031596.39
      2670206.18     10031299.51      2669811.88      10031086.8
#Sta/Elev= 30
  4390.4 2016.61  4529.9 2010.25  4535.1 2008.68  4575.1 2005.04  4585.1 2002.87
  4605.1 2000.77  4655.2  1998.3  4685.2 1994.66  4745.3 1990.36  4805.4  1982.1
  4811.6 1978.21  4820.9 1976.94  4828.2 1973.32  4842.1 1971.37  4912.8 1974.55
  4962.5 1974.89  4969.4  1975.5  4983.5 1974.94  4990.8 1973.13    5026 1973.79
  5047.4 1972.63  5061.6 1974.78  5104.1 1975.62  5146.5 1978.62  5224.1 1986.37
    5414 1997.41  5492.9 1999.24  5571.3 2000.77  5606.8 2005.04  5669.7 2009.06
#Mann= 5 ,-1 , 0
  4390.4      .1       0  4820.9     .07       0  4969.4     .16       0
    5414      .1       0  5492.9     .16       0
Bank Sta=4828.2,4962.5
XS Rating Curve= 0 ,0
Exp/Cntr=0.3,0.1

Type RM Length L Ch R = 1 ,336     ,224,224,224
BEGIN DESCRIPTION:
Mapping XS 5142a43d
END DESCRIPTION:
XS GIS Cut Line= 4
      2670685.31     10032002.61      2670754.76     10031440.55
       2670635.4     10031149.76      2669867.18     10030984.83
#Sta/Elev= 30
  4221.3  2005.9  4314.6 2001.15  4361.2 2000.27    4462 1993.45  4562.8 1990.28
  4582.9 1988.22  4623.2 1986.56  4734.1 1985.13  4754.2 1983.59  4790.3 1977.38
    4829 1974.21  4864.2 1970.78  4935.5 1965.47  4974.4 1963.72  4979.8 1964.57
  4989.6  1963.9  4998.1 1961.21  5001.4 1961.71  5003.8 1964.12    5022 1964.82
  5027.7 1967.23  5051.7 1969.26  5190.9 1972.07  5253.6 1979.75    5323 1984.54
  5441.1 1990.19  5721.6 1999.44  5776.4 2000.69  5820.7 2005.94  5887.7 2009.23
#Mann= 9 ,-1 , 0
  4221.3     .16       0  4314.6      .1       0    4829     .16       0
  4864.2      .1       0  4935.5     .07       0  5027.7      .1       0
    5323     .16       0  5441.1      .1       0  5721.6     .16       0
Bank Sta=4935.5,5022
XS Rating Curve= 0 ,0
Exp/Cntr=0.3,0.1

Type RM Length L Ch R = 1 ,112     ,0,0,0
BEGIN DESCRIPTION:
UNT 1082 IN HEWA 1.0
END DESCRIPTION:
XS GIS Cut Line= 4
      2670915.35     10031933.21      2670930.54     10031227.88
       2670780.8     10031028.23      2669888.84     10030887.16
#Sta/Elev= 30
  4135.8 1991.48  4165.3 1991.62  4485.4 1981.61  4535.4 1976.77  4585.4 1974.13
  4755.4 1973.82  4852.9 1971.32  4896.5 1969.21  4938.3 1965.06  4967.5 1959.26
  4973.7 1958.81  4988.3 1953.99  5002.7 1953.16  5023.7 1954.86  5046.5 1959.18
  5052.9 1959.12  5113.5    1963  5150.3 1969.28  5155.3 1967.75  5194.5 1972.24
  5265.3 1974.53    5316 1980.29  5386.8 1984.78  5508.3  1990.7    5622 1992.78
  5726.9 1997.32  5872.8 1999.96  5903.2 2002.12  5943.7 2007.86  5993.9 2009.82
#Mann= 4 ,-1 , 0
  4135.8      .1       0  4967.5     .07       0  5052.9      .1       0
    5622     .16       0
Bank Sta=4973.7,5046.5
XS Rating Curve= 0 ,0
Exp/Cntr=0.3,0.1

Chan Stop Cuts=-1
Use User Specified Reach Order=0
Composite Channel Slope=5