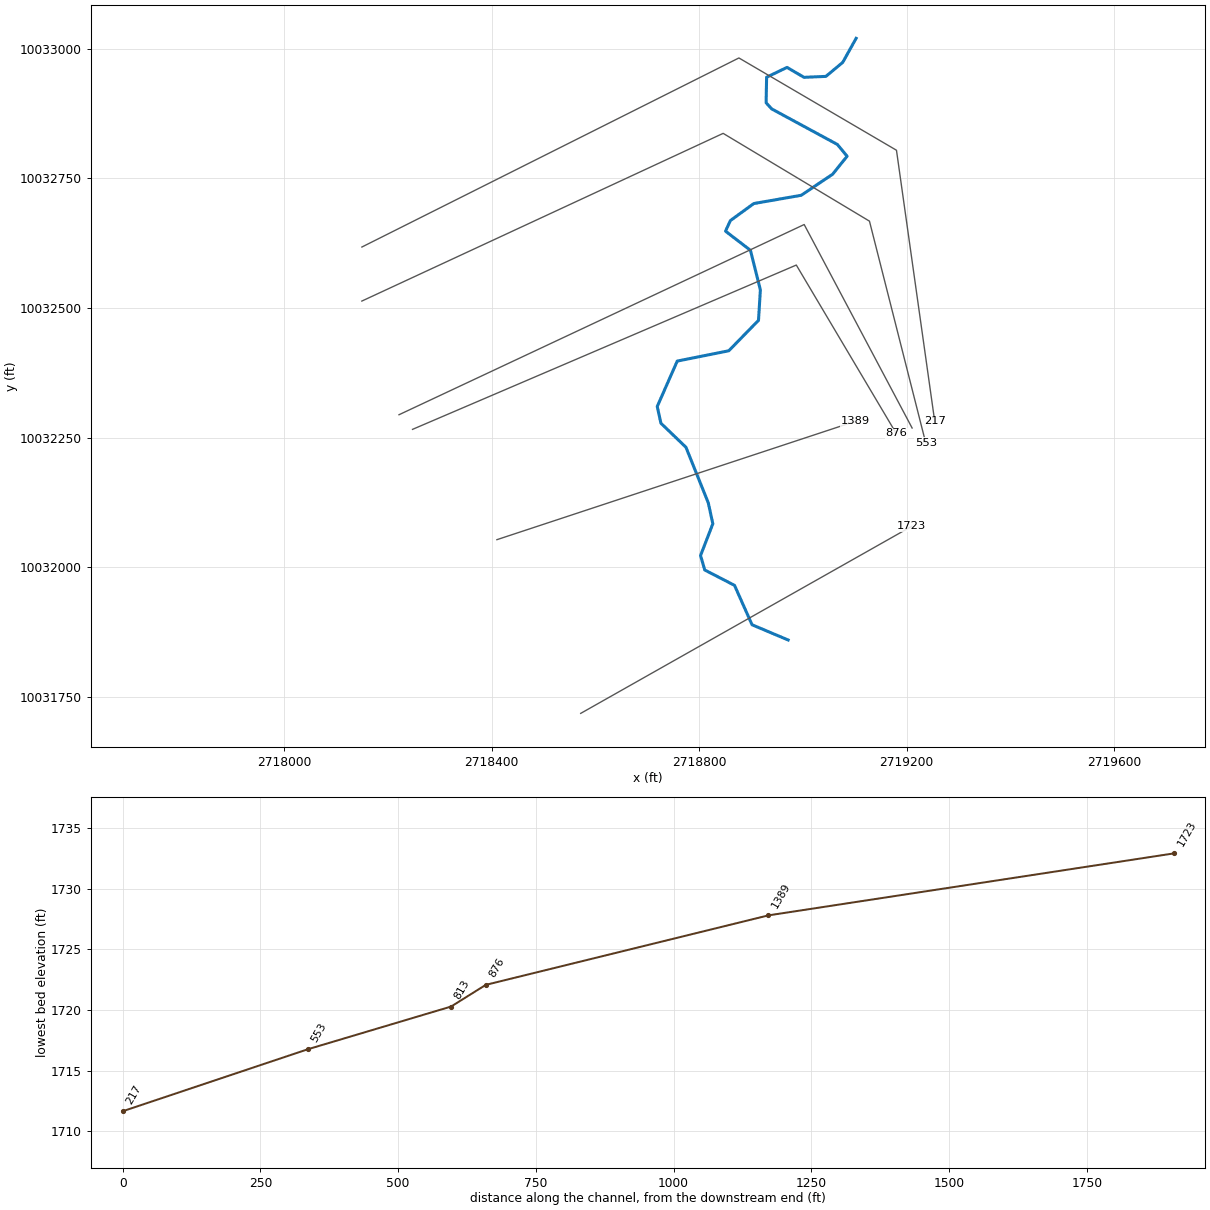
--- UNT 1083 IN HEWA.prj (project) ---

Proj Title=UNT 1083 IN HEWA Base Level Engineering
Current Plan=p01
Default Exp/Contr=0.3,0.1
English Units
Geom File=g01
Flow File=f01
Plan File=p01
Y Axis Title=Elevation
X Axis Title(PF)=Main Channel Distance
X Axis Title(XS)=Station
BEGIN DESCRIPTION:
UNT 1083 IN HEWA
END DESCRIPTION:
DSS Export Rating Curves= 0
DSS Export Rating Curve Sorted= 0
DSS Export Volume Flow Curves= 0
DXF OffsetX= 0
DXF OffsetY= 0
DXF ScaleX= 1
DXF ScaleY= 10

--- UNT 1083 IN HEWA.p01 (plan) ---

Plan Title=Multiple Run
Short Identifier=Multiple
Geom File=g01
Flow File=f01
Subcritical Flow
K Sum by GR= 0
Std Step Tol= 0.01
Critical Tol= 0.01
Num of Std Step Trials= 20
Max Error Tol= 0.3
Flow Tol Ratio= 0.001
Split Flow NTrial= 30
Split Flow Tol= 0.02
Split Flow Ratio= 0.02
Log Output Level= 0
Friction Slope Method= 1
Unsteady Friction Slope Method= 2
Unsteady Bridges Friction Slope Method= 1
Parabolic Critical Depth
Global Vel Dist=  1 , 1 , 1
Global Log Level= 0
CheckData=True
Encroach Param= -1, 0, 0, 0
BEGIN DESCRIPTION:
Multiple Run
END DESCRIPTION:

--- UNT 1083 IN HEWA.f01 (steady flow) ---

Flow Title=Multiple
Number of Profiles=7
Profile Names=10-year,25-year,50-year,1pct_min,100-year,1pct_plu,500-year
River Rch & RM= UNT 1083 IN HEWA,Reach-1,1723
     533     755     944     867    1172    1585    1810
Boundary for River Rch & Prof#=UNT 1083 IN HEWA,Reach-1,1
Up Type=0
Dn Type=3
Dn Slope=0.005
Boundary for River Rch & Prof#=UNT 1083 IN HEWA,Reach-1,2
Up Type=0
Dn Type=3
Dn Slope=0.005
Boundary for River Rch & Prof#=UNT 1083 IN HEWA,Reach-1,3
Up Type=0
Dn Type=3
Dn Slope=0.005
Boundary for River Rch & Prof#=UNT 1083 IN HEWA,Reach-1,4
Up Type=0
Dn Type=3
Dn Slope=0.005
Boundary for River Rch & Prof#=UNT 1083 IN HEWA,Reach-1,5
Up Type=0
Dn Type=3
Dn Slope=0.005
Boundary for River Rch & Prof#=UNT 1083 IN HEWA,Reach-1,6
Up Type=0
Dn Type=3
Dn Slope=0.005
Boundary for River Rch & Prof#=UNT 1083 IN HEWA,Reach-1,7
Up Type=0
Dn Type=3
Dn Slope=0.005

--- UNT 1083 IN HEWA.g01 (geometry) ---

Geom Title=Existing Conditions
Program Version=4.10

River Reach=UNT 1083 IN HEWA,Reach-1
Reach XY= 30
      2718971.43     10031859.67      2718901.82     10031889.07
      2718867.99     10031965.06      2718810.58     10031994.69
      2718802.48     10032022.57      2718826.16     10032083.78
      2718817.37     10032124.28      2718774.27     10032231.38
      2718726.07     10032277.68      2718718.98     10032309.91
      2718757.55     10032397.48      2718856.93     10032417.38
      2718914.22     10032476.03      2718917.85     10032534.72
      2718898.71     10032611.06       2718850.6     10032647.98
        2718860.     10032668.41      2718905.18     10032701.24
      2718996.66     10032717.19      2719057.12     10032757.76
      2719085.09     10032792.47      2719066.33     10032815.16
      2718939.71      10032883.7      2718928.89     10032895.56
      2718929.87     10032944.79      2718969.22     10032963.75
      2719002.01     10032944.61      2719044.18     10032946.42
      2719076.67     10032973.48      2719102.44      10033019.8

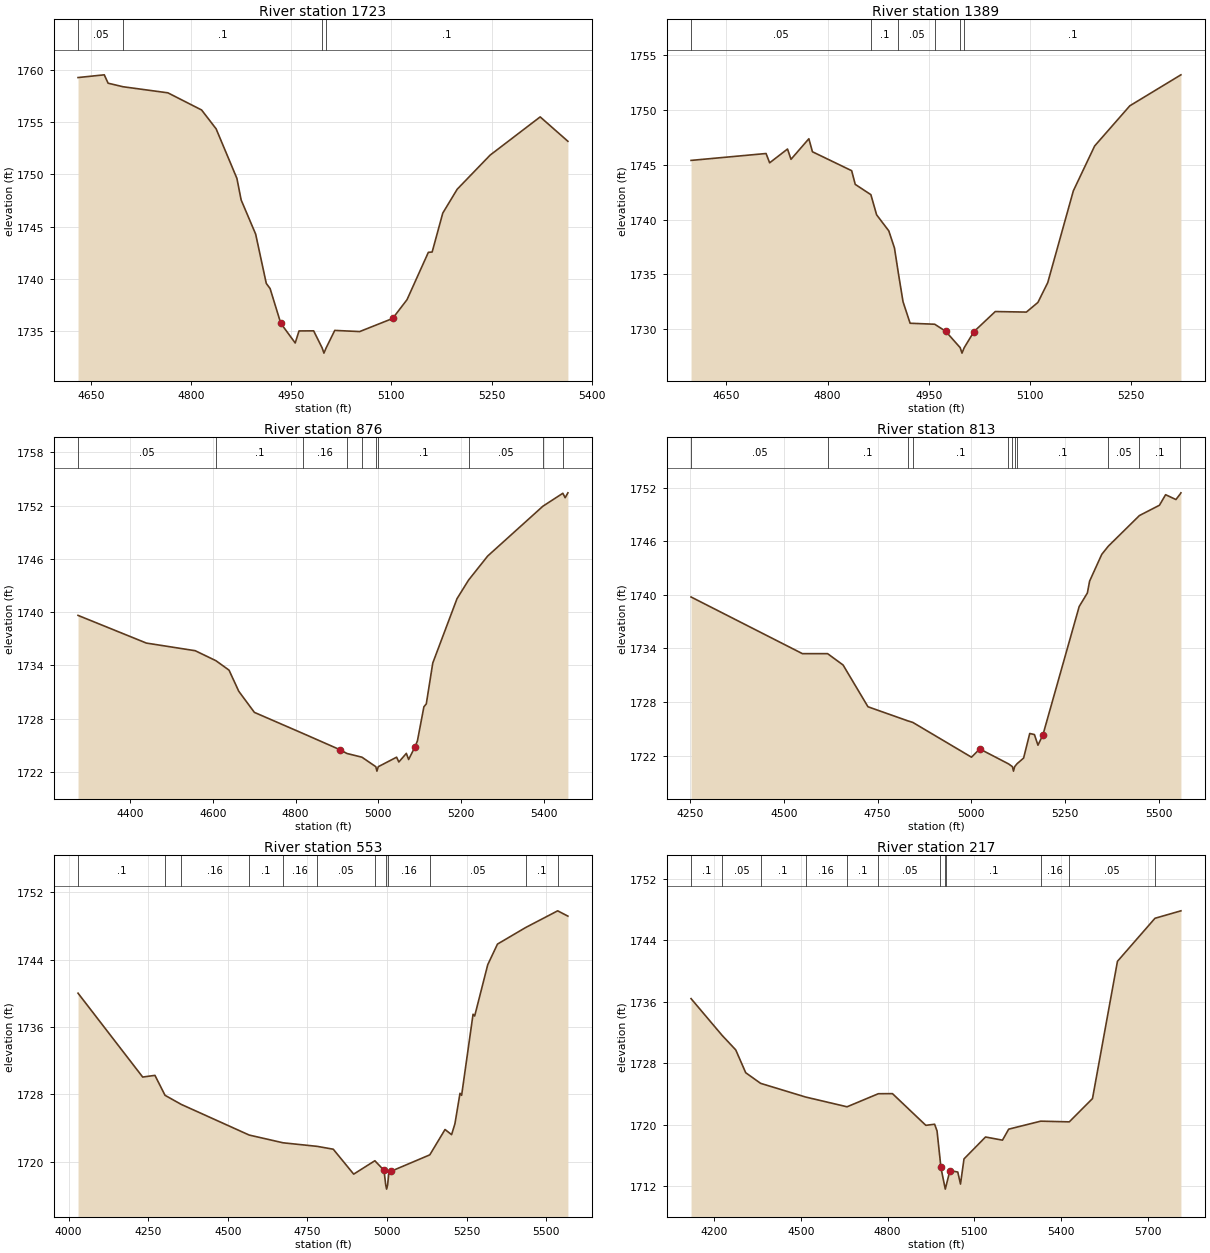
Type RM Length L Ch R = 1 ,1723    ,736,736,736
BEGIN DESCRIPTION:
UNT 1083 IN HEWA 3.0
END DESCRIPTION:
XS GIS Cut Line= 2
      2718571.42     10031718.22       2719209.8     10032079.04
#Sta/Elev= 30
    4631 1759.24  4670.3  1759.5    4676  1758.7  4698.5 1758.36  4765.5 1757.78
    4816 1756.14  4837.7 1754.34  4868.8 1749.61  4875.2 1747.54  4896.9 1744.28
  4912.8 1739.57  4918.5 1739.08  4934.5 1735.76  4956.1 1733.88  4961.8 1735.03
  4983.7 1735.04  4996.4 1733.41  4999.1 1732.91  5002.4 1733.41  5015.3 1735.08
  5052.6 1734.97  5101.9 1736.22  5123.5 1738.02  5155.4 1742.54  5161.1 1742.57
    5177 1746.29  5198.6 1748.57  5247.9 1751.83  5322.8 1755.48  5364.3 1753.15
#Mann= 4 ,-1 , 0
    4631     .05       0  4698.5      .1       0  4996.4     .07       0
  5002.4      .1       0
Bank Sta=4934.5,5101.9
XS Rating Curve= 0 ,0
Exp/Cntr=0.3,0.1

Type RM Length L Ch R = 1 ,1389    ,513,513,513
BEGIN DESCRIPTION:
Mapping XS 15023228
END DESCRIPTION:
XS GIS Cut Line= 2
      2718409.85     10032053.14        2719100.     10032281.02
#Sta/Elev= 30
  4597.5 1745.41  4708.8 1746.04  4714.1 1745.19  4740.6 1746.45  4745.8 1745.51
  4772.3 1747.39  4777.6  1746.2  4835.8 1744.47  4841.1 1743.22  4864.3 1742.28
  4872.8 1740.44  4890.9 1738.97  4899.3 1737.41  4905.1  1735.1    4912  1732.5
  4922.5 1730.53    4959 1730.44  4975.2  1729.8  4996.8  1728.3  4999.5  1727.8
  5002.8  1728.3  5017.3 1729.77  5048.9  1731.6    5095 1731.55  5112.1 1732.43
  5126.7 1734.24  5164.7 1742.63  5196.3 1746.73  5248.5  1750.4  5324.3 1753.23
#Mann= 6 ,-1 , 0
  4597.5     .05       0  4864.3      .1       0  4905.1     .05       0
    4959      .1       0  4996.8     .07       0  5002.8      .1       0
Bank Sta=4975.2,5017.3
XS Rating Curve= 0 ,0
Exp/Cntr=0.3,0.1

Type RM Length L Ch R = 1 ,876     ,63,63,63
BEGIN DESCRIPTION:
Mapping XS 0f422d0d
END DESCRIPTION:
XS GIS Cut Line= 3
      2718247.14     10032265.84      2718987.12     10032582.66
      2719179.77     10032257.97
#Sta/Elev= 30
  4274.9 1739.62  4439.8  1736.5  4557.7 1735.64  4607.9 1734.51  4639.4 1733.45
  4662.9 1731.07  4700.6 1728.69  4818.6  1726.3  4907.3 1724.48  4923.9 1724.06
  4960.2 1723.64  4993.7 1722.57  4996.4 1722.07  4999.7 1722.57  5043.9 1723.64
  5049.3  1723.1  5067.4 1724.07  5072.9 1723.38  5088.4 1724.81  5094.2 1725.49
  5109.8 1729.32  5115.6 1729.65  5131.2 1734.25  5189.7  1741.5  5217.5 1743.59
  5263.8 1746.31    5397 1751.92  5445.2 1753.38  5450.8 1752.88  5457.4 1753.43
#Mann= 10 ,-1 , 0
  4274.9     .05       0  4607.9      .1       0  4818.6     .16       0
  4923.9     .05       0  4960.2      .1       0  4993.7     .07       0
  4999.7      .1       0  5217.5     .05       0    5397      .1       0
  5445.2     .05       0
Bank Sta=4907.3,5088.4
XS Rating Curve= 0 ,0
Exp/Cntr=0.3,0.1

Type RM Length L Ch R = 1 ,813     ,260,260,260
BEGIN DESCRIPTION:
UNT 1083 IN HEWA 2.0
END DESCRIPTION:
XS GIS Cut Line= 3
      2718221.07     10032294.04      2719002.31     10032660.79
      2719210.43      10032268.4
#Sta/Elev= 30
  4252.1 1739.76  4549.3 1733.42  4616.5 1733.42  4657.8 1732.15  4724.2 1727.48
  4830.1 1725.91  4843.8 1725.73  5000.4 1721.84  5022.5 1722.76  5098.9  1721.1
  5109.7 1720.78  5112.5 1720.28  5115.7 1720.78  5122.1 1721.11  5139.5 1721.74
  5155.9 1724.49  5168.4 1724.37  5177.8 1723.18    5191 1724.33  5287.8 1738.69
  5309.7 1740.21  5315.6 1741.53  5348.1 1744.53  5365.5 1745.44  5448.6 1748.87
    5502 1750.02  5518.4  1751.2    5546 1750.66  5557.4 1751.28  5559.3 1751.41
#Mann= 11 ,-1 , 0
  4252.1     .05       0  4616.5      .1       0  4830.1     .16       0
  4843.8      .1       0  5098.9     .16       0  5109.7     .07       0
  5115.7     .16       0  5122.1      .1       0  5365.5     .05       0
  5448.6      .1       0  5557.4     .05       0
Bank Sta=5022.5,5191
XS Rating Curve= 0 ,0
Exp/Cntr=0.3,0.1

Type RM Length L Ch R = 1 ,553     ,336,336,336
BEGIN DESCRIPTION:
Mapping XS 584c4804
END DESCRIPTION:
XS GIS Cut Line= 4
      2718149.41      10032513.2      2718846.06     10032836.57
      2719128.18      10032667.3      2719236.68      10032239.8
#Sta/Elev= 30
  4029.7 1740.03  4232.7 1730.07  4271.2 1730.27  4302.9  1727.9  4353.9 1726.82
  4567.2 1723.18  4673.8 1722.26  4780.4 1721.84  4831.1  1721.5  4895.2 1718.54
  4961.7 1720.13  4990.4 1718.99  4995.8 1717.26  4998.6 1716.76  5001.8 1717.26
    5006  1718.9  5011.8 1718.87  5134.2 1720.83    5182 1723.84  5202.6 1723.23
    5213 1724.51    5229 1728.14  5234.1  1727.9    5270 1737.53  5275.1 1737.32
  5316.1 1743.41  5346.7 1745.86  5435.3 1747.83  5535.7 1749.81  5567.8 1749.18
#Mann= 12 ,-1 , 0
  4029.7      .1       0  4302.9     .05       0  4353.9     .16       0
  4567.2      .1       0  4673.8     .16       0  4780.4     .05       0
  4961.7     .16       0  4995.8     .07       0  5001.8     .16       0
  5134.2     .05       0  5435.3      .1       0  5535.7     .05       0
Bank Sta=4990.4,5011.8
XS Rating Curve= 0 ,0
Exp/Cntr=0.3,0.1

Type RM Length L Ch R = 1 ,217     ,0,0,0
BEGIN DESCRIPTION:
UNT 1083 IN HEWA 1.0
END DESCRIPTION:
XS GIS Cut Line= 4
      2718149.48      10032617.4      2718876.44     10032981.97
      2719180.26     10032804.02      2719254.04     10032281.04
#Sta/Elev= 30
  4120.6 1736.43    4228 1731.65  4275.1 1729.76  4309.6 1726.79    4361 1725.41
  4516.6 1723.63    4660 1722.36    4768 1724.06  4816.9 1724.07  4932.2 1719.95
  4962.6 1720.09    4971 1719.22  4982.3 1715.24  4984.1  1714.5  4996.8 1712.15
  4999.5 1711.65  5002.8 1712.15  5015.5 1714.07  5042.7 1713.87  5052.1 1712.31
  5064.2 1715.58  5138.6 1718.43  5197.2 1718.02  5218.7 1719.45  5329.5 1720.49
  5428.2  1720.4  5508.4 1723.43  5594.7 1741.28  5724.4 1746.88  5814.1 1747.85
#Mann= 12 ,-1 , 0
  4120.6      .1       0    4228     .05       0    4361      .1       0
  4516.6     .16       0    4660      .1       0    4768     .05       0
  4982.3      .1       0  4996.8     .07       0  5002.8      .1       0
  5329.5     .16       0  5428.2     .05       0  5724.4      .1       0
Bank Sta=4984.1,5015.5
XS Rating Curve= 0 ,0
Exp/Cntr=0.3,0.1

Chan Stop Cuts=-1
Use User Specified Reach Order=0
Composite Channel Slope=5