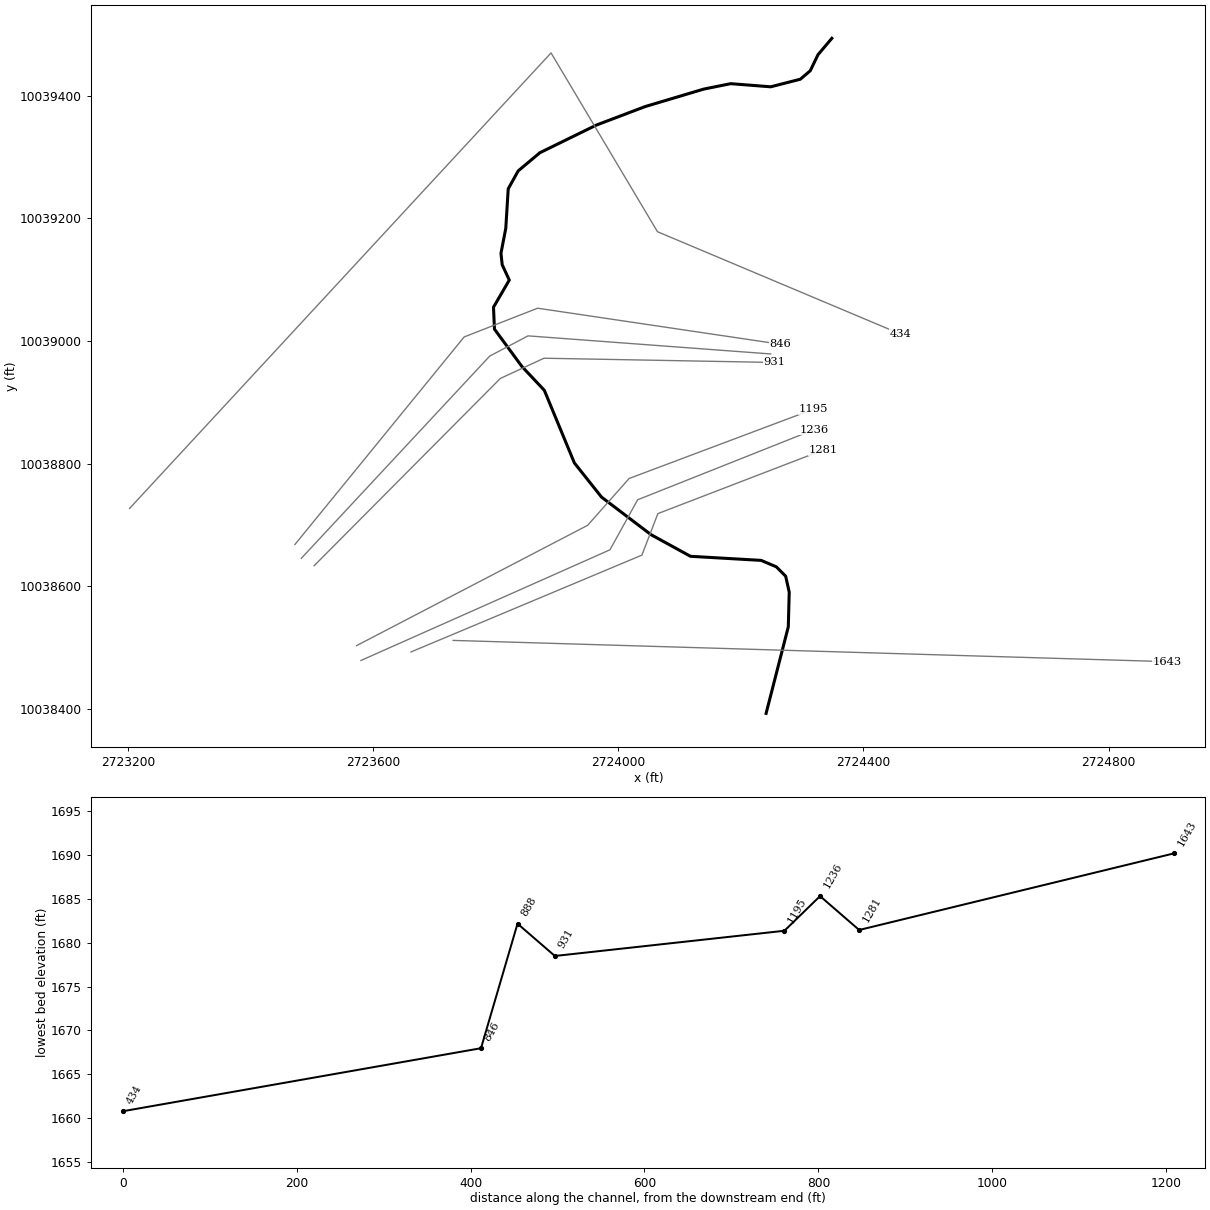
--- UNT 1084 IN HEWA.prj (project) ---

Proj Title=UNT 1084 IN HEWA Base Level Engineering
Current Plan=p01
Default Exp/Contr=0.3,0.1
English Units
Geom File=g01
Flow File=f01
Plan File=p01
BEGIN DESCRIPTION:
UNT 1084 IN HEWA
END DESCRIPTION:

--- UNT 1084 IN HEWA.p01 (plan) ---

Plan Title=Multiple Run
Short Identifier=Multiple
Geom File=g01
Flow File=f01
Subcritical Flow
K Sum by GR= 0
Std Step Tol= 0.01
Critical Tol= 0.01
Num of Std Step Trials= 20
Max Error Tol= 0.3
Flow Tol Ratio= 0.001
Split Flow NTrial= 30
Split Flow Tol= 0.02
Split Flow Ratio= 0.02
Log Output Level= 0
Friction Slope Method= 1
Unsteady Friction Slope Method= 2
Unsteady Bridges Friction Slope Method= 1
Parabolic Critical Depth
Global Vel Dist=  1 , 1 , 1
Global Log Level= 0
CheckData=True
Encroach Param= -1, 0, 0, 0
BEGIN DESCRIPTION:
Multiple Run
END DESCRIPTION:

--- UNT 1084 IN HEWA.f01 (steady flow) ---

Flow Title=Multiple
Number of Profiles=7
Profile Names=10-year,25-year,50-year,1pct_min,100-year,1pct_plu,500-year
River Rch & RM= UNT 1084 IN HEWA,Reach-1,1643
     463     651     809     739    1000    1352    1530
Boundary for River Rch & Prof#=UNT 1084 IN HEWA,Reach-1,1
Up Type=0
Dn Type=3
Dn Slope=0.005
Boundary for River Rch & Prof#=UNT 1084 IN HEWA,Reach-1,2
Up Type=0
Dn Type=3
Dn Slope=0.005
Boundary for River Rch & Prof#=UNT 1084 IN HEWA,Reach-1,3
Up Type=0
Dn Type=3
Dn Slope=0.005
Boundary for River Rch & Prof#=UNT 1084 IN HEWA,Reach-1,4
Up Type=0
Dn Type=3
Dn Slope=0.005
Boundary for River Rch & Prof#=UNT 1084 IN HEWA,Reach-1,5
Up Type=0
Dn Type=3
Dn Slope=0.005
Boundary for River Rch & Prof#=UNT 1084 IN HEWA,Reach-1,6
Up Type=0
Dn Type=3
Dn Slope=0.005
Boundary for River Rch & Prof#=UNT 1084 IN HEWA,Reach-1,7
Up Type=0
Dn Type=3
Dn Slope=0.005

--- UNT 1084 IN HEWA.g01 (geometry) ---

Geom Title=Existing Conditions

River Reach=UNT 1084 IN HEWA,Reach-1
Reach XY= 30
      2724241.23     10038392.59      2724277.46     10038533.81
      2724278.96     10038590.39      2724273.14     10038616.37
      2724257.95     10038631.64      2724233.13     10038642.16
      2724117.87     10038648.81      2724053.41     10038684.17
      2723972.81     10038745.36      2723928.53     10038801.06
      2723879.47     10038919.62      2723842.79     10038958.59
      2723798.12     10039019.37      2723796.56     10039055.14
      2723822.34     10039099.40      2723810.74     10039124.40
      2723808.75     10039143.20      2723816.59     10039183.67
      2723820.59     10039248.29      2723836.87     10039277.51
      2723872.19     10039307.11      2723964.13     10039352.13
      2724044.01     10039382.43      2724139.72     10039410.99
      2724183.42     10039419.77      2724248.80     10039414.67
      2724297.10     10039427.05      2724313.26     10039440.84
      2724325.98     10039467.17      2724348.47     10039493.73

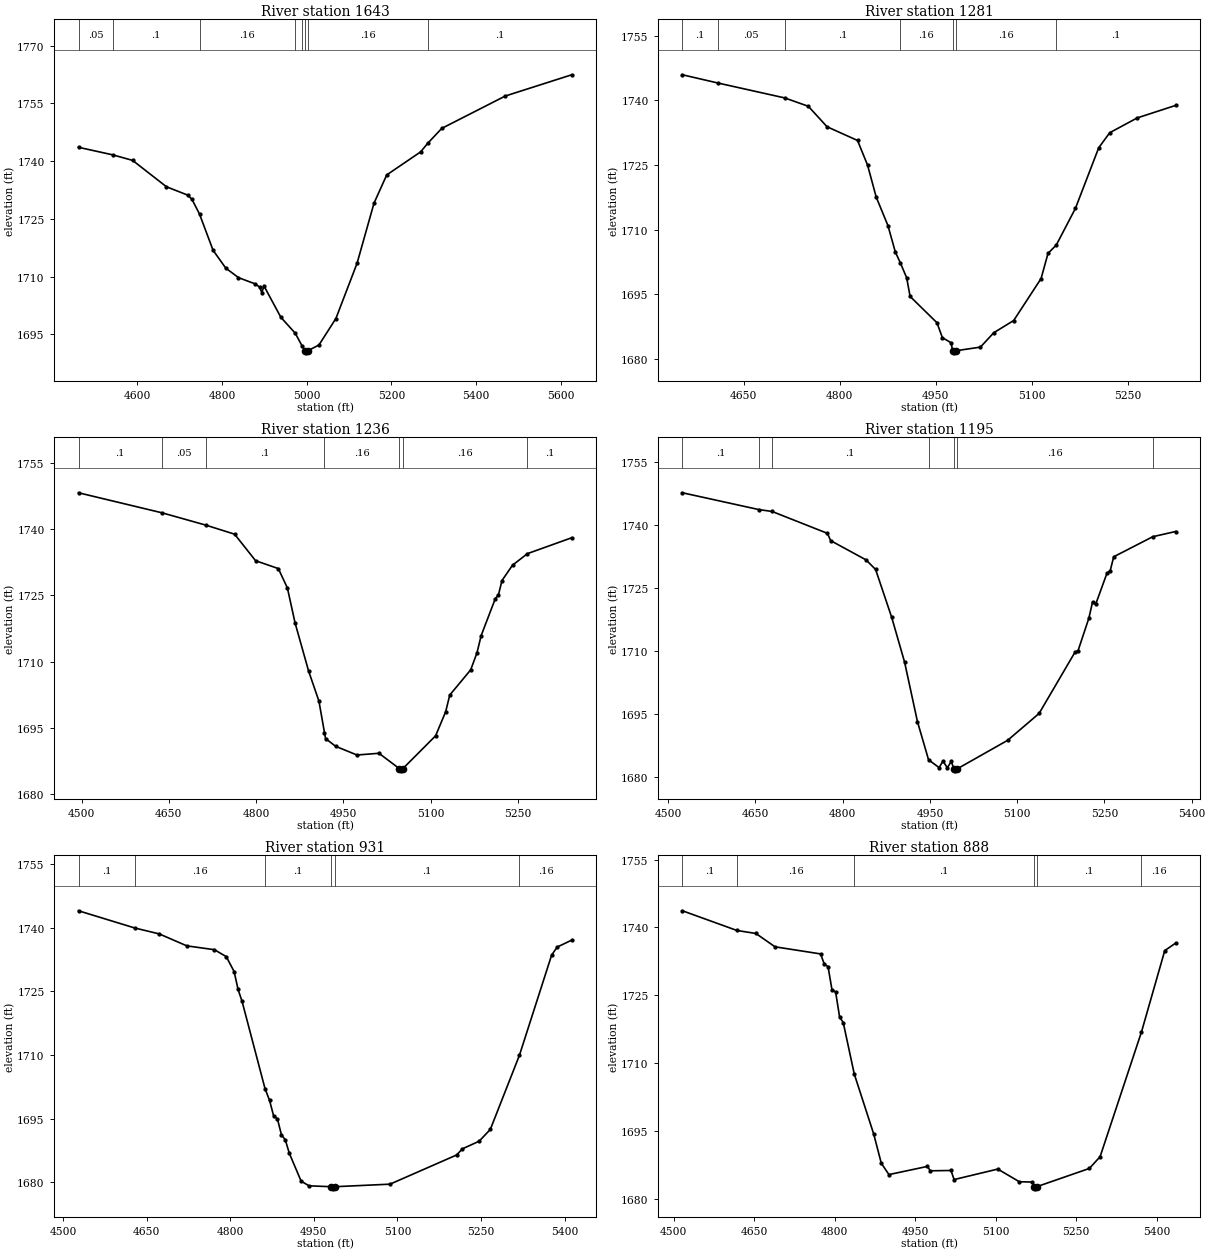
Type RM Length L Ch R = 1,1643,362,362,362
BEGIN DESCRIPTION:
UNT 1084 IN HEWA 2.0
END DESCRIPTION:
XS GIS Cut Line= 2
      2723730.72     10038511.62      2724895.40     10038476.96
#Sta/Elev= 30
  4460.8 1743.61  4541.5 1741.65  4588.6 1740.21  4668.6 1733.35  4718.7 1731.19
  4728.7 1730.11  4746.7 1726.25  4778.7 1716.85  4808.7 1712.22  4838.7 1709.75
  4878.7 1708.10  4888.7 1707.28  4893.9 1705.84  4898.9 1707.59  4938.8 1699.45
  4972.9 1695.29  4988.7 1692.06  4995.8 1690.71  4998.5 1690.21  5001.8 1690.71
  5028.8 1692.25  5068.8 1699.12  5118.8 1713.46  5158.9 1729.10  5188.9 1736.43
  5268.9 1742.41  5285.5 1744.61  5318.9 1748.52  5469.0 1756.93  5626.0 1762.45
#Mann=8,-1,0
  4460.8    0.05       0  4541.5     0.1       0  4746.7    0.16       0
  4972.9     0.1       0  4988.7    0.16       0  4995.8    0.07       0
  5001.8    0.16       0  5285.5     0.1       0
Bank Sta=4995.8,5001.8
Exp/Cntr=0.3,0.1

Type RM Length L Ch R = 1,1281,45,45,45
BEGIN DESCRIPTION:
Mapping XS 6dcb1a5c
END DESCRIPTION:
XS GIS Cut Line= 4
      2723661.94     10038492.77      2724038.65     10038650.75
      2724064.70     10038718.45      2724334.49     10038822.22
#Sta/Elev= 30
  4554.5 1745.92  4609.3 1744.03  4714.4 1740.55  4751.1 1738.61  4780.3 1733.87
  4827.9 1730.69  4843.5 1725.00  4857.1 1717.55  4875.4 1710.95  4886.9 1704.84
  4894.6 1702.37  4904.6 1698.86  4910.0 1694.53  4951.9 1688.44  4960.4 1684.97
  4974.0 1683.80  4976.3 1681.96  4979.1 1681.46  4982.3 1681.96  5019.8 1682.79
  5040.6 1686.12  5071.7 1688.95  5114.5 1698.69  5125.3 1704.51  5138.3 1706.47
  5168.1 1714.95  5204.5 1729.01  5221.7 1732.49  5264.6 1735.92  5324.6 1738.82
#Mann=7,-1,0
  4554.5     0.1       0  4609.3    0.05       0  4714.4     0.1       0
  4894.6    0.16       0  4976.3    0.07       0  4982.3    0.16       0
  5138.3     0.1       0
Bank Sta=4976.3,4982.3
Exp/Cntr=0.3,0.1

Type RM Length L Ch R = 1,1236,41,41,41
BEGIN DESCRIPTION:
Mapping XS 35e50898
END DESCRIPTION:
XS GIS Cut Line= 4
      2723580.34     10038478.88      2723986.57     10038659.43
      2724031.71     10038741.02      2724319.87     10038855.59
#Sta/Elev= 30
  4494.7 1748.21  4638.2 1743.68  4713.7 1740.89  4763.0 1738.85  4799.1 1732.85
  4838.2 1731.07  4853.8 1726.68  4866.9 1718.82  4890.2 1707.91  4908.0 1701.10
  4917.5 1694.00  4919.4 1692.63  4936.7 1690.88  4973.4 1688.91  5011.2 1689.30
  5046.3 1685.83  5049.0 1685.33  5052.3 1685.83  5108.6 1693.26  5125.9 1698.71
  5132.9 1702.47  5168.9 1708.17  5179.7 1712.02  5186.9 1715.92  5211.2 1724.27
  5216.5 1725.07  5222.7 1728.37  5240.8 1731.84  5266.5 1734.45  5342.6 1738.04
#Mann=7,-1,0
  4494.7     0.1       0  4638.2    0.05       0  4713.7     0.1       0
  4917.5    0.16       0  5046.3    0.07       0  5052.3    0.16       0
  5266.5     0.1       0
Bank Sta=5046.3,5052.3
Exp/Cntr=0.3,0.1

Type RM Length L Ch R = 1,1195,264,264,264
BEGIN DESCRIPTION:
Mapping XS 3c5a1baa
END DESCRIPTION:
XS GIS Cut Line= 4
      2723573.35     10038503.16      2723950.11     10038699.36
      2724017.82     10038775.75      2724318.15     10038888.59
#Sta/Elev= 30
  4524.7 1747.65  4656.2 1743.64  4678.7 1743.20  4773.9 1737.98  4779.5 1736.24
  4840.2 1731.66  4856.7 1729.37  4884.4 1717.94  4906.5 1707.29  4928.6 1693.12
  4947.7 1684.01  4965.8 1682.14  4972.5 1683.69  4980.0 1682.10  4986.7 1683.61
  4991.3 1681.87  4994.0 1681.37  4997.3 1681.87  5083.7 1688.65  5137.7 1695.05
  5199.3 1709.63  5204.7 1710.02  5223.2 1717.75  5229.6 1721.63  5234.9 1721.06
  5254.5 1728.53  5259.8 1729.00  5265.9 1732.39  5333.1 1737.18  5372.4 1738.42
#Mann=7,-1,0
  4524.7     0.1       0  4656.2    0.05       0  4678.7     0.1       0
  4947.7    0.16       0  4991.3    0.07       0  4997.3    0.16       0
  5333.1     0.1       0
Bank Sta=4991.3,4997.3
Exp/Cntr=0.3,0.1

Type RM Length L Ch R = 1,931,43,43,43
BEGIN DESCRIPTION:
Mapping XS f017cdab
END DESCRIPTION:
XS GIS Cut Line= 4
      2723503.94     10038633.39      2723807.75     10038938.94
      2723878.93     10038971.93      2724254.53     10038965.00
#Sta/Elev= 30
  4527.8 1744.01  4628.6 1739.96  4672.7 1738.56  4722.2 1735.74  4771.6 1734.84
  4792.9 1733.21  4807.0 1729.69  4814.1 1725.47  4821.2 1722.70  4862.4 1702.12
  4870.6 1699.33  4877.7 1695.77  4884.8 1694.92  4891.9 1691.23  4898.9 1690.01
  4906.0 1686.88  4927.2 1680.31  4941.4 1679.20  4981.5 1678.99  4984.2 1678.49
  4987.5 1678.99  5086.7 1679.59  5206.1 1686.46  5216.7 1687.92  5246.7 1689.72
  5266.7 1692.49  5319.0 1709.98  5376.7 1733.56  5386.7 1735.46  5412.8 1737.10
#Mann=6,-1,0
  4527.8     0.1       0  4628.6    0.16       0  4862.4     0.1       0
  4981.5    0.07       0  4987.5     0.1       0  5319.0    0.16       0
Bank Sta=4981.5,4987.5
Exp/Cntr=0.3,0.1

Type RM Length L Ch R = 1,888,42,42,42
BEGIN DESCRIPTION:
Mapping XS 7594df0f
END DESCRIPTION:
XS GIS Cut Line= 4
      2723483.13     10038645.57      2723790.39     10038975.40
      2723852.89     10039008.39      2724248.75     10038978.87
#Sta/Elev= 30
  4516.6 1743.68  4617.9 1739.33  4653.4 1738.66  4689.0 1735.71  4773.8 1734.14
  4780.9 1731.84  4787.7 1731.34  4795.0 1726.25  4801.9 1725.68  4809.2 1720.21
  4816.0 1718.96  4836.6 1707.56  4872.7 1694.33  4886.9 1687.84  4901.1 1685.33
  4972.7 1687.14  4978.3 1686.17  5016.7 1686.24  5022.4 1684.23  5103.8 1686.55
  5143.9 1683.75  5168.4 1683.68  5171.0 1682.68  5173.7 1682.18  5177.0 1682.68
  5274.3 1686.69  5294.3 1689.29  5371.4 1716.89  5414.7 1734.87  5435.0 1736.53
#Mann=6,-1,0
  4516.6     0.1       0  4617.9    0.16       0  4836.6     0.1       0
  5171.0    0.07       0  5177.0     0.1       0  5371.4    0.16       0
Bank Sta=5171,5177
Exp/Cntr=0.3,0.1

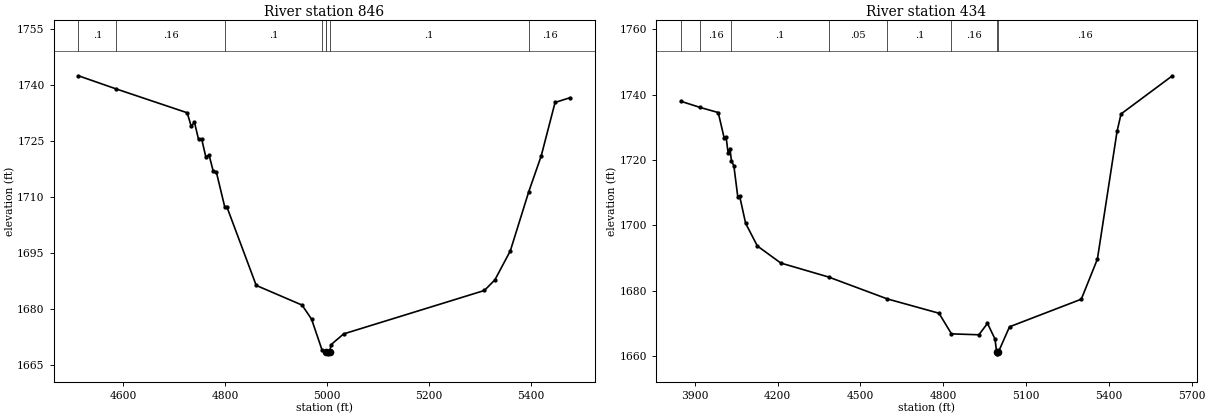
Type RM Length L Ch R = 1,846,412,412,412
BEGIN DESCRIPTION:
Mapping XS 0357d52e
END DESCRIPTION:
XS GIS Cut Line= 4
      2723472.66     10038668.08      2723748.72     10039006.65
      2723868.51     10039053.52      2724264.79     10038994.69
#Sta/Elev= 30
  4511.7 1742.51  4586.4 1738.96  4725.4 1732.59  4733.2 1728.99  4739.7 1730.03
  4747.6 1725.48  4754.0 1725.47  4761.9 1720.79  4768.4 1721.24  4776.3 1717.05
  4782.7 1716.67  4799.0 1707.42  4803.6 1707.26  4861.0 1686.30  4951.1 1681.02
  4969.7 1677.26  4990.3 1668.99  4998.0 1668.46  4999.0 1668.45  5001.7 1667.95
  5005.0 1668.45  5008.2 1670.43  5032.7 1673.29  5309.3 1684.94  5329.9 1687.78
  5360.2 1695.54  5396.5 1711.44  5420.9 1721.00  5448.2 1735.36  5477.8 1736.64
#Mann=8,-1,0
  4511.7     0.1       0  4586.4    0.16       0  4799.0     0.1       0
  4990.3    0.05       0  4998.0     0.1       0  4999.0    0.07       0
  5005.0     0.1       0  5396.5    0.16       0
Bank Sta=4999,5005
Exp/Cntr=0.3,0.1

Type RM Length L Ch R = 1,434,0,0,0
BEGIN DESCRIPTION:
UNT 1084 IN HEWA 1.0
END DESCRIPTION:
XS GIS Cut Line= 4
      2723202.94     10038726.91      2723890.44     10039469.96
      2724064.05     10039178.29      2724459.86     10039011.63
#Sta/Elev= 30
  3849.0 1738.00  3919.7 1736.09  3985.0 1734.54  4006.5 1726.76  4013.4 1727.14
  4020.7 1722.23  4027.5 1723.53  4032.8 1719.84  4041.7 1718.19  4055.9 1708.74
  4062.7 1708.94  4084.2 1700.68  4126.7 1693.73  4211.8 1688.51  4385.2 1684.23
  4598.1 1677.53  4784.7 1673.17  4829.9 1666.86  4929.2 1666.58  4960.4 1670.07
  4987.6 1665.28  4993.6 1661.25  4996.3 1660.75  4999.6 1661.25  5040.2 1669.02
  5300.2 1677.46  5358.5 1689.70  5429.7 1728.75  5444.2 1734.11  5630.2 1745.78
#Mann=8,-1,0
  3849.0     0.1       0  3919.7    0.16       0  4032.8     0.1       0
  4385.2    0.05       0  4598.1     0.1       0  4829.9    0.16       0
  4993.6    0.07       0  4999.6    0.16       0
Bank Sta=4993.6,4999.6
Exp/Cntr=0.3,0.1

Chan Stop Cuts=-1