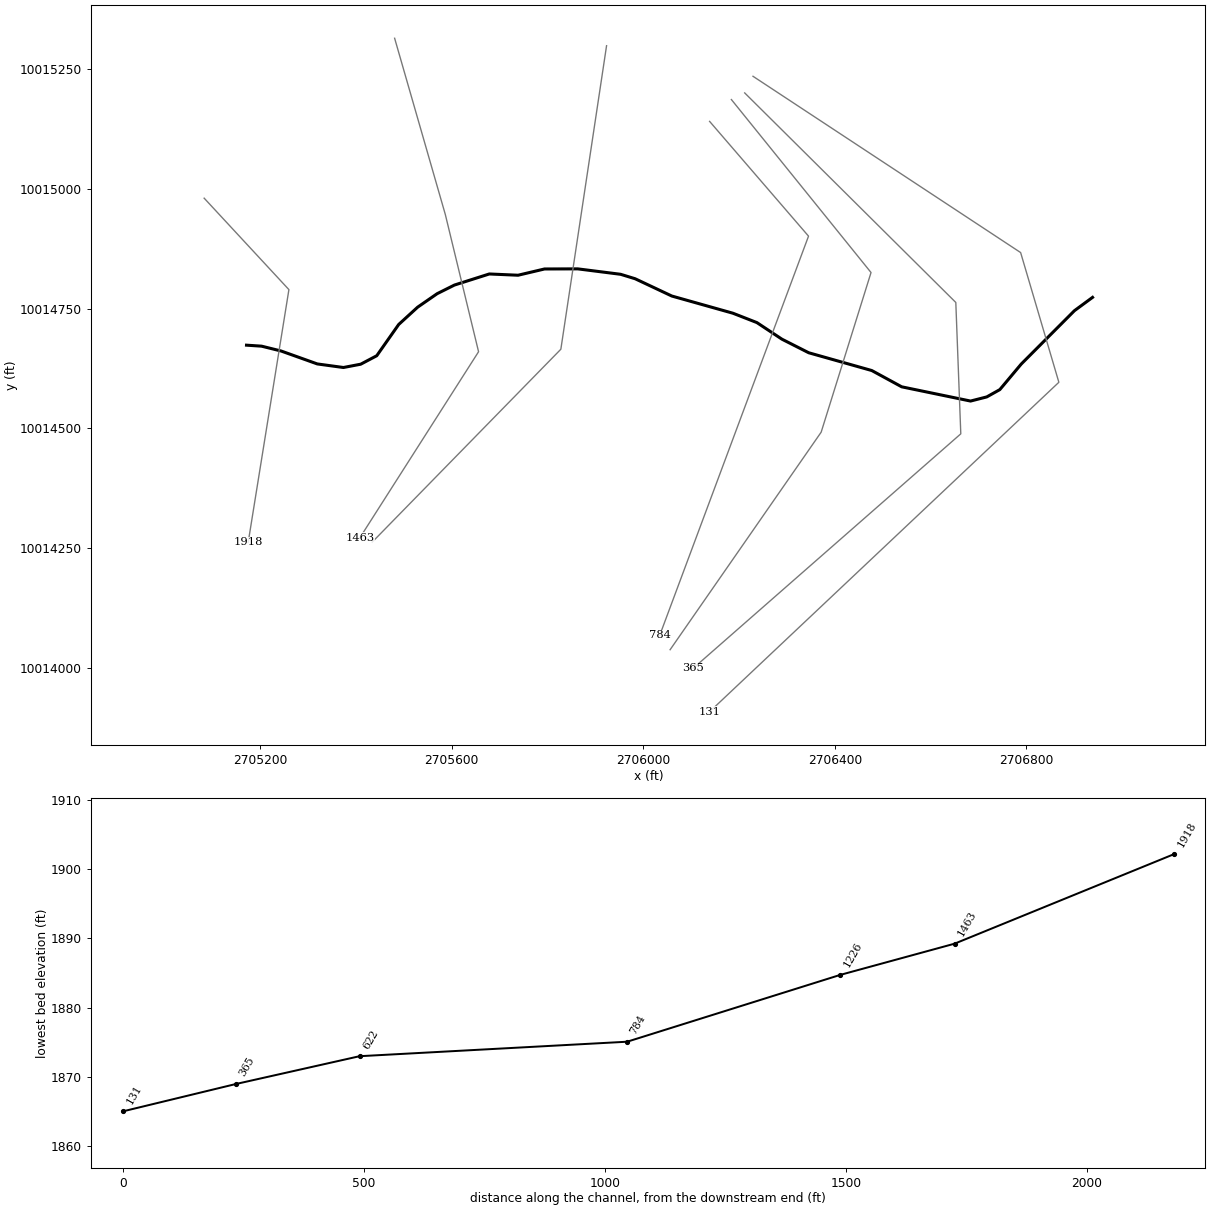
--- UNT 1085 IN HEWA.prj (project) ---

Proj Title=UNT 1085 IN HEWA Base Level Engineering
Current Plan=p01
Default Exp/Contr=0.3,0.1
English Units
Geom File=g01
Flow File=f01
Plan File=p01
Y Axis Title=Elevation
X Axis Title(PF)=Main Channel Distance
X Axis Title(XS)=Station
BEGIN DESCRIPTION:
UNT 1085 IN HEWA
END DESCRIPTION:
DSS Export Rating Curves= 0
DSS Export Rating Curve Sorted= 0
DSS Export Volume Flow Curves= 0
DXF OffsetX= 0
DXF OffsetY= 0
DXF ScaleX= 1
DXF ScaleY= 10

--- UNT 1085 IN HEWA.p01 (plan) ---

Plan Title=Multiple Run
Short Identifier=Multiple
Geom File=g01
Flow File=f01
Subcritical Flow
K Sum by GR= 0
Std Step Tol= 0.01
Critical Tol= 0.01
Num of Std Step Trials= 20
Max Error Tol= 0.3
Flow Tol Ratio= 0.001
Split Flow NTrial= 30
Split Flow Tol= 0.02
Split Flow Ratio= 0.02
Log Output Level= 0
Friction Slope Method= 1
Unsteady Friction Slope Method= 2
Unsteady Bridges Friction Slope Method= 1
Parabolic Critical Depth
Global Vel Dist=  1 , 1 , 1
Global Log Level= 0
CheckData=True
Encroach Param= -1, 0, 0, 0
BEGIN DESCRIPTION:
Multiple Run
END DESCRIPTION:

--- UNT 1085 IN HEWA.f01 (steady flow) ---

Flow Title=Multiple
Program Version=4.10
Number of Profiles= 7
Profile Names=10-year,25-year,50-year,1pct_min,100-year,1pct_plu,500-year
River Rch & RM=UNT 1085 IN HEWA,Reach-1         ,1918
     456     628     770     691     935    1265    1374
Boundary for River Rch & Prof#=UNT 1085 IN HEWA,Reach-1         , 1
Up Type= 0
Dn Type= 3
Dn Slope=0.0085
Boundary for River Rch & Prof#=UNT 1085 IN HEWA,Reach-1         , 2
Up Type= 0
Dn Type= 3
Dn Slope=0.0085
Boundary for River Rch & Prof#=UNT 1085 IN HEWA,Reach-1         , 3
Up Type= 0
Dn Type= 3
Dn Slope=0.0085
Boundary for River Rch & Prof#=UNT 1085 IN HEWA,Reach-1         , 4
Up Type= 0
Dn Type= 3
Dn Slope=0.0085
Boundary for River Rch & Prof#=UNT 1085 IN HEWA,Reach-1         , 5
Up Type= 0
Dn Type= 3
Dn Slope=0.0085
Boundary for River Rch & Prof#=UNT 1085 IN HEWA,Reach-1         , 6
Up Type= 0
Dn Type= 3
Dn Slope=0.0085
Boundary for River Rch & Prof#=UNT 1085 IN HEWA,Reach-1         , 7
Up Type= 0
Dn Type= 3
Dn Slope=0.0085
DSS Import GetInterval= 0
DSS Import GetPeak= 0
DSS Import FillOption= 0

--- UNT 1085 IN HEWA.g01 (geometry) ---

Geom Title=Existing Conditions
Program Version=4.10

River Reach=UNT 1085 IN HEWA,Reach-1
Reach XY= 30
      2705171.19     10014673.91      2705202.68     10014671.83
      2705243.37     10014661.76      2705319.02     10014634.73
      2705373.61     10014627.28       2705409.7     10014634.17
      2705443.18     10014651.82      2705489.08     10014717.12
      2705528.57     10014753.19       2705569.4     10014781.42
      2705605.53     10014799.44      2705678.29     10014822.57
      2705738.43     10014819.95      2705793.74     10014833.01
      2705863.13     10014833.23       2705952.6      10014821.9
      2705982.96      10014812.6      2706059.62     10014776.51
      2706187.18     10014740.64      2706237.35     10014721.04
      2706289.59     10014686.44      2706345.55     10014658.08
      2706477.31     10014620.95       2706539.8     10014586.95
      2706683.59     10014557.23       2706717.5     10014565.88
      2706744.75     10014581.12      2706789.45     10014634.46
      2706900.64     10014745.93      2706938.47     10014773.73

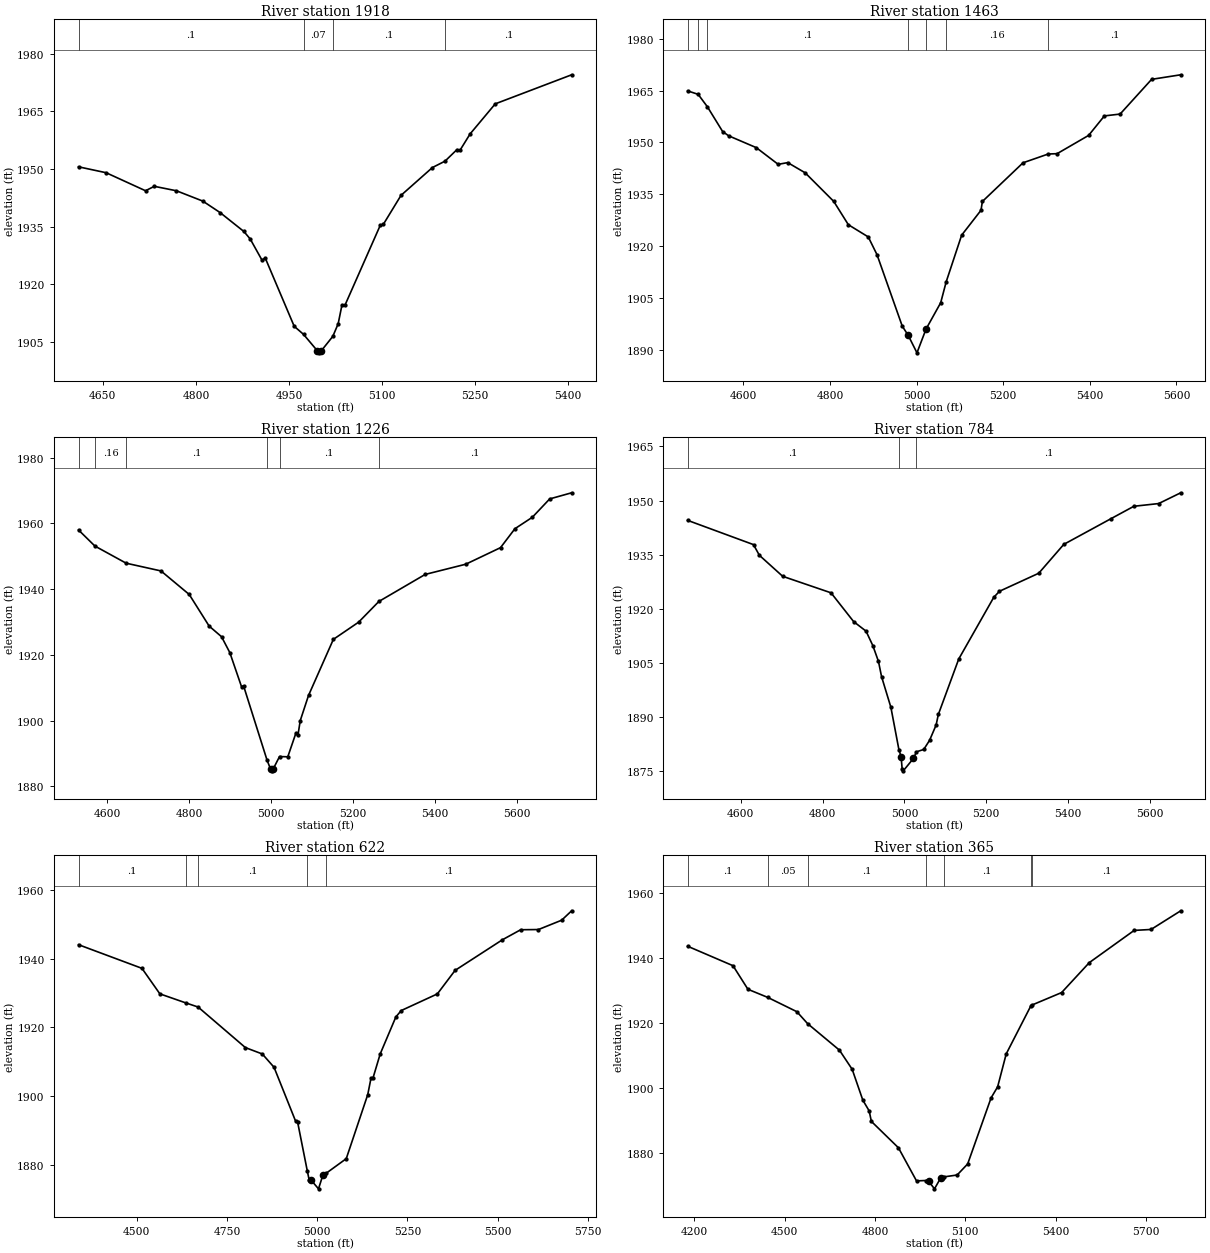
Type RM Length L Ch R = 1 ,1918    ,455,455,455
BEGIN DESCRIPTION:
UNT 1033 IN HEWA 5.1
END DESCRIPTION:
XS GIS Cut Line= 3
      2705082.69     10014980.84      2705259.74     10014789.91
      2705174.67     10014262.11
#Sta/Elev= 30
  4610.8 1950.58  4655.3 1949.04  4718.8 1944.35    4733  1945.5  4768.7 1944.34
  4811.2 1941.65    4839 1938.67  4877.4 1933.74  4887.6 1931.79  4906.7 1926.25
  4911.8 1926.85  4958.5 1909.06  4973.6 1906.95    4996 1902.65  4998.7 1902.15
    5002 1902.65  5020.8 1906.45  5029.4 1909.73  5035.4 1914.53  5040.4 1914.57
  5097.2 1935.34  5102.2  1935.6  5130.7 1943.15  5181.3 1950.39  5201.6 1952.05
  5220.8 1955.05  5225.9 1954.92  5242.1 1959.15  5282.6 1966.97  5405.8 1974.54
#Mann= 4 ,-1 , 0
  4610.8      .1       0  4973.6     .07       0  5020.8      .1       0
  5201.6      .1       0
Bank Sta=4996,5002
XS Rating Curve= 0 ,0
Exp/Cntr=0.3,0.1

Type RM Length L Ch R = 1 ,1463    ,237,237,237
BEGIN DESCRIPTION:
Mapping XS 6726fb85
END DESCRIPTION:
XS GIS Cut Line= 4
      2705480.57     10015314.74      2705586.48     10014946.68
      2705655.92     10014660.22      2705407.67     10014271.35
#Sta/Elev= 30
  4470.9 1964.91  4495.3 1963.91  4516.7  1960.3  4551.8 1953.17  4565.6 1951.94
  4629.6 1948.51  4680.1 1943.69  4702.2 1944.19  4742.5 1941.24  4808.5 1932.98
  4842.2 1926.25  4888.2 1922.72  4908.4 1917.59  4966.7 1896.96  4980.4  1894.3
  5000.7 1889.24  5021.6 1896.09  5055.5 1903.71  5068.2 1909.76  5103.9 1923.23
  5148.6 1930.42  5151.8 1932.96  5245.7 1944.14  5303.8 1946.67  5324.4 1946.77
  5397.2 1952.05  5433.6 1957.68  5469.9 1958.21  5542.7 1968.24    5610 1969.56
#Mann= 7 ,-1 , 0
  4470.9      .1       0  4495.3     .16       0  4516.7      .1       0
  4980.4     .07       0  5021.6      .1       0  5068.2     .16       0
  5303.8      .1       0
Bank Sta=4980.4,5021.6
XS Rating Curve= 0 ,0
Exp/Cntr=0.3,0.1

Type RM Length L Ch R = 1 ,1226    ,442,442,442
BEGIN DESCRIPTION:
Mapping XS 9fe7c3e0
END DESCRIPTION:
XS GIS Cut Line= 3
      2705923.29     10015299.14       2705827.8     10014665.43
      2705433.68     10014262.64
#Sta/Elev= 30
  4529.3    1958  4569.4  1953.1  4645.7 1947.89  4730.7 1945.54  4799.7 1938.38
  4848.3 1928.77  4878.6 1925.53  4898.8 1920.71  4927.4 1910.33  4932.5 1910.55
  4989.9 1887.93  4998.5 1885.24  5001.2 1884.74  5004.5 1885.24  5020.2 1889.09
  5040.4 1889.01  5060.3 1896.24  5065.4 1895.74  5070.8    1900    5091 1907.66
  5151.7 1924.73  5213.4 1929.96  5262.8 1936.25    5376 1944.48    5475 1947.58
  5559.9 1952.62  5595.1 1958.38  5637.6 1961.86    5680 1967.44  5733.7 1969.31
#Mann= 6 ,-1 , 0
  4529.3      .1       0  4569.4     .16       0  4645.7      .1       0
  4989.9     .07       0  5020.2      .1       0  5262.8      .1       0
Bank Sta=4998.5,5004.5
XS Rating Curve= 0 ,0
Exp/Cntr=0.3,0.1

Type RM Length L Ch R = 1 ,784     ,555,555,555
BEGIN DESCRIPTION:
Mapping XS f7547783
END DESCRIPTION:
XS GIS Cut Line= 3
      2706138.54     10015141.14      2706345.16     10014901.54
      2706034.49     10014068.46
#Sta/Elev= 30
  4469.9 1944.53    4631  1937.8  4645.3 1934.85  4702.3 1929.02  4820.5 1924.44
  4875.8 1916.46  4906.1 1913.82  4922.7 1909.81  4936.5 1905.42    4944 1901.22
  4966.8 1892.72  4986.4    1881  4991.8 1879.02  4994.4  1875.6  4997.1  1875.1
  5022.1 1878.56  5029.4 1880.38  5047.1 1881.02  5061.4 1883.56  5077.4  1887.8
  5082.8 1890.72  5132.7  1906.1  5218.3 1923.19  5232.2 1924.87  5328.3 1929.87
  5389.5 1937.87  5505.5 1945.03  5560.8 1948.43  5621.4 1949.18  5675.4 1952.17
#Mann= 3 ,-1 , 0
  4469.9      .1       0  4986.4     .07       0  5029.4      .1       0
Bank Sta=4991.8,5022.1
XS Rating Curve= 0 ,0
Exp/Cntr=0.3,0.1

Type RM Length L Ch R = 1 ,622     ,257,257,257
BEGIN DESCRIPTION:
Mapping XS 68d903c9
END DESCRIPTION:
XS GIS Cut Line= 4
      2706184.03     10015186.74      2706475.73     10014825.59
      2706371.56     10014492.26      2706056.04     10014038.06
#Sta/Elev= 30
  4338.8 1944.05  4514.6 1937.17  4564.2 1929.75  4635.4 1927.14  4670.2 1925.91
  4801.2 1914.11  4848.1 1912.25  4880.6 1908.38  4940.3 1892.71  4945.6  1892.6
  4972.6  1878.3    4978 1875.57  4983.3 1875.54  5003.8 1873.01  5015.8 1876.96
    5025 1877.54  5080.7 1881.79  5140.2 1900.41  5149.1 1905.12  5154.4 1905.12
  5174.8 1912.28  5218.2 1923.04  5233.1 1924.89  5333.1 1929.73  5382.3 1936.58
  5513.3 1945.48    5564  1948.4  5613.2 1948.46  5677.4 1951.17  5705.3 1953.92
#Mann= 5 ,-1 , 0
  4338.8      .1       0  4635.4     .05       0  4670.2      .1       0
  4972.6     .07       0    5025      .1       0
Bank Sta=4983.3,5015.8
XS Rating Curve= 0 ,0
Exp/Cntr=0.3,0.1

Type RM Length L Ch R = 1 ,365     ,234,234,234
BEGIN DESCRIPTION:
Mapping XS 5e809756
END DESCRIPTION:
XS GIS Cut Line= 4
      2706211.83      10015200.6      2706652.81     10014763.09
      2706663.23     10014488.79      2706104.19      10013999.2
#Sta/Elev= 30
  4177.3 1943.54  4328.2 1937.55  4377.8 1930.31  4443.7 1927.81  4540.4 1923.42
  4576.1 1919.75  4681.8 1911.61  4724.2 1905.72  4759.6 1896.24  4780.8 1892.92
  4787.9 1889.72  4877.9 1881.61    4938 1871.43    4968 1871.55    4978 1871.35
  4997.7 1868.99    5018 1872.28    5028 1872.65    5073 1873.24    5108 1876.64
  5185.8 1896.94  5207.6 1900.34  5236.1 1910.46  5318.5 1925.31  5322.5  1925.5
  5420.2  1929.3  5512.3 1938.51  5661.3  1948.4  5717.4 1948.69  5816.1 1954.43
#Mann= 7 ,-1 , 0
  4177.3      .1       0  4443.7     .05       0  4576.1      .1       0
    4968     .07       0    5028      .1       0  5318.5     .16       0
  5322.5      .1       0
Bank Sta=4978,5018
XS Rating Curve= 0 ,0
Exp/Cntr=0.3,0.1

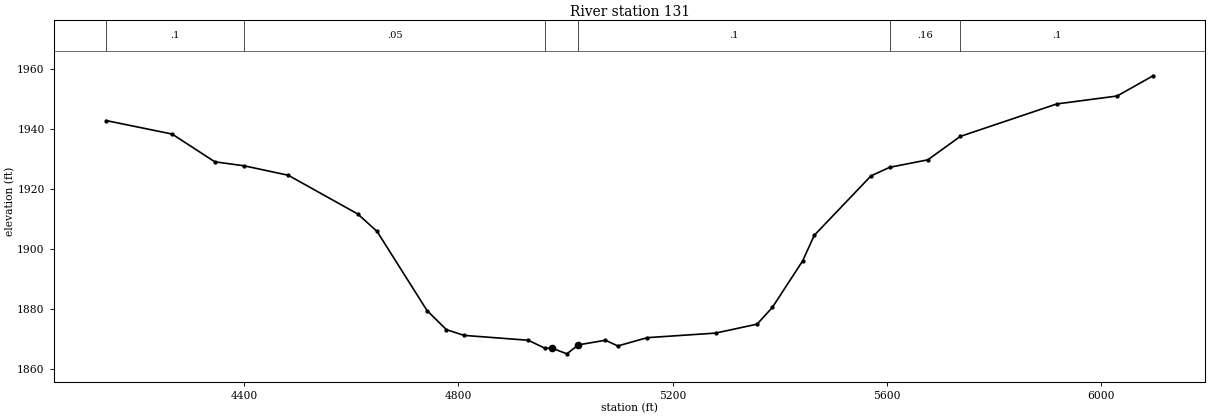
Type RM Length L Ch R = 1 ,131     ,0,0,0
BEGIN DESCRIPTION:
UNT 1033 IN HEWA 1.1
END DESCRIPTION:
XS GIS Cut Line= 4
      2706229.18     10015235.33      2706788.23     10014867.26
      2706868.09     10014596.43      2706138.89      10013908.9
#Sta/Elev= 30
  4142.5 1942.79  4265.5  1938.3  4345.2 1929.05  4399.9 1927.72  4482.3 1924.57
  4611.8 1911.68    4648 1905.86  4741.3 1879.48  4777.5 1873.11  4810.5  1871.2
  4930.2 1869.58  4961.5 1866.91  4974.4 1866.96  5002.3 1865.05    5024 1868.05
  5074.4 1869.58  5097.4 1867.68  5152.3 1870.44  5279.8 1871.96  5357.4 1874.95
  5385.8 1880.52  5442.4 1896.03  5463.9 1904.52  5569.9 1924.35  5604.9 1927.22
  5675.9  1929.7  5736.6 1937.51  5916.6 1948.33  6029.4 1950.98  6096.4 1957.72
#Mann= 6 ,-1 , 0
  4142.5      .1       0  4399.9     .05       0  4961.5     .07       0
    5024      .1       0  5604.9     .16       0  5736.6      .1       0
Bank Sta=4974.4,5024
XS Rating Curve= 0 ,0
Exp/Cntr=0.3,0.1

Chan Stop Cuts=-1
Use User Specified Reach Order=0
Composite Channel Slope=5