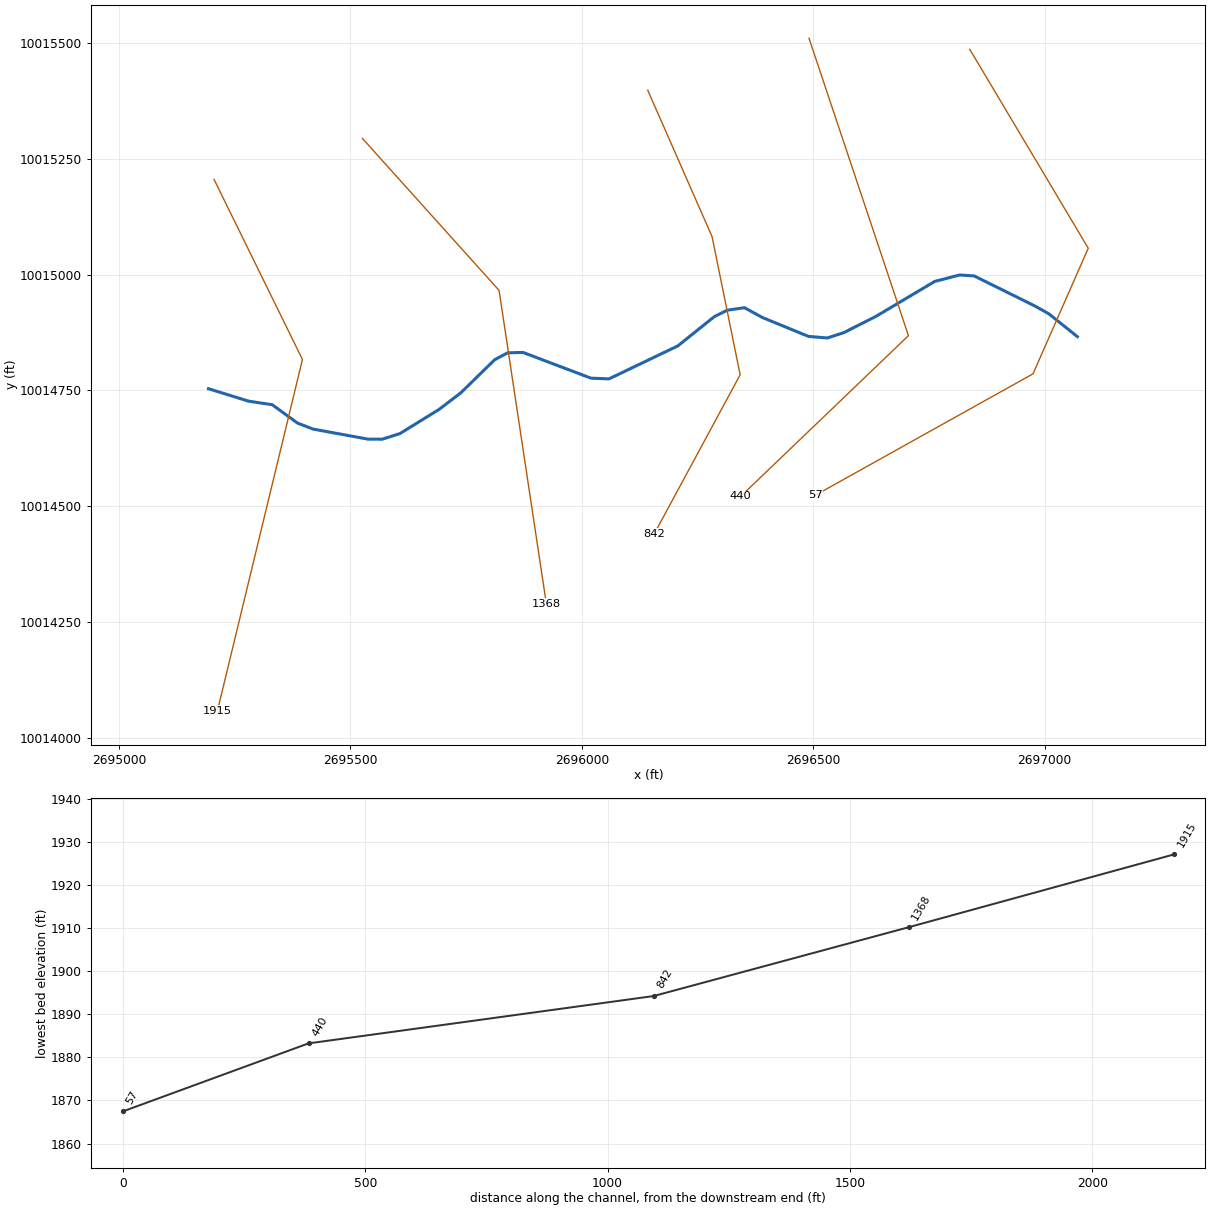
--- UNT 1086 IN HEWA.prj (project) ---

Proj Title=UNT 1086 IN HEWA Base Level Engineering
Current Plan=p01
Default Exp/Contr=0.3,0.1
English Units
Geom File=g01
Flow File=f01
Plan File=p01
Y Axis Title=Elevation
X Axis Title(PF)=Main Channel Distance
X Axis Title(XS)=Station
BEGIN DESCRIPTION:
UNT 1086 IN HEWA
END DESCRIPTION:
DSS Export Rating Curves= 0
DSS Export Rating Curve Sorted= 0
DSS Export Volume Flow Curves= 0
DXF OffsetX= 0
DXF OffsetY= 0
DXF ScaleX= 1
DXF ScaleY= 10

--- UNT 1086 IN HEWA.p01 (plan) ---

Plan Title=Multiple Run
Short Identifier=Multiple
Geom File=g01
Flow File=f01
Subcritical Flow
K Sum by GR= 0
Std Step Tol= 0.01
Critical Tol= 0.01
Num of Std Step Trials= 20
Max Error Tol= 0.3
Flow Tol Ratio= 0.001
Split Flow NTrial= 30
Split Flow Tol= 0.02
Split Flow Ratio= 0.02
Log Output Level= 0
Friction Slope Method= 1
Unsteady Friction Slope Method= 2
Unsteady Bridges Friction Slope Method= 1
Parabolic Critical Depth
Global Vel Dist=  1 , 1 , 1
Global Log Level= 0
CheckData=True
Encroach Param= -1, 0, 0, 0
BEGIN DESCRIPTION:
Multiple Run
END DESCRIPTION:

--- UNT 1086 IN HEWA.f01 (steady flow) ---

Flow Title=Multiple
Number of Profiles=7
Profile Names=10-year,25-year,50-year,1pct_min,100-year,1pct_plu,500-year
River Rch & RM= UNT 1086 IN HEWA,Reach-1,1915
     396     540     658     587     794    1074    1153
Boundary for River Rch & Prof#=UNT 1086 IN HEWA,Reach-1,1
Up Type=0
Dn Type=3
Dn Slope=0.005
Boundary for River Rch & Prof#=UNT 1086 IN HEWA,Reach-1,2
Up Type=0
Dn Type=3
Dn Slope=0.005
Boundary for River Rch & Prof#=UNT 1086 IN HEWA,Reach-1,3
Up Type=0
Dn Type=3
Dn Slope=0.005
Boundary for River Rch & Prof#=UNT 1086 IN HEWA,Reach-1,4
Up Type=0
Dn Type=3
Dn Slope=0.005
Boundary for River Rch & Prof#=UNT 1086 IN HEWA,Reach-1,5
Up Type=0
Dn Type=3
Dn Slope=0.005
Boundary for River Rch & Prof#=UNT 1086 IN HEWA,Reach-1,6
Up Type=0
Dn Type=3
Dn Slope=0.005
Boundary for River Rch & Prof#=UNT 1086 IN HEWA,Reach-1,7
Up Type=0
Dn Type=3
Dn Slope=0.005

--- UNT 1086 IN HEWA.g01 (geometry) ---

Geom Title=Existing Conditions
Program Version=4.10

River Reach=UNT 1086 IN HEWA,Reach-1
Reach XY= 30
      2695193.47     10014753.73      2695279.77     10014726.88
      2695331.25     10014719.08      2695386.08     10014679.34
      2695419.62     10014666.51      2695538.22     10014644.77
      2695568.88     10014644.64      2695607.14     10014656.79
      2695691.16     10014708.61       2695738.6     10014744.73
      2695811.87      10014816.3      2695839.73     10014831.18
        2695873.     10014832.05      2696019.88     10014776.48
      2696058.67     10014774.89      2696207.48     10014846.12
      2696285.85       10014909.      2696313.96     10014923.19
      2696351.46     10014928.65       2696389.9     10014907.58
      2696489.81     10014866.63      2696530.42     10014863.26
      2696566.32     10014874.92      2696634.92      10014909.6
      2696762.41     10014985.35      2696816.16     10014999.28
      2696847.43     10014997.31      2696978.17     10014932.72
      2697008.77     10014915.63      2697070.62     10014866.15

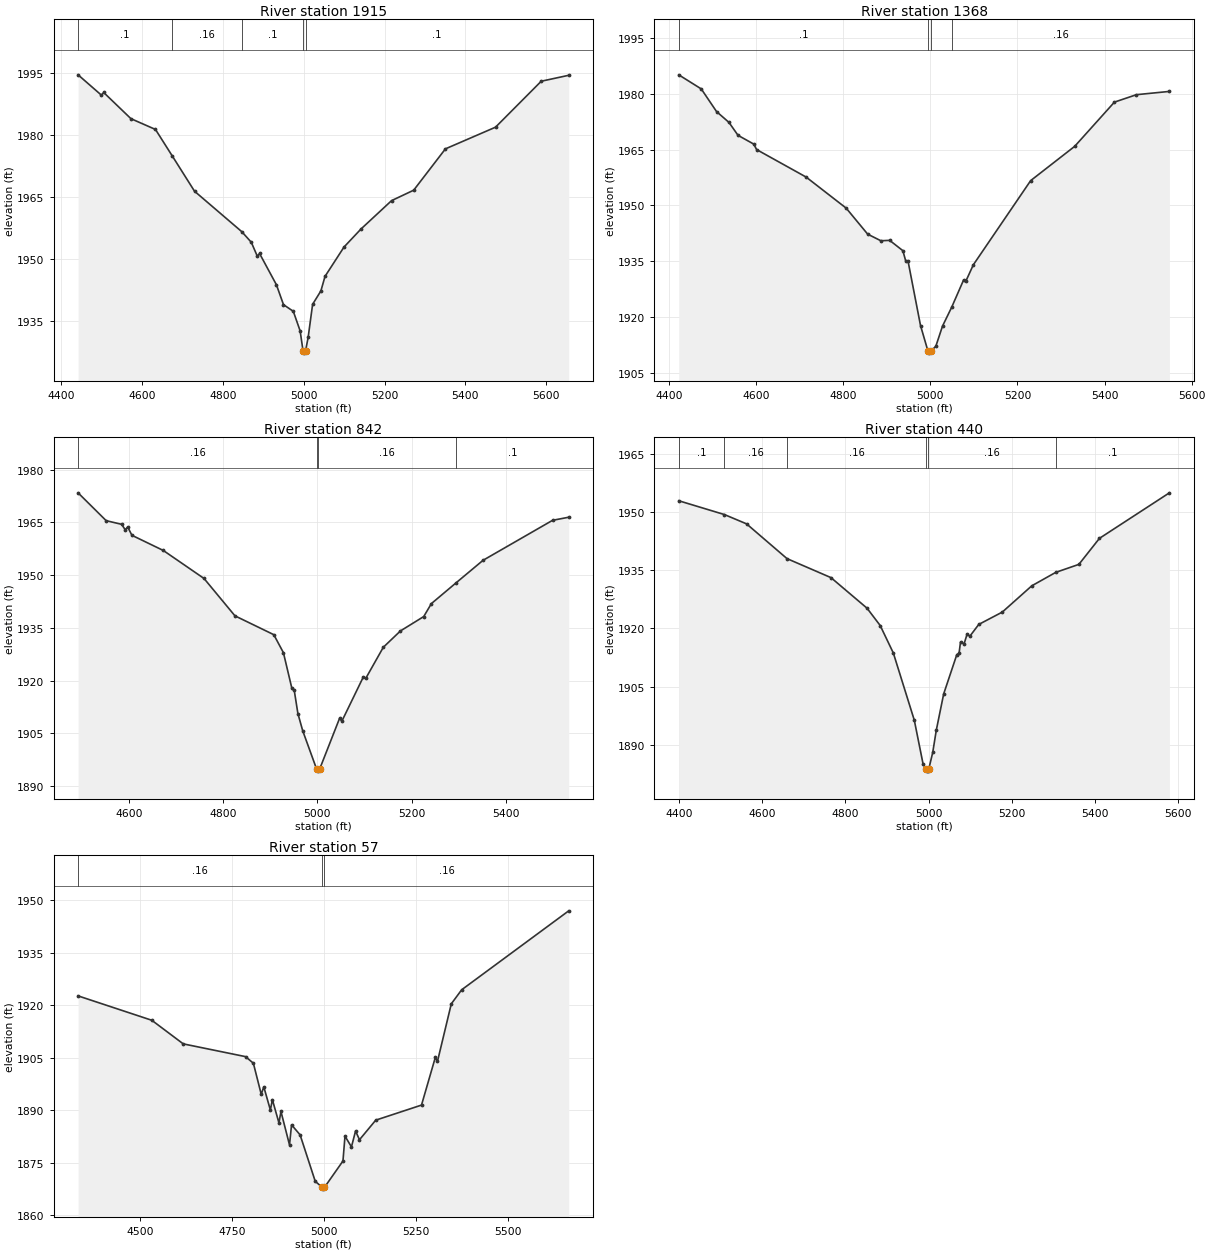
Type RM Length L Ch R = 1 ,1915    ,547,547,547
BEGIN DESCRIPTION:
UNT 1025 IN HEWA 4.6
END DESCRIPTION:
XS GIS Cut Line= 3
      2695205.58      10015205.7      2695396.54     10014816.84
      2695212.79     10014057.57
#Sta/Elev= 30
  4441.5 1994.46  4499.3 1989.54  4504.9 1990.19  4572.3 1983.86  4633.1 1981.25
  4674.4 1974.88  4729.7 1966.32  4846.5 1956.55  4870.2 1953.98  4885.4 1950.54
  4890.6 1951.27  4932.4  1943.7  4949.9 1938.89  4974.2 1937.28  4991.1 1932.55
  4998.4 1927.67  5001.1 1927.17  5004.4 1927.67  5010.9 1930.95    5022 1938.97
  5042.5 1942.22  5052.7 1945.73  5099.7 1952.82  5141.6 1957.17  5217.4 1964.04
  5272.2 1966.57  5350.7 1976.56  5474.7  1981.8  5587.8 1992.91  5655.9 1994.35
#Mann= 5 ,-1 , 0
  4441.5      .1       0  4674.4     .16       0  4846.5      .1       0
  4998.4     .07       0  5004.4      .1       0
Bank Sta=4998.4,5004.4
XS Rating Curve= 0 ,0
Exp/Cntr=0.3,0.1

Type RM Length L Ch R = 1 ,1368    ,526,526,526
BEGIN DESCRIPTION:
Mapping XS 7852e468
END DESCRIPTION:
XS GIS Cut Line= 3
      2695526.18     10015294.14      2695821.31     10014966.03
      2695923.48     10014288.91
#Sta/Elev= 30
  4422.8 1985.08  4474.5 1981.29  4509.6  1975.2    4538  1972.3  4558.9 1968.81
  4594.8 1966.47  4601.6 1964.98  4715.2 1957.59  4807.1 1949.24  4856.4 1942.25
  4886.7 1940.47  4906.9 1940.58  4937.2  1937.8  4943.9 1934.97    4949 1935.04
  4977.7 1917.68  4994.9 1910.76  4997.7 1910.26  5000.9 1910.76  5012.8 1912.09
  5028.2 1917.53  5049.2 1922.59  5076.7 1929.96  5081.8 1929.62    5099 1934.02
  5230.5 1956.64  5331.6 1965.86  5422.7 1977.74  5473.2 1979.74  5548.9 1980.62
#Mann= 4 ,-1 , 0
  4422.8      .1       0  4994.9     .07       0  5000.9      .1       0
  5049.2     .16       0
Bank Sta=4994.9,5000.9
XS Rating Curve= 0 ,0
Exp/Cntr=0.3,0.1

Type RM Length L Ch R = 1 ,842     ,712,712,712
BEGIN DESCRIPTION:
Mapping XS 80100cbd
END DESCRIPTION:
XS GIS Cut Line= 4
       2696142.5     10015398.29      2696281.38     10015082.35
      2696342.14     10014783.74      2696156.36     10014439.97
#Sta/Elev= 30
  4492.4 1973.43    4552 1965.51  4584.8 1964.47  4592.2 1962.95  4597.7  1963.7
  4606.6 1961.35  4673.2 1957.03  4759.5 1949.07  4825.1 1938.44  4907.5 1933.08
  4927.9 1927.96  4945.8 1917.83  4950.9 1917.21  4958.6 1910.65  4968.8 1905.76
  4998.5 1894.77  5001.2 1894.27  5004.5 1894.77  5046.9 1909.26    5052 1908.52
  5097.5 1921.09  5102.6 1920.67  5139.7 1929.49  5176.1 1934.15  5225.5 1938.24
  5241.7 1941.92  5294.7  1947.9  5351.2 1954.23  5498.7 1965.61    5533 1966.49
#Mann= 4 ,-1 , 0
  4492.4     .16       0  4998.5     .07       0  5001.2     .16       0
  5294.7      .1       0
Bank Sta=4998.5,5004.5
XS Rating Curve= 0 ,0
Exp/Cntr=0.3,0.1

Type RM Length L Ch R = 1 ,440     ,383,383,383
BEGIN DESCRIPTION:
Mapping XS 459951d2
END DESCRIPTION:
XS GIS Cut Line= 3
      2696490.85     10015510.64      2696705.69     10014868.29
      2696343.37     10014521.16
#Sta/Elev= 30
  4399.4 1952.88  4509.3 1949.32  4562.4 1946.93  4659.6 1937.98  4765.2 1933.09
  4851.9 1925.22  4883.5 1920.76  4915.1 1913.68  4965.5 1896.37  4986.6 1885.09
  4994.2 1883.77  4996.9 1883.27  4997.4 1883.27  5000.2 1883.77  5009.8  1888.1
  5018.3 1893.79  5036.1 1903.16  5067.7 1913.28    5073 1913.59  5076.5 1916.49
  5085.2 1916.06  5092.1 1918.45  5099.3 1918.05  5120.4 1921.04    5177 1924.22
  5247.8 1930.98  5305.4 1934.44    5361  1936.5  5410.4  1943.2  5578.5 1954.92
#Mann= 6 ,-1 , 0
  4399.4      .1       0  4509.3     .16       0  4659.6     .16       0
  4994.2     .07       0  4997.4     .16       0  5305.4      .1       0
Bank Sta=4994.2,5000.2
XS Rating Curve= 0 ,0
Exp/Cntr=0.3,0.1

Type RM Length L Ch R = 1 ,57      ,0,0,0
BEGIN DESCRIPTION:
UNT 1025 IN HEWA 1.1
END DESCRIPTION:
XS GIS Cut Line= 4
      2696838.08     10015486.77      2697094.15     10015057.09
      2696974.79     10014785.83       2696503.9     10014523.26
#Sta/Elev= 30
  4330.3 1922.69    4531 1915.72  4616.7 1908.97  4786.1 1905.33  4807.5 1903.44
  4828.9 1894.57  4835.9 1896.69  4853.8 1890.07  4859.2 1893.04  4877.1 1886.39
  4882.6 1889.65  4905.9 1880.09  4911.4 1885.84  4934.7 1882.97  4975.9  1869.7
    4995 1867.96  4997.8 1867.46    5001 1867.96  5051.4  1875.5  5056.9  1882.6
  5074.5 1879.53  5085.7 1884.07  5096.4 1881.58  5140.6 1887.17  5265.2 1891.48
  5302.9 1905.13  5308.6 1903.94  5346.3 1920.42  5374.5 1924.43    5666    1947
#Mann= 3 ,-1 , 0
  4330.3     .16       0    4995     .07       0    5001     .16       0
Bank Sta=4995,5001
XS Rating Curve= 0 ,0
Exp/Cntr=0.3,0.1

Chan Stop Cuts=-1
Use User Specified Reach Order=0
Composite Channel Slope=5