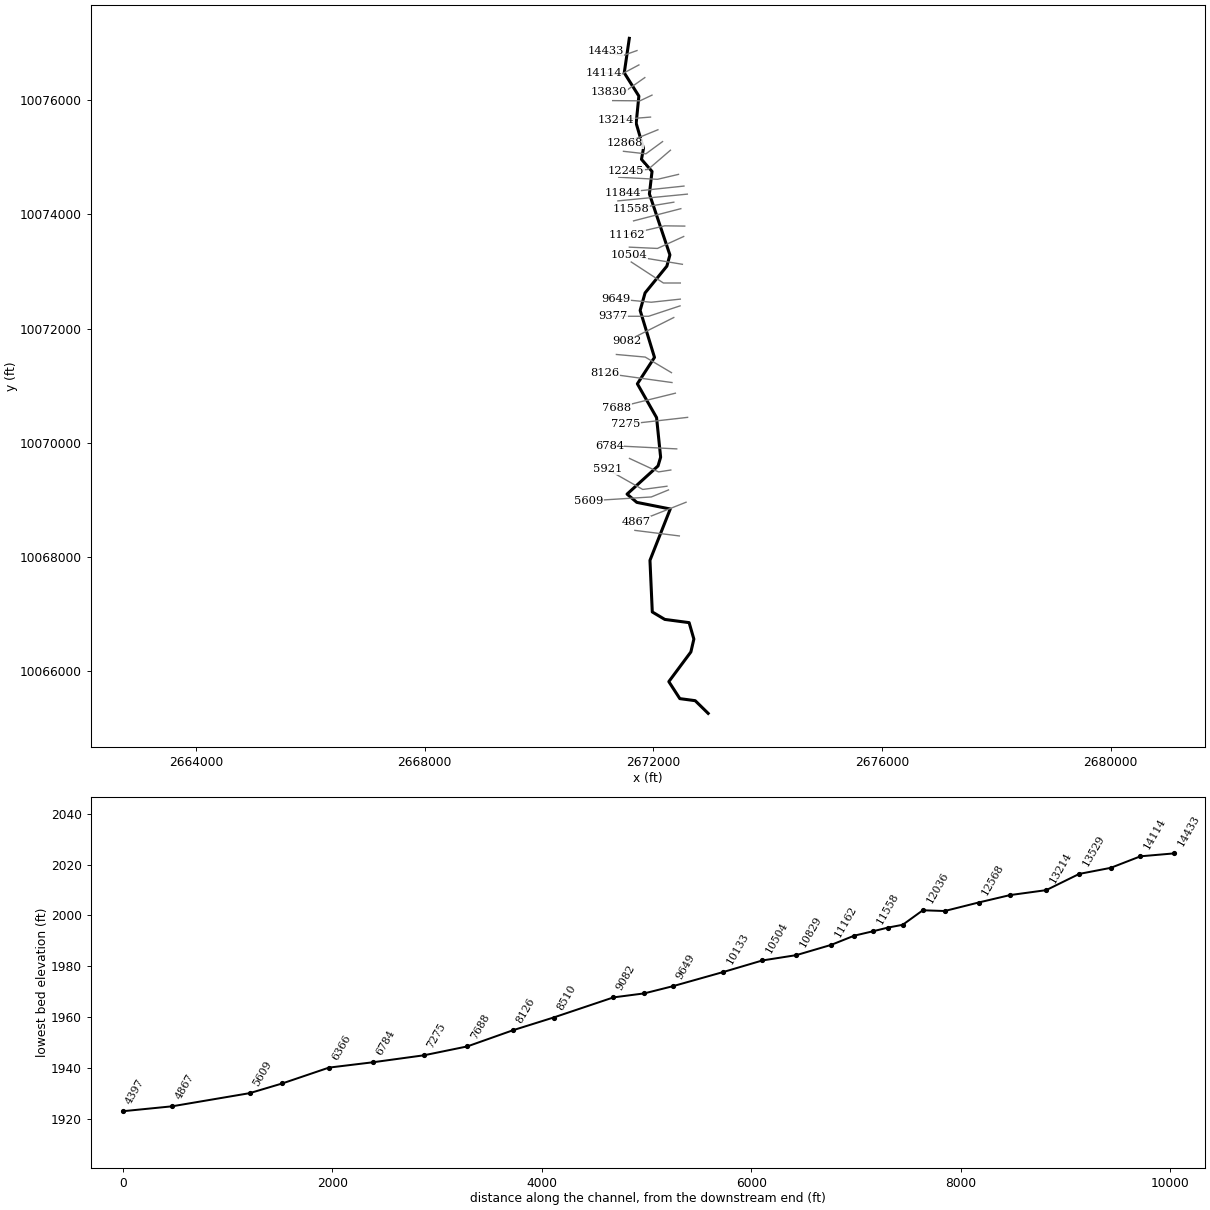
--- WALNUT CREEK 2.prj (project) ---

Proj Title=WALNUT CREEK 2 Base Level Engineering
Current Plan=p01
Default Exp/Contr=0.3,0.1
English Units
Geom File=g01
Flow File=f01
Plan File=p01
Y Axis Title=Elevation
X Axis Title(PF)=Main Channel Distance
X Axis Title(XS)=Station
BEGIN DESCRIPTION:
WALNUT CREEK 2
END DESCRIPTION:
DSS Export Rating Curves= 0
DSS Export Rating Curve Sorted= 0
DSS Export Volume Flow Curves= 0
DXF OffsetX= 0
DXF OffsetY= 0
DXF ScaleX= 1
DXF ScaleY= 10

--- WALNUT CREEK 2.p01 (plan) ---

Plan Title=Multiple Run
Short Identifier=Multiple
Geom File=g01
Flow File=f01
Subcritical Flow
K Sum by GR= 0
Std Step Tol= 0.01
Critical Tol= 0.01
Num of Std Step Trials= 20
Max Error Tol= 0.3
Flow Tol Ratio= 0.001
Split Flow NTrial= 30
Split Flow Tol= 0.02
Split Flow Ratio= 0.02
Log Output Level= 0
Friction Slope Method= 1
Unsteady Friction Slope Method= 2
Unsteady Bridges Friction Slope Method= 1
Parabolic Critical Depth
Global Vel Dist=  1 , 1 , 1
Global Log Level= 0
CheckData=True
Encroach Param= -1, 0, 0, 0
BEGIN DESCRIPTION:
Multiple Run
END DESCRIPTION:

--- WALNUT CREEK 2.f01 (steady flow) ---

Flow Title=Multiple
Number of Profiles=7
Profile Names=10-year,25-year,50-year,1pct_min,100-year,1pct_plu,500-year
River Rch & RM= WALNUT CREEK 2,Reach-1,14433
    1734    2602    3374    3186    4309    5827    7029
River Rch & RM= WALNUT CREEK 2,Reach-1,11702
    2070    3126    4070    3855    5214    7051    8563
River Rch & RM= WALNUT CREEK 2,Reach-1,7275
    2371    3587    4676    4431    5993    8104    9851
Boundary for River Rch & Prof#=WALNUT CREEK 2,Reach-1,1
Up Type=0
Dn Type=3
Dn Slope=0.005
Boundary for River Rch & Prof#=WALNUT CREEK 2,Reach-1,2
Up Type=0
Dn Type=3
Dn Slope=0.005
Boundary for River Rch & Prof#=WALNUT CREEK 2,Reach-1,3
Up Type=0
Dn Type=3
Dn Slope=0.005
Boundary for River Rch & Prof#=WALNUT CREEK 2,Reach-1,4
Up Type=0
Dn Type=3
Dn Slope=0.005
Boundary for River Rch & Prof#=WALNUT CREEK 2,Reach-1,5
Up Type=0
Dn Type=3
Dn Slope=0.005
Boundary for River Rch & Prof#=WALNUT CREEK 2,Reach-1,6
Up Type=0
Dn Type=3
Dn Slope=0.005
Boundary for River Rch & Prof#=WALNUT CREEK 2,Reach-1,7
Up Type=0
Dn Type=3
Dn Slope=0.005

--- WALNUT CREEK 2.g01 (geometry) ---

Geom Title=Existing Conditions
Program Version=4.10

River Reach=WALNUT CREEK 2  ,Reach-1
Reach XY= 30
      2671578.47     10077083.73      2671490.15     10076479.53
      2671745.76     10076072.36       2671698.6     10075597.23
      2671826.38     10075157.94      2671791.74     10074964.78
       2671976.1     10074752.78      2671930.24     10074359.92
      2672288.88     10073291.36      2672235.85     10073094.94
       2671854.5     10072626.12      2671768.35     10072319.36
      2672019.15     10071496.99       2671719.5     10071034.29
      2672055.66     10070442.56      2672126.55     10069749.53
      2672081.34     10069596.44      2671539.24     10069102.95
      2671710.05     10068958.28      2672295.18     10068842.54
      2671939.99     10067943.57      2671980.73     10067039.41
      2672199.55     10066908.97      2672625.26     10066852.58
      2672708.22     10066564.81      2672656.16     10066339.69
      2672269.91     10065819.71      2672462.74     10065521.96
      2672731.57     10065486.15      2672958.47     10065263.73

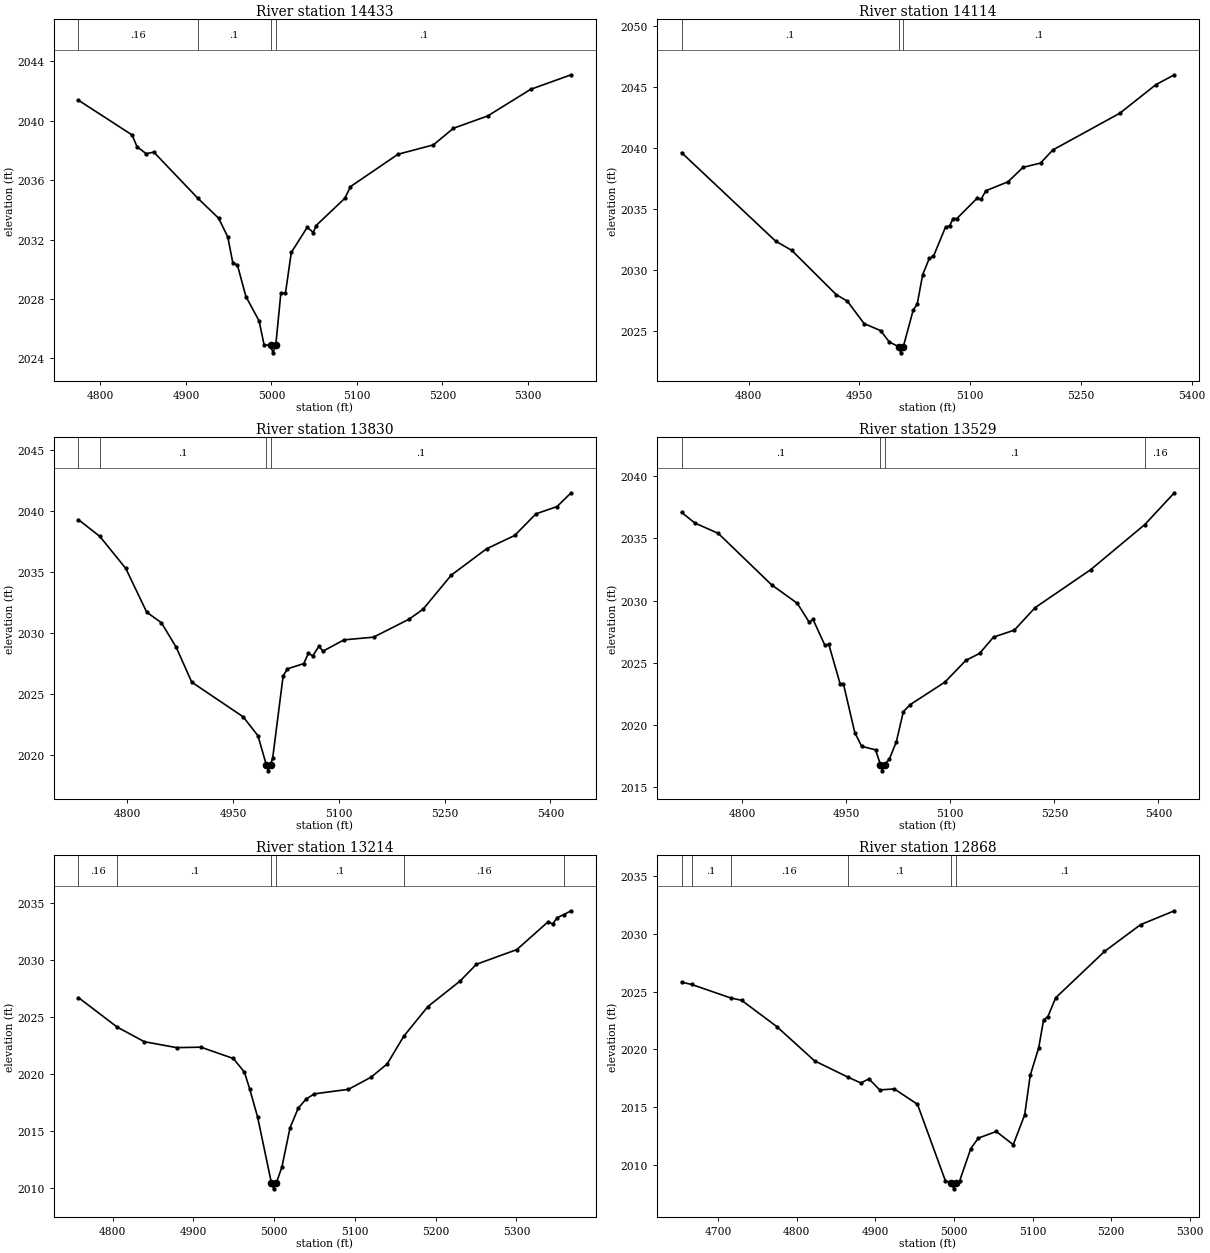
Type RM Length L Ch R = 1 ,14433   ,319,319,319
BEGIN DESCRIPTION:
WALNUT CREEK 2 32.0
END DESCRIPTION:
XS GIS Cut Line= 3
      2671713.05     10076869.69      2671454.21     10076777.25
      2671162.78     10076854.72
#Sta/Elev= 30
  4774.2 2041.38    4837 2039.04  4842.8 2038.25  4853.4 2037.78  4862.5 2037.88
  4913.6  2034.8  4938.3 2033.43    4949 2032.17  4954.9 2030.42  4960.2 2030.29
  4970.2 2028.16  4985.6 2026.52  4991.4 2024.92  4999.1 2024.87  5001.8 2024.37
  5005.1 2024.87  5011.1 2028.41  5016.4 2028.37  5023.3 2031.13  5041.9 2032.82
  5049.1 2032.47  5052.3 2032.94    5086 2034.78  5092.5 2035.56  5148.1 2037.74
  5189.5 2038.37    5213 2039.49  5253.1 2040.32  5303.3 2042.11  5350.6 2043.09
#Mann= 4 ,-1 , 0
  4774.2     .16       0  4913.6      .1       0  4999.1     .07       0
  5005.1      .1       0
Bank Sta=4999.1,5005.1
XS Rating Curve= 0 ,0
Exp/Cntr=0.3,0.1

Type RM Length L Ch R = 1 ,14114   ,284,284,284
BEGIN DESCRIPTION:
Mapping XS bb8305f1
END DESCRIPTION:
XS GIS Cut Line= 3
      2671746.39     10076618.24      2671420.92     10076444.41
       2671125.1     10076481.39
#Sta/Elev= 30
  4709.4 2039.62  4836.6 2032.38  4858.5 2031.62  4918.7    2028  4933.8 2027.46
  4956.5 2025.62  4978.9 2025.05  4990.5 2024.12  5003.5 2023.73  5006.2 2023.23
  5009.5 2023.73  5022.8  2026.7  5028.4 2027.24  5035.8 2029.64  5044.7 2030.96
  5050.4 2031.14  5066.7 2033.53  5072.3 2033.63  5076.9 2034.23  5082.1 2034.23
  5109.6  2035.9  5114.7 2035.79  5121.2  2036.5  5151.4 2037.24  5171.6 2038.42
  5195.3 2038.77  5211.9 2039.84  5302.6 2042.85  5351.5 2045.19  5376.5    2046
#Mann= 3 ,-1 , 0
  4709.4      .1       0  5003.5     .07       0  5009.5      .1       0
Bank Sta=5003.5,5009.5
XS Rating Curve= 0 ,0
Exp/Cntr=0.3,0.1

Type RM Length L Ch R = 1 ,13830   ,301,301,301
BEGIN DESCRIPTION:
WALNUT CREEK 2 31.0
END DESCRIPTION:
XS GIS Cut Line= 3
      2671849.94     10076396.35      2671502.28     10076152.25
      2671228.61     10076148.55
#Sta/Elev= 30
  4730.8 2039.31  4761.2 2037.93    4798  2035.3  4827.7 2031.71  4848.6 2030.84
  4869.5 2028.83  4891.5 2025.97  4964.5 2023.12  4985.4 2021.57  4997.2 2019.19
    5000 2018.69  5003.2 2019.19  5006.3 2019.75  5021.1 2026.49  5027.2 2027.06
  5050.3 2027.49  5056.9 2028.34    5063 2028.12  5071.7  2028.9  5077.8 2028.52
  5107.4 2029.44  5149.2 2029.66  5199.4 2031.13  5219.4 2031.95  5259.4 2034.75
  5309.4 2036.91  5349.4 2038.01  5379.4 2039.78  5409.4 2040.38  5429.3 2041.51
#Mann= 4 ,-1 , 0
  4730.8     .16       0  4761.2      .1       0  4997.2     .07       0
  5003.2      .1       0
Bank Sta=4997.2,5003.2
XS Rating Curve= 0 ,0
Exp/Cntr=0.3,0.1

Type RM Length L Ch R = 1 ,13529   ,315,315,315
BEGIN DESCRIPTION:
WALNUT CREEK 2 30.0
END DESCRIPTION:
XS GIS Cut Line= 3
      2671975.61     10076089.36      2671764.86     10075989.53
      2671287.77     10075993.23
#Sta/Elev= 30
  4712.6 2037.09  4731.6 2036.24  4765.5  2035.4  4842.2 2031.27  4879.3 2029.78
  4896.5 2028.26    4902 2028.49  4919.2 2026.39  4924.8 2026.47    4941 2023.31
  4945.8 2023.31  4962.2 2019.38  4972.2 2018.27  4992.2 2017.99  4999.2  2016.8
  5001.9  2016.3  5005.2  2016.8  5012.2 2017.26  5022.2 2018.65  5032.2 2021.06
  5042.2 2021.63  5092.2 2023.44  5122.2 2025.18  5142.2 2025.75  5162.2 2027.06
  5192.2 2027.62  5222.2 2029.43  5302.2 2032.48  5380.2 2036.11  5422.9 2038.67
#Mann= 4 ,-1 , 0
  4712.6      .1       0  4999.2     .07       0  5005.2      .1       0
  5380.2     .16       0
Bank Sta=4999.2,5005.2
XS Rating Curve= 0 ,0
Exp/Cntr=0.3,0.1

Type RM Length L Ch R = 1 ,13214   ,346,346,346
BEGIN DESCRIPTION:
Mapping XS cbf9a7ab
END DESCRIPTION:
XS GIS Cut Line= 2
       2671949.8     10075704.77      2671341.49     10075656.84
#Sta/Elev= 30
  4757.5 2026.68  4805.6 2024.09  4839.2 2022.81  4879.2 2022.29  4909.3 2022.33
  4949.4 2021.34  4963.1 2020.15  4969.5 2018.71  4979.5  2016.2  4996.6 2010.42
  4999.3 2009.92  5002.6 2010.42  5009.6 2011.84  5019.6 2015.26  5029.7 2016.98
  5039.7  2017.8  5049.7 2018.24    5092 2018.64    5120  2019.7    5140 2020.87
  5160.5 2023.29  5190.2 2025.88  5230.3 2028.13  5250.4 2029.59  5300.5 2030.88
  5339.6 2033.34  5344.7 2033.11  5350.7 2033.69  5358.8 2033.95  5367.7 2034.28
#Mann= 6 ,-1 , 0
  4757.5     .16       0  4805.6      .1       0  4996.6     .07       0
  5002.6      .1       0  5160.5     .16       0  5358.8      .1       0
Bank Sta=4996.6,5002.6
XS Rating Curve= 0 ,0
Exp/Cntr=0.3,0.1

Type RM Length L Ch R = 1 ,12868   ,300,300,300
BEGIN DESCRIPTION:
WALNUT CREEK 2 29.0
END DESCRIPTION:
XS GIS Cut Line= 2
      2672079.24     10075482.89      2671498.63     10075246.21
#Sta/Elev= 30
  4653.5 2025.81  4666.3 2025.61  4715.8 2024.45  4729.9 2024.24  4774.5 2021.98
  4822.6 2019.02  4864.9 2017.62  4881.5 2017.11  4891.9 2017.46  4905.5 2016.51
  4924.2 2016.59  4953.6 2015.27  4989.1 2008.67  4996.9 2008.47  4999.7 2007.97
  5002.9 2008.47  5007.1 2008.62  5021.5 2011.45  5031.1 2012.35  5053.9 2012.92
  5075.5 2011.78    5090 2014.35  5097.1 2017.77  5107.9 2020.15  5114.1 2022.56
  5119.5 2022.83  5129.5 2024.46  5191.6 2028.46  5237.5 2030.77  5280.5 2031.97
#Mann= 6 ,-1 , 0
  4653.5     .16       0  4666.3      .1       0  4715.8     .16       0
  4864.9      .1       0  4996.9     .07       0  5002.9      .1       0
Bank Sta=4996.9,5002.9
XS Rating Curve= 0 ,0
Exp/Cntr=0.3,0.1

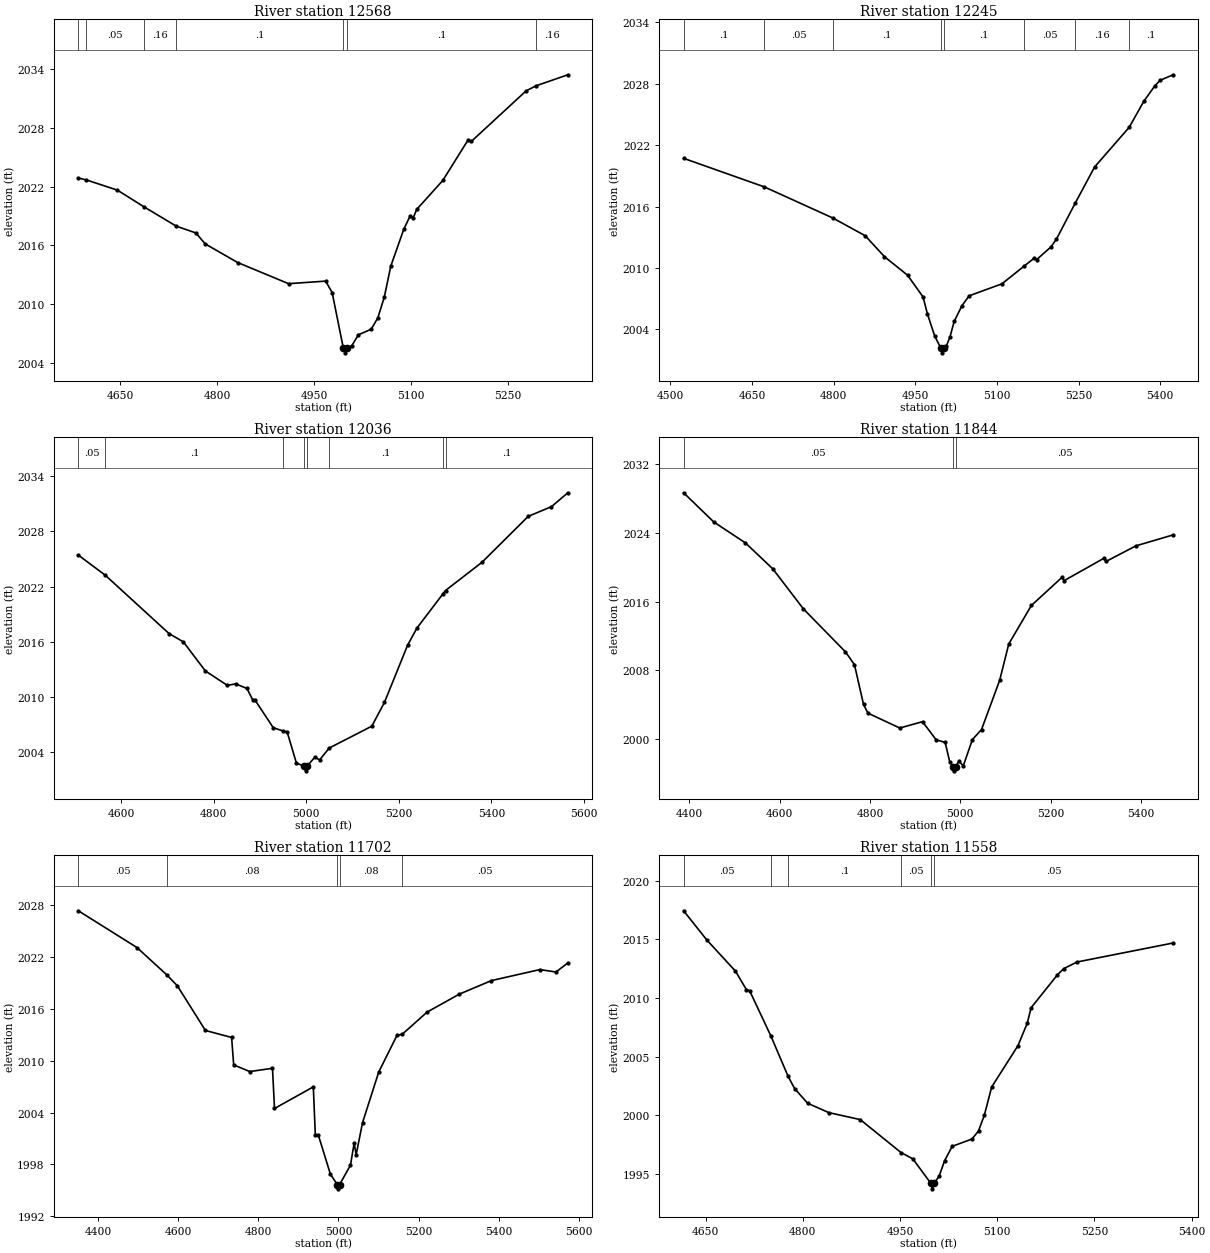
Type RM Length L Ch R = 1 ,12568   ,323,323,323
BEGIN DESCRIPTION:
WALNUT CREEK 2 28.0
END DESCRIPTION:
XS GIS Cut Line= 3
      2672160.54     10075275.76      2671868.41     10075061.28
      2671476.42     10075105.66
#Sta/Elev= 30
  4585.3 2022.87  4597.9 2022.67  4645.8 2021.63  4686.6 2019.94  4736.8 2017.96
    4767 2017.27  4781.6 2016.15  4831.8 2014.25  4910.4  2012.1  4967.8 2012.36
  4977.8 2011.19    4995 2005.55  4997.7 2005.05    5001 2005.55    5008 2005.77
  5018.5 2006.89  5038.2 2007.46  5048.3  2008.6  5058.4 2010.72  5068.4 2013.88
  5088.5 2017.64  5098.2 2018.98  5103.2 2018.83  5108.7 2019.68  5148.9 2022.62
  5187.9 2026.74    5193  2026.6  5277.7 2031.75  5292.8 2032.26  5342.2 2033.39
#Mann= 7 ,-1 , 0
  4585.3      .1       0  4597.9     .05       0  4686.6     .16       0
  4736.8      .1       0    4995     .07       0    5001      .1       0
  5292.8     .16       0
Bank Sta=4995,5001
XS Rating Curve= 0 ,0
Exp/Cntr=0.3,0.1

Type RM Length L Ch R = 1 ,12245   ,209,209,209
BEGIN DESCRIPTION:
Mapping XS 261cbdfa
END DESCRIPTION:
XS GIS Cut Line= 3
      2672298.22     10075124.83      2671906.86     10074788.09
      2671524.63     10074760.79
#Sta/Elev= 30
  4524.2 2020.71  4672.5 2017.92    4798 2014.89  4857.9 2013.15  4893.3  2011.1
  4935.8 2009.29  4964.3 2007.16    4972 2005.55  4985.6 2003.35  4996.5 2002.21
  4999.2 2001.71  5002.5 2002.21  5007.1 2002.39  5013.7 2003.27  5021.4 2004.78
  5035.6 2006.31  5048.9 2007.28  5109.1 2008.45  5149.2 2010.15    5168 2010.94
    5173 2010.82  5199.3 2012.06  5209.3 2012.82  5244.3 2016.38  5279.5 2019.87
  5342.9 2023.73  5369.7 2026.26  5389.8 2027.77  5399.8 2028.33  5423.7 2028.87
#Mann= 8 ,-1 , 0
  4524.2      .1       0  4672.5     .05       0    4798      .1       0
  4996.5     .07       0  5002.5      .1       0  5149.2     .05       0
  5244.3     .16       0  5342.9      .1       0
Bank Sta=4996.5,5002.5
XS Rating Curve= 0 ,0
Exp/Cntr=0.3,0.1

Type RM Length L Ch R = 1 ,12036   ,192,192,192
BEGIN DESCRIPTION:
WALNUT CREEK 2 27.0
END DESCRIPTION:
XS GIS Cut Line= 3
       2672439.3     10074701.64      2672070.68     10074615.17
      2671393.08     10074651.55
#Sta/Elev= 30
  4507.9 2025.42  4566.1 2023.24  4703.9  2016.9  4734.6 2016.01  4782.2 2012.85
  4829.7 2011.28  4847.7 2011.44  4872.2 2010.94  4885.1 2009.64  4890.1 2009.64
  4928.8 2006.69  4950.9 2006.31  4958.8 2006.24  4978.9 2002.84  4995.9  2002.5
  4998.7    2002  5001.9  2002.5  5018.9  2003.5  5028.9 2003.18  5049.9 2004.48
  5141.8 2006.85  5169.1 2009.44  5219.2 2015.66  5239.2  2017.5  5294.5 2021.16
  5300.9 2021.58  5379.4 2024.63  5479.6 2029.63  5529.7 2030.68  5565.1 2032.19
#Mann= 8 ,-1 , 0
  4507.9     .05       0  4566.1      .1       0  4950.9     .05       0
  4995.9    .035       0  5001.9     .05       0  5049.9      .1       0
  5294.5     .05       0  5300.9      .1       0
Bank Sta=4995.9,5001.9
XS Rating Curve= 0 ,0
Exp/Cntr=0.3,0.1

Type RM Length L Ch R = 1 ,11844   ,142,142,142
BEGIN DESCRIPTION:
Mapping XS 25a18b9c
END DESCRIPTION:
XS GIS Cut Line= 2
      2672534.85     10074496.86      2671456.33     10074383.09
#Sta/Elev= 30
    4387  2028.7  4453.8  2025.3  4524.1 2022.85  4584.5 2019.84  4652.5 2015.16
  4745.4 2010.17  4765.5 2008.67  4785.6 2004.03  4795.6 2003.01    4866 2001.28
  4916.3 2002.02  4946.5 1999.91  4966.6  1999.6  4976.6 1997.33  4983.7 1996.79
  4986.4 1996.29  4989.7 1996.79  4996.7 1997.38  5006.8  1996.9  5026.9 1999.94
    5047  2001.1  5087.2 2006.83  5107.4 2011.08  5157.6 2015.57  5225.1 2018.83
  5230.1 2018.46    5318 2021.06    5323  2020.7  5388.9 2022.51  5471.5 2023.79
#Mann= 3 ,-1 , 0
    4387     .05       0  4983.7     .04       0  4989.7     .05       0
Bank Sta=4983.7,4989.7
XS Rating Curve= 0 ,0
Exp/Cntr=0.3,0.1

Type RM Length L Ch R = 1 ,11702   ,144,144,144
BEGIN DESCRIPTION:
Mapping XS e5dc60a0
END DESCRIPTION:
XS GIS Cut Line= 2
      2672593.96     10074355.79      2671379.01     10074237.48
#Sta/Elev= 30
  4351.3 2027.33  4497.5 2023.08  4571.2 2019.95    4598 2018.67  4668.3 2013.49
  4733.6 2012.68  4738.7 2009.51  4778.8 2008.74  4835.5 2009.12  4840.5 2004.47
  4937.3 2006.97  4942.3 2001.44  4949.6 2001.43  4979.8 1996.89  4996.9 1995.68
  4999.6 1995.18  5002.9 1995.68    5030 1997.92  5039.1 2000.46  5044.1 1999.13
  5060.1 2002.84  5100.3 2008.67    5146 2012.93    5159 2013.05  5220.9 2015.61
  5301.3 2017.69  5381.6 2019.26  5502.2 2020.53  5542.4 2020.25    5572  2021.3
#Mann= 5 ,-1 , 0
  4351.3     .05       0  4571.2     .08       0  4996.9     .07       0
  5002.9     .08       0    5159     .05       0
Bank Sta=4996.9,5002.9
XS Rating Curve= 0 ,0
Exp/Cntr=0.3,0.1

Type RM Length L Ch R = 1 ,11558   ,177,177,177
BEGIN DESCRIPTION:
WALNUT CREEK 2 26.0
END DESCRIPTION:
XS GIS Cut Line= 2
      2672357.37     10074214.73       2671612.3     10074092.07
#Sta/Elev= 30
  4616.2 2017.45  4651.8 2014.97  4696.2  2012.3    4713 2010.73  4718.1 2010.62
  4750.8 2006.77  4777.4 2003.32  4787.4 2002.28  4807.6 2001.02  4840.5 2000.22
  4888.7 1999.63  4951.5 1996.82  4969.8 1996.28  4997.2 1994.22    5000 1993.72
  5003.2 1994.22  5010.3  1994.8  5018.9 1996.13  5030.6 1997.35    5061 1997.97
  5071.1 1998.66  5080.1    2000  5091.4 2002.41    5132 2005.94  5146.4 2007.87
  5152.2 2009.17  5192.8 2011.98  5202.5 2012.51  5223.2 2013.08  5371.3  2014.7
#Mann= 6 ,-1 , 0
  4616.2     .05       0  4750.8     .08       0  4777.4      .1       0
  4951.5     .05       0  4997.2     .04       0  5003.2     .05       0
Bank Sta=4997.2,5003.2
XS Rating Curve= 0 ,0
Exp/Cntr=0.3,0.1

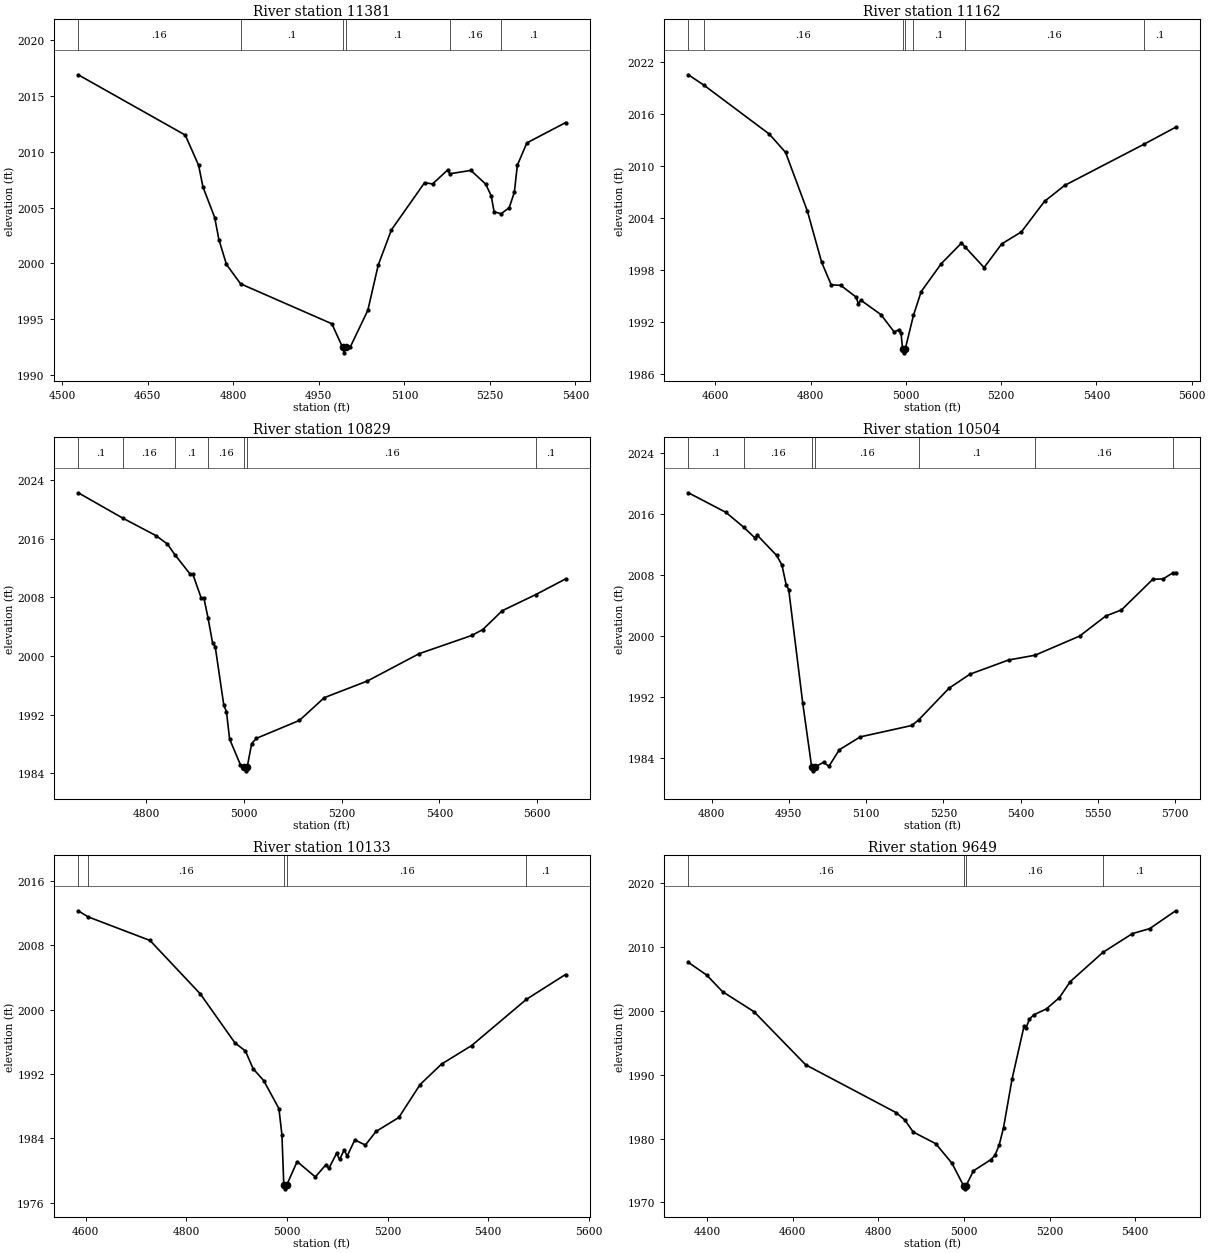
Type RM Length L Ch R = 1 ,11381   ,219,219,219
BEGIN DESCRIPTION:
Mapping XS c9e0113b
END DESCRIPTION:
XS GIS Cut Line= 2
      2672480.23     10074100.97      2671652.78     10073887.29
#Sta/Elev= 30
    4528 2016.87  4715.7 2011.48  4739.2 2008.77  4746.7 2006.85  4767.4  2004.1
  4774.7 2002.14    4788 1999.91  4812.8 1998.18  4972.8 1994.61  4991.6 1992.51
  4994.3 1992.01  4997.6 1992.51  5004.9 1992.51  5035.9 1995.81  5054.1 1999.85
  5077.2    2003  5135.4 2007.22  5149.5 2007.11  5176.1 2008.37  5179.5 2008.02
  5216.7 2008.32  5242.5  2007.1  5252.2 2006.06  5257.4 2004.62  5269.7 2004.45
  5283.8 2004.98  5292.9 2006.37  5298.1 2008.78  5314.8 2010.78  5382.6 2012.59
#Mann= 6 ,-1 , 0
    4528     .16       0  4812.8      .1       0  4991.6     .07       0
  4997.6      .1       0  5179.5     .16       0  5269.7      .1       0
Bank Sta=4991.6,4997.6
XS Rating Curve= 0 ,0
Exp/Cntr=0.3,0.1

Type RM Length L Ch R = 1 ,11162   ,333,333,333
BEGIN DESCRIPTION:
WALNUT CREEK 2 25.0
END DESCRIPTION:
XS GIS Cut Line= 3
      2672548.47     10073796.09      2672198.09     10073800.64
      2671543.11     10073645.99
#Sta/Elev= 30
    4543 2020.52  4575.2 2019.34    4713 2013.67  4747.2 2011.55    4793 2004.77
    4823 1998.85    4843 1996.26    4863  1996.2  4895.8 1994.82  4899.9 1994.04
  4905.1 1994.49  4947.4 1992.82  4975.2 1990.82  4984.6 1991.05  4989.7 1990.66
  4992.8  1988.9  4995.5  1988.4  4998.8  1988.9  5015.7 1992.73    5032 1995.48
  5074.3 1998.71  5116.6 2001.08  5123.8 2000.66  5164.1 1998.25  5201.2 2000.99
  5242.4 2002.37    5291  2005.9  5333.3 2007.74  5498.9 2012.47  5566.4 2014.46
#Mann= 7 ,-1 , 0
    4543      .1       0  4575.2     .16       0  4992.8     .07       0
  4998.8     .16       0  5015.7      .1       0  5123.8     .16       0
  5498.9      .1       0
Bank Sta=4992.8,4998.8
XS Rating Curve= 0 ,0
Exp/Cntr=0.3,0.1

Type RM Length L Ch R = 1 ,10829   ,325,325,325
BEGIN DESCRIPTION:
WALNUT CREEK 2 24.0
END DESCRIPTION:
XS GIS Cut Line= 3
      2672530.32     10073614.09      2672070.68     10073404.75
      2671579.27      10073427.5
#Sta/Elev= 30
  4661.2 2022.24  4752.8 2018.77  4820.7 2016.39  4843.8 2015.25  4859.2 2013.78
  4889.9 2011.19  4895.4  2011.2  4912.9 2007.89  4918.4 2007.87  4926.7 2005.23
    4936 2001.81  4941.5 2001.28    4959 1993.34  4964.5 1992.41  4970.9  1988.7
  4993.1 1985.18  5000.9 1984.86  5003.6 1984.36  5006.9 1984.86  5016.1 1988.08
  5025.9 1988.79  5113.8 1991.23  5164.7 1994.33  5252.9  1996.6  5358.7 2000.32
  5466.2  2002.8  5488.8  2003.6  5528.9 2006.18  5597.6 2008.38  5658.2  2010.5
#Mann= 7 ,-1 , 0
  4661.2      .1       0  4752.8     .16       0  4859.2      .1       0
  4926.7     .16       0  5000.9     .07       0  5006.9     .16       0
  5597.6      .1       0
Bank Sta=5000.9,5006.9
XS Rating Curve= 0 ,0
Exp/Cntr=0.3,0.1

Type RM Length L Ch R = 1 ,10504   ,371,371,371
BEGIN DESCRIPTION:
WALNUT CREEK 2 23.0
END DESCRIPTION:
XS GIS Cut Line= 2
      2672507.51     10073127.18      2671574.65     10073281.89
#Sta/Elev= 30
    4755  2018.8  4827.8 2016.23  4862.3 2014.28  4883.7  2012.9  4888.8 2013.22
  4926.4 2010.56  4936.5 2009.33  4944.7 2006.74  4949.8 2006.05    4977 1991.14
  4994.3 1982.76  4997.1 1982.26  5000.3 1982.76  5017.6 1983.39  5027.7 1982.85
    5048 1985.03  5088.5 1986.72  5188.6 1988.22  5201.7 1988.94  5260.9 1993.12
  5301.4 1994.96  5376.6 1996.83  5427.6 1997.45  5514.3 1999.97    5565 2002.61
  5595.4  2003.4  5656.2 2007.43  5676.3 2007.48  5694.5 2008.25  5700.6 2008.31
#Mann= 7 ,-1 , 0
    4755      .1       0  4862.3     .16       0  4994.3     .07       0
  5000.3     .16       0  5201.7      .1       0  5427.6     .16       0
  5694.5      .1       0
Bank Sta=4994.3,5000.3
XS Rating Curve= 0 ,0
Exp/Cntr=0.3,0.1

Type RM Length L Ch R = 1 ,10133   ,484,484,484
BEGIN DESCRIPTION:
WALNUT CREEK 2 22.0
END DESCRIPTION:
XS GIS Cut Line= 3
      2672471.11     10072799.54      2672175.34     10072799.54
      2671612.29     10073167.34
#Sta/Elev= 30
  4585.3  2012.3  4604.7 2011.55  4727.9 2008.61  4827.9 2001.97  4896.6 1995.89
  4917.6 1994.87  4932.8 1992.67  4953.8  1991.2  4984.1 1987.72  4990.1 1984.45
  4993.8 1978.24  4996.5 1977.74  4999.8 1978.24  5020.3 1981.13  5056.5 1979.22
  5077.6 1980.75  5083.5 1980.31  5098.7 1982.15  5104.6  1981.4  5113.8 1982.56
  5119.7 1981.81  5134.9 1983.82  5155.9 1983.18    5177 1984.87  5222.4 1986.61
  5264.6  1990.7  5307.3 1993.25  5367.1 1995.55    5476  2001.3  5553.6 2004.38
#Mann= 5 ,-1 , 0
  4585.3      .1       0  4604.7     .16       0  4993.8     .07       0
  4999.8     .16       0    5476      .1       0
Bank Sta=4993.8,4999.8
XS Rating Curve= 0 ,0
Exp/Cntr=0.3,0.1

Type RM Length L Ch R = 1 ,9649    ,272,272,272
BEGIN DESCRIPTION:
Mapping XS c245177f
END DESCRIPTION:
XS GIS Cut Line= 3
       2672471.1     10072517.41      2671961.47     10072462.81
      2671338.02     10072521.97
#Sta/Elev= 30
    4356 2007.62  4398.9 2005.63  4435.8 2003.04  4509.5 1999.89  4630.2 1991.57
  4841.4 1984.08  4861.5 1982.95  4881.6 1981.03  4934.1 1979.21    4972 1976.15
  4999.1 1972.63  5001.9 1972.13  5005.1 1972.63  5022.2 1974.95  5062.4 1976.68
  5072.5 1977.37  5082.5 1979.02  5092.6 1981.74  5112.6 1989.37  5140.4  1997.6
  5145.4 1997.38  5152.8 1998.69  5162.9 1999.39    5193 2000.34  5223.1  2002.1
  5248.5 2004.61    5325  2009.2  5393.9 2012.14  5434.1 2012.91  5494.8 2015.71
#Mann= 4 ,-1 , 0
    4356     .16       0  4999.1     .07       0  5005.1     .16       0
    5325      .1       0
Bank Sta=4999.1,5005.1
XS Rating Curve= 0 ,0
Exp/Cntr=0.3,0.1

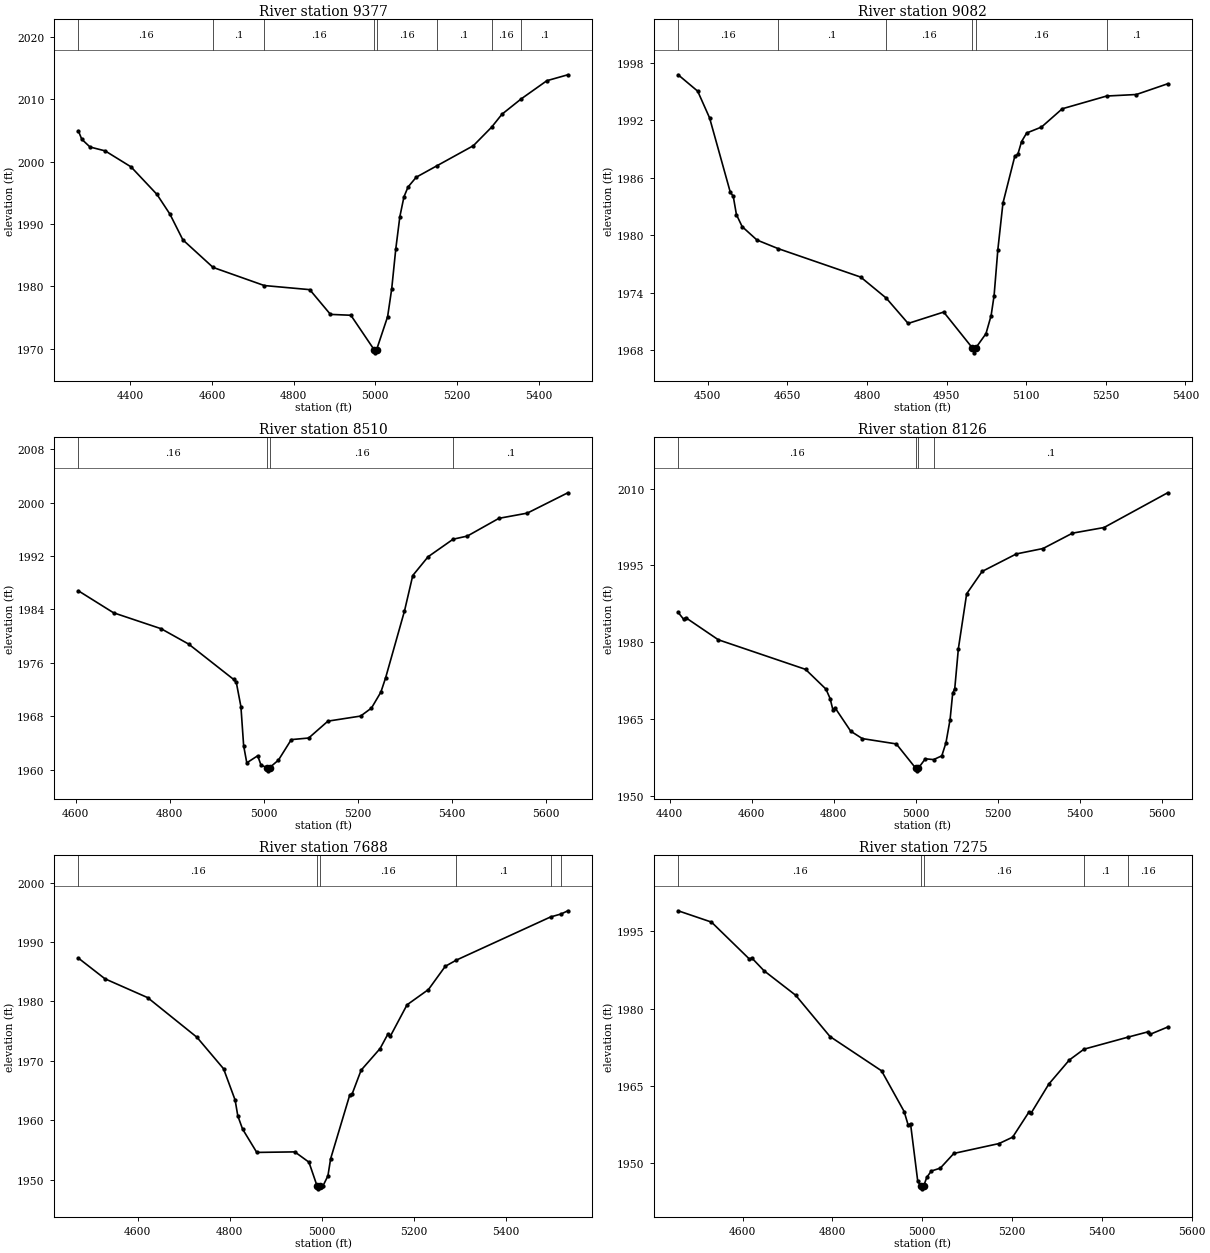
Type RM Length L Ch R = 1 ,9377    ,295,295,295
BEGIN DESCRIPTION:
WALNUT CREEK 2 21.0
END DESCRIPTION:
XS GIS Cut Line= 3
      2672466.53     10072399.09      2671915.97     10072217.08
      2671297.13     10072217.08
#Sta/Elev= 30
  4272.8 2004.93  4281.3 2003.58  4301.4 2002.34  4338.4 2001.72  4401.9 1999.15
  4465.4 1994.73  4497.1 1991.57  4528.8 1987.44  4602.7 1983.02  4728.1 1980.11
  4839.5 1979.45  4890.2 1975.48  4940.2 1975.34  4997.2 1969.81  4999.9 1969.31
  5003.2 1969.81  5030.2 1975.12  5040.2 1979.57  5050.2 1985.99  5060.2 1991.18
  5070.2 1994.34  5080.2 1995.92  5100.2 1997.49  5150.2  1999.3  5240.2 2002.55
  5284.8 2005.52  5310.2  2007.6  5357.3 2010.06  5420.2 2012.98  5471.5 2013.93
#Mann= 8 ,-1 , 0
  4272.8     .16       0  4602.7      .1       0  4728.1     .16       0
  4997.2     .07       0  5003.2     .16       0  5150.2      .1       0
  5284.8     .16       0  5357.3      .1       0
Bank Sta=4997.2,5003.2
XS Rating Curve= 0 ,0
Exp/Cntr=0.3,0.1

Type RM Length L Ch R = 1 ,9082    ,572,572,572
BEGIN DESCRIPTION:
WALNUT CREEK 2 20.0
END DESCRIPTION:
XS GIS Cut Line= 2
      2672356.56     10072195.17      2671532.64     10071781.37
#Sta/Elev= 30
  4444.5 1996.77  4481.3 1995.06  4503.7 1992.27  4542.7 1984.51  4548.3 1984.08
  4554.3 1982.16  4565.1 1980.91    4593 1979.51  4633.1 1978.61  4788.4 1975.64
  4836.4 1973.45  4877.7  1970.8  4944.7 1971.99  4998.9 1968.23  5001.6 1967.73
  5004.9 1968.23  5024.3 1969.73    5034 1971.62  5039.6  1973.7  5046.7 1978.51
  5056.3 1983.37  5078.7 1988.28  5084.3 1988.46  5091.4  1989.8    5101 1990.69
  5128.9 1991.31    5168 1993.22  5251.6 1994.55  5307.6 1994.71  5366.5 1995.83
#Mann= 6 ,-1 , 0
  4444.5     .16       0  4633.1      .1       0  4836.4     .16       0
  4998.9     .07       0  5004.9     .16       0  5251.6      .1       0
Bank Sta=4998.9,5004.9
XS Rating Curve= 0 ,0
Exp/Cntr=0.3,0.1

Type RM Length L Ch R = 1 ,8510    ,384,384,384
BEGIN DESCRIPTION:
WALNUT CREEK 2 19.0
END DESCRIPTION:
XS GIS Cut Line= 3
      2672316.39     10071229.65      2671856.81     10071502.66
      2671352.61     10071548.09
#Sta/Elev= 30
  4605.5  1986.8  4680.4  1983.5  4781.6 1981.11  4840.1 1978.81  4935.6 1973.52
  4941.4 1973.07  4951.2 1969.44    4957 1963.58  4963.7 1961.01  4986.9 1962.07
    4994 1960.65  5006.6 1960.31  5009.4 1959.81  5012.6 1960.31    5031 1961.42
  5058.3 1964.49  5095.3 1964.73  5136.2 1967.26  5205.7 1968.02  5228.8 1969.22
  5248.8 1971.61  5258.9 1973.76    5299 1983.77  5316.6 1989.09  5349.2  1991.9
  5402.4 1994.53  5432.6    1995  5499.8 1997.66  5560.1 1998.44  5646.3 2001.49
#Mann= 4 ,-1 , 0
  4605.5     .16       0  5006.6     .07       0  5012.6     .16       0
  5402.4      .1       0
Bank Sta=5006.6,5012.6
XS Rating Curve= 0 ,0
Exp/Cntr=0.3,0.1

Type RM Length L Ch R = 1 ,8126    ,438,438,438
BEGIN DESCRIPTION:
WALNUT CREEK 2 18.0
END DESCRIPTION:
XS GIS Cut Line= 2
      2672325.52     10071056.72       2671142.9     10071220.47
#Sta/Elev= 30
  4420.9 1985.81  4434.3 1984.46  4439.4 1984.78  4518.9 1980.46  4731.6 1974.68
  4781.4 1970.82  4791.5 1968.98  4798.3 1966.79  4803.4 1967.19  4841.9 1962.59
  4870.1 1961.15    4953 1960.11  5000.5 1955.35  5003.2 1954.85  5006.5 1955.35
  5023.8  1957.2    5044 1957.05    5064 1957.78  5074.1 1960.33  5084.2 1964.88
  5090.5 1969.99  5095.6 1970.93  5104.4 1978.73  5124.6 1989.44  5162.3 1993.81
  5245.7 1997.23  5310.9 1998.29  5382.7 2001.29  5459.6 2002.39  5614.8 2009.18
#Mann= 4 ,-1 , 0
  4420.9     .16       0  5000.5     .07       0  5006.5     .16       0
    5044      .1       0
Bank Sta=5000.5,5006.5
XS Rating Curve= 0 ,0
Exp/Cntr=0.3,0.1

Type RM Length L Ch R = 1 ,7688    ,413,413,413
BEGIN DESCRIPTION:
WALNUT CREEK 2 17.0
END DESCRIPTION:
XS GIS Cut Line= 2
      2672384.67     10070870.15      2671352.61     10070615.55
#Sta/Elev= 30
  4471.1  1987.3    4529 1983.81  4621.7 1980.64  4728.7 1973.97  4786.5 1968.67
  4811.6  1963.4  4817.4 1960.75  4827.7 1958.53  4858.6 1954.59  4941.2 1954.68
  4971.9 1952.95  4989.5 1948.96  4992.2 1948.46  4995.5 1948.96  5002.8 1949.02
  5013.1 1950.64    5019 1953.52  5060.5 1964.25  5065.6 1964.41  5085.2 1968.43
  5126.4 1972.07  5143.4 1974.51  5148.6 1974.14  5184.9 1979.43  5231.5 1982.01
  5267.9 1985.91  5292.1 1986.96  5496.6 1994.22  5519.9 1994.73  5534.1 1995.26
#Mann= 6 ,-1 , 0
  4471.1     .16       0  4989.5     .07       0  4995.5     .16       0
  5292.1      .1       0  5496.6     .16       0  5519.9      .1       0
Bank Sta=4989.5,4995.5
XS Rating Curve= 0 ,0
Exp/Cntr=0.3,0.1

Type RM Length L Ch R = 1 ,7275    ,491,491,491
BEGIN DESCRIPTION:
WALNUT CREEK 2 16.0
END DESCRIPTION:
XS GIS Cut Line= 2
      2672598.49     10070446.95      2671515.53      10070324.1
#Sta/Elev= 30
  4456.6 1998.99  4530.8 1996.79  4615.4  1989.6  4620.5 1989.84  4647.8 1987.34
  4718.3 1982.58  4794.7 1974.56  4909.5  1967.9  4959.8 1959.99    4969 1957.29
    4974 1957.65    4990 1946.51  4997.1 1945.47  4999.8 1944.97  5003.1 1945.47
  5010.1 1947.18  5020.2 1948.43  5040.3 1948.99  5070.5 1951.85  5171.2 1953.77
  5201.4 1955.01  5237.9 1959.92    5243 1959.75  5281.9 1965.32  5327.6    1970
  5360.2  1972.1    5459 1974.46  5501.8 1975.45  5506.9 1974.97  5546.5  1976.4
#Mann= 5 ,-1 , 0
  4456.6     .16       0  4997.1     .07       0  5003.1     .16       0
  5360.2      .1       0    5459     .16       0
Bank Sta=4997.1,5003.1
XS Rating Curve= 0 ,0
Exp/Cntr=0.3,0.1

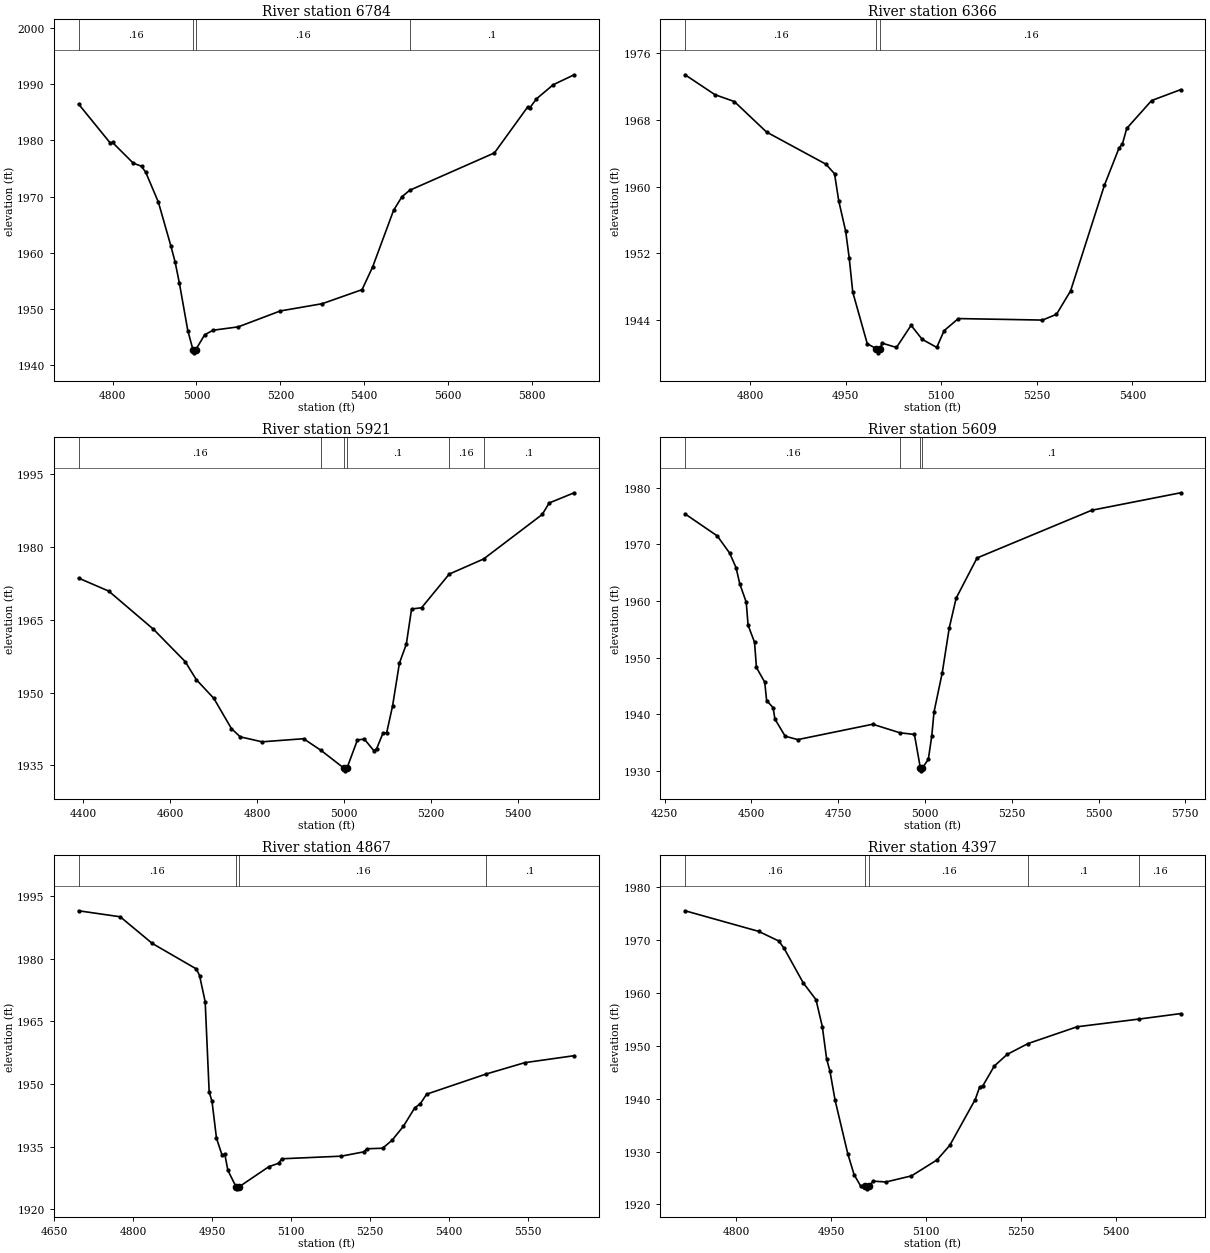
Type RM Length L Ch R = 1 ,6784    ,418,418,418
BEGIN DESCRIPTION:
WALNUT CREEK 2 15.0
END DESCRIPTION:
XS GIS Cut Line= 2
      2672408.36      10069894.9      2671228.64     10069954.07
#Sta/Elev= 30
  4719.1 1986.44  4794.9 1979.48  4799.9 1979.62  4849.2 1975.95  4869.2 1975.38
  4879.2 1974.29  4909.2    1969  4939.3 1961.13  4949.3 1958.29  4959.3 1954.58
  4979.3 1946.17  4991.8  1942.7  4994.6  1942.2  4997.8  1942.7  5019.4  1945.4
  5039.4 1946.22  5099.5 1946.82  5199.8 1949.65  5299.7 1950.94  5394.7 1953.44
  5419.9 1957.48  5469.9 1967.56    5490 1969.99  5508.4 1971.12  5710.2 1977.76
  5789.6 1985.95  5794.6 1985.78  5810.4 1987.38  5850.4 1989.89  5900.3 1991.66
#Mann= 4 ,-1 , 0
  4719.1     .16       0  4991.8     .07       0  4997.8     .16       0
  5508.4      .1       0
Bank Sta=4991.8,4997.8
XS Rating Curve= 0 ,0
Exp/Cntr=0.3,0.1

Type RM Length L Ch R = 1 ,6366    ,445,445,445
BEGIN DESCRIPTION:
WALNUT CREEK 2 14.0
END DESCRIPTION:
XS GIS Cut Line= 3
      2672304.75     10069525.07       2672090.3     10069491.79
      2671581.75     10069727.64
#Sta/Elev= 30
  4698.1 1973.38  4744.9    1971  4775.3 1970.18  4825.9 1966.53  4918.9 1962.69
  4932.6 1961.54  4939.2 1958.29    4950 1954.69  4955.6 1951.48  4961.2 1947.37
    4984 1941.19  4998.4 1940.61  5001.1 1940.11  5004.4 1940.61  5006.9 1941.28
  5029.8 1940.75  5052.7  1943.4  5070.1 1941.73    5093 1940.76  5104.5 1942.76
  5126.9 1944.21  5258.9 1944.03  5280.9 1944.72    5303 1947.52    5356 1960.14
  5378.9 1964.59  5384.4 1965.12  5391.1 1966.96  5430.2  1970.3  5475.7  1971.6
#Mann= 3 ,-1 , 0
  4698.1     .16       0  4998.4     .07       0  5004.4     .16       0
Bank Sta=4998.4,5004.4
XS Rating Curve= 0 ,0
Exp/Cntr=0.3,0.1

Type RM Length L Ch R = 1 ,5921    ,312,312,312
BEGIN DESCRIPTION:
WALNUT CREEK 2 13.0
END DESCRIPTION:
XS GIS Cut Line= 3
      2672237.18     10069241.03      2671813.72     10069184.71
       2671192.8     10069536.84
#Sta/Elev= 30
  4389.3 1973.54  4458.6 1970.87  4561.5 1963.03  4634.7 1956.36  4660.4 1952.64
  4700.7 1948.79  4741.1 1942.58  4761.3 1940.89  4811.6 1939.86  4907.2  1940.5
  4947.7 1938.08  5000.9 1934.39  5003.6 1933.89  5006.9 1934.39  5031.3 1940.26
  5047.2 1940.41  5068.8 1938.07  5075.4 1938.43  5090.4 1941.71  5098.4 1941.66
  5112.1 1947.21  5127.9 1956.04  5143.8 1959.95  5155.9 1967.19  5178.9 1967.44
  5242.6 1974.37  5321.6 1977.47  5456.8 1986.64  5472.7    1989  5530.3  1991.1
#Mann= 6 ,-1 , 0
  4389.3     .16       0  4947.7      .1       0  5000.9     .07       0
  5006.9      .1       0  5242.6     .16       0  5321.6      .1       0
Bank Sta=5000.9,5006.9
XS Rating Curve= 0 ,0
Exp/Cntr=0.3,0.1

Type RM Length L Ch R = 1 ,5609    ,742,742,742
BEGIN DESCRIPTION:
WALNUT CREEK 2 12.0
END DESCRIPTION:
XS GIS Cut Line= 3
      2672264.29     10069176.37      2671963.91      10069053.3
      2670862.97     10068984.49
#Sta/Elev= 30
  4308.8 1975.38  4401.5  1971.5  4436.9 1968.49  4455.5 1965.92  4466.4 1963.03
  4484.9 1959.82  4490.3 1955.74  4508.9 1952.74  4514.3 1948.29  4538.3  1945.7
  4543.7 1942.46  4562.3 1941.21  4567.7 1939.18  4597.1 1936.17  4633.4 1935.57
  4849.3 1938.28  4927.8 1936.77  4969.5 1936.48  4986.6 1930.56  4989.3 1930.06
  4992.6 1930.56  5009.6  1932.1  5019.6 1936.27  5025.9 1940.42  5049.7 1947.38
  5069.7 1955.22  5089.7 1960.52  5149.9 1967.61  5480.5 1976.03  5736.5 1979.11
#Mann= 4 ,-1 , 0
  4308.8     .16       0  4927.8      .1       0  4986.6     .07       0
  4992.6      .1       0
Bank Sta=4986.6,4992.6
XS Rating Curve= 0 ,0
Exp/Cntr=0.3,0.1

Type RM Length L Ch R = 1 ,4867    ,470,470,470
BEGIN DESCRIPTION:
WALNUT CREEK 2 11.0
END DESCRIPTION:
XS GIS Cut Line= 2
      2672571.93     10068961.02      2671696.91     10068613.79
#Sta/Elev= 30
  4696.7  1991.5  4775.7 1990.06  4836.7 1983.67  4920.4 1977.56  4926.4 1975.99
  4937.1 1969.72  4944.7 1948.11  4950.1 1945.82  4958.6 1936.99    4969 1933.04
  4974.4 1933.17  4980.2 1929.33  4995.7 1925.38  4998.5 1924.88  5001.7 1925.38
  5058.1 1930.19    5077 1931.03  5082.4 1932.08  5195.8 1932.71  5238.4 1933.74
  5244.4 1934.48  5274.1 1934.61  5292.2 1936.52  5313.7 1939.88  5335.2 1944.28
  5345.9 1945.28  5357.8 1947.56  5470.2 1952.36  5544.2 1955.11  5638.1 1956.78
#Mann= 4 ,-1 , 0
  4696.7     .16       0  4995.7     .07       0  5001.7     .16       0
  5470.2      .1       0
Bank Sta=4995.7,5001.7
XS Rating Curve= 0 ,0
Exp/Cntr=0.3,0.1

Type RM Length L Ch R = 1 ,4397    ,533,533,533
BEGIN DESCRIPTION:
WALNUT CREEK 2 10.0
END DESCRIPTION:
XS GIS Cut Line= 2
      2672453.82     10068370.73      2671676.08     10068467.95
#Sta/Elev= 30
  4718.8  1975.5  4835.1 1971.61  4867.1 1969.78  4875.4  1968.4  4905.6 1961.89
  4925.8 1958.71  4935.8 1953.63  4942.7 1947.47  4947.8 1945.25    4956 1939.72
  4976.1 1929.59  4986.2  1925.6  4996.3 1923.53  5003.4 1923.45  5006.1 1922.95
  5009.4 1923.45  5016.5  1924.4  5036.6 1924.25  5076.9  1925.4  5117.2 1928.41
  5137.4 1931.16  5177.7 1939.83  5184.6 1942.15  5189.6  1942.4  5207.9 1946.16
  5228.1 1948.35  5261.3 1950.41  5338.9 1953.58  5436.6 1955.03  5502.6 1956.07
#Mann= 5 ,-1 , 0
  4718.8     .16       0  5003.4     .07       0  5009.4     .16       0
  5261.3      .1       0  5436.6     .16       0
Bank Sta=5003.4,5009.4
XS Rating Curve= 0 ,0
Exp/Cntr=0.3,0.1