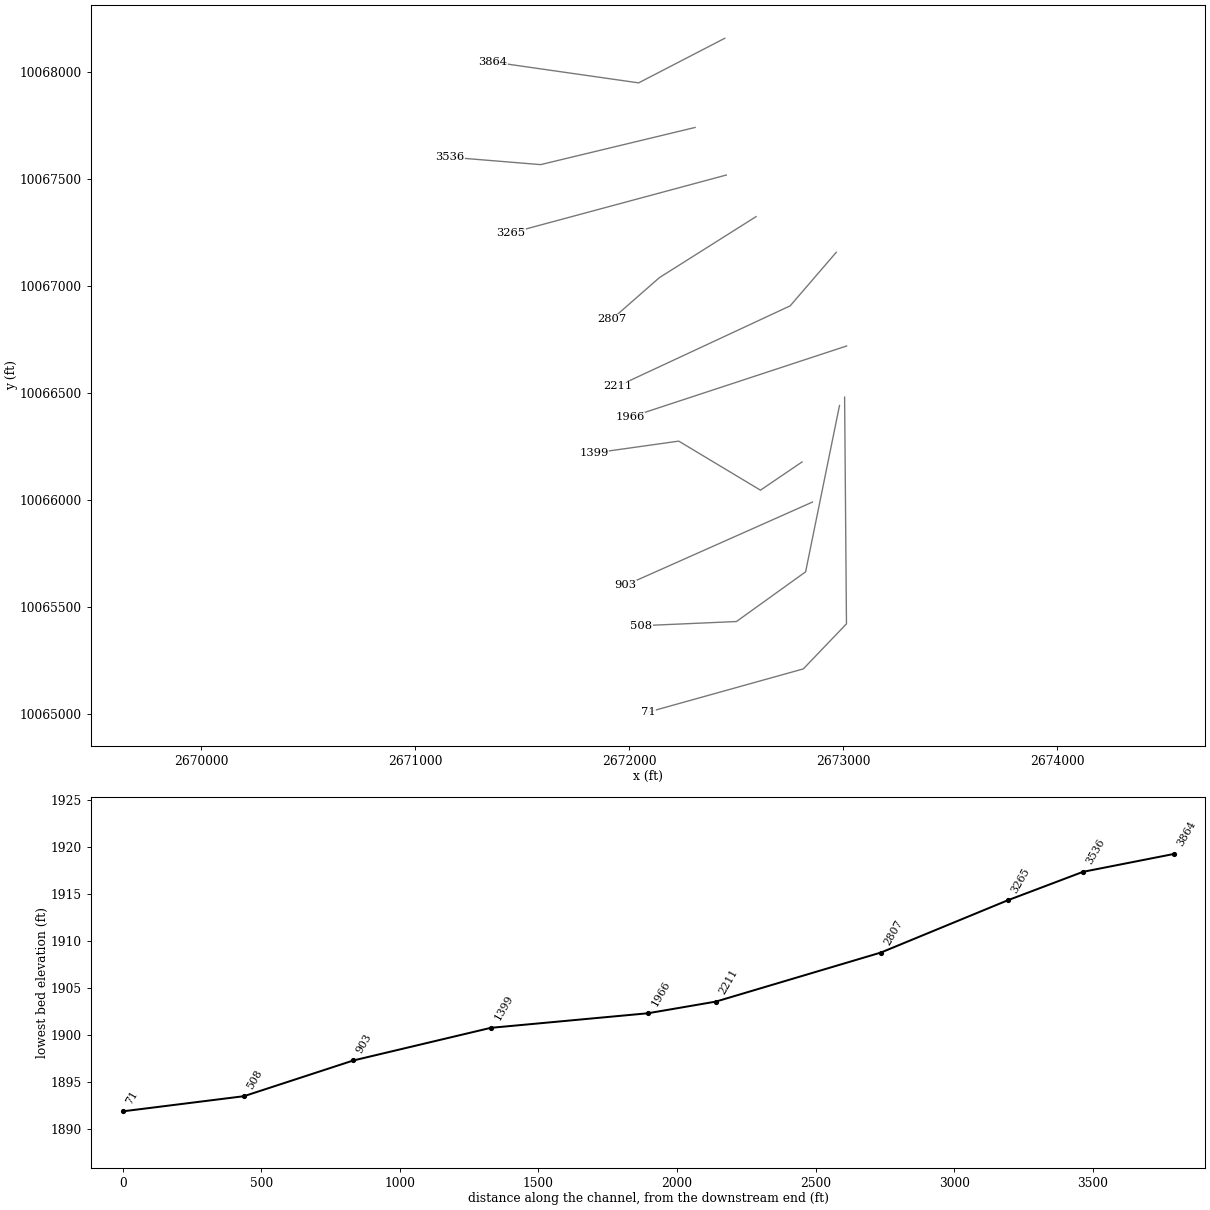
HEC-RAS study WALNUT CREEK 2.prj: WALNUT CREEK 2 Base Level Engineering

--- WALNUT CREEK 2.g01 (geometry) --- (continued)

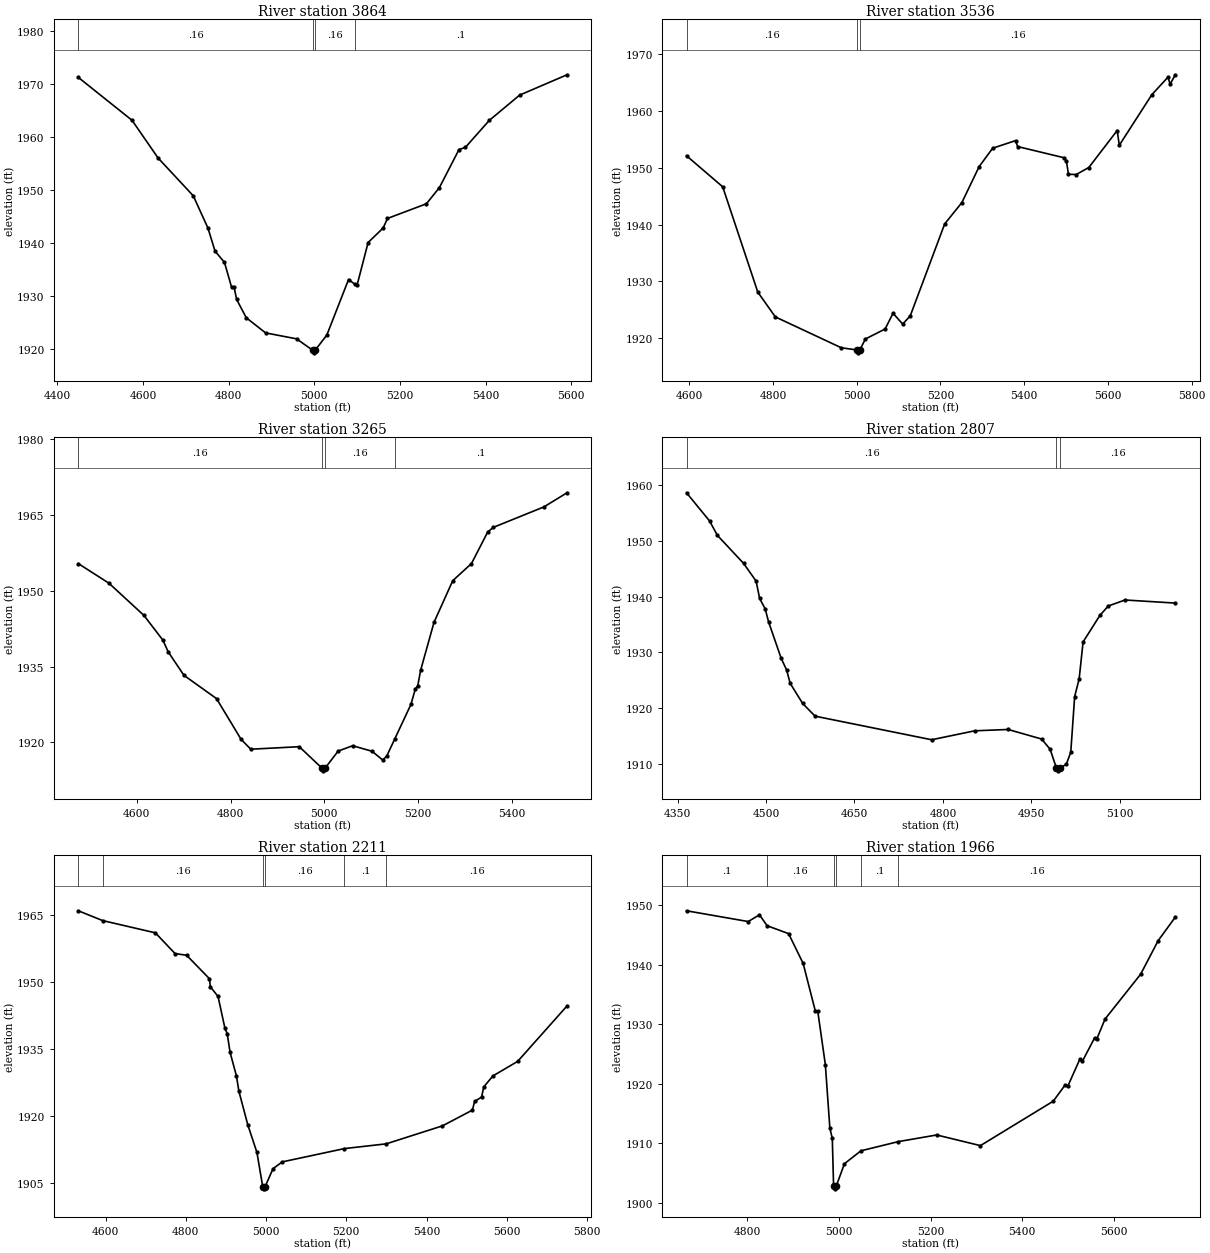
Type RM Length L Ch R = 1 ,3864    ,328,328,328
BEGIN DESCRIPTION:
WALNUT CREEK 2 9.0
END DESCRIPTION:
XS GIS Cut Line= 3
      2672446.85     10068155.43      2672044.12     10067947.12
      2671363.54     10068044.34
#Sta/Elev= 30
    4449 1971.26  4574.5 1963.16  4635.3 1956.05  4717.4 1948.92  4751.7 1942.83
  4768.2 1938.49  4790.3 1936.35  4806.8 1931.69  4812.5 1931.75  4818.7 1929.37
  4841.2 1925.91  4886.3 1923.06  4958.6 1921.94    4996  1919.8  4998.8  1919.3
    5002  1919.8  5029.3 1922.67  5079.9 1933.13  5094.2 1932.27  5100.1 1932.16
  5125.6 1940.11  5160.7 1942.85  5170.8 1944.65  5261.7 1947.42    5292 1950.47
  5337.8 1957.65  5352.6 1958.05  5408.5 1963.15  5479.2 1967.91  5589.9 1971.75
#Mann= 4 ,-1 , 0
    4449     .16       0    4996     .07       0    5002     .16       0
  5094.2      .1       0
Bank Sta=4996,5002
XS Rating Curve= 0 ,0
Exp/Cntr=0.3,0.1

Type RM Length L Ch R = 1 ,3536    ,271,271,271
BEGIN DESCRIPTION:
WALNUT CREEK 2 8.0
END DESCRIPTION:
XS GIS Cut Line= 3
        2672308.     10067738.78      2671585.78     10067565.17
      2671162.79     10067599.84
#Sta/Elev= 30
  4593.6 1952.13    4680 1946.66  4763.9 1928.09  4805.8 1923.73  4963.4 1918.29
  5001.5  1917.9  5004.3  1917.4  5007.5  1917.9  5020.8 1919.84  5067.9  1921.6
  5086.8 1924.37  5109.9 1922.47  5127.9 1923.91  5210.2 1940.12  5251.3 1943.89
  5292.5 1950.22  5324.8 1953.46  5379.4  1954.8  5384.4 1953.75  5494.2  1951.8
  5500.8 1951.22  5505.8 1948.87  5524.3 1948.82  5554.4 1950.06  5622.2 1956.58
  5627.2 1953.98  5704.9 1962.89  5743.6 1965.99  5748.6 1964.74  5760.8  1966.4
#Mann= 3 ,-1 , 0
  4593.6     .16       0  5001.5     .07       0  5007.5     .16       0
Bank Sta=5001.5,5007.5
XS Rating Curve= 0 ,0
Exp/Cntr=0.3,0.1

Type RM Length L Ch R = 1 ,3265    ,458,458,458
BEGIN DESCRIPTION:
WALNUT CREEK 2 7.0
END DESCRIPTION:
XS GIS Cut Line= 2
      2672453.81     10067516.55      2671446.89     10067245.73
#Sta/Elev= 30
  4475.1  1955.4  4540.7 1951.51  4615.3 1945.13  4655.4 1940.27    4667 1937.92
  4700.5 1933.29  4770.1 1928.67  4822.4 1920.62  4843.1 1918.66  4946.6 1919.16
  4995.4 1914.88  4998.2 1914.38  5001.4 1914.88  5029.5 1918.29  5060.5 1919.35
    5102 1918.25  5124.5 1916.52    5133 1917.27  5150.6 1920.75  5184.8 1927.53
  5194.1 1930.56  5199.3 1931.21  5205.5  1934.3  5234.1 1943.79    5274 1952.02
    5314 1955.41  5348.8 1961.69  5360.8 1962.58  5468.7 1966.63  5517.8 1969.42
#Mann= 4 ,-1 , 0
  4475.1     .16       0  4995.4     .07       0  5001.4     .16       0
  5150.6      .1       0
Bank Sta=4995.4,5001.4
XS Rating Curve= 0 ,0
Exp/Cntr=0.3,0.1

Type RM Length L Ch R = 1 ,2807    ,596,596,596
BEGIN DESCRIPTION:
WALNUT CREEK 2 6.0
END DESCRIPTION:
XS GIS Cut Line= 3
      2672592.73     10067322.12      2672141.34     10067037.39
      2671919.09     10066842.93
#Sta/Elev= 30
  4365.1 1958.56  4404.3 1953.51  4417.4 1950.95    4462 1945.92  4483.2 1942.75
  4489.1 1939.66  4498.5 1937.81  4504.4 1935.44  4525.6 1928.97  4534.9 1926.86
  4540.9 1924.48  4562.1 1920.87  4583.2  1918.6  4780.9 1914.38  4853.9 1915.98
  4910.6 1916.22  4967.5 1914.51  4981.8 1912.69  4992.6 1909.32  4995.4 1908.82
  4998.6 1909.32  5009.3 1909.99  5016.9 1912.14  5023.5 1922.11  5031.1 1925.25
  5037.8 1931.88  5066.2 1936.61  5080.5 1938.31    5109 1939.38  5194.1 1938.83
#Mann= 3 ,-1 , 0
  4365.1     .16       0  4992.6     .07       0  4998.6     .16       0
Bank Sta=4992.6,4998.6
XS Rating Curve= 0 ,0
Exp/Cntr=0.3,0.1

Type RM Length L Ch R = 1 ,2211    ,245,245,245
BEGIN DESCRIPTION:
WALNUT CREEK 2 5.0
END DESCRIPTION:
XS GIS Cut Line= 3
      2672967.75     10067155.48      2672752.45     10066905.45
      2671946.91     10066530.46
#Sta/Elev= 30
  4531.8 1966.03  4592.4 1963.83  4723.9 1961.08  4773.2 1956.41  4801.8 1956.05
  4858.8 1950.77    4861 1948.98  4880.2  1946.8  4897.5 1939.62  4903.1 1938.43
  4910.3 1934.22  4925.9 1929.01  4932.3 1925.49  4954.4 1917.98  4977.2 1911.77
  4991.6  1904.1  4994.3  1903.6  4997.6  1904.1  5017.4 1908.13  5040.3 1909.65
  5195.4 1912.64  5299.5  1913.7  5439.7 1917.74  5514.4 1921.27  5519.9 1923.21
  5537.3 1924.21  5542.8  1926.5  5565.7 1928.96  5627.2 1932.21  5750.3 1944.66
#Mann= 6 ,-1 , 0
  4531.8      .1       0  4592.4     .16       0  4991.6     .07       0
  4997.6     .16       0  5195.4      .1       0  5299.5     .16       0
Bank Sta=4991.6,4997.6
XS Rating Curve= 0 ,0
Exp/Cntr=0.3,0.1

Type RM Length L Ch R = 1 ,1966    ,567,567,567
BEGIN DESCRIPTION:
WALNUT CREEK 2 4.0
END DESCRIPTION:
XS GIS Cut Line= 2
      2673016.29     10066717.94      2672002.95     10066384.78
#Sta/Elev= 30
  4667.2 1949.08  4801.8 1947.27  4826.4  1948.4  4843.1 1946.57    4890 1945.24
  4921.8 1940.23  4948.3 1932.24  4953.6 1932.23  4970.2 1923.25  4980.1 1912.54
  4985.4 1910.85  4988.2 1902.86    4991 1902.36  4994.2 1902.86  5011.9 1906.58
  5047.9 1908.75  5129.8  1910.3  5213.3 1911.41  5308.7 1909.62  5467.7 1917.09
  5494.2 1919.87  5499.5 1919.63    5526 1924.19  5531.2 1923.79  5557.8 1927.71
    5563  1927.6  5580.7 1930.89  5658.4 1938.42  5696.5 1944.04  5733.9    1948
#Mann= 6 ,-1 , 0
  4667.2      .1       0  4843.1     .16       0  4988.2     .07       0
  4994.2     .16       0  5047.9      .1       0  5129.8     .16       0
Bank Sta=4988.2,4994.2
XS Rating Curve= 0 ,0
Exp/Cntr=0.3,0.1

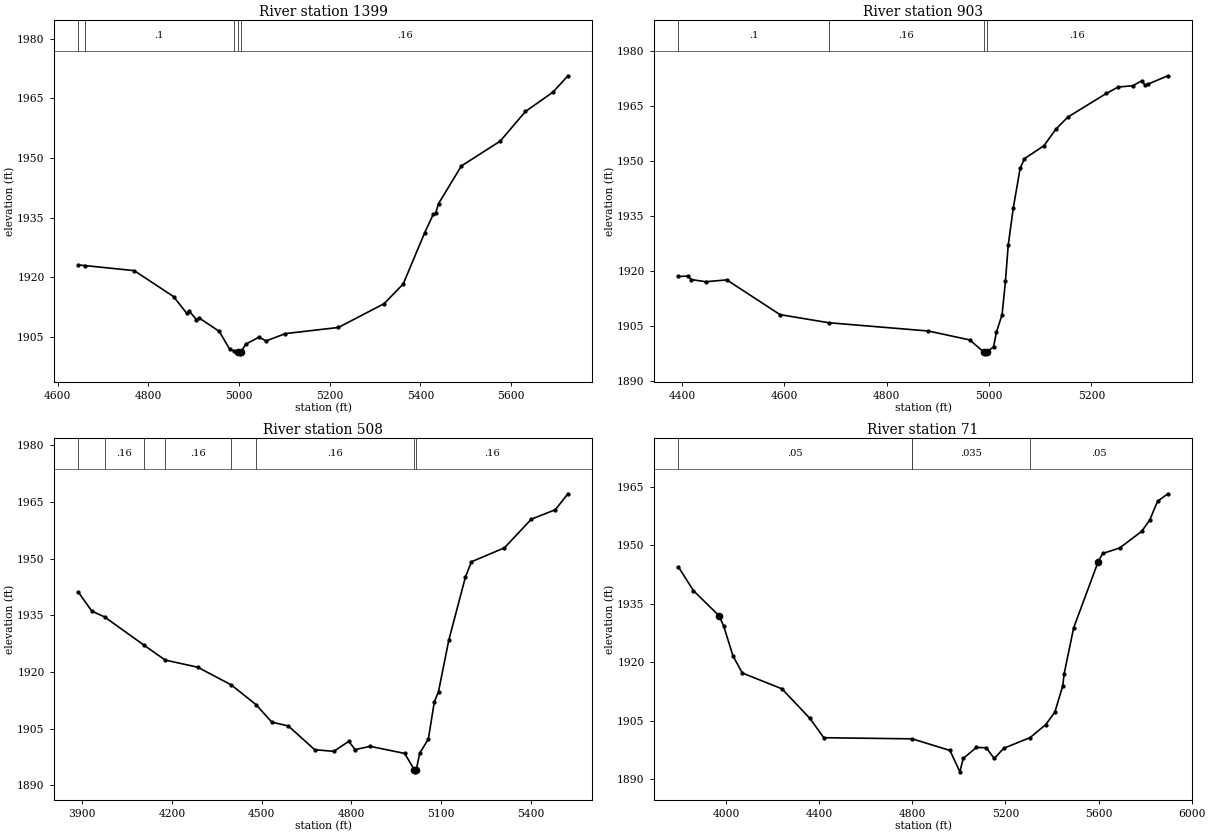
Type RM Length L Ch R = 1 ,1399    ,496,496,496
BEGIN DESCRIPTION:
WALNUT CREEK 2 3.0
END DESCRIPTION:
XS GIS Cut Line= 4
      2672807.97     10066176.26      2672613.56     10066044.34
      2672231.62      10066273.5      2671835.76     10066217.95
#Sta/Elev= 30
  4645.3 1923.14  4659.7 1922.98  4768.6 1921.71  4855.4 1915.19  4884.6 1910.97
  4890.4  1911.5  4905.9  1909.4  4911.8 1909.83  4956.2 1906.45  4979.5 1901.91
  4988.2 1901.58  4998.2 1901.31  5000.9 1900.81  5004.2 1901.31  5014.5 1903.22
  5043.9    1905  5059.5 1904.05  5102.3  1905.9  5218.9 1907.43  5319.9 1913.41
  5362.1 1918.37  5409.6 1931.28  5428.4 1935.85  5433.4 1936.08  5439.9 1938.52
  5490.4 1948.01    5576 1954.23  5631.8 1961.69  5692.4 1966.53  5725.4 1970.65
#Mann= 5 ,-1 , 0
  4645.3     .16       0  4659.7      .1       0  4988.2     .16       0
  4998.2     .07       0  5004.2     .16       0
Bank Sta=4998.2,5004.2
XS Rating Curve= 0 ,0
Exp/Cntr=0.3,0.1

Type RM Length L Ch R = 1 ,903     ,395,395,395
BEGIN DESCRIPTION:
WALNUT CREEK 2 2.0
END DESCRIPTION:
XS GIS Cut Line= 2
      2672856.61     10065988.78      2671982.55     10065600.31
#Sta/Elev= 30
  4392.9 1918.43  4412.5 1918.54  4417.9  1917.6  4446.7    1917  4487.7  1917.5
  4591.7 1908.03  4686.9 1905.82  4881.7 1903.56  4962.4 1901.13  4989.7 1897.84
  4992.5 1897.34  4995.7 1897.84  5008.9 1899.25  5014.6 1903.27  5025.6 1908.04
  5032.1 1917.09  5037.6    1927  5047.5 1937.13  5060.8 1947.87  5069.3 1950.54
  5107.4 1954.08  5130.6 1958.57  5153.9 1961.87  5229.1 1968.31  5252.4 1970.08
  5281.1 1970.42  5298.9 1971.82  5304.3 1970.66  5310.1 1970.83  5349.4 1973.14
#Mann= 4 ,-1 , 0
  4392.9      .1       0  4686.9     .16       0  4989.7     .07       0
  4995.7     .16       0
Bank Sta=4989.7,4995.7
XS Rating Curve= 0 ,0
Exp/Cntr=0.3,0.1

Type RM Length L Ch R = 1 ,508     ,437,437,437
BEGIN DESCRIPTION:
Mapping XS 4ee655b7
END DESCRIPTION:
XS GIS Cut Line= 4
      2672983.08     10066439.86      2672824.66     10065662.96
      2672501.31     10065430.75      2672056.42     10065411.22
#Sta/Elev= 30
  3887.2 1941.11  3932.3 1936.08  3974.9 1934.55  4105.2 1927.15  4177.4 1923.13
    4286 1921.24  4398.4 1916.55  4481.3 1911.31  4533.6 1906.71  4589.3 1905.67
  4677.1  1899.4  4740.9 1898.96  4791.3 1901.63  4812.2 1899.42  4862.5 1900.29
  4977.9 1898.41  5010.5 1894.04  5013.3 1893.54  5016.5 1894.04  5028.2 1898.47
  5057.1 1902.23  5076.9 1912.02    5091 1914.79  5125.2 1928.33  5181.1 1945.14
  5201.1 1949.15  5311.3 1952.83  5401.3 1960.42  5481.4 1962.92  5523.5 1967.14
#Mann= 8 ,-1 , 0
  3887.2      .1       0  3974.9     .16       0  4105.2      .1       0
  4177.4     .16       0  4398.4      .1       0  4481.3     .16       0
  5010.5     .07       0  5016.5     .16       0
Bank Sta=5010.5,5016.5
XS Rating Curve= 0 ,0
Exp/Cntr=0.3,0.1

Type RM Length L Ch R = 1 ,71      ,0,0,0
BEGIN DESCRIPTION:
WALNUT CREEK 2 1.0
END DESCRIPTION:
XS GIS Cut Line= 4
      2673006.96     10066478.97      2673015.64      10065419.9
      2672813.81      10065209.4      2672089.01     10065007.58
#Sta/Elev= 30
  3794.5 1944.48  3859.7 1938.33  3969.7 1931.91  3989.7 1929.26  4029.7 1921.62
  4069.7 1917.23  4239.7  1913.2  4359.8 1905.63  4419.8 1900.67  4799.8 1900.38
    4962  1897.4  5004.2 1891.93  5018.6 1895.35  5075.2 1898.17  5117.6  1898.1
  5151.8 1895.35  5192.3 1897.95  5306.5 1900.72  5372.7    1904  5412.1 1907.18
  5446.3 1913.97  5451.8 1916.92  5493.3 1928.86  5598.7 1945.79  5617.9 1947.85
  5690.6 1949.26  5785.3 1953.52  5819.5 1956.39  5853.7 1961.22  5897.6 1963.14
#Mann= 4 ,-1 , 0
  3794.5     .05       0  4799.8      .1       0  4799.8    .035       0
  5306.5     .05       0
Bank Sta=3969.7,5598.7
XS Rating Curve= 0 ,0
Exp/Cntr=0.3,0.1

Chan Stop Cuts=-1
Use User Specified Reach Order=0
Composite Channel Slope=5