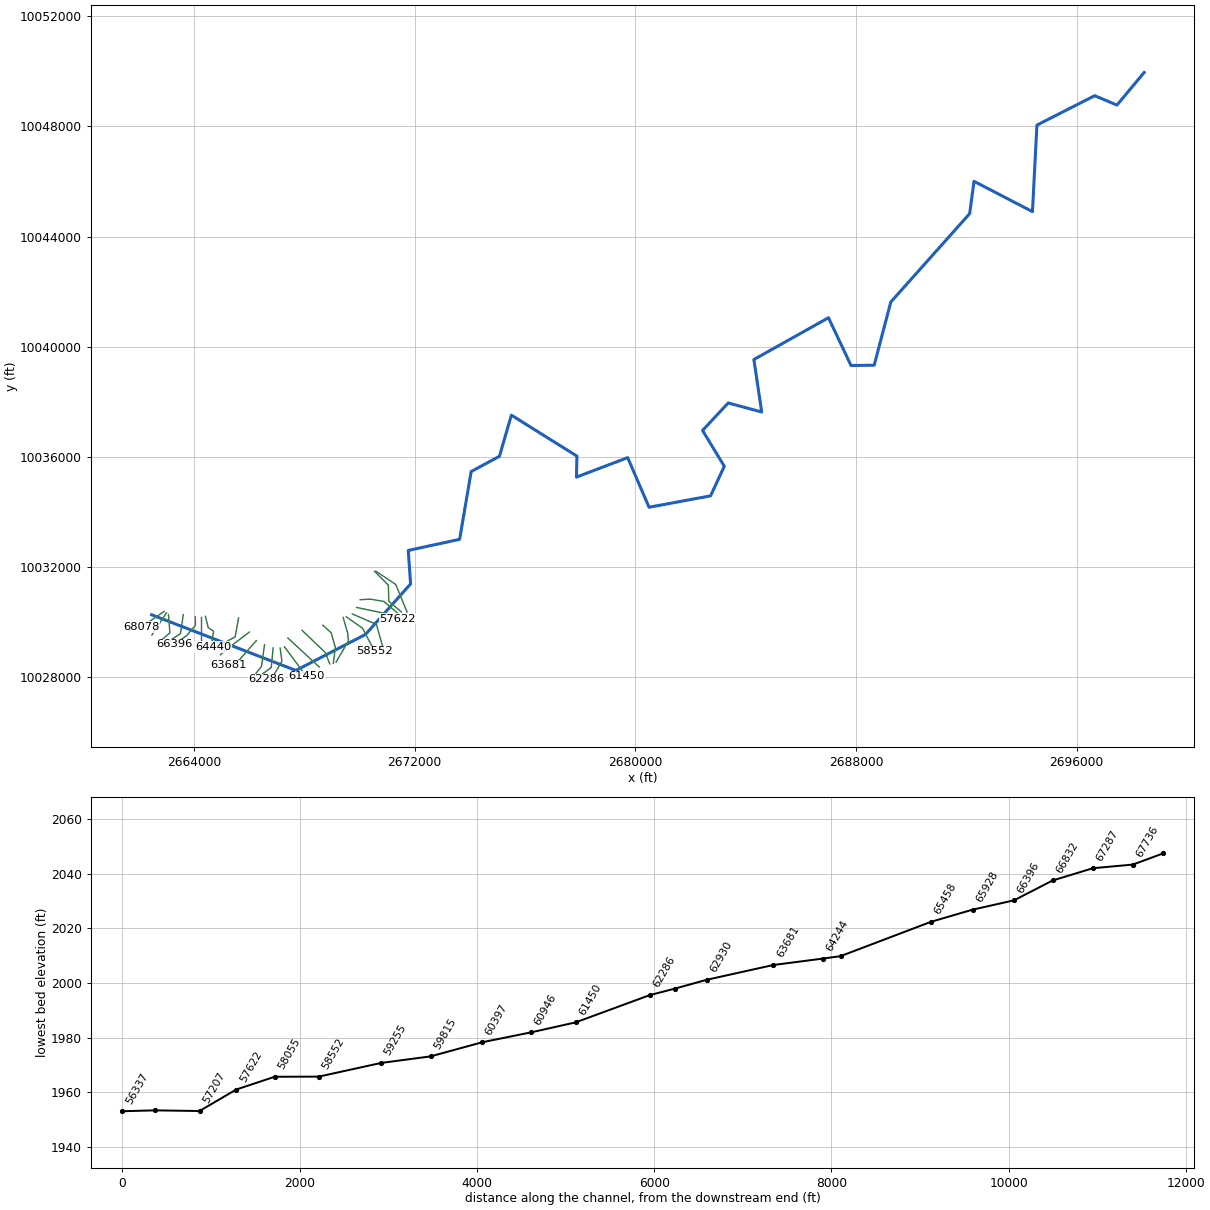
--- WHITE OAK CREEK.prj (project) ---

Proj Title=WHITE OAK CREEK Base Level Engineering
Current Plan=p01
Default Exp/Contr=0.3,0.1
English Units
Geom File=g01
Flow File=f01
Plan File=p01
Y Axis Title=Elevation
X Axis Title(PF)=Main Channel Distance
X Axis Title(XS)=Station
BEGIN DESCRIPTION:
WHITE OAK CREEK
END DESCRIPTION:
DSS Export Rating Curves= 0
DSS Export Rating Curve Sorted= 0
DSS Export Volume Flow Curves= 0
DXF OffsetX= 0
DXF OffsetY= 0
DXF ScaleX= 1
DXF ScaleY= 10

--- WHITE OAK CREEK.p01 (plan) ---

Plan Title=Multiple Run
Short Identifier=Multiple
Geom File=g01
Flow File=f01
Subcritical Flow
K Sum by GR= 0
Std Step Tol= 0.01
Critical Tol= 0.01
Num of Std Step Trials= 20
Max Error Tol= 0.3
Flow Tol Ratio= 0.001
Split Flow NTrial= 30
Split Flow Tol= 0.02
Split Flow Ratio= 0.02
Log Output Level= 0
Friction Slope Method= 1
Unsteady Friction Slope Method= 2
Unsteady Bridges Friction Slope Method= 1
Parabolic Critical Depth
Global Vel Dist=  1 , 1 , 1
Global Log Level= 0
CheckData=True
Encroach Param= -1, 0, 0, 0
BEGIN DESCRIPTION:
Multiple Run
END DESCRIPTION:

--- WHITE OAK CREEK.f01 (steady flow) ---

Flow Title=Multiple
Program Version=4.10
Number of Profiles= 7
Profile Names=10-year,25-year,50-year,1pct_min,100-year,1pct_plu,500-year
River Rch & RM=WHITE OAK CREEK,Reach-1         ,68078
    1008    1450    1827    1678    2269    3068    3499
River Rch & RM=WHITE OAK CREEK,Reach-1         ,67736
    1486    2182    2786    2590    3502    4737    5535
River Rch & RM=WHITE OAK CREEK,Reach-1         ,63681
    1903    2827    3639    3407    4607    6231    7388
River Rch & RM=WHITE OAK CREEK,Reach-1         ,61450
    2428    3649    4734    4463    6036    8162    9816
River Rch & RM=WHITE OAK CREEK,Reach-1         ,58552
    2619    3947    5130    4843    6550    8858   10687
River Rch & RM=WHITE OAK CREEK,Reach-1         ,56702
    3263    4952    6466    6127    8286   11206   13620
River Rch & RM=WHITE OAK CREEK,Reach-1         ,49482
    4593    7058    9294    8872   11998   16226   20015
River Rch & RM=WHITE OAK CREEK,Reach-1         ,41998
    4695    7204    9478    9037   12222   16528   20341
River Rch & RM=WHITE OAK CREEK,Reach-1         ,38088
    5008    7701   10144    9684   13096   17711   21847
River Rch & RM=WHITE OAK CREEK,Reach-1         ,37243
    5008    7701   10144    9684   13096   17711   21847
River Rch & RM=WHITE OAK CREEK,Reach-1         ,36228
    6410    9926   13139   12595   17033   23035   28646
River Rch & RM=WHITE OAK CREEK,Reach-1         ,35249
    6410    9926   13139   12595   17033   23035   28646
River Rch & RM=WHITE OAK CREEK,Reach-1         ,29896
    7001   10866   14405   13827   18699   25288   31530
River Rch & RM=WHITE OAK CREEK,Reach-1         ,27762
    7001   10866   14405   13827   18699   25288   31530
River Rch & RM=WHITE OAK CREEK,Reach-1         ,25852
    7244   11255   14932   14341   19394   26228   32740
River Rch & RM=WHITE OAK CREEK,Reach-1         ,24422
    7294   11314   14994   14383   19452   26306   32759
River Rch & RM=WHITE OAK CREEK,Reach-1         ,17516
    8076   12568   16692   16043   21697   29343   36681
River Rch & RM=WHITE OAK CREEK,Reach-1         ,17021
    8076   12568   16692   16043   21697   29343   36681
River Rch & RM=WHITE OAK CREEK,Reach-1         ,15366
    8367   13014   17279   16600   22450   30360   37916
River Rch & RM=WHITE OAK CREEK,Reach-1         ,14169
    8367   13014   17279   16600   22450   30360   37916
River Rch & RM=WHITE OAK CREEK,Reach-1         ,7733
    8528   13262   17605   16910   22868   30927   38605
Boundary for River Rch & Prof#=WHITE OAK CREEK,Reach-1         , 1
Up Type= 0
Dn Type= 3
Dn Slope=0.009
Boundary for River Rch & Prof#=WHITE OAK CREEK,Reach-1         , 2
Up Type= 0
Dn Type= 3
Dn Slope=0.009
Boundary for River Rch & Prof#=WHITE OAK CREEK,Reach-1         , 3
Up Type= 0
Dn Type= 3
Dn Slope=0.009
Boundary for River Rch & Prof#=WHITE OAK CREEK,Reach-1         , 4
Up Type= 0
Dn Type= 3
Dn Slope=0.009
Boundary for River Rch & Prof#=WHITE OAK CREEK,Reach-1         , 5
Up Type= 0
Dn Type= 3
Dn Slope=0.009
Boundary for River Rch & Prof#=WHITE OAK CREEK,Reach-1         , 6
Up Type= 0
Dn Type= 3
Dn Slope=0.009
Boundary for River Rch & Prof#=WHITE OAK CREEK,Reach-1         , 7
Up Type= 0
Dn Type= 3
Dn Slope=0.009
DSS Import GetInterval= 0
DSS Import GetPeak= 0
DSS Import FillOption= 0

--- WHITE OAK CREEK.g01 (geometry) ---

Geom Title=Existing Conditions
Program Version=4.10

River Reach=WHITE OAK CREEK ,Reach-1
Reach XY= 30
      2662468.47     10030273.73      2667697.49     10028253.65
      2670220.81     10029559.47      2671856.06     10031394.66
      2671771.18     10032608.49      2673633.45     10033011.98
      2674051.58     10035472.57       2675075.9      10036024.8
      2675509.32     10037518.51      2677885.44     10036031.37
      2677867.79     10035270.41      2679726.05     10035976.66
      2680499.57      10034176.4      2682730.93      10034589.6
      2683226.97     10035663.51      2682439.65     10036962.33
      2683369.56       10037961.      2684582.97     10037632.39
      2684300.32     10039537.22      2687003.41     10041053.15
      2687820.39     10039320.97      2688660.93     10039329.65
      2689262.05     10041622.25      2692122.07     10044832.24
       2692279.5     10046003.98      2694397.98     10044904.71
      2694559.68     10048043.89      2696654.42     10049111.43
       2697461.4     10048769.93      2698446.82     10049953.35

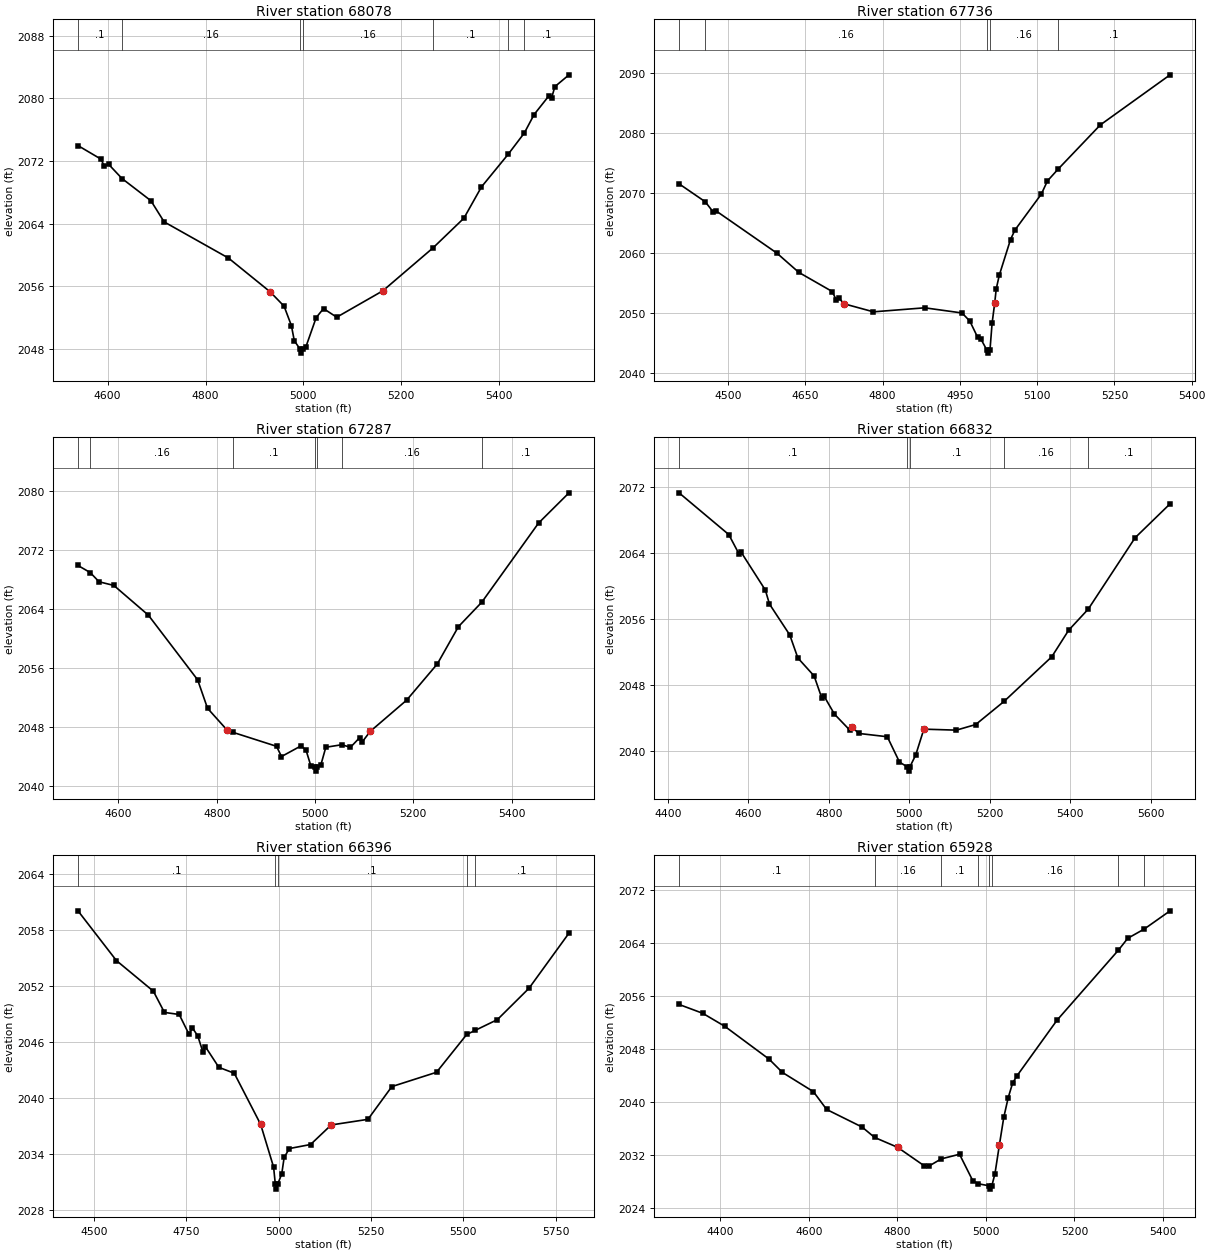
Type RM Length L Ch R = 1 ,68078   ,342,342,342
BEGIN DESCRIPTION:
WHITE OAK CREEK 114.0
END DESCRIPTION:
XS GIS Cut Line= 2
      2662922.32     10030395.86      2662094.63     10029828.46
#Sta/Elev= 30
  4539.3 2073.98  4586.8 2072.23  4592.9 2071.32  4601.7  2071.6  4629.3 2069.77
  4688.4 2066.93  4715.4 2064.23  4846.8 2059.61  4931.9  2055.3  4960.5 2053.46
  4975.4 2050.99  4981.4 2049.05  4993.3 2047.96  4996.1 2047.46  4999.3 2047.96
  5004.7 2048.19  5026.1    2052  5041.1 2053.15  5068.1 2052.05  5162.3 2055.42
  5265.1 2060.92    5328  2064.7  5363.9  2068.7  5418.1 2072.84  5451.5 2075.59
  5471.5 2077.95  5501.3  2080.3  5507.4  2080.1  5513.9 2081.51  5542.8 2083.02
#Mann= 7 ,-1 , 0
  4539.3      .1       0  4629.3     .16       0  4993.3     .07       0
  4999.3     .16       0  5265.1      .1       0  5418.1     .16       0
  5451.5      .1       0
Bank Sta=4931.9,5162.3
XS Rating Curve= 0 ,0
Exp/Cntr=0.3,0.1

Type RM Length L Ch R = 1 ,67736   ,449,449,449
BEGIN DESCRIPTION:
Mapping XS e221245a
END DESCRIPTION:
XS GIS Cut Line= 2
      2663001.02     10030342.81      2662480.21     10029544.24
#Sta/Elev= 30
  4404.7 2071.53  4455.6 2068.54  4471.4  2066.8  4477.3 2066.98  4594.6    2060
  4637.3 2056.79  4702.1 2053.61  4709.7 2052.25  4715.7 2052.47  4724.9 2051.57
  4782.2 2050.23  4881.7  2050.9  4954.1 2050.04  4969.2  2048.7  4984.3 2046.02
  4990.3 2045.78  5002.4 2043.86  5005.2 2043.36  5008.4 2043.86  5012.5 2048.32
 5017.61  2051.7  5020.5 2054.02  5026.5 2056.33  5048.3 2062.26  5056.8 2063.83
    5108  2069.8    5120 2072.01  5140.8 2073.98  5222.7 2081.33  5358.1 2089.66
#Mann= 5 ,-1 , 0
  4404.7      .1       0  4455.6     .16       0  5002.4     .07       0
  5008.4     .16       0  5140.8      .1       0
Bank Sta=4724.9,5017.61
XS Rating Curve= 0 ,0
Exp/Cntr=0.3,0.1

Type RM Length L Ch R = 1 ,67287   ,455,455,455
BEGIN DESCRIPTION:
WHITE OAK CREEK 113.0
END DESCRIPTION:
XS GIS Cut Line= 3
      2663078.57     10030286.53      2663130.66     10029619.83
      2662882.03     10029402.28
#Sta/Elev= 30
  4517.6 2069.95  4542.5 2068.99  4560.5 2067.74  4590.6 2067.24  4660.8 2063.21
  4761.1 2054.43  4781.2 2050.57  4821.3 2047.59  4833.1  2047.3  4921.6 2045.41
  4931.7 2044.02  4971.8 2045.48  4981.8 2044.85  4991.8 2042.68  4998.9 2042.54
  5001.6 2042.04  5004.9 2042.54  5011.9 2042.91  5021.9 2045.28  5054.2 2045.62
  5072.1 2045.28  5090.6 2046.57  5095.6 2045.97  5112.2 2047.43  5186.3 2051.67
  5248.9  2056.6  5291.6 2061.64  5339.4 2064.98  5454.8 2075.71  5516.7 2079.81
#Mann= 7 ,-1 , 0
  4517.6      .1       0  4542.5     .16       0  4833.1      .1       0
  4998.9     .07       0  5004.9      .1       0  5054.2     .16       0
  5339.4      .1       0
Bank Sta=4821.3,5112.2
XS Rating Curve= 0 ,0
Exp/Cntr=0.3,0.1

Type RM Length L Ch R = 1 ,66832   ,436,436,436
BEGIN DESCRIPTION:
WHITE OAK CREEK 111.0
END DESCRIPTION:
XS GIS Cut Line= 3
      2663615.03     10030276.05      2663516.07     10029593.78
      2663074.81     10029297.88
#Sta/Elev= 30
  4427.5 2071.29  4551.1 2066.23    4577 2063.84  4582.1 2064.07    4642  2059.5
  4652.3  2057.8  4702.7 2054.06  4722.9 2051.26  4763.3 2049.08  4782.6 2046.37
  4787.6 2046.67  4813.8 2044.45  4852.8 2042.47  4857.8 2042.87  4874.4 2042.11
  4945.2 2041.71  4975.5 2038.64  4995.2 2038.04    4998 2037.54  5001.2 2038.04
  5015.9  2039.5  5036.1 2042.63  5116.9 2042.51    5165 2043.19  5235.8 2046.01
  5354.1 2051.41  5396.1 2054.63  5444.8 2057.19  5561.2 2065.84  5648.2 2069.96
#Mann= 5 ,-1 , 0
  4427.5      .1       0  4995.2     .07       0  5001.2      .1       0
  5235.8     .16       0  5444.8      .1       0
Bank Sta=4857.8,5036.1
XS Rating Curve= 0 ,0
Exp/Cntr=0.3,0.1

Type RM Length L Ch R = 1 ,66396   ,468,468,468
BEGIN DESCRIPTION:
WHITE OAK CREEK 110.0
END DESCRIPTION:
XS GIS Cut Line= 4
      2664052.53     10030197.94      2664057.74     10029895.87
      2663750.45     10029531.28      2663307.72     10029203.14
#Sta/Elev= 30
  4456.2 2060.01  4560.4 2054.69  4660.4 2051.42  4690.4 2049.15  4730.4 2048.93
  4756.9 2046.82  4766.3 2047.49  4780.6 2046.64  4794.9 2044.89  4801.4 2045.48
  4837.8 2043.28  4879.5 2042.65  4950.9 2037.19  4986.1 2032.61  4990.8 2030.76
  4993.6 2030.26  4996.8 2030.76  5008.1 2031.88  5014.7 2033.66    5029  2034.6
  5086.2 2035.03  5142.1 2037.12  5241.6 2037.72  5306.3 2041.22  5427.3 2042.75
  5509.1 2046.79  5531.5 2047.22  5592.2 2048.38  5677.8 2051.73  5786.2 2057.63
#Mann= 5 ,-1 , 0
  4456.2      .1       0  4990.8     .07       0  4996.8      .1       0
  5509.1     .16       0  5531.5      .1       0
Bank Sta=4950.9,5142.1
XS Rating Curve= 0 ,0
Exp/Cntr=0.3,0.1

Type RM Length L Ch R = 1 ,65928   ,470,470,470
BEGIN DESCRIPTION:
WHITE OAK CREEK 109.0
END DESCRIPTION:
XS GIS Cut Line= 2
      2664266.07     10030177.13      2664266.07     10029068.23
#Sta/Elev= 30
  4307.2 2054.69  4360.6 2053.36  4410.6 2051.39  4510.6 2046.44  4540.6 2044.44
  4610.6 2041.54  4640.6 2038.85  4720.6  2036.2  4748.7 2034.64  4800.6 2033.15
  4860.6 2030.37  4870.6 2030.28  4899.3  2031.4  4940.6  2032.1  4970.6  2028.1
  4982.8 2027.65  5007.6 2027.34  5010.3 2026.84  5013.6 2027.34  5020.6 2029.16
  5030.6  2033.5  5040.6 2037.69  5050.6 2040.65  5060.6 2042.85  5070.6 2043.95
  5160.6  2052.3  5299.3 2062.87  5320.6 2064.67  5357.9 2066.07  5416.1 2068.81
#Mann= 8 ,-1 , 0
  4307.2      .1       0  4748.7     .16       0  4899.3      .1       0
  4982.8     .16       0  5007.6     .07       0  5013.6     .16       0
  5299.3      .1       0  5357.9     .16       0
Bank Sta=4800.6,5030.6
XS Rating Curve= 0 ,0
Exp/Cntr=0.3,0.1

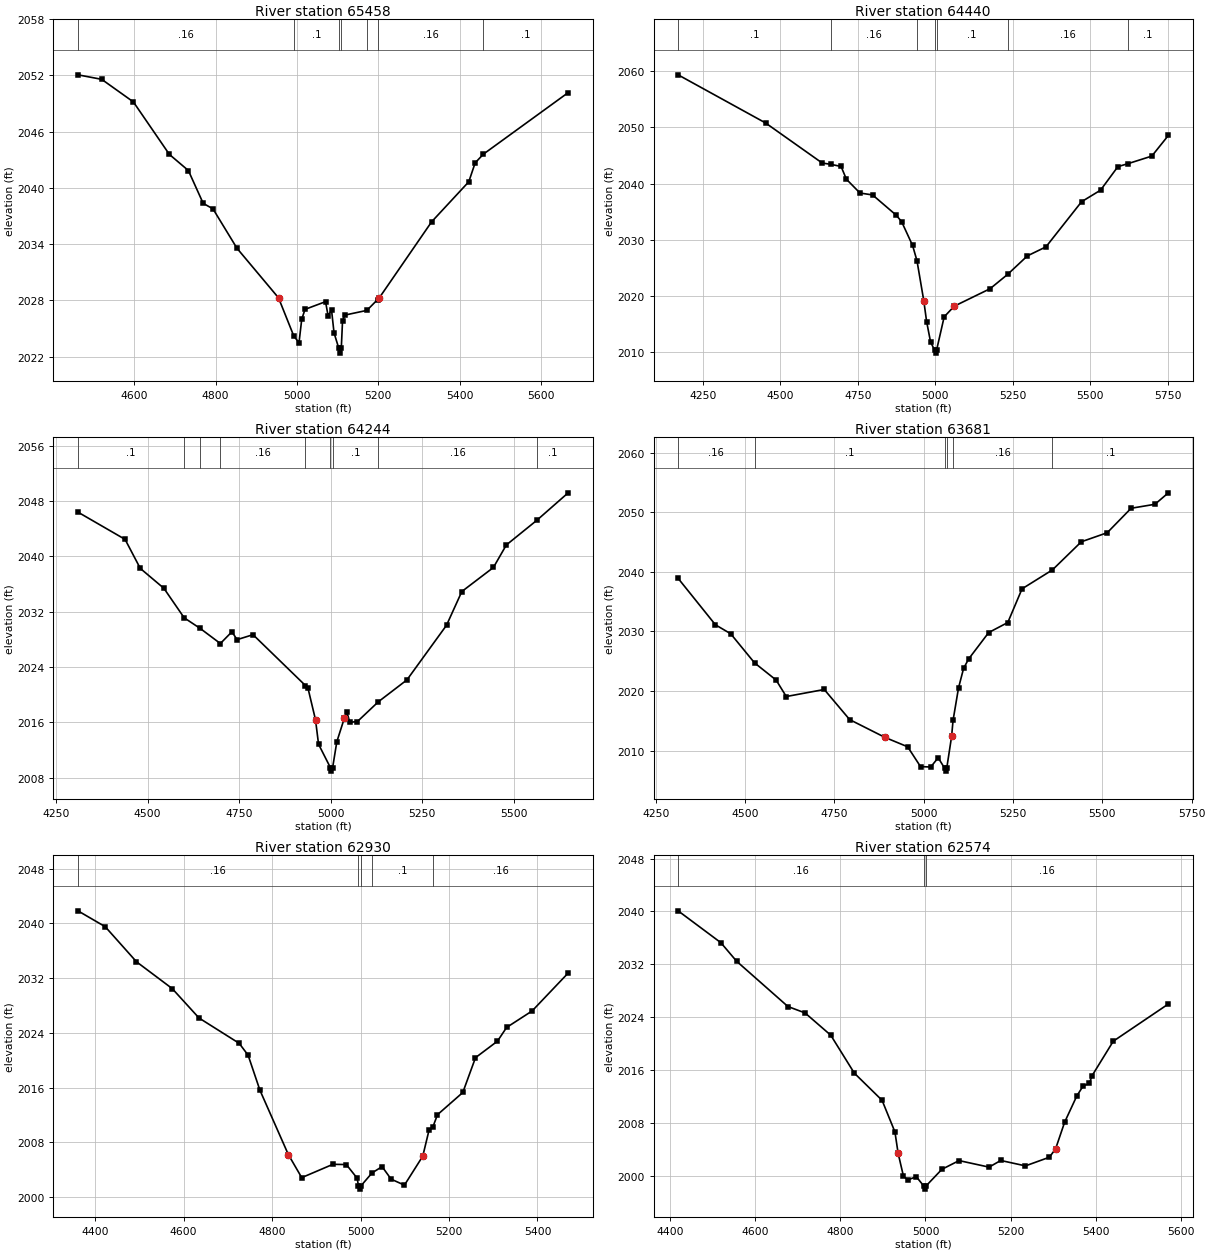
Type RM Length L Ch R = 1 ,65458   ,1018,1018,1018
BEGIN DESCRIPTION:
WHITE OAK CREEK 108.0
END DESCRIPTION:
XS GIS Cut Line= 4
      2664419.73     10030216.14      2664518.68     10029812.53
       2664716.6     10029671.91      2664625.44      10029132.8
#Sta/Elev= 30
  4461.7 2052.07  4520.1 2051.59    4598 2049.18  4686.5 2043.58  4733.2 2041.86
  4769.6 2038.36  4793.7 2037.77  4852.8 2033.56  4954.8 2028.28  4992.6 2024.18
  5005.2  2023.5  5011.9    2026    5020 2027.05  5070.4 2027.87  5076.6 2026.38
  5085.2 2026.95  5091.3 2024.54  5103.1 2022.88  5105.8 2022.38  5109.1 2022.88
  5112.2 2025.84  5118.1 2026.44  5172.1 2026.94  5198.4  2028.1  5201.6 2028.22
  5331.2 2036.39  5422.5 2040.66  5438.2 2042.68  5458.5 2043.61  5666.8 2050.17
#Mann= 7 ,-1 , 0
  4461.7     .16       0  4992.6      .1       0  5103.1     .07       0
  5109.1      .1       0  5172.1      .1       0  5198.4     .16       0
  5458.5      .1       0
Bank Sta=4954.8,5201.6
XS Rating Curve= 0 ,0
Exp/Cntr=0.3,0.1

Type RM Length L Ch R = 1 ,64440   ,196,196,196
BEGIN DESCRIPTION:
WHITE OAK CREEK 106.0
END DESCRIPTION:
XS GIS Cut Line= 4
      2665620.25     10030161.52      2665495.24     10029468.78
      2665044.72      10029229.2      2664698.37      10029104.2
#Sta/Elev= 30
  4170.1 2059.38  4452.4 2050.81  4635.3 2043.67  4662.2 2043.45  4696.2 2043.06
  4713.3 2040.79  4757.2 2038.33  4797.9 2037.99    4874 2034.39  4891.4 2033.25
    4927 2028.99  4941.2 2026.26    4963 2019.19  4972.3 2015.43    4985 2011.81
  4998.3 2010.32    5001 2009.82  5004.3 2010.32  5028.9 2016.28  5061.5 2018.18
  5177.1 2021.29  5233.5 2023.83  5297.6 2027.14  5357.4 2028.74  5472.4 2036.78
  5533.7 2038.84  5589.7 2043.03  5622.3 2043.56  5699.2 2044.91  5752.5 2048.58
#Mann= 7 ,-1 , 0
  4170.1      .1       0  4662.2     .16       0  4941.2      .1       0
  4998.3     .07       0  5004.3      .1       0  5233.5     .16       0
  5622.3      .1       0
Bank Sta=4963,5061.5
XS Rating Curve= 0 ,0
Exp/Cntr=0.3,0.1

Type RM Length L Ch R = 1 ,64244   ,563,563,563
BEGIN DESCRIPTION:
WHITE OAK CREEK 105.0
END DESCRIPTION:
XS GIS Cut Line= 3
      2666013.44     10029648.45      2665128.05      10028976.6
       2664962.4      10028821.3
#Sta/Elev= 30
  4309.7 2046.39  4438.4 2042.45    4480 2038.25  4544.5 2035.37  4599.8 2031.11
  4643.6 2029.57  4698.6 2027.39  4730.2 2029.09  4744.2 2027.95  4787.8 2028.67
    4931 2021.31  4937.6 2020.99  4958.4 2016.36  4966.7 2012.83  4999.1 2009.44
  5001.8 2008.94  5005.1 2009.44  5016.6 2013.19  5037.4 2016.64    5044 2017.48
    5052    2016  5072.8 2016.11    5130 2018.97    5208 2022.13  5316.1 2030.03
  5357.9 2034.91  5444.2 2038.39  5479.4 2041.64  5562.5  2045.2  5648.2 2049.18
#Mann= 9 ,-1 , 0
  4309.7      .1       0  4599.8     .16       0  4643.6      .1       0
  4698.6     .16       0    4931      .1       0  4999.1     .07       0
  5005.1      .1       0    5130     .16       0  5562.5      .1       0
Bank Sta=4958.4,5037.4
XS Rating Curve= 0 ,0
Exp/Cntr=0.3,0.1

Type RM Length L Ch R = 1 ,63681   ,751,751,751
BEGIN DESCRIPTION:
WHITE OAK CREEK 103.0
END DESCRIPTION:
XS GIS Cut Line= 3
      2666263.47     10029335.97       2665654.1     10028643.26
      2665253.27     10028440.25
#Sta/Elev= 30
  4312.8  2038.9  4417.2 2031.11  4459.9 2029.61  4526.6 2024.73  4587.1 2021.84
  4615.5 2019.08  4721.8 2020.26  4792.9 2015.21  4891.6 2012.23  4955.2 2010.65
  4991.2 2007.33  5019.7 2007.26  5040.6 2008.81  5058.6 2007.07  5061.4 2006.57
  5064.6 2007.07 5078.18 2012.39  5082.2 2015.07  5097.5 2020.51  5111.7  2023.8
    5126 2025.39    5182 2029.81  5235.4 2031.49  5275.3 2037.14  5360.4 2040.32
  5441.2 2045.03  5513.7 2046.55  5580.5 2050.65  5647.3 2051.32  5684.7 2053.24
#Mann= 6 ,-1 , 0
  4312.8     .16       0  4526.6      .1       0  5058.6     .07       0
  5064.6      .1       0  5082.2     .16       0  5360.4      .1       0
Bank Sta=4891.6,5078.18
XS Rating Curve= 0 ,0
Exp/Cntr=0.3,0.1

Type RM Length L Ch R = 1 ,62930   ,356,356,356
BEGIN DESCRIPTION:
WHITE OAK CREEK 102.0
END DESCRIPTION:
XS GIS Cut Line= 3
      2666560.34     10029184.88      2666450.97     10028398.47
      2666253.29     10028153.97
#Sta/Elev= 30
    4361 2041.85  4422.7 2039.53  4493.4  2034.4  4574.2 2030.48  4634.8 2026.18
  4725.6 2022.48  4745.8 2020.74  4772.5 2015.62  4836.7 2006.22    4867 2002.84
  4937.6 2004.79  4967.9 2004.75  4992.4 2002.75  4995.2 2001.66    4998 2001.16
  5001.2 2001.66    5026 2003.53  5048.7 2004.45  5069.1 2002.62  5099.2 2001.74
  5140.7 2005.98  5154.8 2009.77  5163.4 2010.22  5173.9 2012.04  5231.2 2015.29
  5259.9 2020.38  5309.5 2022.79  5330.3  2024.8  5387.9 2027.21  5469.4 2032.75
#Mann= 5 ,-1 , 0
    4361     .16       0  4995.2     .07       0  5001.2     .16       0
    5026      .1       0  5163.4     .16       0
Bank Sta=4836.7,5140.7
XS Rating Curve= 0 ,0
Exp/Cntr=0.3,0.1

Type RM Length L Ch R = 1 ,62574   ,288,288,288
BEGIN DESCRIPTION:
WHITE OAK CREEK 101.0
END DESCRIPTION:
XS GIS Cut Line= 3
      2666872.85     10029070.37      2666805.14     10028362.01
      2666453.77     10028098.49
#Sta/Elev= 30
  4419.3 2040.09  4519.6 2035.27  4556.6 2032.46  4677.1  2025.6  4717.3 2024.63
  4777.6 2021.26    4833 2015.51  4898.1  2011.4  4928.3 2006.61  4935.8 2003.37
  4948.3 1999.91  4958.4 1999.35  4978.5 1999.83  4995.6 1998.45  4998.3 1997.95
  5001.6 1998.45  5038.5 2000.95  5078.9 2002.27  5149.3 2001.28  5176.7 2002.29
  5234.7 2001.47  5290.9 2002.78  5305.5 2004.06  5326.7 2008.09  5355.5 2012.09
  5370.1 2013.56  5384.7 2013.95  5390.9 2015.11  5440.9 2020.35  5570.1 2025.98
#Mann= 3 ,-1 , 0
  4419.3     .16       0  4995.6     .07       0  5001.6     .16       0
Bank Sta=4935.8,5305.5
XS Rating Curve= 0 ,0
Exp/Cntr=0.3,0.1

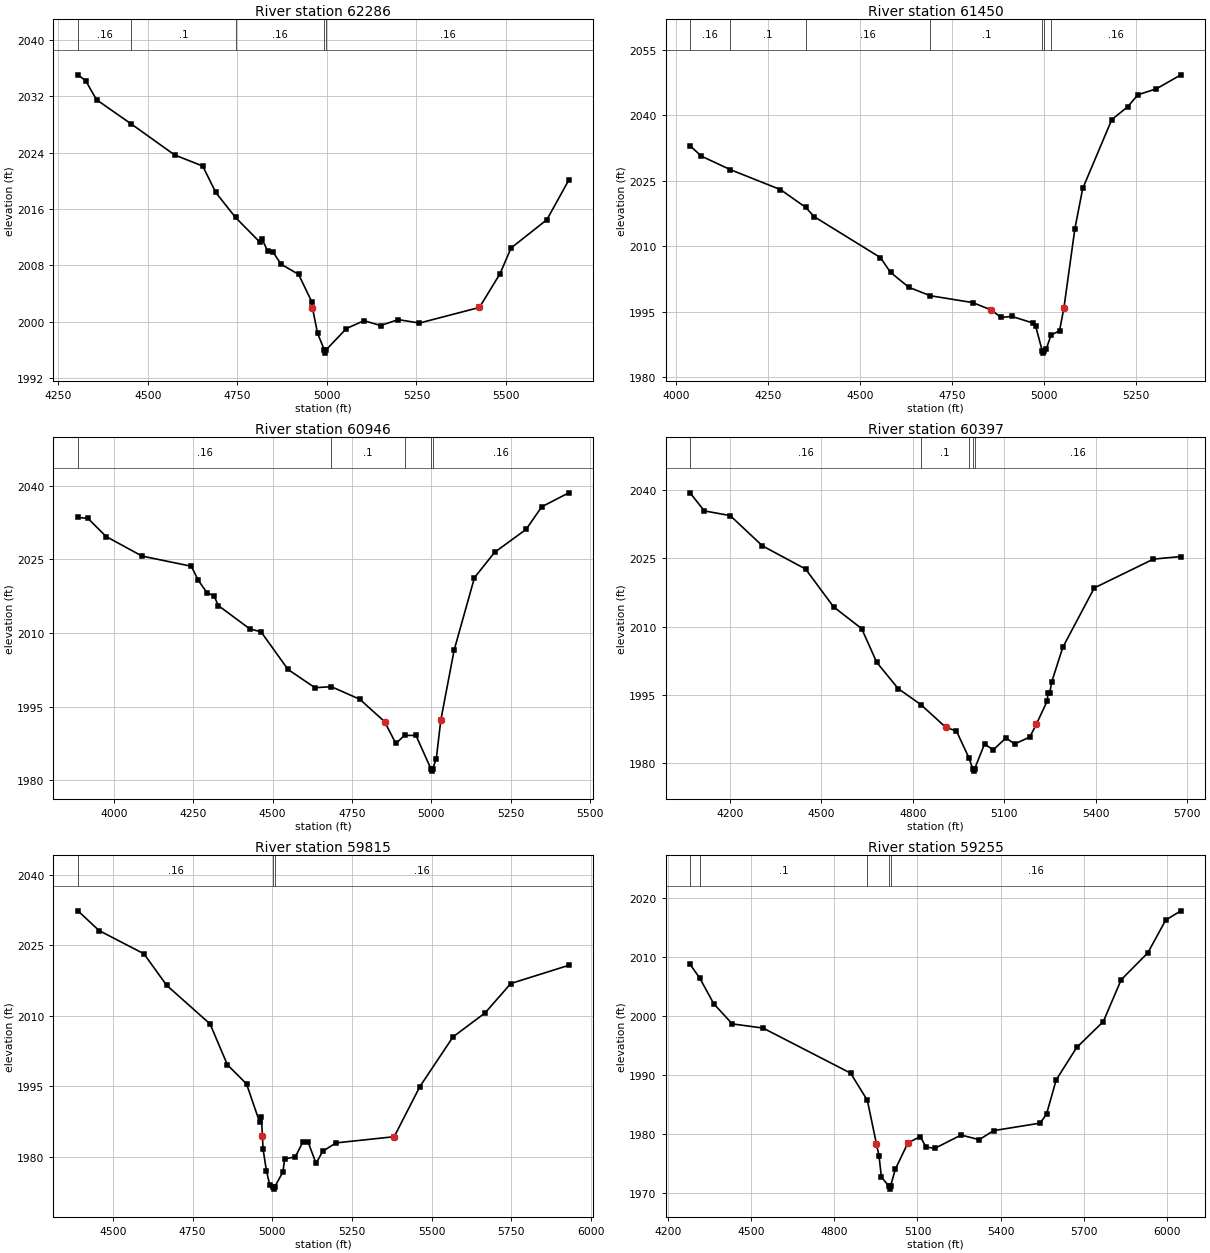
Type RM Length L Ch R = 1 ,62286   ,836,836,836
BEGIN DESCRIPTION:
WHITE OAK CREEK 100.0
END DESCRIPTION:
XS GIS Cut Line= 4
      2667128.06      10029065.1      2667190.55     10028591.18
      2666919.72     10028122.43       2666623.2     10027935.15
#Sta/Elev= 30
  4305.3 2035.06  4326.9 2034.22  4357.1 2031.52  4454.1 2028.08  4575.1 2023.68
  4653.6  2022.1    4690 2018.35  4745.1  2014.8  4813.4 2011.28  4819.1 2011.75
  4834.9 2010.01  4849.7  2009.9  4872.2 2008.16  4921.1 2006.72  4958.4 2002.78
    4960 2001.95  4974.2 1998.33  4992.7 1996.03  4995.5 1995.53  4998.7 1996.03
  5054.6 1999.02  5103.8 2000.14  5149.9 1999.45  5199.6 2000.29  5258.4  1999.8
    5426 2002.02  5483.6 2006.82  5514.2 2010.46  5614.2 2014.48  5675.4  2020.1
#Mann= 5 ,-1 , 0
  4305.3     .16       0  4454.1      .1       0  4745.1     .16       0
  4992.7     .07       0  4998.7     .16       0
Bank Sta=4960,5426
XS Rating Curve= 0 ,0
Exp/Cntr=0.3,0.1

Type RM Length L Ch R = 1 ,61450   ,504,504,504
BEGIN DESCRIPTION:
WHITE OAK CREEK 99.0
END DESCRIPTION:
XS GIS Cut Line= 2
      2667284.29     10029112.03      2668075.97     10028039.09
#Sta/Elev= 30
  4038.4 2033.04    4069 2030.68  4146.9 2027.61  4284.1    2023  4352.3 2018.95
    4376 2016.78  4555.6 2007.43  4583.1 2004.04  4632.8 2000.62    4691 1998.69
  4806.2 1997.12  4856.3 1995.44  4883.4 1993.71  4912.6 1993.96    4969 1992.46
  4977.4  1991.7  4995.2 1986.04    4998 1985.54  5001.2 1986.04  5005.6 1986.38
  5019.2  1989.7  5042.1 1990.65 5053.98 1995.86  5083.8 2014.02  5105.1 2023.26
  5184.1 2039.04    5228 2042.04    5255 2044.73  5305.2 2046.09  5371.8  2049.3
#Mann= 7 ,-1 , 0
  4038.4     .16       0  4146.9      .1       0  4352.3     .16       0
    4691      .1       0  4995.2     .07       0  5001.2      .1       0
  5019.2     .16       0
Bank Sta=4856.3,5053.98
XS Rating Curve= 0 ,0
Exp/Cntr=0.3,0.1

Type RM Length L Ch R = 1 ,60946   ,549,549,549
BEGIN DESCRIPTION:
WHITE OAK CREEK 98.0
END DESCRIPTION:
XS GIS Cut Line= 2
       2667409.3     10029429.72      2668543.53     10028378.74
#Sta/Elev= 30
  3886.8 2033.58  3918.7 2033.35  3975.4 2029.68  4088.8 2025.69  4244.1 2023.62
  4265.7 2020.77    4294 2018.16    4315 2017.66  4329.2  2015.6  4428.4 2010.85
  4463.6 2010.26  4548.6 2002.59  4633.6 1998.87  4684.7 1999.09  4774.8 1996.52
    4853 1991.95  4888.2 1987.51  4915.8 1989.16  4951.7 1989.15  4998.6 1982.38
  5001.3 1981.88  5004.6 1982.38  5015.8 1984.45  5029.9 1992.26  5071.9 2006.53
    5136 2021.31  5199.5 2026.46  5298.7 2031.14    5348 2035.74  5433.1 2038.58
#Mann= 5 ,-1 , 0
  3886.8     .16       0  4684.7      .1       0  4915.8     .16       0
  4998.6     .07       0  5004.6     .16       0
Bank Sta=4853,5029.9
XS Rating Curve= 0 ,0
Exp/Cntr=0.3,0.1

Type RM Length L Ch R = 1 ,60397   ,582,582,582
BEGIN DESCRIPTION:
WHITE OAK CREEK 96.0
END DESCRIPTION:
XS GIS Cut Line= 3
      2667919.71     10029710.98      2668768.68     10028898.47
      2668924.93     10028492.21
#Sta/Elev= 30
  4069.5 2039.43  4116.2 2035.46  4201.1 2034.43  4307.1 2027.77  4448.6 2022.68
  4540.4 2014.37  4632.6 2009.58    4682 2002.17  4752.7 1996.38  4827.2 1992.87
  4908.4  1987.9  4943.6 1987.08  4984.1 1981.24  4997.2 1978.77    5000 1978.27
  5003.2 1978.77  5035.8 1984.25  5064.1 1982.94  5106.2 1985.57  5134.5 1984.23
  5184.2 1985.76  5205.3 1988.52  5240.8 1993.61  5244.4 1995.52  5249.8 1995.52
  5256.5 1997.95  5292.6 2005.49  5395.8 2018.53  5589.7 2024.86  5679.9 2025.43
#Mann= 5 ,-1 , 0
  4069.5     .16       0  4827.2      .1       0  4984.1     .16       0
  4997.2     .07       0  5003.2     .16       0
Bank Sta=4908.4,5205.3
XS Rating Curve= 0 ,0
Exp/Cntr=0.3,0.1

Type RM Length L Ch R = 1 ,59815   ,560,560,560
BEGIN DESCRIPTION:
WHITE OAK CREEK 95.0
END DESCRIPTION:
XS GIS Cut Line= 4
      2668674.92     10029893.27      2668977.01     10029622.43
      2669128.05     10029091.18      2669055.14      10028513.1
#Sta/Elev= 30
  4390.1 2032.34  4456.1 2028.15  4597.3 2023.19  4668.4 2016.49  4804.9 2008.25
    4859 1999.58  4919.2  1995.5  4960.7 1987.29  4965.9 1988.49 4969.09 1984.37
  4971.2 1981.59  4981.6 1977.05    4992    1974  5001.9 1973.59  5004.7 1973.09
  5007.9 1973.59  5033.6 1976.76  5038.8  1979.5  5072.7 1979.98    5096 1983.14
  5111.8 1983.22  5137.6 1978.58  5158.4 1981.15  5199.9 1982.93  5382.8 1984.25
  5463.1 1994.89  5567.3 2005.49  5668.1 2010.61  5748.7 2016.86  5930.8 2020.74
#Mann= 3 ,-1 , 0
  4390.1     .16       0  5001.9     .07       0  5007.9     .16       0
Bank Sta=4969.09,5382.8
XS Rating Curve= 0 ,0
Exp/Cntr=0.3,0.1

Type RM Length L Ch R = 1 ,59255   ,703,703,703
BEGIN DESCRIPTION:
WHITE OAK CREEK 93.0
END DESCRIPTION:
XS GIS Cut Line= 4
       2669409.3     10030179.75      2669575.97      10029606.8
      2669602.01     10029325.55      2669154.08     10028554.69
#Sta/Elev= 30
  4279.5 2008.77  4314.8  2006.4    4365 2002.08  4431.6 1998.67    4543 1997.96
  4858.6 1990.33  4919.1 1985.73  4951.7 1978.39  4961.1 1976.35  4969.7 1972.74
  4996.8 1971.18  4999.5 1970.68  5002.8 1971.18  5019.9 1974.04  5065.5 1978.51
  5110.3 1979.59  5130.3 1977.82  5162.6 1977.59  5257.2 1979.84  5322.7 1979.06
  5374.7 1980.59  5542.4 1981.86  5565.6 1983.39  5600.3 1989.18  5674.3 1994.67
  5770.4 1999.06  5834.9 2006.15  5930.9  2010.7  5995.5 2016.25  6050.2 2017.82
#Mann= 5 ,-1 , 0
  4279.5     .16       0  4314.8      .1       0  4919.1     .16       0
  4996.8     .07       0  5002.8     .16       0
Bank Sta=4951.7,5065.5
XS Rating Curve= 0 ,0
Exp/Cntr=0.3,0.1

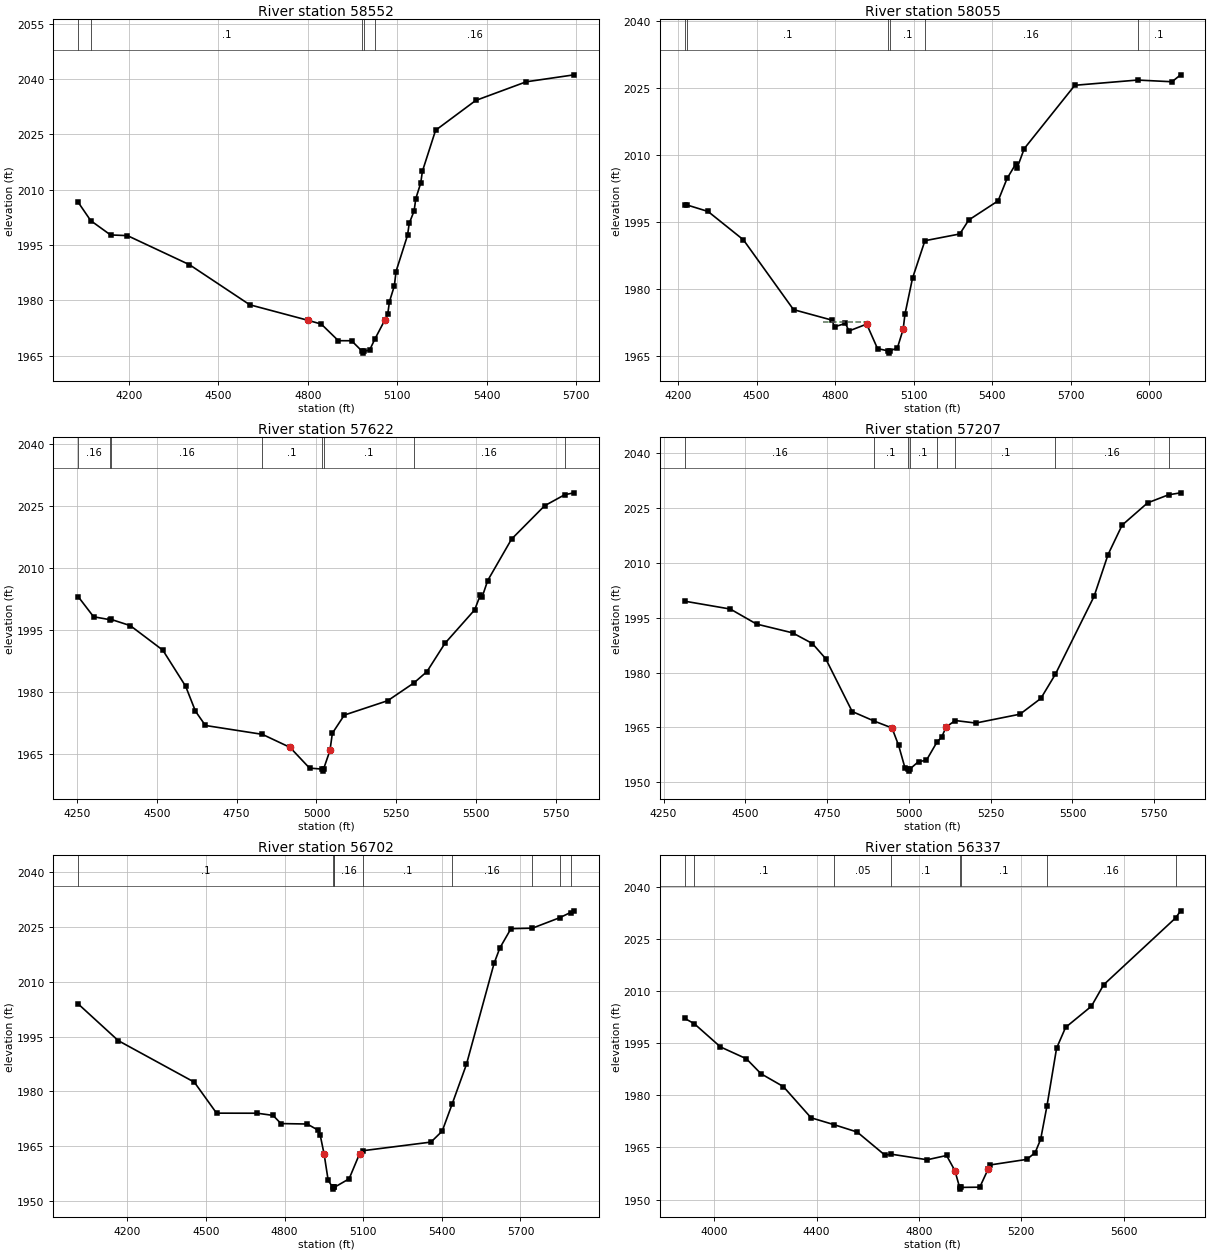
Type RM Length L Ch R = 1 ,58552   ,497,497,497
BEGIN DESCRIPTION:
WHITE OAK CREEK 92.0
END DESCRIPTION:
XS GIS Cut Line= 3
      2669523.93     10030200.53      2670117.64     10029783.89
      2670549.93     10028950.55
#Sta/Elev= 30
  4029.8 2006.55  4071.9 2001.58  4138.3 1997.71  4194.9 1997.53  4403.2 1989.64
  4605.4 1978.78  4800.3 1974.58  4845.4 1973.54  4902.7 1969.04    4947 1969.03
  4982.6 1966.17  4985.3 1965.67  4988.6 1966.17  5007.7  1966.5  5024.5 1969.37
  5059.5 1974.77  5068.4 1976.24  5074.1 1979.62  5090.6 1983.91  5096.2  1987.8
  5134.8 1997.61  5140.4 2000.82  5156.9 2004.24  5162.6 2007.57  5179.1 2011.78
  5184.7 2014.97  5228.9 2026.08  5363.6 2034.17    5533 2039.23  5693.9 2041.12
#Mann= 5 ,-1 , 0
  4029.8     .16       0  4071.9      .1       0  4982.6     .07       0
  4988.6      .1       0  5024.5     .16       0
Bank Sta=4800.3,5059.5
XS Rating Curve= 0 ,0
Exp/Cntr=0.3,0.1

Type RM Length L Ch R = 1 ,58055   ,433,433,433
BEGIN DESCRIPTION:
WHITE OAK CREEK 91.0
END DESCRIPTION:
XS GIS Cut Line= 3
      2669742.63     10030304.72      2670617.64     10029924.51
      2670872.78     10029018.49
#Sta/Elev= 30
  4225.4 1998.87  4234.8 1998.78  4314.6 1997.34  4449.8 1990.99  4641.3 1975.36
  4787.4 1973.02  4798.7 1971.52  4839.8 1972.28  4853.2 1970.58    4921 1972.12
  4962.3 1966.64  5002.9 1966.12  5005.6 1965.62  5008.9 1966.12  5038.3 1966.78
  5060.4 1970.97  5067.2 1974.33  5096.1 1982.39  5143.5 1990.79  5276.8  1992.3
  5310.9 1995.42  5423.3 1999.72  5457.4 2004.72  5491.4 2008.03  5496.6 2007.18
  5523.1 2011.41  5716.4 2025.59  5956.1 2026.76  6087.8 2026.38  6120.7 2027.93
#Mann= 6 ,-1 , 0
  4225.4     .16       0  4234.8      .1       0  5002.9     .07       0
  5008.9      .1       0  5143.5     .16       0  5956.1      .1       0
#XS Ineff= 1 ,-1
 4754.26 4914.77 1972.62
Permanent Ineff=
       F
Bank Sta=4921,5060.4
XS Rating Curve= 0 ,0
Exp/Cntr=0.3,0.1

Type RM Length L Ch R = 1 ,57622   ,415,415,415
BEGIN DESCRIPTION:
WHITE OAK CREEK 90.0
END DESCRIPTION:
XS GIS Cut Line= 3
      2669898.91     10030539.09      2671023.89     10030304.72
      2671392.81     10030138.44
#Sta/Elev= 30
  4253.6 2003.06  4301.8 1998.21  4352.9 1997.51  4357.2 1997.56  4416.6 1996.08
  4518.7 1990.15  4590.2 1981.43  4620.9 1975.42  4652.1 1971.97  4830.5 1969.83
  4917.1 1966.69  4978.4 1961.68  5016.3 1961.45    5019 1960.95  5022.3 1961.45
  5042.3 1965.93  5049.9  1970.1  5087.3 1974.48  5223.5 1977.96  5304.8 1982.21
  5346.1 1984.96  5402.5 1991.79  5495.7 1999.88  5513.3 2003.43  5518.8 2002.89
  5536.4 2006.94  5611.3 2016.96  5714.9 2025.01  5778.3 2027.69  5807.4 2028.13
#Mann= 8 ,-1 , 0
  4253.6     .16       0  4352.9      .1       0  4357.2     .16       0
  4830.5      .1       0  5016.3     .07       0  5022.3      .1       0
  5304.8     .16       0  5778.3      .1       0
Bank Sta=4917.1,5042.3
XS Rating Curve= 0 ,0
Exp/Cntr=0.3,0.1

Type RM Length L Ch R = 1 ,57207   ,505,505,505
BEGIN DESCRIPTION:
WHITE OAK CREEK 89.0
END DESCRIPTION:
XS GIS Cut Line= 4
      2670029.14     10030820.35      2670393.68     10030841.18
      2670883.26     10030757.85      2671383.29     10030335.95
#Sta/Elev= 30
  4314.6 1999.48  4454.2 1997.33  4534.3 1993.23  4644.5 1990.83  4704.9 1987.92
  4745.5  1983.8  4826.6 1969.35  4894.6 1966.71  4948.3 1964.86  4968.6 1960.09
  4988.1 1953.92  4996.1 1953.57  4998.8 1953.07  5002.1 1953.57  5029.5 1955.68
  5053.4 1956.01  5085.5 1960.95  5100.5 1962.41  5113.6  1965.1  5141.5 1966.89
  5204.4  1966.2  5339.6 1968.62  5403.3 1972.92  5447.6  1979.5  5565.9 2000.76
  5608.8 2012.21  5651.7 2020.24  5729.7 2026.33  5793.6 2028.53  5830.6 2029.07
#Mann= 8 ,-1 , 0
  4314.6     .16       0  4894.6      .1       0  4996.1     .07       0
  5002.1      .1       0  5085.5     .16       0  5141.5      .1       0
  5447.6     .16       0  5793.6      .1       0
Bank Sta=4948.3,5113.6
XS Rating Curve= 0 ,0
Exp/Cntr=0.3,0.1

Type RM Length L Ch R = 1 ,56702   ,365,365,365
BEGIN DESCRIPTION:
WHITE OAK CREEK 88.0
END DESCRIPTION:
XS GIS Cut Line= 4
      2670549.96     10031851.56      2671049.93     10031346.39
      2671065.55     10030763.05      2671523.02     10030378.37
#Sta/Elev= 30
  4012.8 2003.93  4165.7  1993.9  4455.7 1982.55  4540.6 1974.08  4696.1 1974.06
  4756.2 1973.46  4786.2 1971.23  4886.3 1971.11  4926.3  1969.5  4936.3 1967.98
 4951.14 1962.78  4966.3 1955.75  4983.3 1953.81  4986.1 1953.31  4989.3 1953.81
  4990.3 1953.82  5046.3 1956.13  5086.3 1962.99  5099.7 1963.82  5358.5 1966.17
  5401.4 1969.17    5439 1976.51  5493.8 1987.39  5599.2    2015  5621.3 2019.23
  5663.7 2024.51  5745.6 2024.65  5849.4  2027.5  5890.9 2028.93  5904.8 2029.39
#Mann= 9 ,-1 , 0
  4012.8      .1       0  4983.3     .07       0  4989.3      .1       0
  4990.3     .16       0  5099.7      .1       0    5439     .16       0
  5745.6      .1       0  5849.4     .16       0  5890.9      .1       0
Bank Sta=4951.14,5086.3
XS Rating Curve= 0 ,0
Exp/Cntr=0.3,0.1

Type RM Length L Ch R = 1 ,56337   ,412,412,412
BEGIN DESCRIPTION:
WHITE OAK CREEK 87.0
END DESCRIPTION:
XS GIS Cut Line= 3
      2670601.98     10031851.62      2671315.55     10031377.64
      2671726.79     10030378.19
#Sta/Elev= 30
  3884.9 2002.17    3922 2000.66  4024.7 1993.95  4125.9 1990.54  4183.1 1986.22
  4270.3 1982.53  4378.5 1973.54  4467.8 1971.57  4558.9 1969.43  4667.1 1962.78
  4692.2 1963.05  4832.3 1961.45    4908 1962.68  4940.4 1958.32    4959 1953.49
  4961.8 1952.99    4965 1953.49  5037.7 1953.55  5070.2 1958.73  5076.7 1959.94
  5221.6 1961.56    5254  1963.5  5275.6 1967.36  5300.2 1976.96  5337.8 1993.59
    5373 1999.58  5473.8 2005.67  5521.7 2011.86  5802.6 2031.09  5822.3 2033.15
#Mann= 8 ,-1 , 0
  3884.9     .16       0    3922      .1       0  4467.8     .05       0
  4692.2      .1       0    4959     .07       0    4965      .1       0
  5300.2     .16       0  5802.6      .1       0
Bank Sta=4940.4,5070.2
XS Rating Curve= 0 ,0
Exp/Cntr=0.3,0.1