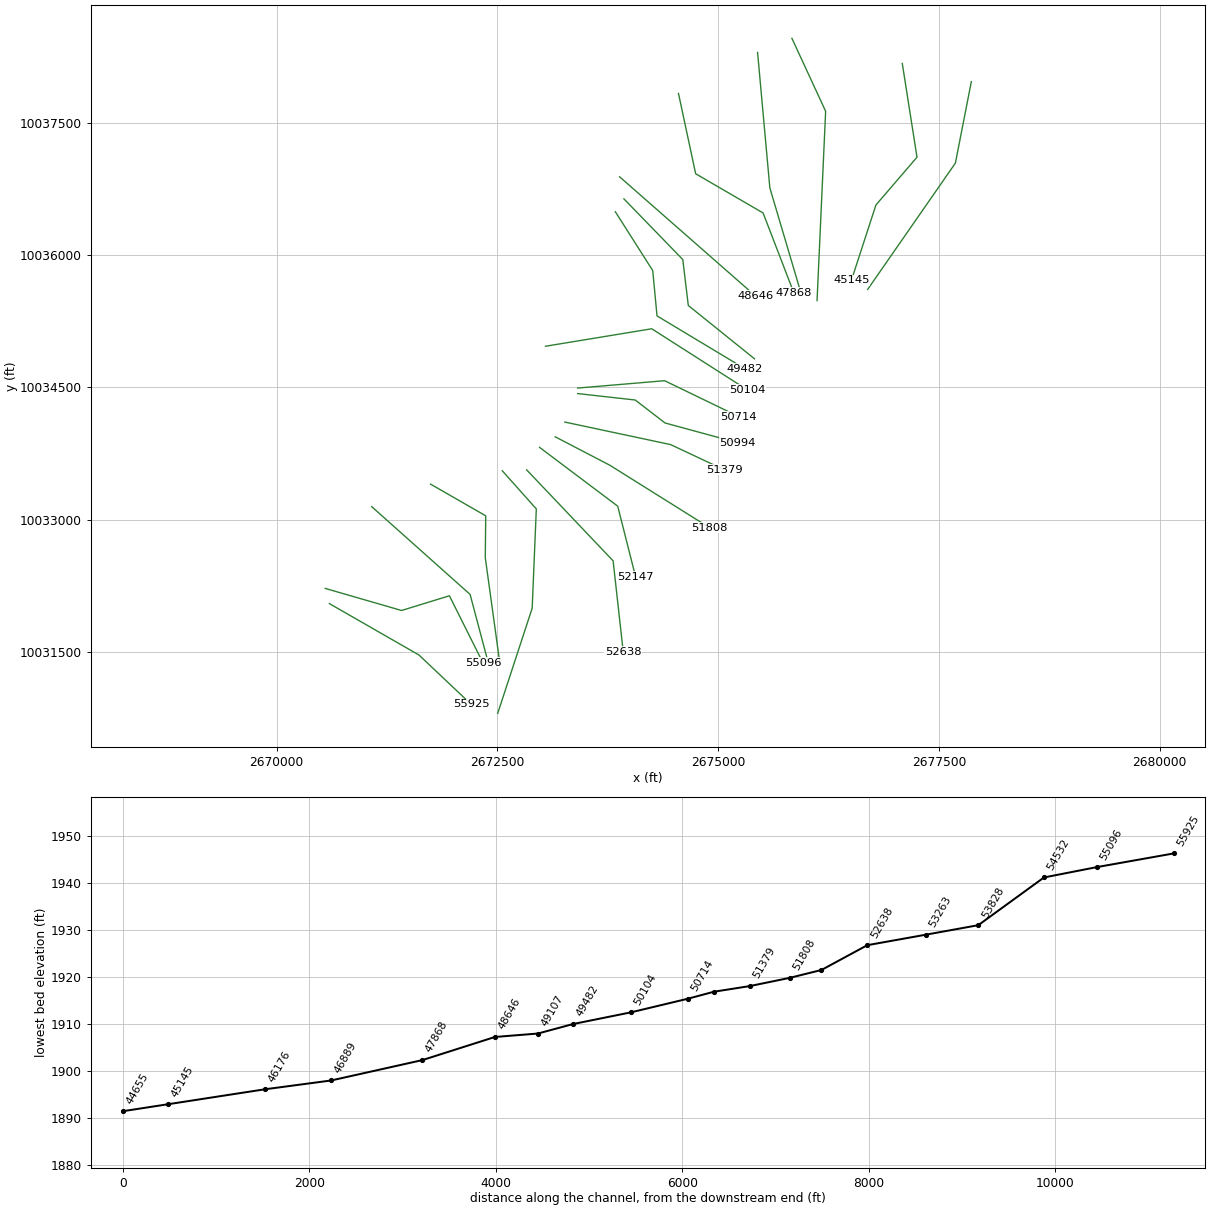
HEC-RAS study WHITE OAK CREEK.prj: WHITE OAK CREEK Base Level Engineering

--- WHITE OAK CREEK.g01 (geometry) --- (continued)

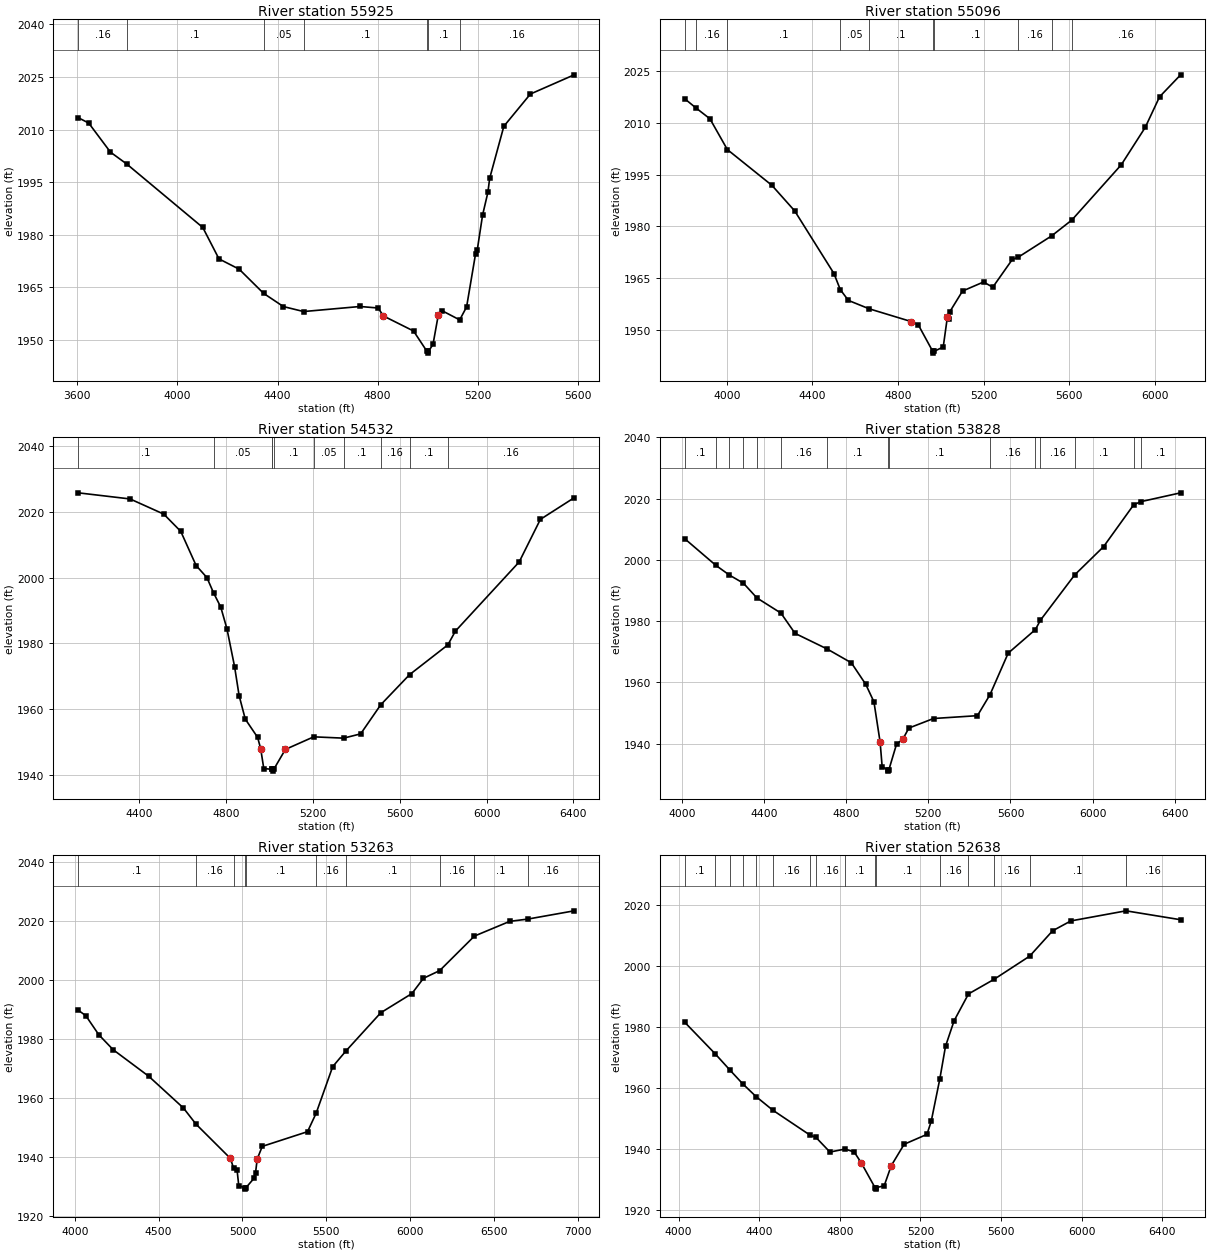
Type RM Length L Ch R = 1 ,55925   ,829,829,829
BEGIN DESCRIPTION:
WHITE OAK CREEK 86.0
END DESCRIPTION:
XS GIS Cut Line= 3
      2670596.76     10032049.54      2671612.43     10031466.18
      2672200.97     10030908.89
#Sta/Elev= 30
  3603.3 2013.39  3645.3 2011.85  3732.1 2003.56  3797.4 2000.16  4101.1 1982.07
  4165.8 1973.11  4246.4 1970.18  4343.9 1963.29  4423.2 1959.51  4504.1 1958.09
  4729.5 1959.53  4801.7  1959.1  4823.2 1956.82  4943.3 1952.54    4997 1946.73
  4999.7 1946.23    5003 1946.73    5021  1948.7  5042.4 1957.18  5056.6 1958.36
  5127.7 1955.71  5155.3 1959.41  5190.9 1974.46  5197.8  1975.6  5219.2 1985.62
  5240.3 1992.05  5247.5 1996.09  5304.2 2010.94  5410.2 2020.13  5585.1 2025.61
#Mann= 7 ,-1 , 0
  3603.3     .16       0  3797.4      .1       0  4343.9     .05       0
  4504.1      .1       0    4997     .07       0    5003      .1       0
  5127.7     .16       0
Bank Sta=4823.2,5042.4
XS Rating Curve= 0 ,0
Exp/Cntr=0.3,0.1

Type RM Length L Ch R = 1 ,55096   ,564,564,564
BEGIN DESCRIPTION:
WHITE OAK CREEK 85.0
END DESCRIPTION:
XS GIS Cut Line= 4
      2670549.93     10032221.39      2671414.51     10031971.39
      2671956.18     10032138.05      2672336.12     10031378.17
#Sta/Elev= 30
  3803.2 2016.95  3853.9 2014.38  3921.1 2011.15  4002.6 2002.23  4210.8 1991.87
  4316.9 1984.49  4500.5 1966.34    4530 1961.69  4567.8 1958.57  4664.5 1956.15
  4861.6 1952.44  4894.3  1951.5  4961.9 1943.81  4964.7 1943.31  4967.9 1943.81
  5010.8  1945.1  5030.3 1953.82  5035.6  1953.2  5042.1 1955.35  5100.9 1961.28
    5199  1963.9  5242.2 1962.39  5333.6 1970.44  5359.6 1971.02  5517.3 1977.26
  5611.5 1981.84  5842.3 1997.83  5954.1 2008.64  6021.2 2017.51  6119.5 2023.87
#Mann= 10 ,-1 , 0
  3803.2      .1       0  3853.9     .16       0  4002.6      .1       0
    4530     .05       0  4664.5      .1       0  4961.9     .07       0
  4967.9      .1       0  5359.6     .16       0  5517.3      .1       0
  5611.5     .16       0
Bank Sta=4861.6,5030.3
XS Rating Curve= 0 ,0
Exp/Cntr=0.3,0.1

Type RM Length L Ch R = 1 ,54532   ,704,704,704
BEGIN DESCRIPTION:
WHITE OAK CREEK 83.0
END DESCRIPTION:
XS GIS Cut Line= 3
      2671075.95     10033148.49      2672190.55     10032153.68
      2672393.47     10031388.83
#Sta/Elev= 30
  4118.6 2025.76  4357.5  2023.9    4513 2019.28  4591.1 2014.04  4661.9 2003.65
  4711.7 1999.98  4742.2 1995.35  4775.5    1991    4804 1984.39  4839.1 1972.92
    4860  1964.1  4888.4 1956.94  4945.3 1951.39  4959.5  1947.9  4973.7 1941.91
  5011.6 1941.67  5013.3 1941.62  5016.1 1941.12  5019.3 1941.62  5073.2 1947.72
  5203.8 1951.55  5341.4 1951.15  5420.1 1952.45  5512.8 1961.31  5645.6 1970.47
  5821.9 1979.52  5856.8 1983.71  6150.5 2004.73  6248.3 2017.69  6403.9 2024.26
#Mann= 10 ,-1 , 0
  4118.6      .1       0  4742.2     .05       0  5011.6      .1       0
  5013.3    .035       0  5019.3      .1       0  5203.8     .05       0
  5341.4      .1       0  5512.8     .16       0  5645.6      .1       0
  5821.9     .16       0
Bank Sta=4959.5,5073.2
XS Rating Curve= 0 ,0
Exp/Cntr=0.3,0.1

Type RM Length L Ch R = 1 ,53828   ,565,565,565
BEGIN DESCRIPTION:
WHITE OAK CREEK 82.0
END DESCRIPTION:
XS GIS Cut Line= 4
      2671742.67     10033403.66      2672367.64      10033044.3
      2672362.43     10032570.35       2672529.1     10031361.99
#Sta/Elev= 30
  4013.8 2006.93  4165.5 1998.22    4232 1995.02  4299.8 1992.39  4365.6 1987.57
  4482.4 1982.62  4551.1    1976  4707.6 1970.89  4825.3 1966.38  4895.3 1959.36
  4935.3 1953.63  4965.3  1940.5  4975.3 1932.45  5002.3 1931.49  5005.1 1930.99
  5008.3 1931.49  5045.3 1939.81  5075.3 1941.35  5105.3 1945.06  5225.5 1948.18
  5439.2 1949.11  5500.3 1955.96  5588.9 1969.53  5721.4 1977.23  5745.9 1980.29
  5912.9 1995.11  6053.2 2004.31  6200.1 2018.01  6235.1 2019.03  6428.5 2021.91
#Mann= 15 ,-1 , 0
  4013.8      .1       0  4165.5     .16       0    4232      .1       0
  4299.8     .16       0  4365.6      .1       0  4482.4     .16       0
  4707.6      .1       0  5002.3     .07       0  5008.3      .1       0
  5500.3     .16       0  5721.4      .1       0  5745.9     .16       0
  5912.9      .1       0  6200.1     .16       0  6235.1      .1       0
Bank Sta=4965.3,5075.3
XS Rating Curve= 0 ,0
Exp/Cntr=0.3,0.1

Type RM Length L Ch R = 1 ,53263   ,625,625,625
BEGIN DESCRIPTION:
WHITE OAK CREEK 80.0
END DESCRIPTION:
XS GIS Cut Line= 4
      2672555.16      10033554.7      2672940.55     10033122.43
      2672893.68     10031997.43      2672503.26     10030805.34
#Sta/Elev= 30
  4019.9 1989.66  4065.3  1987.8    4143 1981.32  4228.3 1976.26  4440.7 1967.25
  4647.8 1956.48  4722.4 1951.03    4928 1939.39  4947.2 1936.03    4968 1935.38
  4978.1 1930.07  5015.1 1929.46  5017.8 1928.96  5021.1 1929.46  5068.1 1932.58
  5078.1 1934.49  5088.1 1939.18  5118.2 1943.46  5388.4 1948.45  5439.8 1954.72
  5538.5 1970.51  5617.4 1975.82  5825.5  1988.8  6011.3 1995.31  6080.3 2000.49
    6177 2003.09  6384.1  2014.8  6595.1  2019.8  6701.8 2020.56  6979.4 2023.37
#Mann= 10 ,-1 , 0
  4019.9      .1       0  4722.4     .16       0  4947.2      .1       0
  5015.1     .07       0  5021.1      .1       0  5439.8     .16       0
  5617.4      .1       0    6177     .16       0  6384.1      .1       0
  6701.8     .16       0
Bank Sta=4928,5088.1
XS Rating Curve= 0 ,0
Exp/Cntr=0.3,0.1

Type RM Length L Ch R = 1 ,52638   ,491,491,491
BEGIN DESCRIPTION:
WHITE OAK CREEK 79.0
END DESCRIPTION:
XS GIS Cut Line= 3
      2672831.15     10033565.17      2673810.35     10032533.89
      2673924.93     10031502.64
#Sta/Elev= 30
  4030.6 1981.62  4180.9  1971.3  4254.3 1965.94  4317.4 1961.43  4384.6 1957.17
  4467.6  1952.7    4654 1944.42  4680.5 1943.83  4751.1 1938.93  4826.5 1939.93
  4871.6 1938.93  4906.8 1935.34  4974.6 1927.24  4977.3 1926.74  4980.6 1927.24
    5020 1927.83  5055.2 1934.46  5119.1 1941.49  5232.3 1944.75  5253.4 1949.06
    5296 1962.97  5324.2 1973.69  5366.7 1982.08  5438.2 1990.92  5565.6 1995.74
  5741.8 2003.35  5855.3 2011.67  5945.9 2014.92  6219.4 2018.24  6490.3 2015.31
#Mann= 16 ,-1 , 0
  4030.6      .1       0  4180.9     .16       0  4254.3     .05       0
  4317.4     .16       0  4384.6     .05       0  4467.6     .16       0
    4654     .05       0  4680.5     .16       0  4826.5      .1       0
  4974.6     .07       0  4980.6      .1       0    5296     .16       0
  5438.2      .1       0  5565.6     .16       0  5741.8      .1       0
  6219.4     .16       0
Bank Sta=4906.8,5055.2
XS Rating Curve= 0 ,0
Exp/Cntr=0.3,0.1

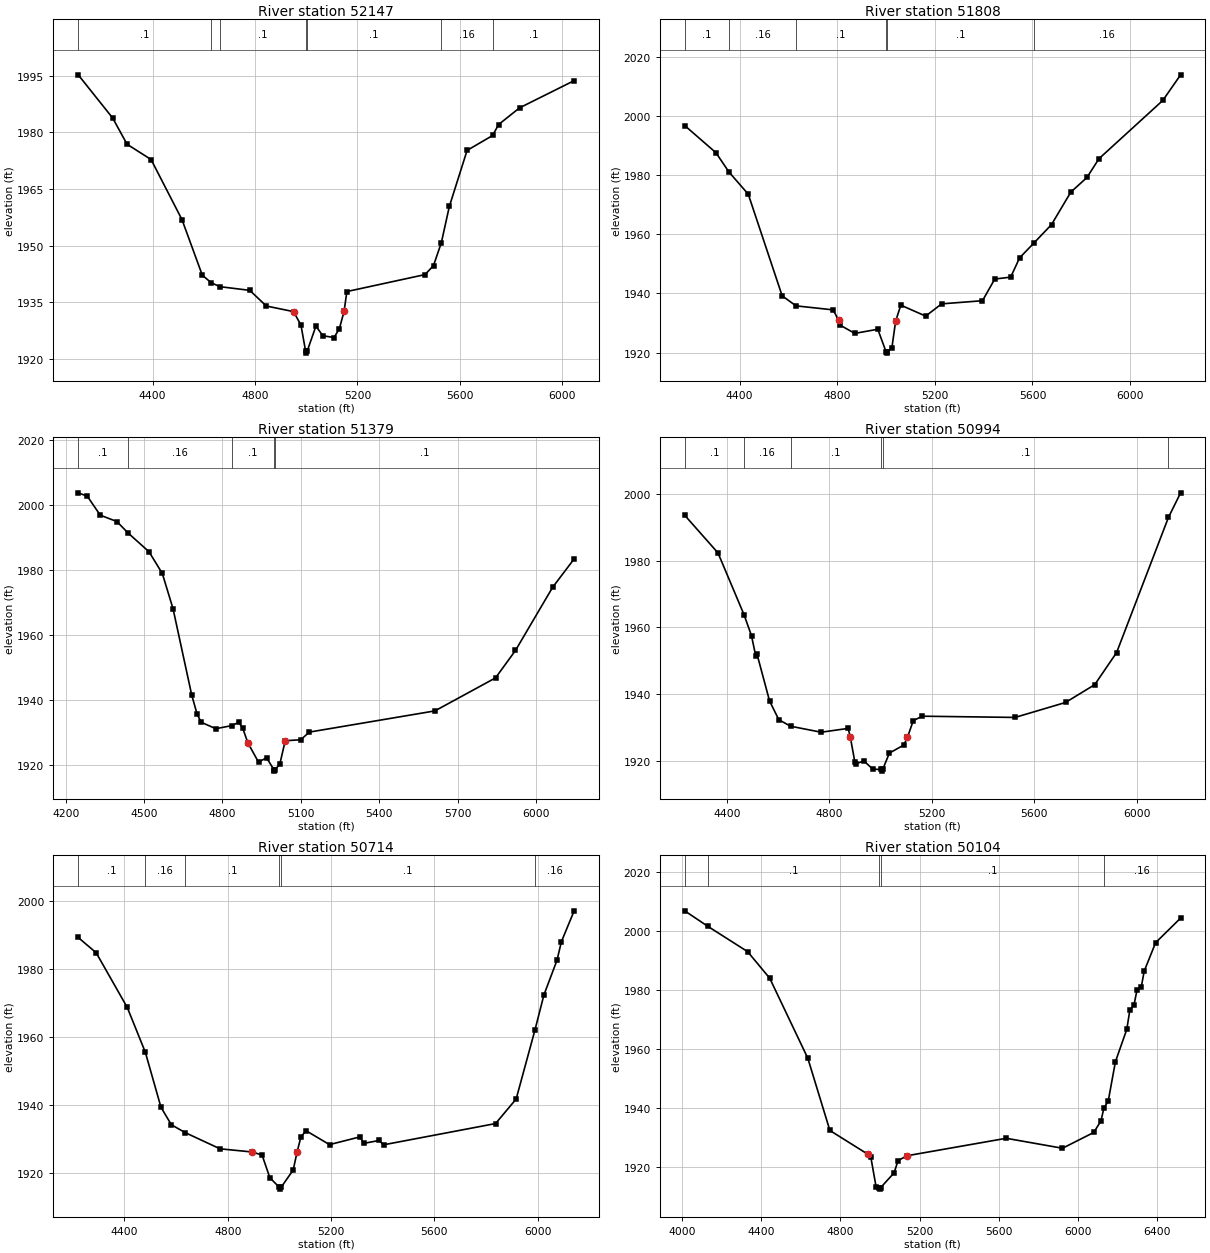
Type RM Length L Ch R = 1 ,52147   ,339,339,339
BEGIN DESCRIPTION:
WHITE OAK CREEK 78.0
END DESCRIPTION:
XS GIS Cut Line= 3
      2672976.99     10033820.36      2673862.43     10033153.68
      2674065.56     10032351.57
#Sta/Elev= 30
    4110 1995.24  4244.5 1983.79  4300.7 1976.84  4394.4 1972.79  4515.2 1956.84
  4594.3 1942.14  4629.7 1940.11  4663.4 1939.09  4779.6 1938.12  4844.2 1933.97
  4950.5 1932.48  4979.5  1928.9  4997.6 1921.98  5000.4 1921.48  5003.6 1921.98
  5037.8 1928.63  5064.9 1926.09  5108.6 1925.61  5129.4 1927.97 5147.73 1932.52
  5158.6  1937.8  5463.9  1942.3  5496.8 1944.69  5527.4 1950.75  5558.7 1960.37
  5627.9 1975.21  5727.5 1979.16  5750.9 1982.07  5832.8 1986.49  6045.8  1993.7
#Mann= 7 ,-1 , 0
    4110      .1       0  4629.7     .16       0  4663.4      .1       0
  4997.6     .07       0  5003.6      .1       0  5527.4     .16       0
  5727.5      .1       0
Bank Sta=4950.5,5147.73
XS Rating Curve= 0 ,0
Exp/Cntr=0.3,0.1

Type RM Length L Ch R = 1 ,51808   ,429,429,429
BEGIN DESCRIPTION:
WHITE OAK CREEK 77.0
END DESCRIPTION:
XS GIS Cut Line= 3
      2673154.14     10033940.12      2673773.89     10033617.22
       2674903.8     10032909.07
#Sta/Elev= 30
  4174.8 1996.85  4302.9 1987.65  4356.2 1981.12  4435.4  1973.6  4574.3 1939.19
  4631.1 1935.81  4783.4 1934.45  4805.5 1930.93  4811.1 1929.32  4871.7 1926.49
  4966.2 1927.89  4999.8 1920.31  5002.5 1919.81  5005.8 1920.31    5024 1921.67
  5039.3 1930.64  5060.5 1936.05  5162.3 1932.34  5227.9 1936.49  5395.2 1937.55
  5445.5 1944.89  5510.7 1945.53  5547.2 1952.06  5605.9 1957.08  5678.1 1963.33
    5757 1974.29  5823.2 1979.26  5872.5 1985.62  6134.2 2005.35  6207.1 2014.01
#Mann= 6 ,-1 , 0
  4174.8      .1       0  4356.2     .16       0  4631.1      .1       0
  4999.8     .07       0  5005.8      .1       0  5605.9     .16       0
Bank Sta=4805.5,5039.3
XS Rating Curve= 0 ,0
Exp/Cntr=0.3,0.1

Type RM Length L Ch R = 1 ,51379   ,385,385,385
BEGIN DESCRIPTION:
WHITE OAK CREEK 76.0
END DESCRIPTION:
XS GIS Cut Line= 3
      2673263.51      10034106.8      2674461.39      10033851.6
      2675070.76     10033565.14
#Sta/Elev= 30
  4247.9 2003.72  4282.6 2002.69  4332.1 1996.85  4396.1 1994.87  4437.9 1991.42
  4518.8 1985.59  4569.7 1978.91  4610.8 1968.05  4682.4 1941.44  4702.8 1935.65
  4718.4 1933.11  4774.4 1931.12  4834.7 1932.05  4861.9 1933.06  4876.7 1931.47
  4897.1 1926.79    4938 1920.81  4968.7 1922.19  4996.4 1918.56  4999.1 1918.06
  5002.4 1918.56  5019.8 1920.33  5040.2 1927.42  5099.5 1927.71  5132.3 1930.07
  5613.1  1936.6  5845.1 1946.76  5921.5 1955.21  6063.8 1974.66    6146 1983.39
#Mann= 5 ,-1 , 0
  4247.9      .1       0  4437.9     .16       0  4834.7      .1       0
  4996.4     .07       0  5002.4      .1       0
Bank Sta=4897.1,5040.2
XS Rating Curve= 0 ,0
Exp/Cntr=0.3,0.1

Type RM Length L Ch R = 1 ,50994   ,280,280,280
BEGIN DESCRIPTION:
WHITE OAK CREEK 75.0
END DESCRIPTION:
XS GIS Cut Line= 4
      2673409.31     10034429.72      2674060.35      10034356.8
      2674398.89     10034096.39      2675221.84     10033872.42
#Sta/Elev= 30
  4235.7 1993.68  4365.7 1982.37  4467.2 1963.83  4496.5  1957.5  4512.8 1951.48
  4517.9 1951.99  4566.9 1937.92    4603  1932.3  4648.8 1930.34  4768.2 1928.54
  4873.7 1929.69  4882.1 1927.03  4899.4  1919.7  4905.7 1919.11  4934.7 1919.93
    4970 1917.44  5002.4 1917.36  5005.1 1916.86  5008.4 1917.36  5034.4 1922.28
  5090.5 1924.68    5105 1927.02  5127.7 1932.03  5163.1 1933.35  5524.8 1932.98
  5721.7 1937.47  5835.7 1942.82    5921 1952.45  6123.3 1993.03  6170.8 2000.41
#Mann= 6 ,-1 , 0
  4235.7      .1       0  4467.2     .16       0  4648.8      .1       0
  5002.4     .07       0  5008.4      .1       0  6123.3     .16       0
Bank Sta=4882.1,5105
XS Rating Curve= 0 ,0
Exp/Cntr=0.3,0.1

Type RM Length L Ch R = 1 ,50714   ,610,610,610
BEGIN DESCRIPTION:
WHITE OAK CREEK 74.0
END DESCRIPTION:
XS GIS Cut Line= 3
      2673409.27     10034492.22      2674393.68     10034575.55
      2675232.22      10034169.3
#Sta/Elev= 30
  4221.3 1989.37  4290.7 1984.89  4411.2 1968.79  4481.2  1955.6  4541.6 1939.45
  4581.8 1934.31  4635.6 1931.98  4770.1 1927.23  4894.6 1926.29    4933 1925.39
  4963.1 1918.72  5000.3 1915.87    5003 1915.37  5006.3 1915.87  5053.5    1921
 5068.18 1926.16  5083.6  1930.8  5103.6 1932.53    5194 1928.46  5312.8 1930.75
  5325.7 1928.81  5386.1 1929.68  5403.1  1928.4  5836.8 1934.65  5916.5 1941.87
    5989 1962.09  6023.9 1972.46  6074.6 1982.68  6091.6 1988.13    6141 1997.21
#Mann= 6 ,-1 , 0
  4221.3      .1       0  4481.2     .16       0  4635.6      .1       0
  5000.3     .07       0  5006.3      .1       0    5989     .16       0
Bank Sta=4894.6,5068.18
XS Rating Curve= 0 ,0
Exp/Cntr=0.3,0.1

Type RM Length L Ch R = 1 ,50104   ,622,622,622
BEGIN DESCRIPTION:
WHITE OAK CREEK 73.0
END DESCRIPTION:
XS GIS Cut Line= 3
      2673044.67     10034966.17      2674247.85      10035164.1
      2675331.17     10034471.39
#Sta/Elev= 30
    4013 2006.91  4130.4 2001.63    4331 1993.06  4442.5 1984.05    4635  1956.9
  4746.5 1932.38  4939.1 1924.28  4953.6 1923.22  4979.6 1913.37  4996.9 1912.98
  4999.6 1912.48  5002.9 1912.98  5070.8 1918.01  5091.1 1922.19  5137.2 1923.82
  5637.4 1929.73  5921.5 1926.35  6079.7 1931.72  6116.1 1935.69  6130.9 1940.06
  6152.4 1942.31  6188.8 1955.71  6246.3 1966.69  6261.5 1973.12  6282.7 1974.99
  6297.9 1980.03    6319 1980.92  6334.3 1986.46  6391.8 1996.09  6518.2 2004.45
#Mann= 5 ,-1 , 0
    4013     .16       0  4130.4      .1       0  4996.9     .07       0
  5002.9      .1       0  6130.9     .16       0
Bank Sta=4939.1,5137.2
XS Rating Curve= 0 ,0
Exp/Cntr=0.3,0.1

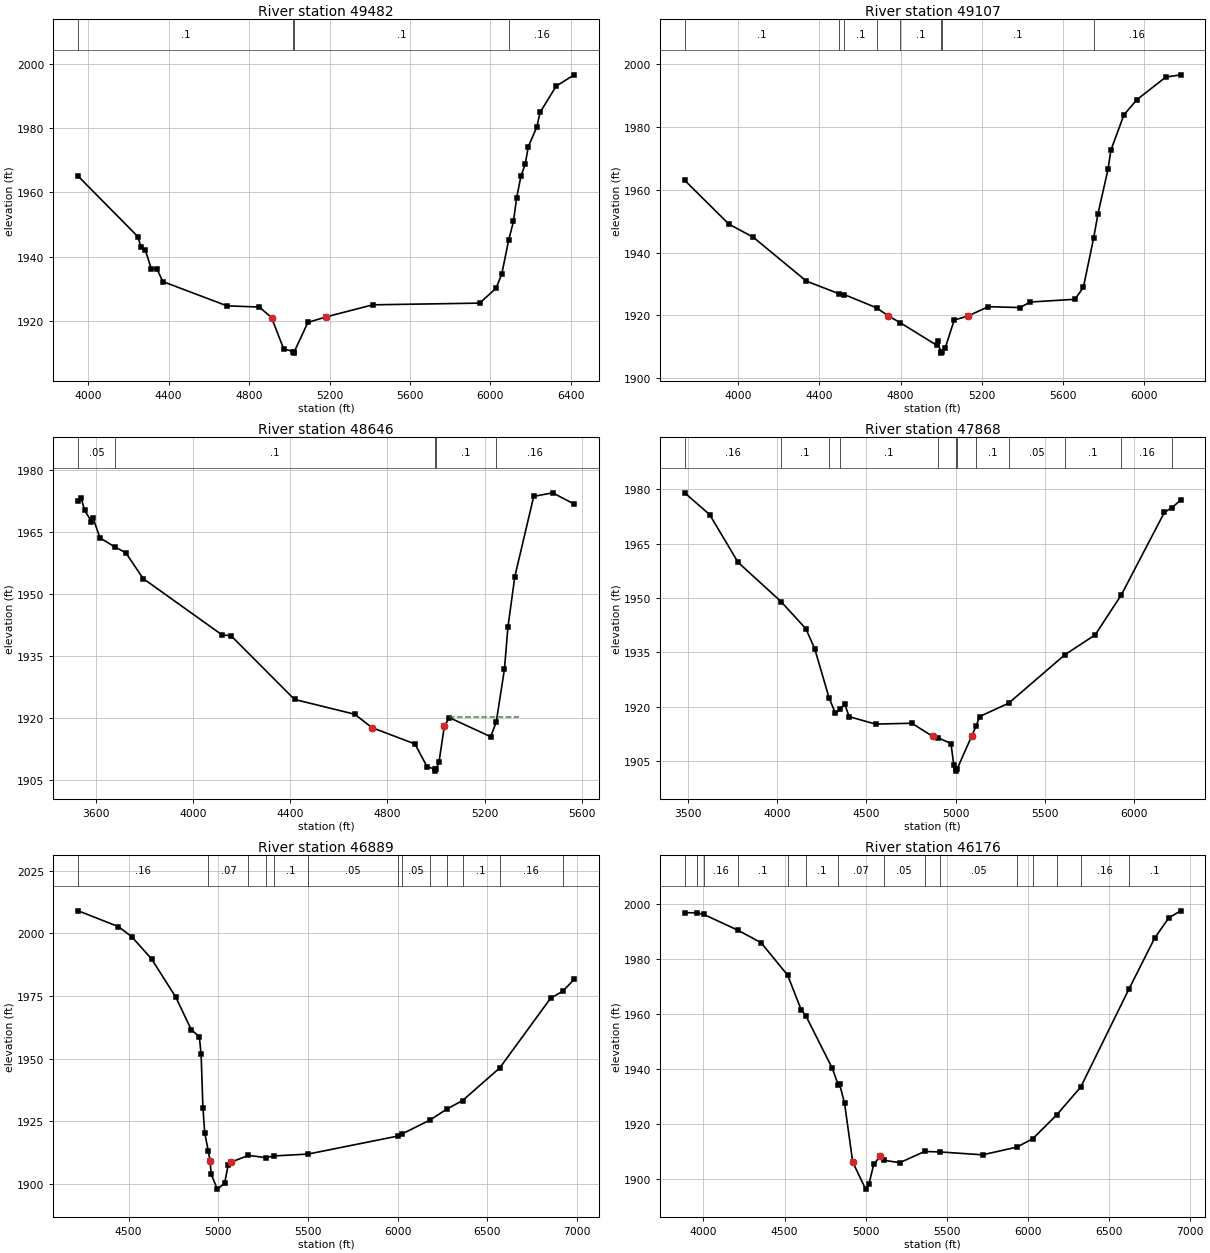
Type RM Length L Ch R = 1 ,49482   ,375,375,375
BEGIN DESCRIPTION:
WHITE OAK CREEK 72.0
END DESCRIPTION:
XS GIS Cut Line= 4
      2673835.52     10036490.48      2674259.13     10035823.82
      2674307.74     10035309.93      2675300.84     10034712.68
#Sta/Elev= 30
    3951 1964.99  4247.4 1946.21  4262.6 1943.07  4283.8  1942.2  4314.3 1936.14
  4341.4 1936.26  4371.9 1932.23  4690.3 1924.69  4851.4 1924.32  4911.7 1921.04
    4972 1911.34  5019.2 1910.49  5021.9 1909.99  5025.2 1910.49  5092.5 1919.53
  5182.9 1921.26    5415 1925.01  5946.4 1925.54  6028.1 1930.19  6056.1 1934.56
  6090.4 1945.13  6114.3 1950.93  6129.9 1958.22  6151.2 1964.95  6172.6 1968.73
  6188.2 1974.22  6230.9 1980.38  6246.4 1984.82  6326.1 1992.98  6415.9 1996.52
#Mann= 4 ,-1 , 0
    3951      .1       0  5019.2     .07       0  5025.2      .1       0
  6090.4     .16       0
Bank Sta=4911.7,5182.9
XS Rating Curve= 0 ,0
Exp/Cntr=0.3,0.1

Type RM Length L Ch R = 1 ,49107   ,461,461,461
BEGIN DESCRIPTION:
WHITE OAK CREEK 71.0
END DESCRIPTION:
XS GIS Cut Line= 4
      2673932.73     10036636.33      2674599.41     10035948.82
      2674661.91     10035427.99      2675411.89     10034823.83
#Sta/Elev= 30
  3735.7 1962.99  3953.7 1949.05  4073.9 1944.87  4335.7 1930.91  4497.2 1926.87
  4522.8 1926.62  4682.4 1922.39  4738.8 1919.86  4798.6 1917.67  4977.4 1910.52
  4982.4 1911.79  4997.7 1908.48  5000.4 1907.98  5003.7 1908.48  5020.8  1909.7
  5064.6 1918.52  5131.6 1919.77  5232.7 1922.76  5389.5 1922.49  5439.1 1924.25
  5659.8 1925.12  5701.5 1928.91  5752.1  1944.6  5773.4 1952.34    5823  1966.5
  5837.4 1972.63  5901.4 1983.83  5965.3 1988.66  6107.7 1995.85    6181 1996.58
#Mann= 8 ,-1 , 0
  3735.7      .1       0  4497.2     .16       0  4522.8      .1       0
  4682.4     .16       0  4798.6      .1       0  4997.7     .07       0
  5003.7      .1       0  5752.1     .16       0
Bank Sta=4738.8,5131.6
XS Rating Curve= 0 ,0
Exp/Cntr=0.3,0.1

Type RM Length L Ch R = 1 ,48646   ,778,778,778
BEGIN DESCRIPTION:
WHITE OAK CREEK 70.0
END DESCRIPTION:
XS GIS Cut Line= 2
      2673884.15      10036886.3      2675418.83     10035539.11
#Sta/Elev= 30
  3526.5 1972.55  3538.4 1973.38  3552.7 1970.33  3581.1 1967.61  3587.8 1968.43
  3616.3 1963.64  3677.7 1961.46  3722.5 1960.05  3793.7 1953.83  4119.2 1940.17
  4155.2 1940.02  4417.1 1924.59  4664.8 1921.01    4736 1917.77  4913.4 1913.81
  4962.8 1908.32  4994.9 1907.75  4997.6 1907.25  5000.9 1907.75  5012.1 1909.45
  5033.9 1918.05  5054.8 1920.19  5224.7 1915.57  5247.6 1919.07  5281.6 1931.91
  5295.8 1942.02  5324.3 1954.29  5402.1 1973.69  5479.9 1974.55  5568.6 1971.84
#Mann= 5 ,-1 , 0
  3526.5     .05       0  3677.7      .1       0  4994.9     .07       0
  5000.9      .1       0  5247.6     .16       0
#XS Ineff= 1 ,-1
  5055.4 5342.33 1920.33
Permanent Ineff=
       F
Bank Sta=4736,5033.9
XS Rating Curve= 0 ,0
Exp/Cntr=0.3,0.1

Type RM Length L Ch R = 1 ,47868   ,979,979,979
BEGIN DESCRIPTION:
WHITE OAK CREEK 68.0
END DESCRIPTION:
XS GIS Cut Line= 4
      2674550.79      10037830.8      2674745.24     10036921.04
      2675509.13      10036476.6      2675856.34     10035573.85
#Sta/Elev= 30
  3480.8 1978.95    3621 1972.95  3780.1 1959.82  4020.9 1949.02  4160.6 1941.53
  4210.1 1936.02  4290.9 1922.46  4326.6 1918.21  4354.2 1919.39  4377.7 1920.94
  4402.9 1917.34  4551.4 1915.29  4754.9 1915.52  4872.4 1911.88  4899.8 1911.56
  4974.2 1909.94  4989.9 1904.08  5001.9 1902.84  5004.6 1902.34  5007.9 1902.84
  5091.7 1912.14  5114.5 1914.64  5134.7 1917.37  5297.9 1921.05  5613.6  1934.4
    5783 1939.85  5929.7 1950.86  6170.8 1973.55    6214 1974.91  6262.1 1976.91
#Mann= 12 ,-1 , 0
  3480.8     .16       0  4020.9      .1       0  4290.9     .05       0
  4354.2      .1       0  4899.8     .05       0  5001.9    .035       0
  5007.9     .05       0  5114.5      .1       0  5297.9     .05       0
  5613.6      .1       0  5929.7     .16       0    6214      .1       0
Bank Sta=4872.4,5091.7
XS Rating Curve= 0 ,0
Exp/Cntr=0.3,0.1

Type RM Length L Ch R = 1 ,46889   ,713,713,713
BEGIN DESCRIPTION:
WHITE OAK CREEK 67.0
END DESCRIPTION:
XS GIS Cut Line= 3
      2675446.63     10038296.01      2675585.52     10036761.32
      2675932.58     10035588.24
#Sta/Elev= 30
  4219.4 2008.94  4442.6 2002.67  4517.5 1998.64  4628.2 1989.77  4763.9 1974.45
  4849.6 1961.57  4894.4 1958.75  4904.5 1951.68  4914.5 1930.48  4924.5 1920.42
  4944.6 1913.15  4954.7 1909.03  4960.3 1904.01  4994.6 1898.01    5035  1900.3
  5055.1 1907.56    5071 1908.78  5168.5 1911.45  5266.9 1910.57  5309.8 1911.23
    5501 1911.99  6000.2 1919.15  6026.3 1920.09  6179.3  1925.5  6275.3 1929.97
  6361.6 1933.31    6569 1946.32  6852.8 1974.14  6919.4 1976.84  6983.7 1981.61
#Mann= 13 ,-1 , 0
  4219.4     .16       0  4944.6     .07       0  5168.5      .1       0
  5266.9     .05       0  5309.8      .1       0    5501     .05       0
  6000.2      .1       0  6026.3     .05       0  6179.3      .1       0
  6275.3     .05       0  6361.6      .1       0    6569     .16       0
  6919.4      .1       0
Bank Sta=4954.7,5071
XS Rating Curve= 0 ,0
Exp/Cntr=0.3,0.1

Type RM Length L Ch R = 1 ,46176   ,1031,1031,1031
BEGIN DESCRIPTION:
WHITE OAK CREEK 65.0
END DESCRIPTION:
XS GIS Cut Line= 3
      2675835.51     10038455.78      2676217.46     10037629.37
      2676120.24     10035483.58
#Sta/Elev= 30
    3884    1997  3957.4 1996.99  4000.7 1996.41  4213.1 1990.58  4355.1 1986.07
  4518.7 1974.22  4602.3 1961.62  4630.3 1959.48  4794.4 1940.22  4831.7 1934.02
  4840.1 1934.32  4870.1 1927.42  4920.2    1906    5000 1896.13  5020.3 1897.98
  5050.3 1905.27  5090.3 1908.09  5110.4 1906.68  5210.5 1905.78  5363.7 1909.88
  5457.9  1909.7    5721 1908.65  5931.8 1911.45  6030.5  1914.5  6177.4 1923.17
  6326.5 1933.39  6622.5    1969  6782.1 1987.72  6869.2  1995.1  6942.4 1997.69
#Mann= 15 ,-1 , 0
    3884     .16       0  3957.4      .1       0  4000.7     .16       0
  4213.1      .1       0  4518.7     .05       0  4630.3      .1       0
  4831.7     .07       0  5110.4     .05       0  5363.7      .1       0
  5457.9     .05       0  5931.8      .1       0  6030.5     .05       0
  6177.4      .1       0  6326.5     .16       0  6622.5      .1       0
Bank Sta=4920.2,5090.3
XS Rating Curve= 0 ,0
Exp/Cntr=0.3,0.1

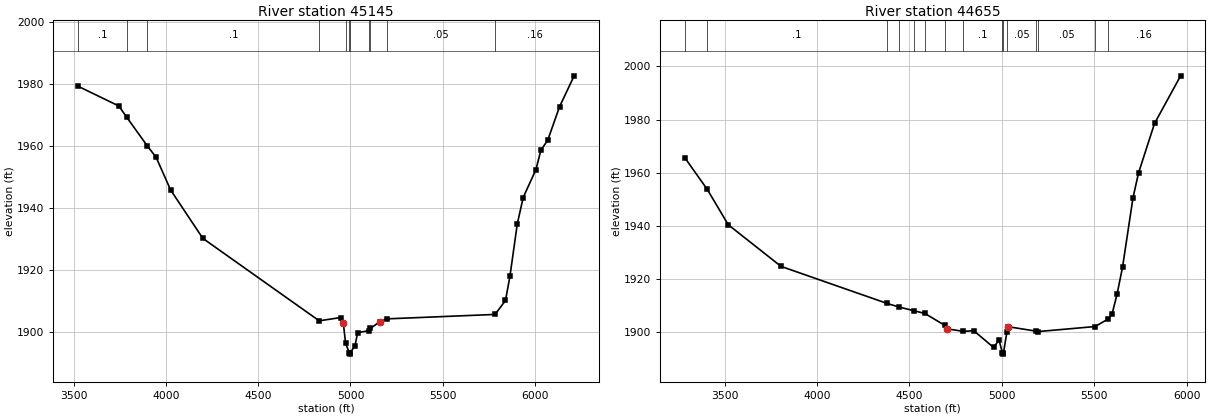
Type RM Length L Ch R = 1 ,45145   ,490,490,490
BEGIN DESCRIPTION:
WHITE OAK CREEK 63.0
END DESCRIPTION:
XS GIS Cut Line= 4
      2677085.52     10038171.06      2677252.19     10037108.54
      2676786.91     10036566.87      2676509.12     10035712.69
#Sta/Elev= 30
  3524.5 1979.26  3744.5 1972.93  3786.5 1969.38  3898.8 1960.07  3946.9 1956.37
  4025.2 1945.87    4200 1930.27  4830.7 1903.71  4946.8 1904.77    4961 1903.06
  4973.7 1896.46  4993.2 1893.48  4995.9 1892.98  4999.2 1893.48  5024.7 1895.73
    5039 1899.92  5100.9 1900.53  5108.5 1901.28  5159.7 1903.46  5197.6 1904.34
  5783.6 1905.77  5840.2 1910.26  5864.2 1918.02  5904.1 1934.94  5936.1 1943.44
  6005.2 1952.45  6031.9 1958.67  6069.1  1961.9    6133 1972.68  6212.3 1982.64
#Mann= 11 ,-1 , 0
  3524.5      .1       0  3786.5     .16       0  3898.8      .1       0
  4830.7     .05       0  4973.7      .1       0  4993.2     .07       0
  4999.2      .1       0  5100.9     .05       0  5108.5      .1       0
  5197.6     .05       0  5783.6     .16       0
Bank Sta=4961,5159.7
XS Rating Curve= 0 ,0
Exp/Cntr=0.3,0.1

Type RM Length L Ch R = 1 ,44655   ,615,615,615
BEGIN DESCRIPTION:
WHITE OAK CREEK 62.0
END DESCRIPTION:
XS GIS Cut Line= 3
      2677867.63     10037965.29      2677687.08      10037041.7
      2676694.04     10035611.16
#Sta/Elev= 30
  3284.5 1965.65  3406.8 1953.61  3520.4 1940.28  3805.7 1924.58  4379.7  1910.6
  4442.2 1909.29  4527.4  1907.8  4583.9 1906.82  4690.2 1902.38  4704.7    1901
  4791.8 1900.08  4847.9 1900.32  4955.2 1894.01  4984.9 1896.79  5002.9 1891.98
  5005.6 1891.48  5008.9 1891.98  5027.4 1899.82  5035.6 1901.81  5184.6 1900.16
  5197.3    1900  5503.8 1901.88  5571.8 1904.59  5596.2 1906.59  5623.2 1914.11
  5652.9  1924.3  5709.6 1950.56  5739.4 1959.85  5825.8  1978.5    5967 1996.48
#Mann= 15 ,-1 , 0
  3284.5     .16       0  3406.8      .1       0  4379.7     .05       0
  4442.2      .1       0  4527.4     .05       0  4583.9      .1       0
  4690.2     .16       0  4791.8      .1       0  5002.9     .07       0
  5008.9      .1       0  5027.4     .05       0  5184.6      .1       0
  5197.3     .05       0  5503.8      .1       0  5571.8     .16       0
Bank Sta=4704.7,5035.6
XS Rating Curve= 0 ,0
Exp/Cntr=0.3,0.1