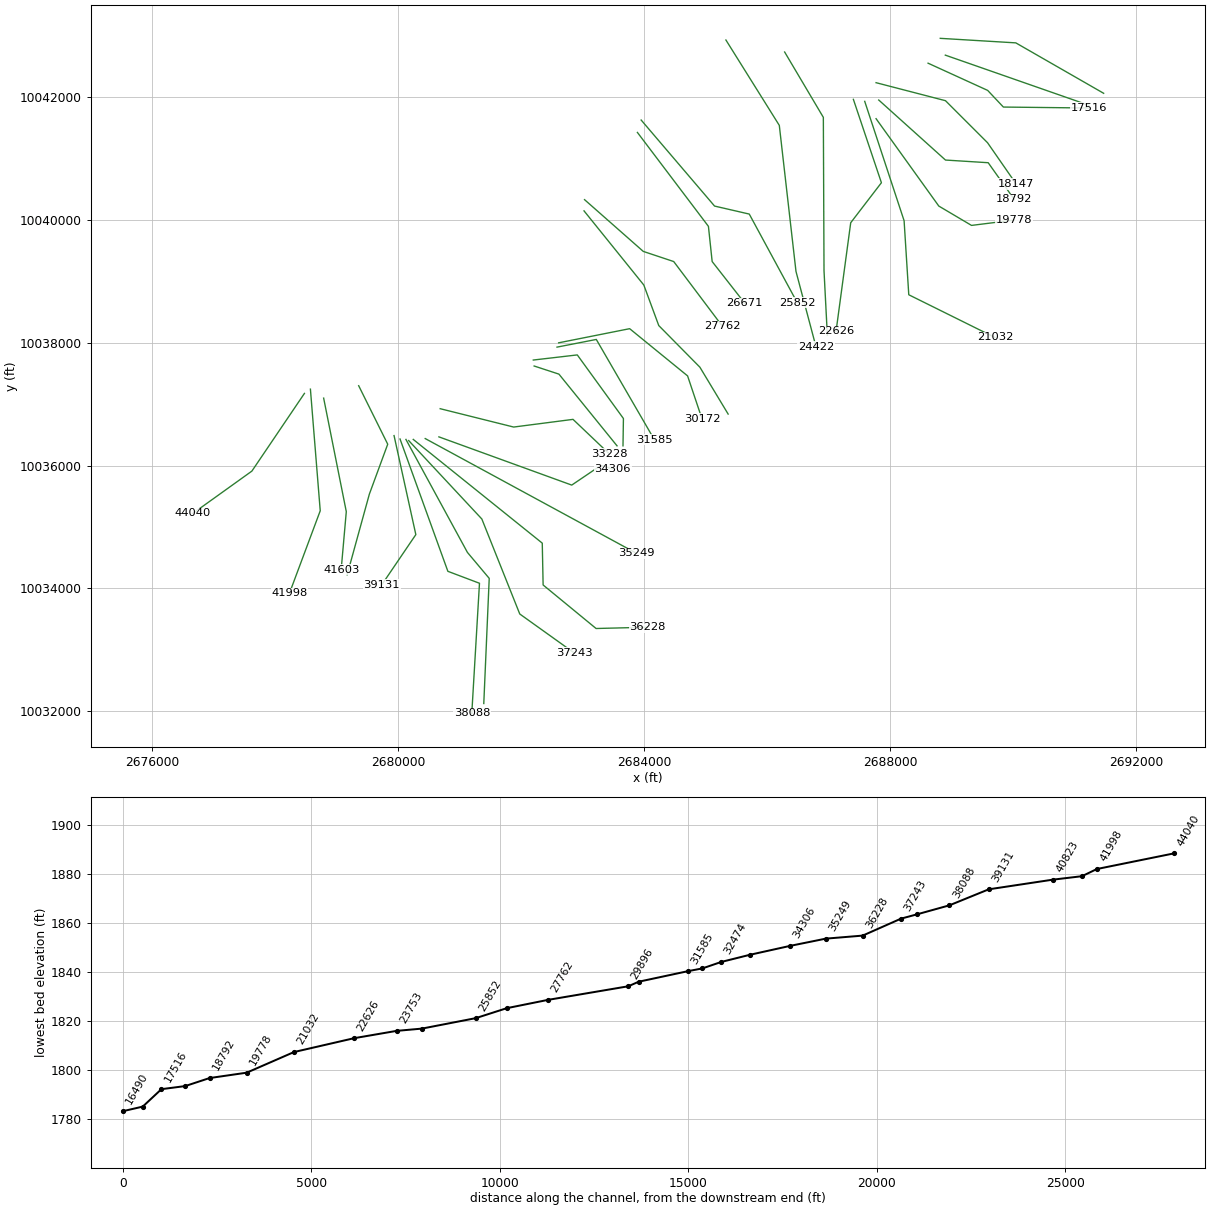
HEC-RAS study WHITE OAK CREEK.prj: WHITE OAK CREEK Base Level Engineering

--- WHITE OAK CREEK.g01 (geometry) --- (continued)

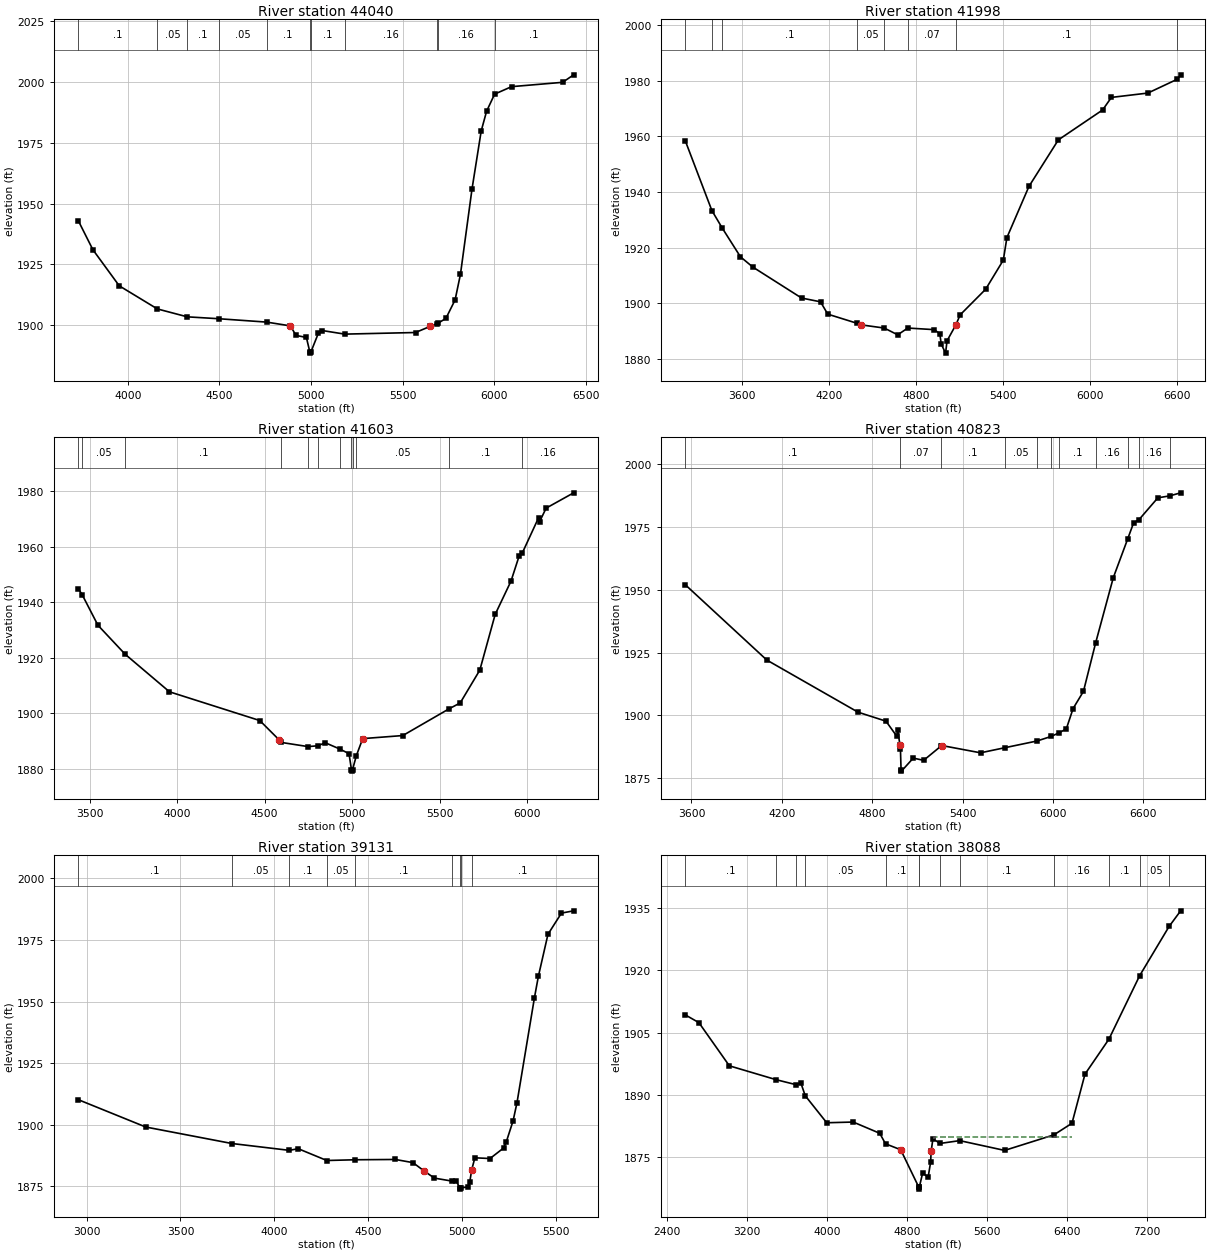
Type RM Length L Ch R = 1 ,44040   ,2042,2042,2042
BEGIN DESCRIPTION:
WHITE OAK CREEK 61.0
END DESCRIPTION:
XS GIS Cut Line= 3
      2678478.75     10037173.64      2677624.58     10035909.76
      2676666.23     10035222.25
#Sta/Elev= 30
  3729.4 1942.95    3809 1931.04  3952.9 1916.21    4161 1906.71  4324.5 1903.46
  4495.2 1902.69  4757.6  1901.3    4888 1899.74  4917.8 1895.83  4974.8    1895
  4993.6 1889.05  4996.3 1888.55  4999.6 1889.05  5040.7 1896.81  5061.7 1897.83
  5184.2 1896.36  5570.8 1897.02  5650.6 1899.54  5690.1 1900.69  5691.9 1900.77
  5736.6 1902.81  5786.9 1910.42  5816.2 1920.97    5879 1955.86  5929.4 1979.82
  5958.9 1987.95  6002.7 1994.97  6095.2 1998.04  6373.9 1999.82  6434.3  2002.9
#Mann= 11 ,-1 , 0
  3729.4      .1       0    4161     .05       0  4324.5      .1       0
  4495.2     .05       0  4757.6      .1       0  4993.6     .07       0
  4999.6      .1       0  5184.2     .16       0  5690.1      .1       0
  5691.9     .16       0  6002.7      .1       0
Bank Sta=4888,5650.6
XS Rating Curve= 0 ,0
Exp/Cntr=0.3,0.1

Type RM Length L Ch R = 1 ,41998   ,395,395,395
BEGIN DESCRIPTION:
WHITE OAK CREEK 58.0
END DESCRIPTION:
XS GIS Cut Line= 3
      2678575.97     10037243.07      2678735.69     10035263.92
      2678235.69     10033923.63
#Sta/Elev= 30
  3211.1 1958.43  3394.5 1933.37  3465.5 1927.12  3591.7 1916.75  3677.1 1913.07
    4013 1901.96  4143.5  1900.6  4193.6 1896.17    4393 1892.93  4421.2 1892.34
  4582.8 1891.18    4676 1888.75  4745.4 1891.18    4926 1890.61  4966.1  1889.2
  4976.2 1885.41    5006 1882.17  5016.3 1886.62  5076.5 1892.26  5106.6 1895.92
  5282.3 1905.11  5404.2 1915.57  5429.1 1923.67  5581.1 1942.06  5783.9 1958.77
    6089 1969.51  6149.7 1974.02  6401.1 1975.58    6605 1980.57  6627.2 1982.13
#Mann= 8 ,-1 , 0
  3211.1      .1       0  3394.5     .05       0  3465.5      .1       0
    4393     .05       0  4582.8      .1       0  4745.4     .07       0
  5076.5      .1       0    6605     .16       0
Bank Sta=4421.2,5076.5
XS Rating Curve= 0 ,0
Exp/Cntr=0.3,0.1

Type RM Length L Ch R = 1 ,41603   ,780,780,780
BEGIN DESCRIPTION:
WHITE OAK CREEK 57.0
END DESCRIPTION:
XS GIS Cut Line= 3
      2678791.26     10037097.21       2679159.3     10035250.03
      2679076.11     10034307.18
#Sta/Elev= 30
  3435.2 1944.83  3457.8 1942.61  3547.3 1931.69  3702.7 1921.27    3956 1907.76
  4471.9 1897.43  4580.8 1890.59  4595.6 1889.55  4747.7 1888.06  4803.6 1888.35
  4845.9 1889.45  4927.9 1887.22  4981.8 1885.52  4995.8 1879.74  4998.6 1879.24
  5001.8 1879.74  5023.8 1884.81    5060 1890.93  5289.1 1892.03  5553.8 1901.66
  5616.9 1903.75    5729 1915.55  5816.9  1935.6  5907.3 1947.57  5953.2  1956.5
  5972.1 1957.72  6065.3 1970.41  6070.3  1968.9    6108  1973.8  6265.2  1979.3
#Mann= 12 ,-1 , 0
  3435.2      .1       0  3457.8     .05       0  3702.7      .1       0
  4595.6     .05       0  4747.7      .1       0  4803.6     .05       0
  4927.9      .1       0  4995.8     .07       0  5001.8      .1       0
  5023.8     .05       0  5553.8      .1       0  5972.1     .16       0
Bank Sta=4580.8,5060
XS Rating Curve= 0 ,0
Exp/Cntr=0.3,0.1

Type RM Length L Ch R = 1 ,40823   ,1692,1692,1692
BEGIN DESCRIPTION:
WHITE OAK CREEK 56.0
END DESCRIPTION:
XS GIS Cut Line= 4
      2679360.67     10037298.69      2679832.91     10036347.26
       2679534.3     10035534.76      2679173.32     10034222.73
#Sta/Elev= 30
    3559 1951.98    4100 1922.02  4705.7 1901.27  4891.3 1897.69    4964 1891.61
  4969.3 1894.14 4983.52 1888.39  4987.2 1886.76  4991.5 1878.31  4994.2 1877.81
  5072.4 1882.99  5141.5 1882.11  5258.1 1887.85  5264.2 1887.97    5519  1885.1
  5679.1 1887.11  5894.5 1889.81  5988.6 1891.63  6042.8 1893.13  6088.7 1894.63
  6133.5 1902.72  6202.3 1909.55  6283.8 1928.97  6400.6 1954.83    6495 1970.05
  6535.4 1976.62    6571 1977.88  6696.2 1986.57  6774.4 1987.34  6847.6 1988.56
#Mann= 11 ,-1 , 0
    3559      .1       0 4983.52     .07       0  5258.1      .1       0
  5679.1     .05       0  5894.5      .1       0  5988.6     .05       0
  6042.8      .1       0  6283.8     .16       0    6495      .1       0
    6571     .16       0  6774.4      .1       0
Bank Sta=4983.52,5264.2
XS Rating Curve= 0 ,0
Exp/Cntr=0.3,0.1

Type RM Length L Ch R = 1 ,39131   ,1043,1043,1043
BEGIN DESCRIPTION:
WHITE OAK CREEK 55.0
END DESCRIPTION:
XS GIS Cut Line= 3
      2679935.78     10036487.45      2680289.95     10034876.34
      2679735.01      10034057.8
#Sta/Elev= 30
  2955.8 1910.19  3315.2 1899.09  3773.8  1892.4    4080 1889.62  4126.8  1890.3
  4279.5  1885.5  4430.4  1885.8  4644.8 1885.92  4738.5 1884.63  4795.5 1881.38
  4852.4 1878.35  4945.7 1877.15  4969.1 1877.25  4987.1 1874.38  4989.9 1873.88
  4993.1 1874.38  5032.1 1874.79    5041 1876.78  5051.2 1881.71  5068.1  1886.6
  5148.8  1886.3  5220.7 1890.55  5235.7 1893.13  5271.6 1901.59  5292.6 1909.02
  5385.5 1951.63  5406.5 1960.33  5457.4 1977.33  5529.3 1985.94  5594.3 1986.86
#Mann= 9 ,-1 , 0
  2955.8      .1       0  3773.8     .05       0    4080      .1       0
  4279.5     .05       0  4430.4      .1       0  4945.7     .16       0
  4987.1     .07       0  4993.1     .16       0  5051.2      .1       0
Bank Sta=4795.5,5051.2
XS Rating Curve= 0 ,0
Exp/Cntr=0.3,0.1

Type RM Length L Ch R = 1 ,38088   ,847,847,847
BEGIN DESCRIPTION:
WHITE OAK CREEK 54.0
END DESCRIPTION:
XS GIS Cut Line= 4
      2680032.99     10036431.92      2680810.78     10034279.11
      2681324.67     10034084.67      2681199.73      10031967.7
#Sta/Elev= 30
  2581.8 1909.24  2718.1 1907.37  3022.9 1896.99  3493.6 1893.64  3688.7 1892.47
  3738.8 1892.86  3782.5  1889.8  3997.6  1883.3  4262.9 1883.47  4528.3 1880.77
  4586.1 1878.24  4738.3 1876.81  4918.8 1867.84  4921.5 1867.34  4924.8 1867.84
  4957.9 1871.21  5012.9 1870.22  5037.7 1873.79  5043.1 1876.45  5060.8 1879.43
  5133.2 1878.33  5329.2    1879  5778.5 1876.65  6272.2 1880.39    6453 1883.18
  6583.2 1894.99  6822.3 1903.38  7130.6 1918.67  7425.4 1930.51  7540.9 1934.26
#Mann= 13 ,-1 , 0
  2581.8      .1       0  3493.6     .05       0  3688.7      .1       0
  3782.5     .05       0  4586.1      .1       0  4918.8     .07       0
  4924.8      .1       0  5133.2     .16       0  5329.2      .1       0
  6272.2     .16       0  6822.3      .1       0  7130.6     .05       0
  7425.4      .1       0
#XS Ineff= 1 ,-1
 5068.98 6456.78 1879.82
Permanent Ineff=
       F
Bank Sta=4738.3,5043.1
XS Rating Curve= 0 ,0
Exp/Cntr=0.3,0.1

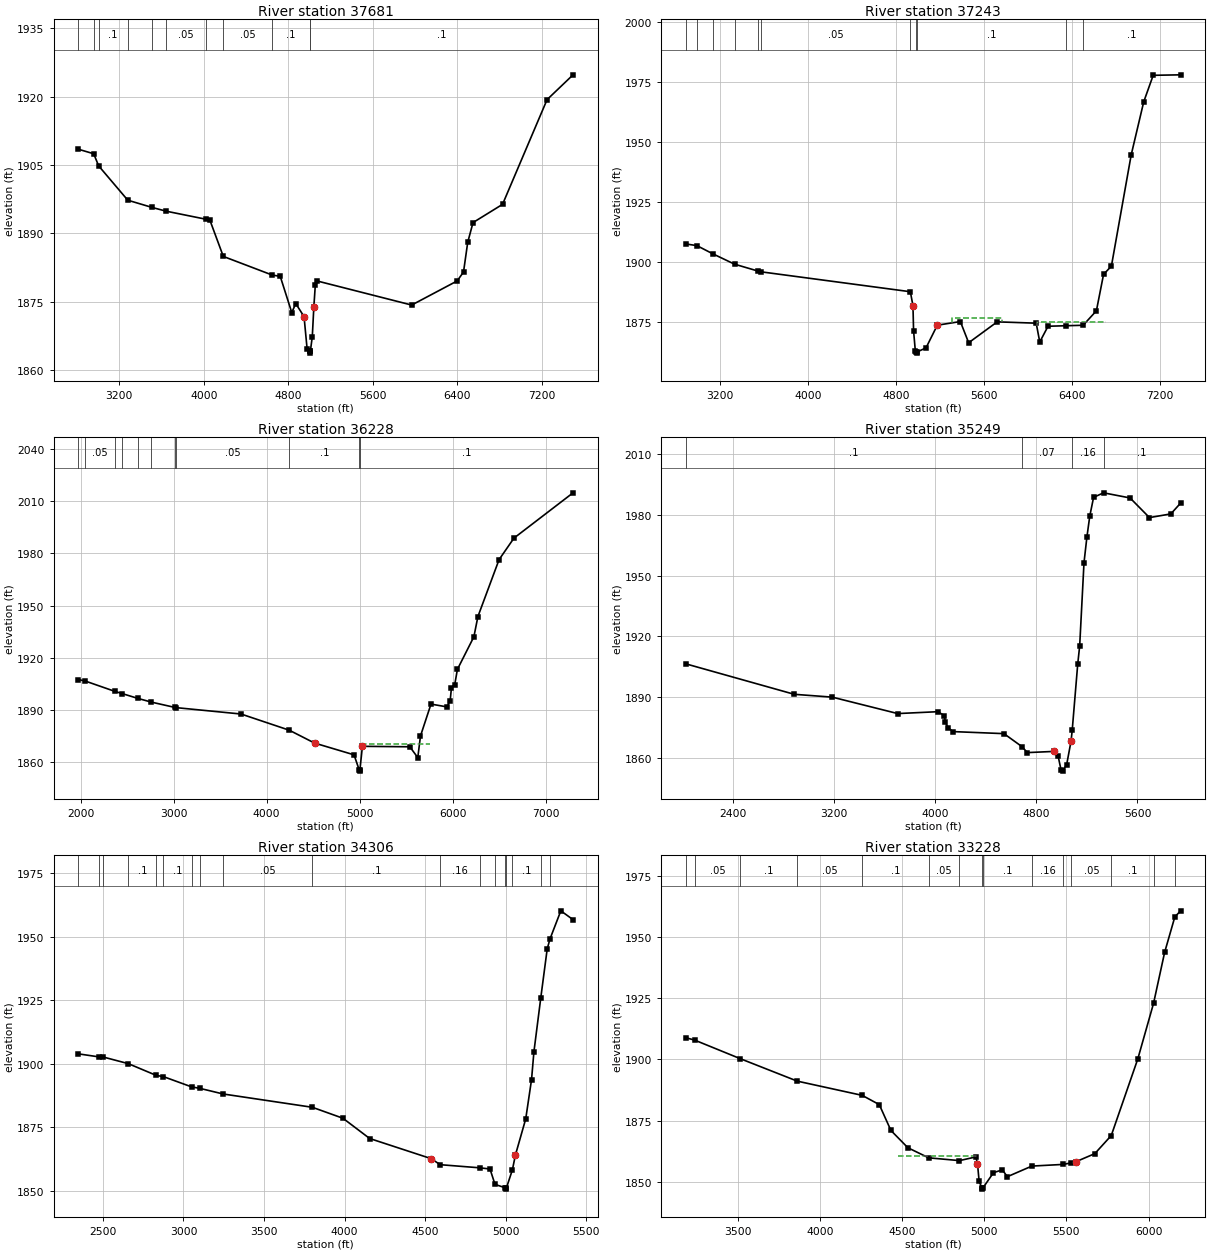
Type RM Length L Ch R = 1 ,37681   ,438,438,438
BEGIN DESCRIPTION:
Mapping XS e712f7ec
END DESCRIPTION:
XS GIS Cut Line= 4
      2680129.01     10036424.76      2681129.03     10034586.18
      2681483.19     10034164.31      2681394.67      10032128.3
#Sta/Elev= 30
  2812.3 1908.46  2958.1 1907.46  3005.1  1904.8  3280.6 1897.27    3512 1895.67
  3645.6 1894.85  4016.3 1893.11  4058.2 1892.86  4184.6 1884.93    4649 1880.83
  4723.2 1880.57  4832.4 1872.62  4870.4 1874.58  4948.7 1871.72  4977.3 1864.71
  5002.9 1864.21  5005.7 1863.71  5008.9 1864.21  5026.7 1867.32  5041.1 1873.73
  5055.4 1878.73  5069.7 1879.56  5967.1 1874.26  6397.5 1879.55  6457.6 1881.51
  6497.6 1888.05  6547.7 1892.36    6827 1896.36  7248.3 1919.34    7494 1924.78
#Mann= 11 ,-1 , 0
  2812.3      .1       0  2958.1     .05       0  3005.1      .1       0
  3280.6     .05       0    3512      .1       0  3645.6     .05       0
  4016.3      .1       0  4184.6     .05       0    4649      .1       0
  5002.9     .07       0  5008.9      .1       0
Bank Sta=4948.7,5041.1
XS Rating Curve= 0 ,0
Exp/Cntr=0.3,0.1

Type RM Length L Ch R = 1 ,37243   ,1015,1015,1015
BEGIN DESCRIPTION:
WHITE OAK CREEK 53.0
END DESCRIPTION:
XS GIS Cut Line= 4
      2680174.12     10036405.88      2681363.33     10035129.87
      2681979.65     10033584.73      2682864.26     10032951.62
#Sta/Elev= 30
  2892.6 1907.46  2992.1 1906.77  3135.9 1903.37  3334.5 1899.02  3551.5 1896.09
  3578.3 1895.81  4931.9 1887.52  4955.7 1881.66  4961.1 1871.24  4977.2 1862.75
  4987.7 1862.39  4990.5 1861.89  4993.7 1862.39  5074.3 1864.09  5176.7 1873.55
  5386.3 1875.07  5461.7 1866.22  5721.2 1874.95  6075.4 1874.39  6107.7 1866.54
    6183 1873.11  6342.3 1873.32    6502 1873.52  6622.4 1879.56  6687.5 1894.78
  6758.7  1898.2  6938.4 1944.61  7052.4 1966.79  7138.4 1977.86  7388.2 1978.06
#Mann= 11 ,-1 , 0
  2892.6      .1       0  2992.1     .05       0  3135.9      .1       0
  3334.5     .05       0  3551.5      .1       0  3578.3     .05       0
  4931.9      .1       0  4987.7     .07       0  4993.7      .1       0
  6342.3     .16       0    6502      .1       0
#XS Ineff= 2 ,-1
 5312.68 5762.25 1876.52    6080 6708.73 1874.72
Permanent Ineff=
       F       F
Bank Sta=4955.7,5176.7
XS Rating Curve= 0 ,0
Exp/Cntr=0.3,0.1

Type RM Length L Ch R = 1 ,36228   ,979,979,979
BEGIN DESCRIPTION:
WHITE OAK CREEK 52.0
END DESCRIPTION:
XS GIS Cut Line= 5
      2680248.27     10036424.95       2682345.5     10034737.45
      2682359.39     10034056.89       2683220.5     10033348.56
      2684053.68     10033369.39
#Sta/Elev= 30
  1975.1 1907.53  2042.6 1906.83  2368.7 1900.76  2447.9 1899.48  2613.2 1896.77
  2758.7 1894.63  3012.3 1891.56  3026.3 1891.43  3725.6 1887.76  4244.2 1878.47
  4515.8 1871.09  4940.7 1864.33  4997.7 1855.47  5000.5 1854.97  5003.7 1855.47
  5030.7 1869.21  5540.7 1868.95  5626.5 1862.73  5655.2 1875.11  5768.5 1893.46
  5939.3 1891.86  5974.4 1895.39  5988.8  1902.9  6023.9  1904.7  6052.6 1913.42
  6229.8 1932.12  6272.9  1943.7  6500.6 1976.41  6660.7 1988.76  7296.1 2014.76
#Mann= 11 ,-1 , 0
  1975.1      .1       0  2042.6     .05       0  2368.7      .1       0
  2447.9     .05       0  2613.2      .1       0  2758.7     .05       0
  3012.3      .1       0  3026.3     .05       0  4244.2      .1       0
  4997.7     .07       0  5003.7      .1       0
#XS Ineff= 1 ,-1
 5040.57 5763.06 1870.29
Permanent Ineff=
       F
Bank Sta=4515.8,5030.7
XS Rating Curve= 0 ,0
Exp/Cntr=0.3,0.1

Type RM Length L Ch R = 1 ,35249   ,943,943,943
BEGIN DESCRIPTION:
WHITE OAK CREEK 50.0
END DESCRIPTION:
XS GIS Cut Line= 2
      2680442.72     10036438.84      2683880.22     10034570.78
#Sta/Elev= 30
  2029.6 1906.52  2886.3 1891.54  3186.5 1890.15  3704.4 1882.06  4020.8 1882.98
  4073.4  1881.1  4080.7 1877.76  4102.5 1875.19  4140.5 1873.19  4544.4 1872.18
  4685.9 1865.83  4729.6 1862.85  4942.5 1863.44  4972.5  1861.2  4995.3  1854.5
  5007.8 1853.73  5040.4 1856.94  5074.9 1868.46  5084.1 1873.75  5127.8 1906.43
  5143.2 1915.33  5177.4 1956.32  5200.1 1968.78  5222.9  1979.2  5253.2 1988.49
  5332.2 1990.71  5541.6 1988.19    5695 1978.52  5864.2 1980.34  5941.9 1985.69
#Mann= 4 ,-1 , 0
  2029.6      .1       0  4685.9     .07       0  5084.1     .16       0
  5332.2      .1       0
Bank Sta=4942.5,5074.9
XS Rating Curve= 0 ,0
Exp/Cntr=0.3,0.1

Type RM Length L Ch R = 1 ,34306   ,1078,1078,1078
BEGIN DESCRIPTION:
WHITE OAK CREEK 48.0
END DESCRIPTION:
XS GIS Cut Line= 4
      2680664.97      10036466.6      2682824.67     10035681.89
      2683296.89     10036001.34      2683491.35     10035945.78
#Sta/Elev= 30
  2347.2 1903.93  2477.2 1902.72  2498.6 1902.74  2657.5 1900.08  2832.4 1895.43
  2875.6 1894.98    3050 1890.96  3101.8 1890.37  3246.2 1888.16  3799.9 1882.93
  3989.4 1878.63  4155.4 1870.67  4537.3 1862.75  4593.1 1860.38  4839.1 1859.15
  4902.1 1858.69  4933.2 1852.64  4998.1 1851.28  5000.8 1850.78  5004.1 1851.28
    5041 1858.35  5060.1 1864.23  5123.9  1878.4  5159.9 1893.83  5174.8 1904.81
  5216.9 1925.77  5257.1 1945.16  5274.2 1949.04  5341.6 1960.12  5417.4 1956.66
#Mann= 18 ,-1 , 0
  2347.2     .05       0  2477.2      .1       0  2498.6     .05       0
  2657.5      .1       0  2832.4     .05       0  2875.6      .1       0
    3050     .05       0  3101.8      .1       0  3246.2     .05       0
  3799.9      .1       0  4593.1     .16       0  4839.1      .1       0
  4933.2     .16       0  4998.1     .07       0  5004.1     .16       0
    5041      .1       0  5216.9     .16       0  5274.2      .1       0
Bank Sta=4537.3,5060.1
XS Rating Curve= 0 ,0
Exp/Cntr=0.3,0.1

Type RM Length L Ch R = 1 ,33228   ,754,754,754
BEGIN DESCRIPTION:
WHITE OAK CREEK 47.0
END DESCRIPTION:
XS GIS Cut Line= 4
      2680685.78     10036924.95      2681880.22     10036626.34
       2682845.5     10036751.34      2683428.84     10036195.78
#Sta/Elev= 30
  3185.1 1908.84  3237.9  1907.9  3516.1  1900.3  3862.6 1891.15  4257.4 1885.35
  4361.5 1881.58  4432.3 1871.03  4535.5 1863.98  4662.1 1859.87  4849.5 1858.73
    4949 1860.24    4959 1857.45  4969.1 1850.23  4986.3  1847.6    4989  1847.1
  4992.3  1847.6  5056.4 1853.82  5110.3 1854.96  5140.7 1852.17  5289.8  1856.5
  5479.6 1857.18  5530.5 1857.82  5559.6 1858.33  5672.9 1861.58  5772.9 1868.96
  5934.6 1900.27    6030 1922.85  6097.5 1943.66  6159.8 1958.18  6195.2 1960.62
#Mann= 15 ,-1 , 0
  3185.1      .1       0  3237.9     .05       0  3516.1      .1       0
  3862.6     .05       0  4257.4      .1       0  4662.1     .05       0
  4849.5      .1       0  4986.3     .07       0  4992.3      .1       0
  5289.8     .16       0  5479.6      .1       0  5530.5     .05       0
  5772.9      .1       0    6030     .16       0  6159.8      .1       0
#XS Ineff= 1 ,-1
 4477.56 4948.86  1860.5
Permanent Ineff=
       F
Bank Sta=4959,5559.6
XS Rating Curve= 0 ,0
Exp/Cntr=0.3,0.1

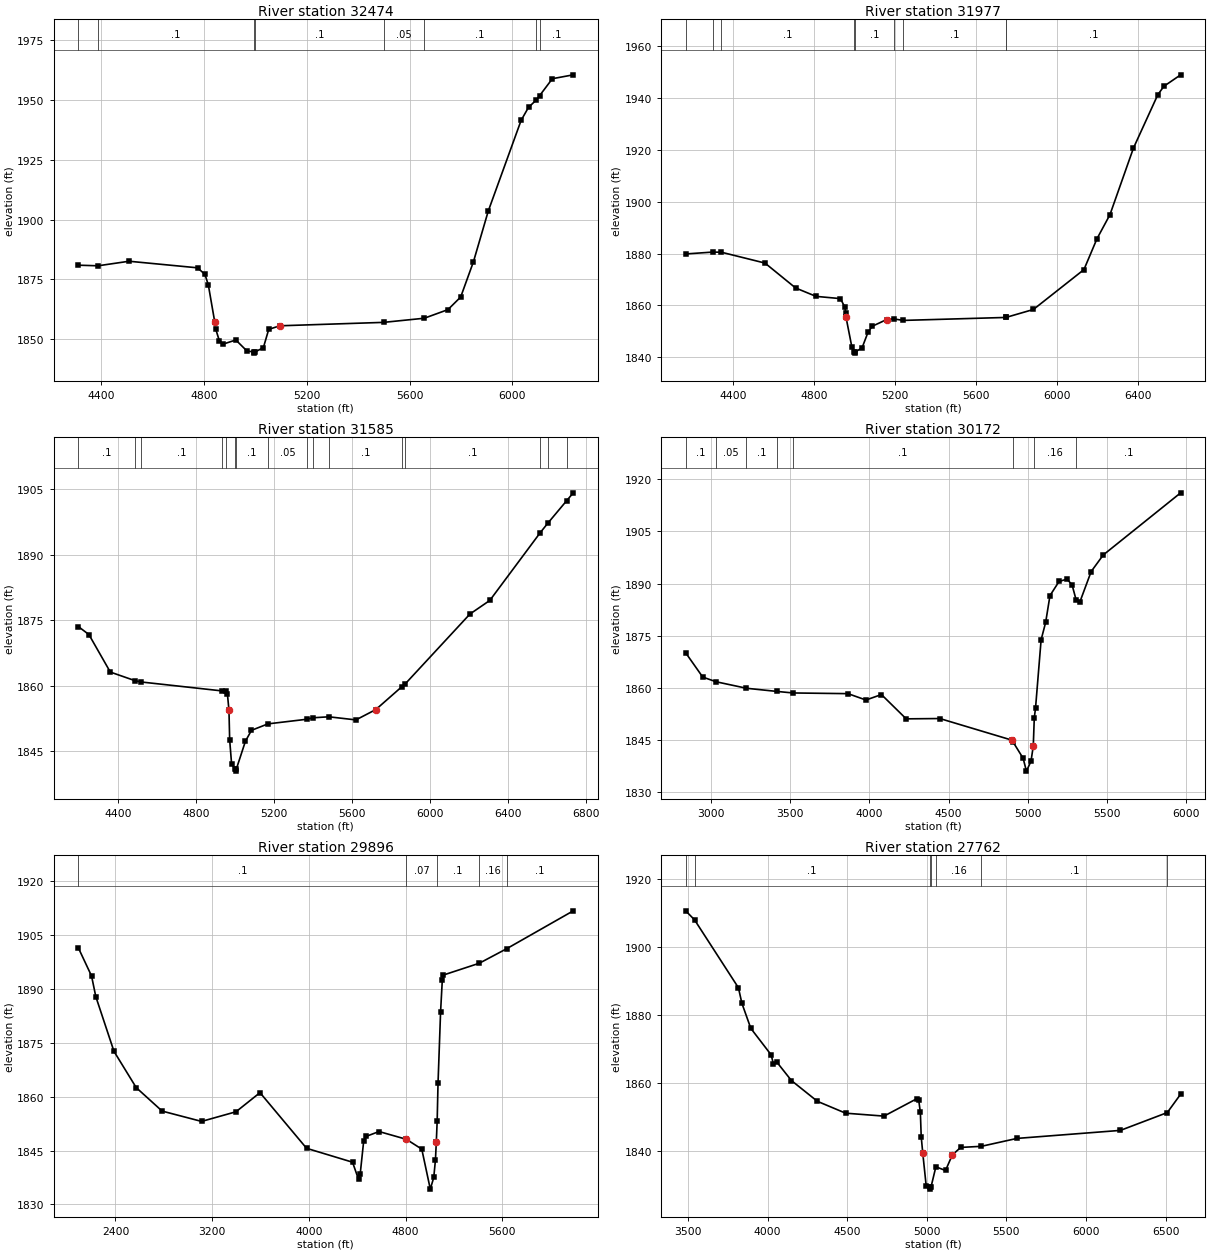
Type RM Length L Ch R = 1 ,32474   ,497,497,497
BEGIN DESCRIPTION:
WHITE OAK CREEK 46.0
END DESCRIPTION:
XS GIS Cut Line= 3
      2682213.55     10037619.39      2682616.33     10037487.45
      2683560.79     10036320.76
#Sta/Elev= 30
  4311.9 1880.96  4388.8 1880.71  4509.3 1882.61  4775.8 1879.86  4804.5  1877.1
  4817.7 1872.66 4842.33 1857.35  4846.2 1854.29  4860.5 1849.33  4874.9 1847.95
  4924.5 1849.69  4967.6  1845.1  4993.4 1844.69  4996.1 1844.19  4999.4 1844.69
  5031.6 1846.46  5052.4 1854.11  5095.5 1855.62  5499.1 1857.05  5657.4 1858.78
  5749.4 1862.38    5799 1867.66  5848.6 1882.41  5906.1 1903.56    6034 1941.53
  6062.8 1946.97  6092.6    1950  6105.6 1951.82  6155.5 1958.94  6236.8 1960.56
#Mann= 8 ,-1 , 0
  4311.9     .05       0  4388.8      .1       0  4993.4     .07       0
  4999.4      .1       0  5499.1     .05       0  5657.4      .1       0
  6092.6     .16       0  6105.6      .1       0
Bank Sta=4842.33,5095.5
XS Rating Curve= 0 ,0
Exp/Cntr=0.3,0.1

Type RM Length L Ch R = 1 ,31977   ,392,392,392
BEGIN DESCRIPTION:
WHITE OAK CREEK 45.0
END DESCRIPTION:
XS GIS Cut Line= 4
      2682199.71     10037716.62      2682914.95     10037799.95
      2683664.95     10036765.22        2683658.      10036320.8
#Sta/Elev= 30
  4166.9 1879.85  4300.1 1880.57  4342.9 1880.52  4558.3 1876.33  4709.3 1866.72
    4810 1863.48  4930.6 1862.61  4951.4 1859.44  4957.6 1857.09 4957.95 1855.47
    4987  1843.9  4998.7 1842.07  5001.4 1841.57  5004.7 1842.07  5037.2  1843.6
  5066.6 1849.62  5087.5 1851.94  5158.6 1854.53  5193.2 1854.78  5241.5  1854.2
  5745.3 1855.34  5749.6  1855.4  5882.7 1858.42  6132.1 1873.81  6196.4 1885.72
  6260.5 1895.02  6376.4 1920.72  6496.5 1941.29  6526.5 1944.56  6609.4 1948.99
#Mann= 9 ,-1 , 0
  4166.9      .1       0  4300.1     .05       0  4342.9      .1       0
  4998.7     .07       0  5004.7      .1       0  5193.2     .05       0
  5241.5      .1       0  5745.3     .16       0  5749.6      .1       0
Bank Sta=4957.95,5158.6
XS Rating Curve= 0 ,0
Exp/Cntr=0.3,0.1

Type RM Length L Ch R = 1 ,31585   ,1297,1297,1297
BEGIN DESCRIPTION:
WHITE OAK CREEK 44.0
END DESCRIPTION:
XS GIS Cut Line= 3
      2682585.11     10037926.69      2683223.97     10038051.68
      2684168.42     10036419.74
#Sta/Elev= 30
  4197.8 1873.55  4252.2 1871.71  4361.9 1863.11    4488 1861.15  4518.1 1860.85
  4933.2  1858.8  4956.2 1858.84  4961.9 1858.13 4969.89 1854.37  4973.5 1847.59
  4983.4 1842.04  5001.9 1840.91  5004.7 1840.41  5007.9 1840.91  5054.4 1847.28
  5085.3 1849.76  5169.6 1851.24    5371 1852.31    5398 1852.63  5481.8 1852.86
  5620.5 1852.15  5722.5 1854.52  5856.1 1859.77  5871.8 1860.34  6204.7 1876.41
  6306.6 1879.53  6565.5 1895.09  6602.9 1897.18  6701.2 1902.43  6734.3 1904.19
#Mann= 16 ,-1 , 0
  4197.8      .1       0    4488     .05       0  4518.1      .1       0
  4933.2     .16       0  4956.2      .1       0  5001.9     .07       0
  5007.9      .1       0  5169.6     .05       0    5371     .16       0
    5398     .05       0  5481.8      .1       0  5856.1     .16       0
  5871.8      .1       0  6565.5     .05       0  6602.9      .1       0
  6701.2     .05       0
Bank Sta=4969.89,5722.5
XS Rating Curve= 0 ,0
Exp/Cntr=0.3,0.1

Type RM Length L Ch R = 1 ,30172   ,276,276,276
BEGIN DESCRIPTION:
Mapping XS 0e324681
END DESCRIPTION:
XS GIS Cut Line= 4
      2682611.85      10037996.8      2683766.35     10038226.83
      2684708.19      10037458.6      2684942.58     10036759.78
#Sta/Elev= 30
  2838.2 1870.12  2946.1 1863.15  3031.1  1861.8  3222.3 1859.94  3417.2 1859.02
  3516.9 1858.59  3864.6 1858.39  3977.9 1856.56  4075.9 1858.13  4232.5 1851.15
    4445 1851.24  4900.2 1845.04  4908.1  1844.5    4972 1839.81  4992.6 1836.13
  5021.6 1838.97    5036 1843.34  5042.4 1851.48  5050.3 1854.28  5085.5 1873.86
  5114.2 1878.86  5141.5 1886.56  5198.9 1890.62  5249.6  1891.3  5281.1 1889.65
  5307.4 1885.25  5330.9 1884.77    5402 1893.48  5478.5 1898.24  5967.9 1916.09
#Mann= 8 ,-1 , 0
  2838.2      .1       0  3031.1     .05       0  3222.3      .1       0
  3417.2     .16       0  3516.9      .1       0  4908.1     .07       0
  5042.4     .16       0  5307.4      .1       0
Bank Sta=4900.2,5036
XS Rating Curve= 0 ,0
Exp/Cntr=0.3,0.1

Type RM Length L Ch R = 1 ,29896   ,2134,2134,2134
BEGIN DESCRIPTION:
WHITE OAK CREEK 42.0
END DESCRIPTION:
XS GIS Cut Line= 5
      2683024.33     10040143.69      2683996.54      10038937.1
       2684239.6     10038277.38        2684908.     10037600.29
      2685367.37     10036837.58
#Sta/Elev= 30
  2092.6 1901.33  2202.3 1893.48  2237.5 1887.75  2387.8 1872.54  2571.8 1862.47
    2786 1855.95  3112.4 1853.08  3397.1 1855.76  3595.5 1861.07  3980.9 1845.61
  4361.2 1841.75  4410.6 1836.97  4424.8 1838.56    4453 1847.53  4474.3 1848.93
  4580.3 1850.27  4806.6 1848.11  4933.9 1845.38  5004.4 1834.27  5032.9 1837.51
    5047 1842.44  5054.1  1847.4  5061.2 1853.23  5068.2 1863.63  5089.5  1883.6
  5103.6 1892.32  5110.6 1893.72  5409.7 1897.02  5636.9 1901.07    6187 1911.58
#Mann= 5 ,-1 , 0
  2092.6      .1       0  4806.6     .07       0  5061.2      .1       0
  5409.7     .16       0  5636.9      .1       0
#XS Ineff= 1 ,-1
 3590.91 4582.39 1850.16
Permanent Ineff=
       F
Bank Sta=4806.6,5054.1
XS Rating Curve= 0 ,0
Exp/Cntr=0.3,0.1

Type RM Length L Ch R = 1 ,27762   ,1091,1091,1091
BEGIN DESCRIPTION:
WHITE OAK CREEK 41.0
END DESCRIPTION:
XS GIS Cut Line= 4
        2683033.     10040325.99      2683987.86     10039483.97
      2684482.65     10039319.04       2685272.6     10038268.68
#Sta/Elev= 30
  3485.9 1910.57  3541.4 1907.93  3817.1 1887.95  3838.9 1883.38  3894.9    1876
  4022.9 1868.19  4037.2 1865.46  4058.1 1866.08  4150.1 1860.64  4313.2 1854.53
  4490.6 1851.04  4731.6 1850.18  4938.9 1855.33  4949.4 1854.92  4959.9 1851.29
  4965.2 1844.16    4975 1839.27  4996.9 1829.48  5020.1  1829.2  5022.9  1828.7
  5026.1  1829.2  5057.3 1835.27    5118 1834.18  5160.2 1838.73  5212.9 1840.97
  5342.6 1841.29  5566.7 1843.62  6216.5 1845.98  6510.8 1851.22  6594.8 1856.64
#Mann= 7 ,-1 , 0
  3485.9     .05       0  3541.4      .1       0  5020.1     .07       0
  5026.1      .1       0  5057.3     .16       0  5342.6      .1       0
  6510.8     .16       0
Bank Sta=4975,5160.2
XS Rating Curve= 0 ,0
Exp/Cntr=0.3,0.1

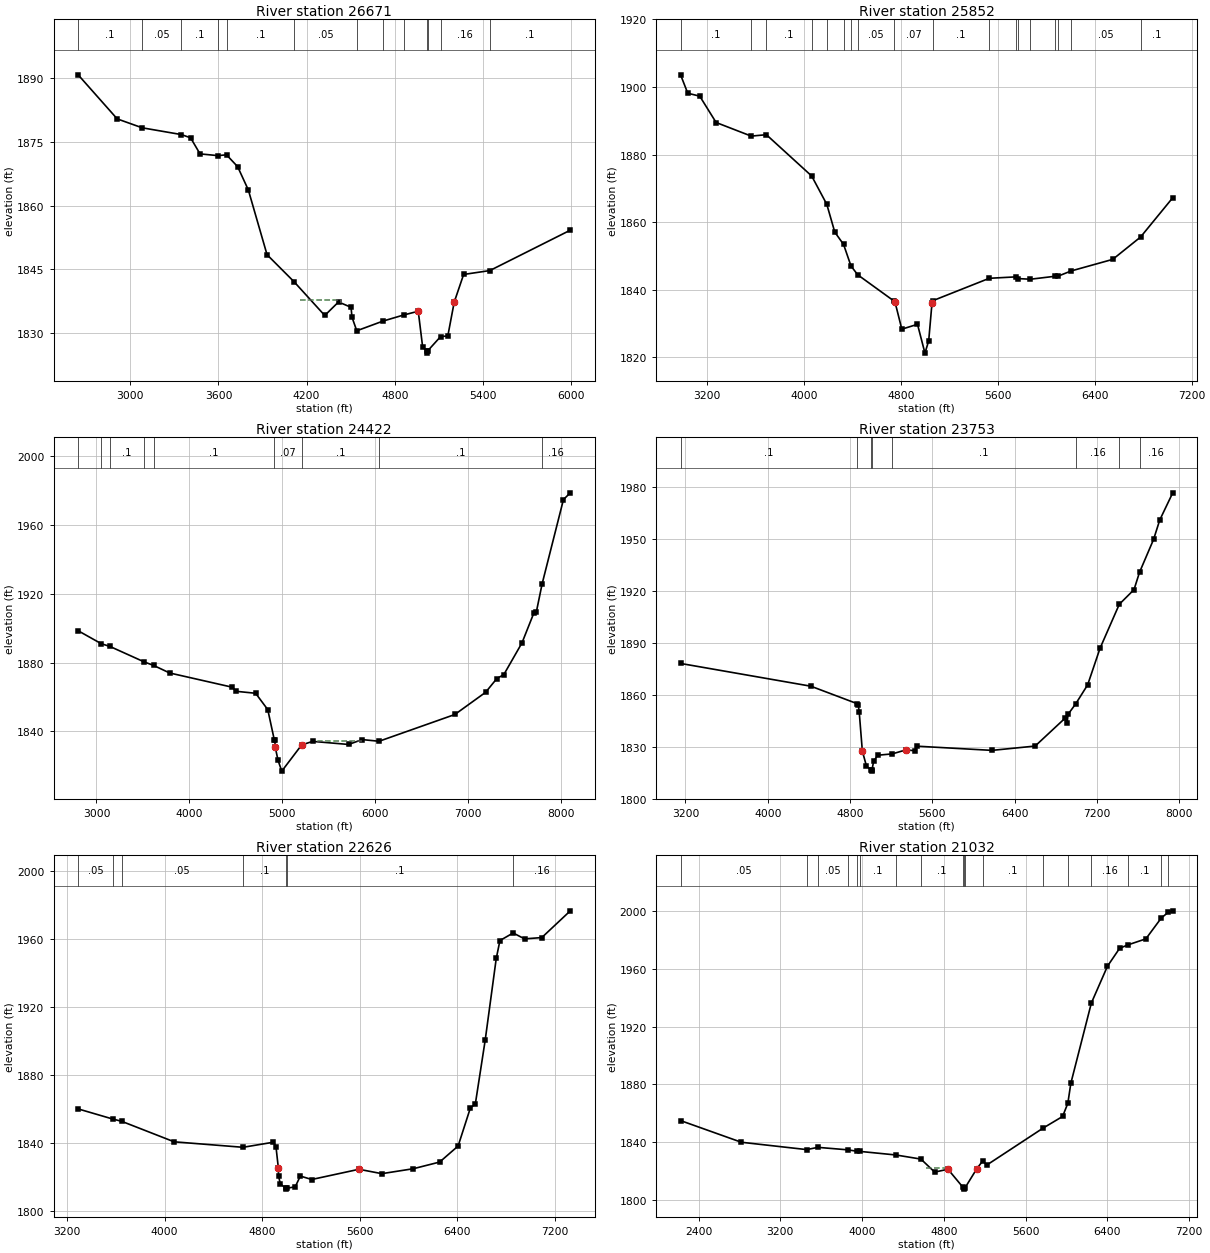
Type RM Length L Ch R = 1 ,26671   ,819,819,819
BEGIN DESCRIPTION:
WHITE OAK CREEK 40.0
END DESCRIPTION:
XS GIS Cut Line= 4
       2683892.4      10041419.7      2685046.89     10039891.96
      2685107.65     10039319.04      2685637.18     10038641.94
#Sta/Elev= 30
  2644.6 1890.82  2910.4 1880.45  3080.5 1878.35  3346.7 1876.76  3409.9    1876
  3474.4 1872.21  3596.4  1871.8  3654.6 1871.99  3730.4  1869.2  3803.2 1863.72
  3930.6 1848.48  4115.7 1842.07  4323.5 1834.17  4417.1 1837.35  4502.5  1836.1
  4508.7 1833.79  4541.4 1830.57  4719.8 1832.85    4860 1834.28    4960 1835.17
  4990.1 1826.72  5017.3 1825.81    5020 1825.31  5023.3 1825.81  5111.8 1829.19
  5161.4 1829.37  5204.7 1837.29  5268.9 1843.83  5447.2 1844.74  5995.2 1854.25
#Mann= 13 ,-1 , 0
  2644.6      .1       0  3080.5     .05       0  3346.7      .1       0
  3596.4     .05       0  3654.6      .1       0  4115.7     .05       0
  4541.4      .1       0  4719.8     .05       0    4860      .1       0
  5017.3     .07       0  5023.3      .1       0  5111.8     .16       0
  5447.2      .1       0
#XS Ineff= 1 ,-1
 4156.53 4436.93 1837.92
Permanent Ineff=
       F
Bank Sta=4960,5204.7
XS Rating Curve= 0 ,0
Exp/Cntr=0.3,0.1

Type RM Length L Ch R = 1 ,25852   ,1430,1430,1430
BEGIN DESCRIPTION:
WHITE OAK CREEK 39.0
END DESCRIPTION:
XS GIS Cut Line= 4
      2683953.14     10041621.56      2685146.72     10040221.82
      2685710.95     10040091.61      2686492.13      10038648.6
#Sta/Elev= 30
  2983.9 1903.62  3043.1 1898.17  3141.9 1897.31    3277 1889.51  3566.9 1885.48
  3691.5  1885.9  4065.4 1873.67  4190.1 1865.28  4255.8 1857.06  4328.2 1853.43
  4389.6 1847.04  4445.1 1844.43    4745 1836.65  4752.7 1836.37  4808.7 1828.34
  4938.1 1829.78  4999.5 1821.25  5030.5  1824.9  5057.8 1836.13    5063 1836.75
  5530.4  1843.4  5750.5 1843.82  5764.8 1843.32  5868.9 1843.12  6068.3 1843.98
  6094.8 1843.99  6205.1 1845.57  6548.6    1849    6778 1855.61  7043.4 1867.24
#Mann= 18 ,-1 , 0
  2983.9      .1       0  3566.9     .05       0  3691.5      .1       0
  4065.4     .05       0  4190.1      .1       0  4328.2     .05       0
  4389.6      .1       0  4445.1     .05       0    4745     .07       0
    5063      .1       0  5530.4     .05       0  5750.5      .1       0
  5764.8     .05       0  5868.9      .1       0  6068.3     .05       0
  6094.8      .1       0  6205.1     .05       0    6778      .1       0
Bank Sta=4752.7,5057.8
XS Rating Curve= 0 ,0
Exp/Cntr=0.3,0.1

Type RM Length L Ch R = 1 ,24422   ,669,669,669
BEGIN DESCRIPTION:
WHITE OAK CREEK 37.0
END DESCRIPTION:
XS GIS Cut Line= 4
       2685331.2     10042923.61      2686199.23     10041534.76
       2686470.5     10039158.45      2686796.01     10037932.37
#Sta/Elev= 30
  2802.7 1898.52  3052.4 1890.98  3144.2 1889.42  3514.4  1880.4  3614.4 1878.39
  3787.7 1873.99  4461.7 1865.72  4501.9 1863.35  4713.3  1862.2  4844.1 1852.68
  4914.1 1835.17  4919.1 1835.12  4924.7 1830.79  4954.8 1823.19  4994.9 1816.97
  5208.8 1832.19  5327.3 1834.25  5713.5 1832.46  5860.7 1835.29  6041.9 1834.32
  6857.8 1849.87  7188.9 1862.76  7309.7 1870.74  7384.9 1873.03  7580.6 1891.48
  7706.3 1908.56  7736.1 1909.67  7797.5 1925.78    8027 1974.75  8100.8 1978.65
#Mann= 9 ,-1 , 0
  2802.7      .1       0  3052.4     .05       0  3144.2      .1       0
  3514.4     .05       0  3614.4      .1       0  4914.1     .07       0
  5208.8      .1       0  6041.9      .1       0  7797.5     .16       0
#XS Ineff= 1 ,-1
 5384.66 5857.95 1834.24
Permanent Ineff=
       F
Bank Sta=4924.7,5208.8
XS Rating Curve= 0 ,0
Exp/Cntr=0.3,0.1

Type RM Length L Ch R = 1 ,23753   ,1127,1127,1127
BEGIN DESCRIPTION:
WHITE OAK CREEK 36.0
END DESCRIPTION:
XS GIS Cut Line= 4
      2686286.04     10042728.34      2686915.38     10041664.96
      2686926.23      10039169.3      2686980.44     10038117.74
#Sta/Elev= 30
  3152.5 1878.16  4419.4 1865.03  4868.1 1854.98  4879.4 1854.45  4889.4 1849.92
  4919.4 1827.61  4959.4 1818.99  5006.4 1816.55  5009.1 1816.05  5012.4 1816.55
  5029.4 1821.79  5069.4 1825.22  5210.8    1826  5339.4 1828.24  5429.4 1827.86
  5449.4 1830.44  6179.4 1828.02  6599.4 1830.51  6889.4 1846.54  6909.4 1843.75
  6919.5 1848.83  6994.4 1854.94  7109.7 1865.82  7229.9  1886.9  7417.4 1912.31
  7560.3 1920.73  7613.9 1930.73  7750.6 1949.72  7810.6 1960.91  7936.8 1976.58
#Mann= 8 ,-1 , 0
  3152.5      .1       0  4868.1     .16       0  5006.4     .07       0
  5012.4     .16       0  5210.8      .1       0  6994.4     .16       0
  7417.4      .1       0  7613.9     .16       0
Bank Sta=4919.4,5339.4
XS Rating Curve= 0 ,0
Exp/Cntr=0.3,0.1

Type RM Length L Ch R = 1 ,22626   ,1594,1594,1594
BEGIN DESCRIPTION:
WHITE OAK CREEK 34.0
END DESCRIPTION:
XS GIS Cut Line= 4
      2687403.66     10041957.94      2687859.39      10040601.6
      2687360.26     10039950.55      2687121.55     10038181.91
#Sta/Elev= 30
  3290.4 1860.16  3575.6 1854.19  3646.1 1852.91  4077.7 1840.84  4642.5 1837.62
    4892 1840.61  4912.8 1837.87 4931.82 1825.68  4933.7 1820.78  4948.2 1816.14
    4995 1813.56  4997.8 1813.06    5001 1813.56  5070.6 1814.43  5112.3 1820.74
  5205.7 1818.71  5593.2 1824.71  5780.6 1822.14  6039.4 1825.05  6254.9 1828.96
  6406.2 1838.37  6507.1 1860.79  6547.5 1863.05  6628.2 1900.45    6719 1948.52
  6749.3 1959.02  6857.5 1963.47  6951.1    1960  7092.5 1960.77  7326.3 1976.47
#Mann= 7 ,-1 , 0
  3290.4     .05       0  3575.6      .1       0  3646.1     .05       0
  4642.5      .1       0    4995     .07       0    5001      .1       0
  6857.5     .16       0
Bank Sta=4931.82,5593.2
XS Rating Curve= 0 ,0
Exp/Cntr=0.3,0.1

Type RM Length L Ch R = 1 ,21032   ,1254,1254,1254
BEGIN DESCRIPTION:
WHITE OAK CREEK 30.0
END DESCRIPTION:
XS GIS Cut Line= 4
      2687588.13     10041925.37      2688228.31     10039983.11
      2688304.27     10038778.68      2689703.73     10038084.37
#Sta/Elev= 30
  2224.6 1854.94  2818.9 1839.92    3458 1834.82  3567.6 1836.38  3858.3 1834.67
  3952.4 1833.65  3974.8  1833.6  4330.6 1831.09  4575.4 1828.24  4709.9 1819.22
  4840.2 1821.18  4982.9    1809  4997.5  1807.9  5000.2  1807.4  5003.5  1807.9
  5120.7 1821.38  5179.1  1826.9  5220.9 1824.15  5768.8 1849.66  5961.2  1857.8
  6012.7 1866.97  6041.9  1880.8  6242.7 1936.51  6400.5 1962.07  6519.3 1974.48
  6601.3 1976.86  6775.9 1981.02  6927.8 1995.58    6993 1999.32  7038.7 2000.46
#Mann= 18 ,-1 , 0
  2224.6     .05       0    3458      .1       0  3567.6     .05       0
  3858.3      .1       0  3952.4     .05       0  3974.8      .1       0
  4330.6     .05       0  4575.4      .1       0  4982.9     .16       0
  4997.5     .07       0  5003.5     .16       0  5179.1      .1       0
  5768.8     .05       0  6012.7      .1       0  6242.7     .16       0
  6601.3      .1       0  6927.8     .16       0    6993      .1       0
#XS Ineff= 1 ,-1
 4622.76 4832.53 1821.94
Permanent Ineff=
       F
Bank Sta=4840.2,5120.7
XS Rating Curve= 0 ,0
Exp/Cntr=0.3,0.1

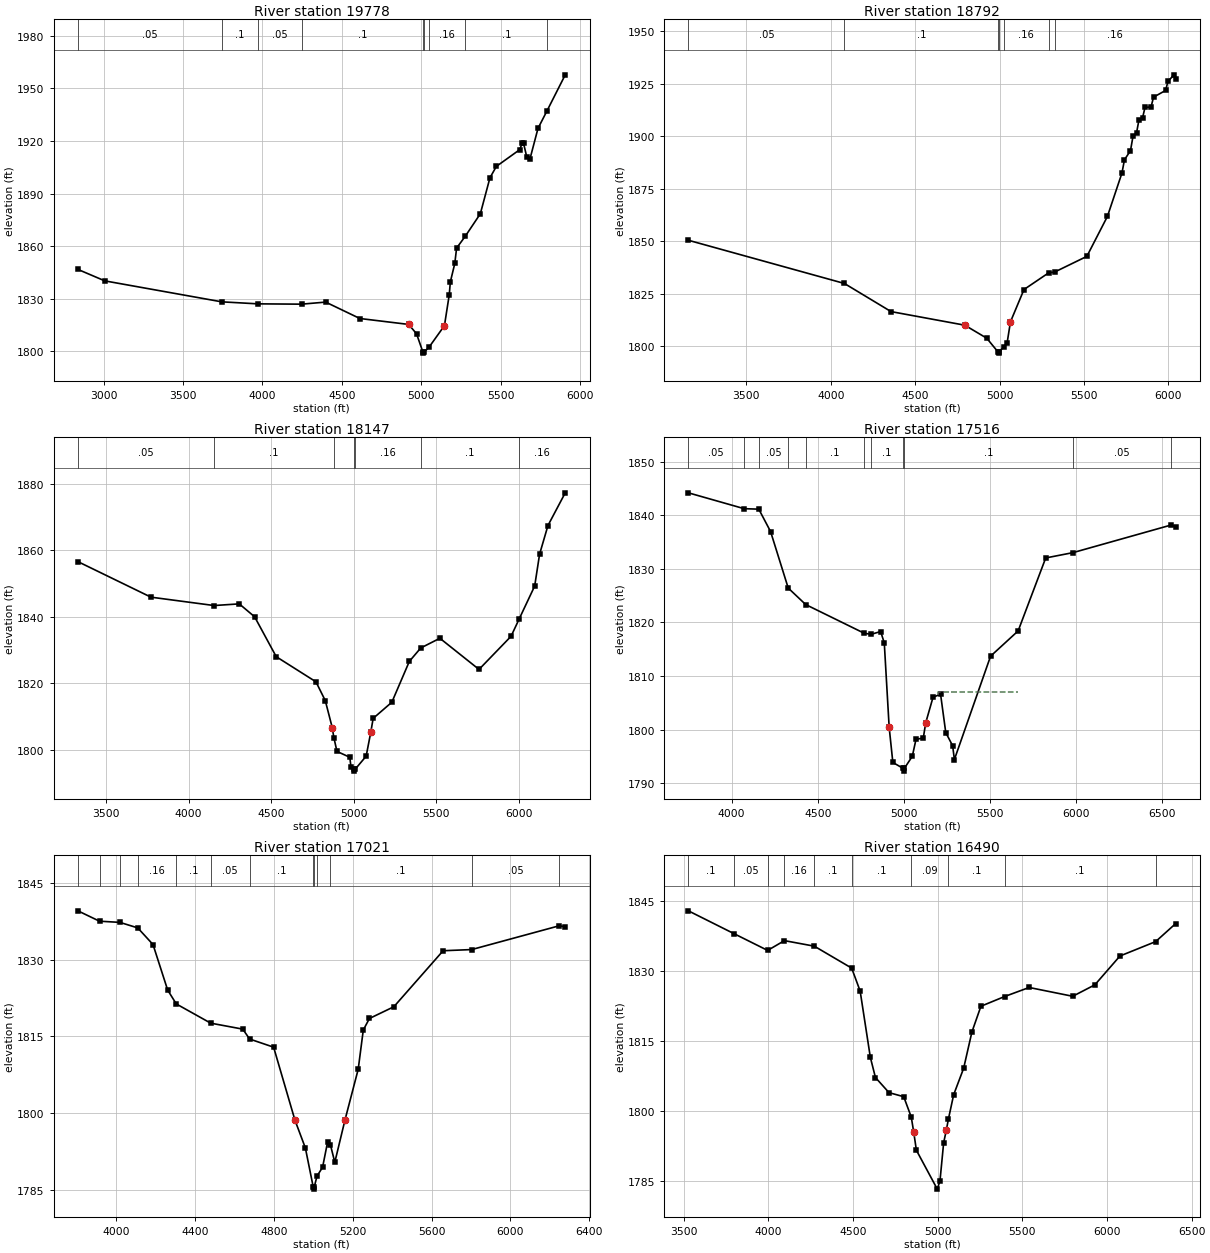
Type RM Length L Ch R = 1 ,19778   ,986,986,986
BEGIN DESCRIPTION:
WHITE OAK CREEK 29.0
END DESCRIPTION:
XS GIS Cut Line= 4
      2687772.57     10041643.28      2688792.55     10040221.82
      2689324.23     10039907.15      2690018.67     10039993.96
#Sta/Elev= 30
  2838.5 1846.74  3007.8  1840.2  3743.8 1828.24    3971 1827.09    4246 1826.91
  4397.9 1828.09    4613 1818.73  4920.3 1815.35  4969.9 1809.99  5010.2 1799.47
    5013 1798.97  5016.2 1799.47  5047.6 1802.25  5145.4 1814.66  5175.9 1832.38
  5182.4 1839.56  5210.5 1850.12  5221.9 1858.91  5277.2 1865.75  5371.4 1878.52
  5431.8 1899.03  5472.2 1905.53    5620 1915.13  5633.4 1918.66  5643.5 1918.63
  5663.6 1910.88  5683.8 1909.84  5734.2 1927.22  5791.7 1937.37  5905.7 1957.78
#Mann= 9 ,-1 , 0
  2838.5     .05       0  3743.8      .1       0    3971     .05       0
    4246      .1       0  5010.2     .07       0  5016.2      .1       0
  5047.6     .16       0  5277.2      .1       0  5791.7     .16       0
Bank Sta=4920.3,5145.4
XS Rating Curve= 0 ,0
Exp/Cntr=0.3,0.1

Type RM Length L Ch R = 1 ,18792   ,645,645,645
BEGIN DESCRIPTION:
WHITE OAK CREEK 27.0
END DESCRIPTION:
XS GIS Cut Line= 4
      2687815.98     10041947.09      2688901.06     10040970.52
       2689595.5     10040927.12      2690018.67     10040330.34
#Sta/Elev= 30
  3156.3  1850.5  4080.7 1829.93    4357 1816.54  4793.9 1810.07  4924.1 1803.87
  4991.3 1797.27    4994 1796.77  4997.3 1797.27  5025.8 1799.92  5044.4 1801.51
  5064.4 1811.66  5144.6 1827.05  5291.1 1835.01  5325.4 1835.34  5517.1 1842.84
  5638.9 1861.86    5725 1882.52  5739.8 1888.81  5775.5 1893.15  5790.3 1899.92
  5811.2 1901.55  5825.9 1907.85  5846.8 1908.69  5861.6 1913.73  5897.3 1913.95
  5912.1 1918.63  5983.4 1921.82  5998.2 1926.24  6033.9 1929.26  6043.5 1927.37
#Mann= 7 ,-1 , 0
  3156.3     .05       0  4080.7      .1       0  4991.3     .07       0
  4997.3      .1       0  5025.8     .16       0  5291.1      .1       0
  5325.4     .16       0
Bank Sta=4793.9,5064.4
XS Rating Curve= 0 ,0
Exp/Cntr=0.3,0.1

Type RM Length L Ch R = 1 ,18147   ,631,631,631
BEGIN DESCRIPTION:
WHITE OAK CREEK 26.0
END DESCRIPTION:
XS GIS Cut Line= 4
      2687772.62     10042229.19      2688901.06     10041936.23
      2689584.65     10041252.64      2690051.23      10040579.9
#Sta/Elev= 30
  3329.5 1856.53  3771.9 1845.84  4154.4 1843.32  4306.7 1843.82  4399.7 1839.93
  4530.6 1827.93  4771.1 1820.37  4827.6 1814.71    4870 1806.55  4879.5 1803.61
  4898.3 1799.43  4976.1 1797.67  4983.2 1794.73  5001.4    1794  5004.1  1793.5
  5007.4    1794  5075.1    1798  5103.4 1805.27  5117.5 1809.37  5230.7 1814.23
  5336.7 1826.52  5405.7 1830.55  5521.6 1833.47  5758.6  1824.1  5952.5 1834.06
    6003 1839.41  6095.7 1849.18  6125.4 1858.76  6176.1 1867.39  6280.8 1877.23
#Mann= 7 ,-1 , 0
  3329.5     .05       0  4154.4      .1       0  4879.5     .16       0
  5001.4     .07       0  5007.4     .16       0  5405.7      .1       0
    6003     .16       0
Bank Sta=4870,5103.4
XS Rating Curve= 0 ,0
Exp/Cntr=0.3,0.1

Type RM Length L Ch R = 1 ,17516   ,495,495,495
BEGIN DESCRIPTION:
WHITE OAK CREEK 25.0
END DESCRIPTION:
XS GIS Cut Line= 4
      2688618.17     10042546.31      2689586.91     10042103.61
      2689842.12     10041832.77      2691232.79     10041817.15
#Sta/Elev= 30
  3748.8 1844.19  4072.4 1841.23  4157.4 1841.14  4225.8 1836.96  4328.2 1826.41
  4429.6 1823.33  4768.7 1817.98  4808.6 1817.77  4864.5 1818.29  4885.6 1816.18
  4913.9 1800.44  4935.3 1793.85  4995.8 1792.73  4998.6 1792.23  5001.8 1792.73
  5048.2    1795  5069.6 1798.15  5112.1 1798.43  5126.3 1801.28  5168.8 1806.05
  5212.4 1806.56  5242.4 1799.43  5282.4 1796.96  5292.4 1794.39  5502.4 1813.69
  5662.4 1818.41  5822.4 1832.03  5981.4 1833.03  6550.3 1838.18  6576.8 1837.85
#Mann= 11 ,-1 , 0
  3748.8     .05       0  4072.4      .1       0  4157.4     .05       0
  4328.2     .16       0  4429.6      .1       0  4768.7     .05       0
  4808.6      .1       0  4995.8     .07       0  5001.8      .1       0
  5981.4     .05       0  6550.3      .1       0
#XS Ineff= 1 ,-1
 5196.31 5659.66 1806.97
Permanent Ineff=
       F
Bank Sta=4913.9,5126.3
XS Rating Curve= 0 ,0
Exp/Cntr=0.3,0.1

Type RM Length L Ch R = 1 ,17021   ,531,531,531
BEGIN DESCRIPTION:
WHITE OAK CREEK 24.0
END DESCRIPTION:
XS GIS Cut Line= 2
      2688898.58     10042677.38      2691233.52     10041861.45
#Sta/Elev= 30
    3805 1839.57  3914.7 1837.54  4018.1 1837.31  4108.7 1836.23  4186.2 1832.97
  4260.6 1824.06  4304.3 1821.35  4478.9 1817.59  4641.7 1816.42  4676.6 1814.48
  4798.3 1812.89  4906.5 1798.61  4959.5 1793.16  4998.9 1785.61  5001.6 1785.11
  5004.9 1785.61  5018.8 1787.68  5046.7 1789.38  5072.4 1794.35  5086.6 1793.78
  5108.8 1790.36  5160.3 1798.61  5227.6 1808.57  5253.4 1816.24  5284.4  1818.5
  5408.6  1820.8  5658.6 1831.76  5803.7 1831.99  6248.4 1836.65  6278.4 1836.44
#Mann= 13 ,-1 , 0
    3805     .05       0  3914.7      .1       0  4018.1     .05       0
  4108.7     .16       0  4304.3      .1       0  4478.9     .05       0
  4676.6      .1       0  4998.9     .07       0  5004.9      .1       0
  5018.8     .05       0  5086.6      .1       0  5803.7     .05       0
  6248.4      .1       0
Bank Sta=4906.5,5160.3
XS Rating Curve= 0 ,0
Exp/Cntr=0.3,0.1

Type RM Length L Ch R = 1 ,16490   ,536,536,536
BEGIN DESCRIPTION:
WHITE OAK CREEK 23.0
END DESCRIPTION:
XS GIS Cut Line= 3
      2688816.08     10042950.83      2690044.38     10042877.04
      2691472.32     10042056.74
#Sta/Elev= 30
  3528.6 1842.98  3798.4 1838.07  3996.6 1834.48  4095.7 1836.58  4272.1 1835.39
  4492.7 1830.68  4542.8 1825.74  4602.9 1811.53    4633 1807.19  4713.1 1803.94
    4800 1803.07  4844.6 1798.69    4859 1795.47  4874.8 1791.57  4998.2 1783.22
  5014.2 1785.03  5035.8 1793.19  5051.6 1795.88  5063.7 1798.23  5094.8 1803.48
  5153.7 1809.16  5202.6 1816.96  5255.8 1822.49  5395.2 1824.57  5540.5 1826.52
  5797.8 1824.63  5928.6 1827.09  6076.7 1833.28  6287.4 1836.37  6405.9 1840.25
#Mann= 10 ,-1 , 0
  3528.6      .1       0  3798.4     .05       0  3996.6      .1       0
  4095.7     .16       0  4272.1      .1       0  4492.7      .1       0
  4844.6     .09       0  5063.7      .1       0  5395.2      .1       0
  6287.4     .05       0
Bank Sta=4859,5051.6
XS Rating Curve= 0 ,0
Exp/Cntr=0.3,0.1