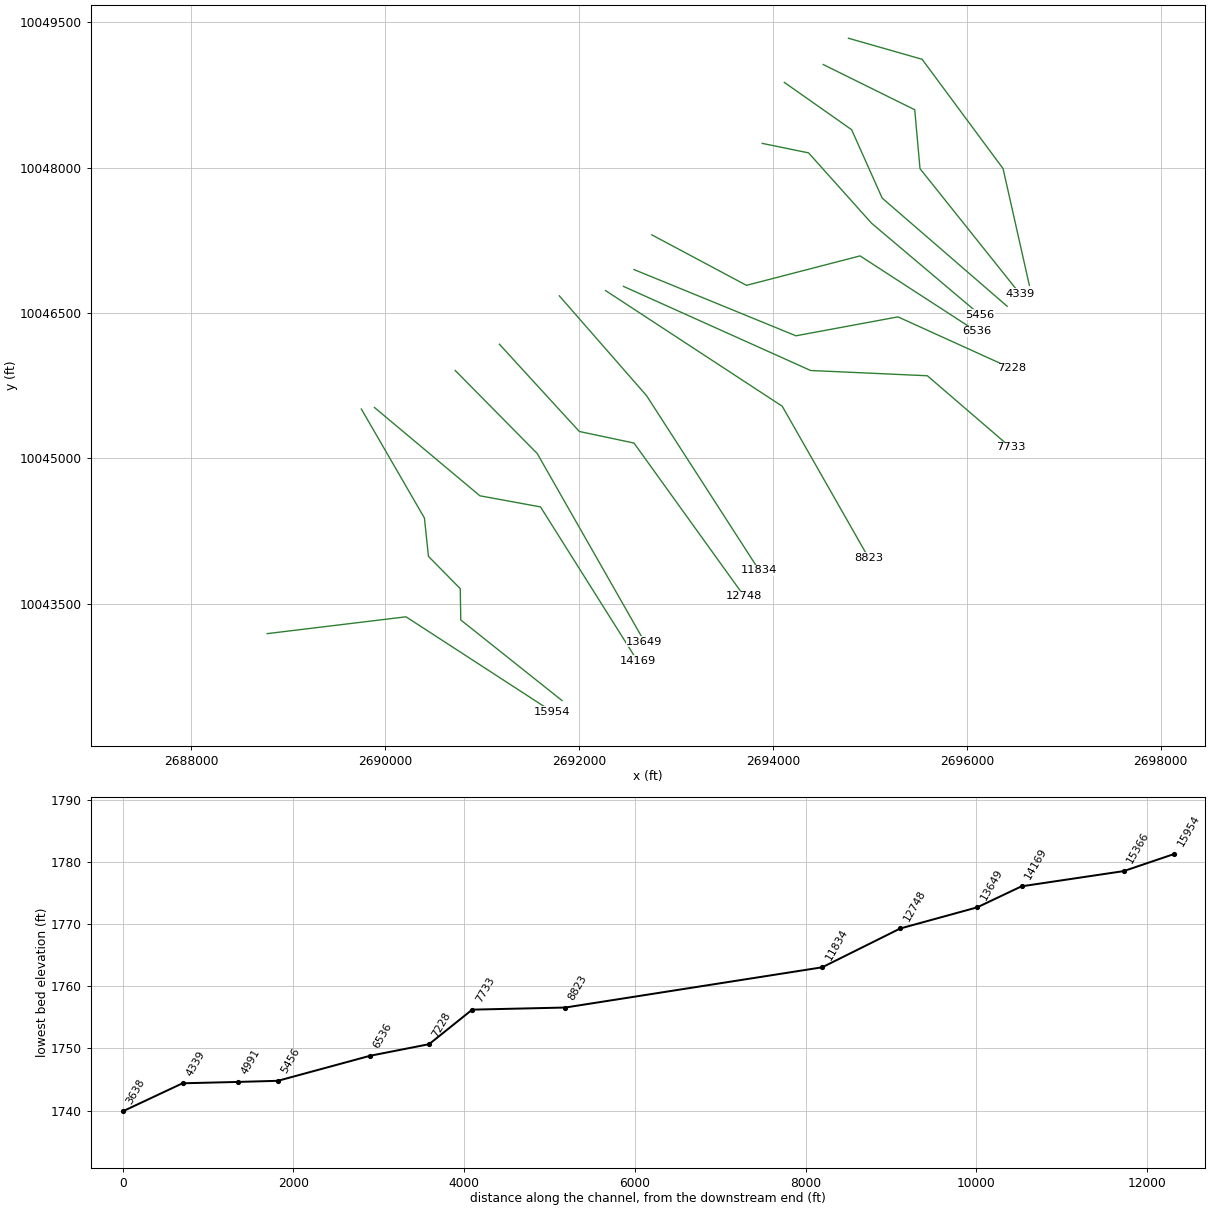
HEC-RAS study WHITE OAK CREEK.prj: WHITE OAK CREEK Base Level Engineering

--- WHITE OAK CREEK.g01 (geometry) --- (continued)

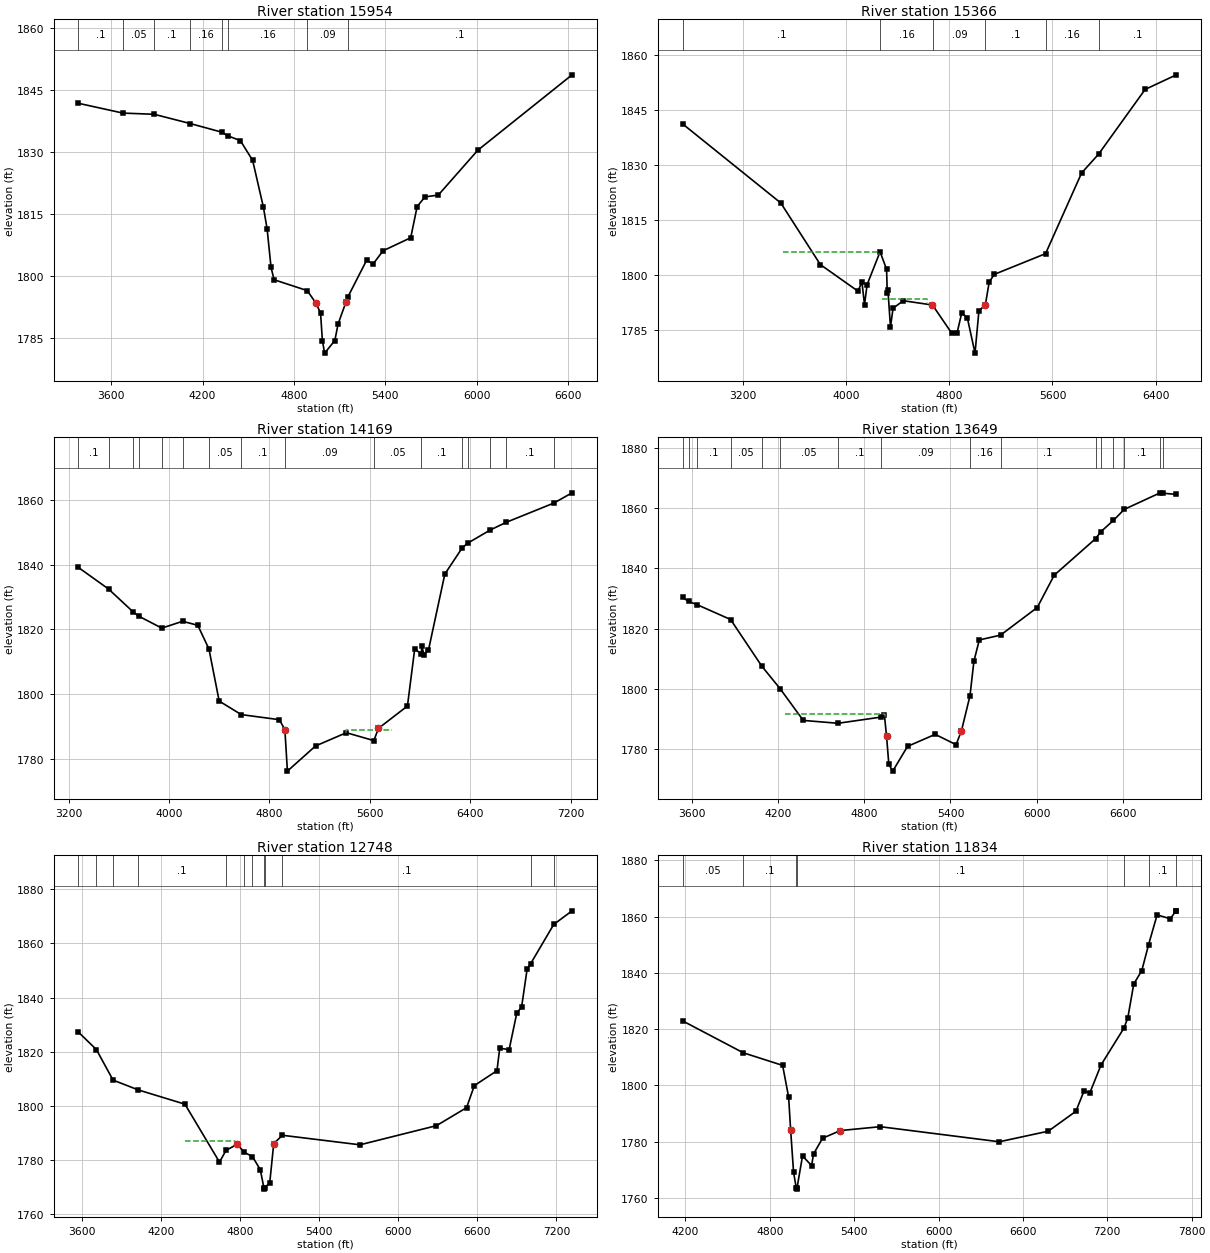
Type RM Length L Ch R = 1 ,15954   ,588,588,588
BEGIN DESCRIPTION:
WHITE OAK CREEK 22.0
END DESCRIPTION:
XS GIS Cut Line= 3
      2688781.37     10043189.55      2690213.65     10043363.16
      2691723.78     10042382.44
#Sta/Elev= 30
  3383.1 1841.77  3676.5 1839.39  3882.1  1839.1  4118.6 1836.86  4326.1 1834.77
  4364.6  1833.9  4447.9 1832.73  4528.5 1827.95    4599 1816.66  4623.6 1811.37
  4649.4 1802.04  4669.5 1799.06  4887.2 1796.43  4944.5 1793.39  4974.7 1790.99
  4986.7 1784.27  5001.6  1781.3  5068.4 1784.35  5089.5 1788.32  5140.9  1793.6
  5153.5 1794.86  5276.7 1803.75  5320.5  1802.9  5385.4 1806.08  5566.7 1809.22
  5608.9 1816.76  5660.3 1819.11  5747.9 1819.55  6007.6 1830.41  6626.5 1848.65
#Mann= 8 ,-1 , 0
  3383.1      .1       0  3676.5     .05       0  3882.1      .1       0
  4118.6     .16       0  4326.1      .1       0  4364.6     .16       0
  4887.2     .09       0  5153.5      .1       0
Bank Sta=4944.5,5140.9
XS Rating Curve= 0 ,0
Exp/Cntr=0.3,0.1

Type RM Length L Ch R = 1 ,15366   ,1197,1197,1197
BEGIN DESCRIPTION:
WHITE OAK CREEK 21.0
END DESCRIPTION:
XS GIS Cut Line= 6
      2689752.51     10045507.66      2690403.54     10044382.69
       2690445.2     10043986.85      2690773.33     10043653.52
      2690778.54      10043330.6       2691823.5     10042498.79
#Sta/Elev= 30
  2735.4 1841.21  3496.3 1819.59  3802.9 1802.75  4094.4 1795.48  4124.6 1798.07
  4144.7 1791.79  4164.8 1797.27  4265.4 1806.25  4315.7 1801.45  4320.9 1794.89
  4325.9 1795.89  4345.8 1785.72  4365.9 1790.82  4444.8 1792.88  4671.1 1791.71
  4678.1 1791.34  4819.5 1784.04    4862 1784.16  4897.3 1789.51  4940.7 1788.23
  5000.5 1778.56  5030.7 1790.12  5080.7 1791.79  5110.7 1798.06  5150.7 1800.09
  5546.8 1805.74  5825.9 1827.79  5956.9 1832.91  6317.7 1850.61  6559.5  1854.6
#Mann= 6 ,-1 , 0
  2735.4      .1       0  4265.4     .16       0  4678.1     .09       0
  5080.7      .1       0  5546.8     .16       0  5956.9      .1       0
#XS Ineff= 2 ,-1
  3514.2 4255.68 1806.18 4281.25 4630.68 1793.29
Permanent Ineff=
       F       F
Bank Sta=4671.1,5080.7
XS Rating Curve= 0 ,0
Exp/Cntr=0.3,0.1

Type RM Length L Ch R = 1 ,14169   ,520,520,520
BEGIN DESCRIPTION:
WHITE OAK CREEK 19.0
END DESCRIPTION:
XS GIS Cut Line= 4
      2689887.88     10045523.34      2690976.45     10044611.85
      2691601.45     10044497.27      2692601.46     10042908.72
#Sta/Elev= 30
    3277 1839.21  3519.1 1832.47    3711 1825.52  3759.7 1824.07  3942.7 1820.39
  4107.7  1822.5  4228.9 1821.27  4317.9 1813.92  4399.3  1797.8  4575.1 1793.61
  4878.6 1792.04  4922.5 1788.93  4942.6 1776.11  5166.5  1783.9  5412.1 1788.01
  5631.1 1785.56  5667.2 1789.34  5898.4 1796.27  5956.1  1813.9  6007.9 1812.47
  6013.8 1814.72  6029.1 1812.22  6065.6 1813.53  6196.3 1837.14  6333.9  1845.2
  6378.2 1846.69    6559  1850.8  6686.9 1853.18  7063.7  1859.1  7209.3 1862.28
#Mann= 16 ,-1 , 0
    3277      .1       0  3519.1      .1       0    3711     .05       0
  3759.7      .1       0  3942.7     .05       0  4107.7      .1       0
  4317.9     .05       0  4575.1      .1       0  4922.5     .09       0
  5631.1     .05       0  6007.9      .1       0  6333.9     .05       0
  6378.2      .1       0    6559     .05       0  6686.9      .1       0
  7063.7     .16       0
#XS Ineff= 1 ,-1
 5411.93 5775.57 1788.84
Permanent Ineff=
       F
Bank Sta=4922.5,5667.2
XS Rating Curve= 0 ,0
Exp/Cntr=0.3,0.1

Type RM Length L Ch R = 1 ,13649   ,901,901,901
BEGIN DESCRIPTION:
WHITE OAK CREEK 18.0
END DESCRIPTION:
XS GIS Cut Line= 3
      2690721.42     10045905.17      2691567.77     10045047.96
      2692673.15     10043108.13
#Sta/Elev= 30
  3534.8 1830.32  3577.8    1829  3636.4 1827.93  3869.5 1823.01  4087.7 1807.47
  4214.5 1800.04  4375.2 1789.54  4617.3 1788.59  4917.6 1790.65    4940 1791.37
  4955.1 1784.25  4970.9 1774.96    4998 1772.72  5101.1 1780.93  5293.6 1784.92
  5439.1 1781.49  5476.6 1786.15  5535.7 1797.71    5563 1809.16  5600.5 1816.23
  5748.3 1817.83  6003.9 1826.99    6122 1837.71  6411.2 1849.88  6445.4 1852.08
  6534.4  1855.9  6609.9 1859.55  6859.3 1865.03  6877.2 1864.92  6972.1  1864.5
#Mann= 16 ,-1 , 0
  3534.8      .1       0  3577.8     .05       0  3636.4      .1       0
  3869.5     .05       0  4087.7      .1       0  4214.5     .05       0
  4617.3      .1       0  4917.6     .09       0  5535.7     .16       0
  5748.3      .1       0  6411.2     .05       0  6445.4      .1       0
  6534.4     .05       0  6609.9      .1       0  6859.3     .16       0
  6877.2     .05       0
#XS Ineff= 1 ,-1
 4247.73 4941.76 1791.54
Permanent Ineff=
       F
Bank Sta=4955.1,5476.6
XS Rating Curve= 0 ,0
Exp/Cntr=0.3,0.1

Type RM Length L Ch R = 1 ,12748   ,914,914,914
BEGIN DESCRIPTION:
WHITE OAK CREEK 16.0
END DESCRIPTION:
XS GIS Cut Line= 4
      2691177.13     10046176.46       2692001.8     10045275.83
      2692566.04     10045156.47      2693704.42     10043573.58
#Sta/Elev= 30
  3571.5 1827.34  3709.2 1820.84  3835.9 1809.56  4027.7 1805.93  4381.2 1800.68
  4643.3 1779.31  4693.2 1783.62  4777.7 1785.89  4830.7 1782.95  4893.8 1781.31
  4952.8 1776.55  4980.4 1769.82  4983.2 1769.32  4986.4 1769.82  5024.8 1771.62
    5055 1786.12  5120.9  1789.2  5709.5 1785.68  6290.1 1792.75  6518.5 1799.39
  6577.4 1807.53  6749.2 1813.04  6770.1 1821.36  6841.3 1820.79  6900.1 1834.41
  6935.8 1836.45  6977.6  1850.4  7005.1 1852.57  7179.9 1867.02  7319.1 1872.05
#Mann= 12 ,-1 , 0
  3571.5     .05       0  3709.2      .1       0  3835.9     .05       0
  4027.7      .1       0  4693.2     .16       0  4830.7      .1       0
  4893.8     .16       0  4980.4     .07       0  4986.4     .16       0
  5120.9      .1       0  7005.1     .05       0  7179.9      .1       0
#XS Ineff= 1 ,-1
 4379.55 4761.36 1787.03
Permanent Ineff=
       F
Bank Sta=4777.7,5055
XS Rating Curve= 0 ,0
Exp/Cntr=0.3,0.1

Type RM Length L Ch R = 1 ,11834   ,3011,3011,3011
BEGIN DESCRIPTION:
WHITE OAK CREEK 15.0
END DESCRIPTION:
XS GIS Cut Line= 3
      2691795.65     10046675.55      2692696.25     10045644.75
      2693857.28     10043843.52
#Sta/Elev= 30
  4179.4 1822.91  4611.6 1811.55  4891.3 1807.07    4934  1795.8  4948.3  1784.1
  4969.2 1769.03    4988 1763.57  4990.8 1763.07    4994 1763.57  5032.8 1774.85
  5097.3 1771.46  5111.3 1775.59  5175.2 1781.17  5302.3  1783.9  5585.5 1785.27
  6432.4 1779.91  6780.3 1783.67    6977 1790.75  7034.4 1797.95  7076.6 1797.38
  7155.6 1807.22    7318 1820.29  7345.9 1823.94  7388.2 1836.01  7445.6 1840.79
  7493.7    1850  7554.5  1860.6  7648.3 1859.19  7688.6 1862.03  7691.2 1862.03
#Mann= 7 ,-1 , 0
  4179.4     .05       0  4611.6      .1       0    4988     .07       0
    4994      .1       0    7318     .16       0  7493.7      .1       0
  7688.6     .05       0
Bank Sta=4948.3,5302.3
XS Rating Curve= 0 ,0
Exp/Cntr=0.3,0.1

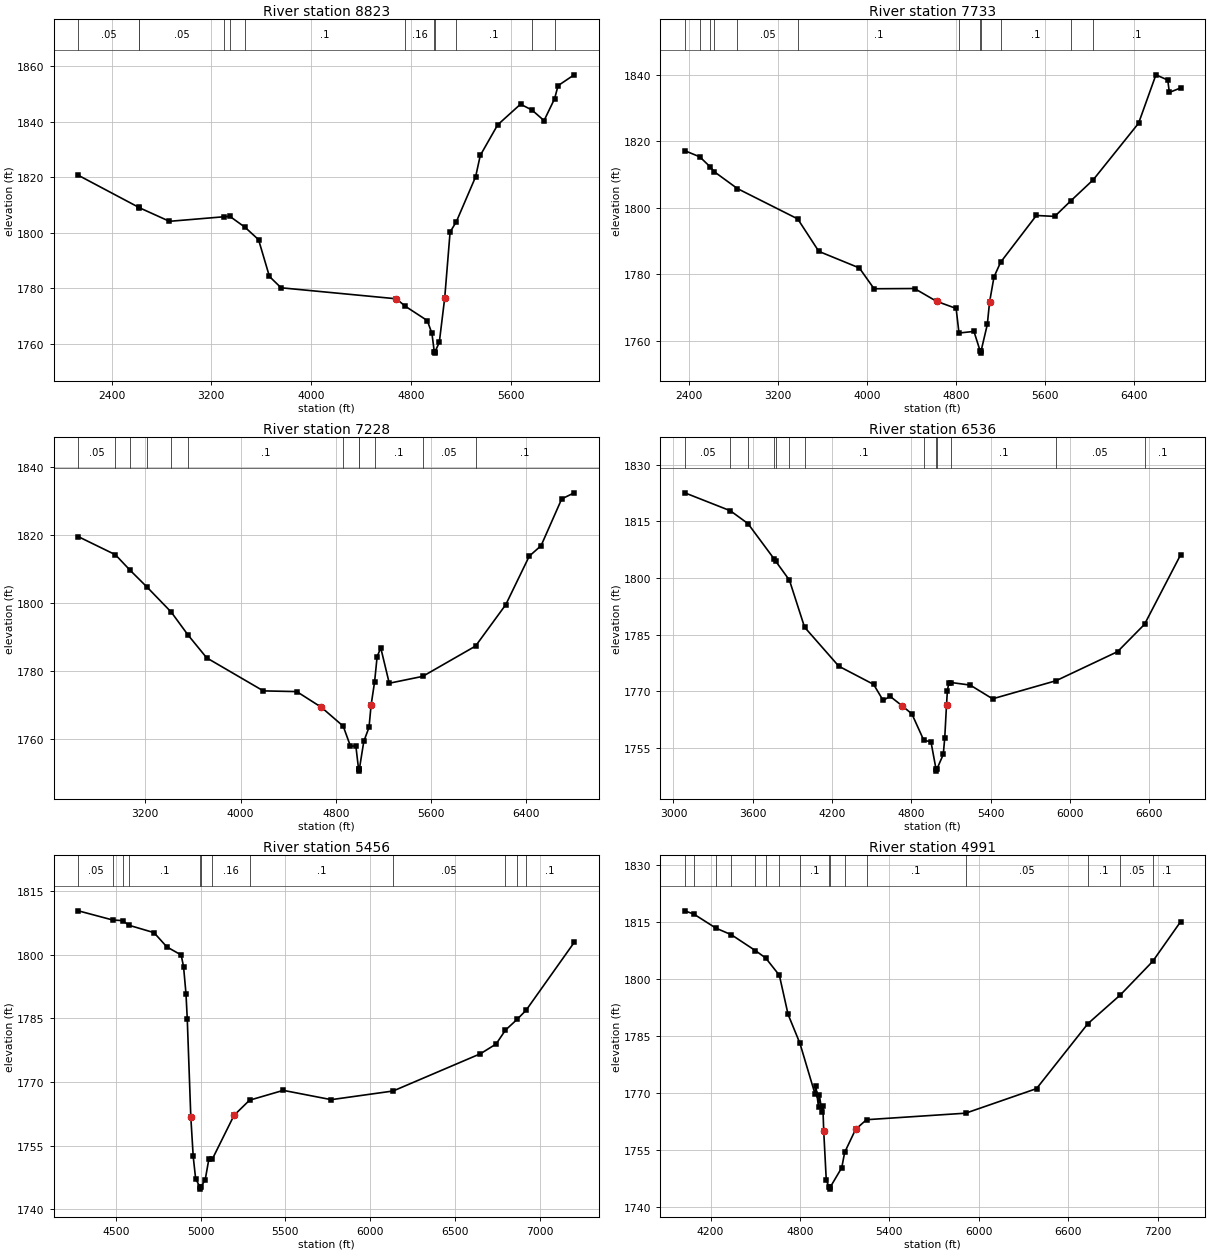
Type RM Length L Ch R = 1 ,8823    ,1090,1090,1090
BEGIN DESCRIPTION:
WHITE OAK CREEK 14.0
END DESCRIPTION:
XS GIS Cut Line= 3
      2692273.07     10046729.82      2694095.99     10045536.25
      2694985.75     10043973.74
#Sta/Elev= 30
  2133.3 1820.66  2619.9 1809.07  2622.6 1808.98  2864.2 1804.08    3298 1805.71
  3348.4 1805.88  3469.8 1801.95  3578.8 1797.47  3666.2  1784.2  3759.7 1780.13
  4683.4 1776.17  4756.3 1773.47  4932.2 1768.32  4969.6 1763.68  4988.3 1757.09
    4991 1756.59  4994.3 1757.09  5028.6 1760.48    5072 1776.45  5115.2 1800.22
  5165.3 1803.94  5319.8 1820.11  5357.3 1827.83    5497 1838.85    5680 1846.28
  5771.8 1844.18  5868.8 1840.37  5953.2 1848.23  5981.2 1852.96  6110.3 1856.86
#Mann= 12 ,-1 , 0
  2133.3     .05       0  2619.9      .1       0  2622.6     .05       0
    3298      .1       0  3348.4     .05       0  3469.8      .1       0
  4756.3     .16       0  4988.3     .07       0  4994.3     .16       0
  5165.3      .1       0  5771.8     .05       0  5953.2      .1       0
Bank Sta=4683.4,5072
XS Rating Curve= 0 ,0
Exp/Cntr=0.3,0.1

Type RM Length L Ch R = 1 ,7733    ,505,505,505
BEGIN DESCRIPTION:
WHITE OAK CREEK 12.0
END DESCRIPTION:
XS GIS Cut Line= 4
      2692457.54     10046773.22      2694388.95     10045905.17
      2695593.38     10045850.92       2696450.6     10045113.06
#Sta/Elev= 30
  2362.7  1817.1  2497.2 1815.26  2588.9  1812.3  2628.2 1810.76  2835.1 1805.72
  3376.9  1796.6  3566.6 1786.84  3930.4 1781.86  4063.1  1775.6  4426.5 1775.67
  4624.1 1771.83  4800.1 1769.69  4825.8 1762.29  4960.2 1762.78  5017.3 1756.75
    5020 1756.25  5023.3 1756.75  5080.3 1764.86  5100.4 1771.57  5140.4 1779.16
    5200 1783.58  5520.8 1797.63  5685.9 1797.35  5832.6  1802.1  6032.1 1808.37
  6439.2 1825.36    6595 1839.91  6701.4 1838.34  6715.7 1834.62  6816.9 1835.97
#Mann= 12 ,-1 , 0
  2362.7     .05       0  2497.2      .1       0  2588.9     .05       0
  2628.2      .1       0  2835.1     .05       0  3376.9      .1       0
  4825.8     .16       0  5017.3     .07       0  5023.3     .16       0
    5200      .1       0  5832.6     .16       0  6032.1      .1       0
Bank Sta=4624.1,5100.4
XS Rating Curve= 0 ,0
Exp/Cntr=0.3,0.1

Type RM Length L Ch R = 1 ,7228    ,692,692,692
BEGIN DESCRIPTION:
WHITE OAK CREEK 11.0
END DESCRIPTION:
XS GIS Cut Line= 4
      2692566.01     10046946.85      2694237.04     10046263.24
      2695289.56     10046458.55      2696461.44     10045926.87
#Sta/Elev= 30
  2638.1 1819.65  2949.5 1814.33  3068.2 1809.93    3218 1804.71  3418.4 1797.45
  3558.7 1790.74  3715.9    1784  4191.3 1774.29    4472 1774.08  4678.9 1769.46
    4862 1763.91    4923 1758.01  4967.9 1758.14  4991.2 1751.19    4994 1750.69
  4997.2 1751.19  5034.9 1759.46  5078.6 1763.55  5095.9 1770.06  5125.4 1776.94
  5146.8 1784.39  5177.3 1786.93  5248.5 1776.54  5529.4 1778.56    5973 1787.47
  6226.6 1799.64  6424.3 1813.93  6523.1 1816.99  6696.4 1830.75  6800.9 1832.54
#Mann= 12 ,-1 , 0
  2638.1     .05       0  2949.5      .1       0  3068.2     .05       0
    3218      .1       0  3418.4     .05       0  3558.7      .1       0
    4862     .16       0  4991.2     .07       0  4997.2     .16       0
  5125.4      .1       0  5529.4     .05       0    5973      .1       0
Bank Sta=4678.9,5095.9
XS Rating Curve= 0 ,0
Exp/Cntr=0.3,0.1

Type RM Length L Ch R = 1 ,6536    ,1080,1080,1080
BEGIN DESCRIPTION:
WHITE OAK CREEK 10.0
END DESCRIPTION:
XS GIS Cut Line= 4
      2692750.47     10047304.93      2693727.06     10046784.08
      2694898.94      10047087.9      2696101.73      10046307.7
#Sta/Elev= 30
  3085.9 1822.53  3429.8 1817.79  3563.5 1814.39    3763 1804.96  3772.4 1804.48
  3877.5 1799.39    3992 1786.94    4251 1776.61  4514.4 1771.79  4586.7 1767.53
  4638.4 1768.65  4727.7 1766.18  4803.7 1763.99  4893.9 1756.99  4948.3 1756.59
  4986.6 1749.32  4989.4 1748.82  4992.6 1749.32  5041.3 1753.24  5052.4 1757.57
 5065.91 1766.36  5072.3 1770.07  5082.6 1772.08  5100.6 1772.29    5245 1771.61
  5414.4 1767.97    5895 1772.77  6359.8 1780.46  6563.8  1787.7    6837 1806.12
#Mann= 13 ,-1 , 0
  3085.9     .05       0  3429.8      .1       0  3563.5     .05       0
    3763     .16       0  3772.4      .1       0  3877.5     .16       0
    3992      .1       0  4893.9     .16       0  4986.6     .07       0
  4992.6     .16       0  5100.6      .1       0    5895     .05       0
  6563.8      .1       0
Bank Sta=4727.7,5065.91
XS Rating Curve= 0 ,0
Exp/Cntr=0.3,0.1

Type RM Length L Ch R = 1 ,5456    ,465,465,465
BEGIN DESCRIPTION:
WHITE OAK CREEK 8.0
END DESCRIPTION:
XS GIS Cut Line= 4
      2693889.83     10048248.92      2694367.25     10048151.26
      2695018.29     10047424.27      2696134.72     10046481.26
#Sta/Elev= 30
  4279.4 1810.36  4481.1 1808.21  4540.3 1808.05  4578.9 1806.95  4725.7 1805.22
  4801.5 1801.86  4885.9 1799.96  4900.1 1797.18  4914.3 1790.88  4921.8 1784.98
  4942.8 1761.81    4957 1752.48  4971.2 1747.27  4996.6 1745.29  4999.3 1744.79
  5002.6 1745.29    5028 1747.05  5048.9 1751.78  5069.1 1751.81  5197.7 1762.17
  5289.2 1765.74  5488.3 1768.06  5771.1 1765.87  6136.1 1767.91  6651.3 1776.69
  6743.6 1778.98  6798.9 1782.26  6867.6 1784.79  6920.2 1786.92    7204  1802.9
#Mann= 12 ,-1 , 0
  4279.4     .05       0  4481.1      .1       0  4540.3     .05       0
  4578.9      .1       0  4996.6     .07       0  5002.6      .1       0
  5069.1     .16       0  5289.2      .1       0  6136.1     .05       0
  6798.9      .1       0  6867.6     .05       0  6920.2      .1       0
Bank Sta=4942.8,5197.7
XS Rating Curve= 0 ,0
Exp/Cntr=0.3,0.1

Type RM Length L Ch R = 1 ,4991    ,652,652,652
BEGIN DESCRIPTION:
WHITE OAK CREEK 7.0
END DESCRIPTION:
XS GIS Cut Line= 4
       2694117.7     10048878.25      2694812.13     10048389.98
       2695126.8     10047684.68      2696417.09     10046567.88
#Sta/Elev= 30
  4026.8 1818.01  4087.5 1817.15  4235.9 1813.44  4339.5  1811.7  4500.5 1807.52
  4569.2 1805.59  4661.5 1801.01  4719.9  1790.7  4799.4 1783.07  4901.2 1769.64
  4906.7 1771.74  4924.5 1766.18  4929.9  1769.4  4947.7 1764.88  4953.2 1766.55
  4959.2 1759.88  4976.4  1746.9  4996.6 1745.11  4999.4 1744.61  5002.6 1745.11
  5080.2 1750.26  5099.6 1754.29  5173.1 1760.37  5246.3 1762.92  5911.7 1764.64
  6387.4 1771.12  6732.1 1788.25  6949.7 1795.82    7167 1804.68  7354.5 1815.15
#Mann= 16 ,-1 , 0
  4026.8      .1       0  4087.5     .05       0  4235.9      .1       0
  4339.5     .05       0  4500.5      .1       0  4569.2     .05       0
  4661.5     .16       0  4799.4      .1       0  4996.6     .07       0
  5002.6      .1       0  5099.6     .16       0  5246.3      .1       0
  5911.7     .05       0  6732.1      .1       0  6949.7     .05       0
    7167      .1       0
Bank Sta=4959.2,5173.1
XS Rating Curve= 0 ,0
Exp/Cntr=0.3,0.1

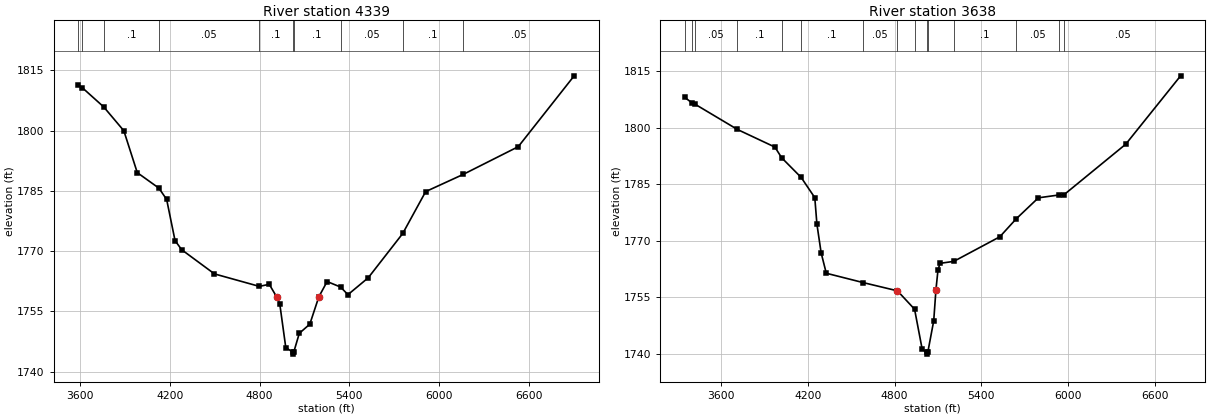
Type RM Length L Ch R = 1 ,4339    ,701,701,701
BEGIN DESCRIPTION:
WHITE OAK CREEK 6.0
END DESCRIPTION:
XS GIS Cut Line= 4
      2694519.15     10049062.73      2695463.17     10048596.14
      2695517.43      10047988.5      2696547.67     10046697.99
#Sta/Elev= 30
  3588.8 1811.33  3614.8  1810.7  3758.8 1805.89    3893 1799.97  3982.8 1789.55
  4127.2  1785.7  4179.1 1782.89  4235.2 1772.64    4280 1770.36  4498.9 1764.35
  4798.4 1761.25  4865.1 1761.76  4915.3 1758.58  4935.4 1756.87  4975.6    1746
  5022.8 1744.89  5025.5 1744.39  5028.8 1744.89  5065.9 1749.57  5136.2 1751.85
  5196.4 1758.64  5251.8 1762.45  5341.4 1761.09  5391.1 1759.19  5526.7 1763.39
  5757.3 1774.41  5910.6 1784.83  6160.3 1789.09  6529.5 1796.01  6903.2 1813.64
#Mann= 10 ,-1 , 0
  3588.8      .1       0  3614.8     .05       0  3758.8      .1       0
  4127.2     .05       0  4798.4      .1       0  5022.8     .07       0
  5028.8      .1       0  5341.4     .05       0  5757.3      .1       0
  6160.3     .05       0
Bank Sta=4915.3,5196.4
XS Rating Curve= 0 ,0
Exp/Cntr=0.3,0.1

Type RM Length L Ch R = 1 ,3638    ,966,966,966
BEGIN DESCRIPTION:
WHITE OAK CREEK 5.0
END DESCRIPTION:
XS GIS Cut Line= 4
      2694779.56     10049333.99      2695539.13     10049116.98
      2696374.63      10047988.5      2696645.91     10046784.04
#Sta/Elev= 30
  3349.5 1808.04  3396.1 1806.69  3419.2 1806.27  3713.6 1799.53  3972.4 1794.86
  4019.6 1792.01  4154.1  1786.8  4248.4 1781.43    4263 1774.42  4292.3 1766.77
  4327.8 1761.35  4582.7 1758.87  4819.9 1756.68  4938.4  1751.8  4991.4 1741.11
  5023.9 1740.37  5026.7 1739.87  5029.9 1740.37  5070.8 1748.72 5086.36 1757.03
    5100 1762.11    5114 1763.98  5209.3  1764.5  5527.8 1771.03  5641.2  1775.8
  5794.5 1781.38  5937.4 1782.14    5972 1782.21  6398.6 1795.62  6778.2 1813.78
#Mann= 15 ,-1 , 0
  3349.5     .16       0  3396.1      .1       0  3419.2     .05       0
  3713.6      .1       0  4019.6     .05       0  4154.1      .1       0
  4582.7     .05       0  4819.9     .16       0  4938.4      .1       0
  5023.9     .07       0  5029.9      .1       0  5209.3      .1       0
  5641.2     .05       0  5937.4      .1       0    5972     .05       0
Bank Sta=4819.9,5086.36
XS Rating Curve= 0 ,0
Exp/Cntr=0.3,0.1