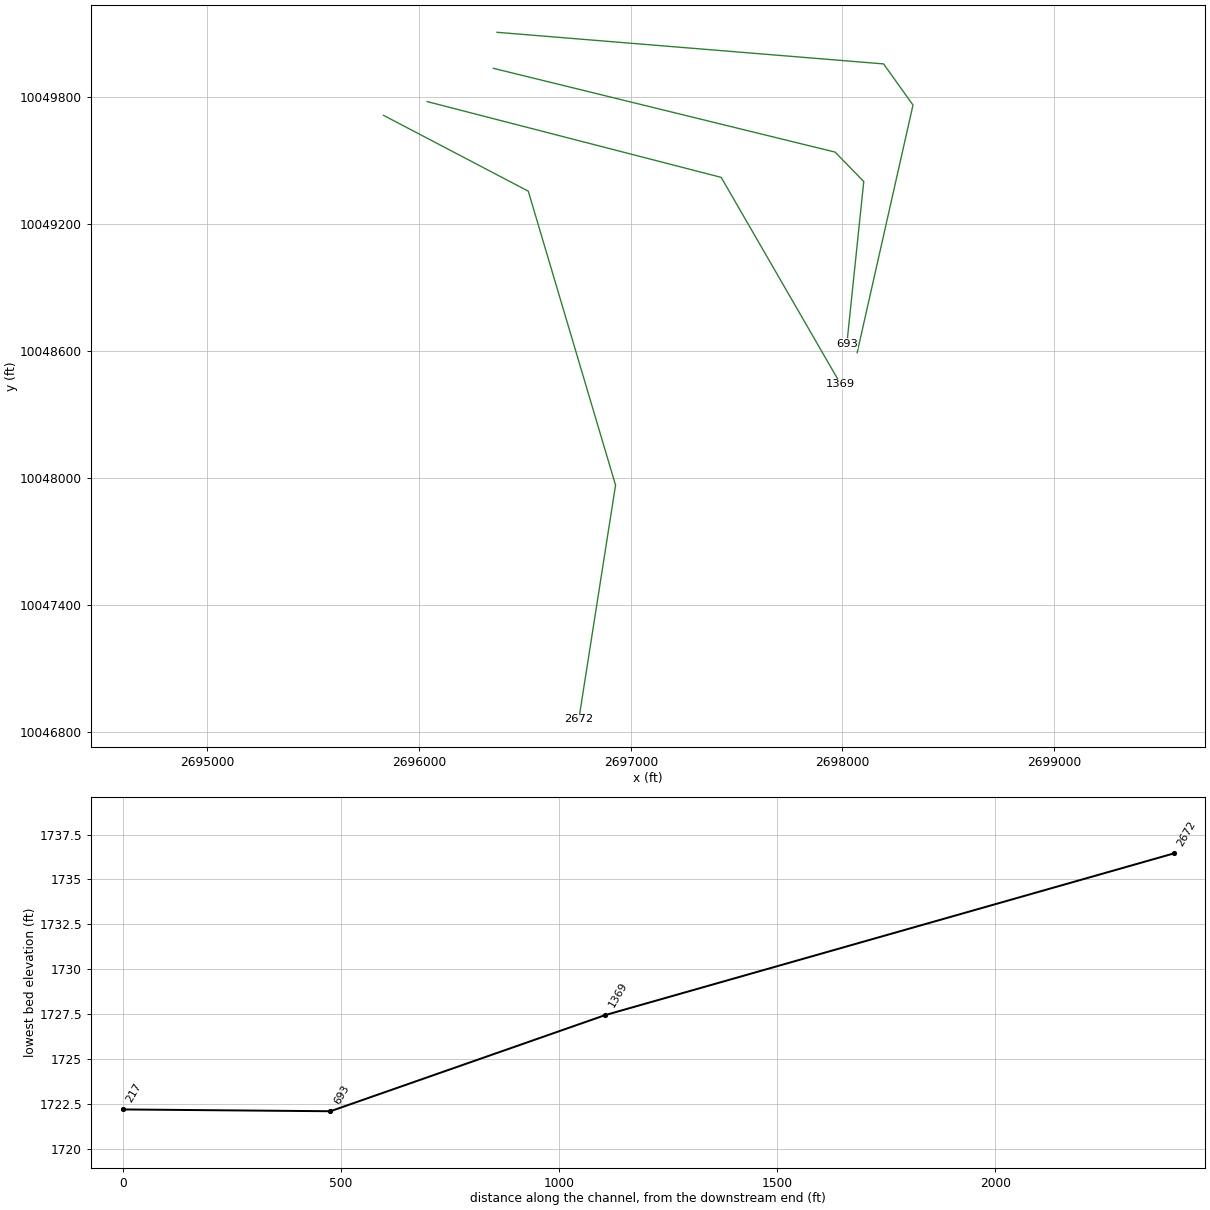
HEC-RAS study WHITE OAK CREEK.prj: WHITE OAK CREEK Base Level Engineering

--- WHITE OAK CREEK.g01 (geometry) --- (continued)

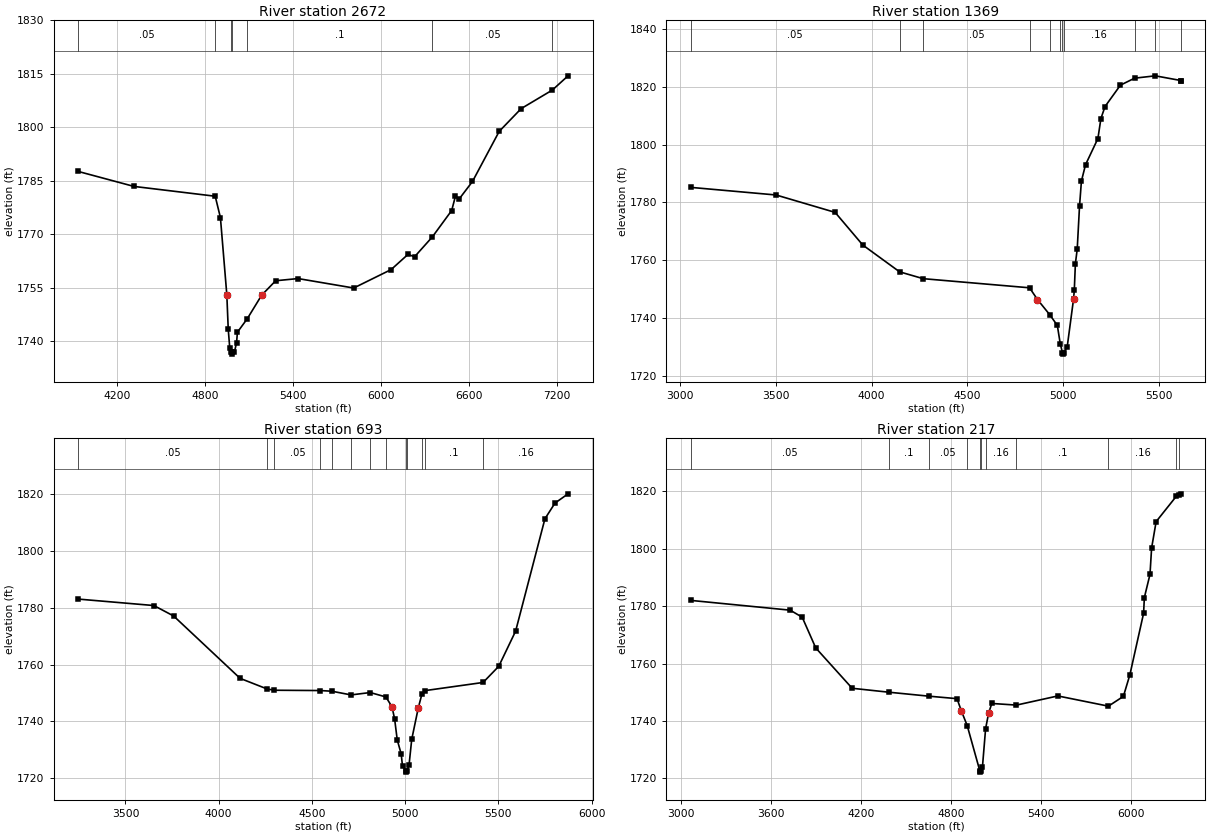
Type RM Length L Ch R = 1 ,2672    ,1303,1303,1303
BEGIN DESCRIPTION:
WHITE OAK CREEK 4.0
END DESCRIPTION:
XS GIS Cut Line= 4
      2695832.13     10049713.75      2696515.69     10049355.69
      2696928.02      10047966.8       2696754.4       10046860.
#Sta/Elev= 30
  3934.8 1787.67  4316.1 1783.46    4870 1780.71  4905.5 1774.73  4949.1 1753.13
  4958.9 1743.41  4969.3 1738.09  4979.3 1736.95  4982.1 1736.45  4985.3 1736.95
  5000.6 1736.95  5015.6 1739.66  5021.4 1742.59  5089.3 1746.42  5186.9 1752.98
  5282.2 1757.02    5435 1757.63  5814.2 1754.98  6069.4 1760.15  6184.2  1764.4
  6229.2 1763.74  6350.4 1769.31  6482.3 1776.71  6507.4 1780.66  6532.9 1779.92
    6624 1784.84  6806.2 1798.89    6956 1805.27  7168.9 1810.48  7275.6 1814.46
#Mann= 7 ,-1 , 0
  3934.8     .05       0    4870      .1       0  4979.3     .07       0
  4985.3      .1       0  5089.3      .1       0  6350.4     .05       0
  7168.9      .1       0
Bank Sta=4949.1,5186.9
XS Rating Curve= 0 ,0
Exp/Cntr=0.3,0.1

Type RM Length L Ch R = 1 ,1369    ,630,630,630
BEGIN DESCRIPTION:
WHITE OAK CREEK 2.0
END DESCRIPTION:
XS GIS Cut Line= 3
       2696038.3     10049778.86      2697427.15     10049420.79
      2697991.38     10048444.24
#Sta/Elev= 30
  3055.1 1785.16  3500.4 1782.53  3809.1 1776.51  3953.7 1765.21  4146.2 1755.93
  4269.7 1753.56  4825.8  1750.4  4867.3 1746.33  4931.6 1741.06    4971 1737.38
  4986.1  1731.1  4997.8 1727.94  5000.6 1727.44  5003.8 1727.94  5022.4 1729.85
 5055.68 1746.43  5059.7 1749.51  5065.4 1758.73    5075 1763.78    5087 1778.59
    5097 1787.36  5118.5 1793.01  5183.2 1802.08  5198.9 1808.99  5220.5 1813.16
  5300.9 1820.55  5375.1 1822.97  5483.3 1823.78  5616.5 1822.16  5617.2 1822.16
#Mann= 11 ,-1 , 0
  3055.1     .05       0  4146.2      .1       0  4269.7     .05       0
  4825.8      .1       0  4931.6     .05       0  4986.1     .16       0
  4997.8     .07       0  5003.8     .16       0  5375.1      .1       0
  5483.3     .16       0  5616.5      .1       0
Bank Sta=4867.3,5055.68
XS Rating Curve= 0 ,0
Exp/Cntr=0.3,0.1

Type RM Length L Ch R = 1 ,693     ,476,476,476
BEGIN DESCRIPTION:
Mapping XS f5ca8bd7
END DESCRIPTION:
XS GIS Cut Line= 4
      2696350.62      10049936.1      2697965.23     10049540.26
      2698100.64     10049401.37      2698020.78     10048634.02
#Sta/Elev= 30
  3245.8 1783.07  3652.5 1780.79  3758.4 1777.11  4115.1 1755.12  4260.9 1751.36
  4299.3 1750.94  4545.9 1750.83  4607.3 1750.59    4710 1749.29  4812.7 1750.13
  4896.7 1748.58  4929.3 1745.13  4943.5 1740.87  4957.6 1733.46  4978.8 1728.48
  4985.9 1724.22    5004 1722.58  5006.8 1722.08    5010 1722.58  5021.2 1724.72
  5035.3 1733.61  5070.8  1744.8  5089.9 1749.57    5108 1750.82  5418.1 1753.68
    5502 1759.37  5592.5 1771.77  5749.7 1811.36  5803.6 1816.89  5873.7 1820.16
#Mann= 13 ,-1 , 0
  3245.8     .05       0  4260.9      .1       0  4299.3     .05       0
  4545.9      .1       0  4607.3     .05       0    4710      .1       0
  4812.7     .05       0  4896.7      .1       0    5004     .07       0
    5010      .1       0  5089.9     .16       0    5108      .1       0
  5418.1     .16       0
Bank Sta=4929.3,5070.8
XS Rating Curve= 0 ,0
Exp/Cntr=0.3,0.1

Type RM Length L Ch R = 1 ,217     ,0,0,0
BEGIN DESCRIPTION:
WHITE OAK CREEK 1.0
END DESCRIPTION:
XS GIS Cut Line= 4
      2696368.05     10050106.23      2698194.39     10049956.93
      2698333.28     10049762.48       2698069.4     10048592.36
#Sta/Elev= 30
  3064.8    1782  3727.4  1778.6  3807.7 1776.15  3898.1 1765.45  4141.2 1751.39
  4386.3 1750.02  4655.1 1748.63  4841.1 1747.77  4870.6 1743.44  4909.1  1738.4
  4993.1 1722.68  4995.8 1722.18  4999.1 1722.68  5010.8 1723.93    5032 1737.33
  5052.6 1742.87  5073.5  1746.1  5237.6 1745.53  5514.2 1748.72  5851.6 1745.16
  5951.7 1748.57  5994.9 1756.08  6086.5 1777.51  6091.7    1783  6129.3 1791.07
    6140 1800.23  6170.3 1809.45  6305.5 1818.31  6322.8 1818.88  6335.7 1819.13
#Mann= 11 ,-1 , 0
  3064.8     .05       0  4386.3      .1       0  4655.1     .05       0
  4909.1     .16       0  4993.1     .07       0  4999.1     .16       0
    5032     .16       0  5237.6      .1       0  5851.6     .16       0
  6305.5      .1       0  6322.8     .16       0
Bank Sta=4870.6,5052.6
XS Rating Curve= 0 ,0
Exp/Cntr=0.3,0.1

Chan Stop Cuts=-1
Use User Specified Reach Order=0
Composite Channel Slope=5