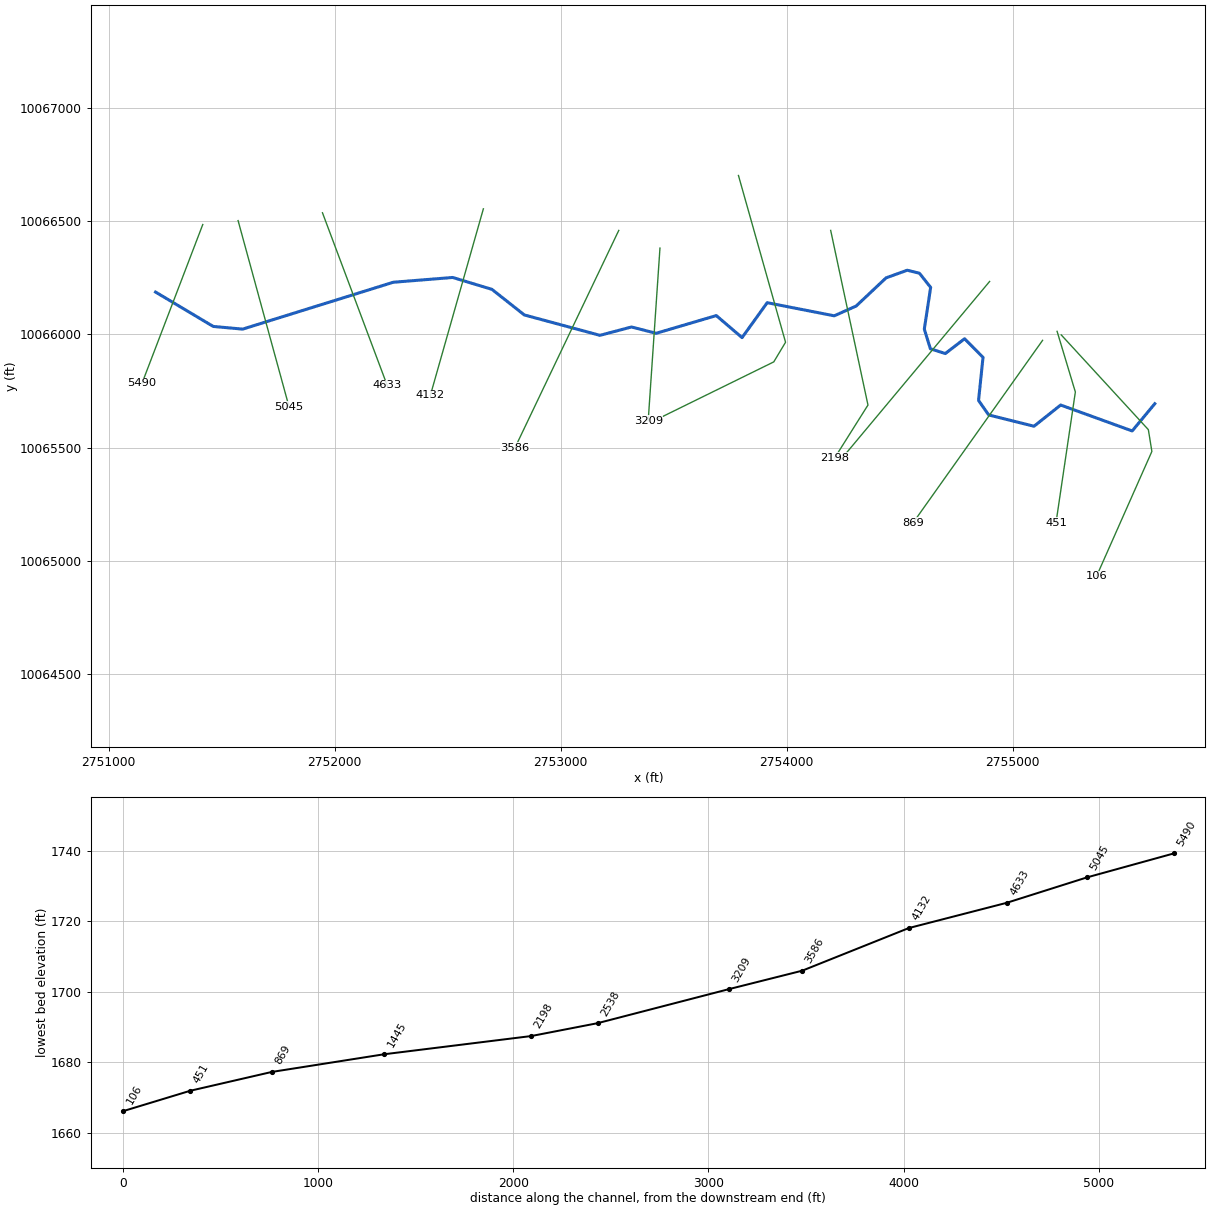
--- WINFRIED CREEK.prj (project) ---

Proj Title=WINFRIED CREEK Base Level Engineering
Current Plan=p01
Default Exp/Contr=0.3,0.1
English Units
Geom File=g01
Flow File=f01
Plan File=p01
BEGIN DESCRIPTION:
WINFRIED CREEK
END DESCRIPTION:

--- WINFRIED CREEK.p01 (plan) ---

Plan Title=Multiple Run
Short Identifier=Multiple
Geom File=g01
Flow File=f01
Subcritical Flow
K Sum by GR= 0
Std Step Tol= 0.01
Critical Tol= 0.01
Num of Std Step Trials= 20
Max Error Tol= 0.3
Flow Tol Ratio= 0.001
Split Flow NTrial= 30
Split Flow Tol= 0.02
Split Flow Ratio= 0.02
Log Output Level= 0
Friction Slope Method= 1
Unsteady Friction Slope Method= 2
Unsteady Bridges Friction Slope Method= 1
Parabolic Critical Depth
Global Vel Dist=  1 , 1 , 1
Global Log Level= 0
CheckData=True
Encroach Param= -1, 0, 0, 0
BEGIN DESCRIPTION:
Multiple Run
END DESCRIPTION:

--- WINFRIED CREEK.f01 (steady flow) ---

Flow Title=Multiple
Number of Profiles=7
Profile Names=10-year,25-year,50-year,1pct_min,100-year,1pct_plu,500-year
River Rch & RM= WINFRIED CREEK,Reach-1,5490
     459     649     810     743    1004    1358    1549
River Rch & RM= WINFRIED CREEK,Reach-1,2198
     702    1017    1291    1200    1623    2195    2579
Boundary for River Rch & Prof#=WINFRIED CREEK,Reach-1,1
Up Type=0
Dn Type=3
Dn Slope=0.005
Boundary for River Rch & Prof#=WINFRIED CREEK,Reach-1,2
Up Type=0
Dn Type=3
Dn Slope=0.005
Boundary for River Rch & Prof#=WINFRIED CREEK,Reach-1,3
Up Type=0
Dn Type=3
Dn Slope=0.005
Boundary for River Rch & Prof#=WINFRIED CREEK,Reach-1,4
Up Type=0
Dn Type=3
Dn Slope=0.005
Boundary for River Rch & Prof#=WINFRIED CREEK,Reach-1,5
Up Type=0
Dn Type=3
Dn Slope=0.005
Boundary for River Rch & Prof#=WINFRIED CREEK,Reach-1,6
Up Type=0
Dn Type=3
Dn Slope=0.005
Boundary for River Rch & Prof#=WINFRIED CREEK,Reach-1,7
Up Type=0
Dn Type=3
Dn Slope=0.005

--- WINFRIED CREEK.g01 (geometry) ---

Geom Title=Existing Conditions

River Reach=WINFRIED CREEK,Reach-1
Reach XY= 30
      2751208.01     10066187.73      2751463.47     10066035.47
      2751593.44     10066023.68      2752259.70     10066231.02
      2752522.62     10066252.15      2752696.16     10066199.64
      2752839.56     10066086.38      2753173.99     10065996.20
      2753313.72     10066033.15      2753422.65     10066005.22
      2753688.67     10066083.56      2753802.73     10065986.07
      2753913.88     10066140.62      2754210.49     10066082.52
      2754307.62     10066125.91      2754439.82     10066250.45
      2754533.42     10066284.21      2754587.42     10066270.82
      2754637.00     10066208.13      2754608.99     10066023.66
      2754635.80     10065936.76      2754701.85     10065915.61
      2754787.15     10065981.15      2754868.65     10065898.69
      2754848.89     10065708.17      2754893.76     10065644.07
      2755094.30     10065594.01      2755212.11     10065687.92
      2755528.55     10065573.25      2755628.47     10065693.73

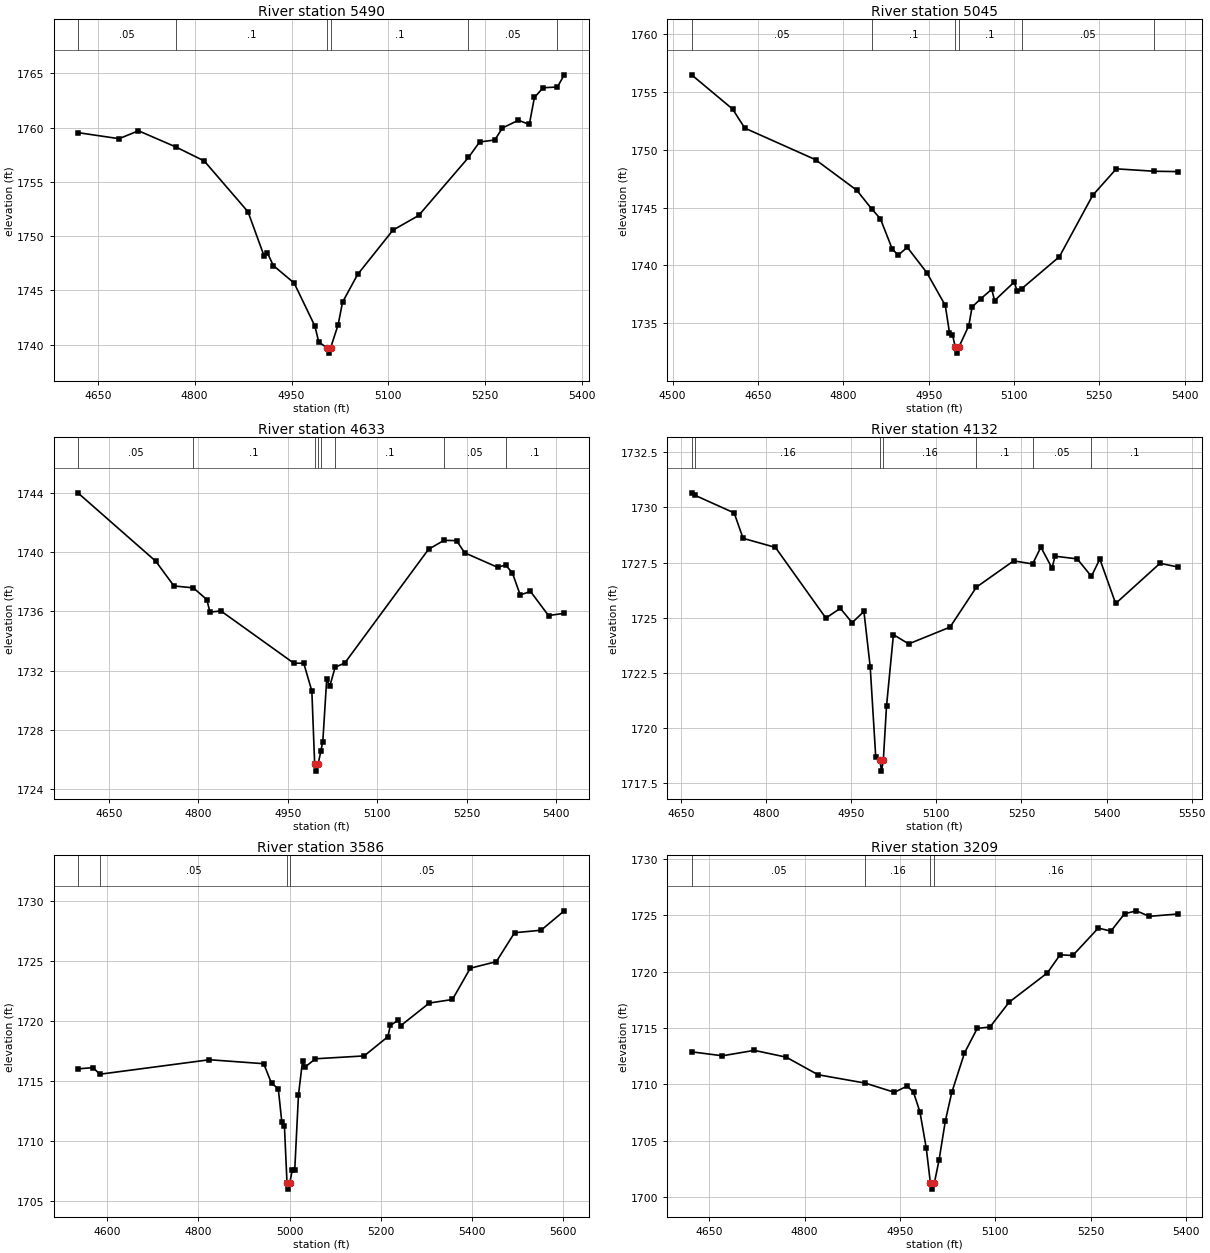
Type RM Length L Ch R = 1,5490,445,445,445
BEGIN DESCRIPTION:
WINFRIED CREEK 12.0
END DESCRIPTION:
XS GIS Cut Line= 2
      2751416.98     10066486.39      2751147.87     10065783.23
#Sta/Elev= 30
  4619.3 1759.53  4683.1 1758.97  4713.1 1759.70  4771.0 1758.21  4814.9 1756.92
  4882.7 1752.24  4907.4 1748.20  4912.8 1748.44  4921.9 1747.29  4954.1 1745.68
  4986.2 1741.72  4992.2 1740.25  5004.6 1739.73  5007.4 1739.23  5010.6 1739.73
  5022.2 1741.85  5029.0 1743.92  5052.3 1746.47  5107.0 1750.55  5146.8 1751.90
  5223.9 1757.24  5241.2 1758.67  5264.6 1758.85  5276.6 1759.96  5301.3 1760.67
  5318.1 1760.28  5326.0 1762.77  5339.5 1763.66  5361.6 1763.73  5372.2 1764.85
#Mann=6,-1,0
  4619.3    0.05       0  4771.0     0.1       0  5004.6    0.07       0
  5010.6     0.1       0  5223.9    0.05       0  5361.6     0.1       0
Bank Sta=5004.6,5010.6
Exp/Cntr=0.3,0.1

Type RM Length L Ch R = 1,5045,412,412,412
BEGIN DESCRIPTION:
WINFRIED CREEK 11.0
END DESCRIPTION:
XS GIS Cut Line= 2
      2751573.21     10066503.77      2751798.91     10065679.10
#Sta/Elev= 30
  4533.3 1756.47  4605.4 1753.51  4626.7 1751.87  4751.1 1749.14  4823.6 1746.50
  4849.8 1744.89  4865.1 1744.04  4885.8 1741.44  4896.2 1740.89  4912.4 1741.57
  4946.9 1739.37  4979.2 1736.55  4986.6 1734.19  4991.8 1734.03  4996.9 1732.93
  4999.6 1732.43  5002.9 1732.93  5020.6 1734.81  5026.3 1736.41  5041.4 1737.12
  5060.8 1737.94  5065.9 1736.97  5100.4 1738.57  5105.6 1737.78  5113.2 1737.98
  5179.8 1740.76  5238.3 1746.06  5279.8 1748.35  5346.7 1748.14  5388.3 1748.11
#Mann=6,-1,0
  4533.3    0.05       0  4849.8     0.1       0  4996.9    0.07       0
  5002.9     0.1       0  5113.2    0.05       0  5346.7     0.1       0
Bank Sta=4996.9,5002.9
Exp/Cntr=0.3,0.1

Type RM Length L Ch R = 1,4633,501,501,501
BEGIN DESCRIPTION:
WINFRIED CREEK 10.0
END DESCRIPTION:
XS GIS Cut Line= 2
      2751946.48     10066538.48      2752232.96     10065774.53
#Sta/Elev= 30
  4597.8 1744.01  4728.7 1739.38  4758.9 1737.72  4791.5 1737.59  4814.1 1736.80
  4819.4 1735.95  4837.8 1736.03  4960.1 1732.50  4976.7 1732.50  4990.3 1730.62
  4995.0 1725.71  4997.8 1725.21  5001.0 1725.71  5005.3 1726.55  5008.7 1727.21
  5015.2 1731.41  5020.6 1730.98  5029.4 1732.23  5045.5 1732.51  5186.1 1740.20
  5212.1 1740.80  5233.0 1740.78  5246.6 1739.96  5301.8 1738.98  5315.4 1739.13
  5326.7 1738.60  5339.8 1737.11  5357.0 1737.35  5387.3 1735.72  5413.7 1735.87
#Mann=8,-1,0
  4597.8    0.05       0  4791.5     0.1       0  4995.0    0.07       0
  5001.0     0.1       0  5005.3    0.16       0  5029.4     0.1       0
  5212.1    0.05       0  5315.4     0.1       0
Bank Sta=4995,5001
Exp/Cntr=0.3,0.1

Type RM Length L Ch R = 1,4132,546,546,546
BEGIN DESCRIPTION:
WINFRIED CREEK 9.0
END DESCRIPTION:
XS GIS Cut Line= 2
      2752658.30     10066555.84      2752423.93     10065731.20
#Sta/Elev= 30
  4668.7 1730.66  4674.5 1730.55  4743.7 1729.75  4759.4 1728.60  4816.4 1728.19
  4905.3 1724.99  4930.8 1725.43  4951.6 1724.78  4972.4 1725.29  4983.5 1722.77
  4993.2 1718.71  5000.6 1718.56  5003.3 1718.06  5006.6 1718.56  5012.2 1721.00
  5024.4 1724.24  5051.3 1723.82  5124.2 1724.58  5170.7 1726.39  5236.3 1727.58
  5269.7 1727.44  5284.3 1728.20  5304.0 1727.25  5309.2 1727.79  5348.3 1727.67
  5373.3 1726.88  5388.2 1727.66  5416.1 1725.65  5494.3 1727.47  5526.0 1727.30
#Mann=7,-1,0
  4668.7    0.05       0  4674.5    0.16       0  5000.6    0.07       0
  5006.6    0.16       0  5170.7     0.1       0  5269.7    0.05       0
  5373.3     0.1       0
Bank Sta=5000.6,5006.6
Exp/Cntr=0.3,0.1

Type RM Length L Ch R = 1,3586,377,377,377
BEGIN DESCRIPTION:
WINFRIED CREEK 8.0
END DESCRIPTION:
XS GIS Cut Line= 2
      2753257.27     10066460.36      2752797.65     10065497.76
#Sta/Elev= 30
  4535.5 1716.01  4569.0 1716.11  4583.5 1715.56  4824.1 1716.77  4943.1 1716.44
  4960.2 1714.80  4975.0 1714.36  4982.9 1711.54  4988.5 1711.24  4994.2 1706.47
  4996.9 1705.97  5000.2 1706.47  5005.6 1707.56  5011.1 1707.54  5019.3 1713.83
  5028.3 1716.68  5033.8 1716.16  5056.5 1716.85  5163.4 1717.09  5215.3 1718.69
  5220.9 1719.64  5238.0 1720.06  5243.5 1719.61  5306.1 1721.50  5357.0 1721.80
  5396.1 1724.41  5453.3 1724.96  5493.1 1727.37  5551.3 1727.58  5602.2 1729.20
#Mann=4,-1,0
  4535.5     0.1       0  4583.5    0.05       0  4994.2    0.04       0
  5000.2    0.05       0
Bank Sta=4994.2,5000.2
Exp/Cntr=0.3,0.1

Type RM Length L Ch R = 1,3209,671,671,671
BEGIN DESCRIPTION:
WINFRIED CREEK 7.0
END DESCRIPTION:
XS GIS Cut Line= 2
      2753439.54     10066382.15      2753387.47     10065618.52
#Sta/Elev= 30
  4622.3 1712.89  4670.8 1712.54  4720.9 1713.02  4771.1 1712.42  4821.2 1710.86
  4895.4 1710.12  4941.5 1709.30  4961.5 1709.86  4971.5 1709.30  4981.6 1707.56
  4991.6 1704.34  4998.1 1701.22  5000.8 1700.72  5004.1 1701.22  5011.6 1703.27
  5021.6 1706.78  5031.7 1709.29  5051.7 1712.79  5071.8 1714.97  5091.8 1715.09
  5121.9 1717.29  5182.0 1719.88  5202.1 1721.49  5222.1 1721.43  5262.2 1723.86
  5282.2 1723.59  5303.5 1725.13  5322.3 1725.39  5342.4 1724.90  5387.7 1725.11
#Mann=4,-1,0
  4622.3    0.05       0  4895.4    0.16       0  4998.1    0.07       0
  5004.1    0.16       0
Bank Sta=4998.1,5004.1
Exp/Cntr=0.3,0.1

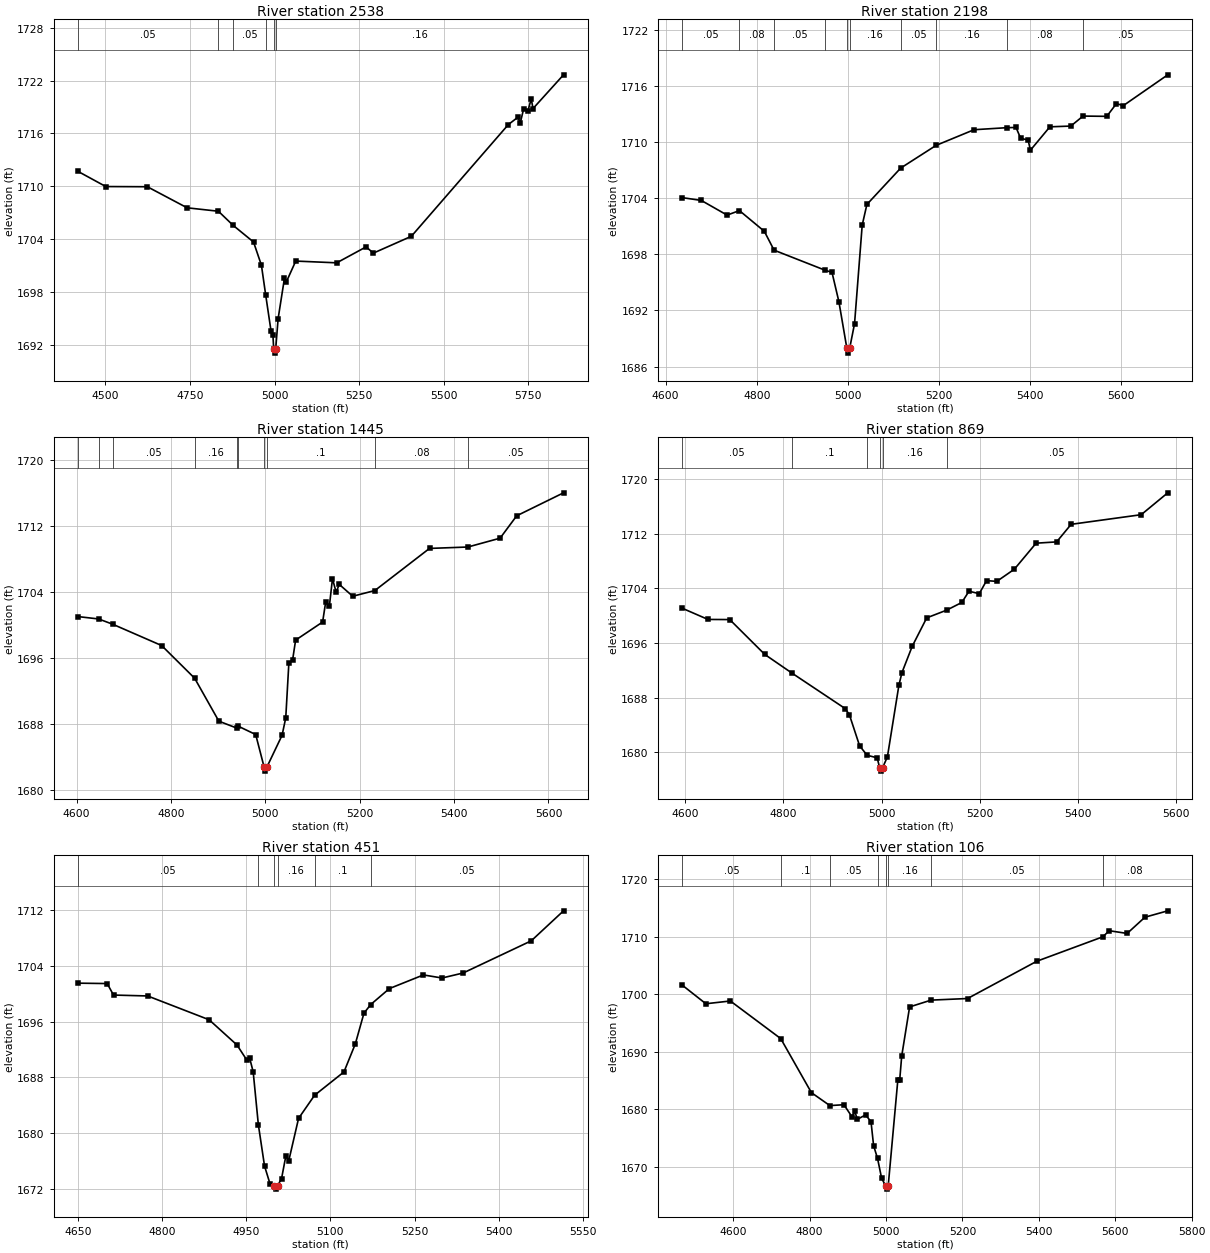
Type RM Length L Ch R = 1,2538,340,340,340
BEGIN DESCRIPTION:
WINFRIED CREEK 6.0
END DESCRIPTION:
XS GIS Cut Line= 4
      2753786.77     10066703.36      2753995.10     10065965.53
      2753943.02     10065878.73      2753433.90     10065628.48
#Sta/Elev= 30
  4418.5 1711.71  4501.2 1709.98  4623.9 1709.96  4741.5 1707.57  4833.9 1707.18
  4877.1 1705.59  4937.7 1703.69  4961.0 1701.06  4973.6 1697.69  4989.6 1693.55
  4995.0 1693.14  4997.2 1691.59  4999.9 1691.09  5003.2 1691.59  5010.4 1695.01
  5029.0 1699.56  5034.2 1699.13  5062.4 1701.53  5183.5 1701.33  5270.4 1703.14
  5291.7 1702.43  5404.1 1704.34  5690.7 1717.01  5718.8 1717.84  5726.0 1717.21
  5735.7 1718.77  5748.3 1718.54  5758.2 1719.90  5763.7 1718.83  5853.7 1722.65
#Mann=6,-1,0
  4418.5    0.05       0  4833.9    0.08       0  4877.1    0.05       0
  4973.6    0.16       0  4997.2    0.07       0  5003.2    0.16       0
Bank Sta=4997.2,5003.2
Exp/Cntr=0.3,0.1

Type RM Length L Ch R = 1,2198,753,753,753
BEGIN DESCRIPTION:
WINFRIED CREEK 5.0
END DESCRIPTION:
XS GIS Cut Line= 3
      2754194.75     10066460.35      2754359.68     10065687.76
      2754212.79     10065454.45
#Sta/Elev= 30
  4636.0 1704.07  4678.2 1703.77  4734.8 1702.20  4761.9 1702.68  4816.5 1700.47
  4837.9 1698.45  4950.7 1696.29  4965.0 1696.08  4980.2 1692.93  4997.7 1687.94
  5000.4 1687.44  5003.7 1687.94  5014.5 1690.59  5031.3 1701.13  5041.6 1703.34
  5115.8 1707.23  5193.6 1709.66  5276.7 1711.33  5349.3 1711.55  5368.8 1711.57
  5379.0 1710.41  5395.3 1710.23  5400.4 1709.14  5443.1 1711.64  5489.0 1711.72
  5515.9 1712.79  5567.9 1712.76  5589.1 1714.12  5604.3 1713.91  5701.7 1717.20
#Mann=10,-1,0
  4636.0    0.05       0  4761.9    0.08       0  4837.9    0.05       0
  4950.7    0.16       0  4997.7    0.07       0  5003.7    0.16       0
  5115.8    0.05       0  5193.6    0.16       0  5349.3    0.08       0
  5515.9    0.05       0
Bank Sta=4997.7,5003.7
Exp/Cntr=0.3,0.1

Type RM Length L Ch R = 1,1445,576,576,576
BEGIN DESCRIPTION:
WINFRIED CREEK 3.0
END DESCRIPTION:
XS GIS Cut Line= 2
      2754897.86     10066234.61      2754238.13     10065444.67
#Sta/Elev= 30
  4602.7 1700.99  4646.8 1700.70  4676.3 1700.07  4780.4 1697.48  4850.3 1693.52
  4901.5 1688.33  4939.5 1687.49  4942.2 1687.73  4979.6 1686.71  4997.4 1682.78
  5000.1 1682.28  5003.4 1682.78  5035.5 1686.62  5043.3 1688.73  5049.9 1695.38
  5057.7 1695.70  5064.2 1698.14  5121.4 1700.33  5127.9 1702.74  5135.7 1702.24
  5142.3 1705.58  5150.1 1703.93  5156.6 1704.89  5185.2 1703.45  5232.1 1704.14
  5347.9 1709.24  5429.2 1709.41  5497.5 1710.48  5532.7 1713.19  5631.9 1715.97
#Mann=10,-1,0
  4602.7    0.05       0  4646.8     0.1       0  4676.3    0.05       0
  4850.3    0.16       0  4939.5    0.05       0  4942.2     0.1       0
  4997.4    0.07       0  5003.4     0.1       0  5232.1    0.08       0
  5429.2    0.05       0
Bank Sta=4997.4,5003.4
Exp/Cntr=0.3,0.1

Type RM Length L Ch R = 1,869,418,418,418
BEGIN DESCRIPTION:
WINFRIED CREEK 2.0
END DESCRIPTION:
XS GIS Cut Line= 2
      2755132.26     10065974.22      2754559.99     10065167.85
#Sta/Elev= 30
  4593.7 1701.11  4646.5 1699.46  4690.8 1699.44  4762.1 1694.34  4818.0 1691.58
  4925.7 1686.42  4934.3 1685.53  4955.2 1680.96  4970.5 1679.58  4990.9 1679.21
  4996.0 1677.76  4998.7 1677.26  5002.0 1677.76  5011.8 1679.36  5035.2 1689.84
  5041.4 1691.68  5062.3 1695.53  5091.8 1699.69  5132.4 1700.82  5163.2 1701.94
  5177.9 1703.59  5198.8 1703.23  5213.6 1705.14  5234.5 1705.03  5270.2 1706.81
  5314.5 1710.62  5356.3 1710.81  5385.8 1713.38  5528.5 1714.79  5582.5 1717.99
#Mann=6,-1,0
  4593.7    0.05       0  4818.0     0.1       0  4970.5    0.16       0
  4996.0    0.07       0  5002.0    0.16       0  5132.4    0.05       0
Bank Sta=4996,5002
Exp/Cntr=0.3,0.1

Type RM Length L Ch R = 1,451,345,345,345
BEGIN DESCRIPTION:
Mapping XS cc93cca5
END DESCRIPTION:
XS GIS Cut Line= 3
      2755196.38     10066013.85      2755277.12     10065745.61
      2755191.47     10065166.84
#Sta/Elev= 30
  4650.2 1701.51  4702.5 1701.45  4713.8 1699.80  4774.6 1699.67  4884.1 1696.25
  4933.8 1692.62  4951.3 1690.45  4956.4 1690.72  4962.6 1688.75  4971.8 1681.16
  4982.8 1675.24  4992.9 1672.59  5000.0 1672.42  5002.7 1671.92  5006.0 1672.42
  5013.1 1673.43  5020.9 1676.75  5025.9 1675.98  5043.4 1682.08  5071.9 1685.40
  5124.3 1688.76  5144.5 1692.78  5159.9 1697.20  5172.0 1698.44  5205.2 1700.73
  5265.8 1702.69  5299.0 1702.25  5336.6 1702.97  5457.9 1707.59  5515.4 1711.90
#Mann=6,-1,0
  4650.2    0.05       0  4971.8    0.16       0  5000.0    0.07       0
  5006.0    0.16       0  5071.9     0.1       0  5172.0    0.05       0
Bank Sta=5000,5006
Exp/Cntr=0.3,0.1

Type RM Length L Ch R = 1,106,0,0,0
BEGIN DESCRIPTION:
WINFRIED CREEK 1.0
END DESCRIPTION:
XS GIS Cut Line= 4
      2755214.62     10065998.21      2755600.03     10065578.95
      2755615.66     10065482.59      2755370.88     10064930.54
#Sta/Elev= 30
  4466.4 1701.60  4528.7 1698.34  4592.8 1698.82  4724.7 1692.28  4804.9 1682.89
  4853.2 1680.64  4890.0 1680.79  4911.0 1678.70  4918.3 1679.66  4925.1 1678.25
  4946.7 1679.02  4960.9 1677.84  4967.7 1673.67  4978.0 1671.45  4988.7 1668.00
  4999.8 1666.62  5002.6 1666.12  5005.8 1666.62  5031.0 1685.03  5035.9 1685.03
  5041.2 1689.24  5061.9 1697.79  5118.1 1698.97  5213.6 1699.25  5394.8 1705.73
  5566.9 1709.96  5584.6 1711.03  5631.2 1710.56  5677.7 1713.38  5737.4 1714.49
#Mann=8,-1,0
  4466.4    0.05       0  4724.7     0.1       0  4853.2    0.05       0
  4978.0    0.16       0  4999.8    0.07       0  5005.8    0.16       0
  5118.1    0.05       0  5566.9    0.08       0
Bank Sta=4999.8,5005.8
Exp/Cntr=0.3,0.1

Chan Stop Cuts=-1