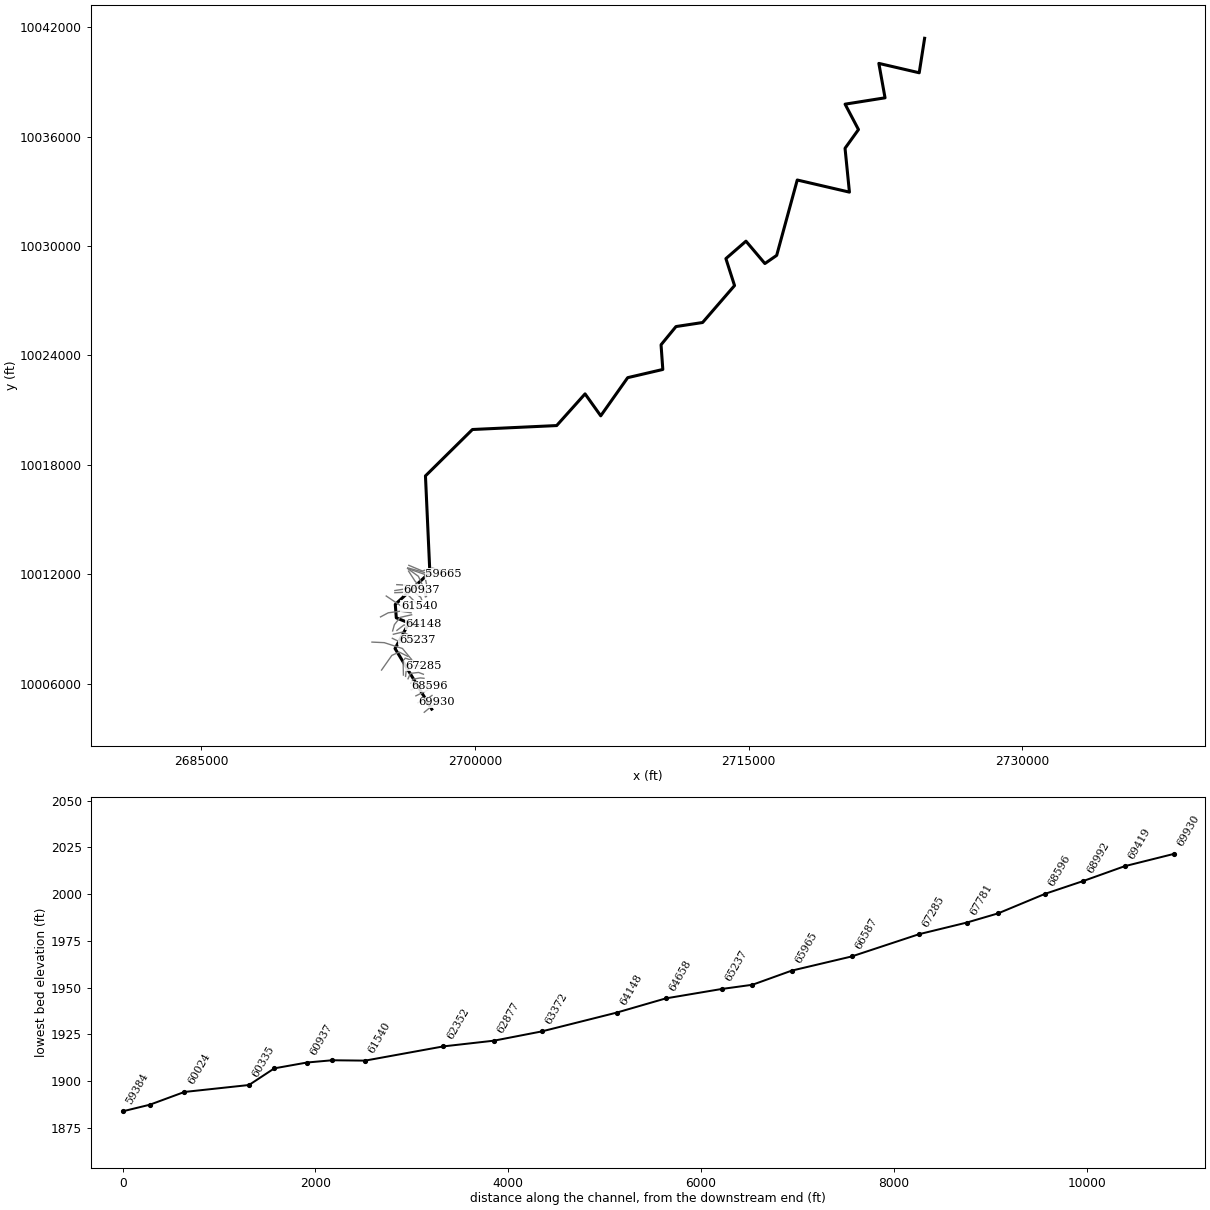
--- WOLF CREEK.prj (project) ---

Proj Title=WOLF CREEK Base Level Engineering
Current Plan=p01
Default Exp/Contr=0.3,0.1
English Units
Geom File=g01
Flow File=f01
Plan File=p01
Y Axis Title=Elevation
X Axis Title(PF)=Main Channel Distance
X Axis Title(XS)=Station
BEGIN DESCRIPTION:
WOLF CREEK
END DESCRIPTION:
DSS Export Rating Curves= 0
DSS Export Rating Curve Sorted= 0
DSS Export Volume Flow Curves= 0
DXF OffsetX= 0
DXF OffsetY= 0
DXF ScaleX= 1
DXF ScaleY= 10

--- WOLF CREEK.p01 (plan) ---

Plan Title=Multiple Run
Short Identifier=Multiple
Geom File=g01
Flow File=f01
Subcritical Flow
K Sum by GR= 0
Std Step Tol= 0.01
Critical Tol= 0.01
Num of Std Step Trials= 20
Max Error Tol= 0.3
Flow Tol Ratio= 0.001
Split Flow NTrial= 30
Split Flow Tol= 0.02
Split Flow Ratio= 0.02
Log Output Level= 0
Friction Slope Method= 1
Unsteady Friction Slope Method= 2
Unsteady Bridges Friction Slope Method= 1
Parabolic Critical Depth
Global Vel Dist=  1 , 1 , 1
Global Log Level= 0
CheckData=True
Encroach Param= -1, 0, 0, 0
BEGIN DESCRIPTION:
Multiple Run
END DESCRIPTION:

--- WOLF CREEK.f01 (steady flow) ---

Flow Title=Multiple
Program Version=4.10
Number of Profiles= 7
Profile Names=10-year,25-year,50-year,1pct_min,100-year,1pct_plu,500-year
River Rch & RM=WOLF CREEK,Reach-1         ,69930
     734    1036    1291    1175    1588    2148    2400
River Rch & RM=WOLF CREEK,Reach-1         ,65965
    1465    2157    2763    2580    3489    4718    5556
River Rch & RM=WOLF CREEK,Reach-1         ,65237
    1875    2790    3598    3378    4568    6178    7360
River Rch & RM=WOLF CREEK,Reach-1         ,64658
    1875    2790    3598    3378    4568    6178    7360
River Rch & RM=WOLF CREEK,Reach-1         ,60598
    2713    4118    5383    5115    6917    9355   11426
River Rch & RM=WOLF CREEK,Reach-1         ,59665
    3114    4748    6224    5928    8017   10842   13304
River Rch & RM=WOLF CREEK,Reach-1         ,57034
    3599    5504    7227    6890    9318   12602   15496
River Rch & RM=WOLF CREEK,Reach-1         ,49683
    5751    8980   11961   11553   15624   21129   26671
River Rch & RM=WOLF CREEK,Reach-1         ,49300
    6796   10655   14229   13772   18625   25189   31927
River Rch & RM=WOLF CREEK,Reach-1         ,45252
    6641   10361   13791   13300   17987   24326   30614
River Rch & RM=WOLF CREEK,Reach-1         ,38592
    7399   11576   15436   14910   20165   27270   34424
River Rch & RM=WOLF CREEK,Reach-1         ,37360
    9887   15578   20875   20249   27384   37034   47131
River Rch & RM=WOLF CREEK,Reach-1         ,35610
    9887   15578   20875   20249   27384   37034   47131
River Rch & RM=WOLF CREEK,Reach-1         ,30024
   10139   15924   21293   20606   27868   37688   47741
River Rch & RM=WOLF CREEK,Reach-1         ,20471
   10301   16182   21643   20954   28337   38323   48597
River Rch & RM=WOLF CREEK,Reach-1         ,19697
   11096   17453   23364   22635   30611   41398   52559
River Rch & RM=WOLF CREEK,Reach-1         ,17386
   11096   17453   23364   22635   30611   41398   52559
River Rch & RM=WOLF CREEK,Reach-1         ,16055
   11043   17344   23195   22450   30361   41059   52035
River Rch & RM=WOLF CREEK,Reach-1         ,11423
   11111   17450   23336   22587   30546   41310   52358
River Rch & RM=WOLF CREEK,Reach-1         ,6984
   10958   17180   22947   22184   30002   40574   51306
River Rch & RM=WOLF CREEK,Reach-1         ,2576
   10959   17176   22939   22173   29987   40554   51271
River Rch & RM=WOLF CREEK,Reach-1         ,1924
   10959   17176   22939   22173   29987   40554   51271
Boundary for River Rch & Prof#=WOLF CREEK,Reach-1         , 1
Up Type= 0
Dn Type= 3
Dn Slope=0.008
Boundary for River Rch & Prof#=WOLF CREEK,Reach-1         , 2
Up Type= 0
Dn Type= 3
Dn Slope=0.008
Boundary for River Rch & Prof#=WOLF CREEK,Reach-1         , 3
Up Type= 0
Dn Type= 3
Dn Slope=0.008
Boundary for River Rch & Prof#=WOLF CREEK,Reach-1         , 4
Up Type= 0
Dn Type= 3
Dn Slope=0.008
Boundary for River Rch & Prof#=WOLF CREEK,Reach-1         , 5
Up Type= 0
Dn Type= 3
Dn Slope=0.008
Boundary for River Rch & Prof#=WOLF CREEK,Reach-1         , 6
Up Type= 0
Dn Type= 3
Dn Slope=0.008
Boundary for River Rch & Prof#=WOLF CREEK,Reach-1         , 7
Up Type= 0
Dn Type= 3
Dn Slope=0.008
DSS Import GetInterval= 0
DSS Import GetPeak= 0
DSS Import FillOption= 0

--- WOLF CREEK.g01 (geometry) ---

Geom Title=Existing Conditions
Program Version=4.10

River Reach=WOLF CREEK      ,Reach-1
Reach XY= 30
      2697628.47     10004613.73      2695618.47     10007933.73
      2696379.09     10009335.49      2695686.11     10009617.39
      2695631.94     10010352.29      2697525.96     10012108.32
      2697285.09     10017396.28      2699860.45     10019940.14
       2704477.3     10020156.19      2706033.13     10021893.09
      2706892.11     10020690.48      2708369.92     10022782.02
      2710294.87     10023231.41      2710198.28     10024584.28
      2711017.12     10025582.99      2712475.87       10025805.
      2714226.43     10027829.46      2713752.42     10029307.49
      2714853.07      10030263.4      2715890.05     10029037.36
       2716536.1     10029484.71      2717663.95     10033616.49
      2720523.52     10032951.26      2720282.91     10035354.93
      2721019.36     10036381.27      2720285.14     10037773.43
      2722475.25     10038121.43      2722135.53     10040008.39
      2724348.47     10039493.73       2724644.2     10041384.63

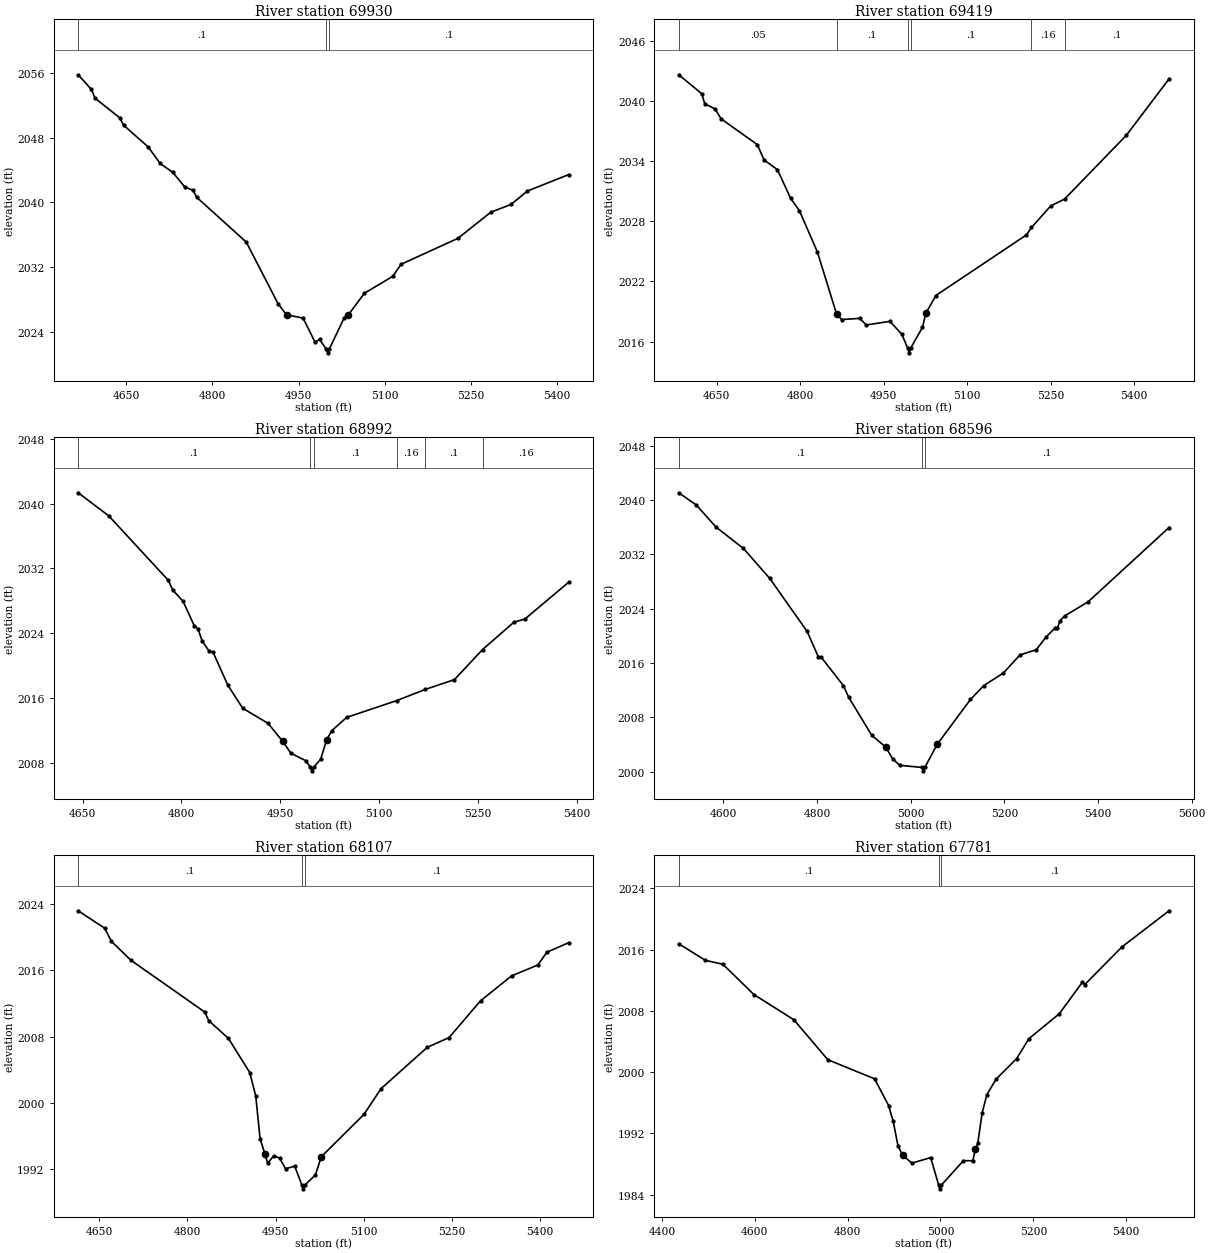
Type RM Length L Ch R = 1 ,69930   ,511,511,511
BEGIN DESCRIPTION:
WOLF CREEK 115.0
END DESCRIPTION:
XS GIS Cut Line= 2
      2697219.69     10004440.97      2697879.45     10004983.54
#Sta/Elev= 30
  4566.2 2055.75  4589.1 2053.94  4595.6 2052.85  4638.6 2050.44  4645.1 2049.54
  4688.1 2046.85  4708.9 2044.81  4731.2  2043.7    4752  2041.9  4766.3  2041.5
  4772.8 2040.63  4858.9 2035.12  4914.8 2027.46  4929.2 2026.15  4957.9 2025.75
  4978.9 2022.76  4986.6 2023.12  4997.9 2021.96  5000.7 2021.46  5003.9 2021.96
  5029.6 2025.79  5036.1 2026.08  5064.8 2028.81  5114.3  2030.9  5128.6 2032.38
  5227.7 2035.58    5285  2038.8  5320.2 2039.76  5348.9 2041.42  5420.4 2043.43
#Mann= 3 ,-1 , 0
  4566.2      .1       0  4997.9     .07       0  5003.9      .1       0
Bank Sta=4929.2,5036.1
XS Rating Curve= 0 ,0
Exp/Cntr=0.3,0.1

Type RM Length L Ch R = 1 ,69419   ,427,427,427
BEGIN DESCRIPTION:
WOLF CREEK 114.0
END DESCRIPTION:
XS GIS Cut Line= 3
      2696868.12     10004961.81      2697393.32     10005178.84
      2697644.29      10005364.9
#Sta/Elev= 30
    4582 2042.62  4623.3 2040.73  4628.7 2039.72  4647.2 2039.22  4658.1 2038.22
    4723 2035.66  4735.2 2034.12  4759.1 2033.16    4783 2030.29  4798.8 2029.05
  4830.8 2024.97  4865.5 2018.75  4866.4  2018.7  4874.5  2018.2    4907 2018.32
  4918.8 2017.66  4961.1 2018.02  4982.7 2016.74  4992.9 2015.38  4995.7 2014.88
  4998.9 2015.38  5019.8 2017.43    5026 2018.85  5043.8  2020.6  5206.6 2026.65
  5215.6 2027.39  5250.4 2029.55    5275 2030.22  5386.1 2036.59  5462.7 2042.21
#Mann= 6 ,-1 , 0
    4582     .05       0  4866.4      .1       0  4992.9     .07       0
  4998.9      .1       0  5215.6     .16       0    5275      .1       0
Bank Sta=4865.5,5026
XS Rating Curve= 0 ,0
Exp/Cntr=0.3,0.1

Type RM Length L Ch R = 1 ,68992   ,396,396,396
BEGIN DESCRIPTION:
WOLF CREEK 113.0
END DESCRIPTION:
XS GIS Cut Line= 2
      2696759.67     10005339.44      2697428.02     10005664.94
#Sta/Elev= 30
  4643.5 2041.33  4689.9 2038.47  4780.1 2030.52  4786.8 2029.33  4802.6 2027.91
  4819.6 2024.88  4825.1 2024.54  4831.3 2023.05  4842.1 2021.76  4847.7 2021.69
  4870.2  2017.6  4892.8 2014.73  4931.4 2012.86  4953.6 2010.64    4966 2009.17
  4988.5 2008.25  4995.1  2007.5  4997.8    2007  5001.1  2007.5    5011 2008.43
  5020.3 2010.86    5028 2011.97  5050.6  2013.6  5126.3 2015.67    5170 2017.06
  5213.9 2018.26  5256.5 2021.97  5304.1 2025.35  5320.7 2025.74  5386.9 2030.27
#Mann= 6 ,-1 , 0
  4643.5      .1       0  4995.1     .07       0  5001.1      .1       0
  5126.3     .16       0    5170      .1       0  5256.5     .16       0
Bank Sta=4953.6,5020.3
XS Rating Curve= 0 ,0
Exp/Cntr=0.3,0.1

Type RM Length L Ch R = 1 ,68596   ,489,489,489
BEGIN DESCRIPTION:
WOLF CREEK 112.0
END DESCRIPTION:
XS GIS Cut Line= 4
      2696525.28     10005664.95      2696768.32      10005842.9
      2697193.67      10005886.3      2697510.54     10005855.92
#Sta/Elev= 30
  4504.6 2041.07  4542.2 2039.26  4583.9 2036.04  4642.6 2032.88  4698.9 2028.47
  4778.4  2020.7  4802.8 2016.91  4808.4 2016.91  4856.2 2012.68  4867.3    2011
  4916.5  2005.4  4946.7 2003.63  4961.8 2001.87  4976.8 2000.96  5024.1 2000.65
  5026.9 2000.15  5030.1 2000.65  5056.3 2004.03  5127.6 2010.65  5155.8 2012.68
    5198 2014.55  5233.3 2017.21  5268.3 2017.98  5288.4  2019.8  5308.1 2021.16
  5313.1  2021.1  5318.6 2022.21  5328.6 2022.94  5378.8 2025.02  5551.7 2035.96
#Mann= 3 ,-1 , 0
  4504.6      .1       0  5024.1     .07       0  5030.1      .1       0
Bank Sta=4946.7,5056.3
XS Rating Curve= 0 ,0
Exp/Cntr=0.3,0.1

Type RM Length L Ch R = 1 ,68107   ,326,326,326
BEGIN DESCRIPTION:
WOLF CREEK 111.0
END DESCRIPTION:
XS GIS Cut Line= 4
      2696512.24     10006042.53      2696612.07     10006255.23
       2697002.7     10006324.67      2697205.04     10006303.14
#Sta/Elev= 30
  4613.9 2023.17  4658.9 2021.07  4670.5 2019.48  4703.6 2017.21  4829.6 2010.96
  4836.2 2009.94  4869.7  2007.8  4906.1 2003.68  4916.3 2000.85  4923.7  1995.7
 4931.82 1993.91  4936.6 1992.74  4946.8 1993.65  4956.9 1993.38  4967.1 1992.09
  4982.7  1992.4  4994.6 1990.17  4997.3 1989.67  5000.6 1990.17  5017.9 1991.34
    5028 1993.54  5100.8 1998.65  5129.6 2001.73  5208.7 2006.73  5245.6 2007.89
  5299.2 2012.32    5352 2015.32  5396.8 2016.64  5412.3 2018.18  5449.1 2019.32
#Mann= 3 ,-1 , 0
  4613.9      .1       0  4994.6     .07       0  5000.6      .1       0
Bank Sta=4931.82,5028
XS Rating Curve= 0 ,0
Exp/Cntr=0.3,0.1

Type RM Length L Ch R = 1 ,67781   ,496,496,496
BEGIN DESCRIPTION:
WOLF CREEK 110.0
END DESCRIPTION:
XS GIS Cut Line= 4
      2696329.94     10006276.89      2696460.16     10006572.07
      2696907.21     10006624.15      2697171.93     10006524.34
#Sta/Elev= 30
  4436.5 2016.75    4494 2014.58  4531.4 2014.08  4598.2 2010.12  4684.4 2006.82
  4757.3 2001.61  4858.1 1999.11  4888.3 1995.62  4898.2 1993.54  4908.4 1990.39
  4918.5  1989.1  4938.6  1988.1  4978.9 1988.82    4996 1985.24  4998.8 1984.74
    5002 1985.24  5049.4 1988.42  5069.5 1988.41  5075.3 1989.93  5080.3 1990.69
  5089.6 1994.64  5099.7 1997.02  5119.8 1999.08  5163.8 2001.74  5190.3 2004.35
  5255.8 2007.61  5305.5 2011.73  5310.8 2011.43  5390.7 2016.34  5492.1 2021.06
#Mann= 3 ,-1 , 0
  4436.5      .1       0    4996     .07       0    5002      .1       0
Bank Sta=4918.5,5075.3
XS Rating Curve= 0 ,0
Exp/Cntr=0.3,0.1

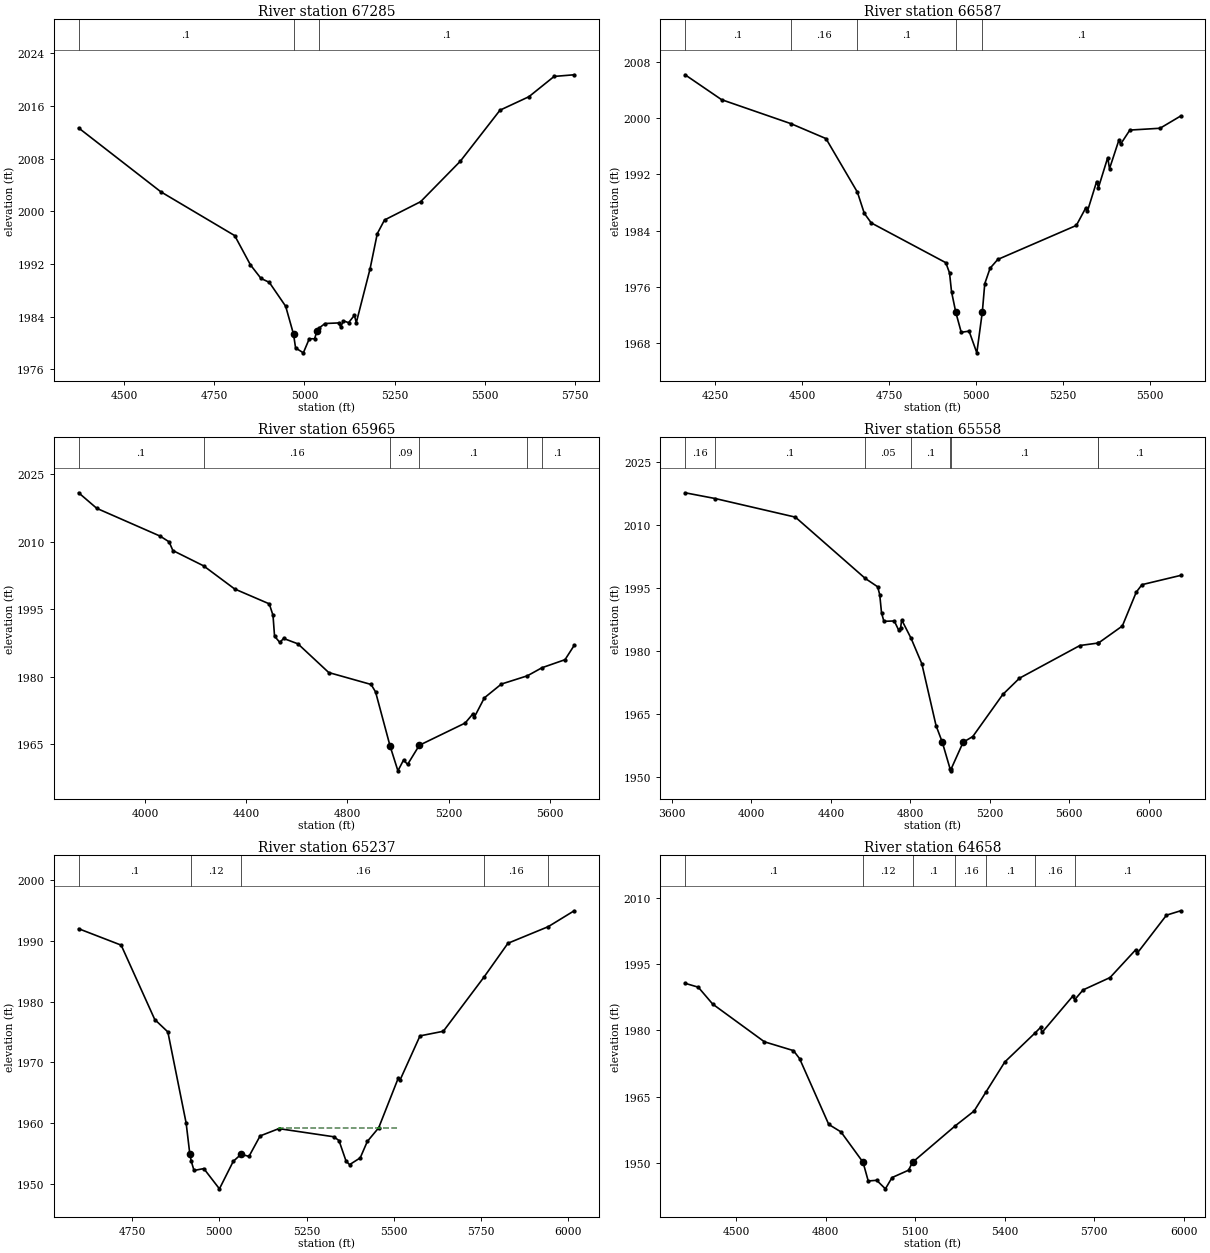
Type RM Length L Ch R = 1 ,67285   ,698,698,698
BEGIN DESCRIPTION:
WOLF CREEK 109.0
END DESCRIPTION:
XS GIS Cut Line= 4
      2696195.41     10006407.18      2696238.81     10006819.46
      2696546.97     10006988.73        2697154.     10006993.07
#Sta/Elev= 30
  4374.2 2012.64    4602 2002.95  4806.7  1996.3  4850.3 1991.86  4879.6  1989.8
  4902.5 1989.21  4947.9 1985.58  4969.7 1981.34  4975.4 1979.25  4996.9 1978.51
  5013.3 1980.64    5028 1980.65  5035.1 1981.85  5040.8 1982.28  5056.9 1982.96
  5094.8 1983.05  5100.5 1982.43  5107.8 1983.37  5122.3 1983.09  5138.4 1984.21
  5143.6 1983.09  5181.8 1991.26  5201.8  1996.6  5221.8 1998.67  5321.9 2001.45
  5431.9 2007.59  5541.9 2015.34  5621.9 2017.38  5691.9 2020.46  5747.4 2020.71
#Mann= 3 ,-1 , 0
  4374.2      .1       0  4969.7     .09       0  5040.8      .1       0
Bank Sta=4969.7,5035.1
XS Rating Curve= 0 ,0
Exp/Cntr=0.3,0.1

Type RM Length L Ch R = 1 ,66587   ,622,622,622
BEGIN DESCRIPTION:
WOLF CREEK 108.0
END DESCRIPTION:
XS GIS Cut Line= 4
      2696077.67     10006478.92      2696060.31     10007194.22
      2696171.42      10007409.5      2696614.69     10007264.05
#Sta/Elev= 30
  4163.8 2006.19  4268.6 2002.65  4468.2 1999.23  4568.7 1997.11    4659 1989.49
  4678.8 1986.48  4698.8 1985.11  4913.1 1979.45  4923.8    1978  4929.6 1975.32
 4941.82 1972.39  4957.5 1969.54    4980 1969.71  5002.3 1966.62  5018.2 1972.48
  5025.1 1976.46  5040.4 1978.66  5062.5 1979.91  5288.3 1984.75  5314.8 1987.19
  5320.1 1986.75  5346.7    1991  5351.9 1990.14  5378.5  1994.4  5383.7 1992.83
  5410.3 1996.84  5415.6 1996.32  5442.1 1998.32  5528.9 1998.58  5588.1 2000.32
#Mann= 5 ,-1 , 0
  4163.8      .1       0  4468.2     .16       0    4659      .1       0
 4941.82     .09       0  5018.2      .1       0
Bank Sta=4941.82,5018.2
XS Rating Curve= 0 ,0
Exp/Cntr=0.3,0.1

Type RM Length L Ch R = 1 ,65965   ,407,407,407
BEGIN DESCRIPTION:
WOLF CREEK 106.0
END DESCRIPTION:
XS GIS Cut Line= 4
      2694878.84     10006754.92      2695443.09     10007557.89
      2695846.74     10007740.18      2696323.83     10007501.63
#Sta/Elev= 30
  3738.2 2020.85  3809.9 2017.39    4060 2011.22  4095.7 2009.94  4110.5 2008.01
  4231.8 2004.61  4354.5 1999.47  4491.3 1996.16  4506.1 1993.61  4512.2 1988.97
  4533.1 1987.58  4547.9 1988.47  4604.6 1987.27  4726.3 1980.89  4893.6 1978.24
  4911.3 1976.58  4968.5 1964.57  4999.6 1959.04  5021.7 1961.43  5037.9 1960.47
  5084.1 1964.72  5265.1 1969.66  5296.4 1971.74    5302 1971.03  5341.2 1975.27
  5408.3 1978.33  5510.9 1980.16  5568.7 1981.96  5659.8 1983.75  5695.9 1986.92
#Mann= 6 ,-1 , 0
  3738.2      .1       0  4231.8     .16       0  4968.5     .09       0
  5084.1      .1       0  5510.9     .16       0  5568.7      .1       0
Bank Sta=4968.5,5084.1
XS Rating Curve= 0 ,0
Exp/Cntr=0.3,0.1

Type RM Length L Ch R = 1 ,65558   ,321,321,321
BEGIN DESCRIPTION:
WOLF CREEK 105.0
END DESCRIPTION:
XS GIS Cut Line= 4
      2694353.67     10008287.05      2695026.43     10008256.67
      2696024.69     10007935.49      2696519.51     10007340.84
#Sta/Elev= 30
    3666 2017.58  3816.9 2016.22  4221.4 2011.79  4573.4 1997.22  4635.7 1995.24
  4646.2 1993.37  4655.3 1989.04  4667.2 1987.03  4719.5 1987.11  4740.8 1985.01
  4751.3 1985.46  4756.8 1987.37  4804.3 1982.97  4858.3 1976.94  4929.9 1962.23
  4961.4 1958.29  5000.4 1951.99  5003.1 1951.49  5006.4 1951.99  5066.4 1958.29
    5115 1959.65    5266 1969.64  5350.1 1973.51  5654.5 1981.28    5747 1981.87
  5747.8 1981.87    5868 1985.91  5938.3 1993.97    5967 1995.74  6161.7 1997.94
#Mann= 8 ,-1 , 0
    3666     .16       0  3816.9      .1       0  4573.4     .05       0
  4804.3      .1       0  5000.4     .07       0  5006.4      .1       0
    5747     .16       0  5747.8      .1       0
Bank Sta=4961.4,5066.4
XS Rating Curve= 0 ,0
Exp/Cntr=0.3,0.1

Type RM Length L Ch R = 1 ,65237   ,579,579,579
BEGIN DESCRIPTION:
WOLF CREEK 104.0
END DESCRIPTION:
XS GIS Cut Line= 3
      2695469.11      10008495.4      2695937.88     10008265.35
      2696823.29     10008408.58
#Sta/Elev= 30
  4597.2 1991.99    4719 1989.29  4815.2 1977.06  4852.7 1975.02  4905.1 1960.03
 4915.45 1955.02  4919.5 1953.81  4927.6 1952.24  4955.7 1952.55  5000.4 1949.22
    5040 1953.74  5062.5 1954.91    5085 1954.55  5116.9 1957.92  5170.6 1959.12
    5328 1957.78  5342.8 1957.16  5363.1 1953.77  5373.2  1953.2  5403.6 1954.31
  5423.9 1957.01  5456.5 1959.26  5513.1 1967.51  5518.2 1967.18  5574.8 1974.37
  5641.6 1975.13  5758.2 1984.05  5826.7  1989.6  5942.1 1992.33  6016.3 1994.94
#Mann= 5 ,-1 , 0
  4597.2      .1       0  4919.5     .12       0  5062.5     .16       0
  5758.2     .16       0  5942.1      .1       0
#XS Ineff= 1 ,-1
 5171.14  5511.7  1959.3
Permanent Ineff=
       T
Bank Sta=4915.45,5062.5
XS Rating Curve= 0 ,0
Exp/Cntr=0.3,0.1

Type RM Length L Ch R = 1 ,64658   ,510,510,510
BEGIN DESCRIPTION:
WOLF CREEK 103.0
END DESCRIPTION:
XS GIS Cut Line= 4
      2695525.58     10008716.75      2696033.37     10008838.27
      2696567.22     10008590.87      2697113.83     10008642.93
#Sta/Elev= 30
  4329.7 1990.67  4373.8 1989.79  4422.1 1985.97  4595.4 1977.44  4692.5 1975.45
  4713.1 1973.64  4810.8 1958.76  4851.8 1957.06  4925.6 1950.21    4943 1945.97
  4971.4 1946.12  5000.5 1944.19  5022.8 1946.74  5077.9  1948.4  5091.5  1950.2
  5234.5 1958.44  5297.7 1961.79  5337.7 1966.13  5400.4 1972.88  5502.4 1979.48
    5520 1980.68    5525 1979.55  5627.9 1987.75  5634.5 1986.96  5662.5 1989.17
  5752.9 1991.97  5838.9 1998.26  5843.9 1997.47  5941.9 2006.08  5989.3 2007.07
#Mann= 7 ,-1 , 0
  4329.7      .1       0  4925.6     .12       0  5091.5      .1       0
  5234.5     .16       0  5337.7      .1       0  5502.4     .16       0
  5634.5      .1       0
Bank Sta=4925.6,5091.5
XS Rating Curve= 0 ,0
Exp/Cntr=0.3,0.1

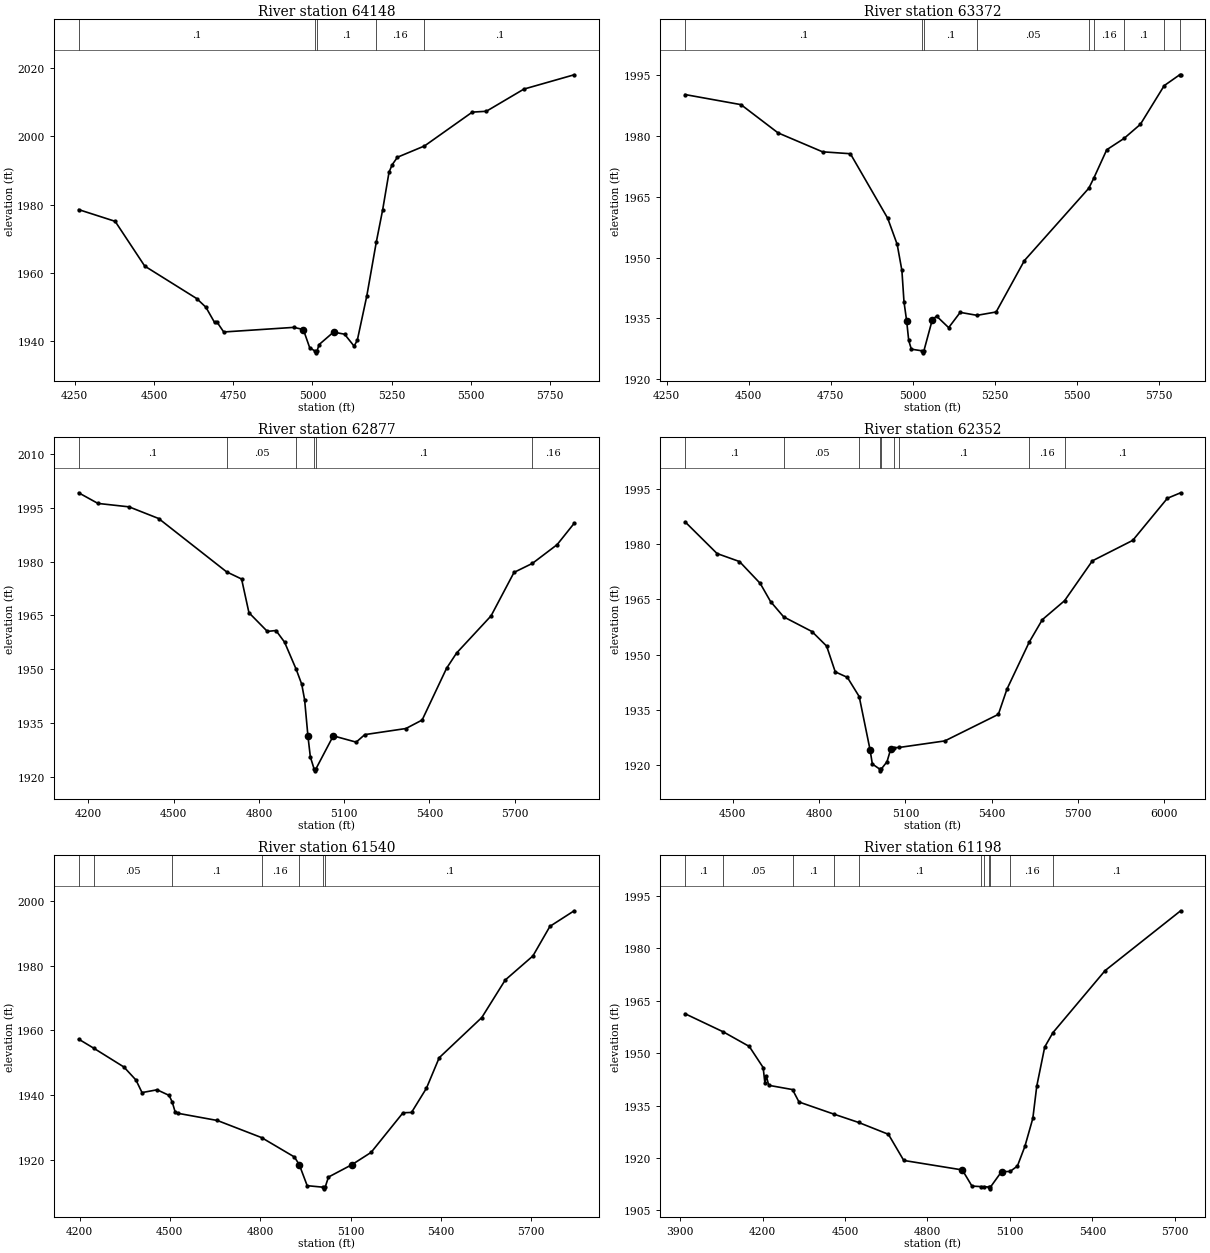
Type RM Length L Ch R = 1 ,64148   ,776,776,776
BEGIN DESCRIPTION:
WOLF CREEK 102.0
END DESCRIPTION:
XS GIS Cut Line= 4
      2695720.84     10008929.39      2696102.81     10009224.55
      2696719.13     10009194.17      2697174.16     10009280.84
#Sta/Elev= 30
  4262.6 1978.54  4377.8  1975.1  4471.1 1961.99    4635 1952.48    4664 1949.94
  4691.2  1945.5  4699.3 1945.55  4720.2 1942.69  4941.2 1944.04  4971.3 1943.41
  4991.3 1938.11  5008.3 1937.08  5011.1 1936.58  5014.3 1937.08  5021.3 1939.02
  5066.5 1942.65  5101.4 1942.04  5131.4 1938.55  5141.5 1940.23  5171.5 1953.24
  5201.5 1969.04  5221.6 1978.49  5241.6 1989.48  5251.6 1991.69  5268.2 1993.88
  5353.5 1997.18  5504.2 2007.09  5548.6 2007.34  5667.1 2013.84  5825.6 2018.03
#Mann= 5 ,-1 , 0
  4262.6      .1       0  5008.3     .07       0  5014.3      .1       0
  5201.5     .16       0  5353.5      .1       0
Bank Sta=4971.3,5066.5
XS Rating Curve= 0 ,0
Exp/Cntr=0.3,0.1

Type RM Length L Ch R = 1 ,63372   ,495,495,495
BEGIN DESCRIPTION:
WOLF CREEK 100.0
END DESCRIPTION:
XS GIS Cut Line= 4
       2695486.5     10008899.07      2695581.98     10009241.92
      2695898.82     10009641.22       2696528.2     10009784.46
#Sta/Elev= 30
  4305.9 1990.11  4476.3 1987.63  4589.3 1980.68    4725 1976.02  4809.9 1975.55
  4923.7 1959.66  4952.6 1953.24    4967 1946.82  4973.4 1939.09  4981.4 1934.46
  4987.8  1929.6  4995.8 1927.44  5028.1 1927.04  5030.8 1926.54  5034.1 1927.04
  5059.8 1934.71  5072.7 1935.59  5109.6 1932.74  5144.8  1936.5  5196.1 1935.77
  5254.4  1936.6  5340.5 1949.24  5536.9 1967.05  5552.3 1969.56  5591.7 1976.53
  5644.2  1979.3  5694.2 1982.78  5766.9 1992.31  5813.8 1994.96    5817 1994.98
#Mann= 9 ,-1 , 0
  4305.9      .1       0  5028.1     .07       0  5034.1      .1       0
  5196.1     .05       0  5536.9      .1       0  5552.3     .16       0
  5644.2      .1       0  5766.9     .16       0  5813.8      .1       0
Bank Sta=4981.4,5059.8
XS Rating Curve= 0 ,0
Exp/Cntr=0.3,0.1

Type RM Length L Ch R = 1 ,62877   ,525,525,525
BEGIN DESCRIPTION:
WOLF CREEK 99.0
END DESCRIPTION:
XS GIS Cut Line= 4
      2694822.47     10009667.29      2695243.44     10009892.96
      2695911.84     10009979.76      2696497.79     10009892.96
#Sta/Elev= 30
  4165.6 1999.22  4233.5 1996.25  4343.1 1995.29  4447.1 1992.04  4686.5 1977.14
  4739.1 1975.15    4765 1965.74  4829.8 1960.52  4860.1 1960.77  4890.3 1957.53
  4931.4 1949.91  4950.8 1945.77  4960.9 1941.45 4972.73 1931.21  4981.1 1925.49
  4994.4  1922.1  4997.2  1921.6  5000.4  1922.1  5061.8 1931.37  5142.4 1929.61
  5172.7 1931.71  5317.3 1933.41  5374.5 1935.78  5460.6 1950.24  5495.8 1954.49
  5617.1 1964.86    5698    1977  5762.6 1979.51  5849.6 1984.74  5909.6  1990.7
#Mann= 6 ,-1 , 0
  4165.6      .1       0  4686.5     .05       0  4931.4      .1       0
  4994.4     .07       0  5000.4      .1       0  5762.6     .16       0
Bank Sta=4972.73,5061.8
XS Rating Curve= 0 ,0
Exp/Cntr=0.3,0.1

Type RM Length L Ch R = 1 ,62352   ,812,812,812
BEGIN DESCRIPTION:
WOLF CREEK 98.0
END DESCRIPTION:
XS GIS Cut Line= 3
      2695134.89     10010813.12      2696167.92     10010118.65
      2696644.37     10010079.67
#Sta/Elev= 30
  4333.9 1986.03    4445 1977.44    4523 1975.27    4595 1969.35    4631 1964.43
  4676.5 1960.28    4775  1956.3    4826 1952.35  4855.9 1945.37    4898 1943.88
  4939.2 1938.67  4976.8  1924.3  4984.9 1920.39    5010 1919.04  5012.7 1918.54
    5016 1919.04  5035.9 1921.01  5049.1 1924.53  5061.7 1924.82  5077.5 1924.87
  5236.9 1926.65    5423 1933.85  5452.9 1940.69  5530.4 1953.45  5575.9 1959.52
  5653.2 1964.66  5749.8 1975.46  5890.2 1981.01  6010.6 1992.42  6056.7 1993.91
#Mann= 9 ,-1 , 0
  4333.9      .1       0  4676.5     .05       0  4939.2      .1       0
    5010     .07       0    5016      .1       0  5061.7     .16       0
  5077.5      .1       0  5530.4     .16       0  5653.2      .1       0
Bank Sta=4976.8,5049.1
XS Rating Curve= 0 ,0
Exp/Cntr=0.3,0.1

Type RM Length L Ch R = 1 ,61540   ,342,342,342
BEGIN DESCRIPTION:
WOLF CREEK 96.0
END DESCRIPTION:
XS GIS Cut Line= 3
      2695608.07     10010995.39      2696185.28     10011017.09
      2696940.46     10010261.91
#Sta/Elev= 30
    4197 1957.28  4247.3 1954.46  4347.5 1948.64  4387.5  1944.6  4407.5 1940.73
  4457.6 1941.59  4497.6 1939.85  4507.9 1937.77  4517.6 1934.72  4527.6  1934.3
  4657.7 1932.09  4804.4  1926.8  4913.6 1920.79  4929.7 1918.42    4956 1911.91
  5009.6 1911.43  5012.3 1910.93  5015.6 1911.43  5026.7 1914.58  5104.5 1918.41
  5168.2 1922.21  5274.2 1934.48  5302.5 1934.58    5352 1942.08  5394.4 1951.52
  5535.9 1963.97  5613.6 1975.57  5705.6 1983.03  5762.1 1992.19  5842.6 1997.01
#Mann= 7 ,-1 , 0
    4197      .1       0  4247.3     .05       0  4507.9      .1       0
  4804.4     .16       0  4929.7      .1       0  5009.6     .07       0
  5015.6      .1       0
Bank Sta=4929.7,5104.5
XS Rating Curve= 0 ,0
Exp/Cntr=0.3,0.1

Type RM Length L Ch R = 1 ,61198   ,261,261,261
BEGIN DESCRIPTION:
WOLF CREEK 95.0
END DESCRIPTION:
XS GIS Cut Line= 4
      2695608.06     10011112.58      2696393.61     10011238.44
      2697027.29     10010739.31      2697101.08     10010552.69
#Sta/Elev= 30
  3918.3  1961.3  4057.9 1956.08  4151.8 1951.93  4202.3 1945.88  4208.7 1941.39
  4213.7 1943.52  4222.5 1940.79  4309.1 1939.57  4332.7 1936.01  4460.8  1932.5
  4549.8 1930.14    4658 1926.75  4713.8 1919.26  4926.8 1916.54    4962 1911.91
  4994.5 1911.76  5004.1 1911.76  5023.2 1911.62  5025.9 1911.12  5029.2 1911.62
  5069.5 1916.03    5101 1916.11  5127.3 1917.65  5154.5 1923.28  5183.4 1931.31
  5197.8 1940.58  5226.7 1951.77  5256.4 1955.87  5446.3 1973.66  5721.2 1990.81
#Mann= 11 ,-1 , 0
  3918.3      .1       0  4057.9     .05       0  4309.1      .1       0
  4460.8     .16       0  4549.8      .1       0  4994.5     .16       0
  5004.1      .1       0  5023.2     .07       0  5029.2      .1       0
    5101     .16       0  5256.4      .1       0
Bank Sta=4926.8,5069.5
XS Rating Curve= 0 ,0
Exp/Cntr=0.3,0.1

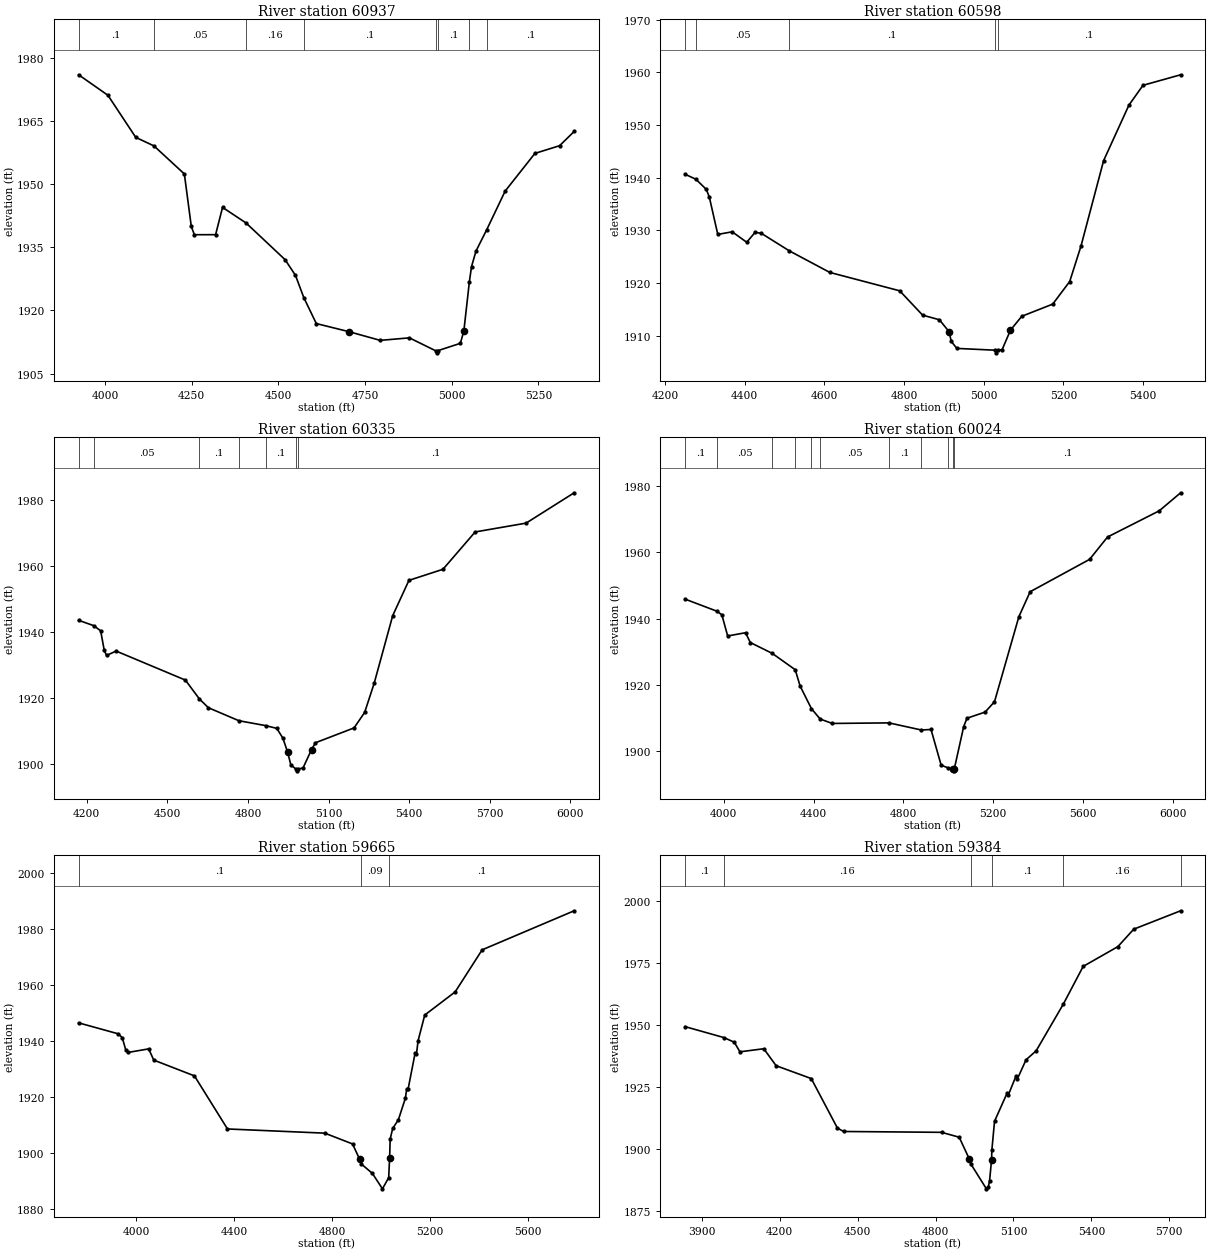
Type RM Length L Ch R = 1 ,60937   ,339,339,339
BEGIN DESCRIPTION:
Mapping XS f7892317
END DESCRIPTION:
XS GIS Cut Line= 3
      2695714.04     10011436.63      2696449.74     10011397.57
      2697093.83     10011143.84
#Sta/Elev= 30
  3924.3 1975.95  4008.8 1971.08    4089 1961.09  4141.5 1959.06  4229.2  1952.4
  4249.2 1939.93    4258 1937.97  4319.3 1937.98  4339.3 1944.46  4407.2 1940.75
  4519.6 1932.05  4549.6 1928.32  4573.7 1923.02  4609.7 1916.87  4702.7 1914.97
  4794.1 1912.88  4878.1 1913.48  4953.6 1910.42  4956.4 1909.92  4959.6 1910.42
  5025.1 1912.18  5035.2 1915.13  5051.2 1926.86  5057.3 1930.41  5070.3 1934.11
  5100.6 1939.07  5154.2 1948.32  5240.1 1957.28  5311.3 1959.11  5353.3 1962.49
#Mann= 8 ,-1 , 0
  3924.3      .1       0  4141.5     .05       0  4407.2     .16       0
  4573.7      .1       0  4953.6     .07       0  4959.6      .1       0
  5051.2     .16       0  5100.6      .1       0
Bank Sta=4702.7,5035.2
XS Rating Curve= 0 ,0
Exp/Cntr=0.3,0.1

Type RM Length L Ch R = 1 ,60598   ,263,263,263
BEGIN DESCRIPTION:
Mapping XS 749ab3b3
END DESCRIPTION:
XS GIS Cut Line= 3
      2696359.44     10012178.41      2696716.23      10011626.3
      2697112.06     10011194.01
#Sta/Elev= 30
  4250.5 1940.66  4277.6 1939.72  4303.7  1937.8  4311.4 1936.31  4332.5 1929.26
  4368.8 1929.75  4405.1 1927.77  4426.2 1929.65  4441.4 1929.48    4512 1926.14
  4613.6 1922.05  4789.1 1918.56  4846.5 1913.95  4888.7 1913.07    4913  1910.8
  4918.4 1908.96  4932.5 1907.64  5028.8  1907.3  5031.6  1906.8  5034.8  1907.3
    5046  1907.4    5067  1911.1  5095.3 1913.73    5173 1916.04  5215.6 1920.32
  5243.9 1927.04  5300.7 1943.25  5364.2 1953.77  5399.5 1957.53    5494 1959.53
#Mann= 5 ,-1 , 0
  4250.5      .1       0  4277.6     .05       0    4512      .1       0
  5028.8     .07       0  5034.8      .1       0
Bank Sta=4913,5067
XS Rating Curve= 0 ,0
Exp/Cntr=0.3,0.1

Type RM Length L Ch R = 1 ,60335   ,670,670,670
BEGIN DESCRIPTION:
WOLF CREEK 93.0
END DESCRIPTION:
XS GIS Cut Line= 4
      2696371.92     10012271.42      2696897.09     10011893.83
      2697161.84     10011312.23      2697282.99     10010767.07
#Sta/Elev= 30
  4169.7 1943.47  4226.1 1941.84  4251.7 1940.28    4265 1934.41  4273.6 1932.82
  4309.2 1934.16    4567 1925.37  4619.3 1919.64  4652.9 1916.99  4766.3 1913.06
    4866 1911.58  4907.2 1910.75  4930.2 1907.74  4947.8 1903.46  4959.5  1899.7
  4978.8 1898.39  4981.6 1897.89  4984.8 1898.39  5004.9 1898.77  5036.4 1904.29
    5051 1906.39  5194.8 1910.89  5234.1 1915.56  5269.5 1924.36  5338.7  1944.9
    5399 1955.56  5525.7 1958.92  5645.5 1970.22    5835 1972.89    6014 1982.08
#Mann= 7 ,-1 , 0
  4169.7      .1       0  4226.1     .05       0  4619.3      .1       0
  4766.3     .05       0    4866      .1       0  4978.8     .07       0
  4984.8      .1       0
Bank Sta=4947.8,5036.4
XS Rating Curve= 0 ,0
Exp/Cntr=0.3,0.1

Type RM Length L Ch R = 1 ,60024   ,359,359,359
BEGIN DESCRIPTION:
Mapping XS 655a9f67
END DESCRIPTION:
XS GIS Cut Line= 4
      2696303.51     10012319.54      2697230.18     10012004.86
      2697345.19     10011449.31      2697340.86     10010788.09
#Sta/Elev= 30
  3827.9 1945.84  3968.5 1942.23  3991.5 1941.15  4017.5 1934.75  4097.2 1935.73
  4118.3 1932.78  4215.4 1929.54  4318.4  1924.6  4340.1  1919.7  4390.6 1912.88
  4429.5 1909.76  4483.1 1908.43  4735.9  1908.6  4880.2 1906.46  4923.3 1906.61
  4968.4 1895.87  4999.8 1895.05  5020.7 1894.67  5023.4 1894.17  5026.7 1894.67
  5068.7 1907.46  5083.4 1910.01    5164 1911.84    5206 1914.96  5314.6 1940.55
  5364.8 1948.06  5629.5  1957.8  5709.5 1964.53  5939.5  1972.4  6035.1 1977.84
#Mann= 11 ,-1 , 0
  3827.9      .1       0  3968.5     .05       0  4215.4      .1       0
  4318.4     .05       0  4390.6      .1       0  4429.5     .05       0
  4735.9      .1       0  4880.2     .05       0  4999.8      .1       0
  5020.7     .07       0  5026.7      .1       0
Bank Sta=5020.7,5026.7
XS Rating Curve= 0 ,0
Exp/Cntr=0.3,0.1

Type RM Length L Ch R = 1 ,59665   ,281,281,281
BEGIN DESCRIPTION:
WOLF CREEK 92.0
END DESCRIPTION:
XS GIS Cut Line= 3
      2696312.87      10012356.5      2697675.73     10011978.89
      2698283.37     10012017.96
#Sta/Elev= 30
  3764.4 1946.64  3925.9 1942.73  3942.4 1941.38    3957 1936.94  3967.4 1936.09
  4050.4 1937.35  4071.1 1933.34  4237.2  1927.7  4372.1 1908.74  4769.4 1907.24
  4882.7 1903.39  4911.7 1897.89  4916.9 1896.34  4963.5 1892.89  5004.8 1887.35
  5030.2 1891.35 5034.09 1898.47  5036.2 1905.07  5046.5 1908.92  5069.7    1912
  5098.4 1919.72    5104 1923.16  5109.2 1922.86  5138.3 1935.92  5143.4 1935.34
  5150.3 1940.26  5177.4 1949.43  5301.6  1957.7  5411.8 1972.73  5787.5 1986.68
#Mann= 3 ,-1 , 0
  3764.4      .1       0  4916.9     .09       0  5030.2      .1       0
Bank Sta=4911.7,5034.09
XS Rating Curve= 0 ,0
Exp/Cntr=0.3,0.1

Type RM Length L Ch R = 1 ,59384   ,526,526,526
BEGIN DESCRIPTION:
WOLF CREEK 91.0
END DESCRIPTION:
XS GIS Cut Line= 4
      2696373.61      10012495.4       2697111.5     10012187.23
      2697658.37     10012343.48      2698183.49     10012217.62
#Sta/Elev= 30
  3835.3 1949.35  3984.6 1944.94  4024.8 1943.04  4046.5 1939.18  4138.3 1940.42
  4185.9 1933.56  4321.2 1928.37  4421.9 1908.37  4445.7 1906.99  4823.3 1906.65
  4890.9 1904.67  4929.9 1895.87  4935.1 1893.97  4995.6 1883.82  5002.7  1884.4
  5007.9 1887.08 5015.62 1895.62  5016.6 1899.38    5027 1911.12  5075.5 1922.52
  5080.7  1921.9  5109.3  1929.3  5114.5 1928.13  5148.3 1935.95  5187.3 1939.59
  5291.8 1958.43  5368.3 1973.68    5502 1981.68    5563 1988.72  5743.7 1996.16
#Mann= 6 ,-1 , 0
  3835.3      .1       0  3984.6     .16       0  4935.1     .12       0
  5016.6      .1       0  5291.8     .16       0  5743.7      .1       0
Bank Sta=4929.9,5015.62
XS Rating Curve= 0 ,0
Exp/Cntr=0.3,0.1