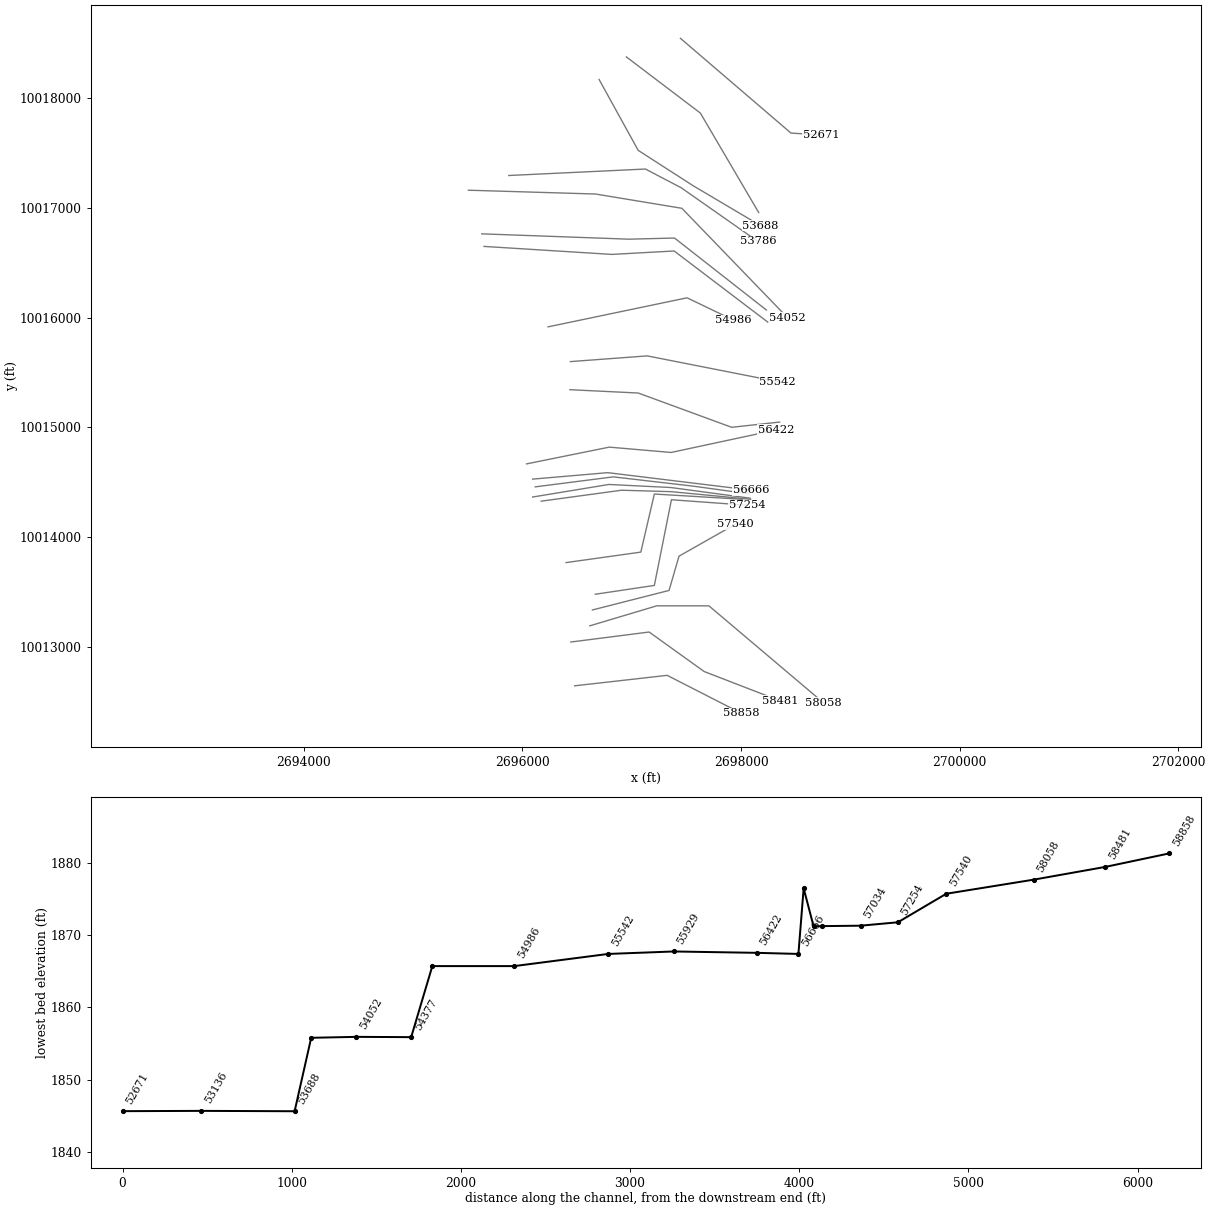
HEC-RAS study WOLF CREEK.prj: WOLF CREEK Base Level Engineering

--- WOLF CREEK.g01 (geometry) --- (continued)

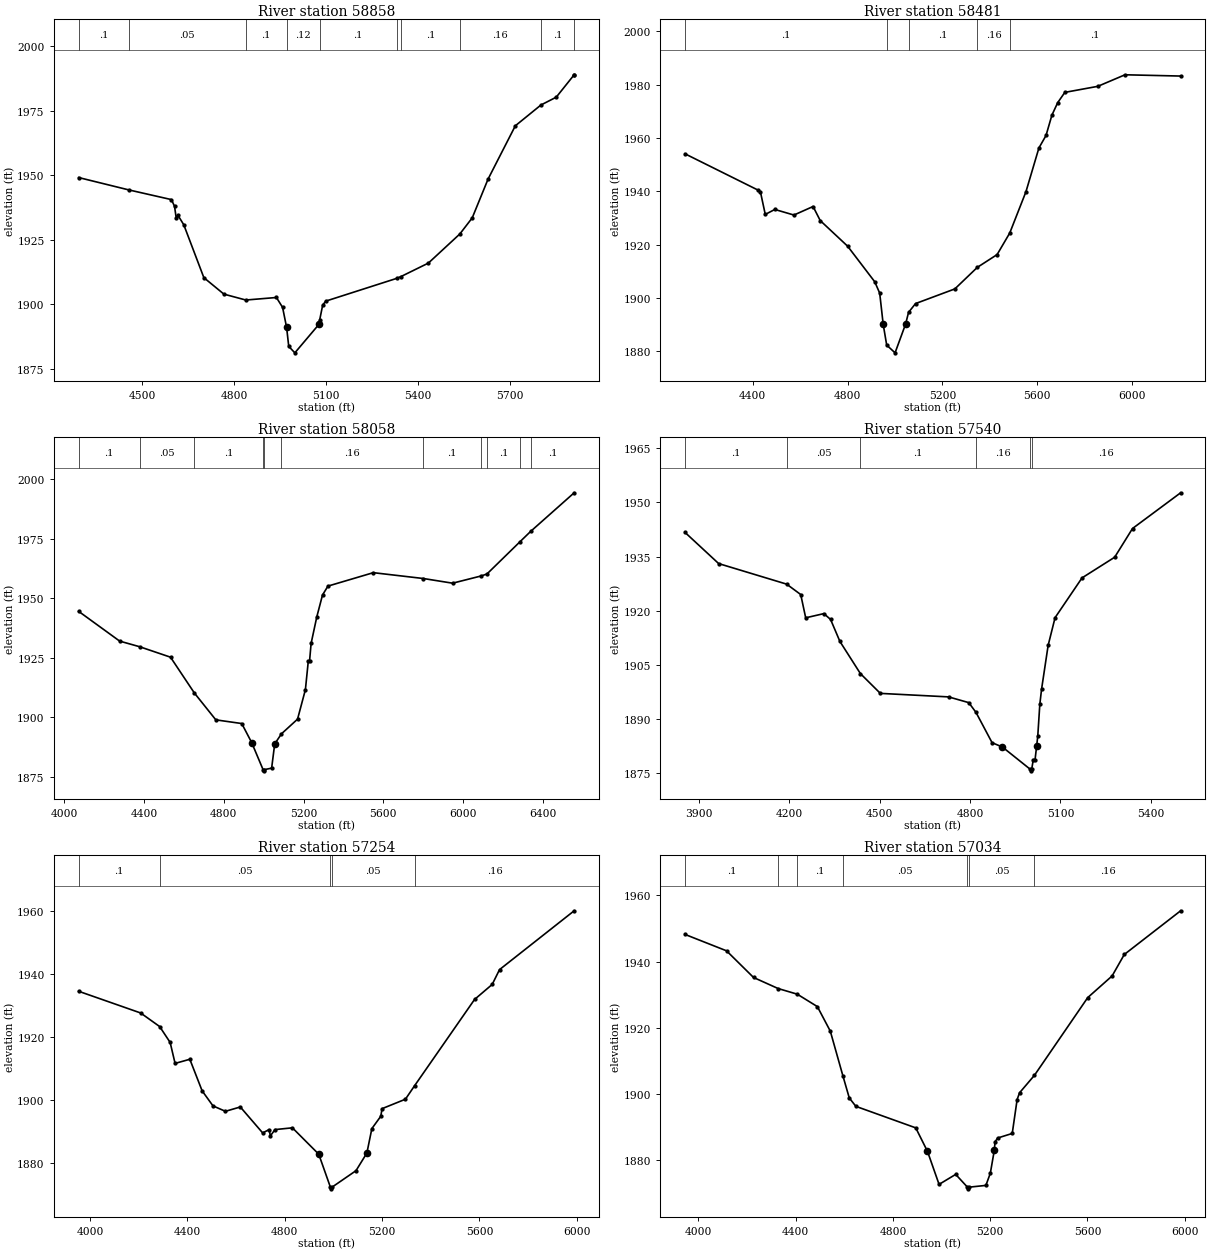
Type RM Length L Ch R = 1 ,58858   ,377,377,377
BEGIN DESCRIPTION:
WOLF CREEK 90.0
END DESCRIPTION:
XS GIS Cut Line= 3
      2696477.86     10012642.96      2697324.17     10012738.44
      2698004.55     10012391.75
#Sta/Elev= 30
    4293  1949.2  4456.5 1944.41  4595.5 1940.65  4605.6 1938.05  4611.3 1933.33
  4616.4 1934.63  4635.8 1930.88  4701.2  1910.4  4766.6 1904.01    4838 1901.73
  4937.7 1902.71  4957.8 1898.89  4970.9 1891.14  4977.9 1883.76  4997.8 1881.26
 5076.48 1892.32  5078.6 1893.94  5088.6 1899.79  5098.7 1901.31  5329.5 1910.11
  5343.4 1910.81    5433 1916.04  5535.7 1927.34    5576 1933.57  5627.6  1948.6
  5716.5 1969.26  5799.9 1977.31  5849.9 1980.35  5907.8 1988.96  5908.3 1989.03
#Mann= 10 ,-1 , 0
    4293      .1       0  4456.5     .05       0    4838      .1       0
  4970.9     .12       0  5078.6      .1       0  5329.5     .16       0
  5343.4      .1       0  5535.7     .16       0  5799.9      .1       0
  5907.8     .16       0
Bank Sta=4970.9,5076.48
XS Rating Curve= 0 ,0
Exp/Cntr=0.3,0.1

Type RM Length L Ch R = 1 ,58481   ,423,423,423
BEGIN DESCRIPTION:
WOLF CREEK 89.0
END DESCRIPTION:
XS GIS Cut Line= 4
       2696443.1     10013042.26      2697159.24     10013133.41
      2697662.71     10012773.17      2698361.49     10012504.07
#Sta/Elev= 30
  4115.1 1954.01  4422.9 1940.41    4433 1939.68  4453.2  1931.3  4493.5 1933.16
  4574.1 1931.07  4654.8 1934.27    4685 1928.99  4800.5 1919.39  4914.9 1906.04
  4935.8 1901.78  4950.5  1890.1  4965.3 1882.29  5000.6  1879.4  5045.1 1890.22
  5057.4 1894.57  5086.9 1897.87  5252.7 1903.37  5347.5 1911.45  5430.9 1916.24
  5484.2 1924.32  5552.6 1939.82  5607.2 1956.22  5637.2  1960.9  5661.9 1968.49
  5686.5 1973.22  5716.5 1977.06  5855.7 1979.33  5970.3 1983.66  6204.9 1983.18
#Mann= 5 ,-1 , 0
  4115.1      .1       0  4965.3     .09       0  5057.4      .1       0
  5347.5     .16       0  5484.2      .1       0
Bank Sta=4950.5,5045.1
XS Rating Curve= 0 ,0
Exp/Cntr=0.3,0.1

Type RM Length L Ch R = 1 ,58058   ,518,518,518
BEGIN DESCRIPTION:
WOLF CREEK 88.0
END DESCRIPTION:
XS GIS Cut Line= 4
      2696616.66     10013189.82      2697228.68     10013372.12
      2697706.11     10013372.12       2698753.8     10012488.95
#Sta/Elev= 30
  4071.4  1944.5  4277.3 1932.02  4377.4 1929.67  4532.4 1925.28  4652.1 1910.27
  4759.8 1899.01  4889.8 1897.47  4939.8 1889.46  4996.8 1878.14  4999.5 1877.64
  5002.8 1878.14  5039.8 1878.77 5055.11 1888.91    5089 1893.15  5169.8 1899.31
  5209.2 1911.68  5223.5 1923.48    5230 1923.63  5237.8 1931.04  5266.4  1942.2
    5295 1951.34  5322.3 1955.08  5549.9 1960.71  5801.1 1958.26  5947.7  1956.3
  6090.8 1959.33    6120 1960.15    6287 1973.77  6339.5 1978.02  6557.7  1994.2
#Mann= 11 ,-1 , 0
  4071.4      .1       0  4377.4     .05       0  4652.1      .1       0
  4996.8     .07       0  5002.8      .1       0    5089     .16       0
  5801.1      .1       0  6090.8     .16       0    6120      .1       0
    6287     .16       0  6339.5      .1       0
Bank Sta=4939.8,5055.11
XS Rating Curve= 0 ,0
Exp/Cntr=0.3,0.1

Type RM Length L Ch R = 1 ,57540   ,286,286,286
BEGIN DESCRIPTION:
Mapping XS 54d47fcb
END DESCRIPTION:
XS GIS Cut Line= 4
      2696640.53     10013334.57      2697341.45     10013512.51
       2697432.6     10013825.01      2697951.29       10014118.
#Sta/Elev= 30
  3854.6 1941.67    3966 1933.06  4191.6 1927.37  4238.3 1924.49  4254.8 1918.05
  4315.1 1919.21  4337.4 1917.59  4368.3 1911.51  4436.3 1902.61  4502.5 1897.13
  4728.9 1896.16  4795.9 1894.57  4819.9 1891.87  4873.3 1883.48  4907.6 1882.28
  4998.9 1876.19  5001.6 1875.69  5004.9 1876.19  5010.1 1878.82  5015.8  1878.7
 5021.14 1882.53  5024.9 1885.29  5031.7 1894.11  5037.5 1898.28  5059.3 1910.41
  5082.3 1918.09  5171.8  1929.1  5280.1 1934.82  5339.3 1942.77    5499 1952.66
#Mann= 6 ,-1 , 0
  3854.6      .1       0  4191.6     .05       0  4436.3      .1       0
  4819.9     .16       0  4998.9     .07       0  5004.9     .16       0
Bank Sta=4907.6,5021.14
XS Rating Curve= 0 ,0
Exp/Cntr=0.3,0.1

Type RM Length L Ch R = 1 ,57254   ,220,220,220
BEGIN DESCRIPTION:
WOLF CREEK 87.0
END DESCRIPTION:
XS GIS Cut Line= 4
       2696666.5     10013477.78       2697206.9     10013558.08
      2697363.15     10014339.33       2698054.4      10014289.5
#Sta/Elev= 30
  3953.3 1934.47    4208 1927.58  4286.2 1923.27  4329.3 1918.23  4349.6 1911.57
  4410.2 1912.88  4460.8 1902.85  4505.4 1898.08  4556.4 1896.36  4617.6 1897.74
  4709.4 1889.51    4736 1890.55  4741.1 1888.56  4760.3 1890.56  4831.7 1891.12
  4939.9 1882.75  4987.9 1872.25  4990.7 1871.75  4993.9 1872.25  5092.9 1877.51
  5137.7 1883.13  5158.1 1890.87  5194.9  1894.8    5200  1897.2    5296  1900.2
  5334.2 1904.54  5580.1 1931.87  5652.6 1936.64  5682.7 1941.34  5989.4 1960.02
#Mann= 5 ,-1 , 0
  3953.3      .1       0  4286.2     .05       0  4987.9     .04       0
  4993.9     .05       0  5334.2     .16       0
Bank Sta=4939.9,5137.7
XS Rating Curve= 0 ,0
Exp/Cntr=0.3,0.1

Type RM Length L Ch R = 1 ,57034   ,228,228,228
BEGIN DESCRIPTION:
WOLF CREEK 86.0
END DESCRIPTION:
XS GIS Cut Line= 4
      2696399.62     10013766.42       2697083.2      10013861.9
       2697206.9     10014391.42       2698009.9     10014343.67
#Sta/Elev= 30
  3945.2 1948.21  4115.7 1943.26  4226.7  1935.2  4328.1 1931.85  4406.5 1930.15
  4489.3 1926.39  4542.5 1918.97  4594.4 1905.43  4620.5 1898.78  4647.6 1896.23
    4894 1889.72  4942.3  1882.6  4989.9 1872.63  5058.3 1875.65  5106.7 1871.78
  5109.4 1871.28  5112.7 1871.78  5182.5 1872.32  5200.8 1876.01 5217.33 1883.03
  5220.1 1885.49  5230.8 1886.65  5290.9 1888.03    5311 1898.29    5321 1900.33
  5382.3 1905.62  5601.5 1929.12  5701.7 1935.66  5751.8 1942.15  5983.6 1955.37
#Mann= 7 ,-1 , 0
  3945.2      .1       0  4328.1     .05       0  4406.5      .1       0
  4594.4     .05       0  5106.7     .04       0  5112.7     .05       0
  5382.3     .16       0
Bank Sta=4942.3,5217.33
XS Rating Curve= 0 ,0
Exp/Cntr=0.3,0.1

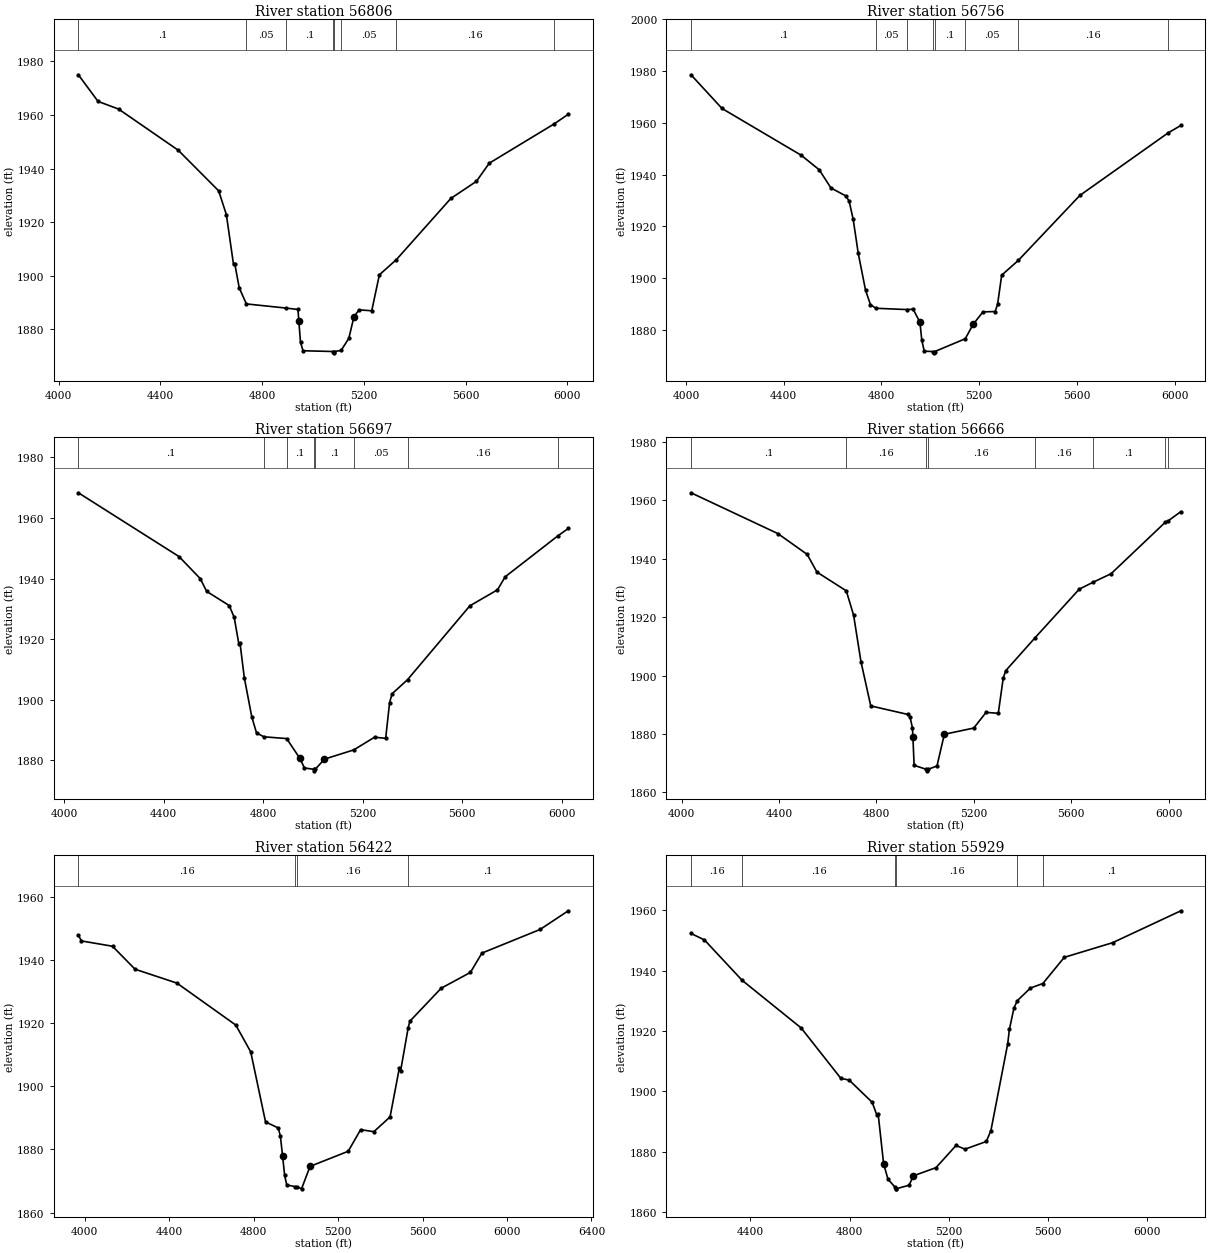
Type RM Length L Ch R = 1 ,56806   ,50,50,50
BEGIN DESCRIPTION:
Mapping XS 95b5ba40
END DESCRIPTION:
XS GIS Cut Line= 4
      2696171.71     10014326.31      2696907.42     10014426.14
      2697358.81     10014413.12      2698087.98     10014343.67
#Sta/Elev= 30
  4077.5 1975.02    4155 1965.08  4235.7 1962.22  4470.1 1946.87  4629.3 1931.69
  4659.5 1922.82  4687.6 1904.24  4692.7  1904.4    4710 1895.53  4738.1 1889.48
  4893.6 1887.94    4941 1887.41  4944.6 1882.98  4951.1 1875.09  4961.1    1872
  5078.5 1871.72  5081.2 1871.22  5084.5 1871.72  5110.6 1872.11  5141.1 1876.63
  5161.1 1884.65  5181.1 1887.25  5231.2 1886.93  5261.2 1900.34  5328.4 1906.05
  5542.4 1928.87  5642.9 1935.25  5693.1    1942  5948.4 1956.68    6004 1960.28
#Mann= 8 ,-1 , 0
  4077.5      .1       0  4738.1     .05       0  4893.6      .1       0
  5078.5     .07       0  5084.5      .1       0  5110.6     .05       0
  5328.4     .16       0  5948.4      .1       0
Bank Sta=4944.6,5161.1
XS Rating Curve= 0 ,0
Exp/Cntr=0.3,0.1

Type RM Length L Ch R = 1 ,56756   ,59,59,59
BEGIN DESCRIPTION:
Mapping XS 5e506eb0
END DESCRIPTION:
XS GIS Cut Line= 4
      2696093.04     10014364.06      2696790.97     10014478.64
      2697356.94     10014450.87      2698082.64     10014353.64
#Sta/Elev= 30
    4020 1978.54  4147.1 1965.52  4471.4 1947.46    4545 1941.86    4593 1934.84
  4653.8 1931.77  4667.5 1929.74  4684.2  1922.7  4704.5 1909.79  4734.8 1895.31
  4754.8  1889.8  4776.9 1888.38  4903.6 1887.88  4929.7 1888.02 4957.39 1882.98
  4965.1 1876.04  4975.1  1871.8  5012.1 1871.67  5014.9 1871.17  5018.1 1871.67
    5143 1876.61  5175.3 1882.16  5215.4 1886.98  5265.4 1887.12  5275.4 1889.92
  5292.2 1901.16    5360 1906.84  5612.3 1931.95  5975.1 1956.19  6026.1 1958.98
#Mann= 8 ,-1 , 0
    4020      .1       0  4776.9     .05       0  4903.6      .1       0
  5012.1     .07       0  5018.1      .1       0    5143     .05       0
    5360     .16       0  5975.1      .1       0
Bank Sta=4957.39,5175.3
XS Rating Curve= 0 ,0
Exp/Cntr=0.3,0.1

Type RM Length L Ch R = 1 ,56697   ,31,31,31
BEGIN DESCRIPTION:
Mapping XS 774d1eab
END DESCRIPTION:
XS GIS Cut Line= 4
      2696117.18     10014456.73      2696831.12     10014547.87
      2697562.46     10014463.24      2698070.28     10014393.79
#Sta/Elev= 30
  4057.7 1968.33  4462.2 1947.25  4547.6 1939.96  4573.1 1935.76  4663.9 1931.06
    4684 1927.13  4702.2  1918.5  4707.3 1918.64  4724.4 1907.27  4754.6 1894.24
  4773.6 1888.97  4803.1 1887.69  4894.6  1887.1  4947.4 1880.61    4966  1877.4
  5003.3 1876.94    5006 1876.44  5009.3 1876.94  5046.6 1880.31  5164.3 1883.36
  5247.9 1887.56  5292.5 1887.18  5308.3 1899.02  5318.4 1901.92  5380.3 1906.56
  5630.7 1930.97  5741.8 1936.26  5772.7 1940.57    5986 1954.19  6026.2 1956.53
#Mann= 8 ,-1 , 0
  4057.7      .1       0  4803.1     .05       0  4894.6      .1       0
  5003.3     .07       0  5009.3      .1       0  5164.3     .05       0
  5380.3     .16       0    5986      .1       0
Bank Sta=4947.4,5046.6
XS Rating Curve= 0 ,0
Exp/Cntr=0.3,0.1

Type RM Length L Ch R = 1 ,56666   ,244,244,244
BEGIN DESCRIPTION:
WOLF CREEK 85.0
END DESCRIPTION:
XS GIS Cut Line= 3
      2696093.04     10014527.25      2696780.56     10014586.28
      2698093.03     10014426.56
#Sta/Elev= 30
  4038.8 1962.59  4395.5 1948.62    4516 1941.49  4556.1 1935.43  4676.6 1929.02
  4706.7 1920.66  4736.8 1904.79  4777.1 1889.61  4928.2 1886.72  4938.3 1885.86
  4948.4 1882.07 4950.28 1878.92  4955.2 1869.27  5005.8 1867.88  5008.6 1867.38
  5011.8 1867.88  5049.1 1869.04  5079.3  1879.9  5200.2 1882.03  5250.6 1887.39
  5300.9 1887.08  5321.1 1899.08  5331.2 1901.65  5450.3  1912.8  5633.4 1929.59
  5690.8 1931.98  5764.3 1934.88  5986.4 1952.47  5998.3 1952.96    6051 1956.15
#Mann= 8 ,-1 , 0
  4038.8      .1       0  4676.6     .16       0  5005.8     .07       0
  5011.8     .16       0  5450.3     .16       0  5690.8      .1       0
  5986.4     .16       0  5998.3      .1       0
Bank Sta=4950.28,5079.3
XS Rating Curve= 0 ,0
Exp/Cntr=0.3,0.1

Type RM Length L Ch R = 1 ,56422   ,493,493,493
BEGIN DESCRIPTION:
Mapping XS 47505da1
END DESCRIPTION:
XS GIS Cut Line= 4
      2696037.49     10014666.14      2696794.44     10014818.92
      2697360.42     10014770.31      2698318.79     10014975.18
#Sta/Elev= 30
    3970 1947.79  3984.7 1945.99  4131.9  1944.3  4238.6 1937.03  4436.6 1932.65
  4715.7 1919.36  4786.4 1910.87  4856.5 1888.71  4916.9  1886.8  4926.9 1884.16
    4937 1878.08    4947 1871.79    4957 1868.76  4997.2 1868.22  5007.2 1868.17
    5027 1867.53  5067.4 1874.64  5248.1 1879.42  5306.8 1886.25  5369.6 1885.62
  5446.3 1890.29  5490.7 1905.93  5495.8 1904.69  5532.2 1918.55  5540.1 1920.58
  5688.6 1931.03  5826.8 1936.02  5881.4 1942.14    6157 1949.62  6290.3 1955.53
#Mann= 4 ,-1 , 0
    3970     .16       0  4997.2     .07       0  5007.2     .16       0
  5532.2      .1       0
Bank Sta=4937,5067.4
XS Rating Curve= 0 ,0
Exp/Cntr=0.3,0.1

Type RM Length L Ch R = 1 ,55929   ,387,387,387
BEGIN DESCRIPTION:
WOLF CREEK 83.0
END DESCRIPTION:
XS GIS Cut Line= 4
      2696434.45     10015342.61      2697059.41     10015312.23
      2697914.45     10014999.73       2698352.8     10015047.47
#Sta/Elev= 30
  4160.2 1952.37  4214.3 1950.24  4366.4 1936.85  4604.7 1921.05  4764.9 1904.35
  4798.5 1903.77  4891.4  1896.4    4910 1892.22  4915.3 1892.66  4937.5 1876.02
  4955.2 1870.89  4984.2 1868.22  4986.9 1867.72  4987.4 1867.72  5040.4 1868.92
  5057.3 1872.02  5148.9 1874.75  5229.9 1882.11  5265.8 1880.86    5352 1883.42
  5370.5 1887.05  5438.3 1915.82    5445 1920.56  5463.5 1927.67  5476.9 1930.09
  5530.2 1934.29  5580.1 1935.78  5666.6 1944.46  5861.2  1949.3  6137.2 1959.89
#Mann= 6 ,-1 , 0
  4160.2     .16       0  4366.4     .16       0  4984.2     .07       0
  4987.4     .16       0  5476.9     .16       0  5580.1      .1       0
Bank Sta=4937.5,5057.3
XS Rating Curve= 0 ,0
Exp/Cntr=0.3,0.1

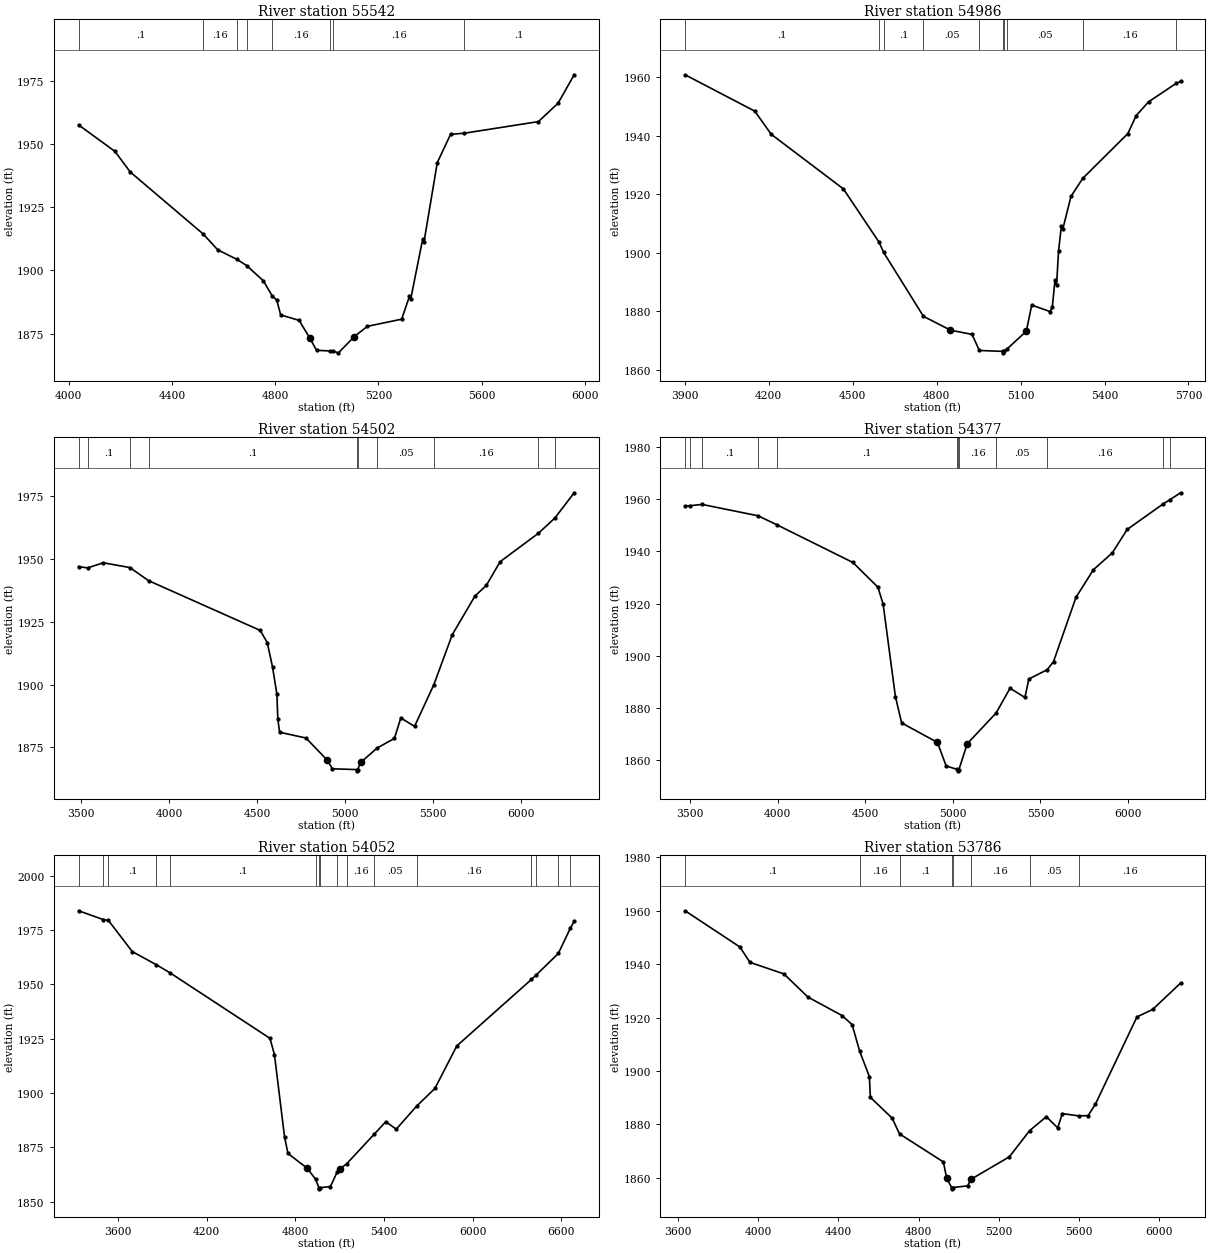
Type RM Length L Ch R = 1 ,55542   ,556,556,556
BEGIN DESCRIPTION:
WOLF CREEK 82.0
END DESCRIPTION:
XS GIS Cut Line= 3
      2696438.77     10015598.69      2697141.88     10015650.77
      2698334.47     10015416.59
#Sta/Elev= 30
  4038.2 1957.48  4178.7 1947.05  4238.4 1938.87  4521.2 1914.34  4577.3  1908.1
  4650.9 1904.37  4689.2 1901.91  4754.4 1895.83    4789 1889.77  4805.8 1888.29
  4821.3 1882.36  4892.6 1880.22  4933.4 1873.35  4960.1 1868.39  5011.6 1868.12
  5025.1 1867.98  5045.2 1867.38  5106.6 1873.82  5157.6 1877.87  5290.1 1880.69
  5320.1 1889.67  5325.2 1888.66  5371.5 1912.33  5376.6 1911.19  5428.1 1942.58
  5479.5 1953.76  5532.7 1954.21    5820 1958.81    5896 1966.05  5958.6 1977.32
#Mann= 8 ,-1 , 0
  4038.2      .1       0  4521.2     .16       0  4650.9      .1       0
  4689.2     .05       0    4789     .16       0  5011.6     .05       0
  5025.1     .16       0  5532.7      .1       0
Bank Sta=4933.4,5106.6
XS Rating Curve= 0 ,0
Exp/Cntr=0.3,0.1

Type RM Length L Ch R = 1 ,54986   ,484,484,484
BEGIN DESCRIPTION:
WOLF CREEK 81.0
END DESCRIPTION:
XS GIS Cut Line= 3
      2696234.73     10015915.52      2697506.46     10016180.28
      2697931.77     10015976.31
#Sta/Elev= 30
  3901.3 1960.76  4150.3 1948.33  4208.9 1940.43  4466.9 1921.75  4594.8 1903.47
  4610.7 1900.03    4753 1878.18  4849.6 1873.45  4926.6    1872  4952.8 1866.51
  5035.9  1866.2  5038.7  1865.7  5041.9  1866.2  5052.6 1867.11  5120.6 1873.09
  5139.8 1882.01    5206  1879.8  5213.6 1881.44  5223.1 1890.67  5228.6 1888.77
  5235.8 1900.56  5245.7 1908.93  5251.3 1908.14  5280.2  1919.2  5322.2 1925.35
  5483.4 1940.66  5513.1 1946.79  5557.4 1951.51  5656.4 1957.84    5672 1958.49
#Mann= 10 ,-1 , 0
  3901.3      .1       0  4594.8     .05       0  4610.7      .1       0
    4753     .05       0  4952.8     .16       0  5035.9     .07       0
  5041.9     .16       0  5052.6     .05       0  5322.2     .16       0
  5656.4      .1       0
Bank Sta=4849.6,5120.6
XS Rating Curve= 0 ,0
Exp/Cntr=0.3,0.1

Type RM Length L Ch R = 1 ,54502   ,125,125,125
BEGIN DESCRIPTION:
Mapping XS 1e9a7f36
END DESCRIPTION:
XS GIS Cut Line= 4
       2695648.6     10016648.78      2696818.75     10016575.87
      2697388.19     10016607.12      2698244.06     10015959.15
#Sta/Elev= 30
  3485.7 1946.89  3536.7 1946.38  3625.8 1948.42    3777 1946.52  3882.9 1941.32
  4517.6 1921.53  4557.6 1916.72  4587.7 1906.94  4612.4 1896.18  4617.8 1886.19
  4627.8 1881.06    4778 1878.74  4898.2 1869.96  4928.2 1866.51  5065.5  1866.2
  5068.2  1865.7  5071.5  1866.2  5088.5 1869.03  5182.1 1874.76  5280.3 1878.59
  5316.6 1886.73  5394.8 1883.39  5504.4 1899.95    5609 1919.81    5738 1935.19
  5802.5 1939.41    5881 1948.84  6099.1 1960.18  6192.1  1966.2  6301.9 1976.25
#Mann= 10 ,-1 , 0
  3485.7     .16       0  3536.7      .1       0    3777     .16       0
  3882.9      .1       0  5065.5     .07       0  5071.5      .1       0
  5182.1     .05       0  5504.4     .16       0  6099.1      .1       0
  6192.1     .16       0
Bank Sta=4898.2,5088.5
XS Rating Curve= 0 ,0
Exp/Cntr=0.3,0.1

Type RM Length L Ch R = 1 ,54377   ,325,325,325
BEGIN DESCRIPTION:
WOLF CREEK 80.0
END DESCRIPTION:
XS GIS Cut Line= 4
      2695627.77     10016763.37        2696975.     10016714.75
      2697391.67     10016725.17      2698231.96     10016068.91
#Sta/Elev= 30
    3470 1957.42  3500.2 1957.51  3566.8 1957.99  3886.2 1953.64  3994.6 1950.18
  4428.4 1935.75  4571.4 1926.29  4601.4 1919.78  4671.5 1884.35  4707.1 1874.26
  4911.6 1866.77  4961.6 1857.76  5025.4 1856.42  5028.6 1856.39  5031.4 1855.89
  5034.6 1856.39  5081.7 1866.27    5247 1878.06  5326.3 1887.53  5411.3 1884.01
  5433.9 1891.09  5538.5 1894.63    5575 1897.78  5703.5 1922.43    5803 1932.98
  5910.6 1939.42  5995.6 1948.38  6199.5  1958.1    6241 1959.86  6301.1 1962.45
#Mann= 12 ,-1 , 0
    3470      .1       0  3500.2     .16       0  3566.8      .1       0
  3886.2     .16       0  3994.6      .1       0  5025.4     .16       0
  5028.6     .07       0  5034.6     .16       0    5247     .05       0
  5538.5     .16       0  6199.5      .1       0    6241     .16       0
Bank Sta=4911.6,5081.7
XS Rating Curve= 0 ,0
Exp/Cntr=0.3,0.1

Type RM Length L Ch R = 1 ,54052   ,266,266,266
BEGIN DESCRIPTION:
WOLF CREEK 79.0
END DESCRIPTION:
XS GIS Cut Line= 4
      2695505.56     10017161.19      2696668.79     10017126.46
      2697458.72     10016996.26      2698426.27     10015998.33
#Sta/Elev= 30
    3333  1983.9  3499.4 1979.86  3534.3 1979.49  3696.1 1965.12  3859.4 1959.06
  3949.7 1955.43  4628.2  1925.2  4658.6 1917.62  4726.6 1879.95  4749.8 1872.22
  4881.5 1865.33  4936.9 1860.33  4959.6 1856.43  4962.4 1855.93  4965.6 1856.43
  5037.4    1857  5083.1 1863.67  5104.5  1865.2  5148.5 1867.54  5333.1 1881.03
  5412.2 1886.84  5482.7 1883.37  5620.3 1893.96  5744.5 1902.12    5893 1921.72
    6398 1952.29  6431.7 1954.45  6580.1 1964.25  6660.9 1975.82  6687.3 1979.09
#Mann= 16 ,-1 , 0
    3333      .1       0  3499.4     .16       0  3534.3      .1       0
  3859.4     .16       0  3949.7      .1       0  4936.9     .16       0
  4959.6     .07       0  4965.6     .16       0  5083.1      .1       0
  5148.5     .16       0  5333.1     .05       0  5620.3     .16       0
    6398      .1       0  6431.7     .16       0  6580.1      .1       0
  6660.9     .16       0
Bank Sta=4881.5,5104.5
XS Rating Curve= 0 ,0
Exp/Cntr=0.3,0.1

Type RM Length L Ch R = 1 ,53786   ,98,98,98
BEGIN DESCRIPTION:
Mapping XS af7496ff
END DESCRIPTION:
XS GIS Cut Line= 4
      2695875.27     10017295.27      2697125.25     10017354.29
      2697451.64     10017184.16      2698153.03     10016694.57
#Sta/Elev= 30
  3634.2    1960  3907.7 1946.44  3957.8 1940.68  4127.3 1936.35  4248.1 1927.64
  4418.3 1920.73  4468.3 1917.33  4506.1 1907.36  4554.5 1897.86  4559.5 1890.09
  4668.5 1882.27    4705 1876.39    4924 1865.89  4940.4 1859.87  4965.1  1856.3
  4967.9  1855.8  4971.1  1856.3  5045.2 1856.91  5061.5 1859.36  5253.6  1867.8
  5354.6 1877.59  5438.3 1882.84    5495 1878.65  5518.1 1883.99  5599.4 1883.15
  5646.8 1883.22  5682.6 1887.43    5891 1920.25  5969.3 1923.02    6109 1932.93
#Mann= 8 ,-1 , 0
  3634.2      .1       0  4506.1     .16       0    4705      .1       0
  4965.1     .07       0  4971.1      .1       0  5061.5     .16       0
  5354.6     .05       0  5599.4     .16       0
Bank Sta=4940.4,5061.5
XS Rating Curve= 0 ,0
Exp/Cntr=0.3,0.1

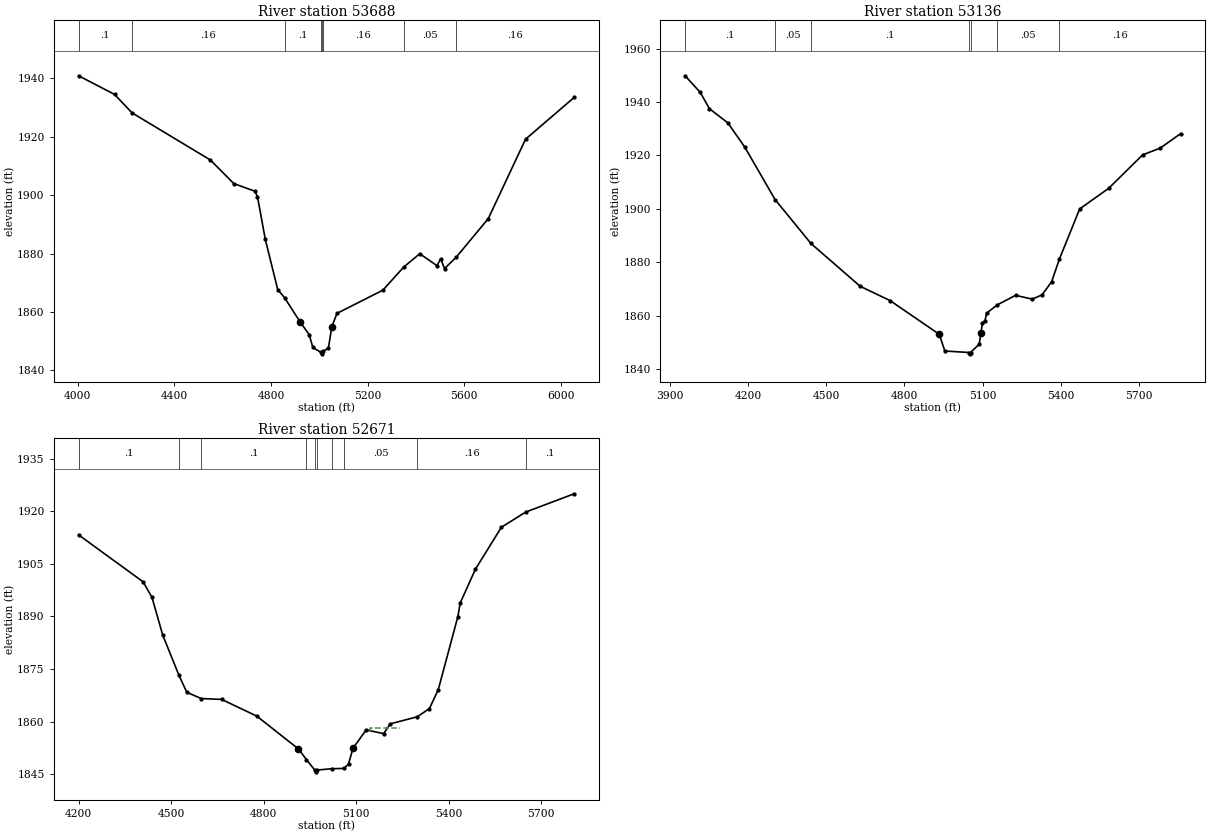
Type RM Length L Ch R = 1 ,53688   ,552,552,552
BEGIN DESCRIPTION:
WOLF CREEK 78.0
END DESCRIPTION:
XS GIS Cut Line= 4
      2696701.65     10018170.25      2697059.27     10017524.43
      2697562.75     10017201.52      2698179.31     10016837.81
#Sta/Elev= 30
  4003.2  1940.9  4152.5 1934.49    4224 1928.22  4548.6 1912.06    4646 1903.96
    4733 1901.37  4743.9 1899.46  4776.3 1884.84  4827.8 1867.66  4855.9  1864.9
  4921.6 1856.45    4958 1852.24  4973.2 1847.86  5006.5 1846.16  5009.3 1845.66
  5012.5 1846.16  5014.1 1846.47  5037.5 1847.59  5051.8 1854.95  5073.1 1859.52
  5263.2 1867.47  5349.9 1875.41  5415.9 1879.94  5487.1 1875.87  5502.7 1878.23
  5518.4 1874.85  5566.7 1878.74  5699.8 1891.99    5854 1919.17  6055.4 1933.49
#Mann= 8 ,-1 , 0
  4003.2      .1       0    4224     .16       0  4855.9      .1       0
  5006.5     .07       0  5012.5      .1       0  5014.1     .16       0
  5349.9     .05       0  5566.7     .16       0
Bank Sta=4921.6,5051.8
XS Rating Curve= 0 ,0
Exp/Cntr=0.3,0.1

Type RM Length L Ch R = 1 ,53136   ,465,465,465
BEGIN DESCRIPTION:
WOLF CREEK 77.0
END DESCRIPTION:
XS GIS Cut Line= 3
      2696950.88     10018376.48      2697627.99     10017864.31
      2698161.41     10016957.92
#Sta/Elev= 30
  3959.2 1949.85  4017.2 1943.64  4052.6 1937.52  4123.3  1932.2  4187.8 1923.18
  4304.7 1903.43  4441.9 1887.04    4631 1870.99  4745.5 1865.65    4934 1853.03
  4955.5 1846.77  5048.2 1846.21  5050.9 1845.71  5054.2 1846.21  5087.3 1849.35
  5094.1  1853.7  5099.9  1857.2  5109.7 1858.14  5115.5 1860.92  5155.4 1863.98
  5226.6 1867.62  5291.3  1866.2  5328.4 1867.82  5365.5 1872.79  5394.2 1881.05
  5472.8    1900  5584.2 1907.72  5713.9 1920.21  5781.4 1922.76  5859.9 1928.17
#Mann= 7 ,-1 , 0
  3959.2      .1       0  4304.7     .05       0  4441.9      .1       0
  5048.2     .07       0  5054.2      .1       0  5155.4     .05       0
  5394.2     .16       0
Bank Sta=4934,5094.1
XS Rating Curve= 0 ,0
Exp/Cntr=0.3,0.1

Type RM Length L Ch R = 1 ,52671   ,335,335,335
BEGIN DESCRIPTION:
WOLF CREEK 76.0
END DESCRIPTION:
XS GIS Cut Line= 3
      2697445.68     10018545.75      2698456.98     10017682.02
       2698734.1      10017664.7
#Sta/Elev= 30
  4199.5 1913.27  4408.7 1899.88  4437.3 1895.48  4472.4 1884.67  4525.2 1873.16
  4550.4 1868.36  4597.4 1866.58  4663.4 1866.34  4777.6 1861.56  4912.7 1852.19
  4938.4 1849.19  4965.6 1846.17  4968.4 1845.67  4971.6 1846.17    5020 1846.55
  5060.6 1846.65  5075.1 1847.95  5089.4 1852.37  5132.2 1857.62  5189.3 1856.57
  5210.2 1859.35    5298 1861.38  5337.5 1863.71  5366.1 1869.09  5429.7 1889.93
  5437.4 1893.85  5486.8 1903.49    5571 1915.45  5650.3  1919.8  5807.1    1925
#Mann= 10 ,-1 , 0
  4199.5      .1       0  4525.2     .05       0  4597.4      .1       0
  4938.4     .05       0  4965.6    .035       0  4971.6     .05       0
    5020     .16       0  5060.6     .05       0    5298     .16       0
  5650.3      .1       0
#XS Ineff= 1 ,-1
 5144.32 5240.91 1858.27
Permanent Ineff=
       T
Bank Sta=4912.7,5089.4
XS Rating Curve= 0 ,0
Exp/Cntr=0.3,0.1