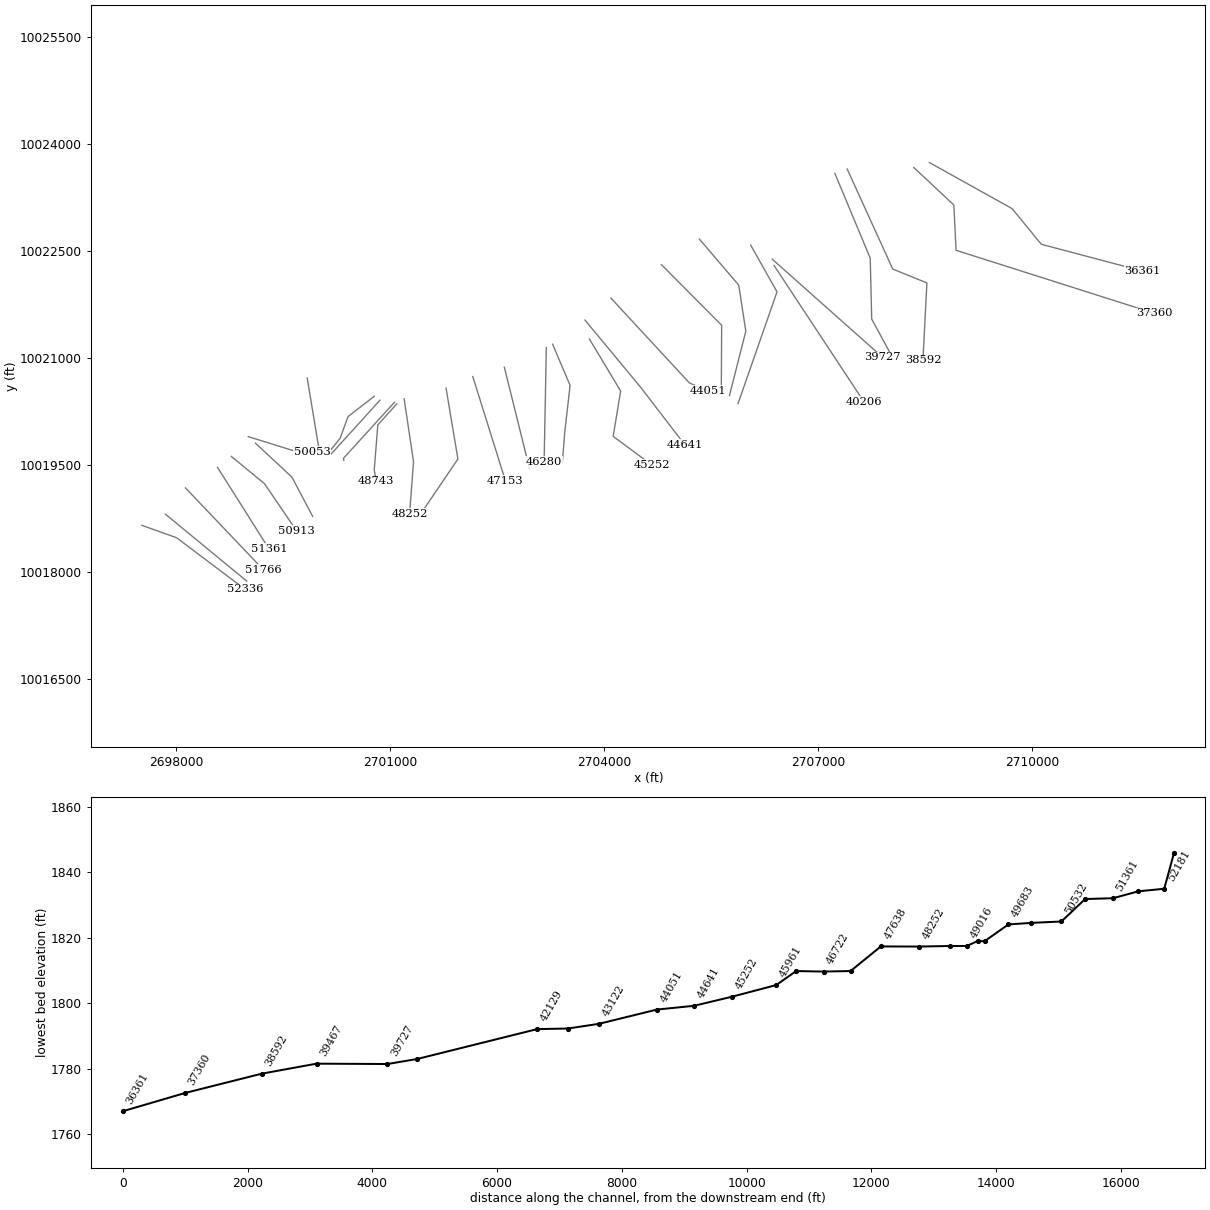
HEC-RAS study WOLF CREEK.prj: WOLF CREEK Base Level Engineering

--- WOLF CREEK.g01 (geometry) --- (continued)

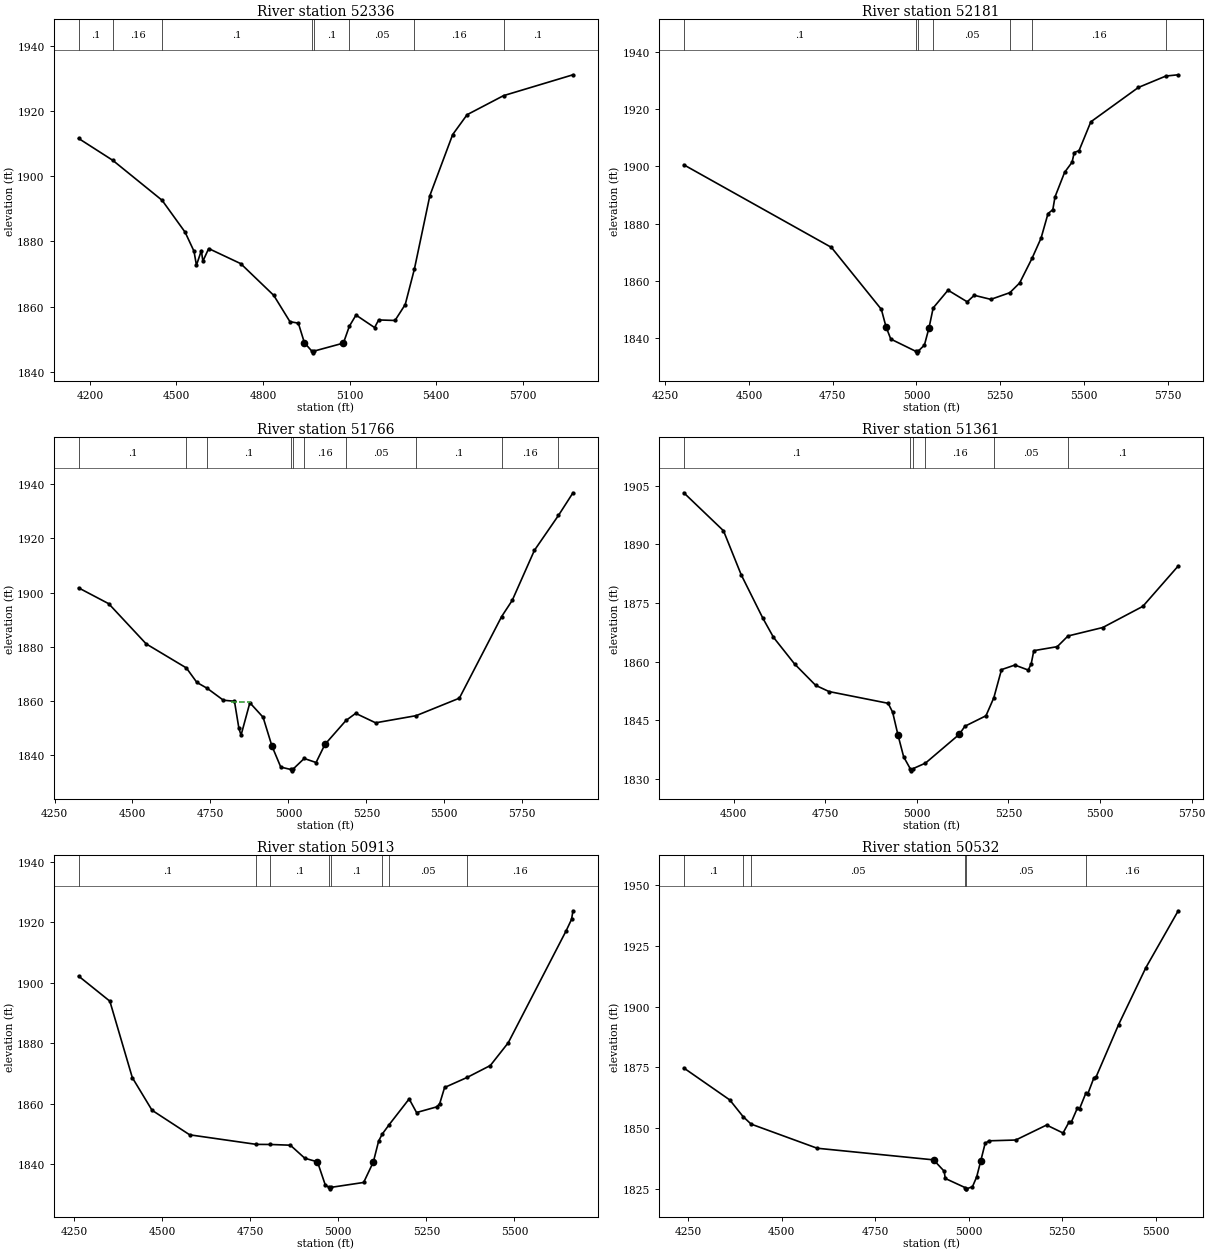
Type RM Length L Ch R = 1 ,52336   ,155,155,155
BEGIN DESCRIPTION:
Mapping XS 6ecf1202
END DESCRIPTION:
XS GIS Cut Line= 3
      2697523.61     10018652.25      2698009.72     10018478.64
      2698966.55     10017757.56
#Sta/Elev= 30
  4160.5 1911.63  4279.1  1904.9  4450.1 1892.63  4529.9 1882.83  4560.7 1876.99
  4569.2 1872.68  4586.2 1877.19  4591.5 1873.93  4611.6 1877.81  4722.7 1873.18
  4837.2 1863.44  4893.4 1855.36  4922.5  1854.9  4943.4 1848.92  4969.5 1846.29
  4972.2 1845.79  4975.5 1846.29  5078.7 1848.78  5099.3 1853.95  5122.4 1857.39
  5186.9 1853.55    5201 1855.89  5257.7 1855.73  5293.1 1860.62  5324.9 1871.52
  5378.5 1894.07  5457.6 1912.81  5507.6 1918.91  5633.9 1924.76  5874.8 1931.17
#Mann= 8 ,-1 , 0
  4160.5      .1       0  4279.1     .16       0  4450.1      .1       0
  4969.5     .07       0  4975.5      .1       0  5099.3     .05       0
  5324.9     .16       0  5633.9      .1       0
Bank Sta=4943.4,5078.7
XS Rating Curve= 0 ,0
Exp/Cntr=0.3,0.1

Type RM Length L Ch R = 1 ,52181   ,415,415,415
BEGIN DESCRIPTION:
WOLF CREEK 74.0
END DESCRIPTION:
XS GIS Cut Line= 2
      2697853.44     10018808.53       2698992.4     10017870.98
#Sta/Elev= 30
  4305.8 1900.54  4746.1 1871.76  4895.2 1850.16    4909 1844.13  4923.3  1839.8
  4998.5  1835.5  5001.3    1835  5004.5  1835.5  5023.7 1837.71  5037.6 1843.81
  5049.8 1850.65  5094.1 1856.84  5151.4 1852.78  5172.3 1855.06  5221.8 1853.64
  5278.6 1855.97  5307.8 1859.35  5344.7 1867.92  5371.7 1874.97  5392.5 1883.55
  5406.8  1884.9  5413.3 1889.35    5442 1897.92  5464.2 1901.43  5470.7 1904.82
    5485 1905.47  5520.2 1915.52  5662.2 1927.51  5744.1 1931.48    5781 1931.92
#Mann= 7 ,-1 , 0
  4305.8      .1       0  4998.5     .07       0  5004.5      .1       0
  5049.8     .05       0  5278.6      .1       0  5344.7     .16       0
  5744.1      .1       0
Bank Sta=4909,5037.6
XS Rating Curve= 0 ,0
Exp/Cntr=0.3,0.1

Type RM Length L Ch R = 1 ,51766   ,405,405,405
BEGIN DESCRIPTION:
Mapping XS 7422dcaa
END DESCRIPTION:
XS GIS Cut Line= 2
      2698134.73     10019176.55      2699227.75     10018028.02
#Sta/Elev= 30
  4327.2 1901.73  4423.9 1895.88    4544 1881.06  4672.9 1872.18  4706.6 1866.83
  4739.8 1864.66  4791.5 1860.28  4827.1 1859.89  4841.3 1849.93  4848.2 1847.37
  4876.5 1859.34  4918.9 1853.99  4947.3 1843.37  4975.6  1835.6  5007.8 1834.72
  5010.5 1834.22  5013.8 1834.72  5050.7 1838.78  5088.8 1837.29  5117.1 1843.95
  5184.7  1852.8  5215.8 1855.43  5279.7 1851.94  5409.8 1854.58  5548.3 1861.03
  5683.9 1891.15  5717.9 1897.13    5789 1915.58  5866.1 1928.46  5912.7 1936.81
#Mann= 10 ,-1 , 0
  4327.2      .1       0  4672.9     .16       0  4739.8      .1       0
  5007.8     .07       0  5013.8      .1       0  5050.7     .16       0
  5184.7     .05       0  5409.8      .1       0  5683.9     .16       0
  5866.1      .1       0
#XS Ineff= 1 ,-1
 4815.68 4877.05  1859.5
Permanent Ineff=
       T
Bank Sta=4947.3,5117.1
XS Rating Curve= 0 ,0
Exp/Cntr=0.3,0.1

Type RM Length L Ch R = 1 ,51361   ,448,448,448
BEGIN DESCRIPTION:
WOLF CREEK 73.0
END DESCRIPTION:
XS GIS Cut Line= 2
      2698582.86     10019465.86      2699303.32     10018324.41
#Sta/Elev= 30
  4363.6 1903.22  4471.9 1893.51  4520.2 1882.27    4579 1871.22  4608.4 1866.26
  4666.1 1859.44  4723.7 1853.97  4760.2 1852.39  4921.4 1849.39  4933.7 1847.12
  4948.5  1841.2  4963.8  1835.7    4982 1832.62  4984.7 1832.12    4988 1832.62
  5023.4  1834.1  5115.6 1841.45  5130.9 1843.52  5188.5  1846.2    5210 1850.82
  5230.9    1858  5267.4 1859.17  5303.9 1857.89  5312.1 1859.52  5319.1 1862.85
  5383.1 1863.87  5412.4  1866.6  5507.4 1868.77  5616.8 1874.18  5713.4 1884.51
#Mann= 6 ,-1 , 0
  4363.6      .1       0    4982     .07       0    4988      .1       0
  5023.4     .16       0    5210     .05       0  5412.4      .1       0
Bank Sta=4948.5,5115.6
XS Rating Curve= 0 ,0
Exp/Cntr=0.3,0.1

Type RM Length L Ch R = 1 ,50913   ,381,381,381
BEGIN DESCRIPTION:
WOLF CREEK 72.0
END DESCRIPTION:
XS GIS Cut Line= 3
      2698778.14      10019617.8      2699242.57     10019235.84
      2699693.69     10018572.17
#Sta/Elev= 30
  4262.6 1902.21  4351.4 1893.91  4415.2 1868.63  4471.2 1857.84  4578.1 1849.72
  4767.6 1846.56  4806.6 1846.53  4863.9 1846.29  4904.9 1841.98  4940.9 1840.78
  4963.2 1833.09  4973.8 1832.36  4976.5 1831.86  4979.8 1832.36    5072 1833.97
  5099.5 1840.73  5114.5 1847.65  5124.7 1849.95  5144.5 1853.09  5201.2 1861.59
  5222.2 1857.09  5279.1 1858.95    5288 1860.05  5301.8 1865.37  5365.9  1868.7
  5431.7 1872.64  5482.6 1880.17  5647.3 1917.27  5662.2 1920.95  5666.4  1923.8
#Mann= 8 ,-1 , 0
  4262.6      .1       0  4767.6     .16       0  4806.6      .1       0
  4973.8     .07       0  4979.8      .1       0  5124.7     .16       0
  5144.5     .05       0  5365.9     .16       0
Bank Sta=4940.9,5099.5
XS Rating Curve= 0 ,0
Exp/Cntr=0.3,0.1

Type RM Length L Ch R = 1 ,50532   ,479,479,479
BEGIN DESCRIPTION:
WOLF CREEK 71.0
END DESCRIPTION:
XS GIS Cut Line= 3
      2699115.38     10019804.22      2699627.55     10019326.77
       2699917.5     10018777.16
#Sta/Elev= 30
  4238.5 1874.77  4361.4 1861.61  4396.8 1854.78  4418.3 1851.67  4594.9 1841.73
  4906.1 1836.94  4934.5 1832.26  4937.3 1829.29  4990.6 1825.51  4993.4 1825.01
  4993.9 1825.01    5010 1825.87  5021.3 1829.89    5032 1836.37  5043.9 1843.71
    5054 1844.78  5125.8 1845.11  5208.2 1851.28  5252.2    1848  5268.6 1852.63
  5274.3 1852.49  5290.6 1858.29  5296.3 1857.98  5313.3 1864.47  5318.3 1864.09
  5334.7 1870.74  5340.3 1871.01  5400.7 1892.64  5473.5 1916.06  5560.1  1939.5
#Mann= 6 ,-1 , 0
  4238.5      .1       0  4396.8     .16       0  4418.3     .05       0
  4990.6     .07       0  4993.9     .05       0  5313.3     .16       0
Bank Sta=4906.1,5032
XS Rating Curve= 0 ,0
Exp/Cntr=0.3,0.1

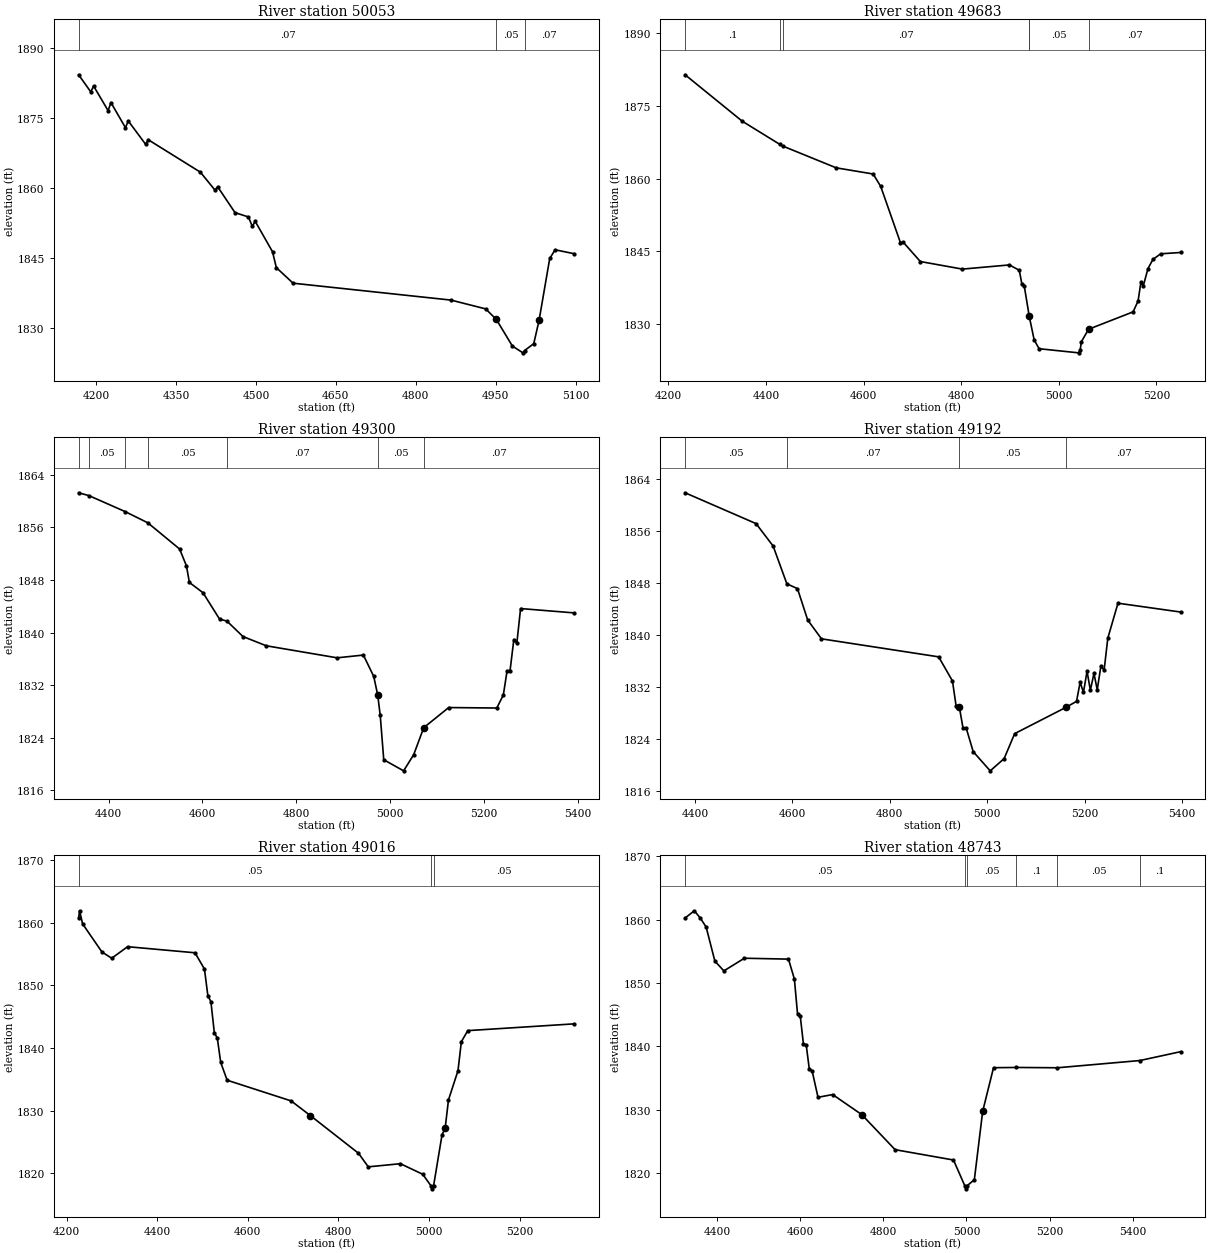
Type RM Length L Ch R = 1 ,50053   ,370,370,370
BEGIN DESCRIPTION:
Mapping XS be80b19e
END DESCRIPTION:
XS GIS Cut Line= 4
      2699014.02     10019896.25      2699639.01     10019701.81
      2699889.01     10019684.45      2699914.27      10019684.2
#Sta/Elev= 30
  4167.1  1884.2  4189.9 1880.53  4195.2 1881.79  4222.5  1876.5  4227.7 1878.25
    4255 1872.86  4260.3  1874.3  4292.8 1869.31    4298 1870.26  4395.7 1863.32
    4423 1859.49  4428.2 1860.18  4460.7 1854.65  4485.9 1853.72  4493.3 1851.68
  4498.5 1852.81  4531.1 1846.27  4538.3 1842.86  4569.7 1839.52  4866.1  1835.9
  4931.4 1834.01  4951.4 1831.74  4981.5 1826.04  5001.3 1824.59  5004.5 1825.09
  5021.6 1826.55  5031.6 1831.55  5051.6 1844.82  5061.7 1846.68  5097.5 1845.84
#Mann= 3 ,-1 , 0
  4167.1     .07       0  4951.4     .05       0  5004.5     .07       0
Bank Sta=4951.4,5031.6
XS Rating Curve= 0 ,0
Exp/Cntr=0.3,0.1

Type RM Length L Ch R = 1 ,49683   ,383,383,383
BEGIN DESCRIPTION:
Mapping XS baf38ad2
END DESCRIPTION:
XS GIS Cut Line= 3
       2699840.4     10020719.16      2700000.12     10019757.37
      2699992.59     10019717.84
#Sta/Elev= 30
  4234.3 1881.39  4351.3 1871.83  4427.9 1867.08  4435.7 1866.65  4543.9 1862.22
  4619.6 1860.95  4635.1 1858.38  4675.5 1846.79  4680.5 1846.98  4716.2 1842.92
  4802.4 1841.36  4898.7 1842.22    4919 1841.11  4924.3 1838.24  4929.3 1837.78
  4939.3 1831.65  4949.4 1826.78  4959.5 1824.96  5040.4 1824.11  5043.6 1824.61
  5046.1 1826.39  5060.9 1828.97  5152.1 1832.55  5162.3 1834.79    5168  1838.6
    5173 1837.89  5182.5 1841.45  5192.7 1843.35  5208.6 1844.51  5249.5 1844.78
#Mann= 6 ,-1 , 0
  4234.3      .1       0  4427.9     .05       0  4435.7     .07       0
  4939.3     .16       0  4939.3     .05       0  5060.9     .07       0
Bank Sta=4939.3,5060.9
XS Rating Curve= 0 ,0
Exp/Cntr=0.3,0.1

Type RM Length L Ch R = 1 ,49300   ,108,108,108
BEGIN DESCRIPTION:
Mapping XS 040c94c4
END DESCRIPTION:
XS GIS Cut Line= 4
      2700781.37     10020462.22      2700413.32      10020177.5
      2700302.21     10019871.95      2700135.18     10019665.51
#Sta/Elev= 30
  4336.2 1861.25  4358.1 1860.82  4435.6 1858.38  4483.7 1856.68  4551.4  1852.7
  4565.9 1850.15  4572.2 1847.62  4601.2 1846.06  4636.5 1842.05  4652.3 1841.74
  4686.3  1839.4  4736.1 1837.99  4887.1 1836.16    4943 1836.58  4965.1 1833.33
  4973.6 1830.47  4978.9 1827.42  4986.4 1820.67  5028.7 1818.98  5050.3 1821.45
  5071.6 1825.54  5124.8  1828.6  5227.3 1828.53  5241.3 1830.52  5249.2 1834.18
  5255.6 1834.23  5263.6 1838.93    5270 1838.38    5278 1843.65  5392.2 1842.99
#Mann= 7 ,-1 , 0
  4336.2      .1       0  4358.1     .05       0  4435.6      .1       0
  4483.7     .05       0  4652.3     .07       0  4973.6     .05       0
  5071.6     .07       0
Bank Sta=4973.6,5071.6
XS Rating Curve= 0 ,0
Exp/Cntr=0.3,0.1

Type RM Length L Ch R = 1 ,49192   ,176,176,176
BEGIN DESCRIPTION:
WOLF CREEK 70.0
END DESCRIPTION:
XS GIS Cut Line= 2
      2700861.26      10020406.7      2700177.31     10019653.09
#Sta/Elev= 30
  4379.6 1861.83  4525.3 1857.09  4560.4 1853.64  4588.6 1847.83  4610.4 1847.09
  4631.4 1842.26  4659.7 1839.37  4900.3  1836.6  4928.7 1832.89  4936.1 1829.08
  4942.9 1828.84  4950.3 1825.67  4957.1  1825.6  4971.3 1822.02  5006.2 1819.07
  5034.8 1820.95  5056.4 1824.79  5162.5 1828.86  5183.5 1829.76  5190.9  1832.7
  5197.7 1831.13  5205.1 1834.39  5211.9 1831.47  5219.3 1834.04    5226 1831.54
  5233.5 1835.16  5240.2 1834.57  5247.7 1839.46  5268.6 1844.85  5397.3 1843.49
#Mann= 4 ,-1 , 0
  4379.6     .05       0  4588.6     .07       0  4942.9     .05       0
  5162.5     .07       0
Bank Sta=4942.9,5162.5
XS Rating Curve= 0 ,0
Exp/Cntr=0.3,0.1

Type RM Length L Ch R = 1 ,49016   ,273,273,273
BEGIN DESCRIPTION:
WOLF CREEK 68.0
END DESCRIPTION:
XS GIS Cut Line= 3
       2701066.1      10020378.9      2700350.82     10019594.17
      2700353.57     10019562.49
#Sta/Elev= 30
  4226.6 1860.78  4228.7 1861.89  4235.4  1859.8    4278 1855.32  4299.6 1854.32
  4334.7 1856.16  4483.4 1855.19  4504.3 1852.59  4511.8 1848.34  4518.5  1847.4
    4526 1842.46  4532.7 1841.56  4540.1 1837.71  4554.3 1834.86  4695.5 1831.56
  4738.1 1829.21  4844.2 1823.21  4865.8 1821.04  4936.7 1821.54  4986.1 1819.85
    5004 1818.03  5006.8 1817.53    5010 1818.03  5028.6 1826.16  5035.4 1827.17
  5042.8 1831.71  5063.8 1836.38  5071.2    1841  5085.4 1842.77  5320.2 1843.85
#Mann= 3 ,-1 , 0
  4226.6     .05       0    5004     .04       0    5010     .05       0
Bank Sta=4738.1,5035.4
XS Rating Curve= 0 ,0
Exp/Cntr=0.3,0.1

Type RM Length L Ch R = 1 ,48743   ,491,491,491
BEGIN DESCRIPTION:
WOLF CREEK 69.0
END DESCRIPTION:
XS GIS Cut Line= 4
      2701097.36     10020356.34      2700830.42     10020059.02
      2700780.51     10019425.33      2700809.24     10019271.21
#Sta/Elev= 30
  4323.2 1860.28  4345.4 1861.42  4359.6 1860.29  4373.8 1858.86  4394.8 1853.48
  4416.4 1851.93  4465.8 1853.93  4571.9 1853.79  4586.1 1850.64  4593.6 1845.17
  4600.3 1844.76  4607.8 1840.42  4614.5 1840.27    4622 1836.41  4628.7 1836.17
  4642.9 1831.98  4678.1 1832.41  4748.1 1829.25  4828.4 1823.71  4968.8 1822.08
  4995.9 1818.03  4998.7 1817.53  5001.9 1818.03    5019 1818.98    5039 1829.76
  5065.1 1836.65  5119.7 1836.69  5218.8 1836.64    5417 1837.78  5515.2 1839.18
#Mann= 6 ,-1 , 0
  4323.2     .05       0  4995.9     .04       0  5001.9     .05       0
  5119.7      .1       0  5218.8     .05       0    5417      .1       0
Bank Sta=4748.1,5039
XS Rating Curve= 0 ,0
Exp/Cntr=0.3,0.1

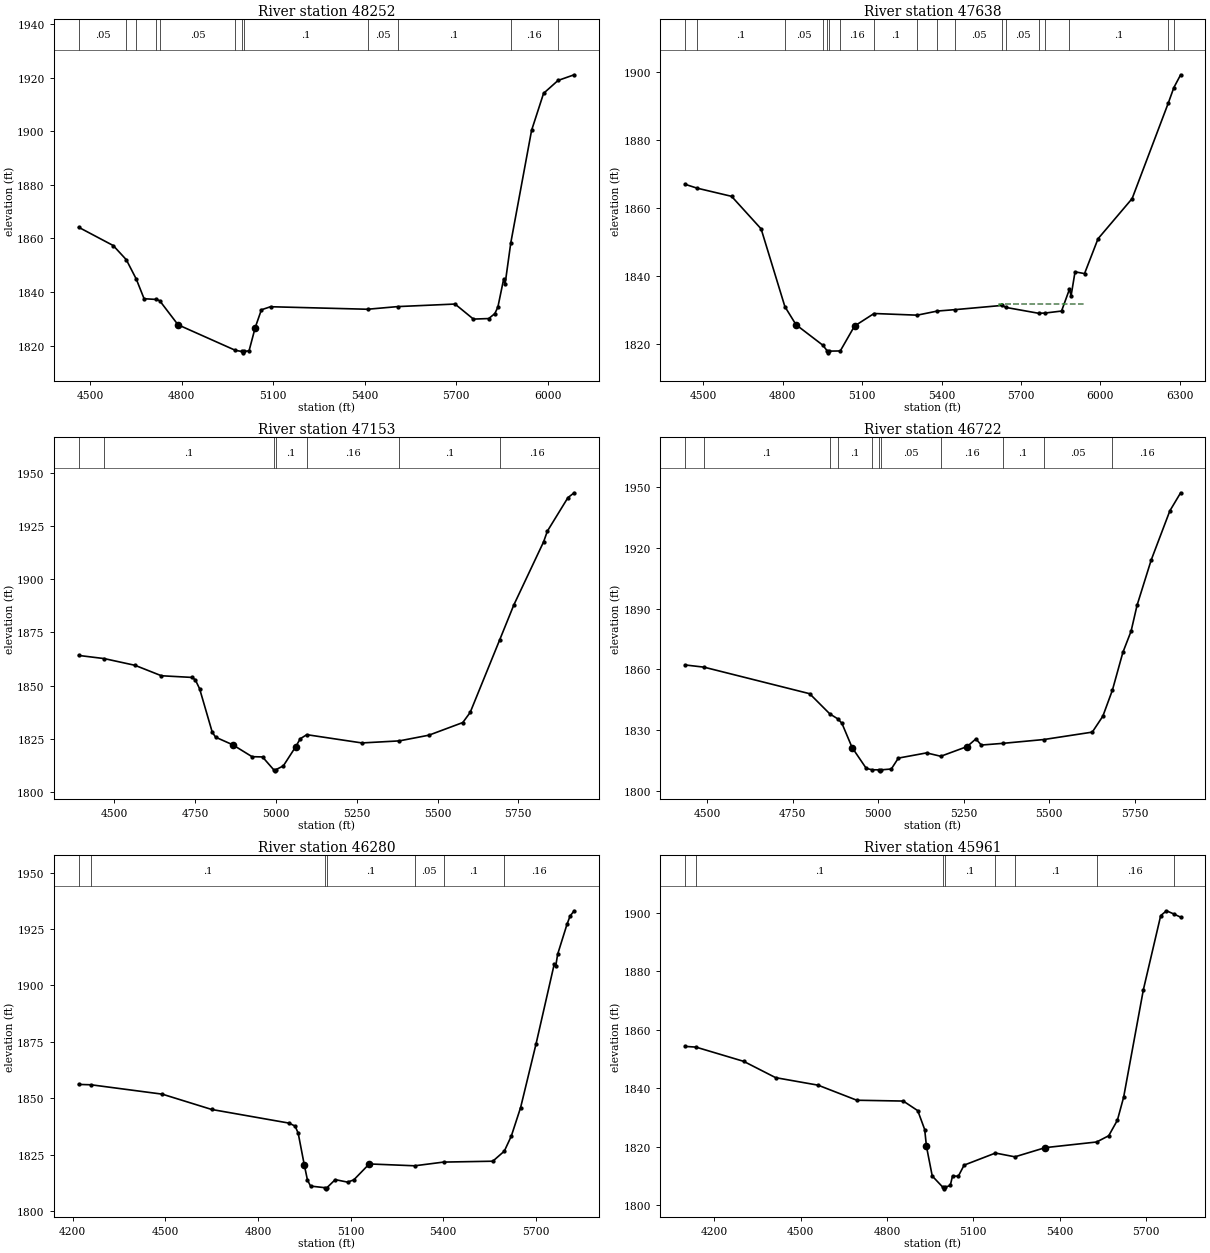
Type RM Length L Ch R = 1 ,48252   ,614,614,614
BEGIN DESCRIPTION:
Mapping XS bcfdd055
END DESCRIPTION:
XS GIS Cut Line= 3
      2701199.78     10020425.75      2701331.72     10019543.82
      2701276.17     10018814.67
#Sta/Elev= 30
    4463 1864.18  4576.3 1857.36  4619.1 1852.08  4651.9 1844.83  4677.4 1837.53
  4717.3 1837.27  4728.5 1836.79  4788.6 1827.82  4976.3  1818.3  4997.9 1817.86
  5000.7 1817.36  5003.9 1817.86  5021.2 1818.12  5041.4  1826.8  5061.6 1833.41
  5091.5 1834.55  5409.2 1833.61  5508.2  1834.6  5695.8 1835.55    5756 1829.94
  5806.1 1830.14  5826.2 1831.99  5836.2 1834.46  5854.8 1844.72  5859.8 1843.06
  5878.4 1858.36  5946.5  1900.3  5985.8  1914.1  6033.1  1918.9    6086 1921.02
#Mann= 12 ,-1 , 0
    4463     .05       0  4619.1      .1       0  4651.9     .05       0
  4717.3      .1       0  4728.5     .05       0  4976.3      .1       0
  4997.9     .07       0  5003.9      .1       0  5409.2     .05       0
  5508.2      .1       0  5878.4     .16       0  6033.1      .1       0
Bank Sta=4788.6,5041.4
XS Rating Curve= 0 ,0
Exp/Cntr=0.3,0.1

Type RM Length L Ch R = 1 ,47638   ,485,485,485
BEGIN DESCRIPTION:
WOLF CREEK 67.0
END DESCRIPTION:
XS GIS Cut Line= 3
      2701787.27     10020576.79      2701953.94     10019581.98
      2701469.68      10018868.6
#Sta/Elev= 30
  4431.7 1866.97  4476.7 1865.84  4607.2 1863.43  4718.7 1853.86  4808.5 1830.98
  4850.5 1825.67  4951.3 1819.67  4969.2  1817.9  4971.9  1817.4  4975.2  1817.9
  5017.6 1817.96  5071.4 1825.28  5145.1 1828.97  5307.9 1828.48  5383.9 1829.69
  5451.9 1830.11  5627.8 1831.34  5644.1 1830.74  5766.6 1829.03  5791.3 1829.11
    5853 1829.69  5882.9 1836.12  5888.9 1834.12  5903.9 1841.22  5939.8 1840.71
  5990.7 1850.95  6119.5 1862.77  6256.7 1891.01    6277 1895.42  6302.6 1899.18
#Mann= 18 ,-1 , 0
  4431.7     .05       0  4476.7      .1       0  4808.5     .05       0
  4951.3      .1       0  4969.2     .07       0  4975.2      .1       0
  5017.6     .16       0  5145.1      .1       0  5307.9     .05       0
  5383.9      .1       0  5451.9     .05       0  5627.8      .1       0
  5644.1     .05       0  5766.6      .1       0  5791.3     .05       0
  5882.9      .1       0  6256.7     .05       0    6277      .1       0
#XS Ineff= 1 ,-1
 5615.06 5936.08 1831.91
Permanent Ineff=
       T
Bank Sta=4850.5,5071.4
XS Rating Curve= 0 ,0
Exp/Cntr=0.3,0.1

Type RM Length L Ch R = 1 ,47153   ,431,431,431
BEGIN DESCRIPTION:
WOLF CREEK 66.0
END DESCRIPTION:
XS GIS Cut Line= 2
      2702162.26     10020738.26      2702620.62     10019274.66
#Sta/Elev= 30
  4389.1 1864.17  4468.4 1862.68  4563.6 1859.52  4645.3 1854.61  4739.7 1853.83
  4750.1 1852.73  4763.5 1848.51  4802.5 1828.14    4813 1825.72  4866.1 1822.14
  4925.8 1816.55  4958.2 1816.43  4992.9 1810.39  4995.7 1809.89  4998.9 1810.39
  5022.6 1812.21  5060.8 1821.21    5075 1824.98  5095.2  1826.9    5266 1823.01
  5381.7 1823.98  5473.2 1826.66    5578  1832.6  5600.9 1837.35  5692.3  1871.5
    5736  1887.9  5828.1 1917.57  5839.9 1922.64  5903.5 1938.39  5922.8 1940.67
#Mann= 7 ,-1 , 0
  4389.1     .05       0  4468.4      .1       0  4992.9     .07       0
  4998.9      .1       0  5095.2     .16       0  5381.7      .1       0
  5692.3     .16       0
Bank Sta=4866.1,5060.8
XS Rating Curve= 0 ,0
Exp/Cntr=0.3,0.1

Type RM Length L Ch R = 1 ,46722   ,442,442,442
BEGIN DESCRIPTION:
WOLF CREEK 65.0
END DESCRIPTION:
XS GIS Cut Line= 2
      2702604.98     10020868.45       2702953.7     10019463.17
#Sta/Elev= 30
  4435.7 1862.13  4490.8 1861.04  4799.6  1847.9  4858.8 1837.87    4882 1835.44
  4893.9 1833.26  4923.7 1821.25    4965 1810.95  4982.3 1810.25  5003.4 1810.23
  5006.1 1809.73  5009.4 1810.23  5038.2 1810.64  5058.8 1816.03  5141.2 1818.61
  5182.8 1816.94  5259.7 1821.74  5285.4 1825.54  5301.1 1822.49    5364 1823.33
  5483.7 1825.22  5625.4 1828.89  5656.3 1836.77  5684.2 1849.64  5714.8 1868.34
  5738.8 1878.83  5756.2 1891.62  5797.5 1914.02  5852.1  1938.4  5883.6 1947.33
#Mann= 11 ,-1 , 0
  4435.7     .05       0  4490.8      .1       0  4858.8     .05       0
    4882      .1       0  4982.3     .05       0  5003.4    .035       0
  5009.4     .05       0  5182.8     .16       0    5364      .1       0
  5483.7     .05       0  5684.2     .16       0
Bank Sta=4923.7,5259.7
XS Rating Curve= 0 ,0
Exp/Cntr=0.3,0.1

Type RM Length L Ch R = 1 ,46280   ,319,319,319
BEGIN DESCRIPTION:
WOLF CREEK 64.0
END DESCRIPTION:
XS GIS Cut Line= 2
      2703193.53     10021144.51      2703162.28     10019540.32
#Sta/Elev= 30
  4219.3 1856.14  4259.5 1855.98  4490.1 1851.83  4650.2 1845.04  4900.2 1839.01
  4920.2 1837.68  4930.2 1834.54  4950.2  1820.3  4960.2 1813.79  4970.2  1811.1
  5017.2 1810.38    5020 1809.88  5023.2 1810.38  5050.2 1813.96  5090.2 1812.85
  5110.3 1813.86  5160.3 1820.91  5307.5 1820.09  5400.7 1821.73  5560.3 1822.12
  5597.6 1826.58  5620.3 1833.27  5650.4 1845.91  5700.4 1874.12    5759  1909.3
    5764 1908.53  5770.4 1913.87  5800.4    1927  5810.4 1930.71  5823.8 1933.07
#Mann= 7 ,-1 , 0
  4219.3     .05       0  4259.5      .1       0  5017.2     .07       0
  5023.2      .1       0  5307.5     .05       0  5400.7      .1       0
  5597.6     .16       0
Bank Sta=4950.2,5160.3
XS Rating Curve= 0 ,0
Exp/Cntr=0.3,0.1

Type RM Length L Ch R = 1 ,45961   ,709,709,709
BEGIN DESCRIPTION:
WOLF CREEK 63.0
END DESCRIPTION:
XS GIS Cut Line= 4
      2703282.05     10021191.39      2703526.86     10020613.23
      2703453.94     10019983.02      2703417.48     10019524.64
#Sta/Elev= 30
  4098.3 1854.29  4135.9 1854.05  4301.9 1849.18  4412.9 1843.61  4560.4 1841.04
  4695.1 1835.89  4856.5 1835.61  4906.9 1832.32  4930.9 1825.88  4937.1 1820.09
  4957.2 1809.99  4994.5 1806.11  4997.2 1805.61  5000.5 1806.11  5019.7 1806.76
  5027.7 1809.98  5047.8 1809.92  5067.9 1813.71  5176.8 1817.84  5244.5 1816.55
  5349.8 1819.69  5528.5 1821.62  5570.5 1823.76  5600.6 1829.06  5622.3 1836.93
  5690.9 1873.67  5751.1 1898.98  5771.2 1900.64  5795.7 1899.59  5820.4 1898.45
#Mann= 8 ,-1 , 0
  4098.3     .05       0  4135.9      .1       0  4994.5     .07       0
  5000.5      .1       0  5176.8     .16       0  5244.5      .1       0
  5528.5     .16       0  5795.7      .1       0
Bank Sta=4937.1,5349.8
XS Rating Curve= 0 ,0
Exp/Cntr=0.3,0.1

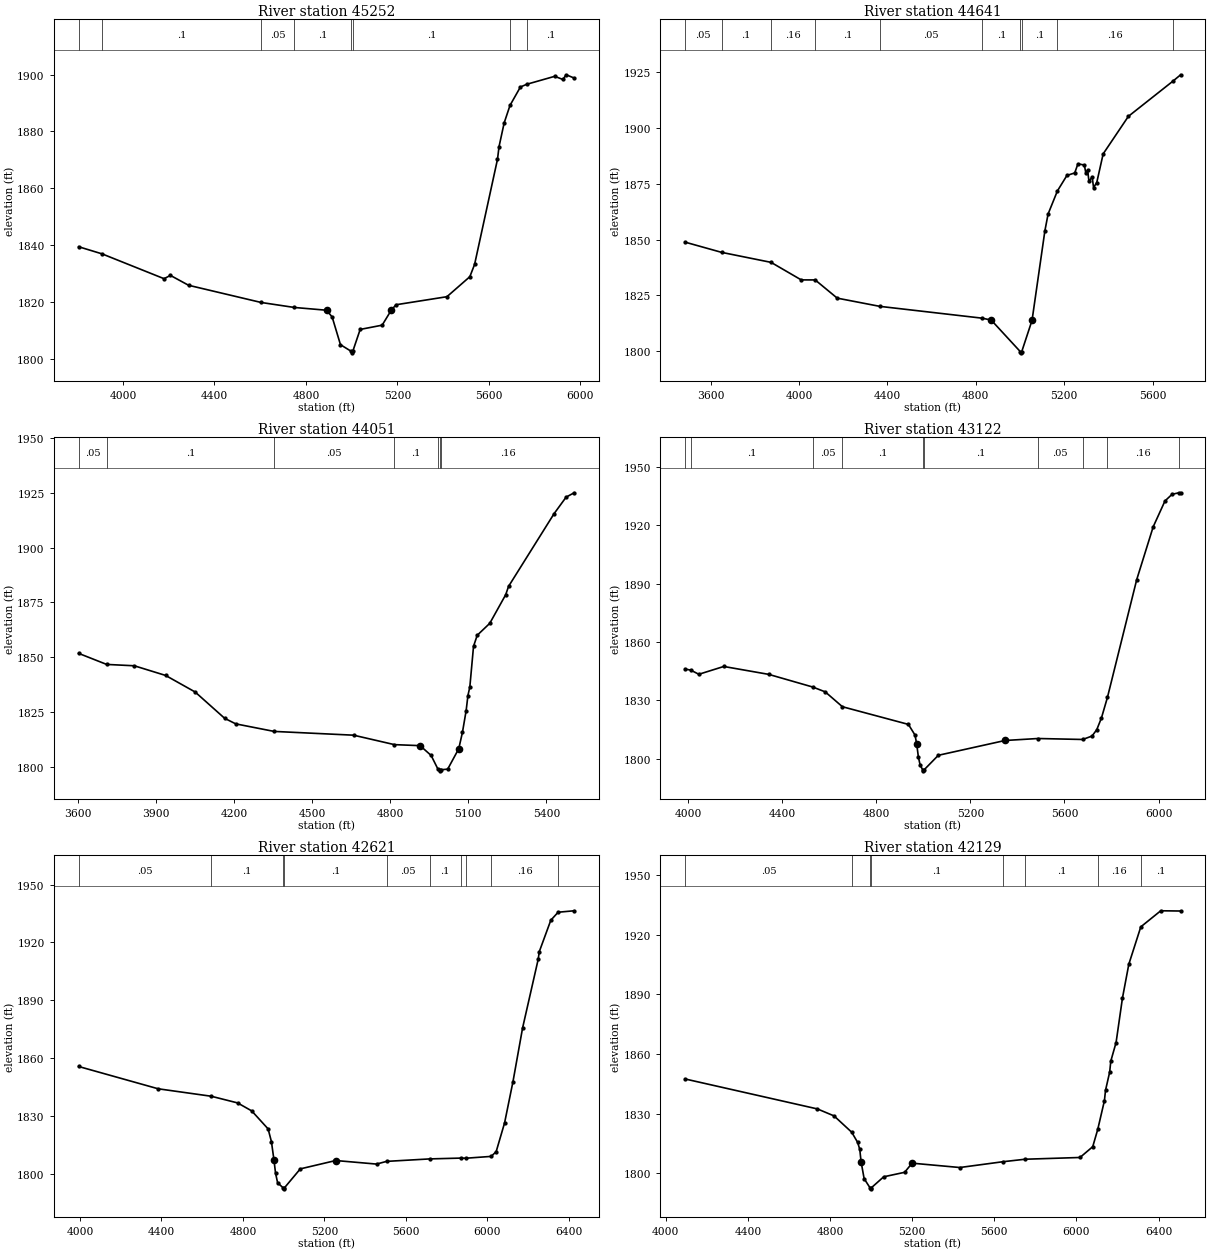
Type RM Length L Ch R = 1 ,45252   ,611,611,611
BEGIN DESCRIPTION:
WOLF CREEK 62.0
END DESCRIPTION:
XS GIS Cut Line= 4
      2703797.69     10021264.27      2704235.19      10020535.1
      2704131.03     10019899.68       2704672.6     10019498.71
#Sta/Elev= 30
  3805.6  1839.4    3908 1836.89  4179.4 1828.15  4207.1 1829.31  4286.7 1825.83
  4604.1 1819.78  4749.6 1818.02  4890.4 1817.05  4914.8 1814.67  4951.2 1804.92
  4998.9 1802.55  5001.6 1802.05  5004.9 1802.55  5037.4 1810.29  5133.6 1811.79
  5174.1 1817.15  5194.4 1818.98    5417 1821.81  5517.2 1828.85    5538 1833.17
  5638.2 1870.18    5645 1874.65  5667.4 1882.99  5693.1 1889.18  5738.4 1895.62
  5765.9 1896.58  5888.7 1899.39  5924.1 1898.28  5938.8 1899.93  5973.7 1898.78
#Mann= 8 ,-1 , 0
  3805.6     .05       0    3908      .1       0  4604.1     .05       0
  4749.6      .1       0  4998.9     .07       0  5004.9      .1       0
  5693.1     .16       0  5765.9      .1       0
Bank Sta=4890.4,5174.1
XS Rating Curve= 0 ,0
Exp/Cntr=0.3,0.1

Type RM Length L Ch R = 1 ,44641   ,590,590,590
BEGIN DESCRIPTION:
WOLF CREEK 61.0
END DESCRIPTION:
XS GIS Cut Line= 3
      2703735.22     10021529.86      2704516.44     10020587.18
      2705136.24     10019779.89
#Sta/Elev= 30
  3484.9 1848.85  3649.9 1844.28  3873.8  1839.8  4010.4 1831.94  4073.4 1831.93
  4173.2 1823.77  4365.7 1820.09  4829.5 1814.79  4869.9 1813.95  5001.9 1799.77
  5004.6 1799.27  5007.9 1799.77  5054.7 1813.83  5112.8 1853.94  5127.3 1861.46
  5169.5  1871.8  5212.5 1878.73  5247.8 1879.85  5262.3 1883.94  5291.3 1883.38
  5297.7 1880.02  5305.9 1881.14  5312.2 1876.12  5326.7 1878.05    5333 1873.32
  5347.5 1875.56  5376.5  1888.4  5490.7 1905.21  5690.9 1920.87    5727 1923.82
#Mann= 10 ,-1 , 0
  3484.9     .05       0  3649.9      .1       0  3873.8     .16       0
  4073.4      .1       0  4365.7     .05       0  4829.5      .1       0
  5001.9     .07       0  5007.9      .1       0  5169.5     .16       0
  5690.9      .1       0
Bank Sta=4869.9,5054.7
XS Rating Curve= 0 ,0
Exp/Cntr=0.3,0.1

Type RM Length L Ch R = 1 ,44051   ,929,929,929
BEGIN DESCRIPTION:
WOLF CREEK 60.0
END DESCRIPTION:
XS GIS Cut Line= 3
      2704099.76      10021837.2      2705198.73     10020649.68
      2705459.13     10020535.11
#Sta/Elev= 30
  3604.1 1851.72  3711.7 1846.68  3817.8 1846.06  3938.1 1841.65  4051.4  1834.1
  4164.8 1822.09  4207.4 1819.56  4354.7 1816.12  4659.8  1814.4  4816.6 1810.09
    4915 1809.63  4957.5 1805.15  4983.4 1798.96  4989.6 1798.64  4992.4 1798.14
  4995.6 1798.64    5021 1798.92  5063.5 1808.23  5077.7 1815.72  5091.9 1825.64
  5098.7 1832.49    5106 1836.39  5120.2 1854.93  5134.4 1859.98  5182.5 1865.41
  5243.7 1878.47  5254.7 1882.28  5429.4 1915.43  5475.7 1922.99  5506.6 1924.97
#Mann= 7 ,-1 , 0
  3604.1     .05       0  3711.7      .1       0  4354.7     .05       0
  4816.6      .1       0  4983.4     .16       0  4989.6     .07       0
  4995.6     .16       0
Bank Sta=4915,5063.5
XS Rating Curve= 0 ,0
Exp/Cntr=0.3,0.1

Type RM Length L Ch R = 1 ,43122   ,501,501,501
BEGIN DESCRIPTION:
WOLF CREEK 59.0
END DESCRIPTION:
XS GIS Cut Line= 3
      2704808.08     10022305.96      2705651.86     10021456.98
      2705646.66     10020547.16
#Sta/Elev= 30
  3987.1 1846.09  4010.7 1845.59  4045.5 1843.42  4151.6 1847.44  4342.5 1843.38
  4530.4 1836.85  4582.9 1834.38    4656 1826.74  4936.5 1817.66  4964.7 1812.15
  4971.8 1807.51  4978.9 1800.94    4986 1796.96  4997.1 1794.29  4999.9 1793.79
  5003.1 1794.29  5063.7 1801.78  5347.3 1809.39  5487.5 1810.41  5677.6 1809.91
  5717.3 1811.69  5737.3 1814.95  5757.3    1821  5782.7 1831.54  5907.3 1892.14
  5977.3 1919.26  6027.3 1932.51  6057.3 1935.92  6086.1 1936.72  6093.9  1936.6
#Mann= 10 ,-1 , 0
  3987.1     .05       0  4010.7      .1       0  4530.4     .05       0
    4656      .1       0  4997.1     .07       0  5003.1      .1       0
  5487.5     .05       0  5677.6      .1       0  5782.7     .16       0
  6086.1      .1       0
Bank Sta=4971.8,5347.3
XS Rating Curve= 0 ,0
Exp/Cntr=0.3,0.1

Type RM Length L Ch R = 1 ,42621   ,492,492,492
BEGIN DESCRIPTION:
WOLF CREEK 58.0
END DESCRIPTION:
XS GIS Cut Line= 4
      2705339.34     10022665.33      2705891.44     10022019.48
       2705990.4     10021373.64      2705761.23     10020472.57
#Sta/Elev= 30
  3993.5 1855.74  4384.1 1844.18  4644.5 1840.32  4773.9 1836.86  4843.2 1832.73
  4923.7  1823.4    4940 1816.81 4952.27 1807.43  4960.3 1800.42  4970.4 1795.48
  4997.7 1792.84  5000.5 1792.34  5003.7 1792.84  5081.7 1802.68  5255.7 1807.01
    5456 1805.17  5505.4 1806.57  5717.5 1807.85  5869.1 1808.27  5895.3 1808.21
  6018.7 1809.15  6043.3  1811.6  6084.6 1826.48  6125.9 1847.91    6173 1875.68
  6249.7 1911.29  6254.9  1915.2  6311.6 1931.52  6347.5 1935.67  6426.3 1936.42
#Mann= 10 ,-1 , 0
  3993.5     .05       0  4644.5      .1       0  4997.7     .07       0
  5003.7      .1       0  5505.4     .05       0  5717.5      .1       0
  5869.1     .05       0  5895.3      .1       0  6018.7     .16       0
  6347.5      .1       0
Bank Sta=4952.27,5255.7
XS Rating Curve= 0 ,0
Exp/Cntr=0.3,0.1

Type RM Length L Ch R = 1 ,42129   ,1923,1923,1923
BEGIN DESCRIPTION:
WOLF CREEK 57.0
END DESCRIPTION:
XS GIS Cut Line= 3
      2706058.09     10022582.01       2706427.9     10021925.73
      2705881.14     10020358.36
#Sta/Elev= 30
  4094.5 1847.46    4739 1832.38  4819.9 1828.87  4905.9 1820.66  4934.6 1815.59
  4945.2 1812.03  4951.4  1805.9  4966.4  1797.3  4995.2 1792.67  4997.9 1792.17
  5001.2 1792.67  5061.7 1798.23  5163.6 1800.49    5200 1805.09  5432.4  1802.9
  5641.8 1805.81  5750.5 1807.07  6017.6 1807.95  6079.7 1813.38  6104.1 1822.08
  6136.6 1836.53    6142 1841.76  6162.3 1850.98  6167.6 1856.42  6193.4 1865.81
  6224.5 1888.22  6255.5 1905.23  6313.8 1924.01  6410.9  1932.1  6507.8 1931.98
#Mann= 8 ,-1 , 0
  4094.5     .05       0  4905.9      .1       0  4995.2     .07       0
  5001.2      .1       0  5641.8     .05       0  5750.5      .1       0
  6104.1     .16       0  6313.8      .1       0
Bank Sta=4951.4,5200
XS Rating Curve= 0 ,0
Exp/Cntr=0.3,0.1

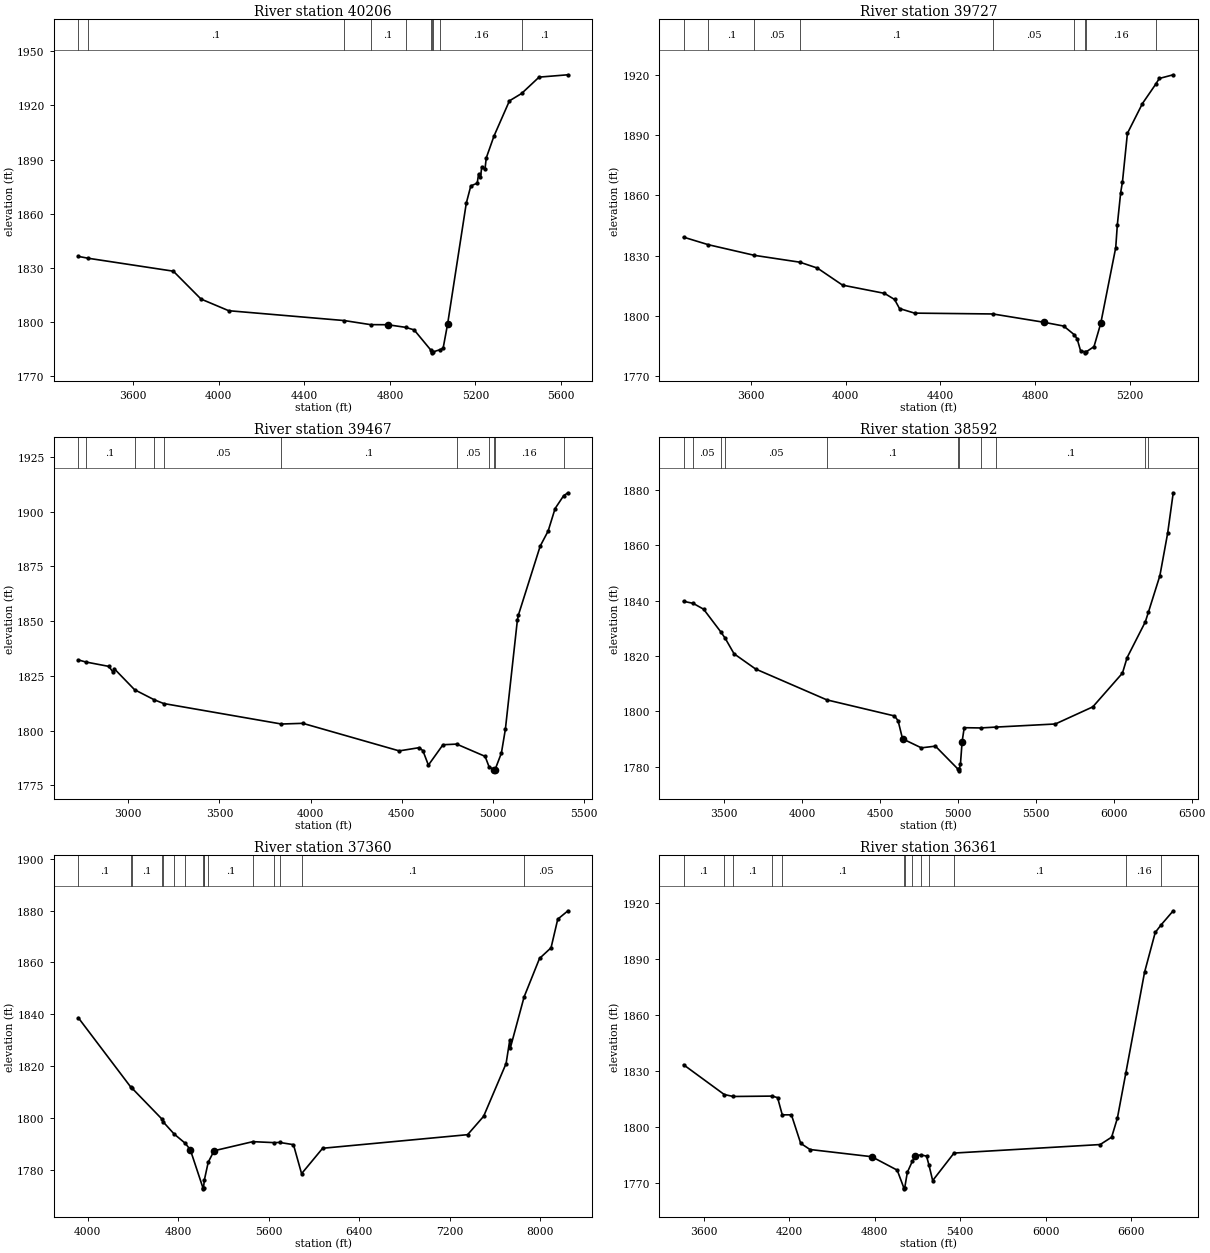
Type RM Length L Ch R = 1 ,40206   ,479,479,479
BEGIN DESCRIPTION:
WOLF CREEK 56.0
END DESCRIPTION:
XS GIS Cut Line= 2
      2706386.23     10022295.52      2707646.64     10020384.07
#Sta/Elev= 30
    3343 1836.43  3389.5  1835.4  3787.2 1828.25  3916.7 1812.82  4046.2 1806.37
  4586.2 1800.92  4709.4 1798.66  4789.9 1798.61  4873.2 1797.17  4913.3 1795.75
  4991.2 1784.59  4995.2 1783.55  4997.9 1783.05  5001.2 1783.55    5032 1784.71
  5048.8 1785.58    5070 1799.13  5157.2 1865.93  5178.3 1875.44  5208.4 1876.98
  5214.4 1881.94  5223.5 1880.11  5229.5 1886.06  5244.5 1884.56  5250.5 1890.93
  5286.7 1903.06  5358.9 1922.54  5415.9 1926.62  5497.5 1935.67  5632.6 1936.97
#Mann= 10 ,-1 , 0
    3343     .05       0  3389.5      .1       0  4586.2     .05       0
  4709.4      .1       0  4873.2     .16       0  4991.2      .1       0
  4995.2     .07       0  5001.2      .1       0    5032     .16       0
  5415.9      .1       0
Bank Sta=4789.9,5070
XS Rating Curve= 0 ,0
Exp/Cntr=0.3,0.1

Type RM Length L Ch R = 1 ,39727   ,1135,1135,1135
BEGIN DESCRIPTION:
WOLF CREEK 55.0
END DESCRIPTION:
XS GIS Cut Line= 2
      2706360.22     10022384.03      2707907.06     10021009.06
#Sta/Elev= 30
  3315.2 1839.15  3419.5  1835.4  3614.5 1830.09  3806.6 1826.68  3880.8 1823.74
    3987 1815.25  4164.3 1811.15  4206.9  1808.1  4227.8 1803.59  4291.4  1801.3
  4622.6 1800.88  4837.4 1796.76  4921.9 1794.85  4966.5 1790.54  4978.7 1788.48
    4993 1782.57  5010.9 1782.01  5013.6 1781.51  5016.9 1782.01  5049.8 1784.58
  5078.3 1796.15  5141.8 1833.99  5148.5 1845.29  5162.7  1861.4  5170.2 1866.72
  5191.1 1890.89  5254.7 1905.75  5309.9 1915.23  5325.8 1918.23  5384.8 1920.07
#Mann= 9 ,-1 , 0
  3315.2     .05       0  3419.5      .1       0  3614.5     .05       0
  3806.6      .1       0  4622.6     .05       0  4966.5     .16       0
  5010.9     .07       0  5016.9     .16       0  5309.9      .1       0
Bank Sta=4837.4,5078.3
XS Rating Curve= 0 ,0
Exp/Cntr=0.3,0.1

Type RM Length L Ch R = 1 ,39467   ,875,875,875
BEGIN DESCRIPTION:
Mapping XS 9b88099f
END DESCRIPTION:
XS GIS Cut Line= 4
      2707239.81     10023585.07       2707734.6     10022397.58
      2707755.43     10021543.41      2708015.84     10021064.28
#Sta/Elev= 30
  2725.9 1832.28  2765.7 1831.35  2893.3 1829.32  2917.2 1826.58  2922.6 1828.29
  3034.6 1818.66  3142.2 1814.08  3193.6 1812.37  3840.3    1803  3957.2 1803.32
  4486.3 1790.73  4596.4 1792.21  4616.4  1790.8  4646.4 1784.23  4726.4 1793.54
  4801.5 1793.83  4957.5 1788.23  4979.5 1783.42    5006 1782.12  5008.7 1781.62
    5012 1782.12    5047 1789.78  5068.8 1800.63  5134.4 1850.31  5140.1 1852.74
  5259.8 1884.26  5303.5 1891.17  5341.5 1901.41  5388.5 1907.29  5412.1 1908.61
#Mann= 11 ,-1 , 0
  2725.9     .05       0  2765.7      .1       0  3034.6     .05       0
  3142.2      .1       0  3193.6     .05       0  3840.3      .1       0
  4801.5     .05       0  4979.5     .16       0    5006     .07       0
    5012     .16       0  5388.5      .1       0
Bank Sta=5006,5012
XS Rating Curve= 0 ,0
Exp/Cntr=0.3,0.1

Type RM Length L Ch R = 1 ,38592   ,1232,1232,1232
BEGIN DESCRIPTION:
WOLF CREEK 54.0
END DESCRIPTION:
XS GIS Cut Line= 4
      2707411.34     10023648.13      2708050.22     10022245.35
      2708529.39      10022050.9      2708473.87     10020968.16
#Sta/Elev= 30
  3239.1 1839.75  3300.2 1839.03  3367.6 1836.91  3476.9 1828.79  3506.1 1826.41
    3563 1820.82  3701.3 1815.33  4158.5 1804.19  4592.7 1798.39  4615.7 1796.67
  4644.3 1790.14    4765 1786.88  4855.4 1787.49  5002.3 1779.08    5005 1778.58
  5008.3 1779.08  5016.2 1781.19  5026.8 1789.15  5040.2 1794.15  5144.8 1794.06
  5241.1 1794.36  5625.2 1795.49  5865.6 1801.67  6055.8 1813.84  6085.8 1819.45
  6202.5 1832.33    6222 1835.76  6296.1 1849.01  6346.2 1864.42  6381.8 1878.93
#Mann= 11 ,-1 , 0
  3239.1      .1       0  3300.2     .05       0  3476.9      .1       0
  3506.1     .05       0  4158.5      .1       0  5002.3     .07       0
  5008.3      .1       0  5144.8     .05       0  5241.1      .1       0
  6202.5     .05       0    6222      .1       0
Bank Sta=4644.3,5026.8
XS Rating Curve= 0 ,0
Exp/Cntr=0.3,0.1

Type RM Length L Ch R = 1 ,37360   ,999,999,999
BEGIN DESCRIPTION:
WOLF CREEK 53.0
END DESCRIPTION:
XS GIS Cut Line= 4
      2708344.62     10023669.54      2708907.13     10023143.49
      2708938.38     10022508.07      2711724.17     10021622.87
#Sta/Elev= 30
  3915.7 1838.66  4381.1 1811.83  4386.1 1811.71  4656.3 1799.53  4667.7 1798.42
    4763 1793.82  4861.3 1790.24  4905.9 1787.75  5016.7 1773.18  5019.5 1772.68
  5022.7 1773.18  5029.9 1776.06  5064.2 1782.95  5116.1 1787.37  5458.9 1790.88
  5647.6  1790.5  5695.4 1790.58  5817.9 1789.72  5889.7 1778.53  6075.9 1788.33
  7357.7 1793.57  7499.3 1800.65  7698.1 1821.02  7730.3 1830.01  7735.6 1827.03
  7857.4 1846.72  7993.6 1861.54  8095.6 1865.66  8154.8 1876.69  8245.1 1879.93
#Mann= 16 ,-1 , 0
  3915.7      .1       0  4381.1     .05       0  4386.1      .1       0
  4656.3     .05       0  4667.7      .1       0    4763     .05       0
  4861.3      .1       0  5016.7     .07       0  5022.7      .1       0
  5029.9     .16       0  5064.2      .1       0  5458.9     .05       0
  5647.6      .1       0  5695.4     .05       0  5889.7      .1       0
  7857.4     .05       0
Bank Sta=4905.9,5116.1
XS Rating Curve= 0 ,0
Exp/Cntr=0.3,0.1

Type RM Length L Ch R = 1 ,36361   ,751,751,751
BEGIN DESCRIPTION:
WOLF CREEK 52.0
END DESCRIPTION:
XS GIS Cut Line= 4
      2708564.09     10023738.41      2709723.84     10023092.57
      2710133.56     10022592.57      2711550.19     10022217.58
#Sta/Elev= 30
  3457.5 1833.48    3743 1817.57  3805.8 1816.52    4080 1816.73  4117.6  1815.9
  4150.5  1806.7  4214.8  1806.7  4279.9 1791.46  4345.1 1788.15  4778.8  1784.3
  4957.9  1777.1  5004.5  1767.6  5007.2  1767.1  5010.5  1767.6  5029.1 1775.93
  5063.4 1781.73  5085.7 1784.55  5122.5 1785.31  5163.9 1784.61  5180.7 1779.92
    5207 1771.51  5356.9 1786.24  6383.6  1790.8  6464.1 1794.74  6504.3 1804.87
  6563.3 1828.86  6695.1 1882.91  6770.4 1904.29    6813 1908.47  6896.8 1915.89
#Mann= 13 ,-1 , 0
  3457.5      .1       0    3743     .16       0  3805.8      .1       0
    4080     .05       0  4150.5      .1       0  5004.5     .07       0
  5010.5      .1       0  5063.4     .16       0  5122.5      .1       0
  5180.7     .16       0  5356.9      .1       0  6563.3     .16       0
    6813      .1       0
Bank Sta=4778.8,5085.7
XS Rating Curve= 0 ,0
Exp/Cntr=0.3,0.1