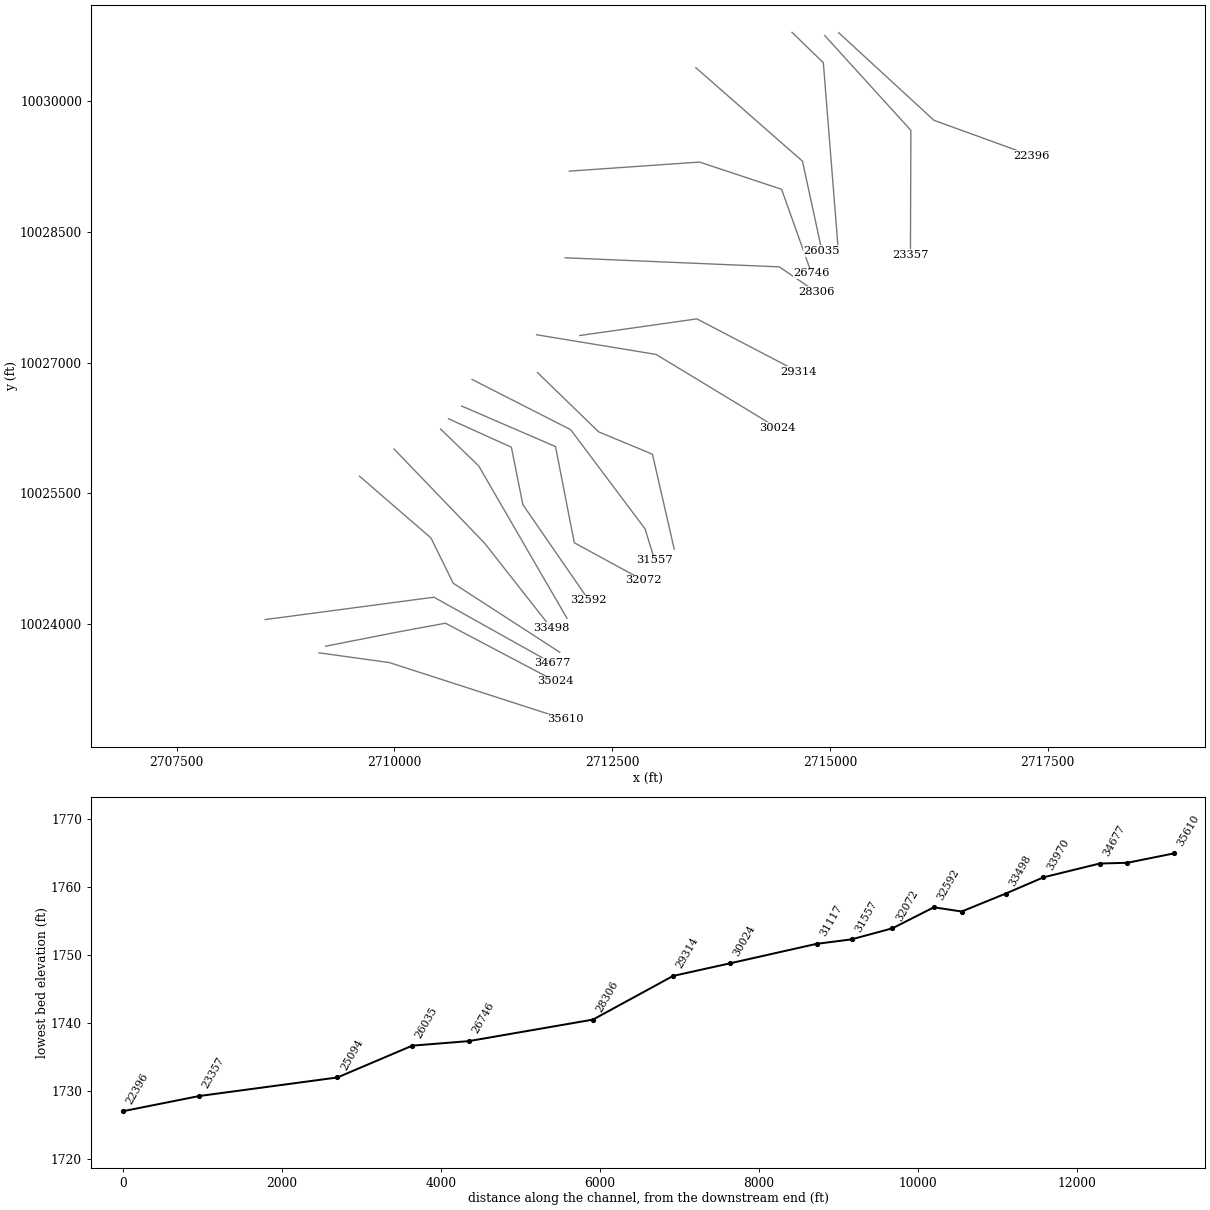
HEC-RAS study WOLF CREEK.prj: WOLF CREEK Base Level Engineering

--- WOLF CREEK.g01 (geometry) --- (continued)

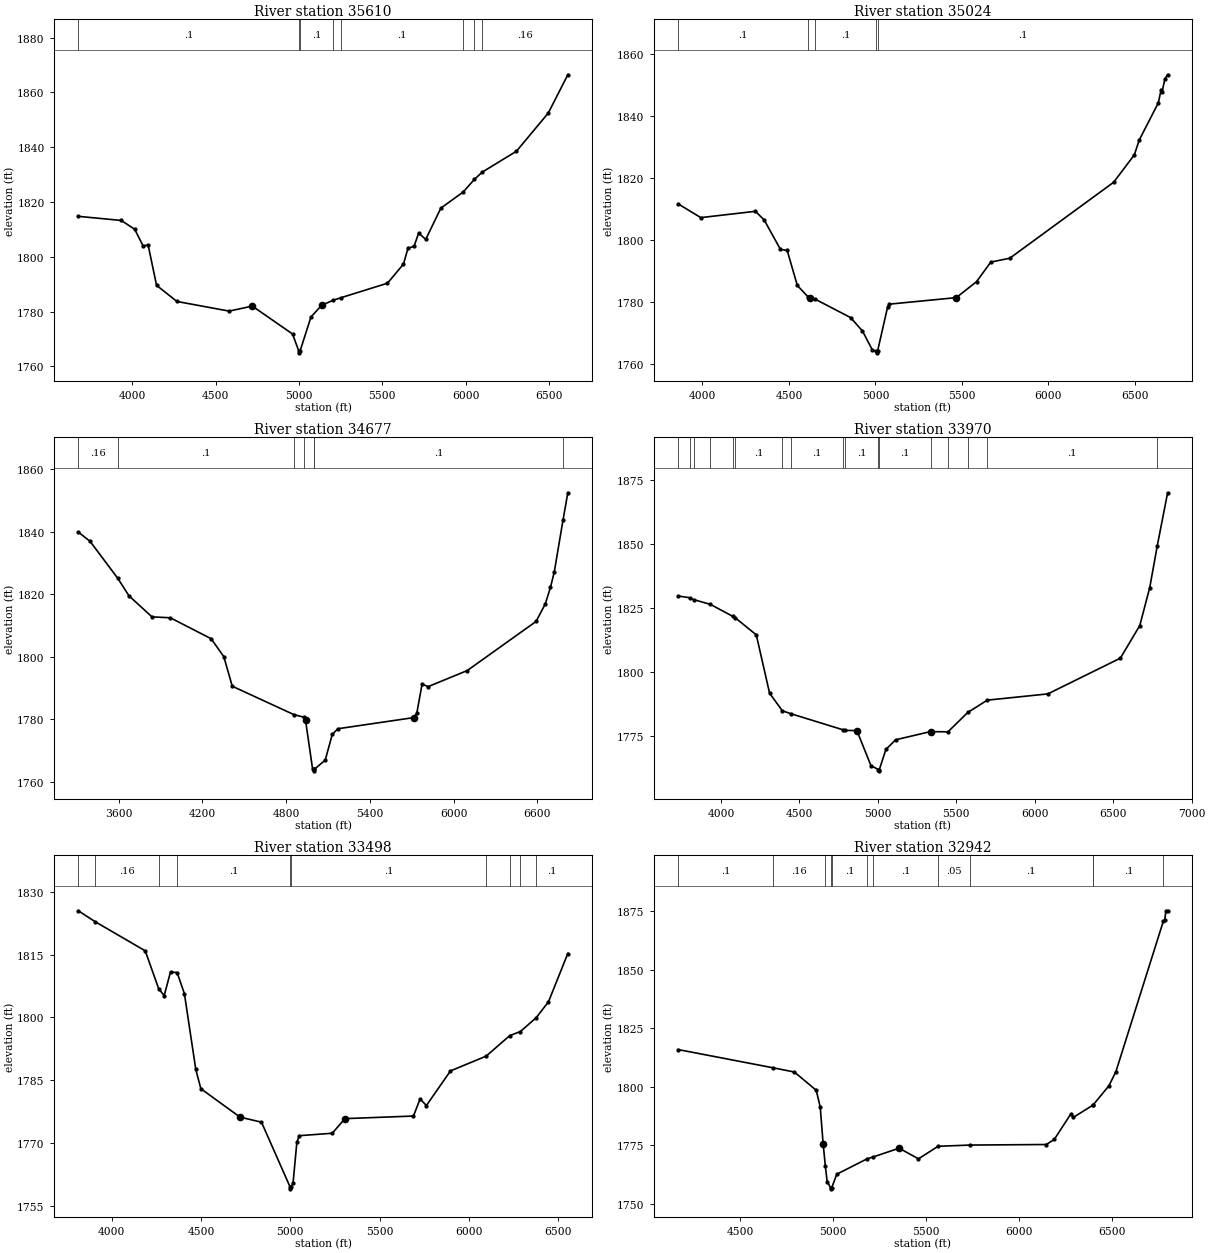
Type RM Length L Ch R = 1 ,35610   ,586,586,586
BEGIN DESCRIPTION:
WOLF CREEK 50.0
END DESCRIPTION:
XS GIS Cut Line= 3
      2709133.56     10023668.96      2709939.11     10023557.85
      2711959.92     10022905.08
#Sta/Elev= 30
  3676.8 1814.77  3934.1 1813.27  4014.9 1810.06  4065.3 1803.99  4095.6 1804.31
  4146.1 1789.59  4268.1 1783.69  4581.7 1780.17  4720.5    1782  4962.2 1771.81
  5000.3 1765.43    5003 1764.93  5006.3 1765.43  5072.6 1778.02  5136.7  1782.3
  5206.5 1784.14    5250 1785.01  5531.5 1790.35  5627.6 1797.33  5654.4 1803.09
  5691.7 1803.89  5718.5 1808.68    5761 1806.34  5851.8 1817.76  5986.1 1823.67
  6052.6 1828.24  6100.3 1830.92  6305.5 1838.54  6496.5  1852.5  6613.6 1866.46
#Mann= 8 ,-1 , 0
  3676.8      .1       0  5000.3     .07       0  5006.3      .1       0
  5206.5     .05       0    5250      .1       0  5986.1     .16       0
  6052.6      .1       0  6100.3     .16       0
Bank Sta=4720.5,5136.7
XS Rating Curve= 0 ,0
Exp/Cntr=0.3,0.1

Type RM Length L Ch R = 1 ,35024   ,347,347,347
BEGIN DESCRIPTION:
WOLF CREEK 49.0
END DESCRIPTION:
XS GIS Cut Line= 4
      2709209.99     10023745.36      2710022.45     10023905.07
      2710584.95     10024009.24      2711848.83     10023342.57
#Sta/Elev= 30
  3859.8 1811.69  3990.7 1807.24  4306.7 1809.28  4357.6 1806.44    4451 1796.98
  4490.1 1796.64  4548.7 1785.31  4611.3 1781.61  4622.6  1781.4  4653.1 1780.85
  4856.6 1774.94  4925.2 1770.61  4983.1 1764.39  5006.2 1764.05  5008.9 1763.55
  5012.2 1764.05  5070.2 1778.29  5080.4 1779.28  5467.4 1781.39  5584.3 1786.54
  5666.7 1792.86  5776.8 1794.13  6376.5 1818.64  6496.2 1827.49    6525 1832.33
  6635.1 1844.31  6651.5 1848.63  6657.1 1847.97  6673.5 1852.14  6688.8 1853.39
#Mann= 5 ,-1 , 0
  3859.8      .1       0  4611.3     .16       0  4653.1      .1       0
  5006.2     .07       0  5012.2      .1       0
Bank Sta=4622.6,5467.4
XS Rating Curve= 0 ,0
Exp/Cntr=0.3,0.1

Type RM Length L Ch R = 1 ,34677   ,707,707,707
BEGIN DESCRIPTION:
WOLF CREEK 48.0
END DESCRIPTION:
XS GIS Cut Line= 3
       2708515.5      10024050.9        2710453.     10024307.85
      2711807.14     10023550.92
#Sta/Elev= 30
  3311.5 1839.83  3395.2  1836.9    3594 1825.05    3674 1819.46    3839 1812.71
  3970.2 1812.42  4262.7 1805.72  4353.5 1799.98    4414 1790.52  4854.9 1781.44
  4930.7 1780.55  4938.6 1779.68    4989 1764.13  4996.1 1763.94  4998.9 1763.44
  5002.1 1763.94  5079.8 1766.86  5130.2 1775.09  5170.6 1776.91  5714.2 1780.48
  5735.9 1781.94  5773.5 1791.17    5817 1790.39  6097.1 1795.53  6589.7 1811.24
  6655.3 1816.78  6692.8 1822.11  6720.4 1827.09  6782.8 1843.65  6817.3 1852.42
#Mann= 7 ,-1 , 0
  3311.5     .16       0    3594      .1       0  4854.9     .16       0
  4930.7      .1       0  4996.1     .07       0  5002.1      .1       0
  6782.8     .16       0
Bank Sta=4938.6,5714.2
XS Rating Curve= 0 ,0
Exp/Cntr=0.3,0.1

Type RM Length L Ch R = 1 ,33970   ,472,472,472
BEGIN DESCRIPTION:
WOLF CREEK 47.0
END DESCRIPTION:
XS GIS Cut Line= 4
      2709598.87     10025696.71      2710418.28      10024988.4
      2710675.22     10024467.57      2711897.45      10023675.9
#Sta/Elev= 30
  3726.6 1829.68  3799.2 1828.99  3825.3 1828.26  3931.7 1826.41  4074.9 1821.73
  4089.5 1821.22  4224.9 1814.48  4309.4 1791.74  4390.5 1784.87    4447 1783.68
  4777.6 1777.43  4787.1 1777.19  4865.9 1777.14  4955.7 1763.44  5003.2 1761.91
  5005.9 1761.41  5009.2 1761.91  5051.1 1769.78  5112.8 1773.53  5337.4 1776.76
  5338.6 1776.71  5446.6 1776.64  5572.8  1784.2    5697    1789  6083.4 1791.45
  6545.6  1805.4  6669.2 1818.12  6732.9 1832.98    6781 1849.36  6846.7 1869.96
#Mann= 17 ,-1 , 0
  3726.6     .05       0  3799.2      .1       0  3825.3     .16       0
  3931.7      .1       0  4074.9     .16       0  4089.5      .1       0
  4390.5     .05       0    4447      .1       0  4777.6     .05       0
  4787.1      .1       0  5003.2     .07       0  5009.2      .1       0
  5338.6     .05       0  5446.6      .1       0  5572.8     .05       0
    5697      .1       0    6781     .16       0
Bank Sta=4865.9,5337.4
XS Rating Curve= 0 ,0
Exp/Cntr=0.3,0.1

Type RM Length L Ch R = 1 ,33498   ,556,556,556
BEGIN DESCRIPTION:
WOLF CREEK 46.0
END DESCRIPTION:
XS GIS Cut Line= 3
      2709994.64     10026009.26      2711036.34      10024925.9
      2711800.25     10023953.64
#Sta/Elev= 30
  3813.3 1825.48  3907.5 1822.87  4187.7 1815.91  4263.1 1806.84  4293.7  1805.2
  4329.2 1810.86  4366.2 1810.72  4406.9 1805.68  4470.7 1787.55    4499 1782.96
  4718.2 1776.17  4838.3 1774.96  4997.9 1759.53  5000.6 1759.03  5003.9 1759.53
    5015 1760.41  5036.4 1770.21  5050.6 1771.74  5234.5 1772.31  5305.3 1775.81
    5689 1776.43  5725.9 1780.51  5761.3 1778.94    5896 1787.21  6095.6 1790.74
  6227.6 1795.64  6287.6 1796.63  6375.6 1799.92  6444.5 1803.73  6552.7 1815.27
#Mann= 10 ,-1 , 0
  3813.3      .1       0  3907.5     .16       0  4263.1     .05       0
  4366.2      .1       0  4997.9     .07       0  5003.9      .1       0
  6095.6     .05       0  6227.6      .1       0  6287.6     .05       0
  6375.6      .1       0
Bank Sta=4718.2,5305.3
XS Rating Curve= 0 ,0
Exp/Cntr=0.3,0.1

Type RM Length L Ch R = 1 ,32942   ,350,350,350
BEGIN DESCRIPTION:
WOLF CREEK 45.0
END DESCRIPTION:
XS GIS Cut Line= 3
      2710529.41     10026238.38      2710966.89     10025814.79
      2711980.76     10024064.83
#Sta/Elev= 30
  4166.9 1815.88  4675.9 1808.11  4791.7 1806.29  4909.3 1798.49  4930.8 1791.32
  4946.6 1775.51  4958.3 1766.12  4968.1 1759.44  4986.7 1756.88  4989.4 1756.38
  4992.7 1756.88  5019.8 1762.63  5182.5  1769.2  5214.6 1769.98  5354.9 1773.74
  5458.9  1769.2  5564.5 1774.56  5735.3 1775.08    6146 1775.32  6189.1  1777.5
  6279.4 1788.54  6291.1 1786.89  6395.2 1792.07  6399.8 1792.41  6483.1 1800.44
  6520.4 1806.48  6775.1 1870.66    6783 1871.29  6788.8 1874.95  6798.3 1875.17
#Mann= 12 ,-1 , 0
  4166.9      .1       0  4675.9     .16       0  4958.3      .1       0
  4986.7     .07       0  4992.7      .1       0  5182.5     .16       0
  5214.6      .1       0  5564.5     .05       0  5735.3      .1       0
  6395.2     .16       0  6399.8      .1       0  6775.1     .16       0
Bank Sta=4946.6,5354.9
XS Rating Curve= 0 ,0
Exp/Cntr=0.3,0.1

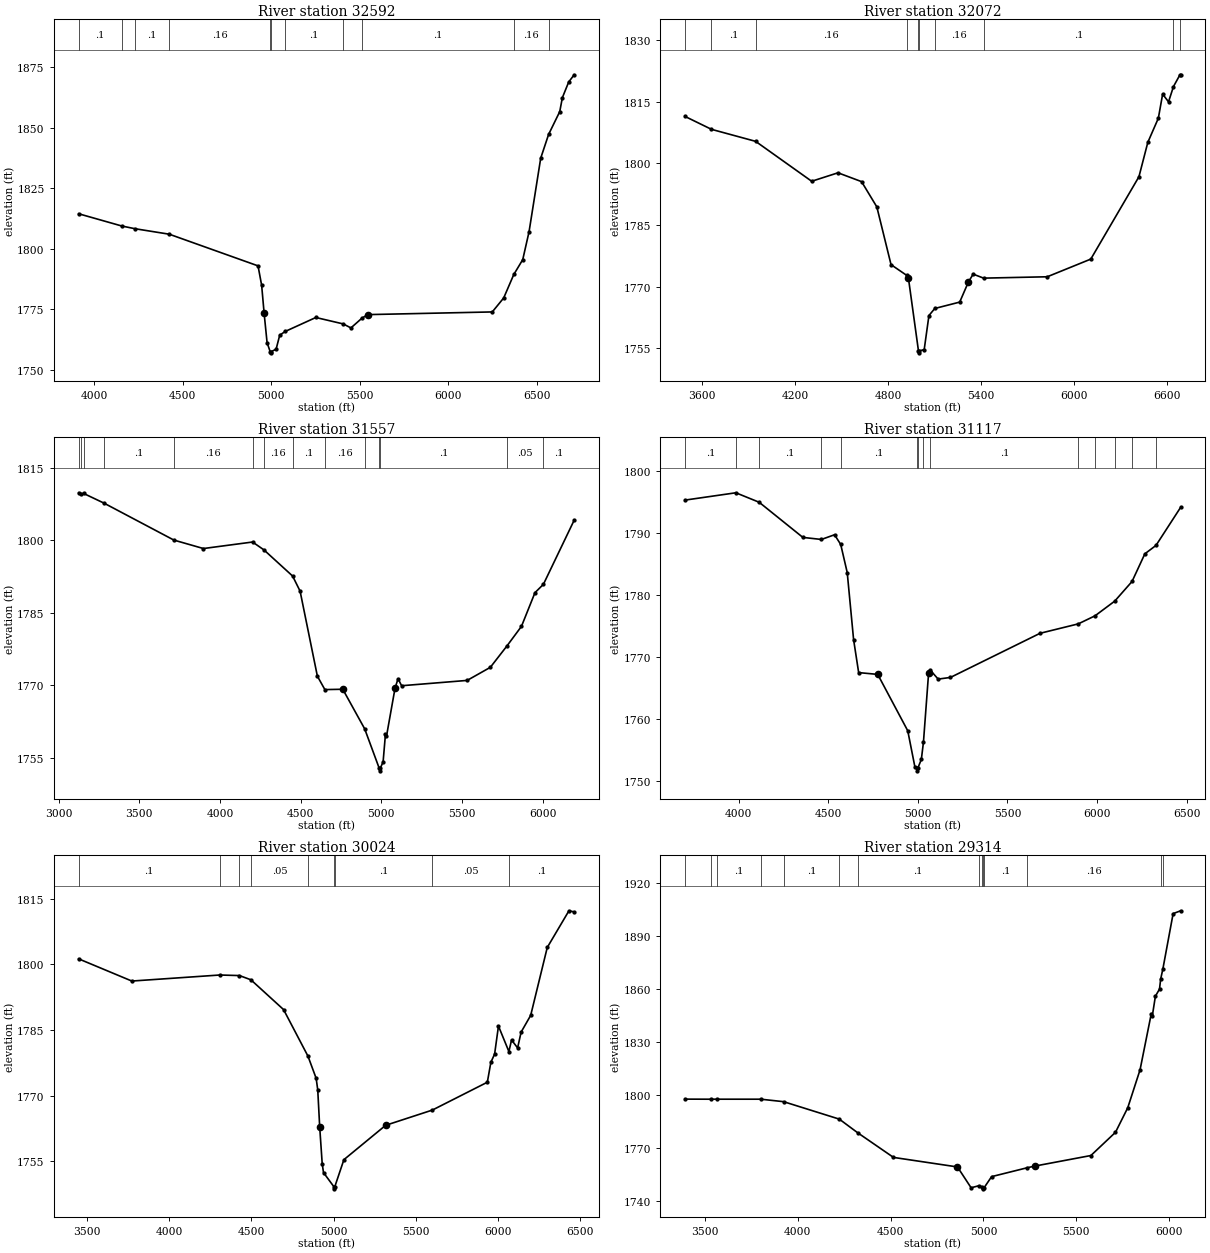
Type RM Length L Ch R = 1 ,32592   ,520,520,520
BEGIN DESCRIPTION:
WOLF CREEK 44.0
END DESCRIPTION:
XS GIS Cut Line= 4
       2710619.7     10026356.44      2711341.89     10026030.07
      2711473.84     10025370.35      2712230.79     10024273.12
#Sta/Elev= 30
  3912.1 1814.49  4156.3 1809.42    4230 1808.31  4423.9 1806.04  4925.2 1792.95
  4945.6 1784.92 4959.66 1773.29  4976.2 1761.25  4993.6  1757.5  4996.4    1757
  4999.6  1757.5  5027.2  1758.5  5047.6 1764.28  5078.3 1765.83  5251.6 1771.61
  5406.4 1768.95  5449.7  1767.3  5510.3 1771.22  5543.4  1772.8    6248 1773.91
  6312.5  1779.7  6369.5 1789.39    6420 1795.53  6455.8 1807.13  6521.4 1837.45
  6565.9 1847.26  6628.9 1856.71  6643.8 1862.49  6679.6 1868.97  6710.4 1871.94
#Mann= 11 ,-1 , 0
  3912.1      .1       0  4156.3     .16       0    4230      .1       0
  4423.9     .16       0  4993.6     .07       0  4999.6     .16       0
  5078.3      .1       0  5406.4     .16       0  5510.3      .1       0
  6369.5     .16       0  6565.9      .1       0
Bank Sta=4959.66,5543.4
XS Rating Curve= 0 ,0
Exp/Cntr=0.3,0.1

Type RM Length L Ch R = 1 ,32072   ,515,515,515
BEGIN DESCRIPTION:
WOLF CREEK 43.0
END DESCRIPTION:
XS GIS Cut Line= 5
      2710772.47     10026502.28      2711848.84     10026037.01
      2712064.11     10024932.85       2712765.5      10024550.9
      2712854.59     10024502.93
#Sta/Elev= 30
  3489.1  1811.4  3659.3 1808.27  3944.1 1805.35  4305.9 1795.64  4475.8  1797.7
  4627.7 1795.55  4726.2 1789.41  4817.9 1775.36  4919.8 1772.73    4930 1772.12
  4994.8 1754.41  4997.6 1753.91  5000.8 1754.41  5031.8 1754.68  5062.4 1762.98
  5100.2  1764.7  5260.9 1766.25  5317.6 1771.18  5347.7 1773.05  5415.3 1772.08
  5825.8 1772.41  6106.8 1776.71  6417.4 1796.74  6474.8 1805.11  6542.7 1810.98
  6570.3 1816.83  6608.4 1814.96  6640.3 1818.68  6680.2 1821.41  6686.5 1821.54
#Mann= 10 ,-1 , 0
  3489.1     .16       0  3659.3      .1       0  3944.1     .16       0
  4919.8      .1       0  4994.8     .07       0  5000.8      .1       0
  5100.2     .16       0  5415.3      .1       0  6640.3     .05       0
  6680.2      .1       0
Bank Sta=4930,5317.6
XS Rating Curve= 0 ,0
Exp/Cntr=0.3,0.1

Type RM Length L Ch R = 1 ,31557   ,440,440,440
BEGIN DESCRIPTION:
WOLF CREEK 42.0
END DESCRIPTION:
XS GIS Cut Line= 4
      2710890.48     10026807.86      2712022.45     10026231.46
      2712876.61     10025092.57      2712987.72     10024731.46
#Sta/Elev= 30
  3124.1 1809.88  3140.4 1809.65  3155.1 1809.74  3281.1 1807.74  3714.6 1800.08
  3897.6 1798.33  4202.3 1799.68  4272.7 1798.05  4450.5 1792.63  4496.9  1789.5
    4604 1771.89  4650.4 1769.11  4761.5 1769.18  4897.2 1760.98  4987.7 1752.78
  4990.4 1752.28  4993.7 1752.78  5011.5 1754.16  5026.1 1759.92  5032.3 1759.43
  5085.3 1769.38    5104 1771.37  5126.1 1769.91  5532.3 1771.01  5676.1 1773.72
  5778.2 1778.11  5869.1 1782.21  5952.8 1789.19    6005 1790.91  6195.8  1804.2
#Mann= 14 ,-1 , 0
  3124.1      .1       0  3140.4     .05       0  3155.1     .16       0
  3281.1      .1       0  3714.6     .16       0  4202.3      .1       0
  4272.7     .16       0  4450.5      .1       0  4650.4     .16       0
  4897.2      .1       0  4987.7     .07       0  4993.7      .1       0
  5778.2     .05       0    6005      .1       0
Bank Sta=4761.5,5085.3
XS Rating Curve= 0 ,0
Exp/Cntr=0.3,0.1

Type RM Length L Ch R = 1 ,31117   ,1093,1093,1093
BEGIN DESCRIPTION:
WOLF CREEK 41.0
END DESCRIPTION:
XS GIS Cut Line= 4
      2711642.23     10026886.85      2712343.63     10026206.28
      2712961.68     10025949.34      2713211.68     10024859.08
#Sta/Elev= 30
    3701  1795.3  3984.2 1796.48  4114.4 1794.95  4358.2 1789.28  4461.6 1788.95
    4535 1789.71  4569.4 1788.14  4605.7 1783.61  4641.2  1772.8  4669.5 1767.47
  4775.9 1767.18  4943.5 1758.08    4983  1752.3  4994.6 1752.12  4997.4 1751.62
  5000.6 1752.12  5019.3 1753.46  5031.1 1756.26  5059.9 1767.45    5070 1767.84
  5113.1 1766.42  5181.7 1766.69  5681.7 1773.81    5895 1775.33  5988.5 1776.63
  6098.4    1779    6195 1782.17  6266.5 1786.63  6328.7 1787.99  6466.2 1794.13
#Mann= 14 ,-1 , 0
    3701      .1       0  3984.2     .16       0  4114.4      .1       0
  4461.6     .16       0  4569.4      .1       0  4994.6     .07       0
  5000.6      .1       0  5031.1     .16       0    5070      .1       0
    5895     .05       0  5988.5      .1       0  6098.4     .05       0
    6195      .1       0  6328.7     .05       0
Bank Sta=4775.9,5059.9
XS Rating Curve= 0 ,0
Exp/Cntr=0.3,0.1

Type RM Length L Ch R = 1 ,30024   ,710,710,710
BEGIN DESCRIPTION:
WOLF CREEK 39.0
END DESCRIPTION:
XS GIS Cut Line= 3
      2711631.78     10027320.87      2713003.35     10027095.17
      2714392.23     10026253.16
#Sta/Elev= 30
  3449.1 1801.27  3772.7  1796.2  4307.9 1797.58  4427.5 1797.45  4496.8 1796.49
  4695.7 1789.68    4844 1779.05  4893.9 1773.98  4903.6 1771.33  4915.3 1762.93
  4930.7 1754.46  4938.6 1752.45  5001.4 1749.24  5004.2 1748.74  5007.4 1749.24
  5062.6  1755.4  5316.6 1763.25  5600.6 1766.73  5935.1 1773.09  5956.5 1777.63
  5979.4 1779.53  6002.8 1785.92  6066.2  1780.1  6082.4 1782.74  6119.3 1780.93
  6140.6 1784.54  6198.8 1788.36  6299.6 1803.87  6431.5 1812.25  6463.3 1811.99
#Mann= 9 ,-1 , 0
  3449.1      .1       0  4307.9     .05       0  4427.5      .1       0
  4496.8     .05       0    4844      .1       0  5001.4     .07       0
  5007.4      .1       0  5600.6     .05       0  6066.2      .1       0
Bank Sta=4915.3,5316.6
XS Rating Curve= 0 ,0
Exp/Cntr=0.3,0.1

Type RM Length L Ch R = 1 ,29314   ,1008,1008,1008
BEGIN DESCRIPTION:
WOLF CREEK 38.0
END DESCRIPTION:
XS GIS Cut Line= 3
      2712126.61     10027312.19       2713472.1     10027503.16
      2714634.39     10026895.99
#Sta/Elev= 30
  3392.4 1797.63  3533.7 1797.58  3563.8 1797.59  3800.1 1797.59  3923.1 1796.19
  4223.4 1786.32  4322.4 1778.61  4515.4 1764.67  4860.1 1759.28  4933.6  1747.5
  4975.4 1748.66    4990 1748.13  4996.8  1747.4  4999.6  1746.9  5002.8  1747.4
    5044  1753.8  5236.2 1758.83  5275.6 1759.74  5579.1 1765.74  5711.6 1778.87
  5777.8 1792.77    5844 1814.21  5904.7 1846.04  5910.3 1844.83  5926.7 1855.83
  5948.8 1859.84  5955.2 1865.58  5966.6 1871.02  6022.2 1902.53  6062.7 1904.13
#Mann= 14 ,-1 , 0
  3392.4      .1       0  3533.7     .16       0  3563.8      .1       0
  3800.1     .16       0  3923.1      .1       0  4223.4     .05       0
  4322.4      .1       0  4975.4     .16       0    4990      .1       0
  4996.8     .07       0  5002.8      .1       0  5236.2     .16       0
  5955.2      .1       0  5966.6     .16       0
Bank Sta=4860.1,5275.6
XS Rating Curve= 0 ,0
Exp/Cntr=0.3,0.1

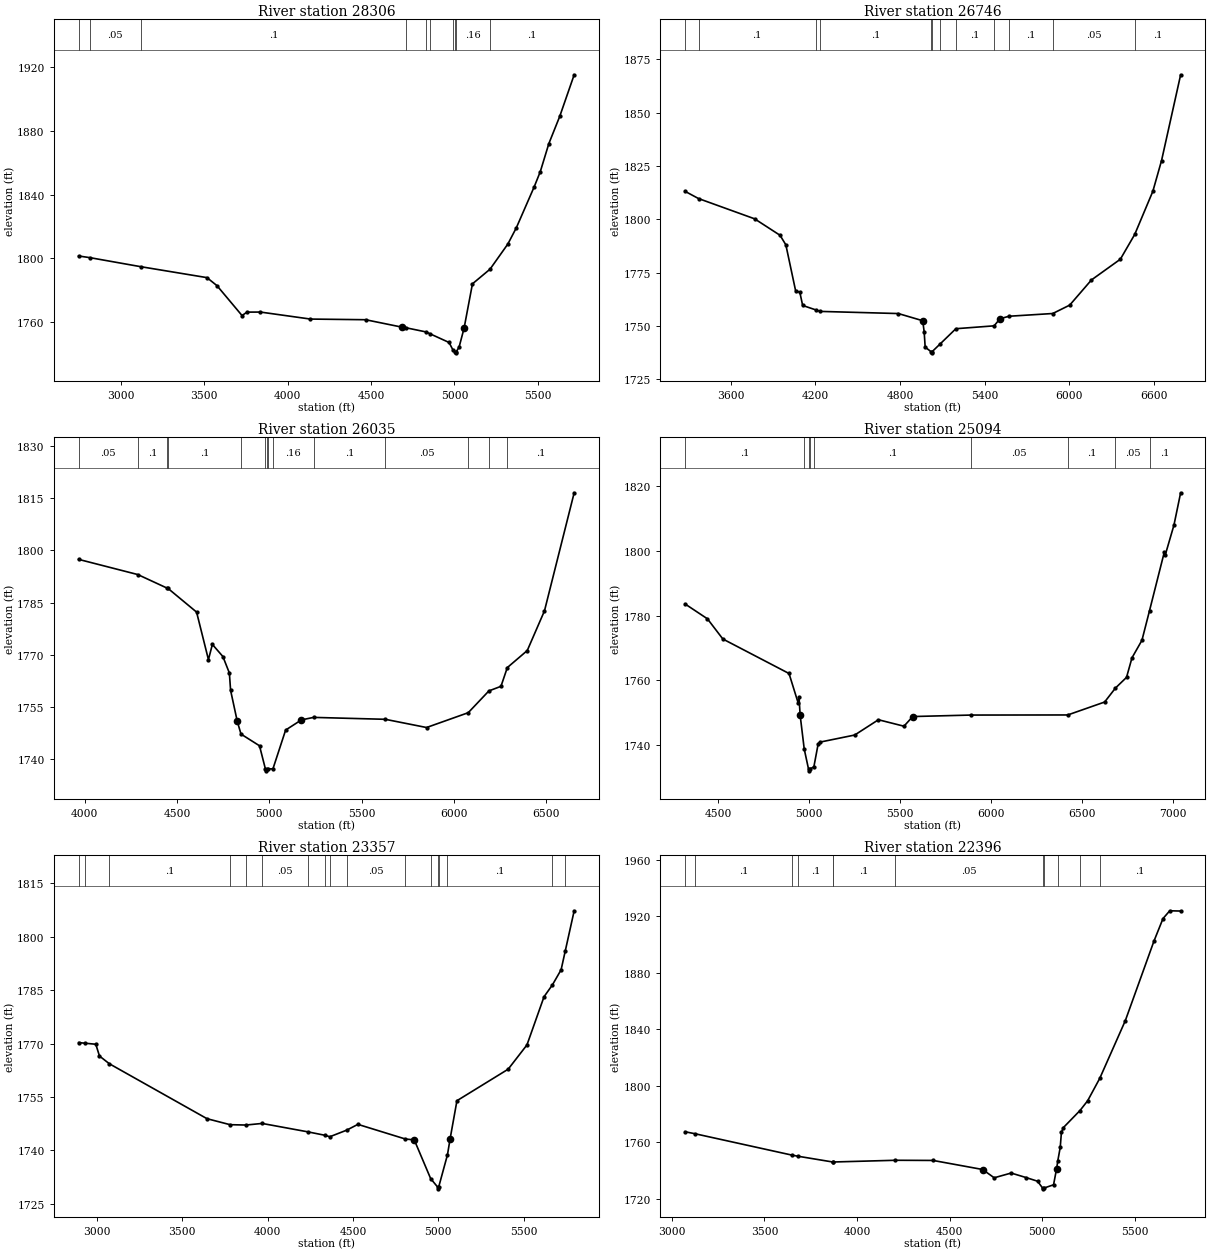
Type RM Length L Ch R = 1 ,28306   ,1560,1560,1560
BEGIN DESCRIPTION:
WOLF CREEK 37.0
END DESCRIPTION:
XS GIS Cut Line= 3
      2711959.91     10028204.55      2714418.28     10028100.38
      2714840.14     10027813.93
#Sta/Elev= 30
  2746.9 1801.39  2814.7 1800.34  3118.7 1794.67  3516.1 1787.78  3576.2 1782.73
  3726.3 1763.94  3756.4 1766.09  3836.4 1766.12  4136.7 1761.71    4467  1761.3
  4687.2 1756.58  4711.1  1756.2  4829.5 1753.62  4855.2 1752.36  4967.4 1746.99
  4991.2 1742.19  5003.4 1740.97  5006.1 1740.47  5009.4 1740.97  5027.5 1744.05
  5057.5    1756  5107.6 1783.87    5213 1793.09  5319.9 1808.92  5370.8 1819.15
  5478.6 1845.09  5514.5  1854.5  5565.4 1872.02  5630.8 1889.19  5717.4 1915.37
#Mann= 10 ,-1 , 0
  2746.9      .1       0  2814.7     .05       0  3118.7      .1       0
  4711.1     .05       0  4829.5      .1       0  4855.2     .05       0
  4991.2     .16       0  5003.4     .07       0  5009.4     .16       0
    5213      .1       0
Bank Sta=4687.2,5057.5
XS Rating Curve= 0 ,0
Exp/Cntr=0.3,0.1

Type RM Length L Ch R = 1 ,26746   ,711,711,711
BEGIN DESCRIPTION:
WOLF CREEK 36.0
END DESCRIPTION:
XS GIS Cut Line= 4
      2712006.86     10029199.34      2713501.61     10029303.51
      2714444.32     10028991.01      2714787.85     10028028.09
#Sta/Elev= 30
  3275.8 1813.07  3371.1 1809.69  3768.6 1800.19    3949 1792.46  3990.2 1787.99
  4059.3 1766.49  4089.4 1765.72  4109.4 1759.55  4202.8 1757.45  4233.6 1756.75
    4788 1755.74  4960.5 1752.38    4971 1747.25  4978.2 1739.98  5020.7 1737.81
  5023.5 1737.31  5026.7 1737.81  5082.9 1741.39  5195.9 1748.63  5467.3 1749.98
  5508.3 1753.29  5572.8 1754.48  5882.9 1755.76  6003.1  1759.7  6157.3 1771.51
  6362.2 1781.23  6464.2 1792.87  6592.6 1813.09  6654.3  1827.5  6789.7 1867.76
#Mann= 12 ,-1 , 0
  3275.8     .05       0  3371.1      .1       0  4202.8     .05       0
  4233.6      .1       0  5020.7     .07       0  5026.7      .1       0
  5082.9     .16       0  5195.9      .1       0  5467.3     .05       0
  5572.8      .1       0  5882.9     .05       0  6464.2      .1       0
Bank Sta=4960.5,5508.3
XS Rating Curve= 0 ,0
Exp/Cntr=0.3,0.1

Type RM Length L Ch R = 1 ,26035   ,941,941,941
BEGIN DESCRIPTION:
WOLF CREEK 35.0
END DESCRIPTION:
XS GIS Cut Line= 3
      2713459.94     10030386.84      2714683.91     10029313.92
      2714907.86     10028282.71
#Sta/Elev= 30
    3968 1797.41  4288.2 1793.05  4447.5 1789.14  4451.3 1789.09  4606.6 1782.26
  4670.8  1768.6  4692.1 1772.97    4749 1769.49  4784.1 1764.76  4790.8 1759.76
  4826.8 1750.88  4847.1  1747.2  4947.3 1743.84  4979.4 1737.14  4982.2 1736.64
  4985.4 1737.14  4993.2 1737.19    5020 1737.21  5088.7 1748.36  5174.1 1751.28
  5240.1    1752  5628.2 1751.45  5851.7 1749.09  6077.4 1753.35  6189.2 1759.61
  6254.6 1760.93  6288.9 1766.31  6396.9 1771.21  6490.1 1782.61  6650.9 1816.55
#Mann= 14 ,-1 , 0
    3968     .05       0  4288.2      .1       0  4447.5     .05       0
  4451.3      .1       0  4847.1     .16       0  4979.4     .07       0
  4985.4     .16       0  4993.2      .1       0    5020     .16       0
  5240.1      .1       0  5628.2     .05       0  6077.4      .1       0
  6189.2     .05       0  6288.9      .1       0
Bank Sta=4826.8,5174.1
XS Rating Curve= 0 ,0
Exp/Cntr=0.3,0.1

Type RM Length L Ch R = 1 ,25094   ,1737,1737,1737
BEGIN DESCRIPTION:
WOLF CREEK 34.0
END DESCRIPTION:
XS GIS Cut Line= 3
      2714564.14     10030793.07      2714923.49     10030444.13
      2715100.44     10028227.07
#Sta/Elev= 30
  4317.9 1783.59  4440.7    1779  4525.6 1772.75  4889.4 1762.08  4939.4 1753.01
  4944.4 1754.73 4950.57 1749.16    4973 1738.71  4996.8 1732.46  4999.5 1731.96
  5002.8 1732.46  5026.1 1733.22  5049.9 1740.38    5060 1740.85  5250.6 1743.04
    5381 1747.77  5521.4 1745.77  5569.6 1748.76  5890.1 1749.22    6422 1749.25
  6624.9 1753.25  6684.5 1757.58  6745.3 1760.88  6775.4 1766.94  6830.1 1772.35
  6871.9 1781.55  6953.1 1799.64  6958.1 1798.71  7006.1 1807.99  7042.9    1818
#Mann= 9 ,-1 , 0
  4317.9      .1       0    4973     .05       0  4996.8    .035       0
  5002.8     .05       0  5026.1      .1       0  5890.1     .05       0
    6422      .1       0  6684.5     .05       0  6871.9      .1       0
Bank Sta=4950.57,5569.6
XS Rating Curve= 0 ,0
Exp/Cntr=0.3,0.1

Type RM Length L Ch R = 1 ,23357   ,961,961,961
BEGIN DESCRIPTION:
WOLF CREEK 33.0
END DESCRIPTION:
XS GIS Cut Line= 3
      2714939.11     10030756.63       2715928.7     10029668.09
      2715923.49     10028237.22
#Sta/Elev= 30
  2893.5 1770.29  2931.2 1770.11    2994 1769.82  3015.6 1766.51  3073.6 1764.34
  3645.4 1748.92  3780.4 1747.24  3873.1 1747.14  3968.1 1747.59  4236.9 1745.22
  4335.3 1744.27  4364.7 1743.86  4463.1  1745.7    4529 1747.33  4806.8 1743.22
    4859 1742.97  4955.1  1732.1    4996 1729.73  4998.7 1729.23    5002 1729.73
  5053.5 1738.79    5069 1743.29    5109 1753.97    5409 1762.82    5519 1769.63
    5619 1783.16  5668.3  1786.5    5719 1790.73  5743.5 1796.05  5795.5 1807.29
#Mann= 17 ,-1 , 0
  2893.5      .1       0  2931.2     .05       0  3073.6      .1       0
  3780.4     .05       0  3873.1      .1       0  3968.1     .05       0
  4236.9      .1       0  4335.3     .05       0  4364.7      .1       0
  4463.1     .05       0  4806.8      .1       0  4955.1     .16       0
    4996     .07       0    5002     .16       0  5053.5      .1       0
  5668.3     .05       0  5743.5      .1       0
Bank Sta=4859,5069
XS Rating Curve= 0 ,0
Exp/Cntr=0.3,0.1

Type RM Length L Ch R = 1 ,22396   ,652,652,652
BEGIN DESCRIPTION:
WOLF CREEK 31.0
END DESCRIPTION:
XS GIS Cut Line= 3
      2715100.59     10030787.87      2716194.32     10029782.67
      2717313.74     10029376.56
#Sta/Elev= 30
  3071.3 1767.42  3125.1 1766.02  3646.4 1750.94  3683.5 1750.03  3868.1 1746.02
  3869.1    1746  4207.6 1747.23  4410.5 1747.11  4678.2 1740.69  4740.5 1734.82
  4832.3 1738.18  4912.2 1735.01  4974.8 1732.39  5002.4 1727.49  5005.2 1726.99
  5008.4 1727.49  5061.2 1729.85 5077.84  1741.3  5084.4 1747.01  5097.3 1756.36
  5103.7 1766.98  5114.4 1770.39  5203.8 1782.44    5245 1789.32  5310.4 1805.17
  5448.7  1846.1  5603.7 1902.58  5652.4 1918.49  5688.8 1923.99  5747.6  1923.8
#Mann= 12 ,-1 , 0
  3071.3     .05       0  3125.1      .1       0  3646.4     .05       0
  3683.5      .1       0  3868.1     .05       0  3869.1      .1       0
  4207.6     .05       0  5002.4    .035       0  5008.4     .05       0
  5084.4     .16       0  5203.8     .05       0  5310.4      .1       0
Bank Sta=4678.2,5077.84
XS Rating Curve= 0 ,0
Exp/Cntr=0.3,0.1