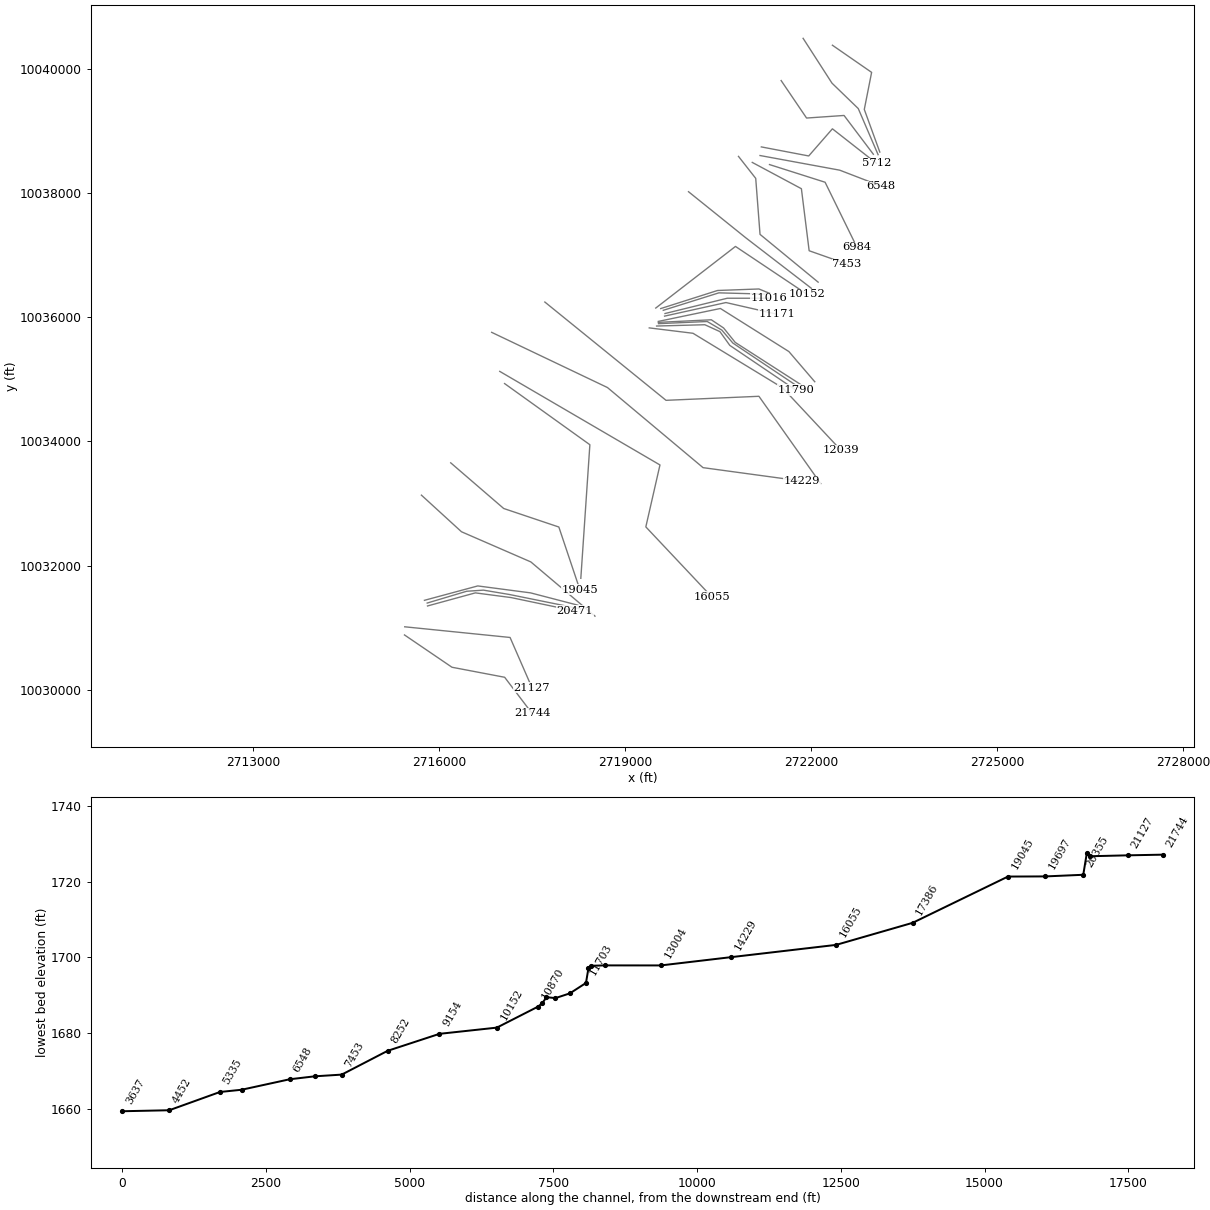
HEC-RAS study WOLF CREEK.prj: WOLF CREEK Base Level Engineering

--- WOLF CREEK.g01 (geometry) --- (continued)

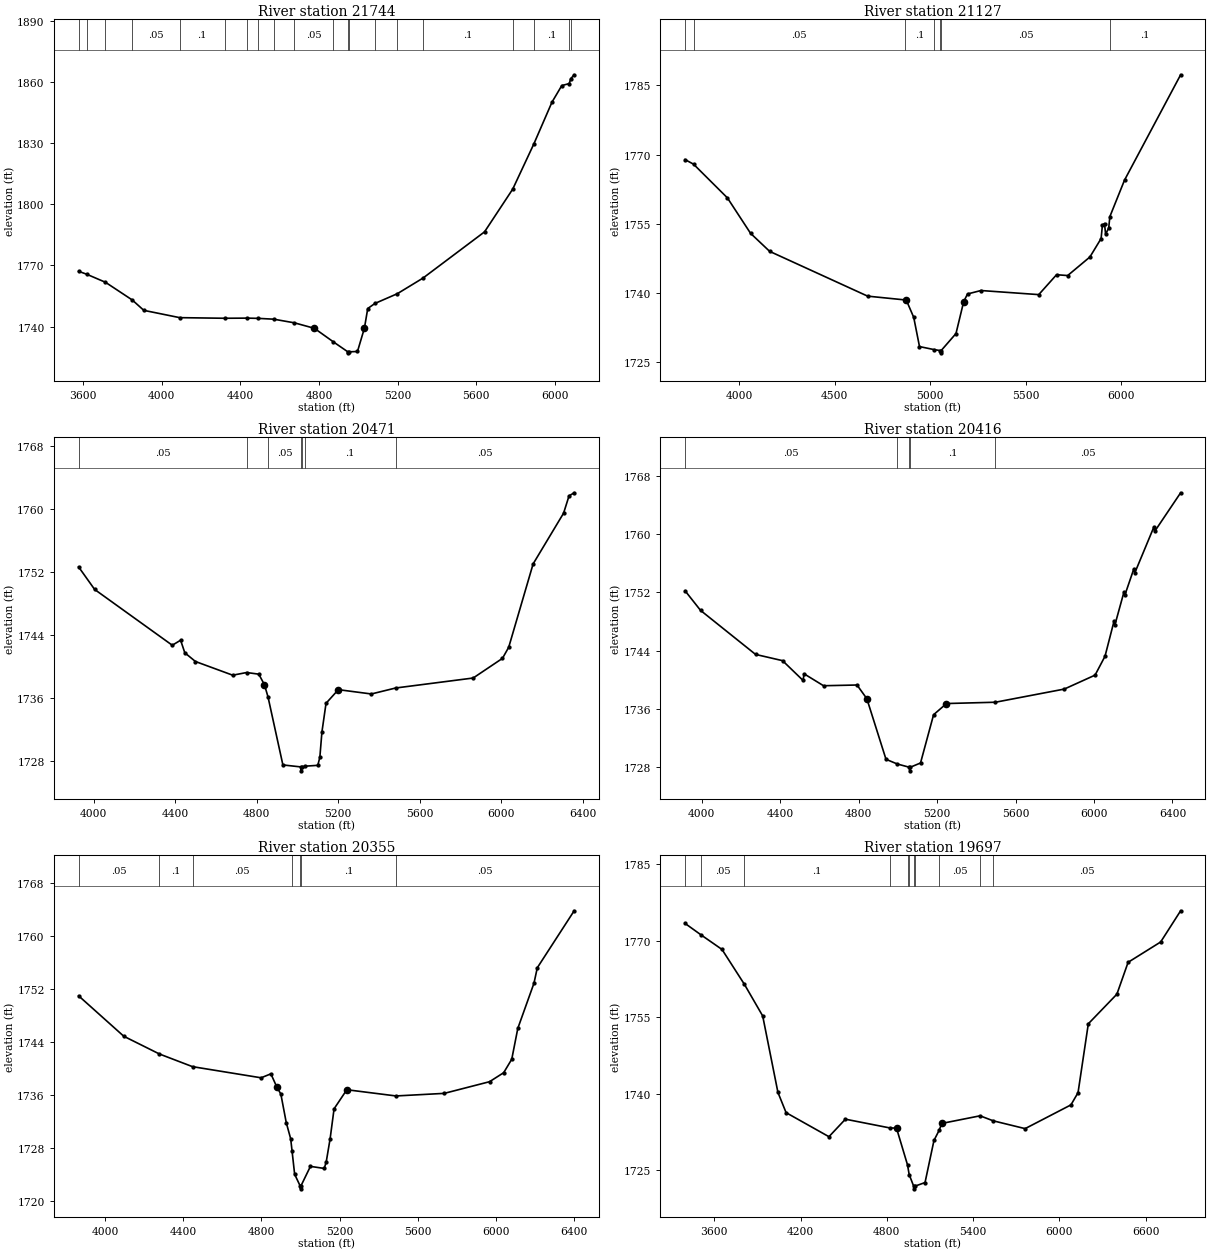
Type RM Length L Ch R = 1 ,21744   ,617,617,617
BEGIN DESCRIPTION:
WOLF CREEK 30.0
END DESCRIPTION:
XS GIS Cut Line= 4
       2715444.3     10030881.65      2716209.95      10030360.8
      2717058.91     10030199.34      2717500.59     10029617.35
#Sta/Elev= 30
  3576.9 1767.13  3617.8 1765.69  3713.4 1761.74  3849.6 1753.06  3908.5 1747.97
  4091.2 1744.39  4319.1 1744.09  4433.3 1744.16  4489.5 1744.04    4569 1743.64
  4674.5 1741.85  4776.2 1739.16  4872.8 1732.51  4946.3 1727.63    4949 1727.13
  4952.3 1727.63  4995.4 1727.79  5030.7 1739.26  5047.6 1748.87  5084.3 1751.36
  5198.2 1756.14  5328.7  1763.8  5641.7 1786.47  5785.2 1807.45  5892.4 1829.56
  5984.8 1850.09  6034.7 1858.23  6072.6  1859.2  6080.3 1861.59  6097.7 1863.52
#Mann= 20 ,-1 , 0
  3576.9      .1       0  3617.8     .05       0  3713.4      .1       0
  3849.6     .05       0  4091.2      .1       0  4319.1     .05       0
  4433.3      .1       0  4489.5     .05       0    4569      .1       0
  4674.5     .05       0  4872.8     .16       0  4946.3     .07       0
  4952.3     .16       0  5084.3      .1       0  5198.2     .05       0
  5328.7      .1       0  5785.2     .16       0  5892.4      .1       0
  6072.6     .16       0  6080.3     .05       0
Bank Sta=4776.2,5030.7
XS Rating Curve= 0 ,0
Exp/Cntr=0.3,0.1

Type RM Length L Ch R = 1 ,21127   ,656,656,656
BEGIN DESCRIPTION:
WOLF CREEK 29.0
END DESCRIPTION:
XS GIS Cut Line= 3
      2715448.35     10031012.79      2717146.23     10030840.92
      2717500.32      10030028.6
#Sta/Elev= 30
  3717.4  1768.9  3761.6 1767.91  3938.6  1760.6  4059.9  1752.9  4159.8 1748.98
  4672.4 1739.26  4867.9 1738.44  4873.4 1738.52  4913.6 1734.65  4943.8 1728.31
  5020.5 1727.65  5051.3 1727.45  5054.1 1726.95  5057.3 1727.45  5134.7 1731.14
  5174.9 1738.05    5195 1739.73  5265.4 1740.48  5567.7 1739.59  5660.9 1743.91
  5719.1 1743.73  5835.4 1747.76    5894 1751.77  5900.9  1754.7  5911.8 1755.02
  5917.4 1752.75  5933.6    1754  5939.9 1756.54  6016.5 1764.45  6310.1 1787.32
#Mann= 7 ,-1 , 0
  3717.4      .1       0  3761.6     .05       0  4867.9      .1       0
  5020.5     .05       0  5051.3     .07       0  5057.3     .05       0
  5939.9      .1       0
Bank Sta=4873.4,5174.9
XS Rating Curve= 0 ,0
Exp/Cntr=0.3,0.1

Type RM Length L Ch R = 1 ,20471   ,55,55,55
BEGIN DESCRIPTION:
WOLF CREEK 28.0
END DESCRIPTION:
XS GIS Cut Line= 4
      2715815.55     10031348.57      2716586.43     10031559.52
      2717161.95       10031484.      2718193.17     10031267.86
#Sta/Elev= 30
  3925.5 1752.65  4004.1 1749.79  4385.3 1742.69  4426.2 1743.33  4446.9 1741.73
  4499.2 1740.62    4682 1738.88  4750.7 1739.22  4810.1 1739.01  4837.7 1737.68
  4855.4 1736.12  4928.5 1727.46  5016.3 1727.21    5019 1726.71  5022.3 1727.21
  5036.2  1727.3  5099.9 1727.41    5110 1728.44  5120.1 1731.64  5140.3  1735.3
  5200.8 1737.04  5362.9 1736.49  5482.1 1737.25  5862.8 1738.52  6006.6 1741.02
  6037.3 1742.43  6157.2 1753.04  6306.9  1759.5  6333.6  1761.7  6358.8 1762.09
#Mann= 7 ,-1 , 0
  3925.5     .05       0  4750.7      .1       0  4855.4     .05       0
  5016.3     .04       0  5022.3     .05       0  5036.2      .1       0
  5482.1     .05       0
Bank Sta=4837.7,5200.8
XS Rating Curve= 0 ,0
Exp/Cntr=0.3,0.1

Type RM Length L Ch R = 1 ,20416   ,61,61,61
BEGIN DESCRIPTION:
Mapping XS ec6d24bd
END DESCRIPTION:
XS GIS Cut Line= 5
      2715810.39     10031395.46       2716445.8     10031585.56
      2716716.63     10031603.79       2717135.9     10031533.48
      2718279.14     10031301.71
#Sta/Elev= 30
  3915.5 1752.23  3994.2 1749.54  4274.7 1743.48  4412.3 1742.62  4516.8  1739.9
  4522.1 1740.81  4621.2 1739.17  4791.9 1739.27    4842 1737.39  4939.7 1729.05
  4997.4  1728.4    5058 1727.96  5060.8 1727.46    5064 1727.96  5115.7 1728.54
  5182.3 1735.18  5248.1 1736.72  5497.5  1736.9  5848.5 1738.71  6005.6 1740.63
  6056.3 1743.23  6101.9 1748.02    6107 1747.57  6152.6 1752.04  6157.7 1751.66
  6203.2 1755.25  6208.3 1754.71  6304.6 1760.96  6309.7 1760.42  6441.8 1765.72
#Mann= 5 ,-1 , 0
  3915.5     .05       0  4997.4      .1       0    5058     .07       0
    5064      .1       0  5497.5     .05       0
Bank Sta=4842,5248.1
XS Rating Curve= 0 ,0
Exp/Cntr=0.3,0.1

Type RM Length L Ch R = 1 ,20355   ,658,658,658
BEGIN DESCRIPTION:
Mapping XS 01f2ccab
END DESCRIPTION:
XS GIS Cut Line= 4
      2715766.12     10031439.73      2716625.49      10031671.5
      2717477.05     10031559.52      2718237.45     10031361.61
#Sta/Elev= 30
  3865.5 1750.94  4096.5 1744.84    4279 1742.16  4448.2 1740.25  4798.9 1738.57
  4848.9 1739.17  4879.6 1737.15  4899.8 1736.12  4927.6 1731.79  4950.2 1729.36
  4957.2 1727.52  4970.4 1724.01  4997.6 1722.31  5000.4 1721.81  5003.6 1722.31
  5051.1  1725.2  5121.7 1724.89  5131.8 1725.85  5151.9 1729.38  5172.1 1733.89
  5237.3 1736.77  5488.7 1735.83  5735.7 1736.22  5967.3 1737.98  6039.6 1739.34
  6080.9 1741.37  6111.9 1746.03  6194.6 1752.85  6211.6 1755.18  6400.2 1763.78
#Mann= 7 ,-1 , 0
  3865.5     .05       0    4279      .1       0  4448.2     .05       0
  4957.2      .1       0  4997.6     .07       0  5003.6      .1       0
  5488.7     .05       0
Bank Sta=4879.6,5237.3
XS Rating Curve= 0 ,0
Exp/Cntr=0.3,0.1

Type RM Length L Ch R = 1 ,19697   ,652,652,652
BEGIN DESCRIPTION:
WOLF CREEK 27.0
END DESCRIPTION:
XS GIS Cut Line= 4
      2715717.24      10033134.9      2716363.09     10032544.61
      2717481.15      10032058.5      2718514.63     10031184.55
#Sta/Elev= 30
  3396.6 1773.35  3505.9 1771.14  3653.3 1768.26  3809.6 1761.41  3936.4 1755.24
  4042.4 1740.27  4099.2  1736.3  4397.4 1731.59  4511.9 1735.02  4820.4 1733.31
  4867.4 1733.27  4944.2 1726.05  4955.5 1724.18  4987.1 1721.88  4989.9 1721.38
  4993.1 1721.88  5065.9 1722.61    5128 1730.85  5163.5 1732.81  5182.5 1734.19
  5448.9 1735.68  5540.2  1734.7  5762.2 1733.17    6081 1737.82  6130.4 1740.21
  6201.9  1753.7  6400.7  1759.5  6478.7 1765.74  6705.2 1769.72  6844.2 1775.83
#Mann= 11 ,-1 , 0
  3396.6      .1       0  3505.9     .05       0  3809.6      .1       0
  4820.4     .05       0  4944.2      .1       0  4955.5     .16       0
  4987.1     .07       0  4993.1     .16       0  5163.5     .05       0
  5448.9      .1       0  5540.2     .05       0
Bank Sta=4867.4,5182.5
XS Rating Curve= 0 ,0
Exp/Cntr=0.3,0.1

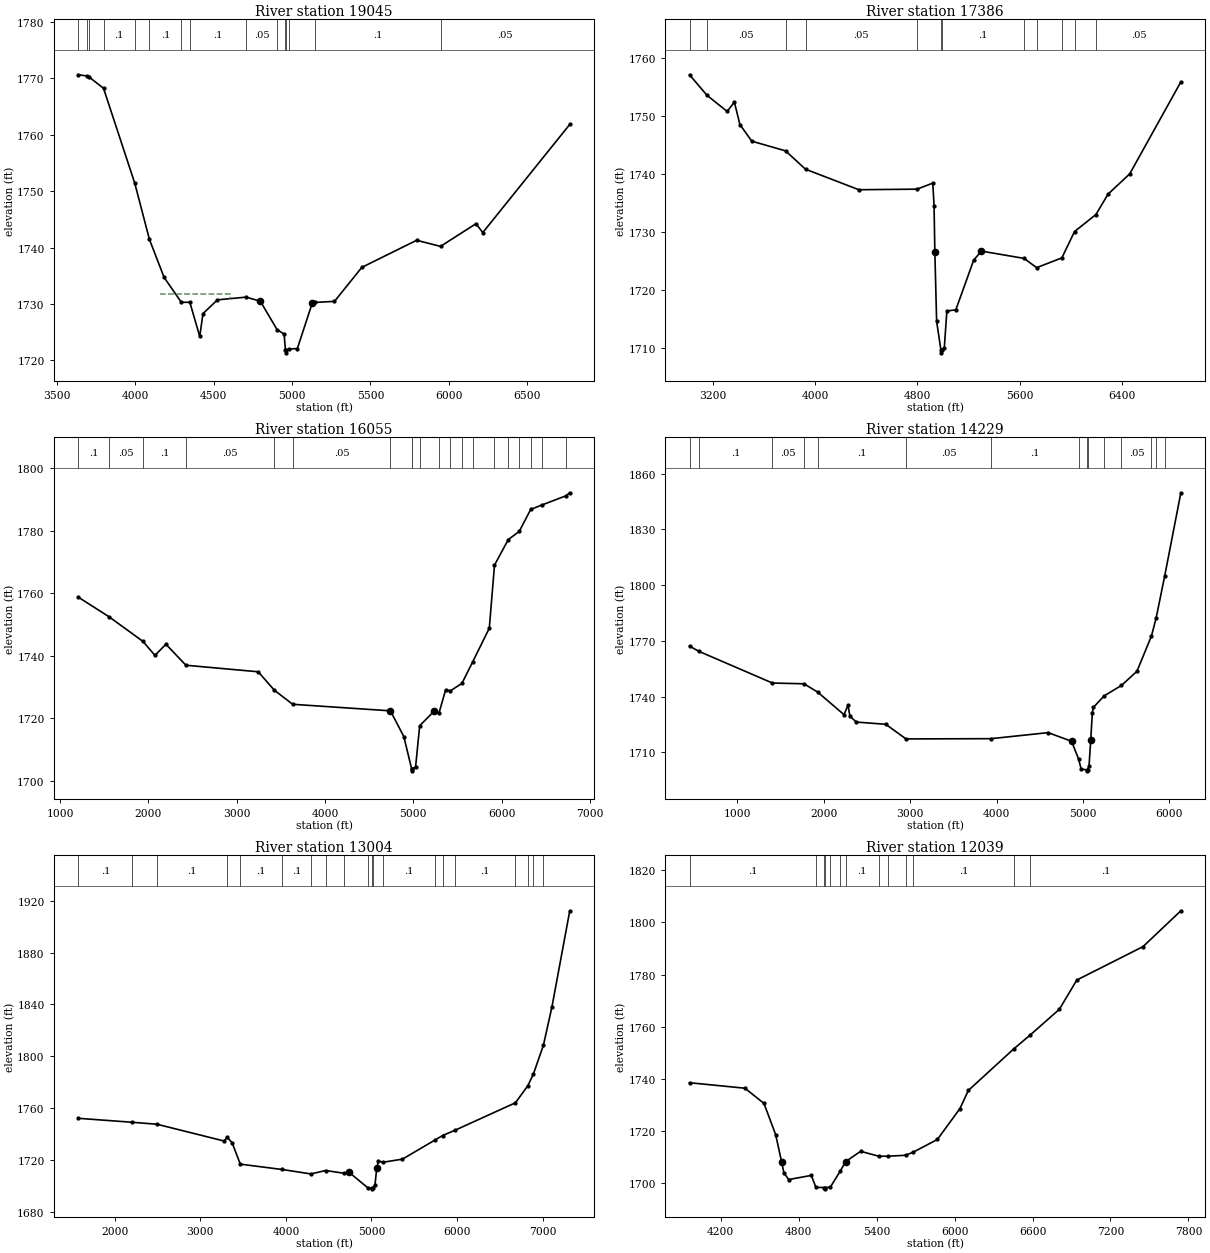
Type RM Length L Ch R = 1 ,19045   ,1659,1659,1659
BEGIN DESCRIPTION:
WOLF CREEK 26.0
END DESCRIPTION:
XS GIS Cut Line= 4
      2716189.51      10033655.7      2717043.65     10032919.61
      2717932.54       10032621.      2718272.55      10031607.9
#Sta/Elev= 30
  3637.1 1770.65  3693.9 1770.43  3701.8 1770.32  3797.1 1768.26  3996.7  1751.4
  4089.8 1741.47  4183.7 1734.71  4293.5 1730.31  4347.8  1730.3  4410.8 1724.26
  4431.7  1728.3  4523.9 1730.74  4706.9 1731.22  4797.5 1730.49  4904.6 1725.43
  4949.1 1724.67  4957.4 1721.84  4960.1 1721.34  4963.4 1721.84  4983.2 1722.02
  5033.5  1722.1  5128.4 1730.15  5147.4 1730.28  5270.3 1730.47  5444.9  1736.5
  5794.4  1741.3  5946.6 1740.22  6172.8 1744.24  6216.3 1742.67    6771 1761.85
#Mann= 15 ,-1 , 0
  3637.1     .05       0  3693.9      .1       0  3701.8     .05       0
  3797.1      .1       0  3996.7     .05       0  4089.8      .1       0
  4293.5     .16       0  4347.8      .1       0  4706.9     .05       0
  4904.6      .1       0  4957.4     .07       0  4963.4      .1       0
  4983.2     .16       0  5147.4      .1       0  5946.6     .05       0
#XS Ineff= 1 ,-1
 4158.24 4603.69 1731.86
Permanent Ineff=
       T
Bank Sta=4797.5,5128.4
XS Rating Curve= 0 ,0
Exp/Cntr=0.3,0.1

Type RM Length L Ch R = 1 ,17386   ,1331,1331,1331
BEGIN DESCRIPTION:
WOLF CREEK 25.0
END DESCRIPTION:
XS GIS Cut Line= 3
      2717057.52     10034933.51      2718432.54     10033947.39
       2718286.7      10031794.6
#Sta/Elev= 30
  3014.1  1757.1  3150.9 1753.56  3309.2 1750.77  3365.7 1752.38  3409.1 1748.51
    3502 1745.64  3766.4 1743.97  3923.3  1740.8  4340.8 1737.26  4796.5 1737.36
  4920.3  1738.4  4930.3 1734.47 4936.36 1726.58  4950.4 1714.54  4983.9 1709.61
  4986.7 1709.11  4989.9 1709.61  5010.5 1709.97  5030.6 1716.33  5100.7 1716.53
  5241.1 1725.13  5301.2 1726.67  5635.2 1725.41  5734.1 1723.81  5931.8  1725.5
  6030.7 1730.04  6198.6 1732.98  6293.5  1736.5  6463.4    1740  6863.9 1755.87
#Mann= 12 ,-1 , 0
  3014.1      .1       0  3150.9     .05       0  3766.4      .1       0
  3923.3     .05       0  4796.5      .1       0  4983.9     .07       0
  4989.9      .1       0  5635.2     .16       0  5734.1      .1       0
  5931.8     .05       0  6030.7      .1       0  6198.6     .05       0
Bank Sta=4936.36,5301.2
XS Rating Curve= 0 ,0
Exp/Cntr=0.3,0.1

Type RM Length L Ch R = 1 ,16055   ,1826,1826,1826
BEGIN DESCRIPTION:
WOLF CREEK 24.0
END DESCRIPTION:
XS GIS Cut Line= 4
      2716979.84     10035129.68      2719562.31     10033621.43
      2719334.45     10032623.17      2720397.79     10031494.72
#Sta/Elev= 30
  1207.9 1758.72    1556 1752.45  1938.6 1744.62  2074.8 1740.14  2198.8 1743.72
  2425.3    1737  3244.5 1734.91  3425.6 1729.06  3634.6 1724.53  4741.9 1722.44
  4893.7 1714.21    4983 1703.78  4985.7 1703.28    4989 1703.78    5027  1704.6
  5073.1 1717.68    5239 1722.41  5291.9 1721.73  5366.4 1729.08  5421.7 1728.84
  5551.6 1731.21  5672.2 1738.01  5861.6 1748.83  5920.5 1768.97    6077 1777.14
  6200.8 1779.73  6330.7 1786.76  6455.8 1788.15  6728.2 1791.09    6773 1792.07
#Mann= 20 ,-1 , 0
  1207.9      .1       0    1556     .05       0  1938.6      .1       0
  2425.3     .05       0  3425.6      .1       0  3634.6     .05       0
  4741.9      .1       0    4983     .07       0    4989     .16       0
  5073.1      .1       0  5291.9     .05       0  5421.7      .1       0
  5551.6     .05       0  5672.2      .1       0  5920.5      .1       0
    6077     .05       0  6200.8      .1       0  6330.7      .1       0
  6455.8     .05       0  6728.2      .1       0
Bank Sta=4741.9,5239
XS Rating Curve= 0 ,0
Exp/Cntr=0.3,0.1

Type RM Length L Ch R = 1 ,14229   ,1225,1225,1225
BEGIN DESCRIPTION:
WOLF CREEK 23.0
END DESCRIPTION:
XS GIS Cut Line= 4
      2716849.67       10035759.      2718715.96     10034869.26
      2720256.76     10033578.03      2721851.83     10033361.01
#Sta/Elev= 30
   445.8 1767.21   551.5 1764.42  1406.2  1747.3  1770.9  1746.9    1929 1742.44
  2234.7 1730.26  2280.1 1735.38  2302.8 1729.49  2376.4 1726.29  2717.7  1725.1
  2952.2 1717.22  3936.9 1717.35  4596.8 1720.61  4868.5 1715.96  4949.4 1706.41
  4979.5 1700.98  5047.2 1700.54  5049.9 1700.04  5053.2 1700.54  5070.3 1702.51
  5090.5 1716.71  5108.7 1731.28  5120.8 1734.19  5245.9 1740.39  5446.2 1746.02
  5625.4 1753.64  5793.1 1772.62  5846.9  1782.2    5947 1805.06  6133.4 1849.71
#Mann= 15 ,-1 , 0
   445.8     .05       0   551.5      .1       0  1406.2     .05       0
  1770.9     .16       0    1929      .1       0  2952.2     .05       0
  3936.9      .1       0  4949.4     .16       0  5047.2     .07       0
  5053.2     .16       0  5245.9      .1       0  5446.2     .05       0
  5793.1      .1       0  5846.9     .05       0    5947     .16       0
Bank Sta=4868.5,5090.5
XS Rating Curve= 0 ,0
Exp/Cntr=0.3,0.1

Type RM Length L Ch R = 1 ,13004   ,965,965,965
BEGIN DESCRIPTION:
WOLF CREEK 22.0
END DESCRIPTION:
XS GIS Cut Line= 4
      2717706.82     10036247.32      2719659.97      10034663.1
      2721157.36      10034728.2      2722154.14     10033319.71
#Sta/Elev= 30
  1576.7 1752.23  2208.1 1749.16  2494.7 1747.65    3279 1734.71  3313.7 1737.53
  3371.6 1733.45  3467.4 1716.89  3954.7 1712.77  4293.4 1709.34  4464.1 1711.99
  4683.3 1709.83  4740.7 1710.49  4956.9 1698.62  5007.9 1698.35  5010.7 1697.85
  5013.9 1698.35    5041 1700.91    5061 1713.82    5081 1719.25  5136.4 1718.37
  5361.3 1720.74  5742.6 1735.53  5830.8 1738.97  5975.7 1743.03  6681.1  1764.2
  6826.3 1777.37  6891.3 1786.43  7008.3 1808.63  7107.9 1838.21  7315.9 1912.25
#Mann= 20 ,-1 , 0
  1576.7      .1       0  2208.1     .05       0  2494.7      .1       0
  3313.7     .05       0  3467.4      .1       0  3954.7      .1       0
  4293.4     .16       0  4464.1     .05       0  4683.3      .1       0
  4956.9     .16       0  5007.9     .07       0  5013.9     .16       0
  5136.4      .1       0  5742.6     .05       0  5830.8      .1       0
  5975.7      .1       0  6681.1     .05       0  6826.3      .1       0
  6891.3     .16       0  7008.3     .16       0
Bank Sta=4740.7,5061
XS Rating Curve= 0 ,0
Exp/Cntr=0.3,0.1

Type RM Length L Ch R = 1 ,12039   ,249,249,249
BEGIN DESCRIPTION:
WOLF CREEK 20.0
END DESCRIPTION:
XS GIS Cut Line= 4
      2719389.59     10035830.63      2720094.86     10035743.83
      2721538.01     10034864.92      2722481.99     10033855.84
#Sta/Elev= 30
  3959.8 1738.55  4385.8 1736.44    4533 1730.63  4623.6 1718.55  4669.7 1707.97
  4686.3 1704.04    4723 1701.42  4897.3 1703.01  4932.9 1698.42  4998.8 1698.36
  5001.6 1697.86  5004.8 1698.36  5043.1 1698.46  5119.9 1704.64  5160.7 1708.23
    5163 1708.34  5276.9 1712.25  5416.6 1710.36  5488.4 1710.37  5624.3 1710.73
  5683.6 1711.97  5867.6 1716.78  6041.9 1728.66  6105.9 1735.58  6457.1 1751.58
  6582.8 1756.86    6807 1766.71  6941.3 1777.93  7450.8 1790.73  7741.9 1804.47
#Mann= 13 ,-1 , 0
  3959.8      .1       0  4932.9     .16       0  4998.8     .07       0
  5004.8     .16       0  5043.1      .1       0  5119.9     .16       0
    5163      .1       0  5416.6     .05       0  5488.4      .1       0
  5624.3     .05       0  5683.6      .1       0  6457.1     .05       0
  6582.8      .1       0
Bank Sta=4669.7,5160.7
XS Rating Curve= 0 ,0
Exp/Cntr=0.3,0.1

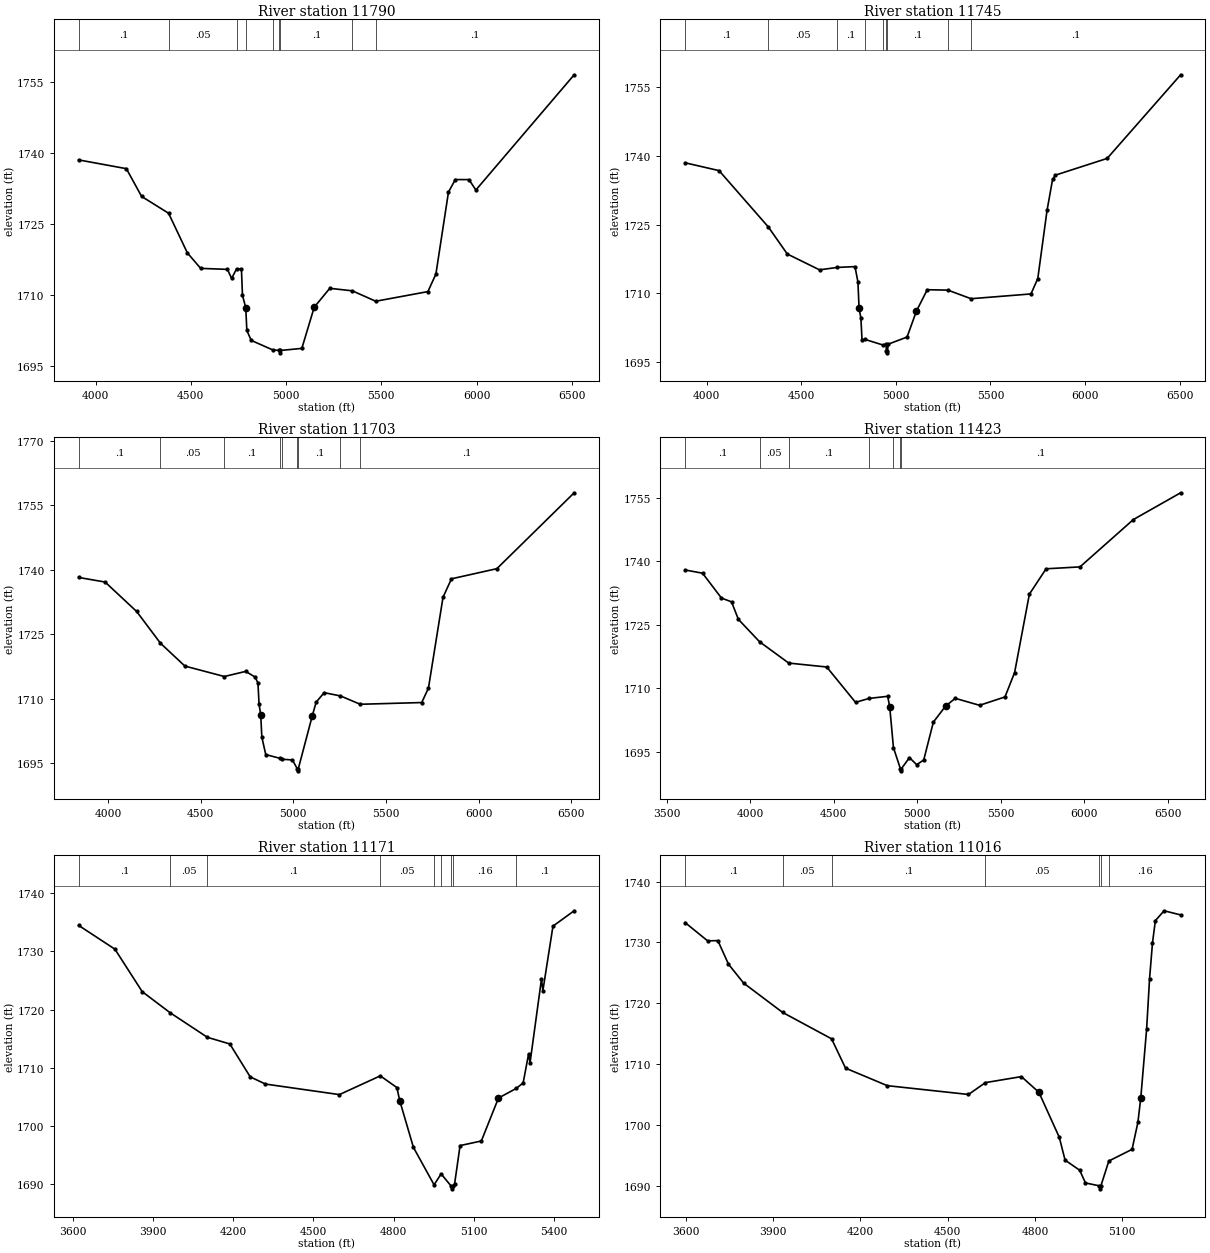
Type RM Length L Ch R = 1 ,11790   ,45,45,45
BEGIN DESCRIPTION:
Mapping XS d5d2b599
END DESCRIPTION:
XS GIS Cut Line= 5
      2719507.96     10035860.69      2720285.72     10035881.52
      2720528.78     10035770.41       2720688.5     10035548.19
      2721750.97     10034829.46
#Sta/Elev= 30
  3910.7 1738.49  4161.3 1736.64  4241.3 1730.78  4382.9 1727.23  4481.4 1718.87
  4551.4 1715.59  4692.1 1715.38  4713.8 1713.47  4739.8 1715.47  4765.4 1715.46
  4770.9 1709.91  4788.1 1707.27  4793.9 1702.48    4817 1700.38  4929.3 1698.39
  4964.2 1698.26    4967 1697.76  4970.2 1698.26  5082.6  1698.7  5147.6 1707.39
  5229.3 1711.38  5347.8 1710.85  5470.5 1708.65  5744.5 1710.69  5786.5  1714.4
  5852.4 1731.69  5888.3 1734.34  5960.2 1734.33  5996.2 1732.13  6512.4 1756.46
#Mann= 9 ,-1 , 0
  3910.7      .1       0  4382.9     .05       0  4739.8      .1       0
  4788.1     .05       0  4929.3      .1       0  4964.2     .07       0
  4970.2      .1       0  5347.8     .05       0  5470.5      .1       0
Bank Sta=4788.1,5147.6
XS Rating Curve= 0 ,0
Exp/Cntr=0.3,0.1

Type RM Length L Ch R = 1 ,11745   ,42,42,42
BEGIN DESCRIPTION:
Mapping XS fbec9674
END DESCRIPTION:
XS GIS Cut Line= 5
      2719539.19     10035898.89      2720323.92     10035933.61
      2720560.03     10035794.72      2720737.11     10035586.39
      2721805.02     10034872.13
#Sta/Elev= 30
  3886.8 1738.45  4066.2 1736.74  4326.1 1724.49  4426.6 1718.58  4596.8 1715.13
  4691.3 1715.66  4784.2 1715.83  4799.8 1712.48  4805.6 1706.83  4815.5 1704.58
  4821.3 1699.89  4838.1 1699.96  4930.8 1698.77  4948.9 1698.92  4949.8 1697.55
  4952.6 1697.05  4955.8 1697.55  4960.5 1698.95  5059.3 1700.49  5108.8 1706.15
  5165.9  1710.8    5275 1710.71  5397.3 1708.84  5713.8 1709.88  5749.8 1713.23
  5798.7 1728.08  5827.9 1734.81  5842.9 1735.76  6116.2  1739.4  6504.4 1757.62
#Mann= 9 ,-1 , 0
  3886.8      .1       0  4326.1     .05       0  4691.3      .1       0
  4838.1     .05       0  4930.8      .1       0  4949.8     .07       0
  4955.8      .1       0    5275     .05       0  5397.3      .1       0
Bank Sta=4805.6,5108.8
XS Rating Curve= 0 ,0
Exp/Cntr=0.3,0.1

Type RM Length L Ch R = 1 ,11703   ,280,280,280
BEGIN DESCRIPTION:
Mapping XS 42bc65f5
END DESCRIPTION:
XS GIS Cut Line= 5
      2719535.71     10035919.72      2720389.89     10035961.39
       2720587.8     10035829.44       2720775.3      10035596.8
       2721854.3     10034902.92
#Sta/Elev= 30
    3841 1738.22  3983.9 1737.15  4154.1  1730.3  4282.8 1722.91  4414.4  1717.6
  4627.3 1715.17  4742.8 1716.36  4793.9 1715.03  4808.9 1713.65  4814.9 1708.74
  4823.9 1706.23  4829.9 1701.06    4851 1697.01  4926.2 1696.15  4939.9 1695.92
    4995 1695.75  5020.8 1693.72  5023.6 1693.22  5026.8 1693.72  5102.2 1706.03
    5123 1709.19  5166.2 1711.41  5254.3 1710.65  5360.9 1708.71  5692.9 1709.11
  5729.2 1712.48  5807.8 1733.61  5853.4  1737.9  6098.4 1740.26  6515.7 1757.92
#Mann= 9 ,-1 , 0
    3841      .1       0  4282.8     .05       0  4627.3      .1       0
  4926.2     .05       0  4939.9      .1       0  5020.8     .07       0
  5026.8      .1       0  5254.3     .05       0  5360.9      .1       0
Bank Sta=4823.9,5102.2
XS Rating Curve= 0 ,0
Exp/Cntr=0.3,0.1

Type RM Length L Ch R = 1 ,11423   ,252,252,252
BEGIN DESCRIPTION:
WOLF CREEK 19.0
END DESCRIPTION:
XS GIS Cut Line= 4
      2719536.26     10035935.23      2720536.27     10036143.57
      2721640.44     10035449.12      2722057.09     10034963.02
#Sta/Elev= 30
  3610.5 1737.98  3714.9 1737.22  3828.1 1731.34  3888.5 1730.44  3929.4  1726.3
  4056.9 1720.98  4230.8 1715.96  4458.3 1715.03  4630.5 1706.67  4711.8  1707.6
  4823.3  1708.1  4835.4 1705.55  4857.6 1695.96  4899.2 1690.97  4901.9 1690.47
  4905.2 1690.97  4953.5 1693.61  4996.4 1691.92  5038.8 1693.03  5096.5    1702
  5169.5 1705.77  5227.2 1707.62  5373.3 1705.97  5525.2 1707.95  5582.9 1713.73
  5671.2 1732.26  5771.3 1738.26  5974.1 1738.71  6293.5  1749.9  6576.6 1756.24
#Mann= 7 ,-1 , 0
  3610.5      .1       0  4056.9     .05       0  4230.8      .1       0
  4711.8     .05       0  4857.6      .1       0  4899.2     .07       0
  4905.2      .1       0
Bank Sta=4835.4,5169.5
XS Rating Curve= 0 ,0
Exp/Cntr=0.3,0.1

Type RM Length L Ch R = 1 ,11171   ,155,155,155
BEGIN DESCRIPTION:
Mapping XS 62c42b9d
END DESCRIPTION:
XS GIS Cut Line= 3
      2719636.37      10036020.4        2720626.     10036239.16
      2721444.43      10036051.9
#Sta/Elev= 30
  3621.8 1734.47  3757.6 1730.38  3859.5 1723.09  3963.8 1719.47  4103.4 1715.24
  4187.2  1714.1  4263.4 1708.45  4320.4 1707.21  4596.9  1705.4  4749.9 1708.62
  4811.9 1706.61  4822.5 1704.37  4873.8 1696.33    4951  1689.9  4977.4 1691.78
  5014.4 1689.71  5017.2 1689.21  5020.4 1689.71  5027.7 1690.04  5048.2 1696.64
  5127.8 1697.43  5191.8 1704.81  5258.3 1706.46  5284.1 1707.41  5304.6 1712.42
  5309.8 1710.84  5352.7 1725.27  5357.8 1723.23  5395.6 1734.34  5474.9 1736.98
#Mann= 9 ,-1 , 0
  3621.8      .1       0  3963.8     .05       0  4103.4      .1       0
  4749.9     .05       0    4951      .1       0  4977.4     .16       0
  5014.4     .07       0  5020.4     .16       0  5258.3      .1       0
Bank Sta=4822.5,5191.8
XS Rating Curve= 0 ,0
Exp/Cntr=0.3,0.1

Type RM Length L Ch R = 1 ,11016   ,73,73,73
BEGIN DESCRIPTION:
Mapping XS 6564959b
END DESCRIPTION:
XS GIS Cut Line= 3
      2719643.36     10036062.08      2720646.83     10036308.61
      2721315.22     10036308.61
#Sta/Elev= 30
  3598.4 1733.28  3675.7 1730.27  3710.9 1730.31  3747.3 1726.44  3799.3 1723.32
    3933  1718.5  4101.4 1714.15  4149.4 1709.32  4292.7 1706.44  4571.6 1704.99
  4629.7 1706.94  4753.3 1707.93  4813.3 1705.35  4883.3 1697.95  4903.3 1694.18
  4953.3 1692.53  4973.3 1690.43  5020.3 1689.96  5023.1 1689.46  5026.3 1689.96
  5053.5 1694.04  5133.3 1695.96  5153.3 1700.39  5163.3 1704.47  5183.3 1715.76
  5193.3 1723.99  5203.3 1729.88  5213.3  1733.6  5243.3 1735.22  5300.1 1734.54
#Mann= 7 ,-1 , 0
  3598.4      .1       0    3933     .05       0  4101.4      .1       0
  4629.7     .05       0  5020.3     .04       0  5026.3     .05       0
  5053.5     .16       0
Bank Sta=4813.3,5163.3
XS Rating Curve= 0 ,0
Exp/Cntr=0.3,0.1

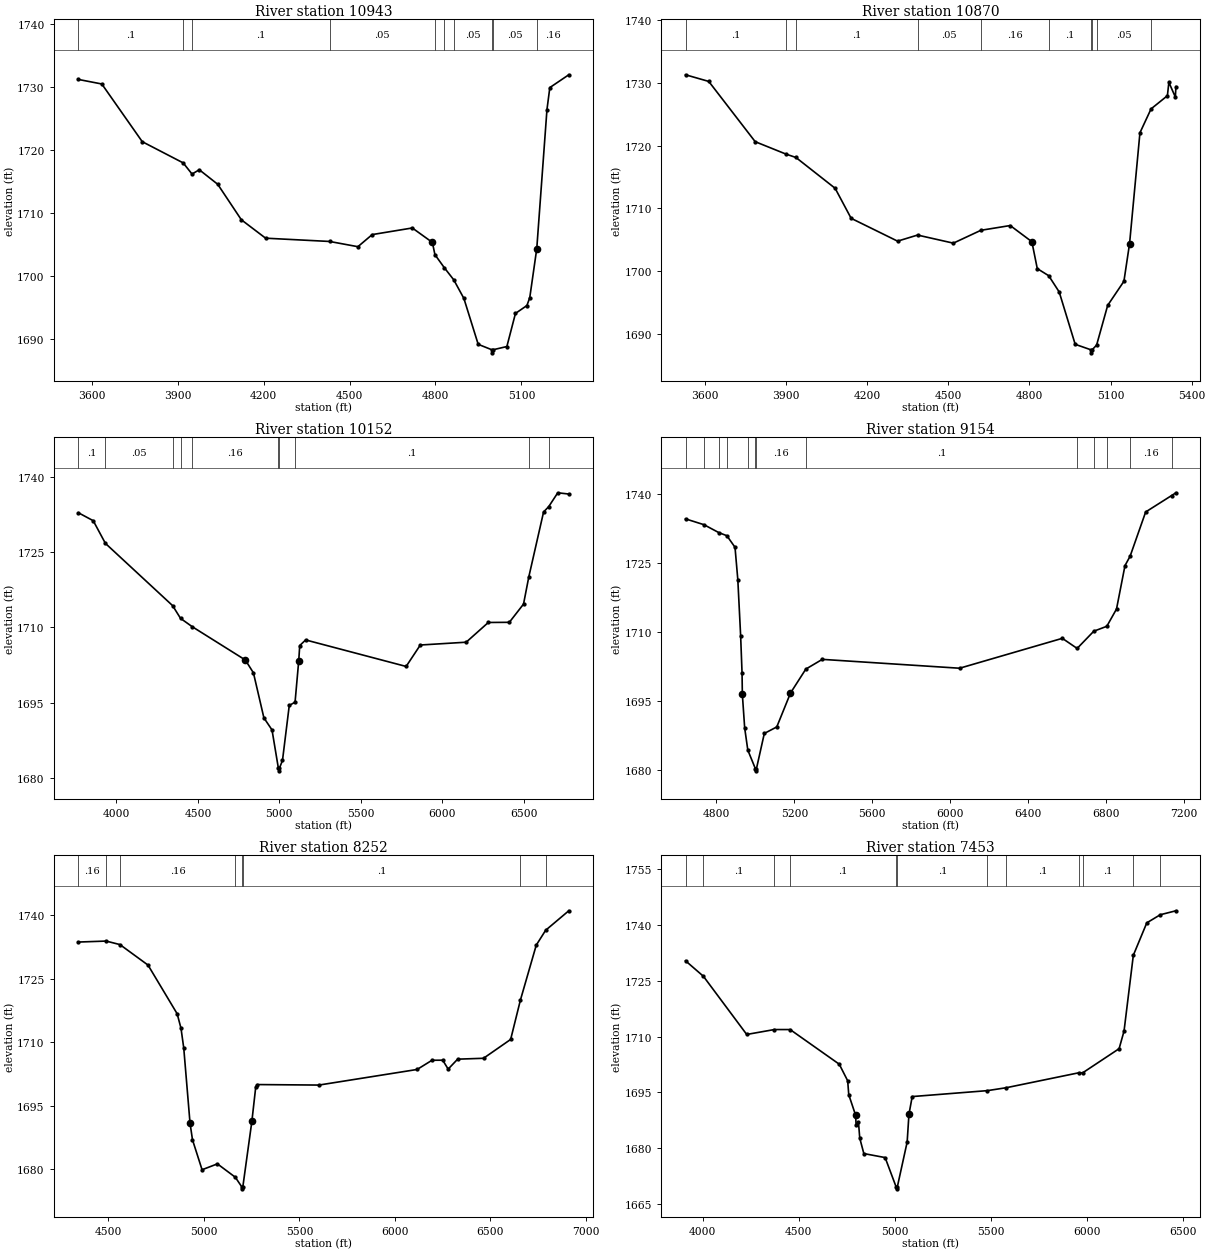
Type RM Length L Ch R = 1 ,10943   ,73,73,73
BEGIN DESCRIPTION:
Mapping XS e456872a
END DESCRIPTION:
XS GIS Cut Line= 3
      2719615.61     10036114.17      2720511.42     10036395.41
      2721284.62     10036374.61
#Sta/Elev= 30
  3553.1 1731.22  3634.9  1730.5  3776.2 1721.35    3919 1717.99    3950 1716.22
  3975.3  1716.9  4039.6  1714.6  4122.1 1708.97  4206.9 1706.05  4430.4 1705.53
  4529.1  1704.7  4579.1 1706.62  4719.1 1707.67  4789.2 1705.38  4798.1 1703.44
  4830.7 1701.38  4863.8 1699.45  4899.2  1696.5  4949.2 1689.22  4996.2 1688.37
    4999 1687.87  5002.2 1688.37  5049.3 1688.87  5079.3 1694.12  5119.3 1695.37
  5129.3 1696.63  5153.7 1704.39  5189.3 1726.44  5199.3 1729.93  5265.5 1731.96
#Mann= 10 ,-1 , 0
  3553.1      .1       0    3919     .05       0    3950      .1       0
  4430.4     .05       0  4798.1     .16       0  4830.7      .1       0
  4863.8     .05       0  4996.2     .04       0  5002.2     .05       0
  5153.7     .16       0
Bank Sta=4789.2,5153.7
XS Rating Curve= 0 ,0
Exp/Cntr=0.3,0.1

Type RM Length L Ch R = 1 ,10870   ,718,718,718
BEGIN DESCRIPTION:
Mapping XS 84d2cc72
END DESCRIPTION:
XS GIS Cut Line= 4
      2719573.95     10036141.95      2720490.58     10036433.61
      2721157.25     10036457.91      2721327.03     10036388.62
#Sta/Elev= 30
  3529.3 1731.31  3615.2 1730.25  3786.8 1720.64  3899.6 1718.68  3937.4 1718.12
  4082.2 1713.21  4141.4 1708.42    4313 1704.78  4386.8 1705.75  4519.1 1704.46
  4620.9 1706.51  4729.3 1707.27  4809.3 1704.69  4829.3  1700.4  4871.5 1699.27
  4910.3 1696.68  4969.4 1688.33  5026.5 1687.47  5029.2 1686.97  5032.5 1687.47
  5048.6 1688.21  5089.5 1694.54  5149.5 1698.38  5170.4  1704.4  5208.7 1722.06
  5249.8 1725.87  5310.2 1727.97  5315.6 1730.11  5339.6 1727.75  5341.7 1729.42
#Mann= 10 ,-1 , 0
  3529.3      .1       0  3899.6     .05       0  3937.4      .1       0
  4386.8     .05       0  4620.9     .16       0  4871.5      .1       0
  5026.5     .07       0  5032.5      .1       0  5048.6     .05       0
  5249.8     .16       0
Bank Sta=4809.3,5170.4
XS Rating Curve= 0 ,0
Exp/Cntr=0.3,0.1

Type RM Length L Ch R = 1 ,10152   ,998,998,998
BEGIN DESCRIPTION:
WOLF CREEK 18.0
END DESCRIPTION:
XS GIS Cut Line= 3
      2719494.62     10036150.53      2720779.33     10037143.57
      2721932.09     10036372.74
#Sta/Elev= 30
  3766.3 1732.81  3857.4 1731.23  3932.3 1726.71  4344.9 1714.31  4393.4 1711.78
  4465.6 1710.11  4791.1 1703.49  4840.9 1700.93  4905.2 1691.96    4955 1689.56
  4994.2 1681.91  4996.9 1681.41  5000.2 1681.91  5019.3 1683.49  5060.9 1694.43
  5096.5 1695.09  5118.9 1703.29  5125.2 1706.36  5161.5 1707.48  5778.3  1702.2
  5865.4 1706.47  6146.9 1707.03  6282.8 1710.96  6411.9 1710.99    6499 1714.62
  6531.4 1720.04  6622.1 1732.97  6653.4 1734.02  6709.2 1736.79  6776.8 1736.54
#Mann= 10 ,-1 , 0
  3766.3      .1       0  3932.3     .05       0  4344.9      .1       0
  4393.4     .05       0  4465.6     .16       0  4994.2     .07       0
  5000.2     .16       0  5096.5      .1       0  6531.4     .16       0
  6653.4     .05       0
Bank Sta=4791.1,5118.9
XS Rating Curve= 0 ,0
Exp/Cntr=0.3,0.1

Type RM Length L Ch R = 1 ,9154    ,902,902,902
BEGIN DESCRIPTION:
WOLF CREEK 17.0
END DESCRIPTION:
XS GIS Cut Line= 3
      2720022.37     10038025.52      2720945.99     10037282.46
      2722001.58     10036469.94
#Sta/Elev= 30
  4641.2 1734.63  4735.9 1733.36  4812.1 1731.64  4853.5 1730.96  4895.3 1728.44
  4909.7 1721.38  4924.1 1709.23  4931.4 1701.05 4932.95 1696.43  4944.9  1689.1
    4961 1684.28  4999.5 1680.27  5002.2 1679.77  5005.5 1680.27  5045.7 1687.91
  5109.7 1689.33  5180.1 1696.71  5258.7 1701.92  5343.3 1704.04  6048.2 1702.11
  6575.5 1708.62  6651.6 1706.42    6737 1710.17  6803.9 1711.24  6853.7    1715
  6897.2 1724.45  6923.6 1726.51  7003.3 1736.13  7136.6 1739.71  7158.7 1740.31
#Mann= 13 ,-1 , 0
  4641.2     .05       0  4735.9      .1       0  4812.1     .16       0
  4853.5      .1       0    4961     .16       0  4999.5     .07       0
  5005.5     .16       0  5258.7      .1       0  6651.6     .05       0
    6737      .1       0  6803.9     .05       0  6923.6     .16       0
  7136.6     .05       0
Bank Sta=4932.95,5180.1
XS Rating Curve= 0 ,0
Exp/Cntr=0.3,0.1

Type RM Length L Ch R = 1 ,8252    ,799,799,799
BEGIN DESCRIPTION:
WOLF CREEK 15.0
END DESCRIPTION:
XS GIS Cut Line= 4
      2720827.95     10038594.94      2721105.71     10038240.79
      2721175.16     10037338.01       2722111.7     10036567.96
#Sta/Elev= 30
  4342.6 1733.69  4487.9 1733.92  4560.2 1733.09  4707.2 1728.24  4859.9 1716.71
    4880 1713.28  4894.4 1708.61 4927.27 1690.83  4940.2 1686.88  4990.3  1679.8
  5070.6 1681.19  5164.3 1678.03  5197.9 1675.78  5200.7 1675.28  5203.9 1675.78
  5251.1 1691.26  5271.1 1699.28  5280.5 1699.96  5602.1 1699.84  6116.2 1703.53
  6194.4 1705.71  6250.4 1705.73    6279 1703.62  6328.6 1705.97  6464.1 1706.18
  6606.2 1710.64  6657.1 1719.92  6740.4 1732.97  6789.5 1736.48  6910.6 1741.09
#Mann= 8 ,-1 , 0
  4342.6     .16       0  4487.9      .1       0  4560.2     .16       0
  5164.3      .1       0  5197.9     .07       0  5203.9      .1       0
  6657.1     .05       0  6789.5     .16       0
Bank Sta=4927.27,5251.1
XS Rating Curve= 0 ,0
Exp/Cntr=0.3,0.1

Type RM Length L Ch R = 1 ,7453    ,469,469,469
BEGIN DESCRIPTION:
WOLF CREEK 14.0
END DESCRIPTION:
XS GIS Cut Line= 4
      2721050.16     10038497.73      2721841.83     10038074.12
      2721966.83     10037074.12      2722577.96     10036858.84
#Sta/Elev= 30
  3909.9 1730.41    4003 1726.24  4228.5 1710.57  4372.5 1711.89  4454.6 1711.89
  4710.4 1702.56  4754.3 1698.09  4759.9 1694.34 4795.45 1688.84  4798.1 1686.27
  4810.5 1686.96  4817.1 1682.66  4838.4 1678.49  4949.3 1677.41  5006.7 1669.49
  5009.5 1668.99  5012.7 1669.49    5064  1681.6  5073.3 1689.06  5090.3 1693.84
    5482 1695.44  5580.6 1696.23  5956.9 1700.24  5978.1 1700.24  6167.7 1706.74
  6193.3 1711.48  6241.7  1731.9  6311.8 1740.63  6381.9 1742.81  6463.5 1743.88
#Mann= 12 ,-1 , 0
  3909.9     .16       0    4003      .1       0  4372.5     .05       0
  4454.6      .1       0  5006.7     .07       0  5012.7      .1       0
    5482     .05       0  5580.6      .1       0  5956.9     .16       0
  5978.1      .1       0  6241.7     .16       0  6381.9      .1       0
Bank Sta=4795.45,5073.3
XS Rating Curve= 0 ,0
Exp/Cntr=0.3,0.1

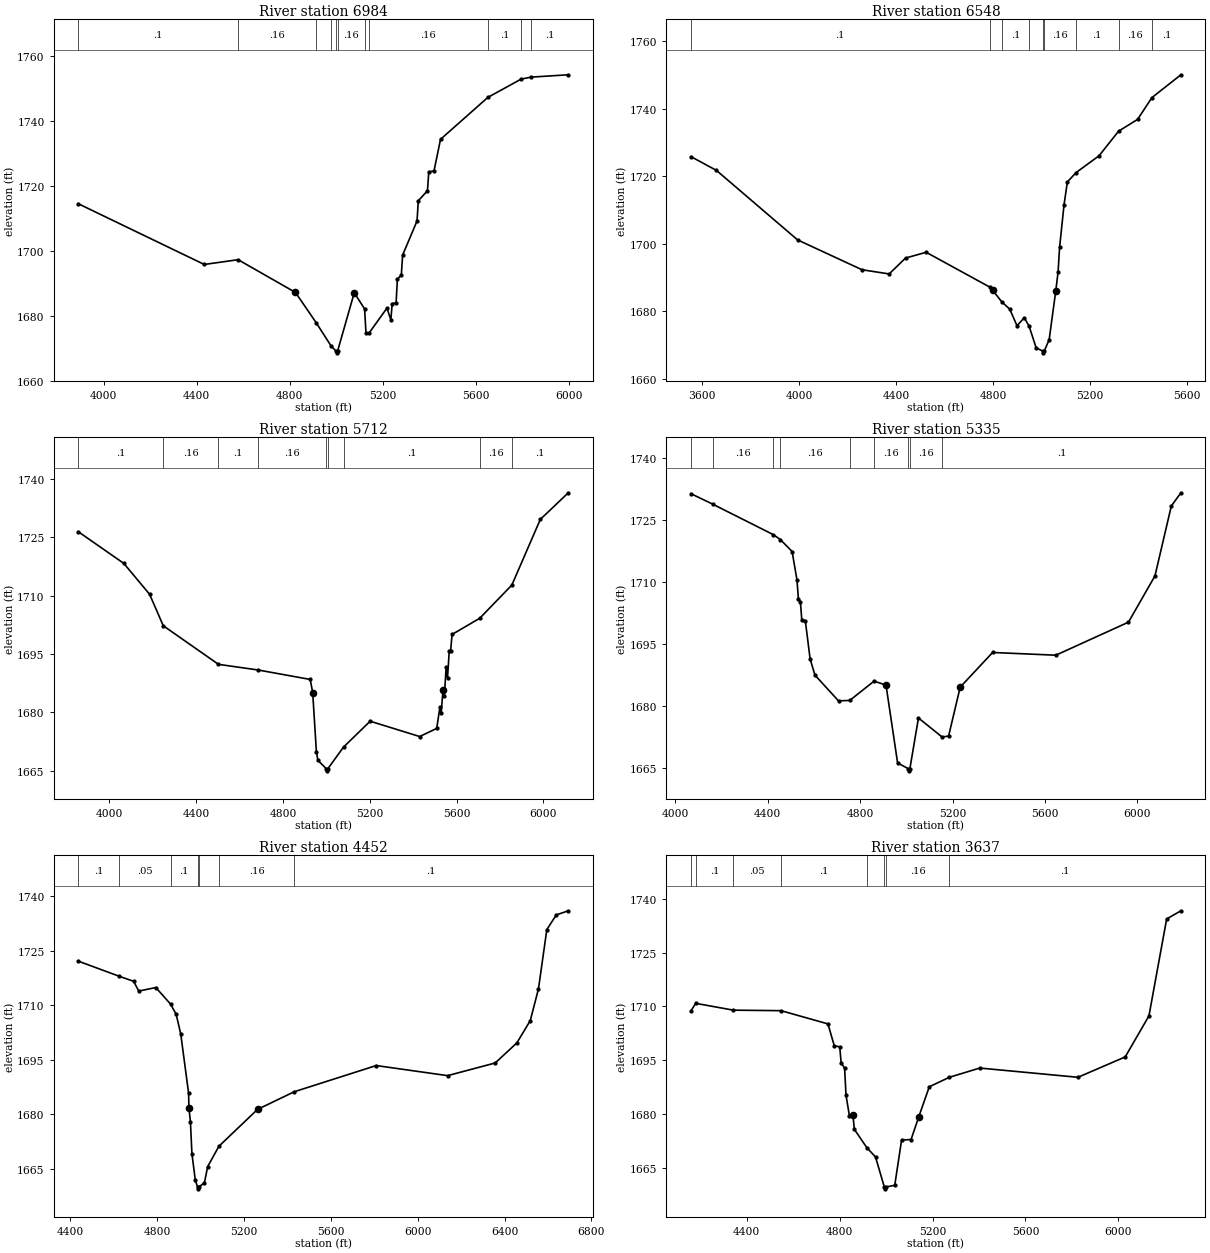
Type RM Length L Ch R = 1 ,6984    ,436,436,436
BEGIN DESCRIPTION:
WOLF CREEK 13.0
END DESCRIPTION:
XS GIS Cut Line= 3
      2721327.91     10038463.02      2722223.77     10038178.29
      2722737.67     10037129.66
#Sta/Elev= 30
  3890.6 1714.41  4432.3 1695.73  4577.9  1697.2  4824.5 1687.13  4913.3 1677.86
  4978.6 1670.58  4999.7 1669.04  5002.5 1668.54  5005.7 1669.04  5077.5 1687.05
  5121.9 1682.06  5128.1 1674.55  5140.1 1674.51  5218.1  1682.3    5235 1678.71
  5240.6 1683.66  5257.5 1683.95  5263.1 1691.21    5280 1692.52  5285.6 1698.62
  5347.5  1709.1  5353.1 1715.35  5392.5 1718.42  5398.1 1724.22  5420.6 1724.51
  5448.6 1734.24  5652.1 1747.13  5795.4 1752.77  5838.2 1753.38  5998.4  1754.1
#Mann= 11 ,-1 , 0
  3890.6      .1       0  4577.9     .16       0  4913.3      .1       0
  4978.6     .16       0  4999.7     .07       0  5005.7     .16       0
  5121.9      .1       0  5140.1     .16       0  5652.1      .1       0
  5795.4     .16       0  5838.2      .1       0
Bank Sta=4824.5,5077.5
XS Rating Curve= 0 ,0
Exp/Cntr=0.3,0.1

Type RM Length L Ch R = 1 ,6548    ,836,836,836
BEGIN DESCRIPTION:
WOLF CREEK 12.0
END DESCRIPTION:
XS GIS Cut Line= 3
      2721175.14     10038608.85      2722459.88     10038372.73
      2723125.03     10038116.37
#Sta/Elev= 30
    3555 1725.85  3660.1 1721.77  3994.4  1701.2  4259.9 1692.36  4371.8 1691.12
  4439.3 1695.82  4524.3 1697.53  4785.5 1687.26  4798.8 1686.24  4836.9 1682.77
  4868.7  1680.7  4898.7 1675.77  4928.7 1678.17  4948.6 1675.63  4977.6 1669.23
  5004.9 1668.26  5007.7 1667.76  5010.9 1668.26  5031.2 1671.66 5058.24 1686.03
  5067.9  1691.7  5074.1 1698.97  5092.5 1711.63  5106.2 1718.35  5141.8 1721.11
    5237 1726.12  5317.2 1733.38  5395.5 1736.87  5454.8 1743.34  5574.1 1750.08
#Mann= 9 ,-1 , 0
    3555      .1       0  4785.5     .16       0  4836.9      .1       0
  4948.6     .16       0  5004.9     .07       0  5010.9     .16       0
  5141.8      .1       0  5317.2     .16       0  5454.8      .1       0
Bank Sta=4798.8,5058.24
XS Rating Curve= 0 ,0
Exp/Cntr=0.3,0.1

Type RM Length L Ch R = 1 ,5712    ,377,377,377
BEGIN DESCRIPTION:
WOLF CREEK 11.0
END DESCRIPTION:
XS GIS Cut Line= 4
      2721196.01     10038747.73      2721959.88      10038601.9
      2722341.83      10039039.4      2723050.13     10038483.87
#Sta/Elev= 30
  3856.7 1726.46  4066.3 1718.32    4185 1710.39  4248.2 1702.29  4502.6 1692.37
  4685.1 1690.92  4925.5 1688.49 4936.93 1685.13  4953.9 1669.96  4960.6 1667.72
  5000.3 1665.49    5003 1664.99  5006.3 1665.49    5079 1671.09  5201.7 1677.75
  5430.1 1673.81  5508.7  1675.9  5523.2 1681.33  5529.5 1679.93  5537.6 1685.78
    5544 1684.19  5552.1 1691.61  5558.4 1688.88  5566.5 1695.87  5572.9 1695.92
  5579.4 1700.06  5706.6  1704.2    5855 1712.75  5986.1 1729.63  6115.3 1736.48
#Mann= 9 ,-1 , 0
  3856.7      .1       0  4248.2     .16       0  4502.6      .1       0
  4685.1     .16       0  5000.3     .07       0  5006.3     .16       0
    5079      .1       0  5706.6     .16       0    5855      .1       0
Bank Sta=4936.93,5537.6
XS Rating Curve= 0 ,0
Exp/Cntr=0.3,0.1

Type RM Length L Ch R = 1 ,5335    ,883,883,883
BEGIN DESCRIPTION:
WOLF CREEK 9.0
END DESCRIPTION:
XS GIS Cut Line= 4
      2721515.42      10039817.2      2721925.16     10039213.01
      2722529.33     10039254.68      2723001.58     10038629.64
#Sta/Elev= 30
  4068.8 1731.27  4162.4 1728.76  4425.3 1721.38  4455.6  1720.2  4506.3 1717.32
  4527.3 1710.46  4533.4 1705.98  4542.3 1705.07  4548.3 1700.72  4563.3 1700.64
  4584.2 1691.39  4605.2 1687.48    4707 1681.28  4755.7 1681.39  4860.5 1686.03
  4912.4  1685.1  4962.5 1666.31  5009.6  1664.9  5012.4  1664.4  5015.6  1664.9
  5052.7 1677.15  5154.9 1672.57    5183 1672.78  5233.2 1684.59  5373.5 1692.96
  5646.8  1692.3    5961 1700.27  6075.5 1711.43  6146.3  1728.3  6187.8 1731.49
#Mann= 9 ,-1 , 0
  4068.8     .05       0  4162.4     .16       0  4425.3      .1       0
  4455.6     .16       0  4755.7      .1       0  4860.5     .16       0
  5009.6     .07       0  5015.6     .16       0  5154.9      .1       0
Bank Sta=4912.4,5233.2
XS Rating Curve= 0 ,0
Exp/Cntr=0.3,0.1

Type RM Length L Ch R = 1 ,4452    ,815,815,815
BEGIN DESCRIPTION:
WOLF CREEK 8.0
END DESCRIPTION:
XS GIS Cut Line= 4
      2721869.58     10040497.78      2722334.88     10039775.51
      2722758.49     10039365.79      2723077.93     10038622.75
#Sta/Elev= 30
  4436.7  1722.1  4625.2 1717.95  4691.3 1716.57    4715 1713.89  4793.6 1714.86
  4861.3 1710.32  4887.3 1707.51  4908.4 1702.12  4944.7 1685.77 4946.02  1681.8
    4953 1678.05  4959.9 1669.24  4975.1 1662.12  4985.7 1660.07  4988.5 1659.57
  4991.7 1660.07  5017.4 1661.22  5032.5 1665.68  5084.4 1671.28  5262.3 1681.39
  5431.4 1686.24  5808.9 1693.43  6137.8 1690.66  6357.2 1694.14  6456.9 1699.65
  6518.8 1705.79  6556.5 1714.51    6595 1730.78  6638.5  1734.8    6694 1735.94
#Mann= 7 ,-1 , 0
  4436.7      .1       0  4625.2     .05       0  4861.3      .1       0
  4985.7     .07       0  4991.7      .1       0  5084.4     .16       0
  5431.4      .1       0
Bank Sta=4946.02,5262.3
XS Rating Curve= 0 ,0
Exp/Cntr=0.3,0.1

Type RM Length L Ch R = 1 ,3637    ,271,271,271
BEGIN DESCRIPTION:
WOLF CREEK 7.0
END DESCRIPTION:
XS GIS Cut Line= 4
      2722341.83     10040386.62      2722973.77     10039949.12
      2722855.71      10039351.9      2723105.71     10038664.42
#Sta/Elev= 30
  4160.3 1708.75  4180.6 1710.88  4343.2 1708.98  4548.1 1708.84    4750 1705.16
    4777 1699.13  4800.7 1698.75  4806.8 1694.32  4821.6 1692.88  4827.7 1685.37
  4842.6 1679.51  4857.4 1679.89  4863.5 1675.87  4916.9  1670.8  4954.8 1668.16
  4992.6 1659.81  4995.3 1659.31  4998.6 1659.81  5037.5  1660.3  5066.9 1672.86
  5107.7 1673.02    5140 1679.17  5186.2 1687.69  5272.6 1690.32  5403.3 1692.89
    5826 1690.32  6029.5 1695.99  6131.6 1707.39  6207.8 1734.33  6269.2 1736.61
#Mann= 8 ,-1 , 0
  4160.3     .05       0  4180.6      .1       0  4343.2     .05       0
  4548.1      .1       0  4916.9     .16       0  4992.6     .07       0
  4998.6     .16       0  5272.6      .1       0
Bank Sta=4857.4,5140
XS Rating Curve= 0 ,0
Exp/Cntr=0.3,0.1