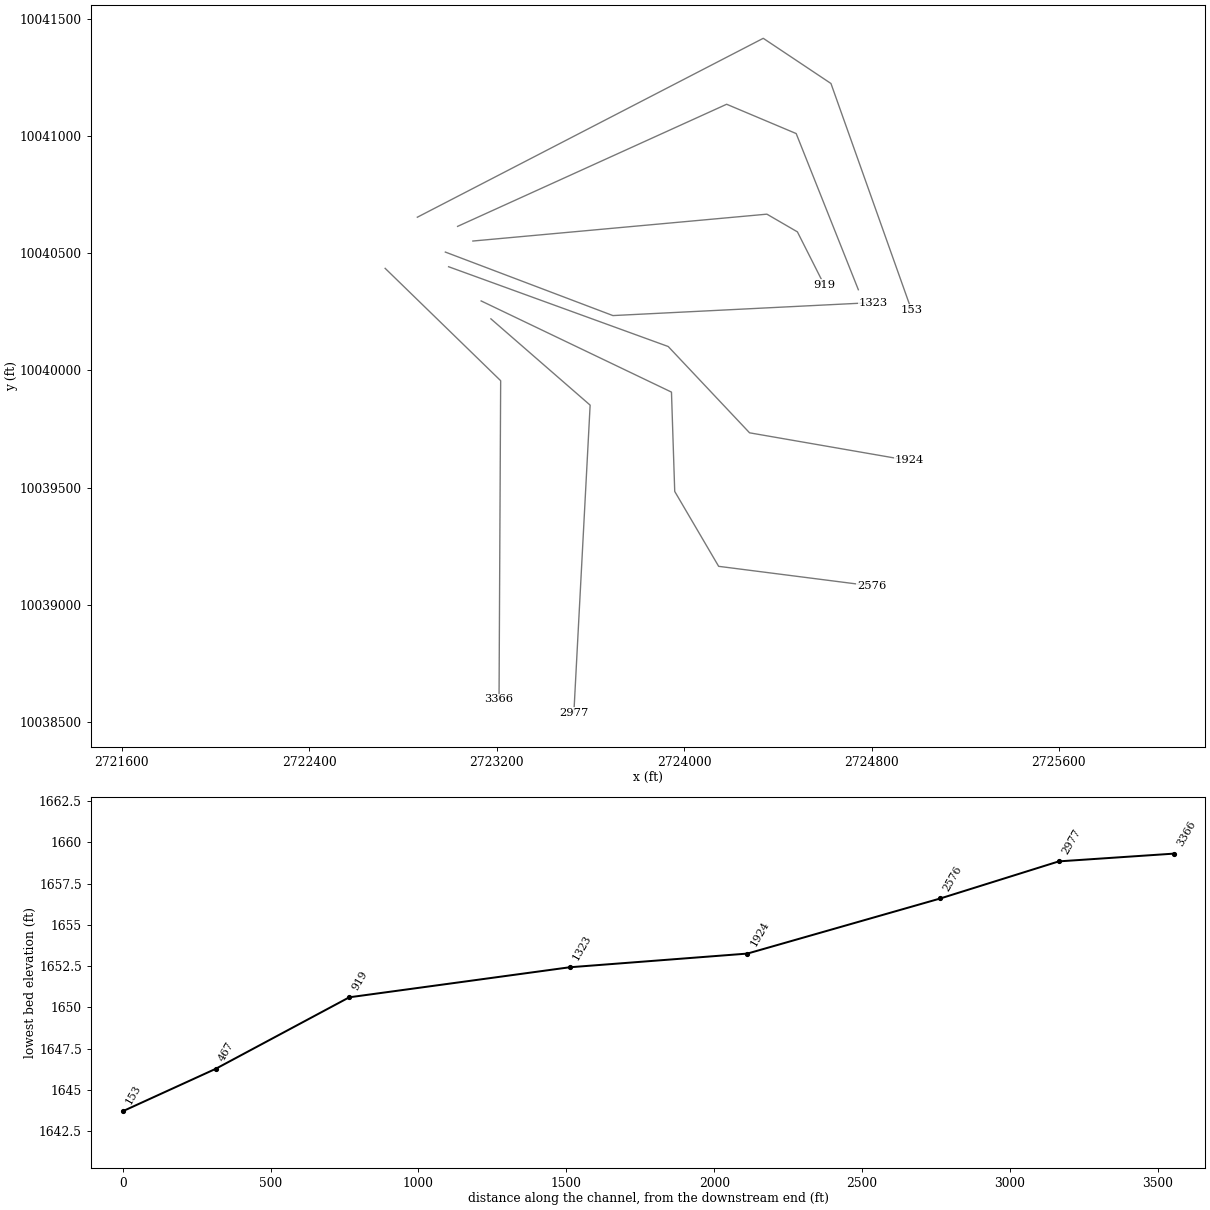
HEC-RAS study WOLF CREEK.prj: WOLF CREEK Base Level Engineering

--- WOLF CREEK.g01 (geometry) --- (continued)

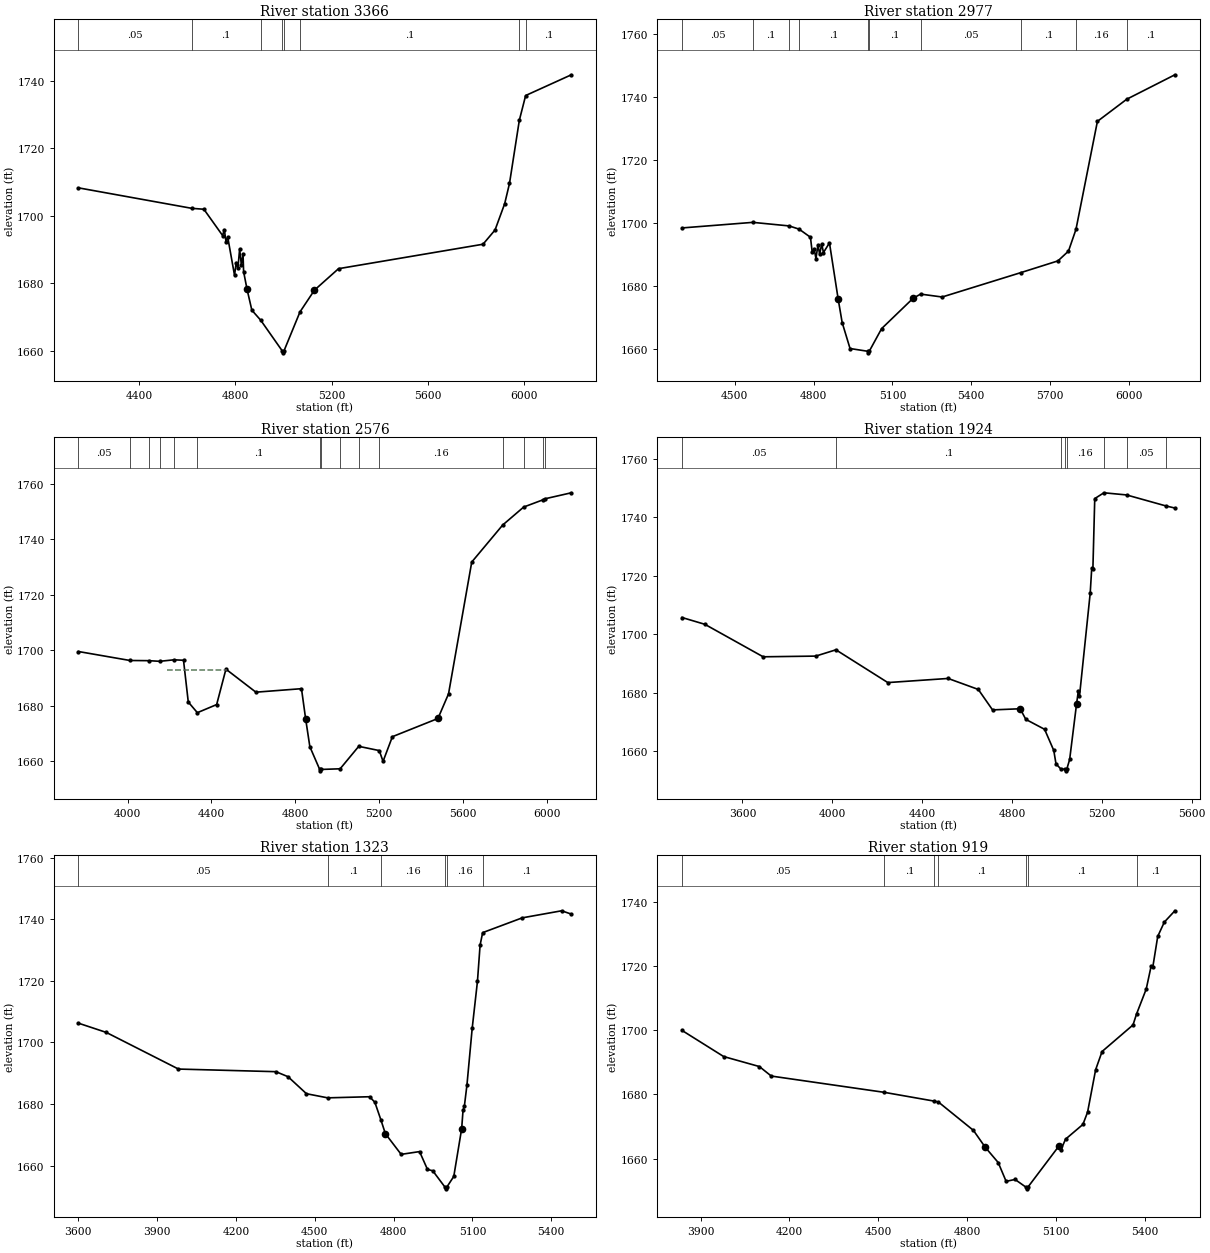
Type RM Length L Ch R = 1 ,3366    ,389,389,389
BEGIN DESCRIPTION:
WOLF CREEK 6.0
END DESCRIPTION:
XS GIS Cut Line= 3
      2722723.74     10040435.27      2723216.83     10039956.07
      2723209.89     10038596.87
#Sta/Elev= 30
  4148.4 1708.31    4619 1702.23  4669.1 1701.96  4746.8 1694.16    4754  1695.9
    4761 1692.33  4768.2 1693.65  4796.4 1682.34  4803.4 1686.14  4810.4  1684.4
  4817.6 1690.15  4824.6 1685.53  4831.7 1688.54  4834.1 1683.43  4848.3 1678.21
  4868.3 1671.99  4905.3 1668.99  4995.3 1659.82  4998.1 1659.32  5001.3 1659.82
  5068.3 1671.48  5128.3 1677.94  5228.3 1684.31  5828.3 1691.57  5878.3  1695.8
  5918.3 1703.61  5938.3 1709.63  5979.2  1728.4  6005.4 1735.73  6195.2 1741.89
#Mann= 8 ,-1 , 0
  4148.4     .05       0    4619      .1       0  4905.3     .16       0
  4995.3     .07       0  5001.3     .16       0  5068.3      .1       0
  5979.2     .16       0  6005.4      .1       0
Bank Sta=4848.3,5128.3
XS Rating Curve= 0 ,0
Exp/Cntr=0.3,0.1

Type RM Length L Ch R = 1 ,2977    ,401,401,401
BEGIN DESCRIPTION:
WOLF CREEK 5.0
END DESCRIPTION:
XS GIS Cut Line= 3
      2723175.19     10040219.93      2723598.77      10039851.9
      2723529.32     10038539.36
#Sta/Elev= 30
  4299.5 1698.49    4569 1700.26  4707.1 1699.13    4745 1698.11  4788.3 1695.53
  4794.9 1690.83  4802.5 1691.78  4809.2 1688.77  4816.8 1693.12  4823.4 1690.09
    4831 1693.41  4837.7 1690.68  4860.6 1693.74 4893.47 1676.05  4908.9 1668.47
  4938.9 1660.22    5006 1659.35  5008.8 1658.85    5012 1659.35  5059.1 1666.54
  5179.2 1676.19  5207.4 1677.49  5289.4 1676.57    5590 1684.34    5730 1688.03
  5770.1 1691.13  5798.6 1698.02  5880.2 1732.31  5991.8 1739.34    6175  1747.1
#Mann= 10 ,-1 , 0
  4299.5     .05       0    4569      .1       0  4707.1     .05       0
    4745      .1       0    5006     .07       0    5012      .1       0
  5207.4     .05       0    5590      .1       0  5798.6     .16       0
  5991.8      .1       0
Bank Sta=4893.47,5179.2
XS Rating Curve= 0 ,0
Exp/Cntr=0.3,0.1

Type RM Length L Ch R = 1 ,2576    ,652,652,652
BEGIN DESCRIPTION:
WOLF CREEK 4.0
END DESCRIPTION:
XS GIS Cut Line= 5
      2723133.51     10040296.33      2723945.99     10039907.46
      2723959.88     10039483.85      2724147.38      10039164.4
      2724800.19     10039081.06
#Sta/Elev= 30
  3765.5 1699.54  4011.2 1696.32  4101.8 1696.25  4153.5 1696.02  4221.3 1696.56
  4266.9  1696.4  4289.6 1681.37    4333 1677.53  4425.1 1680.45  4469.4  1693.2
  4612.5 1684.91  4830.1 1686.17  4850.1 1675.24  4870.1 1665.28  4917.1  1657.1
  4919.9  1656.6  4923.1  1657.1  5014.7 1657.34  5103.5 1665.42  5201.5 1663.89
  5219.6 1660.01  5264.1 1668.89  5481.7 1675.45  5532.2 1684.31    5643 1731.75
    5791 1745.09  5891.1 1751.55  5983.6 1754.16  5991.1 1754.49  6118.6 1756.68
#Mann= 15 ,-1 , 0
  3765.5     .05       0  4011.2      .1       0  4101.8     .05       0
  4153.5      .1       0  4221.3     .05       0    4333      .1       0
  4917.1     .07       0  4923.1      .1       0  5014.7     .16       0
  5103.5      .1       0  5201.5     .16       0    5791     .05       0
  5891.1      .1       0  5983.6     .05       0  5991.1      .1       0
#XS Ineff= 1 ,-1
 4186.93  4473.3 1693.02
Permanent Ineff=
       T
Bank Sta=4850.1,5481.7
XS Rating Curve= 0 ,0
Exp/Cntr=0.3,0.1

Type RM Length L Ch R = 1 ,1924    ,601,601,601
BEGIN DESCRIPTION:
WOLF CREEK 3.0
END DESCRIPTION:
XS GIS Cut Line= 4
       2722994.6     10040442.18       2723932.1      10040101.9
      2724279.33     10039733.85      2724959.93     10039615.78
#Sta/Elev= 30
  3331.2 1705.72  3432.8  1703.4  3692.4 1692.28  3926.6 1692.52  4016.3 1694.67
  4247.4 1683.46  4515.8 1684.87  4650.1 1681.11  4713.6 1674.11  4836.6  1674.5
  4861.7 1670.87  4945.3 1667.47  4986.2 1660.23  4996.1 1655.64  5017.1 1653.93
  5037.8 1653.76  5040.6 1653.26  5043.8 1653.76  5056.9 1657.16  5087.4 1676.01
  5095.5 1680.59  5100.6 1678.75  5148.3 1713.99  5155.2 1722.63  5160.3 1722.27
  5168.6 1746.41  5209.4  1748.4  5310.3 1747.66  5485.4  1743.9  5525.3 1743.18
#Mann= 8 ,-1 , 0
  3331.2     .05       0  4016.3      .1       0  5017.1     .16       0
  5037.8     .07       0  5043.8     .16       0  5209.4      .1       0
  5310.3     .05       0  5485.4      .1       0
Bank Sta=4836.6,5087.4
XS Rating Curve= 0 ,0
Exp/Cntr=0.3,0.1

Type RM Length L Ch R = 1 ,1323    ,745,745,745
BEGIN DESCRIPTION:
WOLF CREEK 2.0
END DESCRIPTION:
XS GIS Cut Line= 3
      2722980.76     10040504.66      2723695.99     10040233.85
      2724805.32     10040289.31
#Sta/Elev= 30
  3600.8 1706.24  3706.4 1703.25  3981.3 1691.34    4352 1690.49  4398.1 1688.86
  4468.3 1683.33    4549 1681.99  4708.5 1682.35  4728.5 1680.56  4751.3 1674.89
  4768.6 1670.35  4828.6 1663.63  4898.7 1664.53  4928.8 1658.73  4948.8  1658.3
  4995.9 1652.93  4998.6 1652.43  5001.9 1652.93  5028.9 1656.46  5058.9 1671.98
  5064.1 1677.95  5069.1 1679.22    5079 1686.18    5099 1704.62    5119 1719.87
    5129 1731.62  5138.8 1735.66  5289.2 1740.46  5439.4 1742.76  5476.3 1741.67
#Mann= 6 ,-1 , 0
  3600.8     .05       0    4549      .1       0  4751.3     .16       0
  4995.9     .07       0  5001.9     .16       0  5138.8      .1       0
Bank Sta=4768.6,5058.9
XS Rating Curve= 0 ,0
Exp/Cntr=0.3,0.1

Type RM Length L Ch R = 1 ,919     ,452,452,452
BEGIN DESCRIPTION:
Mapping XS e98cec99
END DESCRIPTION:
XS GIS Cut Line= 4
      2723098.21      10040551.8      2724353.38     10040666.38
      2724483.59     10040590.86      2724598.17      10040364.3
#Sta/Elev= 30
  3837.5 1699.91  3978.3 1691.78  4098.8 1688.67    4139 1685.71    4521 1680.64
    4690  1677.9  4703.5 1677.63  4821.8 1668.81    4862 1663.52  4905.5  1658.8
  4932.3 1652.94  4962.4 1653.53  4999.6 1651.11  5002.3 1650.61  5005.6 1651.11
  5111.3 1664.01  5117.1 1662.67  5132.9 1666.06  5191.7 1670.66  5207.4 1674.46
  5234.7  1687.7  5256.4 1693.35  5360.9 1701.62  5372.8 1705.02  5405.5 1712.78
  5422.1 1719.91  5427.8 1719.66  5444.4 1729.18  5466.7 1733.63  5502.3 1737.15
#Mann= 7 ,-1 , 0
  3837.5     .05       0    4521      .1       0    4690     .05       0
  4703.5      .1       0  4999.6     .07       0  5005.6      .1       0
  5372.8      .1       0
Bank Sta=4862,5111.3
XS Rating Curve= 0 ,0
Exp/Cntr=0.3,0.1

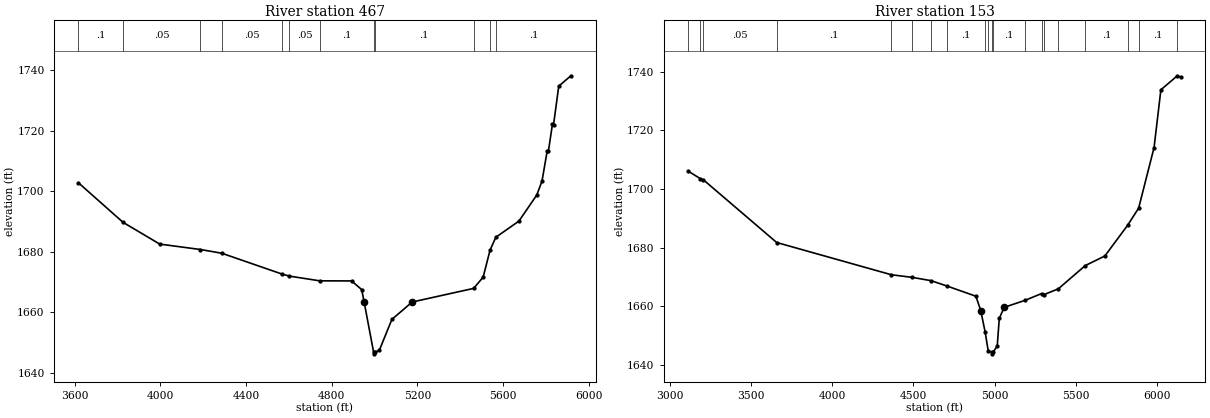
Type RM Length L Ch R = 1 ,467     ,314,314,314
BEGIN DESCRIPTION:
Mapping XS 473e4ac8
END DESCRIPTION:
XS GIS Cut Line= 4
      2723033.03     10040614.28       2724181.5     10041135.13
      2724478.38     10041010.13      2724743.74     10040344.13
#Sta/Elev= 30
  3617.3  1702.8  3825.3 1689.75  3996.7 1682.55  4186.9 1680.76  4286.5 1679.53
  4568.9 1672.62  4602.7 1671.96  4743.7 1670.41  4893.1 1670.37  4940.2  1667.5
  4951.4 1663.47  4995.9 1646.77  4998.6 1646.27  5001.9 1646.77  5022.6 1647.46
  5081.2 1657.66  5175.9  1663.4  5462.7  1667.9  5507.4  1671.6  5539.8 1680.58
  5566.8 1684.82  5674.6 1690.15  5758.1 1698.79  5782.4 1703.37  5806.7  1713.4
  5812.1  1713.2    5831  1722.1  5836.4 1722.07  5860.6 1734.77  5917.4 1738.19
#Mann= 12 ,-1 , 0
  3617.3      .1       0  3825.3     .05       0  4186.9      .1       0
  4286.5     .05       0  4568.9      .1       0  4602.7     .05       0
  4743.7      .1       0  4995.9     .07       0  5001.9      .1       0
  5462.7     .16       0  5539.8     .05       0  5566.8      .1       0
Bank Sta=4951.4,5175.9
XS Rating Curve= 0 ,0
Exp/Cntr=0.3,0.1

Type RM Length L Ch R = 1 ,153     ,0,0,0
BEGIN DESCRIPTION:
WOLF CREEK 1.0
END DESCRIPTION:
XS GIS Cut Line= 4
      2722861.16     10040653.35      2724337.75     10041416.38
      2724626.82     10041223.67      2724970.34     10040258.17
#Sta/Elev= 30
  3113.3 1706.05  3187.4 1703.52  3205.2 1703.17  3657.6 1681.72  4364.2 1670.71
  4490.7 1669.83  4608.9 1668.69    4708 1666.84  4884.9 1663.38  4914.9  1658.5
    4942 1651.16  4960.7 1644.82    4984  1644.2  4986.8  1643.7    4990  1644.2
  5016.6 1646.36  5029.1 1655.79  5059.1 1659.57  5190.5 1662.02  5289.9 1664.29
  5302.1 1663.87  5392.7 1665.89  5558.6 1673.83  5679.8 1677.12  5819.6 1687.58
  5887.8 1693.45  5982.9 1714.16  6024.9 1733.88  6126.2 1738.66  6147.6 1738.23
#Mann= 20 ,-1 , 0
  3113.3     .05       0  3187.4      .1       0  3205.2     .05       0
  3657.6      .1       0  4364.2     .05       0  4490.7      .1       0
  4608.9     .05       0    4708      .1       0    4942     .05       0
  4960.7      .1       0    4984     .07       0    4990      .1       0
  5190.5     .16       0  5289.9      .1       0  5302.1     .16       0
  5392.7     .05       0  5558.6      .1       0  5819.6     .05       0
  5887.8      .1       0  6126.2     .05       0
Bank Sta=4914.9,5059.1
XS Rating Curve= 0 ,0
Exp/Cntr=0.3,0.1

Chan Stop Cuts=-1
Use User Specified Reach Order=0
Composite Channel Slope=5