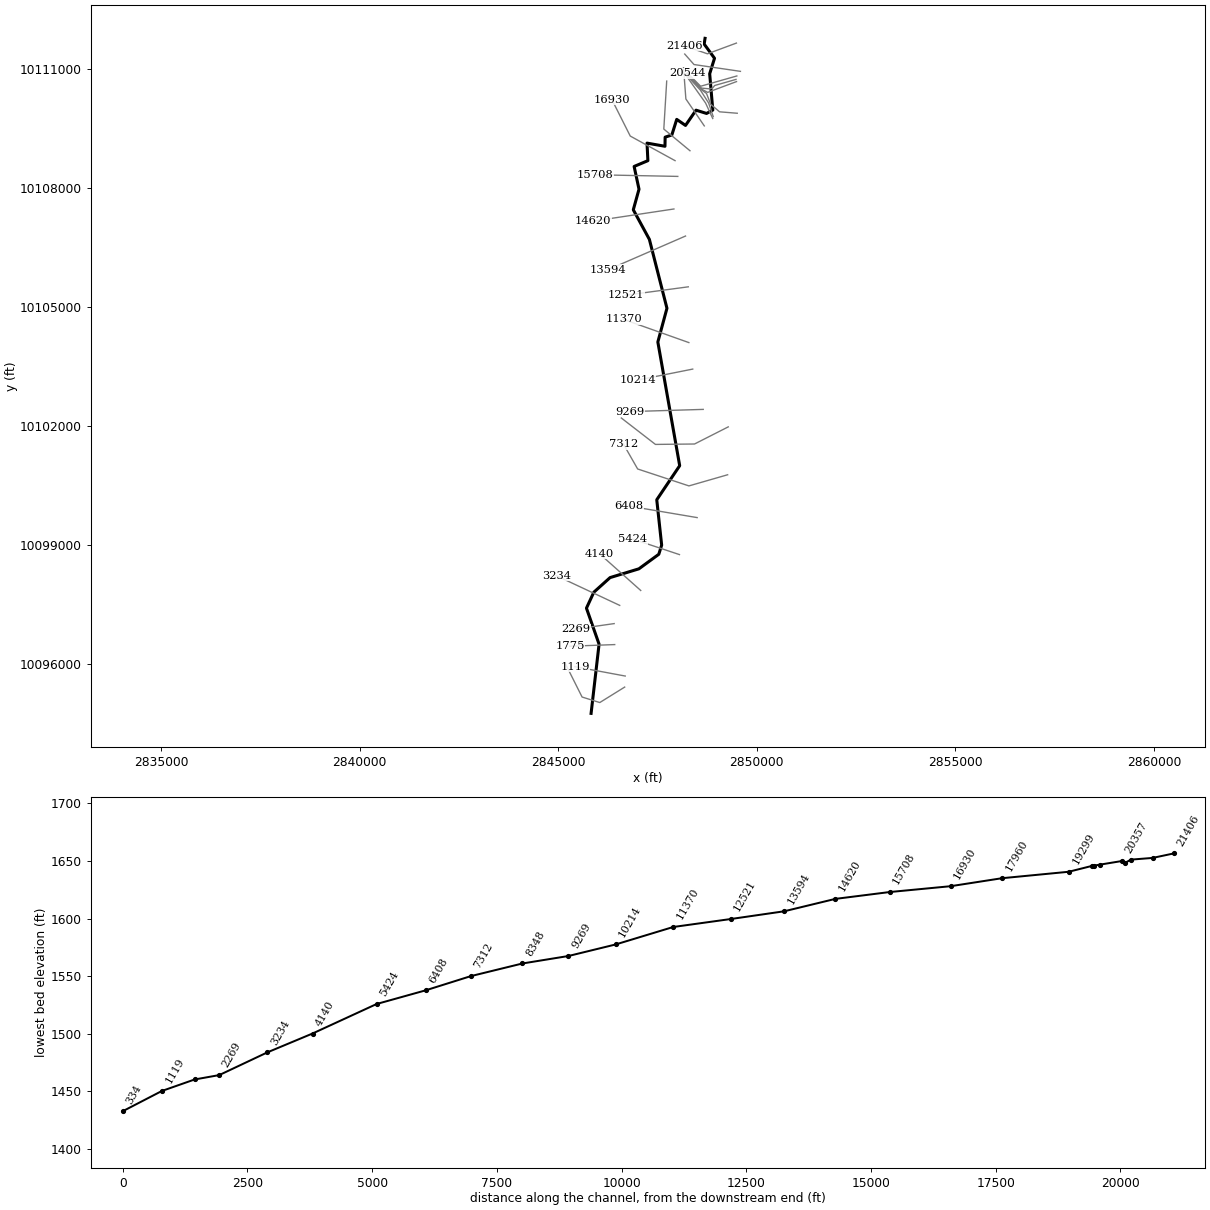
--- BASIN SPRING BRANCH.prj (project) ---

Proj Title=BASIN SPRING BRANCH Base Level Engineering
Current Plan=p01
Default Exp/Contr=0.3,0.1
English Units
Geom File=g01
Flow File=f01
Plan File=p01
BEGIN DESCRIPTION:
BASIN SPRING BRANCH
END DESCRIPTION:

--- BASIN SPRING BRANCH.p01 (plan) ---

Plan Title=Multiple Run
Short Identifier=Multiple
Geom File=g01
Flow File=f01
Subcritical Flow
K Sum by GR= 0
Std Step Tol= 0.01
Critical Tol= 0.01
Num of Std Step Trials= 20
Max Error Tol= 0.3
Flow Tol Ratio= 0.001
Split Flow NTrial= 30
Split Flow Tol= 0.02
Split Flow Ratio= 0.02
Log Output Level= 0
Friction Slope Method= 1
Unsteady Friction Slope Method= 2
Unsteady Bridges Friction Slope Method= 1
Parabolic Critical Depth
Global Vel Dist=  1 , 1 , 1
Global Log Level= 0
CheckData=True
Encroach Param= -1, 0, 0, 0
BEGIN DESCRIPTION:
Multiple Run
END DESCRIPTION:

--- BASIN SPRING BRANCH.f01 (steady flow) ---

Flow Title=Multiple
Number of Profiles=7
Profile Names=10-year,25-year,50-year,1pct_min,100-year,1pct_plu,500-year
River Rch & RM= BASIN SPRING BRA,Reach-1,21406
     637     898    1118    1019    1378    1863    2100
River Rch & RM= BASIN SPRING BRA,Reach-1,16930
    1105    1603    2035    1886    2551    3449    4027
River Rch & RM= BASIN SPRING BRA,Reach-1,13594
    1441    2117    2708    2528    3419    4624    5478
River Rch & RM= BASIN SPRING BRA,Reach-1,7312
    1941    2899    3751    3541    4788    6476    7842
Boundary for River Rch & Prof#=BASIN SPRING BRA,Reach-1,1
Up Type=0
Dn Type=3
Dn Slope=0.005
Boundary for River Rch & Prof#=BASIN SPRING BRA,Reach-1,2
Up Type=0
Dn Type=3
Dn Slope=0.005
Boundary for River Rch & Prof#=BASIN SPRING BRA,Reach-1,3
Up Type=0
Dn Type=3
Dn Slope=0.005
Boundary for River Rch & Prof#=BASIN SPRING BRA,Reach-1,4
Up Type=0
Dn Type=3
Dn Slope=0.005
Boundary for River Rch & Prof#=BASIN SPRING BRA,Reach-1,5
Up Type=0
Dn Type=3
Dn Slope=0.005
Boundary for River Rch & Prof#=BASIN SPRING BRA,Reach-1,6
Up Type=0
Dn Type=3
Dn Slope=0.005
Boundary for River Rch & Prof#=BASIN SPRING BRA,Reach-1,7
Up Type=0
Dn Type=3
Dn Slope=0.005

--- BASIN SPRING BRANCH.g01 (geometry) ---

Geom Title=Existing Conditions

River Reach=BASIN SPRING BRA,Reach-1
Reach XY= 30
      2848696.90     10111775.95      2848674.80     10111631.02
      2848935.23     10111273.12      2848813.71     10110881.63
      2848892.26     10109965.83      2848735.15     10109880.76
      2848469.78     10109963.23      2848205.09     10109578.57
      2847984.00     10109730.91      2847860.84     10109337.41
      2847692.13     10109282.59      2847687.90     10109052.52
      2847235.96     10109131.92      2847257.61     10108689.37
      2846911.15     10108543.20      2847034.05     10107968.85
      2846890.28     10107449.63      2847295.44     10106702.50
      2847737.73     10104964.63      2847508.29     10104113.72
      2848058.48     10100992.64      2847480.96     10100132.47
      2847604.62     10098988.77      2847532.23     10098757.34
      2847031.39     10098390.27      2846305.59     10098169.10
      2845896.23     10097799.95      2845710.54     10097397.86
      2846028.33     10096489.57      2845827.58     10094742.94

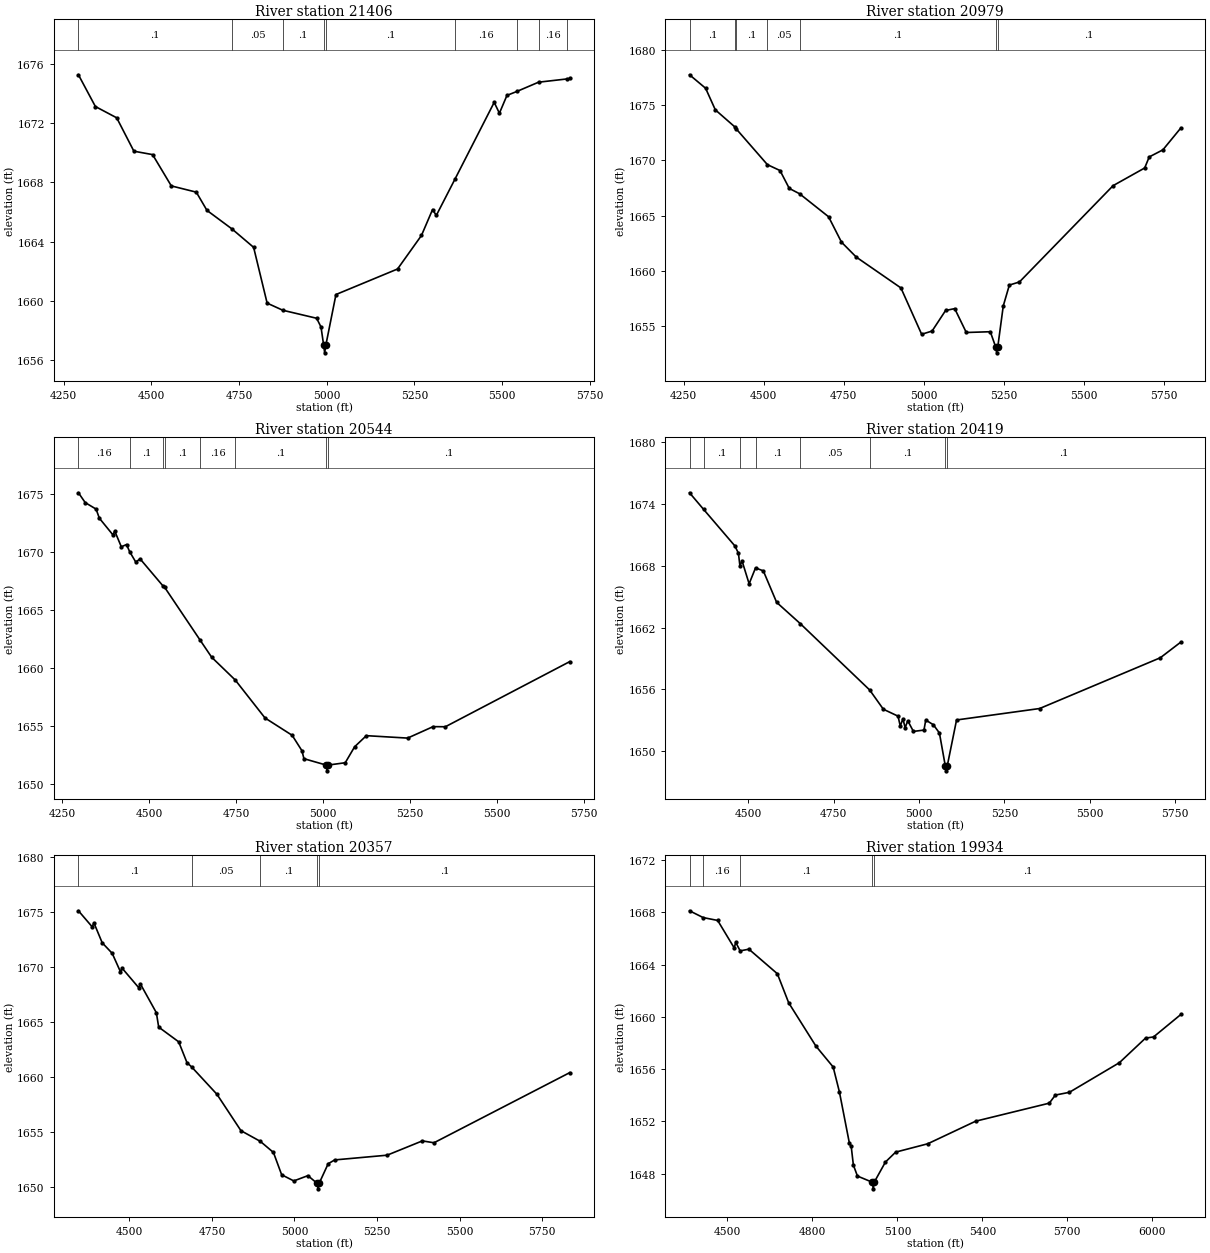
Type RM Length L Ch R = 1,21406,427,427,427
BEGIN DESCRIPTION:
BASIN SPRING BRANCH 39.0
END DESCRIPTION:
XS GIS Cut Line= 3
      2849486.66     10111656.40      2848757.49     10111385.57
      2848168.90     10111588.71
#Sta/Elev= 30
  4292.3 1675.25  4340.7 1673.11  4401.4 1672.35  4450.4 1670.10  4503.7 1669.87
  4557.1 1667.76  4628.3 1667.34  4658.7 1666.11  4730.0 1664.86  4791.7 1663.62
  4830.2 1659.86  4874.9 1659.38  4971.3 1658.84  4983.8 1658.25  4991.4 1657.01
  4994.2 1656.51  4997.4 1657.01  5026.4 1660.44  5201.9 1662.16  5270.1 1664.42
  5301.8 1666.17  5312.4 1665.77  5366.1 1668.24  5477.4 1673.39  5492.3 1672.66
  5513.8 1673.86  5542.4 1674.13  5603.8 1674.75  5685.1 1674.97  5692.8 1675.00
#Mann=9,-1,0
  4292.3     0.1       0  4730.0    0.05       0  4874.9     0.1       0
  4991.4    0.07       0  4997.4     0.1       0  5366.1    0.16       0
  5542.4     0.1       0  5603.8    0.16       0  5685.1    0.05       0
Bank Sta=4991.4,4997.4
Exp/Cntr=0.3,0.1

Type RM Length L Ch R = 1,20979,435,435,435
BEGIN DESCRIPTION:
BASIN SPRING BRANCH 38.0
END DESCRIPTION:
XS GIS Cut Line= 3
      2849588.20     10110942.86      2848418.94     10111114.73
      2848185.28     10111379.56
#Sta/Elev= 30
  4268.3 1677.74  4318.6 1676.52  4348.9 1674.57  4411.3 1672.99  4414.7 1672.83
  4511.7 1669.61  4551.0 1669.08  4580.0 1667.46  4612.1 1666.98  4702.7 1664.90
  4743.1 1662.60  4789.3 1661.25  4928.8 1658.46  4993.5 1654.27  5026.1 1654.56
  5068.3 1656.42  5096.8 1656.59  5133.0 1654.43  5208.0 1654.50  5225.2 1653.09
  5228.0 1652.59  5231.2 1653.09  5248.5 1656.83  5267.5 1658.72  5299.0 1659.00
  5591.6 1667.71  5690.3 1669.31  5704.5 1670.31  5747.2 1670.95  5803.3 1672.93
#Mann=7,-1,0
  4268.3     0.1       0  4411.3    0.05       0  4414.7     0.1       0
  4511.7    0.05       0  4612.1     0.1       0  5225.2    0.07       0
  5231.2     0.1       0
Bank Sta=5225.2,5231.2
Exp/Cntr=0.3,0.1

Type RM Length L Ch R = 1,20544,125,125,125
BEGIN DESCRIPTION:
Mapping XS e7ab85e1
END DESCRIPTION:
XS GIS Cut Line= 3
      2849497.30     10110826.41      2848585.83     10110567.29
      2848256.40     10110898.03
#Sta/Elev= 30
  4296.0 1675.14  4315.6 1674.29  4346.8 1673.73  4356.3 1672.94  4395.4 1671.50
  4400.6 1671.83  4419.5 1670.47  4434.5 1670.67  4443.3 1670.06  4461.1 1669.15
  4473.5 1669.43  4539.7 1667.08  4544.2 1666.97  4646.0 1662.42  4679.5 1660.93
  4747.4 1658.96  4833.1 1655.68  4911.3 1654.18  4939.4 1652.85  4945.2 1652.16
  5009.1 1651.61  5011.9 1651.11  5015.1 1651.61  5064.1 1651.81  5091.1 1653.19
  5124.9 1654.15  5243.6 1653.94  5317.0 1654.93  5352.3 1654.92  5710.4 1660.55
#Mann=8,-1,0
  4296.0    0.16       0  4443.3     0.1       0  4539.7    0.16       0
  4544.2     0.1       0  4646.0    0.16       0  4747.4     0.1       0
  5009.1    0.07       0  5015.1     0.1       0
Bank Sta=5009.1,5015.1
Exp/Cntr=0.3,0.1

Type RM Length L Ch R = 1,20419,62,62,62
BEGIN DESCRIPTION:
Mapping XS df571ccf
END DESCRIPTION:
XS GIS Cut Line= 6
      2849476.28     10110739.74      2848939.78     10110586.09
      2848890.30     10110526.19      2848818.91     10110500.89
      2848604.06     10110520.42      2848249.91     10110890.13
#Sta/Elev= 30
  4327.8 1675.06  4369.1 1673.45  4460.7 1669.91  4471.1 1669.20  4475.4 1667.99
  4481.8 1668.44  4502.4 1666.24  4521.2 1667.78  4544.0 1667.49  4583.0 1664.44
  4652.5 1662.37  4855.4 1655.95  4895.6 1654.08  4938.6 1653.41  4945.1 1652.45
  4952.9 1653.14  4959.4 1652.30  4967.2 1652.96  4983.6 1651.93  5014.5 1652.06
  5019.8 1653.03  5042.0 1652.58  5059.8 1651.78  5076.9 1648.61  5079.7 1648.11
  5082.9 1648.61  5110.0 1653.04  5353.4 1654.15  5706.9 1659.07  5767.0 1660.59
#Mann=8,-1,0
  4327.8    0.16       0  4369.1     0.1       0  4475.4    0.16       0
  4521.2     0.1       0  4652.5    0.05       0  4855.4     0.1       0
  5076.9    0.07       0  5082.9     0.1       0
Bank Sta=5076.9,5082.9
Exp/Cntr=0.3,0.1

Type RM Length L Ch R = 1,20357,423,423,423
BEGIN DESCRIPTION:
Mapping XS 143e440b
END DESCRIPTION:
XS GIS Cut Line= 4
      2849489.48     10110684.48      2848761.62     10110412.34
      2848622.29     10110487.86      2848235.58     10110882.39
#Sta/Elev= 30
  4345.7 1675.14  4387.4 1673.68  4392.7 1674.04  4417.7 1672.23  4448.0 1671.27
  4472.9 1669.60  4478.3 1669.91  4528.2 1668.15  4533.5 1668.48  4581.7 1665.87
  4588.8 1664.56  4649.4 1663.22  4674.3 1661.34  4689.1 1660.92  4765.2 1658.45
  4837.9 1655.14  4896.5 1654.17  4936.3 1653.16  4961.2 1651.13  4998.0 1650.57
  5040.7 1651.05  5068.7 1650.35  5071.5 1649.85  5074.7 1650.35  5102.0 1652.13
  5121.8 1652.48  5280.6 1652.91  5387.2 1654.21  5422.5 1654.04  5833.7 1660.42
#Mann=5,-1,0
  4345.7     0.1       0  4689.1    0.05       0  4896.5     0.1       0
  5068.7    0.07       0  5074.7     0.1       0
Bank Sta=5068.7,5074.7
Exp/Cntr=0.3,0.1

Type RM Length L Ch R = 1,19934,130,130,130
BEGIN DESCRIPTION:
BASIN SPRING BRANCH 37.0
END DESCRIPTION:
XS GIS Cut Line= 6
      2849507.51     10109885.56      2849062.17     10109922.02
      2848838.44     10110112.86      2848734.27     10110383.70
      2848601.46     10110482.66      2848230.33     10110872.01
#Sta/Elev= 30
  4366.1 1668.13  4414.2 1667.61  4465.5 1667.39  4524.1 1665.28  4529.1 1665.72
  4544.9 1665.06  4575.8 1665.19  4676.2 1663.31  4716.3 1661.08  4812.3 1657.77
  4873.2 1656.17  4895.2 1654.27  4930.3 1650.36  4936.9 1650.10  4944.6 1648.66
  4958.9 1647.82  5012.0 1647.34  5014.7 1646.84  5018.0 1647.34  5057.7 1648.89
  5093.8 1649.65  5207.1 1650.29  5376.4 1652.02  5636.3 1653.40  5657.7 1654.02
  5707.1 1654.23  5883.8 1656.50  5976.0 1658.38  6004.3 1658.47  6100.7 1660.19
#Mann=5,-1,0
  4366.1     0.1       0  4414.2    0.16       0  4544.9     0.1       0
  5012.0    0.07       0  5018.0     0.1       0
Bank Sta=5012,5018
Exp/Cntr=0.3,0.1

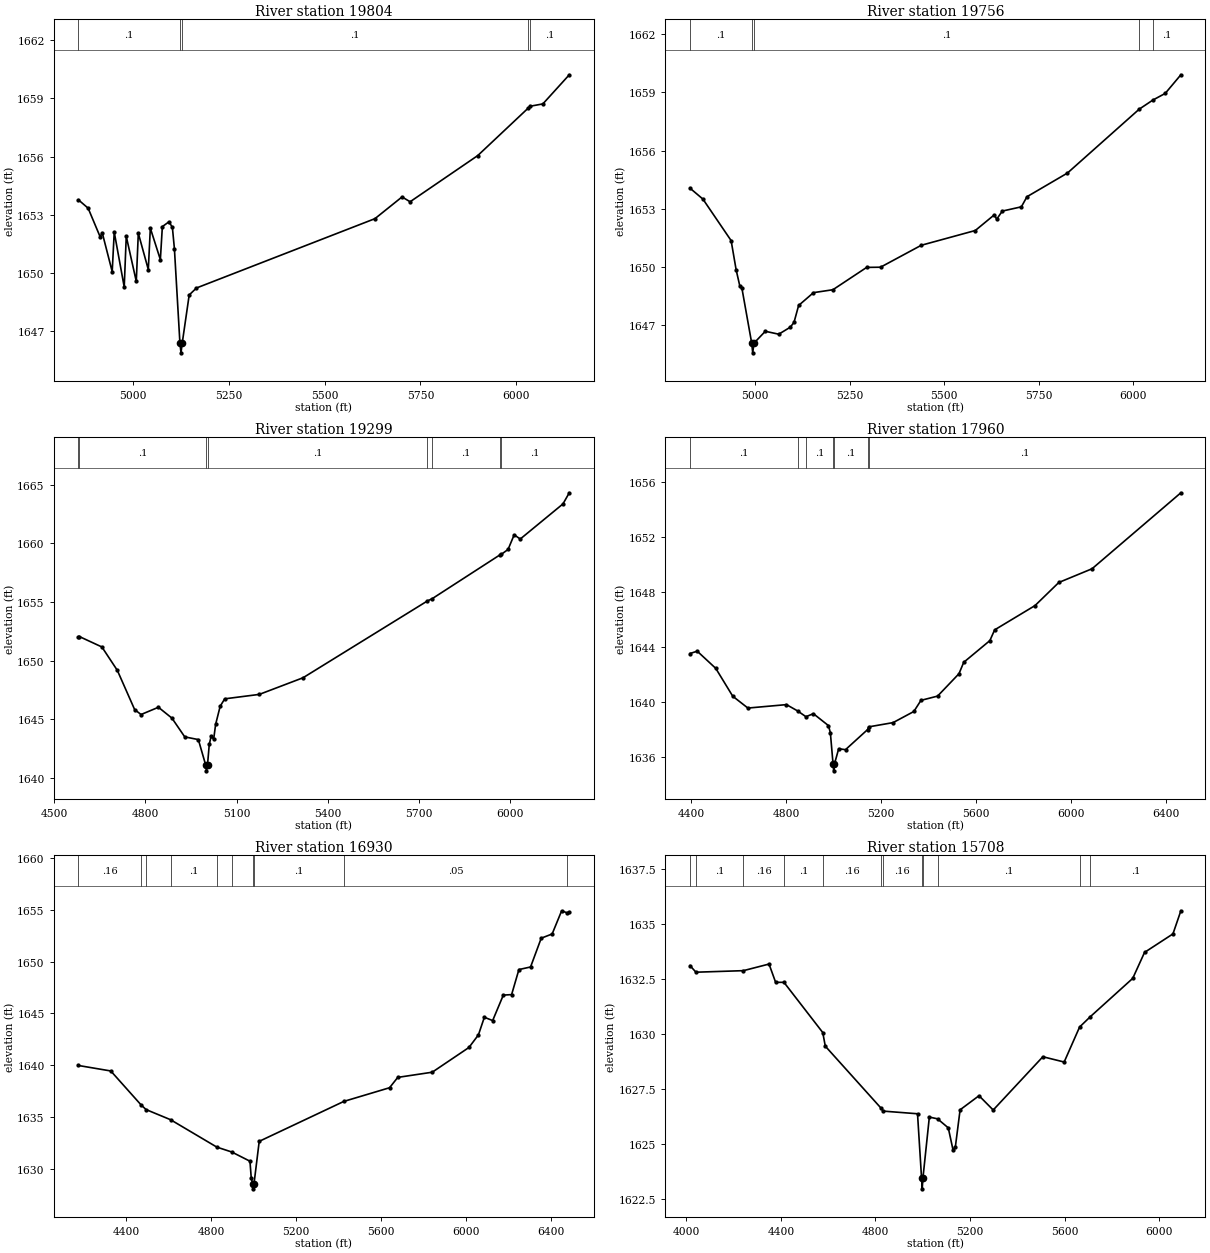
Type RM Length L Ch R = 1,19804,48,48,48
BEGIN DESCRIPTION:
Mapping XS 5600e467
END DESCRIPTION:
XS GIS Cut Line= 4
      2848903.31     10109799.64      2848786.13     10110145.98
      2848578.02     10110472.24      2848216.11     10110858.88
#Sta/Elev= 30
  4856.5 1653.77  4881.9 1653.34  4913.4 1651.86  4918.7 1652.08  4944.8 1650.07
  4950.1 1652.11  4976.2 1649.28  4981.5 1651.89  5007.7 1649.57  5013.0 1652.05
  5039.1 1650.18  5044.4 1652.31  5070.6 1650.69  5075.8 1652.39  5093.1 1652.64
  5102.0 1652.35  5107.3 1651.25  5121.7 1646.39  5124.5 1645.89  5127.7 1646.39
  5145.9 1648.87  5164.9 1649.23  5631.1 1652.80  5701.9 1653.92  5722.9 1653.67
  5899.7 1656.05  6031.2 1658.49  6036.4 1658.59  6069.7 1658.71  6138.7 1660.21
#Mann=5,-1,0
  4856.5     0.1       0  5121.7    0.07       0  5127.7     0.1       0
  6031.2    0.16       0  6036.4     0.1       0
Bank Sta=5121.7,5127.7
Exp/Cntr=0.3,0.1

Type RM Length L Ch R = 1,19756,457,457,457
BEGIN DESCRIPTION:
Mapping XS f4730d4a
END DESCRIPTION:
XS GIS Cut Line= 3
      2848890.29     10109752.77      2848710.83     10110142.81
      2848209.52     10110852.46
#Sta/Elev= 30
  4828.1 1654.06  4862.2 1653.50  4936.9 1651.36  4950.2 1649.85  4959.9 1649.02
  4965.4 1648.91  4991.3 1646.08  4994.0 1645.58  4997.3 1646.08  5027.3 1646.69
  5062.8 1646.54  5093.3 1646.90  5103.2 1647.15  5115.4 1648.02  5154.7 1648.68
  5206.1 1648.83  5295.3 1649.98  5332.0 1649.99  5439.8 1651.12  5582.6 1651.88
  5633.1 1652.69  5639.2 1652.46  5654.0 1652.88  5704.5 1653.10  5719.3 1653.62
  5826.4 1654.84  6016.2 1658.13  6052.4 1658.60  6084.9 1658.94  6126.3 1659.90
#Mann=5,-1,0
  4828.1     0.1       0  4991.3    0.07       0  4997.3     0.1       0
  6016.2    0.16       0  6052.4     0.1       0
Bank Sta=4991.3,4997.3
Exp/Cntr=0.3,0.1

Type RM Length L Ch R = 1,19299,1339,1339,1339
BEGIN DESCRIPTION:
Mapping XS a4aa8cba
END DESCRIPTION:
XS GIS Cut Line= 3
      2848678.13     10109566.57      2848214.27     10110245.79
      2848154.63     10111034.34
#Sta/Elev= 30
  4580.1 1652.03  4583.3 1652.05  4657.3 1651.16  4708.1 1649.16  4765.0 1645.81
  4786.0 1645.39  4843.1 1646.01  4887.6 1645.08  4929.6 1643.48  4974.3 1643.25
  4998.4 1641.08  5001.1 1640.58  5004.4 1641.08  5010.2 1642.84  5016.3 1643.52
  5024.7 1643.29  5031.2 1644.56  5046.1 1646.10  5061.0 1646.73  5174.8 1647.11
  5318.4 1648.53  5727.1 1655.09  5743.2 1655.29  5964.6 1659.01  5969.4 1659.06
  5992.2 1659.49  6012.3 1660.74  6032.3 1660.38  6172.7 1663.38  6193.4 1664.33
#Mann=8,-1,0
  4580.1    0.16       0  4583.3     0.1       0  4998.4    0.07       0
  5004.4     0.1       0  5727.1    0.16       0  5743.2     0.1       0
  5964.6    0.16       0  5969.4     0.1       0
Bank Sta=4998.4,5004.4
Exp/Cntr=0.3,0.1

Type RM Length L Ch R = 1,17960,1030,1030,1030
BEGIN DESCRIPTION:
BASIN SPRING BRANCH 36.0
END DESCRIPTION:
XS GIS Cut Line= 3
      2848317.38     10108939.60      2847658.53     10109486.48
      2847731.45     10110697.44
#Sta/Elev= 30
  4394.6 1643.52  4425.1 1643.69  4503.2 1642.44  4574.9 1640.41  4638.7 1639.55
  4801.4 1639.80  4848.4 1639.34  4883.4 1638.92  4914.7 1639.14  4978.5 1638.27
  4986.4 1637.75  4997.7 1635.48  5000.4 1634.98  5003.7 1635.48  5021.5 1636.59
  5050.2 1636.52  5143.1 1637.98  5147.8 1638.18  5250.8 1638.49  5338.3 1639.30
  5368.3 1640.11  5438.4 1640.42  5528.6 1642.05  5548.6 1642.88  5658.8 1644.46
  5678.9 1645.24  5849.2 1647.01  5949.4 1648.69  6089.6 1649.69  6464.0 1655.22
#Mann=7,-1,0
  4394.6     0.1       0  4848.4    0.05       0  4883.4     0.1       0
  4997.7    0.07       0  5003.7     0.1       0  5143.1    0.16       0
  5147.8     0.1       0
Bank Sta=4997.7,5003.7
Exp/Cntr=0.3,0.1

Type RM Length L Ch R = 1,16930,1222,1222,1222
BEGIN DESCRIPTION:
Mapping XS 6f9dad9a
END DESCRIPTION:
XS GIS Cut Line= 3
      2847942.14     10108689.40      2846813.69     10109310.05
      2846353.64     10110225.82
#Sta/Elev= 30
  4174.2 1639.97  4326.8 1639.44  4469.5 1636.16  4493.0 1635.71  4608.4 1634.73
  4826.6 1632.08  4896.7 1631.61  4982.5 1630.72  4988.7 1629.05  4995.6 1628.55
  4998.4 1628.05  5001.6 1628.55  5026.1 1632.64  5424.9 1636.50  5640.2 1637.82
  5678.8 1638.82  5841.2 1639.32  6014.2 1641.71  6058.9 1642.93  6086.8 1644.63
  6125.9 1644.31  6176.1 1646.77  6215.2 1646.82  6249.6 1649.24  6304.5 1649.49
  6354.7 1652.27  6406.2 1652.68  6451.0 1654.92  6478.1 1654.71  6486.9 1654.81
#Mann=10,-1,0
  4174.2    0.16       0  4469.5     0.1       0  4493.0    0.16       0
  4608.4     0.1       0  4826.6    0.16       0  4896.7     0.1       0
  4995.6    0.07       0  5001.6     0.1       0  5424.9    0.05       0
  6478.1     0.1       0
Bank Sta=4995.6,5001.6
Exp/Cntr=0.3,0.1

Type RM Length L Ch R = 1,15708,1088,1088,1088
BEGIN DESCRIPTION:
BASIN SPRING BRANCH 29.0
END DESCRIPTION:
XS GIS Cut Line= 2
      2848010.60     10108292.06      2845934.92     10108333.85
#Sta/Elev= 30
  4015.5 1633.12  4040.7 1632.82  4241.2 1632.89  4349.8 1633.19  4377.7 1632.36
  4412.9 1632.36  4577.0 1630.08  4587.8 1629.46  4821.4 1626.67  4833.2 1626.51
  4977.8 1626.39  4994.8 1623.48  4997.6 1622.98  5000.8 1623.48  5027.8 1626.24
  5062.4 1626.16  5107.9 1625.75  5127.9 1624.75  5137.9 1624.89  5157.9 1626.57
  5237.9 1627.21  5297.9 1626.56  5507.9 1628.98  5598.0 1628.74  5663.3 1630.33
  5708.7 1630.80  5888.0 1632.54  5938.0 1633.72  6058.1 1634.56  6091.6 1635.61
#Mann=12,-1,0
  4015.5    0.16       0  4040.7     0.1       0  4241.2    0.16       0
  4412.9     0.1       0  4577.0    0.16       0  4821.4     0.1       0
  4833.2    0.16       0  4994.8    0.07       0  5000.8    0.16       0
  5062.4     0.1       0  5663.3    0.05       0  5708.7     0.1       0
Bank Sta=4994.8,5000.8
Exp/Cntr=0.3,0.1

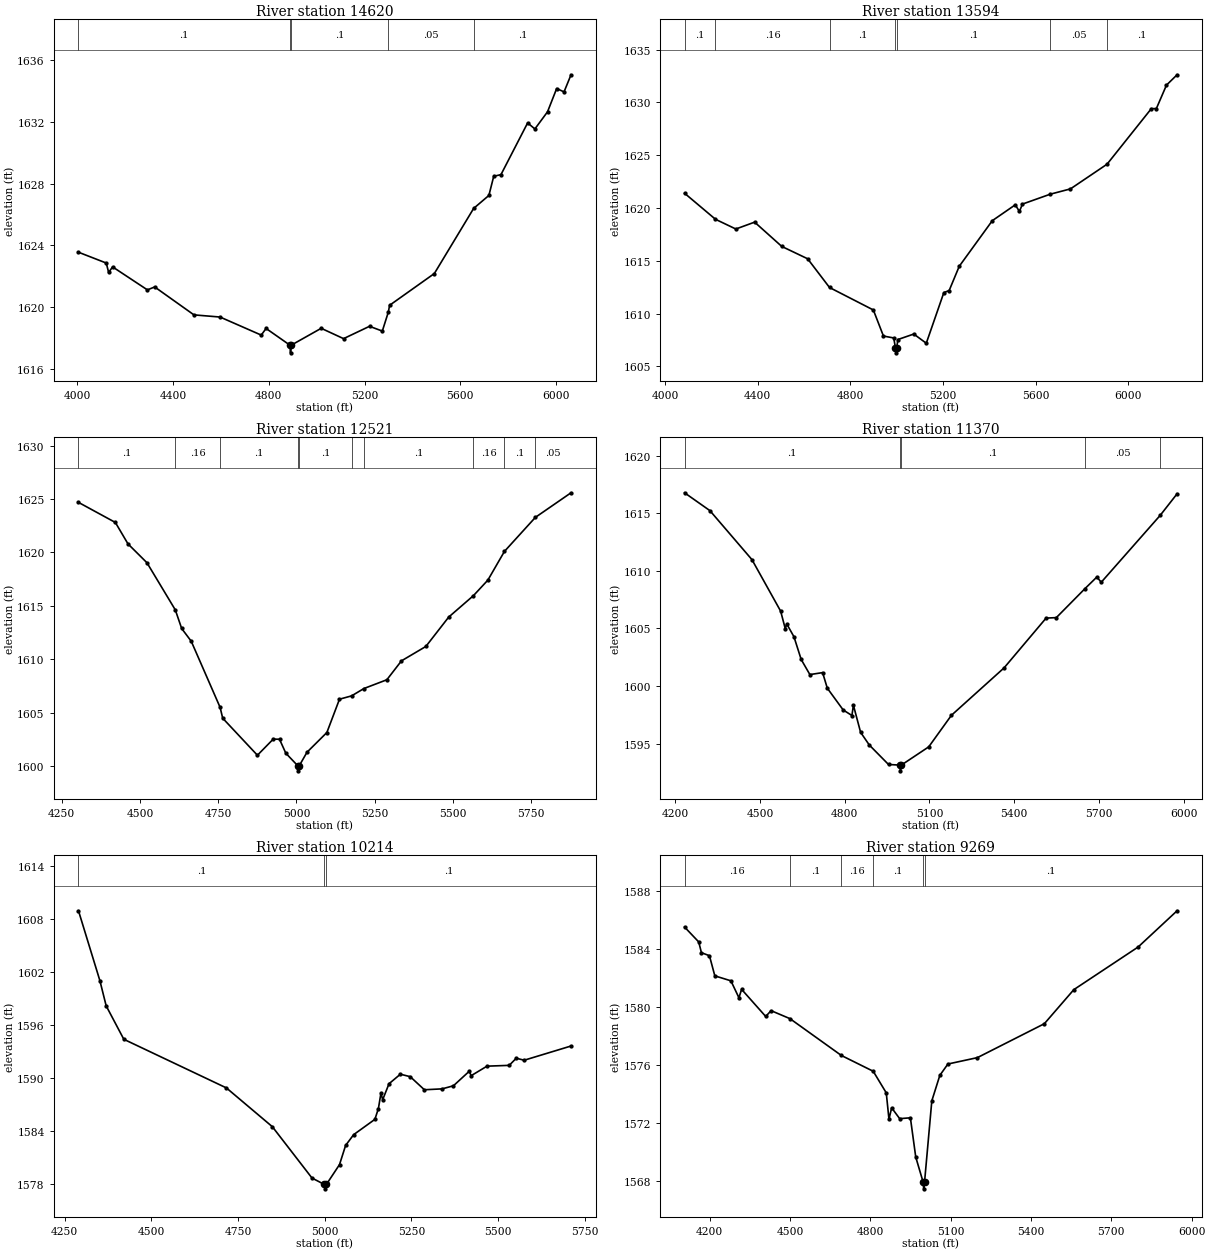
Type RM Length L Ch R = 1,14620,1026,1026,1026
BEGIN DESCRIPTION:
BASIN SPRING BRANCH 31.0
END DESCRIPTION:
XS GIS Cut Line= 2
      2847913.10     10107470.15      2845879.26     10107163.68
#Sta/Elev= 30
  4005.5 1623.56  4121.4 1622.86  4131.5 1622.25  4148.0 1622.61  4293.3 1621.12
  4323.7 1621.31  4487.7 1619.50  4596.7 1619.36  4768.7 1618.19  4788.9 1618.62
  4888.3 1617.54  4891.0 1617.04  4894.3 1617.54  5019.1 1618.63  5112.5 1617.96
  5220.9 1618.76  5274.3 1618.45  5299.6 1619.69  5304.6 1620.12  5491.6 1622.18
  5655.7 1626.40  5719.3 1627.24  5739.5 1628.48  5769.8 1628.59  5881.1 1631.94
  5911.4 1631.55  5964.2 1632.66  6002.4 1634.17  6033.1 1633.95  6062.3 1635.06
#Mann=5,-1,0
  4005.5     0.1       0  4888.3    0.07       0  4894.3     0.1       0
  5299.6    0.05       0  5655.7     0.1       0
Bank Sta=4888.3,4894.3
Exp/Cntr=0.3,0.1

Type RM Length L Ch R = 1,13594,1073,1073,1073
BEGIN DESCRIPTION:
BASIN SPRING BRANCH 30.0
END DESCRIPTION:
XS GIS Cut Line= 2
      2848205.60     10106787.53      2846256.48     10105938.27
#Sta/Elev= 30
  4084.0 1621.40  4217.6 1618.93  4305.4 1618.01  4386.6 1618.66  4503.7 1616.36
  4615.4 1615.19  4709.8 1612.47  4899.0 1610.34  4942.6 1607.87  4987.0 1607.69
  4994.1 1606.78  4996.9 1606.28  5000.1 1606.78  5004.9 1607.54  5073.5 1608.06
  5127.5 1607.19  5203.3 1611.99  5226.2 1612.18  5269.8 1614.48  5412.5 1618.80
  5511.6 1620.30  5529.6 1619.67  5542.5 1620.37  5662.9 1621.31  5749.8 1621.81
  5907.8 1624.15  6098.9 1629.41  6120.7 1629.42  6164.3 1631.64  6210.1 1632.62
#Mann=7,-1,0
  4084.0     0.1       0  4217.6    0.16       0  4709.8     0.1       0
  4994.1    0.07       0  5000.1     0.1       0  5662.9    0.05       0
  5907.8     0.1       0
Bank Sta=4994.1,5000.1
Exp/Cntr=0.3,0.1

Type RM Length L Ch R = 1,12521,1151,1151,1151
BEGIN DESCRIPTION:
BASIN SPRING BRANCH 28.0
END DESCRIPTION:
XS GIS Cut Line= 2
      2848275.32     10105505.93      2846715.05     10105296.97
#Sta/Elev= 30
  4303.4 1624.69  4421.3 1622.81  4461.7 1620.80  4522.2 1619.04  4612.9 1614.62
  4633.2 1612.88  4663.7 1611.69  4756.1 1605.49  4764.3 1604.48  4875.3 1601.01
  4925.8 1602.52  4945.9 1602.51  4966.1 1601.20  5003.5 1600.05  5006.2 1599.55
  5009.5 1600.05  5033.7 1601.29  5097.3 1603.14  5137.6 1606.26  5176.3 1606.57
  5215.8 1607.26  5289.0 1608.08  5335.7 1609.85  5413.7 1611.20  5486.7 1613.95
  5565.8 1615.96  5611.8 1617.41  5664.8 1620.10  5763.8 1623.29  5877.6 1625.59
#Mann=10,-1,0
  4303.4     0.1       0  4612.9    0.16       0  4756.1     0.1       0
  5003.5    0.07       0  5009.5     0.1       0  5176.3    0.05       0
  5215.8     0.1       0  5565.8    0.16       0  5664.8     0.1       0
  5763.8    0.05       0
Bank Sta=5003.5,5009.5
Exp/Cntr=0.3,0.1

Type RM Length L Ch R = 1,11370,1156,1156,1156
BEGIN DESCRIPTION:
BASIN SPRING BRANCH 23.0
END DESCRIPTION:
XS GIS Cut Line= 2
      2848289.21     10104098.94      2846645.43     10104684.02
#Sta/Elev= 30
  4232.4 1616.77  4322.3 1615.22  4471.2 1610.97  4572.9 1606.50  4589.2 1604.98
  4594.5 1605.39  4620.0 1604.28  4645.6 1602.31  4676.4 1601.00  4721.5 1601.17
  4738.1 1599.82  4794.4 1597.93  4825.3 1597.45  4830.6 1598.34  4856.1 1595.99
  4886.9 1594.89  4955.0 1593.20  4994.4 1593.15  4997.2 1592.65  5000.4 1593.15
  5097.4 1594.73  5177.9 1597.47  5364.3 1601.58  5513.2 1605.90  5549.4 1605.94
  5651.1 1608.46  5692.9 1609.46  5708.6 1609.01  5917.0 1614.80  5977.2 1616.68
#Mann=5,-1,0
  4232.4     0.1       0  4994.4    0.07       0  5000.4     0.1       0
  5651.1    0.05       0  5917.0    0.16       0
Bank Sta=4994.4,5000.4
Exp/Cntr=0.3,0.1

Type RM Length L Ch R = 1,10214,945,945,945
BEGIN DESCRIPTION:
BASIN SPRING BRANCH 22.0
END DESCRIPTION:
XS GIS Cut Line= 2
      2848386.77     10103430.27      2846993.66     10103151.65
#Sta/Elev= 30
  4289.7 1608.93  4351.4 1601.03  4369.6 1598.17  4420.5 1594.39  4716.3 1588.89
  4848.9 1584.50  4963.3 1578.69  4998.8 1577.97  5001.6 1577.47  5004.8 1577.97
  5042.6 1580.21  5060.2 1582.38  5083.4 1583.60  5144.6 1585.33  5154.8 1586.55
  5162.1 1588.29  5167.2 1587.56  5185.4 1589.36  5218.2 1590.44  5246.6 1590.16
  5287.4 1588.68  5338.4 1588.78  5371.2 1589.13  5417.1 1590.78  5422.2 1590.27
  5468.1 1591.35  5532.1 1591.44  5552.5 1592.25  5575.2 1592.02  5710.4 1593.63
#Mann=3,-1,0
  4289.7     0.1       0  4998.8    0.07       0  5004.8     0.1       0
Bank Sta=4998.8,5004.8
Exp/Cntr=0.3,0.1

Type RM Length L Ch R = 1,9269,921,921,921
BEGIN DESCRIPTION:
BASIN SPRING BRANCH 21.0
END DESCRIPTION:
XS GIS Cut Line= 2
      2848651.47     10102413.33      2846813.01     10102357.62
#Sta/Elev= 30
  4106.4 1585.53  4159.4 1584.50  4169.4 1583.76  4199.4 1583.55  4219.5 1582.16
  4279.5 1581.82  4309.5 1580.65  4319.5 1581.23  4409.5 1579.36  4429.6 1579.76
  4500.0 1579.21  4692.0 1576.67  4811.0 1575.58  4859.7 1574.09  4869.8 1572.27
  4879.8 1573.06  4909.8 1572.31  4949.8 1572.37  4969.8 1569.66  4996.8 1567.97
  4999.6 1567.47  5002.8 1567.97  5029.8 1573.54  5059.8 1575.30  5089.9 1576.08
  5199.9 1576.52  5450.0 1578.86  5560.1 1581.21  5800.2 1584.15  5945.7 1586.65
#Mann=6,-1,0
  4106.4    0.16       0  4500.0     0.1       0  4692.0    0.16       0
  4811.0     0.1       0  4996.8    0.07       0  5002.8     0.1       0
Bank Sta=4996.8,5002.8
Exp/Cntr=0.3,0.1

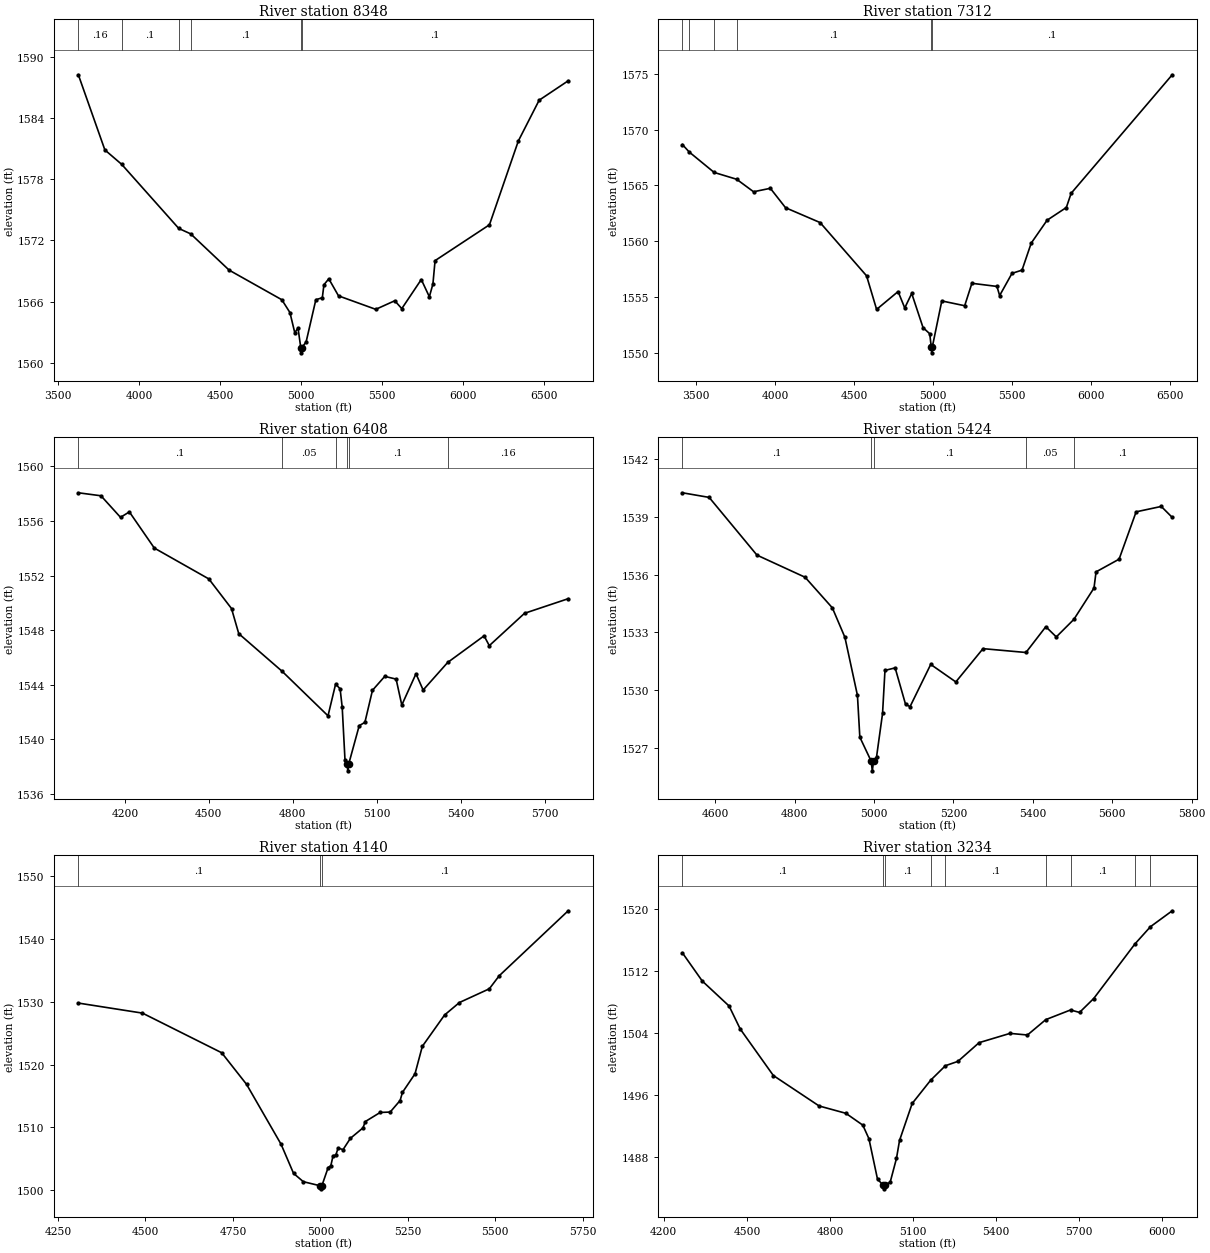
Type RM Length L Ch R = 1,8348,1036,1036,1036
BEGIN DESCRIPTION:
BASIN SPRING BRANCH 16.0
END DESCRIPTION:
XS GIS Cut Line= 4
      2849281.17     10101972.15      2848432.23     10101539.86
      2847447.85     10101529.45      2846588.51     10102196.09
#Sta/Elev= 30
  3625.8 1588.22  3789.6 1580.86  3893.4 1579.45  4246.0 1573.17  4319.6 1572.64
  4556.8 1569.09  4882.2 1566.19  4932.2 1564.94  4962.2 1562.96  4982.2 1563.42
  4999.3 1561.49  5002.0 1560.99  5005.3 1561.49  5032.3 1562.06  5092.3 1566.19
  5132.3 1566.39  5142.3 1567.66  5172.3 1568.24  5232.3 1566.57  5462.3 1565.25
  5579.6 1566.09  5623.0 1565.32  5743.4 1568.17  5793.2 1566.48  5815.2 1567.73
  5828.5 1570.02  6164.3 1573.53  6342.7 1581.74  6471.2 1585.73  6650.5 1587.63
#Mann=6,-1,0
  3625.8    0.16       0  3893.4     0.1       0  4246.0    0.16       0
  4319.6     0.1       0  4999.3    0.07       0  5005.3     0.1       0
Bank Sta=4999.3,5005.3
Exp/Cntr=0.3,0.1

Type RM Length L Ch R = 1,7312,904,904,904
BEGIN DESCRIPTION:
BASIN SPRING BRANCH 15.0
END DESCRIPTION:
XS GIS Cut Line= 4
      2849265.59     10100763.83      2848291.60     10100482.57
      2846999.93     10100909.65      2846640.86     10101539.34
#Sta/Elev= 30
  3413.8 1568.66  3457.2 1567.99  3614.9 1566.16  3757.1 1565.55  3864.1 1564.43
  3970.3 1564.74  4066.5 1563.00  4285.1 1561.67  4579.1 1556.90  4642.6 1553.89
  4778.5 1555.49  4820.6 1554.02  4864.7 1555.32  4936.4 1552.26  4978.6 1551.71
  4988.6 1550.50  4991.3 1550.00  4994.6 1550.50  5055.0 1554.65  5199.8 1554.22
  5245.4 1556.23  5404.0 1555.95  5420.9 1555.13  5499.2 1557.12  5562.6 1557.41
  5620.8 1559.83  5721.2 1561.88  5843.0 1563.02  5873.3 1564.29  6512.9 1574.91
#Mann=6,-1,0
  3413.8    0.16       0  3457.2     0.1       0  3614.9    0.05       0
  3757.1     0.1       0  4988.6    0.07       0  4994.6     0.1       0
Bank Sta=4988.6,4994.6
Exp/Cntr=0.3,0.1

Type RM Length L Ch R = 1,6408,984,984,984
BEGIN DESCRIPTION:
BASIN SPRING BRANCH 14.0
END DESCRIPTION:
XS GIS Cut Line= 2
      2848498.21     10099682.91      2846772.09     10099975.24
#Sta/Elev= 30
  4033.8 1558.06  4114.7 1557.84  4184.5 1556.26  4216.1 1556.66  4305.3 1554.01
  4500.1 1551.75  4581.2 1549.58  4607.1 1547.74  4762.2 1544.98  4926.1 1541.72
  4953.2 1544.04  4969.3 1543.70  4976.8 1542.36  4986.9 1538.45  4994.1 1538.19
  4996.8 1537.69  5000.1 1538.19  5037.6 1541.00  5057.9 1541.24  5085.0 1543.59
  5128.9 1544.61  5169.5 1544.41  5189.8 1542.51  5240.5 1544.80  5266.1 1543.61
  5353.8 1545.63  5483.9 1547.58  5502.5 1546.86  5628.4 1549.23  5784.5 1550.30
#Mann=6,-1,0
  4033.8     0.1       0  4762.2    0.05       0  4953.2     0.1       0
  4994.1    0.07       0  5000.1     0.1       0  5353.8    0.16       0
Bank Sta=4994.1,5000.1
Exp/Cntr=0.3,0.1

Type RM Length L Ch R = 1,5424,1284,1284,1284
BEGIN DESCRIPTION:
BASIN SPRING BRANCH 11.0
END DESCRIPTION:
XS GIS Cut Line= 2
      2848052.36     10098749.58      2846882.26     10099139.61
#Sta/Elev= 30
  4517.7 1540.26  4585.1 1540.02  4705.5 1537.02  4826.7 1535.87  4895.3 1534.28
  4926.9 1532.75  4958.5 1529.73  4964.5 1527.56  4993.1 1526.31  4995.9 1525.81
  4999.1 1526.31  5006.7 1526.55  5021.7 1528.79  5027.8 1531.03  5053.4 1531.16
  5079.7 1529.26  5091.0 1529.15  5143.0 1531.34  5206.2 1530.43  5274.7 1532.16
  5382.8 1531.96  5432.8 1533.30  5459.2 1532.77  5503.4 1533.68  5554.1 1535.31
  5559.3 1536.15  5617.3 1536.81  5660.2 1539.27  5723.5 1539.55  5751.1 1538.98
#Mann=5,-1,0
  4517.7     0.1       0  4993.1    0.07       0  4999.1     0.1       0
  5382.8    0.05       0  5503.4     0.1       0
Bank Sta=4993.1,4999.1
Exp/Cntr=0.3,0.1

Type RM Length L Ch R = 1,4140,906,906,906
BEGIN DESCRIPTION:
BASIN SPRING BRANCH 5.0
END DESCRIPTION:
XS GIS Cut Line= 2
      2847077.27     10097844.06      2846032.98     10098776.96
#Sta/Elev= 30
  4308.1 1529.78  4491.4 1528.18  4717.9 1521.87  4789.0 1516.84  4887.6 1507.31
  4923.3 1502.67  4951.2 1501.35  4998.3 1500.71  5001.1 1500.21  5004.3 1500.71
  5022.2 1503.60  5029.7 1503.87  5036.4 1505.49  5044.0 1505.57  5050.7 1506.69
  5064.9 1506.46  5085.8 1508.25  5121.7 1509.91  5128.4 1510.92  5171.0 1512.37
  5199.5 1512.43  5227.9 1514.27  5234.6 1515.56  5270.5 1518.52  5291.4 1522.89
  5355.0 1527.88  5397.6 1529.87  5482.9 1532.05  5511.3 1534.13  5708.4 1544.47
#Mann=3,-1,0
  4308.1     0.1       0  4998.3    0.07       0  5004.3     0.1       0
Bank Sta=4998.3,5004.3
Exp/Cntr=0.3,0.1

Type RM Length L Ch R = 1,3234,965,965,965
BEGIN DESCRIPTION:
BASIN SPRING BRANCH 6.0
END DESCRIPTION:
XS GIS Cut Line= 2
      2846547.92     10097467.93      2844947.48     10098219.44
#Sta/Elev= 30
  4267.1 1514.37  4338.9 1510.72  4435.7 1507.49  4475.8 1504.52  4595.4 1498.50
  4760.6 1494.56  4857.3 1493.61  4918.3 1492.08  4940.4 1490.33  4971.4 1485.09
  4991.2 1484.34  4994.0 1483.84  4997.2 1484.34  5017.0 1484.68  5039.8 1487.77
  5050.9 1490.10  5096.5 1494.88  5163.2 1497.89  5216.6 1499.77  5261.7 1500.33
  5338.1 1502.75  5449.7 1503.95  5512.6 1503.74  5578.8 1505.73  5668.2 1506.98
  5700.6 1506.66  5751.8 1508.46  5900.6 1515.52  5956.6 1517.75  6035.2 1519.81
#Mann=9,-1,0
  4267.1     0.1       0  4991.2    0.07       0  4997.2     0.1       0
  5163.2    0.16       0  5216.6     0.1       0  5578.8    0.16       0
  5668.2     0.1       0  5900.6    0.16       0  5956.6     0.1       0
Bank Sta=4991.2,4997.2
Exp/Cntr=0.3,0.1

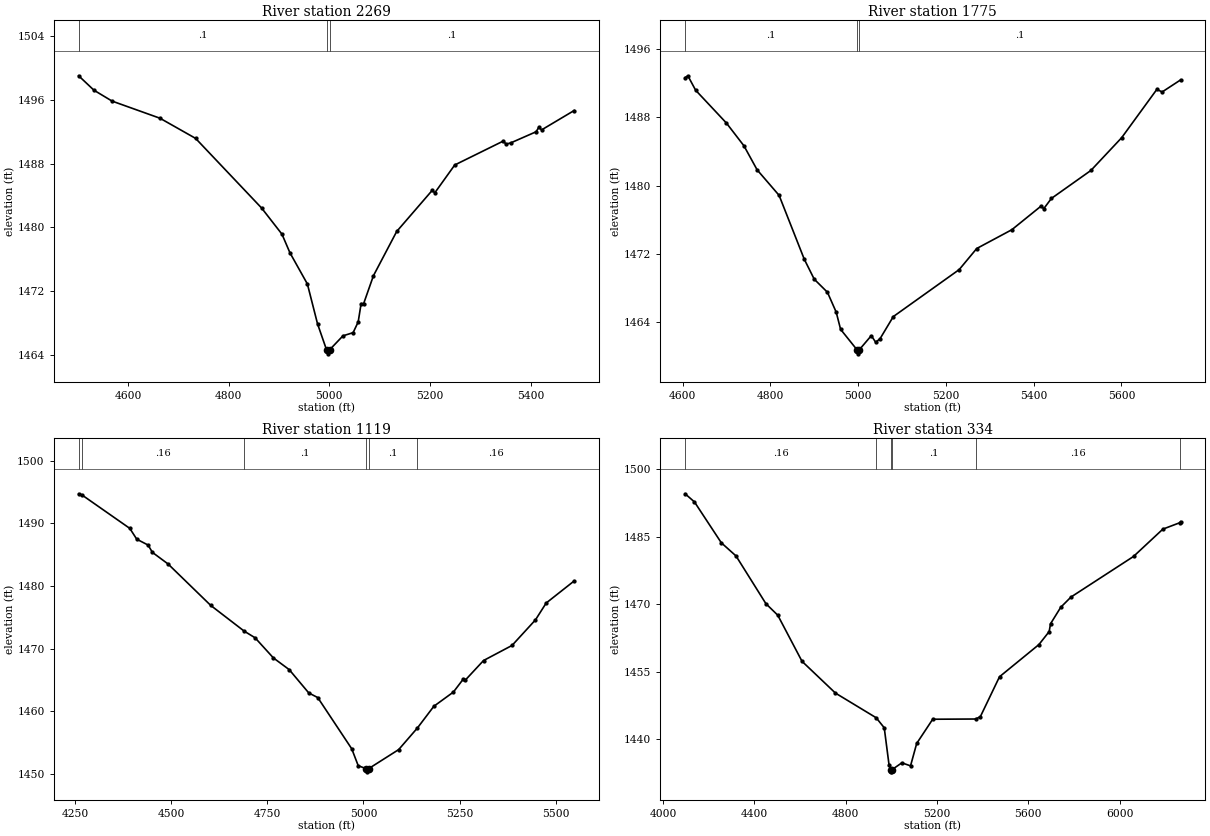
Type RM Length L Ch R = 1,2269,494,494,494
BEGIN DESCRIPTION:
BASIN SPRING BRANCH 4.0
END DESCRIPTION:
XS GIS Cut Line= 2
      2846408.59     10097008.23      2845433.49     10096868.93
#Sta/Elev= 30
  4501.6 1499.03  4532.0 1497.22  4568.1 1495.85  4663.3 1493.70  4734.1 1491.17
  4865.4 1482.42  4905.8 1479.14  4921.6 1476.81  4956.3 1472.89  4976.5 1467.88
  4994.4 1464.62  4997.1 1464.12  5000.4 1464.62  5027.0 1466.38  5047.2 1466.78
  5057.3 1468.13  5063.1 1470.43  5068.1 1470.42  5087.6 1473.93  5133.8 1479.48
  5204.5 1484.65  5209.5 1484.33  5249.2 1487.83  5345.9 1490.84  5351.0 1490.45
  5360.4 1490.60  5410.9 1492.00  5416.6 1492.59  5421.7 1492.23  5486.6 1494.67
#Mann=3,-1,0
  4501.6     0.1       0  4994.4    0.07       0  5000.4     0.1       0
Bank Sta=4994.4,5000.4
Exp/Cntr=0.3,0.1

Type RM Length L Ch R = 1,1775,656,656,656
BEGIN DESCRIPTION:
BASIN SPRING BRANCH 3.0
END DESCRIPTION:
XS GIS Cut Line= 2
      2846422.50     10096478.87      2845294.17     10096437.08
#Sta/Elev= 30
  4605.9 1492.63  4612.2 1492.85  4629.9 1491.16  4700.0 1487.32  4740.0 1484.65
  4770.0 1481.84  4820.1 1478.85  4877.4 1471.38  4900.1 1469.04  4930.2 1467.51
  4950.2 1465.18  4960.2 1463.17  4997.2 1460.80  5000.0 1460.30  5003.2 1460.80
  5030.2 1462.43  5040.2 1461.65  5050.2 1462.08  5080.3 1464.66  5230.4 1470.16
  5270.4 1472.63  5350.4 1474.83  5417.8 1477.63  5422.8 1477.27  5440.5 1478.49
  5530.6 1481.77  5600.6 1485.60  5680.7 1491.25  5693.0 1490.96  5735.0 1492.37
#Mann=3,-1,0
  4605.9     0.1       0  4997.2    0.07       0  5003.2     0.1       0
Bank Sta=4997.2,5003.2
Exp/Cntr=0.3,0.1

Type RM Length L Ch R = 1,1119,785,785,785
BEGIN DESCRIPTION:
BASIN SPRING BRANCH 2.0
END DESCRIPTION:
XS GIS Cut Line= 2
      2846687.16     10095684.83      2845419.50     10095921.65
#Sta/Elev= 30
  4258.8 1494.70  4266.8 1494.54  4391.9 1489.18  4410.1 1487.45  4439.5 1486.52
  4450.8 1485.35  4491.5 1483.50  4602.5 1476.89  4689.7 1472.78  4718.0 1471.72
  4765.6 1468.51  4806.8 1466.64  4857.7 1462.92  4881.1 1462.18  4969.6 1454.00
  4986.4 1451.31  5007.3 1450.83  5010.0 1450.33  5013.3 1450.83  5091.7 1453.88
  5140.6 1457.34  5183.2 1460.79  5234.1 1463.06  5259.9 1465.14  5265.0 1464.96
  5312.5 1468.09  5386.7 1470.50  5447.7 1474.58  5475.6 1477.27  5548.4 1480.79
#Mann=6,-1,0
  4258.8     0.1       0  4266.8    0.16       0  4689.7     0.1       0
  5007.3    0.07       0  5013.3     0.1       0  5140.6    0.16       0
Bank Sta=5007.3,5013.3
Exp/Cntr=0.3,0.1

Type RM Length L Ch R = 1,334,0,0,0
BEGIN DESCRIPTION:
BASIN SPRING BRANCH 1.0
END DESCRIPTION:
XS GIS Cut Line= 4
      2846673.28     10095406.22      2846046.39     10095016.15
      2845600.61     10095155.46      2845168.86     10096018.95
#Sta/Elev= 30
  4096.7 1494.49  4137.7 1492.68  4255.5 1483.60  4319.7 1480.69  4450.7 1470.09
  4502.6 1467.53  4608.9 1457.29  4755.2 1450.24  4933.7 1444.76  4969.1 1442.53
  4990.0 1434.33  4997.5 1433.25  5000.2 1432.75  5003.5 1433.25  5046.2 1434.75
  5084.3 1434.08  5111.2 1439.05  5181.4 1444.43  5369.8 1444.48  5390.2 1445.01
  5474.0 1453.86  5646.7 1461.01  5691.5 1463.89  5697.6 1465.63  5742.3 1469.29
  5787.1 1471.56  6061.0 1480.57  6189.6 1486.64  6265.2 1488.09  6267.5 1488.30
#Mann=6,-1,0
  4096.7    0.16       0  4933.7     0.1       0  4997.5    0.07       0
  5003.5     0.1       0  5369.8    0.16       0  6265.2     0.1       0
Bank Sta=4997.5,5003.5
Exp/Cntr=0.3,0.1

Chan Stop Cuts=-1