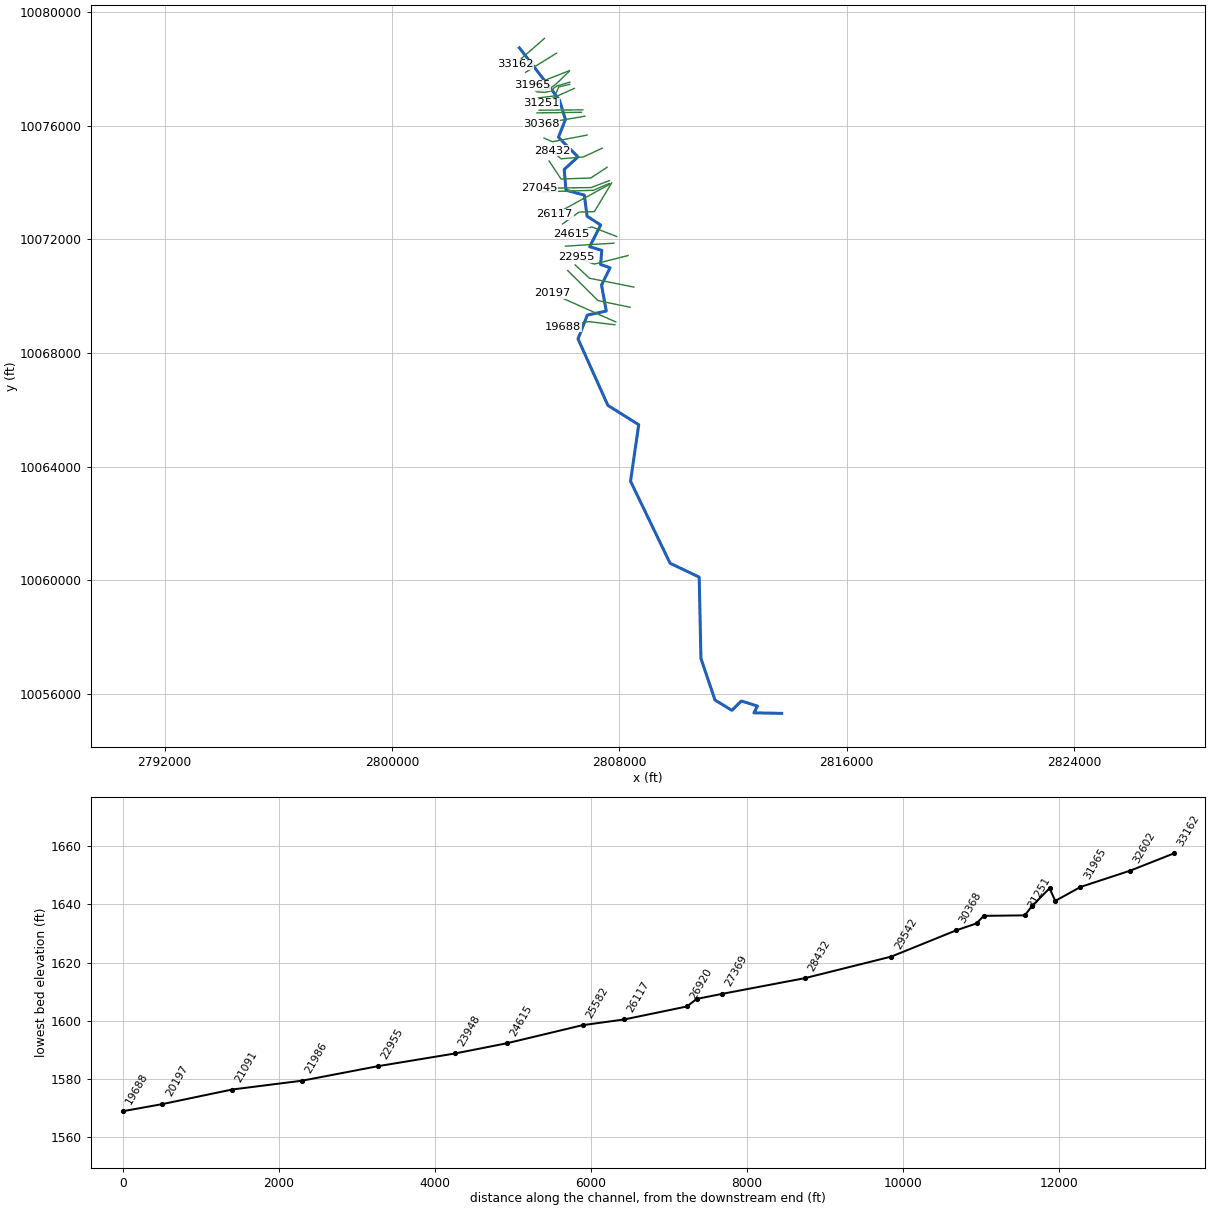
--- CAVE CREEK.prj (project) ---

Proj Title=CAVE CREEK Base Level Engineering
Current Plan=p01
Default Exp/Contr=0.3,0.1
English Units
Geom File=g01
Flow File=f01
Plan File=p01
Y Axis Title=Elevation
X Axis Title(PF)=Main Channel Distance
X Axis Title(XS)=Station
BEGIN DESCRIPTION:
CAVE CREEK
END DESCRIPTION:
DSS Export Rating Curves= 0
DSS Export Rating Curve Sorted= 0
DSS Export Volume Flow Curves= 0
DXF OffsetX= 0
DXF OffsetY= 0
DXF ScaleX= 1
DXF ScaleY= 10

--- CAVE CREEK.p01 (plan) ---

Plan Title=Multiple Run
Short Identifier=Multiple
Geom File=g01
Flow File=f01
Subcritical Flow
K Sum by GR= 0
Std Step Tol= 0.01
Critical Tol= 0.01
Num of Std Step Trials= 20
Max Error Tol= 0.3
Flow Tol Ratio= 0.001
Split Flow NTrial= 30
Split Flow Tol= 0.02
Split Flow Ratio= 0.02
Log Output Level= 0
Friction Slope Method= 1
Unsteady Friction Slope Method= 2
Unsteady Bridges Friction Slope Method= 1
Parabolic Critical Depth
Global Vel Dist=  1 , 1 , 1
Global Log Level= 0
CheckData=True
Encroach Param= -1, 0, 0, 0
BEGIN DESCRIPTION:
Multiple Run
END DESCRIPTION:

--- CAVE CREEK.f01 (steady flow) ---

Flow Title=Multiple
Program Version=4.10
Number of Profiles= 7
Profile Names=10-year,25-year,50-year,1pct_min,100-year,1pct_plu,500-year
River Rch & RM=CAVE CREEK,Reach-1         ,33162
    1132    1661    2126    1991    2692    3641    4335
River Rch & RM=CAVE CREEK,Reach-1         ,27045
    2156    3254    4243    4036    5458    7382    9077
River Rch & RM=CAVE CREEK,Reach-1         ,20197
    2427    3683    4821    4602    6224    8417   10423
River Rch & RM=CAVE CREEK,Reach-1         ,19688
    2512    3808    4979    4748    6421    8684   10729
River Rch & RM=CAVE CREEK,Reach-1         ,14131
    3952    6107    8090    7806   10557   14277   18062
River Rch & RM=CAVE CREEK,Reach-1         ,13599
    3952    6107    8090    7806   10557   14277   18062
River Rch & RM=CAVE CREEK,Reach-1         ,12444
    4437    6875    9123    8814   11920   16120   20446
River Rch & RM=CAVE CREEK,Reach-1         ,6849
    4497    6961    9230    8910   12050   16296   20635
River Rch & RM=CAVE CREEK,Reach-1         ,1906
    4636    7175    9513    9181   12416   16792   21252
Boundary for River Rch & Prof#=CAVE CREEK,Reach-1         , 1
Up Type= 0
Dn Type= 3
Dn Slope=0.0056
Boundary for River Rch & Prof#=CAVE CREEK,Reach-1         , 2
Up Type= 0
Dn Type= 3
Dn Slope=0.0056
Boundary for River Rch & Prof#=CAVE CREEK,Reach-1         , 3
Up Type= 0
Dn Type= 3
Dn Slope=0.0056
Boundary for River Rch & Prof#=CAVE CREEK,Reach-1         , 4
Up Type= 0
Dn Type= 3
Dn Slope=0.0056
Boundary for River Rch & Prof#=CAVE CREEK,Reach-1         , 5
Up Type= 0
Dn Type= 3
Dn Slope=0.0056
Boundary for River Rch & Prof#=CAVE CREEK,Reach-1         , 6
Up Type= 0
Dn Type= 3
Dn Slope=0.0056
Boundary for River Rch & Prof#=CAVE CREEK,Reach-1         , 7
Up Type= 0
Dn Type= 3
Dn Slope=0.0056
DSS Import GetInterval= 0
DSS Import GetPeak= 0
DSS Import FillOption= 0

--- CAVE CREEK.g01 (geometry) ---

Geom Title=Existing Conditions
Program Version=4.10

River Reach=CAVE CREEK      ,Reach-1
Reach XY= 30
      2804488.47     10078743.73      2805896.95      10076908.1
       2806107.4     10076218.72      2805861.47     10075595.05
      2806547.61     10074903.21      2806063.93     10074461.79
      2806126.67     10073730.52      2806771.79     10073560.01
      2806870.41     10072814.36      2807348.23     10072506.61
      2806960.47     10071739.77       2807387.6     10071612.91
      2807344.55     10071116.66      2807676.87     10070998.11
      2807378.57     10070389.59      2807544.84     10069475.04
      2806877.65     10069333.35      2806551.06     10068494.92
        2807601.     10066154.64      2808686.32     10065472.91
      2808398.47     10063483.73      2809790.39     10060594.53
      2810814.06     10060106.62      2810876.98     10057237.99
      2811369.87      10055779.4      2811964.63     10055413.74
      2812298.25      10055743.6      2812864.28     10055565.34
      2812739.63     10055327.14      2813717.09     10055307.55

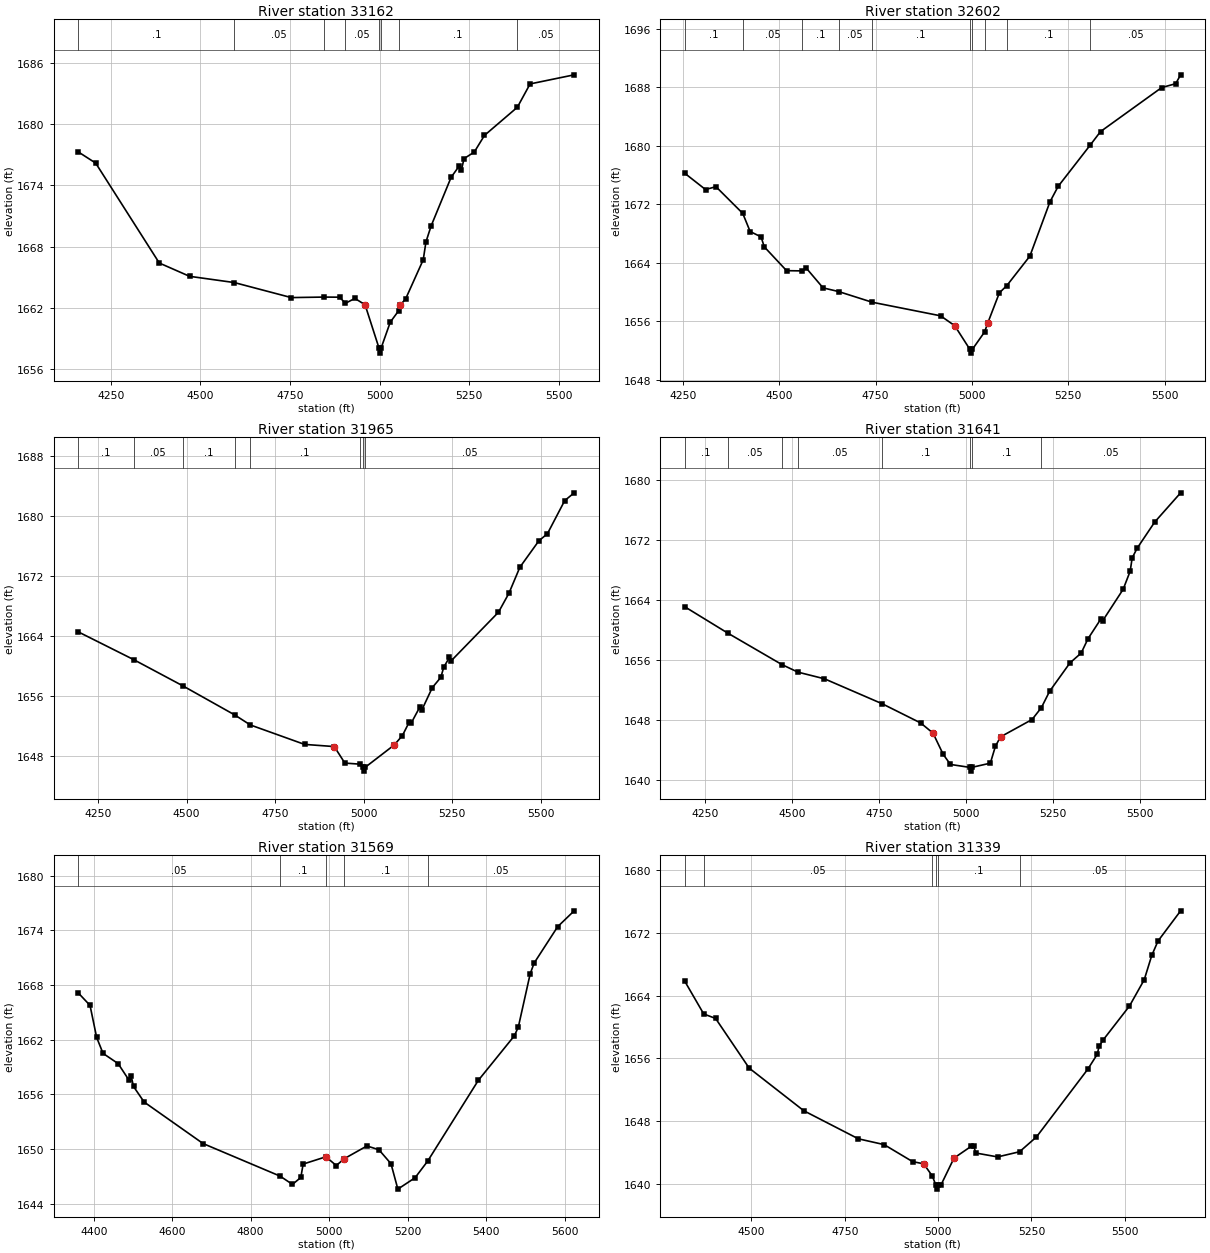
Type RM Length L Ch R = 1 ,33162   ,560,560,560
BEGIN DESCRIPTION:
CAVE CREEK 63.0
END DESCRIPTION:
XS GIS Cut Line= 2
      2805371.34     10079079.38      2804330.15     10078168.33
#Sta/Elev= 30
  4159.4 1677.26  4207.8 1676.17  4385.3  1666.4  4469.8  1665.1  4594.5 1664.49
  4753.6 1663.02  4843.9 1663.07  4888.4 1663.06  4904.5 1662.46  4931.1 1662.94
  4959.5 1662.32  4998.3 1658.09    5001 1657.59  5004.3 1658.09  5029.8 1660.62
  5053.3 1661.74  5058.2 1662.32  5072.5 1662.88  5121.8 1666.72  5129.4 1668.47
  5143.7 1670.02  5199.7 1674.79  5221.5 1675.85  5228.1 1675.47  5235.7 1676.61
  5264.2 1677.25  5292.7 1678.88  5384.4 1681.63  5419.9 1683.91  5542.9  1684.8
#Mann= 8 ,-1 , 0
  4159.4      .1       0  4594.5     .05       0  4843.9      .1       0
  4904.5     .05       0  4998.3    .035       0  5004.3     .05       0
  5053.3      .1       0  5384.4     .05       0
Bank Sta=4959.5,5058.2
XS Rating Curve= 0 ,0
Exp/Cntr=0.3,0.1

Type RM Length L Ch R = 1 ,32602   ,637,637,637
BEGIN DESCRIPTION:
CAVE CREEK 62.0
END DESCRIPTION:
XS GIS Cut Line= 2
      2805796.65     10078558.51      2804703.21     10077881.61
#Sta/Elev= 30
  4255.3 1676.23    4309 1674.01  4336.1  1674.4  4405.6 1670.75  4424.8 1668.27
  4453.1 1667.54  4461.4 1666.18  4519.3 1662.92  4559.8 1662.89  4570.7 1663.25
  4613.9 1660.57    4654 1660.07  4741.1 1658.61  4918.7 1656.75  4955.4  1655.4
  4994.9 1652.15  4997.7 1651.65  5000.9 1652.15  5032.8 1654.54  5041.1 1655.77
  5071.2 1659.89  5090.5 1660.88  5150.3 1664.91  5202.4 1672.33  5223.6 1674.44
  5307.3 1680.12  5333.5 1681.93  5491.9 1687.94  5528.5 1688.48  5541.3 1689.69
#Mann= 10 ,-1 , 0
  4255.3      .1       0  4405.6     .05       0  4559.8      .1       0
    4654     .05       0  4741.1      .1       0  4994.9     .07       0
  5000.9      .1       0  5032.8     .05       0  5090.5      .1       0
  5307.3     .05       0
Bank Sta=4955.4,5041.1
XS Rating Curve= 0 ,0
Exp/Cntr=0.3,0.1

Type RM Length L Ch R = 1 ,31965   ,324,324,324
BEGIN DESCRIPTION:
CAVE CREEK 60.0
END DESCRIPTION:
XS GIS Cut Line= 2
      2806248.02     10077942.18      2804945.92     10077430.03
#Sta/Elev= 30
  4194.5 1664.57  4350.6 1660.88  4489.7 1657.38  4635.9 1653.51  4679.8 1652.18
  4832.8 1649.59  4916.8  1649.3  4946.6  1647.1  4988.8 1646.96  4997.8 1646.53
  5000.5 1646.03  5003.8 1646.53  5085.9 1649.51  5109.1 1650.77  5128.2 1652.56
  5133.5  1652.4  5157.9 1654.54  5163.3 1654.12  5193.4 1657.15  5217.5 1658.52
  5225.6 1659.86  5241.9 1661.19  5247.3 1660.75  5380.1 1667.19  5409.8 1669.73
  5440.5 1673.18  5494.3 1676.71  5518.2 1677.64    5567 1682.05  5593.7 1683.09
#Mann= 8 ,-1 , 0
  4194.5      .1       0  4350.6     .05       0  4489.7      .1       0
  4635.9     .05       0  4679.8      .1       0  4988.8     .05       0
  4997.8    .035       0  5003.8     .05       0
Bank Sta=4916.8,5085.9
XS Rating Curve= 0 ,0
Exp/Cntr=0.3,0.1

Type RM Length L Ch R = 1 ,31641   ,72,72,72
BEGIN DESCRIPTION:
Mapping XS 4e0e7034
END DESCRIPTION:
XS GIS Cut Line= 4
      2806237.26     10077912.33      2805788.01     10077480.44
      2805529.77      10077287.3      2805054.51     10077233.05
#Sta/Elev= 30
  4192.6 1663.11  4315.8 1659.61  4471.7 1655.41  4517.4 1654.41  4593.8 1653.52
  4759.9 1650.19  4870.1 1647.64  4905.5 1646.29  4934.7 1643.46  4955.5 1642.12
  5010.9 1641.73  5013.6 1641.23  5016.9 1641.73  5070.1 1642.29  5084.7 1644.54
  5099.3 1645.79  5189.9  1648.1  5216.7 1649.68  5240.2 1651.85  5298.8 1655.64
  5330.8 1656.94  5350.9 1658.88  5388.2 1661.53  5393.2 1661.28  5451.6 1665.44
  5471.7 1667.85  5477.5 1669.62  5491.8 1670.91  5542.2 1674.39  5616.6 1678.28
#Mann= 8 ,-1 , 0
  4192.6      .1       0  4315.8     .05       0  4471.7      .1       0
  4517.4     .05       0  4759.9      .1       0  5010.9     .07       0
  5016.9      .1       0  5216.7     .05       0
Bank Sta=4905.5,5099.3
XS Rating Curve= 0 ,0
Exp/Cntr=0.3,0.1

Type RM Length L Ch R = 1 ,31569   ,230,230,230
BEGIN DESCRIPTION:
Mapping XS 1d23b8d7
END DESCRIPTION:
XS GIS Cut Line= 6
      2806263.26     10077536.86       2805818.4     10077404.49
      2805692.53     10077326.36      2805642.61     10077233.05
      2805380.03     10077176.62      2805106.54     10077193.99
#Sta/Elev= 30
  4360.8 1667.13  4390.6 1665.77  4407.5 1662.25  4423.8  1660.5  4462.2 1659.38
  4490.1 1657.55  4495.4 1658.01  4501.4 1656.87  4528.5 1655.16  4678.8  1650.6
  4874.9 1647.03  4906.5 1646.12  4927.8 1646.88  4933.7 1648.35  4991.8 1649.15
  5018.1 1648.19  5038.9 1648.95  5096.3 1650.34  5126.9 1649.92  5157.6 1648.39
  5175.1  1645.6    5219 1646.85    5251 1648.67  5380.3 1657.55  5472.2 1662.44
  5482.2 1663.41  5512.3 1669.23  5522.3 1670.41  5582.4 1674.41  5624.4 1676.15
#Mann= 5 ,-1 , 0
  4360.8     .05       0  4874.9      .1       0  4991.8     .07       0
  5038.9      .1       0    5251     .05       0
#Block Obstruct= 2 , 0
         4987.22 1648.19 5064.53         1648.17
Bank Sta=4991.8,5038.9
XS Rating Curve= 0 ,0
Exp/Cntr=0.3,0.1

Type RM Length L Ch R = 1 ,31339   ,88,88,88
BEGIN DESCRIPTION:
Mapping XS eaa1e738
END DESCRIPTION:
XS GIS Cut Line= 4
      2806258.91     10077458.74      2805870.48      10077367.6
      2805733.76     10077052.93      2805151.69     10076981.52
#Sta/Elev= 30
  4321.3 1665.84    4372 1661.67  4403.8  1661.1  4493.8 1654.76  4640.2 1649.32
  4786.3 1645.74  4855.3    1645  4931.6 1642.83  4961.3 1642.55  4984.4    1641
  4994.1 1639.82  4996.8 1639.32  5000.1 1639.82    5008 1639.88  5042.6 1643.28
  5088.8 1644.79  5095.8 1644.77  5100.9 1643.93  5159.4 1643.43  5218.3 1644.09
  5263.6 1645.98  5401.2 1654.63  5426.3 1656.52  5431.4 1657.54  5441.5 1658.31
  5512.7 1662.68  5552.3 1666.04  5572.4 1669.13  5589.1 1670.97  5649.8 1674.83
#Mann= 6 ,-1 , 0
  4321.3      .1       0    4372     .05       0  4984.4      .1       0
  4994.1     .07       0  5000.1      .1       0  5218.3     .05       0
Bank Sta=4961.3,5042.6
XS Rating Curve= 0 ,0
Exp/Cntr=0.3,0.1

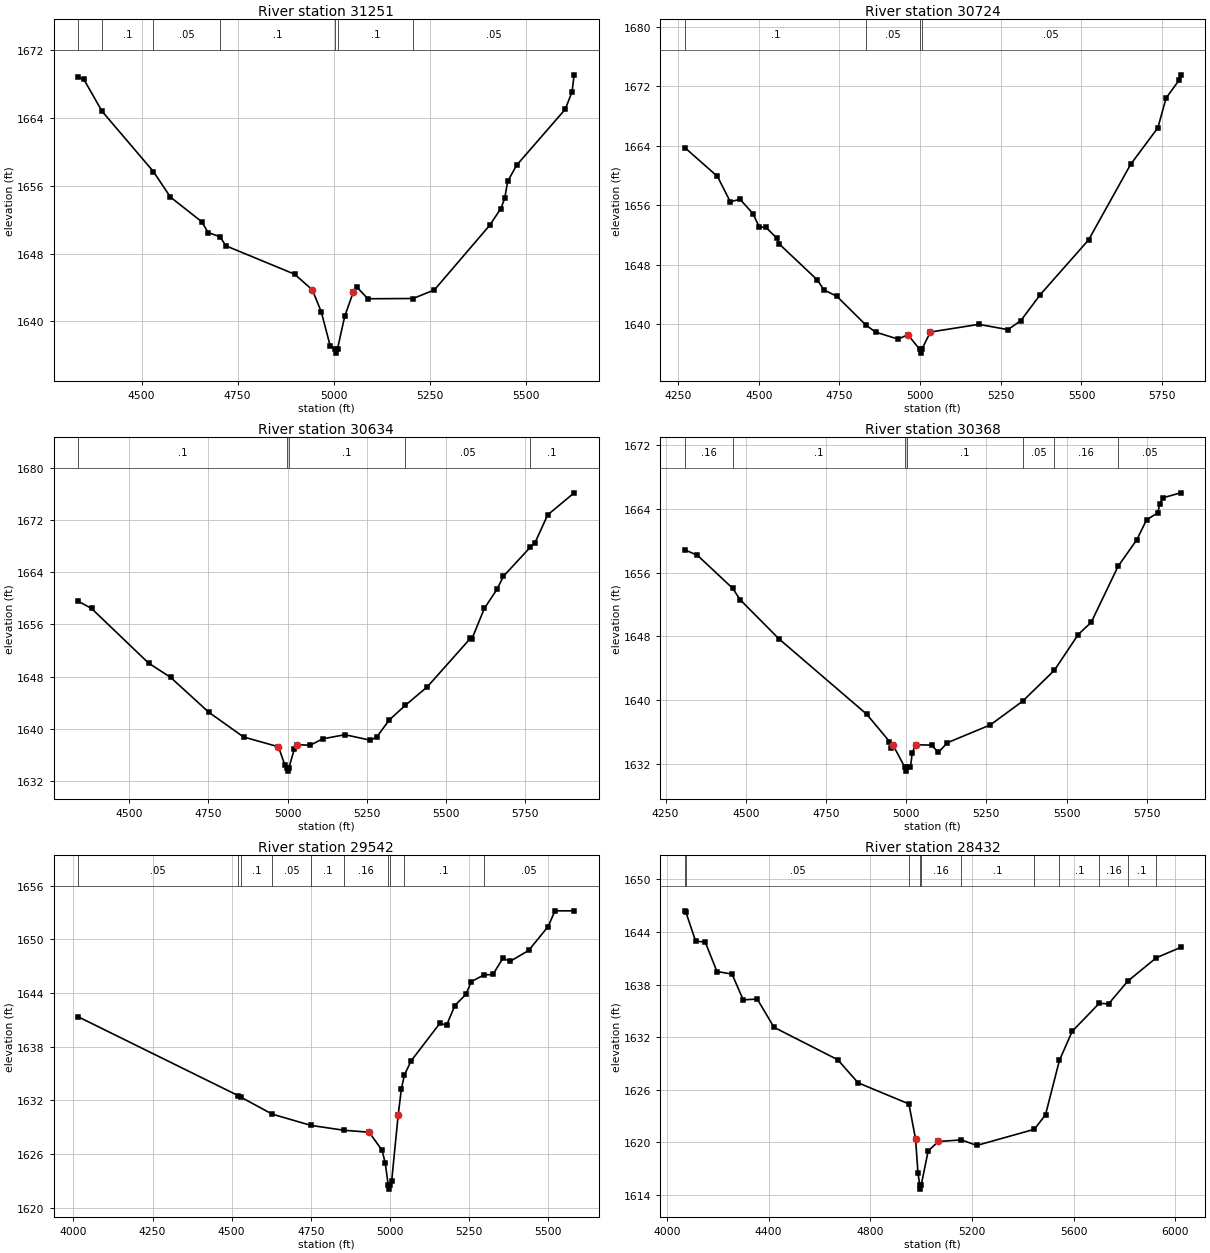
Type RM Length L Ch R = 1 ,31251   ,527,527,527
BEGIN DESCRIPTION:
CAVE CREEK 59.0
END DESCRIPTION:
XS GIS Cut Line= 2
      2806421.63     10077317.18      2805243.42     10076788.72
#Sta/Elev= 30
  4335.2 1668.79  4349.6 1668.53    4397 1664.77  4530.6 1657.67    4575 1654.66
  4656.5 1651.75  4673.2 1650.48  4704.1 1649.98  4719.6 1648.91  4898.3 1645.57
  4944.6 1643.72  4967.8 1641.14    4991 1637.13  5004.2 1636.76    5007 1636.26
  5010.2 1636.76  5029.1 1640.63  5051.1 1643.43  5060.5 1644.05  5089.2 1642.67
  5206.9  1642.7  5262.4 1643.71  5406.9 1651.35  5435.6 1653.31  5445.6 1654.49
  5453.3  1656.5  5476.4  1658.4  5603.3 1665.01    5621 1667.07  5626.5 1669.07
#Mann= 7 ,-1 , 0
  4335.2     .05       0    4397      .1       0  4530.6     .05       0
  4704.1      .1       0  5004.2     .07       0  5010.2      .1       0
  5206.9     .05       0
Bank Sta=4944.6,5051.1
XS Rating Curve= 0 ,0
Exp/Cntr=0.3,0.1

Type RM Length L Ch R = 1 ,30724   ,90,90,90
BEGIN DESCRIPTION:
Mapping XS 652830ed
END DESCRIPTION:
XS GIS Cut Line= 2
      2806719.58     10076561.15      2805183.34     10076548.13
#Sta/Elev= 30
  4270.9 1663.73    4372 1659.86    4412 1656.44    4442 1656.79    4482 1654.85
    4502 1653.02    4522 1653.03  4556.6 1651.52    4562 1650.83    4682 1645.91
    4702 1644.59    4742 1643.74    4832 1639.87    4862 1638.92    4932 1637.97
    4962 1638.57    4999 1636.59  5001.8 1636.09    5005 1636.59    5032 1638.93
  5182.1 1639.96  5272.1 1639.25  5312.1 1640.46  5372.1 1643.95  5522.1 1651.32
  5652.1 1661.46  5736.7  1666.4  5762.1 1670.39  5802.1 1672.78  5807.2 1673.52
#Mann= 4 ,-1 , 0
  4270.9      .1       0    4832     .05       0    4999     .04       0
    5005     .05       0
Bank Sta=4962,5032
XS Rating Curve= 0 ,0
Exp/Cntr=0.3,0.1

Type RM Length L Ch R = 1 ,30634   ,266,266,266
BEGIN DESCRIPTION:
CAVE CREEK 57.0
END DESCRIPTION:
XS GIS Cut Line= 2
      2806670.07     10076475.21        2805105.     10076454.38
#Sta/Elev= 30
  4339.3 1659.53  4380.9 1658.43  4560.9 1650.07  4630.9 1647.86  4750.9 1642.54
  4860.9 1638.74    4971 1637.24    4991 1634.48    4998 1634.01  5000.7 1633.51
    5004 1634.01    5021 1636.86    5031 1637.57    5071 1637.47    5111 1638.46
    5181 1639.09    5261 1638.25    5281 1638.71    5321 1641.36  5371.5 1643.59
    5441 1646.43  5576.7 1653.84  5581.7 1653.76    5621 1658.44    5661 1661.37
    5681 1663.35    5766 1667.82    5781 1668.52    5821 1672.77  5904.5 1676.15
#Mann= 5 ,-1 , 0
  4339.3      .1       0    4998     .07       0    5004      .1       0
  5371.5     .05       0    5766      .1       0
Bank Sta=4971,5031
XS Rating Curve= 0 ,0
Exp/Cntr=0.3,0.1

Type RM Length L Ch R = 1 ,30368   ,826,826,826
BEGIN DESCRIPTION:
CAVE CREEK 56.0
END DESCRIPTION:
XS GIS Cut Line= 2
      2806787.34      10076337.2      2805263.84     10076076.77
#Sta/Elev= 30
  4310.1 1658.86  4349.5 1658.17  4459.2 1654.03  4482.8 1652.58  4603.2 1647.69
  4877.1 1638.21  4948.1 1634.78  4953.5 1633.96  4958.6 1634.38  4995.8 1631.56
  4998.6 1631.06  5001.8 1631.56  5013.6 1631.59  5019.1 1633.36  5029.3 1634.38
    5080 1634.32  5100.3 1633.41  5128.8 1634.63  5262.6 1636.87  5362.8 1639.83
  5462.2 1643.73  5536.5 1648.22  5577.1 1649.76  5660.9  1656.8  5719.1 1660.12
  5749.6 1662.63  5784.9 1663.52  5790.1 1664.58  5800.3 1665.39  5855.7 1666.02
#Mann= 7 ,-1 , 0
  4310.1     .16       0  4459.2      .1       0  4995.8     .07       0
  5001.8      .1       0  5362.8     .05       0  5462.2     .16       0
  5660.9     .05       0
Bank Sta=4958.6,5029.3
XS Rating Curve= 0 ,0
Exp/Cntr=0.3,0.1

Type RM Length L Ch R = 1 ,29542   ,1110,1110,1110
BEGIN DESCRIPTION:
CAVE CREEK 54.0
END DESCRIPTION:
XS GIS Cut Line= 3
       2806870.6     10075673.12      2805649.27     10075438.75
       2805352.9     10075566.14
#Sta/Elev= 30
  4015.7 1641.33    4520 1632.54  4528.5 1632.37  4628.1 1630.46  4750.6  1629.2
  4854.3 1628.66  4934.3 1628.44    4975 1626.43  4985.2 1624.99  4994.3 1622.58
    4997 1622.08  5000.3 1622.58  5005.6 1623.03  5025.9 1630.31  5036.1 1633.28
  5045.8 1634.85  5066.7  1636.4  5158.3 1640.64  5178.7 1640.38  5205.2  1642.6
  5239.8 1643.84  5257.2 1645.27  5296.6 1646.01  5325.5 1646.07  5356.6 1647.87
  5379.9 1647.54  5438.1 1648.75  5499.6 1651.42  5521.4 1653.18  5581.9 1653.18
#Mann= 10 ,-1 , 0
  4015.7     .05       0    4520     .16       0  4528.5      .1       0
  4628.1     .05       0  4750.6      .1       0  4854.3     .16       0
  4994.3     .07       0  5000.3     .16       0  5045.8      .1       0
  5296.6     .05       0
Bank Sta=4934.3,5025.9
XS Rating Curve= 0 ,0
Exp/Cntr=0.3,0.1

Type RM Length L Ch R = 1 ,28432   ,1063,1063,1063
BEGIN DESCRIPTION:
CAVE CREEK 52.0
END DESCRIPTION:
XS GIS Cut Line= 4
      2807407.12     10075212.21      2806735.21      10074902.3
      2805953.96     10074837.19      2805632.26     10075117.38
#Sta/Elev= 30
    4070 1646.42  4074.5 1646.25  4112.6 1642.96  4150.5 1642.85  4196.4 1639.49
  4255.7  1639.2  4299.8 1636.25  4354.8 1636.35  4420.9 1633.12  4671.9 1629.41
  4751.8 1626.78  4951.6 1624.37  4977.8 1620.36  4987.3 1616.46  4994.3 1615.14
  4997.1 1614.64  5000.3 1615.14  5027.4 1619.01  5067.6 1620.08  5158.1 1620.26
  5218.6 1619.63  5444.9 1621.47    5489 1623.13  5543.6 1629.33  5593.9 1632.66
  5700.6 1635.87  5736.8 1635.78  5812.5 1638.39  5924.8 1641.06  6020.5 1642.24
#Mann= 11 ,-1 , 0
    4070      .1       0  4074.5     .05       0  4951.6     .16       0
  4994.3     .07       0  5000.3     .16       0  5158.1      .1       0
  5444.9     .16       0  5543.6      .1       0  5700.6     .16       0
  5812.5      .1       0  5924.8     .05       0
Bank Sta=4977.8,5067.6
XS Rating Curve= 0 ,0
Exp/Cntr=0.3,0.1

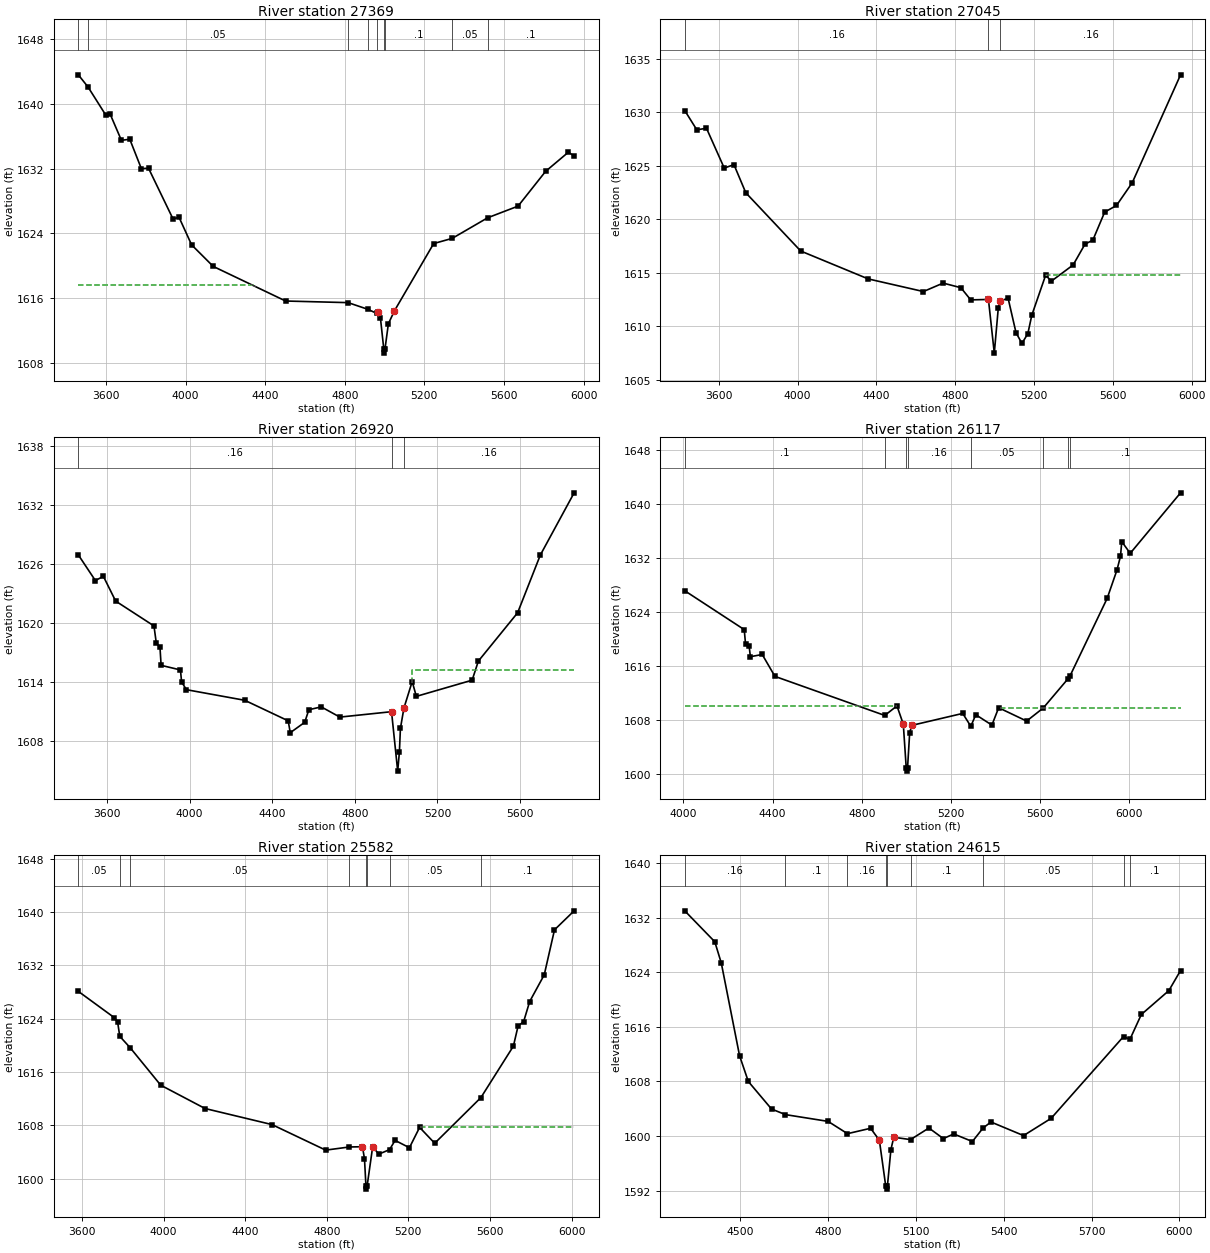
Type RM Length L Ch R = 1 ,27369   ,324,324,324
BEGIN DESCRIPTION:
CAVE CREEK 51.0
END DESCRIPTION:
XS GIS Cut Line= 4
      2807573.73      10074537.7      2806995.63     10074160.11
      2805953.96     10074126.25      2805534.81     10074758.89
#Sta/Elev= 30
  3461.2 1643.56  3509.9 1642.06  3598.9  1638.6  3620.3 1638.76  3677.6 1635.48
  3719.8 1635.61    3778 1631.98  3813.9 1632.04    3937 1625.78  3967.3 1625.98
  4030.5 1622.58  4139.1 1619.92    4503 1615.65  4817.2 1615.45  4915.8 1614.63
  4961.1 1614.12  4969.3 1614.27  4979.3 1613.58  4996.3 1609.72  4999.1 1609.22
  5002.3 1609.72  5019.3 1612.84  5049.3 1614.42    5247 1622.74  5340.2 1623.38
  5518.2 1625.92  5671.1 1627.36  5809.5 1631.65  5923.8 1634.01  5952.8 1633.55
#Mann= 9 ,-1 , 0
  3461.2      .1       0  3509.9     .05       0  4817.2      .1       0
  4915.8     .16       0  4961.1      .1       0  4996.3     .07       0
  5002.3      .1       0  5340.2     .05       0  5518.2      .1       0
#XS Ineff= 2 , 0
         4351.54 1617.64
Permanent Ineff=
       F       F
Bank Sta=4969.3,5049.3
XS Rating Curve= 0 ,0
Exp/Cntr=0.3,0.1

Type RM Length L Ch R = 1 ,27045   ,125,125,125
BEGIN DESCRIPTION:
Mapping XS 578c362a
END DESCRIPTION:
XS GIS Cut Line= 3
      2807654.52     10074068.98      2807016.46     10073824.17
      2805183.33     10073800.74
#Sta/Elev= 30
  3427.2 1630.17  3488.2 1628.37  3537.5 1628.51  3627.6 1624.79  3676.9 1625.11
    3737 1622.48  4015.8 1617.03  4358.6 1614.42  4638.7 1613.24  4738.7 1614.03
  4828.7  1613.6  4878.7 1612.46  4968.7  1612.5  4998.4 1607.48  5018.7  1611.7
  5028.7 1612.38  5068.7  1612.6  5108.7 1609.39  5138.7 1608.39  5168.7  1609.3
  5188.7 1611.02  5258.7 1614.75  5288.7 1614.22  5398.7 1615.73  5458.7 1617.67
  5498.7 1618.05  5558.7 1620.67  5618.7 1621.29  5698.7 1623.42  5943.9 1633.51
#Mann= 3 , 0 , 0
  3427.2     .16       0  4968.7     .07       0  5028.7     .16       0
#XS Ineff= 2 , 0
         4740.58 1614.02 5261.79         1614.79
Permanent Ineff=
       F       F
Bank Sta=4968.7,5028.7
XS Rating Curve= 0 ,0
Exp/Cntr=0.3,0.1

Type RM Length L Ch R = 1 ,26920   ,803,803,803
BEGIN DESCRIPTION:
CAVE CREEK 50.0
END DESCRIPTION:
XS GIS Cut Line= 3
      2807644.07      10073967.4      2807094.58     10073727.82
      2805295.07     10073673.13
#Sta/Elev= 30
  3461.6  1626.9  3544.1 1624.29  3582.8 1624.72  3642.3  1622.2  3827.7 1619.67
  3838.8 1617.96  3856.8 1617.49  3862.3 1615.66  3955.9 1615.19  3961.4 1613.97
  3984.8 1613.18  4267.3  1612.1  4477.4 1610.01  4487.4  1608.8  4557.4 1609.86
  4577.4 1611.14  4637.4 1611.43  4727.5 1610.39  4977.6 1610.94  5007.4 1604.89
  5015.6 1606.82  5020.6 1609.24  5037.6 1611.31  5077.6 1614.01  5097.6  1612.5
  5367.8 1614.15  5397.8 1616.09  5587.9 1621.01  5697.9 1626.89  5861.4 1633.22
#Mann= 3 , 0 , 0
  3461.6     .16       0  4977.6     .07       0  5037.6     .16       0
#XS Ineff= 2 , 0
                         5074.97         1615.22
Permanent Ineff=
       F       F
Bank Sta=4977.6,5037.6
XS Rating Curve= 0 ,0
Exp/Cntr=0.3,0.1

Type RM Length L Ch R = 1 ,26117   ,535,535,535
BEGIN DESCRIPTION:
CAVE CREEK 49.0
END DESCRIPTION:
XS GIS Cut Line= 2
      2807683.12     10073949.17      2805733.07     10072881.72
#Sta/Elev= 30
  4006.2 1627.11  4272.9 1621.36  4278.6 1619.27  4294.7 1618.98  4300.4 1617.35
  4353.5 1617.68  4410.5 1614.44    4903 1608.66  4957.7 1610.07  4986.1 1607.37
  4999.2 1600.92  5001.9 1600.42  5005.2 1600.92  5014.7  1606.1    5024 1607.19
  5252.6 1608.96  5288.8 1607.05  5311.1 1608.77  5383.4 1607.23  5413.7  1609.8
  5539.1 1607.83  5613.3 1609.75  5723.2 1614.03  5734.1 1614.54  5900.3 1625.99
  5943.9 1630.15    5960 1632.22  5965.7 1634.38  6003.6 1632.65  6229.3  1641.6
#Mann= 8 ,-1 , 0
  4006.2      .1       0    4903     .16       0  4999.2     .07       0
  5005.2     .16       0  5288.8     .05       0  5613.3      .1       0
  5723.2     .16       0  5734.1      .1       0
#XS Ineff= 2 , 0
         4958.42 1610.07 5419.06         1609.83
Permanent Ineff=
       F       F
Bank Sta=4986.1,5024
XS Rating Curve= 0 ,0
Exp/Cntr=0.3,0.1

Type RM Length L Ch R = 1 ,25582   ,967,967,967
BEGIN DESCRIPTION:
CAVE CREEK 47.0
END DESCRIPTION:
XS GIS Cut Line= 4
      2807732.44     10073983.89      2807124.78     10072976.92
      2806586.59     10072959.55      2806005.02     10072542.91
#Sta/Elev= 30
  3582.5 1628.11  3759.2 1624.16  3774.7 1623.59  3785.6 1621.37  3836.5 1619.66
  3986.3 1614.04  4203.7 1610.54  4531.7 1608.13  4794.9  1604.3  4910.5 1604.77
    4975 1604.81    4985 1603.01  4992.1 1598.95  4994.8 1598.45  4998.1 1598.95
  5025.1  1604.8  5055.1  1603.7  5107.7 1604.37  5135.1 1605.76  5205.2 1604.66
  5255.2 1607.71  5329.2 1605.33  5555.6 1612.18  5714.9  1619.9  5737.6 1622.89
  5765.2 1623.59  5794.7 1626.59    5866 1630.59  5916.3 1637.34  6012.5 1640.19
#Mann= 8 ,-1 , 0
  3582.5     .05       0  3785.6      .1       0  3836.5     .05       0
  4910.5     .16       0  4992.1     .07       0  4998.1     .16       0
  5107.7     .05       0  5555.6      .1       0
#XS Ineff= 2 , 0
                         5255.13         1607.71
Permanent Ineff=
       F       F
Bank Sta=4975,5025.1
XS Rating Curve= 0 ,0
Exp/Cntr=0.3,0.1

Type RM Length L Ch R = 1 ,24615   ,667,667,667
BEGIN DESCRIPTION:
CAVE CREEK 45.0
END DESCRIPTION:
XS GIS Cut Line= 3
      2807914.76     10072100.16      2807037.98     10072438.72
       2806326.2     10072195.68
#Sta/Elev= 30
  4311.8 1632.99  4414.3 1628.46  4436.5 1625.34  4498.8 1611.78  4528.7    1608
  4607.9 1603.97  4655.5 1603.15  4800.9 1602.16  4867.1 1600.36    4946 1601.15
  4975.9  1599.4  4997.5 1592.74  5000.3 1592.24  5003.5 1592.74  5015.3 1598.03
  5025.1 1599.84  5082.2 1599.49    5145 1601.19  5194.2 1599.64  5229.7 1600.32
  5293.4 1599.21  5329.6 1601.18  5356.8 1602.07    5468 1600.08    5562  1602.6
  5809.1 1614.58  5830.9 1614.16  5869.9 1617.81  5963.9 1621.31  6003.8 1624.25
#Mann= 9 ,-1 , 0
  4311.8     .16       0  4655.5      .1       0  4867.1     .16       0
  4997.5     .07       0  5003.5     .16       0  5082.2      .1       0
  5329.6     .05       0  5809.1     .16       0  5830.9      .1       0
Bank Sta=4975.9,5025.1
XS Rating Curve= 0 ,0
Exp/Cntr=0.3,0.1

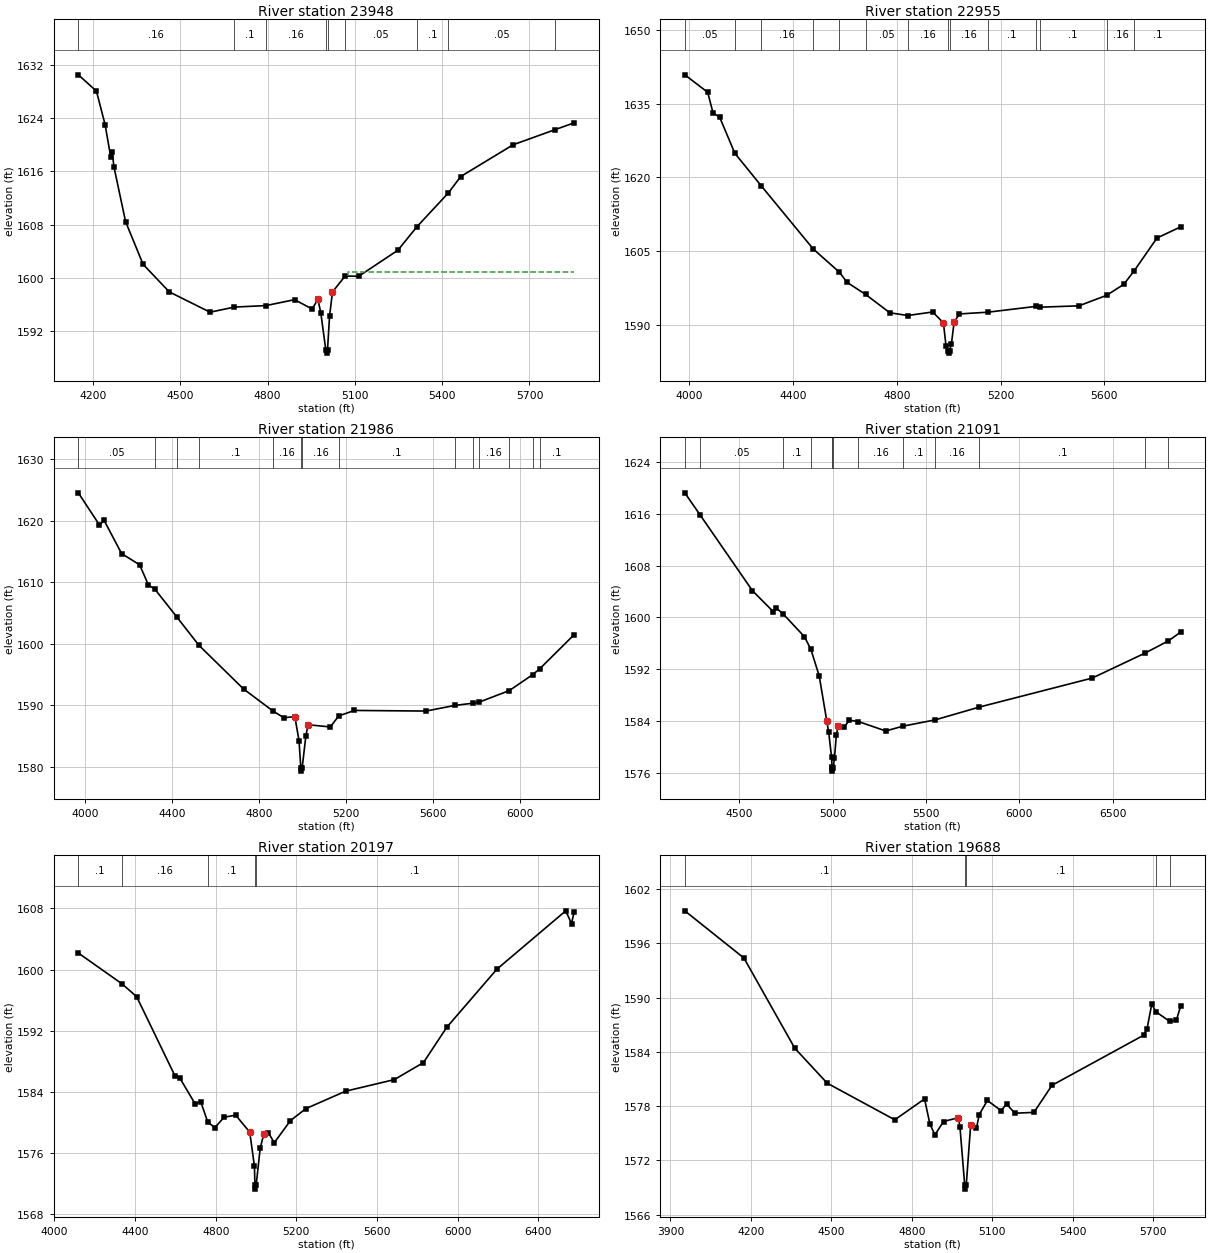
Type RM Length L Ch R = 1 ,23948   ,993,993,993
BEGIN DESCRIPTION:
CAVE CREEK 44.0
END DESCRIPTION:
XS GIS Cut Line= 2
      2807810.52      10071865.8      2806109.21     10071761.64
#Sta/Elev= 30
  4149.2 1630.46  4211.4 1628.02  4241.4 1622.95  4260.7 1618.08  4265.7 1618.85
  4271.5 1616.68  4311.6 1608.44  4371.7 1602.04  4461.8  1597.9  4602.1 1594.85
  4685.7 1595.62    4794 1595.84  4892.6 1596.73  4952.8 1595.33  4972.8 1596.78
  4982.8 1594.74  4999.8 1589.21  5002.6 1588.71  5005.8 1589.21  5012.9 1594.29
  5022.9 1597.89  5066.2 1600.27  5113.1 1600.24  5247.5 1604.14  5313.6 1607.69
  5421.6 1612.76  5463.7  1615.2    5644 1619.97  5786.5 1622.21  5853.7 1623.26
#Mann= 9 ,-1 , 0
  4149.2     .16       0  4685.7      .1       0    4794     .16       0
  4999.8     .07       0  5005.8     .16       0  5066.2     .05       0
  5313.6      .1       0  5421.6     .05       0  5786.5      .1       0
#XS Ineff= 2 , 0
                         5077.79         1600.82
Permanent Ineff=
       F       F
Bank Sta=4972.8,5022.9
XS Rating Curve= 0 ,0
Exp/Cntr=0.3,0.1

Type RM Length L Ch R = 1 ,22955   ,969,969,969
BEGIN DESCRIPTION:
CAVE CREEK 41.0
END DESCRIPTION:
XS GIS Cut Line= 3
      2808314.02     10071431.78      2807124.78     10071127.96
      2806482.91     10071362.16
#Sta/Elev= 30
    3983 1640.85  4071.1 1637.31  4091.9 1633.09  4117.1 1632.27  4175.9 1624.91
  4276.6 1618.36  4478.1 1605.46  4578.8 1600.75    4608  1598.7  4679.6 1596.24
  4773.1 1592.51  4841.8 1591.95  4938.3 1592.67  4979.6 1590.46  4989.9 1585.66
  4997.2 1584.81  4999.9 1584.31  5003.2 1584.81  5010.5 1586.22  5020.8 1590.58
    5041 1592.27  5151.5 1592.63  5335.5  1593.8  5350.3 1593.64  5501.8 1593.92
  5608.5 1596.05  5674.5 1598.28  5715.2 1601.06  5802.6  1607.7  5893.7 1609.96
#Mann= 14 ,-1 , 0
    3983     .05       0  4175.9      .1       0  4276.6     .16       0
  4478.1     .05       0  4578.8      .1       0  4679.6     .05       0
  4841.8     .16       0  4997.2     .07       0  5003.2     .16       0
  5151.5      .1       0  5335.5     .16       0  5350.3      .1       0
  5608.5     .16       0  5715.2      .1       0
Bank Sta=4979.6,5020.8
XS Rating Curve= 0 ,0
Exp/Cntr=0.3,0.1

Type RM Length L Ch R = 1 ,21986   ,895,895,895
BEGIN DESCRIPTION:
CAVE CREEK 40.0
END DESCRIPTION:
XS GIS Cut Line= 3
      2808514.79     10070318.93      2806952.29     10070631.43
      2806449.58     10071099.47
#Sta/Elev= 30
  3969.8  1624.5  4066.8 1619.29  4088.4 1620.02  4168.8 1614.64  4251.6 1612.82
  4292.4 1609.53  4321.2 1608.89  4422.7 1604.35  4524.2 1599.76  4729.7 1592.66
  4862.9 1589.14  4914.5    1588  4965.5 1588.17  4984.7 1584.29  4993.1 1579.83
  4995.8 1579.33  4999.1 1579.83  5016.4 1585.09  5026.6 1586.86  5128.6  1586.5
  5167.5 1588.29  5239.6 1589.18  5568.6 1589.08  5702.6    1590  5782.9 1590.35
  5811.1  1590.5  5951.6  1592.4  6058.8 1594.97  6092.1 1595.95  6250.1 1601.48
#Mann= 14 ,-1 , 0
  3969.8     .05       0  4321.2      .1       0  4422.7     .05       0
  4524.2      .1       0  4862.9     .16       0  4993.1     .07       0
  4999.1     .16       0  5167.5      .1       0  5702.6     .16       0
  5782.9      .1       0  5811.1     .16       0  5951.6      .1       0
  6058.8     .16       0  6092.1      .1       0
Bank Sta=4965.5,5026.6
XS Rating Curve= 0 ,0
Exp/Cntr=0.3,0.1

Type RM Length L Ch R = 1 ,21091   ,894,894,894
BEGIN DESCRIPTION:
CAVE CREEK 39.0
END DESCRIPTION:
XS GIS Cut Line= 3
      2808383.49     10069608.86      2807254.99     10069843.24
       2806187.3     10070902.25
#Sta/Elev= 30
  4207.7 1619.21  4291.1 1615.74  4570.3 1604.11  4682.6 1600.87  4698.4 1601.43
  4735.5 1600.51  4848.8 1597.02    4883 1595.09  4927.8 1590.98  4968.6 1583.99
  4978.8 1582.26    4994 1578.45  4996.1 1576.94  4996.3  1576.8    4999  1576.3
  5002.3  1576.8  5009.5  1578.3  5019.7 1581.88  5029.9 1583.31  5060.5 1583.04
  5089.2 1584.15  5137.1 1583.95  5284.5 1582.49  5374.3 1583.22  5548.5  1584.2
  5786.2 1586.18  6390.6 1590.65  6673.7  1594.5  6797.7 1596.37  6864.1 1597.73
#Mann= 13 ,-1 , 0
  4207.7      .1       0  4291.1     .05       0  4735.5      .1       0
    4883     .16       0  4996.1      .1       0  4996.3     .07       0
  5002.3      .1       0  5137.1     .16       0  5374.3      .1       0
  5548.5     .16       0  5786.2      .1       0  6673.7     .16       0
  6797.7     .05       0
Bank Sta=4968.6,5029.9
XS Rating Curve= 0 ,0
Exp/Cntr=0.3,0.1

Type RM Length L Ch R = 1 ,20197   ,509,509,509
BEGIN DESCRIPTION:
Mapping XS cb48f9c4
END DESCRIPTION:
XS GIS Cut Line= 2
      2807879.28     10069091.54      2805633.17     10070094.83
#Sta/Elev= 30
  4118.3 1602.16  4334.5 1598.14  4407.5 1596.46  4598.7 1586.04  4621.9  1585.8
    4697 1582.47  4725.7 1582.71  4760.1 1580.07  4795.4 1579.32  4841.8 1580.69
  4899.2 1580.95  4968.8 1578.73    4992 1574.27  4994.5 1571.78  4997.2 1571.28
  5000.5 1571.78  5020.7 1576.65  5038.4 1578.47  5061.1 1578.67  5090.3 1577.34
  5170.9 1580.25  5247.3 1581.81  5444.4 1584.09  5685.7  1585.6  5830.5 1587.83
  5946.6 1592.46  6195.1 1600.05  6536.5 1607.68  6565.2 1606.01  6578.3 1607.58
#Mann= 5 ,-1 , 0
  4118.3      .1       0  4334.5     .16       0  4760.1      .1       0
  4994.5     .07       0  5000.5      .1       0
Bank Sta=4968.8,5038.4
XS Rating Curve= 0 ,0
Exp/Cntr=0.3,0.1

Type RM Length L Ch R = 1 ,19688   ,660,660,660
BEGIN DESCRIPTION:
CAVE CREEK 37.0
END DESCRIPTION:
XS GIS Cut Line= 3
       2807845.3     10068992.54      2806916.45     10069105.39
      2806022.91     10068923.21
#Sta/Elev= 30
  3953.8 1599.61  4174.1 1594.39  4363.6 1584.41  4484.5 1580.54  4736.3 1576.49
  4847.2  1578.8  4867.3    1576  4885.9 1574.83  4917.9  1576.3  4973.5 1576.73
  4979.3 1575.64  4996.7 1569.32  4999.4 1568.82  5002.7 1569.32    5019 1575.91
  5040.5 1575.54  5050.7 1577.05  5081.3 1578.63  5132.4  1577.5  5152.8 1578.24
  5183.4 1577.22  5254.8 1577.31  5322.2 1580.31  5663.1 1585.84    5676 1586.52
  5693.7 1589.27  5710.3 1588.42  5761.2 1587.37  5785.5  1587.5  5801.4 1589.06
#Mann= 5 ,-1 , 0
  3953.8      .1       0  4996.7     .07       0  5002.7      .1       0
  5710.3     .05       0  5761.2      .1       0
Bank Sta=4973.5,5019
XS Rating Curve= 0 ,0
Exp/Cntr=0.3,0.1