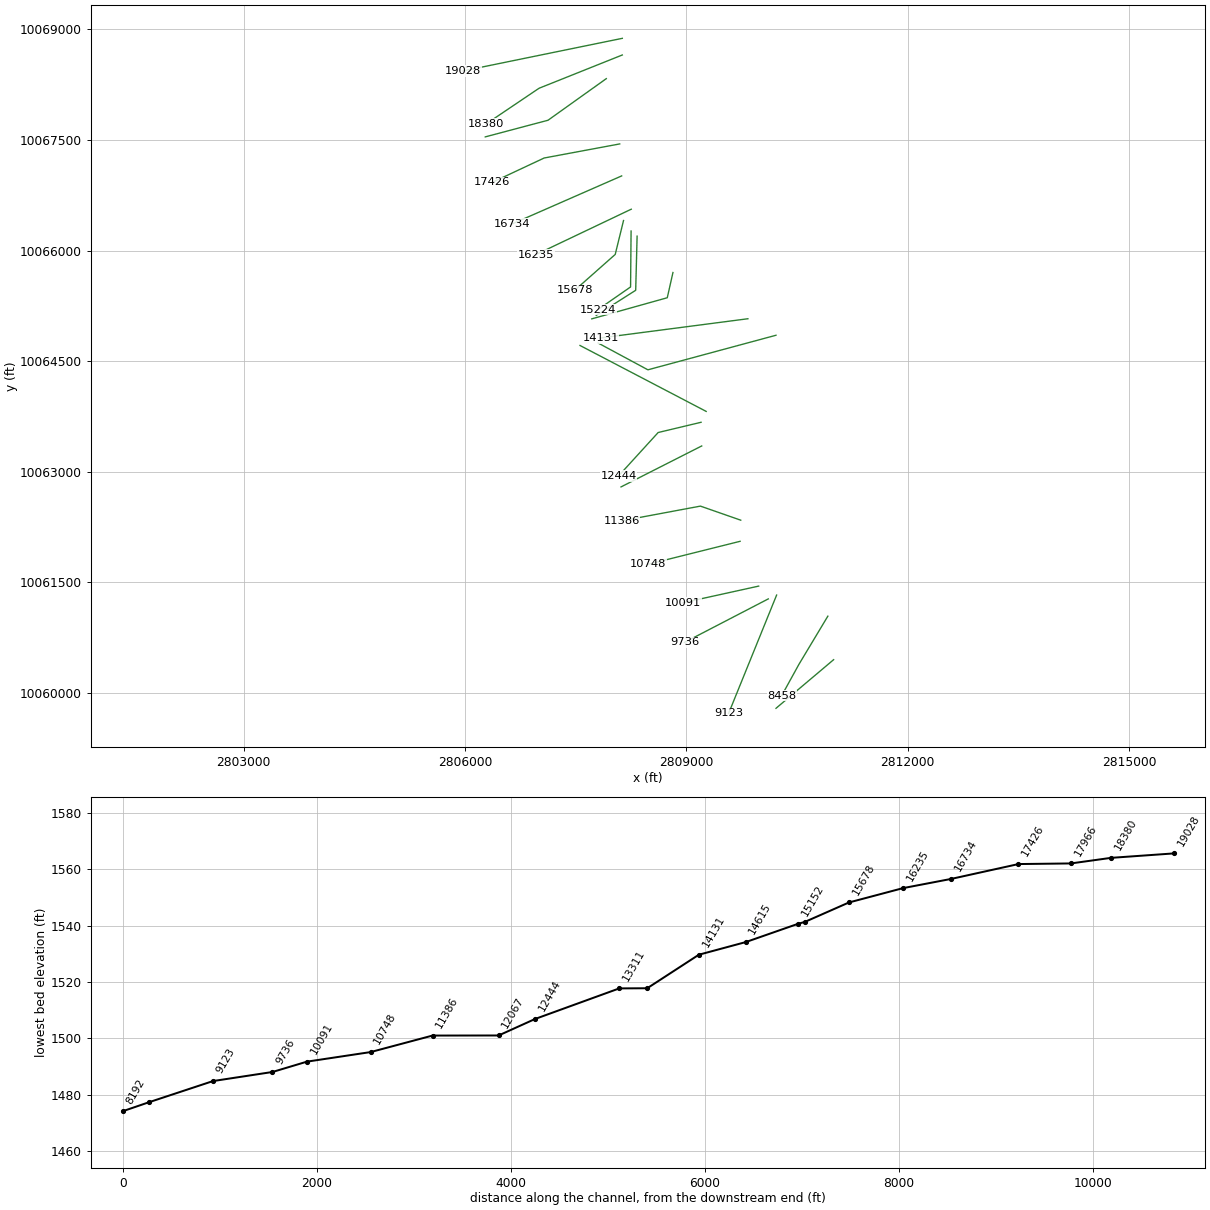
HEC-RAS study CAVE CREEK.prj: CAVE CREEK Base Level Engineering

--- CAVE CREEK.g01 (geometry) --- (continued)

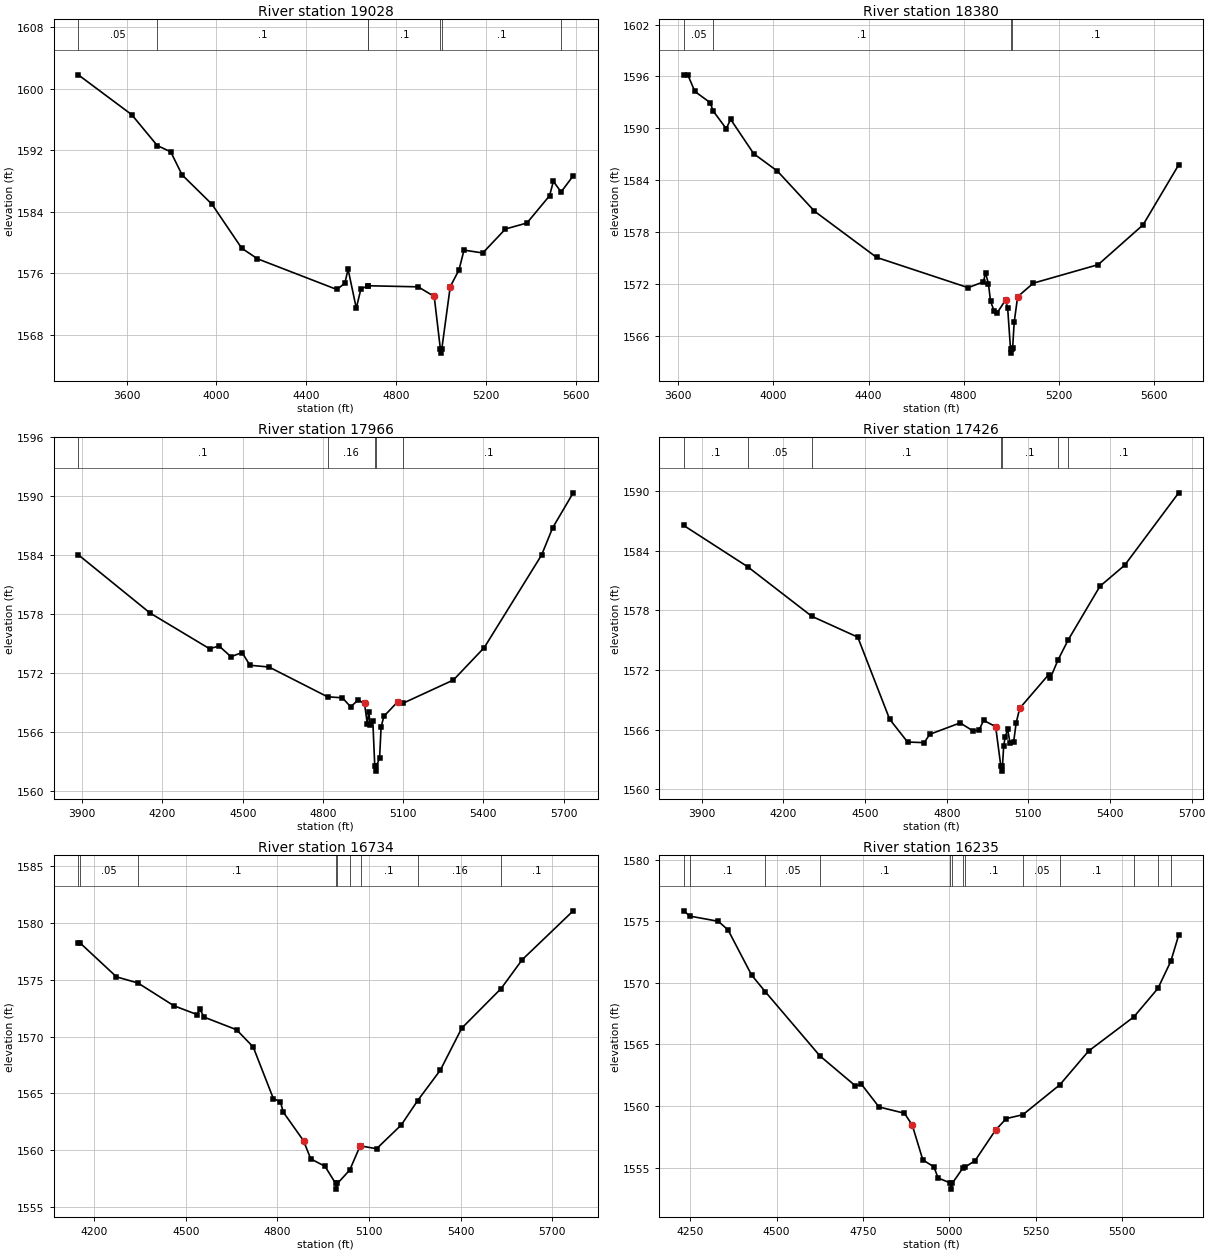
Type RM Length L Ch R = 1 ,19028   ,648,648,648
BEGIN DESCRIPTION:
CAVE CREEK 35.0
END DESCRIPTION:
XS GIS Cut Line= 2
       2808131.7     10068879.69      2805971.83     10068437.31
#Sta/Elev= 30
  3384.9 1601.82    3623 1596.63  3736.8 1592.61  3796.5  1591.8  3847.5 1588.79
  3980.2 1584.98  4112.9 1579.25  4183.2 1577.87  4536.2 1573.88  4572.3 1574.67
  4586.7 1576.52  4623.3 1571.44  4643.7 1573.93    4677 1574.38  4677.6 1574.36
  4898.9 1574.22  4970.4 1572.97    4998 1566.09  5000.7 1565.59    5004 1566.09
  5041.8 1574.24  5080.8 1576.42  5103.1    1579  5186.8 1578.63  5287.7 1581.75
  5383.5 1582.53  5484.3 1586.08  5501.2 1587.95  5535.7 1586.57  5589.6 1588.68
#Mann= 7 ,-1 , 0
  3384.9     .05       0  3736.8      .1       0    4677     .16       0
  4677.6      .1       0    4998     .07       0    5004      .1       0
  5535.7     .05       0
Bank Sta=4970.4,5041.8
XS Rating Curve= 0 ,0
Exp/Cntr=0.3,0.1

Type RM Length L Ch R = 1 ,18380   ,414,414,414
BEGIN DESCRIPTION:
CAVE CREEK 34.0
END DESCRIPTION:
XS GIS Cut Line= 3
      2808131.71     10068653.99      2807003.26     10068202.61
      2806284.78     10067717.85
#Sta/Elev= 30
  3622.5 1596.17  3639.4 1596.19  3669.1 1594.27  3733.7 1592.97  3745.7 1592.03
    3801 1589.97  3819.8 1591.04  3916.8 1587.07  4016.4 1585.06  4172.5 1580.42
  4433.8 1575.08  4818.8 1571.58  4883.2 1572.25  4891.9  1573.3  4904.2 1572.04
  4913.2 1569.99  4928.1 1568.91  4940.2 1568.63  4976.4 1570.16  4985.1 1569.21
  4997.1 1564.51  4999.8 1564.01  5003.1 1564.51  5006.1 1564.62  5012.5 1567.56
  5027.1 1570.53    5093  1572.1  5365.9 1574.24  5554.7 1578.84  5704.6 1585.78
#Mann= 4 ,-1 , 0
  3622.5     .05       0  3745.7      .1       0  4997.1     .07       0
  5003.1      .1       0
Bank Sta=4976.4,5027.1
XS Rating Curve= 0 ,0
Exp/Cntr=0.3,0.1

Type RM Length L Ch R = 1 ,17966   ,540,540,540
BEGIN DESCRIPTION:
CAVE CREEK 33.0
END DESCRIPTION:
XS GIS Cut Line= 3
      2807914.68      10068332.8      2807124.78     10067768.58
      2806274.12      10067542.9
#Sta/Elev= 30
  3885.2 1584.04  4153.7 1578.11  4376.1 1574.48  4411.7 1574.76    4456 1573.67
  4497.7 1574.09  4527.2  1572.8  4598.5 1572.62  4817.3 1569.59  4872.8 1569.49
  4903.8 1568.57  4931.5 1569.26  4955.6 1568.92  4965.9 1566.85  4971.7 1568.06
  4976.9 1566.73  4986.6 1567.15  4993.9 1562.53  4996.7 1562.03  4999.9 1562.53
  5011.9 1563.37  5017.6 1566.52    5028 1567.61  5079.7 1569.08  5100.6 1568.95
    5288  1571.3  5403.4  1574.6  5617.7 1584.01  5659.1 1586.78    5736 1590.34
#Mann= 5 ,-1 , 0
  3885.2      .1       0  4817.3     .16       0  4993.9     .07       0
  4999.9     .16       0  5100.6      .1       0
Bank Sta=4955.6,5079.7
XS Rating Curve= 0 ,0
Exp/Cntr=0.3,0.1

Type RM Length L Ch R = 1 ,17426   ,692,692,692
BEGIN DESCRIPTION:
CAVE CREEK 32.0
END DESCRIPTION:
XS GIS Cut Line= 3
      2808097.01      10067447.4       2807072.7     10067256.43
      2806369.59     10066926.58
#Sta/Elev= 30
  3833.8 1586.56  4068.8  1582.4  4304.3 1577.41  4473.2 1575.31  4590.3 1567.04
  4656.3 1564.74  4717.3 1564.68  4737.7 1565.52  4849.5 1566.67  4895.4 1565.88
  4918.3 1565.91  4935.6 1566.93  4979.8 1566.29  4998.9 1562.31  5001.7 1561.81
  5004.9 1562.31  5009.5 1564.39  5015.1 1565.26    5024 1566.02  5032.4 1564.69
  5046.1 1564.77  5055.2 1566.67  5068.2 1568.14  5174.8 1571.54  5180.3 1571.15
  5208.8    1573  5246.2 1575.02  5362.9 1580.43  5454.1 1582.56  5652.4 1589.85
#Mann= 7 ,-1 , 0
  3833.8      .1       0  4068.8     .05       0  4304.3      .1       0
  4998.9     .07       0  5004.9      .1       0  5208.8     .16       0
  5246.2      .1       0
Bank Sta=4979.8,5068.2
XS Rating Curve= 0 ,0
Exp/Cntr=0.3,0.1

Type RM Length L Ch R = 1 ,16734   ,499,499,499
BEGIN DESCRIPTION:
CAVE CREEK 31.0
END DESCRIPTION:
XS GIS Cut Line= 2
        2808123.     10067013.35      2806638.69     10066362.34
#Sta/Elev= 30
  4147.8 1578.28  4152.4 1578.28  4272.9 1575.26  4343.1 1574.72    4461 1572.71
  4536.6 1571.94  4545.9 1572.41  4559.9 1571.71    4666  1570.6  4720.6 1569.08
  4786.6 1564.53    4810 1564.23  4818.8 1563.35  4885.6 1560.81  4908.9 1559.22
  4955.7 1558.56  4990.6 1557.05  4993.3 1556.55  4996.6 1557.05  5036.9 1558.24
    5070 1560.31  5072.3 1560.36  5124.6 1560.11  5205.7 1562.21  5259.3 1564.36
  5333.5 1567.04  5403.6 1570.74  5532.5 1574.23  5601.5 1576.77  5768.6 1581.08
#Mann= 9 ,-1 , 0
  4147.8      .1       0  4152.4     .05       0  4343.1      .1       0
  4990.6     .07       0  4996.6      .1       0  5036.9     .16       0
  5072.3      .1       0  5259.3     .16       0  5532.5      .1       0
Bank Sta=4885.6,5070
XS Rating Curve= 0 ,0
Exp/Cntr=0.3,0.1

Type RM Length L Ch R = 1 ,16235   ,557,557,557
BEGIN DESCRIPTION:
CAVE CREEK 29.0
END DESCRIPTION:
XS GIS Cut Line= 2
      2808253.22     10066561.97      2806959.85     10065945.66
#Sta/Elev= 30
  4231.1 1575.85  4248.8 1575.42  4331.1    1575  4359.3  1574.3  4427.4 1570.64
  4466.9 1569.29  4625.4 1564.07  4728.1 1561.64  4745.2 1561.78  4796.2 1559.93
  4869.8 1559.42  4892.5 1558.46  4923.2 1555.63  4955.1 1555.07  4967.5 1554.16
    5003 1553.76  5005.7 1553.26    5009 1553.76  5040.1 1555.01  5045.1 1555.05
  5074.1 1555.56  5133.6 1558.05  5164.9 1558.99  5212.7  1559.3  5319.8 1561.73
    5403 1564.47    5534 1567.24  5603.6 1569.55  5641.1 1571.76  5663.8 1573.88
#Mann= 13 ,-1 , 0
  4231.1     .05       0  4248.8      .1       0  4466.9     .05       0
  4625.4      .1       0    5003     .07       0    5009      .1       0
  5040.1     .05       0  5045.1      .1       0  5212.7     .05       0
  5319.8      .1       0    5534     .16       0  5603.6      .1       0
  5641.1     .16       0
Bank Sta=4892.5,5133.6
XS Rating Curve= 0 ,0
Exp/Cntr=0.3,0.1

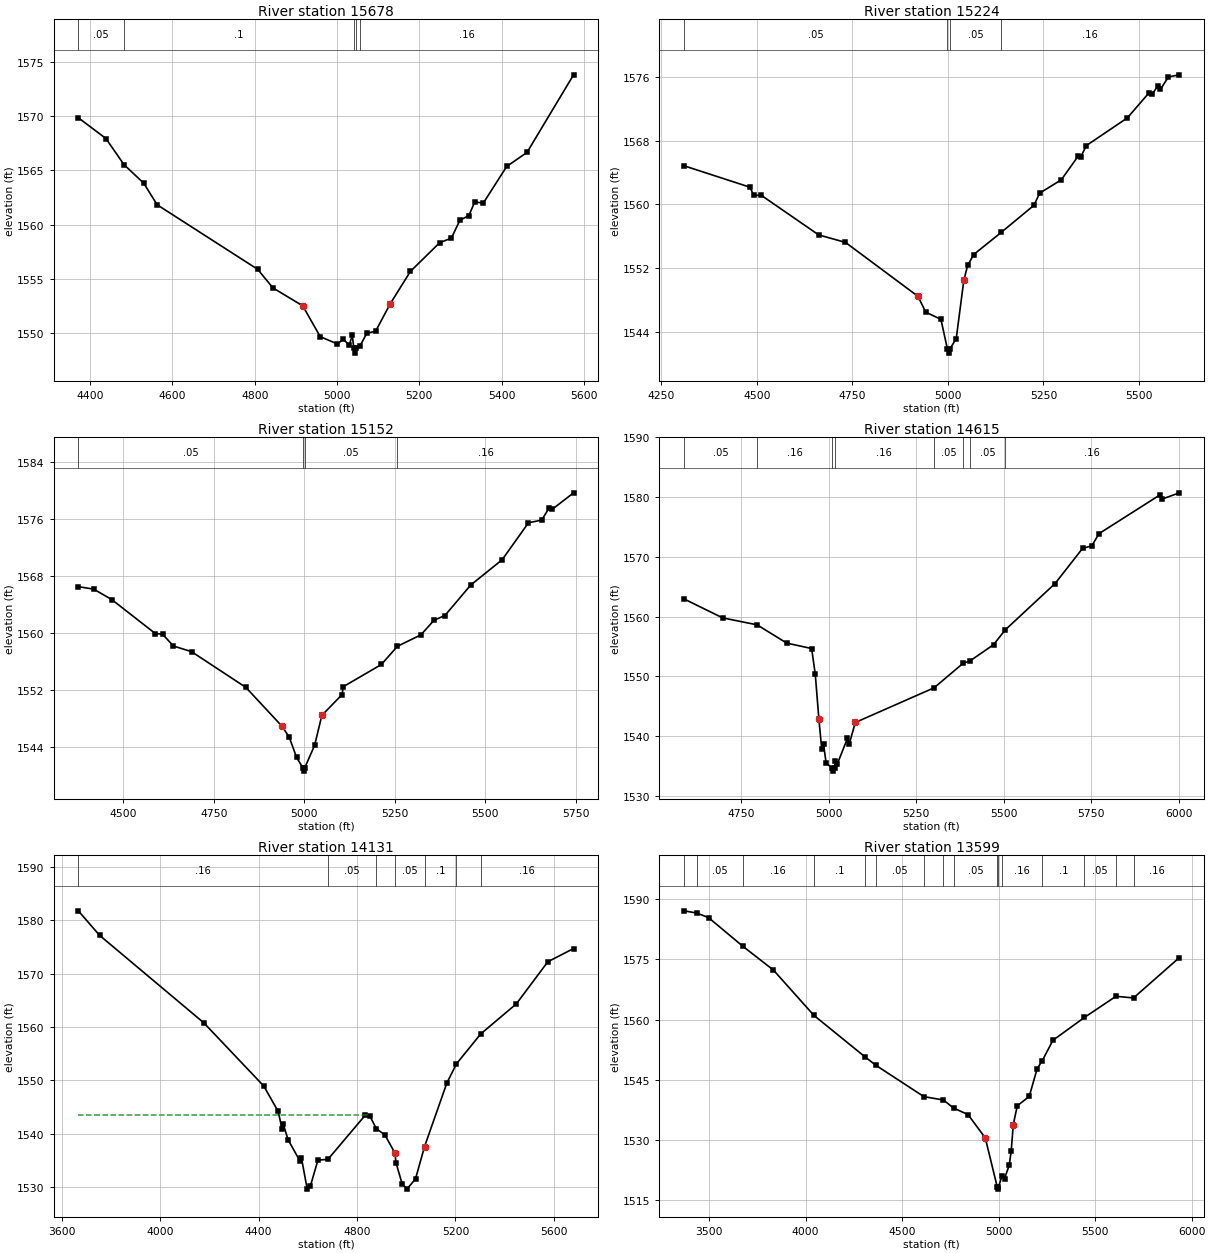
Type RM Length L Ch R = 1 ,15678   ,454,454,454
BEGIN DESCRIPTION:
CAVE CREEK 28.0
END DESCRIPTION:
XS GIS Cut Line= 3
      2808148.39     10066408.15      2808035.56     10065948.13
      2807488.68     10065463.75
#Sta/Elev= 30
    4371 1569.83  4438.1 1567.92    4482 1565.52    4530 1563.81  4562.8 1561.82
  4807.2 1555.88  4844.3 1554.17  4916.7 1552.52  4959.4 1549.68  5001.2 1549.01
  5015.4 1549.46  5029.6 1548.88  5037.1 1549.81  5040.8 1548.67  5043.6 1548.17
  5046.8 1548.67  5055.4 1548.79  5072.3 1549.99    5094 1550.19  5129.1 1552.69
  5178.5 1555.69  5249.6 1558.33    5278 1558.75  5298.9  1560.4  5320.7 1560.83
  5334.9 1562.08  5355.8 1561.98  5412.7 1565.35    5462 1566.64  5575.2 1573.78
#Mann= 5 ,-1 , 0
    4371     .05       0    4482      .1       0  5040.8     .07       0
  5046.8      .1       0  5055.4     .16       0
Bank Sta=4916.7,5129.1
XS Rating Curve= 0 ,0
Exp/Cntr=0.3,0.1

Type RM Length L Ch R = 1 ,15224   ,72,72,72
BEGIN DESCRIPTION:
Mapping XS 611e0b55
END DESCRIPTION:
XS GIS Cut Line= 3
      2808250.83     10066265.82      2808243.89     10065507.16
      2807802.33     10065200.66
#Sta/Elev= 30
  4309.5 1564.87  4481.6 1562.18  4491.6 1561.17  4511.6 1561.15  4661.6 1556.17
  4731.6 1555.23  4921.6 1548.43  4941.6 1546.45  4981.6 1545.53  4998.6 1541.78
  5001.4 1541.28  5004.6 1541.78  5021.6 1543.09  5041.6 1550.49  5051.6 1552.33
  5067.4  1553.7  5139.2 1556.48  5225.1  1559.9    5240 1561.43  5296.7 1563.11
  5341.3 1566.13  5347.4 1565.98  5362.2 1567.42  5469.6 1570.91  5526.3 1574.07
  5535.1 1573.93  5549.5 1574.95  5556.1 1574.49    5577 1576.07  5605.7 1576.33
#Mann= 4 ,-1 , 0
  4309.5     .05       0  4998.6     .04       0  5004.6     .05       0
  5139.2     .16       0
Bank Sta=4921.6,5041.6
XS Rating Curve= 0 ,0
Exp/Cntr=0.3,0.1

Type RM Length L Ch R = 1 ,15152   ,537,537,537
BEGIN DESCRIPTION:
CAVE CREEK 27.0
END DESCRIPTION:
XS GIS Cut Line= 3
      2808332.43     10066196.39      2808313.33     10065462.02
      2807778.64     10065121.76
#Sta/Elev= 30
  4375.7 1566.47  4418.4 1566.12  4468.4 1564.65  4588.4 1559.89  4608.4 1559.81
  4638.4 1558.14  4688.5 1557.35  4838.5 1552.34  4938.5 1546.88  4958.6 1545.34
  4978.6 1542.53  4995.6 1541.08  4998.3 1540.58  5001.6 1541.08  5028.6 1544.19
  5048.6  1548.4  5104.4 1551.32  5107.8 1552.43  5213.2 1555.55  5257.4  1558.1
  5322.4 1559.71  5358.8 1561.77  5388.7 1562.42  5459.8 1566.69  5546.8 1570.25
  5619.6 1575.44    5656 1575.81  5677.2 1577.57    5685 1577.32  5744.1 1579.64
#Mann= 4 ,-1 , 0
  4375.7     .05       0  4995.6     .04       0  5001.6     .05       0
  5257.4     .16       0
Bank Sta=4938.5,5048.6
XS Rating Curve= 0 ,0
Exp/Cntr=0.3,0.1

Type RM Length L Ch R = 1 ,14615   ,484,484,484
BEGIN DESCRIPTION:
CAVE CREEK 26.0
END DESCRIPTION:
XS GIS Cut Line= 3
      2808818.32      10065702.8      2808741.35     10065360.87
      2807717.59     10065074.28
#Sta/Elev= 30
  4587.9 1562.93  4697.8 1559.77  4795.9 1558.61  4881.1 1555.54  4951.8 1554.64
  4962.2 1550.33  4972.5 1542.83  4980.6 1537.82  4985.8  1538.6  4993.3 1535.43
  5011.1 1534.62  5013.8 1534.12  5017.1 1534.62  5019.9 1535.87  5025.1 1535.31
    5054  1539.6  5059.2 1538.66  5076.4 1542.26  5301.4 1548.07  5384.6 1552.19
  5402.7 1552.52    5471 1555.28  5503.9 1557.73  5646.7 1565.52  5725.4 1571.42
  5751.4 1571.82  5772.1 1573.87  5945.7 1580.34  5950.9 1579.63  6001.5  1580.7
#Mann= 8 ,-1 , 0
  4587.9     .05       0  4795.9     .16       0  5011.1     .07       0
  5017.1     .16       0  5301.4     .05       0  5384.6     .16       0
  5402.7     .05       0  5503.9     .16       0
Bank Sta=4972.5,5076.4
XS Rating Curve= 0 ,0
Exp/Cntr=0.3,0.1

Type RM Length L Ch R = 1 ,14131   ,532,532,532
BEGIN DESCRIPTION:
CAVE CREEK 25.0
END DESCRIPTION:
XS GIS Cut Line= 2
      2809834.24     10065075.88      2807837.75     10064815.47
#Sta/Elev= 30
    3667 1581.75  3753.5 1577.16  4177.1 1560.78  4421.1 1548.93  4479.6 1544.18
  4495.1 1540.95  4500.1 1541.81  4519.9 1538.88    4569 1534.82  4574.1  1535.5
  4597.6 1529.63  4610.7 1530.23    4641 1535.05  4682.1 1535.22  4832.6 1543.42
  4852.7 1543.28  4878.4 1540.97  4913.2 1539.79  4953.6 1536.45    4959 1534.51
  4983.8 1530.58    5004 1529.68    5038 1531.57  5074.6  1537.6  5165.4 1549.51
  5204.4  1553.1  5303.3 1558.71  5447.7 1564.32  5575.8 1572.21  5680.4 1574.69
#Mann= 7 ,-1 , 0
    3667     .16       0  4682.1     .05       0  4878.4     .16       0
  4953.6     .05       0  5074.6      .1       0  5204.4     .05       0
  5303.3     .16       0
#XS Ineff= 2 , 0
         4839.15 1543.58
Permanent Ineff=
       F       F
Bank Sta=4953.6,5074.6
XS Rating Curve= 0 ,0
Exp/Cntr=0.3,0.1

Type RM Length L Ch R = 1 ,13599   ,288,288,288
BEGIN DESCRIPTION:
CAVE CREEK 24.0
END DESCRIPTION:
XS GIS Cut Line= 3
      2810215.07     10064851.92      2808478.95     10064383.17
      2807802.65     10064747.33
#Sta/Elev= 30
  3370.3 1587.12  3435.5 1586.57  3496.9 1585.42    3673 1578.34  3832.9 1572.35
  4042.8 1561.05  4309.7 1550.62  4364.7 1548.58  4612.8 1540.79  4713.8 1539.95
  4766.4 1537.95  4841.6 1536.31  4930.9 1530.49    4993 1518.23  4995.7 1517.73
    4999 1518.23  5016.9 1520.92  5030.7 1520.37  5055.2 1523.76  5065.4 1527.34
  5075.9 1533.84  5096.6 1538.51  5158.7 1540.85  5199.5 1547.75  5225.8 1549.73
  5281.4 1554.84  5444.4 1560.53  5608.1 1565.81  5698.9  1565.4  5936.7 1575.47
#Mann= 16 ,-1 , 0
  3370.3      .1       0  3435.5     .05       0    3673     .16       0
  4042.8      .1       0  4309.7     .16       0  4364.7     .05       0
  4612.8      .1       0  4713.8     .16       0  4766.4     .05       0
    4993     .04       0    4999     .05       0  5016.9     .16       0
  5225.8      .1       0  5444.4     .05       0  5608.1      .1       0
  5698.9     .16       0
Bank Sta=4930.9,5075.9
XS Rating Curve= 0 ,0
Exp/Cntr=0.3,0.1

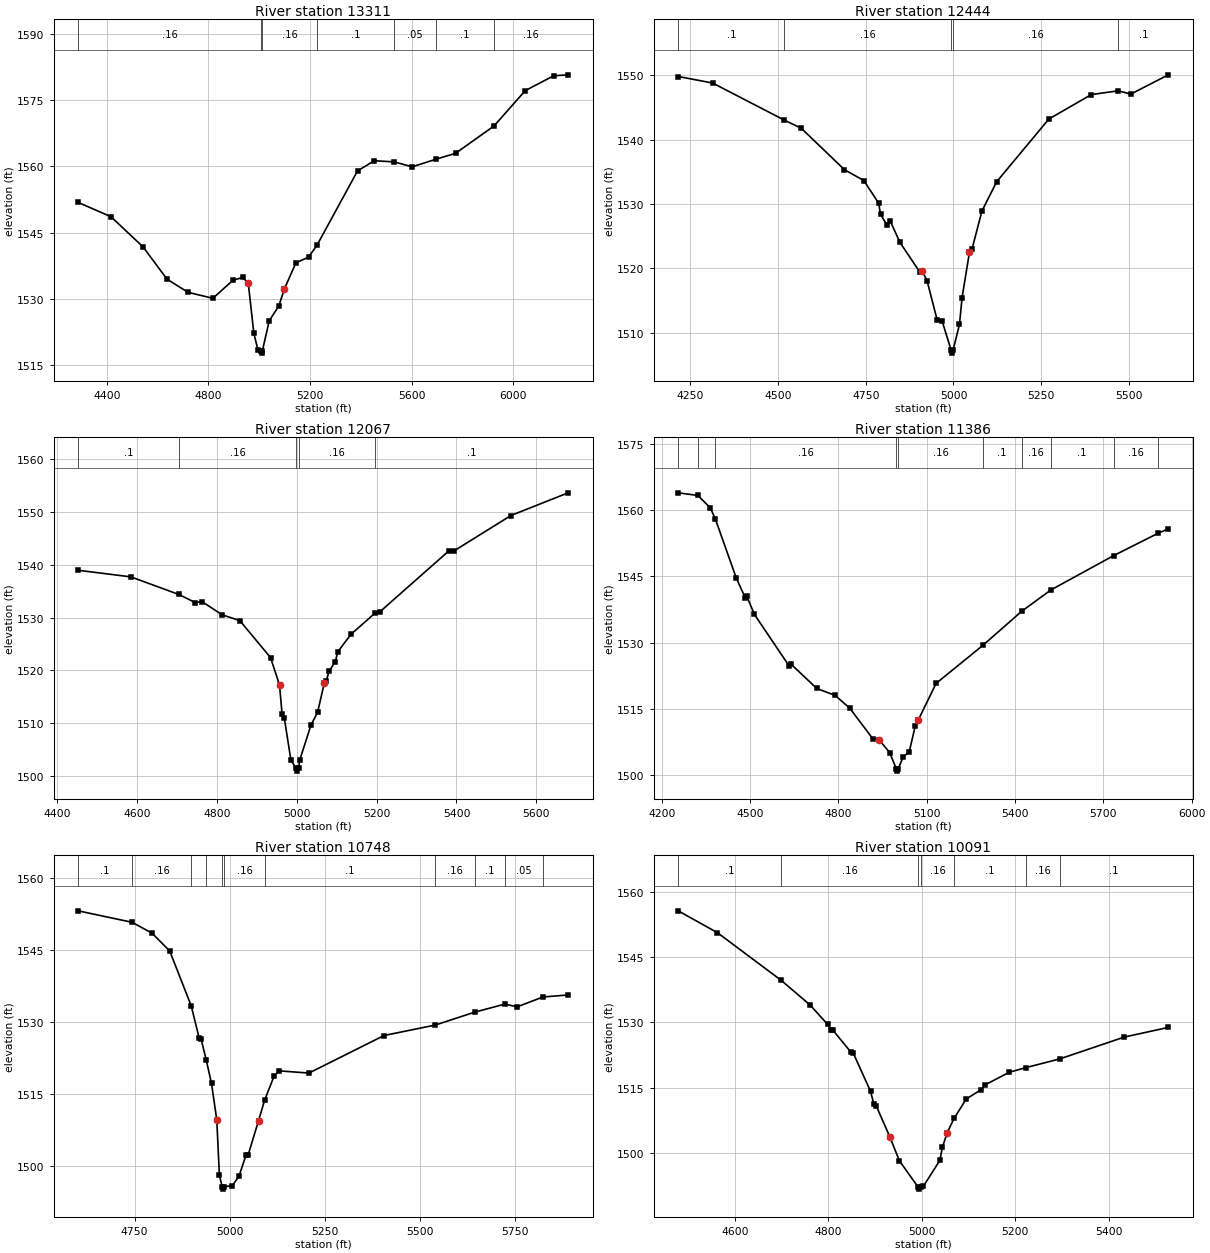
Type RM Length L Ch R = 1 ,13311   ,867,867,867
BEGIN DESCRIPTION:
CAVE CREEK 23.0
END DESCRIPTION:
XS GIS Cut Line= 2
      2809268.89     10063818.93      2807558.82     10064713.02
#Sta/Elev= 30
  4286.6 1551.84  4416.3 1548.59  4543.1 1541.72    4637 1534.43  4719.7 1531.46
  4817.4  1530.1  4896.4 1534.19  4934.8 1534.82  4956.9 1533.51  4978.9 1522.14
  4995.4 1518.32  5006.3 1518.18    5009 1517.68  5012.3 1518.18  5039.5 1525.03
    5077 1528.35  5099.5 1532.29  5144.3 1538.12  5194.1 1539.43  5227.2  1542.1
  5387.1 1558.97  5453.3 1561.27  5531.3 1561.02  5602.2 1559.89    5696 1561.62
  5773.2 1562.96  5924.7 1569.16  6047.4 1577.15  6159.3 1580.52  6216.3 1580.74
#Mann= 7 ,-1 , 0
  4286.6     .16       0  5006.3     .07       0  5012.3     .16       0
  5227.2      .1       0  5531.3     .05       0    5696      .1       0
  5924.7     .16       0
#XS Ineff= 2 , 0
         4922.86 1532.69
Permanent Ineff=
       F       F
Bank Sta=4956.9,5099.5
XS Rating Curve= 0 ,0
Exp/Cntr=0.3,0.1

Type RM Length L Ch R = 1 ,12444   ,377,377,377
BEGIN DESCRIPTION:
CAVE CREEK 22.0
END DESCRIPTION:
XS GIS Cut Line= 3
      2809199.44     10063671.36      2808617.84     10063532.47
      2808079.61     10062942.16
#Sta/Elev= 30
  4215.4  1549.8  4313.4 1548.79  4518.1 1543.02    4566 1541.77  4689.3 1535.33
  4744.6 1533.64  4786.7 1530.13  4792.1 1528.42  4810.5 1526.69  4819.1 1527.42
  4847.5 1524.03  4904.3 1519.41    4911 1519.65  4925.2 1517.98  4953.6 1511.97
  4967.8 1511.79  4993.1 1507.34  4995.9 1506.84  4999.1 1507.34  5017.1  1511.3
  5024.5 1515.45  5045.5 1522.49  5052.9 1523.01  5081.3 1528.94  5123.2 1533.46
  5271.8 1543.19  5392.7 1546.99  5469.6 1547.58  5505.6 1547.07  5612.2 1550.06
#Mann= 5 ,-1 , 0
  4215.4      .1       0  4518.1     .16       0  4993.1     .07       0
  4999.1     .16       0  5469.6      .1       0
Bank Sta=4911,5045.5
XS Rating Curve= 0 ,0
Exp/Cntr=0.3,0.1

Type RM Length L Ch R = 1 ,12067   ,681,681,681
BEGIN DESCRIPTION:
CAVE CREEK 20.0
END DESCRIPTION:
XS GIS Cut Line= 2
      2809208.16      10063350.2      2808114.37     10062794.62
#Sta/Elev= 30
  4452.7 1538.95  4584.9  1537.7    4705 1534.37  4746.3 1532.84  4762.9 1533.03
  4813.1 1530.54  4857.6 1529.43  4934.6 1522.44  4957.1 1517.24  4963.3 1511.84
  4968.9 1511.09  4985.5 1503.06  4998.9 1501.47  5001.7 1500.97  5004.9 1501.47
  5007.8 1503.09  5035.6 1509.65  5052.3 1512.08  5068.9 1517.55  5074.5 1518.04
  5080.5 1519.81  5096.8 1521.68  5102.9 1523.53  5135.7 1526.82  5195.1 1530.78
  5208.1 1531.08  5380.5 1542.58  5394.5 1542.64  5536.3  1549.3  5679.5 1553.59
#Mann= 5 ,-1 , 0
  4452.7      .1       0    4705     .16       0  4998.9     .07       0
  5004.9     .16       0  5195.1      .1       0
Bank Sta=4957.1,5068.9
XS Rating Curve= 0 ,0
Exp/Cntr=0.3,0.1

Type RM Length L Ch R = 1 ,11386   ,638,638,638
BEGIN DESCRIPTION:
CAVE CREEK 19.0
END DESCRIPTION:
XS GIS Cut Line= 3
      2809737.61     10062343.24      2809190.76     10062534.21
       2808123.3      10062334.6
#Sta/Elev= 30
  4255.3 1563.85  4322.1 1563.26  4364.3 1560.46  4381.6 1557.93  4452.1  1544.7
  4483.2 1540.08  4488.5 1540.44  4514.3 1536.37  4633.2 1524.62  4638.5 1525.14
  4726.3 1519.62  4788.4 1518.06  4838.2 1515.18    4916 1508.31  4938.6 1507.98
  4973.7 1505.15  4996.6 1501.44  4999.4 1500.94  5002.6 1501.44    5020 1504.16
  5040.3  1505.3  5060.7 1511.09  5070.9 1512.47  5131.6 1520.77  5290.2 1529.35
  5422.2 1537.06  5521.8  1541.9  5734.5 1549.64  5885.9 1554.71  5920.5 1555.71
#Mann= 10 ,-1 , 0
  4255.3     .16       0  4322.1      .1       0  4381.6     .16       0
  4996.6     .07       0  5002.6     .16       0  5290.2      .1       0
  5422.2     .16       0  5521.8      .1       0  5734.5     .16       0
  5885.9      .1       0
Bank Sta=4938.6,5070.9
XS Rating Curve= 0 ,0
Exp/Cntr=0.3,0.1

Type RM Length L Ch R = 1 ,10748   ,657,657,657
BEGIN DESCRIPTION:
CAVE CREEK 18.0
END DESCRIPTION:
XS GIS Cut Line= 2
      2809728.93     10062056.77        2808479.     10061744.29
#Sta/Elev= 30
  4601.1 1553.16  4743.1 1550.77  4795.7 1548.49  4842.1 1544.78  4898.5 1533.36
  4919.4 1526.64  4924.6 1526.44    4938 1522.05    4952 1517.14  4965.8 1509.56
  4972.7 1497.97    4980 1495.58  4982.7 1495.08    4986 1495.58    5007 1495.83
  5024.2 1497.77  5043.1 1502.27  5048.3 1502.22  5075.7 1509.38  5091.4  1513.6
    5117 1518.77  5130.7 1519.76    5208  1519.3  5405.6 1527.14  5540.1 1529.32
  5644.2 1532.02  5722.7 1533.68    5756 1533.14  5823.3 1535.18  5889.5  1535.6
#Mann= 11 ,-1 , 0
  4601.1      .1       0  4743.1     .16       0  4898.5      .1       0
    4938     .16       0    4980     .07       0    4986     .16       0
  5091.4      .1       0  5540.1     .16       0  5644.2      .1       0
  5722.7     .05       0  5823.3      .1       0
Bank Sta=4965.8,5075.7
XS Rating Curve= 0 ,0
Exp/Cntr=0.3,0.1

Type RM Length L Ch R = 1 ,10091   ,355,355,355
BEGIN DESCRIPTION:
CAVE CREEK 17.0
END DESCRIPTION:
XS GIS Cut Line= 2
      2809980.64     10061449.13      2808956.41     10061223.45
#Sta/Elev= 30
  4478.9  1555.6    4563 1550.57  4699.5 1539.62  4761.2 1533.97  4798.6 1529.53
  4804.9 1528.19    4810 1528.19  4848.6 1523.14  4853.7 1522.88  4890.7 1514.12
  4897.4 1511.27  4902.5 1510.86  4931.7 1503.72  4952.2 1498.21  4992.1 1492.18
  4994.8 1491.68  4998.1 1492.18  5003.4 1492.29  5038.8 1498.27  5044.3 1501.26
  5054.6 1504.64  5069.5 1507.97  5095.5 1512.39  5126.2 1514.46  5136.5 1515.68
  5187.7 1518.53  5222.7 1519.58  5295.3 1521.58  5433.4  1526.6  5527.7 1528.82
#Mann= 7 ,-1 , 0
  4478.9      .1       0  4699.5     .16       0  4992.1     .07       0
  4998.1     .16       0  5069.5      .1       0  5222.7     .16       0
  5295.3      .1       0
Bank Sta=4931.7,5054.6
XS Rating Curve= 0 ,0
Exp/Cntr=0.3,0.1

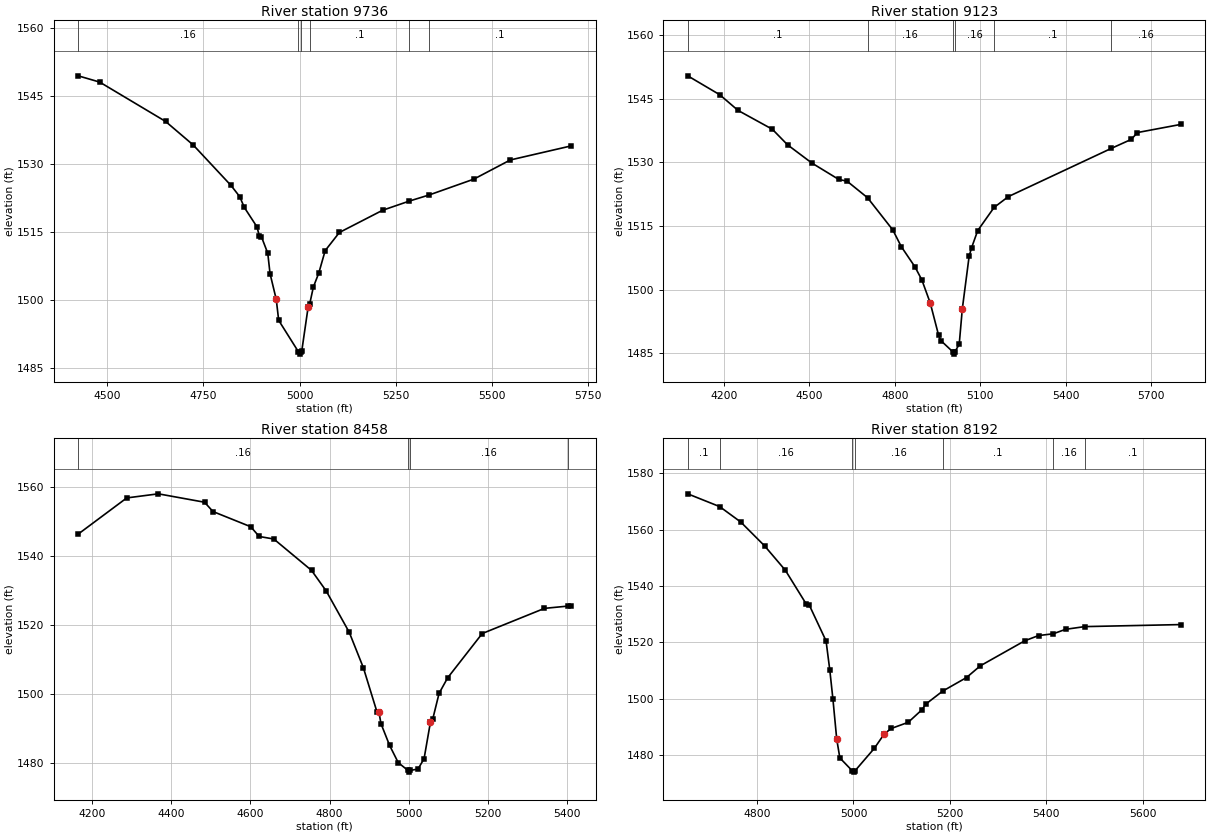
Type RM Length L Ch R = 1 ,9736    ,613,613,613
BEGIN DESCRIPTION:
CAVE CREEK 16.0
END DESCRIPTION:
XS GIS Cut Line= 2
      2810110.89     10061275.52      2808973.76     10060685.26
#Sta/Elev= 30
  4424.6 1549.39  4480.4 1548.01  4651.7 1539.33  4723.7 1534.12  4821.7 1525.21
  4844.2 1522.76  4856.4 1520.35  4889.3 1516.06    4895 1514.14  4900.7 1513.91
  4917.2 1510.26  4923.1 1505.78  4939.3 1500.06  4945.6 1495.46    4997 1488.51
  4999.7 1488.01    5003 1488.51  5005.6 1488.71  5022.1 1498.38  5026.1 1499.04
  5035.7 1502.81  5049.9 1505.92  5066.4 1510.84  5103.3 1514.84  5215.6 1519.74
  5284.8 1521.76  5336.8 1523.12  5452.6  1526.6  5547.4 1530.83  5705.8 1533.94
#Mann= 6 ,-1 , 0
  4424.6     .16       0    4997     .07       0    5003     .16       0
  5026.1      .1       0  5284.8     .05       0  5336.8      .1       0
Bank Sta=4939.3,5022.1
XS Rating Curve= 0 ,0
Exp/Cntr=0.3,0.1

Type RM Length L Ch R = 1 ,9123    ,665,665,665
BEGIN DESCRIPTION:
CAVE CREEK 15.0
END DESCRIPTION:
XS GIS Cut Line= 2
      2810223.73     10061327.57      2809573.08     10059722.64
#Sta/Elev= 30
  4072.8 1550.43  4185.1 1545.98  4249.6 1542.27    4370 1537.83  4423.6 1534.15
  4508.6 1529.87  4603.1    1526  4632.5 1525.58  4704.4 1521.68  4793.3 1514.07
  4822.8 1510.16    4871 1505.37  4895.1 1502.31  4924.6 1496.86  4954.1 1489.22
  4961.8 1487.99  5004.7 1485.29  5007.4 1484.79  5010.7 1485.29  5026.4  1487.1
  5037.3 1495.47  5061.3 1507.89  5069.7 1509.85  5091.3 1513.92  5148.9 1519.39
  5199.2 1521.95  5559.8 1533.29  5630.8 1535.44  5652.4 1537.05  5804.6 1538.97
#Mann= 6 ,-1 , 0
  4072.8      .1       0  4704.4     .16       0  5004.7     .07       0
  5010.7     .16       0  5148.9      .1       0  5559.8     .16       0
Bank Sta=4924.6,5037.3
XS Rating Curve= 0 ,0
Exp/Cntr=0.3,0.1

Type RM Length L Ch R = 1 ,8458    ,266,266,266
BEGIN DESCRIPTION:
CAVE CREEK 14.0
END DESCRIPTION:
XS GIS Cut Line= 3
      2810918.16     10061041.11      2810527.56     10060390.11
       2810293.3     10059964.97
#Sta/Elev= 30
  4165.2 1546.38  4287.8 1556.89  4367.5 1558.08  4484.1 1555.64  4505.5 1552.93
  4600.7 1548.52  4622.1 1545.69    4659 1544.95  4754.2 1535.84  4791.2 1529.87
  4849.5 1517.83  4885.2 1507.51  4919.4 1494.72  4924.4 1494.72  4929.4 1491.34
  4951.2 1485.01    4973    1480  4997.5 1477.72  5000.2 1477.22  5003.5 1477.72
    5023 1478.12  5038.3 1481.12  5054.4 1491.77  5060.1 1492.59  5076.2 1500.12
  5097.9 1504.63  5185.1 1517.49  5342.2  1524.8  5400.4 1525.45  5409.8 1525.44
#Mann= 4 ,-1 , 0
  4165.2     .16       0  4997.5     .07       0  5003.5     .16       0
  5400.4      .1       0
Bank Sta=4924.4,5054.4
XS Rating Curve= 0 ,0
Exp/Cntr=0.3,0.1

Type RM Length L Ch R = 1 ,8192    ,633,633,633
BEGIN DESCRIPTION:
CAVE CREEK 13.0
END DESCRIPTION:
XS GIS Cut Line= 2
      2810996.27     10060450.84      2810215.05     10059791.15
#Sta/Elev= 30
  4656.3 1572.65  4722.5 1568.13  4766.4 1562.65  4815.8  1554.2  4858.7 1545.59
  4901.6 1533.75  4908.1 1533.35  4943.2 1520.55    4951 1510.16  4957.5 1499.83
  4965.3 1485.78  4971.8 1479.11  4997.4 1474.58  5000.2 1474.08  5003.4 1474.58
  5043.3 1482.51  5064.1 1487.66  5078.4 1489.54  5113.6 1491.72  5142.2  1496.2
  5149.9 1498.15  5184.8 1502.75  5234.5 1507.58    5263 1511.72  5355.4 1520.61
  5383.9 1522.45  5414.4 1523.08  5439.9 1524.66  5479.7 1525.62  5678.8 1526.34
#Mann= 7 ,-1 , 0
  4656.3      .1       0  4722.5     .16       0  4997.4     .07       0
  5003.4     .16       0  5184.8      .1       0  5414.4     .16       0
  5479.7      .1       0
Bank Sta=4965.3,5064.1
XS Rating Curve= 0 ,0
Exp/Cntr=0.3,0.1