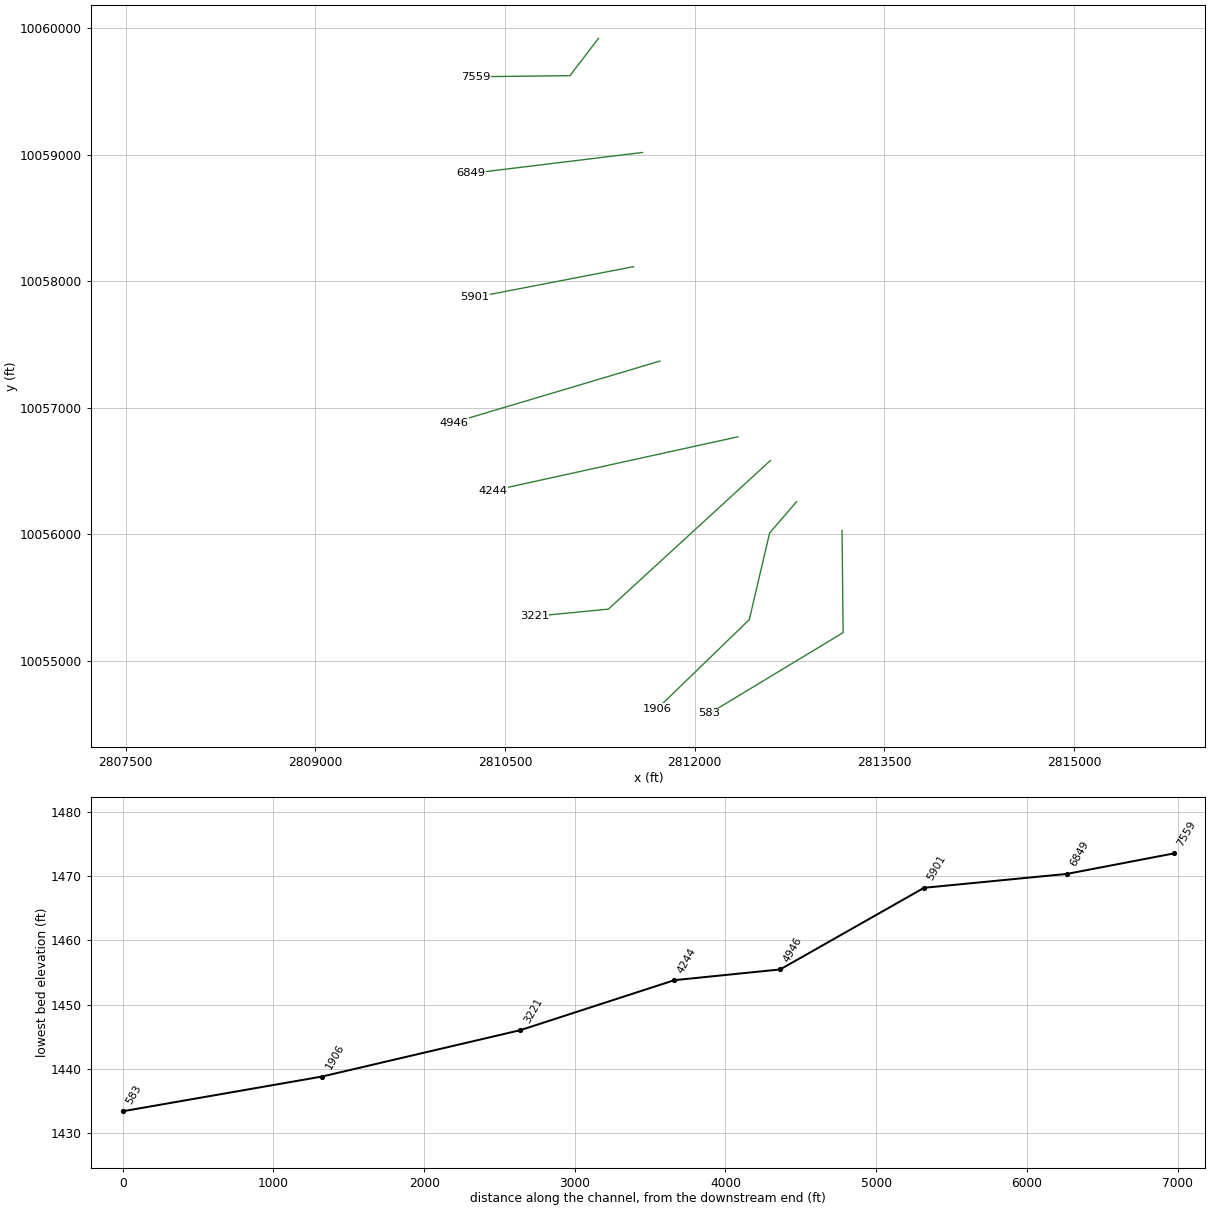
HEC-RAS study CAVE CREEK.prj: CAVE CREEK Base Level Engineering

--- CAVE CREEK.g01 (geometry) --- (continued)

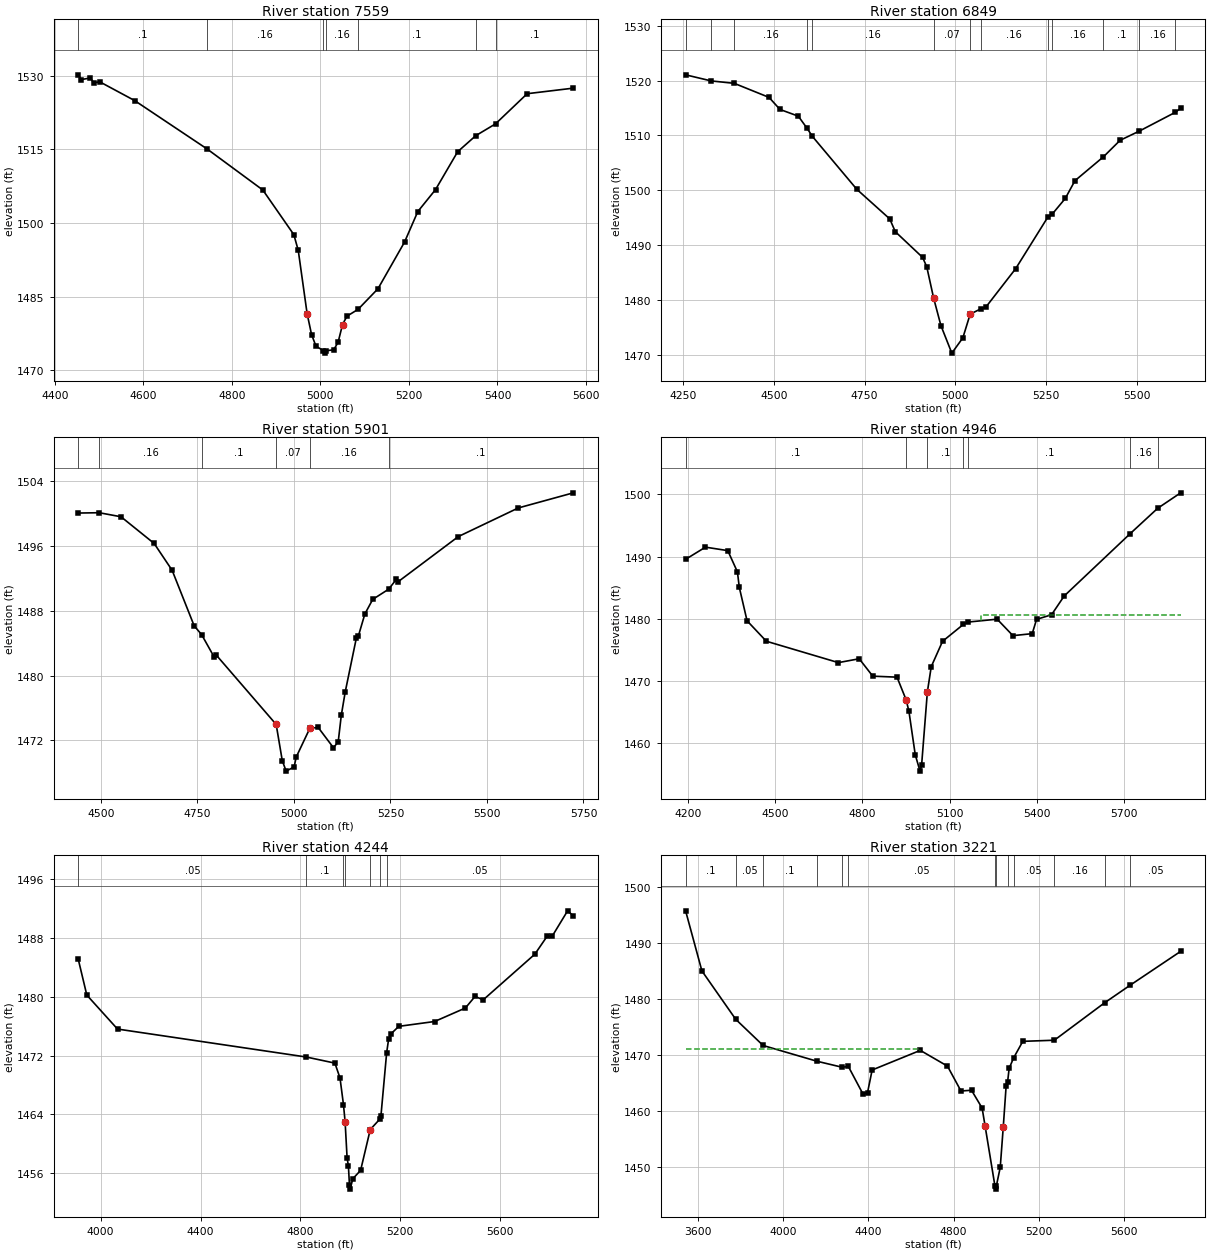
Type RM Length L Ch R = 1 ,7559    ,710,710,710
BEGIN DESCRIPTION:
CAVE CREEK 12.0
END DESCRIPTION:
XS GIS Cut Line= 3
      2811239.37     10059921.37      2811013.67     10059626.22
      2810267.18     10059617.54
#Sta/Elev= 30
  4453.3 1530.16  4459.8 1529.19  4480.6 1529.52  4488.1 1528.52  4501.5 1528.75
  4580.4 1524.93  4744.4 1515.06  4870.1 1506.72  4940.1 1497.64  4950.1 1494.43
  4970.1 1481.56  4980.1 1477.32  4990.1 1474.94  5007.1 1474.03  5009.8 1473.53
  5013.1 1474.03  5030.1 1474.19  5040.1 1475.75  5050.1 1479.35  5060.1 1481.05
  5085.2 1482.44  5130.1 1486.63  5190.1 1496.12  5220.1 1502.34  5260.1  1506.8
  5310.1 1514.51    5351 1517.78  5395.6 1520.18  5467.1 1526.32  5571.4 1527.45
#Mann= 7 ,-1 , 0
  4453.3      .1       0  4744.4     .16       0  5007.1     .07       0
  5013.1     .16       0  5085.2      .1       0    5351     .16       0
  5395.6      .1       0
Bank Sta=4970.1,5050.1
XS Rating Curve= 0 ,0
Exp/Cntr=0.3,0.1

Type RM Length L Ch R = 1 ,6849    ,948,948,948
BEGIN DESCRIPTION:
CAVE CREEK 11.0
END DESCRIPTION:
XS GIS Cut Line= 2
      2811586.61     10059018.58      2810232.91     10058853.71
#Sta/Elev= 30
  4257.2 1521.05  4327.7 1519.94  4391.1  1519.5    4487 1516.94  4517.2 1514.74
  4567.6 1513.52  4591.8 1511.31  4606.5 1509.83  4728.8 1500.19  4819.5  1494.8
  4834.8 1492.47  4910.1 1487.78  4921.5 1486.06  4940.4 1480.37  4960.5 1475.36
  4990.5 1470.34  5020.9 1473.12  5041.1 1477.45  5069.6 1478.38  5084.8 1478.77
  5166.4 1485.73  5254.4 1495.06  5266.7 1495.64    5303 1498.52  5329.7 1501.76
  5408.3 1506.12  5454.1 1509.12  5507.4 1510.81  5606.2 1514.22  5620.9 1514.96
#Mann= 13 ,-1 , 0
  4257.2     .16       0  4327.7      .1       0  4391.1     .16       0
  4591.8      .1       0  4606.5     .16       0  4940.4     .07       0
  5041.1      .1       0  5069.6     .16       0  5254.4      .1       0
  5266.7     .16       0  5408.3      .1       0  5507.4     .16       0
  5606.2      .1       0
Bank Sta=4940.4,5041.1
XS Rating Curve= 0 ,0
Exp/Cntr=0.3,0.1

Type RM Length L Ch R = 1 ,5901    ,955,955,955
BEGIN DESCRIPTION:
CAVE CREEK 9.0
END DESCRIPTION:
XS GIS Cut Line= 2
       2811517.1      10058115.8      2810258.45     10057872.75
#Sta/Elev= 30
  4441.9 1500.09  4496.1 1500.13  4552.5 1499.63  4638.3 1496.33  4684.9 1493.01
  4741.9 1486.15  4761.2 1485.06  4793.7 1482.29  4798.8 1482.55  4954.3 1473.95
  4970.1 1469.47  4980.1 1468.18  5000.7  1468.7  5006.2 1469.92  5041.4 1473.47
  5063.1 1473.58  5102.5 1471.08  5114.9 1471.79  5122.9 1475.08  5133.1 1477.98
  5161.7 1484.59  5166.8 1484.83    5184 1487.62  5204.4 1489.42  5245.4 1490.67
  5265.3 1491.88  5270.4 1491.61  5425.9 1497.18  5581.2 1500.72  5723.8 1502.59
#Mann= 6 ,-1 , 0
  4441.9      .1       0  4496.1     .16       0  4761.2      .1       0
  4954.3     .07       0  5041.4     .16       0  5245.4      .1       0
Bank Sta=4954.3,5041.4
XS Rating Curve= 0 ,0
Exp/Cntr=0.3,0.1

Type RM Length L Ch R = 1 ,4946    ,702,702,702
BEGIN DESCRIPTION:
CAVE CREEK 7.0
END DESCRIPTION:
XS GIS Cut Line= 2
      2811725.45     10057369.27      2810093.51     10056883.16
#Sta/Elev= 30
  4191.8 1489.56  4260.1 1491.52  4336.9 1490.96    4370 1487.54  4376.5 1485.05
  4403.2 1479.67  4469.5 1476.38  4717.3 1472.94  4788.9 1473.56  4835.6 1470.76
    4919  1470.6  4950.3 1466.95  4959.9 1465.12  4981.7 1458.11  4998.1 1455.48
  5003.5 1456.42  5023.4 1468.24  5036.7 1472.29  5075.6 1476.37  5147.3 1479.09
  5164.3 1479.47  5263.4 1479.93  5317.7 1477.28    5384  1477.6    5399  1479.9
  5450.4 1480.64    5494 1483.66  5721.4 1493.71  5815.5 1497.77  5894.6 1500.26
#Mann= 7 ,-1 , 0
  4191.8      .1       0  4950.3     .07       0  5023.4      .1       0
  5147.3     .16       0  5164.3      .1       0  5721.4     .16       0
  5815.5      .1       0
#XS Ineff= 2 , 0
                         5207.98         1480.54
Permanent Ineff=
       F       F
Bank Sta=4950.3,5023.4
XS Rating Curve= 0 ,0
Exp/Cntr=0.3,0.1

Type RM Length L Ch R = 1 ,4244    ,1023,1023,1023
BEGIN DESCRIPTION:
CAVE CREEK 6.0
END DESCRIPTION:
XS GIS Cut Line= 2
      2812341.81     10056770.32      2810405.99     10056344.96
#Sta/Elev= 30
  3910.6 1485.11  3944.7 1480.25  4067.6 1475.62  4823.6 1471.81  4937.9 1470.98
  4958.4 1468.95  4972.2 1465.34  4978.8 1462.99  4986.8 1458.04    4992 1456.99
  4996.3 1454.31  4999.1 1453.81  5009.6 1455.22  5040.9 1456.37  5079.5 1461.93
  5117.3 1463.33  5122.2 1463.77  5145.2 1472.42  5152.9 1474.22  5163.1 1474.99
  5193.8 1475.99  5337.2 1476.65  5460.4 1478.49  5499.1 1480.07  5531.7  1479.6
  5738.4 1485.82  5787.7 1488.27  5808.2 1488.29  5869.6 1491.73  5892.6 1491.05
#Mann= 7 ,-1 , 0
  3910.6     .05       0  4823.6      .1       0  4972.2     .16       0
  4978.8     .07       0  5079.5     .16       0  5117.3      .1       0
  5145.2     .05       0
Bank Sta=4978.8,5079.5
XS Rating Curve= 0 ,0
Exp/Cntr=0.3,0.1

Type RM Length L Ch R = 1 ,3221    ,1315,1315,1315
BEGIN DESCRIPTION:
CAVE CREEK 5.0
END DESCRIPTION:
XS GIS Cut Line= 3
      2812598.18     10056582.17      2811317.49     10055407.47
      2810732.16     10055350.84
#Sta/Elev= 30
  3540.9 1495.67  3617.5 1484.95  3776.4 1476.32  3905.1 1471.65  4158.2 1468.84
  4276.3 1467.77  4305.5 1467.91  4374.7 1462.96  4395.7 1463.25  4417.3 1467.28
  4643.6 1470.78  4771.2 1467.97  4834.7 1463.53  4884.1 1463.67    4934 1460.49
  4948.2 1457.24  4994.5 1446.53  4997.3 1446.03  5000.5 1446.53  5019.1 1449.91
  5033.2 1457.04  5046.8 1464.42  5053.6 1465.11    5061 1467.57  5081.7 1469.42
  5125.1 1472.39  5273.3 1472.59  5509.2 1479.26    5631 1482.44  5866.8 1488.44
#Mann= 13 ,-1 , 0
  3540.9      .1       0  3776.4     .05       0  3905.1      .1       0
  4158.2     .05       0  4276.3      .1       0  4305.5     .05       0
  4994.5    .035       0  5000.5     .05       0  5053.6      .1       0
  5081.7     .05       0  5273.3     .16       0  5509.2      .1       0
    5631     .05       0
#XS Ineff= 2 , 0
         4641.17 1470.95
Permanent Ineff=
       F       F
Bank Sta=4948.2,5033.2
XS Rating Curve= 0 ,0
Exp/Cntr=0.3,0.1

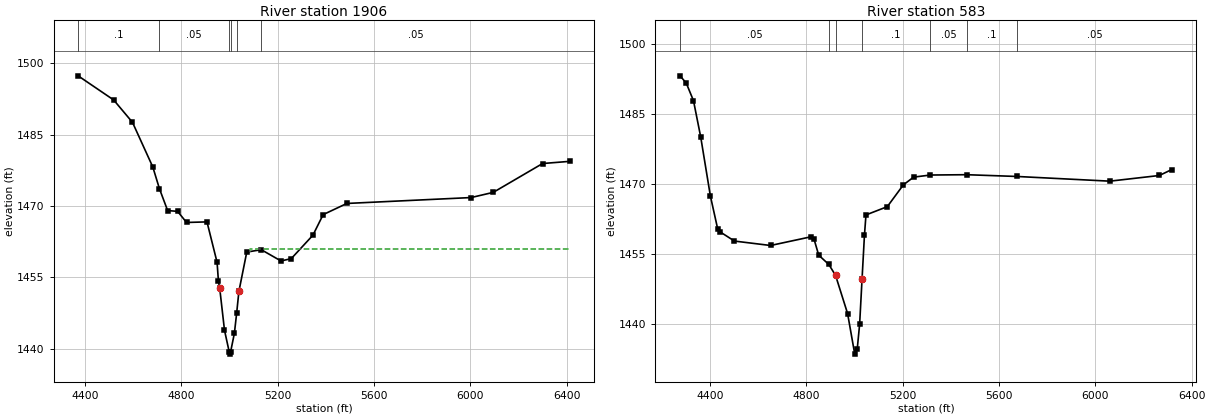
Type RM Length L Ch R = 1 ,1906    ,1323,1323,1323
BEGIN DESCRIPTION:
CAVE CREEK 2.0
END DESCRIPTION:
XS GIS Cut Line= 4
      2812804.37     10056255.68      2812592.47     10056009.41
      2812432.09     10055324.95      2811703.24     10054618.96
#Sta/Elev= 30
  4371.1 1497.37  4518.8 1492.29  4596.9 1487.58  4681.4 1478.18  4708.8 1473.63
  4742.9 1469.02  4784.2 1468.86  4821.5 1466.52  4906.4 1466.64  4948.3 1458.13
    4954 1454.11  4959.2  1452.7  4979.1 1443.85  4998.6 1439.32  5001.4 1438.82
  5004.6 1439.32  5020.2 1443.21  5029.9 1447.57  5038.9 1452.01  5071.6 1460.29
  5131.9 1460.79  5213.9 1458.42  5256.4 1458.91  5346.4 1463.84  5388.9 1468.17
  5487.4 1470.52  6003.4 1471.76  6095.5 1472.85  6300.5 1478.92  6413.7 1479.38
#Mann= 6 ,-1 , 0
  4371.1      .1       0  4708.8     .05       0  4998.6    .035       0
  5004.6     .05       0  5029.9     .16       0  5131.9     .05       0
#XS Ineff= 2 , 0
                         5085.24         1460.91
Permanent Ineff=
       F       F
Bank Sta=4959.2,5038.9
XS Rating Curve= 0 ,0
Exp/Cntr=0.3,0.1

Type RM Length L Ch R = 1 ,583     ,0,0,0
BEGIN DESCRIPTION:
CAVE CREEK 1.0
END DESCRIPTION:
XS GIS Cut Line= 3
      2813165.24     10056029.48      2813173.83     10055221.85
      2812117.09     10054583.22
#Sta/Elev= 30
  4275.1 1493.26  4300.8 1491.69  4330.8 1487.91  4360.8 1480.11  4400.9 1467.44
  4430.9 1460.43  4440.9 1459.72  4500.9 1457.73  4650.9 1456.78  4820.9 1458.67
  4830.9 1458.25  4850.9  1454.7  4892.9  1452.7  4920.9 1450.35  4970.9 1442.14
  5000.6 1433.42  5010.9  1434.5  5020.9 1439.85  5030.9 1449.53  5040.9 1458.98
  5047.2 1463.35  5135.8 1465.13  5202.4 1469.81  5245.1 1471.48    5315 1471.93
  5465.2    1472  5674.3 1471.62  6060.1 1470.61  6265.7 1471.83  6317.5 1473.11
#Mann= 7 ,-1 , 0
  4275.1     .05       0  4892.9      .1       0  4920.9     .07       0
  5030.9      .1       0    5315     .05       0  5465.2      .1       0
  5674.3     .05       0
#XS Ineff= 2 , 0
         4820.32 1458.56
Permanent Ineff=
       F       F
Bank Sta=4920.9,5030.9
XS Rating Curve= 0 ,0
Exp/Cntr=0.3,0.1

Chan Stop Cuts=-1
Use User Specified Reach Order=0
Composite Channel Slope=5