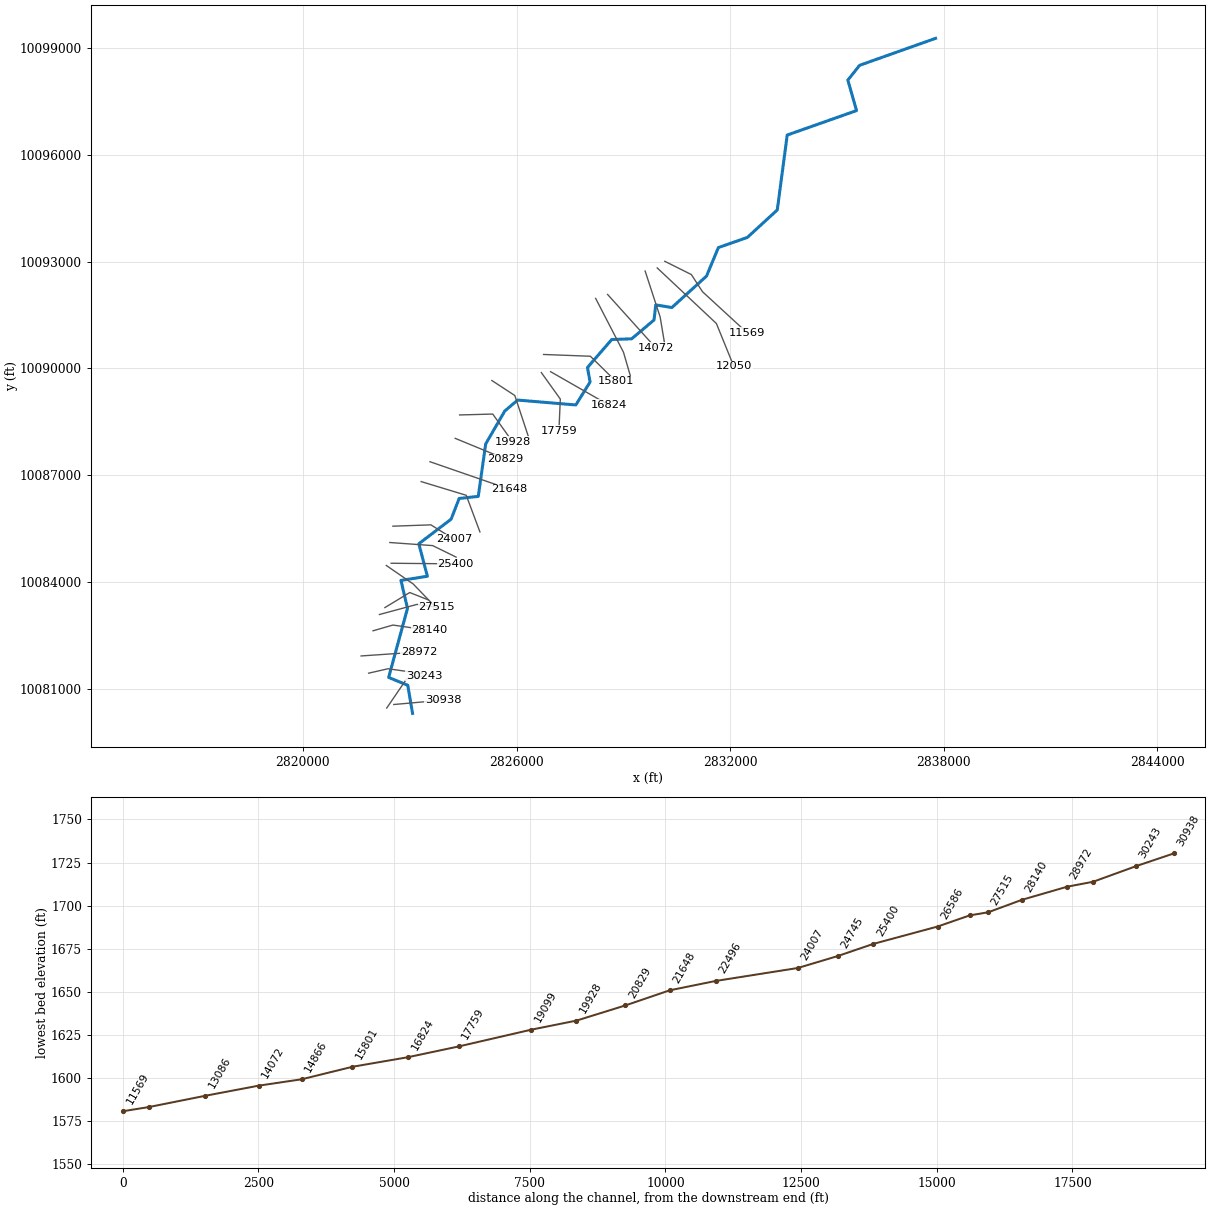
--- DRY HOLLOW CREEK.prj (project) ---

Proj Title=DRY HOLLOW CREEK Base Level Engineering
Current Plan=p01
Default Exp/Contr=0.3,0.1
English Units
Geom File=g01
Flow File=f01
Plan File=p01
Y Axis Title=Elevation
X Axis Title(PF)=Main Channel Distance
X Axis Title(XS)=Station
BEGIN DESCRIPTION:
DRY HOLLOW CREEK
END DESCRIPTION:
DSS Export Rating Curves= 0
DSS Export Rating Curve Sorted= 0
DSS Export Volume Flow Curves= 0
DXF OffsetX= 0
DXF OffsetY= 0
DXF ScaleX= 1
DXF ScaleY= 10

--- DRY HOLLOW CREEK.p01 (plan) ---

Plan Title=Multiple Run
Short Identifier=Multiple
Geom File=g01
Flow File=f01
Subcritical Flow
K Sum by GR= 0
Std Step Tol= 0.01
Critical Tol= 0.01
Num of Std Step Trials= 20
Max Error Tol= 0.3
Flow Tol Ratio= 0.001
Split Flow NTrial= 30
Split Flow Tol= 0.02
Split Flow Ratio= 0.02
Log Output Level= 0
Friction Slope Method= 1
Unsteady Friction Slope Method= 2
Unsteady Bridges Friction Slope Method= 1
Parabolic Critical Depth
Global Vel Dist=  1 , 1 , 1
Global Log Level= 0
CheckData=True
Encroach Param= -1, 0, 0, 0
BEGIN DESCRIPTION:
Multiple Run
END DESCRIPTION:

--- DRY HOLLOW CREEK.f01 (steady flow) ---

Flow Title=Multiple
Program Version=4.10
Number of Profiles= 7
Profile Names=10-year,25-year,50-year,1pct_min,100-year,1pct_plu,500-year
River Rch & RM=DRY HOLLOW CREEK,Reach-1         ,30938
     891    1292    1640    1524    2061    2788    3269
River Rch & RM=DRY HOLLOW CREEK,Reach-1         ,30243
    1069    1561    1991    1858    2513    3398    4017
River Rch & RM=DRY HOLLOW CREEK,Reach-1         ,26586
    1658    2472    3197    3020    4084    5523    6694
River Rch & RM=DRY HOLLOW CREEK,Reach-1         ,22496
    2191    3297    4290    4072    5507    7447    9116
River Rch & RM=DRY HOLLOW CREEK,Reach-1         ,14866
    2376    3580    4662    4426    5985    8094    9914
River Rch & RM=DRY HOLLOW CREEK,Reach-1         ,12050
    3566    5460    7186    6888    9315   12597   15727
River Rch & RM=DRY HOLLOW CREEK,Reach-1         ,10790
    3566    5460    7186    6888    9315   12597   15727
River Rch & RM=DRY HOLLOW CREEK,Reach-1         ,4977
    3692    5649    7432    7118    9626   13018   16229
Boundary for River Rch & Prof#=DRY HOLLOW CREEK,Reach-1         , 1
Up Type= 0
Dn Type= 3
Dn Slope=0.0062
Boundary for River Rch & Prof#=DRY HOLLOW CREEK,Reach-1         , 2
Up Type= 0
Dn Type= 3
Dn Slope=0.0062
Boundary for River Rch & Prof#=DRY HOLLOW CREEK,Reach-1         , 3
Up Type= 0
Dn Type= 3
Dn Slope=0.0062
Boundary for River Rch & Prof#=DRY HOLLOW CREEK,Reach-1         , 4
Up Type= 0
Dn Type= 3
Dn Slope=0.0062
Boundary for River Rch & Prof#=DRY HOLLOW CREEK,Reach-1         , 5
Up Type= 0
Dn Type= 3
Dn Slope=0.0062
Boundary for River Rch & Prof#=DRY HOLLOW CREEK,Reach-1         , 6
Up Type= 0
Dn Type= 3
Dn Slope=0.0062
Boundary for River Rch & Prof#=DRY HOLLOW CREEK,Reach-1         , 7
Up Type= 0
Dn Type= 3
Dn Slope=0.0062
DSS Import GetInterval= 0
DSS Import GetPeak= 0
DSS Import FillOption= 0

--- DRY HOLLOW CREEK.g01 (geometry) ---

Geom Title=Existing Conditions
Program Version=4.10

River Reach=DRY HOLLOW CREEK,Reach-1
Reach XY= 30
      2823080.03      10080301.9      2822945.02     10081091.89
      2822408.26     10081312.45       2822937.4     10083254.14
      2822754.19     10084039.59      2823495.86     10084157.03
      2823255.37     10085069.97      2824163.26     10085761.65
      2824388.68     10086343.56      2824925.36     10086402.58
      2825134.66     10087877.61       2825670.3     10088803.04
      2826033.24     10089109.98      2827666.05     10088972.58
      2828066.31     10089617.64      2827993.84      10090025.9
      2828675.55      10090812.4      2829234.17     10090831.62
      2829863.66     10091361.01      2829911.23     10091785.49
       2830364.6     10091711.52      2831337.64     10092594.03
       2831670.8     10093396.41      2832484.96     10093681.95
      2833326.01     10094454.77      2833604.99     10096560.51
      2835552.98     10097248.03      2835308.31     10098105.48
      2835639.48     10098521.42      2837773.75     10099279.31

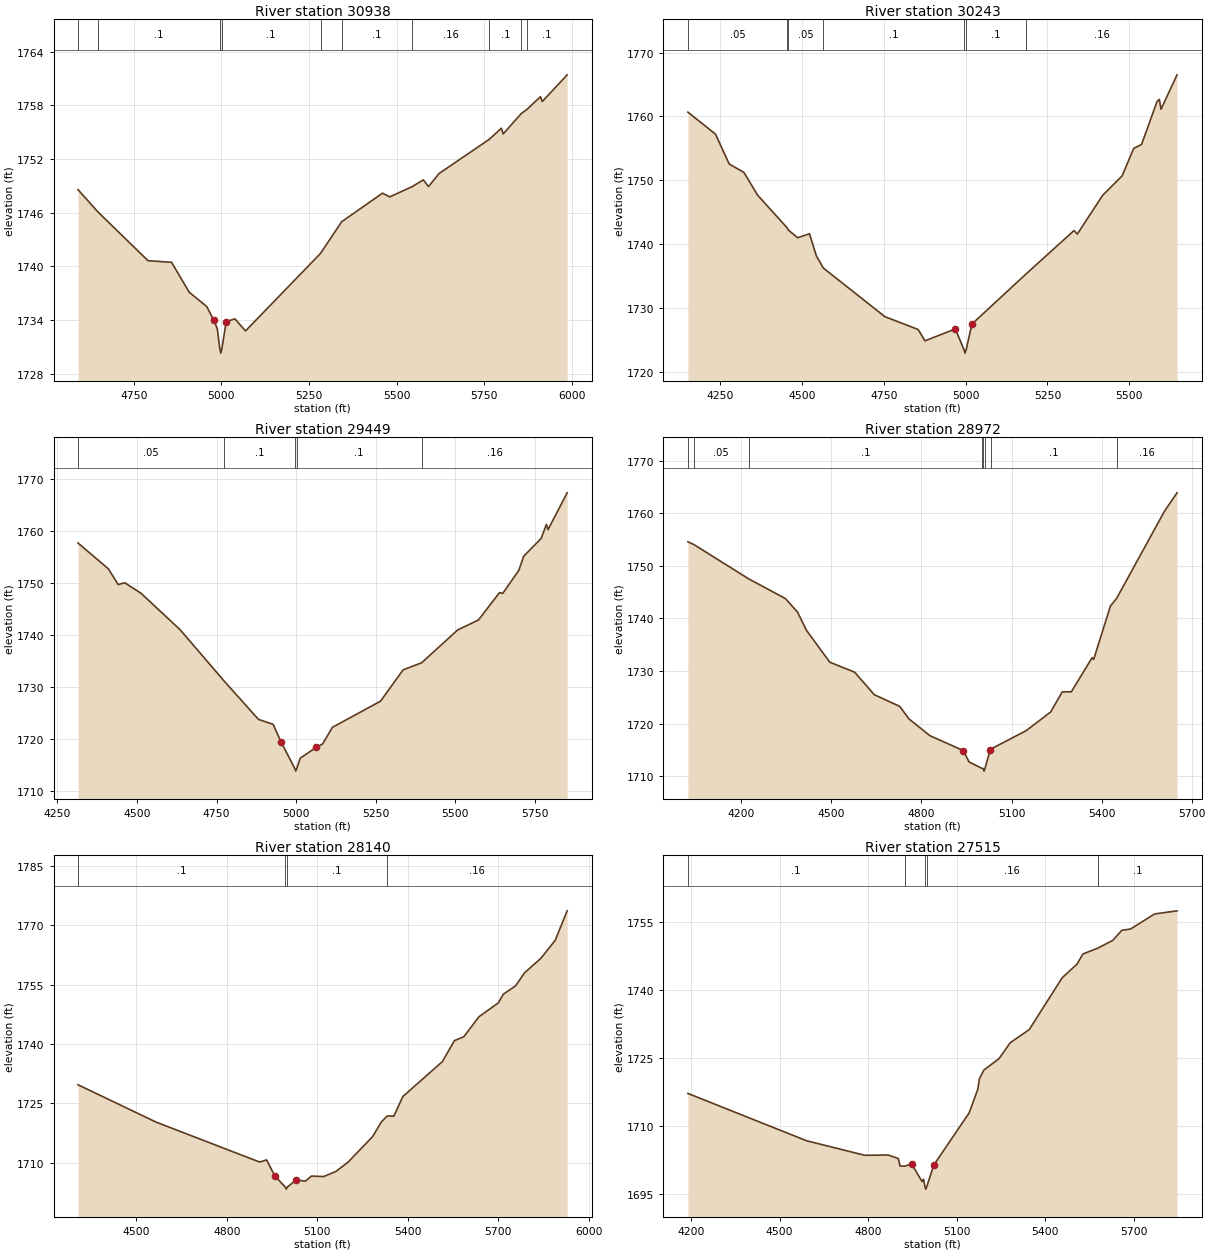
Type RM Length L Ch R = 1 ,30938   ,695,695,695
BEGIN DESCRIPTION:
UNT091 IN NNOGR 9.0
END DESCRIPTION:
XS GIS Cut Line= 2
      2822552.59     10080551.12      2823942.36     10080675.21
#Sta/Elev= 30
  4591.1 1748.57  4648.3 1746.06  4790.9 1740.62    4858 1740.44  4908.2  1737.1
  4958.4 1735.49  4978.5 1733.96  4988.6 1732.99  4995.6 1730.78  4998.3 1730.28
  5001.6 1730.78  5013.8 1733.81  5038.8 1734.11  5068.9 1732.76    5283 1741.44
  5343.3 1744.98  5459.6 1748.17  5480.5 1747.76  5544.1  1748.9  5576.1 1749.66
  5590.9 1748.91  5621.1 1750.37  5764.7 1754.21  5798.9 1755.44    5804  1754.8
  5855.6 1757.08  5872.1 1757.56  5910.4 1758.97  5915.4 1758.42  5986.4 1761.41
#Mann= 10 ,-1 , 0
  4591.1     .05       0  4648.3      .1       0  4995.6     .07       0
  5001.6      .1       0    5283     .16       0  5343.3      .1       0
  5544.1     .16       0  5764.7      .1       0  5855.6     .16       0
  5872.1      .1       0
Bank Sta=4978.5,5013.8
XS Rating Curve= 0 ,0
Exp/Cntr=0.3,0.1

Type RM Length L Ch R = 1 ,30243   ,794,794,794
BEGIN DESCRIPTION:
UNT091 IN NNOGR 8.0
END DESCRIPTION:
XS GIS Cut Line= 3
      2822354.01     10080451.88      2822912.41     10081270.86
      2823408.74     10081357.72
#Sta/Elev= 30
  4151.2 1760.68  4235.6 1757.23  4277.5 1752.55  4322.3 1751.24  4364.2 1747.67
  4453.9 1742.59  4458.4 1742.18  4486.9 1740.99  4522.8 1741.62  4543.8 1738.15
  4565.3 1736.24  4753.2 1728.62  4854.8 1726.61  4875.8 1724.83  4968.6 1726.69
  4995.5  1723.4  4998.2  1722.9  5001.5  1723.4  5019.4 1727.46    5185 1735.32
  5331.3 1742.11  5341.5 1741.57  5418.9 1747.64  5478.3 1750.68    5514 1755.01
  5537.8 1755.61  5585.1 1762.34  5592.2 1762.68  5597.3 1761.13  5646.3 1766.53
#Mann= 7 ,-1 , 0
  4151.2     .05       0  4453.9      .1       0  4458.4     .05       0
  4565.3      .1       0  4995.5     .07       0  5001.5      .1       0
    5185     .16       0
Bank Sta=4968.6,5019.4
XS Rating Curve= 0 ,0
Exp/Cntr=0.3,0.1

Type RM Length L Ch R = 1 ,29449   ,477,477,477
BEGIN DESCRIPTION:
UNT091 IN NNOGR 5.0
END DESCRIPTION:
XS GIS Cut Line= 3
      2821845.22     10081432.18      2822391.22     10081556.27
      2823359.12     10081419.77
#Sta/Elev= 30
  4314.5 1757.63  4410.1 1752.66  4440.9 1749.65  4461.4    1750  4512.7 1747.97
  4635.7 1740.96  4773.8 1731.12  4881.7 1723.75  4927.8  1722.8  4952.4 1719.45
    4996 1714.31  4998.7 1713.81    5002 1714.31    5013  1716.3  5063.5 1718.38
  5083.7 1719.06    5114 1722.22  5265.5 1727.25  5336.2 1733.26  5394.7 1734.63
  5507.9 1740.93  5573.2 1742.85  5639.2  1748.1  5649.4 1747.95  5699.8 1752.36
  5715.5  1755.1  5770.4 1758.53  5786.7 1761.22  5791.7 1760.19  5851.9 1767.27
#Mann= 5 ,-1 , 0
  4314.5     .05       0  4773.8      .1       0    4996     .07       0
    5002      .1       0  5394.7     .16       0
Bank Sta=4952.4,5063.5
XS Rating Curve= 0 ,0
Exp/Cntr=0.3,0.1

Type RM Length L Ch R = 1 ,28972   ,832,832,832
BEGIN DESCRIPTION:
UNT091 IN NNOGR 4.0
END DESCRIPTION:
XS GIS Cut Line= 2
      2821634.21     10081916.14      2823259.88     10082027.83
#Sta/Elev= 30
  4021.9 1754.59  4041.5 1754.08  4224.1 1747.55  4346.7 1743.79    4387 1741.23
  4417.1 1737.73  4494.8 1731.67  4577.5 1729.78    4643 1725.49  4727.8 1723.27
  4757.9 1720.91    4828  1717.7  4939.2 1714.87  4958.4 1712.71  5001.7 1711.47
  5005.5 1711.45  5008.2 1710.95  5011.5 1711.45  5028.5 1714.88  5030.8 1715.14
  5148.8 1718.65  5230.4 1722.21  5269.1 1726.05  5299.2 1726.04  5368.6 1732.55
  5373.6  1732.2  5429.5 1742.37  5450.3 1743.84  5609.9 1760.45  5651.4 1763.91
#Mann= 8 ,-1 , 0
  4021.9      .1       0  4041.5     .05       0  4224.1      .1       0
  5001.7     .05       0  5005.5     .07       0  5011.5     .05       0
  5030.8      .1       0  5450.3     .16       0
Bank Sta=4939.2,5028.5
XS Rating Curve= 0 ,0
Exp/Cntr=0.3,0.1

Type RM Length L Ch R = 1 ,28140   ,625,625,625
BEGIN DESCRIPTION:
UNT091 IN NNOGR 2.0
END DESCRIPTION:
XS GIS Cut Line= 3
      2821969.33     10082623.48      2822527.72      10082784.8
      2823557.69     10082635.88
#Sta/Elev= 30
  4306.9 1729.73  4566.2 1720.28  4909.1  1710.2  4932.4 1710.74  4959.6 1706.65
  4994.7 1703.85  4997.4 1703.35  5000.7 1703.85  5030.3 1705.68  5060.6 1705.36
  5080.9 1706.65  5121.3 1706.53  5161.7  1707.8  5202.1 1710.15    5284 1716.65
  5313.2 1720.39  5332.2 1721.83  5354.3 1721.81    5384 1726.76  5515.3  1735.6
  5555.1  1740.9    5586 1741.86  5636.6 1746.94  5700.7 1750.45  5717.4 1752.63
  5757.8 1754.74  5788.1 1758.08  5841.4 1761.67  5889.2 1766.24  5928.8  1773.7
#Mann= 4 ,-1 , 0
  4306.9      .1       0  4994.7     .07       0  5000.7      .1       0
  5332.2     .16       0
Bank Sta=4959.6,5030.3
XS Rating Curve= 0 ,0
Exp/Cntr=0.3,0.1

Type RM Length L Ch R = 1 ,27515   ,340,340,340
BEGIN DESCRIPTION:
Mapping XS 2cd8df5e
END DESCRIPTION:
XS GIS Cut Line= 3
      2822149.75     10083081.34      2823205.34     10083366.07
      2823763.95      10083282.8
#Sta/Elev= 30
  4189.2 1717.19  4591.8 1706.75  4788.5 1703.55  4868.3 1703.61  4902.5 1702.83
  4908.2  1701.2  4923.7 1701.16  4948.1 1701.61  4982.9 1697.75  4988.1 1698.28
  4992.7 1696.59  4995.5 1696.09  4998.7 1696.59  5022.8 1701.41  5142.5 1712.89
  5171.8 1718.08  5177.3 1720.39  5192.5 1722.34  5244.3 1724.89  5281.5 1728.35
  5346.3 1731.26  5457.6 1742.67  5508.1 1745.69  5528.3 1747.94  5579.2 1749.24
  5629.4 1750.93  5659.8 1753.14  5690.1 1753.45    5771 1756.76  5847.3 1757.45
#Mann= 5 ,-1 , 0
  4189.2      .1       0  4923.7     .16       0  4992.7     .07       0
  4998.7     .16       0  5579.2      .1       0
Bank Sta=4948.1,5022.8
XS Rating Curve= 0 ,0
Exp/Cntr=0.3,0.1

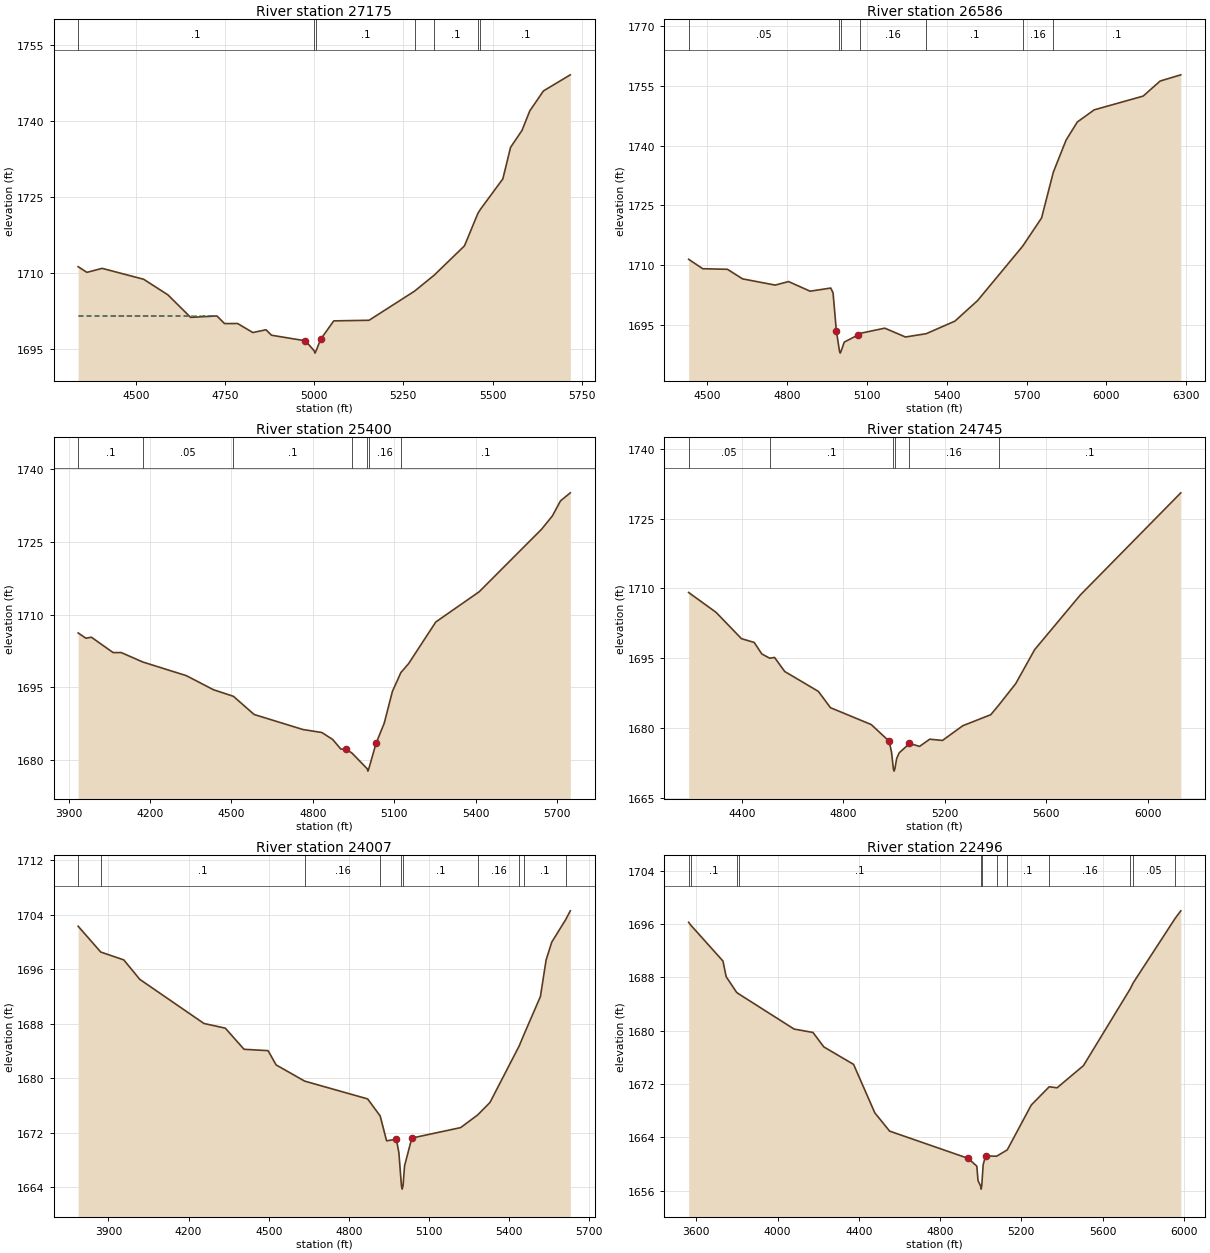
Type RM Length L Ch R = 1 ,27175   ,589,589,589
BEGIN DESCRIPTION:
UNT091 IN NNOGR 1.0
END DESCRIPTION:
XS GIS Cut Line= 3
      2822302.59     10083275.81      2823000.47      10083699.4
      2823524.17     10083491.31
#Sta/Elev= 30
  4338.2 1711.33  4362.9 1710.21  4405.5    1711  4521.8 1708.85  4589.6 1705.79
  4653.6 1701.33  4727.3 1701.61  4748.6 1700.11  4785.4 1700.12  4828.1 1698.34
  4864.9 1698.89  4880.4 1697.81  4975.4 1696.71  4999.6 1694.78  5002.3 1694.28
  5005.6 1694.78    5018    1697  5054.9 1700.64  5153.9 1700.76  5281.3  1706.5
  5336.7 1709.67  5421.4 1715.44  5459.1 1721.86  5466.2 1722.65    5529 1728.65
  5550.6 1734.86  5582.8 1738.22  5604.4 1742.05  5642.9    1746  5718.1 1749.17
#Mann= 7 ,-1 , 0
  4338.2      .1       0  4999.6     .07       0  5005.6      .1       0
  5281.3     .16       0  5336.7      .1       0  5459.1     .16       0
  5466.2      .1       0
#XS Ineff= 2 , 0
         4726.54 1701.64
Permanent Ineff=
       F       F
Bank Sta=4975.4,5018
XS Rating Curve= 0 ,0
Exp/Cntr=0.3,0.1

Type RM Length L Ch R = 1 ,26586   ,1186,1186,1186
BEGIN DESCRIPTION:
DRY HOLLOW CREEK 53.0
END DESCRIPTION:
XS GIS Cut Line= 3
       2822341.6     10084460.04      2823098.55     10083938.86
      2823743.62     10083268.98
#Sta/Elev= 30
  4430.2 1711.43  4483.2 1709.06  4575.9 1708.92  4632.8 1706.51  4755.1 1704.95
  4805.8 1705.83  4886.3 1703.41  4964.1  1704.2  4972.7 1702.98    4985 1693.52
  4996.9 1688.33  4999.7 1687.83  5002.9 1688.33  5014.8  1690.6  5065.6 1692.37
  5075.8 1692.82    5167 1694.11  5244.8 1691.89  5322.8 1692.72  5430.5 1695.88
  5515.4 1701.03  5685.1 1714.74    5756 1721.82  5800.3 1733.35  5847.8 1741.37
  5890.3 1745.97  5953.8 1749.03  6137.8 1752.49  6201.6 1756.28  6279.2 1757.84
#Mann= 7 ,-1 , 0
  4430.2     .05       0  4996.9    .035       0  5002.9     .05       0
  5075.8     .16       0  5322.8      .1       0  5685.1     .16       0
  5800.3      .1       0
Bank Sta=4985,5065.6
XS Rating Curve= 0 ,0
Exp/Cntr=0.3,0.1

Type RM Length L Ch R = 1 ,25400   ,655,655,655
BEGIN DESCRIPTION:
DRY HOLLOW CREEK 51.0
END DESCRIPTION:
XS GIS Cut Line= 2
      2822479.64     10084522.32      2824294.56     10084504.97
#Sta/Elev= 30
  3934.6 1706.23  3963.4 1705.14  3983.4 1705.35  4063.4 1702.19  4093.4 1702.19
  4173.4 1700.23  4333.4 1697.43  4433.4 1694.53  4507.4 1693.16  4583.5 1689.42
  4763.5 1686.32  4833.5  1685.7  4873.5 1684.26  4903.5 1682.28  4923.5 1682.25
  4944.6 1681.45  5000.5 1678.24  5003.2 1677.74  5006.5 1678.24  5033.5 1683.51
  5063.5 1687.64  5093.5 1694.17  5124.8 1698.06  5153.5 1699.92  5253.5 1708.49
  5413.5 1714.72  5643.5  1727.6  5683.5 1730.36  5713.5 1733.46  5749.6 1735.12
#Mann= 7 ,-1 , 0
  3934.6      .1       0  4173.4     .05       0  4507.4      .1       0
  4944.6     .16       0  5000.5     .07       0  5006.5     .16       0
  5124.8      .1       0
Bank Sta=4923.5,5033.5
XS Rating Curve= 0 ,0
Exp/Cntr=0.3,0.1

Type RM Length L Ch R = 1 ,24745   ,738,738,738
BEGIN DESCRIPTION:
DRY HOLLOW CREEK 50.0
END DESCRIPTION:
XS GIS Cut Line= 3
      2822440.88     10085105.34      2823644.56     10085018.47
      2824302.27     10084695.82
#Sta/Elev= 30
  4190.2 1709.11  4298.1 1704.85  4398.3 1699.18  4448.5 1698.37  4478.5 1695.89
  4509.5 1694.98  4528.7 1695.14  4568.8 1692.12  4701.4 1687.84  4749.2 1684.33
  4909.6 1680.71  4980.7  1677.1  4989.9 1674.69  4996.9 1671.19  4999.6 1670.69
  5002.9 1671.19  5009.9 1673.41  5019.9 1674.63  5057.2 1676.46    5060 1676.66
  5100.1 1676.01  5140.2 1677.56  5190.4 1677.29  5270.6 1680.46  5380.9 1682.83
  5412.7 1684.92  5479.3 1689.53  5553.5 1696.81  5733.5 1708.57  6129.6 1730.55
#Mann= 6 ,-1 , 0
  4190.2     .05       0  4509.5      .1       0  4996.9     .07       0
  5002.9      .1       0  5057.2     .16       0  5412.7      .1       0
Bank Sta=4980.7,5060
XS Rating Curve= 0 ,0
Exp/Cntr=0.3,0.1

Type RM Length L Ch R = 1 ,24007   ,1511,1511,1511
BEGIN DESCRIPTION:
DRY HOLLOW CREEK 48.0
END DESCRIPTION:
XS GIS Cut Line= 3
      2822527.71     10085564.48      2823594.92     10085601.71
       2824252.6     10085192.21
#Sta/Elev= 30
  3786.5 1702.31  3871.2 1698.52  3957.4 1697.37  4017.4 1694.51  4257.5 1688.04
  4337.6 1687.35  4407.6 1684.25  4497.7 1684.05  4527.7 1681.96  4634.6 1679.58
  4870.3 1676.97  4917.3 1674.47  4941.3 1670.82  4977.9 1671.05  4987.3 1669.09
  4996.9 1664.23  4999.6 1663.73  5002.9 1664.23  5008.6 1667.15  5035.7 1671.22
  5218.6 1672.76  5282.7 1674.63  5328.4 1676.45  5437.7 1684.74    5455 1686.36
  5517.2 1691.99  5538.5 1697.35  5559.7 1699.98  5611.7 1703.27  5629.1 1704.57
#Mann= 10 ,-1 , 0
  3786.5     .05       0  3871.2      .1       0  4634.6     .16       0
  4917.3      .1       0  4996.9     .07       0  5002.9      .1       0
  5282.7     .16       0  5437.7     .05       0    5455      .1       0
  5611.7     .05       0
Bank Sta=4977.9,5035.7
XS Rating Curve= 0 ,0
Exp/Cntr=0.3,0.1

Type RM Length L Ch R = 1 ,22496   ,848,848,848
BEGIN DESCRIPTION:
DRY HOLLOW CREEK 46.0
END DESCRIPTION:
XS GIS Cut Line= 3
      2823321.89     10086817.83      2824587.67     10086433.13
      2824972.35     10085403.18
#Sta/Elev= 30
  3562.7 1696.28  3572.1 1695.89  3731.6 1690.46  3747.3 1688.12  3799.2 1685.74
  3810.8  1685.5  4081.7 1680.25  4174.6 1679.74    4228 1677.57  4374.4 1674.95
  4478.9 1667.68  4551.8 1664.93  4938.4 1660.84  4981.1 1659.67  4987.2 1657.48
  4999.4 1656.72  5002.2 1656.22  5005.4 1656.72  5012.2 1659.86  5023.8 1661.21
  5078.5 1661.16  5130.8 1662.11  5249.2 1668.85  5337.4 1671.59    5376 1671.43
  5505.9 1674.76  5737.2 1686.34  5750.7 1687.18  5957.3 1696.87  5985.1    1698
#Mann= 12 ,-1 , 0
  3562.7     .05       0  3572.1      .1       0  3799.2     .16       0
  3810.8      .1       0  4999.4     .07       0  5005.4      .1       0
  5078.5     .16       0  5130.8      .1       0  5337.4     .16       0
  5737.2      .1       0  5750.7     .05       0  5957.3      .1       0
Bank Sta=4938.4,5023.8
XS Rating Curve= 0 ,0
Exp/Cntr=0.3,0.1

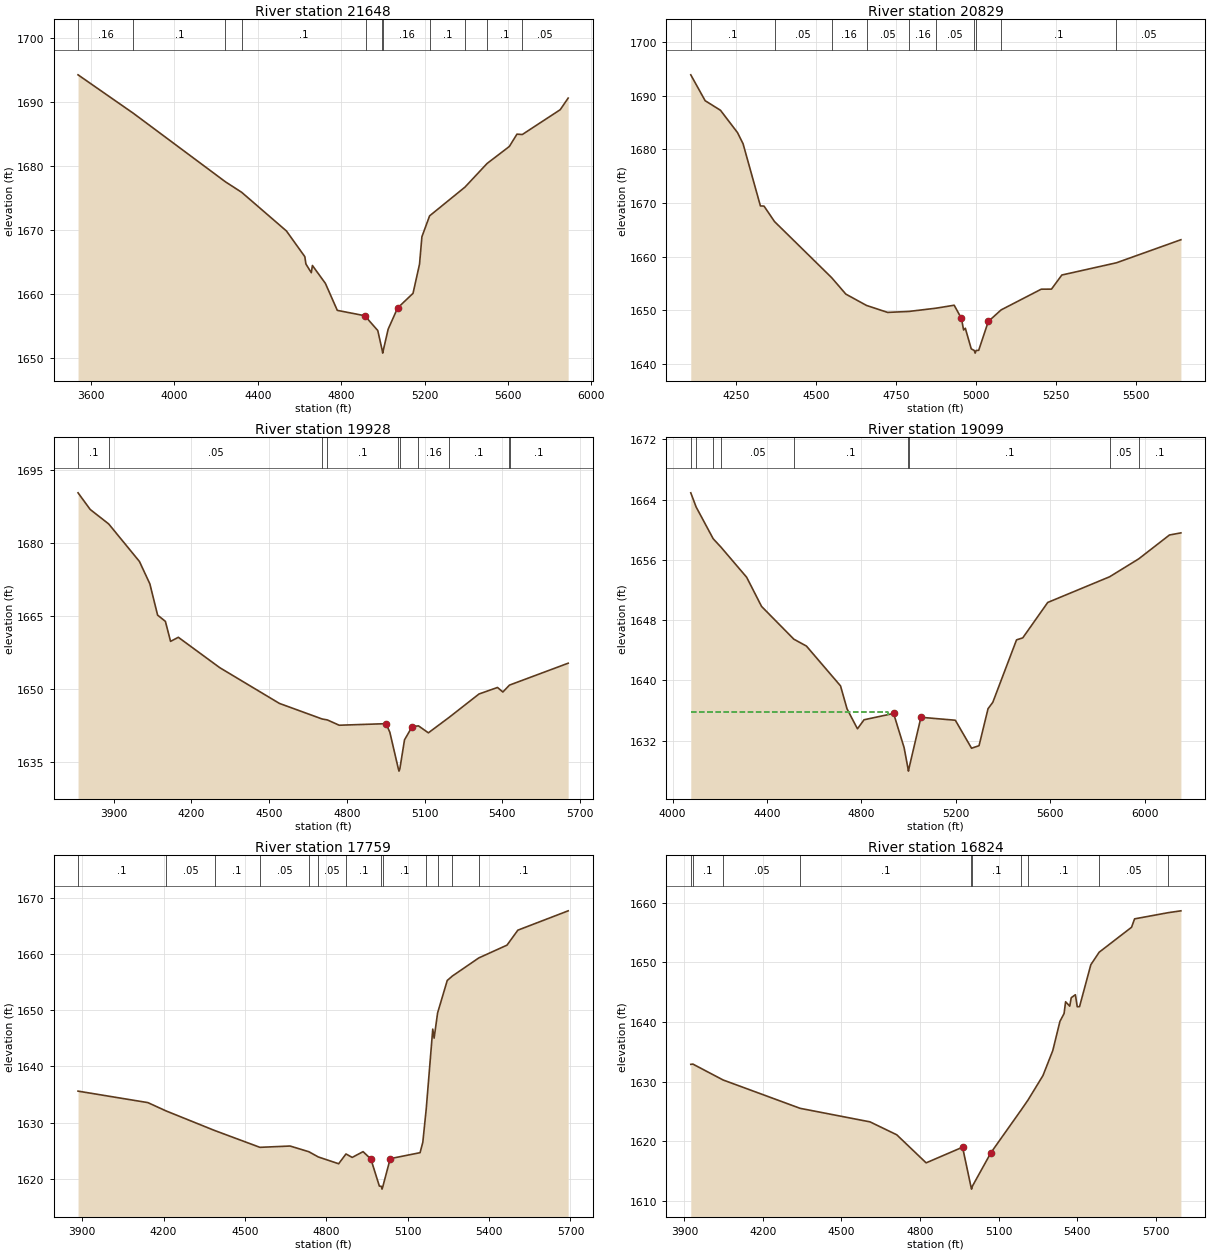
Type RM Length L Ch R = 1 ,21648   ,819,819,819
BEGIN DESCRIPTION:
DRY HOLLOW CREEK 45.0
END DESCRIPTION:
XS GIS Cut Line= 2
      2823570.14     10087376.23      2825791.37     10086606.87
#Sta/Elev= 30
  3537.6 1694.26    3803 1688.25  4244.5 1677.55  4322.4 1675.91  4537.1 1669.87
  4625.2 1665.86  4630.5 1664.71  4656.4 1663.35  4661.7 1664.48    4724 1661.68
    4781 1657.47  4911.6 1656.64  4916.4  1656.5  4975.1 1654.32    4996 1651.29
  4998.8 1650.79    5002 1651.29  5024.9 1654.53  5070.3 1657.84  5144.2 1660.13
  5175.4 1664.69  5186.8 1668.97  5223.7 1672.23  5393.3 1676.72  5499.3 1680.41
  5606.2 1683.07  5642.6 1684.99  5668.5 1684.94  5850.1 1688.81  5888.3 1690.63
#Mann= 11 ,-1 , 0
  3537.6     .16       0    3803      .1       0  4244.5     .05       0
  4322.4      .1       0  4916.4     .16       0    4996     .07       0
    5002     .16       0  5223.7      .1       0  5393.3     .05       0
  5499.3      .1       0  5668.5     .05       0
Bank Sta=4911.6,5070.3
XS Rating Curve= 0 ,0
Exp/Cntr=0.3,0.1

Type RM Length L Ch R = 1 ,20829   ,901,901,901
BEGIN DESCRIPTION:
DRY HOLLOW CREEK 40.0
END DESCRIPTION:
XS GIS Cut Line= 2
      2824277.47     10088033.92      2825692.07     10087450.71
#Sta/Elev= 30
  4109.2 1693.87    4154 1689.05  4201.9 1687.26  4255.1  1683.1  4272.5 1681.01
  4326.6 1669.43  4337.8  1669.4  4370.7 1666.51  4549.1 1656.05  4593.3 1652.99
  4657.8 1650.88  4723.8 1649.58  4790.1 1649.76  4875.2 1650.37  4931.5 1650.92
    4954 1648.48  4960.9  1646.3  4966.3 1646.63  4984.8 1642.78  4994.2 1642.49
    4997 1641.99  5000.2 1642.49    5008 1642.51  5038.1  1647.9  5078.1 1650.05
  5203.3 1653.91  5235.2 1653.92  5267.6 1656.55    5438 1658.83  5639.3 1663.13
#Mann= 10 ,-1 , 0
  4109.2      .1       0  4370.7     .05       0  4549.1     .16       0
  4657.8     .05       0  4790.1     .16       0  4875.2     .05       0
  4994.2     .04       0  5000.2     .05       0  5078.1      .1       0
    5438     .05       0
#XS Ineff= 2 , 0
         4927.35 1650.86
Permanent Ineff=
       F       F
Bank Sta=4954,5038.1
XS Rating Curve= 0 ,0
Exp/Cntr=0.3,0.1

Type RM Length L Ch R = 1 ,19928   ,829,829,829
BEGIN DESCRIPTION:
DRY HOLLOW CREEK 39.0
END DESCRIPTION:
XS GIS Cut Line= 3
      2824401.51     10088691.63      2825332.23     10088716.45
      2825890.65     10087934.65
#Sta/Elev= 30
  3762.4  1690.3  3809.4 1686.88  3880.8 1683.91  3999.4 1676.21  4039.5 1671.63
  4069.5  1665.2  4099.5 1663.92  4119.5 1659.81  4149.5 1660.65  4309.5 1654.41
  4539.6 1647.08  4704.6 1643.88  4724.6 1643.69  4770.5  1642.6  4951.2 1642.92
  4965.9 1641.16  4998.6 1633.68  5001.3 1633.18  5004.6 1633.68  5022.5  1639.6
  5051.9 1642.31  5076.4 1642.47  5114.6 1641.04  5193.6 1644.17    5310 1649.01
  5381.3 1650.35  5402.2 1649.42  5427.3 1650.82  5427.9 1650.84  5654.2 1655.33
#Mann= 10 ,-1 , 0
  3762.4      .1       0  3880.8     .05       0  4704.6     .16       0
  4724.6      .1       0  4998.6     .07       0  5004.6      .1       0
  5076.4     .16       0  5193.6      .1       0  5427.3     .16       0
  5427.9      .1       0
Bank Sta=4951.2,5051.9
XS Rating Curve= 0 ,0
Exp/Cntr=0.3,0.1

Type RM Length L Ch R = 1 ,19099   ,1340,1340,1340
BEGIN DESCRIPTION:
DRY HOLLOW CREEK 36.0
END DESCRIPTION:
XS GIS Cut Line= 3
      2825307.41     10089659.56      2825952.69     10089237.64
      2826361.88     10087997.69
#Sta/Elev= 30
  4077.4  1664.9  4100.1 1663.02  4172.2 1658.81  4205.5 1657.68  4314.1 1653.69
  4377.4 1649.81  4514.2 1645.46  4567.4 1644.55  4711.9 1639.26  4739.3 1636.22
  4783.6 1633.56  4811.6 1634.76  4936.7  1635.6  4981.3 1631.06  4996.9 1628.44
  4999.7 1627.94  5002.9 1628.44  5052.6 1635.09  5198.3  1634.7  5267.1 1630.98
  5298.8 1631.32  5336.9 1636.23  5357.1 1637.08  5457.6 1645.37  5484.1 1645.64
  5589.8 1650.34    5852 1653.75  5975.3 1656.13  6105.6  1659.3  6154.1 1659.58
#Mann= 9 ,-1 , 0
  4077.4      .1       0  4100.1     .05       0  4172.2      .1       0
  4205.5     .05       0  4514.2      .1       0  4996.9     .07       0
  5002.9      .1       0    5852     .05       0  5975.3      .1       0
#XS Ineff= 2 , 0
         4913.74 1635.79
Permanent Ineff=
       F       F
Bank Sta=4936.7,5052.6
XS Rating Curve= 0 ,0
Exp/Cntr=0.3,0.1

Type RM Length L Ch R = 1 ,17759   ,935,935,935
BEGIN DESCRIPTION:
DRY HOLLOW CREEK 35.0
END DESCRIPTION:
XS GIS Cut Line= 3
      2826697.28     10089882.89      2827230.85     10089138.37
      2827191.46     10088248.41
#Sta/Elev= 30
  3884.7 1635.61    4142 1633.57  4209.3 1632.09  4387.8 1628.62  4555.1 1625.62
  4666.4 1625.85  4735.4 1624.84  4770.3 1623.91  4845.4  1622.7  4872.4 1624.44
  4895.4 1623.83  4935.4 1624.85  4964.1 1623.55  4995.5 1618.73  5002.5 1618.69
  5005.3 1618.19  5008.5 1618.69  5035.5 1623.61  5145.6 1624.67  5155.7 1626.53
  5168.3 1632.48  5192.3 1646.63  5197.3 1645.03  5210.2 1649.52  5245.7 1655.28
  5264.9 1656.08  5362.1 1659.29    5466 1661.56    5506 1664.22  5691.5 1667.66
#Mann= 13 ,-1 , 0
  3884.7      .1       0  4209.3     .05       0  4387.8      .1       0
  4555.1     .05       0  4735.4      .1       0  4770.3     .05       0
  4872.4      .1       0  5002.5     .07       0  5008.5      .1       0
  5168.3     .16       0  5210.2      .1       0  5264.9     .16       0
  5362.1      .1       0
Bank Sta=4964.1,5035.5
XS Rating Curve= 0 ,0
Exp/Cntr=0.3,0.1

Type RM Length L Ch R = 1 ,16824   ,1023,1023,1023
BEGIN DESCRIPTION:
DRY HOLLOW CREEK 34.0
END DESCRIPTION:
XS GIS Cut Line= 2
      2826957.83     10089907.75      2828581.98      10088977.9
#Sta/Elev= 30
  3924.5 1632.88  3932.4 1632.93  4047.9 1630.26  4342.1  1625.5  4608.8 1623.23
    4711 1621.06  4823.2 1616.35  4962.3 1618.98  4993.9 1612.44  4996.6 1611.94
  4999.9 1612.44  5070.8 1618.07  5187.2  1625.3  5212.3  1626.9  5269.3    1631
  5306.8  1635.2  5334.1  1640.1  5349.9 1641.41  5355.7 1643.39  5371.5 1642.65
  5377.3 1644.07  5393.1 1644.57  5400.2 1642.55  5408.9 1642.57  5452.1 1649.61
  5483.8  1651.7  5607.5 1655.89  5619.1  1657.3  5747.5 1658.34    5796 1658.65
#Mann= 10 ,-1 , 0
  3924.5     .05       0  3932.4      .1       0  4047.9     .05       0
  4342.1      .1       0  4993.9     .07       0  4999.9      .1       0
  5187.2     .05       0  5212.3      .1       0  5483.8     .05       0
  5747.5      .1       0
Bank Sta=4962.3,5070.8
XS Rating Curve= 0 ,0
Exp/Cntr=0.3,0.1

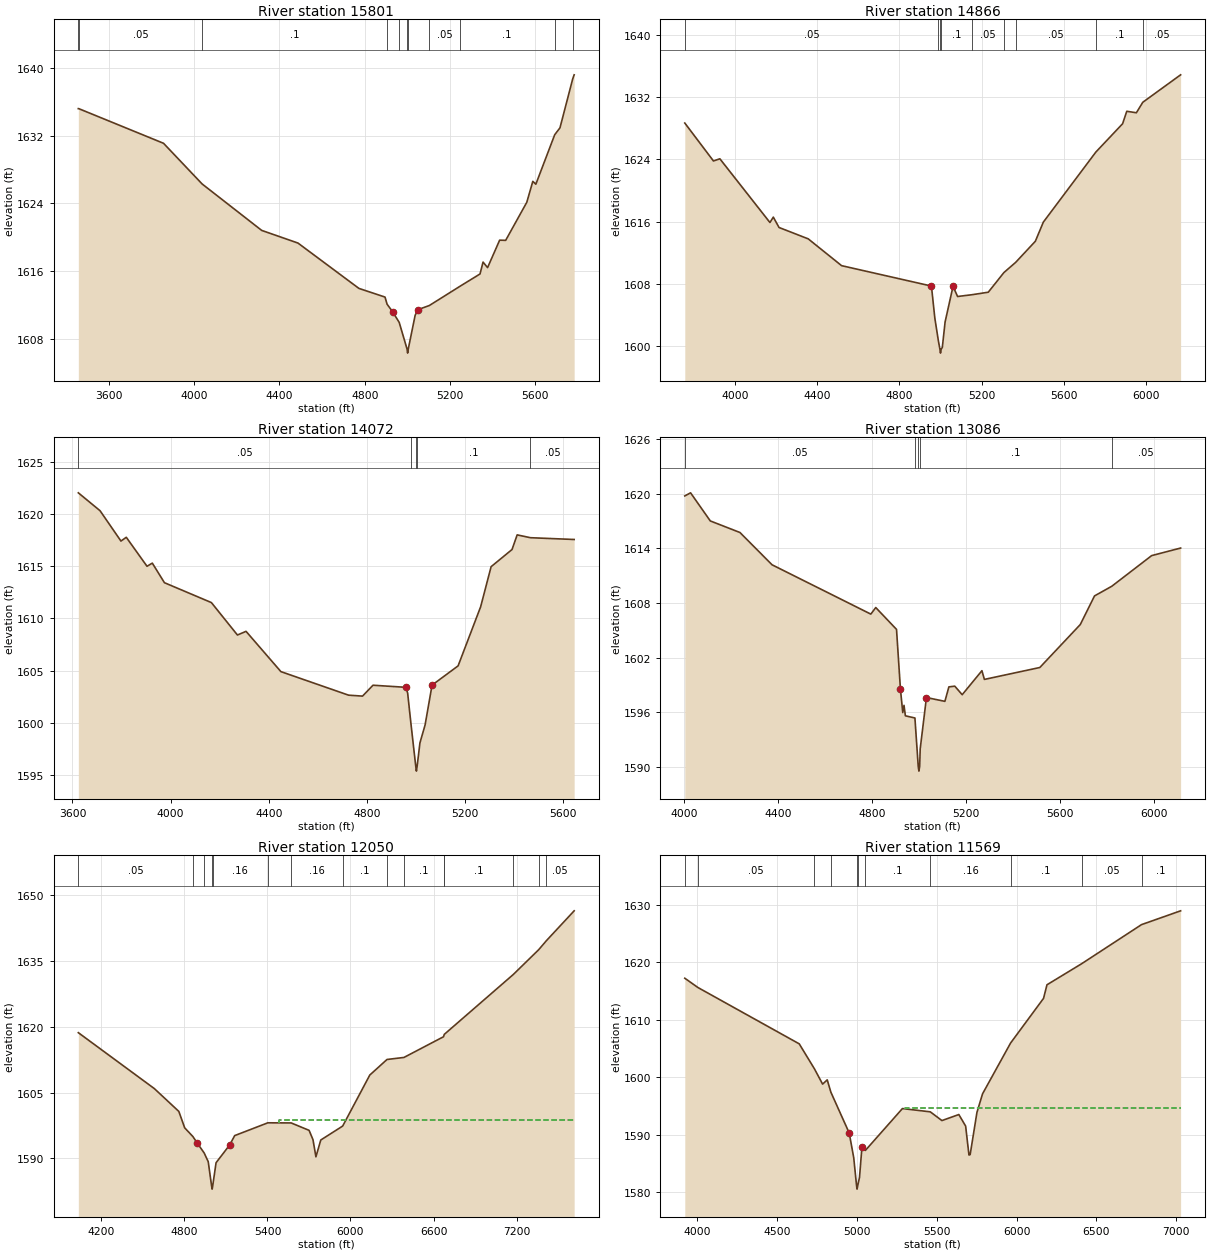
Type RM Length L Ch R = 1 ,15801   ,935,935,935
BEGIN DESCRIPTION:
DRY HOLLOW CREEK 29.0
END DESCRIPTION:
XS GIS Cut Line= 3
      2826759.32     10090391.71      2828074.69     10090342.07
      2828793.98     10089635.18
#Sta/Elev= 30
  3457.1 1635.17  3458.9 1635.17  3856.5 1631.09  4037.5  1626.3  4316.9 1620.83
    4487 1619.34  4772.8    1614  4895.1 1612.98  4904.8 1612.14  4930.5 1611.26
  4961.6    1610  4998.2 1606.88    5001 1606.38  5004.2 1606.88  5036.5 1610.85
  5050.7 1611.51  5103.2 1611.99  5244.6 1614.22  5340.5  1615.7  5354.7  1617.1
    5376 1616.45  5432.5 1619.68  5460.8 1619.66  5559.8 1624.14  5588.1 1626.61
  5602.3 1626.27  5690.8  1632.1  5715.4 1632.91  5775.1 1638.67  5781.9 1639.15
#Mann= 11 ,-1 , 0
  3457.1      .1       0  3458.9     .05       0  4037.5      .1       0
  4904.8     .05       0  4961.6      .1       0  4998.2     .07       0
  5004.2      .1       0  5103.2     .05       0  5244.6      .1       0
  5690.8     .05       0  5775.1      .1       0
Bank Sta=4930.5,5050.7
XS Rating Curve= 0 ,0
Exp/Cntr=0.3,0.1

Type RM Length L Ch R = 1 ,14866   ,794,794,794
BEGIN DESCRIPTION:
DRY HOLLOW CREEK 28.0
END DESCRIPTION:
XS GIS Cut Line= 3
      2828223.61     10091967.66      2829005.38     10090453.75
       2829203.7     10089772.05
#Sta/Elev= 30
  3755.1 1628.66  3894.6 1623.79  3925.9 1624.07  4169.6 1615.89  4186.1 1616.58
  4213.9 1615.25    4356 1613.79  4518.4 1610.35  4955.8 1607.73  4972.3 1603.62
  4989.6  1600.7  4997.1 1599.62  4999.9 1599.12  5003.1 1599.62  5008.8 1599.85
  5022.3 1603.12  5060.9 1607.69  5083.1 1606.39  5153.6 1606.62  5232.5 1606.94
  5308.5 1609.46  5366.1 1610.78  5461.6 1613.48  5500.6 1615.94  5756.1 1624.93
  5886.4 1628.57  5906.8 1630.17  5953.5 1629.98  5984.9 1631.33  6168.9 1634.85
#Mann= 9 ,-1 , 0
  3755.1     .05       0  4989.6      .1       0  4997.1     .07       0
  5003.1      .1       0  5153.6     .05       0  5308.5      .1       0
  5366.1     .05       0  5756.1      .1       0  5984.9     .05       0
Bank Sta=4955.8,5060.9
XS Rating Curve= 0 ,0
Exp/Cntr=0.3,0.1

Type RM Length L Ch R = 1 ,14072   ,986,986,986
BEGIN DESCRIPTION:
DRY HOLLOW CREEK 26.0
END DESCRIPTION:
XS GIS Cut Line= 2
      2828558.64     10092079.38      2829910.84     10090578.32
#Sta/Elev= 30
  3623.8 1622.01  3712.3  1620.3  3797.5  1617.4  3819.2 1617.76  3903.6 1614.99
  3925.3 1615.29  3974.6 1613.42    4166 1611.52  4272.1 1608.42  4307.2 1608.77
  4449.2 1604.92    4725 1602.67  4781.8 1602.58  4824.4 1603.62  4958.9 1603.42
  4965.7 1602.86  4979.4 1599.88  4998.5 1595.91  5001.3 1595.41  5004.5 1595.91
  5015.7 1598.11  5036.7 1599.82  5065.1 1603.63  5171.2 1605.47  5263.1 1611.12
  5305.7 1614.95  5390.9 1616.59  5411.9 1617.99  5466.2 1617.72  5644.1 1617.55
#Mann= 5 ,-1 , 0
  3623.8     .05       0  4979.4      .1       0  4998.5     .07       0
  5004.5      .1       0  5466.2     .05       0
Bank Sta=4958.9,5065.1
XS Rating Curve= 0 ,0
Exp/Cntr=0.3,0.1

Type RM Length L Ch R = 1 ,13086   ,1036,1036,1036
BEGIN DESCRIPTION:
DRY HOLLOW CREEK 25.0
END DESCRIPTION:
XS GIS Cut Line= 3
      2829613.44     10092737.08      2830035.36      10091446.5
      2830159.45     10090701.97
#Sta/Elev= 30
  4002.8 1619.77  4027.4 1620.11  4111.5 1617.02  4237.8 1615.75  4374.6  1612.2
  4795.4 1606.78  4816.4  1607.5  4904.9  1605.1  4921.6 1598.53  4931.5 1595.96
  4936.8 1596.75  4942.7  1595.6  4983.3 1595.36  4997.5 1590.02  5000.3 1589.52
  5003.5 1590.02  5005.8 1591.97  5032.4 1597.61    5111 1597.19    5128 1598.78
  5153.1 1598.86  5184.7 1597.92  5268.8 1600.56  5279.3  1599.6  5515.5 1600.91
  5687.8 1605.63  5748.6 1608.78  5822.1 1609.84    5992 1613.21  6115.4 1614.04
#Mann= 5 ,-1 , 0
  4002.8     .05       0  4983.3      .1       0  4997.5     .07       0
  5003.5      .1       0  5822.1     .05       0
Bank Sta=4921.6,5032.4
XS Rating Curve= 0 ,0
Exp/Cntr=0.3,0.1

Type RM Length L Ch R = 1 ,12050   ,481,481,481
BEGIN DESCRIPTION:
DRY HOLLOW CREEK 24.0
END DESCRIPTION:
XS GIS Cut Line= 3
      2829953.13     10092824.77      2831615.47     10091262.25
      2832105.29     10090057.21
#Sta/Elev= 30
  4033.7 1618.67  4582.9 1605.92  4759.7 1600.72  4802.2 1596.97  4861.1    1595
  4894.1 1593.44  4942.9 1591.24  4972.2 1589.26  4997.5  1583.5  5000.3    1583
  5003.5  1583.5  5028.8 1589.02  5127.5 1593.08  5163.2  1595.2  5402.9 1598.12
  5571.4 1598.09  5700.9  1596.4  5729.1 1594.27  5750.2 1590.37  5785.4  1594.2
  5943.6 1597.38  6139.5 1609.01  6263.9 1612.56  6386.1 1613.02    6672 1617.74
  6677.6 1618.28  7176.7 1631.95  7359.5 1637.58    7415 1639.63  7615.9 1646.45
#Mann= 15 ,-1 , 0
  4033.7     .05       0  4861.1      .1       0  4942.9     .16       0
  4997.5     .07       0  5003.5     .16       0  5402.9      .1       0
  5571.4     .16       0  5943.6      .1       0  6263.9     .05       0
  6386.1      .1       0    6672     .05       0  6677.6      .1       0
  7176.7     .05       0  7359.5      .1       0    7415     .05       0
#XS Ineff= 2 , 0
                          5483.8         1598.86
Permanent Ineff=
       F       F
Bank Sta=4894.1,5127.5
XS Rating Curve= 0 ,0
Exp/Cntr=0.3,0.1

Type RM Length L Ch R = 1 ,11569   ,779,779,779
BEGIN DESCRIPTION:
DRY HOLLOW CREEK 23.0
END DESCRIPTION:
XS GIS Cut Line= 4
      2830165.82     10093011.38      2830912.35     10092638.11
      2831224.85     10092156.34      2832474.82     10091006.19
#Sta/Elev= 30
    3921 1617.23    4003 1615.62  4638.2 1605.82  4733.4 1601.48  4784.7 1598.82
  4813.7 1599.56  4836.5 1597.42  4951.6 1590.31  4979.8 1586.02  4997.9 1581.06
  5000.6 1580.56  5003.9 1581.06    5016 1582.61  5031.2 1587.85  5052.8 1587.29
    5285 1594.57  5459.5    1594  5532.5 1592.48  5638.5 1593.53  5681.1 1591.52
    5702 1586.49  5709.4 1586.56    5752  1593.9  5787.1 1597.13  5962.8 1605.96
  6169.4 1613.73  6190.9 1616.09  6408.1 1619.75  6783.4 1626.55  7028.5 1628.95
#Mann= 11 ,-1 , 0
    3921      .1       0    4003     .05       0  4733.4      .1       0
  4836.5     .16       0  4997.9     .07       0  5003.9     .16       0
  5052.8      .1       0  5459.5     .16       0  5962.8      .1       0
  6408.1     .05       0  6783.4      .1       0
#XS Ineff= 2 , 0
                         5304.11         1594.75
Permanent Ineff=
       F       F
Bank Sta=4951.6,5031.2
XS Rating Curve= 0 ,0
Exp/Cntr=0.3,0.1