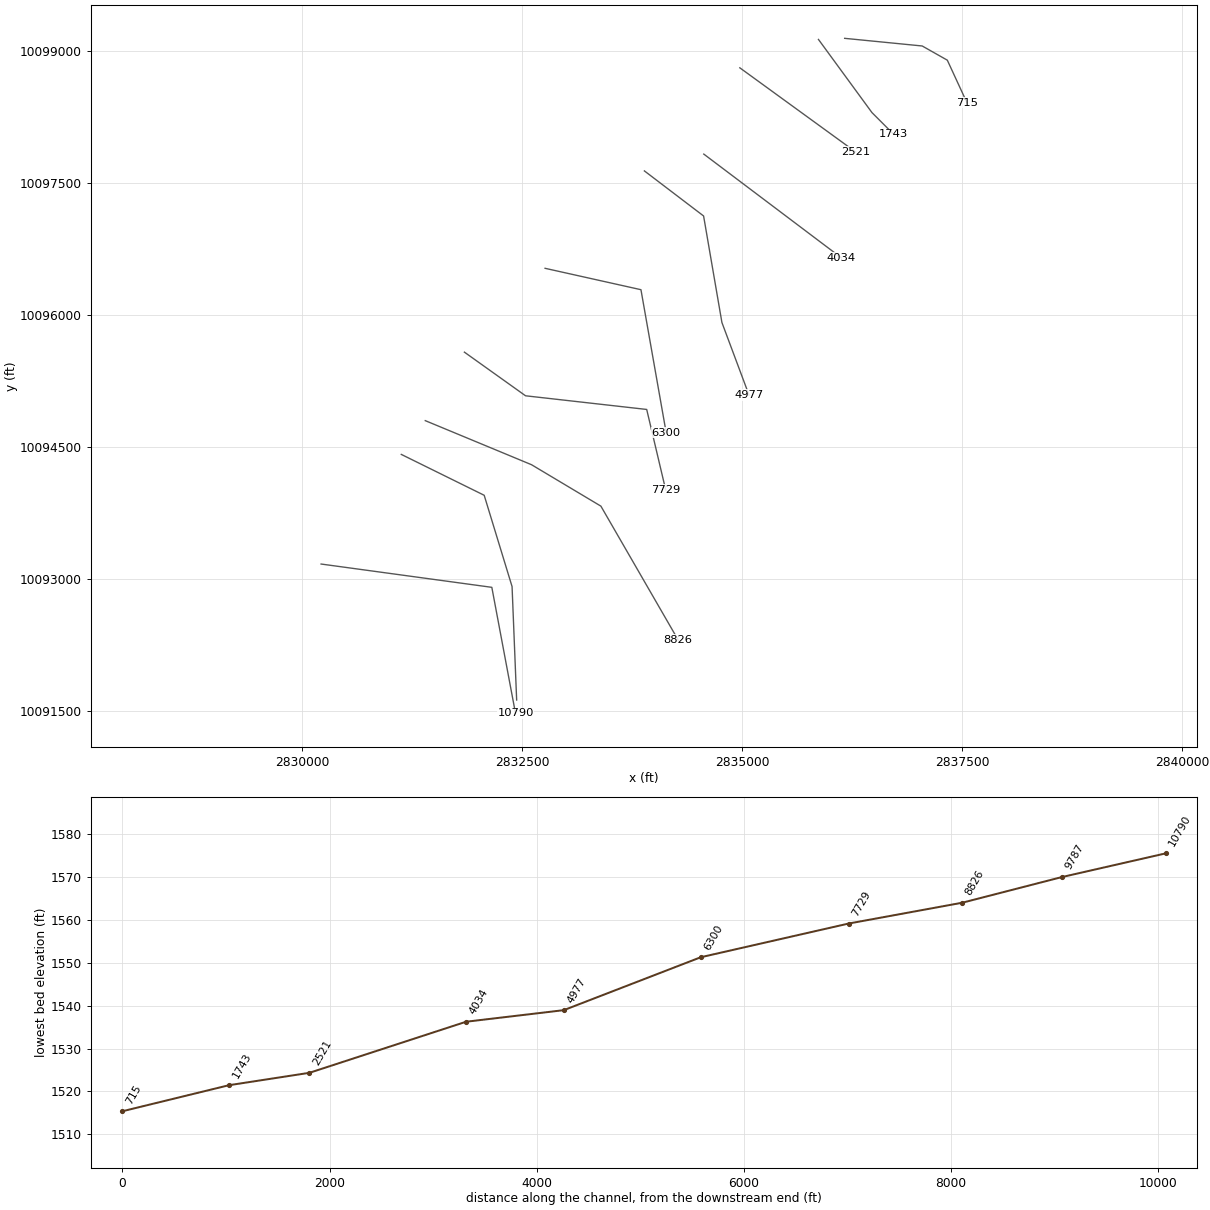
HEC-RAS study DRY HOLLOW CREEK.prj: DRY HOLLOW CREEK Base Level Engineering

--- DRY HOLLOW CREEK.g01 (geometry) --- (continued)

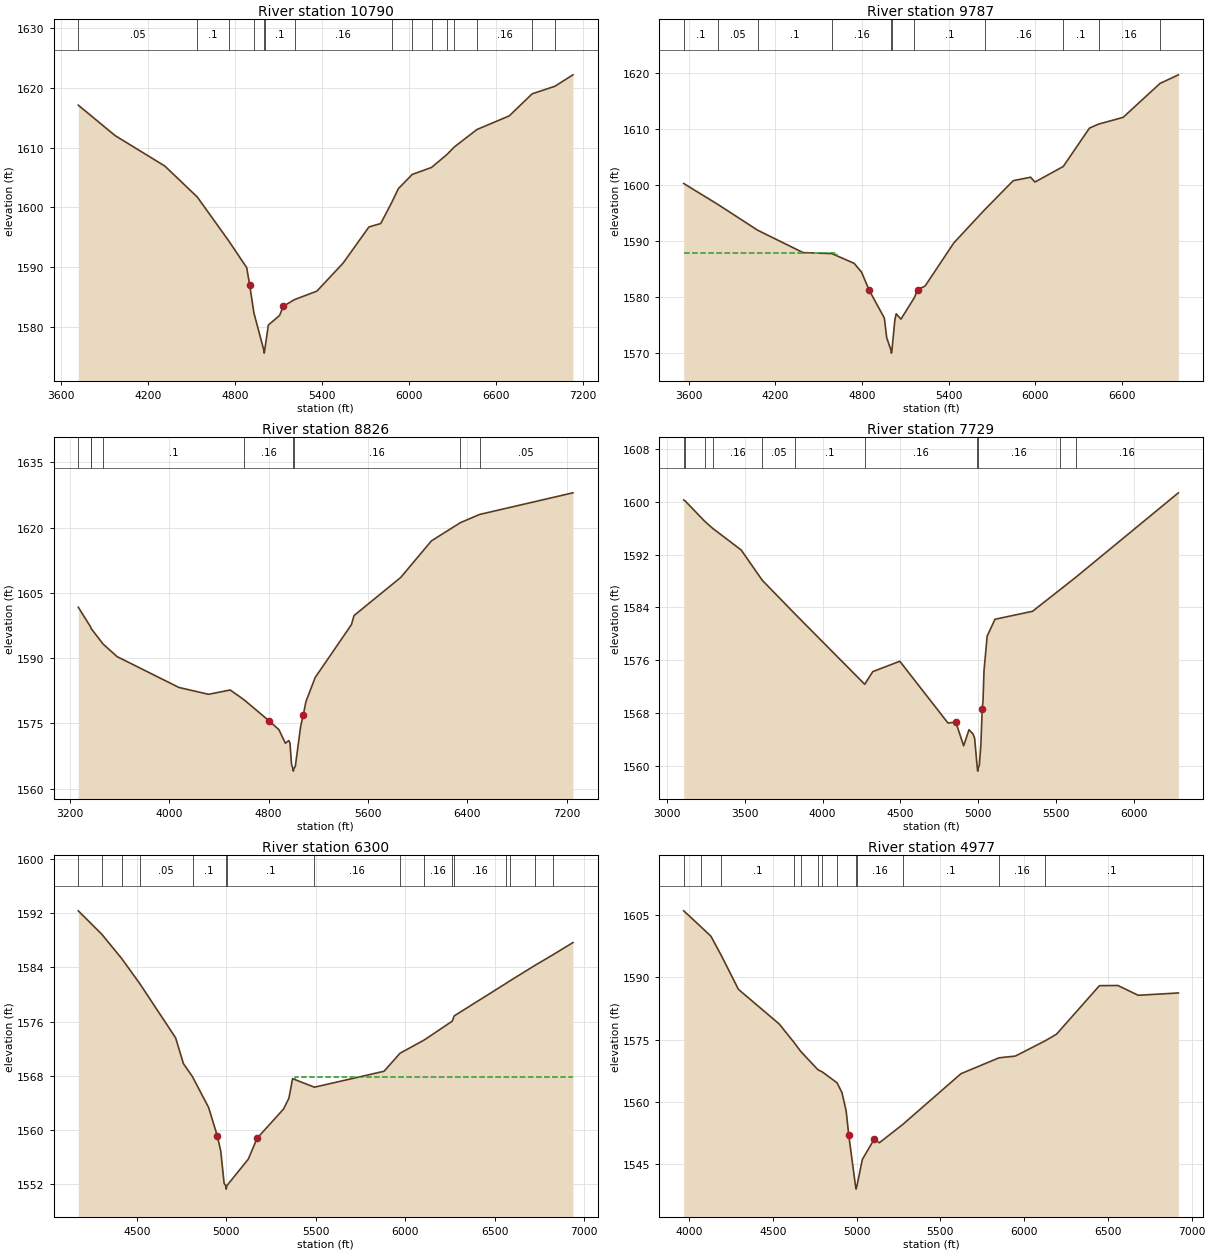
Type RM Length L Ch R = 1 ,10790   ,1003,1003,1003
BEGIN DESCRIPTION:
DRY HOLLOW CREEK 18.0
END DESCRIPTION:
XS GIS Cut Line= 3
      2830216.04     10093166.61      2832156.13     10092901.86
      2832425.22     10091469.58
#Sta/Elev= 30
  3717.4 1617.11  3972.2    1612  4315.3  1606.9  4539.3 1601.71  4755.5 1594.39
  4880.3 1589.88  4900.7    1587  4930.1 1582.29  4998.6 1576.05  5001.4 1575.55
  5004.6 1576.05  5029.9 1580.26  5107.3 1581.86  5132.8  1583.4  5210.6 1584.52
    5365 1585.94  5546.1 1590.64  5724.4  1596.7  5805.8 1597.27  5881.5 1600.79
  5927.3 1603.11  6023.3  1605.5  6156.7 1606.67  6262.6 1608.83  6313.8  1610.1
  6469.6 1613.02  6693.1 1615.31  6851.5 1619.01  7008.2 1620.27  7132.8 1622.19
#Mann= 15 ,-1 , 0
  3717.4     .05       0  4539.3      .1       0  4755.5     .16       0
  4930.1      .1       0  4998.6     .07       0  5004.6      .1       0
  5210.6     .16       0  5881.5      .1       0  6023.3     .16       0
  6156.7      .1       0  6262.6     .16       0  6313.8      .1       0
  6469.6     .16       0  6851.5      .1       0  7008.2     .05       0
Bank Sta=4900.7,5132.8
XS Rating Curve= 0 ,0
Exp/Cntr=0.3,0.1

Type RM Length L Ch R = 1 ,9787    ,961,961,961
BEGIN DESCRIPTION:
DRY HOLLOW CREEK 17.0
END DESCRIPTION:
XS GIS Cut Line= 4
      2831127.51     10094412.26      2832069.32     10093947.87
      2832386.16     10092910.54      2832438.24     10091621.51
#Sta/Elev= 30
    3565 1600.32  3800.4  1596.6  4077.3 1591.97  4391.9 1587.97  4590.9  1587.8
  4744.9 1586.06  4796.2 1584.49  4849.4 1581.24    4954 1576.29  4970.6 1572.76
  5000.4 1570.52  5003.2 1570.02  5006.4 1570.52  5027.2 1576.02  5036.2 1577.04
    5069 1576.09  5162.4 1579.96    5184 1581.34  5236.3 1582.01    5435 1589.71
  5647.9 1595.61  5846.6 1600.83  5966.7 1601.44  5996.8 1600.58  6192.8 1603.36
  6374.1 1610.21  6437.4 1610.93  6607.3 1612.13  6862.6 1618.19  6989.8 1619.73
#Mann= 11 ,-1 , 0
    3565      .1       0  3800.4     .05       0  4077.3      .1       0
  4590.9     .16       0  5000.4     .07       0  5006.4     .16       0
  5162.4      .1       0  5647.9     .16       0  6192.8      .1       0
  6437.4     .16       0  6862.6      .1       0
#XS Ineff= 2 , 0
         4625.83 1587.95
Permanent Ineff=
       F       F
Bank Sta=4849.4,5184
XS Rating Curve= 0 ,0
Exp/Cntr=0.3,0.1

Type RM Length L Ch R = 1 ,8826    ,1097,1097,1097
BEGIN DESCRIPTION:
DRY HOLLOW CREEK 16.0
END DESCRIPTION:
XS GIS Cut Line= 4
      2831399.87     10094795.98      2832607.52     10094295.09
      2833395.48     10093824.46      2834273.85     10092303.48
#Sta/Elev= 30
  3268.6  1601.7  3368.6 1597.15    3371 1596.86  3468.2 1593.24    3581 1590.35
    4079 1583.26  4317.2 1581.69    4492 1582.68  4603.9 1580.41  4803.6 1575.61
  4883.4 1573.58  4935.9 1570.44  4963.1 1571.07  4972.9 1570.47  4984.8 1565.66
  4997.1 1564.54  4999.8 1564.04  5003.1 1564.54  5015.7 1565.15  5058.5 1574.32
  5079.9 1576.99  5101.3 1580.02  5175.2 1585.54  5467.1 1597.69  5488.5 1599.79
  5864.1 1608.54  6111.1 1616.94  6344.5 1621.13    6499 1623.01  7250.2 1627.98
#Mann= 9 ,-1 , 0
  3268.6     .16       0  3368.6      .1       0    3371     .16       0
  3468.2      .1       0  4603.9     .16       0  4997.1     .07       0
  5003.1     .16       0  6344.5      .1       0    6499     .05       0
Bank Sta=4803.6,5079.9
XS Rating Curve= 0 ,0
Exp/Cntr=0.3,0.1

Type RM Length L Ch R = 1 ,7729    ,1429,1429,1429
BEGIN DESCRIPTION:
DRY HOLLOW CREEK 15.0
END DESCRIPTION:
XS GIS Cut Line= 4
      2831844.47     10095574.33       2832539.5     10095078.36
      2833916.02     10094923.16      2834131.94      10094008.9
#Sta/Elev= 30
  3108.1 1600.26  3117.4 1600.12  3242.5 1597.05  3293.6 1595.98  3477.3 1592.69
  3612.9  1588.1  3825.6 1582.94  4271.1 1572.34  4323.2 1574.26  4496.7 1575.83
  4806.2 1566.47  4856.5  1566.6  4906.9 1563.02  4941.3 1565.46  4967.2  1564.8
  4977.3 1564.19  4994.4 1559.68  4997.2 1559.18  5000.4 1559.68  5007.5 1560.02
  5017.6  1563.2  5026.2 1568.62  5031.2 1569.79  5037.7 1574.42  5057.8 1579.63
  5108.1 1582.19  5349.5  1583.4  5528.8 1586.72  5626.1 1588.53  6286.6 1601.35
#Mann= 11 ,-1 , 0
  3108.1      .1       0  3117.4     .16       0  3242.5      .1       0
  3293.6     .16       0  3612.9     .05       0  3825.6      .1       0
  4271.1     .16       0  4994.4     .07       0  5000.4     .16       0
  5528.8      .1       0  5626.1     .16       0
#XS Ineff= 2 , 0
         4498.19 1575.51
Permanent Ineff=
       F       F
Bank Sta=4856.5,5026.2
XS Rating Curve= 0 ,0
Exp/Cntr=0.3,0.1

Type RM Length L Ch R = 1 ,6300    ,1323,1323,1323
BEGIN DESCRIPTION:
DRY HOLLOW CREEK 9.0
END DESCRIPTION:
XS GIS Cut Line= 3
      2832761.28     10096527.01      2833850.72     10096283.95
      2834137.18     10094660.66
#Sta/Elev= 30
  4172.9 1592.32  4304.1 1588.88  4414.7 1585.32  4516.8 1581.59  4717.1  1573.6
  4760.6  1569.8  4811.5 1567.87  4901.2 1563.35  4949.8 1559.18  4969.2 1556.93
  4988.1 1552.15  4996.9 1551.81  4999.7 1551.31  5002.9 1551.81  5122.9 1555.72
  5172.2  1558.8  5319.8  1563.1  5350.3 1564.72  5370.6 1567.59  5492.8 1566.33
  5881.9 1568.68    5971 1571.33  6107.1  1573.3  6262.5 1576.05  6274.2 1576.84
    6563 1581.62  6584.6 1581.99  6726.3  1584.3  6825.5 1585.84  6937.5 1587.64
#Mann= 16 ,-1 , 0
  4172.9      .1       0  4304.1     .05       0  4414.7      .1       0
  4516.8     .05       0  4811.5      .1       0  4996.9     .07       0
  5002.9      .1       0  5492.8     .16       0    5971      .1       0
  6107.1     .16       0  6262.5      .1       0  6274.2     .16       0
    6563      .1       0  6584.6     .16       0  6726.3      .1       0
  6825.5     .16       0
#XS Ineff= 2 , 0
                          5382.1          1567.9
Permanent Ineff=
       F       F
Bank Sta=4949.8,5172.2
XS Rating Curve= 0 ,0
Exp/Cntr=0.3,0.1

Type RM Length L Ch R = 1 ,4977    ,943,943,943
BEGIN DESCRIPTION:
DRY HOLLOW CREEK 8.0
END DESCRIPTION:
XS GIS Cut Line= 4
      2833889.82     10097633.75      2834562.52     10097121.62
      2834770.86     10095910.68      2835078.51     10095087.38
#Sta/Elev= 30
  3967.9 1606.08  4069.9 1602.26  4130.3 1599.96  4193.2 1595.24  4294.6 1587.14
  4537.8  1578.8  4625.2  1574.4  4666.7 1572.17  4768.9 1567.76  4794.9 1567.24
  4883.7 1564.59  4912.7 1562.22  4937.5 1557.88  4953.3 1551.94  4994.4 1539.46
  4997.2 1538.96  5000.4 1539.46  5034.5 1546.14  5105.5 1551.03  5135.9 1550.14
    5275 1554.54    5623  1566.8  5850.2 1570.63  5947.7 1571.05  6124.5  1574.7
    6193 1576.31  6449.7 1588.03  6560.2 1588.07  6681.4 1585.71    6921 1586.27
#Mann= 13 ,-1 , 0
  3967.9      .1       0  4069.9     .05       0  4193.2      .1       0
  4625.2     .05       0  4666.7      .1       0  4768.9     .05       0
  4794.9      .1       0  4883.7     .16       0  4994.4     .07       0
  5000.4     .16       0    5275      .1       0  5850.2     .16       0
  6124.5      .1       0
Bank Sta=4953.3,5105.5
XS Rating Curve= 0 ,0
Exp/Cntr=0.3,0.1

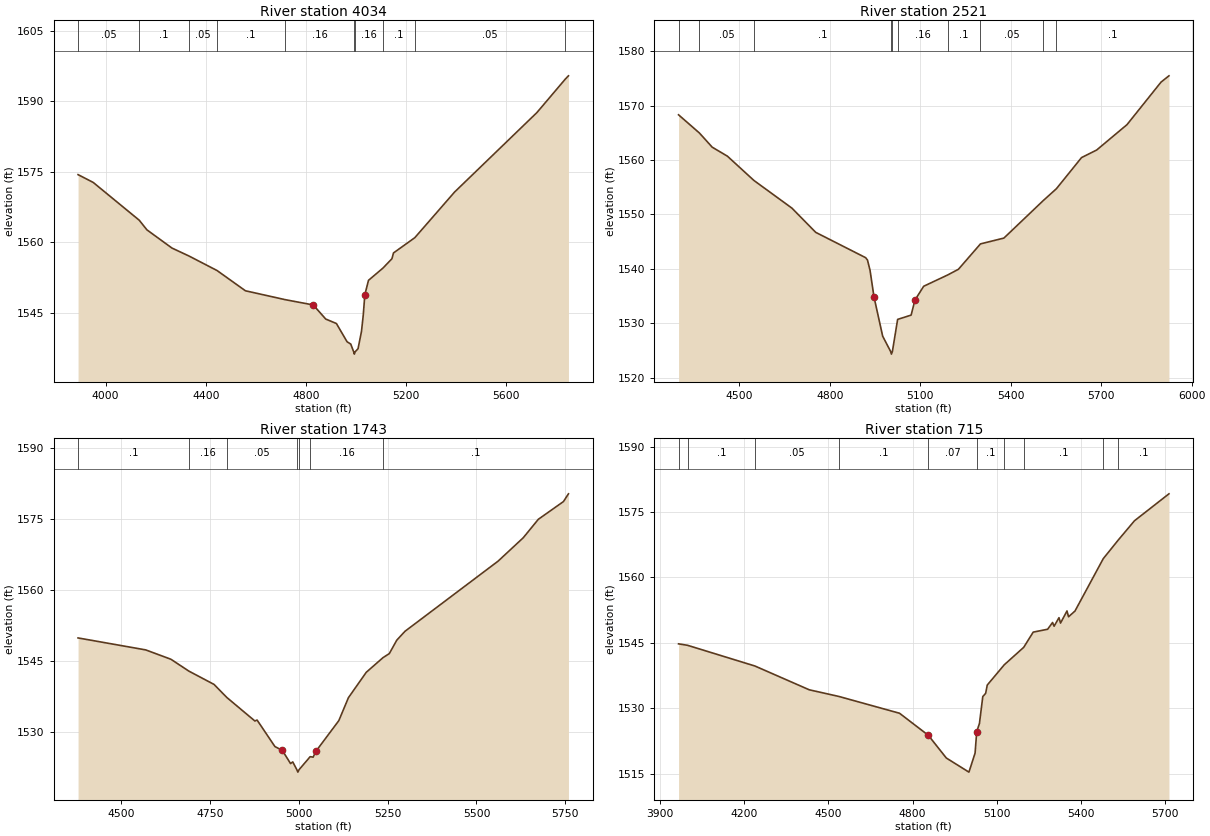
Type RM Length L Ch R = 1 ,4034    ,1513,1513,1513
BEGIN DESCRIPTION:
DRY HOLLOW CREEK 7.0
END DESCRIPTION:
XS GIS Cut Line= 2
      2834564.78     10097824.87      2836128.36     10096645.98
#Sta/Elev= 30
  3889.8 1574.43  3950.3 1572.77  4134.2 1564.73  4164.7 1562.69  4264.6 1558.82
  4332.5 1557.13  4444.7 1554.04  4558.2 1549.73    4718 1547.83  4828.8 1546.72
  4878.8 1543.72  4921.4 1542.77  4964.1 1538.88  4978.7  1538.4  4990.3 1536.76
    4993 1536.26  4996.3 1536.76  5007.8 1537.41  5021.6  1541.1  5028.7  1544.6
  5034.9 1548.87  5049.5 1551.95  5106.8 1554.53  5143.2 1556.55  5149.4 1557.78
  5234.5 1561.02    5393 1570.71  5721.9 1587.62  5835.8 1594.77    5848 1595.44
#Mann= 10 ,-1 , 0
  3889.8     .05       0  4134.2      .1       0  4332.5     .05       0
  4444.7      .1       0    4718     .16       0  4990.3     .07       0
  4996.3     .16       0  5106.8      .1       0  5234.5     .05       0
  5835.8      .1       0
Bank Sta=4828.8,5034.9
XS Rating Curve= 0 ,0
Exp/Cntr=0.3,0.1

Type RM Length L Ch R = 1 ,2521    ,778,778,778
BEGIN DESCRIPTION:
DRY HOLLOW CREEK 3.0
END DESCRIPTION:
XS GIS Cut Line= 2
       2834974.3      10098805.2      2836289.68     10097849.69
#Sta/Elev= 30
  4298.9 1568.31  4368.3 1564.95  4410.5 1562.36  4460.8 1560.71  4548.7 1556.25
  4674.8 1551.16  4753.7 1546.71  4919.2 1542.06  4925.3 1541.62  4933.8 1539.72
  4946.8 1534.86  4975.6 1527.64  5001.9 1524.84  5004.7 1524.34  5007.9 1524.84
  5025.2 1530.72  5069.9 1531.51  5082.7 1534.28  5111.6 1536.81  5191.8  1538.9
  5226.8 1539.93  5299.8 1544.59  5377.5 1545.66  5507.8 1552.54  5551.6 1554.73
  5634.9 1560.45  5685.1 1561.84  5785.6  1566.5  5898.5 1574.32  5924.7 1575.47
#Mann= 10 ,-1 , 0
  4298.9      .1       0  4368.3     .05       0  4548.7      .1       0
  5001.9     .07       0  5007.9      .1       0  5025.2     .16       0
  5191.8      .1       0  5299.8     .05       0  5507.8     .16       0
  5551.6      .1       0
Bank Sta=4946.8,5082.7
XS Rating Curve= 0 ,0
Exp/Cntr=0.3,0.1

Type RM Length L Ch R = 1 ,1743    ,1028,1028,1028
BEGIN DESCRIPTION:
DRY HOLLOW CREEK 2.0
END DESCRIPTION:
XS GIS Cut Line= 3
      2835867.75     10099127.84      2836475.79     10098296.44
      2836723.48     10098048.75
#Sta/Elev= 30
  4378.6 1549.83    4569  1547.3    4640 1545.32  4690.3 1542.82  4761.3    1540
  4797.1 1537.25  4876.3 1532.26  4882.5 1532.46  4932.7 1526.85  4953.6 1526.03
  4976.7 1523.25  4982.9  1523.6  4994.5 1521.94  4997.3 1521.44  5000.5 1521.94
  5031.9 1524.71  5040.3 1524.61  5047.7 1525.81  5112.6 1532.34  5139.6 1537.19
  5189.8 1542.56  5236.9 1545.66  5254.7 1546.52  5275.7 1549.36  5298.7 1551.23
  5560.9 1566.08  5631.6 1571.02  5674.1 1574.93  5744.8 1578.68  5758.9 1580.32
#Mann= 7 ,-1 , 0
  4378.6      .1       0  4690.3     .16       0  4797.1     .05       0
  4994.5    .035       0  5000.5     .05       0  5031.9     .16       0
  5236.9      .1       0
Bank Sta=4953.6,5047.7
XS Rating Curve= 0 ,0
Exp/Cntr=0.3,0.1

Type RM Length L Ch R = 1 ,715     ,0,0,0
BEGIN DESCRIPTION:
DRY HOLLOW CREEK 1.0
END DESCRIPTION:
XS GIS Cut Line= 4
      2836165.56     10099140.27      2837046.62     10099053.41
      2837332.04     10098892.09      2837555.27     10098408.41
#Sta/Elev= 30
    3967 1544.78    3999 1544.45    4239  1539.7  4432.2 1534.25  4537.8 1532.72
  4753.7 1528.87  4856.3 1523.81  4920.2 1518.61  5000.8 1515.37  5022.7 1519.74
  5028.5 1524.65  5038.2 1526.51  5050.1 1532.69  5060.3 1533.43    5066 1535.33
  5126.7 1539.99  5195.8 1543.98  5229.6 1547.47    5281 1548.13  5298.5 1549.68
    5304 1548.82  5321.4 1550.78  5326.9 1549.54  5349.9 1552.33  5355.4 1550.99
  5378.3  1552.3  5479.1 1564.32  5532.9 1568.62  5590.3 1573.01  5712.9 1579.18
#Mann= 10 ,-1 , 0
    3967     .05       0    3999      .1       0    4239     .05       0
  4537.8      .1       0  4856.3     .07       0  5028.5      .1       0
  5126.7     .16       0  5195.8      .1       0  5479.1     .16       0
  5532.9      .1       0
Bank Sta=4856.3,5028.5
XS Rating Curve= 0 ,0
Exp/Cntr=0.3,0.1

Chan Stop Cuts=-1
Use User Specified Reach Order=0
Composite Channel Slope=5