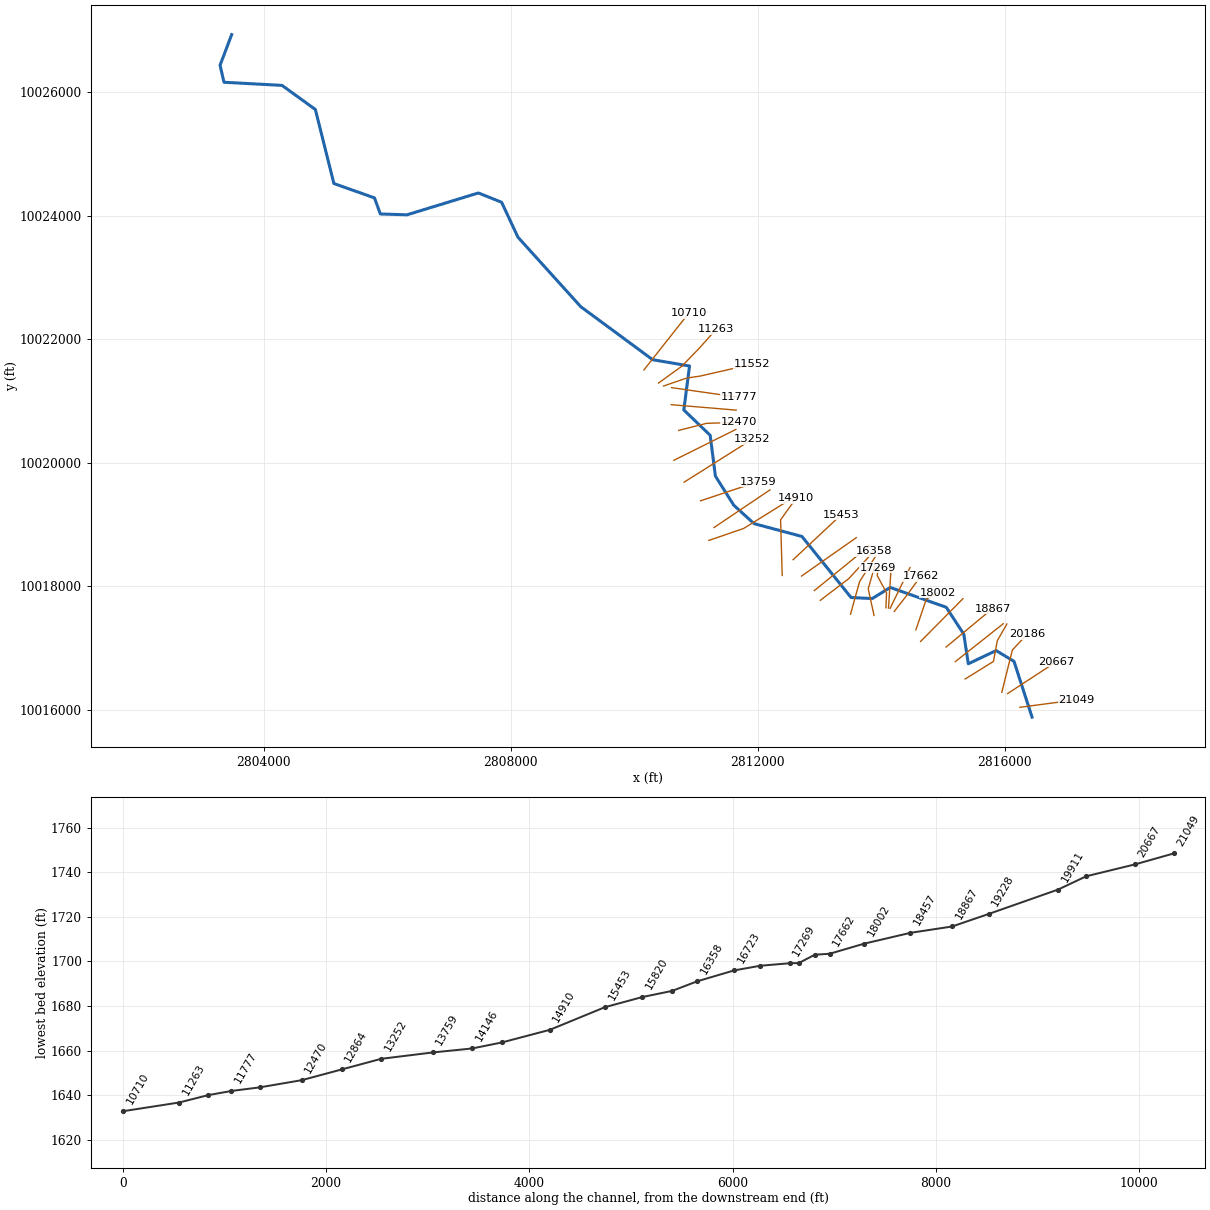
--- EAST FORK HUNTERS CREEK.prj (project) ---

Proj Title=EAST FORK HUNTERS CREEK Base Level Engineering
Current Plan=p01
Default Exp/Contr=0.3,0.1
English Units
Geom File=g01
Flow File=f01
Plan File=p01
Y Axis Title=Elevation
X Axis Title(PF)=Main Channel Distance
X Axis Title(XS)=Station
BEGIN DESCRIPTION:
EAST FORK HUNTERS CREEK
END DESCRIPTION:
DSS Export Rating Curves= 0
DSS Export Rating Curve Sorted= 0
DSS Export Volume Flow Curves= 0
DXF OffsetX= 0
DXF OffsetY= 0
DXF ScaleX= 1
DXF ScaleY= 10

--- EAST FORK HUNTERS CREEK.p01 (plan) ---

Plan Title=Multiple Run
Short Identifier=Multiple
Geom File=g01
Flow File=f01
Subcritical Flow
K Sum by GR= 0
Std Step Tol= 0.01
Critical Tol= 0.01
Num of Std Step Trials= 20
Max Error Tol= 0.3
Flow Tol Ratio= 0.001
Split Flow NTrial= 30
Split Flow Tol= 0.02
Split Flow Ratio= 0.02
Log Output Level= 0
Friction Slope Method= 1
Unsteady Friction Slope Method= 2
Unsteady Bridges Friction Slope Method= 1
Parabolic Critical Depth
Global Vel Dist=  1 , 1 , 1
Global Log Level= 0
CheckData=True
Encroach Param= -1, 0, 0, 0
BEGIN DESCRIPTION:
Multiple Run
END DESCRIPTION:

--- EAST FORK HUNTERS CREEK.f01 (steady flow) ---

Flow Title=Multiple
Program Version=4.10
Number of Profiles= 7
Profile Names=10-year,25-year,50-year,1pct_min,100-year,1pct_plu,500-year
River Rch & RM=EAST FORK HUNTER,Reach-1         ,21049
    1051    1545    1982    1862    2518    3405    4076
River Rch & RM=EAST FORK HUNTER,Reach-1         ,20186
    1332    1975    2545    2398    3243    4386    5290
River Rch & RM=EAST FORK HUNTER,Reach-1         ,14438
    2111    3197    4178    3987    5392    7292    9020
River Rch & RM=EAST FORK HUNTER,Reach-1         ,11552
    2694    4119    5418    5200    7032    9510   11899
River Rch & RM=EAST FORK HUNTER,Reach-1         ,10710
    2694    4119    5418    5200    7032    9510   11899
River Rch & RM=EAST FORK HUNTER,Reach-1         ,6746
    2913    4463    5878    5645    7634   10325   12941
River Rch & RM=EAST FORK HUNTER,Reach-1         ,3508
    4413    6837    9074    8769   11859   16038   20350
Boundary for River Rch & Prof#=EAST FORK HUNTER,Reach-1         , 1
Up Type= 0
Dn Type= 1
Dn Known WS=1565.17
Boundary for River Rch & Prof#=EAST FORK HUNTER,Reach-1         , 2
Up Type= 0
Dn Type= 1
Dn Known WS=1567.3
Boundary for River Rch & Prof#=EAST FORK HUNTER,Reach-1         , 3
Up Type= 0
Dn Type= 1
Dn Known WS=1568.88
Boundary for River Rch & Prof#=EAST FORK HUNTER,Reach-1         , 4
Up Type= 0
Dn Type= 1
Dn Known WS=1568.71
Boundary for River Rch & Prof#=EAST FORK HUNTER,Reach-1         , 5
Up Type= 0
Dn Type= 1
Dn Known WS=1570.66
Boundary for River Rch & Prof#=EAST FORK HUNTER,Reach-1         , 6
Up Type= 0
Dn Type= 1
Dn Known WS=1572.67
Boundary for River Rch & Prof#=EAST FORK HUNTER,Reach-1         , 7
Up Type= 0
Dn Type= 1
Dn Known WS=1574.41
Set Internal Change=EAST FORK HUNTER,Reach-1         ,413     , 7 , 3 ,1574.41
Set Internal Change=EAST FORK HUNTER,Reach-1         ,413     , 6 , 3 ,1572.67
Set Internal Change=EAST FORK HUNTER,Reach-1         ,413     , 5 , 3 ,1570.66
Set Internal Change=EAST FORK HUNTER,Reach-1         ,413     , 4 , 3 ,1568.71
Set Internal Change=EAST FORK HUNTER,Reach-1         ,413     , 3 , 3 ,1568.88
Set Internal Change=EAST FORK HUNTER,Reach-1         ,413     , 2 , 3 ,1567.3
Set Internal Change=EAST FORK HUNTER,Reach-1         ,413     , 1 , 3 ,1565.17
DSS Import GetInterval= 0
DSS Import GetPeak= 0
DSS Import FillOption= 0

--- EAST FORK HUNTERS CREEK.g01 (geometry) ---

Geom Title=Existing Conditions
Program Version=4.10

River Reach=EAST FORK HUNTER,Reach-1
Reach XY= 30
      2816440.84      10015879.9      2816148.16     10016783.75
      2815858.48     10016958.21      2815408.48      10016743.9
      2815335.54      10017222.5      2815051.43     10017659.07
      2814144.43       10017980.       2813852.2     10017800.27
      2813509.62     10017816.82      2812714.63     10018805.86
      2811938.47     10019013.73      2811610.15     10019311.78
      2811311.68     10019785.06      2811228.47     10020443.73
      2810801.17     10020854.87       2810893.6     10021566.54
       2810295.9     10021669.01      2809131.93     10022527.18
      2808114.63     10023652.66      2807850.02     10024218.41
      2807473.33     10024369.03      2806317.85     10024015.19
      2805885.72     10024028.99      2805791.46     10024289.31
      2805134.11     10024521.59      2804833.36     10025721.48
       2804293.6     10026111.34      2803353.64     10026161.93
      2803290.24     10026438.18      2803478.68     10026934.32

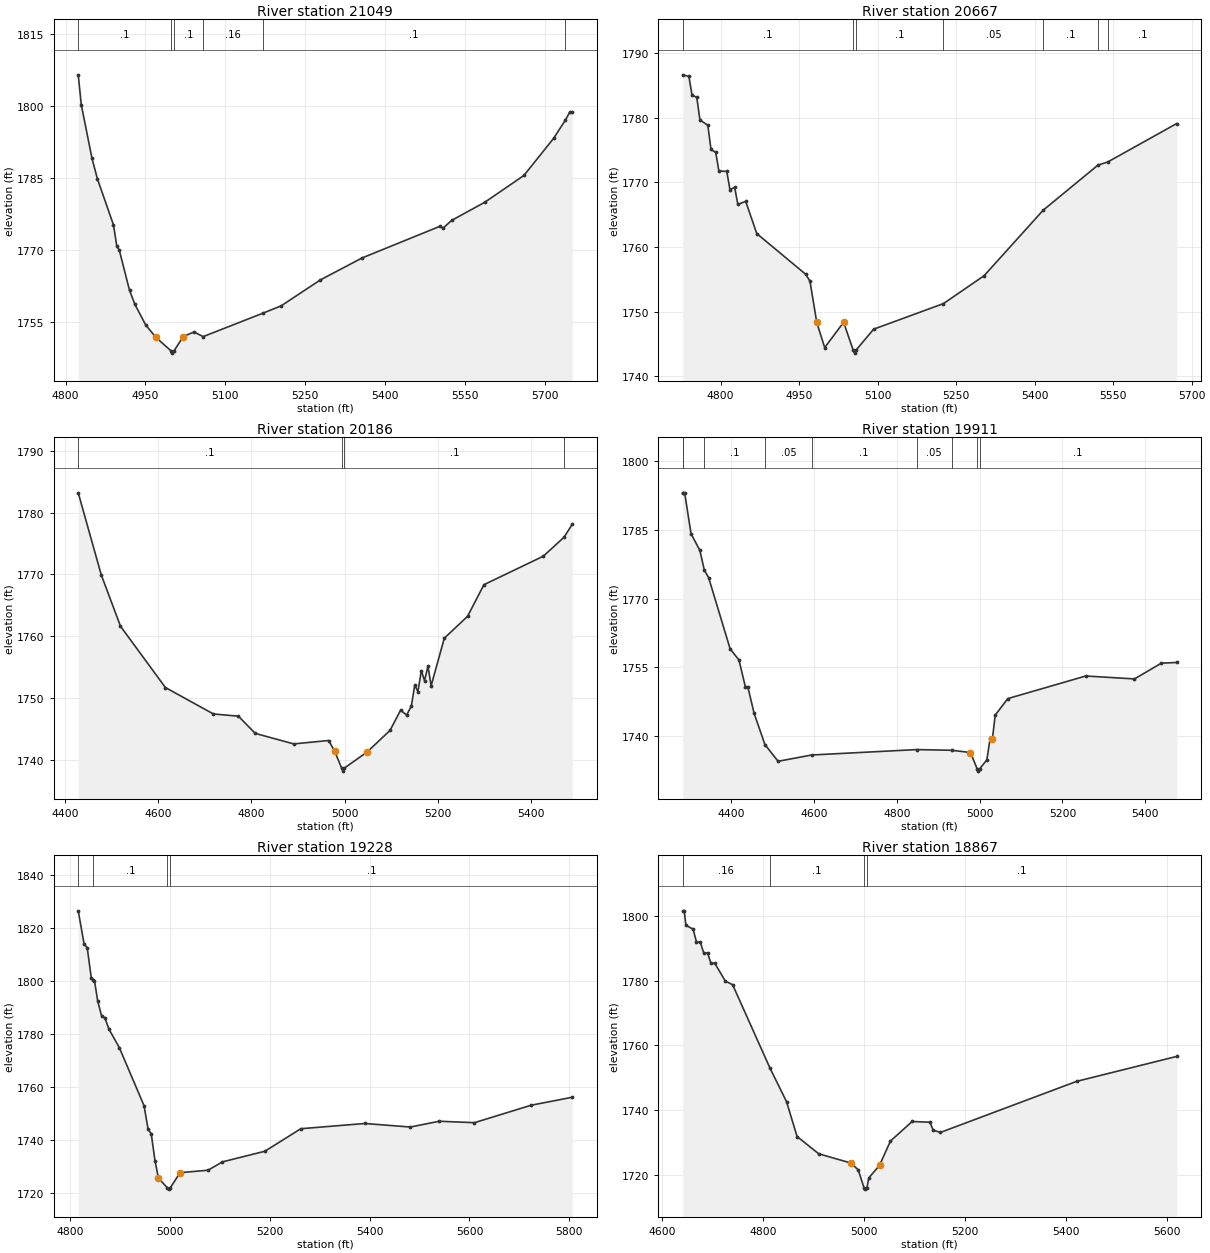
Type RM Length L Ch R = 1 ,21049   ,382,382,382
BEGIN DESCRIPTION:
EAST FORK HUNTERS CREEK 44.0
END DESCRIPTION:
XS GIS Cut Line= 2
      2816242.86     10016039.14      2817163.07     10016160.67
#Sta/Elev= 30
  4823.9 1806.55  4829.6 1800.31  4849.7 1789.14  4859.8 1784.88  4890.1 1775.23
  4896.2 1770.89  4901.2 1769.89  4920.3 1761.56  4930.4 1758.64  4950.6 1754.36
  4969.6 1751.78    4998 1748.97  5000.8 1748.47    5004 1748.97  5021.2 1751.93
  5041.4 1752.88  5058.7 1751.92  5170.7  1756.8  5205.2 1758.34  5278.7 1763.74
  5357.3 1768.34  5504.2 1774.97  5509.3 1774.55  5525.5 1776.17  5587.8 1779.96
  5661.3 1785.55  5717.2 1793.31  5738.8 1797.04  5747.2 1798.73  5752.1 1798.73
#Mann= 6 ,-1 , 0
  4823.9      .1       0    4998     .07       0    5004      .1       0
  5058.7     .16       0  5170.7      .1       0  5738.8     .16       0
Bank Sta=4969.6,5021.2
XS Rating Curve= 0 ,0
Exp/Cntr=0.3,0.1

Type RM Length L Ch R = 1 ,20667   ,481,481,481
BEGIN DESCRIPTION:
Mapping XS 135af219
END DESCRIPTION:
XS GIS Cut Line= 2
      2816044.97     10016261.37      2816835.03     10016777.68
#Sta/Elev= 30
  4727.7 1786.69  4739.5 1786.44  4745.5 1783.55  4754.6 1783.19  4760.6 1779.69
  4775.7 1778.87  4781.7 1775.14  4790.8 1774.65  4796.8 1771.78  4811.9 1771.72
  4817.9  1768.9    4827 1769.23    4833 1766.62  4848.1 1767.06  4869.2 1762.08
  4962.7 1755.77  4970.8 1754.71  4983.8 1748.31  4998.9 1744.41  5035.1 1748.33
  5053.2 1744.05  5055.9 1743.55  5059.2 1744.05  5092.4 1747.26  5225.9 1751.23
  5303.6 1755.56  5416.3  1765.7  5520.9 1772.69  5539.9 1773.19  5671.5 1779.14
#Mann= 7 ,-1 , 0
  4727.7      .1       0  5053.2     .07       0  5059.2      .1       0
  5225.9     .05       0  5416.3      .1       0  5520.9     .16       0
  5539.9      .1       0
Bank Sta=4983.8,5035.1
XS Rating Curve= 0 ,0
Exp/Cntr=0.3,0.1

Type RM Length L Ch R = 1 ,20186   ,275,275,275
BEGIN DESCRIPTION:
EAST FORK HUNTERS CREEK 43.0
END DESCRIPTION:
XS GIS Cut Line= 3
      2815951.21      10016282.2      2816121.35     10016966.22
      2816363.94     10017226.14
#Sta/Elev= 30
  4428.2 1783.18  4477.6 1769.92  4518.9 1761.62  4615.3 1751.71  4718.3 1747.44
    4772 1747.08  4808.1  1744.3  4890.8  1742.6  4965.6 1743.15  4978.6 1741.43
  4993.5  1738.7  4996.3  1738.2  4999.5  1738.7  5048.1 1741.28  5097.4 1744.78
  5120.2 1748.05  5133.1 1747.26  5143.3 1748.74  5150.5 1752.12  5157.3 1751.05
  5164.7 1754.45  5171.5  1752.8  5178.8 1755.16  5185.7 1752.01    5214 1759.69
  5263.8 1763.21    5299 1768.33  5426.5 1772.94  5471.2 1776.02  5488.6  1778.1
#Mann= 4 ,-1 , 0
  4428.2      .1       0  4993.5     .07       0  4999.5      .1       0
  5471.2     .05       0
Bank Sta=4978.6,5048.1
XS Rating Curve= 0 ,0
Exp/Cntr=0.3,0.1

Type RM Length L Ch R = 1 ,19911   ,683,683,683
BEGIN DESCRIPTION:
EAST FORK HUNTERS CREEK 42.0
END DESCRIPTION:
XS GIS Cut Line= 4
      2815357.45     10016497.46       2815815.8      10016782.2
       2815878.3       10017119.      2816033.69     10017388.35
#Sta/Elev= 30
  4282.9  1793.1  4284.1  1793.1  4287.6 1793.11    4303 1784.17  4324.3 1780.52
  4335.1 1776.21  4345.5 1774.56  4397.5 1758.97  4418.7 1756.57  4434.1 1750.74
    4440 1750.73  4455.3 1744.92  4481.4 1738.08  4513.2 1734.41  4594.5 1735.79
    4848 1736.97  4932.6 1736.82  4977.9 1736.33    4994 1732.76  4996.7 1732.26
    5000 1732.76  5017.3  1734.7  5025.7 1739.58  5030.7  1739.2  5037.6 1744.51
  5068.1 1748.12  5256.3 1753.06    5374 1752.42  5438.7 1755.86    5476 1756.02
#Mann= 9 ,-1 , 0
  4282.9      .1       0  4284.1     .05       0  4335.1      .1       0
  4481.4     .05       0  4594.5      .1       0    4848     .05       0
  4932.6      .1       0    4994     .07       0    5000      .1       0
Bank Sta=4977.9,5030.7
XS Rating Curve= 0 ,0
Exp/Cntr=0.3,0.1

Type RM Length L Ch R = 1 ,19228   ,361,361,361
BEGIN DESCRIPTION:
EAST FORK HUNTERS CREEK 41.0
END DESCRIPTION:
XS GIS Cut Line= 2
      2815197.78     10016778.75      2815974.47     10017392.47
#Sta/Elev= 30
  4816.1  1826.6  4827.8 1814.09  4834.1  1812.6  4842.2  1801.3  4846.5 1800.57
  4848.6 1800.22  4855.2 1792.38    4863 1786.79  4869.4 1786.16  4877.5 1781.88
  4898.3 1774.89    4948 1752.86    4956 1744.03  4962.4 1742.22  4969.9 1732.05
  4976.8  1725.5  4994.6 1721.81  4997.4 1721.31  5000.6 1721.81  5020.1 1727.54
  5076.2 1728.46  5105.1 1731.63    5190 1735.64  5262.2 1744.17  5390.4 1746.14
  5481.7  1744.8  5539.5 1746.99    5610 1746.45  5723.8 1753.06    5806 1756.07
#Mann= 4 ,-1 , 0
  4816.1     .05       0  4846.5      .1       0  4994.6     .07       0
  5000.6      .1       0
Bank Sta=4976.8,5020.1
XS Rating Curve= 0 ,0
Exp/Cntr=0.3,0.1

Type RM Length L Ch R = 1 ,18867   ,410,410,410
BEGIN DESCRIPTION:
EAST FORK HUNTERS CREEK 40.0
END DESCRIPTION:
XS GIS Cut Line= 2
      2815048.44     10017014.84      2815801.26      10017639.3
#Sta/Elev= 30
  4640.6  1801.5  4643.6  1801.5  4646.9 1797.04  4661.2 1795.84  4667.7 1791.98
  4675.6 1791.76  4682.1 1788.54  4689.9 1788.44  4696.4 1785.35  4704.2 1785.31
    4725 1779.82  4739.4 1778.72  4813.1 1753.09  4846.2 1742.63    4867  1731.9
    4910 1726.56  4973.8 1723.71  4988.1 1721.61  4999.4 1716.17  5002.2 1715.67
  5005.4 1716.17  5008.9 1719.09  5030.4 1723.06  5051.9  1730.5  5094.9 1736.53
  5130.1  1736.3  5136.5 1733.85  5150.9 1733.16  5420.4  1748.9  5618.7  1756.6
#Mann= 4 ,-1 , 0
  4640.6     .16       0  4813.1      .1       0  4999.4     .07       0
  5005.4      .1       0
Bank Sta=4973.8,5030.4
XS Rating Curve= 0 ,0
Exp/Cntr=0.3,0.1

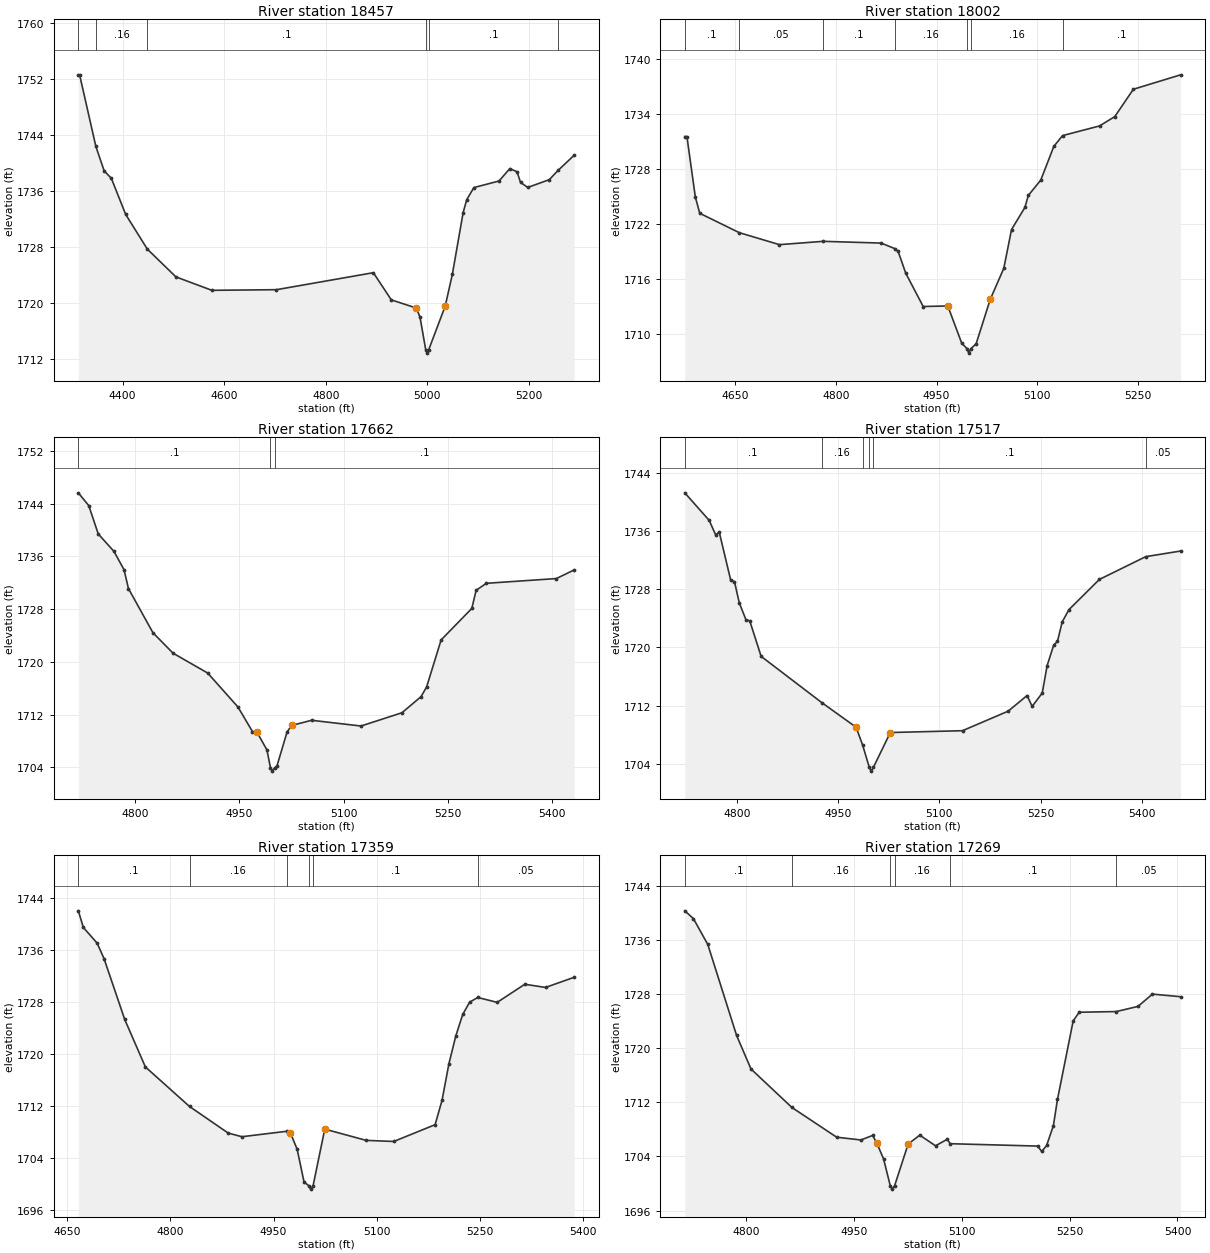
Type RM Length L Ch R = 1 ,18457   ,455,455,455
BEGIN DESCRIPTION:
EAST FORK HUNTERS CREEK 39.0
END DESCRIPTION:
XS GIS Cut Line= 2
      2814635.24     10017105.12      2815322.33     10017799.14
#Sta/Elev= 30
  4312.7 1752.61  4315.2 1752.61  4347.2 1742.38  4363.5 1738.89  4377.7 1737.81
  4405.9 1732.66  4448.6 1727.69  4504.9 1723.72  4575.7  1721.8  4702.9 1721.89
  4893.8 1724.32  4929.2 1720.43  4978.7 1719.26  4985.8 1717.93  4996.9 1713.32
  4999.7 1712.82  5002.9 1713.32  5035.3 1719.54  5049.4 1724.09  5070.6  1732.9
  5077.7 1734.76  5091.8 1736.49  5141.3 1737.43  5162.5  1739.2  5176.7 1738.75
  5183.7 1737.23  5197.9 1736.51  5240.3 1737.62    5258 1738.97  5289.3 1741.11
#Mann= 6 ,-1 , 0
  4312.7      .1       0  4347.2     .16       0  4448.6      .1       0
  4996.9     .07       0  5002.9      .1       0    5258     .05       0
Bank Sta=4978.7,5035.3
XS Rating Curve= 0 ,0
Exp/Cntr=0.3,0.1

Type RM Length L Ch R = 1 ,18002   ,340,340,340
BEGIN DESCRIPTION:
EAST FORK HUNTERS CREEK 38.0
END DESCRIPTION:
XS GIS Cut Line= 3
      2814558.86     10017292.63      2814728.99     10017792.61
      2814914.93     10017892.47
#Sta/Elev= 30
  4574.7 1731.51  4577.9 1731.51  4590.4 1724.94    4597 1723.17    4656 1721.06
  4715.8 1719.76  4781.1 1720.12  4867.4 1719.93  4887.4 1719.34  4892.8 1719.02
    4904 1716.67  4930.1 1713.03  4966.8 1713.09  4987.6 1709.03  4995.4 1708.46
  4998.1 1707.96  5001.4 1708.46    5009 1708.97  5030.1 1713.81  5050.3 1717.19
  5061.8  1721.4  5081.7  1723.8  5086.9 1725.12  5105.4 1726.78  5124.9 1730.45
  5137.9 1731.62    5193 1732.67  5215.8 1733.69  5243.4 1736.66  5313.9 1738.23
#Mann= 7 ,-1 , 0
  4574.7      .1       0    4656     .05       0  4781.1      .1       0
  4887.4     .16       0  4995.4     .07       0  5001.4     .16       0
  5137.9      .1       0
Bank Sta=4966.8,5030.1
XS Rating Curve= 0 ,0
Exp/Cntr=0.3,0.1

Type RM Length L Ch R = 1 ,17662   ,145,145,145
BEGIN DESCRIPTION:
Mapping XS 5462df41
END DESCRIPTION:
XS GIS Cut Line= 3
      2814209.27     10017591.86      2814421.99     10017865.12
       2814636.6      10018162.1
#Sta/Elev= 30
  4718.6 1745.62  4733.6 1743.68  4747.2 1739.39  4769.8 1736.74  4784.3 1733.96
  4790.6 1731.11  4825.9  1724.4  4854.8  1721.3  4904.6 1718.29    4948 1713.15
  4968.9 1709.42  4975.2 1709.36  4989.7 1706.63  4994.8 1703.92  4997.6 1703.42
  5000.8 1703.92  5004.1  1704.2  5018.6 1709.34  5025.1 1710.34  5053.9 1711.13
  5124.9 1710.26  5183.7 1712.27  5211.2 1714.71  5219.2 1716.18  5240.1 1723.32
  5284.2 1728.09  5290.4 1730.84  5305.1  1731.9  5405.7 1732.62  5431.3 1733.93
#Mann= 3 ,-1 , 0
  4718.6      .1       0  4994.8     .07       0  5000.8      .1       0
Bank Sta=4975.2,5025.1
XS Rating Curve= 0 ,0
Exp/Cntr=0.3,0.1

Type RM Length L Ch R = 1 ,17517   ,158,158,158
BEGIN DESCRIPTION:
Mapping XS 1cea4990
END DESCRIPTION:
XS GIS Cut Line= 2
       2814141.8     10017641.24      2814464.11     10018301.46
#Sta/Elev= 30
  4722.8 1741.22    4759 1737.43  4768.4 1735.47  4773.9  1735.8  4790.9  1729.2
  4796.4 1729.03  4803.5 1726.12  4813.4  1723.8    4819 1723.65  4835.9 1718.77
  4925.6 1712.43  4976.6 1709.04  4986.4 1706.56  4996.2 1703.51  4998.9 1703.01
  5002.2 1703.51  5027.3 1708.31  5134.3 1708.56  5201.9 1711.24    5230 1713.39
  5237.5  1711.9  5252.5 1713.74  5259.7  1717.5  5269.5 1720.33    5275 1720.81
    5282 1723.49    5292 1725.18  5337.1 1729.33  5405.9 1732.46  5457.5 1733.23
#Mann= 6 ,-1 , 0
  4722.8      .1       0  4925.6     .16       0  4986.4      .1       0
  4996.2     .07       0  5002.2      .1       0  5405.9     .05       0
Bank Sta=4976.6,5027.3
XS Rating Curve= 0 ,0
Exp/Cntr=0.3,0.1

Type RM Length L Ch R = 1 ,17359   ,90,90,90
BEGIN DESCRIPTION:
Mapping XS c6064296
END DESCRIPTION:
XS GIS Cut Line= 2
      2814115.77     10017646.49      2814162.65     10018365.26
#Sta/Elev= 30
  4666.3    1742  4673.6 1739.44  4693.6 1737.04  4703.6 1734.67  4733.7 1725.31
  4763.7 1718.02  4827.8 1711.95    4884 1707.86    4904  1707.3  4969.3 1708.14
  4974.2 1707.93  4984.2 1705.37  4994.2 1700.35  5001.3 1699.75    5004 1699.25
  5007.3 1699.75  5024.3 1708.47  5084.4 1706.74  5124.5 1706.57  5184.6 1709.15
  5194.7  1712.9  5204.7 1718.53  5214.7 1722.79  5224.7 1726.08  5234.7 1727.96
  5246.5 1728.69  5274.8 1727.94  5314.9 1730.72    5345 1730.23  5386.6 1731.79
#Mann= 6 ,-1 , 0
  4666.3      .1       0  4827.8     .16       0  4969.3      .1       0
  5001.3     .07       0  5007.3      .1       0  5246.5     .05       0
Bank Sta=4974.2,5024.3
XS Rating Curve= 0 ,0
Exp/Cntr=0.3,0.1

Type RM Length L Ch R = 1 ,17269   ,290,290,290
BEGIN DESCRIPTION:
EAST FORK HUNTERS CREEK 37.0
END DESCRIPTION:
XS GIS Cut Line= 4
       2814074.1     10017651.72      2814084.52     10017891.26
      2813933.48     10018172.51       2813949.1     10018302.67
#Sta/Elev= 30
  4714.3 1740.29  4726.3 1739.14  4746.3 1735.32  4786.4 1721.88  4806.4 1716.93
  4863.4 1711.24  4925.7 1706.85  4959.4 1706.44  4975.7 1707.11  4981.3 1706.04
  4990.9 1703.66  5000.3 1699.68    5003 1699.18  5006.3 1699.68  5025.2 1705.85
  5041.4 1707.15  5063.3 1705.58  5079.6 1706.55  5083.6 1705.89  5205.4 1705.54
  5211.1 1704.74  5217.9 1705.63  5227.3 1708.55    5233 1712.43  5254.9 1724.05
  5263.3 1725.31  5314.9 1725.41    5345 1726.17  5365.2 1727.99  5404.4  1727.6
#Mann= 6 ,-1 , 0
  4714.3      .1       0  4863.4     .16       0  5000.3     .07       0
  5006.3     .16       0  5083.6      .1       0  5314.9     .05       0
Bank Sta=4981.3,5025.2
XS Rating Curve= 0 ,0
Exp/Cntr=0.3,0.1

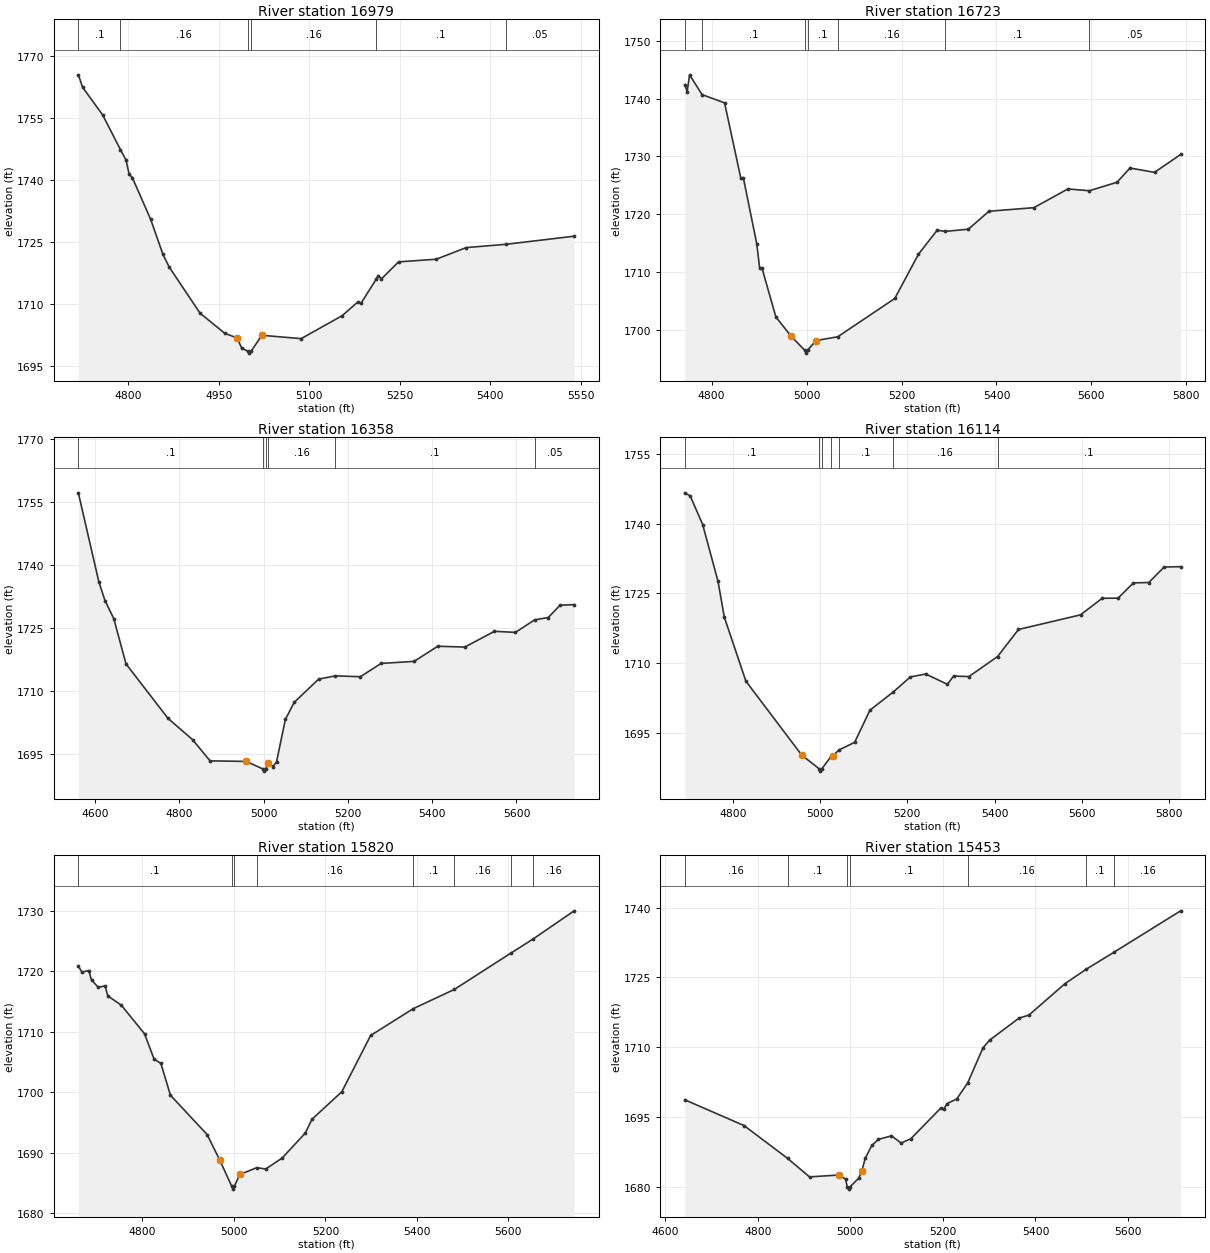
Type RM Length L Ch R = 1 ,16979   ,256,256,256
BEGIN DESCRIPTION:
Mapping XS 2462837a
END DESCRIPTION:
XS GIS Cut Line= 3
      2813881.39     10017526.67      2813787.64     10017958.97
       2813891.8     10018323.53
#Sta/Elev= 30
  4717.5 1765.47  4724.7 1762.43  4757.7 1755.78  4787.2 1747.37  4796.4 1744.87
  4801.8 1741.35  4806.9 1740.59  4837.3 1730.47  4857.7 1721.97    4868 1718.91
  4919.1 1707.73  4960.1 1702.85  4980.5 1701.71  4988.2 1699.26    4998 1698.54
  5000.8 1698.04    5004 1698.54  5021.5 1702.36  5086.6 1701.55  5154.5  1707.1
  5180.7 1710.45  5185.9 1710.14  5211.2 1715.99  5214.5 1716.83  5219.7 1716.03
    5248 1720.15  5310.4 1720.79  5360.1 1723.61  5426.2 1724.41    5539 1726.37
#Mann= 6 ,-1 , 0
  4717.5      .1       0  4787.2     .16       0    4998     .07       0
    5004     .16       0  5211.2      .1       0  5426.2     .05       0
Bank Sta=4980.5,5021.5
XS Rating Curve= 0 ,0
Exp/Cntr=0.3,0.1

Type RM Length L Ch R = 1 ,16723   ,365,365,365
BEGIN DESCRIPTION:
EAST FORK HUNTERS CREEK 36.0
END DESCRIPTION:
XS GIS Cut Line= 3
      2813501.19     10017547.51      2813647.02     10018073.55
      2813912.64     10018495.42
#Sta/Elev= 30
  4743.5 1742.42  4748.4 1741.19  4753.6  1744.1  4779.9 1740.68  4827.3 1739.25
  4861.6 1726.18  4866.8  1726.3  4895.2 1714.83  4901.1 1710.69  4906.3 1710.61
  4935.4 1702.21  4967.9 1698.85    4996 1696.46  4998.8 1695.96    5002 1696.46
  5019.8 1698.13  5065.6 1698.79  5185.8 1705.41  5235.6 1713.06    5275 1717.22
  5292.6 1717.02  5340.9  1717.4  5384.1  1720.5  5478.7 1721.12  5550.5 1724.36
  5595.7 1724.05    5654 1725.52  5681.2 1727.98  5732.9 1727.23  5787.9 1730.32
#Mann= 7 ,-1 , 0
  4743.5     .16       0  4779.9      .1       0    4996     .07       0
    5002      .1       0  5065.6     .16       0  5292.6      .1       0
  5595.7     .05       0
Bank Sta=4967.9,5019.8
XS Rating Curve= 0 ,0
Exp/Cntr=0.3,0.1

Type RM Length L Ch R = 1 ,16358   ,244,244,244
BEGIN DESCRIPTION:
EAST FORK HUNTERS CREEK 35.0
END DESCRIPTION:
XS GIS Cut Line= 3
      2813011.57     10017771.44      2813475.14     10018125.64
      2813876.19     10018563.14
#Sta/Elev= 30
    4560 1757.22  4608.8 1736.02  4623.4 1731.57  4644.2 1727.29  4673.2 1716.54
    4773 1703.57  4831.1 1698.53  4872.7 1693.48  4958.8 1693.35  4998.6 1691.54
  5001.3 1691.04  5004.6 1691.54  5011.2 1693.09  5022.4 1692.14  5030.6 1693.31
  5051.4 1703.33  5072.3 1707.39  5130.4 1712.92  5170.4  1713.7  5229.4 1713.49
  5278.7 1716.65    5357 1717.14  5413.1 1720.74  5477.2 1720.54  5547.8 1724.29
  5597.5 1724.03  5643.2 1727.02  5675.2 1727.56  5703.5 1730.49  5736.9 1730.63
#Mann= 6 ,-1 , 0
    4560      .1       0  4998.6     .07       0  5004.6      .1       0
  5011.2     .16       0  5170.4      .1       0  5643.2     .05       0
Bank Sta=4958.8,5011.2
XS Rating Curve= 0 ,0
Exp/Cntr=0.3,0.1

Type RM Length L Ch R = 1 ,16114   ,294,294,294
BEGIN DESCRIPTION:
EAST FORK HUNTERS CREEK 34.0
END DESCRIPTION:
XS GIS Cut Line= 2
      2812915.23     10017929.95      2813798.05     10018646.46
#Sta/Elev= 30
  4689.8 1746.66  4702.1 1746.01  4730.8 1739.84    4766 1727.59  4780.4 1719.92
  4829.9 1706.13  4957.8 1690.24  4997.9 1687.27  5000.7 1686.77  5003.9 1687.27
  5025.1  1689.9  5028.8 1690.02  5043.8 1691.35  5079.2 1692.96  5114.4 1699.89
  5166.6 1703.71  5207.1 1707.04  5242.3 1707.67  5291.9 1705.46  5306.2 1707.23
  5341.4 1707.12    5407 1711.43  5454.9 1717.25  5597.2  1720.4    5647 1723.97
  5683.4    1724  5718.6 1727.28  5753.8 1727.36    5789 1730.69  5826.8 1730.77
#Mann= 7 ,-1 , 0
  4689.8      .1       0  4997.9     .07       0  5003.9      .1       0
  5025.1     .16       0  5043.8      .1       0  5166.6     .16       0
    5407      .1       0
Bank Sta=4957.8,5028.8
XS Rating Curve= 0 ,0
Exp/Cntr=0.3,0.1

Type RM Length L Ch R = 1 ,15820   ,367,367,367
BEGIN DESCRIPTION:
EAST FORK HUNTERS CREEK 33.0
END DESCRIPTION:
XS GIS Cut Line= 2
      2812706.89     10018164.32      2813594.24     10018786.61
#Sta/Elev= 30
  4659.9 1720.86  4667.8 1719.85  4682.6 1720.12  4688.7 1718.57  4703.5 1717.35
  4718.3 1717.59  4724.4 1715.93    4754 1714.39  4804.6 1709.67  4825.5 1705.49
  4840.3 1704.78  4861.3 1699.51  4941.4 1693.02  4968.5 1688.89  4995.1  1684.5
  4997.9    1684  5001.1  1684.5  5012.9 1686.42  5049.7 1687.54  5069.6 1687.33
  5105.3 1689.13  5155.9 1693.26  5170.7 1695.55  5235.9  1700.1  5298.8 1709.39
  5391.9 1713.82  5481.5 1716.99  5605.3    1723  5654.7 1725.37  5743.7 1729.99
#Mann= 8 ,-1 , 0
  4659.9      .1       0  4995.1     .07       0  5001.1      .1       0
  5049.7     .16       0  5391.9      .1       0  5481.5     .16       0
  5605.3      .1       0  5654.7     .16       0
Bank Sta=4968.5,5012.9
XS Rating Curve= 0 ,0
Exp/Cntr=0.3,0.1

Type RM Length L Ch R = 1 ,15453   ,543,543,543
BEGIN DESCRIPTION:
EAST FORK HUNTERS CREEK 32.0
END DESCRIPTION:
XS GIS Cut Line= 2
      2812571.49     10018429.95       2813354.4     10019161.21
#Sta/Elev= 30
  4642.3 1698.68  4770.3 1693.14  4864.3 1686.09  4911.8  1682.1  4975.4 1682.51
  4989.6 1681.61  4993.4 1679.97  4996.2 1679.47  4999.4 1679.97  5017.9 1681.81
  5024.8 1683.36  5032.1 1686.09  5046.3 1688.86  5060.4 1690.16  5088.8 1690.93
  5109.8 1689.39  5130.8 1690.31  5194.8 1696.84  5201.6 1696.66    5209 1697.87
    5230 1698.87  5253.5 1702.32  5286.6 1709.86  5300.8  1711.5  5364.3 1716.24
  5385.8  1716.9  5463.5 1723.64  5509.8 1726.77    5570 1730.44  5713.6 1739.32
#Mann= 7 ,-1 , 0
  4642.3     .16       0  4864.3      .1       0  4993.4     .07       0
  4999.4      .1       0  5253.5     .16       0  5509.8      .1       0
    5570     .16       0
Bank Sta=4975.4,5024.8
XS Rating Curve= 0 ,0
Exp/Cntr=0.3,0.1

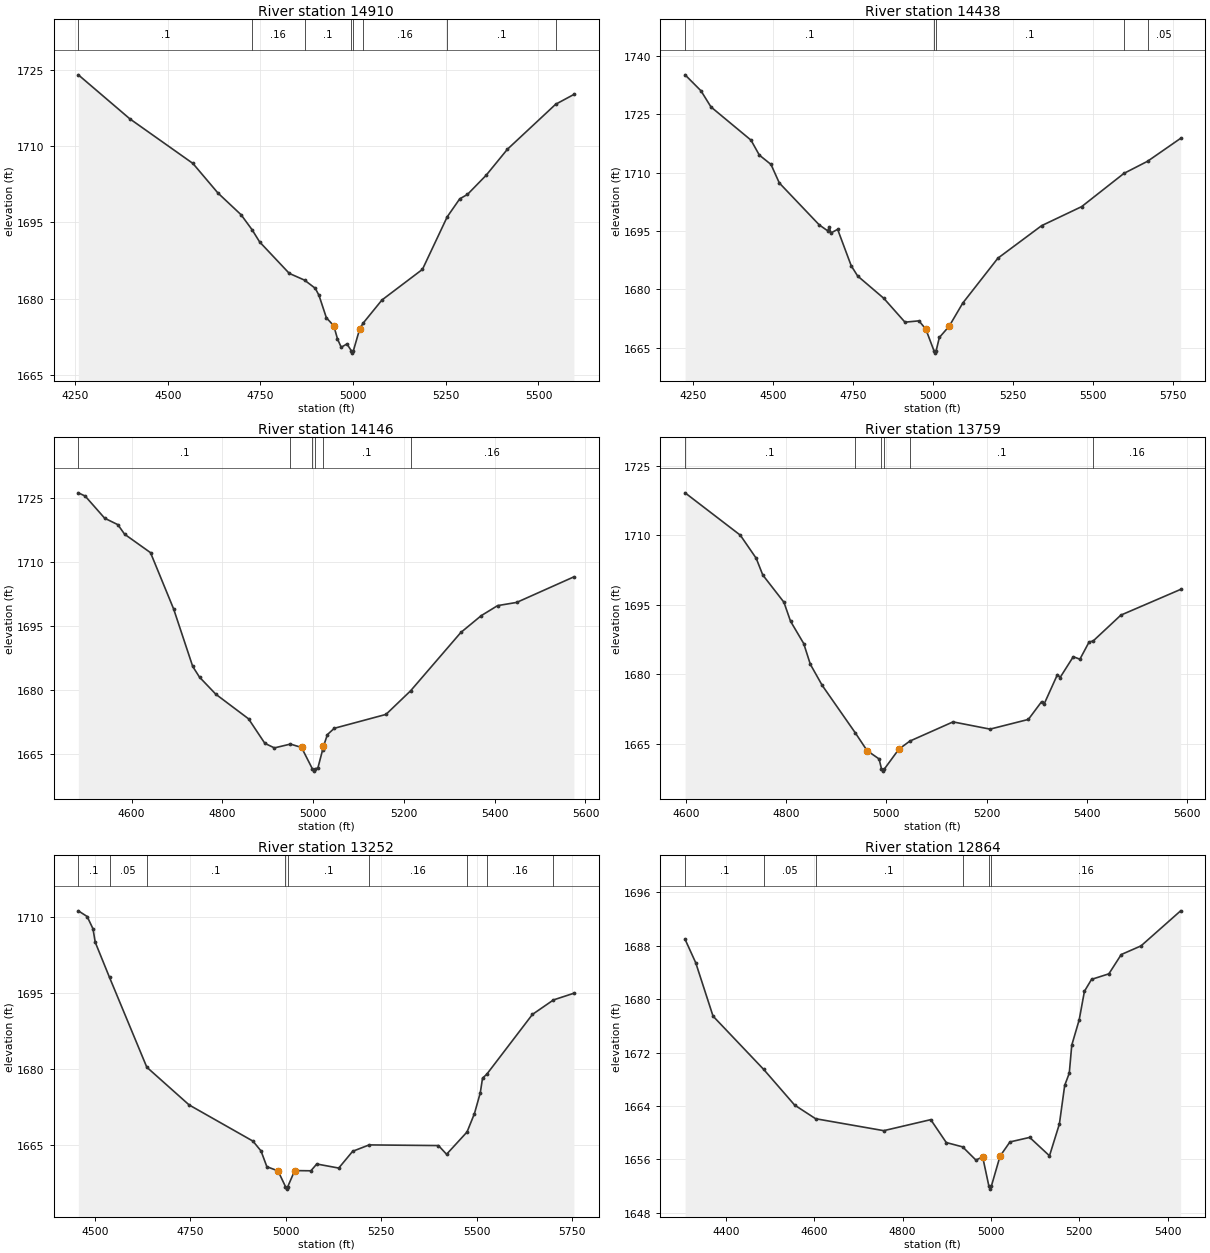
Type RM Length L Ch R = 1 ,14910   ,472,472,472
BEGIN DESCRIPTION:
EAST FORK HUNTERS CREEK 31.0
END DESCRIPTION:
XS GIS Cut Line= 3
      2812394.42     10018174.74      2812368.38      10019075.8
      2812623.07     10019429.25
#Sta/Elev= 30
  4258.5 1724.02  4397.6 1715.36  4567.6  1706.6  4635.2 1700.78  4697.7  1696.5
  4727.7 1693.52  4747.7 1691.16  4827.7 1684.97  4868.8 1683.65  4897.8 1682.04
  4907.8 1680.66  4927.8 1676.24  4947.8 1674.66  4957.8 1672.08  4967.8 1670.44
  4983.3  1671.1  4994.8 1669.79  4997.6 1669.29  5000.8 1669.79  5017.8 1674.07
  5026.9 1675.18  5077.8 1679.74    5187 1685.76  5253.9  1696.1  5287.6 1699.63
  5308.5  1700.5  5358.8 1704.26  5416.2 1709.38  5546.4 1718.23  5595.6 1720.16
#Mann= 8 ,-1 , 0
  4258.5      .1       0  4727.7     .16       0  4868.8      .1       0
  4994.8     .07       0  5000.8      .1       0  5026.9     .16       0
  5253.9      .1       0  5546.4     .05       0
Bank Sta=4947.8,5017.8
XS Rating Curve= 0 ,0
Exp/Cntr=0.3,0.1

Type RM Length L Ch R = 1 ,14438   ,292,292,292
BEGIN DESCRIPTION:
EAST FORK HUNTERS CREEK 30.0
END DESCRIPTION:
XS GIS Cut Line= 3
      2811206.88     10018742.45      2811769.42     10018935.17
      2812580.56     10019439.54
#Sta/Elev= 30
  4225.6  1735.1  4275.3    1731  4306.6 1726.85  4431.8 1718.32  4457.8 1714.49
  4494.3 1712.08  4520.3 1707.33  4645.4 1696.54  4671.2 1695.06  4676.7  1695.9
    4682 1694.49  4702.7 1695.41  4745.2 1686.06  4765.3 1683.43  4847.2 1677.69
  4913.3 1671.57    4957 1671.91  4978.3 1669.81  5004.5 1664.12  5007.3 1663.62
  5010.5 1664.12  5020.8 1667.64  5051.5 1670.53    5094 1676.47  5203.8    1688
  5340.7 1696.36  5465.9 1701.25    5598 1709.78    5672  1712.9  5775.4 1718.79
#Mann= 5 ,-1 , 0
  4225.6      .1       0  5004.5     .07       0  5010.5      .1       0
    5598      .1       0    5672     .05       0
Bank Sta=4978.3,5051.5
XS Rating Curve= 0 ,0
Exp/Cntr=0.3,0.1

Type RM Length L Ch R = 1 ,14146   ,387,387,387
BEGIN DESCRIPTION:
EAST FORK HUNTERS CREEK 29.0
END DESCRIPTION:
XS GIS Cut Line= 2
      2811290.24     10018950.79      2812196.51     10019560.18
#Sta/Elev= 30
  4482.4 1726.24  4497.5 1725.48  4540.5 1720.28  4569.5 1718.77  4584.5 1716.52
  4641.5  1712.2  4692.5 1698.97  4734.5  1685.5  4749.5 1682.98  4785.5 1678.97
  4857.5 1673.21  4893.5 1667.45  4914.5 1666.38  4949.9 1667.28  4974.3 1666.48
  4998.4 1661.43  5001.2 1660.93  5004.4 1661.43  5010.4 1661.69  5020.7 1665.89
  5022.5 1666.72  5031.4 1669.51  5046.4 1670.98  5160.4 1674.24  5214.6 1679.77
  5325.4 1693.47  5370.4 1697.42  5406.4 1699.77  5448.4 1700.52  5574.5 1706.52
#Mann= 6 ,-1 , 0
  4482.4      .1       0  4949.9     .16       0  4998.4     .07       0
  5004.4     .16       0  5020.7      .1       0  5214.6     .16       0
Bank Sta=4974.3,5022.5
XS Rating Curve= 0 ,0
Exp/Cntr=0.3,0.1

Type RM Length L Ch R = 1 ,13759   ,507,507,507
BEGIN DESCRIPTION:
EAST FORK HUNTERS CREEK 28.0
END DESCRIPTION:
XS GIS Cut Line= 2
      2811071.46     10019383.08      2812009.04      10019695.6
#Sta/Elev= 30
  4598.6 1719.17  4708.7 1710.04  4740.4 1705.06  4753.6 1701.44  4795.7 1695.58
  4808.9 1691.48  4835.2 1686.66  4848.4 1682.19  4872.1 1677.63  4938.3 1667.36
  4961.7 1663.55  4985.5 1661.77  4990.3 1659.64  4993.1 1659.14  4996.3 1659.64
    5025 1663.88  5046.9 1665.62    5133 1669.76  5206.8  1668.2  5283.2 1670.29
  5309.6 1674.12  5314.8 1673.65  5341.2 1679.97  5346.5 1679.33  5372.8 1683.82
    5386 1683.28  5404.4 1687.01  5412.3  1687.2  5467.7 1692.79  5586.9 1698.34
#Mann= 6 ,-1 , 0
  4598.6      .1       0  4938.3     .16       0  4990.3     .07       0
  4996.3     .16       0  5046.9      .1       0  5412.3     .16       0
Bank Sta=4961.7,5025
XS Rating Curve= 0 ,0
Exp/Cntr=0.3,0.1

Type RM Length L Ch R = 1 ,13252   ,388,388,388
BEGIN DESCRIPTION:
EAST FORK HUNTERS CREEK 27.0
END DESCRIPTION:
XS GIS Cut Line= 2
       2810805.9     10019685.19      2811904.13     10020377.44
#Sta/Elev= 30
  4456.3 1711.23  4479.4 1710.11  4494.7 1707.69  4500.6 1705.03  4538.1 1698.07
  4635.7 1680.36  4746.6 1672.91  4913.7 1665.77  4934.9 1663.83  4950.2 1660.72
  4979.4 1659.89    4999 1656.79  5001.7 1656.29    5005 1656.79  5023.2 1659.95
  5065.6 1659.91  5080.9 1661.25  5138.5 1660.45    5175 1663.76  5218.3 1665.02
  5399.8 1664.89    5421 1663.17  5474.6 1667.57    5494  1671.2  5509.3  1675.3
  5515.2  1678.2  5526.2 1678.96  5645.9 1690.78    5701 1693.64  5754.5 1694.96
#Mann= 9 ,-1 , 0
  4456.3      .1       0  4538.1     .05       0  4635.7      .1       0
    4999     .07       0    5005      .1       0  5218.3     .16       0
  5474.6      .1       0  5526.2     .16       0    5701     .05       0
Bank Sta=4979.4,5023.2
XS Rating Curve= 0 ,0
Exp/Cntr=0.3,0.1

Type RM Length L Ch R = 1 ,12864   ,394,394,394
BEGIN DESCRIPTION:
EAST FORK HUNTERS CREEK 26.0
END DESCRIPTION:
XS GIS Cut Line= 2
      2810639.23     10020039.35      2811643.36     10020538.82
#Sta/Elev= 30
  4307.8 1688.96  4331.9 1685.45  4371.1 1677.45  4485.8 1669.46  4555.8 1664.12
  4603.2 1662.08  4757.4 1660.29  4863.8 1661.94  4898.9 1658.51    4936 1657.86
  4965.9 1655.89  4981.3 1656.35  4995.2 1652.03  4997.9 1651.53  5001.2 1652.03
  5020.6 1656.47    5043  1658.6  5087.7 1659.28  5132.5 1656.52  5154.9 1661.29
  5166.9 1667.07  5177.3 1668.91  5182.9  1673.1  5199.7 1676.89  5211.6 1681.18
  5227.7 1682.96  5266.9 1683.79  5294.9 1686.68  5339.7 1687.98  5429.3 1693.23
#Mann= 6 ,-1 , 0
  4307.8      .1       0  4485.8     .05       0  4603.2      .1       0
    4936     .16       0  4995.2     .07       0  5001.2     .16       0
Bank Sta=4981.3,5020.6
XS Rating Curve= 0 ,0
Exp/Cntr=0.3,0.1

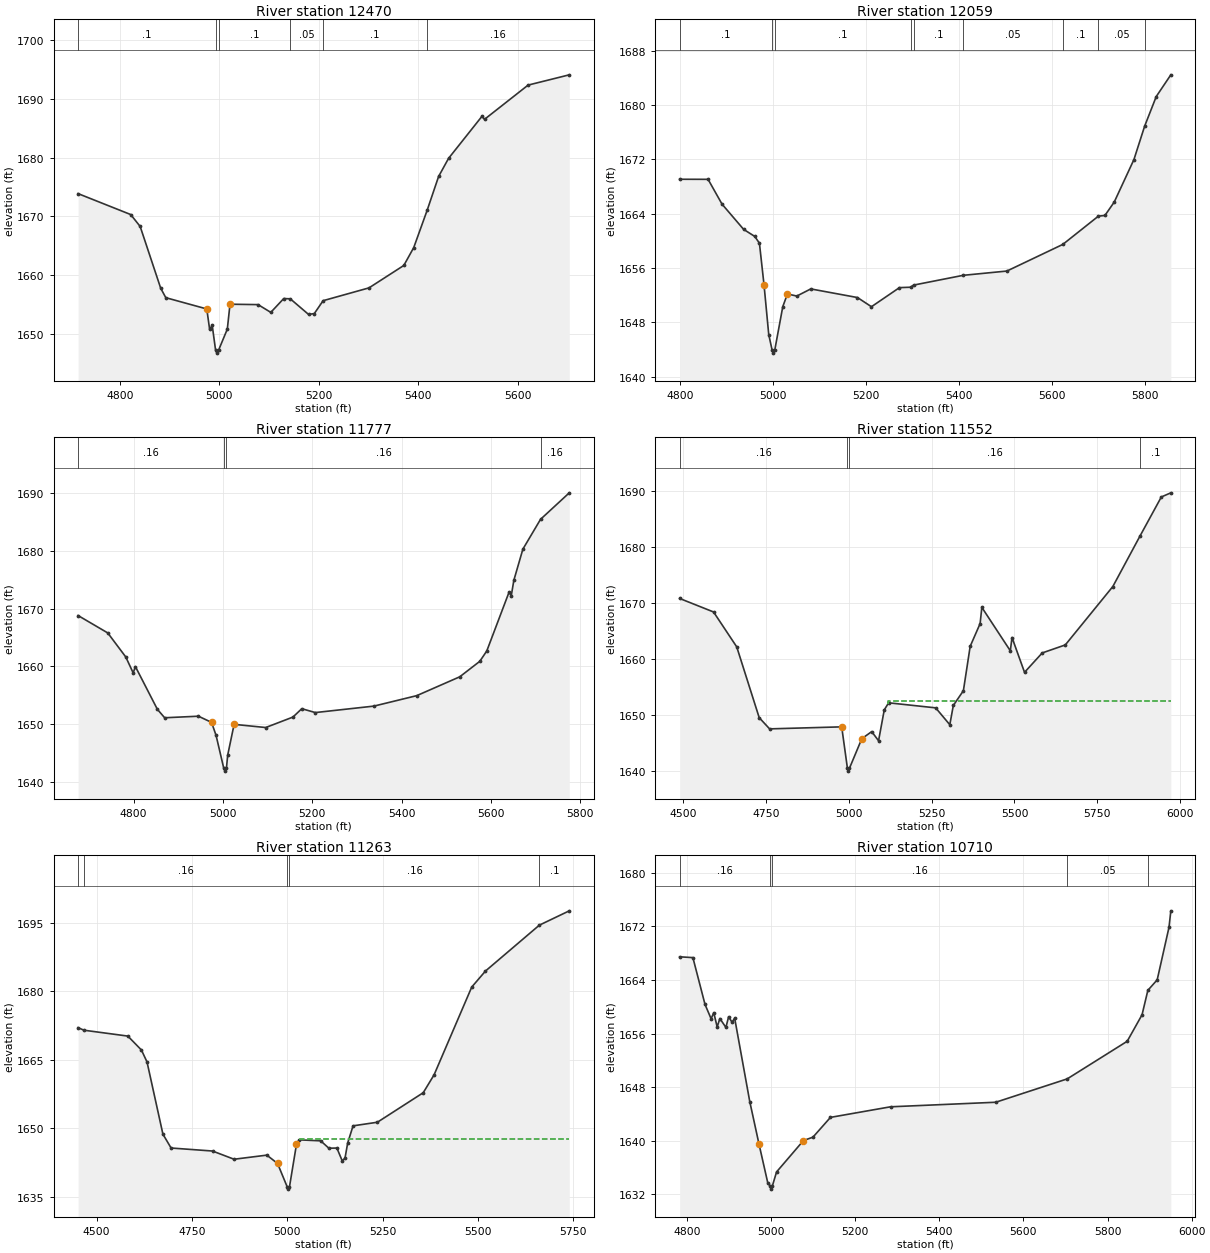
Type RM Length L Ch R = 1 ,12470   ,411,411,411
BEGIN DESCRIPTION:
EAST FORK HUNTERS CREEK 25.0
END DESCRIPTION:
XS GIS Cut Line= 3
      2810717.34     10020523.72      2811170.46      10020638.3
      2811691.34     10020653.93
#Sta/Elev= 30
  4715.6 1673.86  4821.4  1670.3  4840.5 1668.27  4881.8 1657.76  4892.1 1656.14
  4974.6 1654.22  4980.3 1650.75  4985.5 1651.43  4992.3  1647.2    4995  1646.7
  4998.3  1647.2  5015.9 1650.79  5021.3 1655.03  5077.8 1654.96  5103.4 1653.64
  5129.4 1655.99  5142.6 1655.95  5179.4 1653.29    5191 1653.44  5208.7 1655.63
    5301 1657.81  5371.1 1661.63  5391.1 1664.68    5418 1671.01  5441.1 1676.78
  5461.1 1679.86  5528.5 1687.04  5533.5 1686.51  5621.2 1692.34  5704.1 1694.09
#Mann= 6 ,-1 , 0
  4715.6      .1       0  4992.3     .07       0  4998.3      .1       0
  5142.6     .05       0  5208.7      .1       0    5418     .16       0
Bank Sta=4974.6,5021.3
XS Rating Curve= 0 ,0
Exp/Cntr=0.3,0.1

Type RM Length L Ch R = 1 ,12059   ,282,282,282
BEGIN DESCRIPTION:
EAST FORK HUNTERS CREEK 24.0
END DESCRIPTION:
XS GIS Cut Line= 2
      2810597.59     10020940.38      2811649.67     10020851.84
#Sta/Elev= 30
  4798.9 1669.08    4860 1669.07  4890.1 1665.41  4936.5  1661.7  4960.3 1660.67
  4970.4 1659.67  4980.4 1653.46  4990.4 1646.23  4997.5 1643.99  5000.2 1643.49
  5003.5 1643.99  5020.6 1650.33  5030.6  1652.2  5050.7 1651.89  5080.8 1652.94
  5181.2 1651.67  5211.2 1650.32  5271.4 1653.13  5295.3 1653.19  5301.6  1653.5
  5408.2 1654.94  5502.3 1655.57  5622.5 1659.49    5699 1663.65    5713 1663.75
  5733.1 1665.73  5775.4 1671.98  5798.4 1676.89  5823.4 1681.26  5854.7 1684.45
#Mann= 9 ,-1 , 0
  4798.9      .1       0  4997.5     .07       0  5003.5      .1       0
  5295.3     .05       0  5301.6      .1       0  5408.2     .05       0
  5622.5      .1       0    5699     .05       0  5798.4     .16       0
Bank Sta=4980.4,5030.6
XS Rating Curve= 0 ,0
Exp/Cntr=0.3,0.1

Type RM Length L Ch R = 1 ,11777   ,225,225,225
BEGIN DESCRIPTION:
EAST FORK HUNTERS CREEK 23.0
END DESCRIPTION:
XS GIS Cut Line= 2
      2810602.74     10021216.43      2811691.28     10021060.18
#Sta/Elev= 30
  4675.8 1668.79  4742.2 1665.78  4782.6 1661.61  4799.1 1658.86  4804.1 1659.95
  4853.3 1652.55  4869.6 1651.09  4945.2 1651.36  4974.6 1650.29  4984.7 1648.04
  5001.9 1642.35  5004.6 1641.85  5007.9 1642.35  5010.7 1644.61  5025.1 1649.95
  5095.8  1649.4  5156.8 1651.21  5176.6 1652.66  5206.9 1651.99  5338.2 1653.11
    5434 1654.92  5530.2 1658.18  5575.1 1660.86  5590.8 1662.66  5640.6 1672.83
  5645.6 1672.22  5651.4  1674.9  5671.6 1680.29  5711.1 1685.45  5775.5 1690.04
#Mann= 4 ,-1 , 0
  4675.8     .16       0  5001.9     .07       0  5007.9     .16       0
  5711.1     .16       0
Bank Sta=4974.6,5025.1
XS Rating Curve= 0 ,0
Exp/Cntr=0.3,0.1

Type RM Length L Ch R = 1 ,11552   ,289,289,289
BEGIN DESCRIPTION:
Mapping XS db106c1f
END DESCRIPTION:
XS GIS Cut Line= 4
      2810471.66     10021242.23      2810846.02     10021371.01
      2811067.64     10021403.95      2811909.15     10021595.61
#Sta/Elev= 30
    4489 1670.82  4591.4 1668.41  4661.4 1662.18  4729.2 1649.55  4760.6 1647.55
  4978.3 1647.91  4995.6 1640.51  4998.3 1640.01  5001.6 1640.51    5039  1645.8
  5068.9 1647.06  5089.6 1645.43  5106.8 1650.94    5120  1652.2    5262  1651.3
  5304.7 1648.29  5315.3 1651.73  5345.7 1654.36  5366.2 1662.28  5396.2 1666.34
  5401.4 1669.23  5487.4 1661.48  5492.5 1663.85  5530.3 1657.64  5583.7  1661.1
  5653.4 1662.53  5796.9 1672.95    5879 1681.97  5943.3 1688.93    5972 1689.67
#Mann= 4 ,-1 , 0
    4489     .16       0  4995.6     .07       0  5001.6     .16       0
    5879      .1       0
#XS Ineff= 2 , 0
                          5118.1         1652.57
Permanent Ineff=
       T       T
Bank Sta=4978.3,5039
XS Rating Curve= 0 ,0
Exp/Cntr=0.3,0.1

Type RM Length L Ch R = 1 ,11263   ,553,553,553
BEGIN DESCRIPTION:
Mapping XS 786e2b56
END DESCRIPTION:
XS GIS Cut Line= 4
      2810390.83     10021290.17      2810768.15     10021562.68
      2811052.66     10021856.18      2811328.18     10022164.64
#Sta/Elev= 30
  4451.4 1672.06  4466.5  1671.5  4581.8 1670.21  4617.4 1667.16  4632.1 1664.54
  4673.8 1648.71  4695.2 1645.68  4803.8 1645.02  4860.3 1643.22  4946.2 1644.12
  4974.3  1642.3  4999.6 1637.17  5002.3 1636.67  5005.6 1637.17  5023.9 1646.46
  5030.9 1647.47  5087.5 1647.25  5108.8 1645.64  5129.9 1645.67    5144 1642.85
  5151.2 1643.47  5158.2 1646.78  5172.3 1650.54  5236.1 1651.33  5356.3  1657.8
  5384.8 1661.73  5483.4 1680.95  5519.4 1684.46  5660.7 1694.52  5739.2 1697.66
#Mann= 5 ,-1 , 0
  4451.4      .1       0  4466.5     .16       0  4999.6     .07       0
  5005.6     .16       0  5660.7      .1       0
#XS Ineff= 2 , 0
                         5034.13         1647.59
Permanent Ineff=
       T       T
Bank Sta=4974.3,5023.9
XS Rating Curve= 0 ,0
Exp/Cntr=0.3,0.1

Type RM Length L Ch R = 1 ,10710   ,378,378,378
BEGIN DESCRIPTION:
EAST FORK HUNTERS CREEK 22.0
END DESCRIPTION:
XS GIS Cut Line= 2
      2810154.86     10021502.91      2810878.46     10022419.13
#Sta/Elev= 30
    4783 1667.47  4814.5 1667.35  4843.3 1660.36  4857.8 1658.21  4864.1 1659.13
  4872.2 1656.99  4878.6 1658.25    4893 1656.92  4899.4 1658.52  4907.5  1657.7
  4913.8  1658.3  4949.7 1645.83  4971.6  1639.5  4992.4 1633.72  4997.5 1633.26
  5000.2 1632.76  5003.5 1633.26  5013.4 1635.33  5077.3 1640.02  5099.8 1640.52
  5141.5 1643.48  5284.2 1645.06  5534.3 1645.74  5704.2 1649.23  5846.8 1654.85
  5882.1 1658.81  5895.9 1662.46  5918.1 1664.03  5946.2 1671.89  5950.5 1674.34
#Mann= 5 ,-1 , 0
    4783     .16       0  4997.5     .07       0  5003.5     .16       0
  5704.2     .05       0  5895.9      .1       0
Bank Sta=4971.6,5077.3
XS Rating Curve= 0 ,0
Exp/Cntr=0.3,0.1