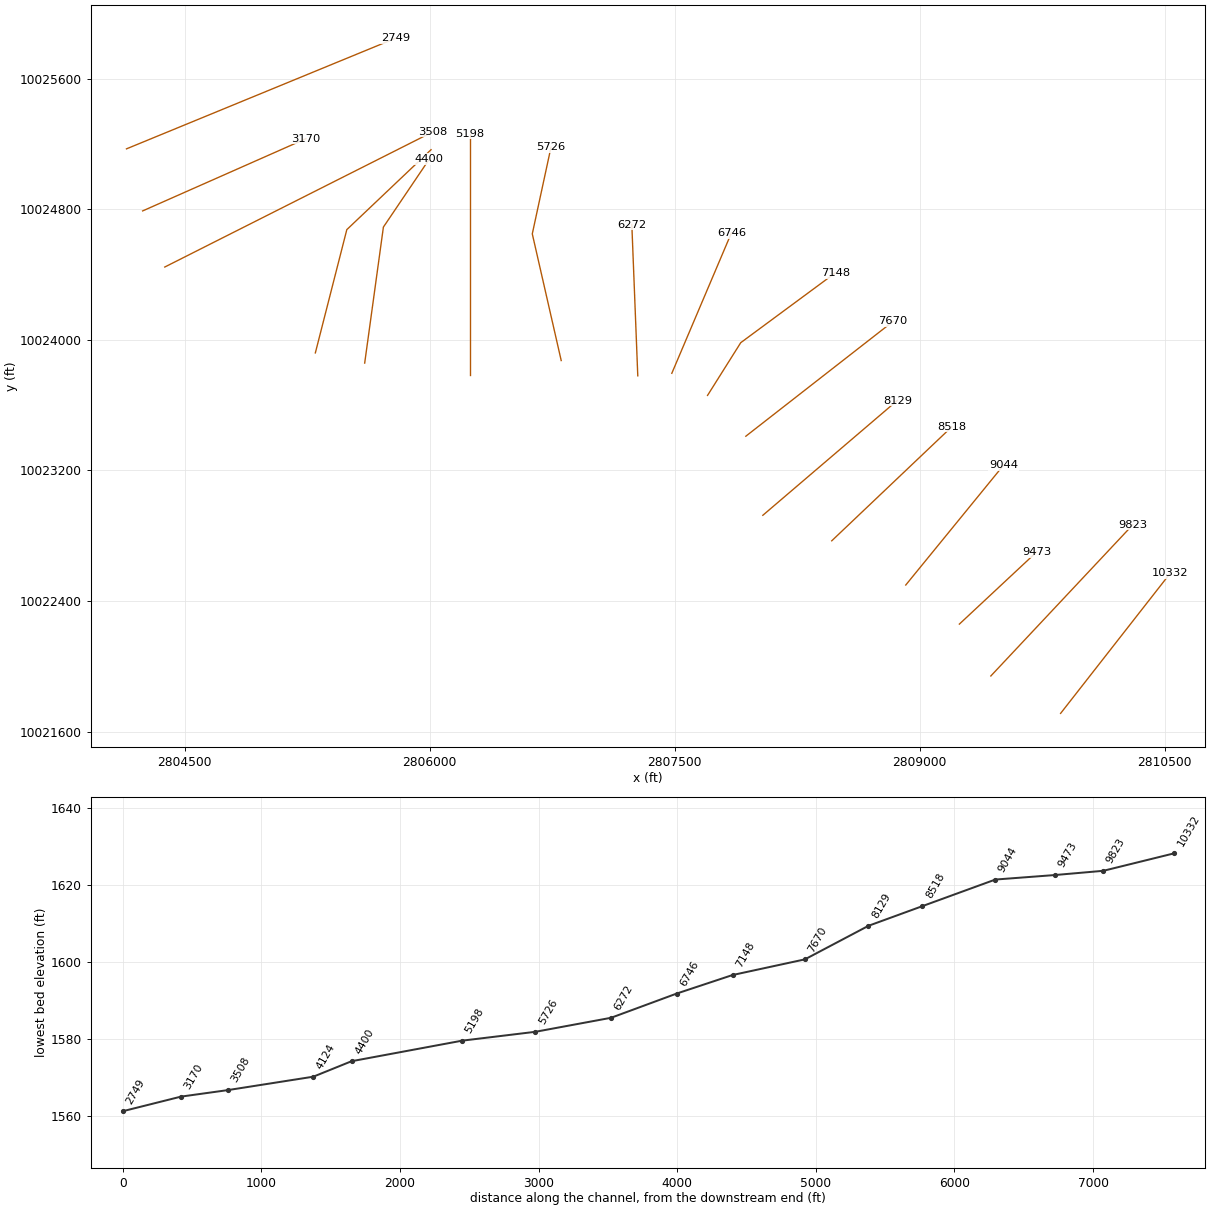
HEC-RAS study EAST FORK HUNTERS CREEK.prj: EAST FORK HUNTERS CREEK Base Level Engineering

--- EAST FORK HUNTERS CREEK.g01 (geometry) --- (continued)

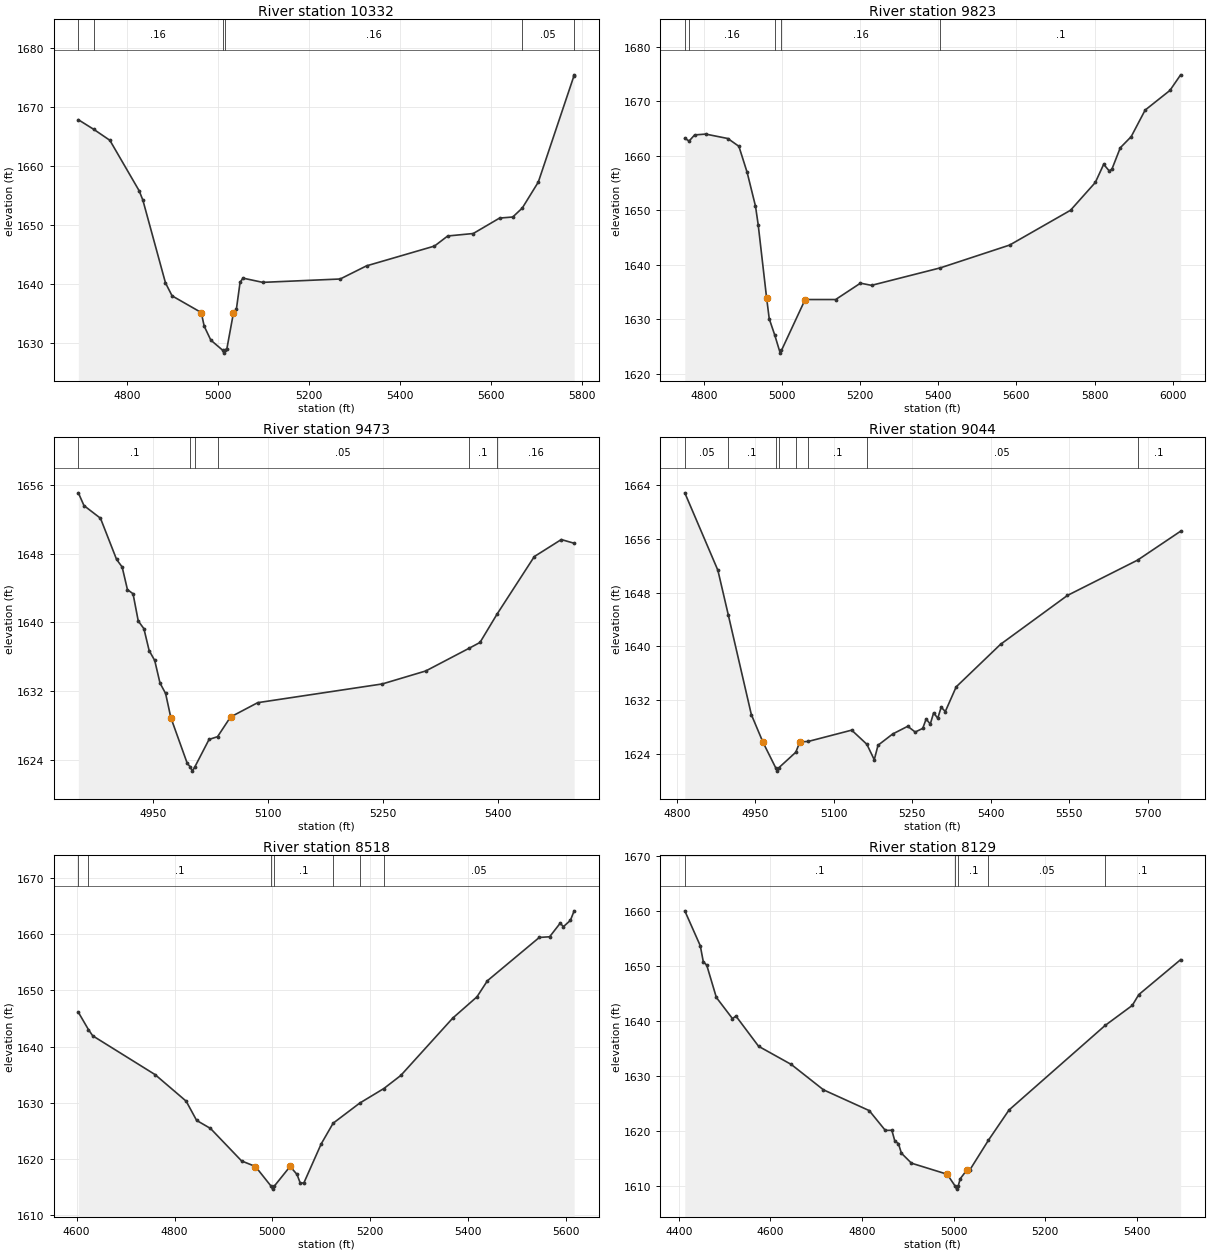
Type RM Length L Ch R = 1 ,10332   ,509,509,509
BEGIN DESCRIPTION:
EAST FORK HUNTERS CREEK 21.0
END DESCRIPTION:
XS GIS Cut Line= 2
      2809863.16      10021711.2      2810533.53     10022568.65
#Sta/Elev= 30
  4693.7 1667.91  4727.7 1666.27  4762.9 1664.42  4827.1 1655.87  4835.3 1654.28
    4885 1640.22  4899.5 1638.02  4963.5 1635.19    4970 1632.87  4984.5 1630.51
  5010.4  1628.8  5013.2  1628.3  5016.4  1628.8  5019.8 1629.06  5034.2 1635.12
  5040.6 1635.73  5048.7 1640.29    5055 1641.03  5098.4 1640.31  5268.5 1640.88
  5326.3 1643.11  5475.5 1646.47  5504.5 1648.18  5560.6  1648.6  5618.4 1651.22
  5647.3  1651.4  5668.2 1652.92  5703.4 1657.33  5781.4  1675.3  5782.1 1675.53
#Mann= 6 ,-1 , 0
  4693.7      .1       0  4727.7     .16       0  5010.4     .07       0
  5016.4     .16       0  5668.2     .05       0  5781.4     .16       0
Bank Sta=4963.5,5034.2
XS Rating Curve= 0 ,0
Exp/Cntr=0.3,0.1

Type RM Length L Ch R = 1 ,9823    ,350,350,350
BEGIN DESCRIPTION:
EAST FORK HUNTERS CREEK 20.0
END DESCRIPTION:
XS GIS Cut Line= 2
      2809436.12     10021940.41      2810304.66     10022866.16
#Sta/Elev= 30
    4751 1663.18  4762.1 1662.68  4776.2  1663.8  4804.6 1663.95  4861.2 1663.14
  4889.5 1661.71  4910.6 1656.93    4932 1650.73  4938.9 1647.33  4960.4 1633.93
  4967.2 1630.07  4981.4 1627.07  4995.3 1623.78  4998.5 1624.28  5059.1 1633.61
  5137.2 1633.61  5200.7 1636.61    5229 1636.21  5405.3 1639.42  5582.7  1643.6
  5738.5 1649.98    5802 1655.08  5823.4 1658.41  5837.6  1657.2  5844.5 1657.52
  5865.9 1661.44  5893.8 1663.48  5929.5 1668.35    5993 1671.96  6020.4 1674.82
#Mann= 5 ,-1 , 0
    4751      .1       0  4762.1     .16       0  4981.4     .07       0
  4998.5     .16       0  5405.3      .1       0
Bank Sta=4960.4,5059.1
XS Rating Curve= 0 ,0
Exp/Cntr=0.3,0.1

Type RM Length L Ch R = 1 ,9473    ,429,429,429
BEGIN DESCRIPTION:
EAST FORK HUNTERS CREEK 19.0
END DESCRIPTION:
XS GIS Cut Line= 2
      2809243.36     10022258.07      2809716.25     10022699.78
#Sta/Elev= 30
  4852.5 1655.08  4859.9 1653.59  4881.4 1652.12  4902.4 1647.33  4909.7 1646.44
  4916.6 1643.81  4923.9 1643.33  4930.7 1640.16  4938.1 1639.26  4944.9 1636.72
  4952.2 1635.56  4959.1 1632.93  4966.4 1631.72  4973.2 1628.92  4994.7 1623.57
  4998.6 1623.18  5001.3 1622.68  5004.6 1623.18  5023.1 1626.37  5034.2 1626.69
  5051.1 1628.98  5086.6 1630.65  5249.2 1632.83  5305.9 1634.34  5362.2 1636.97
  5376.7 1637.66  5398.7 1640.92  5447.6 1647.66  5482.8 1649.64  5499.6 1649.21
#Mann= 6 ,-1 , 0
  4852.5      .1       0  4998.6     .07       0  5004.6      .1       0
  5034.2     .05       0  5362.2      .1       0  5398.7     .16       0
Bank Sta=4973.2,5051.1
XS Rating Curve= 0 ,0
Exp/Cntr=0.3,0.1

Type RM Length L Ch R = 1 ,9044    ,526,526,526
BEGIN DESCRIPTION:
EAST FORK HUNTERS CREEK 18.0
END DESCRIPTION:
XS GIS Cut Line= 2
      2808915.25     10022497.67      2809513.86     10023231.62
#Sta/Elev= 30
  4815.4 1662.79  4878.6  1651.3  4898.4 1644.71  4942.5  1629.9  4964.8 1625.78
    4989 1622.01  4991.8 1621.51    4995 1622.01  5027.4 1624.31  5035.1 1625.83
  5051.5 1625.92  5134.2 1627.59  5163.2 1625.49  5177.3  1623.2  5184.5 1625.35
  5212.5 1627.02  5241.2 1628.16  5255.5 1627.31  5269.9 1627.85  5276.4 1629.24
  5284.3 1628.49  5290.7 1630.16  5298.6 1629.35  5305.1    1631    5313 1630.35
  5333.8 1634.01  5418.5 1640.32  5546.3 1647.57  5680.3 1652.81  5762.5  1657.1
#Mann= 8 ,-1 , 0
  4815.4     .05       0  4898.4      .1       0    4989     .07       0
    4995      .1       0  5027.4     .16       0  5051.5      .1       0
  5163.2     .05       0  5680.3      .1       0
Bank Sta=4964.8,5035.1
XS Rating Curve= 0 ,0
Exp/Cntr=0.3,0.1

Type RM Length L Ch R = 1 ,8518    ,389,389,389
BEGIN DESCRIPTION:
EAST FORK HUNTERS CREEK 17.0
END DESCRIPTION:
XS GIS Cut Line= 2
      2808462.13     10022768.51      2809196.49     10023466.42
#Sta/Elev= 30
  4603.5 1646.12  4624.2 1643.02  4632.9 1641.92  4760.3 1635.01  4823.8 1630.28
  4845.2 1626.85  4873.5 1625.42  4937.1 1619.63  4965.4 1618.64  4997.6 1615.11
  5000.3 1614.61  5003.6 1615.11  5036.2 1618.65  5050.3 1617.23  5057.2 1615.63
  5064.5 1615.75  5099.7 1622.66  5124.1 1626.35  5178.4 1629.93  5227.8 1632.53
  5262.3 1634.85  5368.6 1645.08    5418 1648.86  5439.4 1651.73  5545.4 1659.44
  5566.5 1659.56  5587.9 1661.96  5594.8 1661.37  5608.9 1662.48  5616.6 1664.18
#Mann= 7 ,-1 , 0
  4603.5     .05       0  4624.2      .1       0  4997.6     .07       0
  5003.6      .1       0  5124.1     .05       0  5178.4      .1       0
  5227.8     .05       0
Bank Sta=4965.4,5036.2
XS Rating Curve= 0 ,0
Exp/Cntr=0.3,0.1

Type RM Length L Ch R = 1 ,8129    ,459,459,459
BEGIN DESCRIPTION:
EAST FORK HUNTERS CREEK 16.0
END DESCRIPTION:
XS GIS Cut Line= 2
      2808040.23     10022924.73      2808863.15     10023627.86
#Sta/Elev= 30
  4413.1    1660  4446.9 1653.66  4453.4  1650.8  4461.1 1650.11    4482 1644.28
  4517.1 1640.45  4524.8  1640.9  4574.2 1635.42  4645.6 1632.12  4715.8 1627.52
  4815.7 1623.75  4850.9 1620.15  4865.1 1620.18  4871.7  1618.2  4879.4 1617.77
    4886 1616.02  4907.9 1614.21  4985.9  1612.2  5003.7    1610  5006.5  1609.5
  5009.7    1610  5014.4 1611.39  5028.7 1612.95  5035.3 1612.98    5076 1618.38
  5120.9 1623.86  5330.7  1639.2  5389.9 1642.83  5404.2  1644.8  5495.5 1651.14
#Mann= 5 ,-1 , 0
  4413.1      .1       0  5003.7     .07       0  5009.7      .1       0
    5076     .05       0  5330.7      .1       0
Bank Sta=4985.9,5028.7
XS Rating Curve= 0 ,0
Exp/Cntr=0.3,0.1

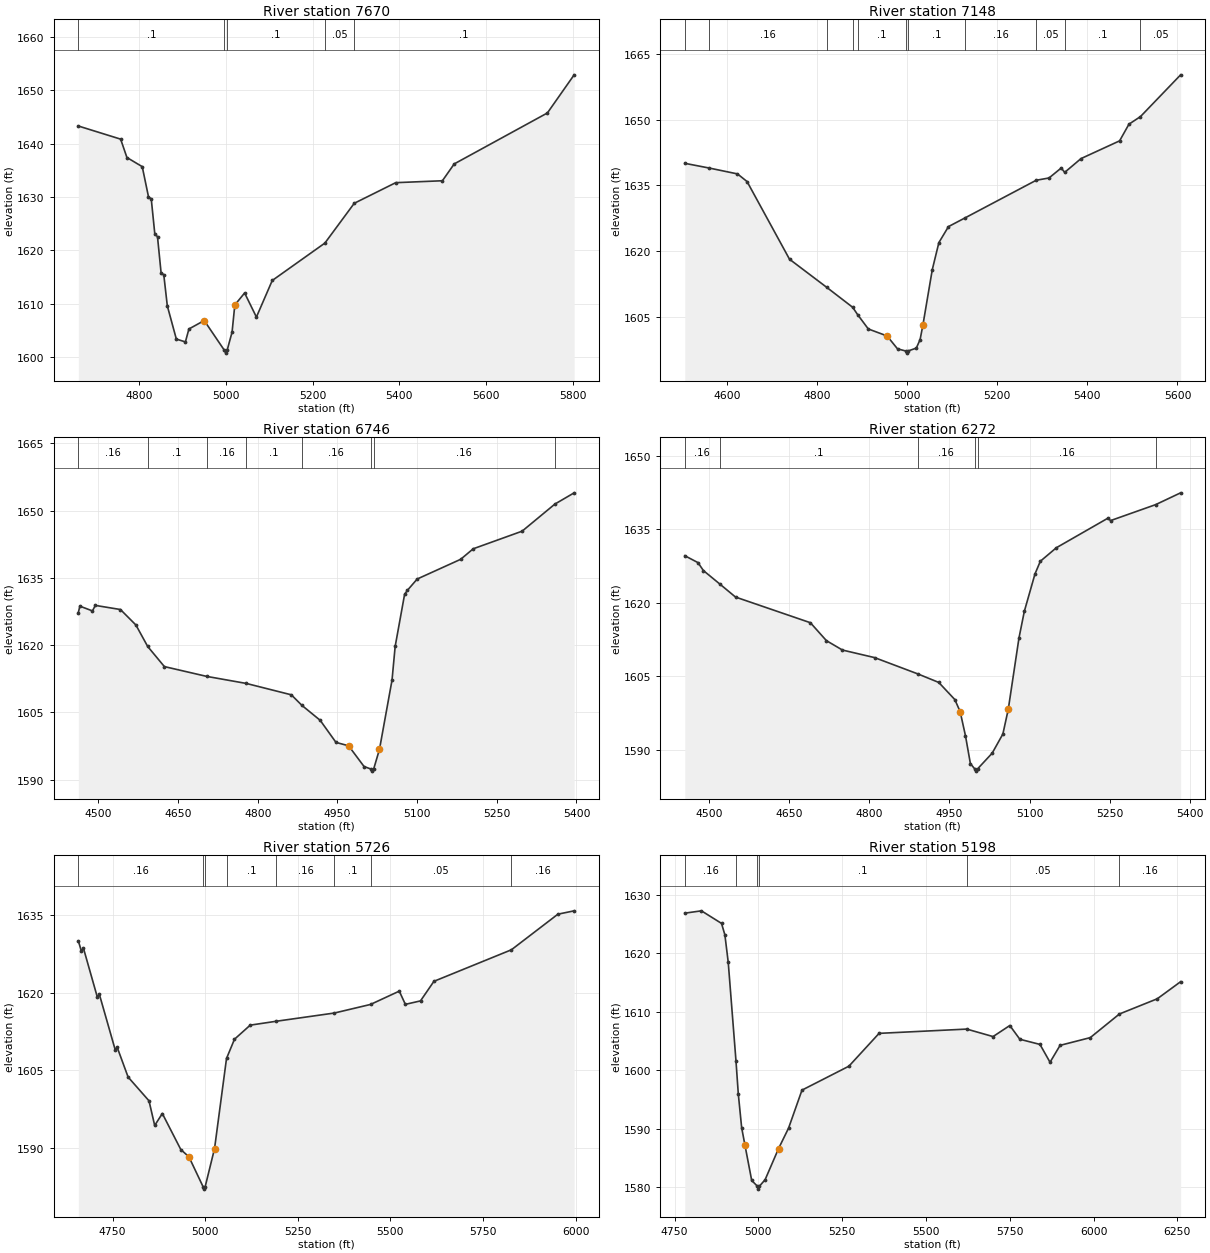
Type RM Length L Ch R = 1 ,7670    ,522,522,522
BEGIN DESCRIPTION:
EAST FORK HUNTERS CREEK 15.0
END DESCRIPTION:
XS GIS Cut Line= 2
       2807936.1     10023409.14      2808837.13     10024112.26
#Sta/Elev= 30
    4660  1643.3  4757.5 1640.84    4772  1637.4  4807.3 1635.69  4821.7 1630.06
  4828.1 1629.64  4836.2 1623.17  4842.5 1622.55  4850.7 1615.86    4857 1615.43
  4865.1 1609.63  4885.9 1603.41  4906.8 1602.88  4914.9  1605.3  4950.2 1606.88
  4996.9 1601.28  4999.7 1600.78  5002.9 1601.28  5014.4 1604.72  5020.7  1609.8
  5043.3 1612.04  5070.5 1607.53    5107 1614.38  5228.3 1621.38    5296 1628.83
  5391.6 1632.69  5499.2 1633.05  5526.4  1636.2  5741.2 1645.74  5802.9 1652.88
#Mann= 5 ,-1 , 0
    4660      .1       0  4996.9     .07       0  5002.9      .1       0
  5228.3     .05       0    5296      .1       0
Bank Sta=4950.2,5020.7
XS Rating Curve= 0 ,0
Exp/Cntr=0.3,0.1

Type RM Length L Ch R = 1 ,7148    ,402,402,402
BEGIN DESCRIPTION:
EAST FORK HUNTERS CREEK 14.0
END DESCRIPTION:
XS GIS Cut Line= 3
       2807701.7     10023659.11      2807904.84     10023982.05
      2808482.73     10024408.96
#Sta/Elev= 30
    4507 1640.06  4561.7 1638.97  4623.9 1637.64  4645.1  1635.9  4739.3 1618.16
  4821.8 1611.74  4879.4 1607.18  4890.5 1605.49  4914.1 1602.23  4955.8 1600.63
  4978.9 1597.69  4996.7 1597.21  4999.5 1596.71  5002.7 1597.21  5020.6 1597.86
    5029  1599.8  5035.2 1603.09  5056.1  1615.8  5070.7 1621.96    5092 1625.61
  5128.8  1627.6  5286.6 1636.19    5315 1636.71  5342.1 1638.99  5349.8 1637.99
    5386 1641.14  5471.6 1645.19  5492.4    1649  5517.9 1650.73    5607 1660.27
#Mann= 11 ,-1 , 0
    4507      .1       0  4561.7     .16       0  4821.8      .1       0
  4879.4     .16       0  4890.5      .1       0  4996.7     .07       0
  5002.7      .1       0  5128.8     .16       0  5286.6     .05       0
  5349.8      .1       0  5517.9     .05       0
Bank Sta=4955.8,5035.2
XS Rating Curve= 0 ,0
Exp/Cntr=0.3,0.1

Type RM Length L Ch R = 1 ,6746    ,474,474,474
BEGIN DESCRIPTION:
EAST FORK HUNTERS CREEK 13.0
END DESCRIPTION:
XS GIS Cut Line= 2
      2807482.97     10023794.57      2807847.55     10024653.94
#Sta/Elev= 30
  4462.2 1627.26  4465.1 1628.68  4488.8 1627.62  4494.2 1628.85  4541.5 1627.93
  4570.6 1624.48  4592.8 1619.69  4624.2 1615.21  4703.7 1613.03  4778.6 1611.45
  4863.2 1608.92  4883.2 1606.56  4917.5 1603.24  4947.3 1598.31    4971 1597.56
  5000.1 1592.94  5012.3 1592.41    5015 1591.91  5018.3 1592.41  5029.2 1596.78
  5052.8  1612.2  5058.7  1619.7  5076.5 1631.33  5081.9 1632.23  5100.2 1634.73
    5182 1639.12  5205.7 1641.47  5297.7 1645.39  5359.4 1651.43  5395.7 1653.94
#Mann= 8 ,-1 , 0
  4462.2     .16       0  4592.8      .1       0  4703.7     .16       0
  4778.6      .1       0  4883.2     .16       0  5012.3     .07       0
  5018.3     .16       0  5359.4     .05       0
Bank Sta=4971,5029.2
XS Rating Curve= 0 ,0
Exp/Cntr=0.3,0.1

Type RM Length L Ch R = 1 ,6272    ,546,546,546
BEGIN DESCRIPTION:
EAST FORK HUNTERS CREEK 12.0
END DESCRIPTION:
XS GIS Cut Line= 2
      2807274.63     10023778.94      2807238.17     10024706.03
#Sta/Elev= 30
  4454.7 1629.59  4479.4 1628.18  4489.5 1626.56  4520.1 1623.82  4549.6 1621.15
  4689.7 1615.91  4719.7 1612.25  4749.7 1610.33  4809.8 1608.79  4890.5 1605.47
  4929.9 1603.72  4959.9 1600.23  4969.9 1597.78  4979.9 1592.83  4989.1 1587.15
  4996.9 1586.11  4999.7 1585.61  5002.9 1586.11  5029.9 1589.28  5049.9 1593.19
    5060 1598.24    5080 1612.78    5090 1618.22    5110 1625.88    5120 1628.46
    5150 1631.22  5246.4 1637.25  5251.4 1636.76  5335.8 1640.02  5382.5 1642.43
#Mann= 6 ,-1 , 0
  4454.7     .16       0  4520.1      .1       0  4890.5     .16       0
  4996.9     .07       0  5002.9     .16       0  5335.8     .05       0
Bank Sta=4969.9,5060
XS Rating Curve= 0 ,0
Exp/Cntr=0.3,0.1

Type RM Length L Ch R = 1 ,5726    ,528,528,528
BEGIN DESCRIPTION:
EAST FORK HUNTERS CREEK 11.0
END DESCRIPTION:
XS GIS Cut Line= 3
      2806805.88     10023872.66       2806628.8     10024648.72
      2806743.24     10025179.31
#Sta/Elev= 30
  4657.3 1630.05  4665.8 1628.04    4671 1628.68  4708.8 1619.12    4714 1619.73
  4756.9 1608.95  4762.1 1609.47  4791.7 1603.68  4848.1 1599.08  4863.5  1594.3
  4884.1 1596.62    4934 1589.64  4955.9 1588.23  4993.9 1582.47  4996.6 1581.97
  4999.9 1582.47  5025.1 1589.83  5057.4 1607.28  5078.9 1611.01  5121.4 1613.74
  5192.2  1614.5  5348.7 1616.09  5446.2 1617.75  5523.9 1620.33  5540.3 1617.77
  5581.2 1618.44  5617.4 1622.23  5826.6 1628.34  5952.2 1635.24  5996.1 1635.89
#Mann= 8 ,-1 , 0
  4657.3     .16       0  4993.9     .07       0  4999.9     .16       0
  5057.4      .1       0  5192.2     .16       0  5348.7      .1       0
  5446.2     .05       0  5826.6     .16       0
Bank Sta=4955.9,5025.1
XS Rating Curve= 0 ,0
Exp/Cntr=0.3,0.1

Type RM Length L Ch R = 1 ,5198    ,798,798,798
BEGIN DESCRIPTION:
EAST FORK HUNTERS CREEK 10.0
END DESCRIPTION:
XS GIS Cut Line= 2
      2806248.59     10023784.14      2806248.59     10025263.34
#Sta/Elev= 30
  4780.6 1626.83  4830.2 1627.23  4890.2 1625.08  4900.2 1623.12  4910.2 1618.42
  4933.2 1601.65  4940.2 1595.94  4950.2 1590.18  4960.2 1587.14  4980.2 1581.15
  4997.2 1580.17  4999.9 1579.67  5003.2 1580.17  5020.2 1581.28  5060.2 1586.59
  5090.2  1590.1  5130.2 1596.59  5270.2 1600.68  5360.2 1606.29  5621.8 1607.02
  5700.2 1605.74  5750.2 1607.63  5780.2 1605.28  5840.2  1604.4  5870.2 1601.35
  5900.2 1604.24  5990.2 1605.56  6077.2  1609.6  6190.2  1612.2  6259.8 1615.12
#Mann= 6 ,-1 , 0
  4780.6     .16       0  4933.2      .1       0  4997.2     .07       0
  5003.2      .1       0  5621.8     .05       0  6077.2     .16       0
Bank Sta=4960.2,5060.2
XS Rating Curve= 0 ,0
Exp/Cntr=0.3,0.1

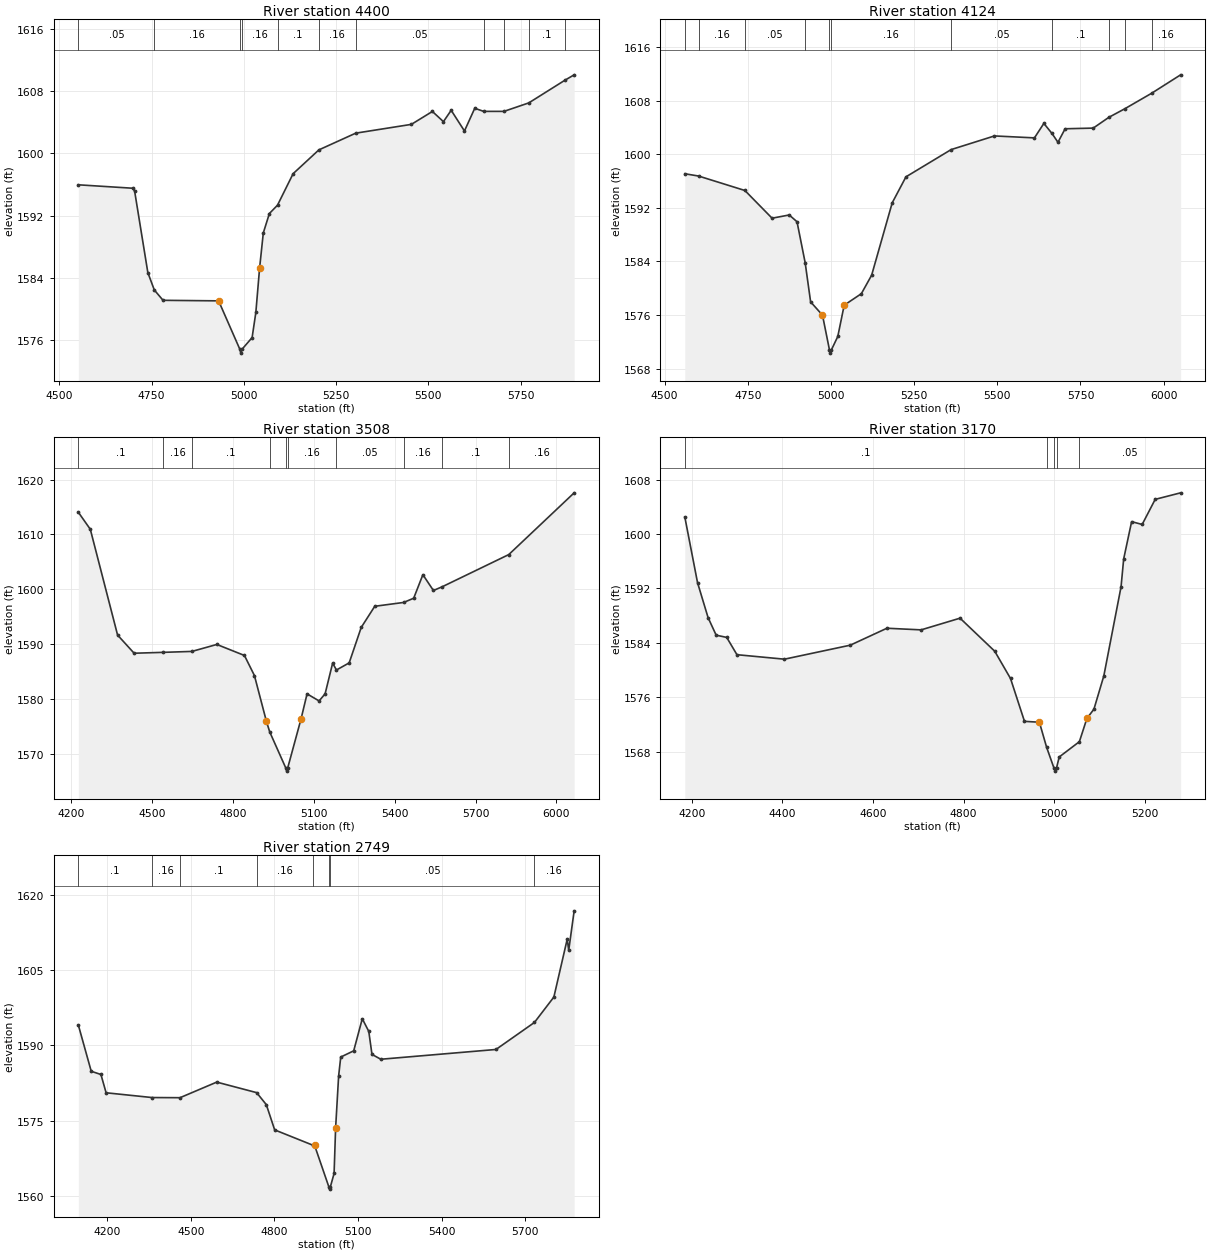
Type RM Length L Ch R = 1 ,4400    ,276,276,276
BEGIN DESCRIPTION:
EAST FORK HUNTERS CREEK 9.0
END DESCRIPTION:
XS GIS Cut Line= 3
      2805602.76     10023857.09      2805717.34     10024690.38
      2805998.56     10025107.02
#Sta/Elev= 30
  4551.6 1595.97  4699.1 1595.53  4704.1 1595.18    4740 1584.68  4757.5 1582.45
  4781.2 1581.12  4931.8 1581.05  4989.3 1574.83    4992 1574.33  4995.3 1574.83
  5022.6 1576.33  5032.7 1579.56  5042.8 1585.23  5052.9 1589.78  5069.4 1592.28
  5091.4 1593.35  5133.7  1597.4  5203.5 1600.46  5303.4 1602.61  5454.2 1603.74
  5511.2  1605.4  5541.1 1604.09  5562.1 1605.55  5598.1 1602.89    5626 1605.81
  5650.2 1605.41  5705.1 1605.41  5772.4  1606.5  5870.8 1609.43  5895.4 1610.11
#Mann= 11 ,-1 , 0
  4551.6     .05       0  4757.5     .16       0  4989.3     .07       0
  4995.3     .16       0  5091.4      .1       0  5203.5     .16       0
  5303.4     .05       0  5650.2      .1       0  5705.1     .05       0
  5772.4      .1       0  5870.8     .16       0
Bank Sta=4931.8,5042.8
XS Rating Curve= 0 ,0
Exp/Cntr=0.3,0.1

Type RM Length L Ch R = 1 ,4124    ,616,616,616
BEGIN DESCRIPTION:
EAST FORK HUNTERS CREEK 8.0
END DESCRIPTION:
XS GIS Cut Line= 3
      2805300.67     10023919.55      2805493.38     10024674.76
      2806008.97     10025164.31
#Sta/Elev= 30
  4560.6 1597.11  4601.9 1596.77  4741.2 1594.61  4822.9 1590.47  4874.5 1590.95
  4897.9 1589.94  4922.4 1583.82  4938.8 1577.97  4974.5 1575.98  4995.4 1570.81
  4998.1 1570.31  5001.4 1570.81  5020.5  1572.8  5039.7 1577.47  5091.3 1579.19
  5122.2 1581.95  5184.1 1592.77  5225.4 1596.65  5361.2 1600.72  5491.4 1602.76
  5611.6 1602.47  5639.9 1604.63  5664.3 1603.13  5682.3 1601.81  5703.8 1603.83
  5788.3 1603.93  5835.6 1605.55  5883.9 1606.84  5963.6 1609.13    6051 1611.89
#Mann= 11 ,-1 , 0
  4560.6      .1       0  4601.9     .16       0  4741.2     .05       0
  4922.4     .16       0  4995.4     .07       0  5001.4     .16       0
  5361.2     .05       0  5664.3      .1       0  5835.6     .05       0
  5883.9      .1       0  5963.6     .16       0
Bank Sta=4974.5,5039.7
XS Rating Curve= 0 ,0
Exp/Cntr=0.3,0.1

Type RM Length L Ch R = 1 ,3508    ,338,338,338
BEGIN DESCRIPTION:
EAST FORK HUNTERS CREEK 7.0
END DESCRIPTION:
XS GIS Cut Line= 2
      2804378.79     10024445.59      2806019.43     10025273.72
#Sta/Elev= 30
  4227.7 1614.04  4272.1 1610.93  4373.2 1591.64  4434.5 1588.33  4542.3 1588.49
  4648.7 1588.66  4741.1 1589.93  4843.4 1587.92  4880.4 1584.26    4925 1575.88
  4937.2 1573.97  4997.3 1567.33    5000 1566.83  5003.3 1567.33  5053.2 1576.35
  5075.5 1580.92  5120.1 1579.63  5142.4 1580.93  5170.3 1586.53  5184.4 1585.27
  5231.6 1586.57  5276.2 1593.03  5326.4 1596.89  5433.5 1597.59  5470.7 1598.36
  5504.8 1602.65  5543.8 1599.77  5576.8 1600.46  5823.2 1606.32  6065.5 1617.58
#Mann= 10 ,-1 , 0
  4227.7      .1       0  4542.3     .16       0  4648.7      .1       0
  4937.2     .16       0  4997.3     .07       0  5003.3     .16       0
  5184.4     .05       0  5433.5     .16       0  5576.8      .1       0
  5823.2     .16       0
Bank Sta=4925,5053.2
XS Rating Curve= 0 ,0
Exp/Cntr=0.3,0.1

Type RM Length L Ch R = 1 ,3170    ,421,421,421
BEGIN DESCRIPTION:
EAST FORK HUNTERS CREEK 6.0
END DESCRIPTION:
XS GIS Cut Line= 2
      2804243.35     10024789.33      2805243.34     10025232.03
#Sta/Elev= 30
  4184.9 1602.52    4213 1592.85  4236.3  1587.7  4254.1 1585.13  4277.4  1584.8
  4299.9 1582.26  4404.7  1581.6  4549.9 1583.66  4630.7 1586.15  4706.1 1585.91
    4792 1587.63  4868.5 1582.77  4903.3 1578.76  4934.1 1572.46    4967 1572.33
    4983 1568.63  4998.9 1565.64  5001.7 1565.14  5004.9 1565.64  5010.7 1567.22
  5055.2 1569.47  5071.8 1572.89  5087.3 1574.25  5109.1 1579.14  5147.1 1592.24
  5152.9 1596.34  5170.4 1601.82  5193.7 1601.41  5222.4  1605.1  5278.5 1606.06
#Mann= 5 ,-1 , 0
  4184.9      .1       0    4983     .16       0  4998.9     .07       0
  5004.9     .16       0  5055.2     .05       0
Bank Sta=4967,5071.8
XS Rating Curve= 0 ,0
Exp/Cntr=0.3,0.1

Type RM Length L Ch R = 1 ,2749    ,489,489,489
BEGIN DESCRIPTION:
EAST FORK HUNTERS CREEK 5.0
END DESCRIPTION:
XS GIS Cut Line= 2
       2804144.4     10025169.54      2805790.27     10025846.64
#Sta/Elev= 30
  4096.3 1594.08  4142.6 1584.85  4177.4 1584.21    4196 1580.56  4360.9 1579.61
  4461.3 1579.58  4593.1 1582.69  4736.3 1580.59  4771.1 1578.19    4801 1573.16
  4939.6 1570.07  4944.1  1570.1  4995.2 1561.84  4997.9 1561.34  5001.2 1561.84
  5014.3 1564.47  5019.8 1573.55  5030.6 1583.91  5038.2 1587.69  5084.7 1588.93
  5115.5 1595.33  5138.8 1592.81  5150.3 1588.22    5182 1587.25  5595.3  1589.2
  5733.4 1594.59  5803.2 1599.66  5851.1 1611.21  5856.5    1609    5876 1616.86
#Mann= 8 ,-1 , 0
  4096.3      .1       0  4360.9     .16       0  4461.3      .1       0
  4736.3     .16       0  4939.6     .05       0  4995.2     .04       0
  5001.2     .05       0  5733.4     .16       0
Bank Sta=4944.1,5019.8
XS Rating Curve= 0 ,0
Exp/Cntr=0.3,0.1