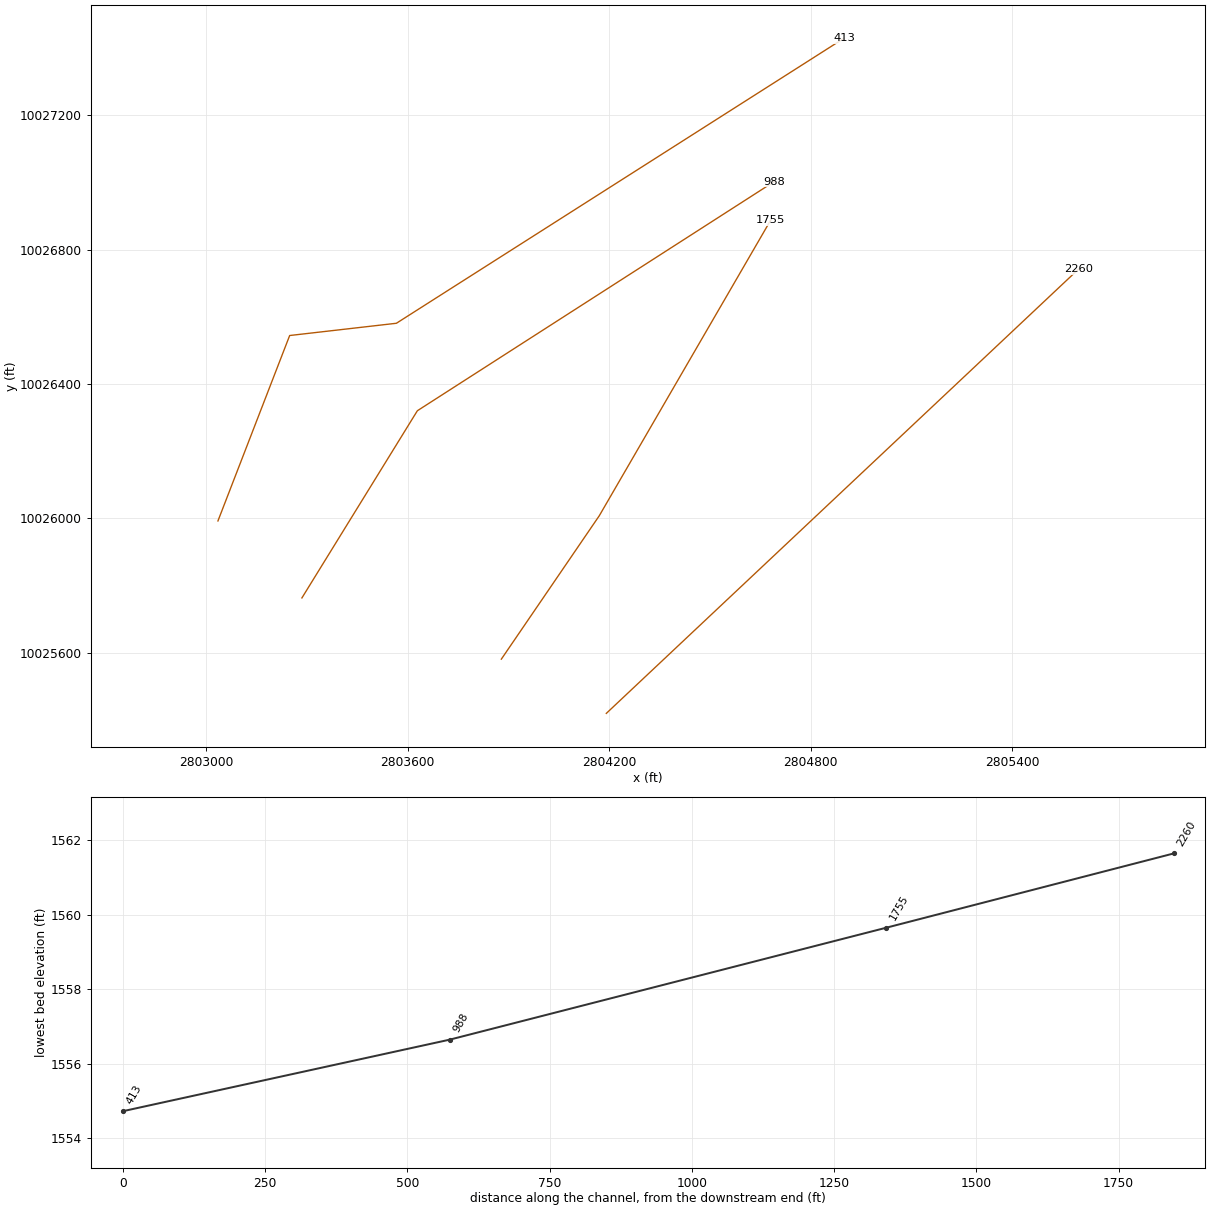
HEC-RAS study EAST FORK HUNTERS CREEK.prj: EAST FORK HUNTERS CREEK Base Level Engineering

--- EAST FORK HUNTERS CREEK.g01 (geometry) --- (continued)

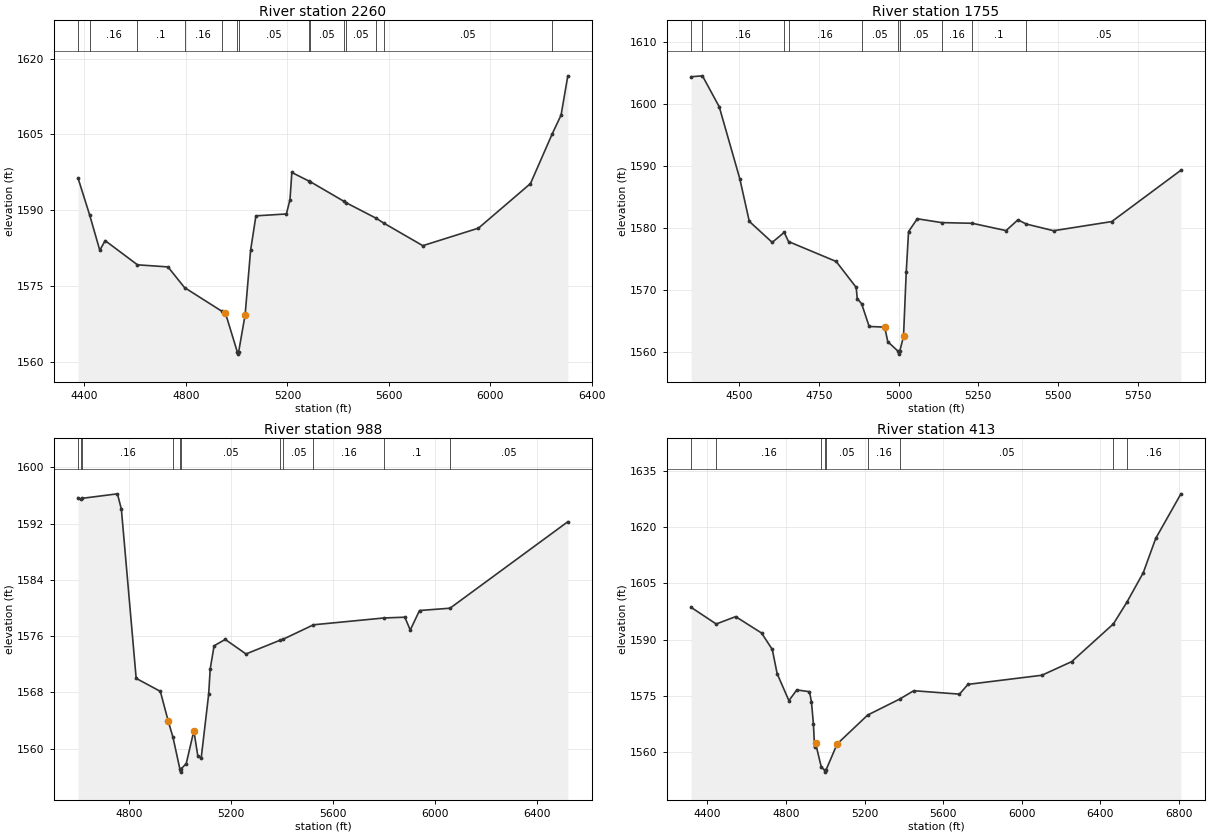
Type RM Length L Ch R = 1 ,2260    ,505,505,505
BEGIN DESCRIPTION:
EAST FORK HUNTERS CREEK 4.0
END DESCRIPTION:
XS GIS Cut Line= 2
      2804191.32     10025419.57      2805597.56     10026742.48
#Sta/Elev= 30
  4374.6  1596.4  4420.9 1589.03  4460.4 1582.14  4481.5 1584.05    4609 1579.27
  4729.1 1578.86  4794.4 1574.78  4942.3 1570.08  4955.7 1569.75    5002 1562.14
  5004.8 1561.64    5008 1562.14  5033.3 1569.42  5054.8  1582.1  5075.8 1588.94
    5196 1589.31  5210.2 1592.16  5217.4  1597.5  5284.5 1595.81  5290.1 1595.68
  5423.7 1591.78  5431.7 1591.52  5550.4 1588.45  5579.3 1587.52  5733.7 1583.05
    5953 1586.51  6158.1 1595.31  6244.4 1605.19  6278.7 1608.82  6305.3 1616.58
#Mann= 14 ,-1 , 0
  4374.6      .1       0  4420.9     .16       0    4609      .1       0
  4794.4     .16       0  4942.3     .05       0    5002     .04       0
    5008     .05       0  5284.5      .1       0  5290.1     .05       0
  5423.7      .1       0  5431.7     .05       0  5550.4      .1       0
  5579.3     .05       0  6244.4     .16       0
Bank Sta=4955.7,5033.3
XS Rating Curve= 0 ,0
Exp/Cntr=0.3,0.1

Type RM Length L Ch R = 1 ,1755    ,767,767,767
BEGIN DESCRIPTION:
EAST FORK HUNTERS CREEK 3.0
END DESCRIPTION:
XS GIS Cut Line= 3
      2803878.82     10025581.04      2804170.46     10026008.09
      2804680.87     10026888.28
#Sta/Elev= 30
  4350.1  1604.4  4385.5 1604.55  4438.1 1599.56  4502.5 1587.96  4532.3 1581.07
  4604.1 1577.68  4641.7 1579.29  4655.2 1577.81  4804.5  1574.6  4867.2 1570.42
  4870.6 1568.59  4884.2 1567.79  4907.9 1564.11  4956.7 1564.01  4966.2 1561.65
  4997.9 1560.15  5000.7 1559.65  5003.9 1560.15  5015.5  1562.5    5024 1572.85
  5031.3 1579.42  5058.7 1581.49  5134.9 1580.87  5230.9 1580.76  5336.8 1579.58
  5374.1 1581.32  5399.9 1580.64  5485.9 1579.56  5668.1 1581.04  5884.7 1589.32
#Mann= 10 ,-1 , 0
  4350.1      .1       0  4385.5     .16       0  4641.7      .1       0
  4655.2     .16       0  4884.2     .05       0  4997.9     .04       0
  5003.9     .05       0  5134.9     .16       0  5230.9      .1       0
  5399.9     .05       0
Bank Sta=4956.7,5015.5
XS Rating Curve= 0 ,0
Exp/Cntr=0.3,0.1

Type RM Length L Ch R = 1 ,988     ,575,575,575
BEGIN DESCRIPTION:
EAST FORK HUNTERS CREEK 2.0
END DESCRIPTION:
XS GIS Cut Line= 3
      2803285.04     10025763.29       2803628.8     10026320.59
      2804691.29     10027002.88
#Sta/Elev= 30
  4601.2 1595.69  4613.4 1595.49  4617.2  1595.6  4755.5 1596.24  4770.9 1594.05
  4828.8 1569.99  4923.4 1568.14  4954.2 1563.92  4972.8 1561.62  4999.6 1557.15
  5002.4 1556.65  5005.6 1557.15  5024.7 1557.85  5054.7 1562.53  5070.1 1558.97
  5083.4 1558.66  5112.7 1567.75  5118.7 1571.35  5133.9 1574.62  5177.4 1575.53
  5258.8 1573.46  5391.8 1575.41    5405 1575.57    5523 1577.61    5799 1578.58
  5880.7 1578.69  5901.8 1576.86  5938.1 1579.64  6057.6 1579.97  6518.7 1592.27
#Mann= 11 ,-1 , 0
  4601.2     .16       0  4613.4      .1       0  4617.2     .16       0
  4972.8     .05       0  4999.6     .04       0  5005.6     .05       0
  5391.8     .16       0    5405     .05       0    5523     .16       0
    5799      .1       0  6057.6     .05       0
Bank Sta=4954.2,5054.7
XS Rating Curve= 0 ,0
Exp/Cntr=0.3,0.1

Type RM Length L Ch R = 1 ,413     ,0,0,0
BEGIN DESCRIPTION:
EAST FORK HUNTERS CREEK 1.0
END DESCRIPTION:
XS GIS Cut Line= 4
      2803035.06      10025992.5      2803248.59     10026544.55
       2803566.3     10026581.01      2804898.65     10027429.34
#Sta/Elev= 30
  4318.1 1598.61  4445.5 1594.18  4544.6 1596.14  4676.3 1591.78  4730.9 1587.39
  4755.4 1580.98  4815.3 1573.77  4855.5 1576.62  4919.9 1576.15    4930 1573.49
  4940.1 1567.55  4945.9 1561.39  4950.9 1562.44    4980  1556.1  4997.5 1555.23
  5000.2 1554.73  5003.5 1555.23  5060.9 1562.24    5216 1569.93    5380 1574.22
  5450.3 1576.41  5682.9  1575.5  5726.3  1578.1  6102.2 1580.53  6253.7 1584.16
  6465.9 1594.21  6534.5 1599.99  6617.7 1607.83  6681.2 1616.98  6809.3 1628.84
#Mann= 9 ,-1 , 0
  4318.1      .1       0  4445.5     .16       0    4980     .05       0
  4997.5     .04       0  5003.5     .05       0    5216     .16       0
    5380     .05       0  6465.9      .1       0  6534.5     .16       0
Bank Sta=4950.9,5060.9
XS Rating Curve= 0 ,0
Exp/Cntr=0.3,0.1

Chan Stop Cuts=-1
Use User Specified Reach Order=0
Composite Channel Slope=5