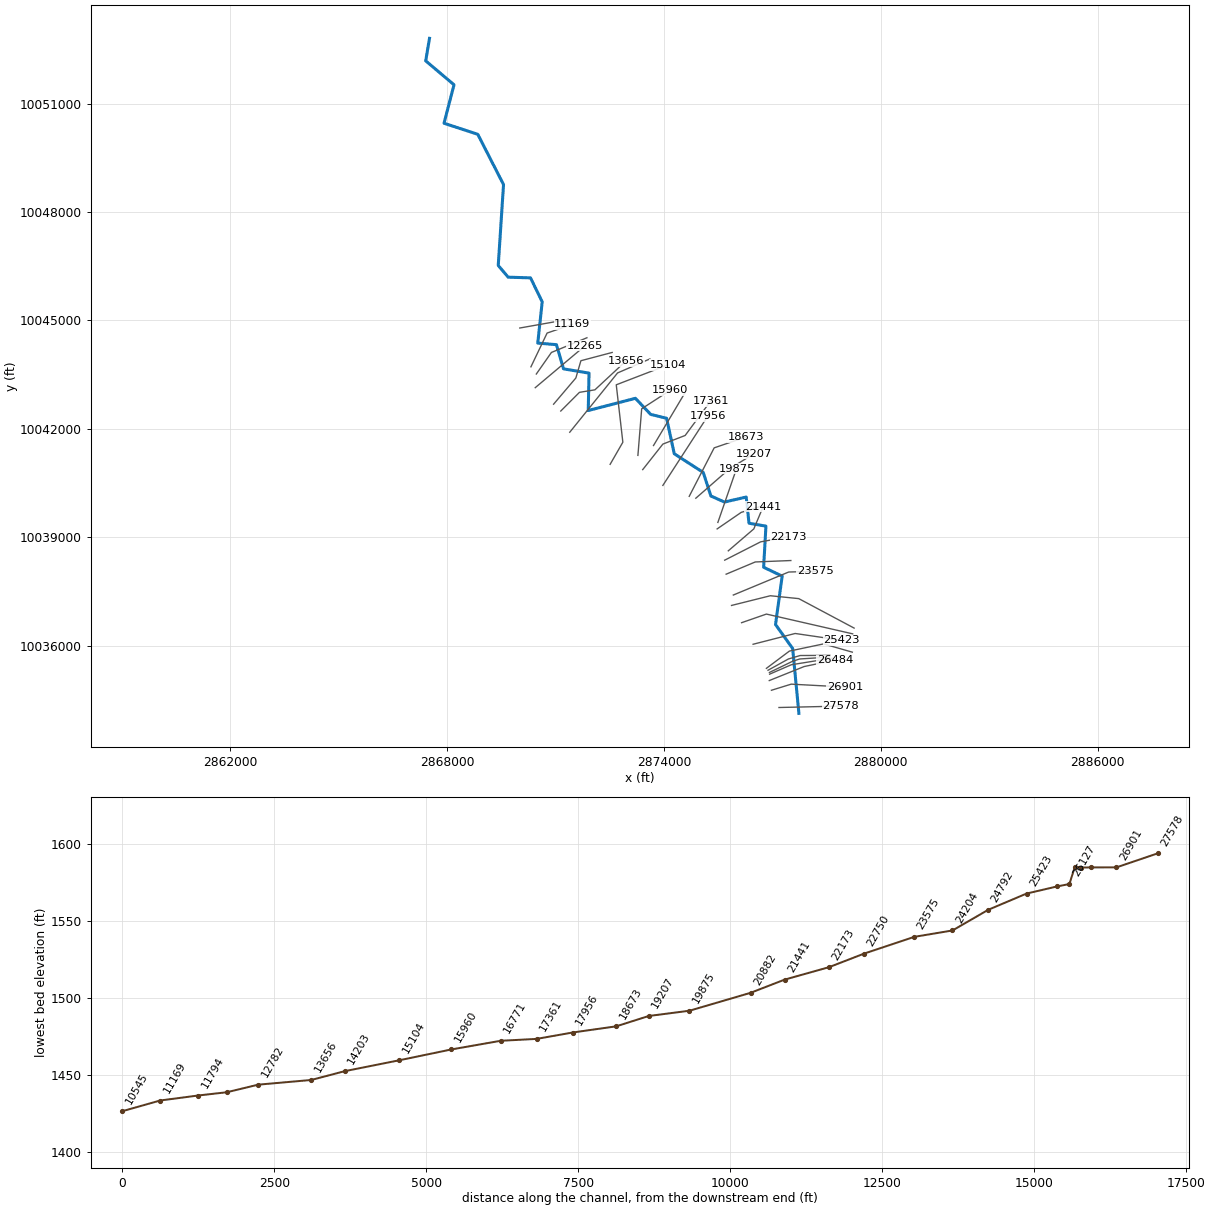
--- EAST FORK ROCKY CREEK.prj (project) ---

Proj Title=EAST FORK ROCKY CREEK Base Level Engineering
Current Plan=p01
Default Exp/Contr=0.3,0.1
English Units
Geom File=g01
Flow File=f01
Plan File=p01
Y Axis Title=Elevation
X Axis Title(PF)=Main Channel Distance
X Axis Title(XS)=Station
BEGIN DESCRIPTION:
EAST FORK ROCKY CREEK
END DESCRIPTION:
DSS Export Rating Curves= 0
DSS Export Rating Curve Sorted= 0
DSS Export Volume Flow Curves= 0
DXF OffsetX= 0
DXF OffsetY= 0
DXF ScaleX= 1
DXF ScaleY= 10

--- EAST FORK ROCKY CREEK.p01 (plan) ---

Plan Title=Multiple Run
Short Identifier=Multiple
Geom File=g01
Flow File=f01
Subcritical Flow
K Sum by GR= 0
Std Step Tol= 0.01
Critical Tol= 0.01
Num of Std Step Trials= 20
Max Error Tol= 0.3
Flow Tol Ratio= 0.001
Split Flow NTrial= 30
Split Flow Tol= 0.02
Split Flow Ratio= 0.02
Log Output Level= 0
Friction Slope Method= 1
Unsteady Friction Slope Method= 2
Unsteady Bridges Friction Slope Method= 1
Parabolic Critical Depth
Global Vel Dist=  1 , 1 , 1
Global Log Level= 0
CheckData=True
Encroach Param= -1, 0, 0, 0
BEGIN DESCRIPTION:
Multiple Run
END DESCRIPTION:

--- EAST FORK ROCKY CREEK.f01 (steady flow) ---

Flow Title=Multiple
Program Version=4.10
Number of Profiles= 7
Profile Names=10-year,25-year,50-year,1pct_min,100-year,1pct_plu,500-year
River Rch & RM=EAST FORK ROCKY,Reach-1         ,27578
    1110    1639    2108    1986    2686    3633    4376
River Rch & RM=EAST FORK ROCKY,Reach-1         ,26901
    1385    2060    2661    2516    3402    4601    5580
River Rch & RM=EAST FORK ROCKY,Reach-1         ,22173
    1860    2806    3661    3491    4721    6385    7882
River Rch & RM=EAST FORK ROCKY,Reach-1         ,21441
    2415    3687    4846    4652    6291    8508   10645
River Rch & RM=EAST FORK ROCKY,Reach-1         ,17956
    2583    3928    5148    4922    6657    9002   11179
River Rch & RM=EAST FORK ROCKY,Reach-1         ,8185
    3418    5260    6950    6695    9054   12245   15432
River Rch & RM=EAST FORK ROCKY,Reach-1         ,6273
    3909    6036    7993    7712   10430   14105   17837
River Rch & RM=EAST FORK ROCKY,Reach-1         ,1259
    4158    6433    8530    8238   11142   15068   19095
Boundary for River Rch & Prof#=EAST FORK ROCKY,Reach-1         , 1
Up Type= 0
Dn Type= 1
Dn Known WS=1375.54
Boundary for River Rch & Prof#=EAST FORK ROCKY,Reach-1         , 2
Up Type= 0
Dn Type= 1
Dn Known WS=1377.67
Boundary for River Rch & Prof#=EAST FORK ROCKY,Reach-1         , 3
Up Type= 0
Dn Type= 1
Dn Known WS=1378.89
Boundary for River Rch & Prof#=EAST FORK ROCKY,Reach-1         , 4
Up Type= 0
Dn Type= 1
Dn Known WS=1378.77
Boundary for River Rch & Prof#=EAST FORK ROCKY,Reach-1         , 5
Up Type= 0
Dn Type= 1
Dn Known WS=1380.04
Boundary for River Rch & Prof#=EAST FORK ROCKY,Reach-1         , 6
Up Type= 0
Dn Type= 1
Dn Known WS=1381.31
Boundary for River Rch & Prof#=EAST FORK ROCKY,Reach-1         , 7
Up Type= 0
Dn Type= 1
Dn Known WS=1382.41
DSS Import GetInterval= 0
DSS Import GetPeak= 0
DSS Import FillOption= 0

--- EAST FORK ROCKY CREEK.g01 (geometry) ---

Geom Title=Existing Conditions
Program Version=4.10

River Reach=EAST FORK ROCKY ,Reach-1
Reach XY= 30
      2877735.81     10034126.13      2877563.37     10035920.24
      2877089.38     10036584.16      2877273.15       10037924.
      2876760.19     10038169.24      2876824.08     10039306.36
      2876356.23     10039386.99      2876277.87     10040111.72
      2875676.83     10039973.43      2875302.95     10040139.67
      2875089.08     10040793.14      2874288.53     10041308.99
      2874076.47     10042290.83      2873635.74     10042399.21
      2873213.68     10042843.34       2871909.4     10042505.73
      2871931.13     10043540.08      2871225.86     10043658.94
      2871029.82     10044328.41      2870513.07     10044370.73
      2870636.03     10045513.71      2870312.69     10046176.42
      2869694.04     10046195.12      2869420.14     10046519.53
      2869566.05     10048757.72      2868854.22     10050148.12
      2867920.23     10050454.57      2868196.58      10051518.4
      2867413.51     10052181.06      2867518.47     10052803.73

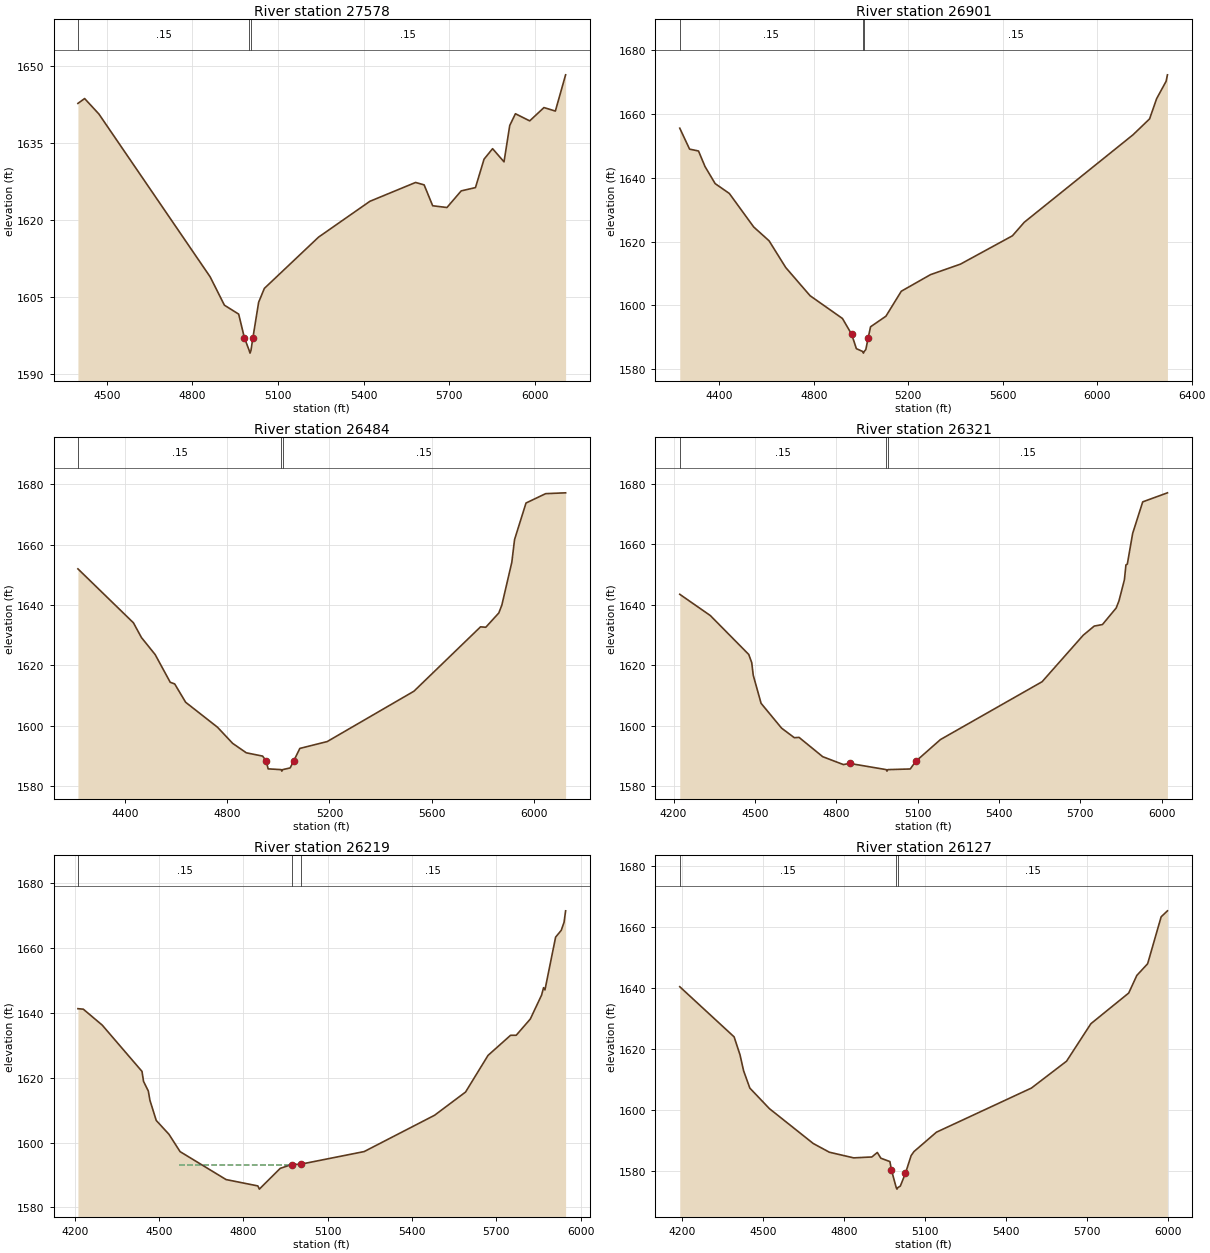
Type RM Length L Ch R = 1 ,27578   ,677,677,677
BEGIN DESCRIPTION:
EAST FORK ROCKY CREEK 59.0
END DESCRIPTION:
XS GIS Cut Line= 2
      2877185.01     10034288.42      2878894.35     10034328.17
#Sta/Elev= 30
  4398.6  1642.8  4422.1 1643.75  4472.1 1640.74  4862.2 1609.01  4912.2 1603.49
  4962.2 1601.75  4982.2 1597.15  4999.2 1594.65    5002 1594.15  5005.2 1594.65
  5012.2 1597.17  5032.2 1604.06  5052.2 1606.76  5242.3 1616.75  5422.3 1623.73
  5582.4  1627.4  5612.4 1626.93  5642.4 1622.86  5692.4 1622.52  5742.4 1625.76
  5792.4  1626.4  5822.4 1631.93  5852.4 1633.98  5892.5 1631.42  5912.5 1638.49
  5932.5 1640.79  5982.5  1639.4  6032.5 1641.99  6072.5 1641.31  6108.4 1648.37
#Mann= 3 ,-1 , 0
  4398.6     .15       0  4999.2     .05       0  5005.2     .15       0
Bank Sta=4982.2,5012.2
XS Rating Curve= 0 ,0
Exp/Cntr=0.3,0.1

Type RM Length L Ch R = 1 ,26901   ,417,417,417
BEGIN DESCRIPTION:
EAST FORK ROCKY CREEK 58.0
END DESCRIPTION:
XS GIS Cut Line= 3
       2876976.2      10034765.7      2877523.08     10034934.74
      2879014.05     10034855.22
#Sta/Elev= 30
  4231.9 1655.59  4273.5 1649.02  4311.3 1648.44  4338.7 1643.59  4381.8 1638.21
  4441.9 1635.12    4545 1624.62  4610.2 1620.28  4680.7  1611.9  4783.9 1603.06
    4921 1595.92  4959.9 1590.98  4979.9 1586.46    5007 1585.56  5009.7 1585.06
    5013 1585.56    5020 1586.19    5030 1589.88    5040 1593.32    5105 1596.63
  5170.2 1604.47    5294 1609.67  5420.6 1612.96  5640.9 1621.85    5691 1626.09
  6151.6 1653.52  6221.7  1658.5  6251.7 1664.86  6291.8  1670.3  6297.4 1672.32
#Mann= 3 ,-1 , 0
  4231.9     .15       0    5007     .05       0    5013     .15       0
Bank Sta=4959.9,5030
XS Rating Curve= 0 ,0
Exp/Cntr=0.3,0.1

Type RM Length L Ch R = 1 ,26484   ,163,163,163
BEGIN DESCRIPTION:
EAST FORK ROCKY CREEK 57.0
END DESCRIPTION:
XS GIS Cut Line= 3
      2876916.55     10035034.18      2877881.04     10035421.96
      2878734.81     10035600.66
#Sta/Elev= 30
  4213.8 1651.96  4431.4 1634.11  4462.8 1629.24  4516.6  1623.6  4575.7 1614.43
  4593.1 1613.89  4636.2 1607.81  4761.1 1599.55  4820.3 1594.22    4874 1591.09
    4938    1590    4952 1588.31  4959.5 1585.78  5010.4 1585.53  5013.2 1585.03
  5016.4 1585.53  5045.8 1586.09  5059.5 1588.36  5083.7 1592.54  5191.2 1594.82
    5531 1611.47  5792.2 1632.78  5812.6 1632.63  5863.7 1637.36  5875.6 1639.95
  5914.8 1654.17  5925.5 1661.66  5970.4 1673.75  6047.6 1676.85  6125.6 1677.12
#Mann= 3 ,-1 , 0
  4213.8     .15       0  5010.4     .05       0  5016.4     .15       0
Bank Sta=4952,5059.5
XS Rating Curve= 0 ,0
Exp/Cntr=0.3,0.1

Type RM Length L Ch R = 1 ,26321   ,102,102,102
BEGIN DESCRIPTION:
Mapping XS 4176645a
END DESCRIPTION:
XS GIS Cut Line= 3
      2876925.04     10035210.52      2877524.01     10035470.95
      2878655.12     10035652.96
#Sta/Elev= 30
  4222.9 1643.49  4335.7 1636.45  4477.4 1623.58  4488.3 1620.91    4494 1616.68
  4522.9 1607.41  4598.7 1599.18  4645.6 1596.04  4662.8 1596.15  4750.3 1589.75
  4826.4 1587.15  4849.5 1587.53  4984.4 1585.48  4987.2 1584.98  4990.4 1585.48
    5073 1585.69  5093.3 1588.21  5184.4 1595.42  5559.4 1614.56  5711.1 1629.95
  5751.6 1632.97    5782 1633.48  5832.6 1638.95  5842.8 1641.28    5863  1648.3
  5868.6 1653.22  5873.7 1653.46  5893.4 1663.63  5930.5 1674.07  6021.7 1677.06
#Mann= 3 ,-1 , 0
  4222.9     .15       0  4984.4     .05       0  4990.4     .15       0
Bank Sta=4849.5,5093.3
XS Rating Curve= 0 ,0
Exp/Cntr=0.3,0.1

Type RM Length L Ch R = 1 ,26219   ,92,92,92
BEGIN DESCRIPTION:
Mapping XS 7d2bcd87
END DESCRIPTION:
XS GIS Cut Line= 4
      2876920.76     10035258.29      2877558.74     10035566.43
      2877758.39     10035631.54      2878573.93     10035683.59
#Sta/Elev= 30
  4211.1 1641.34  4230.2 1641.19  4297.4 1636.28  4439.1 1621.97  4444.7 1618.87
  4461.7  1615.9  4467.3 1613.06  4489.9 1606.81  4535.1 1602.55  4574.7 1597.19
  4738.5 1588.56  4851.5  1586.6  4856.8 1585.61  4931.1 1592.02  4971.9  1593.2
  5003.5  1593.3  5229.9 1597.21  5480.4 1608.42  5590.6 1615.58  5670.8 1626.92
  5750.9 1633.12    5771 1633.13  5821.1 1638.14  5861.2 1645.51  5868.3 1647.82
  5873.3 1647.14  5911.3 1663.44  5931.3 1665.54  5941.3 1668.02  5946.8 1671.56
#Mann= 3 , 0 , 0
  4211.1     .15       0  4971.9     .05       0  5003.5     .15       0
#XS Ineff= 1 ,-1
  4570.2 4962.65 1593.04
Permanent Ineff=
       T
Bank Sta=4971.9,5003.5
XS Rating Curve= 0 ,0
Exp/Cntr=0.3,0.1

Type RM Length L Ch R = 1 ,26127   ,198,198,198
BEGIN DESCRIPTION:
Mapping XS 2f0257ea
END DESCRIPTION:
XS GIS Cut Line= 4
      2876881.63     10035319.02      2877445.89     10035631.54
      2877771.41     10035727.02      2878591.74     10035731.36
#Sta/Elev= 30
  4191.5 1640.39  4392.6    1624  4414.4 1618.15  4427.9 1612.87  4450.8 1607.26
  4523.1 1600.55  4685.7 1589.13  4745.2 1586.29  4835.1 1584.45  4902.3 1584.74
  4922.6 1586.21  4935.7 1584.33  4969.1 1583.24  4974.7 1580.53  4992.5 1574.73
  4995.3 1574.23  4998.5 1574.73  5007.7 1575.23  5026.8 1579.45  5047.6 1585.18
  5058.1  1586.5  5141.3 1592.84  5492.8 1607.27  5622.8 1616.05  5712.8  1628.3
  5852.8 1638.33  5882.8 1644.08  5922.8  1647.9  5972.8 1663.24  5996.1  1665.2
#Mann= 3 ,-1 , 0
  4191.5     .15       0  4992.5     .05       0  4998.5     .15       0
Bank Sta=4974.7,5026.8
XS Rating Curve= 0 ,0
Exp/Cntr=0.3,0.1

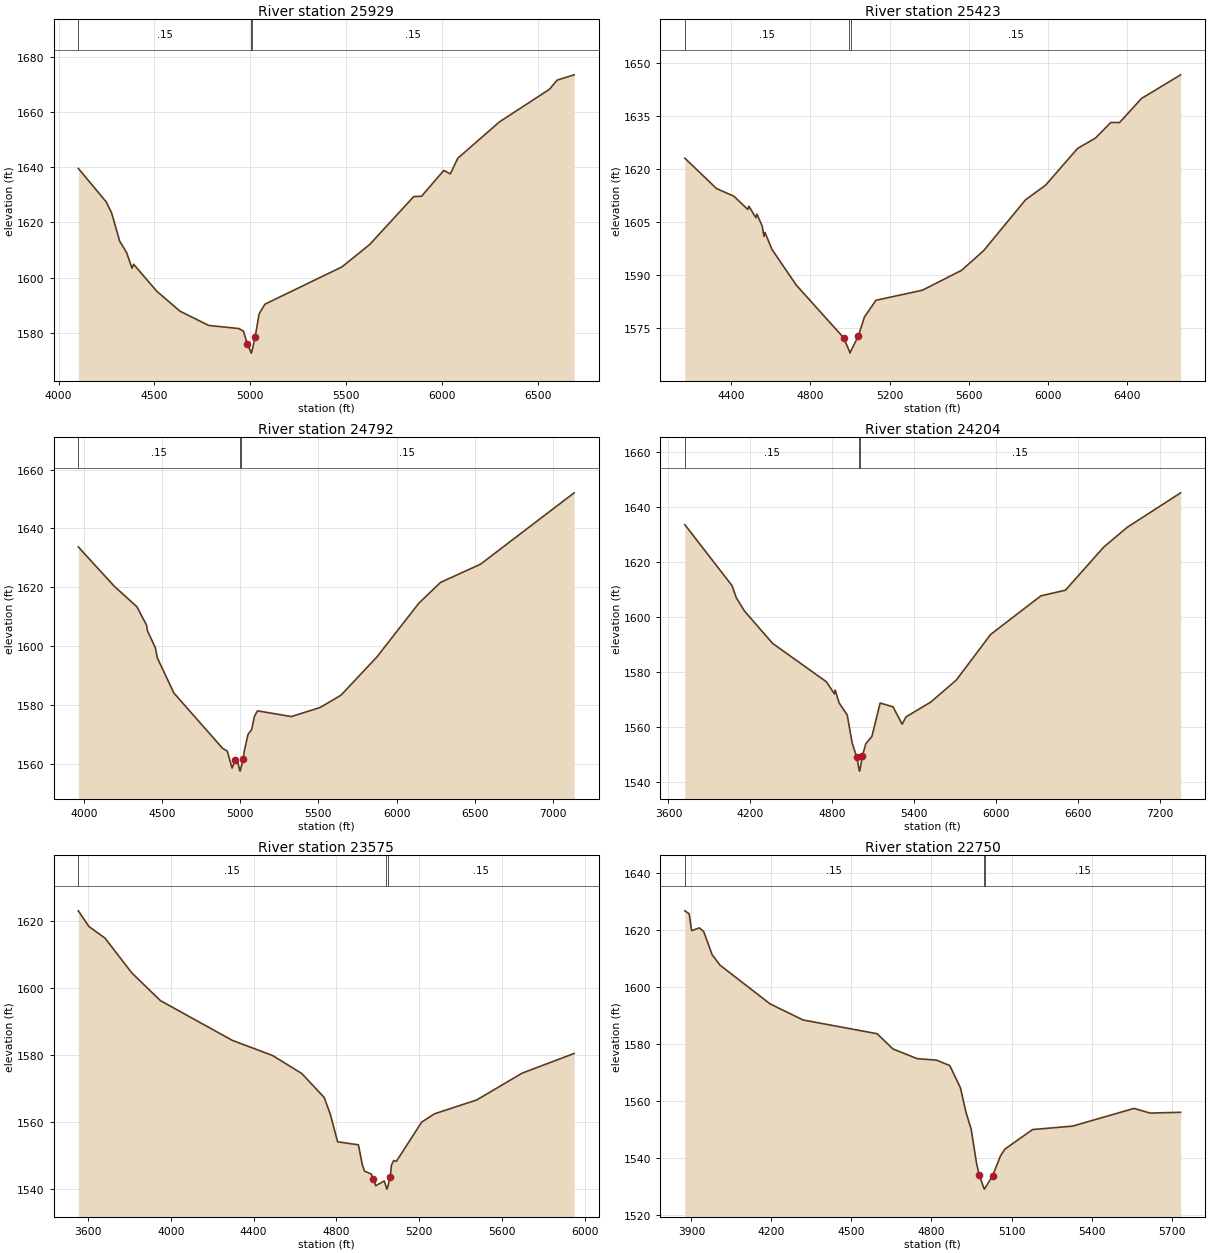
Type RM Length L Ch R = 1 ,25929   ,506,506,506
BEGIN DESCRIPTION:
EAST FORK ROCKY CREEK 56.0
END DESCRIPTION:
XS GIS Cut Line= 4
      2876836.99     10035372.25      2877473.36     10035849.53
      2878417.98      10036048.4      2879213.47     10035819.69
#Sta/Elev= 30
  4102.8 1639.58  4247.7 1627.52  4276.8 1623.43  4318.5 1613.29  4354.6 1609.12
  4383.1 1603.45  4391.4 1604.88  4512.3 1595.12  4633.1 1587.91  4783.1 1582.73
  4941.1  1581.6  4964.8 1580.64  4985.2 1576.06  5002.7  1573.2  5005.4  1572.7
  5008.7  1573.2  5026.1 1578.68  5046.6  1586.9  5077.2 1590.43  5478.9 1603.91
  5623.2 1611.99  5853.9 1629.39  5894.3 1629.49  6011.1 1638.86  6044.8 1637.59
  6083.7 1643.26  6301.5 1656.43  6561.2 1668.17  6602.9 1671.56  6691.3 1673.46
#Mann= 3 ,-1 , 0
  4102.8     .15       0  5002.7     .05       0  5008.7     .15       0
Bank Sta=4985.2,5026.1
XS Rating Curve= 0 ,0
Exp/Cntr=0.3,0.1

Type RM Length L Ch R = 1 ,25423   ,631,631,631
BEGIN DESCRIPTION:
EAST FORK ROCKY CREEK 55.0
END DESCRIPTION:
XS GIS Cut Line= 3
      2876469.12     10036038.46      2877632.46     10036336.75
      2878924.26     10036147.95
#Sta/Elev= 30
  4165.1 1623.03  4325.8 1614.44  4412.6 1612.33  4483.8 1608.56    4489  1609.5
  4524.6 1606.23  4529.7 1607.24  4556.7 1603.84  4565.3 1600.96  4570.5 1602.07
  4606.1 1597.27  4728.5 1587.24    4968 1572.38  4997.6 1568.54  5000.4 1568.04
  5003.6 1568.54  5041.9 1572.79  5072.9 1578.19  5131.1 1582.94  5366.1 1585.78
  5564.5  1591.4  5675.3 1596.91  5887.6 1611.28  5988.6 1615.38  6150.3 1625.75
  6241.3  1628.7  6318.8 1633.11  6362.6 1633.06  6473.7 1639.85  6671.6 1646.53
#Mann= 3 ,-1 , 0
  4165.1     .15       0  4997.6     .05       0  5003.6     .15       0
Bank Sta=4968,5041.9
XS Rating Curve= 0 ,0
Exp/Cntr=0.3,0.1

Type RM Length L Ch R = 1 ,24792   ,588,588,588
BEGIN DESCRIPTION:
EAST FORK ROCKY CREEK 53.0
END DESCRIPTION:
XS GIS Cut Line= 3
      2876150.92     10036635.06      2876836.99     10036873.69
      2879223.44      10036326.8
#Sta/Elev= 30
  3962.7 1633.73    4193 1620.35  4337.6 1613.39  4399.8  1607.1  4405.1 1605.24
  4456.7 1599.31  4468.3 1596.02  4574.2 1584.06  4885.4 1565.28  4916.3 1564.28
  4947.1 1558.52  4967.6 1561.25  4981.5 1560.84  4995.4 1557.97  4998.1 1557.47
  5001.4 1557.97  5018.9 1561.62  5024.4 1564.14  5049.7 1570.03  5072.4 1571.57
  5090.7 1576.18  5110.2 1577.97  5326.7 1576.03  5511.3 1579.12  5644.7  1583.3
  5875.4 1596.37  6143.1 1614.59    6282 1621.67  6537.3 1627.84  7137.4 1652.13
#Mann= 3 ,-1 , 0
  3962.7     .15       0  4995.4     .05       0  5001.4     .15       0
Bank Sta=4967.6,5018.9
XS Rating Curve= 0 ,0
Exp/Cntr=0.3,0.1

Type RM Length L Ch R = 1 ,24204   ,629,629,629
BEGIN DESCRIPTION:
EAST FORK ROCKY CREEK 52.0
END DESCRIPTION:
XS GIS Cut Line= 4
      2875872.45     10037112.33      2876946.37     10037380.81
      2877731.89     10037301.26      2879263.14     10036485.92
#Sta/Elev= 30
  3719.6 1633.68    4066 1611.45  4096.9 1607.08  4155.9  1602.3  4362.1  1590.5
  4756.6 1576.53  4815.6 1572.09  4820.8 1573.53  4850.5 1568.78  4909.1 1564.44
  4945.3 1554.27  4979.4 1549.06  4996.5 1544.53  4999.3 1544.03  5002.5 1544.53
  5019.6 1549.45  5045.2 1553.98    5090 1556.68  5150.3 1568.79    5245 1567.41
  5311.1 1561.09  5339.8 1563.76  5522.2 1569.19  5707.6 1577.13  5959.8 1593.75
  6327.6 1607.77  6507.2 1609.82  6788.3 1625.52  6958.3 1632.63  7350.9 1645.23
#Mann= 3 ,-1 , 0
  3719.6     .15       0  4996.5     .05       0  5002.5     .15       0
Bank Sta=4979.4,5019.6
XS Rating Curve= 0 ,0
Exp/Cntr=0.3,0.1

Type RM Length L Ch R = 1 ,23575   ,825,825,825
BEGIN DESCRIPTION:
EAST FORK ROCKY CREEK 51.0
END DESCRIPTION:
XS GIS Cut Line= 3
      2875922.19     10037400.69      2877453.48     10038037.07
      2878189.25     10038056.95
#Sta/Elev= 30
  3553.8 1623.17  3605.1 1618.47  3682.1 1615.04  3812.2 1604.58  3950.4 1596.29
    4297 1584.41    4492 1579.86  4632.7 1574.48    4741 1567.31  4770.7 1562.26
  4805.9 1554.04  4906.3 1553.13  4924.7  1547.3  4935.9 1545.24  4968.4 1544.41
  4977.8 1542.87    4990 1540.89    5031 1542.31  5041.2 1540.37  5043.9 1539.87
  5047.2 1540.37  5060.2 1543.58  5065.8 1547.03  5076.7 1548.43  5089.5 1548.19
    5212 1559.94  5272.9  1562.4  5477.1 1566.55  5697.2 1574.59  5948.1 1580.48
#Mann= 3 ,-1 , 0
  3553.8     .15       0  5041.2     .05       0  5047.2     .15       0
Bank Sta=4977.8,5060.2
XS Rating Curve= 0 ,0
Exp/Cntr=0.3,0.1

Type RM Length L Ch R = 1 ,22750   ,577,577,577
BEGIN DESCRIPTION:
EAST FORK ROCKY CREEK 49.0
END DESCRIPTION:
XS GIS Cut Line= 3
       2875723.3      10037977.4      2876528.74     10038315.48
      2877513.12     10038355.25
#Sta/Elev= 30
  3875.2 1626.58  3891.6 1625.56  3900.8 1619.62    3930  1620.6  3945.9 1619.37
  3977.5 1611.23  4006.7 1607.57  4195.3 1593.92    4319 1588.29  4596.6 1583.47
    4655 1578.17  4745.9 1574.75  4818.5 1574.22  4868.5 1572.32  4908.6 1564.48
  4928.6 1556.15  4948.6 1550.05  4968.6 1538.19  4978.6 1534.07  4995.6 1529.48
  4998.4 1528.98  5001.6 1529.48  5028.7 1533.58  5058.7 1540.66  5075.3 1543.02
  5178.8 1549.87  5329.3 1551.08  5559.1 1557.29  5619.2 1555.66  5733.9 1555.92
#Mann= 3 ,-1 , 0
  3875.2     .15       0  4995.6     .05       0  5001.6     .15       0
Bank Sta=4978.6,5028.7
XS Rating Curve= 0 ,0
Exp/Cntr=0.3,0.1

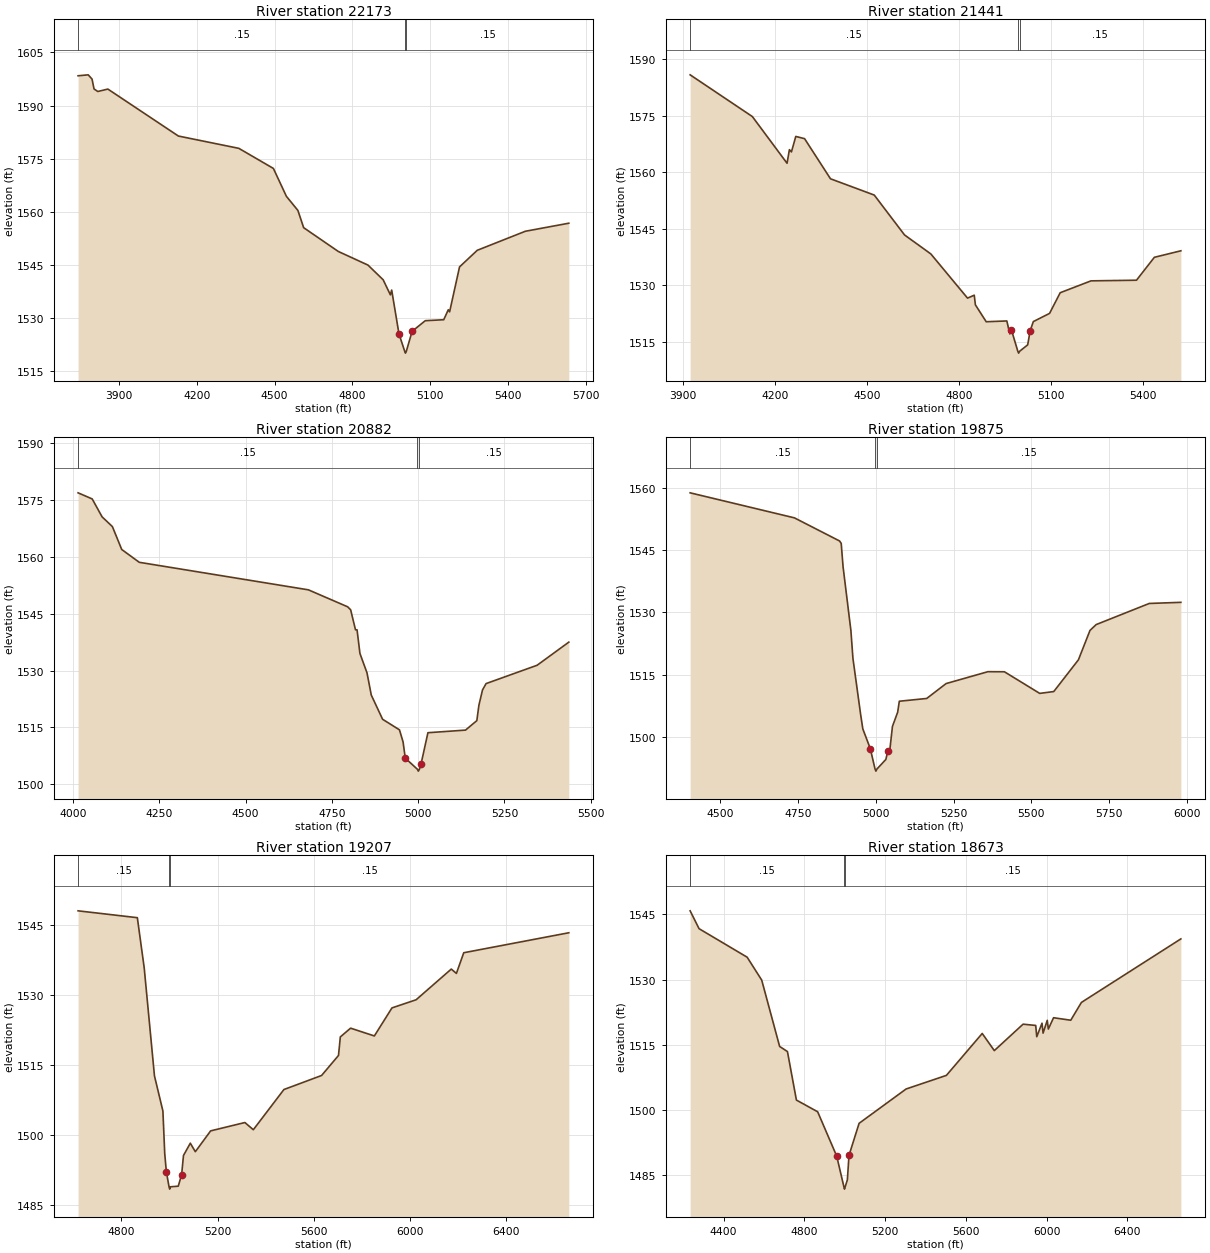
Type RM Length L Ch R = 1 ,22173   ,732,732,732
BEGIN DESCRIPTION:
EAST FORK ROCKY CREEK 48.0
END DESCRIPTION:
XS GIS Cut Line= 3
      2875683.59     10038365.22      2876677.89     10038872.31
       2877443.5     10039011.51
#Sta/Elev= 30
  3741.2 1598.39  3780.3 1598.66  3795.1 1597.46  3802.8 1594.68  3817.3 1593.96
  3856.2 1594.64  4128.5 1581.39  4361.8 1577.92  4495.2 1572.25  4545.3 1564.39
  4589.8  1560.4    4612 1555.54  4745.7 1548.83  4860.2 1544.99  4918.9 1540.84
  4946.7  1536.6  4951.8 1537.94  4979.9 1525.58  5002.2 1520.65  5004.9 1520.15
  5008.2 1520.65  5030.7 1526.31  5081.5  1529.3  5152.7 1529.57  5170.3 1532.39
  5175.4  1531.8  5213.7 1544.47  5282.1 1549.16  5467.8 1554.53  5635.5  1556.8
#Mann= 3 ,-1 , 0
  3741.2     .15       0  5002.2     .05       0  5008.2     .15       0
Bank Sta=4979.9,5030.7
XS Rating Curve= 0 ,0
Exp/Cntr=0.3,0.1

Type RM Length L Ch R = 1 ,21441   ,559,559,559
BEGIN DESCRIPTION:
EAST FORK ROCKY CREEK 46.0
END DESCRIPTION:
XS GIS Cut Line= 3
      2875782.99     10038623.73      2876488.97     10039230.27
      2876747.52      10039846.8
#Sta/Elev= 30
  3923.9  1585.9  4126.7 1574.82  4239.7 1562.43  4247.4 1566.04    4254 1565.44
  4268.2 1569.55  4296.8 1568.96  4381.3 1558.31  4523.9 1553.99  4622.7  1543.4
  4708.3 1538.37  4827.9 1526.64  4849.8 1527.42  4853.5 1524.86  4888.8 1520.37
    4956 1520.58  4965.6 1517.15    4971  1518.2  4991.8 1512.54  4994.5 1512.04
  4997.8 1512.54    5024 1514.24  5031.9 1517.94  5042.3 1520.41  5095.3 1522.59
  5129.9 1528.07  5230.4 1531.22  5378.5 1531.39  5436.8 1537.47  5523.2  1539.2
#Mann= 3 ,-1 , 0
  3923.9     .15       0  4991.8     .05       0  4997.8     .15       0
Bank Sta=4971,5031.9
XS Rating Curve= 0 ,0
Exp/Cntr=0.3,0.1

Type RM Length L Ch R = 1 ,20882   ,1007,1007,1007
BEGIN DESCRIPTION:
EAST FORK ROCKY CREEK 45.0
END DESCRIPTION:
XS GIS Cut Line= 3
      2875474.72     10039230.25      2876140.95     10039687.67
      2876727.61     10039866.65
#Sta/Elev= 30
  4014.8 1576.94  4055.7 1575.33  4084.4 1570.59  4114.2 1568.03  4141.2 1561.99
    4192  1558.6    4682 1551.33  4795.7 1546.85  4804.4 1546.05  4818.4 1540.78
  4822.9 1540.78  4831.3 1534.52  4851.7 1529.43  4864.1 1523.56  4896.9 1517.16
  4945.8 1514.37  4956.3 1511.15  4962.6  1506.9  4997.6 1503.97  5000.4 1503.47
  5003.6 1503.97  5008.5 1505.45  5028.2 1513.61  5137.1  1514.3  5169.9  1516.8
  5175.8 1520.83  5186.3  1524.9  5196.7 1526.58  5344.5 1531.42  5436.3 1537.52
#Mann= 3 ,-1 , 0
  4014.8     .15       0  4997.6     .05       0  5003.6     .15       0
Bank Sta=4962.6,5008.5
XS Rating Curve= 0 ,0
Exp/Cntr=0.3,0.1

Type RM Length L Ch R = 1 ,19875   ,668,668,668
BEGIN DESCRIPTION:
EAST FORK ROCKY CREEK 43.0
END DESCRIPTION:
XS GIS Cut Line= 2
      2875494.65     10039409.29      2876011.35     10040899.77
#Sta/Elev= 30
  4403.1 1558.75  4738.3 1552.73  4883.4 1547.17  4888.7  1546.6  4894.7 1540.96
  4919.8 1525.67  4926.4 1518.94    4951 1505.52  4958.2 1501.96  4982.1 1497.25
  4997.5 1492.31  5000.2 1491.81  5003.5 1492.31  5032.2 1494.62  5039.1 1496.75
  5044.4 1496.52  5053.4 1502.56  5070.2 1505.99  5075.5 1508.62  5163.6 1509.29
  5225.9 1512.87  5360.3 1515.73  5413.3 1515.71  5526.8 1510.51    5572 1510.95
  5651.3 1518.59  5688.4 1525.65  5708.3 1527.06    5879 1532.14  5980.6 1532.41
#Mann= 3 ,-1 , 0
  4403.1     .15       0  4997.5     .05       0  5003.5     .15       0
Bank Sta=4982.1,5039.1
XS Rating Curve= 0 ,0
Exp/Cntr=0.3,0.1

Type RM Length L Ch R = 1 ,19207   ,534,534,534
BEGIN DESCRIPTION:
EAST FORK ROCKY CREEK 42.0
END DESCRIPTION:
XS GIS Cut Line= 3
      2874884.73      10040079.4      2875809.18     10040886.67
      2876499.24     10041316.33
#Sta/Elev= 30
  4619.7 1548.03  4866.1 1546.56  4894.6 1535.83  4937.3 1512.66  4972.4 1505.13
    4980    1496  4986.7 1492.12  4997.9  1488.9  5000.6  1488.4  5003.9  1488.9
  5036.2 1489.03  5050.2 1491.49  5057.9 1495.61  5086.3 1498.24  5107.2 1496.42
  5170.8 1500.88  5313.2 1502.67  5348.3 1501.13  5475.5 1509.74  5632.1 1512.75
  5702.4 1517.04    5710 1521.01  5752.7 1522.89  5851.5 1521.22  5924.7 1527.23
    6025 1528.97  6171.3 1535.55  6192.6 1534.62  6223.1 1539.05  6659.9 1543.33
#Mann= 3 ,-1 , 0
  4619.7     .15       0  4997.9     .05       0  5003.9     .15       0
Bank Sta=4986.7,5050.2
XS Rating Curve= 0 ,0
Exp/Cntr=0.3,0.1

Type RM Length L Ch R = 1 ,18673   ,717,717,717
BEGIN DESCRIPTION:
EAST FORK ROCKY CREEK 40.0
END DESCRIPTION:
XS GIS Cut Line= 3
      2874702.41     10040131.46      2875392.52     10041472.61
       2876264.2     10041771.84
#Sta/Elev= 30
  4234.6 1545.83  4278.6 1541.72  4516.9 1535.14    4589 1529.86  4677.7 1514.57
  4716.4 1513.39  4760.8 1502.21    4866 1499.51  4960.3 1489.29  4996.1 1482.18
  4998.8 1481.68  5002.1 1482.18  5013.1 1483.82  5021.2 1489.46  5071.2 1496.85
  5303.9 1504.76  5503.5  1507.9  5680.8 1517.56  5740.7 1513.61  5883.1  1519.7
  5945.7 1519.41  5950.9 1516.81  5976.9 1519.93  5982.2 1517.64  6002.9 1520.59
  6008.2 1518.58  6034.1 1521.19  6119.2 1520.61  6172.1 1524.72  6664.5 1539.36
#Mann= 3 ,-1 , 0
  4234.6     .15       0  4996.1     .05       0  5002.1     .15       0
Bank Sta=4960.3,5021.2
XS Rating Curve= 0 ,0
Exp/Cntr=0.3,0.1

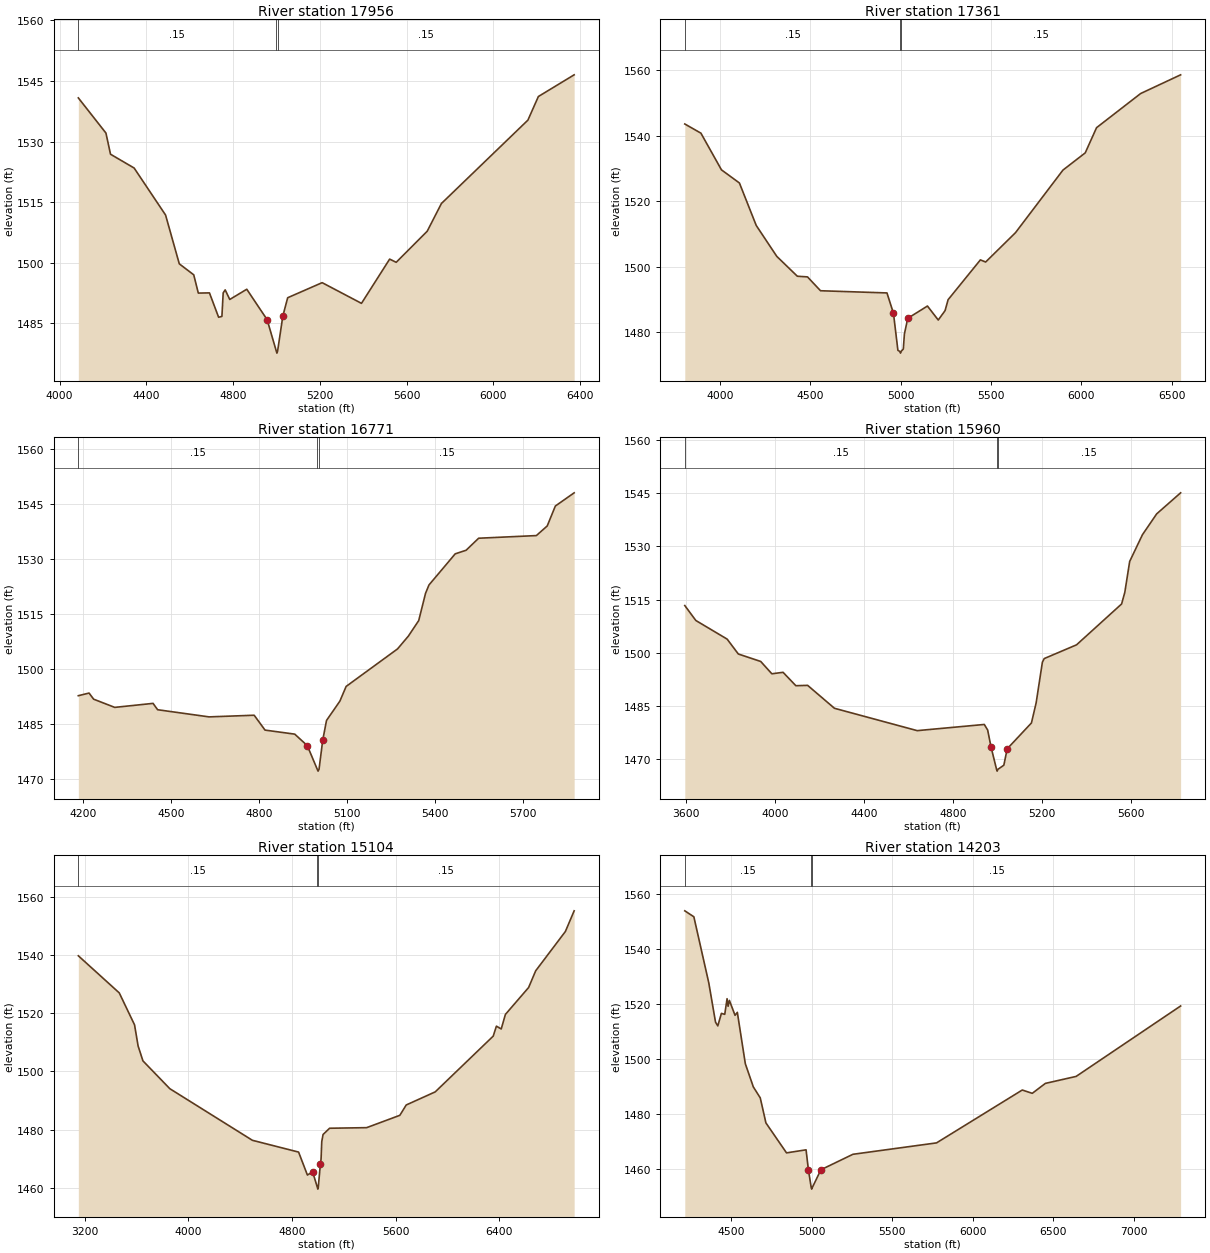
Type RM Length L Ch R = 1 ,17956   ,595,595,595
BEGIN DESCRIPTION:
EAST FORK ROCKY CREEK 38.0
END DESCRIPTION:
XS GIS Cut Line= 2
       2873973.3     10040433.42      2875216.21     10042352.48
#Sta/Elev= 30
  4086.1 1540.83  4213.4 1532.13  4234.5 1526.89  4343.3 1523.48  4488.4 1511.84
  4551.7 1499.76  4618.3 1497.04  4639.4 1492.52  4690.8 1492.57    4733 1486.54
  4748.2 1486.75  4754.1 1492.58  4763.3 1493.31  4784.4 1490.94  4862.9 1493.47
  4956.6 1485.95    4999 1478.16  5001.8 1477.66    5005 1478.16  5029.1 1486.83
  5051.5 1491.37  5210.4  1495.1  5391.8 1489.98  5521.7 1500.93  5551.9 1500.14
  5694.9 1507.83  5760.4 1514.69  6159.3 1535.33  6207.5 1541.17  6372.5 1546.54
#Mann= 3 ,-1 , 0
  4086.1     .15       0    4999     .05       0    5005     .15       0
Bank Sta=4956.6,5029.1
XS Rating Curve= 0 ,0
Exp/Cntr=0.3,0.1

Type RM Length L Ch R = 1 ,17361   ,590,590,590
BEGIN DESCRIPTION:
EAST FORK ROCKY CREEK 37.0
END DESCRIPTION:
XS GIS Cut Line= 4
       2873416.5     10040870.96       2873973.3      10041576.9
      2874589.79     10041815.55      2875294.08     10042767.83
#Sta/Elev= 30
  3805.7 1543.62  3894.9 1540.81  4008.7 1529.58  4108.1 1525.56  4201.1 1512.57
  4314.9 1503.11  4428.7 1497.03  4484.8 1496.83    4557 1492.59  4924.8 1491.92
  4960.8 1485.68  4985.3 1474.36  4996.9    1474  4999.6  1473.5  5002.9    1474
  5015.3 1474.77  5021.3 1479.35  5039.8 1484.15  5148.9 1487.91  5208.7 1483.63
  5246.5 1486.52  5263.2 1489.85  5441.9 1502.03  5471.1 1501.38  5636.1 1510.35
    5899 1529.51  6022.3 1534.78    6085 1542.49  6329.1 1552.94  6550.3 1558.66
#Mann= 3 ,-1 , 0
  3805.7     .15       0  4996.9     .05       0  5002.9     .15       0
Bank Sta=4960.8,5039.8
XS Rating Curve= 0 ,0
Exp/Cntr=0.3,0.1

Type RM Length L Ch R = 1 ,16771   ,811,811,811
BEGIN DESCRIPTION:
EAST FORK ROCKY CREEK 36.0
END DESCRIPTION:
XS GIS Cut Line= 2
      2873714.79     10041537.16      2874579.79     10042988.78
#Sta/Elev= 30
  4184.5 1492.82  4221.1 1493.54  4236.7 1491.87  4308.6 1489.64  4439.2 1490.73
  4454.7    1489    4630 1487.05  4783.8  1487.5  4820.8 1483.45    4922 1482.35
  4964.8 1479.22  4998.8 1472.77  5001.5 1472.27  5004.8 1472.77  5017.4 1480.68
  5030.3 1486.07  5075.8 1491.33  5097.2 1495.35  5272.4 1505.57  5309.4 1509.07
  5344.6  1513.3  5367.8 1520.71  5379.5 1522.99    5469 1531.48    5506 1532.45
  5548.8 1535.73  5745.5 1536.45  5782.5 1539.07  5810.2  1544.5  5874.3  1548.1
#Mann= 3 ,-1 , 0
  4184.5     .15       0  4998.8     .05       0  5004.8     .15       0
Bank Sta=4964.8,5017.4
XS Rating Curve= 0 ,0
Exp/Cntr=0.3,0.1

Type RM Length L Ch R = 1 ,15960   ,856,856,856
BEGIN DESCRIPTION:
EAST FORK ROCKY CREEK 34.0
END DESCRIPTION:
XS GIS Cut Line= 3
      2873283.14     10041264.28      2873387.31     10042553.34
      2874168.52     10043061.12
#Sta/Elev= 30
  3596.2  1513.3  3645.8 1509.09  3786.3 1503.84  3836.4 1499.65  3936.8 1497.55
  3986.9 1494.07  4037.1 1494.49  4094.6 1490.71  4147.4 1490.81  4267.8 1484.35
    4639 1478.05  4940.3 1479.79  4955.4  1478.2  4970.6  1473.4  4995.2 1467.14
  4997.9 1466.64  5001.2 1467.14  5027.9 1468.31    5043 1472.93  5151.8 1480.22
  5172.9  1485.9  5200.9 1497.35  5209.1 1498.36  5354.1 1502.23  5556.4 1513.75
  5570.7 1517.01  5592.6 1525.73  5649.9 1533.27  5713.8 1539.14  5821.2 1545.07
#Mann= 3 ,-1 , 0
  3596.2     .15       0  4995.2     .05       0  5001.2     .15       0
Bank Sta=4970.6,5043
XS Rating Curve= 0 ,0
Exp/Cntr=0.3,0.1

Type RM Length L Ch R = 1 ,15104   ,901,901,901
BEGIN DESCRIPTION:
EAST FORK ROCKY CREEK 32.0
END DESCRIPTION:
XS GIS Cut Line= 4
       2872514.9     10041016.86      2872866.47     10041628.86
      2872684.18      10043217.4       2874103.5     10043764.29
#Sta/Elev= 30
  3151.9 1539.74  3467.8 1526.99  3585.7 1516.01  3613.1 1508.77  3650.4 1503.65
  3857.6  1494.1  4494.9 1476.37  4851.5 1472.32  4919.5 1464.44  4959.8 1465.54
    4997  1460.1  4999.8  1459.6    5003  1460.1  5019.7 1468.26  5024.8 1469.86
  5030.2 1475.92  5040.3 1478.36  5090.6 1480.51  5376.4 1480.71  5632.7 1484.95
  5681.9  1488.5  5905.7    1493  6353.2 1512.15  6377.9 1515.57    6415  1514.6
  6447.2  1519.6  6626.3 1528.84  6680.9 1534.58    6910 1548.08  6977.7 1555.18
#Mann= 3 ,-1 , 0
  3151.9     .15       0    4997     .05       0    5003     .15       0
Bank Sta=4959.8,5019.7
XS Rating Curve= 0 ,0
Exp/Cntr=0.3,0.1

Type RM Length L Ch R = 1 ,14203   ,547,547,547
BEGIN DESCRIPTION:
EAST FORK ROCKY CREEK 30.0
END DESCRIPTION:
XS GIS Cut Line= 3
      2871397.97     10041905.04      2872720.44     10043545.69
      2873614.43     10043933.09
#Sta/Elev= 30
  4211.1  1553.9  4267.4 1551.73  4360.2 1527.65  4402.1 1513.33  4416.2 1511.96
  4438.6 1516.53  4459.4 1516.17  4473.8 1521.88  4480.2 1519.12  4488.2 1521.25
  4523.4 1515.83  4537.7  1516.9  4587.3 1498.19  4636.9 1489.76  4680.1 1485.73
  4715.3 1476.62  4843.3  1465.7  4964.8 1466.81  4979.2 1459.61    4997 1452.99
  4999.7 1452.49    5003 1452.99  5057.1 1459.55  5255.9 1465.18  5775.7 1469.34
  6308.4  1488.6  6370.7  1487.4  6452.1 1491.02  6643.2 1493.56  7292.7 1519.23
#Mann= 3 ,-1 , 0
  4211.1     .15       0    4997     .05       0    5003     .15       0
Bank Sta=4979.2,5057.1
XS Rating Curve= 0 ,0
Exp/Cntr=0.3,0.1

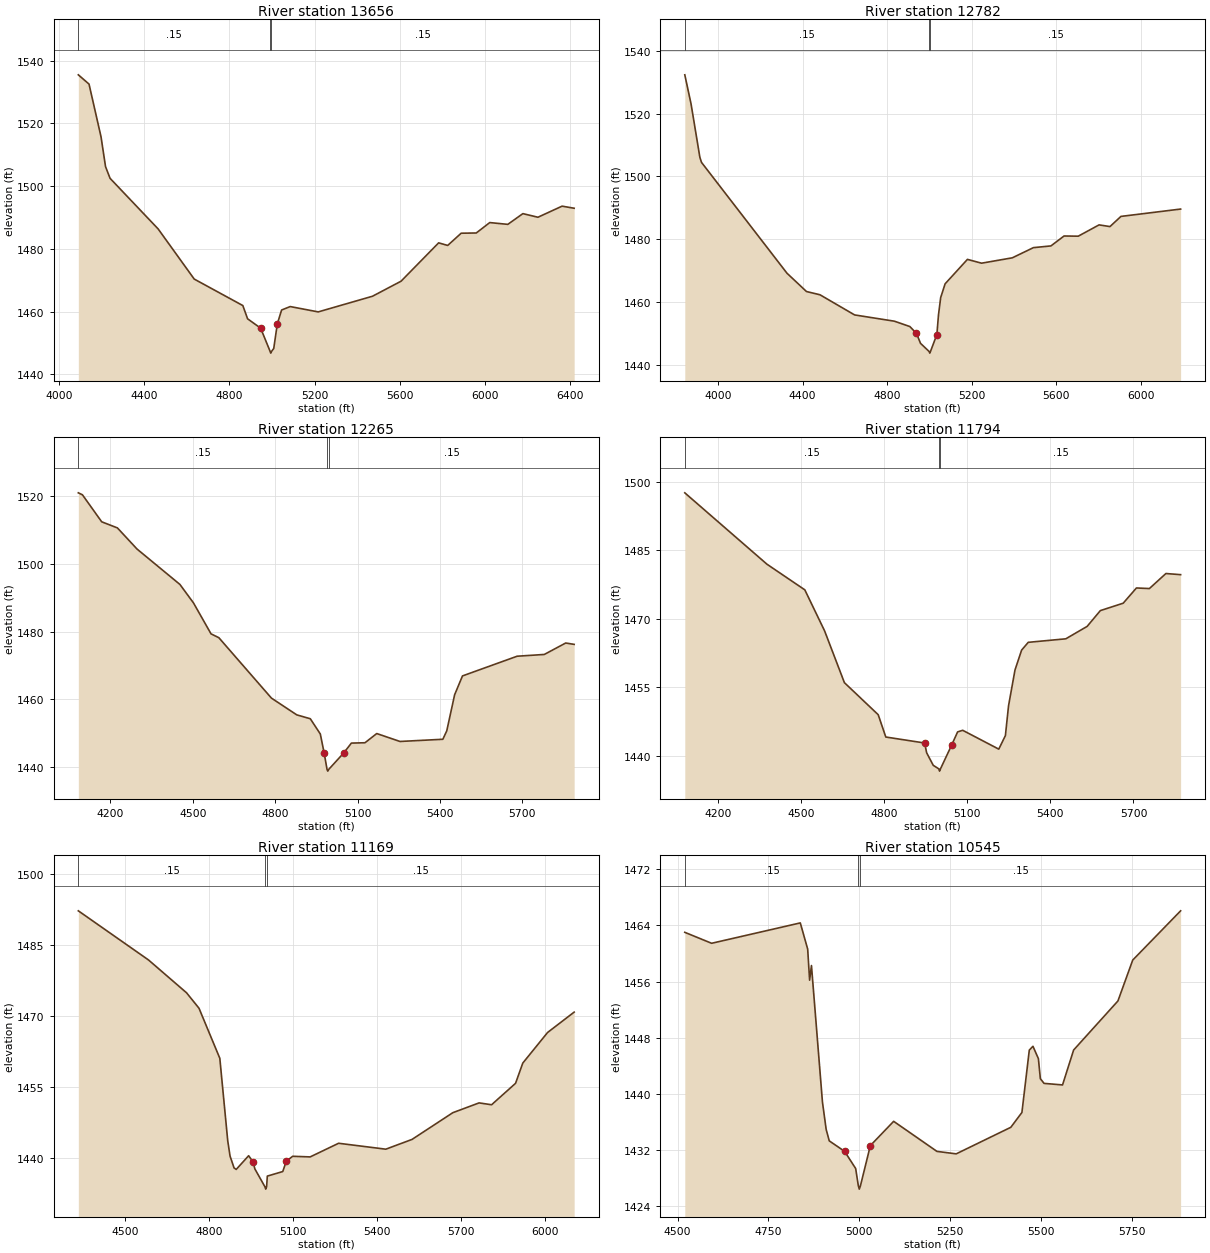
Type RM Length L Ch R = 1 ,13656   ,874,874,874
BEGIN DESCRIPTION:
EAST FORK ROCKY CREEK 29.0
END DESCRIPTION:
XS GIS Cut Line= 4
      2871149.41     10042491.72      2871666.44     10043008.75
        2872094.     10043078.35      2872949.13     10043873.82
#Sta/Elev= 30
  4089.1 1535.49  4139.4 1532.54  4195.9 1515.73  4217.1 1506.22  4238.4  1502.5
  4464.6 1486.37  4634.3 1470.39  4862.9 1461.95  4885.3 1457.73  4946.8 1454.74
  4991.6 1447.29  4994.3 1446.79  4997.6 1447.29  5008.3 1448.27    5025 1456.07
  5045.2 1460.53  5085.8 1461.63  5217.5 1459.93  5472.8 1464.92  5607.1 1469.71
    5784 1481.94  5826.5 1481.11    5890 1485.01  5960.9 1485.08  6024.4  1488.4
  6109.4 1487.83  6180.2 1491.25  6251.1  1490.1  6364.5 1493.63  6421.4 1492.97
#Mann= 3 ,-1 , 0
  4089.1     .15       0  4991.6     .05       0  4997.6     .15       0
Bank Sta=4946.8,5025
XS Rating Curve= 0 ,0
Exp/Cntr=0.3,0.1

Type RM Length L Ch R = 1 ,12782   ,517,517,517
BEGIN DESCRIPTION:
EAST FORK ROCKY CREEK 27.0
END DESCRIPTION:
XS GIS Cut Line= 4
      2870950.54     10042680.65      2871567.01     10043406.48
      2871706.21     10043883.76      2872571.33     10044112.47
#Sta/Elev= 30
  3843.2 1532.38  3872.8 1523.11  3914.5 1506.09  3922.2 1504.49  4326.4 1469.18
  4418.6 1463.35  4482.3 1462.32    4646  1455.9  4834.3  1453.9  4907.2  1452.2
  4938.5 1450.02  4957.8 1446.84  4998.7 1444.23  5001.4 1443.73  5004.7 1444.23
  5035.1 1449.66  5042.6 1455.87    5053 1461.41  5073.9  1465.8  5179.5 1473.59
  5246.4 1472.38  5391.8 1474.09  5491.5 1477.33  5574.3 1477.88  5636.3 1481.04
  5703.5 1480.98  5801.8 1484.58  5853.5 1484.04  5905.3 1487.28  6187.5 1489.62
#Mann= 3 ,-1 , 0
  3843.2     .15       0  4998.7     .05       0  5004.7     .15       0
Bank Sta=4938.5,5035.1
XS Rating Curve= 0 ,0
Exp/Cntr=0.3,0.1

Type RM Length L Ch R = 1 ,12265   ,471,471,471
BEGIN DESCRIPTION:
EAST FORK ROCKY CREEK 26.0
END DESCRIPTION:
XS GIS Cut Line= 2
      2870443.44     10043138.04      2871824.51     10044300.53
#Sta/Elev= 30
  4083.5    1521  4098.4 1520.42  4168.6 1512.44  4225.8 1510.64  4297.3 1504.39
  4453.4 1493.94  4502.8 1488.48  4566.6 1479.35  4595.2  1478.2  4786.4 1460.38
  4878.7 1455.42  4928.1 1454.27  4964.5 1449.77  4978.8 1444.05    4989  1439.3
  4991.7  1438.8    4995  1439.3  5049.1 1444.11  5077.7 1447.08  5127.1 1447.18
    5170  1449.9  5254.6 1447.56  5410.6 1448.21  5424.9  1450.7  5453.5 1461.35
  5482.1 1466.92  5681.1 1472.74    5780 1473.26    5858 1476.64  5888.7 1476.24
#Mann= 3 ,-1 , 0
  4083.5     .15       0    4989     .05       0    4995     .15       0
Bank Sta=4978.8,5049.1
XS Rating Curve= 0 ,0
Exp/Cntr=0.3,0.1

Type RM Length L Ch R = 1 ,11794   ,625,625,625
BEGIN DESCRIPTION:
EAST FORK ROCKY CREEK 25.0
END DESCRIPTION:
XS GIS Cut Line= 3
      2870473.24     10043515.86      2870890.86     10044112.46
      2871872.65     10044519.06
#Sta/Elev= 30
  4079.5 1497.55  4376.2 1481.94    4513 1476.33  4584.5 1467.35    4656 1456.03
  4778.1 1449.02  4805.5 1444.14  4945.9 1442.83    4953  1440.7  4976.9 1437.95
    4997 1437.18  4999.7 1436.68    5003 1437.18  5043.3 1442.36  5064.9 1445.26
  5083.3 1445.61  5213.6 1441.49  5237.5 1444.45  5248.9 1450.99  5272.2 1458.81
  5296.1 1463.15    5320 1464.85  5455.7 1465.62  5532.8 1468.34  5580.5 1471.79
    5663 1473.41  5710.8 1476.74  5757.6 1476.61  5817.2  1479.9  5870.4 1479.65
#Mann= 3 ,-1 , 0
  4079.5     .15       0    4997     .05       0    5003     .15       0
Bank Sta=4945.9,5043.3
XS Rating Curve= 0 ,0
Exp/Cntr=0.3,0.1

Type RM Length L Ch R = 1 ,11169   ,624,624,624
BEGIN DESCRIPTION:
EAST FORK ROCKY CREEK 23.0
END DESCRIPTION:
XS GIS Cut Line= 3
      2870324.08     10043714.72      2870771.54      10044649.4
      2871467.59     10044888.05
#Sta/Elev= 30
  4332.8 1492.17  4583.6  1481.8  4719.6 1474.87  4764.1 1471.61  4838.5 1461.04
  4866.7 1443.68    4875 1440.42  4889.4  1437.9  4897.1 1437.59  4941.5 1440.48
  4957.4 1439.16  4963.7  1437.7  4999.7 1433.93  5002.5 1433.43  5005.7 1433.93
  5008.3 1436.18  5063.4 1437.14  5076.3 1439.34  5098.9 1440.36  5161.4 1440.23
  5263.1 1443.11  5431.6 1441.86  5525.4 1443.92  5671.2 1449.56    5765 1451.63
  5809.8 1451.24  5895.4 1455.76  5921.4 1460.04  6009.9 1466.49  6104.9 1470.79
#Mann= 3 ,-1 , 0
  4332.8     .15       0  4999.7     .05       0  5005.7     .15       0
Bank Sta=4957.4,5076.3
XS Rating Curve= 0 ,0
Exp/Cntr=0.3,0.1

Type RM Length L Ch R = 1 ,10545   ,555,555,555
BEGIN DESCRIPTION:
EAST FORK ROCKY CREEK 22.0
END DESCRIPTION:
XS GIS Cut Line= 2
      2870015.81     10044788.61      2871358.16     10045027.25
#Sta/Elev= 30
    4520    1463  4593.8 1461.44  4837.6 1464.34  4857.9 1460.61  4863.2 1456.19
  4868.3 1458.27  4898.5 1438.85  4908.7 1434.96  4917.2 1433.32  4959.4 1431.83
  4989.9 1429.38  4997.1 1426.95  4999.8 1426.45  5003.1 1426.95  5030.2 1432.64
  5094.3  1436.1  5213.4 1431.82  5266.3 1431.47  5416.5 1435.25    5447 1437.36
  5467.3 1446.24  5477.4 1446.78  5492.3 1445.02  5497.7 1442.17  5507.9  1441.5
  5558.7 1441.28  5589.2 1446.25    5711 1453.23  5751.7 1459.05  5883.4 1466.06
#Mann= 3 ,-1 , 0
    4520     .15       0  4997.1     .05       0  5003.1     .15       0
Bank Sta=4959.4,5030.2
XS Rating Curve= 0 ,0
Exp/Cntr=0.3,0.1