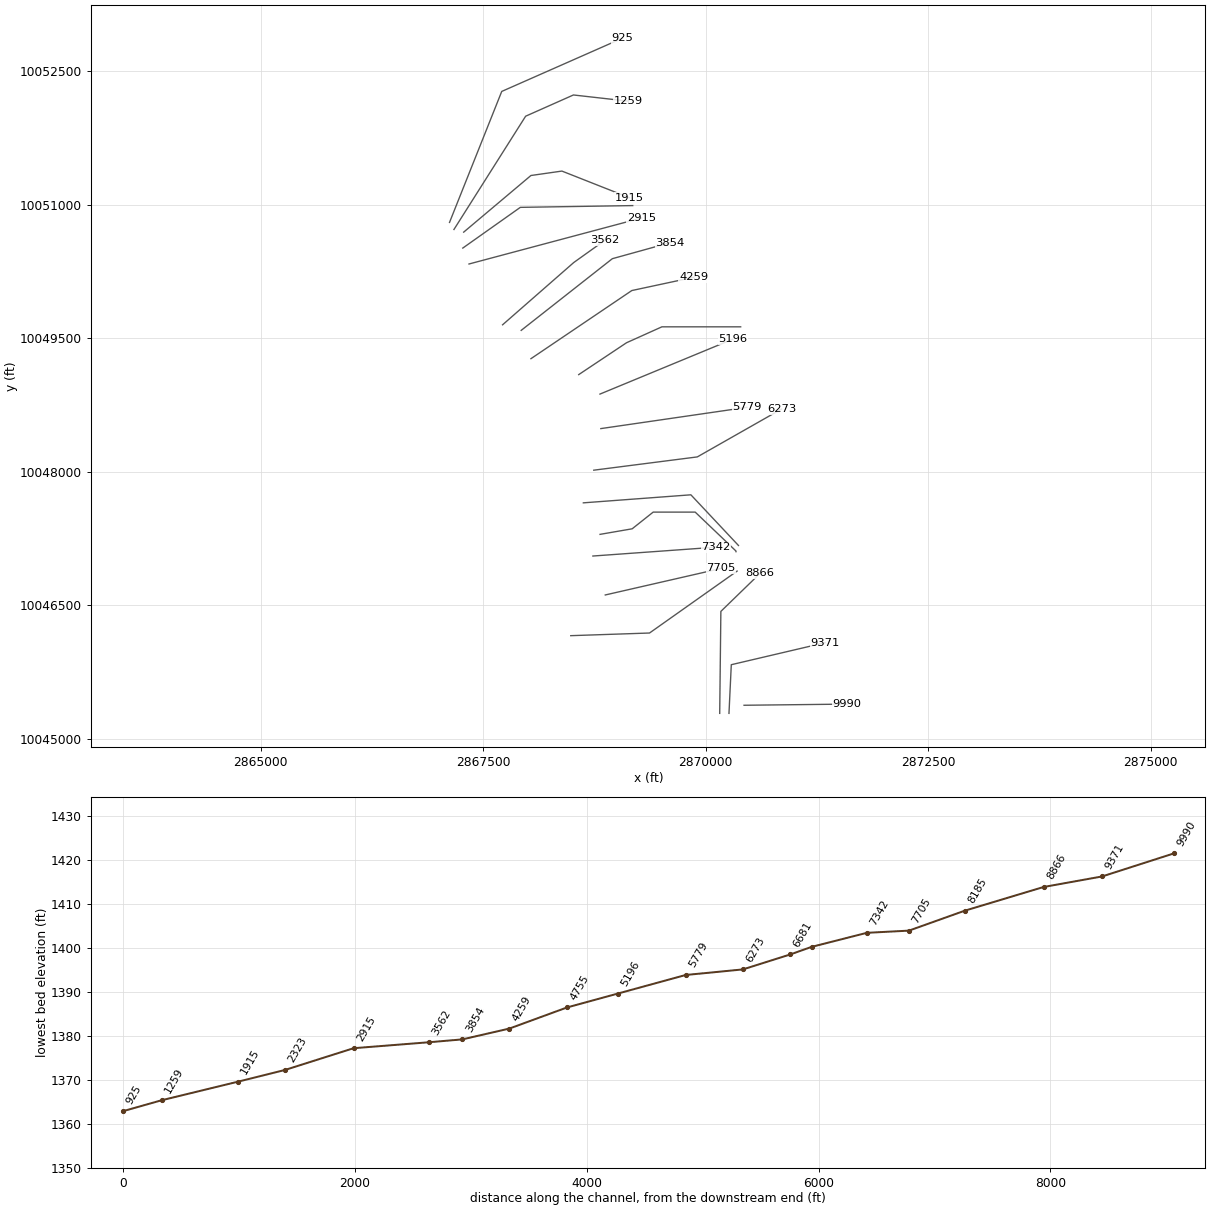
HEC-RAS study EAST FORK ROCKY CREEK.prj: EAST FORK ROCKY CREEK Base Level Engineering

--- EAST FORK ROCKY CREEK.g01 (geometry) --- (continued)

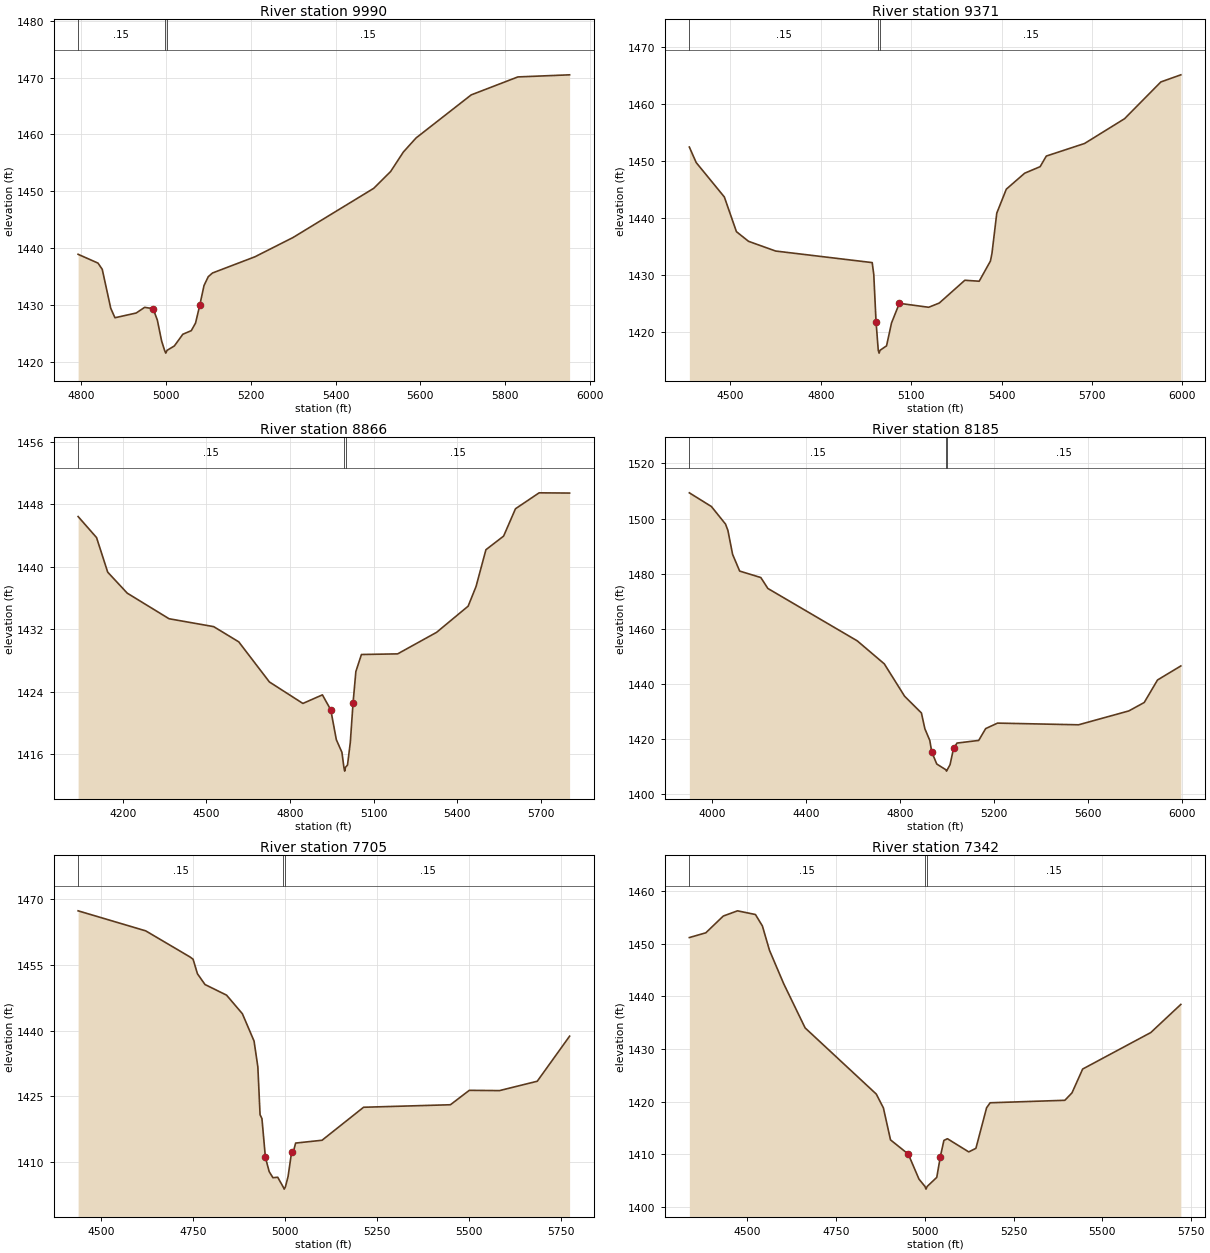
Type RM Length L Ch R = 1 ,9990    ,619,619,619
BEGIN DESCRIPTION:
EAST FORK ROCKY CREEK 21.0
END DESCRIPTION:
XS GIS Cut Line= 2
      2870431.55     10045378.86      2871590.48     10045391.88
#Sta/Elev= 30
    4793 1438.88  4839.9 1437.33  4849.9 1436.24  4869.9 1429.39  4879.9 1427.71
  4929.9 1428.54  4949.9 1429.54  4969.9 1429.31  4979.9 1427.28  4989.9 1423.62
  4996.9 1421.98  4999.7 1421.48  5002.9 1421.98  5019.9 1422.74  5039.9  1424.8
  5059.9 1425.44  5069.9 1426.77  5079.9 1429.92  5089.9 1433.38  5099.9 1434.94
  5109.9 1435.59  5209.9 1438.44  5299.9 1441.84    5490 1450.49    5530 1453.46
    5560 1456.89    5590 1459.37    5720 1466.95    5830 1470.11    5952 1470.48
#Mann= 3 ,-1 , 0
    4793     .15       0  4996.9     .05       0  5002.9     .15       0
Bank Sta=4969.9,5079.9
XS Rating Curve= 0 ,0
Exp/Cntr=0.3,0.1

Type RM Length L Ch R = 1 ,9371    ,505,505,505
BEGIN DESCRIPTION:
EAST FORK ROCKY CREEK 20.0
END DESCRIPTION:
XS GIS Cut Line= 3
      2870262.31     10045287.74      2870288.35     10045834.59
      2871343.05     10046081.99
#Sta/Elev= 30
    4364 1452.41  4386.7 1449.69  4480.1 1443.65  4520.2 1437.56  4560.2 1435.87
  4650.3 1434.16  4970.7 1432.13  4975.9 1430.07  4983.5 1421.73  4990.8 1416.74
  4993.5 1416.24  4996.8 1416.74  5018.3 1417.52  5034.8 1421.53  5060.8 1424.98
  5158.1 1424.29  5193.2 1425.03  5278.1 1429.03  5325.7 1428.86    5363  1432.4
  5368.1 1433.75  5384.1 1440.82  5415.7 1445.02  5476.5 1447.82  5527.9 1448.97
  5548.4 1450.83  5675.4 1453.04  5807.9 1457.38  5928.5 1463.84  5994.8 1465.09
#Mann= 3 ,-1 , 0
    4364     .15       0  4990.8     .05       0  4996.8     .15       0
Bank Sta=4983.5,5060.8
XS Rating Curve= 0 ,0
Exp/Cntr=0.3,0.1

Type RM Length L Ch R = 1 ,8866    ,681,681,681
BEGIN DESCRIPTION:
EAST FORK ROCKY CREEK 19.0
END DESCRIPTION:
XS GIS Cut Line= 3
      2870158.14     10045287.69      2870171.16     10046433.54
      2870613.67     10046863.04
#Sta/Elev= 30
  4039.9 1446.45    4106 1443.76    4146 1439.33    4216 1436.64    4366 1433.36
    4526 1432.35    4616  1430.4    4726 1425.26    4846 1422.51    4916 1423.61
    4946 1421.69    4966 1417.86    4986 1416.25    4993 1414.34  4995.8 1413.84
    4999 1414.34    5006 1414.62    5016  1417.5    5026 1422.61    5036  1426.6
    5056 1428.78  5185.8 1428.86  5325.5 1431.62  5438.6 1434.97  5466.9 1437.48
  5502.4  1442.2  5565.9 1443.95  5608.4 1447.45  5693.3 1449.49  5802.5 1449.46
#Mann= 3 ,-1 , 0
  4039.9     .15       0    4993     .05       0    4999     .15       0
Bank Sta=4946,5026
XS Rating Curve= 0 ,0
Exp/Cntr=0.3,0.1

Type RM Length L Ch R = 1 ,8185    ,480,480,480
BEGIN DESCRIPTION:
EAST FORK ROCKY CREEK 18.0
END DESCRIPTION:
XS GIS Cut Line= 3
      2868484.59      10046160.8      2869369.52     10046190.62
      2870353.72     10046886.52
#Sta/Elev= 30
  3903.3 1509.34  3997.2 1504.37  4057.3 1497.99  4067.3 1495.72  4087.3 1487.03
  4117.3 1480.97  4207.3 1478.63  4237.4 1474.66  4617.6 1455.67  4732.6 1447.33
  4819.1 1435.58  4890.5 1429.53  4905.2 1423.81  4926.2 1419.56  4934.4 1415.41
  4955.7 1411.02  4994.5 1408.94  4997.3 1408.44  5000.5 1408.94  5012.3 1410.77
  5027.1 1416.66  5041.9 1418.61  5134.2 1419.57  5163.7 1423.85  5214.2 1425.85
  5558.9 1425.24    5773 1430.27  5838.3 1433.32  5894.9 1441.48  5994.1 1446.58
#Mann= 3 ,-1 , 0
  3903.3     .15       0  4994.5     .05       0  5000.5     .15       0
Bank Sta=4934.4,5027.1
XS Rating Curve= 0 ,0
Exp/Cntr=0.3,0.1

Type RM Length L Ch R = 1 ,7705    ,363,363,363
BEGIN DESCRIPTION:
EAST FORK ROCKY CREEK 16.0
END DESCRIPTION:
XS GIS Cut Line= 2
      2868872.38      10046618.2      2870174.18     10046916.32
#Sta/Elev= 30
  4438.1 1467.25  4621.8 1462.69  4741.8 1456.77  4750.5 1456.24  4762.4 1452.92
  4782.9 1450.48  4841.5 1448.06  4884.4 1443.84  4916.2 1437.61  4926.5 1431.73
  4932.5 1420.85  4937.6 1419.98    4947 1411.15  4957.3  1407.9  4967.5 1406.52
  4980.5 1406.62  4995.3 1404.42  4998.1 1403.92  5001.3 1404.42  5008.6 1406.78
  5018.3 1412.39  5023.4 1412.53  5029.1  1414.4  5100.9 1415.04  5213.8 1422.55
  5449.7 1423.12    5501  1426.4  5583.1 1426.34  5685.7 1428.47  5773.6 1438.73
#Mann= 3 ,-1 , 0
  4438.1     .15       0  4995.3     .05       0  5001.3     .15       0
Bank Sta=4947,5018.3
XS Rating Curve= 0 ,0
Exp/Cntr=0.3,0.1

Type RM Length L Ch R = 1 ,7342    ,477,477,477
BEGIN DESCRIPTION:
EAST FORK ROCKY CREEK 15.0
END DESCRIPTION:
XS GIS Cut Line= 2
      2868733.15      10047055.7      2870114.38     10047155.07
#Sta/Elev= 30
  4336.3 1451.14  4382.7 1452.04  4431.9 1455.22    4472 1456.21  4522.5 1455.51
  4542.1 1453.34  4562.2  1448.7  4602.3 1442.36  4662.5    1434    4863 1421.45
    4883 1418.83  4903.1 1412.76  4953.2 1410.06  4983.3 1405.32  5000.3 1403.92
  5003.1 1403.42  5006.3 1403.92  5033.4 1405.65  5043.4 1409.55  5053.5 1412.66
  5063.5 1412.98  5123.6 1410.48  5143.7 1411.16  5173.8 1418.85  5183.8  1419.8
  5394.3 1420.27  5414.4 1421.68  5444.5  1426.2  5636.4 1433.12  5721.1 1438.46
#Mann= 3 ,-1 , 0
  4336.3     .15       0  5000.3     .05       0  5006.3     .15       0
Bank Sta=4953.2,5043.4
XS Rating Curve= 0 ,0
Exp/Cntr=0.3,0.1

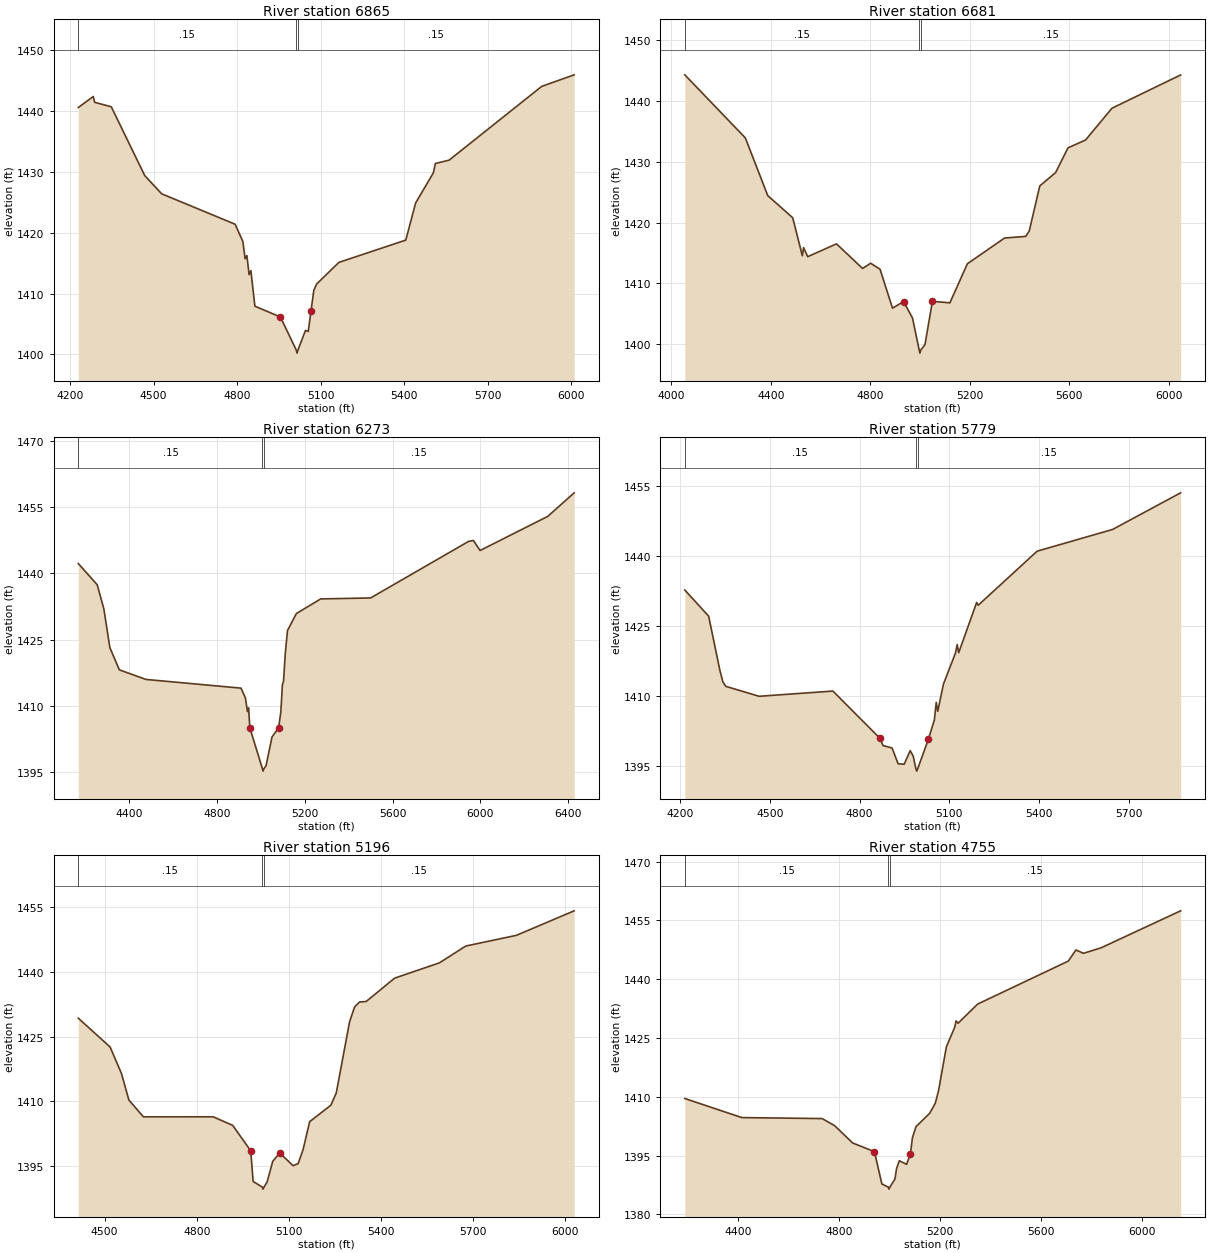
Type RM Length L Ch R = 1 ,6865    ,184,184,184
BEGIN DESCRIPTION:
Mapping XS eb50cb11
END DESCRIPTION:
XS GIS Cut Line= 6
      2868813.43     10047299.11      2869174.53      10047361.6
      2869410.64      10047549.1      2869882.86      10047549.1
      2870341.19      10047111.6      2870341.19     10047104.61
#Sta/Elev= 30
  4229.6 1440.56  4283.2 1442.36  4288.3 1441.41    4348 1440.67  4468.1 1429.37
    4529 1426.38  4792.6 1421.39  4820.6 1418.54  4828.6 1415.72    4835 1416.24
    4843  1413.1  4849.4 1413.76  4863.8 1407.93  4955.4 1406.15  5012.4 1400.72
  5015.1 1400.22  5018.4 1400.72  5045.4 1403.95  5055.4 1403.78  5065.4 1407.19
  5075.4 1410.53  5085.4 1411.56  5165.4 1415.12  5405.7 1418.78  5441.2 1424.89
  5504.8 1429.83    5512 1431.36  5561.4 1431.91  5893.8 1444.02  6010.4 1445.92
#Mann= 3 ,-1 , 0
  4229.6     .15       0  5012.4     .05       0  5018.4     .15       0
Bank Sta=4955.4,5065.4
XS Rating Curve= 0 ,0
Exp/Cntr=0.3,0.1

Type RM Length L Ch R = 1 ,6681    ,408,408,408
BEGIN DESCRIPTION:
EAST FORK ROCKY CREEK 14.0
END DESCRIPTION:
XS GIS Cut Line= 3
      2868625.89     10047653.27      2869834.25     10047743.55
      2870368.98     10047174.09
#Sta/Elev= 30
  4054.7 1444.32    4298 1433.94  4388.2 1424.43  4488.5 1420.78  4527.1 1414.54
  4532.1 1415.87  4548.7 1414.38  4664.4 1416.49  4769.3 1412.44  4801.7  1413.3
  4839.5 1412.31  4889.6  1405.9    4934 1406.99  4969.8 1404.29  4996.9    1399
  4999.7  1398.5  5002.9    1399    5020 1399.89    5050 1407.03  5120.2 1406.78
  5190.4 1413.21    5340 1417.45    5425 1417.72  5439.1  1418.6  5481.6 1426.04
  5545.1 1428.22  5594.9  1432.3  5665.3 1433.58  5771.7 1438.82  6047.6  1444.3
#Mann= 3 ,-1 , 0
  4054.7     .15       0  4996.9     .05       0  5002.9     .15       0
Bank Sta=4934,5050
XS Rating Curve= 0 ,0
Exp/Cntr=0.3,0.1

Type RM Length L Ch R = 1 ,6273    ,494,494,494
BEGIN DESCRIPTION:
EAST FORK ROCKY CREEK 13.0
END DESCRIPTION:
XS GIS Cut Line= 3
      2868743.08      10048020.2      2869906.46     10048169.35
      2870851.11     10048706.31
#Sta/Elev= 30
  4167.7 1442.24  4253.8 1437.43    4284 1431.96  4311.3 1423.17  4354.6 1418.11
  4475.7 1415.93  4909.1 1413.95  4929.3  1411.7  4938.4 1408.62  4943.5 1409.47
  4949.4 1404.93  5006.9  1395.6  5009.7  1395.1  5012.9  1395.6  5023.1 1396.33
  5050.3 1402.86  5080.5 1404.93  5090.6  1408.6  5097.7 1414.73  5102.8 1415.51
  5110.7 1421.76  5120.8 1427.03  5161.2 1430.89  5272.1 1434.22  5499.7 1434.44
  5946.6  1447.3  5968.2 1447.49  5998.6 1445.22    6307 1452.97  6427.2 1458.32
#Mann= 3 ,-1 , 0
  4167.7     .15       0  5006.9     .05       0  5012.9     .15       0
Bank Sta=4949.4,5080.5
XS Rating Curve= 0 ,0
Exp/Cntr=0.3,0.1

Type RM Length L Ch R = 1 ,5779    ,583,583,583
BEGIN DESCRIPTION:
EAST FORK ROCKY CREEK 12.0
END DESCRIPTION:
XS GIS Cut Line= 2
      2868822.59     10048487.54      2870463.33     10048726.19
#Sta/Elev= 30
  4215.8 1432.74  4295.6 1427.12  4332.9 1415.56    4343 1413.03  4353.1 1412.04
  4464.3 1409.91  4711.1 1411.03  4868.5 1400.87  4878.6 1399.33  4908.9  1398.8
  4929.1 1395.41  4949.3 1395.31  4969.5 1398.23  4979.6 1397.06  4988.6 1394.33
  4991.3 1393.83  4994.6 1394.33  5030.2 1400.65  5050.4 1404.84  5056.6 1408.61
  5061.7 1406.68  5080.7 1412.53  5121.1 1419.23  5126.7 1421.02  5131.8 1419.28
  5191.8 1430.07  5196.8 1429.46  5393.9 1441.08  5646.6 1445.76  5873.8 1453.62
#Mann= 3 ,-1 , 0
  4215.8     .15       0  4988.6     .05       0  4994.6     .15       0
Bank Sta=4868.5,5030.2
XS Rating Curve= 0 ,0
Exp/Cntr=0.3,0.1

Type RM Length L Ch R = 1 ,5196    ,441,441,441
BEGIN DESCRIPTION:
EAST FORK ROCKY CREEK 11.0
END DESCRIPTION:
XS GIS Cut Line= 2
      2868812.72     10048875.34      2870303.87     10049491.68
#Sta/Elev= 30
  4414.7 1429.25  4518.3 1422.56  4555.3 1416.39  4579.2 1410.28  4626.5 1406.38
  4853.7 1406.39  4917.1  1404.4  4975.7 1398.51  4983.6 1391.39    5013 1390.12
  5015.8 1389.62    5019 1390.12    5029 1391.28  5047.5 1396.09  5070.1    1398
  5113.4 1395.06    5130 1395.53  5145.9 1398.74  5167.5 1405.26  5236.5 1409.08
  5254.1 1411.91  5297.4 1428.43  5313.6 1431.85  5329.8 1433.01  5351.5 1433.13
    5444 1438.54  5589.5 1442.08  5675.4 1445.98  5840.5 1448.47  6028.2 1454.15
#Mann= 3 ,-1 , 0
  4414.7     .15       0    5013     .05       0    5019     .15       0
Bank Sta=4975.7,5070.1
XS Rating Curve= 0 ,0
Exp/Cntr=0.3,0.1

Type RM Length L Ch R = 1 ,4755    ,496,496,496
BEGIN DESCRIPTION:
EAST FORK ROCKY CREEK 10.0
END DESCRIPTION:
XS GIS Cut Line= 4
      2868574.07      10049094.1        2869111.     10049452.05
      2869508.73     10049631.03      2870393.58     10049631.03
#Sta/Elev= 30
  4187.7 1409.56  4413.9 1404.69  4732.3 1404.44  4781.9 1402.63  4853.5 1398.21
  4939.9    1396  4969.2 1387.77  4994.8 1386.94  4997.6 1386.44  5000.8 1386.94
    5021    1389  5027.6 1391.72  5038.6 1393.68  5067.3 1392.76  5082.4 1395.42
  5090.4 1399.55  5104.4 1402.36  5159.2 1405.82  5181.1 1408.36    5194 1411.55
    5225 1422.72  5257.9  1427.7  5263.5 1429.35  5271.5 1428.76  5348.9 1433.64
  5708.9 1444.63  5738.9 1447.46  5768.9  1446.6  5838.9 1448.01    6154 1457.44
#Mann= 3 ,-1 , 0
  4187.7     .15       0  4994.8     .05       0  5000.8     .15       0
Bank Sta=4939.9,5082.4
XS Rating Curve= 0 ,0
Exp/Cntr=0.3,0.1

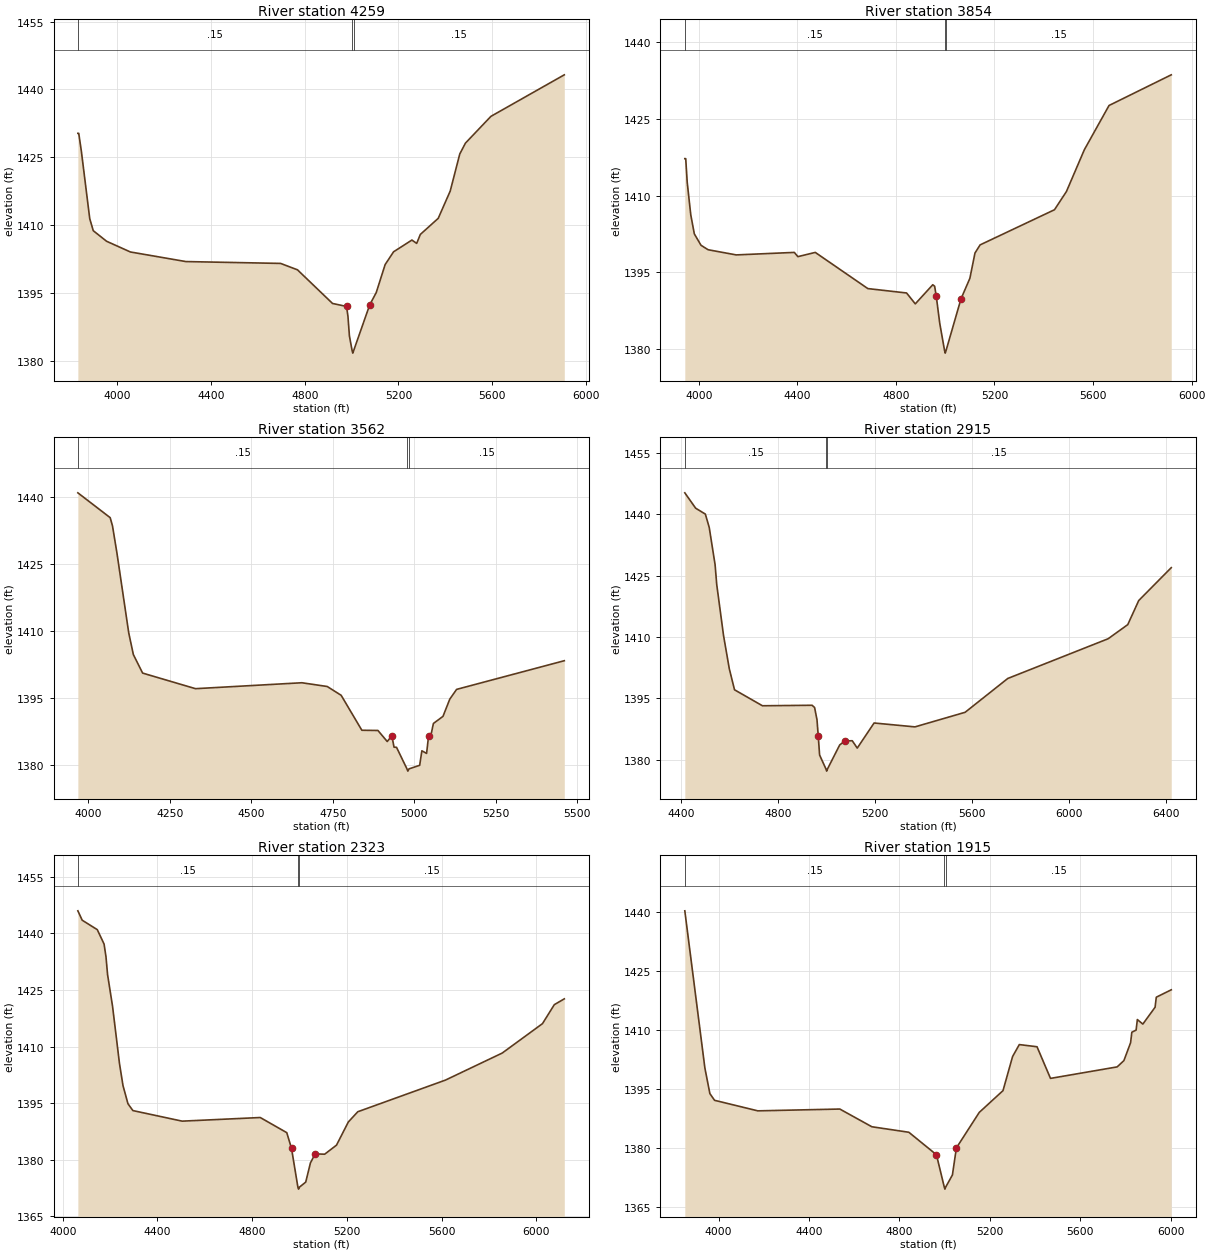
Type RM Length L Ch R = 1 ,4259    ,405,405,405
BEGIN DESCRIPTION:
EAST FORK ROCKY CREEK 9.0
END DESCRIPTION:
XS GIS Cut Line= 3
      2868037.15     10049273.09      2869170.66     10050038.71
      2869865.05      10050187.5
#Sta/Elev= 30
  3830.7 1430.28  3834.5 1430.28  3845.6 1426.35  3881.5 1411.39  3896.5 1408.74
  3953.5  1406.4  4055.3 1404.03  4292.2 1401.91  4696.7  1401.5  4768.7 1400.09
  4918.6 1392.64  4978.4 1391.98  4984.5  1389.8  4990.8 1385.43  5002.5 1382.15
  5005.2 1381.65  5008.5 1382.15  5077.4 1392.32  5105.4 1395.06  5143.3 1401.24
  5179.3 1404.07  5257.7 1406.67  5278.1 1405.93  5293.8 1407.92  5370.2 1411.48
  5421.3 1417.51  5462.2 1425.72  5486.4 1428.12  5595.2 1434.04  5908.7 1443.23
#Mann= 3 ,-1 , 0
  3830.7     .15       0  5002.5     .05       0  5008.5     .15       0
Bank Sta=4978.4,5077.4
XS Rating Curve= 0 ,0
Exp/Cntr=0.3,0.1

Type RM Length L Ch R = 1 ,3854    ,292,292,292
BEGIN DESCRIPTION:
EAST FORK ROCKY CREEK 8.0
END DESCRIPTION:
XS GIS Cut Line= 3
      2867927.72     10049591.24       2868951.9     10050396.67
      2869598.23     10050575.65
#Sta/Elev= 30
  3943.6 1417.25  3947.3 1417.25  3953.3 1412.64  3967.8 1406.25  3982.2 1402.53
  4009.4 1400.29  4038.3 1399.42  4152.2 1398.41    4388  1398.9  4402.4 1398.07
  4472.9  1398.9  4686.2 1391.82  4843.4 1390.96  4878.7 1388.83  4949.6 1392.57
  4957.3 1392.28  4963.7 1390.35  4978.1 1384.98  4997.5 1379.69  5000.2 1379.19
  5003.5 1379.69  5064.1  1389.8  5100.1 1393.82  5120.9 1398.78  5141.7 1400.37
  5443.5 1407.25    5492 1410.82  5564.6 1418.99  5664.8 1427.65  5917.2 1433.65
#Mann= 3 ,-1 , 0
  3943.6     .15       0  4997.5     .05       0  5003.5     .15       0
Bank Sta=4963.7,5064.1
XS Rating Curve= 0 ,0
Exp/Cntr=0.3,0.1

Type RM Length L Ch R = 1 ,3562    ,647,647,647
BEGIN DESCRIPTION:
EAST FORK ROCKY CREEK 7.0
END DESCRIPTION:
XS GIS Cut Line= 3
      2867718.48     10049653.74      2868518.47     10050353.73
      2868868.46     10050603.72
#Sta/Elev= 30
  3967.4 1441.04  4066.6 1435.46  4073.7 1433.62  4087.4 1427.49  4123.5 1409.61
  4137.7 1404.72  4166.2 1400.55  4328.5 1397.05    4655 1398.38  4732.8 1397.54
  4775.6 1395.56  4839.1 1387.71  4888.5 1387.66    4917 1385.18  4931.2 1386.46
  4937.9  1383.9  4945.5 1383.88  4977.6 1379.03  4980.3 1378.53  4983.6 1379.03
  5016.6 1379.84  5023.3  1383.1  5037.8 1382.51  5043.9 1386.42  5052.5 1387.08
  5058.7 1389.23  5088.2 1390.84    5109  1394.7  5129.9 1396.89  5460.5 1403.33
#Mann= 3 ,-1 , 0
  3967.4     .15       0  4977.6     .05       0  4983.6     .15       0
Bank Sta=4931.2,5043.9
XS Rating Curve= 0 ,0
Exp/Cntr=0.3,0.1

Type RM Length L Ch R = 1 ,2915    ,592,592,592
BEGIN DESCRIPTION:
EAST FORK ROCKY CREEK 6.0
END DESCRIPTION:
XS GIS Cut Line= 2
      2867341.11     10050337.02      2869280.06     10050854.07
#Sta/Elev= 30
  4414.9  1445.3  4459.6 1441.54  4499.7 1440.09  4515.7 1436.81  4539.8 1427.72
  4546.7 1422.79  4574.7 1410.36  4598.5 1402.22    4620 1397.09  4735.1 1393.18
    4940  1393.3  4950.3 1392.75  4960.2 1389.77  4965.4 1385.72    4971 1381.12
  4997.3 1377.68  5000.1 1377.18  5003.3 1377.68  5053.8 1383.58  5074.5 1384.55
  5105.6 1384.62  5126.3 1382.82  5195.7 1388.96  5364.3 1388.01  5571.3 1391.58
  5747.2 1399.86  6161.2 1409.58  6242.2 1413.04  6287.5 1418.94  6421.6 1426.98
#Mann= 3 ,-1 , 0
  4414.9     .15       0  4997.3     .05       0  5003.3     .15       0
Bank Sta=4965.4,5074.5
XS Rating Curve= 0 ,0
Exp/Cntr=0.3,0.1

Type RM Length L Ch R = 1 ,2323    ,408,408,408
BEGIN DESCRIPTION:
EAST FORK ROCKY CREEK 4.0
END DESCRIPTION:
XS GIS Cut Line= 3
      2867271.45     10050515.97      2867917.79     10050973.38
      2869180.62     10050993.27
#Sta/Elev= 30
  4063.7 1445.96  4082.1 1443.47  4145.8 1440.97  4174.4 1437.16  4182.5 1433.79
  4189.2 1429.07  4210.1 1420.73  4239.6 1405.47  4254.4 1399.65  4275.3 1394.85
  4296.2 1393.04  4504.2 1390.24  4834.1  1391.2  4946.2 1387.19  4966.2 1383.02
  4993.2 1372.73    4996 1372.23  4999.2 1372.73  5026.2 1374.09  5046.2 1379.19
  5066.2 1381.57  5106.2 1381.48  5156.2 1383.88  5206.2 1390.02  5246.2 1392.73
  5616.3 1401.11  5856.3 1408.28  6026.3 1416.07  6076.3  1421.1  6118.5 1422.64
#Mann= 3 ,-1 , 0
  4063.7     .15       0  4993.2     .05       0  4999.2     .15       0
Bank Sta=4966.2,5066.2
XS Rating Curve= 0 ,0
Exp/Cntr=0.3,0.1

Type RM Length L Ch R = 1 ,1915    ,656,656,656
BEGIN DESCRIPTION:
EAST FORK ROCKY CREEK 3.0
END DESCRIPTION:
XS GIS Cut Line= 4
      2867281.43     10050694.98      2868037.11     10051331.34
      2868385.13     10051381.06       2869140.8     10051082.77
#Sta/Elev= 30
  3850.4 1440.27  3939.2 1400.33  3961.3 1393.82  3982.1 1392.12  4173.4 1389.44
  4536.1  1389.9  4677.9  1385.4  4841.5    1384  4963.6 1378.29  4998.3 1370.05
  5001.1 1369.55  5004.3 1370.05  5034.3 1373.16  5051.8 1380.02  5152.9 1389.04
    5258 1394.58  5300.4 1403.24  5330.1 1406.28  5408.5 1405.73  5468.1 1397.69
    5763 1400.61  5792.8 1402.21  5822.5 1406.77  5827.9 1409.42  5846.9 1409.97
  5852.3 1412.64  5876.6 1411.49  5930.8 1415.77  5936.1 1418.32  6002.3  1420.2
#Mann= 3 ,-1 , 0
  3850.4     .15       0  4998.3     .05       0  5004.3     .15       0
Bank Sta=4963.6,5051.8
XS Rating Curve= 0 ,0
Exp/Cntr=0.3,0.1

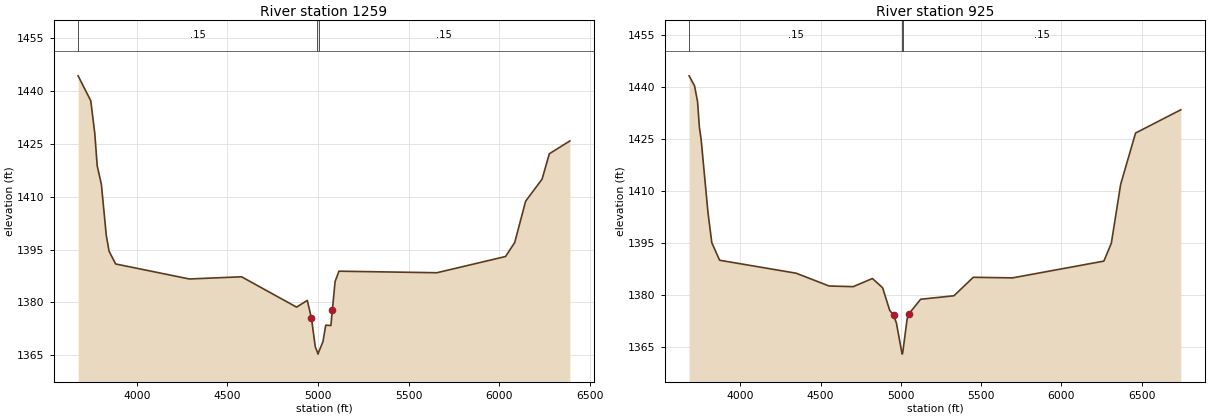
Type RM Length L Ch R = 1 ,1259    ,334,334,334
BEGIN DESCRIPTION:
EAST FORK ROCKY CREEK 2.0
END DESCRIPTION:
XS GIS Cut Line= 4
      2867172.03     10050724.78      2867977.45     10051997.55
      2868514.39     10052236.19      2869130.89     10052166.59
#Sta/Elev= 30
  3676.2 1444.33    3746 1437.25  3768.1 1428.04  3781.5 1418.79  3804.5 1413.55
  3831.6 1399.05  3846.9 1394.55  3883.3 1390.93  4290.2 1386.67  4578.4 1387.29
    4882 1378.68  4941.2 1380.59  4964.1 1375.54  4985.3 1367.43  4997.4 1365.84
  5000.1 1365.34  5003.4 1365.84  5027.7 1368.89  5042.9 1373.55  5071.4 1373.46
  5079.4  1377.8  5094.6 1385.93  5115.8 1388.88  5656.3 1388.44  6035.7 1393.05
  6086.1 1397.03  6146.4 1408.75    6237    1415  6277.2 1422.21  6390.4 1425.85
#Mann= 3 ,-1 , 0
  3676.2     .15       0  4997.4     .05       0  5003.4     .15       0
Bank Sta=4964.1,5079.4
XS Rating Curve= 0 ,0
Exp/Cntr=0.3,0.1

Type RM Length L Ch R = 1 ,925     ,0,0,0
BEGIN DESCRIPTION:
EAST FORK ROCKY CREEK 1.0
END DESCRIPTION:
XS GIS Cut Line= 3
      2867122.31      10050804.3      2867708.98     10052275.96
      2869061.24     10052872.55
#Sta/Elev= 30
  3681.7  1443.3  3715.3 1440.45  3734.2  1435.9  3745.7 1428.43  3756.4    1425
  3799.5 1403.66  3823.1 1395.06  3871.7 1389.99  4348.5 1386.24  4553.7 1382.54
  4703.8 1382.36  4823.3 1384.71  4886.8 1382.04  4931.1  1375.5  4955.4 1374.08
  4972.9 1371.81  5006.3 1363.35  5009.1 1362.85  5012.3 1363.35    5039 1372.87
  5048.3 1374.38  5123.6 1378.71    5331 1379.72  5451.5 1385.06  5695.6 1384.89
  6264.7 1389.74  6311.3 1394.92  6369.3 1411.94  6462.1 1426.76    6744 1433.49
#Mann= 3 ,-1 , 0
  3681.7     .15       0  5006.3     .05       0  5012.3     .15       0
Bank Sta=4955.4,5048.3
XS Rating Curve= 0 ,0
Exp/Cntr=0.3,0.1

Chan Stop Cuts=-1
Use User Specified Reach Order=0
Composite Channel Slope=5