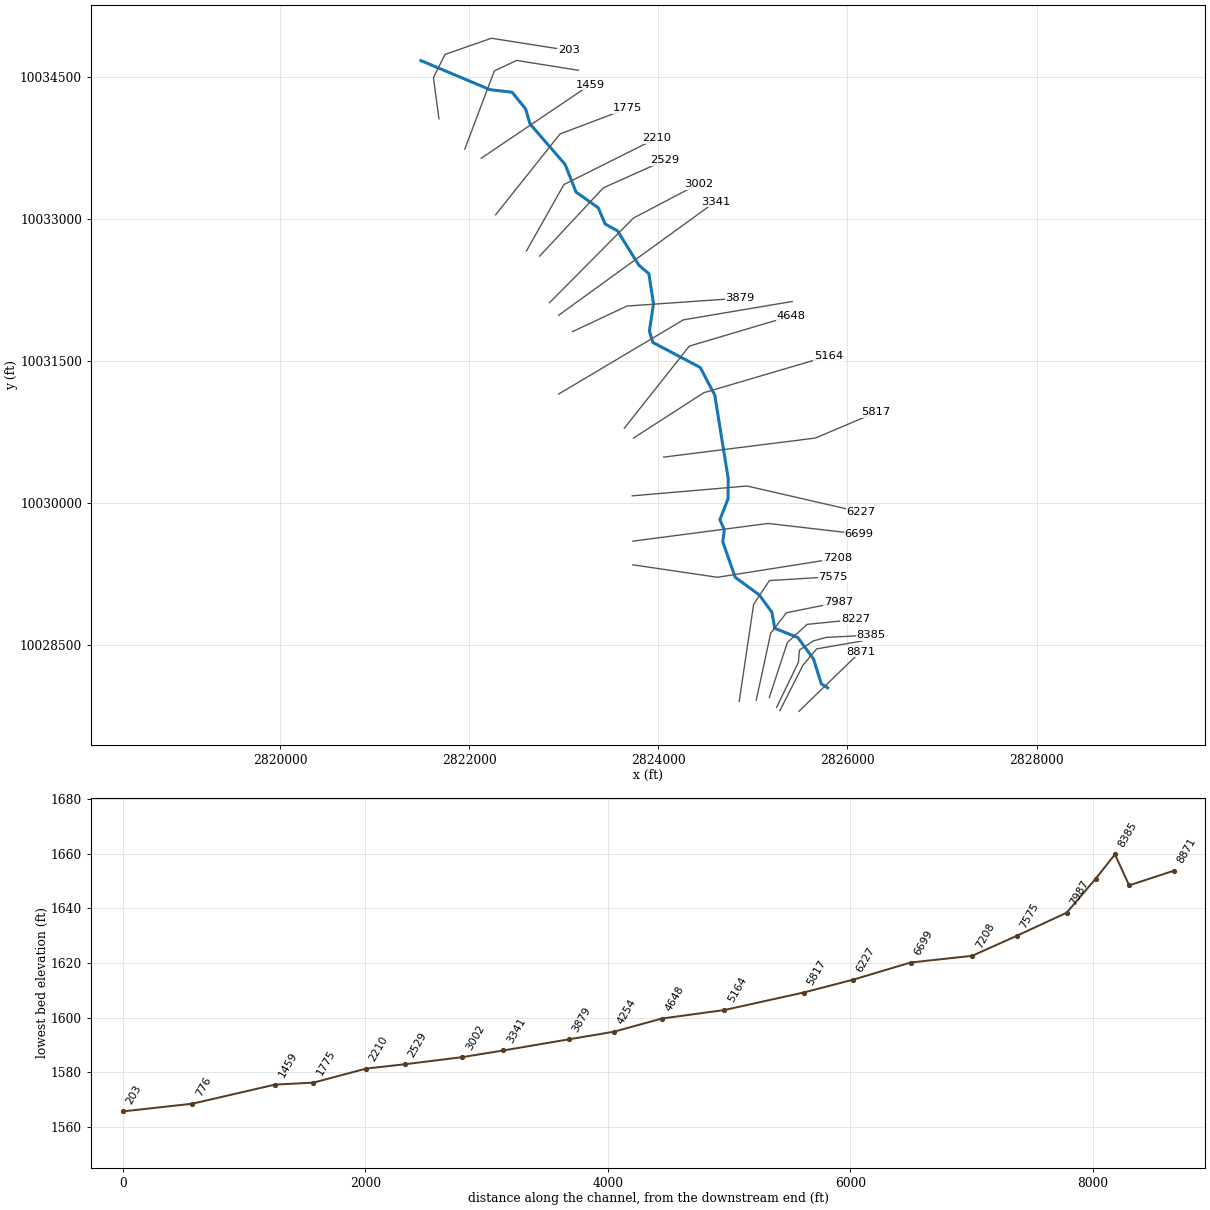
--- EAST FORK THREEMILE CREEK.prj (project) ---

Proj Title=EAST FORK THREEMILE CREEK Base Level Engineering
Current Plan=p01
Default Exp/Contr=0.3,0.1
English Units
Geom File=g01
Flow File=f01
Plan File=p01
Y Axis Title=Elevation
X Axis Title(PF)=Main Channel Distance
X Axis Title(XS)=Station
BEGIN DESCRIPTION:
EAST FORK THREEMILE CREEK
END DESCRIPTION:
DSS Export Rating Curves= 0
DSS Export Rating Curve Sorted= 0
DSS Export Volume Flow Curves= 0
DXF OffsetX= 0
DXF OffsetY= 0
DXF ScaleX= 1
DXF ScaleY= 10

--- EAST FORK THREEMILE CREEK.p01 (plan) ---

Plan Title=Multiple Run
Short Identifier=Multiple
Geom File=g01
Flow File=f01
Subcritical Flow
K Sum by GR= 0
Std Step Tol= 0.01
Critical Tol= 0.01
Num of Std Step Trials= 20
Max Error Tol= 0.3
Flow Tol Ratio= 0.001
Split Flow NTrial= 30
Split Flow Tol= 0.02
Split Flow Ratio= 0.02
Log Output Level= 0
Friction Slope Method= 1
Unsteady Friction Slope Method= 2
Unsteady Bridges Friction Slope Method= 1
Parabolic Critical Depth
Global Vel Dist=  1 , 1 , 1
Global Log Level= 0
CheckData=True
Encroach Param= -1, 0, 0, 0
BEGIN DESCRIPTION:
Multiple Run
END DESCRIPTION:

--- EAST FORK THREEMILE CREEK.f01 (steady flow) ---

Flow Title=Multiple
Program Version=4.10
Number of Profiles= 7
Profile Names=10-year,25-year,50-year,1pct_min,100-year,1pct_plu,500-year
River Rch & RM=EAST FORK THREEM,Reach-1         ,8871
     830    1200    1522    1413    1911    2585    3026
River Rch & RM=EAST FORK THREEM,Reach-1         ,7208
    2356    3581    4692    4486    6066    8204   10188
Boundary for River Rch & Prof#=EAST FORK THREEM,Reach-1         , 1
Up Type= 0
Dn Type= 1
Dn Known WS=1572.72
Boundary for River Rch & Prof#=EAST FORK THREEM,Reach-1         , 2
Up Type= 0
Dn Type= 1
Dn Known WS=1573.5
Boundary for River Rch & Prof#=EAST FORK THREEM,Reach-1         , 3
Up Type= 0
Dn Type= 1
Dn Known WS=1574
Boundary for River Rch & Prof#=EAST FORK THREEM,Reach-1         , 4
Up Type= 0
Dn Type= 1
Dn Known WS=1573.92
Boundary for River Rch & Prof#=EAST FORK THREEM,Reach-1         , 5
Up Type= 0
Dn Type= 1
Dn Known WS=1574.68
Boundary for River Rch & Prof#=EAST FORK THREEM,Reach-1         , 6
Up Type= 0
Dn Type= 1
Dn Known WS=1575.39
Boundary for River Rch & Prof#=EAST FORK THREEM,Reach-1         , 7
Up Type= 0
Dn Type= 1
Dn Known WS=1576.03
DSS Import GetInterval= 0
DSS Import GetPeak= 0
DSS Import FillOption= 0

--- EAST FORK THREEMILE CREEK.g01 (geometry) ---

Geom Title=Existing Conditions
Program Version=4.10

River Reach=EAST FORK THREEM,Reach-1
Reach XY= 30
      2825789.84     10028042.17      2825722.88     10028084.38
      2825641.34     10028346.15      2825474.83     10028573.59
      2825231.96     10028670.65      2825199.66     10028842.67
      2825067.28     10029023.99      2824812.61     10029210.74
      2824681.29     10029585.07      2824697.61     10029713.23
      2824650.57     10029819.27      2824736.64     10030039.54
      2824738.42     10030254.73      2824596.27     10031137.71
      2824442.41     10031429.44      2823940.88     10031694.23
      2823905.16     10031813.35      2823948.08     10032103.54
      2823899.08     10032421.14      2823793.42     10032510.95
      2823567.85     10032873.59      2823435.84     10032947.04
      2823364.28     10033117.56      2823129.16      10033283.9
      2823013.04     10033576.44      2822641.27     10034005.53
      2822596.02     10034162.71       2822452.5     10034339.71
      2822219.72     10034366.51      2821488.47     10034673.73

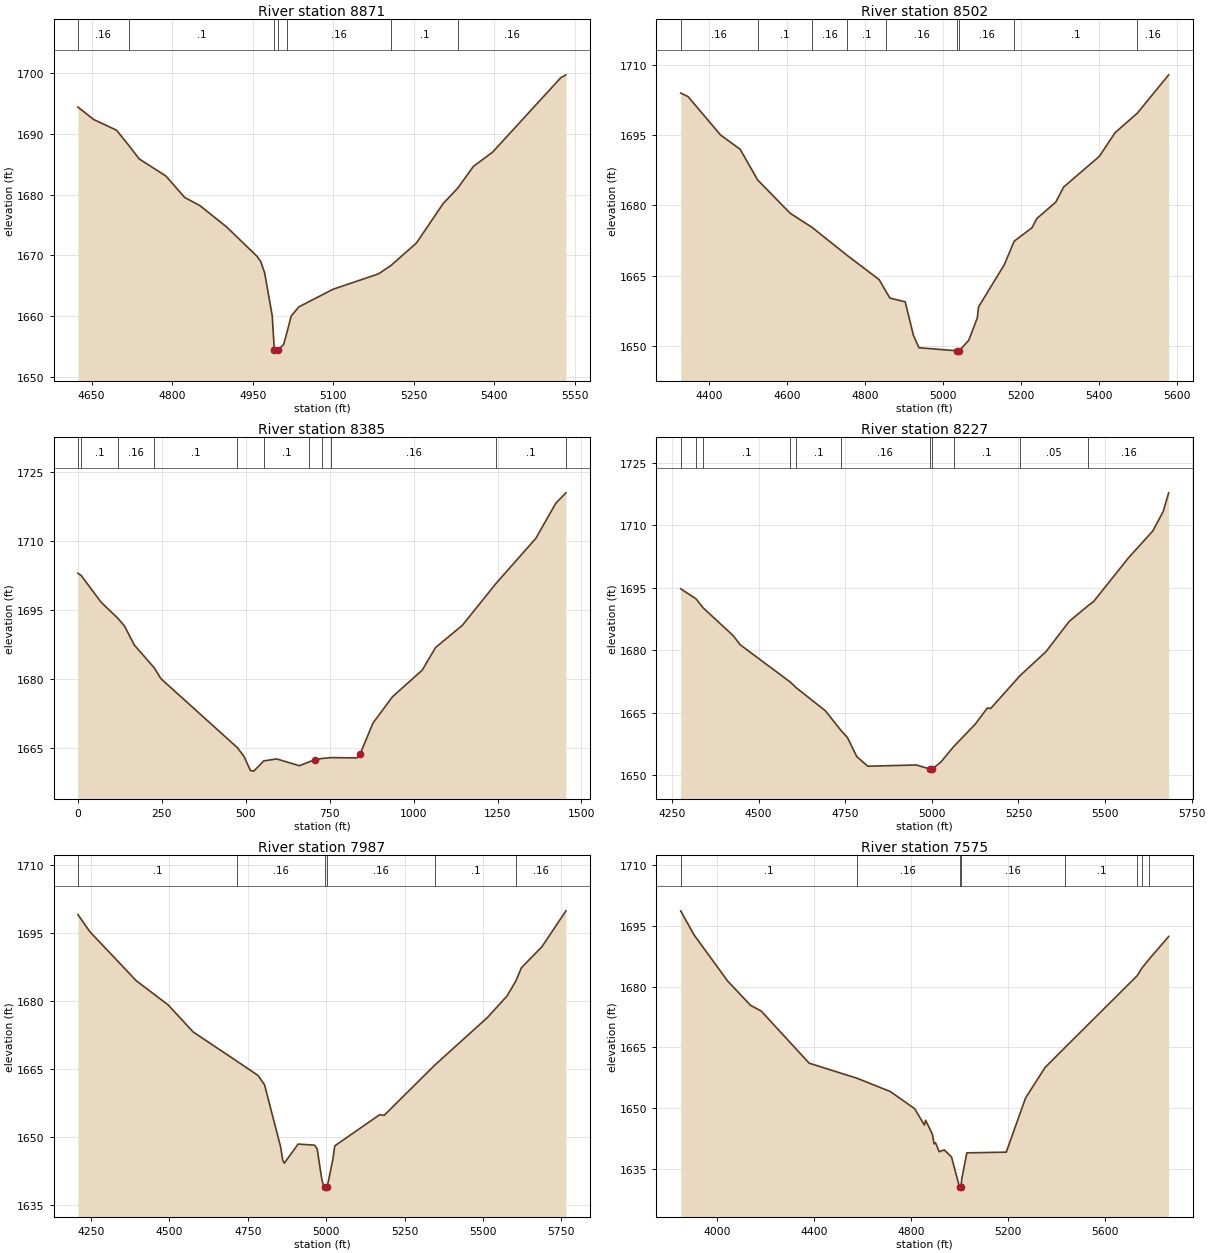
Type RM Length L Ch R = 1 ,8871    ,369,369,369
BEGIN DESCRIPTION:
EAST FORK THREEMILE CREEK 19.0
END DESCRIPTION:
XS GIS Cut Line= 2
      2825486.81     10027793.97      2826139.62     10028425.95
#Sta/Elev= 30
  4624.7 1694.44  4654.1 1692.39  4696.5 1690.63    4719 1688.17  4738.7  1685.9
  4788.4 1683.08  4823.6 1679.53  4851.9 1678.19  4901.6 1674.67  4958.2 1669.83
  4965.1 1668.96  4972.3 1667.12  4986.4 1660.07  4990.4 1654.37  4993.2 1653.87
  4996.4 1654.37  5007.6 1655.28  5014.2  1657.4  5021.7 1659.98  5035.9 1661.49
  5099.6  1664.4  5184.3 1666.94  5207.5 1668.32    5255 1672.03  5304.7 1678.53
  5331.7 1681.06  5361.2 1684.68  5396.5 1686.99  5523.8 1699.29  5533.3 1699.76
#Mann= 7 ,-1 , 0
  4624.7     .16       0    4719      .1       0  4990.4     .07       0
  4996.4      .1       0  5014.2     .16       0  5207.5      .1       0
  5331.7     .16       0
Bank Sta=4990.4,4996.4
XS Rating Curve= 0 ,0
Exp/Cntr=0.3,0.1

Type RM Length L Ch R = 1 ,8502    ,117,117,117
BEGIN DESCRIPTION:
Mapping XS fe3a963e
END DESCRIPTION:
XS GIS Cut Line= 4
      2825285.42     10027800.93      2825528.47     10028280.08
       2825674.3     10028453.69      2826153.51     10028537.03
#Sta/Elev= 30
  4327.3 1703.97  4346.2 1703.22  4429.6 1695.02  4479.8 1691.97  4524.4 1685.45
  4607.7 1678.34  4664.2  1675.3  4753.5 1669.37    4836 1664.16  4854.4 1661.49
  4863.8 1660.22  4902.7 1659.44  4923.5 1652.34  4937.8 1649.64    5035 1648.99
  5037.7 1648.49    5041 1648.99  5065.3 1651.21  5087.4    1656  5090.6 1658.35
  5156.4 1667.33  5181.9 1672.37  5227.5 1675.24  5240.1 1677.21  5288.4  1680.7
  5308.7 1683.93    5400 1690.46  5440.6 1695.53  5497.4 1699.68  5577.7 1707.86
#Mann= 9 ,-1 , 0
  4327.3     .16       0  4524.4      .1       0  4664.2     .16       0
  4753.5      .1       0  4854.4     .16       0    5035     .07       0
    5041     .16       0  5181.9      .1       0  5497.4     .16       0
Bank Sta=5035,5041
XS Rating Curve= 0 ,0
Exp/Cntr=0.3,0.1

Type RM Length L Ch R = 1 ,8385    ,158,158,158
BEGIN DESCRIPTION:
Mapping XS f0af2587
END DESCRIPTION:
XS GIS Cut Line= 6
     2825250.693    10027835.639     2825481.176    10028311.628
     2825491.592    10028440.534     2825638.728     10028538.19
     2825772.842    10028574.649     2826250.693    10028599.528
#Sta/Elev= 30
       01702.8899.8844441702.39569.191121696.578118.61331693.127138.38221691.464
168.03561687.283227.34221682.331247.11111679.984474.45331665.007494.22221663.151
513.99111659.992523.87551659.872553.17471662.087 592.0041662.524659.9554 1661.05
688.46981661.879707.47951662.337726.48921662.617755.00371662.814830.7305 1662.74
840.13141663.505878.94991670.325937.17771676.0511025.5361681.8211065.3711686.747
1145.0421691.562 1244.631700.5991364.1361710.4891423.8891718.1491453.7661720.381
#Mann= 11 ,-1 , 0
       0     .16       09.884444      .1       0118.6133     .16       0
227.3422      .1       0474.4533     .16       0553.1747      .1       0
688.4698     .16       0726.4892     .07       0755.0037     .16       0
 1244.63      .1       01453.766     .05       0
Bank Sta=707.4795,840.1314
XS Rating Curve= 0 ,0
Exp/Cntr=0.3,0.1

Type RM Length L Ch R = 1 ,8227    ,240,240,240
BEGIN DESCRIPTION:
Mapping XS acb46d28
END DESCRIPTION:
XS GIS Cut Line= 4
      2825173.48     10027940.08      2825364.46      10028521.7
      2825572.79     10028712.67      2826084.16     10028764.67
#Sta/Elev= 30
  4274.8 1694.78  4319.2 1692.35  4339.3 1690.23    4426 1683.55    4447 1681.31
  4591.7 1672.34  4607.8 1671.05  4692.9 1665.45  4736.7 1660.85  4756.6    1659
  4783.1 1654.48  4814.9 1652.16    4955 1652.46  4994.6 1651.48  4997.3 1650.98
  5000.6 1651.48  5025.9 1653.15  5062.9 1656.87  5124.6  1662.2  5160.3 1666.16
  5169.6 1666.01  5254.6 1673.92  5329.7  1679.7  5396.4 1686.94  5452.1 1690.79
  5466.8 1691.69  5567.3 1702.18  5637.7 1708.65  5667.8 1713.33  5683.6 1717.82
#Mann= 11 ,-1 , 0
  4274.8      .1       0  4319.2     .16       0  4339.3      .1       0
  4591.7     .16       0  4607.8      .1       0  4736.7     .16       0
  4994.6     .07       0  5000.6     .16       0  5062.9      .1       0
  5254.6     .05       0  5452.1     .16       0
Bank Sta=4994.6,5000.6
XS Rating Curve= 0 ,0
Exp/Cntr=0.3,0.1

Type RM Length L Ch R = 1 ,7987    ,412,412,412
BEGIN DESCRIPTION:
EAST FORK THREEMILE CREEK 18.0
END DESCRIPTION:
XS GIS Cut Line= 4
      2825035.41     10027912.01      2825188.19     10028620.36
      2825354.86     10028835.64      2825903.43     10028946.74
#Sta/Elev= 30
  4208.2 1698.99  4246.1 1695.23  4394.1 1684.42  4496.4 1679.05  4575.8 1673.11
  4714.4 1666.71  4782.8 1663.52  4803.3 1661.48  4854.4 1647.87  4861.3  1644.9
  4866.4 1644.18  4910.6  1648.4  4963.3 1648.15  4971.4  1647.3  4985.9 1640.71
  4992.2 1639.03  4997.3 1638.96  5000.1 1638.46  5003.3 1638.96  5021.2 1644.96
  5027.5    1648  5170.6 1654.87  5185.1 1654.73  5346.1 1665.78  5514.9 1676.33
  5577.3 1681.07  5605.9 1684.47  5622.8 1687.27  5688.3 1691.91  5764.8 1699.82
#Mann= 6 ,-1 , 0
  4208.2      .1       0  4714.4     .16       0  4997.3     .07       0
  5003.3     .16       0  5346.1      .1       0  5605.9     .16       0
Bank Sta=4997.3,5003.3
XS Rating Curve= 0 ,0
Exp/Cntr=0.3,0.1

Type RM Length L Ch R = 1 ,7575    ,367,367,367
BEGIN DESCRIPTION:
EAST FORK THREEMILE CREEK 17.0
END DESCRIPTION:
XS GIS Cut Line= 4
      2824854.87     10027898.18      2825007.64     10028925.92
       2825174.3     10029175.92      2825847.93     10029217.58
#Sta/Elev= 30
    3848 1698.69  3902.8 1692.79  4041.6 1681.38  4136.7 1675.34  4180.4 1673.95
  4378.4 1661.07  4575.4 1657.36    4713 1654.08    4814 1649.83    4854 1645.79
  4859.1 1646.97    4887 1643.55    4894 1641.15    4900 1641.43    4915 1639.21
    4936 1639.65  4966.1 1637.91  4999.1 1630.47  5001.9 1629.97  5005.1 1630.47
  5008.1  1632.4  5029.2 1638.93  5192.1  1639.1  5271.8 1652.49    5352 1659.99
  5436.4 1665.05  5732.8 1682.69  5751.6 1684.53    5782 1686.77  5862.4 1692.36
#Mann= 8 ,-1 , 0
    3848      .1       0  4575.4     .16       0  4999.1     .07       0
  5005.1     .16       0  5436.4      .1       0  5732.8     .16       0
  5751.6      .1       0    5782     .16       0
Bank Sta=4999.1,5005.1
XS Rating Curve= 0 ,0
Exp/Cntr=0.3,0.1

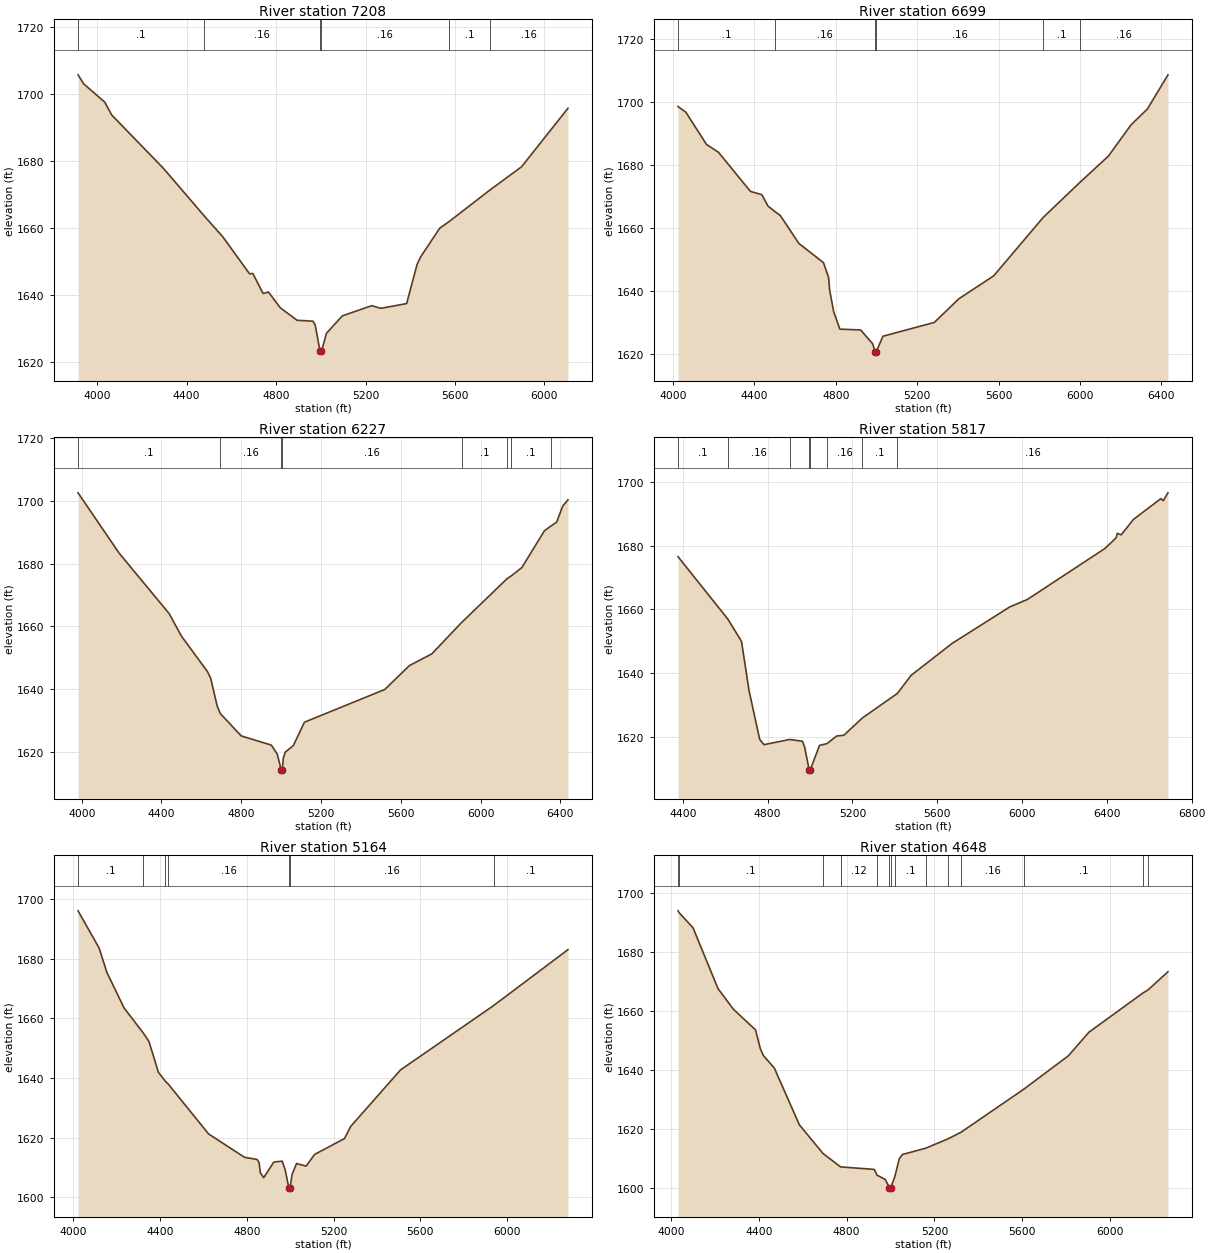
Type RM Length L Ch R = 1 ,7208    ,509,509,509
BEGIN DESCRIPTION:
EAST FORK THREEMILE CREEK 16.0
END DESCRIPTION:
XS GIS Cut Line= 3
      2823729.82     10029342.59      2824625.69     10029210.64
      2825895.02     10029411.79
#Sta/Elev= 30
  3914.6 1705.64  3939.8 1702.96  4034.5 1697.47  4064.8 1693.69  4297.3 1677.69
  4476.6 1663.74  4561.9 1657.34  4681.4 1646.31  4696.3 1646.39  4742.1 1640.42
    4766 1640.87    4819 1636.18  4893.8 1632.45  4964.7 1632.18  4974.8 1631.14
  4996.9 1623.15  4999.6 1622.65  5002.9 1623.15  5025.4 1628.56  5096.3 1633.76
  5227.9  1636.8  5268.4 1636.01  5383.9 1637.42  5430.4 1649.05  5446.2 1651.31
  5531.7 1659.89  5574.5 1661.91  5754.5  1671.2  5897.7 1678.21  6105.3 1695.67
#Mann= 6 ,-1 , 0
  3914.6      .1       0  4476.6     .16       0  4996.9     .07       0
  5002.9     .16       0  5574.5      .1       0  5754.5     .16       0
Bank Sta=4996.9,5002.9
XS Rating Curve= 0 ,0
Exp/Cntr=0.3,0.1

Type RM Length L Ch R = 1 ,6699    ,472,472,472
BEGIN DESCRIPTION:
EAST FORK THREEMILE CREEK 15.0
END DESCRIPTION:
XS GIS Cut Line= 3
      2823729.82     10029592.58      2825160.42     10029780.08
      2826118.77     10029668.97
#Sta/Elev= 30
  4025.1  1698.6  4064.1 1696.75  4164.9 1686.55  4223.4 1684.08    4381  1671.6
  4437.2 1670.56  4467.5 1666.91  4499.8 1665.27    4528 1663.91  4618.8 1655.07
  4739.8 1648.95    4765 1644.27  4770.1 1640.25  4790.2 1633.29  4820.5  1627.8
  4922.6 1627.54  4981.9 1623.12  4993.4 1620.67  4996.2 1620.17  4999.4 1620.67
  5032.3 1625.55  5284.4 1629.93  5405.4 1637.46  5576.7 1644.77  5819.8 1663.34
  6002.4 1674.62  6140.5 1682.86  6251.2 1692.77  6331.7 1697.82  6432.7 1708.68
#Mann= 6 ,-1 , 0
  4025.1      .1       0  4499.8     .16       0  4993.4     .07       0
  4999.4     .16       0  5819.8      .1       0  6002.4     .16       0
Bank Sta=4993.4,4999.4
XS Rating Curve= 0 ,0
Exp/Cntr=0.3,0.1

Type RM Length L Ch R = 1 ,6227    ,410,410,410
BEGIN DESCRIPTION:
EAST FORK THREEMILE CREEK 14.0
END DESCRIPTION:
XS GIS Cut Line= 3
      2823722.91     10030071.75      2824938.19     10030175.92
      2826143.71     10029898.79
#Sta/Elev= 30
  3981.5 1702.55  4187.8 1683.32  4438.7 1664.06  4498.9 1657.01  4629.4 1645.69
  4646.6 1643.54  4679.6 1634.53  4695.6 1632.19    4800 1625.11  4950.6  1622.2
  4980.7 1619.28  4999.9  1614.4  5002.7  1613.9  5005.9  1614.4  5010.8 1618.08
  5020.8 1619.96    5061 1622.03  5116.7 1629.48  5519.6 1639.91  5642.7  1647.5
  5755.6 1651.26  5905.8  1661.3  6133.7 1675.26  6153.4 1676.07  6207.1 1678.75
  6319.9 1690.45  6350.6 1691.88  6381.5 1693.22  6412.3 1698.38  6438.2 1700.32
#Mann= 8 ,-1 , 0
  3981.5      .1       0  4695.6     .16       0  4999.9     .07       0
  5005.9     .16       0  5905.8      .1       0  6133.7     .16       0
  6153.4      .1       0  6350.6     .16       0
Bank Sta=4999.9,5005.9
XS Rating Curve= 0 ,0
Exp/Cntr=0.3,0.1

Type RM Length L Ch R = 1 ,5817    ,653,653,653
BEGIN DESCRIPTION:
EAST FORK THREEMILE CREEK 13.0
END DESCRIPTION:
XS GIS Cut Line= 3
      2824056.22     10030481.47      2825660.42     10030682.86
      2826299.29     10030953.69
#Sta/Elev= 30
  4377.5 1676.56  4612.8 1656.92  4676.9 1649.96  4712.4  1634.5  4762.7 1619.15
  4782.9 1617.49  4904.1 1619.12  4964.3 1618.56  4974.4 1616.83  4995.7 1609.67
  4998.4 1609.17  5001.7 1609.67  5044.9 1617.27  5080.2 1617.81  5125.6  1620.2
  5159.6 1620.44  5246.7 1625.87    5412 1633.58  5476.4 1639.25  5669.8 1649.29
  5941.9 1660.77  6024.8  1663.1  6391.1 1679.15  6443.9 1682.49  6449.3 1683.91
  6467.6 1683.43  6525.8  1688.3    6655 1694.81  6665.6 1694.14  6688.2 1696.63
#Mann= 8 ,-1 , 0
  4377.5      .1       0  4612.8     .16       0  4904.1      .1       0
  4995.7     .07       0  5001.7      .1       0  5080.2     .16       0
  5246.7      .1       0    5412     .16       0
Bank Sta=4995.7,5001.7
XS Rating Curve= 0 ,0
Exp/Cntr=0.3,0.1

Type RM Length L Ch R = 1 ,5164    ,516,516,516
BEGIN DESCRIPTION:
EAST FORK THREEMILE CREEK 12.0
END DESCRIPTION:
XS GIS Cut Line= 3
       2823736.8     10030682.86      2824479.86     10031162.03
      2825799.28     10031550.91
#Sta/Elev= 30
  4021.7 1696.02  4118.9 1683.56  4154.6 1675.42  4233.7  1663.5  4319.8 1655.35
  4348.6 1652.28  4392.5 1641.91    4425 1638.87  4437.7 1637.97  4623.8 1621.25
  4790.1  1613.4  4847.5  1612.7  4856.6 1611.69  4862.7 1608.22  4877.9 1606.59
  4924.8 1611.83  4963.3 1612.12  4977.4 1609.16  4993.7 1603.25  4996.4 1602.75
  4999.7 1603.25  5008.7 1607.63  5029.5 1611.33  5073.7 1610.47  5112.9 1614.38
  5250.8  1619.7  5278.9 1623.73  5509.1  1642.7  5938.8 1664.29  6281.4 1683.01
#Mann= 7 ,-1 , 0
  4021.7      .1       0  4319.8     .16       0    4425      .1       0
  4437.7     .16       0  4993.7     .07       0  4999.7     .16       0
  5938.8      .1       0
Bank Sta=4993.7,4999.7
XS Rating Curve= 0 ,0
Exp/Cntr=0.3,0.1

Type RM Length L Ch R = 1 ,4648    ,394,394,394
BEGIN DESCRIPTION:
EAST FORK THREEMILE CREEK 11.0
END DESCRIPTION:
XS GIS Cut Line= 3
      2823639.58     10030787.03      2824327.08     10031655.08
      2825403.45     10031974.52
#Sta/Elev= 30
  4032.6  1693.8  4038.5 1693.09  4100.9 1688.06  4214.7 1667.46  4285.2 1660.45
  4385.6  1653.5    4407 1647.19  4421.4  1644.8  4471.1 1640.58  4584.9 1621.39
  4692.7 1611.66    4773 1607.14  4926.2 1606.29  4938.4 1604.36  4975.9 1602.88
  4994.9 1600.12  4997.6 1599.62  5000.9 1600.12  5019.6  1603.9    5040 1609.96
  5054.4 1611.35  5160.4 1613.48    5262 1616.65  5321.4  1618.9  5605.9 1633.41
    5809 1644.71  5902.8 1652.71  6149.2 1666.01    6172 1667.04  6262.7 1673.19
#Mann= 14 ,-1 , 0
  4032.6     .16       0  4038.5      .1       0  4692.7     .16       0
    4773     .12       0  4938.4     .16       0  4994.9     .07       0
  5000.9     .16       0  5019.6      .1       0  5160.4     .16       0
    5262      .1       0  5321.4     .16       0  5605.9      .1       0
  6149.2     .05       0    6172      .1       0
Bank Sta=4994.9,5000.9
XS Rating Curve= 0 ,0
Exp/Cntr=0.3,0.1

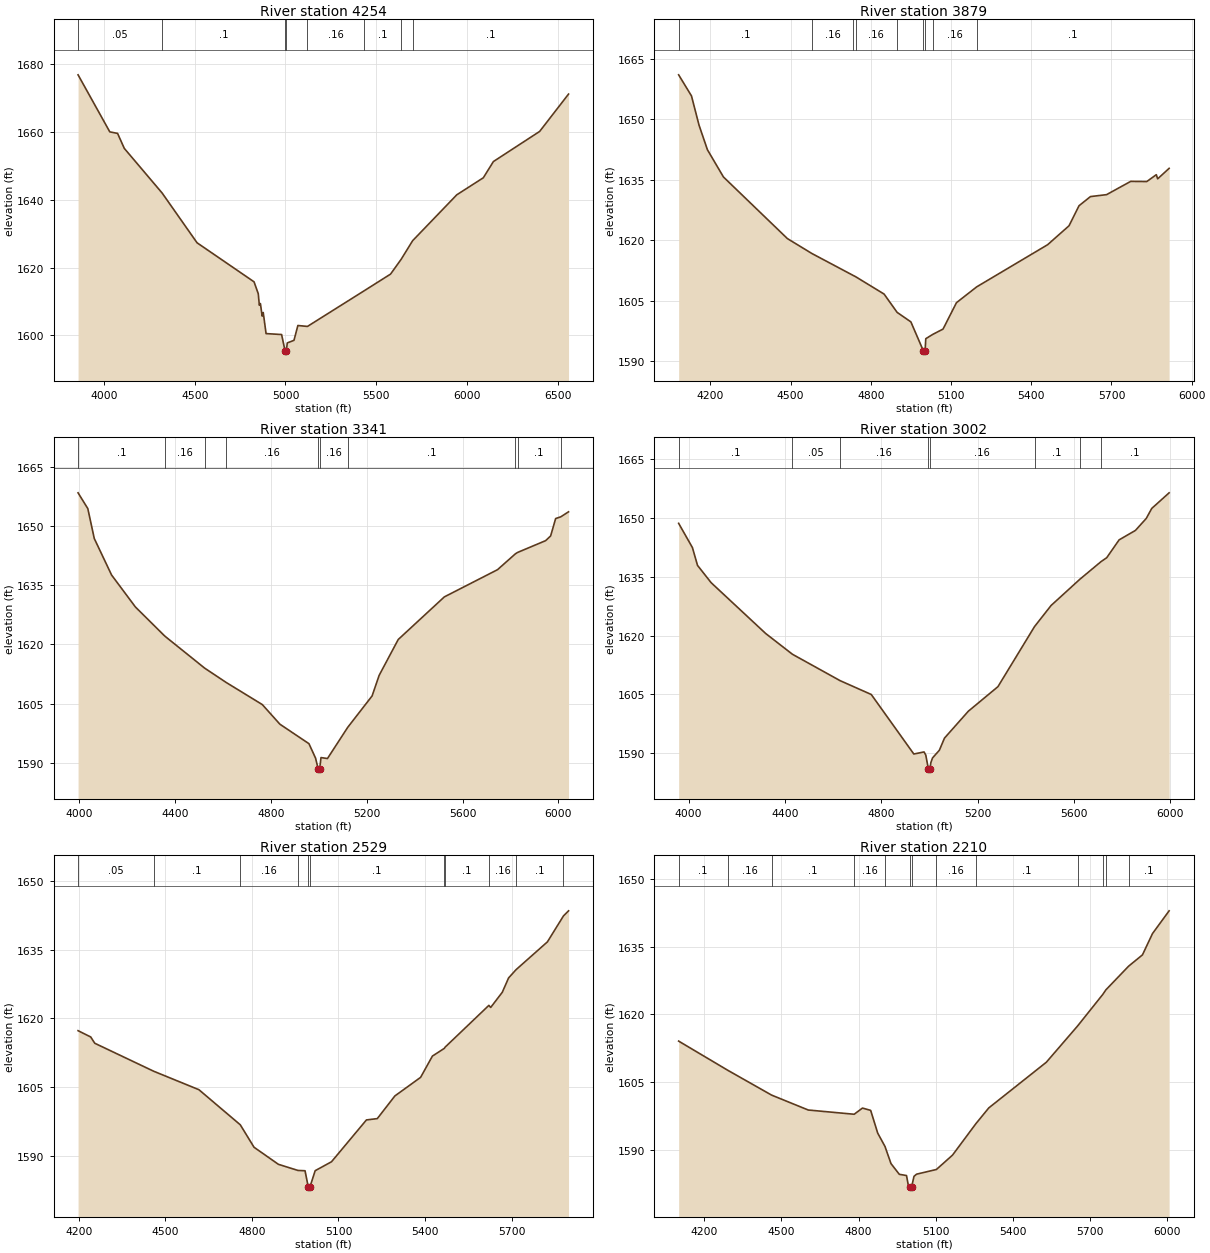
Type RM Length L Ch R = 1 ,4254    ,375,375,375
BEGIN DESCRIPTION:
EAST FORK THREEMILE CREEK 10.0
END DESCRIPTION:
XS GIS Cut Line= 3
      2822945.17     10031148.16      2824264.58     10031932.86
       2825415.4     10032126.97
#Sta/Elev= 30
  3857.2 1676.72  4032.1 1659.93  4074.9 1659.48  4111.9 1655.07  4320.5 1641.92
  4512.6 1627.29  4826.7 1615.79    4850 1612.29  4855.9  1608.9  4861.8 1609.39
  4871.5 1605.69  4877.4 1606.75    4893 1600.55  4978.6 1600.27  4998.3  1595.3
    5001  1594.8  5004.3  1595.3  5009.8  1597.8  5046.8 1598.57  5068.2 1602.93
  5121.1 1602.66  5432.5 1613.12  5578.8 1618.06  5637.5 1622.44  5700.6  1627.9
  5943.9 1641.41    6090 1646.42  6145.4 1651.19  6400.3 1660.06  6559.4 1671.05
#Mann= 8 ,-1 , 0
  3857.2     .05       0  4320.5      .1       0  4998.3     .07       0
  5004.3      .1       0  5121.1     .16       0  5432.5      .1       0
  5637.5     .16       0  5700.6      .1       0
Bank Sta=4998.3,5004.3
XS Rating Curve= 0 ,0
Exp/Cntr=0.3,0.1

Type RM Length L Ch R = 1 ,3879    ,538,538,538
BEGIN DESCRIPTION:
EAST FORK THREEMILE CREEK 9.0
END DESCRIPTION:
XS GIS Cut Line= 3
      2823090.97     10031807.86      2823667.36     10032078.69
      2824861.81     10032162.03
#Sta/Elev= 30
  4081.5 1661.01  4129.5 1655.78  4157.8 1648.51  4189.2 1642.42  4249.1 1635.67
  4488.2 1620.39  4579.8 1616.69  4733.4 1611.28  4743.3 1610.94  4849.8 1606.63
  4898.5 1602.09    4950 1599.73  4997.1 1592.48  4999.9 1591.98  5003.1 1592.48
  5005.7 1595.56  5031.4 1596.61  5070.3 1597.95  5120.4 1604.49  5196.2 1608.42
  5461.3 1618.87  5541.4 1623.57  5578.8 1628.54  5621.6 1630.81  5681.8 1631.29
    5772 1634.58  5832.2 1634.54  5867.8 1636.24  5872.8 1635.21  5915.7 1637.81
#Mann= 9 ,-1 , 0
  4081.5      .1       0  4579.8     .16       0  4733.4      .1       0
  4743.3     .16       0  4898.5      .1       0  4997.1     .07       0
  5003.1      .1       0  5031.4     .16       0  5196.2      .1       0
Bank Sta=4997.1,5003.1
XS Rating Curve= 0 ,0
Exp/Cntr=0.3,0.1

Type RM Length L Ch R = 1 ,3341    ,339,339,339
BEGIN DESCRIPTION:
EAST FORK THREEMILE CREEK 8.0
END DESCRIPTION:
XS GIS Cut Line= 2
      2822945.17      10031981.5      2824604.16     10033182.35
#Sta/Elev= 30
  3994.5  1658.4  4035.2 1654.41  4062.2 1646.83  4134.4 1637.59  4233.9 1629.49
  4356.9  1622.1  4523.3 1613.99    4614 1610.33    4764 1604.76  4837.2  1599.8
  4958.6 1594.86  4986.2  1591.2  4997.3 1588.41  5000.1 1587.91  5003.3 1588.41
  5008.9 1591.34  5035.9  1591.1  5120.6 1599.01  5222.3 1606.96  5251.7 1612.17
  5331.4 1621.25  5523.9 1632.04  5745.9 1638.93  5820.4 1642.94  5829.4 1643.29
    5947 1646.29  5967.8 1647.49  5988.7 1651.89    6010 1652.32  6042.5 1653.59
#Mann= 10 ,-1 , 0
  3994.5      .1       0  4356.9     .16       0  4523.3      .1       0
    4614     .16       0  4997.3     .07       0  5003.3     .16       0
  5120.6      .1       0  5820.4     .05       0  5829.4      .1       0
    6010     .05       0
Bank Sta=4997.3,5003.3
XS Rating Curve= 0 ,0
Exp/Cntr=0.3,0.1

Type RM Length L Ch R = 1 ,3002    ,473,473,473
BEGIN DESCRIPTION:
EAST FORK THREEMILE CREEK 7.0
END DESCRIPTION:
XS GIS Cut Line= 3
      2822847.89     10032113.39       2823736.8     10033009.25
      2824422.35     10033369.34
#Sta/Elev= 30
  3958.5  1648.6  4015.7 1642.42  4036.9 1637.88  4093.5 1633.47  4319.8 1620.53
  4430.9 1615.24  4628.9 1608.51  4758.2 1604.99    4935 1589.82  4977.4 1590.35
  4984.5 1589.57  4995.6 1585.96  4998.4 1585.46  5001.6 1585.96  5005.7 1587.63
  5012.8 1588.84    5041 1590.78  5062.2 1593.87  5161.2 1600.72  5284.2 1606.98
  5436.1 1622.29  5504.8 1627.66  5624.2 1634.34    5712 1638.83  5735.9 1639.84
  5787.2 1644.38    5855 1646.79  5900.1 1649.85  5922.7 1652.39  5994.9 1656.37
#Mann= 8 ,-1 , 0
  3958.5      .1       0  4430.9     .05       0  4628.9     .16       0
  4995.6     .07       0  5001.6     .16       0  5436.1      .1       0
  5624.2     .16       0    5712      .1       0
Bank Sta=4995.6,5001.6
XS Rating Curve= 0 ,0
Exp/Cntr=0.3,0.1

Type RM Length L Ch R = 1 ,2529    ,319,319,319
BEGIN DESCRIPTION:
EAST FORK THREEMILE CREEK 6.0
END DESCRIPTION:
XS GIS Cut Line= 3
      2822743.72     10032606.44      2823417.36     10033328.69
       2824068.3     10033619.54
#Sta/Elev= 30
  4197.1 1617.34    4241 1615.97  4255.1  1614.6  4459.4 1608.51  4616.2 1604.49
  4759.6 1596.85  4807.2 1591.97  4891.7 1588.25  4959.4 1586.92  4984.1 1586.85
  4995.2 1583.35    4998 1582.85  5001.2 1583.35  5019.2 1586.86  5075.9 1588.81
  5196.9 1597.91  5234.6  1598.2  5295.5 1603.13  5384.8 1607.18  5425.7 1611.81
  5466.8 1613.48    5470 1613.77  5621.5 1622.85  5627.8  1622.4  5667.9 1625.69
  5689.8 1628.82  5715.7 1630.62  5824.4 1636.67    5880 1642.31  5897.7 1643.43
#Mann= 11 ,-1 , 0
  4197.1     .05       0  4459.4      .1       0  4759.6     .16       0
  4959.4      .1       0  4995.2     .07       0  5001.2      .1       0
  5466.8     .16       0    5470      .1       0  5621.5     .16       0
  5715.7      .1       0    5880     .16       0
Bank Sta=4995.2,5001.2
XS Rating Curve= 0 ,0
Exp/Cntr=0.3,0.1

Type RM Length L Ch R = 1 ,2210    ,435,435,435
BEGIN DESCRIPTION:
EAST FORK THREEMILE CREEK 5.0
END DESCRIPTION:
XS GIS Cut Line= 3
      2822604.88     10032662.07      2823000.69     10033363.42
      2823985.16     10033855.65
#Sta/Elev= 30
    4101 1614.05  4291.3 1607.61  4462.3 1602.09  4604.6 1598.79  4783.1 1597.85
  4815.4 1599.22  4847.2 1598.71  4874.6 1593.67  4902.8 1590.73  4926.2 1586.92
  4958.5 1584.55  4986.5 1584.28  4993.3 1582.18  5000.3 1581.77    5003 1581.27
  5006.3 1581.77  5015.6  1584.1  5025.6 1584.58  5102.7 1585.62  5165.4 1588.81
  5255.8 1595.74  5306.3 1599.26  5529.9 1609.37  5651.2 1617.39  5749.4  1624.4
  5761.3  1625.4  5849.6 1630.64  5903.3 1633.14  5942.4 1637.86    6007  1642.9
#Mann= 13 ,-1 , 0
    4101      .1       0  4291.3     .16       0  4462.3      .1       0
  4783.1     .16       0  4902.8      .1       0  5000.3     .07       0
  5006.3      .1       0  5102.7     .16       0  5255.8      .1       0
  5651.2     .16       0  5749.4      .1       0  5761.3     .16       0
  5849.6      .1       0
Bank Sta=5000.3,5006.3
XS Rating Curve= 0 ,0
Exp/Cntr=0.3,0.1

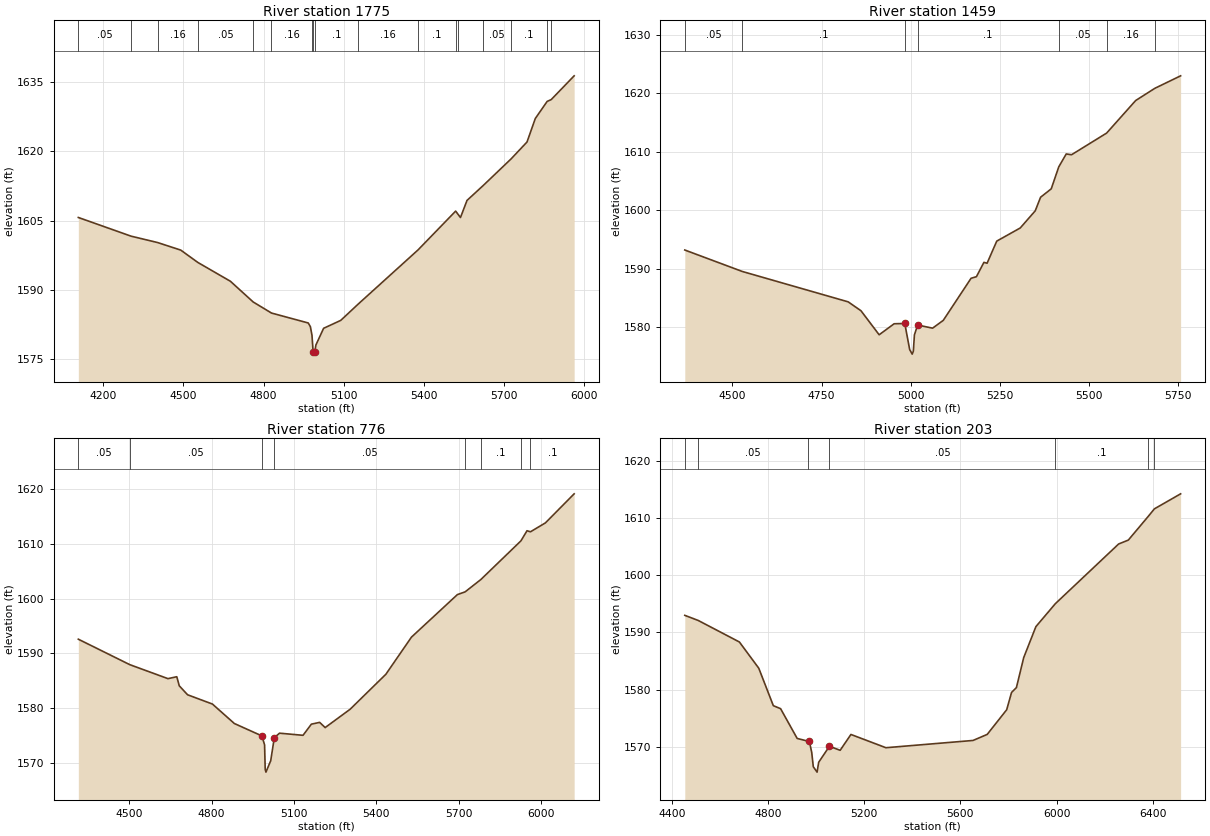
Type RM Length L Ch R = 1 ,1775    ,316,316,316
BEGIN DESCRIPTION:
EAST FORK THREEMILE CREEK 4.0
END DESCRIPTION:
XS GIS Cut Line= 3
      2822278.45     10033043.95      2822959.03     10033898.14
      2823673.55     10034168.69
#Sta/Elev= 30
  4106.4 1605.67  4303.6 1601.63  4403.4 1600.24  4489.8 1598.61  4553.8 1595.94
  4675.6 1591.87  4761.1 1587.38  4829.5 1584.99  4967.1 1582.84  4975.1 1582.05
  4981.1 1580.17  4985.4  1576.6  4988.1  1576.1  4991.4  1576.6  4995.9 1578.09
  5024.7 1581.69  5088.8  1583.4  5154.9 1586.97  5377.8 1598.63    5519 1607.05
  5527.4 1606.39    5537 1605.66  5561.5 1609.36  5622.8 1612.62  5726.6 1618.35
  5786.1    1622  5817.2 1627.09  5861.5 1630.78  5876.8 1631.18  5962.6 1636.32
#Mann= 17 ,-1 , 0
  4106.4     .05       0  4303.6      .1       0  4403.4     .16       0
  4553.8     .05       0  4761.1      .1       0  4829.5     .16       0
  4981.1      .1       0  4985.4     .07       0  4991.4      .1       0
  5154.9     .16       0  5377.8      .1       0    5519     .05       0
  5527.4     .16       0  5622.8     .05       0  5726.6      .1       0
  5861.5     .05       0  5876.8      .1       0
Bank Sta=4985.4,4991.4
XS Rating Curve= 0 ,0
Exp/Cntr=0.3,0.1

Type RM Length L Ch R = 1 ,1459    ,683,683,683
BEGIN DESCRIPTION:
EAST FORK THREEMILE CREEK 3.0
END DESCRIPTION:
XS GIS Cut Line= 2
      2822125.73     10033641.22      2823278.33     10034418.87
#Sta/Elev= 30
  4366.3 1593.19  4527.6 1589.52  4824.3 1584.33  4860.3 1582.81  4911.3  1578.7
  4953.3 1580.58  4983.2 1580.63  4996.9 1576.17    5004 1575.39  5007.2 1575.89
  5010.2 1578.68  5019.2 1580.36  5061.2 1579.83  5091.1 1581.16  5169.1 1588.36
  5184.1 1588.63  5205.1 1591.08    5214 1590.93  5241.1 1594.71    5307 1596.96
    5349 1599.89    5364 1602.21  5393.9 1603.65  5414.9 1607.39  5435.9 1609.61
  5450.9 1609.48  5549.2 1613.18  5630.7 1618.75  5684.3 1620.83  5756.7 1622.97
#Mann= 7 ,-1 , 0
  4366.3     .05       0  4527.6      .1       0  4983.2     .05       0
  5019.2      .1       0  5414.9     .05       0  5549.2     .16       0
  5684.3      .1       0
Bank Sta=4983.2,5019.2
XS Rating Curve= 0 ,0
Exp/Cntr=0.3,0.1

Type RM Length L Ch R = 1 ,776     ,573,573,573
BEGIN DESCRIPTION:
EAST FORK THREEMILE CREEK 2.0
END DESCRIPTION:
XS GIS Cut Line= 4
      2821952.08     10033738.42      2822264.58     10034564.81
      2822500.69     10034675.92      2823153.49     10034571.75
#Sta/Elev= 30
  4314.6  1592.6    4502 1587.96    4641 1585.41  4673.1 1585.76  4682.2  1584.1
  4712.4 1582.47  4802.9 1580.78  4882.8 1577.23  4983.1 1574.97  4992.8 1573.34
  4995.1 1568.87  4997.8 1568.37  5015.2 1570.46  5028.3 1574.67  5047.3 1575.47
  5132.8 1575.08  5163.1 1577.11  5193.3 1577.44  5213.4 1576.49  5304.3 1579.83
  5434.5 1586.21  5527.7 1592.98  5694.9 1600.73  5723.1 1601.23  5780.4 1603.48
  5926.2 1610.52  5948.4 1612.37  5961.1 1612.18  6015.6 1613.81  6120.1  1619.1
#Mann= 8 ,-1 , 0
  4314.6     .05       0    4502     .05       0  4983.1    .035       0
  5028.3     .05       0  5723.1     .05       0  5780.4      .1       0
  5926.2     .05       0  5961.1      .1       0
Bank Sta=4983.1,5028.3
XS Rating Curve= 0 ,0
Exp/Cntr=0.3,0.1

Type RM Length L Ch R = 1 ,203     ,0,0,0
BEGIN DESCRIPTION:
EAST FORK THREEMILE CREEK 1.0
END DESCRIPTION:
XS GIS Cut Line= 5
      2821678.69     10034058.65       2821620.6     10034494.32
      2821743.22     10034739.56      2822233.71     10034910.59
      2823053.34     10034781.51
#Sta/Elev= 30
  4453.3 1592.98  4508.9 1592.09  4680.4 1588.32  4761.1 1583.73  4821.6 1577.18
  4851.9 1576.65  4920.9 1571.44  4965.6 1570.97  4971.2 1571.01  4981.6 1568.94
  4987.9 1566.49  5003.7 1565.55  5010.3 1567.27    5055 1570.07  5099.7 1569.37
  5144.5 1572.14  5290.2 1569.82  5652.5 1571.09  5711.5 1572.15  5792.5 1576.46
  5812.8 1579.49    5833 1580.34  5863.4 1585.59    5914    1591    5995 1595.02
  6258.2 1605.46  6298.7 1606.15    6382 1610.32  6407.1 1611.61  6516.2 1614.24
#Mann= 7 ,-1 , 0
  4453.3     .16       0  4508.9     .05       0  4965.6    .035       0
    5055     .05       0    5995      .1       0    6382     .05       0
  6407.1      .1       0
Bank Sta=4971.2,5055
XS Rating Curve= 0 ,0
Exp/Cntr=0.3,0.1

Chan Stop Cuts=-1
Use User Specified Reach Order=0
Composite Channel Slope=5