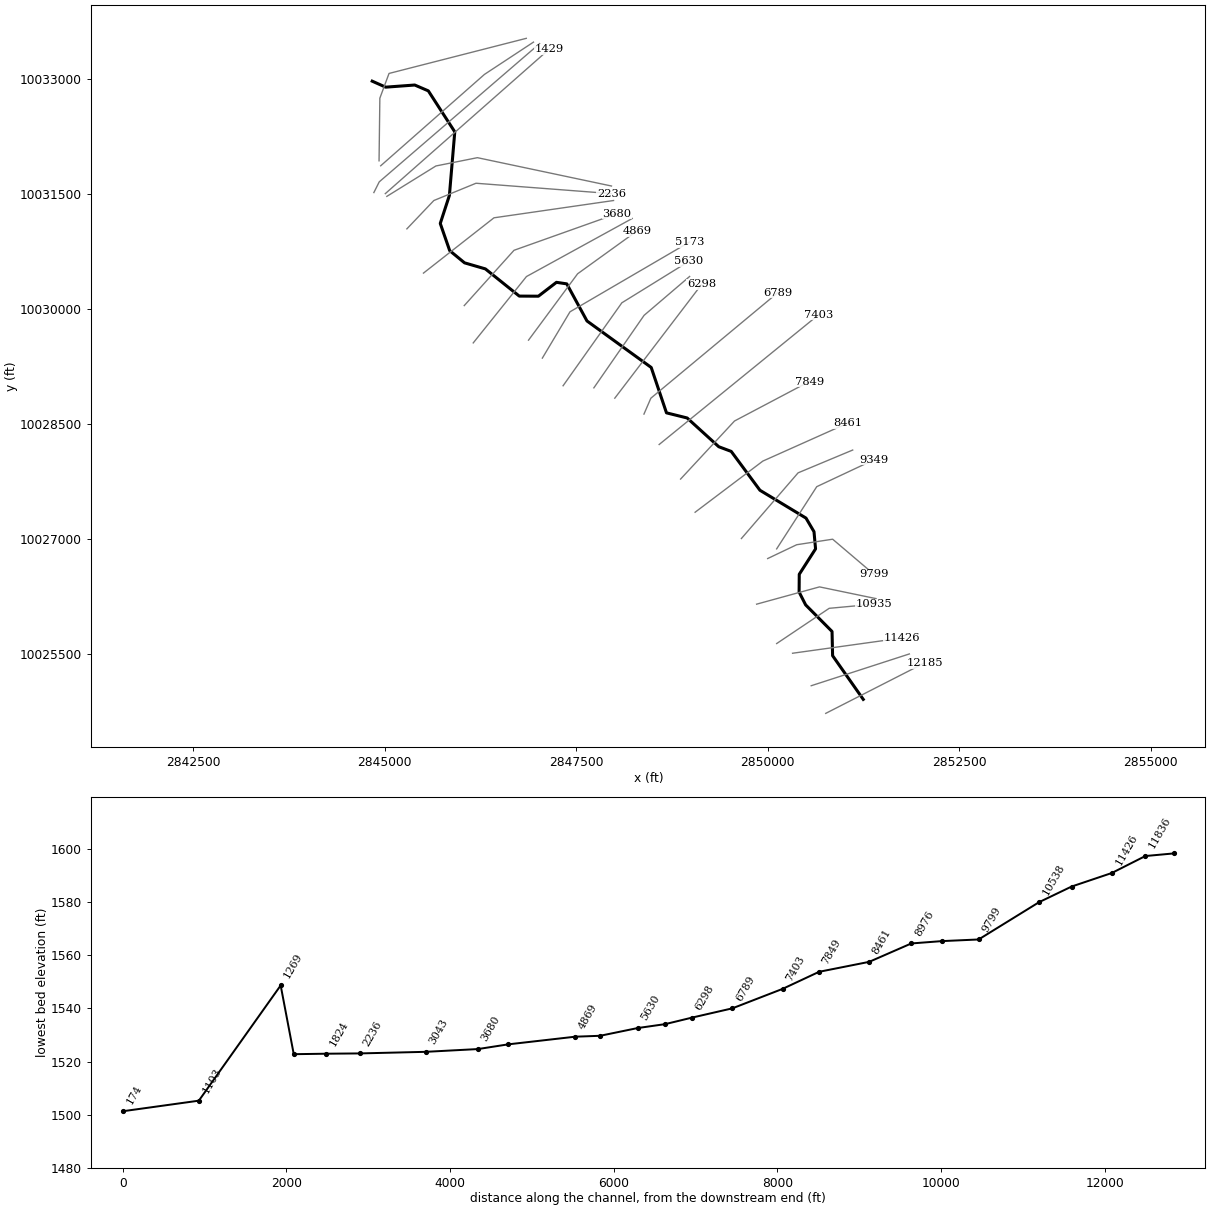
--- EAST FORK WILLIAMS CREEK.prj (project) ---

Proj Title=EAST FORK WILLIAMS CREEK Base Level Engineering
Current Plan=p01
Default Exp/Contr=0.3,0.1
English Units
Geom File=g01
Flow File=f01
Plan File=p01
Y Axis Title=Elevation
X Axis Title(PF)=Main Channel Distance
X Axis Title(XS)=Station
BEGIN DESCRIPTION:
EAST FORK WILLIAMS CREEK
END DESCRIPTION:
DSS Export Rating Curves= 0
DSS Export Rating Curve Sorted= 0
DSS Export Volume Flow Curves= 0
DXF OffsetX= 0
DXF OffsetY= 0
DXF ScaleX= 1
DXF ScaleY= 10

--- EAST FORK WILLIAMS CREEK.p01 (plan) ---

Plan Title=Multiple Run
Short Identifier=Multiple
Geom File=g01
Flow File=f01
Subcritical Flow
K Sum by GR= 0
Std Step Tol= 0.01
Critical Tol= 0.01
Num of Std Step Trials= 20
Max Error Tol= 0.3
Flow Tol Ratio= 0.001
Split Flow NTrial= 30
Split Flow Tol= 0.02
Split Flow Ratio= 0.02
Log Output Level= 0
Friction Slope Method= 1
Unsteady Friction Slope Method= 2
Unsteady Bridges Friction Slope Method= 1
Parabolic Critical Depth
Global Vel Dist=  1 , 1 , 1
Global Log Level= 0
CheckData=True
Encroach Param= -1, 0, 0, 0
BEGIN DESCRIPTION:
Multiple Run
END DESCRIPTION:

--- EAST FORK WILLIAMS CREEK.f01 (steady flow) ---

Flow Title=Multiple
Program Version=4.10
Number of Profiles= 7
Profile Names=10-year,25-year,50-year,1pct_min,100-year,1pct_plu,500-year
River Rch & RM=EAST FORK WILLIA,Reach-1         ,12185
    1321    1958    2525    2383    3223    4359    5267
River Rch & RM=EAST FORK WILLIA,Reach-1         ,9349
    2526    3851    5058    4849    6557    8868   11067
River Rch & RM=EAST FORK WILLIA,Reach-1         ,6298
    2582    3928    5151    4929    6665    9014   11207
River Rch & RM=EAST FORK WILLIA,Reach-1         ,1429
    2670    4059    5318    5082    6873    9295   11530
River Rch & RM=EAST FORK WILLIA,Reach-1         ,1269
    2670    4059    5318    5082    6873    9295   11530
Boundary for River Rch & Prof#=EAST FORK WILLIA,Reach-1         , 1
Up Type= 0
Dn Type= 1
Dn Known WS=1509.68
Boundary for River Rch & Prof#=EAST FORK WILLIA,Reach-1         , 2
Up Type= 0
Dn Type= 1
Dn Known WS=1510.68
Boundary for River Rch & Prof#=EAST FORK WILLIA,Reach-1         , 3
Up Type= 0
Dn Type= 1
Dn Known WS=1511.45
Boundary for River Rch & Prof#=EAST FORK WILLIA,Reach-1         , 4
Up Type= 0
Dn Type= 1
Dn Known WS=1511.33
Boundary for River Rch & Prof#=EAST FORK WILLIA,Reach-1         , 5
Up Type= 0
Dn Type= 1
Dn Known WS=1512.21
Boundary for River Rch & Prof#=EAST FORK WILLIA,Reach-1         , 6
Up Type= 0
Dn Type= 1
Dn Known WS=1513.18
Boundary for River Rch & Prof#=EAST FORK WILLIA,Reach-1         , 7
Up Type= 0
Dn Type= 1
Dn Known WS=1514
DSS Import GetInterval= 0
DSS Import GetPeak= 0
DSS Import FillOption= 0

--- EAST FORK WILLIAMS CREEK.g01 (geometry) ---

Geom Title=Existing Conditions
Program Version=4.10

River Reach=EAST FORK WILLIA,Reach-1
Reach XY= 30
      2851248.47     10024903.73       2850848.4     10025473.81
      2850841.01     10025790.08      2850496.35     10026137.18
      2850411.16     10026304.95      2850413.08     10026536.52
      2850625.85     10026868.22      2850605.52     10027092.58
      2850501.03     10027270.23      2849899.88     10027633.47
      2849525.09     10028140.52      2849362.34      10028201.7
      2848949.53     10028577.05      2848679.95     10028643.92
      2848480.56     10029236.37       2847642.2     10029843.24
      2847378.38     10030327.64      2847243.57     10030347.71
      2847007.76     10030166.69      2846758.16     10030167.99
      2846316.13     10030522.85      2846043.61     10030602.18
      2845849.98     10030761.64      2845726.89      10031116.1
      2845846.15     10031482.17      2845916.35     10032312.09
      2845571.13     10032846.94      2845393.75      10032923.2
       2845014.3     10032895.31      2844838.47     10032973.73

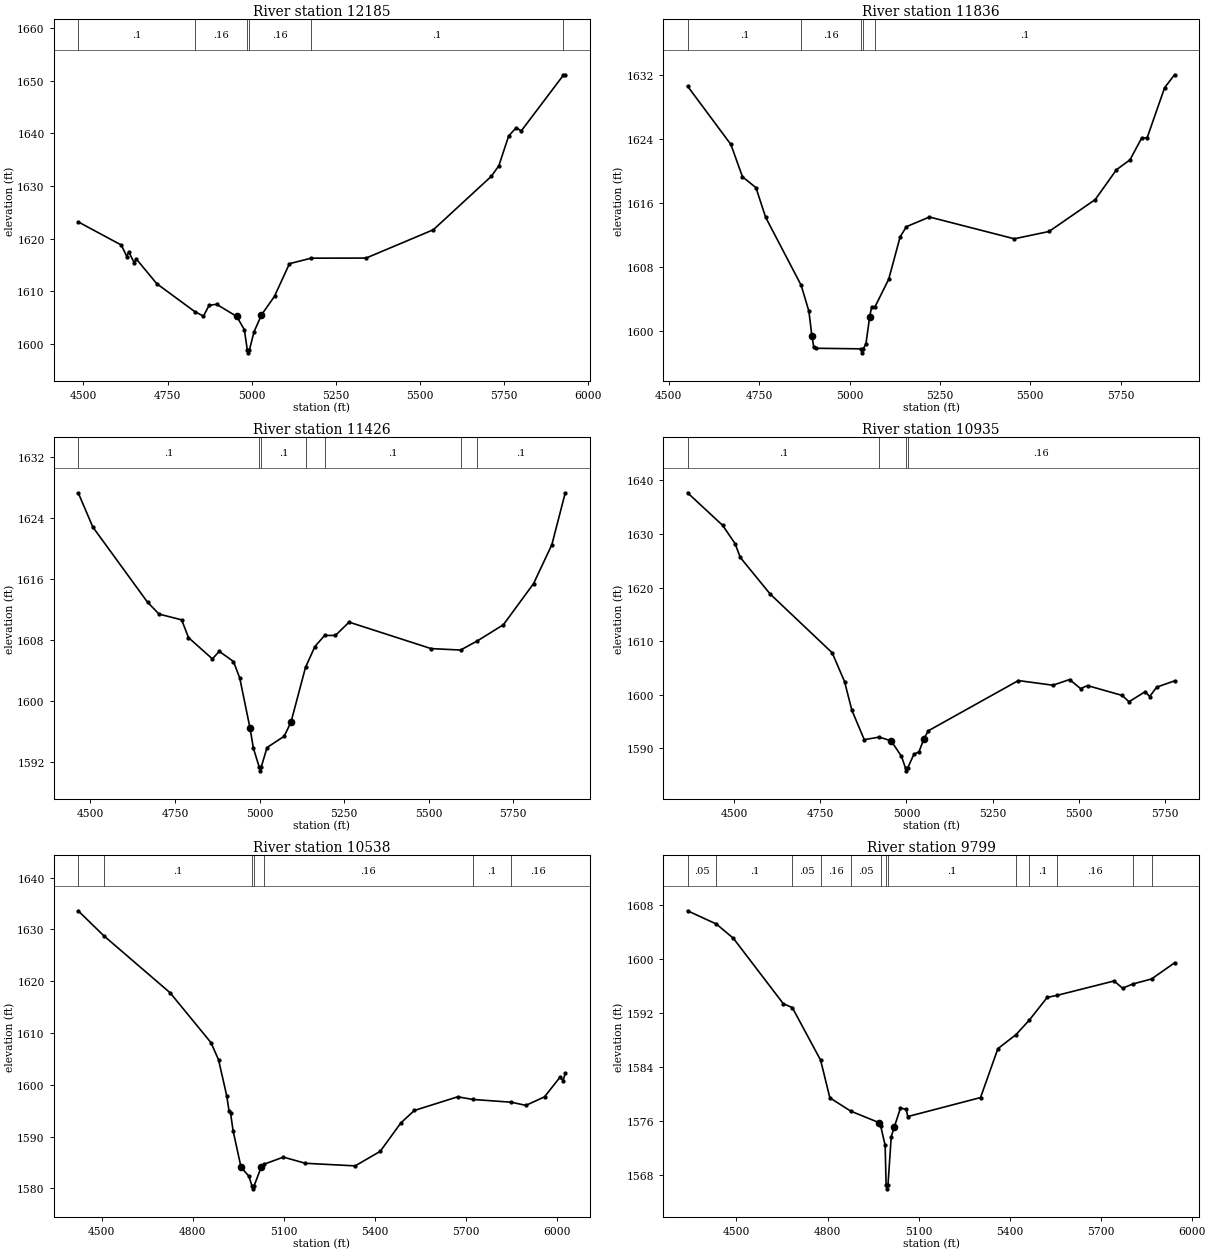
Type RM Length L Ch R = 1 ,12185   ,349,349,349
BEGIN DESCRIPTION:
EAST FORK WILLIAMS CREEK 27.0
END DESCRIPTION:
XS GIS Cut Line= 2
       2850758.7     10024720.95      2852048.02     10025379.13
#Sta/Elev= 30
  4484.4 1623.16  4612.4 1618.76    4629 1616.57  4634.6 1617.48  4651.2 1615.34
  4656.8 1616.13  4717.9 1611.41  4831.1 1606.09  4856.8 1605.24  4873.5  1607.3
  4895.7 1607.49  4955.7 1605.18  4978.2 1602.67  4987.2 1598.76  4989.9 1598.26
  4993.2 1598.76  5006.8 1602.21    5029 1605.45  5067.9 1609.02  5112.3 1615.21
  5176.8 1616.26  5340.2 1616.28  5540.2 1621.67  5712.4 1631.83  5734.6 1633.81
  5764.1 1639.52  5786.5 1641.08  5801.3 1640.45  5926.8 1651.07    5932 1651.13
#Mann= 6 ,-1 , 0
  4484.4      .1       0  4831.1     .16       0  4987.2     .07       0
  4993.2     .16       0  5176.8      .1       0  5926.8     .16       0
Bank Sta=4955.7,5029
XS Rating Curve= 0 ,0
Exp/Cntr=0.3,0.1

Type RM Length L Ch R = 1 ,11836   ,410,410,410
BEGIN DESCRIPTION:
EAST FORK WILLIAMS CREEK 26.0
END DESCRIPTION:
XS GIS Cut Line= 2
      2850569.21     10025081.83      2851850.36     10025496.85
#Sta/Elev= 30
  4552.1 1630.59    4672  1623.3    4704 1619.26  4741.3 1617.91    4768 1614.21
  4866.3 1605.71  4887.7 1602.46    4896 1599.36  4901.2 1597.97  4908.7 1597.84
  5031.9 1597.77  5034.6 1597.27  5037.9 1597.77  5045.4 1598.39  5055.9 1601.81
  5061.2 1603.02  5070.8 1603.05  5108.4 1606.47    5140 1611.76  5157.2 1613.03
  5221.1 1614.24  5455.6 1611.52  5551.6 1612.43  5679.5 1616.42  5738.3 1620.15
  5775.5 1621.38  5807.5 1624.07  5823.2 1624.16  5871.5 1630.41  5898.8 1632.01
#Mann= 5 ,-1 , 0
  4552.1      .1       0  4866.3     .16       0  5031.9     .07       0
  5037.9     .16       0  5070.8      .1       0
Bank Sta=4896,5055.9
XS Rating Curve= 0 ,0
Exp/Cntr=0.3,0.1

Type RM Length L Ch R = 1 ,11426   ,491,491,491
BEGIN DESCRIPTION:
EAST FORK WILLIAMS CREEK 25.0
END DESCRIPTION:
XS GIS Cut Line= 2
      2850325.66     10025505.89      2851751.11     10025704.37
#Sta/Elev= 30
  4464.1 1627.26  4507.3 1622.78  4668.9 1612.95  4703.2 1611.39  4769.8 1610.64
    4790 1608.32  4860.7 1605.53  4880.9 1606.52    4923 1605.19  4941.5 1603.03
  4971.8 1596.49  4981.9 1593.84    4999 1591.39  5001.8 1590.89    5005 1591.39
  5022.2 1593.94  5072.7 1595.41  5092.9 1597.26  5135.9 1604.43  5163.6 1607.15
  5192.4  1608.6  5224.2  1608.6  5264.6 1610.34  5506.9 1606.88  5594.1 1606.69
  5643.4 1607.88  5720.7    1610  5809.8 1615.38  5863.9 1620.47  5903.3 1627.23
#Mann= 7 ,-1 , 0
  4464.1      .1       0    4999     .07       0    5005      .1       0
  5135.9     .16       0  5192.4      .1       0  5594.1     .05       0
  5643.4      .1       0
Bank Sta=4971.8,5092.9
XS Rating Curve= 0 ,0
Exp/Cntr=0.3,0.1

Type RM Length L Ch R = 1 ,10935   ,397,397,397
BEGIN DESCRIPTION:
EAST FORK WILLIAMS CREEK 24.0
END DESCRIPTION:
XS GIS Cut Line= 3
       2850118.1     10025632.19      2850803.81     10026092.34
      2851390.22     10026146.47
#Sta/Elev= 30
    4364  1637.7  4466.1 1631.61  4502.2  1628.2  4517.1 1625.64  4604.2 1618.79
  4784.2 1607.83  4820.2 1602.44  4841.2 1597.14  4877.3 1591.62    4921  1592.1
  4955.3  1591.4  4985.3 1588.53  4997.3  1586.3    5000  1585.8  5003.3  1586.3
  5021.3 1588.87  5036.3 1589.35  5050.9 1591.83  5063.3 1593.27    5325 1602.65
  5425.4 1601.78  5473.8 1602.84  5505.8 1601.15  5525.9 1601.71  5626.3 1599.88
  5646.4  1598.7  5693.1 1600.56  5706.6 1599.67  5726.7 1601.42  5778.7 1602.59
#Mann= 4 ,-1 , 0
    4364      .1       0    4921     .16       0  4997.3     .07       0
  5003.3     .16       0
Bank Sta=4955.3,5050.9
XS Rating Curve= 0 ,0
Exp/Cntr=0.3,0.1

Type RM Length L Ch R = 1 ,10538   ,739,739,739
BEGIN DESCRIPTION:
EAST FORK WILLIAMS CREEK 23.0
END DESCRIPTION:
XS GIS Cut Line= 3
      2849856.43     10026146.46      2850677.49     10026372.03
      2851415.23     10026219.08
#Sta/Elev= 30
  4422.7 1633.58  4506.7 1628.78  4725.6 1617.76  4860.4 1608.13  4885.3 1604.81
  4912.2 1597.87  4919.7 1595.02  4924.9 1594.52    4933 1591.17  4959.3  1584.1
  4984.8 1582.39  4995.9 1580.43  4998.7 1579.93  5001.9 1580.43  5026.3 1584.21
  5033.7 1584.65  5098.9 1586.05  5171.5 1584.86  5335.5 1584.36  5418.1 1587.17
    5486 1592.65  5530.5 1595.05  5673.5 1597.69  5722.7 1597.18  5850.3 1596.64
  5898.1 1596.03  5959.4 1597.68  6010.5 1601.46  6020.7 1600.83  6027.6 1602.22
#Mann= 7 ,-1 , 0
  4422.7     .05       0  4506.7      .1       0  4995.9     .07       0
  5001.9      .1       0  5033.7     .16       0  5722.7      .1       0
  5850.3     .16       0
Bank Sta=4959.3,5026.3
XS Rating Curve= 0 ,0
Exp/Cntr=0.3,0.1

Type RM Length L Ch R = 1 ,9799    ,450,450,450
BEGIN DESCRIPTION:
EAST FORK WILLIAMS CREEK 22.0
END DESCRIPTION:
XS GIS Cut Line= 4
      2850000.85     10026741.96      2850379.76     10026922.39
      2850848.92     10026994.57      2851390.24     10026534.45
#Sta/Elev= 30
  4338.8 1607.18    4434 1605.21  4489.9 1603.09  4654.4 1593.38  4684.1 1592.81
  4777.3    1585  4807.8 1579.41  4876.4 1577.44  4969.6 1575.73  4975.6 1575.16
  4989.9 1572.37  4993.2  1566.4    4996  1565.9  4999.2  1566.4  5010.1 1573.67
  5020.2 1575.09  5040.5  1577.9  5059.4 1577.69  5064.5 1576.63  5304.3 1579.45
  5361.5 1586.71  5421.6 1588.81  5465.2 1590.96    5524 1594.32    5556 1594.62
  5744.4 1596.76  5772.2 1595.69  5807.1 1596.32  5867.9 1597.06  5943.6 1599.45
#Mann= 13 ,-1 , 0
  4338.8     .05       0    4434      .1       0  4684.1     .05       0
  4777.3     .16       0  4876.4     .05       0  4975.6      .1       0
  4993.2     .07       0  4999.2      .1       0  5421.6     .16       0
  5465.2      .1       0    5556     .16       0  5807.1      .1       0
  5867.9     .16       0
Bank Sta=4969.6,5020.2
XS Rating Curve= 0 ,0
Exp/Cntr=0.3,0.1

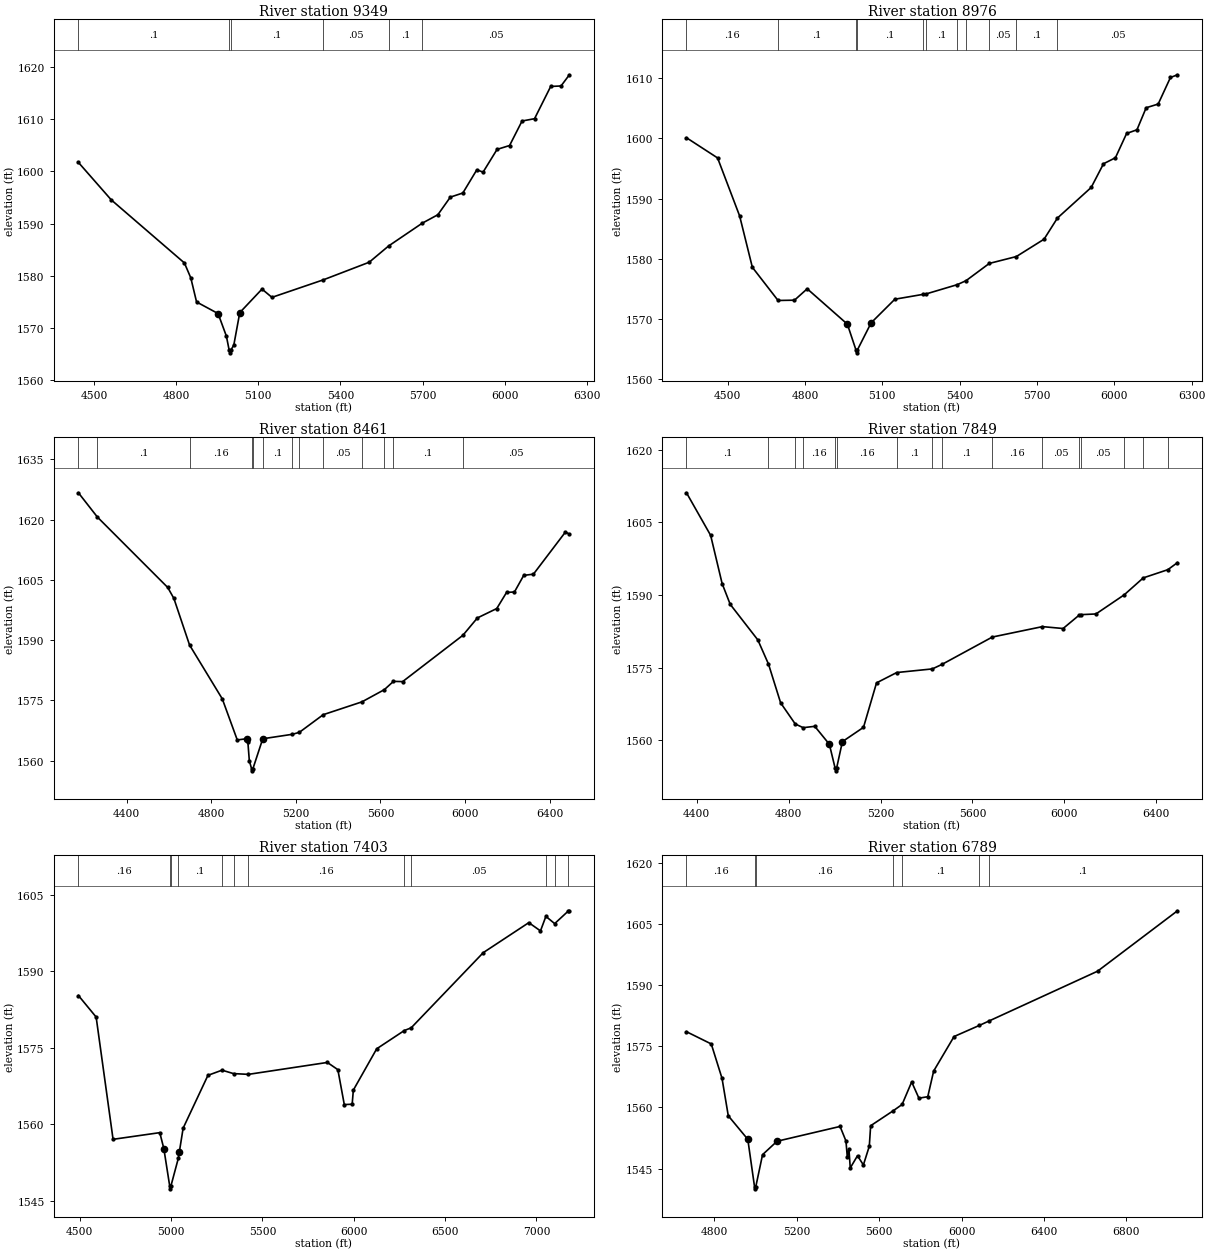
Type RM Length L Ch R = 1 ,9349    ,373,373,373
BEGIN DESCRIPTION:
EAST FORK WILLIAMS CREEK 21.0
END DESCRIPTION:
XS GIS Cut Line= 3
      2850118.13     10026868.29       2850641.4     10027680.26
      2851390.27     10028032.14
#Sta/Elev= 30
  4443.1  1601.7  4563.2 1594.53  4830.3 1582.47  4853.6 1579.62  4874.7 1575.01
  4953.3 1572.79  4983.6 1568.48  4993.8 1565.78  4996.6 1565.28  4999.8 1565.78
  5010.7 1566.76  5032.5 1572.97  5113.7 1577.47    5150 1575.89  5337.6 1579.24
  5505.3 1582.61  5576.2 1585.72  5699.1 1590.08    5756 1591.69  5801.6 1595.06
  5847.3 1595.85  5898.4 1600.29  5921.2 1599.84  5972.3 1604.19    6018 1604.93
  6063.6 1609.62  6109.2 1610.06  6168.2 1616.23  6205.9 1616.32  6236.5 1618.46
#Mann= 6 ,-1 , 0
  4443.1      .1       0  4993.8     .07       0  4999.8      .1       0
  5337.6     .05       0  5576.2      .1       0  5699.1     .05       0
Bank Sta=4953.3,5032.5
XS Rating Curve= 0 ,0
Exp/Cntr=0.3,0.1

Type RM Length L Ch R = 1 ,8976    ,515,515,515
BEGIN DESCRIPTION:
EAST FORK WILLIAMS CREEK 20.0
END DESCRIPTION:
XS GIS Cut Line= 3
      2849657.97     10027003.59       2850397.8     10027860.71
      2851110.56     10028158.44
#Sta/Elev= 30
  4340.4  1600.1    4461 1596.75  4546.6 1587.12  4595.9  1578.6  4695.7 1573.09
  4759.4 1573.14  4808.7 1575.03  4964.5 1569.16  4997.7  1564.9  5000.4  1564.4
  5003.7  1564.9  5056.7 1569.38  5148.8  1573.3    5256 1574.09    5271 1574.19
    5391 1575.72    5425 1576.38  5515.1 1579.24    5620 1580.38  5727.5 1583.26
  5779.4 1586.77  5910.4 1591.85  5958.1 1595.78  6004.4 1596.78  6047.8 1600.81
  6087.9 1601.42  6123.6 1605.08  6170.2 1605.69  6217.8  1610.1  6245.1 1610.55
#Mann= 11 ,-1 , 0
  4340.4     .16       0  4695.7      .1       0  4997.7     .07       0
  5003.7      .1       0    5256     .05       0    5271      .1       0
    5391     .05       0    5425      .1       0  5515.1     .05       0
    5620      .1       0  5779.4     .05       0
Bank Sta=4964.5,5056.7
XS Rating Curve= 0 ,0
Exp/Cntr=0.3,0.1

Type RM Length L Ch R = 1 ,8461    ,612,612,612
BEGIN DESCRIPTION:
EAST FORK WILLIAMS CREEK 19.0
END DESCRIPTION:
XS GIS Cut Line= 3
      2849053.45     10027346.42      2849937.66     10028014.09
      2851045.66     10028509.53
#Sta/Elev= 30
  4171.6 1626.66  4261.2 1620.63    4594  1603.1  4623.1 1600.37  4697.2 1588.78
    4852 1575.38  4922.8 1565.16  4966.5 1565.47  4972.8 1564.73  4979.8    1560
  4990.6 1557.98  4993.4 1557.48  4996.6 1557.98  5043.3 1565.46  5183.2 1566.57
  5216.4 1567.06  5329.3 1571.45  5512.3 1574.64  5618.3 1577.68  5661.3 1579.74
  5704.8 1579.68  5989.6  1591.2  6058.2 1595.52  6149.8 1597.86  6196.2 1601.87
  6233.5 1601.98  6277.3 1606.11  6323.2 1606.41  6474.5 1616.89  6493.3 1616.38
#Mann= 13 ,-1 , 0
  4171.6     .16       0  4261.2      .1       0  4697.2     .16       0
  4990.6     .07       0  4996.6     .16       0  5043.3      .1       0
  5183.2     .16       0  5216.4      .1       0  5329.3     .05       0
  5512.3      .1       0  5618.3     .05       0  5661.3      .1       0
  5989.6     .05       0
Bank Sta=4966.5,5043.3
XS Rating Curve= 0 ,0
Exp/Cntr=0.3,0.1

Type RM Length L Ch R = 1 ,7849    ,446,446,446
BEGIN DESCRIPTION:
EAST FORK WILLIAMS CREEK 17.0
END DESCRIPTION:
XS GIS Cut Line= 3
      2848863.98     10027779.48      2849567.75     10028537.38
      2850542.19     10029051.67
#Sta/Elev= 30
  4355.9 1611.08    4461  1602.3  4510.9 1592.37  4546.1 1588.08  4666.3 1580.74
  4712.7 1575.75  4765.5 1567.76    4829 1563.41  4863.5 1562.64    4914 1562.92
  4977.5 1559.22  5002.8 1554.24  5005.6 1553.74  5008.8 1554.24  5034.2 1559.76
    5126 1562.71  5182.7 1571.88  5270.6 1574.01  5425.6 1574.76  5468.3 1575.71
  5686.5 1581.33  5904.6 1583.48  5994.4 1583.09  6065.3 1585.89  6072.5 1585.95
  6137.3 1586.09  6260.1 1590.03  6343.2 1593.53    6450 1595.22    6492 1596.68
#Mann= 16 ,-1 , 0
  4355.9      .1       0  4712.7     .16       0    4829      .1       0
  4863.5     .16       0  5002.8     .07       0  5008.8     .16       0
  5270.6      .1       0  5425.6     .16       0  5468.3      .1       0
  5686.5     .16       0  5904.6     .05       0  6065.3      .1       0
  6072.5     .05       0  6260.1      .1       0  6343.2     .05       0
    6450      .1       0
Bank Sta=4977.5,5034.2
XS Rating Curve= 0 ,0
Exp/Cntr=0.3,0.1

Type RM Length L Ch R = 1 ,7403    ,614,614,614
BEGIN DESCRIPTION:
EAST FORK WILLIAMS CREEK 16.0
END DESCRIPTION:
XS GIS Cut Line= 2
       2848584.3     10028230.61      2850668.49     10029926.84
#Sta/Elev= 30
  4492.9 1585.27    4590 1581.04  4682.6 1557.04  4938.3 1558.35  4960.6  1555.2
  4992.8 1547.82  4995.5 1547.32  4998.8 1547.82  5040.3 1553.39  5045.3 1554.56
  5066.1 1559.23  5201.9  1569.6  5278.9 1570.61  5341.8 1569.94  5423.2 1569.79
  5855.4 1572.13  5912.9 1570.71  5948.1 1563.86  5991.2 1563.93  5997.6  1566.7
  6125.5 1574.81  6276.9  1578.4    6314 1578.92  6708.6 1593.68  6957.9 1599.57
  7021.8 1597.95  7051.4  1600.8  7099.5 1599.38  7174.3 1601.86  7180.1  1601.9
#Mann= 12 ,-1 , 0
  4492.9     .16       0  4992.8     .07       0  4998.8     .16       0
  5040.3      .1       0  5278.9     .16       0  5341.8      .1       0
  5423.2     .16       0  6276.9      .1       0    6314     .05       0
  7051.4      .1       0  7099.5     .05       0  7174.3      .1       0
Bank Sta=4960.6,5045.3
XS Rating Curve= 0 ,0
Exp/Cntr=0.3,0.1

Type RM Length L Ch R = 1 ,6789    ,491,491,491
BEGIN DESCRIPTION:
EAST FORK WILLIAMS CREEK 15.0
END DESCRIPTION:
XS GIS Cut Line= 3
      2848385.84     10028627.64      2848476.05     10028835.12
      2850134.78     10030214.39
#Sta/Elev= 30
  4664.3 1578.63  4784.6 1575.62  4836.9 1567.15  4867.2 1557.96    4962 1552.17
  4994.7  1540.5  4997.5    1540  5000.7  1540.5  5033.6  1548.4  5103.9  1551.7
  5409.9 1555.34  5438.5 1551.76    5445 1547.79  5452.8 1549.85  5459.3 1545.13
  5494.5 1548.14  5523.1 1545.87  5551.8 1550.48  5558.3 1555.51  5669.2 1559.24
    5711 1560.74  5757.5 1566.28  5792.6 1562.29  5835.6 1562.65  5864.2 1568.96
  5963.2 1577.44  6086.2 1580.18  6131.9 1581.24  6659.7  1593.5  7047.8 1608.36
#Mann= 7 ,-1 , 0
  4664.3     .16       0  4994.7     .07       0  5000.7     .16       0
  5669.2     .05       0    5711      .1       0  6086.2     .16       0
  6131.9      .1       0
Bank Sta=4962,5103.9
XS Rating Curve= 0 ,0
Exp/Cntr=0.3,0.1

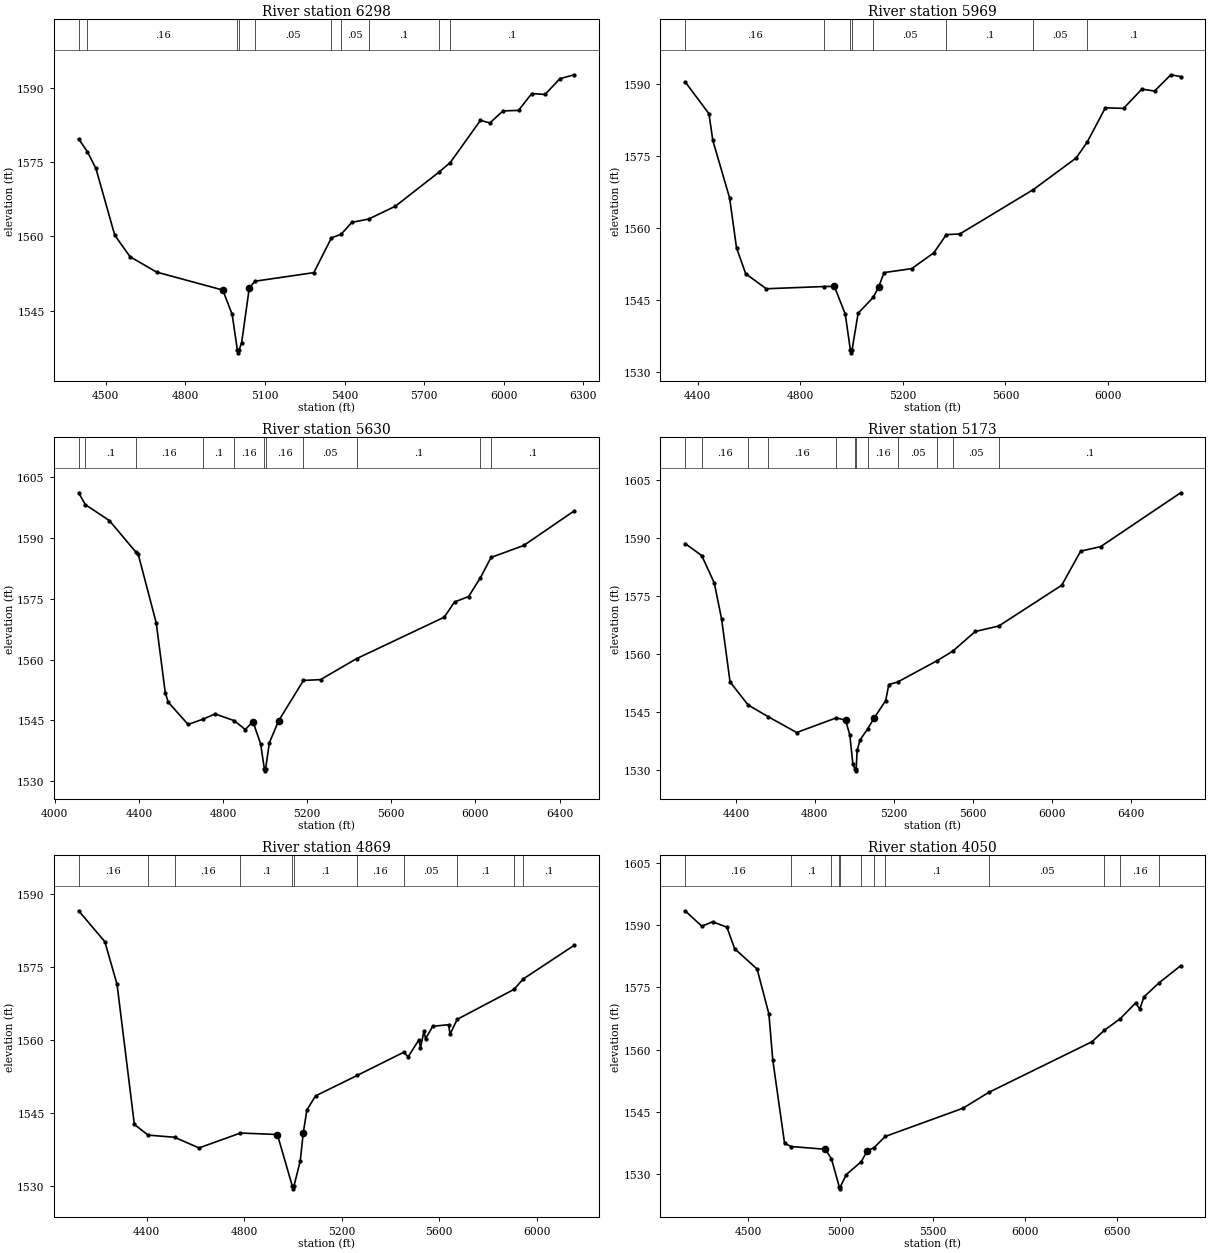
Type RM Length L Ch R = 1 ,6298    ,329,329,329
BEGIN DESCRIPTION:
EAST FORK WILLIAMS CREEK 14.0
END DESCRIPTION:
XS GIS Cut Line= 2
      2848005.23     10028835.57      2849137.59     10030319.34
#Sta/Elev= 30
  4398.5 1579.67  4431.9 1577.04  4463.5 1573.71  4534.6 1560.24  4592.3 1555.91
    4692 1552.81  4941.5 1549.19  4976.8 1544.27  4996.6 1537.03  4999.3 1536.53
  5002.6 1537.03  5012.6 1538.59  5041.2  1549.6  5062.8 1550.97  5284.4  1552.7
  5350.7 1559.71  5387.5 1560.45  5427.7 1562.84  5490.7  1563.5  5591.2 1566.08
  5754.6 1572.91  5798.4  1574.9    5912  1583.4  5947.4 1582.88  5997.3 1585.31
  6055.4 1585.41  6105.3 1588.81  6155.2 1588.62  6211.3  1591.8    6265 1592.59
#Mann= 10 ,-1 , 0
  4398.5      .1       0  4431.9     .16       0  4996.6     .07       0
  5002.6     .16       0  5062.8     .05       0  5350.7      .1       0
  5387.5     .05       0  5490.7      .1       0  5754.6     .05       0
  5798.4      .1       0
Bank Sta=4941.5,5041.2
XS Rating Curve= 0 ,0
Exp/Cntr=0.3,0.1

Type RM Length L Ch R = 1 ,5969    ,339,339,339
BEGIN DESCRIPTION:
Mapping XS 45f0504a
END DESCRIPTION:
XS GIS Cut Line= 3
      2847731.81     10028970.14      2848387.18     10029916.29
      2848981.79      10030424.1
#Sta/Elev= 30
  4350.7  1590.4  4443.9 1583.76  4458.7 1578.24  4524.3 1566.26  4551.3  1555.9
  4587.1 1550.51  4667.5 1547.39    4892 1547.85    4933 1547.88  4975.5  1542.1
  4995.6 1534.57  4998.3 1534.07  5001.6 1534.57  5025.6  1542.3  5085.2 1545.64
    5106 1547.81  5126.9 1550.75  5234.4 1551.57  5320.8 1554.85  5369.6 1558.64
  5422.2 1558.77  5708.7 1567.99  5876.6 1574.59  5919.5 1577.91  5989.9 1584.99
    6061 1584.88  6132.4 1588.88  6181.8 1588.48  6245.4 1591.86  6283.6 1591.48
#Mann= 8 ,-1 , 0
  4350.7     .16       0    4892      .1       0  4995.6     .07       0
  5001.6      .1       0  5085.2     .05       0  5369.6      .1       0
  5708.7     .05       0  5919.5      .1       0
Bank Sta=4933,5106
XS Rating Curve= 0 ,0
Exp/Cntr=0.3,0.1

Type RM Length L Ch R = 1 ,5630    ,457,457,457
BEGIN DESCRIPTION:
EAST FORK WILLIAMS CREEK 13.0
END DESCRIPTION:
XS GIS Cut Line= 3
      2847330.22     10028997.52      2848097.11      10030080.2
      2848972.25     10030621.52
#Sta/Elev= 30
  4113.8 1601.15  4145.4 1598.24  4260.1 1594.29  4387.2 1586.45  4396.7 1586.07
  4482.8 1569.03  4525.8 1551.82  4539.4 1549.54  4634.2 1544.02  4703.7  1545.3
  4762.2 1546.61  4853.7 1544.95  4905.7 1542.77  4942.5 1544.68  4978.8 1539.29
  4996.7 1533.08  4999.4 1532.58  5002.7 1533.08  5020.6 1539.52  5064.9 1544.95
  5182.6 1554.87  5264.2 1555.08  5435.4 1560.25  5851.9 1570.47  5900.7 1574.22
  5967.7 1575.56  6024.2 1580.23  6074.5  1585.2    6230 1588.16  6469.6 1596.68
#Mann= 11 ,-1 , 0
  4113.8     .05       0  4145.4      .1       0  4387.2     .16       0
  4703.7      .1       0  4853.7     .16       0  4996.7     .07       0
  5002.7     .16       0  5182.6     .05       0  5435.4      .1       0
  6024.2     .05       0  6074.5      .1       0
Bank Sta=4942.5,5064.9
XS Rating Curve= 0 ,0
Exp/Cntr=0.3,0.1

Type RM Length L Ch R = 1 ,5173    ,304,304,304
BEGIN DESCRIPTION:
EAST FORK WILLIAMS CREEK 12.0
END DESCRIPTION:
XS GIS Cut Line= 3
      2847059.54      10029358.4      2847420.44     10029962.91
      2848981.26     10030874.14
#Sta/Elev= 30
  4142.4 1588.46  4226.5 1585.35  4290.4 1578.25  4327.4 1568.93  4370.2 1552.68
  4461.7 1546.71  4563.9 1543.67  4707.7 1539.59  4908.4 1543.37  4955.7 1542.79
  4977.2 1538.92  4992.9 1531.33  5003.3 1530.18    5006 1529.68  5009.3 1530.18
  5014.4 1534.97  5029.4  1537.7  5067.8 1540.53  5100.4 1543.33  5159.1 1547.86
  5174.8 1551.98  5219.7 1552.65  5420.9  1558.2  5499.5 1560.65  5612.9 1565.71
  5731.8 1567.12  6051.1 1577.67    6147 1586.48  6248.7 1587.66  6653.8 1601.58
#Mann= 12 ,-1 , 0
  4142.4      .1       0  4226.5     .16       0  4461.7     .05       0
  4563.9     .16       0  4908.4      .1       0  5003.3     .07       0
  5009.3      .1       0  5067.8     .16       0  5219.7     .05       0
  5420.9      .1       0  5499.5     .05       0  5731.8      .1       0
Bank Sta=4955.7,5100.4
XS Rating Curve= 0 ,0
Exp/Cntr=0.3,0.1

Type RM Length L Ch R = 1 ,4869    ,819,819,819
BEGIN DESCRIPTION:
EAST FORK WILLIAMS CREEK 11.0
END DESCRIPTION:
XS GIS Cut Line= 3
      2846879.08     10029592.97      2847519.69     10030459.13
      2848294.51     10031017.73
#Sta/Elev= 30
  4120.9  1586.5  4228.4 1580.15  4278.5 1571.38  4349.4 1542.59  4405.5 1540.39
  4514.3 1539.94  4614.6 1537.75  4784.6 1540.81    4936 1540.51  4997.7 1529.84
  5000.5 1529.34  5003.7 1529.84  5029.8 1535.05  5042.4 1540.89  5057.1 1545.55
  5092.5 1548.44  5262.9 1552.64    5454 1557.41  5472.6 1556.48  5516.7 1559.98
  5522.9 1558.33  5537.6 1561.75  5543.8 1560.19  5573.2 1562.75  5638.2 1563.09
  5644.4 1561.13  5673.5 1564.18    5907 1570.35  5943.6 1572.45  6153.4  1579.4
#Mann= 11 ,-1 , 0
  4120.9     .16       0  4405.5     .05       0  4514.3     .16       0
  4784.6      .1       0  4997.7     .07       0  5003.7      .1       0
  5262.9     .16       0    5454     .05       0  5673.5      .1       0
    5907     .16       0  5943.6      .1       0
Bank Sta=4936,5042.4
XS Rating Curve= 0 ,0
Exp/Cntr=0.3,0.1

Type RM Length L Ch R = 1 ,4050    ,370,370,370
BEGIN DESCRIPTION:
EAST FORK WILLIAMS CREEK 9.0
END DESCRIPTION:
XS GIS Cut Line= 3
      2846157.35     10029556.94      2846852.03     10030423.05
      2848232.48     10031180.94
#Sta/Elev= 30
  4158.6 1593.42  4249.5  1589.7  4307.1 1590.77  4385.2 1589.47  4427.1 1584.28
  4548.7  1579.4  4612.7 1568.56  4633.5 1557.55  4697.6 1537.42  4733.4 1536.65
  4918.4 1535.99  4951.7 1533.69  4993.8 1526.96  4996.6 1526.46  4999.8 1526.96
    5032 1529.89  5112.5 1532.98  5145.6  1535.6  5182.3 1536.38  5243.1 1539.07
  5664.1 1545.87  5804.2 1549.69  6363.4 1561.89    6430 1564.63  6515.7  1567.4
  6599.5 1571.21  6622.4 1569.76  6645.2  1572.7  6727.4 1576.09  6843.7 1580.18
#Mann= 12 ,-1 , 0
  4158.6     .16       0  4733.4      .1       0  4951.7     .16       0
  4993.8     .07       0  4999.8     .16       0  5112.5     .05       0
  5182.3     .16       0  5243.1      .1       0  5804.2     .05       0
    6430      .1       0  6515.7     .16       0  6727.4      .1       0
Bank Sta=4918.4,5145.6
XS Rating Curve= 0 ,0
Exp/Cntr=0.3,0.1

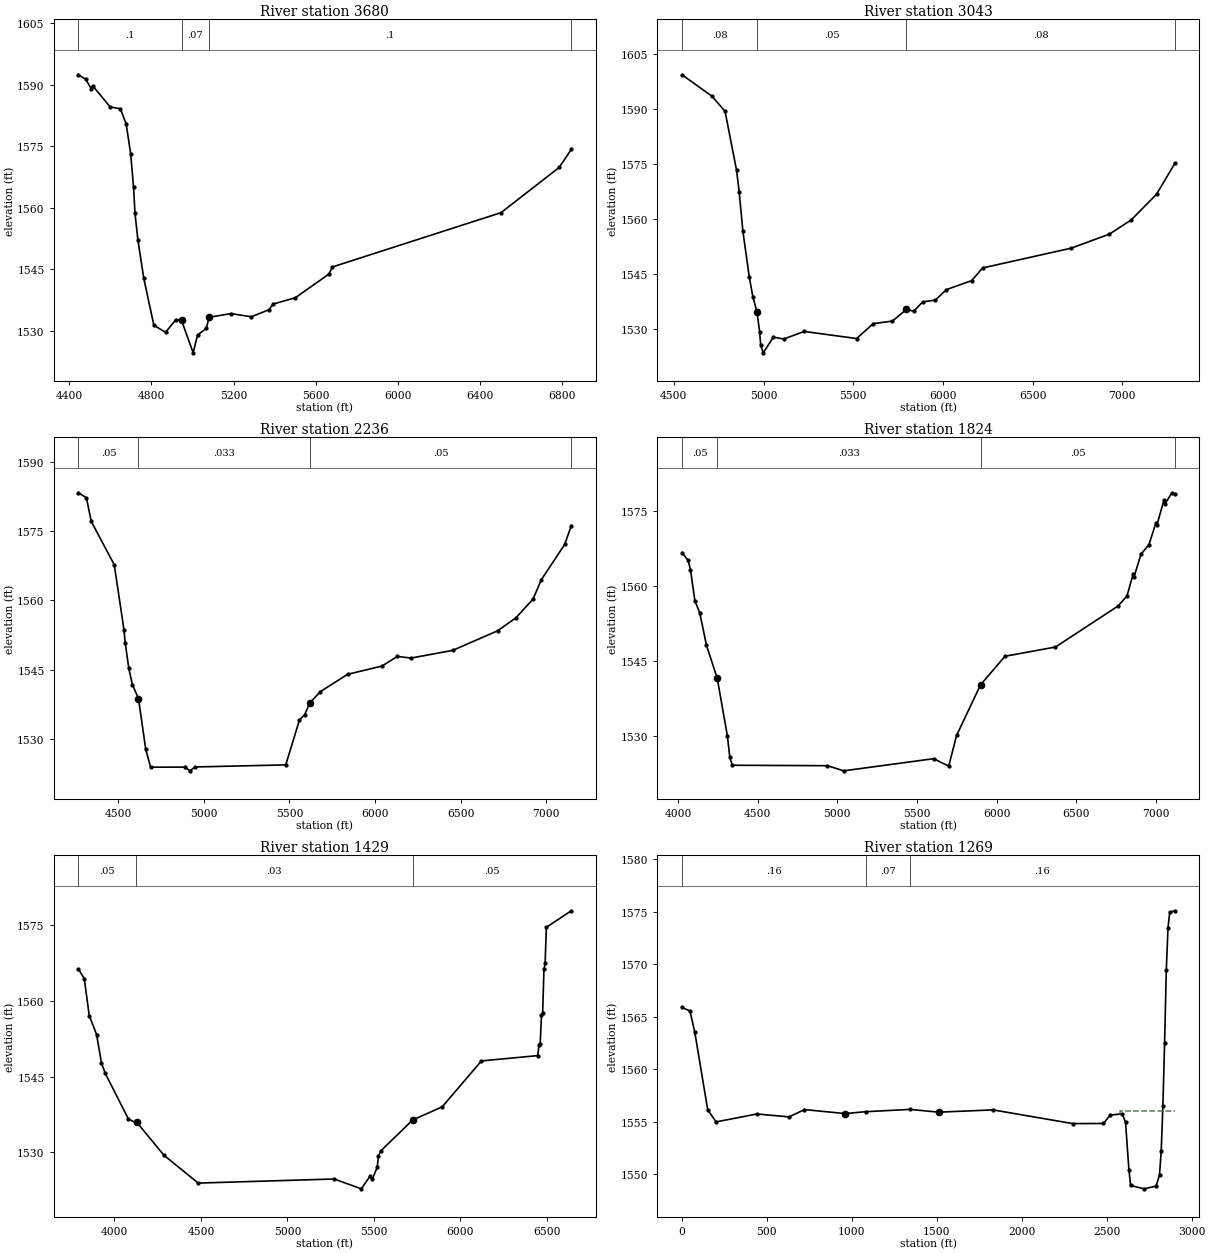
Type RM Length L Ch R = 1 ,3680    ,637,637,637
BEGIN DESCRIPTION:
EAST FORK WILLIAMS CREEK 8.0
END DESCRIPTION:
XS GIS Cut Line= 3
      2846040.03     10030044.11      2846689.63     10030765.89
      2848033.68     10031243.98
#Sta/Elev= 30
  4445.7  1592.4  4479.8 1591.34  4508.2 1589.01  4514.9 1589.71  4600.1 1584.56
  4649.4 1584.13  4677.8 1580.38  4699.5 1573.17  4713.7 1564.96  4720.5 1558.67
  4734.7 1552.19  4763.1 1542.89  4812.4  1531.4  4869.2 1529.69  4918.5 1532.72
  4946.9 1532.62  5003.5 1524.69  5024.7 1529.03  5067.3 1530.62  5081.5 1533.35
  5187.6 1534.25    5287 1533.47  5372.2  1535.2  5393.1 1536.58  5500.4  1538.1
  5664.4 1543.88  5680.9  1545.6  6501.4 1558.83  6784.7 1569.85  6843.3 1574.24
#Mann= 4 ,-1 , 0
  4445.7      .1       0  4946.9     .07       0  5081.5      .1       0
  6843.3     .16       0
Bank Sta=4946.9,5081.5
XS Rating Curve= 0 ,0
Exp/Cntr=0.3,0.1

Type RM Length L Ch R = 1 ,3043    ,807,807,807
BEGIN DESCRIPTION:
EAST FORK WILLIAMS CREEK 7.0
END DESCRIPTION:
XS GIS Cut Line= 3
      2845507.69     10030468.14      2846427.99     10031189.94
      2847988.89     10031415.51
#Sta/Elev= 30
  4545.5  1599.3  4713.3 1593.45  4785.6 1589.36  4849.7 1573.34  4864.2 1567.54
    4885 1556.73  4920.3 1544.38  4941.1 1538.78  4963.6  1534.8  4978.1 1529.42
  4984.4 1525.65  4998.7 1523.65    5055 1527.93  5112.8 1527.41  5226.7 1529.47
  5518.7 1527.54  5611.8 1531.61  5717.9 1532.28  5796.4 1535.45  5836.8 1534.98
  5887.3 1537.51  5958.1 1538.01  6018.7 1540.84  6160.1  1543.3  6220.8 1546.74
  6715.9 1552.14    6928 1555.96  7049.3 1559.81  7190.7 1566.82  7292.2 1575.18
#Mann= 4 ,-1 , 0
  4545.5     .08       0  4963.6     .05       0  5796.4     .08       0
  7292.2     .16       0
Bank Sta=4963.6,5796.4
XS Rating Curve= 0 ,0
Exp/Cntr=0.3,0.1

Type RM Length L Ch R = 1 ,2236    ,412,412,412
BEGIN DESCRIPTION:
EAST FORK WILLIAMS CREEK 5.0
END DESCRIPTION:
XS GIS Cut Line= 4
       2845291.2     10031045.61      2845643.04      10031415.5
      2846193.41     10031641.06      2847961.74     10031505.73
#Sta/Elev= 30
    4268 1583.33  4314.3 1582.23  4342.6 1577.12  4476.9 1567.72  4533.5 1553.67
  4540.8 1550.83  4561.8 1545.26  4582.9 1541.75  4618.4 1538.73  4660.9  1527.7
  4689.2 1523.84  4889.8 1523.86  4918.9 1523.05  4948.6 1523.89  5478.7 1524.34
  5558.9  1534.1    5589 1535.21  5619.1 1537.75  5679.2 1540.18  5839.7 1543.97
  6040.3 1545.76  6130.6 1547.85  6210.8  1547.5  6454.3 1549.17  6715.8  1553.4
  6822.6  1556.2  6922.9 1560.27  6972.2 1564.52  7107.9 1572.12  7146.8 1576.21
#Mann= 4 ,-1 , 0
    4268     .05       0  4618.4    .033       0  5619.1     .05       0
  7146.8     .16       0
Bank Sta=4618.4,5619.1
XS Rating Curve= 0 ,0
Exp/Cntr=0.3,0.1

Type RM Length L Ch R = 1 ,1824    ,395,395,395
BEGIN DESCRIPTION:
EAST FORK WILLIAMS CREEK 4.0
END DESCRIPTION:
XS GIS Cut Line= 4
      2845029.51     10031469.62      2845670.11     10031866.62
      2846211.45     10031974.88      2847961.79     10031604.97
#Sta/Elev= 30
  4024.2 1566.72  4062.3 1565.17  4077.7 1563.27  4105.3 1557.06  4135.6 1554.66
  4178.1 1548.11  4245.5 1541.53  4309.2 1529.97  4324.6 1525.69    4340 1524.06
  4937.9 1523.97  5039.7 1522.94  5604.7 1525.38  5699.1 1523.88  5748.8 1530.05
  5899.2 1540.19  6052.5 1545.92  6369.4 1547.77  6762.5 1555.99  6819.1 1558.05
  6856.9 1562.38    6862 1561.75  6906.6 1566.39  6956.3 1568.29    7001 1572.72
  7006.1 1572.18  7050.7 1577.23  7055.8 1576.38  7100.4 1578.71  7118.9 1578.47
#Mann= 4 ,-1 , 0
  4024.2     .05       0  4245.5    .033       0  5899.2     .05       0
  7118.9     .05       0
Bank Sta=4245.5,5899.2
XS Rating Curve= 0 ,0
Exp/Cntr=0.3,0.1

Type RM Length L Ch R = 1 ,1429    ,160,160,160
BEGIN DESCRIPTION:
EAST FORK WILLIAMS CREEK 3.0
END DESCRIPTION:
XS GIS Cut Line= 2
      2845009.53     10031505.44      2847146.69     10033389.27
#Sta/Elev= 30
    3792 1566.28  3825.6 1564.42    3854  1557.1  3896.7 1553.33  3924.3 1547.79
    3946 1545.69  4080.7 1536.59  4123.4 1535.85  4130.1 1535.91  4285.7 1529.42
    4484  1523.9  5270.4 1524.71  5426.6 1522.76  5476.2 1525.22  5490.5 1524.71
  5518.9    1527  5525.6  1529.2  5539.8 1530.29  5723.9 1536.41  5894.6 1539.01
  6121.3 1548.11  6446.7 1549.16  6454.3 1551.26    6461 1551.53  6468.5 1557.13
  6475.2 1557.57  6482.7 1566.24  6489.4 1567.44  6496.6 1574.59  6640.9 1577.86
#Mann= 3 ,-1 , 0
    3792     .05       0  4123.4     .03       0  5723.9     .05       0
Bank Sta=4130.1,5723.9
XS Rating Curve= 0 ,0
Exp/Cntr=0.3,0.1

Type RM Length L Ch R = 1 ,1269    ,1000,1000,1000
BEGIN DESCRIPTION:
Mapping XS 7414e3d0
END DESCRIPTION:
XS GIS Cut Line= 3
     2844860.155    10031519.379     2844930.282    10031659.102
     2847023.458    10033463.564
#Sta/Elev= 30
       01565.88647.314481565.53675.703161563.502151.40631556.144200.86781554.987
 440.8591555.739630.85211555.462720.84881556.156960.84011555.7791080.8361555.955
1340.8261556.176 1510.821555.9121830.8081556.1292300.7911554.8222480.7851554.835
2520.7831555.6312590.7811555.756 2610.781554.9592630.7791550.4252640.7791548.933
2720.7761548.6152790.7731548.8812810.7731549.9342820.772 1552.212830.7721556.534
2840.7711562.5372850.7711569.4332860.771 1573.442870.7711574.9352900.7691575.078
#Mann= 3 ,-1 , 0
       0     .16       01080.836     .07       01340.826     .16       0
#XS Ineff= 2 , 0
                         2581.18         1555.99
Permanent Ineff=
       T       T
Bank Sta=960.8401,1510.82
XS Rating Curve= 0 ,0
Exp/Cntr=0.3,0.1

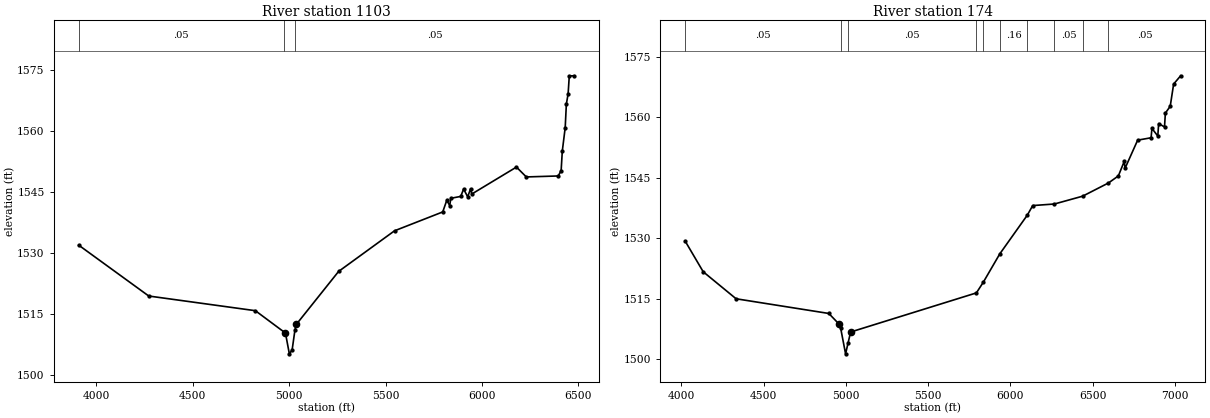
Type RM Length L Ch R = 1 ,1103    ,929,929,929
BEGIN DESCRIPTION:
EAST FORK WILLIAMS CREEK 2.0
END DESCRIPTION:
XS GIS Cut Line= 3
      2844949.42     10031869.01      2846303.59     10033061.72
       2846943.8     10033483.32
#Sta/Elev= 30
  3907.7 1531.97  4271.6 1519.47  4824.7 1515.87  4972.8 1510.66  4980.3 1510.51
    5001 1505.28  5015.4 1506.22  5029.7 1511.02  5037.2 1512.51  5256.4  1525.5
  5546.7 1535.48  5796.8 1540.11  5817.9 1542.97    5833 1541.67  5838.9 1543.46
  5890.2 1543.92  5905.2 1545.73  5926.3 1543.82  5941.4 1545.79  5947.4  1544.5
  6179.3 1551.12  6230.5  1548.7  6396.2 1548.94  6411.2 1550.27  6417.2 1555.05
  6432.3 1560.82  6438.3 1566.61  6447.4 1569.08  6453.4 1573.49  6478.8 1573.53
#Mann= 3 ,-1 , 0
  3907.7     .05       0  4972.8    .035       0  5029.7     .05       0
Bank Sta=4980.3,5037.2
XS Rating Curve= 0 ,0
Exp/Cntr=0.3,0.1

Type RM Length L Ch R = 1 ,174     ,0,0,0
BEGIN DESCRIPTION:
EAST FORK WILLIAMS CREEK 1.0
END DESCRIPTION:
XS GIS Cut Line= 4
      2844927.91     10031933.73      2844938.33     10032751.42
      2845058.12     10033074.33      2846849.76     10033532.66
#Sta/Elev= 30
  4022.5 1529.29  4132.5 1521.66  4332.5 1514.96    4896 1511.32    4960  1508.6
  4967.7 1507.72  4997.8 1501.31  5013.4 1504.08  5028.4 1506.72  5792.8 1516.42
  5834.2 1519.03  5934.9 1526.09  6101.9 1535.68  6135.1 1538.07  6266.9 1538.46
  6438.5  1540.4  6595.2 1543.67  6655.5 1545.42  6691.1 1549.01  6696.3 1547.32
  6772.8 1554.29  6854.4 1554.88  6859.6  1557.2  6895.2 1555.31  6900.4  1558.4
    6936 1557.56  6941.2    1561  6970.7 1562.69  6991.4  1568.2    7034 1570.25
#Mann= 10 ,-1 , 0
  4022.5     .05       0  4967.7    .035       0  5013.4     .05       0
  5792.8      .1       0  5834.2     .05       0  5934.9     .16       0
  6101.9      .1       0  6266.9     .05       0  6438.5      .1       0
  6595.2     .05       0
Bank Sta=4960,5028.4
XS Rating Curve= 0 ,0
Exp/Cntr=0.3,0.1

Chan Stop Cuts=-1
Use User Specified Reach Order=0
Composite Channel Slope=5