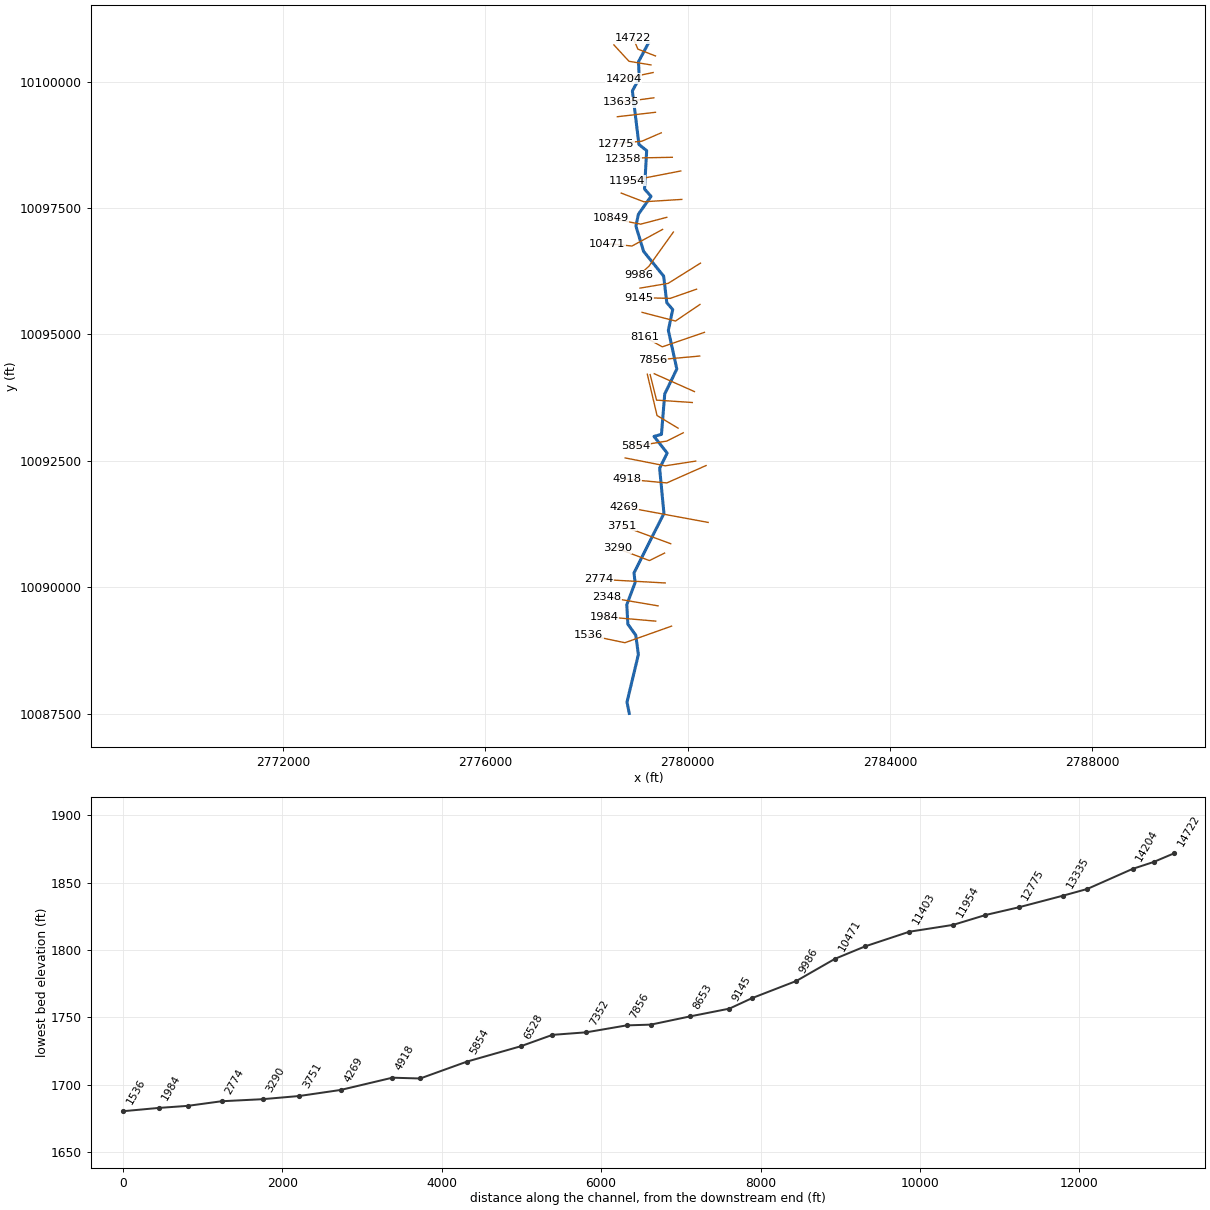
--- GAMENTHALER CREEK.prj (project) ---

Proj Title=GAMENTHALER CREEK Base Level Engineering
Current Plan=p01
Default Exp/Contr=0.3,0.1
English Units
Geom File=g01
Flow File=f01
Plan File=p01
Y Axis Title=Elevation
X Axis Title(PF)=Main Channel Distance
X Axis Title(XS)=Station
BEGIN DESCRIPTION:
GAMENTHALER CREEK
END DESCRIPTION:
DSS Export Rating Curves= 0
DSS Export Rating Curve Sorted= 0
DSS Export Volume Flow Curves= 0
DXF OffsetX= 0
DXF OffsetY= 0
DXF ScaleX= 1
DXF ScaleY= 10

--- GAMENTHALER CREEK.p01 (plan) ---

Plan Title=Multiple Run
Short Identifier=Multiple
Geom File=g01
Flow File=f01
Subcritical Flow
K Sum by GR= 0
Std Step Tol= 0.01
Critical Tol= 0.01
Num of Std Step Trials= 20
Max Error Tol= 0.3
Flow Tol Ratio= 0.001
Split Flow NTrial= 30
Split Flow Tol= 0.02
Split Flow Ratio= 0.02
Log Output Level= 0
Friction Slope Method= 1
Unsteady Friction Slope Method= 2
Unsteady Bridges Friction Slope Method= 1
Parabolic Critical Depth
Global Vel Dist=  1 , 1 , 1
Global Log Level= 0
CheckData=True
Encroach Param= -1, 0, 0, 0
BEGIN DESCRIPTION:
Multiple Run
END DESCRIPTION:

--- GAMENTHALER CREEK.f01 (steady flow) ---

Flow Title=Multiple
Program Version=4.10
Number of Profiles= 7
Profile Names=10-year,25-year,50-year,1pct_min,100-year,1pct_plu,500-year
River Rch & RM=GAMENTHALER CREE,Reach-1         ,14722
     969    1416    1808    1690    2285    3090    3666
River Rch & RM=GAMENTHALER CREE,Reach-1         ,5854
    1556    2326    3013    2852    3857    5216    6350
Boundary for River Rch & Prof#=GAMENTHALER CREE,Reach-1         , 1
Up Type= 0
Dn Type= 3
Dn Slope=0.0062
Boundary for River Rch & Prof#=GAMENTHALER CREE,Reach-1         , 2
Up Type= 0
Dn Type= 3
Dn Slope=0.0062
Boundary for River Rch & Prof#=GAMENTHALER CREE,Reach-1         , 3
Up Type= 0
Dn Type= 3
Dn Slope=0.0062
Boundary for River Rch & Prof#=GAMENTHALER CREE,Reach-1         , 4
Up Type= 0
Dn Type= 3
Dn Slope=0.0062
Boundary for River Rch & Prof#=GAMENTHALER CREE,Reach-1         , 5
Up Type= 0
Dn Type= 3
Dn Slope=0.0062
Boundary for River Rch & Prof#=GAMENTHALER CREE,Reach-1         , 6
Up Type= 0
Dn Type= 3
Dn Slope=0.0062
Boundary for River Rch & Prof#=GAMENTHALER CREE,Reach-1         , 7
Up Type= 0
Dn Type= 3
Dn Slope=0.0062
DSS Import GetInterval= 0
DSS Import GetPeak= 0
DSS Import FillOption= 0

--- GAMENTHALER CREEK.g01 (geometry) ---

Geom Title=Existing Conditions
Program Version=4.10

River Reach=GAMENTHALER CREE,Reach-1
Reach XY= 30
      2779224.17     10100759.49      2779030.39     10100395.74
      2779046.68      10100069.3      2778909.77     10099818.81
      2779040.07      10098759.1       2779192.2     10098637.62
      2779150.18     10097879.12      2779278.52     10097732.76
      2779028.54      10097378.8      2778979.75     10097144.17
      2779131.58     10096645.09      2779528.47     10096153.73
      2779590.44     10095629.37      2779707.57     10095493.37
      2779620.72      10095083.8       2779788.7     10094317.28
      2779549.68     10093823.73      2779484.75     10093024.57
       2779338.2     10092983.27      2779597.95     10092654.25
      2779448.81     10092353.59      2779533.64     10091460.39
      2778942.48     10090284.32      2778963.56     10090090.59
      2778799.47     10089653.33      2778820.17     10089269.38
      2778977.22     10089049.22      2779028.73     10088668.71
      2778803.53     10087726.85      2778848.47     10087503.73

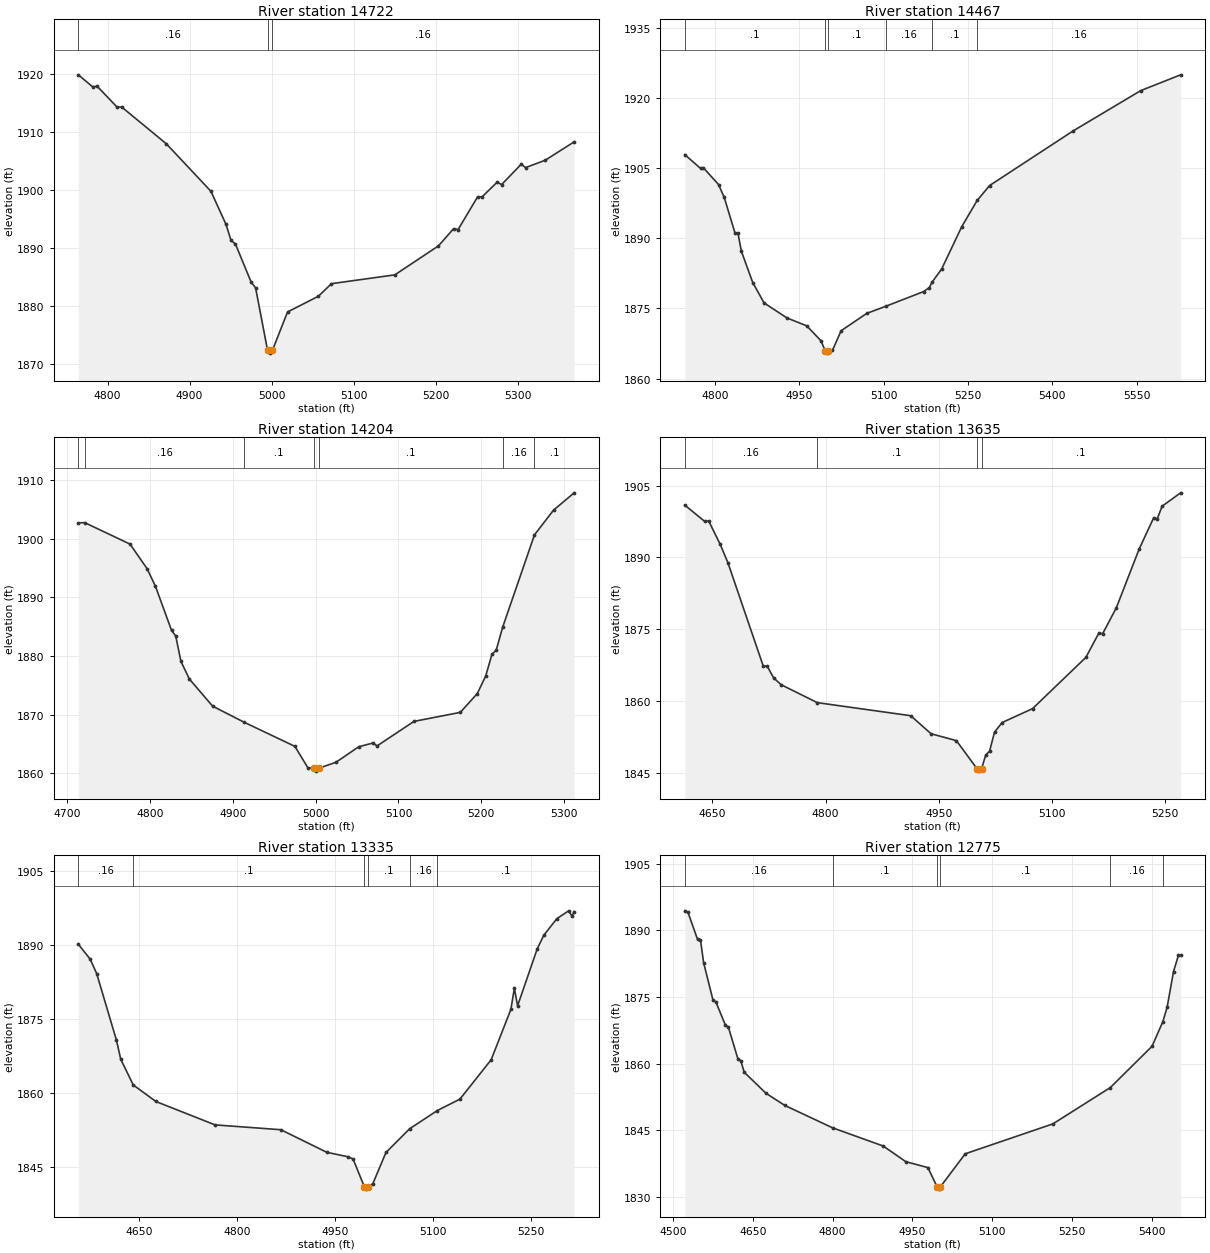
Type RM Length L Ch R = 1 ,14722   ,255,255,255
BEGIN DESCRIPTION:
GAMENTHALER CREEK 32.0
END DESCRIPTION:
XS GIS Cut Line= 3
      2779366.39     10100511.07      2779017.41     10100646.49
      2778929.14     10100859.39
#Sta/Elev= 30
  4764.3 1919.83  4781.8 1917.76  4787.2 1917.87  4811.7 1914.24  4817.1 1914.29
  4871.6 1907.94    4926 1899.75  4944.4 1894.05  4950.6 1891.26  4955.9 1890.66
  4975.1 1884.08  4980.5  1883.1  4995.1 1872.33  4997.8 1871.83  5001.1 1872.33
  5019.5 1878.93  5057.1 1881.64  5073.1 1883.81  5150.4 1885.33  5203.6 1890.33
    5222 1893.29  5227.5 1893.14  5251.3 1898.78  5256.8 1898.79  5275.2 1901.32
  5280.6  1900.9  5304.5  1904.4  5309.9 1903.83  5333.8  1905.1  5369.1 1908.27
#Mann= 3 ,-1 , 0
  4764.3     .16       0  4995.1     .07       0  5001.1     .16       0
Bank Sta=4995.1,5001.1
XS Rating Curve= 0 ,0
Exp/Cntr=0.3,0.1

Type RM Length L Ch R = 1 ,14467   ,263,263,263
BEGIN DESCRIPTION:
Mapping XS 01933a99
END DESCRIPTION:
XS GIS Cut Line= 3
      2779277.62     10100333.56      2778842.71     10100405.18
      2778544.24      10100729.6
#Sta/Elev= 30
  4746.5 1907.85  4774.7 1904.89  4779.7 1905.02  4806.5 1901.46  4816.6 1898.72
  4835.8 1891.09  4840.9 1891.16    4847 1887.25  4867.3 1880.52  4887.5 1876.16
  4928.1 1872.96  4963.3 1871.27  4988.9 1868.04    4996 1865.94  4998.8 1865.44
    5002 1865.94  5009.1 1866.03  5024.4 1870.22    5070 1873.93  5103.9 1875.45
  5171.3  1878.6  5181.4 1879.46    5186 1880.57  5203.3 1883.44    5239 1892.47
  5266.3 1898.05  5288.4 1901.24    5437 1912.92  5557.2 1921.53  5628.1  1924.9
#Mann= 6 ,-1 , 0
  4746.5      .1       0    4996     .07       0    5002      .1       0
  5103.9     .16       0    5186      .1       0  5266.3     .16       0
Bank Sta=4996,5002
XS Rating Curve= 0 ,0
Exp/Cntr=0.3,0.1

Type RM Length L Ch R = 1 ,14204   ,569,569,569
BEGIN DESCRIPTION:
GAMENTHALER CREEK 31.0
END DESCRIPTION:
XS GIS Cut Line= 2
      2779319.52     10100182.96      2778734.08     10100058.62
#Sta/Elev= 30
  4713.6 1902.75  4721.4 1902.78    4776 1899.12  4796.5 1894.94  4806.7 1891.91
  4826.1 1884.38  4831.2 1883.41  4837.4  1879.1  4847.6 1876.07  4875.7 1871.43
  4913.8 1868.68    4975 1864.56  4990.7  1860.9  4997.9 1860.83  5000.7 1860.33
  5003.9 1860.83  5024.6 1861.84    5052 1864.49  5069.1 1865.13  5074.2 1864.64
  5118.8 1868.83  5174.7 1870.37  5195.2 1873.59  5205.4 1876.61  5212.9 1880.31
    5218    1881  5225.8 1884.92  5264.2  1900.7  5287.2 1904.92  5312.1 1907.88
#Mann= 7 ,-1 , 0
  4713.6      .1       0  4721.4     .16       0  4913.8      .1       0
  4997.9     .07       0  5003.9      .1       0  5225.8     .16       0
  5264.2      .1       0
Bank Sta=4997.9,5003.9
XS Rating Curve= 0 ,0
Exp/Cntr=0.3,0.1

Type RM Length L Ch R = 1 ,13635   ,300,300,300
BEGIN DESCRIPTION:
GAMENTHALER CREEK 30.0
END DESCRIPTION:
XS GIS Cut Line= 2
      2779335.09     10099682.95      2778684.08     10099594.41
#Sta/Elev= 30
  4613.4 1900.92  4639.9  1897.5    4645 1897.63  4660.4  1892.7  4670.5 1888.91
  4717.4 1867.31  4722.5 1867.34  4731.1 1864.86  4741.2 1863.43    4789  1859.7
  4912.8 1856.97  4939.7 1853.21  4973.3 1851.77  5000.6 1845.91  5003.3 1845.41
  5006.6 1845.91  5012.2 1848.79  5017.2 1849.54  5023.8 1853.54  5033.9 1855.55
  5074.2 1858.45  5144.9 1869.15  5162.1 1874.24  5167.1 1874.09  5185.2 1879.49
  5215.5 1891.77  5234.5  1898.2  5239.5 1898.07  5245.8 1900.68  5270.4 1903.48
#Mann= 4 ,-1 , 0
  4613.4     .16       0    4789      .1       0  5000.6     .07       0
  5006.6      .1       0
Bank Sta=5000.6,5006.6
XS Rating Curve= 0 ,0
Exp/Cntr=0.3,0.1

Type RM Length L Ch R = 1 ,13335   ,560,560,560
BEGIN DESCRIPTION:
GAMENTHALER CREEK 29.0
END DESCRIPTION:
XS GIS Cut Line= 2
      2779366.41      10099396.5      2778612.27     10099308.08
#Sta/Elev= 30
  4557.1  1890.1  4575.2 1887.08  4585.2 1884.15  4615.4 1870.69  4622.1 1866.78
  4641.2  1861.6  4675.8 1858.25  4766.5 1853.51  4867.2 1852.53  4937.6 1847.96
  4970.1 1847.05  4977.9 1846.59    4995    1841  4997.8  1840.5    5001    1841
  5008.1  1841.6  5028.2 1847.92  5064.3 1852.71  5106.8 1856.41  5141.5 1858.73
  5189.3  1866.7  5219.5  1876.9  5224.8 1881.15  5229.8 1877.64  5259.8 1889.14
  5269.9 1891.91    5290 1895.29    5308 1896.86    5313 1895.77  5316.4 1896.72
#Mann= 6 ,-1 , 0
  4557.1     .16       0  4641.2      .1       0    4995     .07       0
    5001      .1       0  5064.3     .16       0  5106.8      .1       0
Bank Sta=4995,5001
XS Rating Curve= 0 ,0
Exp/Cntr=0.3,0.1

Type RM Length L Ch R = 1 ,12775   ,417,417,417
BEGIN DESCRIPTION:
GAMENTHALER CREEK 28.0
END DESCRIPTION:
XS GIS Cut Line= 3
      2779480.95     10098990.24      2779095.54     10098823.58
      2778585.09      10098776.7
#Sta/Elev= 30
  4522.2  1894.4  4528.2 1894.05  4546.2 1887.96  4551.7 1887.87  4557.6 1882.73
  4575.2 1874.33  4580.6 1873.91  4598.7 1868.64  4604.1 1868.26  4622.1 1861.09
  4627.6 1860.64  4633.9  1858.1  4674.6 1853.38  4710.1 1850.63    4800 1845.59
  4895.3 1841.49  4937.8 1837.97  4979.3 1836.64  4996.8 1832.29  4999.5 1831.79
  5002.8 1832.29  5049.6 1839.74  5214.5 1846.47  5322.6 1854.65  5401.1 1863.95
  5421.3 1869.48  5429.3  1872.7  5441.3 1880.73  5450.5 1884.35  5454.7 1884.35
#Mann= 6 ,-1 , 0
  4522.2     .16       0    4800      .1       0  4996.8     .07       0
  5002.8      .1       0  5322.6     .16       0  5421.3      .1       0
Bank Sta=4996.8,5002.8
XS Rating Curve= 0 ,0
Exp/Cntr=0.3,0.1

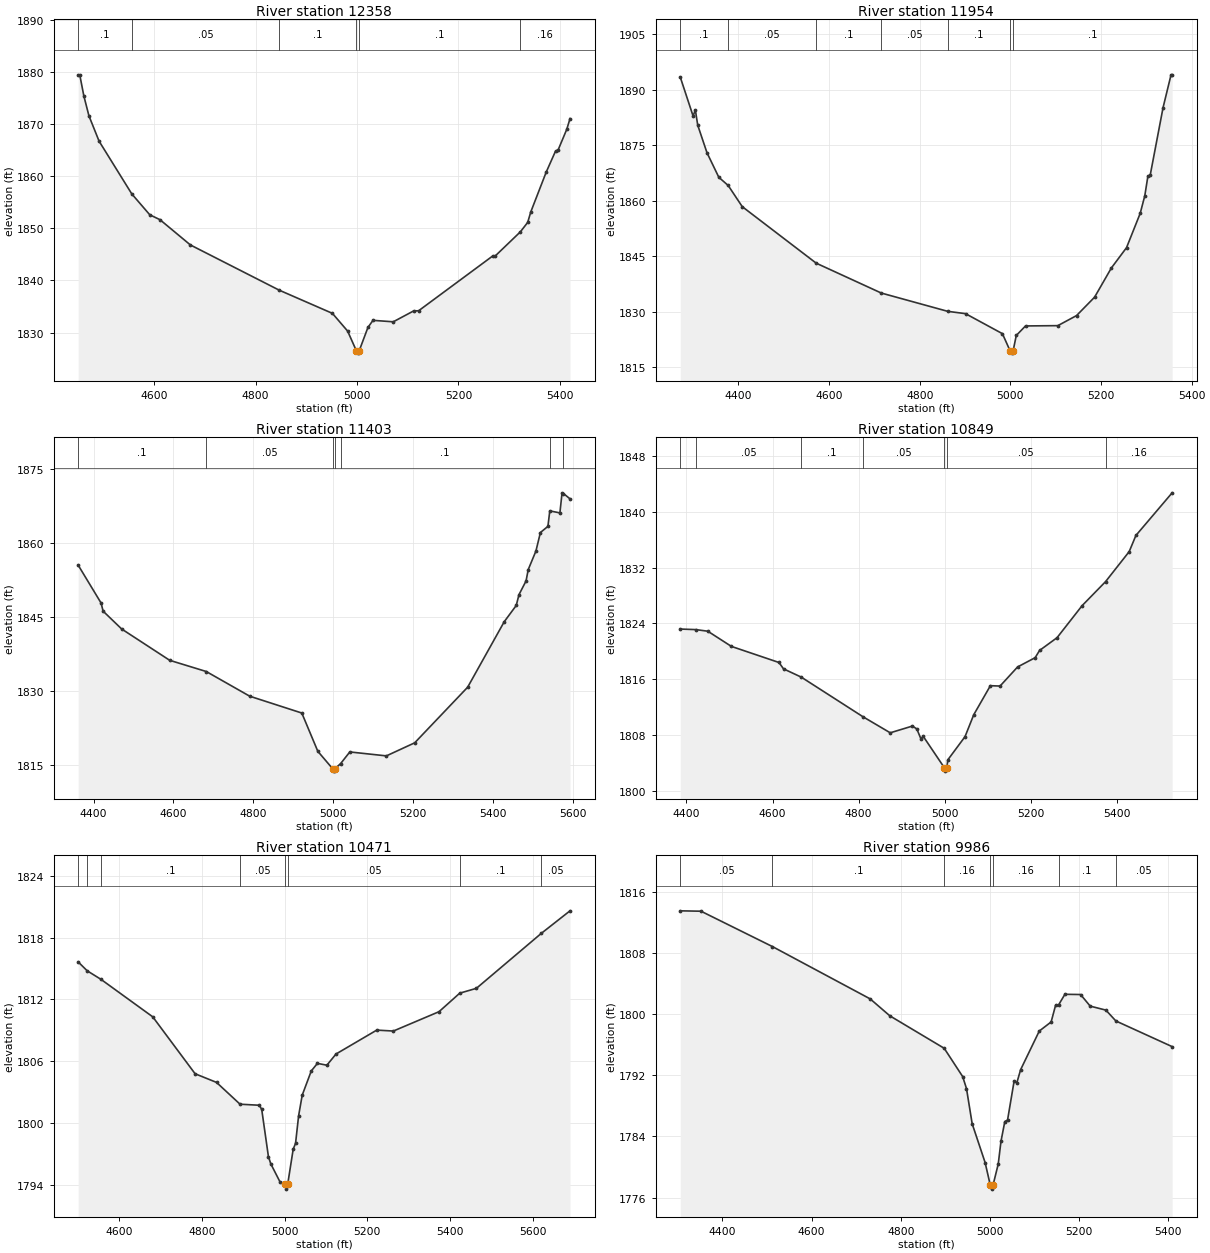
Type RM Length L Ch R = 1 ,12358   ,404,404,404
BEGIN DESCRIPTION:
GAMENTHALER CREEK 27.0
END DESCRIPTION:
XS GIS Cut Line= 3
      2779699.75     10098505.87        2778882.     10098490.24
      2778732.21     10098464.42
#Sta/Elev= 30
  4450.2 1879.46  4453.4 1879.46  4461.5 1875.39  4471.5 1871.59  4491.5 1866.73
    4556 1856.61  4591.5  1852.6  4611.5 1851.67  4671.5 1846.82  4846.5 1838.15
  4951.6 1833.69  4981.6 1830.29  4998.6 1826.56  5001.3 1826.06  5004.6 1826.56
  5021.6 1830.98  5031.6 1832.35  5071.6 1832.07  5111.6 1834.15  5121.6 1834.19
  5267.4 1844.68  5272.4 1844.68  5322.2 1849.33  5336.7 1851.15  5342.7 1853.14
  5373.2  1860.8  5391.5 1864.81  5396.6 1865.03  5413.8 1869.03  5420.1 1871.06
#Mann= 6 ,-1 , 0
  4450.2      .1       0    4556     .05       0  4846.5      .1       0
  4998.6     .07       0  5004.6      .1       0  5322.2     .16       0
Bank Sta=4998.6,5004.6
XS Rating Curve= 0 ,0
Exp/Cntr=0.3,0.1

Type RM Length L Ch R = 1 ,11954   ,551,551,551
BEGIN DESCRIPTION:
GAMENTHALER CREEK 26.0
END DESCRIPTION:
XS GIS Cut Line= 3
       2779866.4     10098235.04        2779007.     10098068.37
      2778798.64     10098042.32
#Sta/Elev= 30
  4271.5 1893.39  4299.8 1882.87  4304.8  1884.5  4310.1 1880.37  4330.5 1872.93
  4356.6  1866.3  4377.3 1864.08  4408.3 1858.36  4571.5 1843.08  4715.2    1835
  4861.6 1830.06    4901 1829.43  4982.4 1824.02  4999.8 1819.26  5002.6 1818.76
  5005.8 1819.26    5013 1823.54  5033.4 1826.11  5104.7 1826.19    5146 1828.91
  5185.8 1833.89  5222.8 1841.78  5256.3 1847.28  5286.5 1856.57  5296.6 1861.32
  5303.4 1866.57  5308.5 1866.86  5336.9 1885.14  5354.5    1894  5356.9    1894
#Mann= 7 ,-1 , 0
  4271.5      .1       0  4377.3     .05       0  4571.5      .1       0
  4715.2     .05       0  4861.6      .1       0  4999.8     .07       0
  5005.8      .1       0
Bank Sta=4999.8,5005.8
XS Rating Curve= 0 ,0
Exp/Cntr=0.3,0.1

Type RM Length L Ch R = 1 ,11403   ,554,554,554
BEGIN DESCRIPTION:
GAMENTHALER CREEK 25.0
END DESCRIPTION:
XS GIS Cut Line= 3
      2779887.25     10097672.54      2779137.21     10097625.66
      2778689.26     10097797.55
#Sta/Elev= 30
  4361.3 1855.44  4418.8 1847.74  4423.8  1846.1  4470.3 1842.48  4590.5 1836.13
    4682 1833.86  4790.9 1828.85  4921.2 1825.44  4961.3 1817.68  4998.3 1814.16
  5001.1 1813.66  5004.3 1814.16  5018.3 1815.18  5041.4 1817.55  5132.9 1816.75
  5203.8  1819.4  5336.4 1830.68  5427.9 1843.95    5458 1847.25  5464.9 1849.45
  5482.6 1852.23    5488 1854.52  5507.3 1858.29  5518.5 1862.04  5537.3 1863.29
    5542 1866.43  5567.3 1866.02  5572.7 1870.09  5576.2 1869.95  5592.6 1868.87
#Mann= 7 ,-1 , 0
  4361.3      .1       0    4682     .05       0  4998.3    .035       0
  5004.3     .05       0  5018.3      .1       0    5542     .16       0
  5576.2      .1       0
Bank Sta=4998.3,5004.3
XS Rating Curve= 0 ,0
Exp/Cntr=0.3,0.1

Type RM Length L Ch R = 1 ,10849   ,378,378,378
BEGIN DESCRIPTION:
GAMENTHALER CREEK 24.0
END DESCRIPTION:
XS GIS Cut Line= 3
      2779590.35     10097318.37      2779074.71     10097182.95
      2778475.79     10097297.53
#Sta/Elev= 30
  4385.5 1823.19  4421.6 1823.11  4449.5 1822.88  4504.3  1820.7  4614.9 1818.39
  4625.4 1817.48  4666.7 1816.29  4809.9 1810.61  4873.4  1808.3    4925 1809.27
  4935.2 1808.85  4944.8 1807.42  4949.9 1807.81    4999  1803.3  5001.7  1802.8
    5005  1803.3  5007.1 1804.41  5047.2 1807.75  5067.5  1810.9  5106.1 1815.06
  5128.6 1815.01  5169.3 1817.75  5210.1 1819.08  5220.4 1820.12    5261 1821.95
  5319.4 1826.56  5373.8    1830  5428.7 1834.31  5444.2 1836.62  5528.4 1842.74
#Mann= 7 ,-1 , 0
  4385.5      .1       0  4421.6     .05       0  4666.7      .1       0
  4809.9     .05       0    4999    .035       0    5005     .05       0
  5373.8     .16       0
Bank Sta=4999,5005
XS Rating Curve= 0 ,0
Exp/Cntr=0.3,0.1

Type RM Length L Ch R = 1 ,10471   ,485,485,485
BEGIN DESCRIPTION:
GAMENTHALER CREEK 23.0
END DESCRIPTION:
XS GIS Cut Line= 3
      2779506.95     10097078.76      2778902.83     10096750.66
      2778403.19      10096797.5
#Sta/Elev= 30
    4501 1815.64    4523 1814.77  4556.3 1813.94  4681.4  1810.3  4783.8 1804.77
  4835.6 1803.93  4892.5 1801.81  4939.2 1801.71  4944.9  1801.3  4961.1 1796.72
  4966.8 1796.02  4988.6  1794.3  5001.8 1794.06  5004.6 1793.56  5007.8 1794.06
    5021 1797.44  5026.7 1798.01  5034.1 1800.69  5042.8 1802.69  5064.7 1805.04
  5079.6 1805.78  5102.4  1805.6  5124.6 1806.69    5223 1809.01  5263.2 1808.92
  5373.6  1810.8  5423.7  1812.6    5464 1813.07  5620.9 1818.41  5690.3  1820.6
#Mann= 8 ,-1 , 0
    4501      .1       0    4523     .05       0  4556.3      .1       0
  4892.5     .05       0  5001.8    .035       0  5007.8     .05       0
  5423.7      .1       0  5620.9     .05       0
Bank Sta=5001.8,5007.8
XS Rating Curve= 0 ,0
Exp/Cntr=0.3,0.1

Type RM Length L Ch R = 1 ,9986    ,554,554,554
BEGIN DESCRIPTION:
GAMENTHALER CREEK 22.0
END DESCRIPTION:
XS GIS Cut Line= 3
      2779720.56     10097026.73      2779236.16     10096349.62
      2779034.06     10096168.24
#Sta/Elev= 30
  4305.2 1813.54  4351.8 1813.49  4512.1 1808.86  4731.5 1802.01  4775.7 1799.79
  4897.7 1795.54  4939.1 1791.84  4947.7 1790.27  4960.5 1785.65  4989.5 1780.58
  5001.2  1777.6    5004  1777.1  5007.2  1777.6    5019 1780.39  5025.1 1783.35
  5033.7 1785.94  5039.9 1786.15  5054.6 1791.24  5060.8 1791.04  5069.3 1792.75
  5111.1  1797.8  5137.7 1798.99  5147.7 1801.17  5154.3 1801.21  5168.6 1802.61
  5203.8 1802.58  5225.4 1801.06  5260.6 1800.54    5283 1799.12  5409.3 1795.76
#Mann= 7 ,-1 , 0
  4305.2     .05       0  4512.1      .1       0  4897.7     .16       0
  5001.2     .07       0  5007.2     .16       0  5154.3      .1       0
    5283     .05       0
Bank Sta=5001.2,5007.2
XS Rating Curve= 0 ,0
Exp/Cntr=0.3,0.1

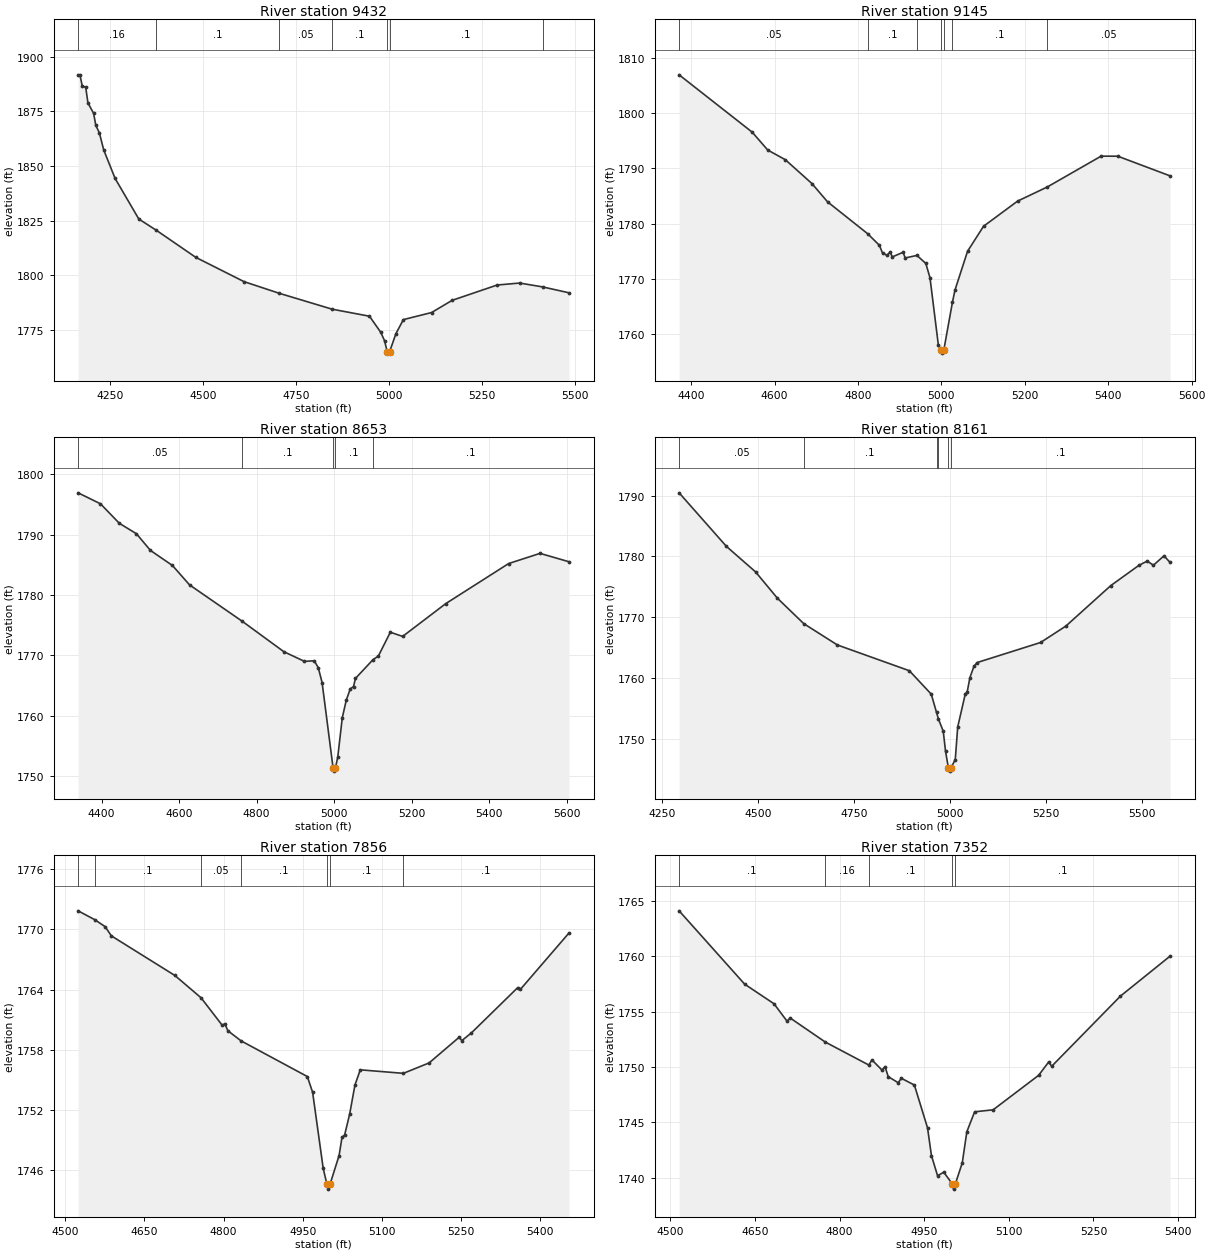
Type RM Length L Ch R = 1 ,9432    ,287,287,287
BEGIN DESCRIPTION:
GAMENTHALER CREEK 21.0
END DESCRIPTION:
XS GIS Cut Line= 3
      2780256.98     10096412.11      2779616.37     10096011.08
      2779059.08     10095917.33
#Sta/Elev= 30
  4163.6 1891.67  4168.8 1891.43  4174.7 1886.67  4184.2 1885.91  4190.1 1878.81
  4205.4 1874.05  4211.3 1868.52  4220.7 1865.23  4232.6  1857.3  4263.2 1844.28
    4327 1825.72  4374.4 1820.55  4480.4 1808.18  4610.2 1797.08  4705.2 1791.74
  4847.1 1784.49  4947.7 1781.27  4978.1  1773.9  4988.2 1770.08  4995.6 1764.89
  4998.4 1764.39  5001.6 1764.89  5018.7 1773.25  5038.9 1779.72  5114.7 1782.95
  5170.2 1788.54  5291.3 1795.54  5351.8 1796.44  5413.7 1794.67  5484.5 1791.98
#Mann= 7 ,-1 , 0
  4163.6     .16       0  4374.4      .1       0  4705.2     .05       0
  4847.1      .1       0  4995.6     .07       0  5001.6      .1       0
  5413.7     .05       0
Bank Sta=4995.6,5001.6
XS Rating Curve= 0 ,0
Exp/Cntr=0.3,0.1

Type RM Length L Ch R = 1 ,9145    ,492,492,492
BEGIN DESCRIPTION:
GAMENTHALER CREEK 20.0
END DESCRIPTION:
XS GIS Cut Line= 3
       2780178.9      10095896.5      2779658.04      10095714.2
      2779033.27     10095729.82
#Sta/Elev= 30
  4371.3 1806.94  4546.4 1796.56  4583.7 1793.32    4626 1791.56  4689.6 1787.25
  4727.2 1783.93  4823.4 1778.15  4851.4 1776.06  4859.1 1774.62  4869.7 1774.26
  4877.1 1774.83  4882.4 1773.96  4908.1 1774.79  4913.4 1773.77  4941.3 1774.23
  4962.7 1772.78  4972.7 1770.18  4992.7 1758.03  4999.7 1757.03  5002.5 1756.53
  5005.7 1757.03  5026.6 1765.78  5032.7 1767.98  5062.8 1774.99  5101.1 1779.51
  5182.8 1784.07  5253.8 1786.62  5382.9 1792.21  5422.9  1792.2  5548.1 1788.64
#Mann= 7 ,-1 , 0
  4371.3     .05       0  4823.4      .1       0  4941.3     .05       0
  4999.7    .035       0  5005.7     .05       0  5026.6      .1       0
  5253.8     .05       0
Bank Sta=4999.7,5005.7
XS Rating Curve= 0 ,0
Exp/Cntr=0.3,0.1

Type RM Length L Ch R = 1 ,8653    ,492,492,492
BEGIN DESCRIPTION:
GAMENTHALER CREEK 19.0
END DESCRIPTION:
XS GIS Cut Line= 3
      2780246.56      10095594.4      2779762.21     10095266.29
      2779102.15      10095437.8
#Sta/Elev= 30
  4339.3 1796.93  4397.1 1795.11  4445.7 1791.88    4490 1790.14    4526 1787.38
  4582.9 1784.88  4626.9 1781.67    4763 1775.63  4870.5 1770.58  4923.6 1768.98
  4948.9 1769.08  4959.2 1767.93  4969.1 1765.47  4997.5 1751.28  5000.3 1750.78
  5003.5 1751.28  5009.6 1753.15  5021.2 1759.63  5031.5 1762.55  5041.8 1764.41
  5050.2 1764.81  5055.3 1766.16  5100.4 1769.26  5114.2 1769.85  5145.2 1773.81
    5177 1773.12  5288.3 1778.56  5450.5  1785.2  5531.6 1786.89  5606.3  1785.5
#Mann= 5 ,-1 , 0
  4339.3     .05       0    4763      .1       0  4997.5    .035       0
  5003.5      .1       0  5100.4      .1       0
Bank Sta=4997.5,5003.5
XS Rating Curve= 0 ,0
Exp/Cntr=0.3,0.1

Type RM Length L Ch R = 1 ,8161    ,305,305,305
BEGIN DESCRIPTION:
GAMENTHALER CREEK 18.0
END DESCRIPTION:
XS GIS Cut Line= 3
       2780335.1     10095042.32      2779501.79     10094755.87
      2779153.19     10094948.38
#Sta/Elev= 30
  4294.9 1790.48  4418.2 1781.66    4494 1777.47  4551.2 1773.12  4619.8 1768.94
  4707.4 1765.43  4894.9 1761.19  4952.1 1757.33  4965.7 1754.33  4970.9 1753.21
  4983.3 1751.23  4989.3 1747.91  4996.8 1745.16  4999.6 1744.66  5002.8 1745.16
  5014.6 1746.54    5021 1751.94  5040.5  1757.3  5045.8 1757.72  5052.7 1760.04
  5063.3 1761.92  5071.8 1762.54    5237 1765.84    5303 1768.55  5419.8  1775.2
  5493.2 1778.54  5514.9 1779.24    5531 1778.56  5558.5  1780.1  5574.3 1779.04
#Mann= 6 ,-1 , 0
  4294.9     .05       0  4619.8      .1       0  4965.7     .16       0
  4970.9      .1       0  4996.8     .07       0  5002.8      .1       0
Bank Sta=4996.8,5002.8
XS Rating Curve= 0 ,0
Exp/Cntr=0.3,0.1

Type RM Length L Ch R = 1 ,7856    ,504,504,504
BEGIN DESCRIPTION:
GAMENTHALER CREEK 17.0
END DESCRIPTION:
XS GIS Cut Line= 2
      2780241.37     10094573.58      2779314.31     10094490.25
#Sta/Elev= 30
  4524.2 1771.85  4555.7 1770.97  4575.3 1770.28  4587.4 1769.35  4707.8  1765.4
  4757.3 1763.18  4797.4 1760.44  4802.5 1760.58  4808.2 1759.89  4833.2 1758.88
  4958.9 1755.32  4968.9 1753.75    4989 1746.15    4996 1744.59  4998.8 1744.09
    5002 1744.59  5019.1 1747.44  5024.6 1749.25  5029.6 1749.49  5039.2 1751.59
  5049.2 1754.48  5059.3 1755.99    5141 1755.64  5189.8 1756.68  5246.8 1759.24
  5251.8  1758.9  5270.1 1759.68  5357.8 1764.19  5362.8 1764.01    5455 1769.64
#Mann= 7 ,-1 , 0
  4524.2     .05       0  4555.7      .1       0  4757.3     .05       0
  4833.2      .1       0    4996     .07       0    5002      .1       0
    5141      .1       0
Bank Sta=4996,5002
XS Rating Curve= 0 ,0
Exp/Cntr=0.3,0.1

Type RM Length L Ch R = 1 ,7352    ,426,426,426
BEGIN DESCRIPTION:
GAMENTHALER CREEK 16.0
END DESCRIPTION:
XS GIS Cut Line= 2
      2780137.19     10093870.46       2779341.9     10094223.92
#Sta/Elev= 30
  4515.4 1764.12  4631.6 1757.49  4683.6 1755.72  4706.8 1754.14  4712.3 1754.43
  4774.4 1752.26  4851.7 1750.18  4857.3 1750.64  4875.1 1749.72  4880.5 1750.03
  4886.1 1749.13  4903.8 1748.58  4909.3 1748.98  4932.5 1748.37  4955.8  1744.5
  4962.7    1742  4973.6 1740.17  4984.6 1740.49  4999.3 1739.46    5002 1738.96
  5005.3 1739.46  5017.4 1741.34  5025.5 1744.15  5039.3 1745.95  5072.1 1746.13
  5152.8 1749.25  5170.5 1750.45    5176 1750.07  5297.8 1756.41  5385.7 1760.02
#Mann= 5 ,-1 , 0
  4515.4      .1       0  4774.4     .16       0  4851.7      .1       0
  4999.3     .07       0  5005.3      .1       0
Bank Sta=4999.3,5005.3
XS Rating Curve= 0 ,0
Exp/Cntr=0.3,0.1

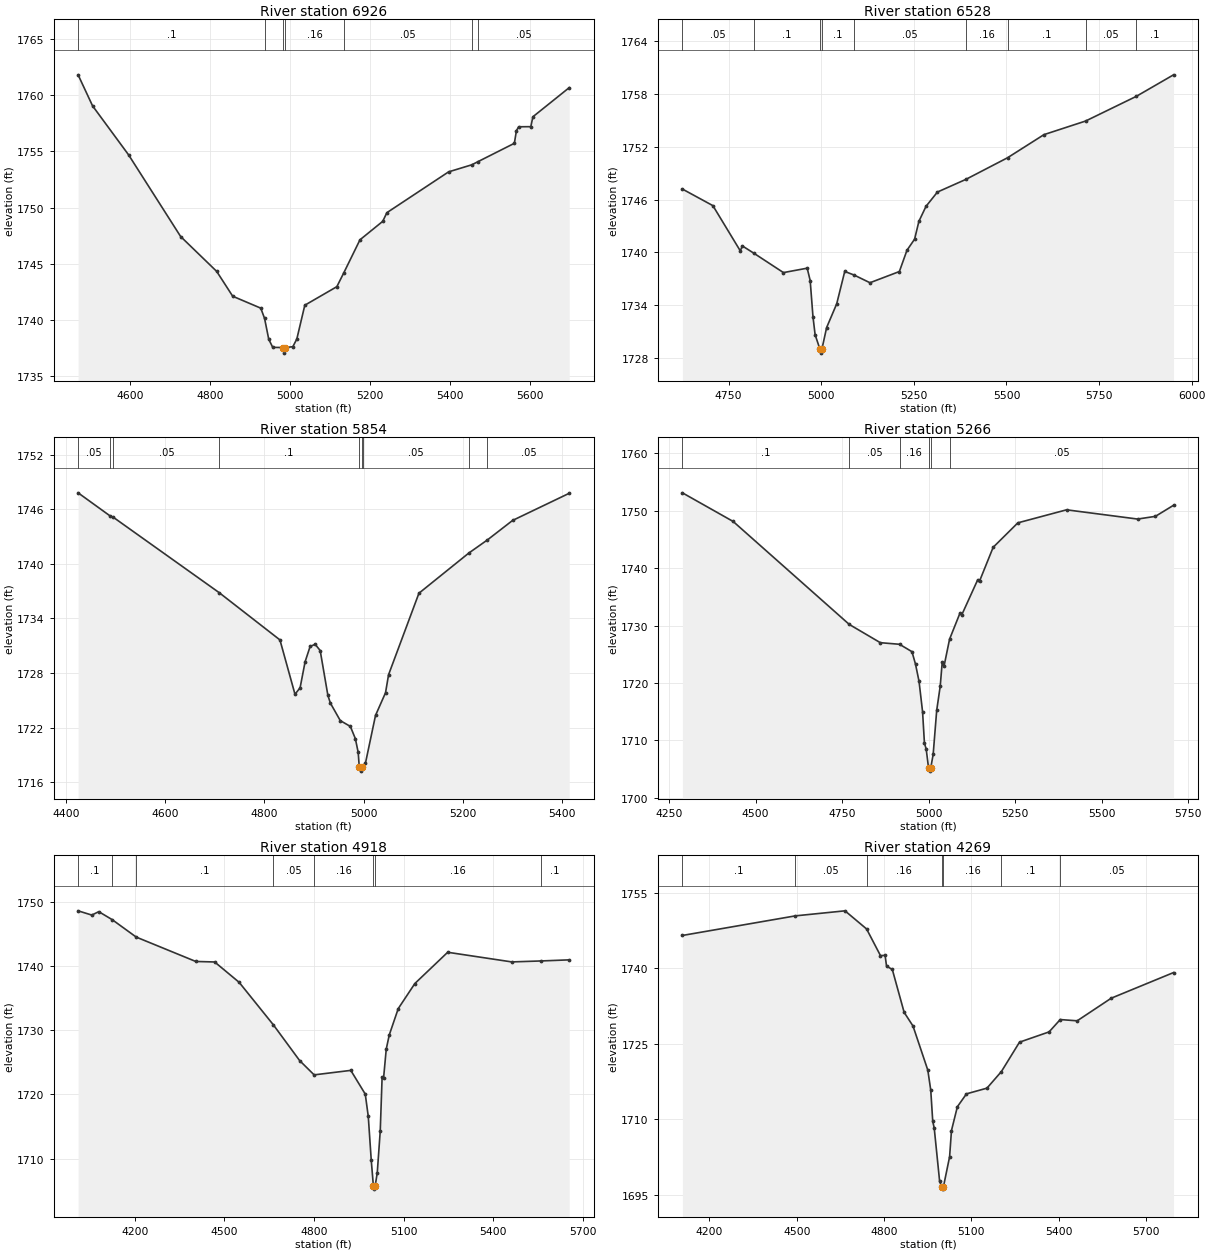
Type RM Length L Ch R = 1 ,6926    ,398,398,398
BEGIN DESCRIPTION:
GAMENTHALER CREEK 15.0
END DESCRIPTION:
XS GIS Cut Line= 3
      2780094.54     10093654.33      2779387.92     10093701.21
      2779261.19     10094206.38
#Sta/Elev= 30
  4469.6 1761.81  4505.8 1759.05    4596 1754.69  4726.2 1747.43  4816.4 1744.33
  4856.5 1742.12  4926.7 1741.06  4936.2 1740.15  4946.7 1738.29  4956.7 1737.57
  4982.5 1737.56  4985.3 1737.06  4988.5 1737.56  5006.9 1737.63  5016.9 1738.31
  5036.9 1741.32  5117.1 1742.97  5134.6 1744.21    5175 1747.14  5231.9 1748.78
  5242.3 1749.55  5396.7 1753.18  5454.9 1753.81  5470.9  1754.1  5561.3 1755.72
  5566.5 1756.85  5572.1 1757.19  5602.5  1757.2  5607.7 1758.08  5698.6 1760.67
#Mann= 7 ,-1 , 0
  4469.6      .1       0  4936.2     .16       0  4982.5     .07       0
  4988.5     .16       0  5134.6     .05       0  5454.9      .1       0
  5470.9     .05       0
Bank Sta=4982.5,4988.5
XS Rating Curve= 0 ,0
Exp/Cntr=0.3,0.1

Type RM Length L Ch R = 1 ,6528    ,674,674,674
BEGIN DESCRIPTION:
GAMENTHALER CREEK 14.0
END DESCRIPTION:
XS GIS Cut Line= 3
      2779814.26     10093146.51      2779397.62     10093396.49
      2779204.91     10094214.21
#Sta/Elev= 30
  4625.1 1747.19  4707.4 1745.31  4781.3 1740.19  4787.1 1740.74    4819 1739.89
  4897.9 1737.72    4962 1738.22  4970.1 1736.82  4977.6 1732.73  4983.4 1730.68
    4996 1729.09  4998.7 1728.59    5002 1729.09  5014.5 1731.49  5041.7 1734.18
  5063.4 1737.85  5088.8 1737.44  5131.5 1736.57  5210.9 1737.84  5231.4 1740.25
    5252 1741.51  5263.6 1743.53  5282.8 1745.23  5313.6 1746.85  5390.1 1748.28
    5503 1750.74  5601.3 1753.36  5713.6  1754.9  5850.6  1757.7  5951.1 1760.14
#Mann= 9 ,-1 , 0
  4625.1     .05       0    4819      .1       0    4996     .07       0
    5002      .1       0  5088.8     .05       0  5390.1     .16       0
    5503      .1       0  5713.6     .05       0  5850.6      .1       0
Bank Sta=4996,5002
XS Rating Curve= 0 ,0
Exp/Cntr=0.3,0.1

Type RM Length L Ch R = 1 ,5854    ,588,588,588
BEGIN DESCRIPTION:
GAMENTHALER CREEK 13.0
END DESCRIPTION:
XS GIS Cut Line= 3
      2779915.71     10093055.38      2779590.18     10092891.31
      2778973.22     10092789.79
#Sta/Elev= 30
  4424.6 1747.83    4489 1745.29  4495.8 1745.13    4709 1736.84  4831.4 1731.64
  4861.7 1725.66    4872 1726.37  4882.1 1729.24  4892.2 1730.92  4902.4 1731.16
  4912.5 1730.47    4928 1725.54    4933 1724.69    4953 1722.76  4973.3 1722.12
  4983.4 1720.77  4989.1 1719.26  4991.2  1717.7    4994  1717.2  4997.2  1717.7
  4998.1 1717.75  5003.7 1718.07    5024 1723.33  5044.2 1725.83  5050.3 1727.81
  5111.5 1736.78    5212  1741.2  5249.6 1742.65  5300.2 1744.79  5414.4 1747.78
#Mann= 9 ,-1 , 0
  4424.6     .05       0    4489      .1       0  4495.8     .05       0
    4709      .1       0  4991.2     .04       0  4997.2      .1       0
  4998.1     .05       0    5212      .1       0  5249.6     .05       0
Bank Sta=4991.2,4997.2
XS Rating Curve= 0 ,0
Exp/Cntr=0.3,0.1

Type RM Length L Ch R = 1 ,5266    ,348,348,348
BEGIN DESCRIPTION:
GAMENTHALER CREEK 12.0
END DESCRIPTION:
XS GIS Cut Line= 3
      2780163.28     10092495.46      2779559.08      10092401.7
      2778767.39     10092557.96
#Sta/Elev= 30
  4288.7 1753.14  4435.3 1748.15  4770.6 1730.21  4860.3 1727.03  4915.8 1726.75
  4951.7 1725.46  4961.9 1723.29  4972.1  1720.3  4982.3 1715.01  4987.7 1709.53
  4992.8 1708.49  4999.7 1705.15  5002.4 1704.65  5005.7 1705.15  5012.9 1707.55
  5023.1 1715.23  5033.3 1719.45    5039  1723.6  5044.1 1722.88  5060.3 1727.64
  5090.4 1732.19  5095.4 1731.86  5141.7 1738.01  5146.8 1737.75  5186.2 1743.65
  5257.5 1747.91  5398.2 1750.18  5603.4 1748.57  5654.7 1749.04  5707.1 1750.97
#Mann= 6 ,-1 , 0
  4288.7      .1       0  4770.6     .05       0  4915.8     .16       0
  4999.7     .07       0  5005.7     .16       0  5060.3     .05       0
Bank Sta=4999.7,5005.7
XS Rating Curve= 0 ,0
Exp/Cntr=0.3,0.1

Type RM Length L Ch R = 1 ,4918    ,649,649,649
BEGIN DESCRIPTION:
GAMENTHALER CREEK 11.0
END DESCRIPTION:
XS GIS Cut Line= 3
       2780366.4     10092406.92      2779590.33     10092063.16
      2778798.68     10092136.08
#Sta/Elev= 30
  4010.1 1748.55    4056 1747.89  4079.3 1748.42  4124.1 1747.18  4204.8 1744.46
  4403.9 1740.67  4467.2 1740.59    4549 1737.43  4663.6 1730.81  4751.7 1725.24
  4800.1 1723.02  4922.8 1723.72  4971.2 1720.03  4981.3 1716.56  4991.3 1709.72
  4998.4 1705.74  5001.1 1705.24  5004.4 1705.74  5011.4 1707.79  5021.4 1714.31
  5027.6 1722.62  5032.6 1722.55  5041.5 1727.04  5051.6 1729.24  5081.7 1733.34
  5137.3 1737.24  5247.1  1742.1  5461.5  1740.6  5559.9 1740.75  5653.9 1740.92
#Mann= 8 ,-1 , 0
  4010.1      .1       0  4124.1     .05       0  4204.8      .1       0
  4663.6     .05       0  4800.1     .16       0  4998.4     .07       0
  5004.4     .16       0  5559.9      .1       0
Bank Sta=4998.4,5004.4
XS Rating Curve= 0 ,0
Exp/Cntr=0.3,0.1

Type RM Length L Ch R = 1 ,4269    ,518,518,518
BEGIN DESCRIPTION:
GAMENTHALER CREEK 10.0
END DESCRIPTION:
XS GIS Cut Line= 2
      2780408.05     10091281.91      2778747.81     10091588.98
#Sta/Elev= 30
  4106.9 1746.51  4495.3  1750.4  4665.8  1751.4  4740.1  1747.8  4787.8 1742.51
  4803.7 1742.55  4808.7 1740.42  4828.5 1739.76  4869.2 1731.24  4899.7 1728.52
  4950.6 1719.76  4960.7 1715.78  4967.5 1709.62  4972.6 1708.27  4991.2 1697.68
  4998.4 1696.64  5001.1 1696.14  5004.4 1696.64  5025.5 1702.58  5031.9 1707.77
  5052.2  1712.5  5083.5 1715.06  5153.9 1716.19  5203.5 1719.48  5265.8 1725.32
  5367.5 1727.36  5405.8 1729.81  5464.1 1729.56  5581.1 1734.05  5795.3 1739.14
#Mann= 7 ,-1 , 0
  4106.9      .1       0  4495.3     .05       0  4740.1     .16       0
  4998.4     .07       0  5004.4     .16       0  5203.5      .1       0
  5405.8     .05       0
Bank Sta=4998.4,5004.4
XS Rating Curve= 0 ,0
Exp/Cntr=0.3,0.1

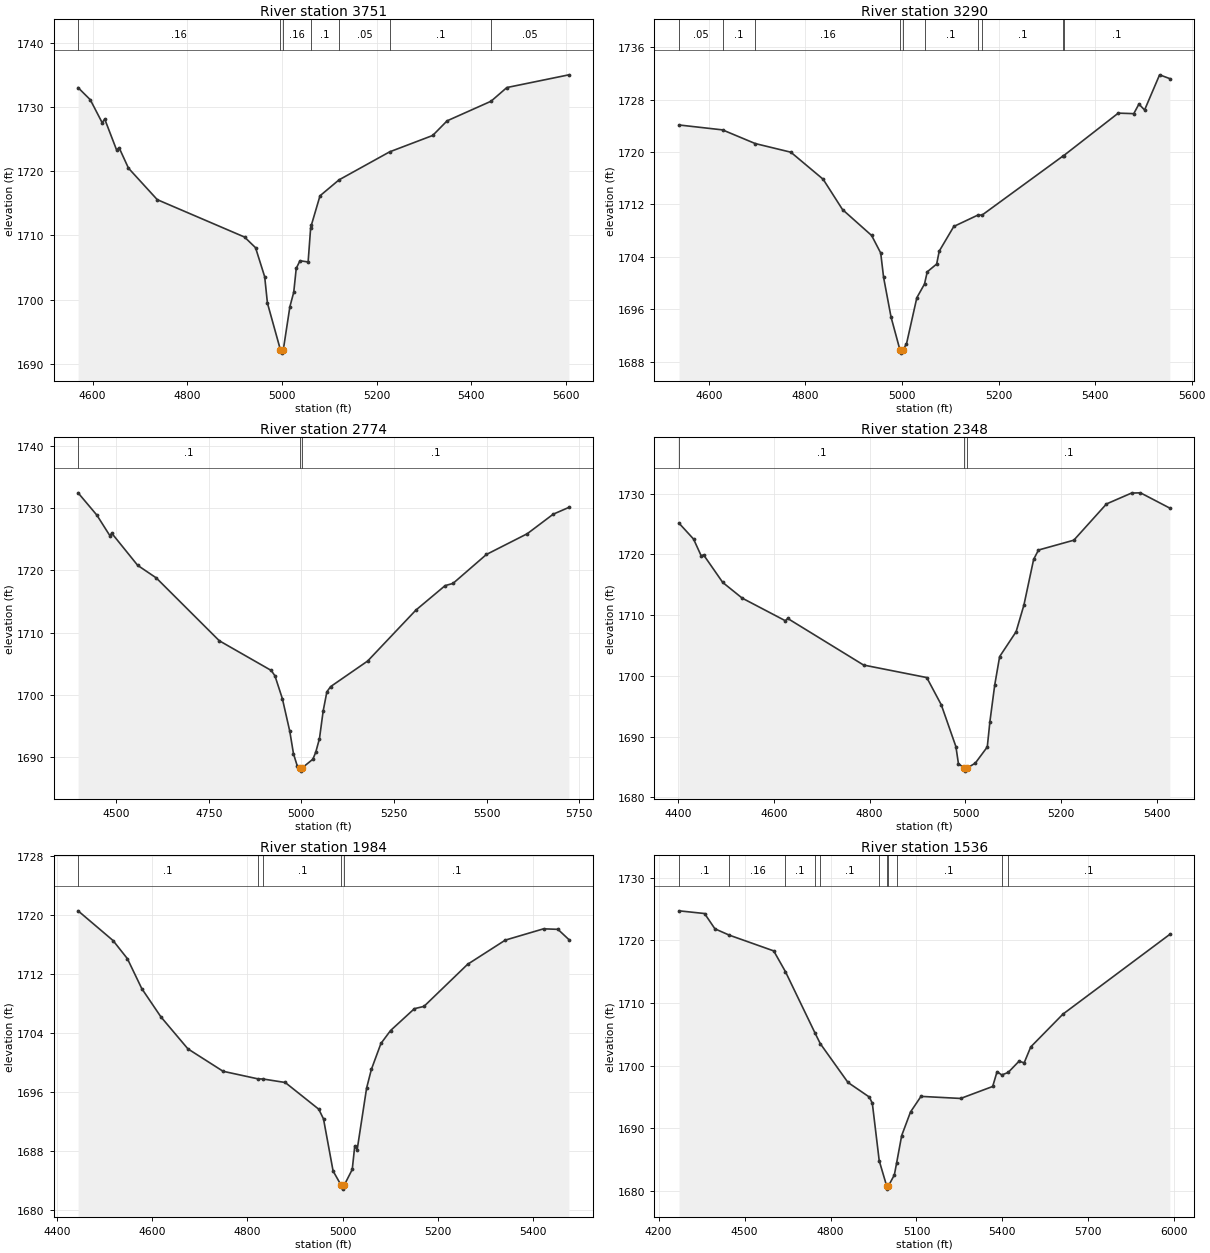
Type RM Length L Ch R = 1 ,3751    ,461,461,461
BEGIN DESCRIPTION:
GAMENTHALER CREEK 8.0
END DESCRIPTION:
XS GIS Cut Line= 2
      2779668.41     10090860.05      2778695.43     10091219.07
#Sta/Elev= 30
  4569.3 1732.99  4595.1  1731.1  4620.2 1727.53  4625.6 1728.09  4650.7 1723.28
    4656 1723.63  4675.8 1720.45  4736.6 1715.55    4921 1709.73  4944.3 1708.07
  4963.6 1703.55  4969.4 1699.45  4996.9 1692.16  4999.6 1691.66  5002.9 1692.16
  5016.9  1698.9    5025 1701.14  5030.3 1704.86  5038.2 1706.04  5055.4 1705.85
  5060.7 1711.14  5062.2 1711.57  5080.5 1716.15  5120.7 1718.63  5227.6 1722.99
  5318.6 1725.54  5349.1 1727.82  5441.9 1730.87  5475.3    1733  5606.4 1734.98
#Mann= 7 ,-1 , 0
  4569.3     .16       0  4996.9     .07       0  5002.9     .16       0
  5062.2      .1       0  5120.7     .05       0  5227.6      .1       0
  5441.9     .05       0
Bank Sta=4996.9,5002.9
XS Rating Curve= 0 ,0
Exp/Cntr=0.3,0.1

Type RM Length L Ch R = 1 ,3290    ,516,516,516
BEGIN DESCRIPTION:
GAMENTHALER CREEK 7.0
END DESCRIPTION:
XS GIS Cut Line= 3
      2779545.93     10090675.18      2779246.43     10090526.73
      2778608.61     10090768.84
#Sta/Elev= 30
  4538.3 1724.13  4628.4 1723.38  4696.2 1721.29  4769.9 1719.97  4836.8 1715.84
    4877  1711.2  4937.2 1707.25    4956 1704.57    4962 1700.84  4977.4 1694.79
  4995.8 1689.78  4998.5 1689.28  5001.8 1689.78  5009.4 1690.69  5030.8 1697.74
  5046.7 1699.84  5052.4  1701.7  5071.9 1702.89  5077.2 1704.86  5107.4 1708.63
  5156.8 1710.35  5166.2 1710.38  5334.5 1719.44    5335 1719.45    5448 1725.94
  5480.1 1725.86  5490.8 1727.32  5502.5 1726.42  5533.6 1731.79  5554.8 1731.21
#Mann= 10 ,-1 , 0
  4538.3     .05       0  4628.4      .1       0  4696.2     .16       0
  4995.8     .07       0  5001.8     .16       0  5046.7      .1       0
  5156.8     .05       0  5166.2      .1       0  5334.5     .05       0
    5335      .1       0
Bank Sta=4995.8,5001.8
XS Rating Curve= 0 ,0
Exp/Cntr=0.3,0.1

Type RM Length L Ch R = 1 ,2774    ,426,426,426
BEGIN DESCRIPTION:
GAMENTHALER CREEK 6.0
END DESCRIPTION:
XS GIS Cut Line= 2
      2779559.08     10090083.99      2778236.19     10090156.91
#Sta/Elev= 30
  4397.3 1732.44    4448 1728.86  4483.2 1725.55  4488.2 1725.95  4558.2 1720.79
  4608.2 1718.78  4778.5 1708.68  4918.7 1703.91  4928.7 1703.05  4948.8 1699.37
  4968.8 1694.13  4978.8 1690.52  4988.8  1688.6  4995.8 1688.24  4998.6 1687.74
  5001.8 1688.24  5031.2 1689.66  5038.9 1690.79  5048.9 1692.96  5058.9  1697.4
  5068.9 1700.48  5078.9 1701.31  5179.1 1705.43  5309.3 1713.61  5388.2 1717.54
  5409.4 1717.89  5499.6 1722.54  5609.8 1725.87  5679.9 1729.01  5722.2  1730.1
#Mann= 3 ,-1 , 0
  4397.3      .1       0  4995.8     .07       0  5001.8      .1       0
Bank Sta=4995.8,5001.8
XS Rating Curve= 0 ,0
Exp/Cntr=0.3,0.1

Type RM Length L Ch R = 1 ,2348    ,364,364,364
BEGIN DESCRIPTION:
GAMENTHALER CREEK 5.0
END DESCRIPTION:
XS GIS Cut Line= 2
      2779418.45     10089630.87      2778408.06     10089802.74
#Sta/Elev= 30
  4401.9 1725.14  4432.3 1722.52  4448.2 1719.76  4453.2 1719.92  4493.2 1715.38
  4533.8  1712.8  4623.8 1709.08  4628.9 1709.45  4787.3 1701.78  4919.2 1699.72
  4949.6 1695.22  4980.1 1688.34  4985.3 1685.56  4997.4 1684.81  5000.1 1684.31
  5003.4 1684.81  5020.6 1685.63  5045.6 1688.29  5051.1 1692.48  5061.2 1698.52
  5071.4 1703.17  5105.8 1707.27  5122.1 1711.66  5142.4 1719.18  5152.5 1720.72
  5226.3 1722.34  5294.5 1728.31  5346.8  1730.1  5365.5 1730.14  5426.8 1727.62
#Mann= 3 ,-1 , 0
  4401.9      .1       0  4997.4     .07       0  5003.4      .1       0
Bank Sta=4997.4,5003.4
XS Rating Curve= 0 ,0
Exp/Cntr=0.3,0.1

Type RM Length L Ch R = 1 ,1984    ,448,448,448
BEGIN DESCRIPTION:
GAMENTHALER CREEK 4.0
END DESCRIPTION:
XS GIS Cut Line= 2
       2779371.6     10089328.78      2778345.51     10089417.33
#Sta/Elev= 30
  4444.7 1720.52  4518.1 1716.49  4548.2 1714.03  4578.3 1709.98  4618.5 1706.14
  4675.2  1701.8    4749 1698.76  4821.6 1697.74  4833.3 1697.71  4879.4 1697.24
  4949.7 1693.62  4959.7  1692.3  4979.8 1685.24  4996.9 1683.28  4999.6 1682.78
  5002.9 1683.28    5020 1685.45  5025.3 1688.65  5030.3 1688.12  5050.1 1696.47
  5060.1 1699.01  5080.2 1702.53  5100.3 1704.28  5150.4 1707.25  5170.5 1707.56
  5262.1 1713.27  5341.2 1716.55  5421.4 1718.08  5451.6 1718.01  5474.6 1716.62
#Mann= 5 ,-1 , 0
  4444.7      .1       0  4821.6     .16       0  4833.3      .1       0
  4996.9     .07       0  5002.9      .1       0
Bank Sta=4996.9,5002.9
XS Rating Curve= 0 ,0
Exp/Cntr=0.3,0.1

Type RM Length L Ch R = 1 ,1536    ,595,595,595
BEGIN DESCRIPTION:
GAMENTHALER CREEK 3.0
END DESCRIPTION:
XS GIS Cut Line= 3
      2779684.06     10089229.82      2778762.21      10088901.7
      2778043.42     10089052.75
#Sta/Elev= 30
  4271.3 1724.71  4360.4 1724.28  4396.6 1721.84  4447.4 1720.82  4601.8 1718.32
  4642.7 1715.01  4745.9 1705.23  4764.3 1703.53    4861 1697.34  4935.6 1695.01
    4946 1694.01    4970 1684.86    4996 1680.83  4998.8 1680.33    5002 1680.83
  5022.8 1682.59  5030.9 1684.54  5048.4 1688.87  5079.2 1692.63  5115.8 1695.12
  5254.3 1694.79    5366  1696.7  5381.3 1699.06  5397.7 1698.54  5419.9 1698.93
    5458 1700.73  5475.9 1700.47  5498.9 1703.01  5611.3 1708.24  5984.3 1720.96
#Mann= 11 ,-1 , 0
  4271.3      .1       0  4447.4     .16       0  4642.7      .1       0
  4745.9     .16       0  4764.3      .1       0    4970     .16       0
    4996     .07       0    5002     .16       0  5030.9      .1       0
  5397.7     .05       0  5419.9      .1       0
Bank Sta=4996,5002
XS Rating Curve= 0 ,0
Exp/Cntr=0.3,0.1