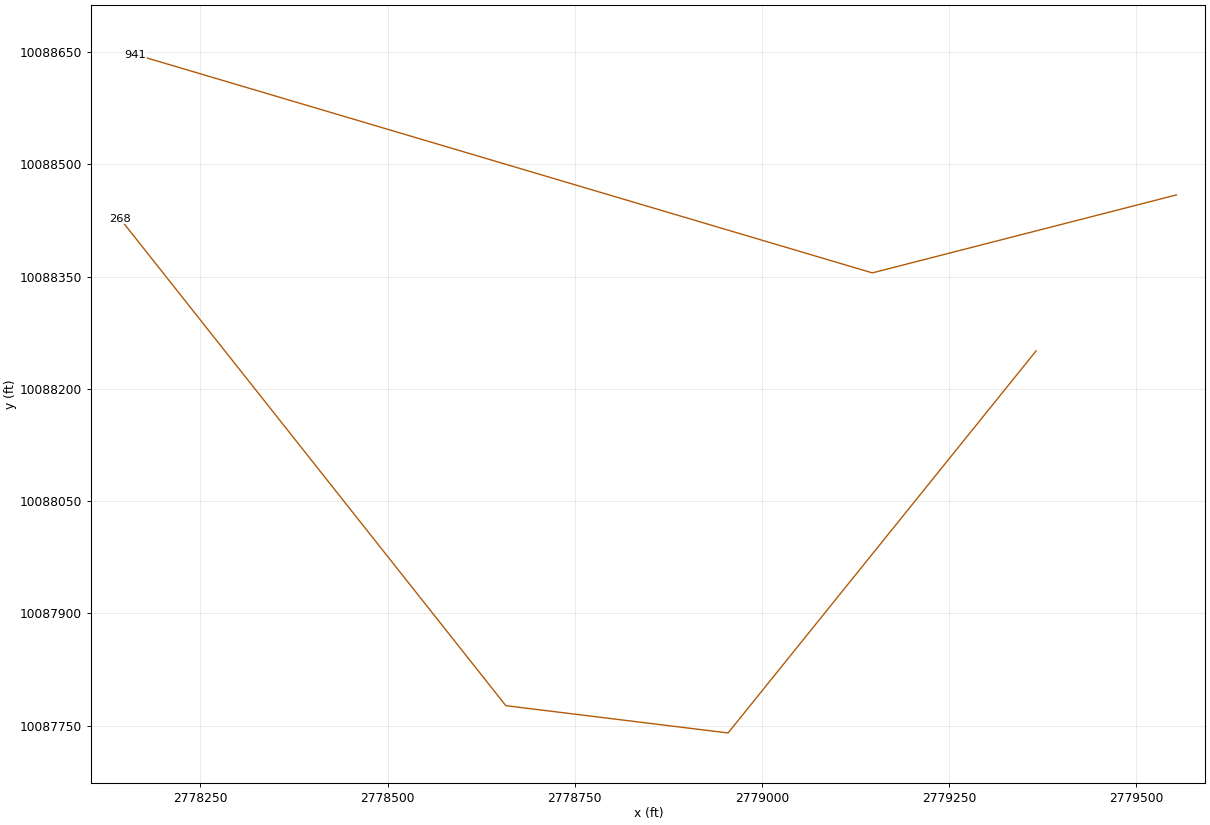
HEC-RAS study GAMENTHALER CREEK.prj: GAMENTHALER CREEK Base Level Engineering

--- GAMENTHALER CREEK.g01 (geometry) --- (continued)

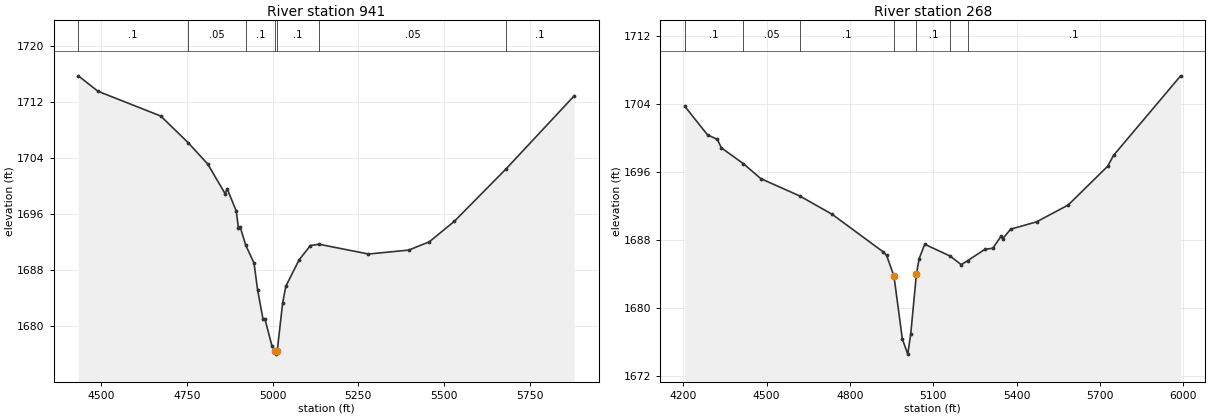
Type RM Length L Ch R = 1 ,941     ,673,673,673
BEGIN DESCRIPTION:
GAMENTHALER CREEK 2.0
END DESCRIPTION:
XS GIS Cut Line= 3
      2779553.92     10088459.01      2779147.62     10088354.83
      2778163.36     10088646.46
#Sta/Elev= 30
  4433.6 1715.73  4490.8 1713.53  4673.9    1710  4753.7 1706.21  4810.9 1703.16
  4862.1  1698.9  4867.3 1699.66  4893.9  1696.5  4900.5 1694.09  4905.8 1694.17
  4921.5 1691.63    4946 1689.03  4956.5 1685.18  4972.2 1681.04  4977.5 1681.12
  4998.2 1677.23  5007.7 1676.56  5010.5 1676.06  5013.7 1676.56  5029.5 1683.36
  5038.7 1685.73  5077.2 1689.48  5110.4 1691.54  5135.8 1691.72  5279.8 1690.33
  5397.3 1690.89  5457.1 1692.07  5530.1 1694.99  5680.7 1702.45  5879.6 1712.87
#Mann= 7 ,-1 , 0
  4433.6      .1       0  4753.7     .05       0  4921.5      .1       0
  5007.7     .07       0  5013.7      .1       0  5135.8     .05       0
  5680.7      .1       0
Bank Sta=5007.7,5013.7
XS Rating Curve= 0 ,0
Exp/Cntr=0.3,0.1

Type RM Length L Ch R = 1 ,268     ,0,0,0
BEGIN DESCRIPTION:
GAMENTHALER CREEK 1.0
END DESCRIPTION:
XS GIS Cut Line= 4
      2779366.38     10088250.66      2778954.91     10087740.24
      2778658.04      10087776.7      2778142.92      10088427.1
#Sta/Elev= 30
  4205.5 1703.76  4287.4 1700.39  4322.6 1699.87    4337 1698.87  4416.5    1697
  4479.4 1695.23  4618.5 1693.21  4735.3 1691.05    4918 1686.65  4931.9 1686.19
  4958.3 1683.74  4988.5 1676.34    5008 1674.57  5018.7 1676.96  5038.9 1683.96
    5049 1685.83  5069.1 1687.51    5161 1686.11  5200.4 1685.11  5223.4 1685.58
  5285.4 1686.91  5314.2 1687.05  5343.1 1688.43  5349.5 1688.16  5378.3 1689.29
  5471.3 1690.15  5585.1 1692.13  5727.7 1696.71  5748.5 1697.98  5989.9 1707.35
#Mann= 7 ,-1 , 0
  4205.5      .1       0  4416.5     .05       0  4618.5      .1       0
  4958.3     .07       0  5038.9      .1       0    5161     .16       0
  5223.4      .1       0
Bank Sta=4958.3,5038.9
XS Rating Curve= 0 ,0
Exp/Cntr=0.3,0.1

Chan Stop Cuts=-1
Use User Specified Reach Order=0
Composite Channel Slope=5