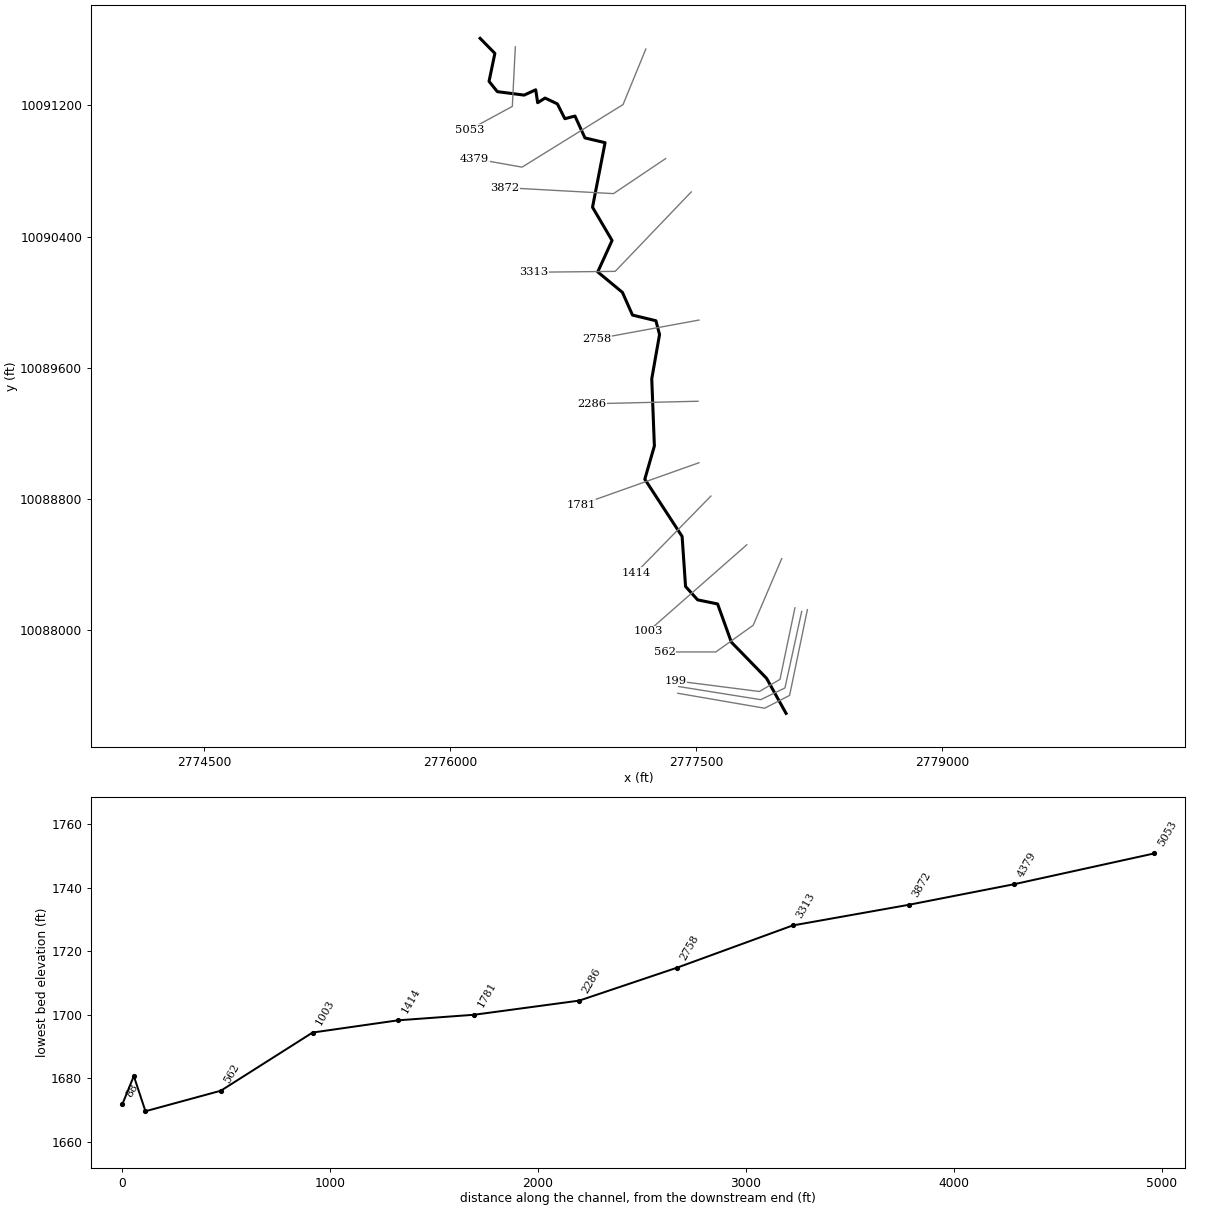
--- HICKORY CREEK.prj (project) ---

Proj Title=HICKORY CREEK Base Level Engineering
Current Plan=p01
Default Exp/Contr=0.3,0.1
English Units
Geom File=g01
Flow File=f01
Plan File=p01
BEGIN DESCRIPTION:
HICKORY CREEK
END DESCRIPTION:

--- HICKORY CREEK.p01 (plan) ---

Plan Title=Multiple Run
Short Identifier=Multiple
Geom File=g01
Flow File=f01
Subcritical Flow
K Sum by GR= 0
Std Step Tol= 0.01
Critical Tol= 0.01
Num of Std Step Trials= 20
Max Error Tol= 0.3
Flow Tol Ratio= 0.001
Split Flow NTrial= 30
Split Flow Tol= 0.02
Split Flow Ratio= 0.02
Log Output Level= 0
Friction Slope Method= 1
Unsteady Friction Slope Method= 2
Unsteady Bridges Friction Slope Method= 1
Parabolic Critical Depth
Global Vel Dist=  1 , 1 , 1
Global Log Level= 0
CheckData=True
Encroach Param= -1, 0, 0, 0
BEGIN DESCRIPTION:
Multiple Run
END DESCRIPTION:

--- HICKORY CREEK.f01 (steady flow) ---

Flow Title=Multiple
Number of Profiles=7
Profile Names=10-year,25-year,50-year,1pct_min,100-year,1pct_plu,500-year
River Rch & RM= HICKORY CREEK,Reach-1,5053
     516     731     916     842    1138    1539    1763
Boundary for River Rch & Prof#=HICKORY CREEK,Reach-1,1
Up Type=0
Dn Type=3
Dn Slope=0.005
Boundary for River Rch & Prof#=HICKORY CREEK,Reach-1,2
Up Type=0
Dn Type=3
Dn Slope=0.005
Boundary for River Rch & Prof#=HICKORY CREEK,Reach-1,3
Up Type=0
Dn Type=3
Dn Slope=0.005
Boundary for River Rch & Prof#=HICKORY CREEK,Reach-1,4
Up Type=0
Dn Type=3
Dn Slope=0.005
Boundary for River Rch & Prof#=HICKORY CREEK,Reach-1,5
Up Type=0
Dn Type=3
Dn Slope=0.005
Boundary for River Rch & Prof#=HICKORY CREEK,Reach-1,6
Up Type=0
Dn Type=3
Dn Slope=0.005
Boundary for River Rch & Prof#=HICKORY CREEK,Reach-1,7
Up Type=0
Dn Type=3
Dn Slope=0.005

--- HICKORY CREEK.g01 (geometry) ---

Geom Title=Existing Conditions

River Reach=HICKORY CREEK,Reach-1
Reach XY= 30
      2776183.47     10091608.73      2776273.50     10091517.04
      2776237.96     10091346.74      2776288.39     10091283.78
      2776452.09     10091262.67      2776522.40     10091295.01
      2776534.34     10091216.23      2776579.48     10091244.66
      2776654.57     10091209.07      2776700.14     10091118.79
      2776761.84     10091135.04      2776822.66     10091001.65
      2776945.26     10090972.65      2776868.72     10090579.17
      2776987.92     10090376.36      2776900.51     10090184.80
      2777050.98     10090060.20      2777112.45     10089921.71
      2777255.09     10089887.20      2777277.34     10089803.34
      2777229.85     10089533.39      2777245.84     10089123.82
      2777187.51     10088921.24      2777414.90     10088572.26
      2777435.84     10088267.33      2777509.44     10088185.76
      2777631.21     10088160.73      2777715.03     10087927.92
      2777929.61     10087707.61      2778048.47     10087493.73

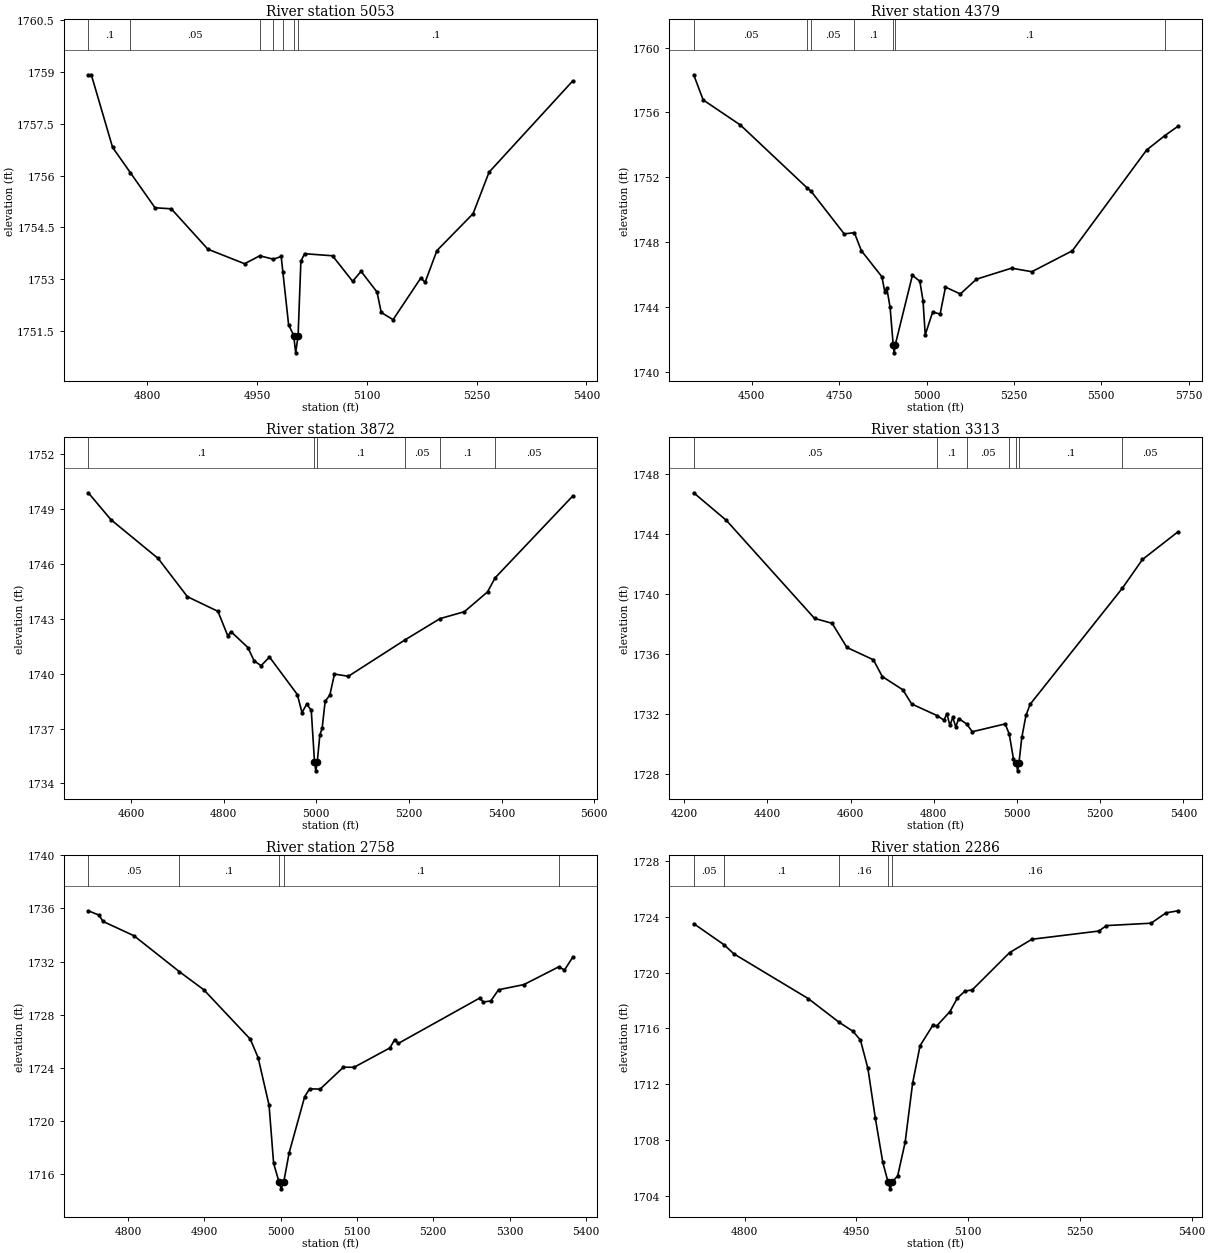
Type RM Length L Ch R = 1,5053,674,674,674
BEGIN DESCRIPTION:
HICKORY CREEK 10.0
END DESCRIPTION:
XS GIS Cut Line= 3
      2776398.21     10091556.84      2776379.86     10091193.82
      2776117.96     10091051.62
#Sta/Elev= 30
  4719.7 1758.92  4723.8 1758.92  4752.8 1756.82  4777.3 1756.08  4810.8 1755.07
  4833.0 1755.04  4883.0 1753.87  4933.1 1753.45  4953.9 1753.68  4972.5 1753.58
  4983.1 1753.66  4985.4 1753.21  4993.2 1751.69  5000.2 1751.37  5002.9 1750.87
  5006.2 1751.37  5010.0 1753.52  5015.0 1753.74  5053.2 1753.68  5080.7 1752.94
  5092.2 1753.23  5114.0 1752.63  5119.7 1752.04  5135.9 1751.83  5173.9 1753.04
  5179.6 1752.91  5195.8 1753.83  5245.2 1754.90  5267.0 1756.10  5381.2 1758.74
#Mann=7,-1,0
  4719.7     0.1       0  4777.3    0.05       0  4953.9     0.1       0
  4972.5    0.05       0  4985.4     0.1       0  5000.2    0.07       0
  5006.2     0.1       0
Bank Sta=5000.2,5006.2
Exp/Cntr=0.3,0.1

Type RM Length L Ch R = 1,4379,507,507,507
BEGIN DESCRIPTION:
HICKORY CREEK 9.0
END DESCRIPTION:
XS GIS Cut Line= 4
      2777193.78     10091543.56      2777054.88     10091205.00
      2776439.29     10090823.58      2776148.65     10090875.13
#Sta/Elev= 30
  4334.1 1758.32  4361.1 1756.77  4467.8 1755.22  4659.3 1751.33  4669.4 1751.15
  4764.7 1748.51  4793.5 1748.59  4813.5 1747.48  4872.3 1745.87  4880.5 1744.96
  4886.4 1745.16  4895.8 1743.98  4904.6 1741.68  4907.4 1741.18  4910.6 1741.68
  4959.6 1745.96  4980.9 1745.59  4989.9 1744.40  4996.3 1742.29  5017.5 1743.70
  5038.8 1743.57  5054.2 1745.23  5096.7 1744.81  5142.8 1745.72  5243.2 1746.40
  5301.1 1746.18  5416.9 1747.47  5629.4 1753.68  5680.8 1754.56  5719.4 1755.15
#Mann=7,-1,0
  4334.1    0.05       0  4659.3     0.1       0  4669.4    0.05       0
  4793.5     0.1       0  4904.6    0.07       0  4910.6     0.1       0
  5680.8    0.05       0
Bank Sta=4904.6,4910.6
Exp/Cntr=0.3,0.1

Type RM Length L Ch R = 1,3872,559,559,559
BEGIN DESCRIPTION:
HICKORY CREEK 8.0
END DESCRIPTION:
XS GIS Cut Line= 3
      2777314.32     10090875.68      2776996.58     10090662.12
      2776335.12     10090698.58
#Sta/Elev= 30
  4507.9 1749.89  4556.7 1748.42  4658.6 1746.30  4721.7 1744.21  4787.6 1743.41
  4808.7 1742.08  4816.2 1742.29  4852.3 1741.43  4865.7 1740.70  4880.7 1740.44
  4898.9 1740.91  4959.0 1738.86  4969.0 1737.87  4979.0 1738.33  4989.0 1738.01
  4996.0 1735.19  4998.8 1734.69  5002.0 1735.19  5007.5 1736.64  5012.5 1737.02
  5019.0 1738.49  5029.1 1738.83  5039.1 1739.98  5069.1 1739.86  5190.8 1741.84
  5266.8 1743.01  5319.5 1743.39  5369.4 1744.47  5385.8 1745.24  5553.2 1749.71
#Mann=6,-1,0
  4507.9     0.1       0  4996.0    0.07       0  5002.0     0.1       0
  5190.8    0.05       0  5266.8     0.1       0  5385.8    0.05       0
Bank Sta=4996,5002
Exp/Cntr=0.3,0.1

Type RM Length L Ch R = 1,3313,555,555,555
BEGIN DESCRIPTION:
HICKORY CREEK 7.0
END DESCRIPTION:
XS GIS Cut Line= 3
      2777470.52     10090672.51      2777007.00     10090188.16
      2776512.83     10090182.96
#Sta/Elev= 30
  4222.6 1746.73  4301.1 1744.89  4513.1 1738.35  4555.5 1738.02  4591.0 1736.41
  4654.6 1735.59  4676.0 1734.47  4725.3 1733.59  4746.7 1732.64  4807.5 1731.87
  4824.4 1731.56  4831.3 1732.00  4838.6 1731.21  4845.5 1731.74  4852.7 1731.11
  4859.6 1731.67  4878.6 1731.31  4892.6 1730.79  4971.5 1731.31  4981.3 1730.63
  4991.5 1728.96  4998.5 1728.68  5001.3 1728.18  5004.5 1728.68  5011.5 1730.41
  5021.5 1731.88  5031.5 1732.62  5253.4 1740.37  5301.6 1742.28  5387.2 1744.13
#Mann=7,-1,0
  4222.6    0.05       0  4807.5     0.1       0  4878.6    0.05       0
  4981.3     0.1       0  4998.5    0.07       0  5004.5     0.1       0
  5253.4    0.05       0
Bank Sta=4998.5,5004.5
Exp/Cntr=0.3,0.1

Type RM Length L Ch R = 1,2758,472,472,472
BEGIN DESCRIPTION:
HICKORY CREEK 6.0
END DESCRIPTION:
XS GIS Cut Line= 2
      2777517.39     10089891.28      2776892.90     10089776.79
#Sta/Elev= 30
  4747.9 1735.82  4762.0 1735.49  4767.1 1735.02  4807.8 1733.94  4867.3 1731.24
  4899.3 1729.88  4960.3 1726.16  4970.5 1724.77  4984.8 1721.20  4990.8 1716.82
  4998.0 1715.41  5000.7 1714.91  5004.0 1715.41  5011.1 1717.61  5031.5 1721.84
  5037.9 1722.43  5051.8 1722.41  5082.3 1724.06  5096.2 1724.05  5143.3 1725.51
  5149.3 1726.12  5154.4 1725.85  5260.7 1729.25  5265.8 1728.96  5275.5 1729.04
  5285.6 1729.88  5318.9 1730.27  5364.7 1731.61  5372.0 1731.36  5382.8 1732.32
#Mann=5,-1,0
  4747.9    0.05       0  4867.3     0.1       0  4998.0    0.07       0
  5004.0     0.1       0  5364.7    0.16       0
Bank Sta=4998,5004
Exp/Cntr=0.3,0.1

Type RM Length L Ch R = 1,2286,505,505,505
BEGIN DESCRIPTION:
HICKORY CREEK 5.0
END DESCRIPTION:
XS GIS Cut Line= 2
      2777512.22     10089396.49      2776862.31     10089380.90
#Sta/Elev= 30
  4731.6 1723.50  4772.5 1721.98  4785.4 1721.34  4885.4 1718.13  4926.7 1716.44
  4945.4 1715.79  4955.4 1715.16  4965.4 1713.13  4975.4 1709.56  4985.4 1706.40
  4992.4 1705.01  4995.2 1704.51  4998.4 1705.01  5005.4 1705.45  5015.4 1707.85
  5025.4 1712.07  5035.4 1714.76  5052.8 1716.24  5057.8 1716.18  5075.5 1717.20
  5085.5 1718.17  5095.5 1718.66  5105.5 1718.76  5155.5 1721.42  5185.5 1722.38
  5275.5 1722.97  5285.5 1723.36  5345.5 1723.53  5365.5 1724.27  5381.7 1724.42
#Mann=5,-1,0
  4731.6    0.05       0  4772.5     0.1       0  4926.7    0.16       0
  4992.4    0.07       0  4998.4    0.16       0
Bank Sta=4992.4,4998.4
Exp/Cntr=0.3,0.1

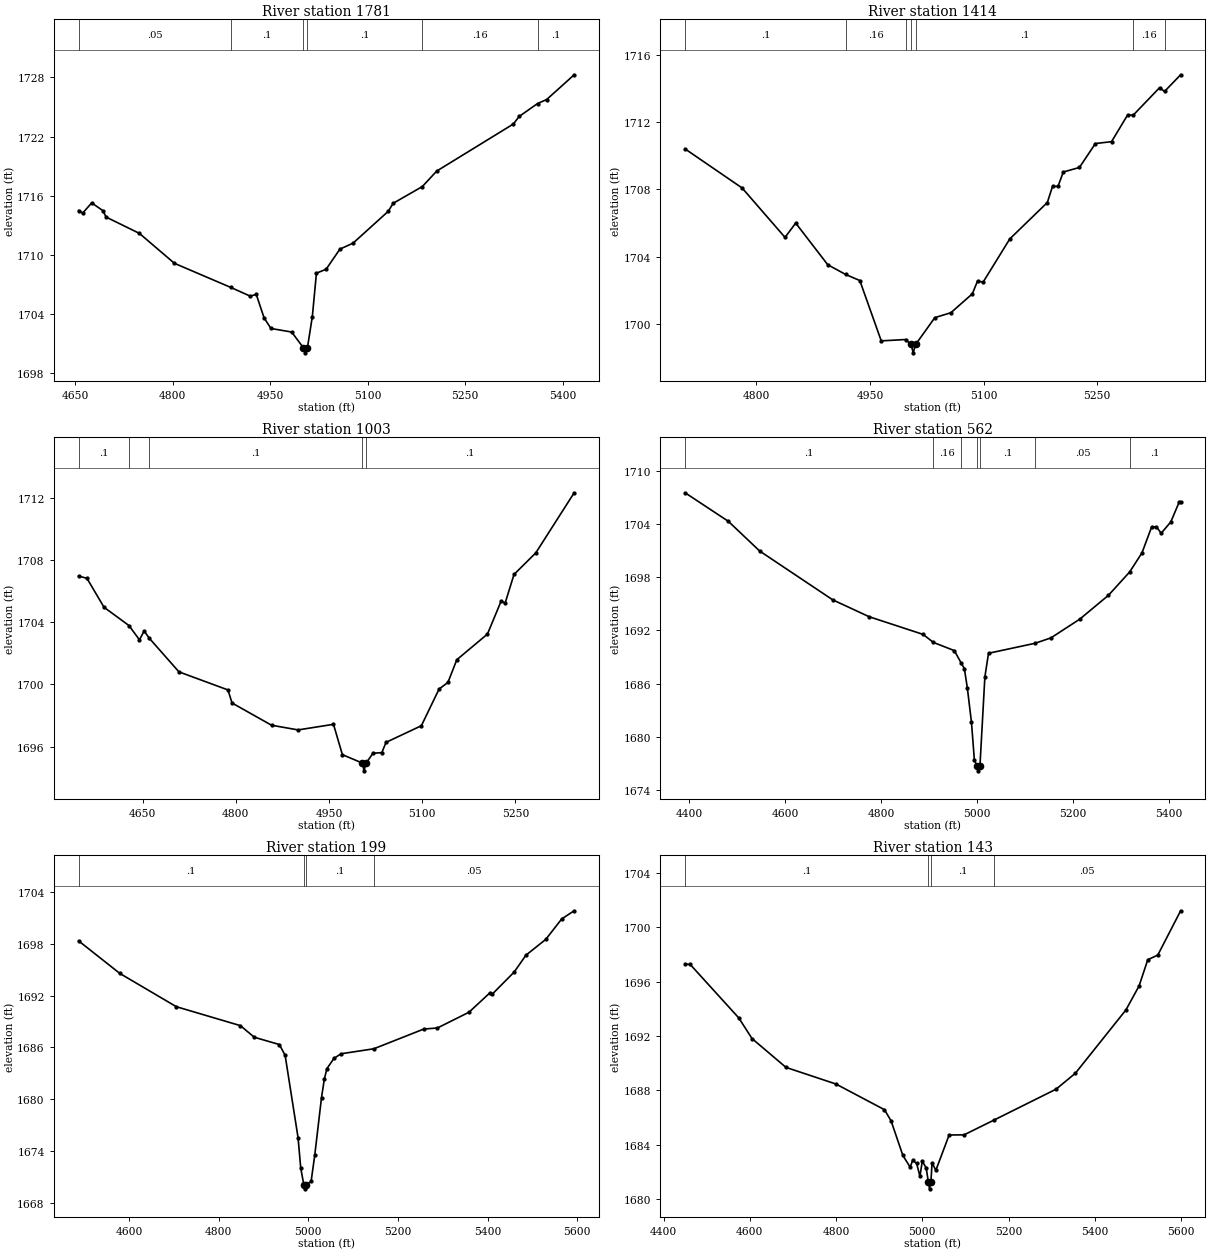
Type RM Length L Ch R = 1,1781,367,367,367
BEGIN DESCRIPTION:
HICKORY CREEK 4.0
END DESCRIPTION:
XS GIS Cut Line= 2
      2777517.43     10089021.50      2776798.69     10088766.30
#Sta/Elev= 30
  4655.2 1714.50  4661.4 1714.24  4675.3 1715.27  4692.3 1714.50  4697.6 1713.83
  4748.7 1712.18  4802.7 1709.14  4889.6 1706.69  4919.4 1705.81  4928.6 1705.99
  4940.6 1703.61  4951.2 1702.53  4983.1 1702.17  5001.3 1700.56  5004.0 1700.06
  5007.3 1700.56  5014.9 1703.74  5021.2 1708.14  5036.1 1708.54  5057.3 1710.58
  5077.6 1711.19  5131.6 1714.41  5139.3 1715.23  5184.2 1716.93  5206.3 1718.50
  5324.4 1723.28  5333.2 1724.04  5361.5 1725.35  5375.6 1725.76  5417.9 1728.27
#Mann=6,-1,0
  4655.2    0.05       0  4889.6     0.1       0  5001.3    0.07       0
  5007.3     0.1       0  5184.2    0.16       0  5361.5     0.1       0
Bank Sta=5001.3,5007.3
Exp/Cntr=0.3,0.1

Type RM Length L Ch R = 1,1414,411,411,411
BEGIN DESCRIPTION:
HICKORY CREEK 3.0
END DESCRIPTION:
XS GIS Cut Line= 2
      2777590.35     10088818.39      2777132.71     10088350.34
#Sta/Elev= 30
  4705.7 1710.40  4781.1 1708.08  4837.7 1705.15  4851.8 1706.00  4894.1 1703.53
  4917.8 1702.95  4936.5 1702.59  4964.8 1699.01  4996.9 1699.09  5004.3 1698.80
  5007.0 1698.30  5010.3 1698.80  5035.6 1700.39  5056.8 1700.68  5085.1 1701.80
  5092.1 1702.57  5099.3 1702.49  5134.6 1705.06  5184.2 1707.22  5191.1 1708.18
  5198.3 1708.18  5205.3 1709.03  5226.6 1709.30  5247.7 1710.72  5269.0 1710.83
  5290.2 1712.41  5297.8 1712.41  5332.6 1714.04  5339.0 1713.81  5360.3 1714.80
#Mann=7,-1,0
  4705.7     0.1       0  4917.8    0.16       0  4996.9     0.1       0
  5004.3    0.07       0  5010.3     0.1       0  5297.8    0.16       0
  5339.0     0.1       0
Bank Sta=5004.3,5010.3
Exp/Cntr=0.3,0.1

Type RM Length L Ch R = 1,1003,441,441,441
BEGIN DESCRIPTION:
HICKORY CREEK 2.0
END DESCRIPTION:
XS GIS Cut Line= 2
      2777809.07     10088521.49      2777210.09     10087995.42
#Sta/Elev= 30
  4547.2 1706.97  4560.6 1706.82  4588.1 1704.96  4628.1 1703.79  4645.1 1702.87
  4652.6 1703.44  4660.7 1702.98  4708.6 1700.81  4787.4 1699.65  4794.0 1698.81
  4857.6 1697.38  4900.3 1697.08  4957.2 1697.44  4971.5 1695.49  5003.6 1694.95
  5006.3 1694.45  5009.6 1694.95  5020.8 1695.58  5035.0 1695.62  5041.7 1696.28
  5098.6 1697.35  5127.1 1699.71  5141.3 1700.13  5155.6 1701.59  5204.9 1703.24
  5226.7 1705.34  5233.4 1705.24  5247.6 1707.07  5282.7 1708.46  5344.4 1712.32
#Mann=5,-1,0
  4547.2     0.1       0  4628.1    0.05       0  4660.7     0.1       0
  5003.6    0.07       0  5009.6     0.1       0
Bank Sta=5003.6,5009.6
Exp/Cntr=0.3,0.1

Type RM Length L Ch R = 1,562,363,363,363
BEGIN DESCRIPTION:
Mapping XS 9ba87d2a
END DESCRIPTION:
XS GIS Cut Line= 4
      2778021.91     10088436.80      2777848.28     10088030.95
      2777620.42     10087868.19      2777307.87     10087868.19
#Sta/Elev= 30
  4391.0 1707.55  4481.4 1704.32  4546.6 1700.97  4698.9 1695.46  4775.0 1693.55
  4887.7 1691.55  4909.0 1690.65  4952.8 1689.72  4967.4 1688.29  4973.7 1687.69
  4979.9 1685.52  4988.5 1681.64  4994.6 1677.37  5000.2 1676.64  5002.9 1676.14
  5006.2 1676.64  5016.5 1686.74  5024.1 1689.42  5121.4 1690.55  5154.4 1691.16
  5214.4 1693.27  5274.4 1695.97  5318.7 1698.61  5344.4 1700.77  5364.4 1703.68
  5374.4 1703.71  5384.4 1702.98  5404.4 1704.25  5422.2 1706.53  5425.0 1706.53
#Mann=7,-1,0
  4391.0     0.1       0  4909.0    0.16       0  4967.4     0.1       0
  5000.2    0.07       0  5006.2     0.1       0  5121.4    0.05       0
  5318.7     0.1       0
Bank Sta=5000.2,5006.2
Exp/Cntr=0.3,0.1

Type RM Length L Ch R = 1,199,56,56,56
BEGIN DESCRIPTION:
Mapping XS 21195674
END DESCRIPTION:
XS GIS Cut Line= 4
      2778102.64     10088137.12      2778011.49     10087700.91
      2777885.63     10087627.13      2777375.69     10087692.22
#Sta/Elev= 30
  4487.7 1698.31  4579.7 1694.55  4705.7 1690.71  4848.7 1688.52  4879.6 1687.18
  4935.5 1686.34  4948.4 1685.10  4977.3 1675.57  4983.2 1672.08  4990.0 1670.17
  4992.7 1669.67  4996.0 1670.17  5006.4 1670.53  5014.5 1673.55  5029.6 1680.22
  5035.9 1682.35  5041.7 1683.56  5057.4 1684.74  5073.1 1685.27  5146.4 1685.85
  5257.8 1688.13  5288.1 1688.25  5358.6 1690.07  5405.9 1692.34  5410.9 1692.18
  5459.4 1694.71  5485.7 1696.66  5530.0 1698.49  5565.5 1700.85  5593.3 1701.79
#Mann=4,-1,0
  4487.7     0.1       0  4990.0    0.07       0  4996.0     0.1       0
  5146.4    0.05       0
Bank Sta=4990,4996
Exp/Cntr=0.3,0.1

Type RM Length L Ch R = 1,143,55,55,55
BEGIN DESCRIPTION:
Mapping XS 045987f5
END DESCRIPTION:
XS GIS Cut Line= 4
      2778143.86     10088115.36      2778041.88     10087648.83
      2777894.31     10087577.21      2777393.27     10087657.47
#Sta/Elev= 30
  4450.0 1697.29  4461.9 1697.26  4574.5 1693.33  4605.2 1691.81  4684.0 1689.69
  4799.7 1688.47  4912.3 1686.58  4927.6 1685.76  4954.9 1683.22  4971.9 1682.35
  4977.5 1682.85  4986.9 1682.63  4994.5 1681.68  5000.0 1682.80  5009.1 1682.29
  5014.0 1681.26  5016.8 1680.76  5020.0 1681.26  5022.6 1682.68  5031.4 1682.12
  5062.2 1684.72  5096.8 1684.73  5165.8 1685.81  5310.2 1688.09  5354.9 1689.26
  5472.2 1693.92  5502.6 1695.68  5522.8 1697.61  5546.0 1697.95  5599.0 1701.21
#Mann=4,-1,0
  4450.0     0.1       0  5014.0    0.07       0  5020.0     0.1       0
  5165.8    0.05       0
Bank Sta=5014,5020
Exp/Cntr=0.3,0.1

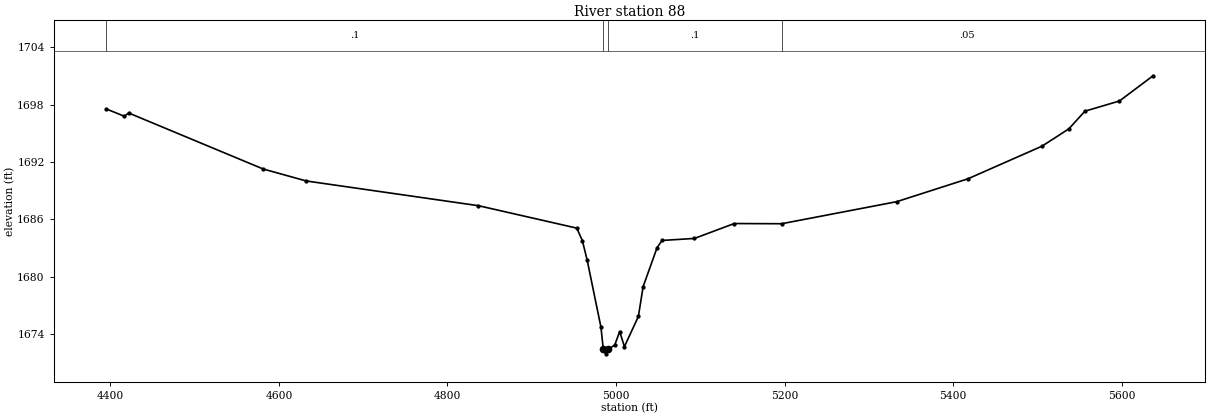
Type RM Length L Ch R = 1,88,0,0,0
BEGIN DESCRIPTION:
HICKORY CREEK 1.0
END DESCRIPTION:
XS GIS Cut Line= 4
      2778178.59     10088126.23      2778070.09     10087603.25
      2777918.18     10087525.13      2777388.70     10087616.27
#Sta/Elev= 30
  4395.1 1697.56  4416.6 1696.79  4421.8 1697.13  4581.5 1691.26  4632.5 1690.01
  4836.8 1687.42  4953.5 1685.07  4960.1 1683.76  4965.7 1681.76  4982.2 1674.68
  4984.9 1672.40  4987.6 1671.90  4990.9 1672.40  4998.5 1672.81  5004.4 1674.24
  5010.0 1672.65  5026.6 1675.82  5032.2 1678.94  5048.8 1683.03  5054.7 1683.78
  5093.1 1683.99  5140.3 1685.55  5196.6 1685.53  5333.1 1687.84  5417.7 1690.24
  5505.6 1693.66  5537.5 1695.48  5556.4 1697.32  5597.4 1698.39  5637.3 1701.03
#Mann=4,-1,0
  4395.1     0.1       0  4984.9    0.07       0  4990.9     0.1       0
  5196.6    0.05       0
Bank Sta=4984.9,4990.9
Exp/Cntr=0.3,0.1

Chan Stop Cuts=-1