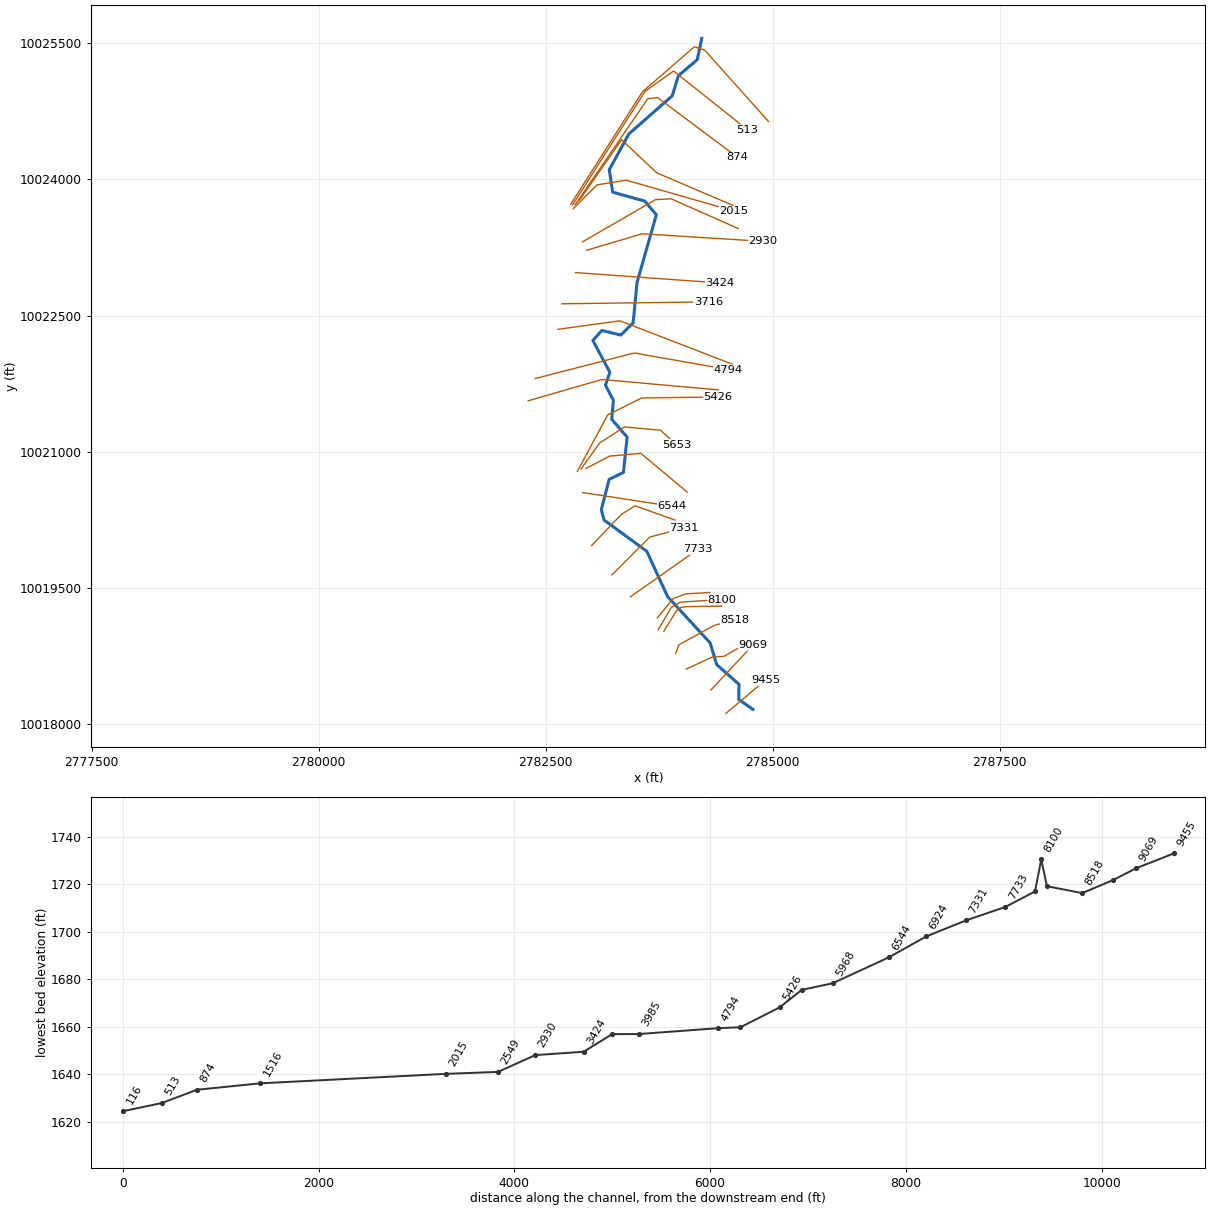
--- HOPFS CREEK.prj (project) ---

Proj Title=HOPFS CREEK Base Level Engineering
Current Plan=p01
Default Exp/Contr=0.3,0.1
English Units
Geom File=g01
Flow File=f01
Plan File=p01
Y Axis Title=Elevation
X Axis Title(PF)=Main Channel Distance
X Axis Title(XS)=Station
BEGIN DESCRIPTION:
HOPFS CREEK
END DESCRIPTION:
DSS Export Rating Curves= 0
DSS Export Rating Curve Sorted= 0
DSS Export Volume Flow Curves= 0
DXF OffsetX= 0
DXF OffsetY= 0
DXF ScaleX= 1
DXF ScaleY= 10

--- HOPFS CREEK.p01 (plan) ---

Plan Title=Multiple Run
Short Identifier=Multiple
Geom File=g01
Flow File=f01
Subcritical Flow
K Sum by GR= 0
Std Step Tol= 0.01
Critical Tol= 0.01
Num of Std Step Trials= 20
Max Error Tol= 0.3
Flow Tol Ratio= 0.001
Split Flow NTrial= 30
Split Flow Tol= 0.02
Split Flow Ratio= 0.02
Log Output Level= 0
Friction Slope Method= 1
Unsteady Friction Slope Method= 2
Unsteady Bridges Friction Slope Method= 1
Parabolic Critical Depth
Global Vel Dist=  1 , 1 , 1
Global Log Level= 0
CheckData=True
Encroach Param= -1, 0, 0, 0
BEGIN DESCRIPTION:
Multiple Run
END DESCRIPTION:

--- HOPFS CREEK.f01 (steady flow) ---

Flow Title=Multiple
Program Version=4.10
Number of Profiles= 7
Profile Names=10-year,25-year,50-year,1pct_min,100-year,1pct_plu,500-year
River Rch & RM=HOPFS CREEK,Reach-1         ,9455
     730    1053    1333    1236    1671    2260    2637
River Rch & RM=HOPFS CREEK,Reach-1         ,5968
    2178    3284    4278    4064    5495    7432    9116
River Rch & RM=HOPFS CREEK,Reach-1         ,5426
    2178    3284    4278    4064    5495    7432    9116
River Rch & RM=HOPFS CREEK,Reach-1         ,5026
    2178    3284    4278    4064    5495    7432    9116
Boundary for River Rch & Prof#=HOPFS CREEK,Reach-1         , 1
Up Type= 0
Dn Type= 3
Dn Slope=0.005
Boundary for River Rch & Prof#=HOPFS CREEK,Reach-1         , 2
Up Type= 0
Dn Type= 3
Dn Slope=0.005
Boundary for River Rch & Prof#=HOPFS CREEK,Reach-1         , 3
Up Type= 0
Dn Type= 3
Dn Slope=0.005
Boundary for River Rch & Prof#=HOPFS CREEK,Reach-1         , 4
Up Type= 0
Dn Type= 3
Dn Slope=0.005
Boundary for River Rch & Prof#=HOPFS CREEK,Reach-1         , 5
Up Type= 0
Dn Type= 3
Dn Slope=0.005
Boundary for River Rch & Prof#=HOPFS CREEK,Reach-1         , 6
Up Type= 0
Dn Type= 3
Dn Slope=0.005
Boundary for River Rch & Prof#=HOPFS CREEK,Reach-1         , 7
Up Type= 0
Dn Type= 3
Dn Slope=0.005
DSS Import GetInterval= 0
DSS Import GetPeak= 0
DSS Import FillOption= 0

--- HOPFS CREEK.g01 (geometry) ---

Geom Title=Existing Conditions
Program Version=4.10

River Reach=HOPFS CREEK     ,Reach-1
Reach XY= 30
      2784781.69     10018166.54      2784625.44     10018275.91
      2784628.04     10018442.58      2784383.25     10018658.72
      2784310.33     10018898.31      2783842.48     10019407.05
      2783613.53     10019906.28      2783142.15     10020251.31
      2783112.51     10020364.48      2783198.74     10020698.41
      2783355.93     10020774.55      2783396.52     10021163.81
      2783227.18     10021358.98      2783245.57     10021568.08
      2783158.33     10021734.74      2783206.34     10021877.66
      2783019.79     10022227.95      2783117.86     10022337.53
      2783326.99     10022287.24      2783462.75     10022421.15
      2783505.54     10022865.62      2783718.22     10023611.72
      2783589.48     10023761.91      2783237.13     10023860.53
       2783200.4     10024108.27      2783415.93     10024501.27
       2783893.6     10024921.05      2783960.75     10025142.18
      2784168.52     10025318.74      2784218.47     10025553.73

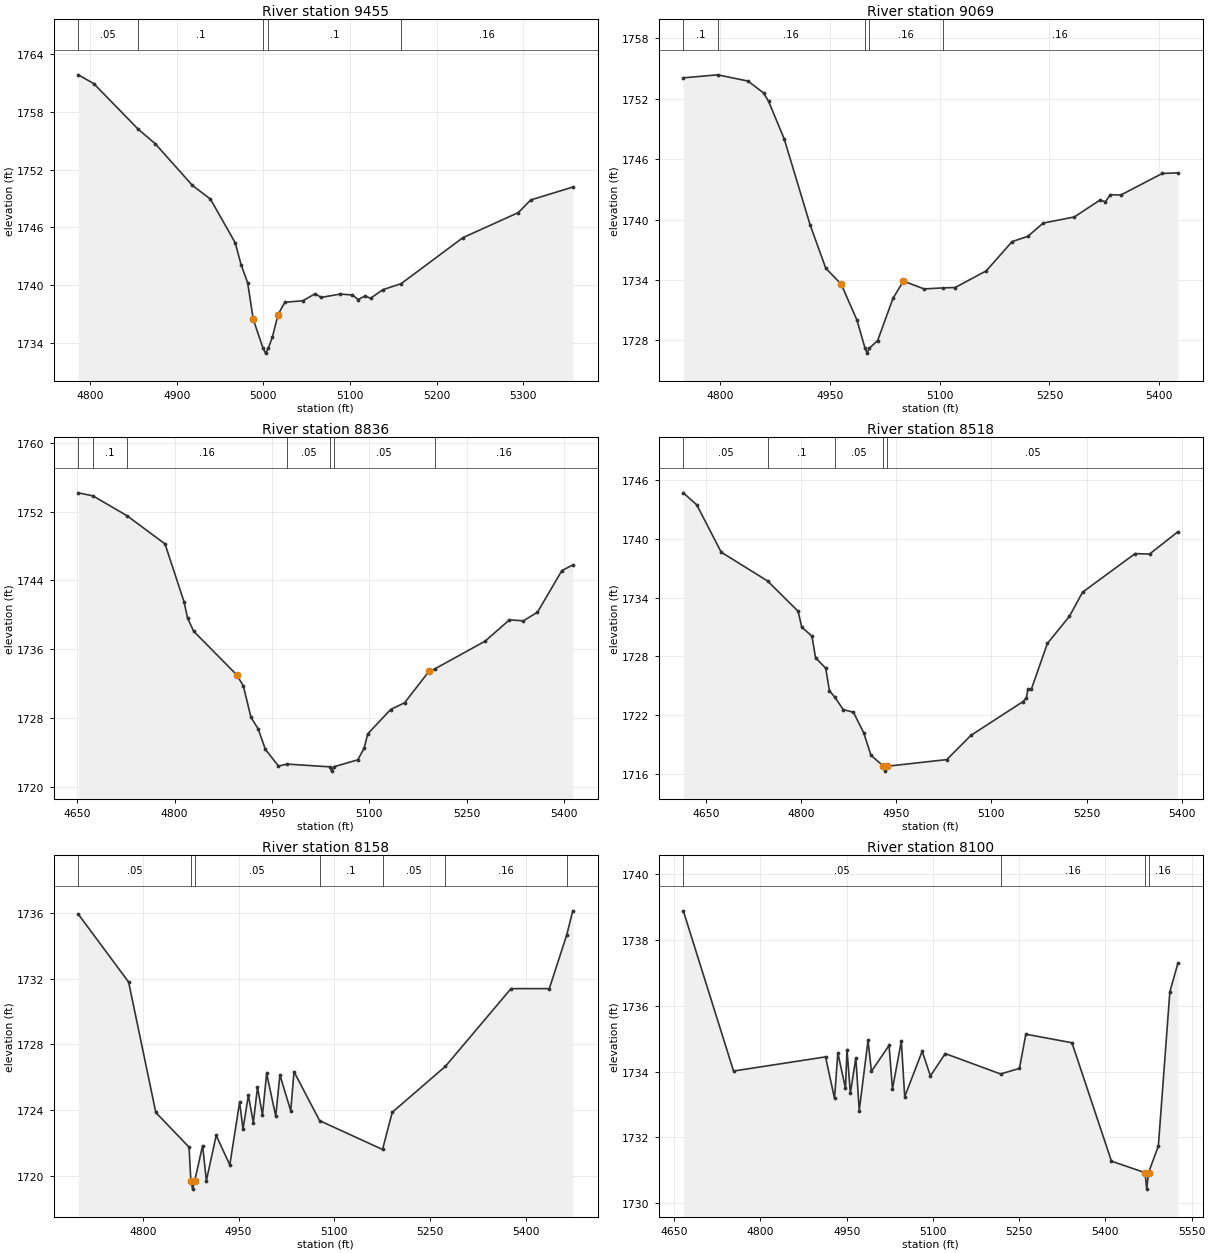
Type RM Length L Ch R = 1 ,9455    ,386,386,386
BEGIN DESCRIPTION:
HOPFS CREEK 18.0
END DESCRIPTION:
XS GIS Cut Line= 2
      2784484.78     10018122.24      2784921.34      10018489.5
#Sta/Elev= 30
  4786.5 1761.82  4804.4 1760.91  4855.7 1756.18  4875.3 1754.68  4918.2 1750.36
    4939 1748.94  4967.6 1744.41  4974.3 1742.15  4981.9 1740.28  4988.4 1736.47
  4999.7 1733.48  5002.5 1732.98  5005.7 1733.48  5010.5 1734.66    5017 1736.98
  5024.8 1738.25  5045.6 1738.41  5059.9 1739.14  5066.5 1738.75  5088.5  1739.1
  5102.8 1739.01  5109.4 1738.53  5117.1  1738.9  5123.7 1738.67    5138 1739.56
  5158.8 1740.17  5230.3 1744.95  5294.1 1747.54  5308.4 1748.85    5357 1750.19
#Mann= 5 ,-1 , 0
  4786.5     .05       0  4855.7      .1       0  4999.7     .07       0
  5005.7      .1       0  5158.8     .16       0
Bank Sta=4988.4,5017
XS Rating Curve= 0 ,0
Exp/Cntr=0.3,0.1

Type RM Length L Ch R = 1 ,9069    ,233,233,233
BEGIN DESCRIPTION:
HOPFS CREEK 17.0
END DESCRIPTION:
XS GIS Cut Line= 2
      2784318.14     10018379.21      2784779.91     10018872.23
#Sta/Elev= 30
  4749.9 1754.09  4796.8 1754.39  4838.3 1753.77  4859.5 1752.59  4866.3 1751.77
  4887.8 1748.01    4923 1739.51  4944.5 1735.17  4965.5  1733.6    4987 1730.04
  4998.1 1727.24  5000.9 1726.74  5004.1 1727.24  5015.3 1727.98  5036.3 1732.18
  5050.5  1733.9  5078.8 1733.12  5104.3 1733.22  5121.3 1733.26  5163.8 1734.92
    5199 1737.82  5220.4 1738.34  5241.5 1739.66    5284 1740.27  5319.1 1741.95
  5326.4 1741.78  5333.3 1742.48  5347.5 1742.45  5404.1 1744.59  5425.4 1744.65
#Mann= 5 ,-1 , 0
  4749.9      .1       0  4796.8     .16       0  4998.1     .07       0
  5004.1     .16       0  5104.3     .16       0
Bank Sta=4965.5,5050.5
XS Rating Curve= 0 ,0
Exp/Cntr=0.3,0.1

Type RM Length L Ch R = 1 ,8836    ,318,318,318
BEGIN DESCRIPTION:
HOPFS CREEK 16.0
END DESCRIPTION:
XS GIS Cut Line= 4
      2784047.34     10018609.26      2784328.56     10018740.32
      2784463.98     10018750.74      2784738.32     10018907.01
#Sta/Elev= 30
  4651.5 1754.18  4674.3 1753.82  4726.7 1751.51  4785.1 1748.24  4814.3 1741.53
  4819.9 1739.61  4829.3 1738.07  4895.5 1733.01  4905.8 1731.71  4917.5 1728.07
  4928.6 1726.72  4939.7 1724.34  4959.9 1722.39  4973.1 1722.62  5038.9  1722.3
  5041.6  1721.8  5044.9  1722.3    5082 1723.11    5092 1724.48  5097.3 1726.13
  5132.7 1728.97  5154.3 1729.76  5191.8 1733.42  5200.4 1733.68  5278.2 1736.92
  5315.7  1739.4  5337.3 1739.29  5358.9 1740.29  5396.4 1745.13  5413.3 1745.79
#Mann= 7 ,-1 , 0
  4651.5     .05       0  4674.3      .1       0  4726.7     .16       0
  4973.1     .05       0  5038.9    .033       0  5044.9     .05       0
  5200.4     .16       0
Bank Sta=4895.5,5191.8
XS Rating Curve= 0 ,0
Exp/Cntr=0.3,0.1

Type RM Length L Ch R = 1 ,8518    ,360,360,360
BEGIN DESCRIPTION:
HOPFS CREEK 15.0
END DESCRIPTION:
XS GIS Cut Line= 4
      2783932.74     10018783.75      2783966.58     10018877.47
      2784357.21     10019091.01       2784583.6     10019150.87
#Sta/Elev= 30
  4614.7 1744.69  4635.9 1743.46  4674.4 1738.63  4747.4 1735.69  4795.5  1732.6
  4801.2 1730.98  4817.3 1730.06    4823 1727.86  4839.1 1726.77  4844.8 1724.49
  4853.7 1723.79  4866.6 1722.56  4882.7 1722.28  4898.8  1720.2  4910.3 1717.89
    4930 1716.77  4932.8 1716.27    4936 1716.77  5029.8 1717.45  5067.7 1719.92
  5149.3 1723.35    5155 1723.71  5157.4 1724.61  5162.8 1724.61  5188.2 1729.31
  5222.9 1732.08  5243.6 1734.54  5326.3 1738.48  5349.2 1738.44  5393.7 1740.71
#Mann= 5 ,-1 , 0
  4614.7     .05       0  4747.4      .1       0  4853.7     .05       0
    4930    .033       0    4936     .05       0
Bank Sta=4930,4936
XS Rating Curve= 0 ,0
Exp/Cntr=0.3,0.1

Type RM Length L Ch R = 1 ,8158    ,58,58,58
BEGIN DESCRIPTION:
HOPFS CREEK 14.0
END DESCRIPTION:
XS GIS Cut Line= 5
      2783799.95     10019025.06      2783936.96     10019247.67
      2783983.83     10019286.74      2784041.12     10019297.15
      2784435.23      10019302.8
#Sta/Elev= 30
  4698.9 1735.96  4777.8 1731.81  4820.4 1723.85  4872.5 1721.73  4875.3 1719.67
  4878.1 1719.17  4881.3 1719.67  4893.7 1721.83  4899.6 1719.69    4915 1722.45
  4936.3 1720.65  4951.7 1724.48    4957 1722.83  4965.4  1724.9  4973.2 1723.23
  4979.7 1725.39  4987.5 1723.69    4994 1726.23  5008.3 1723.63  5014.8 1726.14
  5031.8 1723.95  5036.9 1726.34    5077 1723.35  5175.6 1721.59  5190.8 1723.86
  5274.2 1726.67  5376.9 1731.41  5436.9 1731.41  5464.1 1734.68  5473.7 1736.16
#Mann= 7 ,-1 , 0
  4698.9     .05       0  4875.3    .035       0  4881.3     .05       0
    5077      .1       0  5175.6     .05       0  5274.2     .16       0
  5464.1     .05       0
Bank Sta=4875.3,4881.3
XS Rating Curve= 0 ,0
Exp/Cntr=0.3,0.1

Type RM Length L Ch R = 1 ,8100    ,64,64,64
BEGIN DESCRIPTION:
Mapping XS 4fadc9d9
END DESCRIPTION:
XS GIS Cut Line= 4
      2783738.87     10019043.76      2783882.27     10019286.74
      2783978.62     10019346.63      2784442.31     10019375.75
#Sta/Elev= 30
  4665.8 1738.89  4753.2 1734.02  4913.2 1734.45  4928.8 1733.19  4934.6 1734.57
  4947.9 1733.49  4950.5 1734.67  4956.4 1733.35  4965.9 1734.42  4971.8 1732.82
  4987.1 1734.95    4993 1734.01  5023.7  1734.8  5029.6 1733.47    5045 1734.93
  5050.9 1733.24  5081.3 1734.62  5095.6 1733.87  5121.4 1734.55  5217.7 1733.93
  5250.5  1734.1  5261.6 1735.14  5341.8 1734.88  5410.5 1731.28    5469 1730.93
  5471.8 1730.43    5475 1730.93  5492.1 1731.74  5512.1 1736.43    5526 1737.29
#Mann= 4 ,-1 , 0
  4665.8     .05       0  5217.7     .16       0    5469    .035       0
    5475     .16       0
Bank Sta=5469,5475
XS Rating Curve= 0 ,0
Exp/Cntr=0.3,0.1

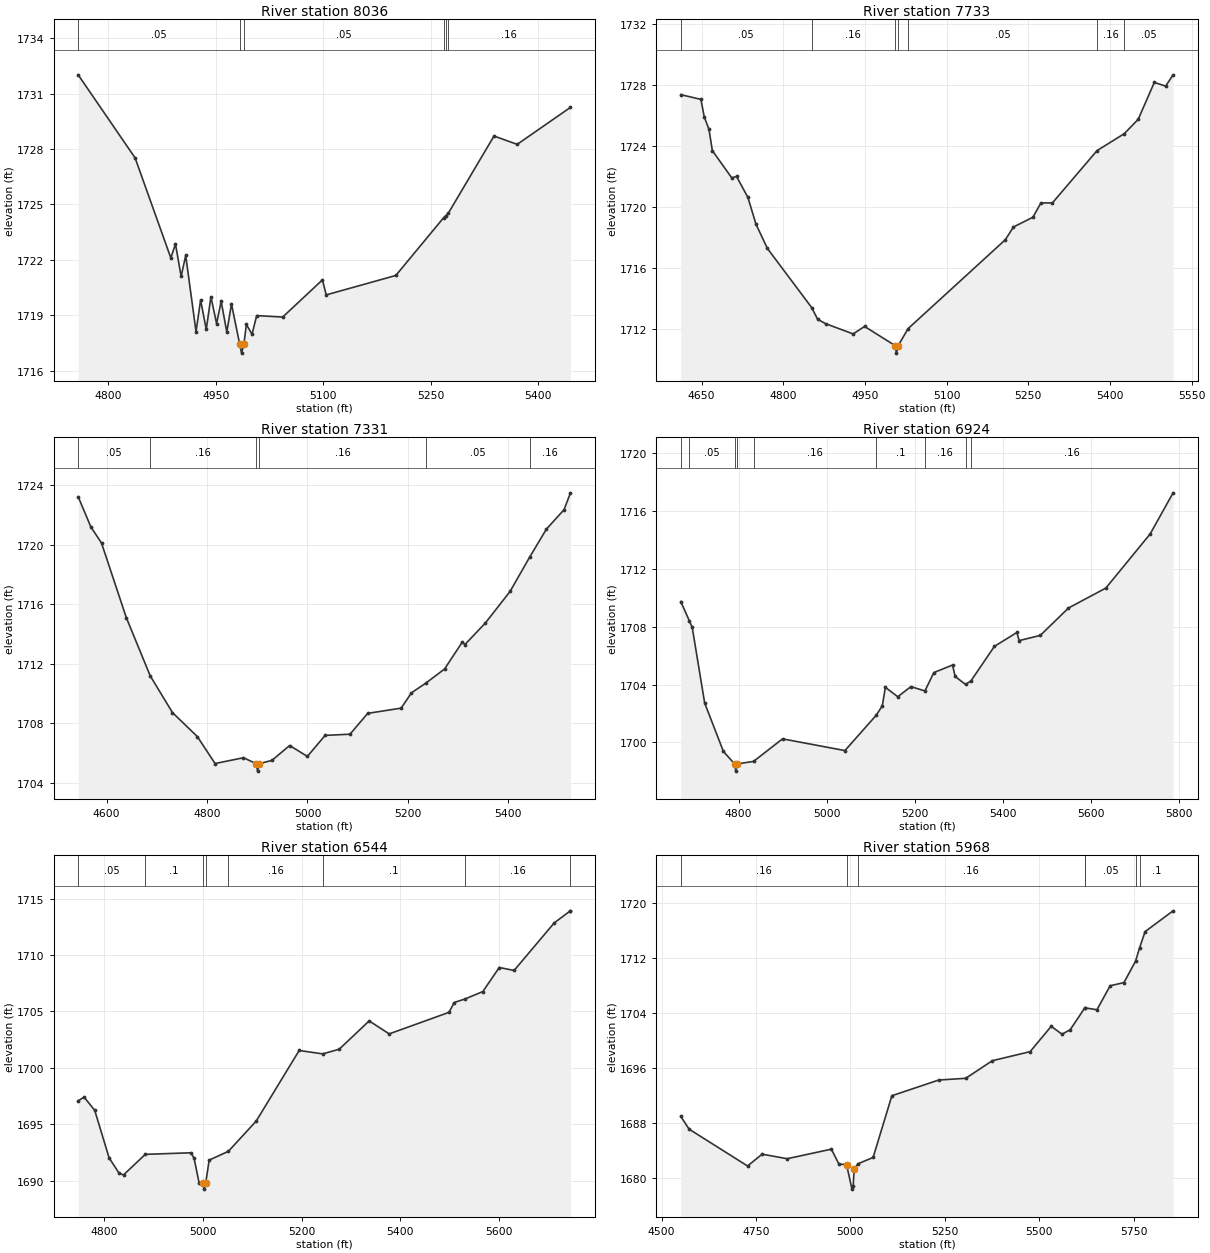
Type RM Length L Ch R = 1 ,8036    ,303,303,303
BEGIN DESCRIPTION:
Mapping XS 7a658796
END DESCRIPTION:
XS GIS Cut Line= 4
      2783728.63     10019172.16       2783903.1      10019385.7
      2784043.73     10019437.78      2784305.06      10019453.3
#Sta/Elev= 30
  4757.7 1732.01  4837.2 1727.52  4887.1 1722.11  4893.6 1722.86  4901.5 1721.11
  4907.9 1722.24  4922.3 1718.12  4928.7 1719.83  4936.6 1718.24  4943.1 1720.01
    4951 1718.56  4957.4 1719.76  4965.3  1718.1  4971.8 1719.62  4983.2 1717.46
  4985.9 1716.96  4989.2 1717.46  4992.6 1718.51  5000.5 1717.98    5007 1718.99
  5043.3 1718.91  5098.8 1720.92  5104.1 1720.11  5201.3 1721.16    5268 1724.28
  5270.7 1724.38  5274.5 1724.52  5338.4  1728.7  5370.8 1728.25  5445.2 1730.25
#Mann= 6 ,-1 , 0
  4757.7     .05       0  4983.2    .035       0  4989.2     .05       0
    5268     .16       0  5270.7     .05       0  5274.5     .16       0
Bank Sta=4983.2,4989.2
XS Rating Curve= 0 ,0
Exp/Cntr=0.3,0.1

Type RM Length L Ch R = 1 ,7733    ,402,402,402
BEGIN DESCRIPTION:
Mapping XS 8e7bf24f
END DESCRIPTION:
XS GIS Cut Line= 2
      2783434.39     10019406.56      2784173.67     10019927.17
#Sta/Elev= 30
  4611.7 1727.39  4648.7 1727.08  4654.9 1725.92  4663.5 1725.12  4669.7 1723.72
  4705.4 1721.93  4714.1 1722.03    4735 1720.65  4749.8  1718.9  4770.7 1717.31
  4852.3 1713.42    4863 1712.66  4877.8 1712.37  4928.3  1711.7  4949.3 1712.19
  5005.1 1710.94  5007.8 1710.44  5011.1 1710.94  5029.3 1712.05  5207.9 1717.88
  5222.7 1718.71  5258.4 1719.35  5273.2 1720.29  5294.2 1720.29  5376.2 1723.72
  5426.2 1724.83  5451.8 1725.77  5481.4 1728.19  5502.3 1727.95  5515.9 1728.69
#Mann= 7 ,-1 , 0
  4611.7     .05       0  4852.3     .16       0  5005.1     .07       0
  5011.1     .16       0  5029.3     .05       0  5376.2     .16       0
  5426.2     .05       0
Bank Sta=5005.1,5011.1
XS Rating Curve= 0 ,0
Exp/Cntr=0.3,0.1

Type RM Length L Ch R = 1 ,7331    ,407,407,407
BEGIN DESCRIPTION:
HOPFS CREEK 13.0
END DESCRIPTION:
XS GIS Cut Line= 3
      2783229.51       10019647.      2783646.16     10020063.65
      2784024.91     10020162.23
#Sta/Elev= 30
  4543.3 1723.22  4568.5  1721.2  4589.8 1720.11  4639.2  1715.1  4686.8 1711.19
  4731.2 1708.72  4780.7 1707.11    4816  1705.3  4872.6 1705.69  4897.9 1705.29
  4900.6 1704.79  4903.9 1705.29  4929.2 1705.51  4964.5 1706.51  4999.9 1705.78
  5035.2 1707.19  5084.7 1707.27  5120.1 1708.67  5186.6 1709.02  5207.2 1710.05
  5235.8  1710.7  5273.1 1711.65  5308.5 1713.46  5313.6 1713.29  5354.2 1714.73
  5403.6 1716.86  5442.4 1719.15  5475.9 1721.04  5511.1 1722.35  5523.9 1723.48
#Mann= 6 ,-1 , 0
  4543.3     .05       0  4686.8     .16       0  4897.9     .07       0
  4903.9     .16       0  5235.8     .05       0  5442.4     .16       0
Bank Sta=4897.9,4903.9
XS Rating Curve= 0 ,0
Exp/Cntr=0.3,0.1

Type RM Length L Ch R = 1 ,6924    ,380,380,380
BEGIN DESCRIPTION:
HOPFS CREEK 12.0
END DESCRIPTION:
XS GIS Cut Line= 4
      2783005.55     10019969.91      2783333.66     10020313.65
       2783484.7      10020407.4      2783922.17     10020251.16
#Sta/Elev= 30
  4668.8 1709.74  4688.2 1708.41  4694.8 1707.95  4723.1 1702.72  4765.6 1699.38
  4790.9 1698.52  4793.6 1698.02  4796.9 1698.52  4833.9 1698.69  4899.8 1700.25
  5041.4 1699.44    5113  1701.9  5126.3 1702.54  5133.2 1703.81  5161.4 1703.16
  5191.2 1703.86    5223 1703.56  5243.2 1704.83  5285.7 1705.35  5291.6 1704.56
  5315.3 1704.01  5327.6 1704.26  5380.7 1706.64  5431.7  1707.6    5437 1707.04
    5485  1707.4  5548.8 1709.29  5633.7 1710.67  5734.3 1714.41  5786.3 1717.25
#Mann= 9 ,-1 , 0
  4668.8      .1       0  4688.2     .05       0  4790.9     .07       0
  4796.9     .05       0  4833.9     .16       0    5113      .1       0
    5223     .16       0  5315.3      .1       0  5327.6     .16       0
Bank Sta=4790.9,4796.9
XS Rating Curve= 0 ,0
Exp/Cntr=0.3,0.1

Type RM Length L Ch R = 1 ,6544    ,576,576,576
BEGIN DESCRIPTION:
HOPFS CREEK 11.0
END DESCRIPTION:
XS GIS Cut Line= 2
      2782906.56     10020553.23      2783890.94     10020402.19
#Sta/Elev= 30
  4748.1 1697.08  4760.1 1697.41  4781.6 1696.24  4810.7 1692.03    4831 1690.66
  4839.9 1690.52  4883.9 1692.34  4976.6 1692.48  4982.7 1691.98  4992.8  1689.8
    5000 1689.76  5002.7 1689.26    5006 1689.76  5013.1 1691.83    5052 1692.61
  5108.3 1695.29  5195.2 1701.54  5242.7 1701.24  5276.1 1701.65  5336.8 1704.16
  5377.3 1703.01  5498.3 1704.92  5508.8 1705.79  5530.5  1706.1  5566.7 1706.76
  5599.9 1708.89    5630 1708.63  5711.1 1712.84  5743.7 1713.91    5744 1713.91
#Mann= 8 ,-1 , 0
  4748.1     .05       0  4883.9      .1       0    5000     .07       0
    5006      .1       0    5052     .16       0  5242.7      .1       0
  5530.5     .16       0  5743.7      .1       0
Bank Sta=5000,5006
XS Rating Curve= 0 ,0
Exp/Cntr=0.3,0.1

Type RM Length L Ch R = 1 ,5968    ,315,315,315
BEGIN DESCRIPTION:
HOPFS CREEK 10.0
END DESCRIPTION:
XS GIS Cut Line= 4
      2782943.07     10020818.88      2783203.45     10020954.27
       2783547.2     10020985.52      2784057.41     10020558.61
#Sta/Elev= 30
  4550.8  1688.9    4573 1687.04  4727.7 1681.68  4766.3  1683.4  4832.6 1682.74
  4949.7 1684.13  4969.8 1681.95  4989.9 1681.88  5004.2 1678.31  5007.5 1678.81
    5010  1681.2    5020    1682  5060.2 1682.92  5109.9 1691.91    5234  1694.2
  5305.5 1694.45  5375.8 1697.01    5476 1698.33  5531.9 1702.02  5560.6 1700.87
  5582.3 1701.53  5620.1 1704.64  5621.8  1704.7    5653 1704.44  5688.1 1707.93
  5724.5 1708.39  5755.2 1711.49  5765.9 1713.44  5780.5 1715.81  5854.7 1718.84
#Mann= 7 ,-1 , 0
  4550.8     .16       0  4989.9     .07       0    5020     .16       0
  5620.1     .16       0  5621.8     .05       0  5755.2     .16       0
  5765.9      .1       0
Bank Sta=4989.9,5010
XS Rating Curve= 0 ,0
Exp/Cntr=0.3,0.1

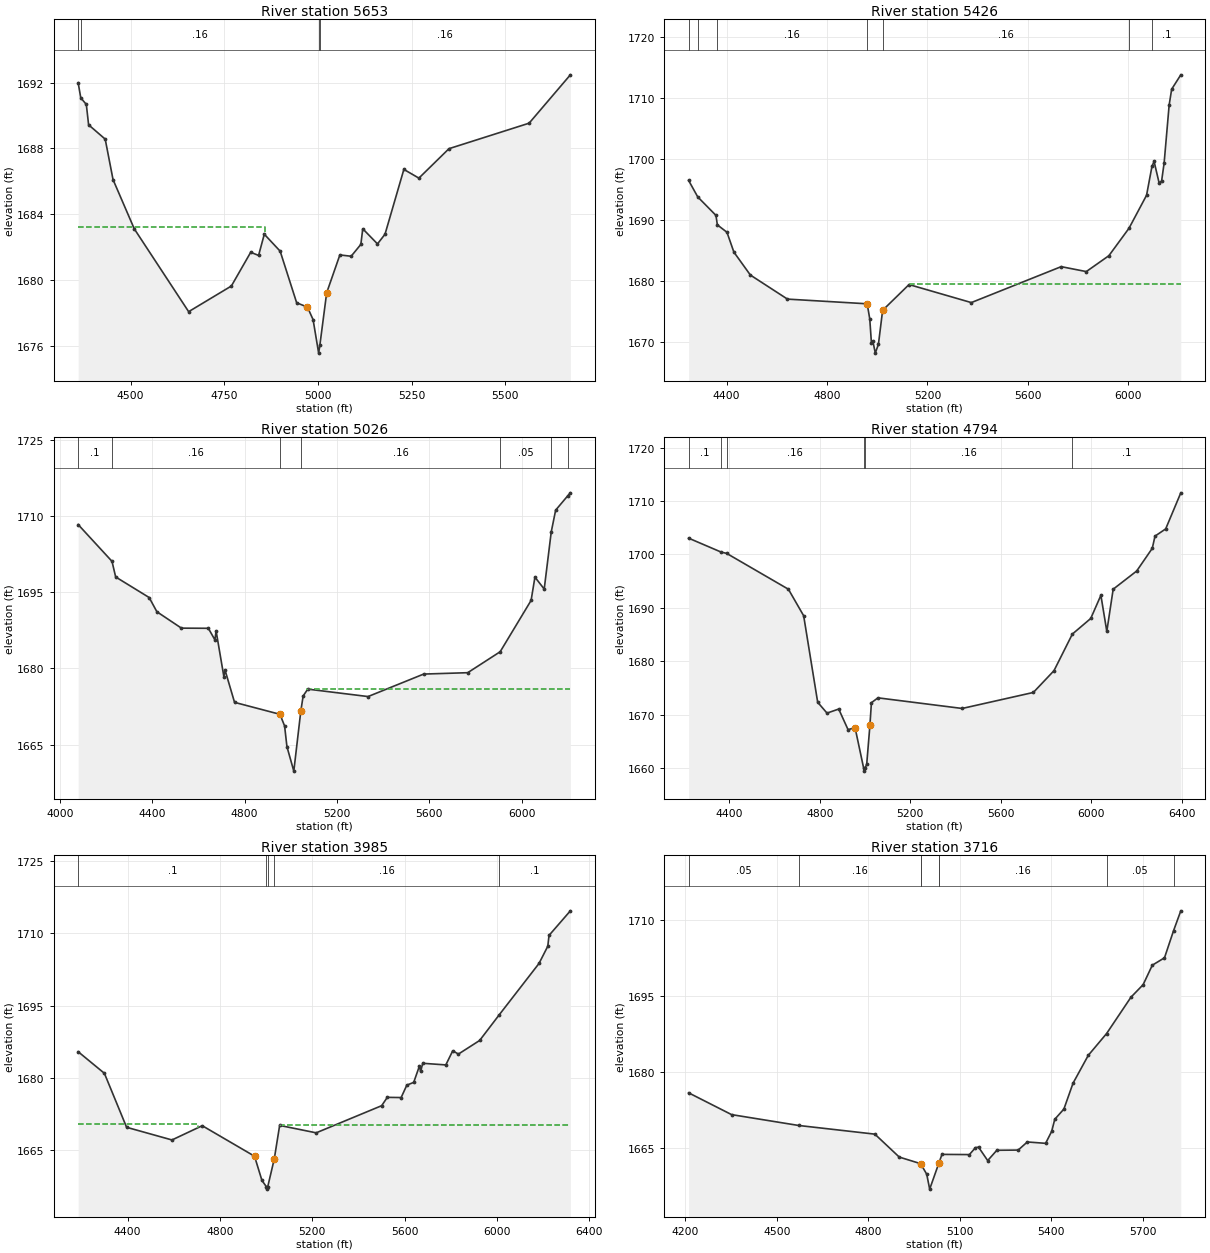
Type RM Length L Ch R = 1 ,5653    ,227,227,227
BEGIN DESCRIPTION:
Mapping XS 6f1a389d
END DESCRIPTION:
XS GIS Cut Line= 5
      2782890.02     10020812.15      2783093.16     10021098.64
       2783369.2     10021275.72      2783765.04     10021239.26
      2783939.01     10021078.27
#Sta/Elev= 30
    4360 1691.99    4367 1691.07  4381.8 1690.67  4387.9 1689.43  4432.2 1688.56
  4453.1  1686.1  4509.7 1683.11  4654.9 1678.07  4768.9 1679.63  4820.5 1681.68
  4841.6 1681.49  4856.8 1682.78  4899.1 1681.75  4943.2 1678.61  4971.8 1678.35
    4987 1677.59  5001.9 1675.55  5005.2 1676.05  5023.3 1679.22  5058.5 1681.52
  5088.6 1681.44  5114.5 1682.16  5119.6 1683.11  5158.9 1682.19    5179 1682.78
  5229.3 1686.72  5269.4 1686.19  5349.7 1687.98  5563.6 1689.53  5673.7 1692.47
#Mann= 4 ,-1 , 0
    4360     .05       0    4367     .16       0  5001.9     .07       0
  5005.2     .16       0
#XS Ineff= 2 , 0
         4857.96 1683.21
Permanent Ineff=
       T       T
Bank Sta=4971.8,5023.3
XS Rating Curve= 0 ,0
Exp/Cntr=0.3,0.1

Type RM Length L Ch R = 1 ,5426    ,400,400,400
BEGIN DESCRIPTION:
HOPFS CREEK 9.0
END DESCRIPTION:
XS GIS Cut Line= 4
      2782849.27     10020787.58      2783182.62      10021407.4
      2783557.62      10021594.9      2784394.81      10021605.3
#Sta/Elev= 30
    4249 1696.52  4285.5  1693.8    4358 1690.77  4363.6 1689.21  4401.8    1688
  4429.4 1684.74  4495.1 1680.97  4642.8 1677.02  4960.3 1676.25  4970.5 1673.78
  4977.1 1669.86  4982.7 1670.17  4992.6 1668.15  5005.1 1669.61  5021.8 1675.18
    5127 1679.41    5375 1676.45  5732.9 1682.35  5832.9 1681.54  5922.9 1684.15
  6002.9 1688.65  6072.9 1694.07  6094.6 1698.85  6102.9 1699.62  6122.9  1696.1
  6132.9 1696.42  6142.9 1699.37  6162.9 1708.89  6172.9 1711.49  6209.3 1713.85
#Mann= 7 ,-1 , 0
    4249     .16       0  4285.5     .05       0  4363.6     .16       0
  4960.3     .07       0  5021.8     .16       0  6002.9     .05       0
  6094.6      .1       0
#XS Ineff= 2 , 0
                          5131.9         1679.55
Permanent Ineff=
       T       T
Bank Sta=4960.3,5021.8
XS Rating Curve= 0 ,0
Exp/Cntr=0.3,0.1

Type RM Length L Ch R = 1 ,5026    ,232,232,232
BEGIN DESCRIPTION:
HOPFS CREEK 8.0
END DESCRIPTION:
XS GIS Cut Line= 3
      2782307.57     10021563.63      2783120.12     10021798.02
      2784401.33     10021683.44
#Sta/Elev= 30
  4079.4 1708.28    4226 1701.05  4241.9 1697.98  4386.9 1693.94  4420.5 1691.14
  4526.7 1687.92  4643.3 1687.89  4671.7 1685.62  4676.9 1687.37  4710.6 1678.38
  4715.8 1679.65  4756.8 1673.33  4953.5 1670.98  4973.6 1668.69  4983.7 1664.63
  5013.5 1659.81  5043.9 1671.63  5053.9 1674.58    5074 1675.93  5335.1 1674.47
    5576 1678.89  5766.8 1679.16  5907.3 1683.28  6041.3 1693.37  6057.9 1697.95
  6098.1  1695.6  6128.6 1706.85  6147.6 1711.11  6200.7 1713.97  6211.4 1714.52
#Mann= 7 ,-1 , 0
  4079.4      .1       0    4226     .16       0  4953.5     .07       0
  5043.9     .16       0  5907.3     .05       0  6128.6      .1       0
  6200.7     .05       0
#XS Ineff= 2 , 0
                         5071.95         1675.93
Permanent Ineff=
       T       T
Bank Sta=4953.5,5043.9
XS Rating Curve= 0 ,0
Exp/Cntr=0.3,0.1

Type RM Length L Ch R = 1 ,4794    ,809,809,809
BEGIN DESCRIPTION:
HOPFS CREEK 7.0
END DESCRIPTION:
XS GIS Cut Line= 3
      2782385.71     10021808.43      2783474.28     10022089.69
      2784510.75     10021907.39
#Sta/Elev= 30
  4220.1 1703.06  4364.5 1700.44  4388.2 1700.21  4661.5 1693.49    4729 1688.52
    4791 1672.31  4832.3 1670.28    4884 1671.04  4925.3 1667.18  4956.3 1667.55
  4994.6 1659.91  4997.3 1659.41  5000.6 1659.91  5007.9 1660.75  5022.1 1668.04
  5028.6 1672.23  5057.6 1673.14  5429.9 1671.15  5744.7 1674.15    5836 1678.23
  5917.3 1685.09  5998.5 1688.01  6043.4 1692.35  6069.6 1685.59  6097.7 1693.49
  6201.6  1696.9  6270.6 1701.15  6282.8 1703.44  6329.9 1704.79  6396.8 1711.55
#Mann= 6 ,-1 , 0
  4220.1      .1       0  4364.5     .05       0  4388.2     .16       0
  4994.6     .07       0  5000.6     .16       0  5917.3      .1       0
Bank Sta=4956.3,5022.1
XS Rating Curve= 0 ,0
Exp/Cntr=0.3,0.1

Type RM Length L Ch R = 1 ,3985    ,269,269,269
BEGIN DESCRIPTION:
HOPFS CREEK 6.0
END DESCRIPTION:
XS GIS Cut Line= 3
      2782635.78     10022350.11      2783318.03     10022443.86
      2784665.24      10021923.7
#Sta/Elev= 30
  4185.8 1685.45  4299.5 1680.97  4395.7 1669.77  4592.3 1667.14  4723.5  1670.1
    4950 1663.77  4982.1 1658.75  5001.3 1657.44  5004.1 1656.94  5007.3 1657.44
  5035.7 1663.23  5058.9 1670.16  5217.2 1668.62  5500.8 1674.25  5525.4 1675.98
  5585.3 1675.94  5609.9 1678.51  5639.8 1679.09  5664.4 1682.46  5669.8 1681.35
  5678.9 1683.05  5778.9 1682.71  5808.9 1685.64  5833.5 1684.96  5925.4 1687.78
  6011.2 1693.16  6182.7 1703.76  6220.8 1707.34  6226.1 1709.58  6318.6 1714.68
#Mann= 5 ,-1 , 0
  4185.8      .1       0  5001.3     .07       0  5007.3      .1       0
  5035.7     .16       0  6011.2      .1       0
#XS Ineff= 2 , 0
         4704.94 1670.53 5061.05         1670.29
Permanent Ineff=
       T       T
Bank Sta=4950,5035.7
XS Rating Curve= 0 ,0
Exp/Cntr=0.3,0.1

Type RM Length L Ch R = 1 ,3716    ,292,292,292
BEGIN DESCRIPTION:
HOPFS CREEK 5.0
END DESCRIPTION:
XS GIS Cut Line= 2
      2782677.38     10022631.35      2784291.94     10022652.19
#Sta/Elev= 30
  4210.3  1675.9  4351.4  1671.6  4571.4 1669.46  4821.4 1667.75  4901.4 1663.23
  4971.5 1661.93  4991.5 1659.85  5001.2 1656.91    5032 1662.15  5041.5 1663.76
  5131.5 1663.72  5151.5 1665.09  5161.5 1665.19  5191.5 1662.54  5221.5 1664.57
  5291.5 1664.61  5321.5 1666.21  5381.5 1665.94  5401.5 1668.31  5411.5 1670.68
  5441.5  1672.7  5471.5  1677.8  5521.5 1683.29  5581.5 1687.58  5661.5 1694.75
  5701.5 1697.23  5731.5 1701.06  5771.5 1702.52  5801.2 1707.86    5825 1711.78
#Mann= 8 ,-1 , 0
  4210.3     .05       0  4571.4     .16       0  4971.5     .05       0
  4971.5     .07       0    5032     .05       0    5032     .16       0
  5581.5     .05       0  5801.2      .1       0
Bank Sta=4971.5,5032
XS Rating Curve= 0 ,0
Exp/Cntr=0.3,0.1

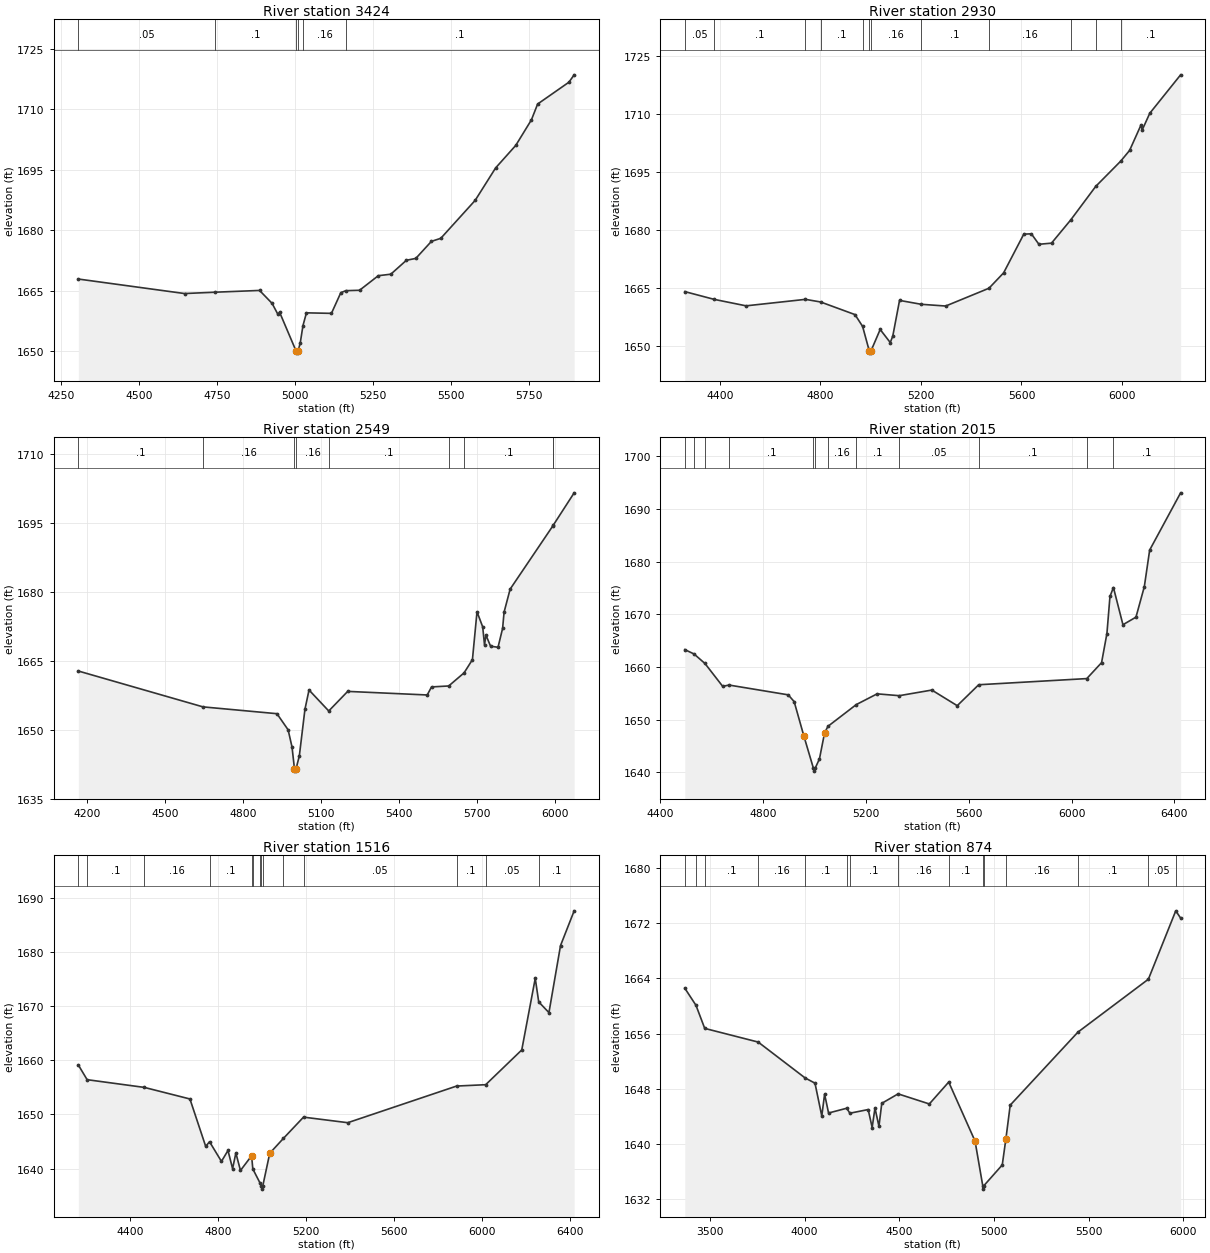
Type RM Length L Ch R = 1 ,3424    ,494,494,494
BEGIN DESCRIPTION:
HOPFS CREEK 4.0
END DESCRIPTION:
XS GIS Cut Line= 2
      2782828.46      10022975.1      2784415.24     10022860.65
#Sta/Elev= 30
  4304.9 1667.89  4645.8 1664.29  4742.9 1664.62  4886.4 1665.06  4926.5 1661.86
  4945.5 1659.09  4950.5 1659.68  5003.7    1650  5006.5  1649.5  5009.7    1650
  5016.7 1651.92  5025.7 1656.34  5036.8  1659.5    5117 1659.37  5147.1  1664.5
  5163.2    1665  5207.2  1665.1  5267.4 1668.72  5307.5 1669.09  5357.6 1672.55
  5387.7 1673.01  5437.8 1677.24  5467.9    1678  5578.2 1687.42  5643.9 1695.48
  5708.5 1701.07  5758.7 1707.41  5778.6 1711.33    5879 1716.75  5895.8 1718.58
#Mann= 6 ,-1 , 0
  4304.9     .05       0  4742.9      .1       0  5003.7     .07       0
  5009.7      .1       0  5025.7     .16       0  5163.2      .1       0
Bank Sta=5003.7,5009.7
XS Rating Curve= 0 ,0
Exp/Cntr=0.3,0.1

Type RM Length L Ch R = 1 ,2930    ,381,381,381
BEGIN DESCRIPTION:
HOPFS CREEK 3.0
END DESCRIPTION:
XS GIS Cut Line= 3
      2782948.23     10023219.89      2783562.82     10023402.19
      2784890.95     10023318.86
#Sta/Elev= 30
  4261.2 1664.03  4378.5 1662.01  4504.9 1660.34  4741.1 1662.02  4801.4 1661.34
    4938 1658.07  4968.3 1655.01  4995.1 1648.58  4997.8 1648.08  5001.1 1648.58
  5038.2 1654.21  5078.3 1650.82  5088.3  1652.5  5115.2 1661.75  5201.5 1660.74
  5298.7 1660.29  5470.8  1664.9  5529.1 1668.89  5609.3 1678.93  5639.4 1679.01
  5669.4  1676.3  5719.5 1676.59  5796.2 1682.63  5895.3  1691.3  5994.4 1697.83
  6030.1 1700.63  6075.2 1707.19  6080.3 1705.95  6110.3 1710.26    6233 1720.23
#Mann= 12 ,-1 , 0
  4261.2     .05       0  4378.5      .1       0  4741.1     .05       0
  4801.4      .1       0  4968.3     .16       0  4995.1     .07       0
  5001.1     .16       0  5201.5      .1       0  5470.8     .16       0
  5796.2      .1       0  5895.3     .05       0  5994.4      .1       0
Bank Sta=4995.1,5001.1
XS Rating Curve= 0 ,0
Exp/Cntr=0.3,0.1

Type RM Length L Ch R = 1 ,2549    ,534,534,534
BEGIN DESCRIPTION:
HOPFS CREEK 2.0
END DESCRIPTION:
XS GIS Cut Line= 4
      2782906.56     10023313.64      2783708.66     10023777.19
      2783880.53     10023787.61      2784620.11     10023459.48
#Sta/Elev= 30
  4165.3 1662.78    4645 1654.98  4929.5  1653.5  4972.5 1649.99  4987.5 1646.25
  4996.9 1641.51  4999.6 1641.01  5002.9 1641.51  5015.6 1644.32  5037.2 1654.46
  5052.9 1658.65  5128.8 1654.09  5201.7 1658.35  5507.7 1657.57  5524.2 1659.32
  5590.3 1659.53  5649.3 1662.37  5681.6 1665.25  5699.2 1675.66  5721.1 1672.38
  5728.1 1668.46  5733.6 1670.59  5751.4 1668.18  5780.1 1667.94  5797.7 1672.05
  5803.4 1675.59  5826.7 1680.59    5992 1694.42  5993.4 1694.56    6073 1701.53
#Mann= 9 ,-1 , 0
  4165.3      .1       0    4645     .16       0  4996.9     .07       0
  5002.9     .16       0  5128.8      .1       0  5590.3     .05       0
  5649.3      .1       0    5992     .16       0  5993.4      .1       0
Bank Sta=4996.9,5002.9
XS Rating Curve= 0 ,0
Exp/Cntr=0.3,0.1

Type RM Length L Ch R = 1 ,2015    ,1899,1899,1899
BEGIN DESCRIPTION:
Mapping XS 929c4fb7
END DESCRIPTION:
XS GIS Cut Line= 4
      2782804.22     10023679.49      2783064.66     10023939.93
      2783387.58     10023992.02      2784574.31     10023651.96
#Sta/Elev= 30
  4494.7 1663.29  4530.6 1662.46  4573.2 1660.65  4642.1 1656.31  4667.1 1656.55
  4897.3 1654.69  4920.4  1653.4    4958 1646.89  4995.6 1640.69  4998.3 1640.19
  5001.6 1640.69  5018.8 1642.51  5038.9 1647.49    5052 1648.71  5162.2 1652.84
  5243.3 1654.88  5329.3 1654.53  5456.2  1655.6  5555.1 1652.63  5638.7 1656.61
  6059.4 1657.78  6116.9 1660.81  6137.7 1666.34  6149.6  1673.4  6163.1 1675.09
  6200.1 1668.02  6250.8 1669.46  6283.3 1675.25  6304.1 1682.21  6424.6 1693.09
#Mann= 12 ,-1 , 0
  4494.7     .16       0  4530.6      .1       0  4573.2     .16       0
  4667.1      .1       0  4995.6     .07       0  5001.6      .1       0
    5052     .16       0  5162.2      .1       0  5329.3     .05       0
  5638.7      .1       0  6059.4     .05       0  6163.1      .1       0
Bank Sta=4958,5038.9
XS Rating Curve= 0 ,0
Exp/Cntr=0.3,0.1

Type RM Length L Ch R = 1 ,1516    ,642,642,642
BEGIN DESCRIPTION:
Mapping XS 954e036c
END DESCRIPTION:
XS GIS Cut Line= 4
      2782873.38     10023773.67       2783335.2     10024436.89
      2783724.09     10024072.31      2784560.93     10023714.66
#Sta/Elev= 30
  4166.2 1659.16  4206.1 1656.44  4465.9 1655.01  4672.9 1652.87  4744.5  1644.1
  4761.9 1644.96    4816 1641.32  4845.7 1643.34  4866.6 1639.98  4881.5 1642.87
  4902.4 1639.64    4953 1642.36  4953.5 1642.13  4958.4 1639.93  4992.2 1637.24
  4997.2 1636.69  4999.9 1636.19  5003.2 1636.69  5035.3 1642.82  5097.2 1645.57
  5188.7 1649.51  5389.5 1648.48  5883.8 1655.26  6015.7 1655.51  6179.6 1661.94
  6240.8 1675.18  6256.6 1670.83    6303 1668.85  6355.6 1681.25  6417.5 1687.68
#Mann= 14 ,-1 , 0
  4166.2     .16       0  4206.1      .1       0  4465.9     .16       0
  4761.9      .1       0  4953.5     .16       0  4958.4      .1       0
  4992.2     .16       0  4997.2     .07       0  5003.2     .16       0
  5097.2      .1       0  5188.7     .05       0  5883.8      .1       0
  6015.7     .05       0  6256.6      .1       0
Bank Sta=4953,5035.3
XS Rating Curve= 0 ,0
Exp/Cntr=0.3,0.1

Type RM Length L Ch R = 1 ,874     ,361,361,361
BEGIN DESCRIPTION:
Mapping XS 07e3b720
END DESCRIPTION:
XS GIS Cut Line= 4
       2782824.8     10023721.64       2783623.4     10024888.28
      2783731.04     10024902.17      2784609.55     10024245.89
#Sta/Elev= 30
  3366.9 1662.59    3426 1660.11  3472.1 1656.77  3754.5 1654.79  4002.2  1649.6
  4054.5 1648.84  4090.4 1644.09  4105.3 1647.24  4126.3 1644.52    4222 1645.21
  4238.9 1644.49  4335.5 1645.02  4356.5 1642.42  4371.4 1645.24  4392.4 1642.59
  4407.3 1645.92  4493.5 1647.29  4658.5 1645.83  4760.9    1649  4899.9 1640.46
  4940.6    1634  4943.4  1633.5  4946.6    1634  5043.7    1637  5063.1 1640.82
  5085.7 1645.66  5443.4 1656.23  5815.5 1663.89  5960.1 1673.79  5985.8 1672.74
#Mann= 15 ,-1 , 0
  3366.9      .1       0    3426     .16       0  3472.1      .1       0
  3754.5     .16       0  4002.2      .1       0    4222     .16       0
  4238.9      .1       0  4493.5     .16       0  4760.9      .1       0
  4940.6     .07       0  4946.6      .1       0  5063.1     .16       0
  5443.4      .1       0  5815.5     .05       0  5960.1      .1       0
Bank Sta=4899.9,5063.1
XS Rating Curve= 0 ,0
Exp/Cntr=0.3,0.1

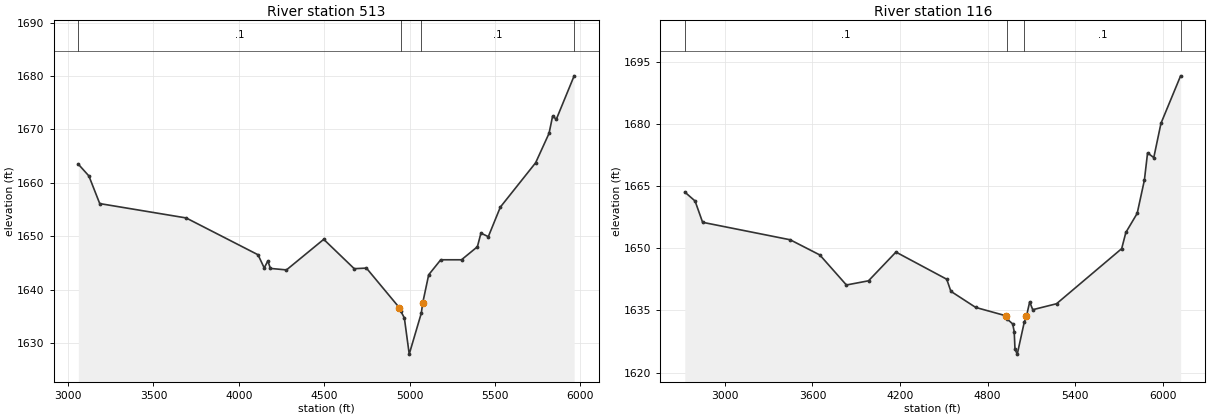
Type RM Length L Ch R = 1 ,513     ,397,397,397
BEGIN DESCRIPTION:
Mapping XS bb6abb80
END DESCRIPTION:
XS GIS Cut Line= 4
      2782797.01     10023721.62      2783595.62     10024971.62
      2783908.12     10025193.84      2784720.15     10024548.38
#Sta/Elev= 30
  3059.8 1663.49  3121.6 1661.29  3185.1 1656.11  3691.2 1653.42  4112.2 1646.52
  4148.6 1644.05  4169.7 1645.36    4185 1643.96  4278.9 1643.68  4497.1 1649.41
  4675.8 1643.91  4747.2 1644.02  4940.5 1636.58  4948.5 1635.95  4969.3 1634.69
  4997.9  1627.9  5068.6 1635.57  5076.7 1637.46  5111.9 1642.77  5182.5 1645.58
  5304.1 1645.58  5397.1 1648.02  5417.9 1650.57  5461.1 1649.91  5531.6 1655.45
  5738.3 1663.76  5816.8 1669.27  5837.6 1672.48  5859.6 1671.92  5963.9 1680.05
#Mann= 4 ,-1 , 0
  3059.8      .1       0  4948.5     .05       0  5068.6      .1       0
  5963.9      .1       0
Bank Sta=4940.5,5076.7
XS Rating Curve= 0 ,0
Exp/Cntr=0.3,0.1

Type RM Length L Ch R = 1 ,116     ,0,0,0
BEGIN DESCRIPTION:
HOPFS CREEK 1.0
END DESCRIPTION:
XS GIS Cut Line= 5
      2782776.44     10023728.09      2783564.66     10024964.24
      2784137.58     10025460.77      2784252.16     10025422.57
       2784953.1     10024638.35
#Sta/Elev= 30
  2725.6 1663.61    2796 1661.44  2847.6  1656.3  3447.6 1652.08  3650.7 1648.41
  3832.7 1641.16  3984.2 1642.17  4172.1 1649.11    4520 1642.55  4548.5 1639.63
  4718.5 1635.74  4924.5 1633.73  4931.3 1633.02  4971.8 1631.76  4982.4 1629.88
  4987.7 1625.63  5003.2 1624.46    5051 1632.15    5066 1633.58  5088.3 1637.08
  5109.3 1635.19  5272.3 1636.63  5718.7 1649.94  5747.1 1653.84  5824.8 1658.46
  5874.2 1666.49  5895.9 1673.07  5938.5 1671.93  5987.8 1680.21  6122.4 1691.68
#Mann= 4 ,-1 , 0
  2725.6      .1       0  4931.3     .05       0    5051      .1       0
  6122.4      .1       0
Bank Sta=4924.5,5066
XS Rating Curve= 0 ,0
Exp/Cntr=0.3,0.1

Chan Stop Cuts=-1
Use User Specified Reach Order=0
Composite Channel Slope=5