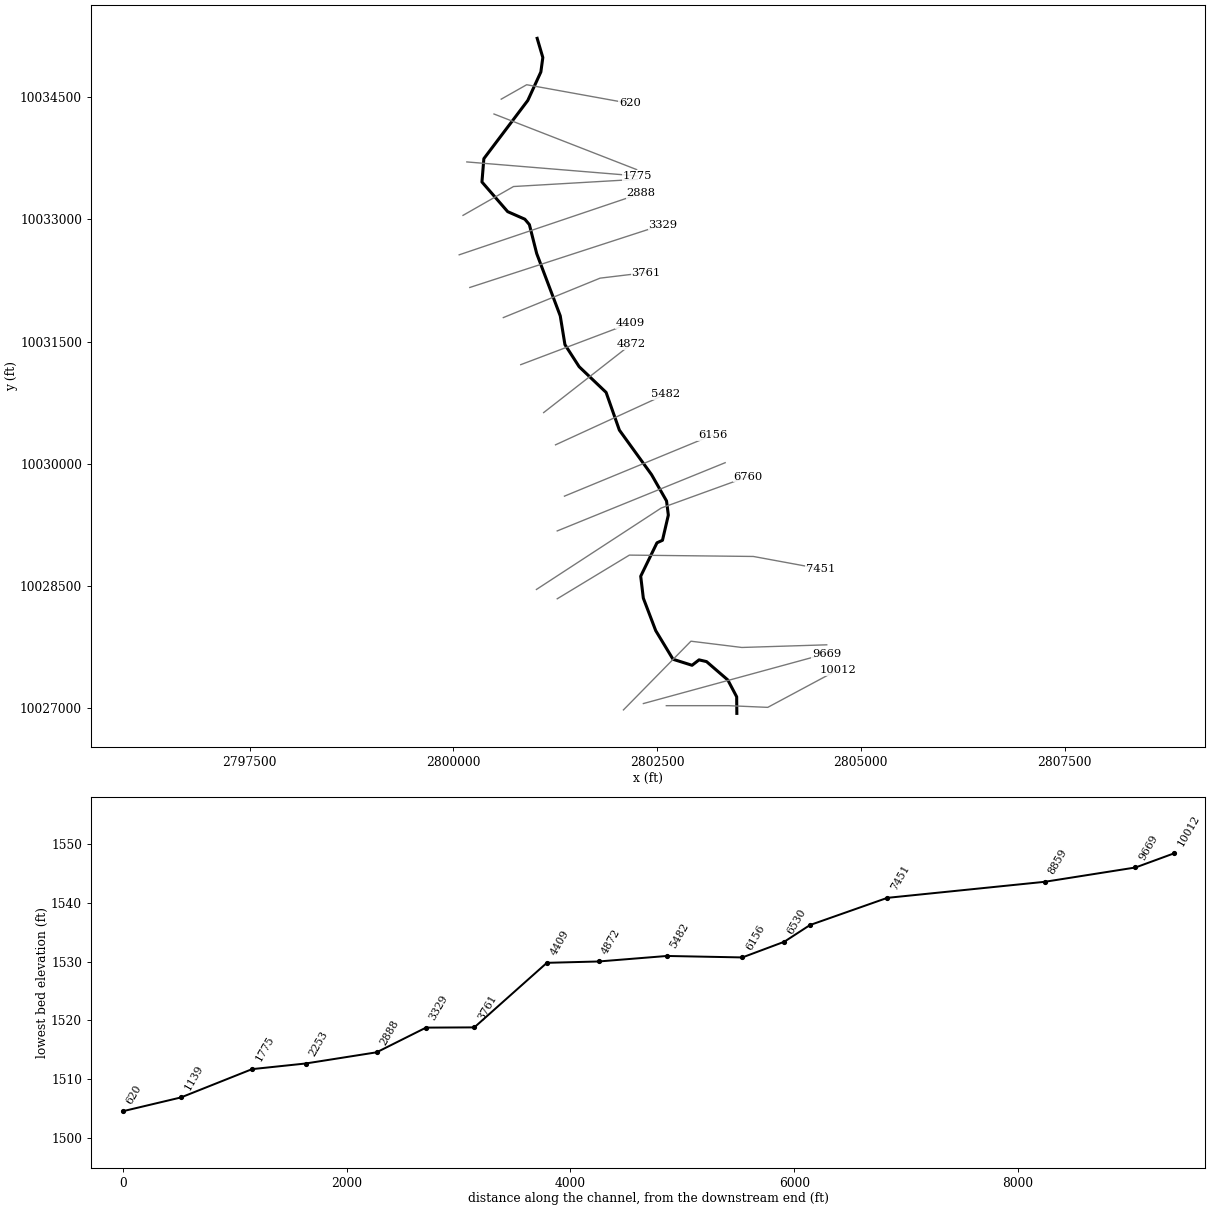
--- HUNTERS CREEK.prj (project) ---

Proj Title=HUNTERS CREEK Base Level Engineering
Current Plan=p01
Default Exp/Contr=0.3,0.1
English Units
Geom File=g01
Flow File=f01
Plan File=p01
Y Axis Title=Elevation
X Axis Title(PF)=Main Channel Distance
X Axis Title(XS)=Station
BEGIN DESCRIPTION:
HUNTERS CREEK
END DESCRIPTION:
DSS Export Rating Curves= 0
DSS Export Rating Curve Sorted= 0
DSS Export Volume Flow Curves= 0
DXF OffsetX= 0
DXF OffsetY= 0
DXF ScaleX= 1
DXF ScaleY= 10

--- HUNTERS CREEK.p01 (plan) ---

Plan Title=Multiple Run
Short Identifier=Multiple
Geom File=g01
Flow File=f01
Subcritical Flow
K Sum by GR= 0
Std Step Tol= 0.01
Critical Tol= 0.01
Num of Std Step Trials= 20
Max Error Tol= 0.3
Flow Tol Ratio= 0.001
Split Flow NTrial= 30
Split Flow Tol= 0.02
Split Flow Ratio= 0.02
Log Output Level= 0
Friction Slope Method= 1
Unsteady Friction Slope Method= 2
Unsteady Bridges Friction Slope Method= 1
Parabolic Critical Depth
Global Vel Dist=  1 , 1 , 1
Global Log Level= 0
CheckData=True
Encroach Param= -1, 0, 0, 0
BEGIN DESCRIPTION:
Multiple Run
END DESCRIPTION:

--- HUNTERS CREEK.f01 (steady flow) ---

Flow Title=Multiple
Program Version=4.10
Number of Profiles= 7
Profile Names=10-year,25-year,50-year,1pct_min,100-year,1pct_plu,500-year
River Rch & RM=HUNTERS CREEK,Reach-1         ,10012
    5882    9200   12288   11942   16150   21841   28026
River Rch & RM=HUNTERS CREEK,Reach-1         ,6530
    5850    9122   12157   11787   15941   21558   27533
Boundary for River Rch & Prof#=HUNTERS CREEK,Reach-1         , 1
Up Type= 0
Dn Type= 3
Dn Slope=0.00447
Boundary for River Rch & Prof#=HUNTERS CREEK,Reach-1         , 2
Up Type= 0
Dn Type= 3
Dn Slope=0.00447
Boundary for River Rch & Prof#=HUNTERS CREEK,Reach-1         , 3
Up Type= 0
Dn Type= 3
Dn Slope=0.00447
Boundary for River Rch & Prof#=HUNTERS CREEK,Reach-1         , 4
Up Type= 0
Dn Type= 3
Dn Slope=0.00447
Boundary for River Rch & Prof#=HUNTERS CREEK,Reach-1         , 5
Up Type= 0
Dn Type= 3
Dn Slope=0.00447
Boundary for River Rch & Prof#=HUNTERS CREEK,Reach-1         , 6
Up Type= 0
Dn Type= 3
Dn Slope=0.00447
Boundary for River Rch & Prof#=HUNTERS CREEK,Reach-1         , 7
Up Type= 0
Dn Type= 3
Dn Slope=0.00447
DSS Import GetInterval= 0
DSS Import GetPeak= 0
DSS Import FillOption= 0

--- HUNTERS CREEK.g01 (geometry) ---

Geom Title=Existing Conditions
Program Version=4.10

River Reach=HUNTERS CREEK   ,Reach-1
Reach XY= 30
      2803478.68     10026934.32      2803476.62     10027137.94
       2803367.7     10027344.65      2803106.87     10027570.02
      2803014.78     10027591.41        2802929.      10027524.9
      2802695.54     10027598.71      2802482.92     10027950.86
      2802331.01     10028349.49        2802299.     10028618.44
      2802498.64     10029029.04      2802566.06     10029059.87
        2802638.     10029368.96      2802615.98      10029542.7
      2802432.23     10029865.55      2802037.03     10030412.79
      2801874.29     10030875.92       2801543.6     10031191.25
      2801369.08      10031462.4      2801311.63     10031815.66
      2801022.69     10032580.77      2800932.88     10032936.49
        2800877.     10033002.82      2800666.38     10033095.51
       2800350.7     10033459.76      2800374.16     10033746.09
       2800913.4     10034461.12      2801073.76     10034810.97
       2801097.8     10034988.35      2801028.47     10035223.73

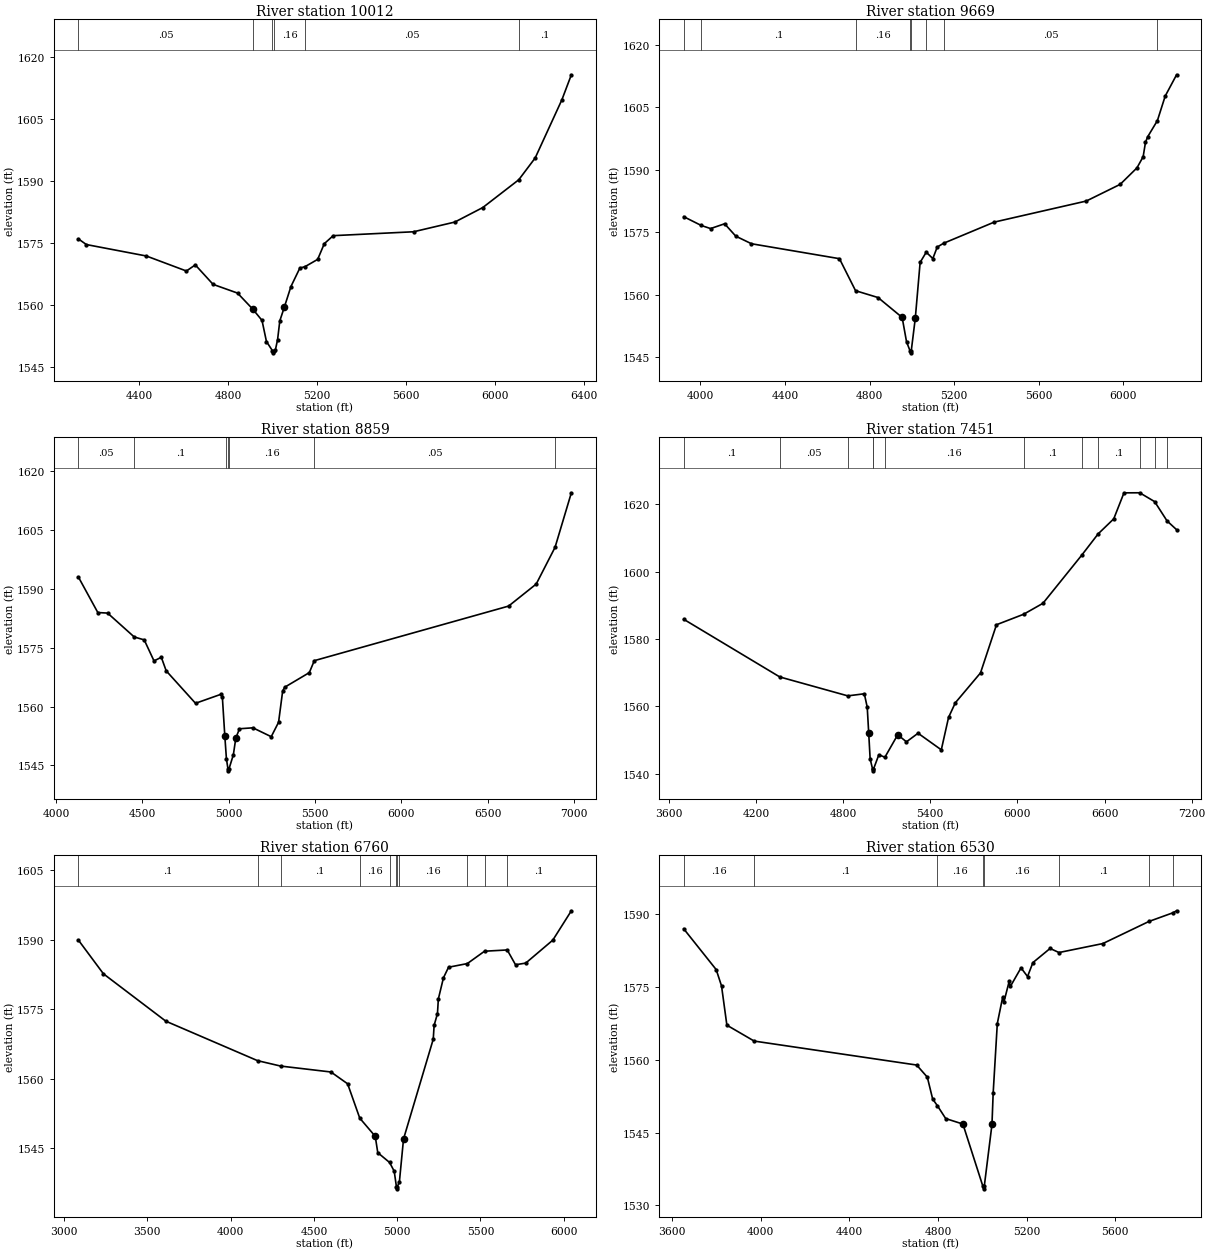
Type RM Length L Ch R = 1 ,10012   ,343,343,343
BEGIN DESCRIPTION:
Mapping XS 42e0bab3
END DESCRIPTION:
XS GIS Cut Line= 4
       2802613.2     10027028.92       2803378.8     10027028.92
      2803857.96     10027008.09      2804714.01     10027467.18
#Sta/Elev= 30
  4126.7 1576.02    4162 1574.67    4432  1571.9    4612 1568.27    4652 1569.75
    4732 1565.04    4842 1562.93  4910.4 1559.05    4952 1556.33    4972 1551.22
  4999.1 1548.98  5001.8 1548.48  5005.1 1548.98  5012.1 1549.16  5022.1 1551.68
  5032.1 1556.22  5052.1 1559.47  5082.1 1564.51  5122.1 1568.97    5146 1569.34
  5202.3 1571.08  5232.3 1574.89  5272.3 1576.82  5633.5 1577.76  5819.2 1580.11
    5945 1583.62  6106.8 1590.34  6180.6 1595.61  6300.8 1609.69  6343.3 1615.73
#Mann= 6 ,-1 , 0
  4126.7     .05       0  4910.4     .16       0  4999.1     .07       0
  5005.1     .16       0    5146     .05       0  6106.8      .1       0
Bank Sta=4910.4,5052.1
XS Rating Curve= 0 ,0
Exp/Cntr=0.3,0.1

Type RM Length L Ch R = 1 ,9669    ,810,810,810
BEGIN DESCRIPTION:
Mapping XS 614beec4
END DESCRIPTION:
XS GIS Cut Line= 2
      2802331.88     10027054.96      2804580.41     10027669.14
#Sta/Elev= 30
    3921 1578.73  4004.1 1576.62  4048.1 1575.88  4114.4 1577.03  4167.2 1574.06
  4241.5 1572.24  4657.5 1568.66  4733.7 1560.98  4840.1 1559.34  4954.1 1554.57
  4974.8 1548.74  4991.2 1546.58  4993.9 1546.08  4997.2 1546.58  5016.3 1554.41
  5039.1 1567.77    5068 1570.21  5099.2 1568.69    5120 1571.45  5150.6 1572.37
  5389.5 1577.43  5824.9 1582.48  5985.1 1586.48  6064.5 1590.43  6093.9 1593.12
  6104.8 1596.54  6115.1 1597.88  6161.3 1601.78  6198.1 1607.65  6251.9 1612.76
#Mann= 8 ,-1 , 0
    3921     .05       0  4004.1      .1       0  4733.7     .16       0
  4991.2     .07       0  4997.2     .16       0    5068      .1       0
  5150.6     .05       0  6161.3      .1       0
Bank Sta=4954.1,5016.3
XS Rating Curve= 0 ,0
Exp/Cntr=0.3,0.1

Type RM Length L Ch R = 1 ,8859    ,1408,1408,1408
BEGIN DESCRIPTION:
HUNTERS CREEK 16.0
END DESCRIPTION:
XS GIS Cut Line= 4
       2802087.1     10026976.81      2802915.25     10027820.59
      2803540.18     10027743.63      2804581.84     10027776.18
#Sta/Elev= 30
  4129.7 1592.92  4241.6 1583.93  4298.2 1583.79  4452.5 1577.71  4510.3 1576.97
  4566.9 1571.62  4609.3 1572.54  4637.6 1569.09  4807.4 1560.83  4955.8 1563.14
  4962.9 1562.35  4977.1 1552.46  4986.3 1546.72  4995.2 1544.14    4998 1543.64
  5001.2 1544.14  5026.5 1547.73  5040.7 1551.98    5062 1554.35  5139.7 1554.59
  5245.8 1552.33  5288.3    1556    5312 1563.94  5323.7 1564.92  5466.4 1568.64
  5495.2 1571.68  6620.3 1585.57  6780.3 1591.18  6889.4 1600.53  6983.8 1614.41
#Mann= 7 ,-1 , 0
  4129.7     .05       0  4452.5      .1       0  4986.3     .16       0
  4995.2     .07       0  5001.2     .16       0  5495.2     .05       0
  6889.4      .1       0
Bank Sta=4977.1,5040.7
XS Rating Curve= 0 ,0
Exp/Cntr=0.3,0.1

Type RM Length L Ch R = 1 ,7451    ,691,691,691
BEGIN DESCRIPTION:
HUNTERS CREEK 13.0
END DESCRIPTION:
XS GIS Cut Line= 4
      2801274.65     10028341.44      2802160.05     10028877.88
      2803681.24     10028861.25      2804504.67     10028709.56
#Sta/Elev= 30
  3702.1 1585.84  4363.6 1568.74  4831.9 1563.13  4945.8 1563.75  4965.8 1559.77
  4975.8 1552.24  4985.8 1544.45  5002.8  1541.4  5005.5  1540.9  5008.8  1541.4
  5045.8 1545.67  5087.4 1544.93  5175.8  1551.6  5235.8  1549.5  5315.8 1552.05
  5475.8 1547.13  5525.8 1556.74  5572.5 1561.08  5745.8 1569.94  5855.8 1584.22
  6042.8 1587.33  6175.8 1590.58  6441.6 1604.78    6556 1611.17  6663.3 1615.62
  6733.7 1623.33  6842.1 1623.35  6945.1 1620.72  7030.3 1615.01  7095.9 1612.41
#Mann= 12 ,-1 , 0
  3702.1      .1       0  4363.6     .05       0  4831.9      .1       0
  5002.8     .07       0  5008.8      .1       0  5087.4     .16       0
  6042.8      .1       0  6441.6     .16       0    6556      .1       0
  6842.1     .16       0  6945.1      .1       0  7030.3     .16       0
Bank Sta=4975.8,5175.8
XS Rating Curve= 0 ,0
Exp/Cntr=0.3,0.1

Type RM Length L Ch R = 1 ,6760    ,230,230,230
BEGIN DESCRIPTION:
HUNTERS CREEK 12.0
END DESCRIPTION:
XS GIS Cut Line= 3
       2801019.4     10028455.99      2802550.67     10029456.01
      2803613.14     10029841.41
#Sta/Elev= 30
  3086.8 1589.94  3236.5 1582.69  3611.2 1572.46  4161.6 1563.94  4300.3 1562.77
  4602.5 1561.49  4702.6 1558.94  4775.4 1551.53  4868.5  1547.6  4883.6 1544.07
  4954.7 1541.95  4982.4 1540.06  4995.4 1536.76  4998.2 1536.26  5001.4 1536.76
  5013.3 1537.72  5038.3 1547.03  5216.7 1568.57    5222 1571.57    5242 1574.09
  5247.3 1577.25    5278 1581.83  5308.6 1584.11  5421.4  1584.9  5524.7 1587.57
  5660.9 1587.84  5710.6 1584.65  5771.9    1585  5934.5 1589.96  6045.9  1596.3
#Mann= 11 ,-1 , 0
  3086.8      .1       0  4161.6     .05       0  4300.3      .1       0
  4775.4     .16       0  4954.7     .05       0  4995.4    .035       0
  5001.4     .05       0  5013.3     .16       0  5421.4      .1       0
  5524.7     .16       0  5660.9      .1       0
Bank Sta=4868.5,5038.3
XS Rating Curve= 0 ,0
Exp/Cntr=0.3,0.1

Type RM Length L Ch R = 1 ,6530    ,374,374,374
BEGIN DESCRIPTION:
HUNTERS CREEK 11.0
END DESCRIPTION:
XS GIS Cut Line= 2
       2801274.6     10029174.74      2803335.29     10030012.55
#Sta/Elev= 30
  3652.5 1587.03  3799.1 1578.62  3823.2 1575.25  3847.3 1567.16  3970.6 1563.88
  4703.9 1558.94    4752 1556.44  4776.1 1551.93  4797.7 1550.54    4835  1547.9
  4912.6 1546.77    5003 1533.91  5005.8 1533.41    5009 1533.91  5043.8 1546.68
  5049.2 1553.14  5067.9  1567.5  5091.9 1572.88  5097.3 1571.85  5121.4 1576.19
  5126.8 1575.14  5174.9 1578.98  5204.4 1577.19  5228.5 1580.06  5306.1 1582.98
  5346.3 1582.14  5544.3 1583.99  5752.4 1588.55  5860.8 1590.34    5877 1590.75
#Mann= 8 ,-1 , 0
  3652.5     .16       0  3970.6      .1       0  4797.7     .16       0
    5003     .07       0    5009     .16       0  5346.3      .1       0
  5752.4     .05       0  5860.8      .1       0
Bank Sta=4912.6,5043.8
XS Rating Curve= 0 ,0
Exp/Cntr=0.3,0.1

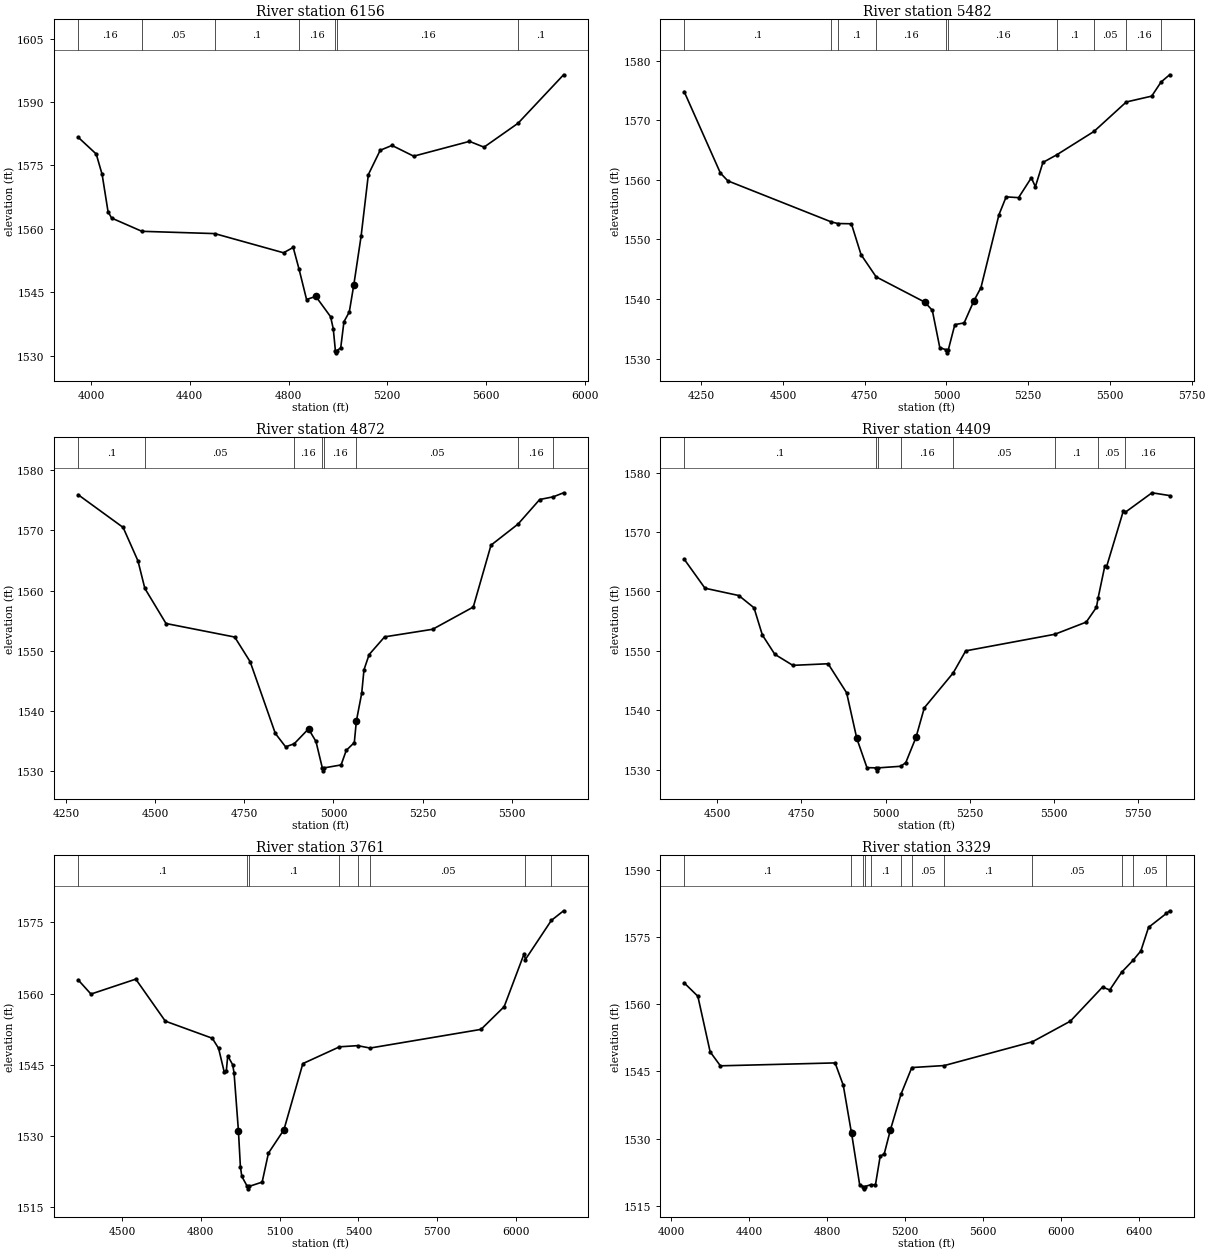
Type RM Length L Ch R = 1 ,6156    ,674,674,674
BEGIN DESCRIPTION:
HUNTERS CREEK 10.0
END DESCRIPTION:
XS GIS Cut Line= 2
      2801363.13     10029601.83      2803180.88     10030351.84
#Sta/Elev= 30
  3947.8 1581.68  4021.1 1577.71    4045 1572.89    4069 1564.08  4083.4 1562.58
    4206 1559.45    4501 1558.91  4779.9 1554.38    4819 1555.64  4842.6 1550.53
  4873.1 1543.34  4910.4 1544.08  4970.4 1539.28  4981.3 1536.41  4989.9 1531.24
  4992.7 1530.74  4995.9 1531.24  5011.5 1531.93  5024.5 1538.08  5046.2  1540.4
  5064.7 1546.88  5094.1 1558.33  5123.4 1572.85  5171.3 1578.59  5219.1 1579.74
  5307.1  1577.2    5533  1580.7  5591.9 1579.33  5729.6 1584.97  5914.2 1596.43
#Mann= 7 ,-1 , 0
  3947.8     .16       0    4206     .05       0    4501      .1       0
  4842.6     .16       0  4989.9     .07       0  4995.9     .16       0
  5729.6      .1       0
Bank Sta=4910.4,5064.7
XS Rating Curve= 0 ,0
Exp/Cntr=0.3,0.1

Type RM Length L Ch R = 1 ,5482    ,610,610,610
BEGIN DESCRIPTION:
HUNTERS CREEK 9.0
END DESCRIPTION:
XS GIS Cut Line= 2
      2801253.79     10030232.05      2802602.72     10030851.83
#Sta/Elev= 30
  4198.1 1574.79  4308.9 1561.13  4331.8 1559.82  4648.1 1552.94  4668.2 1552.67
  4709.5 1552.63    4739 1547.45  4785.1 1543.73  4933.9 1539.49  4956.9 1538.12
  4979.8 1531.87  4999.8 1531.49  5002.6 1530.99  5005.8 1531.49  5025.8 1535.72
  5054.3 1536.01  5083.6 1539.66  5105.7 1541.93  5160.7 1554.15  5182.7 1557.14
  5220.7 1557.01  5259.7 1560.34  5272.1 1558.84  5295.1 1562.91  5337.1 1564.18
  5451.3 1568.11  5550.1 1573.05  5627.8 1574.03  5656.5  1576.4  5682.6 1577.61
#Mann= 10 ,-1 , 0
  4198.1      .1       0  4648.1     .16       0  4668.2      .1       0
  4785.1     .16       0  4999.8     .07       0  5005.8     .16       0
  5337.1      .1       0  5451.3     .05       0  5550.1     .16       0
  5656.5     .05       0
Bank Sta=4933.9,5083.6
XS Rating Curve= 0 ,0
Exp/Cntr=0.3,0.1

Type RM Length L Ch R = 1 ,4872    ,463,463,463
BEGIN DESCRIPTION:
HUNTERS CREEK 8.0
END DESCRIPTION:
XS GIS Cut Line= 2
      2801107.97     10030627.89      2802180.87     10031466.42
#Sta/Elev= 30
    4284 1575.95  4410.2 1570.51  4451.9 1564.94  4471.1 1560.38  4530.5 1554.54
  4723.2 1552.29  4766.6 1548.18  4837.1 1536.27    4866 1534.04  4890.1 1534.55
  4930.2 1537.02  4951.1 1534.94  4968.9 1530.55  4971.6 1530.05  4974.9 1530.55
  5021.6 1531.03  5036.1 1533.45  5058.7 1534.75  5064.4 1538.31  5079.5 1542.97
  5085.8 1546.85  5100.3 1549.38  5143.7 1552.32  5278.4 1553.58  5392.4 1557.28
  5442.1 1567.56    5518 1571.07  5578.7 1575.15  5616.8  1575.6  5645.7 1576.27
#Mann= 8 ,-1 , 0
    4284      .1       0  4471.1     .05       0  4890.1     .16       0
  4968.9     .07       0  4974.9     .16       0  5064.4     .05       0
    5518     .16       0  5616.8     .05       0
Bank Sta=4930.2,5064.4
XS Rating Curve= 0 ,0
Exp/Cntr=0.3,0.1

Type RM Length L Ch R = 1 ,4409    ,648,648,648
BEGIN DESCRIPTION:
HUNTERS CREEK 7.0
END DESCRIPTION:
XS GIS Cut Line= 2
      2800826.74     10031216.43      2802174.58     10031726.43
#Sta/Elev= 30
  4401.8 1565.44  4463.6 1560.55    4564 1559.32  4609.1 1557.26  4633.9 1552.68
  4670.9 1549.43  4724.4 1547.57  4829.1 1547.84  4884.1 1542.95  4914.2 1535.29
  4944.4 1530.36  4971.6 1530.32  4974.3 1529.82  4977.6 1530.32  5045.2 1530.59
  5059.7 1531.21  5089.9 1535.44  5114.7 1540.43  5200.5  1546.3  5237.6 1550.01
  5502.1  1552.8  5595.4 1554.85  5625.6 1557.33  5630.7 1558.93  5650.4 1564.26
  5655.8 1564.18  5705.4 1573.53  5711.7 1573.35  5790.6 1576.61  5842.9 1576.14
#Mann= 8 ,-1 , 0
  4401.8      .1       0  4971.6     .07       0  4977.6      .1       0
  5045.2     .16       0  5200.5     .05       0  5502.1      .1       0
  5630.7     .05       0  5711.7     .16       0
Bank Sta=4914.2,5089.9
XS Rating Curve= 0 ,0
Exp/Cntr=0.3,0.1

Type RM Length L Ch R = 1 ,3761    ,432,432,432
BEGIN DESCRIPTION:
HUNTERS CREEK 6.0
END DESCRIPTION:
XS GIS Cut Line= 3
      2800613.17     10031794.55      2801800.67     10032278.92
      2802363.13     10032346.63
#Sta/Elev= 30
  4332.6  1562.9  4381.5  1559.9  4552.2 1563.05  4664.6 1554.19  4843.6 1550.58
  4867.5 1548.46  4889.1 1543.45  4897.1 1543.74  4902.5 1546.88  4921.1    1545
  4926.5 1543.29  4943.1 1531.09  4950.6 1523.52    4956 1521.44    4977 1519.31
  4979.8 1518.81    4983 1519.31  5033.5 1520.23  5057.5 1526.35  5116.4 1531.27
  5188.5 1545.23  5328.1 1548.77  5397.3 1549.02  5444.5 1548.51  5867.1 1552.45
  5955.3 1557.24  6031.4 1568.42  6036.1 1567.19    6135 1575.44  6181.6 1577.47
#Mann= 8 ,-1 , 0
  4332.6      .1       0    4977     .07       0    4983      .1       0
  5328.1     .05       0  5397.3      .1       0  5444.5     .05       0
  6036.1      .1       0    6135     .16       0
Bank Sta=4943.1,5116.4
XS Rating Curve= 0 ,0
Exp/Cntr=0.3,0.1

Type RM Length L Ch R = 1 ,3329    ,441,441,441
BEGIN DESCRIPTION:
HUNTERS CREEK 5.0
END DESCRIPTION:
XS GIS Cut Line= 2
      2800201.69     10032164.34      2802571.48     10032935.17
#Sta/Elev= 30
  4067.2 1564.76  4137.4 1561.78  4200.5 1549.37  4253.1 1546.24    4842 1546.89
    4884 1541.89  4924.6  1531.6  4926.7 1531.15  4968.2 1519.64  4987.5 1519.27
  4990.3 1518.77  4993.5 1519.27  5024.3 1519.68  5049.2 1519.69  5073.3 1526.01
  5094.3 1526.59  5125.9 1531.94  5180.1 1539.89  5235.7 1545.85  5402.6  1546.3
    5855 1551.61  6049.7 1556.21  6214.7 1563.82  6251.9 1563.18  6312.5 1567.12
  6370.8 1569.76  6411.6  1571.9  6450.9 1577.15  6542.9 1580.28  6559.2 1580.86
#Mann= 12 ,-1 , 0
  4067.2      .1       0  4924.6     .16       0  4987.5     .07       0
  4993.5     .16       0  5024.3      .1       0  5180.1     .16       0
  5235.7     .05       0  5402.6      .1       0    5855     .05       0
  6312.5      .1       0  6370.8     .05       0  6542.9      .1       0
Bank Sta=4926.7,5125.9
XS Rating Curve= 0 ,0
Exp/Cntr=0.3,0.1

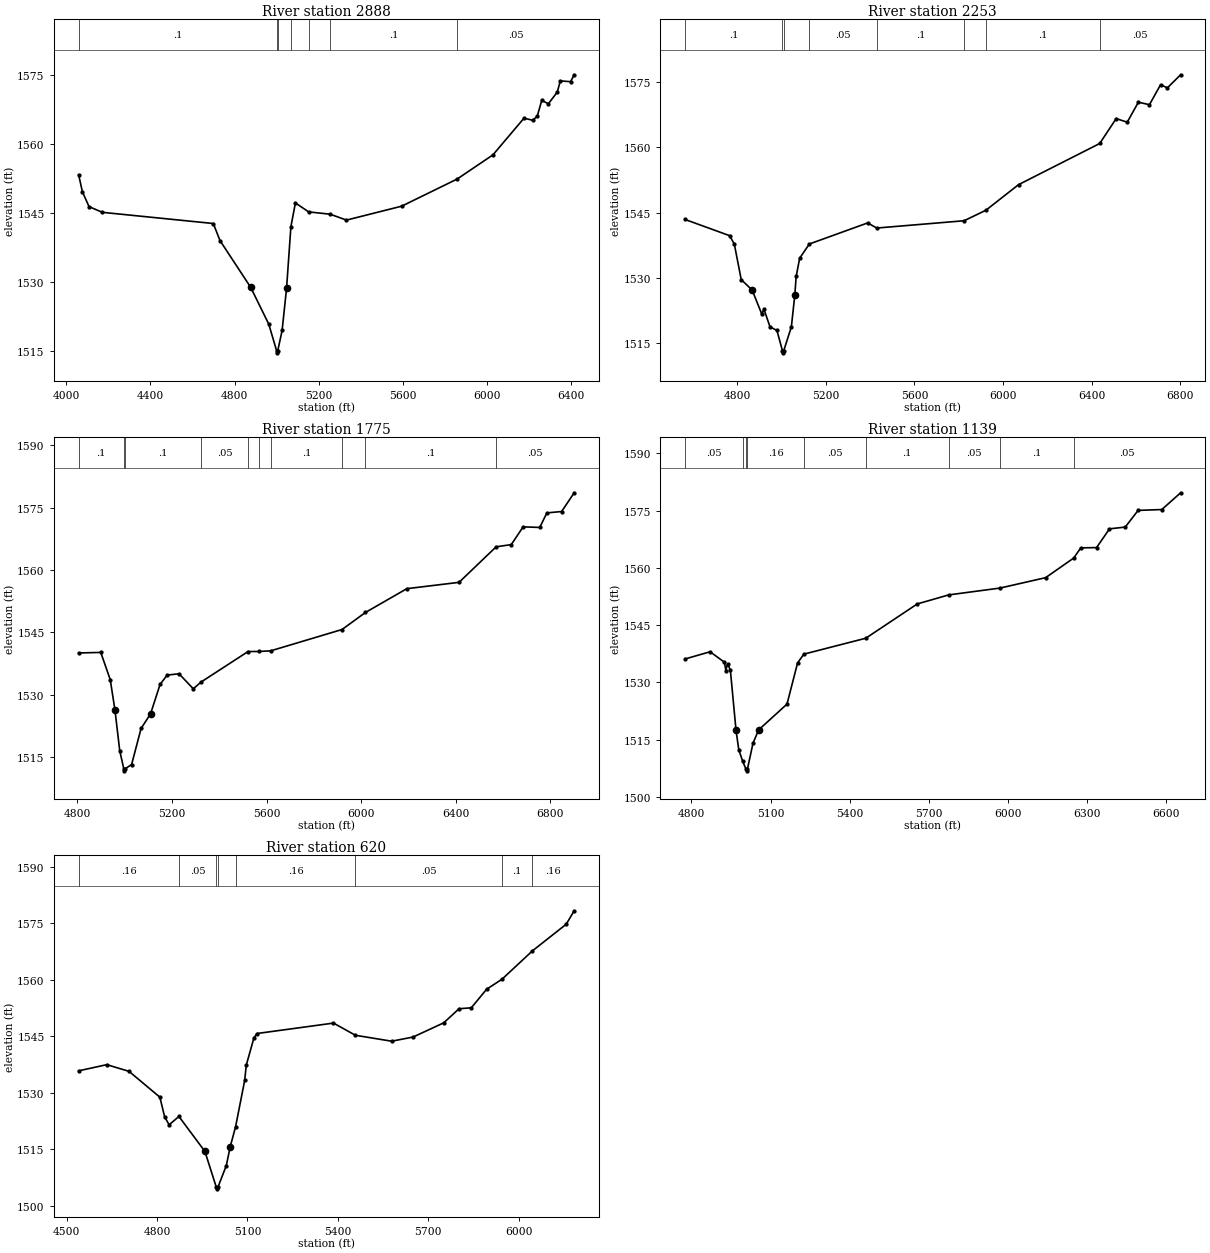
Type RM Length L Ch R = 1 ,2888    ,635,635,635
BEGIN DESCRIPTION:
HUNTERS CREEK 4.0
END DESCRIPTION:
XS GIS Cut Line= 2
      2800071.54     10032565.39      2802304.63     10033320.17
#Sta/Elev= 30
  4058.2 1553.28  4076.1 1549.59  4107.7 1546.35  4171.1 1545.11  4698.9 1542.68
  4730.5 1538.98  4876.8 1528.79  4962.8 1520.78  4999.6 1515.06  5002.4 1514.56
  5005.6 1515.06  5026.1 1519.42  5047.2 1528.55    5068 1542.02  5089.4 1547.15
  5152.3 1545.21    5255  1544.7  5332.2 1543.42  5594.9 1546.45  5858.4 1552.34
  6028.9  1557.6  6176.7 1565.58  6218.6 1565.13    6240 1566.04  6261.1 1569.45
  6292.8 1568.72    6335 1571.26  6349.6 1573.69  6398.3 1573.52  6415.4 1575.02
#Mann= 7 ,-1 , 0
  4058.2      .1       0  4999.6     .07       0  5005.6      .1       0
    5068     .16       0  5152.3     .05       0    5255      .1       0
  5858.4     .05       0
Bank Sta=4876.8,5047.2
XS Rating Curve= 0 ,0
Exp/Cntr=0.3,0.1

Type RM Length L Ch R = 1 ,2253    ,478,478,478
BEGIN DESCRIPTION:
HUNTERS CREEK 3.0
END DESCRIPTION:
XS GIS Cut Line= 3
      2800118.41     10033049.78      2800738.17     10033403.92
      2802258.99     10033492.47
#Sta/Elev= 30
  4564.8 1543.39  4765.3 1539.67  4786.9 1537.75  4818.2 1529.53  4867.6 1527.12
  4910.7 1521.62  4920.8 1522.69  4948.2 1518.64  4979.5  1517.8  5004.2 1513.15
    5007 1512.65  5010.2 1513.15  5044.6 1518.65  5060.1 1525.97  5066.2 1530.25
  5082.1 1534.47  5125.7 1537.74  5389.1  1542.6    5430 1541.42  5824.3  1543.1
  5922.8 1545.52  6070.2 1551.42  6436.7 1560.91    6511 1566.65  6560.9 1565.82
  6611.2 1570.43  6661.2 1569.85  6711.3 1574.45  6742.1 1573.74    6802 1576.75
#Mann= 8 ,-1 , 0
  4564.8      .1       0  5004.2     .07       0  5010.2      .1       0
  5125.7     .05       0    5430      .1       0  5824.3     .05       0
  5922.8      .1       0  6436.7     .05       0
Bank Sta=4867.6,5060.1
XS Rating Curve= 0 ,0
Exp/Cntr=0.3,0.1

Type RM Length L Ch R = 1 ,1775    ,636,636,636
BEGIN DESCRIPTION:
Mapping XS 34b0dc83
END DESCRIPTION:
XS GIS Cut Line= 2
      2800165.25     10033706.01      2802253.59     10033534.15
#Sta/Elev= 30
  4805.4 1540.05    4899 1540.18  4939.1 1533.62  4959.1 1526.28  4979.2 1516.53
  4996.3 1512.19    4999 1511.69  5002.3 1512.19  5029.4 1513.21  5069.5 1521.89
  5109.6 1525.41  5149.8 1532.49  5179.9 1534.73    5230 1535.04  5290.2 1531.44
    5323 1533.05  5521.7 1540.39  5569.9 1540.41    5618 1540.57  5919.1 1545.69
  6018.4  1549.8  6193.3 1555.52    6414 1557.04  6570.8 1565.59  6634.8 1566.12
  6684.9 1570.39  6755.2 1570.25  6785.3 1573.75  6847.7 1574.08  6900.8 1578.59
#Mann= 10 ,-1 , 0
  4805.4      .1       0  4996.3     .07       0  5002.3      .1       0
    5323     .05       0  5521.7     .16       0  5569.9     .05       0
    5618      .1       0  5919.1     .05       0  6018.4      .1       0
  6570.8     .05       0
Bank Sta=4959.1,5109.6
XS Rating Curve= 0 ,0
Exp/Cntr=0.3,0.1

Type RM Length L Ch R = 1 ,1139    ,519,519,519
BEGIN DESCRIPTION:
HUNTERS CREEK 2.0
END DESCRIPTION:
XS GIS Cut Line= 2
      2800498.62     10034294.54      2802248.62     10033612.25
#Sta/Elev= 30
  4776.2 1536.15    4871 1538.03  4925.4 1535.28  4930.7 1533.09    4937 1534.91
  4947.8 1533.23  4969.2  1517.5  4979.7 1512.37  4994.5 1509.36  5006.6 1507.36
  5009.4 1506.86  5012.6 1507.36  5033.6  1514.1  5055.1 1517.59  5162.4 1524.33
  5202.6 1535.11  5226.4 1537.41  5460.9 1541.57  5656.2 1550.55  5774.9 1552.91
  5970.2 1554.71  6142.8 1557.43  6249.3 1562.57    6276 1565.23  6335.8  1565.3
  6384.8 1570.21  6444.5 1570.67  6493.3 1575.04  6583.1 1575.26  6654.5 1579.65
#Mann= 9 ,-1 , 0
  4776.2     .05       0  4994.5     .16       0  5006.6     .07       0
  5012.6     .16       0  5226.4     .05       0  5460.9      .1       0
  5774.9     .05       0  5970.2      .1       0  6249.3     .05       0
Bank Sta=4969.2,5055.1
XS Rating Curve= 0 ,0
Exp/Cntr=0.3,0.1

Type RM Length L Ch R = 1 ,620     ,0,0,0
BEGIN DESCRIPTION:
HUNTERS CREEK 1.0
END DESCRIPTION:
XS GIS Cut Line= 3
      2800587.15     10034476.86      2800899.63     10034653.92
      2802164.41     10034424.91
#Sta/Elev= 30
  4539.7 1535.85  4633.2 1537.49  4706.8 1535.72  4809.3 1528.86  4825.1 1523.63
  4840.1 1521.52  4872.5 1523.73  4958.7 1514.46  4996.3 1505.01  4999.1 1504.51
  5002.3 1505.01  5029.8 1510.69  5042.6 1515.64  5060.6 1521.02  5090.8 1533.32
  5096.1 1537.37  5121.3 1544.57  5131.4 1545.76  5385.5 1548.53  5458.4 1545.29
  5578.6 1543.72  5649.7 1544.83  5751.3  1548.6  5802.1 1552.34  5842.8 1552.59
  5893.6 1557.52  5944.8 1560.19  6045.9 1567.73  6157.8 1574.79  6184.2 1578.36
#Mann= 8 ,-1 , 0
  4539.7     .16       0  4872.5     .05       0  4996.3     .04       0
  5002.3     .05       0  5060.6     .16       0  5458.4     .05       0
  5944.8      .1       0  6045.9     .16       0
Bank Sta=4958.7,5042.6
XS Rating Curve= 0 ,0
Exp/Cntr=0.3,0.1

Chan Stop Cuts=-1
Use User Specified Reach Order=0
Composite Channel Slope=5