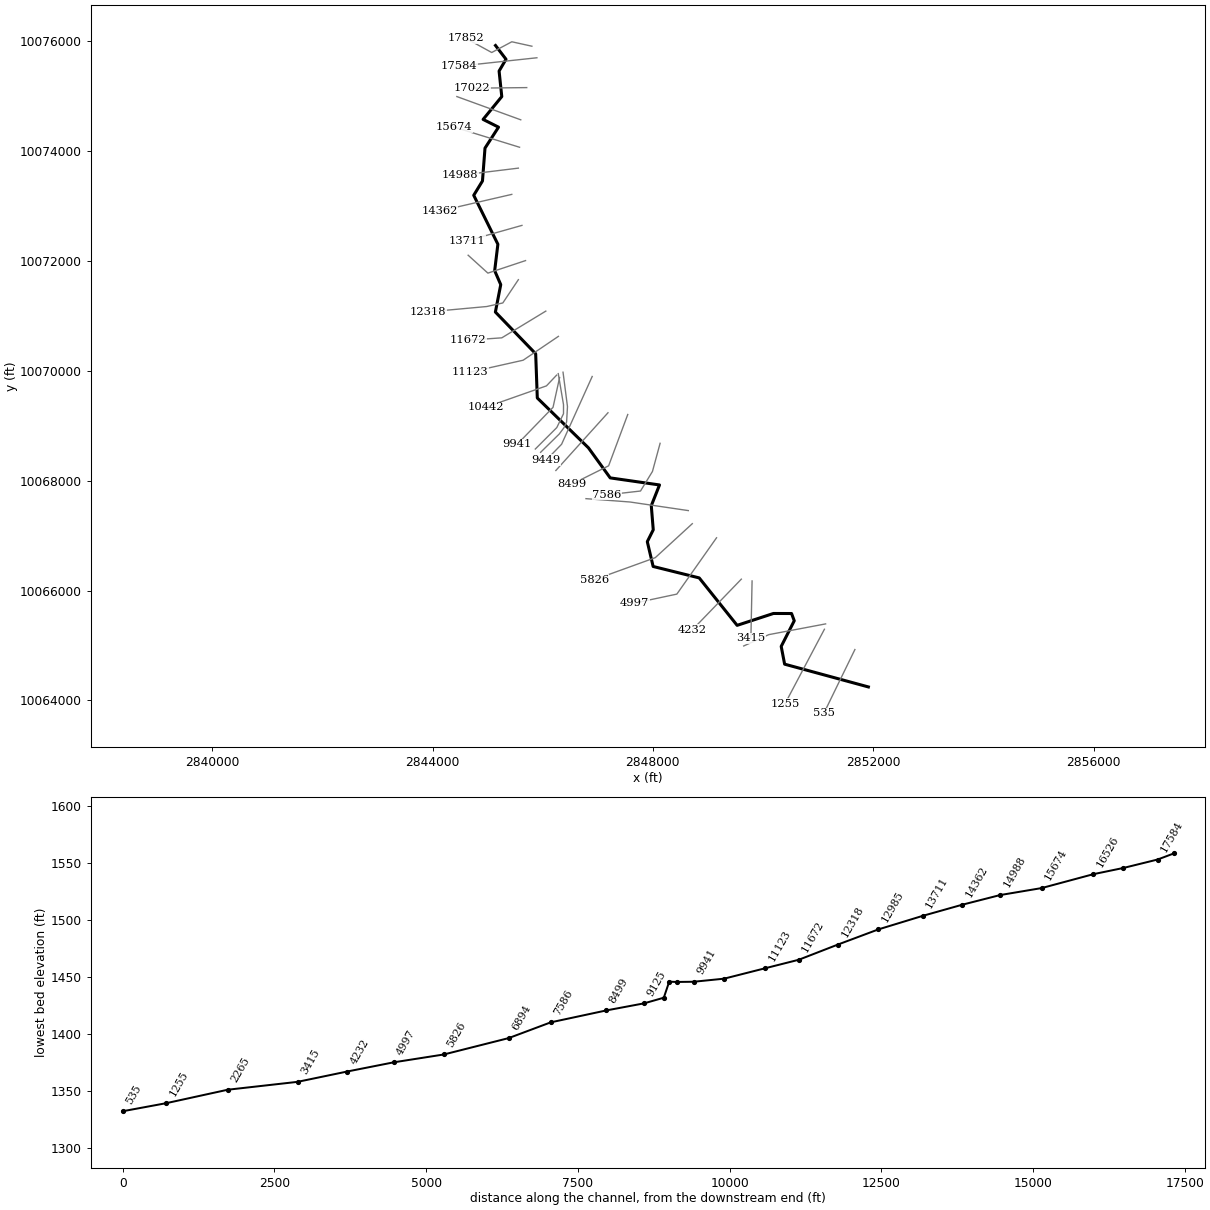
--- IRON ROCK CREEK.prj (project) ---

Proj Title=IRON ROCK CREEK Base Level Engineering
Current Plan=p01
Default Exp/Contr=0.3,0.1
English Units
Geom File=g01
Flow File=f01
Plan File=p01
BEGIN DESCRIPTION:
IRON ROCK CREEK
END DESCRIPTION:

--- IRON ROCK CREEK.p01 (plan) ---

Plan Title=Multiple Run
Short Identifier=Multiple
Geom File=g01
Flow File=f01
Subcritical Flow
K Sum by GR= 0
Std Step Tol= 0.01
Critical Tol= 0.01
Num of Std Step Trials= 20
Max Error Tol= 0.3
Flow Tol Ratio= 0.001
Split Flow NTrial= 30
Split Flow Tol= 0.02
Split Flow Ratio= 0.02
Log Output Level= 0
Friction Slope Method= 1
Unsteady Friction Slope Method= 2
Unsteady Bridges Friction Slope Method= 1
Parabolic Critical Depth
Global Vel Dist=  1 , 1 , 1
Global Log Level= 0
CheckData=True
Encroach Param= -1, 0, 0, 0
BEGIN DESCRIPTION:
Multiple Run
END DESCRIPTION:

--- IRON ROCK CREEK.f01 (steady flow) ---

Flow Title=Multiple
Number of Profiles=7
Profile Names=10-year,25-year,50-year,1pct_min,100-year,1pct_plu,500-year
River Rch & RM= IRON ROCK CREEK,Reach-1,17852
     929    1351    1720    1603    2168    2932    3457
River Rch & RM= IRON ROCK CREEK,Reach-1,12318
    1737    2617    3410    3247    4391    5938    7313
River Rch & RM= IRON ROCK CREEK,Reach-1,11123
    2116    3218    4218    4037    5460    7384    9192
River Rch & RM= IRON ROCK CREEK,Reach-1,8499
    2522    3850    5059    4850    6560    8871   11081
Boundary for River Rch & Prof#=IRON ROCK CREEK,Reach-1,1
Up Type=0
Dn Type=3
Dn Slope=0.005
Boundary for River Rch & Prof#=IRON ROCK CREEK,Reach-1,2
Up Type=0
Dn Type=3
Dn Slope=0.005
Boundary for River Rch & Prof#=IRON ROCK CREEK,Reach-1,3
Up Type=0
Dn Type=3
Dn Slope=0.005
Boundary for River Rch & Prof#=IRON ROCK CREEK,Reach-1,4
Up Type=0
Dn Type=3
Dn Slope=0.005
Boundary for River Rch & Prof#=IRON ROCK CREEK,Reach-1,5
Up Type=0
Dn Type=3
Dn Slope=0.005
Boundary for River Rch & Prof#=IRON ROCK CREEK,Reach-1,6
Up Type=0
Dn Type=3
Dn Slope=0.005
Boundary for River Rch & Prof#=IRON ROCK CREEK,Reach-1,7
Up Type=0
Dn Type=3
Dn Slope=0.005

--- IRON ROCK CREEK.g01 (geometry) ---

Geom Title=Existing Conditions

River Reach=IRON ROCK CREEK,Reach-1
Reach XY= 30
      2845144.01     10075913.24      2845334.29     10075663.06
      2845208.74     10075448.83      2845257.45     10074984.14
      2844918.65     10074568.84      2845198.27     10074428.02
      2844952.96     10074046.58      2844907.04     10073449.24
      2844748.47     10073188.79      2845186.69     10072298.15
      2845128.54     10071817.68      2845238.70     10071563.69
      2845141.48     10071065.02      2845872.94     10070306.16
      2845902.33     10069502.08      2846830.37     10068595.65
      2847225.65     10068048.54      2848120.73     10067919.99
      2847971.53     10067542.87      2848007.17     10067104.22
      2847898.98     10066888.44      2848005.05     10066437.33
      2848841.35     10066229.22      2849529.69     10065366.29
      2850188.31     10065582.26      2850517.75     10065581.49
      2850566.52     10065449.68      2850329.78     10064983.27
      2850391.79     10064660.34      2851912.37     10064246.02

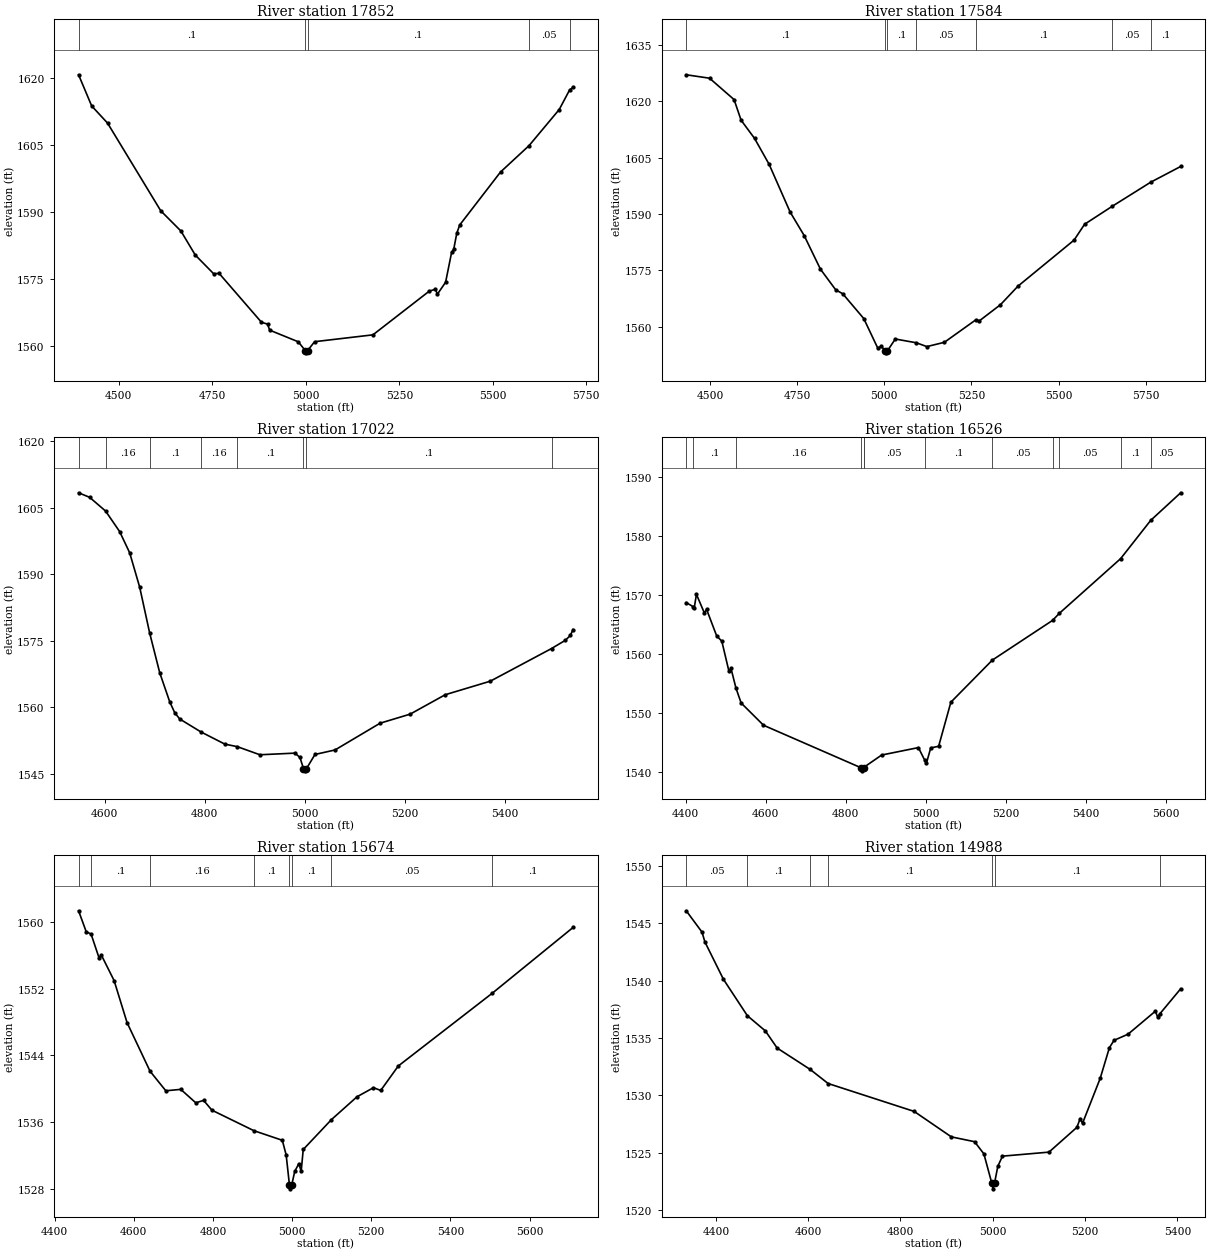
Type RM Length L Ch R = 1,17852,268,268,268
BEGIN DESCRIPTION:
IRON ROCK CREEK 40.0
END DESCRIPTION:
XS GIS Cut Line= 4
      2845804.03     10075900.37      2845439.47     10075981.09
      2845074.89     10075785.78      2844606.11     10076043.61
#Sta/Elev= 30
  4392.4 1620.61  4427.4 1613.65  4469.8 1609.82  4612.1 1590.22  4665.9 1585.71
  4704.4 1580.33  4753.2 1576.18  4768.3 1576.22  4881.4 1565.31  4897.6 1564.90
  4903.3 1563.55  4979.7 1560.95  4998.6 1558.98  5001.4 1558.48  5004.6 1558.98
  5023.5 1560.97  5179.4 1562.50  5330.1 1572.27  5346.2 1572.68  5351.9 1571.60
  5373.7 1574.26  5389.7 1580.91  5395.4 1581.62  5403.6 1585.22  5411.5 1587.06
  5520.5 1598.88  5596.7 1604.77  5677.5 1612.85  5705.2 1617.22  5714.4 1617.79
#Mann=5,-1,0
  4392.4     0.1       0  4998.6    0.07       0  5004.6     0.1       0
  5596.7    0.05       0  5705.2     0.1       0
Bank Sta=4998.6,5004.6
Exp/Cntr=0.3,0.1

Type RM Length L Ch R = 1,17584,562,562,562
BEGIN DESCRIPTION:
IRON ROCK CREEK 39.0
END DESCRIPTION:
XS GIS Cut Line= 2
      2845894.94     10075690.12      2844484.30     10075538.21
#Sta/Elev= 30
  4431.5 1627.04  4498.4 1626.13  4568.8 1620.44  4588.9 1614.97  4627.7 1610.10
  4669.3 1603.24  4729.7 1590.53  4769.9 1584.29  4816.6 1575.35  4860.4 1569.86
  4880.6 1568.81  4940.9 1562.22  4981.1 1554.35  4991.2 1554.84  5002.6 1553.60
  5005.3 1553.10  5008.6 1553.60  5031.4 1556.78  5092.0 1555.77  5121.9 1554.76
  5172.2 1555.90  5261.9 1561.84  5272.8 1561.62  5333.2 1565.90  5383.5 1570.84
  5544.4 1583.08  5574.5 1587.29  5653.7 1592.06  5764.2 1598.47  5850.3 1602.66
#Mann=7,-1,0
  4431.5     0.1       0  5002.6    0.07       0  5008.6     0.1       0
  5092.0    0.05       0  5261.9     0.1       0  5653.7    0.05       0
  5764.2     0.1       0
Bank Sta=5002.6,5008.6
Exp/Cntr=0.3,0.1

Type RM Length L Ch R = 1,17022,496,496,496
BEGIN DESCRIPTION:
IRON ROCK CREEK 38.0
END DESCRIPTION:
XS GIS Cut Line= 2
      2845710.41     10075147.58      2844723.27     10075136.74
#Sta/Elev= 30
  4548.2 1608.33  4570.2 1607.31  4602.1 1604.22  4630.2 1599.59  4650.2 1594.82
  4670.2 1587.07  4690.2 1576.71  4710.2 1567.80  4730.2 1561.25  4740.2 1558.79
  4750.2 1557.38  4792.7 1554.46  4840.2 1551.73  4865.3 1551.15  4910.2 1549.33
  4980.2 1549.70  4990.2 1548.73  4997.2 1546.21  4999.9 1545.71  5003.2 1546.21
  5020.2 1549.40  5060.2 1550.41  5150.2 1556.44  5210.2 1558.48  5280.2 1562.85
  5370.2 1565.90  5492.4 1573.25  5520.2 1575.12  5530.2 1576.23  5535.4 1577.54
#Mann=8,-1,0
  4548.2     0.1       0  4602.1    0.16       0  4690.2     0.1       0
  4792.7    0.16       0  4865.3     0.1       0  4997.2    0.07       0
  5003.2     0.1       0  5492.4    0.05       0
Bank Sta=4997.2,5003.2
Exp/Cntr=0.3,0.1

Type RM Length L Ch R = 1,16526,852,852,852
BEGIN DESCRIPTION:
IRON ROCK CREEK 37.0
END DESCRIPTION:
XS GIS Cut Line= 2
      2845601.91     10074561.66      2844442.15     10074984.38
#Sta/Elev= 30
  4401.6 1568.75  4419.0 1568.06  4421.7 1567.89  4427.1 1570.15  4447.0 1566.97
  4452.3 1567.63  4477.6 1563.10  4490.4 1562.22  4508.1 1557.15  4513.4 1557.59
  4525.7 1554.27  4538.7 1551.73  4594.5 1547.96  4838.7 1540.73  4841.4 1540.23
  4844.7 1540.73  4845.8 1540.86  4889.5 1542.91  4981.2 1544.17  4996.5 1542.10
  5001.1 1541.49  5012.0 1544.12  5031.7 1544.39  5062.3 1551.87  5165.9 1559.01
  5316.2 1565.74  5333.0 1566.93  5486.0 1576.20  5561.1 1582.69  5636.0 1587.37
#Mann=12,-1,0
  4401.6    0.05       0  4419.0     0.1       0  4525.7    0.16       0
  4838.7    0.07       0  4844.7    0.16       0  4845.8    0.05       0
  4996.5     0.1       0  5165.9    0.05       0  5316.2     0.1       0
  5333.0    0.05       0  5486.0     0.1       0  5561.1    0.05       0
Bank Sta=4838.7,4844.7
Exp/Cntr=0.3,0.1

Type RM Length L Ch R = 1,15674,686,686,686
BEGIN DESCRIPTION:
IRON ROCK CREEK 35.0
END DESCRIPTION:
XS GIS Cut Line= 2
      2845580.27     10074062.51      2844386.69     10074431.44
#Sta/Elev= 30
  4460.6 1561.31  4479.9 1558.80  4492.2 1558.52  4512.6 1555.63  4517.8 1556.04
  4550.4 1552.95  4583.1 1547.92  4641.2 1542.10  4681.0 1539.76  4718.8 1539.93
  4756.7 1538.32  4776.5 1538.61  4797.4 1537.44  4903.7 1534.98  4975.4 1533.83
  4985.1 1532.07  4993.3 1528.52  4996.0 1528.02  4999.3 1528.52  5006.8 1530.12
  5017.2 1531.04  5023.0 1530.10  5028.2 1532.73  5099.5 1536.31  5164.0 1539.04
  5205.6 1540.13  5224.0 1539.80  5268.4 1542.73  5506.1 1551.45  5709.9 1559.31
#Mann=8,-1,0
  4460.6    0.05       0  4492.2     0.1       0  4641.2    0.16       0
  4903.7     0.1       0  4993.3    0.07       0  4999.3     0.1       0
  5099.5    0.05       0  5506.1     0.1       0
Bank Sta=4993.3,4999.3
Exp/Cntr=0.3,0.1

Type RM Length L Ch R = 1,14988,626,626,626
BEGIN DESCRIPTION:
IRON ROCK CREEK 34.0
END DESCRIPTION:
XS GIS Cut Line= 2
      2845558.57     10073682.74      2844495.21     10073552.54
#Sta/Elev= 30
  4335.9 1546.10  4370.1 1544.24  4376.3 1543.39  4416.6 1540.12  4468.4 1536.95
  4507.3 1535.63  4533.0 1534.13  4604.4 1532.27  4643.4 1531.04  4829.7 1528.61
  4910.3 1526.39  4960.6 1525.97  4980.8 1524.91  4997.9 1522.36  5000.7 1521.86
  5003.9 1522.36  5011.0 1523.83  5021.1 1524.71  5121.8 1525.06  5182.3 1527.22
  5189.5 1527.99  5194.5 1527.57  5232.7 1531.48  5252.8 1534.17  5262.9 1534.81
  5293.1 1535.34  5352.4 1537.35  5357.4 1536.82  5362.3 1537.13  5407.2 1539.30
#Mann=7,-1,0
  4335.9    0.05       0  4468.4     0.1       0  4604.4    0.05       0
  4643.4     0.1       0  4997.9    0.07       0  5003.9     0.1       0
  5362.3    0.05       0
Bank Sta=4997.9,5003.9
Exp/Cntr=0.3,0.1

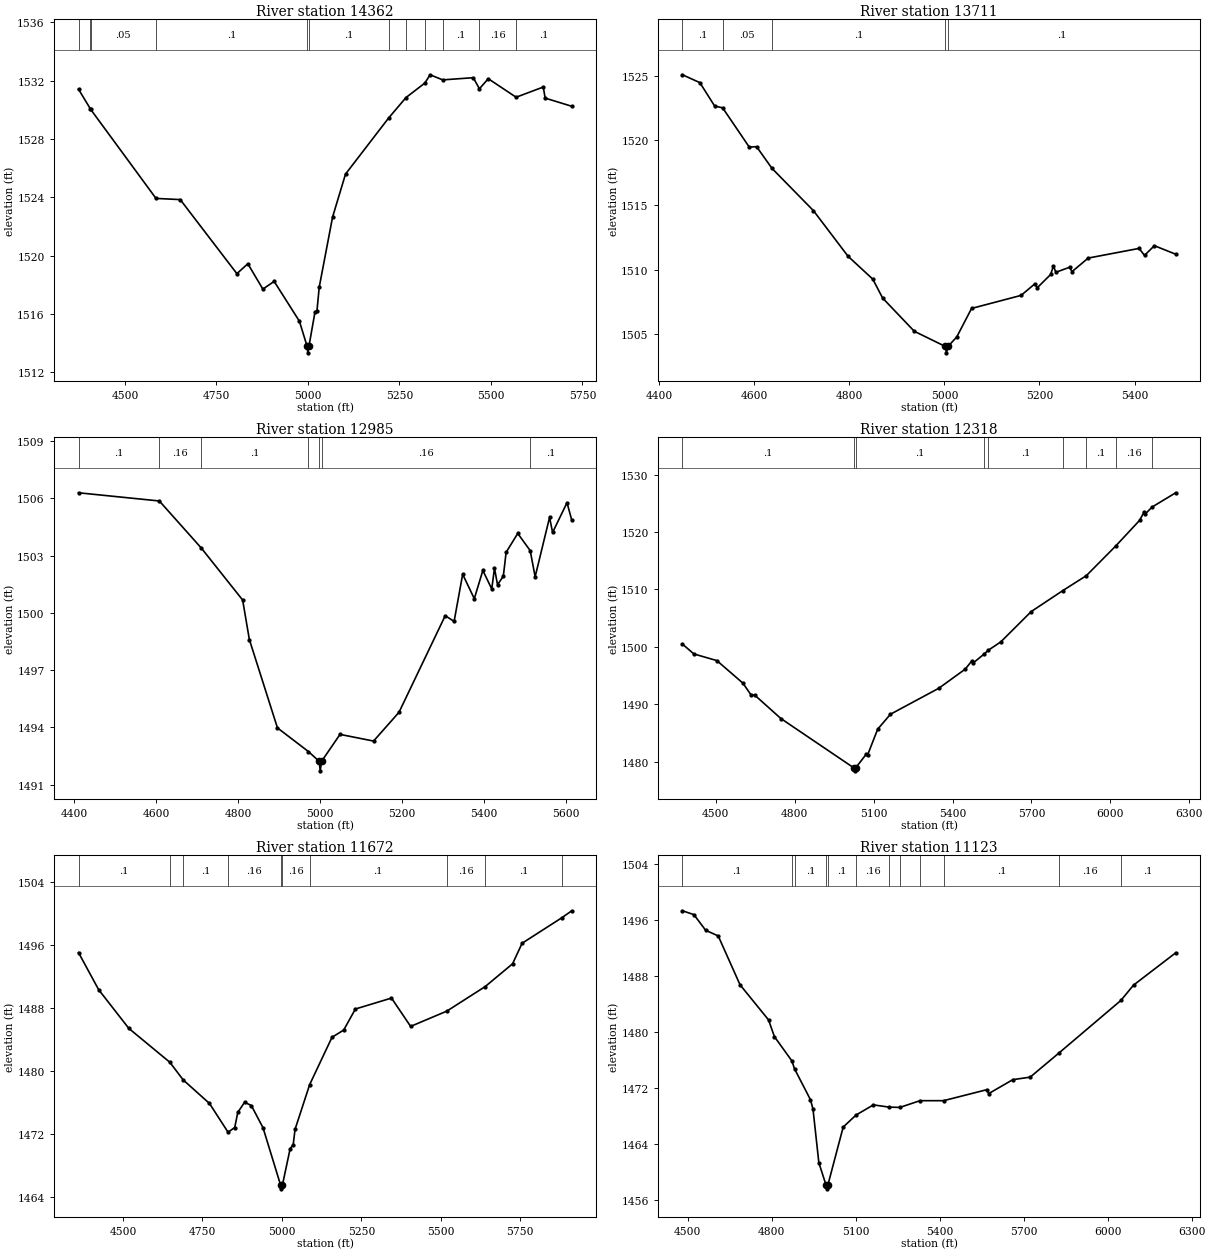
Type RM Length L Ch R = 1,14362,651,651,651
BEGIN DESCRIPTION:
IRON ROCK CREEK 32.0
END DESCRIPTION:
XS GIS Cut Line= 2
      2845439.19     10073205.31      2844126.29     10072901.50
#Sta/Elev= 30
  4373.1 1531.41  4405.8 1530.05  4406.2 1530.03  4584.8 1523.92  4651.0 1523.84
  4805.8 1518.76  4835.7 1519.44  4876.8 1517.70  4907.6 1518.23  4976.6 1515.50
  4997.0 1513.83  4999.7 1513.33  5003.0 1513.83  5019.3 1516.15  5024.4 1516.17
  5030.8 1517.84  5067.2 1522.64  5102.6 1525.59  5220.5 1529.44  5267.9 1530.84
  5319.3 1531.83  5333.7 1532.40  5368.1 1532.05  5451.6 1532.20  5468.4 1531.44
  5492.6 1532.13  5568.7 1530.86  5642.9 1531.56  5648.0 1530.80  5720.7 1530.24
#Mann=12,-1,0
  4373.1    0.05       0  4405.8     0.1       0  4406.2    0.05       0
  4584.8     0.1       0  4997.0    0.07       0  5003.0     0.1       0
  5220.5    0.16       0  5267.9     0.1       0  5319.3    0.16       0
  5368.1     0.1       0  5468.4    0.16       0  5568.7     0.1       0
Bank Sta=4997,5003
Exp/Cntr=0.3,0.1

Type RM Length L Ch R = 1,13711,726,726,726
BEGIN DESCRIPTION:
IRON ROCK CREEK 31.0
END DESCRIPTION:
XS GIS Cut Line= 2
      2845623.66     10072641.08      2844625.36     10072358.95
#Sta/Elev= 30
  4449.1 1525.09  4485.7 1524.48  4516.8 1522.67  4533.6 1522.53  4589.6 1519.49
  4605.0 1519.52  4637.4 1517.84  4724.7 1514.56  4797.4 1511.03  4849.4 1509.26
  4870.2 1507.79  4936.7 1505.22  5001.7 1504.05  5004.4 1503.55  5007.7 1504.05
  5026.0 1504.78  5057.2 1506.99  5161.3 1508.00  5190.1 1508.89  5195.3 1508.59
  5223.5 1509.62  5229.3 1510.28  5234.5 1509.79  5263.3 1510.18  5268.5 1509.84
  5302.4 1510.89  5409.5 1511.64  5420.9 1511.10  5441.7 1511.85  5486.5 1511.19
#Mann=5,-1,0
  4449.1     0.1       0  4533.6    0.05       0  4637.4     0.1       0
  5001.7    0.07       0  5007.7     0.1       0
Bank Sta=5001.7,5007.7
Exp/Cntr=0.3,0.1

Type RM Length L Ch R = 1,12985,667,667,667
BEGIN DESCRIPTION:
IRON ROCK CREEK 30.0
END DESCRIPTION:
XS GIS Cut Line= 3
      2845688.72     10072000.87      2845005.16     10071773.02
      2844647.06     10072098.57
#Sta/Elev= 30
  4409.9 1506.29  4607.3 1505.86  4709.9 1503.39  4810.7 1500.67  4827.1 1498.60
  4895.7 1493.97  4971.4 1492.73  4997.5 1492.22  5000.2 1491.72  5003.5 1492.22
  5048.5 1493.63  5130.4 1493.28  5192.6 1494.79  5305.4 1499.85  5327.1 1499.55
  5348.0 1502.02  5376.4 1500.74  5397.3 1502.22  5419.0 1501.25  5425.7 1502.34
  5433.1 1501.47  5447.3 1501.92  5454.1 1503.17  5482.5 1504.16  5512.9 1503.26
  5525.0 1501.89  5560.2 1505.00  5567.6 1504.21  5602.8 1505.77  5614.4 1504.86
#Mann=7,-1,0
  4409.9     0.1       0  4607.3    0.16       0  4709.9     0.1       0
  4971.4    0.16       0  4997.5    0.07       0  5003.5    0.16       0
  5512.9     0.1       0
Bank Sta=4997.5,5003.5
Exp/Cntr=0.3,0.1

Type RM Length L Ch R = 1,12318,646,646,646
BEGIN DESCRIPTION:
IRON ROCK CREEK 28.0
END DESCRIPTION:
XS GIS Cut Line= 4
      2845558.53     10071653.63      2845276.43     10071230.48
      2844983.46     10071165.38      2843921.80     10071067.88
#Sta/Elev= 30
  4373.3 1500.47  4416.9 1498.75  4504.0 1497.60  4603.1 1493.67  4633.2 1491.67
  4648.2 1491.58  4747.4 1487.51  5025.3 1478.90  5028.0 1478.40  5031.3 1478.90
  5071.8 1481.29  5076.9 1481.14  5115.3 1485.65  5164.0 1488.26  5347.7 1492.78
  5448.1 1496.11  5473.3 1497.55  5478.3 1497.18  5520.5 1498.76  5535.9 1499.40
  5583.2 1500.85  5699.1 1506.14  5818.5 1509.77  5908.5 1512.39  6020.5 1517.57
  6110.9 1522.02  6127.7 1523.44  6132.7 1523.14  6158.1 1524.33  6248.1 1526.82
#Mann=9,-1,0
  4373.3     0.1       0  5025.3    0.07       0  5031.3     0.1       0
  5520.5    0.16       0  5535.9     0.1       0  5818.5    0.16       0
  5908.5     0.1       0  6020.5    0.16       0  6158.1     0.1       0
Bank Sta=5025.3,5031.3
Exp/Cntr=0.3,0.1

Type RM Length L Ch R = 1,11672,549,549,549
BEGIN DESCRIPTION:
IRON ROCK CREEK 27.0
END DESCRIPTION:
XS GIS Cut Line= 3
      2846056.86     10071082.15      2845258.29     10070596.06
      2844642.70     10070552.71
#Sta/Elev= 30
  4360.1 1495.00  4423.5 1490.29  4518.4 1485.38  4647.4 1481.08  4689.4 1478.84
  4772.2 1475.85  4830.6 1472.20  4851.6 1472.79  4861.2 1474.71  4882.6 1476.00
  4903.9 1475.59  4940.7 1472.76  4995.8 1465.51  4998.6 1465.01  5001.8 1465.51
  5026.0 1470.11  5035.6 1470.60  5041.4 1472.56  5087.5 1478.25  5157.7 1484.25
  5194.5 1485.17  5231.3 1487.84  5344.9 1489.23  5405.1 1485.63  5518.9 1487.57
  5639.8 1490.69  5725.9 1493.58  5755.9 1496.19  5881.8 1499.45  5912.1 1500.31
#Mann=10,-1,0
  4360.1     0.1       0  4647.4    0.05       0  4689.4     0.1       0
  4830.6    0.16       0  4995.8    0.07       0  5001.8    0.16       0
  5087.5     0.1       0  5518.9    0.16       0  5639.8     0.1       0
  5881.8    0.05       0
Bank Sta=4995.8,5001.8
Exp/Cntr=0.3,0.1

Type RM Length L Ch R = 1,11123,681,681,681
BEGIN DESCRIPTION:
IRON ROCK CREEK 25.0
END DESCRIPTION:
XS GIS Cut Line= 3
      2846285.54     10070622.84      2845645.36     10070188.82
      2844681.53     10069972.23
#Sta/Elev= 30
  4481.8 1497.29  4522.7 1496.74  4564.6 1494.51  4609.5 1493.70  4687.4 1486.73
  4789.2 1481.72  4810.2 1479.33  4872.5 1475.87  4882.1 1474.73  4939.0 1470.32
  4947.9 1469.00  4968.9 1461.33  4994.8 1458.11  4997.5 1457.61  5000.8 1458.11
  5055.8 1466.43  5102.0 1468.15  5163.6 1469.59  5220.0 1469.27  5258.4 1469.23
  5329.9 1470.19  5414.1 1470.19  5569.8 1471.77  5574.9 1471.19  5661.5 1473.19
  5723.5 1473.55  5827.0 1477.02  6047.5 1484.50  6092.5 1486.68  6243.1 1491.29
#Mann=12,-1,0
  4481.8     0.1       0  4872.5    0.05       0  4882.1     0.1       0
  4994.8    0.07       0  5000.8     0.1       0  5102.0    0.16       0
  5220.0    0.05       0  5258.4     0.1       0  5329.9    0.05       0
  5414.1     0.1       0  5827.0    0.16       0  6047.5     0.1       0
Bank Sta=4994.8,5000.8
Exp/Cntr=0.3,0.1

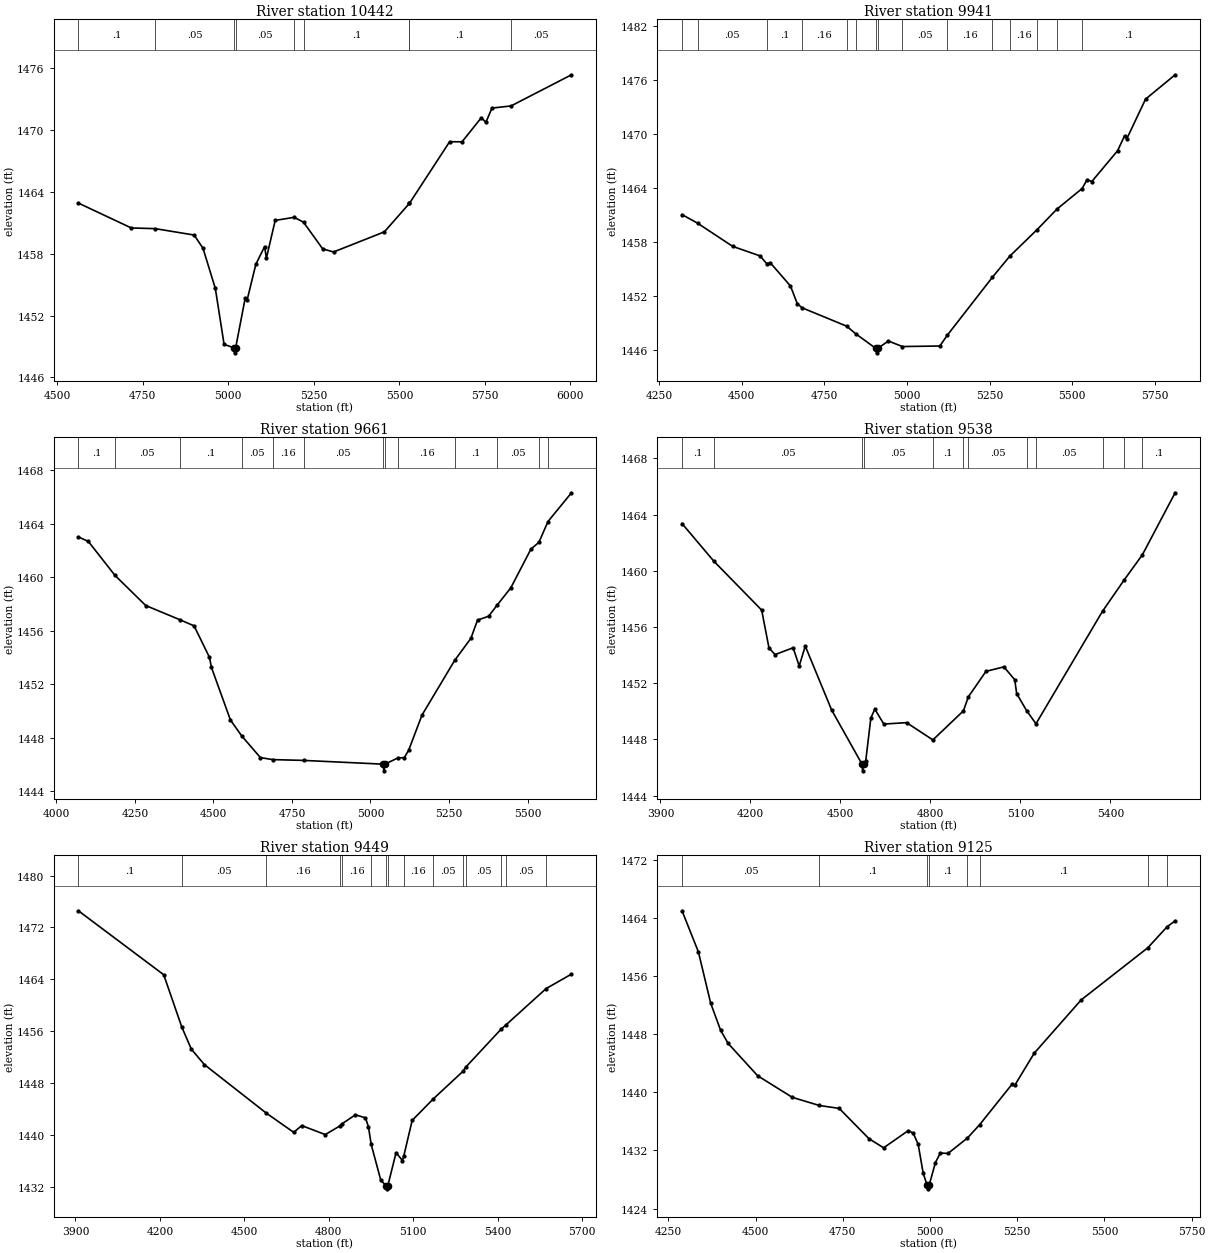
Type RM Length L Ch R = 1,10442,501,501,501
BEGIN DESCRIPTION:
IRON ROCK CREEK 23.0
END DESCRIPTION:
XS GIS Cut Line= 3
      2846252.97     10069917.53      2846068.53     10069722.24
      2844962.61     10069331.91
#Sta/Elev= 30
  4561.6 1462.91  4716.2 1460.50  4786.7 1460.43  4900.0 1459.81  4925.7 1458.54
  4961.9 1454.64  4987.5 1449.21  5015.4 1448.89  5018.2 1448.39  5021.4 1448.89
  5049.4 1453.73  5054.7 1453.49  5080.3 1456.97  5105.9 1458.69  5111.2 1457.57
  5136.9 1461.23  5192.5 1461.53  5219.9 1461.05  5275.7 1458.47  5307.5 1458.17
  5456.0 1460.12  5528.9 1462.87  5529.1 1462.87  5646.8 1468.86  5683.0 1468.85
  5739.6 1471.19  5752.9 1470.74  5770.5 1472.12  5826.5 1472.33  6003.0 1475.35
#Mann=9,-1,0
  4561.6     0.1       0  4786.7    0.05       0  5015.4    0.04       0
  5021.4    0.05       0  5192.5    0.16       0  5219.9     0.1       0
  5528.9    0.16       0  5529.1     0.1       0  5826.5    0.05       0
Bank Sta=5015.4,5021.4
Exp/Cntr=0.3,0.1

Type RM Length L Ch R = 1,9941,280,280,280
BEGIN DESCRIPTION:
IRON ROCK CREEK 22.0
END DESCRIPTION:
XS GIS Cut Line= 3
      2846307.25     10069874.17      2846187.89     10069331.61
      2845536.86     10068658.88
#Sta/Elev= 30
  4319.8 1461.06  4366.7 1460.11  4472.9 1457.53  4555.8 1456.47  4575.8 1455.61
  4586.5 1455.72  4647.9 1453.12  4668.4 1451.16  4682.8 1450.70  4817.6 1448.66
  4845.1 1447.81  4905.8 1446.19  4908.6 1445.69  4911.8 1446.19  4944.1 1447.00
  4986.7 1446.39  5099.7 1446.45  5122.5 1447.66  5258.4 1454.08  5311.3 1456.44
  5394.2 1459.40  5454.1 1461.68  5530.1 1463.96  5545.2 1464.95  5559.4 1464.74
  5637.3 1468.16  5658.4 1469.81  5665.6 1469.52  5722.0 1473.90  5811.5 1476.61
#Mann=15,-1,0
  4319.8     0.1       0  4366.7    0.05       0  4575.8     0.1       0
  4682.8    0.16       0  4817.6     0.1       0  4845.1    0.16       0
  4905.8   0.033       0  4911.8    0.16       0  4986.7    0.05       0
  5122.5    0.16       0  5258.4     0.1       0  5311.3    0.16       0
  5394.2     0.1       0  5454.1    0.16       0  5530.1     0.1       0
Bank Sta=4905.8,4911.8
Exp/Cntr=0.3,0.1

Type RM Length L Ch R = 1,9661,123,123,123
BEGIN DESCRIPTION:
Mapping XS 06855c4f
END DESCRIPTION:
XS GIS Cut Line= 5
      2846282.59     10069945.05      2846378.08     10069380.78
      2846378.08     10069215.85      2846256.55     10068964.12
      2845865.92     10068573.48
#Sta/Elev= 30
  4070.4 1463.00  4102.2 1462.66  4186.6 1460.13  4284.7 1457.87  4392.2 1456.82
  4438.6 1456.35  4487.6 1453.99  4493.9 1453.24  4554.3 1449.31  4590.2 1448.12
  4649.7 1446.50  4689.0 1446.35  4787.3 1446.29  5039.9 1446.01  5042.7 1445.51
  5045.9 1446.01  5087.7 1446.48  5107.3 1446.49  5121.4 1447.05  5163.9 1449.68
  5268.5 1453.79  5319.4 1455.41  5340.6 1456.78  5376.0 1457.07  5402.3 1457.88
  5446.7 1459.20  5510.3 1462.08  5536.0 1462.60  5564.8 1464.15  5639.6 1466.30
#Mann=13,-1,0
  4070.4     0.1       0  4186.6    0.05       0  4392.2     0.1       0
  4590.2    0.05       0  4689.0    0.16       0  4787.3    0.05       0
  5039.9   0.033       0  5045.9    0.05       0  5087.7    0.16       0
  5268.5     0.1       0  5402.3    0.05       0  5536.0    0.16       0
  5564.8    0.05       0
Bank Sta=5039.9,5045.9
Exp/Cntr=0.3,0.1

Type RM Length L Ch R = 1,9538,89,89,89
BEGIN DESCRIPTION:
Mapping XS e09fce37
END DESCRIPTION:
XS GIS Cut Line= 6
      2846369.40     10069971.03      2846450.13     10069345.05
      2846434.33     10069065.47      2846384.99     10068959.60
      2846300.39     10068846.36      2845962.46     10068513.76
#Sta/Elev= 30
  3972.0 1463.36  4077.6 1460.69  4237.4 1457.20  4261.7 1454.52  4281.8 1454.03
  4342.3 1454.52  4362.5 1453.22  4382.7 1454.64  4470.6 1450.09  4571.2 1446.26
  4574.0 1445.76  4577.2 1446.26  4584.3 1446.47  4601.3 1449.52  4614.5 1450.15
  4644.6 1449.09  4720.4 1449.19  4808.1 1447.96  4909.8 1450.03  4926.2 1451.02
  4984.9 1452.84  5044.8 1453.16  5081.0 1452.24  5087.3 1451.26  5120.6 1450.04
  5151.7 1449.11  5373.5 1457.12  5444.8 1459.32  5506.4 1461.14  5615.5 1465.55
#Mann=12,-1,0
  3972.0     0.1       0  4077.6    0.05       0  4571.2   0.033       0
  4577.2    0.05       0  4808.1     0.1       0  4909.8    0.16       0
  4926.2    0.05       0  5120.6    0.16       0  5151.7    0.05       0
  5373.5     0.1       0  5444.8    0.05       0  5506.4     0.1       0
Bank Sta=4571.2,4577.2
Exp/Cntr=0.3,0.1

Type RM Length L Ch R = 1,9449,324,324,324
BEGIN DESCRIPTION:
IRON ROCK CREEK 15.0
END DESCRIPTION:
XS GIS Cut Line= 3
      2846898.93     10069892.97      2846343.36     10068660.30
      2846065.59     10068373.85
#Sta/Elev= 30
  3910.5 1474.57  4213.6 1464.70  4277.5 1456.66  4311.6 1453.22  4357.9 1450.84
  4577.6 1443.36  4675.1 1440.39  4703.7 1441.43  4787.2 1440.04  4840.2 1441.40
  4846.6 1441.70  4894.3 1443.09  4929.8 1442.63  4940.6 1441.25  4950.2 1438.55
  4984.6 1432.97  5003.5 1432.17  5006.3 1431.67  5009.5 1432.17  5038.6 1437.24
  5061.4 1436.04  5065.8 1436.69  5095.9 1442.23  5170.2 1445.52  5276.5 1449.81
  5285.4 1450.41  5412.2 1456.33  5428.4 1456.94  5571.3 1462.56  5661.6 1464.80
#Mann=15,-1,0
  3910.5     0.1       0  4277.5    0.05       0  4577.6    0.16       0
  4840.2     0.1       0  4846.6    0.16       0  4950.2     0.1       0
  5003.5    0.07       0  5009.5     0.1       0  5065.8    0.16       0
  5170.2    0.05       0  5276.5    0.16       0  5285.4    0.05       0
  5412.2     0.1       0  5428.4    0.05       0  5571.3     0.1       0
Bank Sta=5003.5,5009.5
Exp/Cntr=0.3,0.1

Type RM Length L Ch R = 1,9125,626,626,626
BEGIN DESCRIPTION:
IRON ROCK CREEK 21.0
END DESCRIPTION:
XS GIS Cut Line= 2
      2847185.37     10069233.21      2846239.18     10068182.85
#Sta/Elev= 30
  4289.0 1464.95  4336.0 1459.28  4371.2 1452.23  4399.6 1448.52  4421.2 1446.71
  4505.7 1442.27  4605.1 1439.30  4682.6 1438.18  4739.6 1437.78  4824.8 1433.62
  4867.0 1432.36  4937.7 1434.73  4951.9 1434.38  4966.1 1432.82  4980.3 1428.89
  4991.5 1427.22  4994.2 1426.72  4997.5 1427.22  5015.4 1430.33  5029.6 1431.65
  5051.3 1431.58  5107.3 1433.71  5142.1 1435.53  5235.2 1441.11  5242.6 1440.93
  5298.7 1445.37  5433.2 1452.69  5624.3 1459.86  5680.0 1462.77  5702.7 1463.56
#Mann=8,-1,0
  4289.0    0.05       0  4682.6     0.1       0  4991.5    0.07       0
  4997.5     0.1       0  5107.3    0.16       0  5142.1     0.1       0
  5624.3    0.05       0  5680.0    0.16       0
Bank Sta=4991.5,4997.5
Exp/Cntr=0.3,0.1

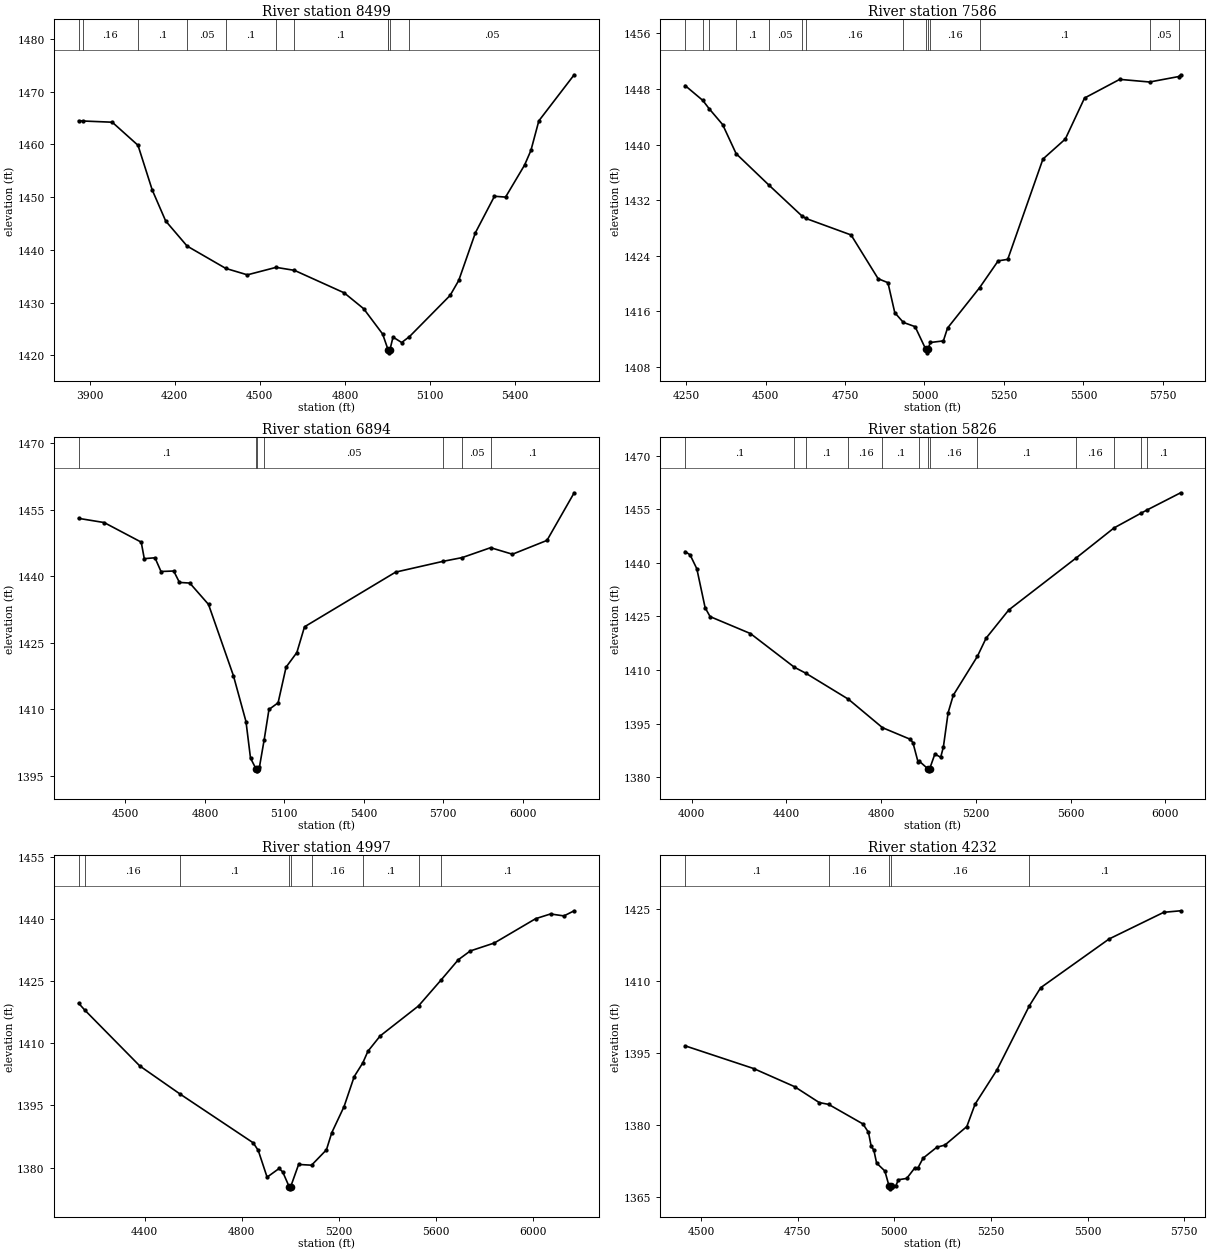
Type RM Length L Ch R = 1,8499,913,913,913
BEGIN DESCRIPTION:
IRON ROCK CREEK 19.0
END DESCRIPTION:
XS GIS Cut Line= 3
      2847544.24     10069201.45      2847197.00     10068268.24
      2846524.23     10067931.86
#Sta/Elev= 30
  3860.8 1464.50  3875.6 1464.45  3979.4 1464.22  4070.2 1459.84  4120.4 1451.36
  4167.8 1445.48  4243.4 1440.72  4379.8 1436.48  4455.9 1435.26  4557.2 1436.68
  4622.1 1436.11  4797.3 1431.85  4866.1 1428.84  4933.1 1424.03  4952.0 1421.09
  4952.5 1420.96  4955.3 1420.46  4958.5 1420.96  4969.7 1423.45  5000.2 1422.42
  5027.4 1423.52  5171.0 1431.35  5201.5 1434.19  5260.4 1443.26  5327.5 1450.17
  5366.7 1450.01  5433.7 1456.08  5456.1 1458.86  5484.0 1464.47  5608.7 1473.22
#Mann=11,-1,0
  3860.8    0.05       0  3875.6    0.16       0  4070.2     0.1       0
  4243.4    0.05       0  4379.8     0.1       0  4557.2    0.16       0
  4622.1     0.1       0  4952.0    0.16       0  4952.5    0.07       0
  4958.5    0.16       0  5027.4    0.05       0
Bank Sta=4952.5,4958.5
Exp/Cntr=0.3,0.1

Type RM Length L Ch R = 1,7586,692,692,692
BEGIN DESCRIPTION:
IRON ROCK CREEK 17.0
END DESCRIPTION:
XS GIS Cut Line= 4
      2848131.56     10068677.68      2847992.66     10068165.50
      2847775.65     10067809.60      2847168.03     10067740.16
#Sta/Elev= 30
  4246.8 1448.49  4302.5 1446.35  4322.4 1445.16  4364.9 1442.87  4407.4 1438.68
  4510.5 1434.16  4613.6 1429.75  4626.7 1429.36  4769.0 1426.98  4854.2 1420.68
  4885.0 1420.11  4906.5 1415.79  4933.5 1414.39  4970.4 1413.78  5004.2 1410.51
  5006.9 1410.01  5010.2 1410.51  5018.7 1411.50  5059.4 1411.73  5072.4 1413.57
  5173.7 1419.41  5231.8 1423.25  5261.9 1423.47  5372.7 1437.91  5443.1 1440.79
  5503.5 1446.69  5614.2 1449.38  5708.3 1449.00  5799.2 1449.78  5805.9 1450.04
#Mann=14,-1,0
  4246.8    0.16       0  4302.5     0.1       0  4322.4    0.16       0
  4407.4     0.1       0  4510.5    0.05       0  4613.6     0.1       0
  4626.7    0.16       0  4933.5     0.1       0  5004.2    0.07       0
  5010.2     0.1       0  5018.7    0.16       0  5173.7     0.1       0
  5708.3    0.05       0  5799.2     0.1       0
Bank Sta=5004.2,5010.2
Exp/Cntr=0.3,0.1

Type RM Length L Ch R = 1,6894,1068,1068,1068
BEGIN DESCRIPTION:
Mapping XS cb573013
END DESCRIPTION:
XS GIS Cut Line= 3
      2848643.71     10067453.70      2847584.68     10067609.95
      2846786.09     10067670.71
#Sta/Elev= 30
  4323.2 1453.01  4419.5 1452.07  4559.6 1447.66  4571.1 1443.94  4611.5 1444.14
  4634.3 1441.05  4682.3 1441.16  4703.9 1438.59  4742.9 1438.45  4813.7 1433.64
  4907.8 1417.59  4955.2 1407.28  4972.3 1399.05  4992.6 1396.68  4995.4 1396.18
  4998.6 1396.68  5005.8 1396.95  5023.9 1403.18  5042.0 1409.99  5076.5 1411.50
  5106.6 1419.52  5147.3 1422.81  5176.2 1428.60  5520.3 1440.91  5699.6 1443.34
  5771.6 1444.18  5879.0 1446.41  5961.5 1444.94  6091.9 1448.05  6194.6 1458.77
#Mann=7,-1,0
  4323.2     0.1       0  4992.6    0.07       0  4998.6     0.1       0
  5023.9    0.05       0  5699.6     0.1       0  5771.6    0.05       0
  5879.0     0.1       0
Bank Sta=4992.6,4998.6
Exp/Cntr=0.3,0.1

Type RM Length L Ch R = 1,5826,829,829,829
BEGIN DESCRIPTION:
IRON ROCK CREEK 13.0
END DESCRIPTION:
XS GIS Cut Line= 3
      2848716.09     10067215.72      2848043.36     10066597.24
      2846936.56     10066195.75
#Sta/Elev= 30
  3972.9 1443.14  3994.0 1442.22  4022.4 1438.33  4057.5 1427.41  4078.5 1424.94
  4248.7 1420.20  4434.1 1410.77  4481.9 1409.12  4662.3 1401.82  4805.8 1393.87
  4923.8 1390.60  4934.5 1389.65  4955.8 1384.30  4961.5 1384.47  4998.6 1382.29
  5001.4 1381.79  5004.6 1382.29  5026.9 1386.48  5051.5 1385.59  5062.9 1388.47
  5082.9 1398.07  5104.7 1402.95  5206.2 1413.80  5243.0 1418.90  5338.7 1426.80
  5623.1 1441.35  5782.9 1449.75  5894.9 1453.81  5921.0 1454.73  6064.1 1459.59
#Mann=13,-1,0
  3972.9     0.1       0  4434.1    0.16       0  4481.9     0.1       0
  4662.3    0.16       0  4805.8     0.1       0  4961.5    0.16       0
  4998.6    0.07       0  5004.6    0.16       0  5206.2     0.1       0
  5623.1    0.16       0  5782.9     0.1       0  5894.9    0.16       0
  5921.0     0.1       0
Bank Sta=4998.6,5004.6
Exp/Cntr=0.3,0.1

Type RM Length L Ch R = 1,4997,765,765,765
BEGIN DESCRIPTION:
IRON ROCK CREEK 11.0
END DESCRIPTION:
XS GIS Cut Line= 3
      2849155.85     10066958.90      2848435.37     10065934.60
      2847663.09     10065769.73
#Sta/Elev= 30
  4128.1 1419.68  4152.9 1418.06  4380.3 1404.53  4546.9 1397.72  4847.3 1385.98
  4868.2 1384.15  4904.7 1377.68  4954.4 1379.78  4969.2 1378.93  4995.8 1375.36
  4998.6 1374.86  5001.8 1375.36  5034.6 1380.75  5087.9 1380.57  5149.2 1384.28
  5171.3 1388.43  5221.9 1394.73  5263.7 1401.97  5299.2 1405.29  5320.3 1408.10
  5370.9 1411.80  5528.8 1419.04  5620.0 1425.18  5692.5 1430.18  5742.0 1432.31
  5841.1 1434.23  6011.2 1440.10  6072.6 1441.24  6127.9 1440.77  6170.1 1442.01
#Mann=9,-1,0
  4128.1     0.1       0  4152.9    0.16       0  4546.9     0.1       0
  4995.8    0.07       0  5001.8     0.1       0  5087.9    0.16       0
  5299.2     0.1       0  5528.8    0.16       0  5620.0     0.1       0
Bank Sta=4995.8,5001.8
Exp/Cntr=0.3,0.1

Type RM Length L Ch R = 1,4232,817,817,817
BEGIN DESCRIPTION:
IRON ROCK CREEK 9.0
END DESCRIPTION:
XS GIS Cut Line= 2
      2849605.89     10066206.64      2848716.08     10065284.28
#Sta/Elev= 30
  4458.8 1396.55  4635.8 1391.83  4741.8 1388.06  4805.6 1384.75  4830.1 1384.36
  4918.8 1380.29  4933.0 1378.56  4939.9 1375.73  4947.1 1374.79  4954.1 1372.15
  4975.4 1370.51  4986.6 1367.29  4989.3 1366.79  4992.6 1367.29  5003.7 1367.42
  5010.6 1368.68  5032.0 1368.96  5053.1 1371.17  5060.3 1371.04  5074.2 1373.16
  5109.7 1375.44  5130.8 1375.90  5187.4 1379.75  5208.7 1384.40  5265.3 1391.53
  5349.2 1404.89  5378.5 1408.65  5555.3 1418.78  5696.7 1424.33  5740.4 1424.65
#Mann=5,-1,0
  4458.8     0.1       0  4830.1    0.16       0  4986.6    0.07       0
  4992.6    0.16       0  5349.2     0.1       0
Bank Sta=4986.6,4992.6
Exp/Cntr=0.3,0.1

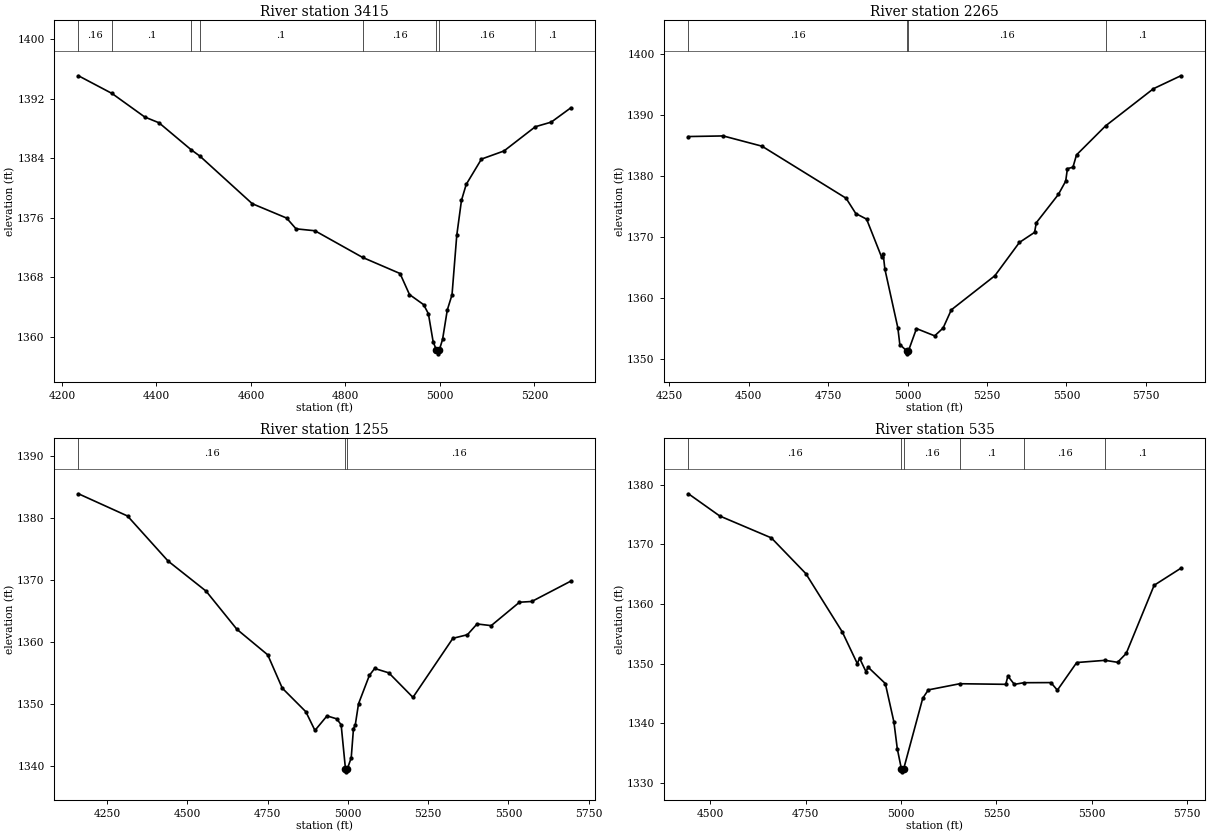
Type RM Length L Ch R = 1,3415,1150,1150,1150
BEGIN DESCRIPTION:
IRON ROCK CREEK 7.0
END DESCRIPTION:
XS GIS Cut Line= 2
      2849801.17     10066174.06      2849779.47     10065132.38
#Sta/Elev= 30
  4235.0 1395.11  4306.0 1392.73  4375.4 1389.56  4405.4 1388.79  4472.9 1385.19
  4492.1 1384.30  4602.7 1377.91  4675.4 1375.98  4695.4 1374.53  4735.4 1374.27
  4836.1 1370.69  4915.5 1368.52  4935.5 1365.69  4965.5 1364.33  4975.5 1363.11
  4985.5 1359.36  4992.5 1358.22  4995.2 1357.72  4998.5 1358.22  5005.5 1359.66
  5015.5 1363.62  5025.5 1365.66  5035.5 1373.64  5045.5 1378.36  5055.5 1380.50
  5087.8 1383.91  5135.5 1385.00  5201.8 1388.26  5235.5 1388.88  5276.9 1390.80
#Mann=8,-1,0
  4235.0    0.16       0  4306.0     0.1       0  4472.9    0.16       0
  4492.1     0.1       0  4836.1    0.16       0  4992.5    0.07       0
  4998.5    0.16       0  5201.8     0.1       0
Bank Sta=4992.5,4998.5
Exp/Cntr=0.3,0.1

Type RM Length L Ch R = 1,2265,1010,1010,1010
BEGIN DESCRIPTION:
IRON ROCK CREEK 5.0
END DESCRIPTION:
XS GIS Cut Line= 3
      2851135.83     10065392.81      2850104.99     10065197.50
      2849649.23     10064991.32
#Sta/Elev= 30
  4310.3 1386.42  4419.6 1386.52  4541.7 1384.84  4806.3 1376.31  4836.9 1373.80
  4870.9 1372.88  4918.2 1366.65  4923.2 1367.10  4928.5 1364.68  4969.2 1355.08
  4975.5 1352.33  4996.7 1351.30  4999.5 1350.80  5002.7 1351.30  5027.9 1354.94
  5085.2 1353.75  5111.7 1355.03  5137.5 1358.01  5274.5 1363.60  5351.8 1369.06
  5399.5 1370.71  5405.0 1372.29  5474.3 1376.92  5497.5 1379.11  5502.9 1381.16
  5520.3 1381.39  5531.5 1383.41  5622.8 1388.16  5773.6 1394.26  5859.7 1396.38
#Mann=4,-1,0
  4310.3    0.16       0  4996.7    0.07       0  5002.7    0.16       0
  5622.8     0.1       0
Bank Sta=4996.7,5002.7
Exp/Cntr=0.3,0.1

Type RM Length L Ch R = 1,1255,720,720,720
BEGIN DESCRIPTION:
IRON ROCK CREEK 2.0
END DESCRIPTION:
XS GIS Cut Line= 2
      2851114.11     10065295.16      2850397.96     10063938.81
#Sta/Elev= 30
  4160.5 1383.93  4313.3 1380.34  4439.7 1373.06  4557.9 1368.21  4654.2 1362.03
  4750.1 1357.91  4795.4 1352.53  4868.8 1348.72  4897.2 1345.70  4934.8 1348.05
  4965.0 1347.57  4978.8 1346.61  4992.2 1339.51  4995.0 1339.01  4998.2 1339.51
  5010.2 1341.28  5017.2 1345.99  5022.9 1346.61  5032.9 1350.00  5066.9 1354.61
  5083.3 1355.71  5127.3 1355.00  5202.5 1351.04  5326.9 1360.58  5372.1 1361.16
  5402.2 1362.90  5446.3 1362.63  5534.3 1366.41  5572.7 1366.53  5694.3 1369.82
#Mann=3,-1,0
  4160.5    0.16       0  4992.2    0.07       0  4998.2    0.16       0
Bank Sta=4992.2,4998.2
Exp/Cntr=0.3,0.1

Type RM Length L Ch R = 1,535,0,0,0
BEGIN DESCRIPTION:
IRON ROCK CREEK 1.0
END DESCRIPTION:
XS GIS Cut Line= 2
      2851667.50     10064926.25      2851103.25     10063765.20
#Sta/Elev= 30
  4442.8 1378.48  4524.8 1374.76  4660.2 1371.09  4750.4 1365.12  4846.2 1355.33
  4885.7 1350.01  4891.3 1350.96  4908.3 1348.68  4913.9 1349.43  4959.0 1346.69
  4981.5 1340.26  4990.4 1335.76  5001.1 1332.40  5003.8 1331.90  5007.1 1332.40
  5057.1 1344.23  5071.8 1345.63  5154.3 1346.66  5274.8 1346.56  5280.3 1347.94
  5297.3 1346.55  5322.1 1346.83  5393.1 1346.85  5410.1 1345.58  5460.8 1350.21
  5535.2 1350.58  5568.0 1350.25  5590.6 1351.74  5663.8 1363.15  5733.7 1366.00
#Mann=6,-1,0
  4442.8    0.16       0  5001.1    0.07       0  5007.1    0.16       0
  5154.3     0.1       0  5322.1    0.16       0  5535.2     0.1       0
Bank Sta=5001.1,5007.1
Exp/Cntr=0.3,0.1

Chan Stop Cuts=-1