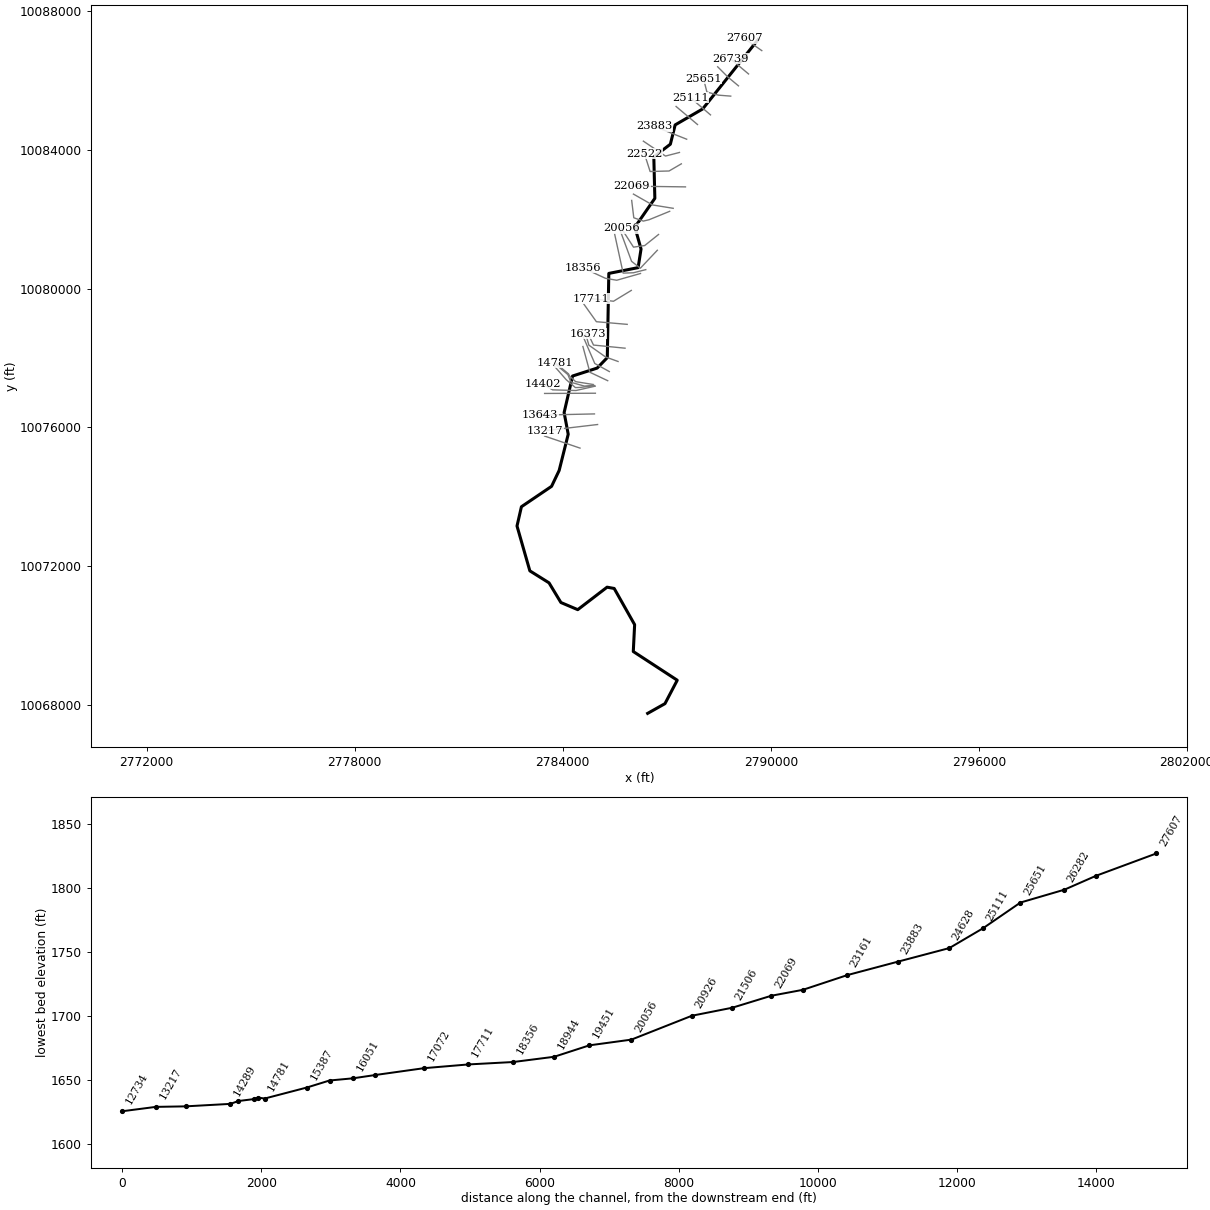
--- KIEHNE CREEK.prj (project) ---

Proj Title=KIEHNE CREEK Base Level Engineering
Current Plan=p01
Default Exp/Contr=0.3,0.1
English Units
Geom File=g01
Flow File=f01
Plan File=p01
Y Axis Title=Elevation
X Axis Title(PF)=Main Channel Distance
X Axis Title(XS)=Station
BEGIN DESCRIPTION:
KIEHNE CREEK
END DESCRIPTION:
DSS Export Rating Curves= 0
DSS Export Rating Curve Sorted= 0
DSS Export Volume Flow Curves= 0
DXF OffsetX= 0
DXF OffsetY= 0
DXF ScaleX= 1
DXF ScaleY= 10

--- KIEHNE CREEK.p01 (plan) ---

Plan Title=Multiple Run
Short Identifier=Multiple
Geom File=g01
Flow File=f01
Subcritical Flow
K Sum by GR= 0
Std Step Tol= 0.01
Critical Tol= 0.01
Num of Std Step Trials= 20
Max Error Tol= 0.3
Flow Tol Ratio= 0.001
Split Flow NTrial= 30
Split Flow Tol= 0.02
Split Flow Ratio= 0.02
Log Output Level= 0
Friction Slope Method= 1
Unsteady Friction Slope Method= 2
Unsteady Bridges Friction Slope Method= 1
Parabolic Critical Depth
Global Vel Dist=  1 , 1 , 1
Global Log Level= 0
CheckData=True
Encroach Param= -1, 0, 0, 0
BEGIN DESCRIPTION:
Multiple Run
END DESCRIPTION:

--- KIEHNE CREEK.f01 (steady flow) ---

Flow Title=Multiple
Number of Profiles=7
Profile Names=10-year,25-year,50-year,1pct_min,100-year,1pct_plu,500-year
River Rch & RM= KIEHNE CREEK,Reach-1,27607
     912    1334    1704    1594    2156    2915    3463
River Rch & RM= KIEHNE CREEK,Reach-1,20056
     782    1124    1418    1311    1772    2397    2778
River Rch & RM= KIEHNE CREEK,Reach-1,18356
    1254    1855    2385    2243    3033    4102    4926
River Rch & RM= KIEHNE CREEK,Reach-1,9458
    1431    2120    2730    2567    3472    4695    5643
River Rch & RM= KIEHNE CREEK,Reach-1,1428
    2271    3443    4501    4291    5804    7849    9701
Boundary for River Rch & Prof#=KIEHNE CREEK,Reach-1,1
Up Type=0
Dn Type=3
Dn Slope=0.005
Boundary for River Rch & Prof#=KIEHNE CREEK,Reach-1,2
Up Type=0
Dn Type=3
Dn Slope=0.005
Boundary for River Rch & Prof#=KIEHNE CREEK,Reach-1,3
Up Type=0
Dn Type=3
Dn Slope=0.005
Boundary for River Rch & Prof#=KIEHNE CREEK,Reach-1,4
Up Type=0
Dn Type=3
Dn Slope=0.005
Boundary for River Rch & Prof#=KIEHNE CREEK,Reach-1,5
Up Type=0
Dn Type=3
Dn Slope=0.005
Boundary for River Rch & Prof#=KIEHNE CREEK,Reach-1,6
Up Type=0
Dn Type=3
Dn Slope=0.005
Boundary for River Rch & Prof#=KIEHNE CREEK,Reach-1,7
Up Type=0
Dn Type=3
Dn Slope=0.005

--- KIEHNE CREEK.g01 (geometry) ---

Geom Title=Existing Conditions
Program Version=4.10

River Reach=KIEHNE CREEK    ,Reach-1
Reach XY= 30
      2789638.47     10087193.73      2788034.87      10085187.2
      2787242.27     10084727.54      2787103.76     10084170.96
      2786626.54     10083805.18      2786656.23     10082609.38
      2786080.94     10081778.22      2786258.08     10081148.42
        2786174.     10080610.72      2785328.41     10080443.88
      2785284.81     10078015.25      2784993.36       10077714.
      2784283.13     10077484.45      2784039.44     10076430.12
       2784157.4      10075804.1      2783896.03      10074759.9
      2783677.54     10074302.61       2782807.6     10073713.69
       2782680.3     10073157.97      2783050.85     10071864.63
      2783604.06     10071518.74      2783946.94     10070951.24
      2784432.73     10070745.22      2785278.47     10071393.73
      2785483.65     10071356.62      2786073.25     10070312.66
      2786034.53     10069537.36      2787302.33       10068710.
       2786948.3     10068034.44      2786448.47     10067753.73

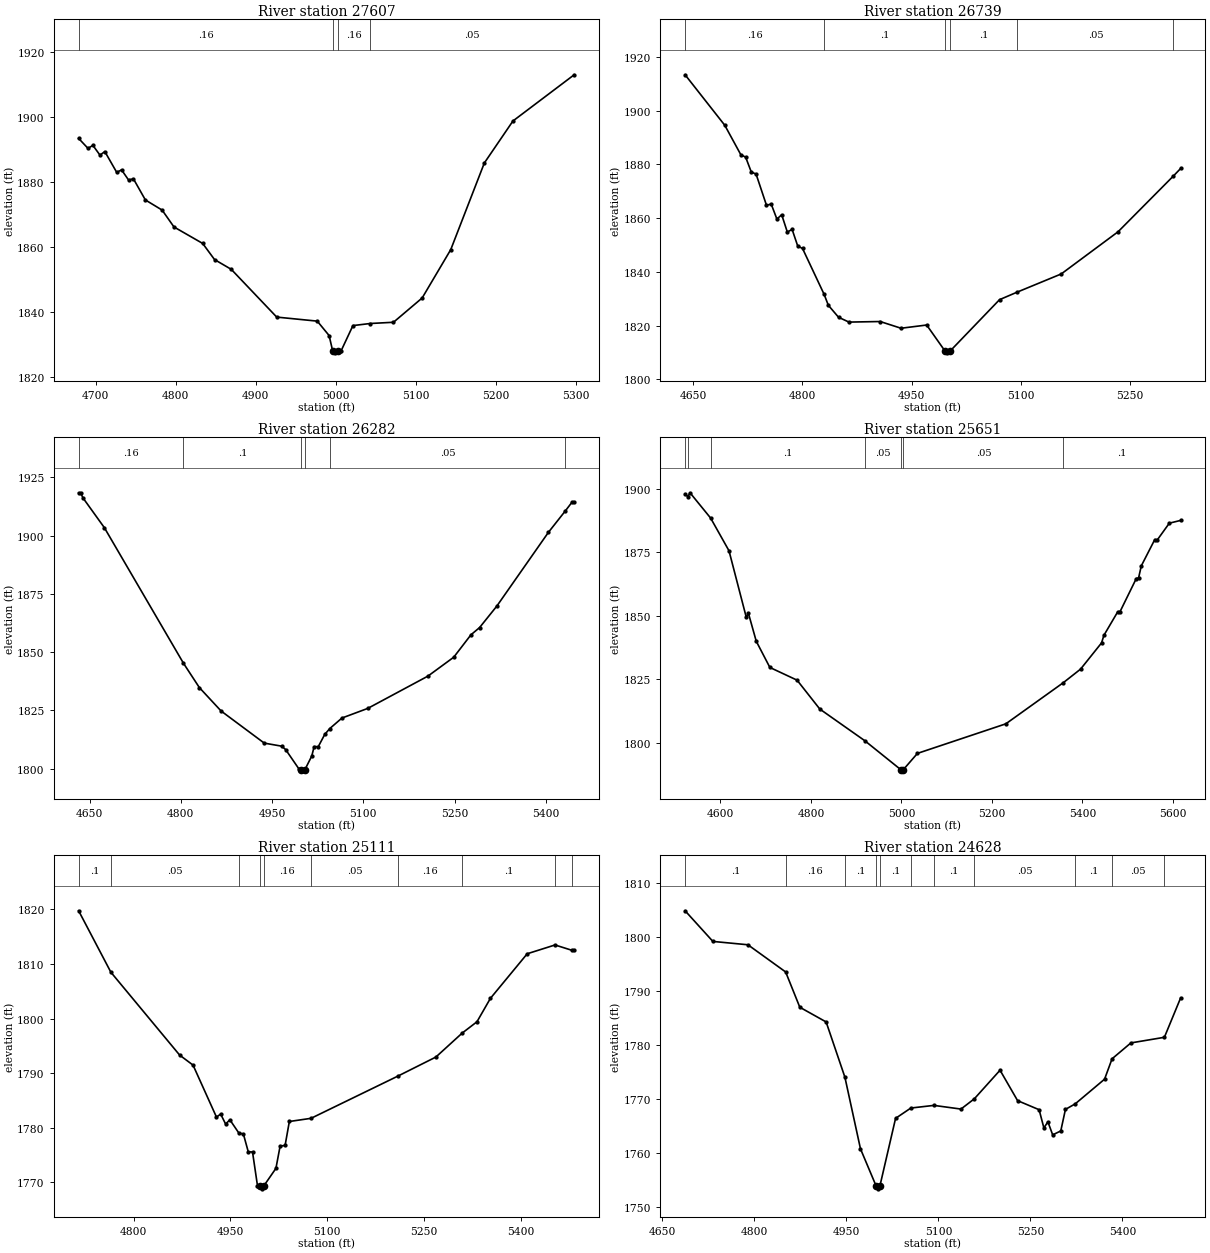
Type RM Length L Ch R = 1 ,27607   ,868,868,868
BEGIN DESCRIPTION:
KIEHNE CREEK 44.0
END DESCRIPTION:
XS GIS Cut Line= 2
      2789740.91     10086870.48      2789233.97     10087224.64
#Sta/Elev= 30
  4678.9 1893.32  4690.6 1890.25  4696.7 1891.18  4705.5 1888.18  4711.6 1889.27
  4726.4 1882.89  4732.5 1883.64  4741.2 1880.53  4747.3 1880.88  4762.2 1874.39
  4783.1 1871.27  4797.9 1866.08  4833.7 1861.02  4848.5 1856.06  4869.4 1853.05
  4926.1 1838.37  4976.7 1837.13  4991.5 1832.69    4996 1827.88  4998.8 1827.38
    5002 1827.88  5006.4 1827.97  5021.2 1835.76  5042.7  1836.4  5071.8 1836.78
  5107.6 1844.25  5143.3 1859.13  5185.2 1885.76  5220.9 1898.67  5297.3 1912.88
#Mann= 4 ,-1 , 0
  4678.9     .16       0    4996     .07       0    5002     .16       0
  5042.7     .05       0
Bank Sta=4996,5002
XS Rating Curve= 0 ,0
Exp/Cntr=0.3,0.1

Type RM Length L Ch R = 1 ,26739   ,457,457,457
BEGIN DESCRIPTION:
KIEHNE CREEK 42.0
END DESCRIPTION:
XS GIS Cut Line= 2
      2789358.98     10086196.85      2788838.15     10086634.35
#Sta/Elev= 30
  4639.2 1913.36  4693.7 1894.56  4715.8 1883.57  4722.3 1882.73  4730.1 1877.15
  4736.6 1876.44  4750.9 1864.82  4757.4 1865.26  4765.2 1859.68  4771.8 1861.29
  4779.5 1854.86  4786.1 1855.83  4793.8 1849.65  4800.4 1848.73  4830.1 1831.63
  4835.8 1827.61  4849.8 1823.15  4864.1 1821.35    4907 1821.56  4935.6 1819.06
  4970.8 1820.26  4996.4 1810.41  4999.1 1809.91  5002.4 1810.41  5070.8 1829.69
  5095.2 1832.52  5155.5 1839.26  5233.5 1854.95  5309.6 1875.74  5319.4  1878.5
#Mann= 6 ,-1 , 0
  4639.2     .16       0  4830.1      .1       0  4996.4     .07       0
  5002.4      .1       0  5095.2     .05       0  5309.6      .1       0
Bank Sta=4996.4,5002.4
XS Rating Curve= 0 ,0
Exp/Cntr=0.3,0.1

Type RM Length L Ch R = 1 ,26282   ,631,631,631
BEGIN DESCRIPTION:
KIEHNE CREEK 41.0
END DESCRIPTION:
XS GIS Cut Line= 3
      2789068.43     10085853.76      2788768.47     10086103.73
      2788468.49     10086403.71
#Sta/Elev= 30
    4632 1918.38  4635.2 1918.38  4639.1 1916.19  4674.3  1903.4  4804.4 1845.18
  4830.5 1834.75  4866.3 1824.68  4937.2 1810.91  4965.8  1809.6  4972.4 1808.12
  4994.5 1799.71    4998 1799.51  5000.7 1799.01    5004 1799.51  5015.3 1805.38
  5019.2  1809.4    5026  1809.4  5036.6 1814.63  5044.9 1817.16  5064.9 1821.68
  5107.3 1825.81  5206.3 1839.68  5248.7 1847.79    5277 1857.41  5291.2 1860.52
  5319.5 1869.72  5404.3 1901.38  5432.3 1910.64  5443.2 1914.36  5446.7 1914.36
#Mann= 6 ,-1 , 0
    4632     .16       0  4804.4      .1       0    4998     .07       0
    5004      .1       0  5044.9     .05       0  5432.3      .1       0
Bank Sta=4998,5004
XS Rating Curve= 0 ,0
Exp/Cntr=0.3,0.1

Type RM Length L Ch R = 1 ,25651   ,540,540,540
BEGIN DESCRIPTION:
KIEHNE CREEK 40.0
END DESCRIPTION:
XS GIS Cut Line= 4
      2788845.14     10085557.95      2788490.94     10085585.73
      2788157.61     10085676.01      2788060.37     10086057.99
#Sta/Elev= 30
  4522.1 1897.82  4528.4 1896.99    4533 1898.47  4578.5 1888.51  4619.1 1875.63
  4657.1 1849.55  4662.1 1850.96  4679.3 1840.01  4709.4 1829.69  4769.5 1824.68
  4819.7 1813.31  4918.9 1800.87  4998.4 1789.48  5001.1 1788.98  5004.4 1789.48
  5035.4 1795.85  5230.7 1807.49  5357.9 1823.72  5395.8 1829.03  5442.2 1839.36
  5447.4 1842.35    5478 1851.63  5483.1 1851.69  5518.9 1864.71    5524 1864.95
    5530 1869.69  5559.8 1880.06  5564.9 1879.81  5591.9  1886.5  5616.9 1887.59
#Mann= 7 ,-1 , 0
  4522.1      .1       0  4528.4     .16       0  4578.5      .1       0
  4918.9     .05       0  4998.4    .035       0  5004.4     .05       0
  5357.9      .1       0
Bank Sta=4998.4,5004.4
XS Rating Curve= 0 ,0
Exp/Cntr=0.3,0.1

Type RM Length L Ch R = 1 ,25111   ,483,483,483
BEGIN DESCRIPTION:
KIEHNE CREEK 38.0
END DESCRIPTION:
XS GIS Cut Line= 2
      2788261.75     10085016.31      2787678.41     10085516.31
#Sta/Elev= 30
  4714.8 1819.73  4764.8 1808.48  4871.4 1793.31  4892.2 1791.47  4928.5 1781.96
    4935 1782.51  4942.7 1780.68  4949.3 1781.46  4963.3 1779.02  4970.2 1778.88
  4977.8  1775.6  4984.4 1775.57  4992.1 1769.39  4995.7 1769.32  4998.5 1768.82
  5001.7 1769.32  5020.7 1772.57  5027.2 1776.66  5034.9 1776.76  5041.5 1781.15
  5075.1 1781.73  5210.1 1789.48  5268.7 1792.95  5309.5 1797.34  5332.4 1799.41
  5353.2 1803.69  5410.3 1811.86  5453.4 1813.47    5480 1812.48  5483.1 1812.48
#Mann= 10 ,-1 , 0
  4714.8      .1       0  4764.8     .05       0  4963.3     .16       0
  4995.7     .07       0  5001.7     .16       0  5075.1     .05       0
  5210.1     .16       0  5309.5      .1       0  5453.4     .16       0
    5480      .1       0
Bank Sta=4995.7,5001.7
XS Rating Curve= 0 ,0
Exp/Cntr=0.3,0.1

Type RM Length L Ch R = 1 ,24628   ,745,745,745
BEGIN DESCRIPTION:
KIEHNE CREEK 37.0
END DESCRIPTION:
XS GIS Cut Line= 2
      2787886.79     10084738.49      2787269.08     10085259.04
#Sta/Elev= 30
    4687 1804.84  4732.3 1799.17  4789.4 1798.55  4850.9 1793.52    4874 1786.99
  4916.9 1784.27  4947.5 1774.05  4972.9 1760.79  4998.5 1753.89  5001.2 1753.39
  5004.5 1753.89  5030.1 1766.43    5055 1768.34  5092.6 1768.83  5136.7 1768.15
  5158.5 1770.05  5200.4 1775.34    5229 1769.71  5264.1 1768.03  5271.9 1764.65
  5278.4  1765.8  5286.2 1763.38  5299.4  1764.1    5307 1768.09  5322.9 1769.11
  5370.8 1773.68    5383 1777.45  5413.7 1780.39  5468.3 1781.43  5494.8 1788.72
#Mann= 11 ,-1 , 0
    4687      .1       0  4850.9     .16       0  4947.5      .1       0
  4998.5     .07       0  5004.5      .1       0    5055     .16       0
  5092.6      .1       0  5158.5     .05       0  5322.9      .1       0
    5383     .05       0  5468.3      .1       0
Bank Sta=4998.5,5004.5
XS Rating Curve= 0 ,0
Exp/Cntr=0.3,0.1

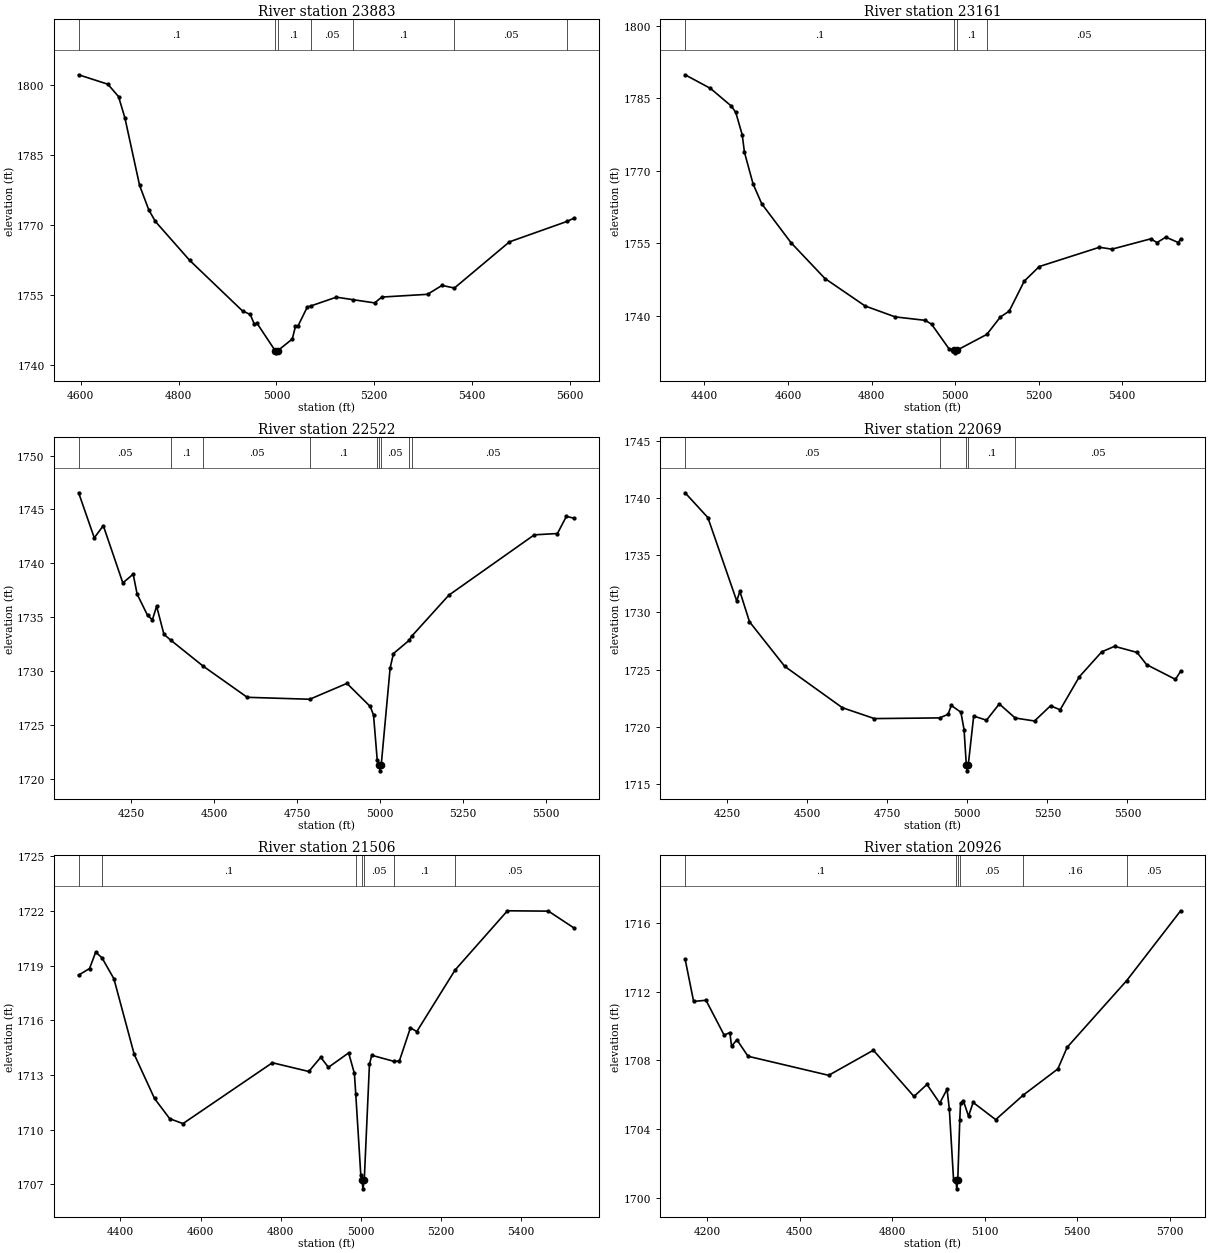
Type RM Length L Ch R = 1 ,23883   ,722,722,722
BEGIN DESCRIPTION:
KIEHNE CREEK 36.0
END DESCRIPTION:
XS GIS Cut Line= 2
       2787574.3     10084314.89      2786633.08     10084688.61
#Sta/Elev= 30
  4595.8 1802.22  4655.5  1800.2  4677.4 1797.55  4690.5 1792.92  4720.4 1778.53
  4739.1 1773.31  4752.7 1770.81  4822.8 1762.48  4930.8 1751.65  4946.4 1750.91
  4955.1 1748.78  4960.5    1749  4997.2 1743.19  4999.9 1742.69  5003.2 1743.19
  5032.5 1745.65  5038.8 1748.34  5044.2 1748.46  5063.1  1752.5  5069.8 1752.71
  5122.5 1754.61  5157.1 1754.06  5200.8 1753.38  5215.4 1754.63  5308.8 1755.22
  5338.5 1757.13  5363.7 1756.56  5476.2 1766.45  5594.3 1770.84  5608.5 1771.55
#Mann= 7 ,-1 , 0
  4595.8      .1       0  4997.2     .07       0  5003.2      .1       0
  5069.8     .05       0  5157.1      .1       0  5363.7     .05       0
  5594.3      .1       0
Bank Sta=4997.2,5003.2
XS Rating Curve= 0 ,0
Exp/Cntr=0.3,0.1

Type RM Length L Ch R = 1 ,23161   ,639,639,639
BEGIN DESCRIPTION:
KIEHNE CREEK 34.0
END DESCRIPTION:
XS GIS Cut Line= 3
      2787365.93     10083932.95      2786963.16     10083828.79
      2786324.72     10084259.04
#Sta/Elev= 30
  4353.8 1789.88  4414.4 1787.06  4464.8 1783.37  4475.1 1782.07  4490.5 1777.44
  4495.8 1773.84  4516.4 1767.29  4537.1 1763.17  4607.3 1755.09  4688.5 1747.67
  4784.6 1741.98  4856.5 1739.72  4928.5    1739  4943.5 1738.22  4985.5 1733.09
  4997.5 1732.77  5000.2 1732.27  5003.5 1732.77  5075.9 1736.09  5108.4 1739.71
  5129.4  1740.9  5165.4 1747.12  5201.4 1750.15  5345.3 1754.14  5375.3 1753.75
  5468.2 1755.89  5483.2 1755.11  5504.2 1756.24  5534.2 1755.12  5539.7 1755.89
#Mann= 4 ,-1 , 0
  4353.8      .1       0  4997.5     .07       0  5003.5      .1       0
  5075.9     .05       0
Bank Sta=4997.5,5003.5
XS Rating Curve= 0 ,0
Exp/Cntr=0.3,0.1

Type RM Length L Ch R = 1 ,22522   ,453,453,453
BEGIN DESCRIPTION:
KIEHNE CREEK 32.0
END DESCRIPTION:
XS GIS Cut Line= 4
      2787420.36     10083604.62      2787066.66     10083398.47
      2786519.78     10083383.28      2786357.02     10083893.25
#Sta/Elev= 30
  4092.2 1746.55  4139.3 1742.37  4166.5  1743.5  4225.3 1738.19  4256.4    1739
  4268.3 1737.15  4299.7 1735.18  4314.3 1734.77    4327 1736.03    4349 1733.42
  4370.4 1732.86  4467.1 1730.47  4599.8 1727.58  4787.9  1727.4  4899.9 1728.87
    4970 1726.73    4980 1725.93    4991  1721.8    4997 1721.26  4999.7 1720.76
    5003 1721.26    5030 1730.31    5040 1731.64    5087 1732.86  5094.4 1733.23
  5206.6 1737.05    5464 1742.65  5533.6 1742.77  5560.5 1744.36    5584 1744.19
#Mann= 9 ,-1 , 0
  4092.2     .05       0  4370.4      .1       0  4467.1     .05       0
  4787.9      .1       0    4991     .05       0    4997    .035       0
    5003     .05       0    5087      .1       0  5094.4     .05       0
Bank Sta=4997,5003
XS Rating Curve= 0 ,0
Exp/Cntr=0.3,0.1

Type RM Length L Ch R = 1 ,22069   ,563,563,563
BEGIN DESCRIPTION:
KIEHNE CREEK 31.0
END DESCRIPTION:
XS GIS Cut Line= 2
      2787539.58      10082939.9      2785992.22     10082960.71
#Sta/Elev= 30
  4118.7 1740.46  4189.8 1738.29  4279.8 1731.01  4289.8 1731.83  4319.8 1729.18
  4429.8 1725.28  4609.9 1721.66  4709.9 1720.71  4913.2 1720.77  4939.9 1721.08
  4949.9 1721.86  4979.9 1721.27  4989.9 1719.74  4996.9 1716.64  4999.6 1716.14
  5002.9 1716.64  5019.9 1720.93  5059.9 1720.57  5099.9 1721.99  5149.5 1720.76
  5209.9  1720.5  5259.9 1721.83  5289.9 1721.48  5349.9 1724.37  5419.9 1726.55
  5459.9 1727.03  5529.9  1726.5  5559.9 1725.43    5650 1724.14  5666.2 1724.85
#Mann= 5 ,-1 , 0
  4118.7     .05       0  4913.2      .1       0  4996.9     .07       0
  5002.9      .1       0  5149.5     .05       0
Bank Sta=4996.9,5002.9
XS Rating Curve= 0 ,0
Exp/Cntr=0.3,0.1

Type RM Length L Ch R = 1 ,21506   ,580,580,580
BEGIN DESCRIPTION:
KIEHNE CREEK 30.0
END DESCRIPTION:
XS GIS Cut Line= 3
      2787185.34     10082321.85      2786588.16     10082419.06
      2786039.56     10082731.56
#Sta/Elev= 30
  4295.9 1718.49  4323.1 1718.85  4338.5 1719.75  4354.1 1719.44  4383.9 1718.29
  4434.6 1714.14  4485.2 1711.72  4523.1 1710.61  4556.2 1710.34  4779.3 1713.68
  4870.2  1713.2  4899.9 1713.98  4919.2 1713.43  4969.6 1714.22    4984 1713.09
  4987.3 1711.98  4999.9 1707.52  5002.6 1707.26  5005.4 1706.76  5008.6 1707.26
  5021.5 1713.59  5027.2 1714.09  5083.6 1713.75  5096.2 1713.78  5123.8  1715.6
  5139.6 1715.39  5235.2 1718.77  5365.8 1722.02  5468.1    1722  5532.3 1721.07
#Mann= 7 ,-1 , 0
  4295.9     .16       0  4354.1      .1       0  4987.3     .05       0
  5002.6    .035       0  5008.6     .05       0  5083.6      .1       0
  5235.2     .05       0
Bank Sta=5002.6,5008.6
XS Rating Curve= 0 ,0
Exp/Cntr=0.3,0.1

Type RM Length L Ch R = 1 ,20926   ,870,870,870
BEGIN DESCRIPTION:
KIEHNE CREEK 29.0
END DESCRIPTION:
XS GIS Cut Line= 5
      2787084.06     10082235.29       2786489.4     10081992.22
      2786324.47     10081953.16      2786048.86     10082048.64
      2785988.17     10082549.38
#Sta/Elev= 30
  4127.7 1713.89  4155.4 1711.42  4195.5 1711.49  4254.4 1709.46    4273 1709.61
  4278.4 1708.81  4295.8 1709.19  4331.8 1708.23  4593.6 1707.12  4738.7 1708.58
  4870.4 1705.89  4912.6 1706.59    4954  1705.5  4977.7 1706.31  4985.1 1705.16
  4998.9 1701.02  5006.5 1701.01  5009.2 1700.51  5012.5 1701.01    5019 1704.53
  5021.5 1705.48  5030.6 1705.64  5047.4 1704.74  5062.4 1705.54  5135.6 1704.54
  5225.1 1705.97  5337.2 1707.49  5367.4 1708.75  5560.4 1712.63  5735.7  1716.7
#Mann= 6 ,-1 , 0
  4127.7      .1       0  5006.5     .07       0  5012.5      .1       0
    5019     .05       0  5225.1     .16       0  5560.4     .05       0
Bank Sta=5006.5,5012.5
XS Rating Curve= 0 ,0
Exp/Cntr=0.3,0.1

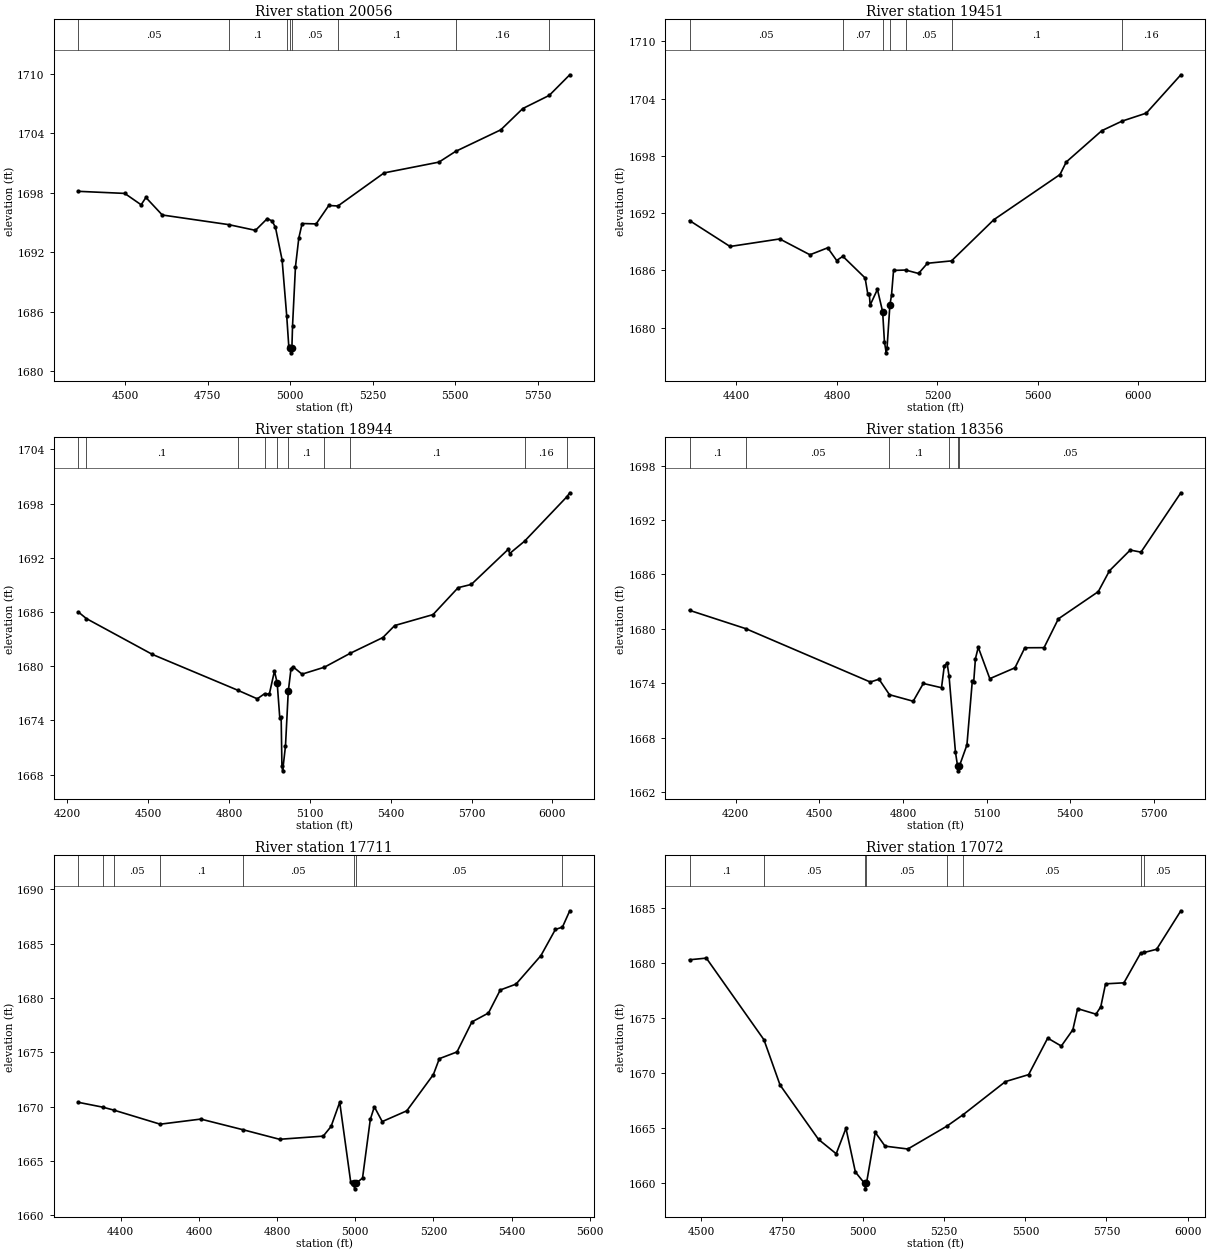
Type RM Length L Ch R = 1 ,20056   ,605,605,605
BEGIN DESCRIPTION:
KIEHNE CREEK 27.0
END DESCRIPTION:
XS GIS Cut Line= 4
      2786762.82     10081566.71      2786363.53     10081247.28
      2786040.61     10081202.14      2785687.09     10081749.75
#Sta/Elev= 30
    4358 1698.15  4498.4 1697.94  4548.1 1696.79  4562.5 1697.53  4612.1 1695.76
    4813 1694.79  4894.6 1694.21  4930.5  1695.4  4945.1 1695.15  4955.2 1694.51
  4975.4 1691.21  4989.3 1685.58  4995.6 1682.49    4999 1682.34  5001.7 1681.84
    5005 1682.34    5007 1684.59  5015.8 1690.52  5025.9 1693.42    5036  1694.9
  5078.5 1694.86  5116.8 1696.72  5144.5 1696.67  5284.4 1700.01  5450.7  1701.1
    5501 1702.18  5638.1 1704.36  5704.8 1706.51  5785.1 1707.84  5847.2 1709.92
#Mann= 8 ,-1 , 0
    4358     .05       0    4813      .1       0  4989.3     .05       0
    4999     .04       0    5005     .05       0  5144.5      .1       0
    5501     .16       0  5785.1      .1       0
Bank Sta=4999,5005
XS Rating Curve= 0 ,0
Exp/Cntr=0.3,0.1

Type RM Length L Ch R = 1 ,19451   ,507,507,507
BEGIN DESCRIPTION:
Mapping XS 460f1cba
END DESCRIPTION:
XS GIS Cut Line= 4
      2786728.14     10081111.89      2786238.53      10080594.5
      2785985.06     10080792.42      2785665.62     10081656.98
#Sta/Elev= 30
    4213 1691.23  4374.3 1688.51  4572.1  1689.3  4692.3 1687.64  4763.1 1688.37
  4798.7 1687.04  4823.3 1687.48  4911.9 1685.21  4922.4 1683.56  4928.5 1683.56
    4932 1682.37  4960.9 1684.01  4981.7 1681.67  4988.8 1678.53  4995.9 1677.36
  4999.2 1677.86  5010.7 1682.42    5017 1683.39  5025.1    1686  5073.2 1686.04
  5124.6 1685.68  5159.9 1686.75  5255.8    1687  5424.4 1691.32  5687.5 1696.05
  5712.6 1697.37    5854 1700.65  5934.4 1701.65  6031.2 1702.49  6168.6 1706.51
#Mann= 7 ,-1 , 0
    4213     .05       0  4823.3     .07       0  4981.7     .05       0
  5010.7     .07       0  5073.2     .05       0  5255.8      .1       0
  5934.4     .16       0
Bank Sta=4981.7,5010.7
XS Rating Curve= 0 ,0
Exp/Cntr=0.3,0.1

Type RM Length L Ch R = 1 ,18944   ,588,588,588
BEGIN DESCRIPTION:
Mapping XS 851508d0
END DESCRIPTION:
XS GIS Cut Line= 4
      2786394.76     10080552.83      2786037.14     10080462.56
        2785742.     10080452.14      2785495.48     10081584.05
#Sta/Elev= 30
  4241.8 1685.99  4271.3 1685.27  4516.4  1681.3  4832.9 1677.34  4905.2 1676.39
  4932.1 1676.95  4949.9  1676.9    4969 1679.47  4979.2 1678.12  4988.7 1674.29
  4993.8 1674.37  4996.7 1668.92  4999.4 1668.42  5009.9 1671.18  5020.2  1677.2
  5030.4 1679.72  5037.8 1679.94  5071.3 1679.12  5154.3 1679.89  5248.9 1681.41
  5371.1 1683.17  5415.1  1684.5  5557.2 1685.71  5650.3 1688.69  5699.3 1689.05
  5836.4 1692.94  5841.5 1692.47  5896.6 1693.83    6054 1698.76  6064.4 1699.19
#Mann= 10 ,-1 , 0
  4241.8     .05       0  4271.3      .1       0  4832.9     .05       0
  4932.1      .1       0  4979.2     .07       0  5020.2      .1       0
  5154.3     .05       0  5248.9      .1       0  5896.6     .16       0
    6054      .1       0
Bank Sta=4979.2,5020.2
XS Rating Curve= 0 ,0
Exp/Cntr=0.3,0.1

Type RM Length L Ch R = 1 ,18356   ,645,645,645
BEGIN DESCRIPTION:
KIEHNE CREEK 25.0
END DESCRIPTION:
XS GIS Cut Line= 4
      2786241.96     10080441.71      2785557.98     10080247.28
      2785231.59     10080302.84      2784578.77     10080604.94
#Sta/Elev= 30
  4034.8 1682.04  4236.3 1680.02    4683 1674.13  4714.2 1674.44  4751.7 1672.73
  4836.7 1672.01    4873 1673.97  4938.3  1673.5  4948.3 1675.93  4958.4  1676.2
  4965.3 1674.78  4988.3 1666.38    4996 1664.83  4998.7 1664.33    5002 1664.83
  5029.4 1667.19  5048.6 1674.22  5053.6  1674.1  5059.8  1676.7    5070 1677.96
  5111.4  1674.5  5201.6  1675.7    5237 1677.91  5305.8 1677.92  5357.2  1681.1
  5500.2  1684.1  5540.5 1686.41  5614.8 1688.69  5653.4 1688.46  5796.3 1695.01
#Mann= 6 ,-1 , 0
  4034.8      .1       0  4236.3     .05       0  4751.7      .1       0
  4965.3     .05       0    4996    .035       0    5002     .05       0
Bank Sta=4996,5002
XS Rating Curve= 0 ,0
Exp/Cntr=0.3,0.1

Type RM Length L Ch R = 1 ,17711   ,639,639,639
BEGIN DESCRIPTION:
KIEHNE CREEK 24.0
END DESCRIPTION:
XS GIS Cut Line= 3
      2785977.01     10079953.76      2785463.16     10079641.29
       2784811.9      10079717.5
#Sta/Elev= 30
  4291.6  1670.4  4353.4 1669.96  4381.8 1669.69  4500.8 1668.39  4604.6 1668.86
  4712.6 1667.88  4806.2    1667  4917.9 1667.29    4938 1668.18  4960.1 1670.41
  4988.3 1663.05  4995.4 1662.94  4998.2 1662.44  5001.4 1662.94  5018.5 1663.43
  5038.4 1668.83  5048.7 1669.99  5068.9 1668.63  5131.7 1669.62  5199.8 1672.96
    5215 1674.42  5260.2 1675.04  5298.3  1677.8  5340.7 1678.62  5370.9 1680.74
  5411.2 1681.28    5475 1683.91  5511.9 1686.31    5530 1686.53  5548.7 1688.03
#Mann= 8 ,-1 , 0
  4291.6     .05       0  4353.4      .1       0  4381.8     .05       0
  4500.8      .1       0  4712.6     .05       0  4995.4    .035       0
  5001.4     .05       0    5530      .1       0
Bank Sta=4995.4,5001.4
XS Rating Curve= 0 ,0
Exp/Cntr=0.3,0.1

Type RM Length L Ch R = 1 ,17072   ,699,699,699
BEGIN DESCRIPTION:
KIEHNE CREEK 22.0
END DESCRIPTION:
XS GIS Cut Line= 3
      2785859.01     10078974.62      2784970.11     10079051.01
      2784608.99     10079557.96
#Sta/Elev= 30
  4464.6 1680.27  4516.5 1680.42  4694.1 1673.02  4743.7 1668.92  4862.3 1663.99
  4916.8 1662.69  4946.9    1665  4975.9 1661.04  5004.1 1660.01  5006.9 1659.51
  5010.1 1660.01  5037.2 1664.62  5067.4 1663.38  5137.6 1663.12  5257.4 1665.18
    5308 1666.23  5438.5 1669.23  5509.9 1669.86  5568.8 1673.17  5610.7 1672.45
  5646.3 1673.93  5661.1 1675.84  5717.6 1675.34  5732.4 1676.01  5747.1 1678.09
  5803.7 1678.18  5855.6 1680.89  5866.1 1680.93  5904.5 1681.22  5979.2 1684.71
#Mann= 8 ,-1 , 0
  4464.6      .1       0  4694.1     .05       0  5004.1    .035       0
  5010.1     .05       0  5257.4      .1       0    5308     .05       0
  5855.6      .1       0  5866.1     .05       0
Bank Sta=5004.1,5010.1
XS Rating Curve= 0 ,0
Exp/Cntr=0.3,0.1

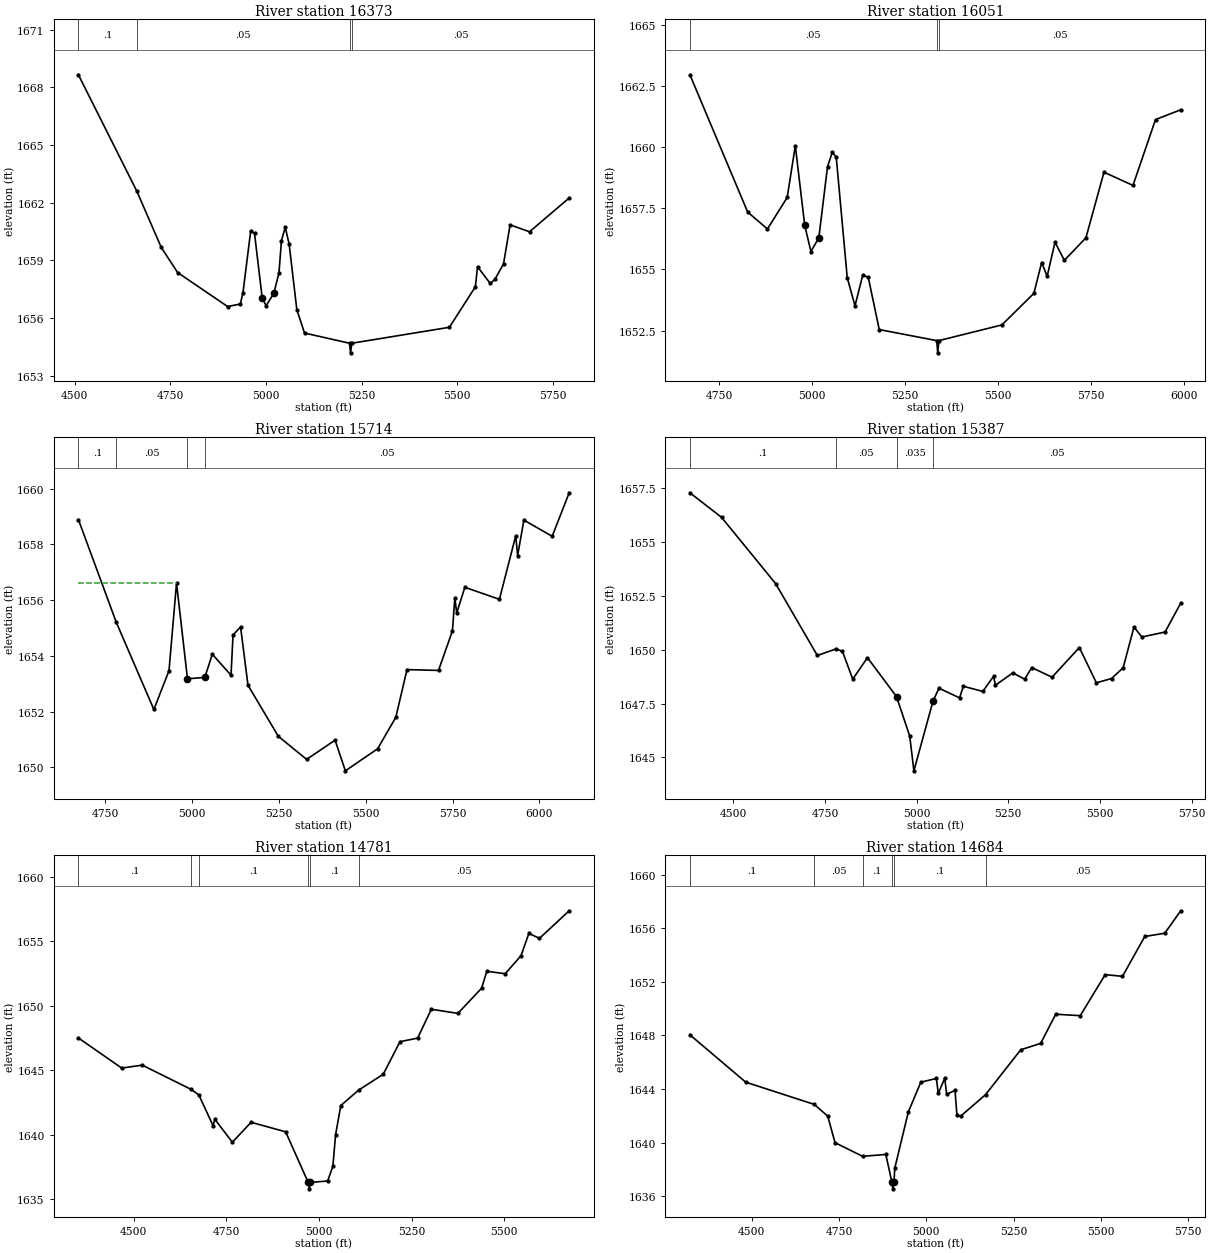
Type RM Length L Ch R = 1 ,16373   ,322,322,322
BEGIN DESCRIPTION:
KIEHNE CREEK 21.0
END DESCRIPTION:
XS GIS Cut Line= 3
      2785796.54     10078287.11      2784886.77      10078377.4
      2784727.51     10078709.77
#Sta/Elev= 30
  4509.6 1668.65  4662.4 1662.59  4726.1 1659.67  4768.9 1658.36  4899.6 1656.59
  4932.9 1656.72  4939.8 1657.32  4959.9 1660.52  4969.9  1660.4    4990 1657.04
  5000.1 1656.63  5020.2 1657.27  5033.8 1658.33  5040.3 1660.02  5050.3 1660.71
  5060.4 1659.84  5080.5 1656.43  5100.6 1655.21  5218.2 1654.68  5220.9 1654.18
  5224.2 1654.68  5479.3 1655.51  5547.2 1657.62  5552.8 1658.66  5586.1 1657.79
  5598.1    1658  5620.8 1658.81  5637.9 1660.84  5688.7 1660.48  5792.4 1662.24
#Mann= 4 ,-1 , 0
  4509.6      .1       0  4662.4     .05       0  5218.2    .035       0
  5224.2     .05       0
#XS Ineff= 2 , 0
       0                 5046.22       0 1656.61
Permanent Ineff=
       F       T
Bank Sta=4990,5020.2
XS Rating Curve= 0 ,0
Exp/Cntr=0.3,0.1

Type RM Length L Ch R = 1 ,16051   ,337,337,337
BEGIN DESCRIPTION:
Mapping XS eccfb730
END DESCRIPTION:
XS GIS Cut Line= 4
      2785594.72     10077903.97      2785234.48     10078034.17
      2784752.71     10078374.89      2784657.28      10078708.9
#Sta/Elev= 30
  4670.7 1662.95  4826.2 1657.34  4879.4 1656.65  4932.5 1657.94  4954.3 1660.05
  4979.6  1656.8  4996.3 1655.73  5017.6 1656.29    5041  1659.2  5053.7 1659.78
  5064.4 1659.59    5094 1654.66  5114.9 1653.51  5135.8 1654.77  5150.6 1654.67
  5180.2 1652.54  5334.7 1652.09  5337.5 1651.59  5340.7 1652.09    5510 1652.73
  5596.2 1654.02  5617.1 1655.28  5631.9 1654.72    5653 1656.11  5678.2 1655.37
  5736.2 1656.29  5784.8 1658.97  5862.8 1658.43  5923.4 1661.12  5991.2 1661.52
#Mann= 3 ,-1 , 0
  4670.7     .05       0  5334.7    .035       0  5340.7     .05       0
#XS Ineff= 2 , 0
       0                 5052.44       0 1655.81
Permanent Ineff=
       F       T
Bank Sta=4979.6,5017.6
XS Rating Curve= 0 ,0
Exp/Cntr=0.3,0.1

Type RM Length L Ch R = 1 ,15714   ,327,327,327
BEGIN DESCRIPTION:
Mapping XS 4c63f190
END DESCRIPTION:
XS GIS Cut Line= 3
      2785342.96     10077613.18      2784924.15     10077845.37
      2784553.28     10078702.07
#Sta/Elev= 30
  4673.4 1658.89  4782.6  1655.2  4890.6 1652.08  4934.1 1653.47  4955.8 1656.61
  4987.3 1653.18  5037.1 1653.23  5058.8 1654.06  5112.6 1653.31  5118.4 1654.75
  5140.1 1655.04  5161.4 1652.95  5248.6 1651.12  5330.2 1650.29    5412 1650.98
  5441.7 1649.88  5534.4 1650.67  5586.9  1651.8    5619 1653.51  5709.7 1653.48
  5749.8  1654.9  5756.7 1656.08  5762.1 1655.54  5785.6 1656.46    5885 1656.03
    5932 1658.31  5937.4  1657.6  5955.4 1658.87  6036.8 1658.29  6085.8 1659.85
#Mann= 4 ,-1 , 0
  4673.4      .1       0  4782.6     .05       0  4987.3    .035       0
  5037.1     .05       0
#XS Ineff= 2 , 0
       0 4955.56 1656.61 5139.43       0  1653.3
Permanent Ineff=
       T       T
Bank Sta=4987.3,5037.1
XS Rating Curve= 0 ,0
Exp/Cntr=0.3,0.1

Type RM Length L Ch R = 1 ,15387   ,606,606,606
BEGIN DESCRIPTION:
KIEHNE CREEK 20.0
END DESCRIPTION:
XS GIS Cut Line= 3
      2785296.53      10077349.6      2784782.61     10077592.67
      2784581.21     10078335.76
#Sta/Elev= 30
  4381.8  1657.3    4468 1656.16  4615.6 1653.08  4729.3 1649.74  4779.5 1650.04
  4797.6 1649.94  4825.9 1648.64  4865.9 1649.64  4945.2 1647.83  4981.3 1645.99
  4992.6 1644.38  5044.6 1647.61  5060.9 1648.22  5117.2 1647.77  5127.5 1648.31
  5180.4 1648.07  5209.9 1648.77  5215.1 1648.36  5262.2 1648.93  5294.8 1648.64
    5314 1649.18  5369.3 1648.73  5443.8 1650.11  5490.2 1648.47  5531.6 1648.67
  5563.3 1649.17  5592.7 1651.06  5614.5  1650.6  5677.6 1650.83  5720.2 1652.17
#Mann= 4 ,-1 , 0
  4381.8      .1       0  4779.5     .05       0  4945.2    .035       0
  5044.6     .05       0
Bank Sta=4945.2,5044.6
XS Rating Curve= 0 ,0
Exp/Cntr=0.3,0.1

Type RM Length L Ch R = 1 ,14781   ,97,97,97
BEGIN DESCRIPTION:
Mapping XS acf20cd3
END DESCRIPTION:
XS GIS Cut Line= 5
      2784878.55     10077239.91      2784370.77     10077322.37
      2784194.98      10077487.3      2784166.77     10077545.89
      2783778.28      10077867.1
#Sta/Elev= 30
  4350.8  1647.5  4467.8 1645.16  4523.1 1645.39  4654.7 1643.51    4676 1643.07
  4714.2 1640.69  4719.2 1641.18  4766.3  1639.4  4816.9 1640.95  4910.1 1640.21
    4971 1636.28  4973.8 1635.78    4977 1636.28  5023.4 1636.39  5037.6 1637.53
  5044.9 1639.98    5059 1642.25  5107.6 1643.46  5173.5 1644.68  5218.7 1647.21
  5266.4 1647.49  5303.3 1649.73    5375 1649.41  5438.8 1651.36  5453.2 1652.68
  5502.7 1652.49  5545.4 1653.89  5566.5 1655.62  5595.2 1655.24  5675.4 1657.38
#Mann= 6 ,-1 , 0
  4350.8      .1       0  4654.7     .05       0    4676      .1       0
    4971     .07       0    4977      .1       0  5107.6     .05       0
Bank Sta=4971,4977
XS Rating Curve= 0 ,0
Exp/Cntr=0.3,0.1

Type RM Length L Ch R = 1 ,14684   ,56,56,56
BEGIN DESCRIPTION:
KIEHNE CREEK 18.0
END DESCRIPTION:
XS GIS Cut Line= 6
       2784898.1     10077213.86       2784622.5     10077194.33
      2784292.64     10077287.65      2784225.37     10077335.39
      2784147.24     10077526.36      2783765.27     10077845.39
#Sta/Elev= 30
  4323.2 1648.05  4483.2 1644.51  4679.4 1642.85    4718 1641.97  4738.8 1639.99
  4817.8 1638.97  4884.3 1639.11  4901.7 1637.04  4904.5 1636.54  4907.7 1637.04
  4909.9 1638.08  4948.9  1642.3  4984.5 1644.51  5029.1 1644.79  5034.5 1643.67
  5053.1 1644.81  5058.5  1643.6  5082.5  1643.9  5087.9 1642.07  5098.6 1641.97
  5169.9 1643.58  5270.6 1646.93  5327.8 1647.41  5370.8 1649.59  5441.1 1649.48
  5512.6 1652.55  5562.1 1652.42  5625.9  1655.4  5683.1 1655.64  5728.8 1657.32
#Mann= 6 ,-1 , 0
  4323.2      .1       0  4679.4     .05       0  4817.8      .1       0
  4901.7     .07       0  4907.7      .1       0  5169.9     .05       0
Bank Sta=4901.7,4907.7
XS Rating Curve= 0 ,0
Exp/Cntr=0.3,0.1

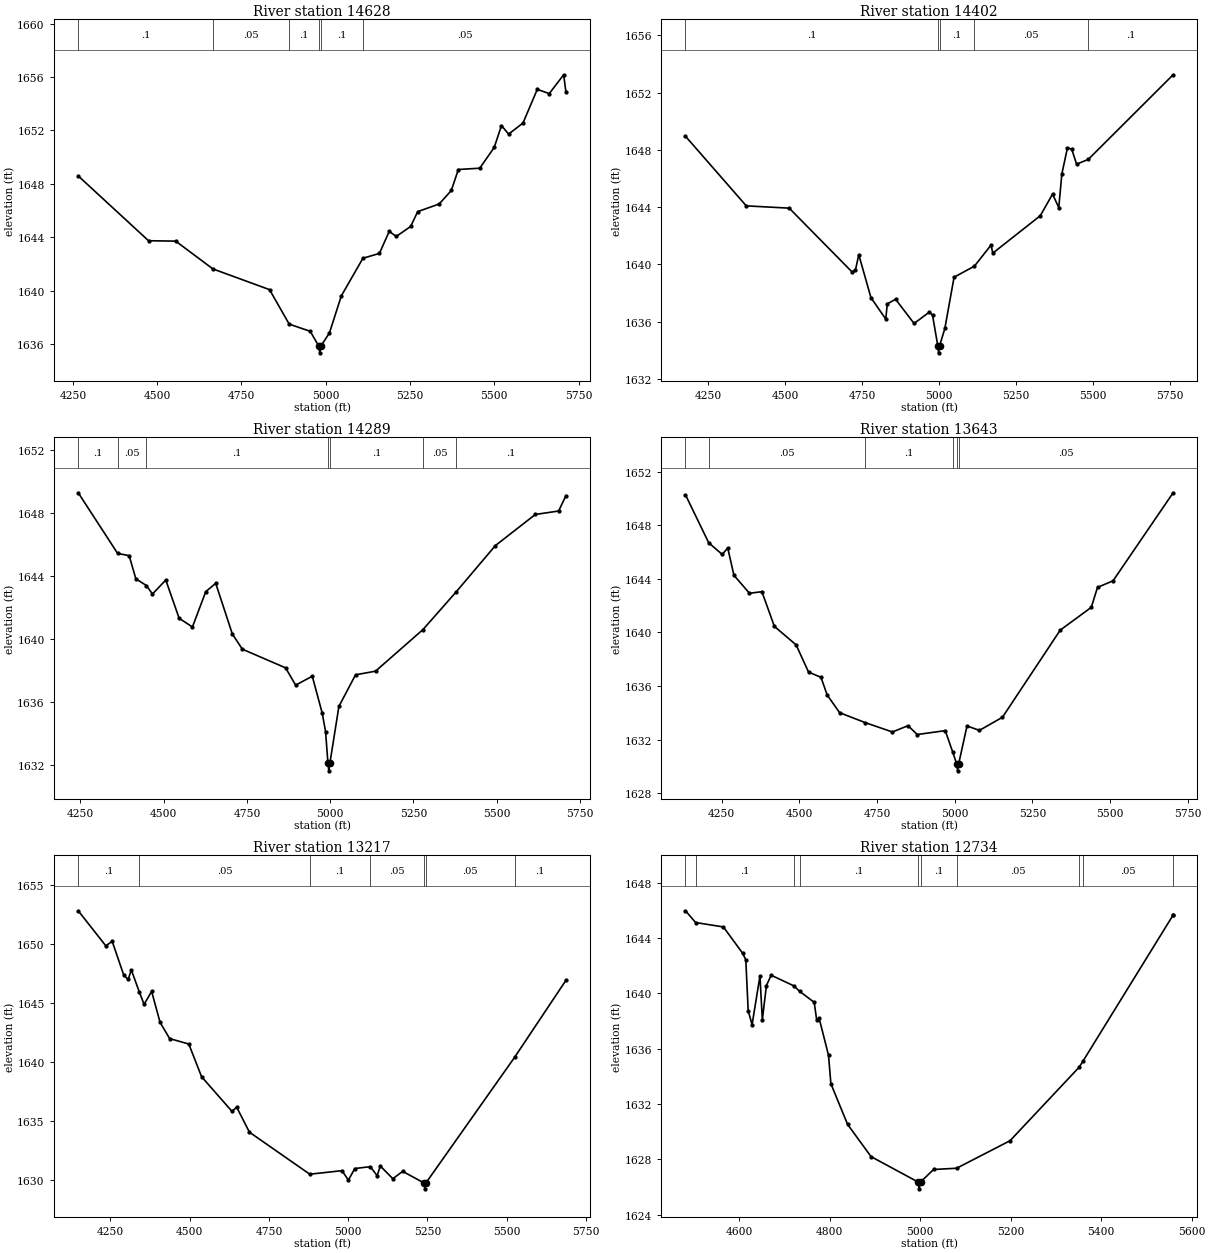
Type RM Length L Ch R = 1 ,14628   ,226,226,226
BEGIN DESCRIPTION:
Mapping XS 222c6acc
END DESCRIPTION:
XS GIS Cut Line= 5
      2784915.52     10077205.19      2784500.97     10077155.27
      2784364.25     10077150.93      2784097.33     10077380.96
      2783742.54     10077787.67
#Sta/Elev= 30
  4265.9  1648.6  4474.4 1643.75    4555 1643.72  4665.3 1641.64  4833.3 1640.09
  4891.6 1637.51    4954 1636.97  4979.5 1635.86  4982.3 1635.36  4985.5 1635.86
    5011 1636.85  5046.2 1639.62  5110.3 1642.44  5159.2  1642.8  5188.3 1644.45
  5209.2 1644.07  5251.9 1644.82  5272.8 1645.93  5336.4  1646.5  5372.5 1647.51
  5393.3 1649.08  5456.9 1649.18  5499.7 1650.73  5521.3 1652.37  5542.4 1651.73
  5585.1 1652.56  5627.5 1655.08  5662.9 1654.76  5705.7 1656.17  5712.3  1654.9
#Mann= 6 ,-1 , 0
  4265.9      .1       0  4665.3     .05       0  4891.6      .1       0
  4979.5     .07       0  4985.5      .1       0  5110.3     .05       0
Bank Sta=4979.5,4985.5
XS Rating Curve= 0 ,0
Exp/Cntr=0.3,0.1

Type RM Length L Ch R = 1 ,14402   ,113,113,113
BEGIN DESCRIPTION:
Mapping XS 0c3c302f
END DESCRIPTION:
XS GIS Cut Line= 4
      2784937.17     10077192.16      2784381.62     10077066.29
       2783706.7     10077085.82      2783414.32     10077259.09
#Sta/Elev= 30
  4175.2 1648.95  4372.8 1644.09  4512.4 1643.93  4717.3 1639.46  4727.6 1639.61
  4738.4 1640.68    4778 1637.68  4826.1 1636.19  4831.1 1637.25    4858 1637.57
  4918.1 1635.88  4968.1 1636.68  4978.1 1636.46  4995.1 1634.33  4997.8 1633.83
  5001.1 1634.33  5018.1 1635.53  5048.1 1639.11  5114.2 1639.88  5168.2 1641.35
    5174 1640.79  5328.2  1643.4  5368.2 1644.91  5388.3 1643.97  5398.3 1646.31
  5416.6 1648.15  5430.6 1648.04  5446.2    1647  5484.1 1647.33  5759.9 1653.24
#Mann= 5 ,-1 , 0
  4175.2      .1       0  4995.1     .07       0  5001.1      .1       0
  5114.2     .05       0  5484.1      .1       0
Bank Sta=4995.1,5001.1
XS Rating Curve= 0 ,0
Exp/Cntr=0.3,0.1

Type RM Length L Ch R = 1 ,14289   ,646,646,646
BEGIN DESCRIPTION:
KIEHNE CREEK 17.0
END DESCRIPTION:
XS GIS Cut Line= 2
      2784941.47     10076988.17      2783476.68     10076981.66
#Sta/Elev= 30
  4243.3  1649.3  4361.7 1645.44  4396.3  1645.3  4416.3 1643.83    4448  1643.4
  4466.3 1642.86  4506.3 1643.75  4546.3 1641.32  4586.3 1640.76  4626.3 1643.01
  4656.3 1643.54  4706.3 1640.31  4736.3 1639.35  4866.3 1638.16  4896.3 1637.06
  4946.3 1637.63  4976.3 1635.27  4986.3 1634.09  4993.3 1632.11  4996.1 1631.61
  4999.3 1632.11  5026.3 1635.71  5076.3 1637.72  5136.3 1637.95  5278.9  1640.6
  5377.5 1642.97  5496.3 1645.94  5616.3 1647.92  5686.3 1648.14  5708.1 1649.11
#Mann= 7 ,-1 , 0
  4243.3      .1       0  4361.7     .05       0    4448      .1       0
  4993.3     .07       0  4999.3      .1       0  5278.9     .05       0
  5377.5      .1       0
Bank Sta=4993.3,4999.3
XS Rating Curve= 0 ,0
Exp/Cntr=0.3,0.1

Type RM Length L Ch R = 1 ,13643   ,426,426,426
BEGIN DESCRIPTION:
KIEHNE CREEK 16.0
END DESCRIPTION:
XS GIS Cut Line= 2
      2784914.55     10076391.29      2783345.14     10076356.56
#Sta/Elev= 30
  4133.1 1650.27  4207.9 1646.69  4251.4 1645.82  4269.2  1646.3  4289.2 1644.26
  4339.2 1642.92  4379.2 1643.04  4419.3 1640.45  4489.3 1639.07  4529.3 1637.04
  4569.3 1636.65  4589.3 1635.33  4629.3 1634.01  4711.5 1633.27  4799.3 1632.57
  4849.4 1633.04  4879.4 1632.38  4969.4 1632.67  4993.3 1631.08  5006.4 1630.17
  5009.1 1629.67  5012.4 1630.17  5039.4 1633.02  5079.4 1632.69  5153.6 1633.67
  5339.5 1640.17  5439.5 1641.87  5459.5 1643.36  5509.5 1643.85  5702.9 1650.42
#Mann= 6 ,-1 , 0
  4133.1      .1       0  4207.9     .05       0  4711.5      .1       0
  4993.3     .05       0  5006.4    .035       0  5012.4     .05       0
Bank Sta=5006.4,5012.4
XS Rating Curve= 0 ,0
Exp/Cntr=0.3,0.1

Type RM Length L Ch R = 1 ,13217   ,483,483,483
BEGIN DESCRIPTION:
KIEHNE CREEK 15.0
END DESCRIPTION:
XS GIS Cut Line= 2
      2785004.83     10076085.73      2783477.06     10075905.18
#Sta/Elev= 30
  4148.3 1652.83  4235.3 1649.86  4255.4 1650.24  4291.9 1647.38  4305.8 1647.01
  4315.8 1647.82  4341.2 1645.93  4356.1  1644.9  4379.8    1646  4406.4 1643.38
  4436.7    1642  4497.1 1641.54  4537.4 1638.77  4633.5 1635.83  4648.1 1636.19
  4688.4 1634.07  4878.7 1630.51  4980.4 1630.81  5000.6 1630.01  5020.7 1630.99
  5069.8 1631.15  5091.2 1630.38  5101.3  1631.2  5140.8 1630.13  5171.7 1630.75
  5239.2 1629.77    5242 1629.27  5245.2 1629.77  5524.8 1640.41  5686.7 1646.93
#Mann= 7 ,-1 , 0
  4148.3      .1       0  4341.2     .05       0  4878.7      .1       0
  5069.8     .05       0  5239.2     .07       0  5245.2     .05       0
  5524.8      .1       0
Bank Sta=5239.2,5245.2
XS Rating Curve= 0 ,0
Exp/Cntr=0.3,0.1

Type RM Length L Ch R = 1 ,12734   ,371,371,371
BEGIN DESCRIPTION:
KIEHNE CREEK 14.0
END DESCRIPTION:
XS GIS Cut Line= 2
      2784497.91     10075405.16      2783477.05      10075752.4
#Sta/Elev= 30
  4480.7 1645.97  4503.2 1645.12  4564.6  1644.8  4606.9 1642.91  4614.1 1642.43
  4619.4 1638.74    4628 1637.73  4645.4 1641.25  4650.7 1638.09  4659.7 1640.56
  4670.2 1641.31  4719.7 1640.55  4733.4 1640.14  4765.3 1639.35  4770.9 1638.07
  4776.2 1638.21    4797 1635.52  4802.3 1633.46  4839.2 1630.52  4891.1 1628.19
  4994.7 1626.36  4997.4 1625.86  5000.7 1626.36  5029.4 1627.26  5080.3 1627.35
  5198.4 1629.34  5351.3 1634.66  5359.4 1635.08  5558.6 1645.64    5559 1645.64
#Mann= 10 ,-1 , 0
  4480.7     .05       0  4503.2      .1       0  4719.7     .05       0
  4733.4      .1       0  4994.7     .07       0  5000.7      .1       0
  5080.3     .05       0  5351.3      .1       0  5359.4     .05       0
  5558.6      .1       0
Bank Sta=4994.7,5000.7
XS Rating Curve= 0 ,0
Exp/Cntr=0.3,0.1