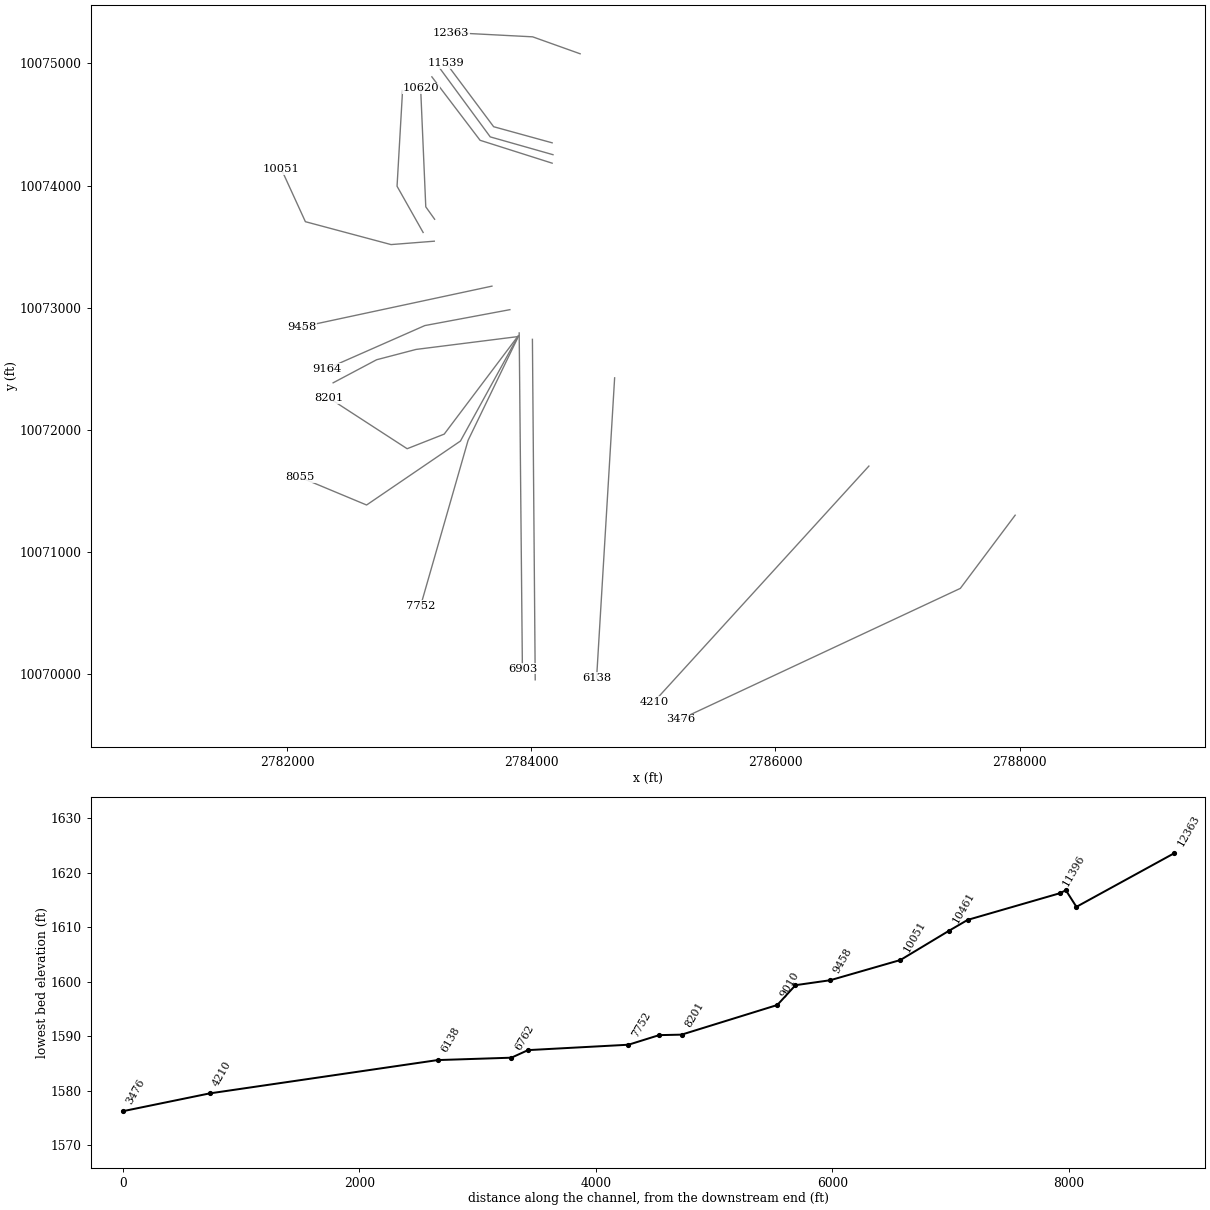
HEC-RAS study KIEHNE CREEK.prj: KIEHNE CREEK Base Level Engineering

--- KIEHNE CREEK.g01 (geometry) --- (continued)

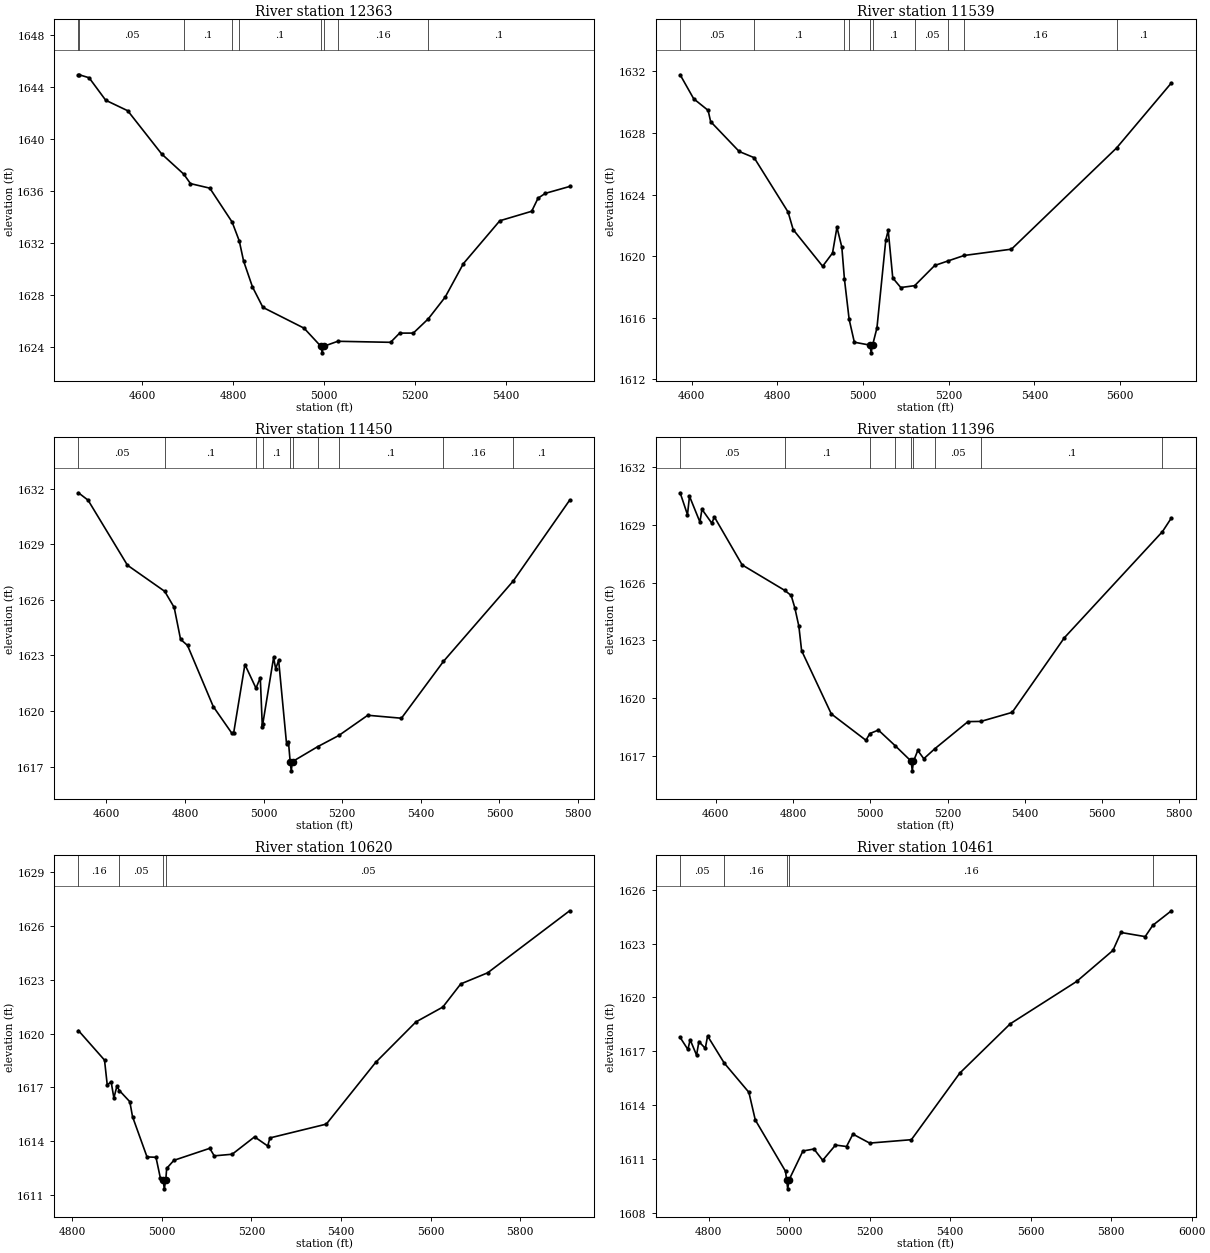
Type RM Length L Ch R = 1 ,12363   ,824,824,824
BEGIN DESCRIPTION:
KIEHNE CREEK 13.0
END DESCRIPTION:
XS GIS Cut Line= 3
      2784400.62      10075078.8      2784011.77     10075217.67
      2783345.08      10075252.4
#Sta/Elev= 30
  4460.1 1644.95  4462.1 1644.95  4483.6 1644.72  4520.1 1642.99  4568.6 1642.18
  4643.3 1638.85  4691.8  1637.3  4706.6 1636.57  4749.1 1636.22  4798.2 1633.61
  4813.9 1632.16  4823.4 1630.61  4842.9 1628.62  4865.9 1627.04  4956.4 1625.44
  4993.5 1624.04  4996.2 1623.54  4999.5 1624.04  5030.6 1624.43  5146.7 1624.35
  5166.7 1625.06  5196.7 1625.06  5229.7 1626.16  5266.8 1627.83  5306.9 1630.41
    5387 1633.71  5457.1 1634.44  5471.1 1635.45  5487.1 1635.82  5540.6 1636.35
#Mann= 9 ,-1 , 0
  4460.1      .1       0  4462.1     .05       0  4691.8      .1       0
  4798.2     .16       0  4813.9      .1       0  4993.5     .07       0
  4999.5      .1       0  5030.6     .16       0  5229.7      .1       0
Bank Sta=4993.5,4999.5
XS Rating Curve= 0 ,0
Exp/Cntr=0.3,0.1

Type RM Length L Ch R = 1 ,11539   ,89,89,89
BEGIN DESCRIPTION:
Mapping XS 2b60eda2
END DESCRIPTION:
XS GIS Cut Line= 3
      2784171.45     10074349.63      2783692.33     10074481.56
      2783303.47     10075002.35
#Sta/Elev= 30
  4572.8 1631.78  4604.5 1630.22  4638.1 1629.47    4644 1628.74  4710.7  1626.8
  4745.5  1626.4  4824.8 1622.87  4836.7 1621.73  4905.5 1619.35  4928.6 1620.21
  4938.9 1621.88  4950.3 1620.59  4956.4 1618.51  4967.4  1615.9  4979.5 1614.42
  5016.1 1614.23  5018.8 1613.73  5022.1 1614.23  5032.3 1615.35    5053 1621.07
  5058.6 1621.68  5069.2 1618.59  5087.9 1617.97  5120.3 1618.09  5167.1  1619.4
  5198.7  1619.7  5235.8 1620.05  5346.4 1620.46  5591.8 1627.03  5719.7 1631.25
#Mann= 10 ,-1 , 0
  4572.8     .05       0  4745.5      .1       0  4956.4     .05       0
  4967.4      .1       0  5016.1     .07       0  5022.1      .1       0
  5120.3     .05       0  5198.7      .1       0  5235.8     .16       0
  5591.8      .1       0
Bank Sta=5016.1,5022.1
XS Rating Curve= 0 ,0
Exp/Cntr=0.3,0.1

Type RM Length L Ch R = 1 ,11450   ,54,54,54
BEGIN DESCRIPTION:
Mapping XS 799ee698
END DESCRIPTION:
XS GIS Cut Line= 3
      2784178.41      10074252.4      2783664.55     10074398.23
      2783240.92     10074974.65
#Sta/Elev= 30
    4529 1631.78  4553.6 1631.38  4653.7 1627.87  4748.5 1626.46  4772.6 1625.59
  4788.8 1623.87  4806.5 1623.54    4872 1620.24  4918.6 1618.82    4924 1618.83
  4952.5 1622.51  4980.7 1621.23  4991.6  1621.8  4996.8 1619.15  4997.8 1619.28
  5025.5 1622.89  5030.7 1622.28  5038.3 1622.73  5058.5 1618.21  5063.2 1618.35
  5067.6 1617.27  5070.3 1616.77  5073.6 1617.27  5137.2 1618.07  5191.5 1618.68
    5265 1619.77  5350.6 1619.61  5457.6 1622.68  5635.1 1627.02  5778.5 1631.38
#Mann= 10 ,-1 , 0
    4529     .05       0  4748.5      .1       0  4980.7     .05       0
  4997.8      .1       0  5067.6     .07       0  5073.6      .1       0
  5137.2     .05       0  5191.5      .1       0  5457.6     .16       0
  5635.1      .1       0
Bank Sta=5067.6,5073.6
XS Rating Curve= 0 ,0
Exp/Cntr=0.3,0.1

Type RM Length L Ch R = 1 ,11396   ,776,776,776
BEGIN DESCRIPTION:
KIEHNE CREEK 12.0
END DESCRIPTION:
XS GIS Cut Line= 3
      2784171.48     10074182.96      2783581.22     10074370.45
      2783186.36     10074890.01
#Sta/Elev= 30
  4507.5 1630.67  4526.5 1629.53  4531.7 1630.49  4558.7 1629.15    4564 1629.81
  4589.4 1629.09  4596.2 1629.41    4668 1626.92  4777.8  1625.6    4795 1625.33
  4804.4 1624.69  4814.9 1623.73    4822 1622.46  4898.9 1619.17  4988.5  1617.8
  4998.7 1618.15  5020.8 1618.33  5064.6 1617.51  5105.7 1616.71  5108.5 1616.21
  5111.7 1616.71  5122.8 1617.27  5138.4 1616.84  5166.4 1617.35  5252.8 1618.77
    5286 1618.78  5367.2 1619.25  5502.3 1623.13  5756.3 1628.65  5779.4 1629.36
#Mann= 9 ,-1 , 0
  4507.5     .05       0  4777.8      .1       0  4998.7     .05       0
  5064.6      .1       0  5105.7    .035       0  5111.7      .1       0
  5166.4     .05       0    5286      .1       0  5756.3     .05       0
Bank Sta=5105.7,5111.7
XS Rating Curve= 0 ,0
Exp/Cntr=0.3,0.1

Type RM Length L Ch R = 1 ,10620   ,159,159,159
BEGIN DESCRIPTION:
KIEHNE CREEK 11.0
END DESCRIPTION:
XS GIS Cut Line= 3
      2783209.04     10073723.76      2783136.53     10073825.55
      2783094.48     10074796.67
#Sta/Elev= 30
  4813.5 1620.17  4871.8 1618.52  4877.9 1617.13  4886.5 1617.32  4892.7 1616.41
  4899.4 1617.06  4905.1 1616.82  4928.3  1616.2  4934.3 1615.37  4966.7 1613.12
  4986.7  1613.1  4996.7 1611.92  5002.6 1611.84  5005.3 1611.34  5008.6 1611.84
  5010.6 1612.48  5026.7 1612.93  5106.8  1613.6  5116.8 1613.18  5156.9 1613.27
  5206.9 1614.24  5236.2 1613.73  5241.2 1614.18  5367.1 1614.95  5477.2 1618.39
  5567.2 1620.65  5627.3 1621.48  5667.3 1622.77  5727.4 1623.39  5910.5 1626.85
#Mann= 4 ,-1 , 0
  4813.5     .16       0  4905.1     .05       0  5002.6     .04       0
  5008.6     .05       0
Bank Sta=5002.6,5008.6
XS Rating Curve= 0 ,0
Exp/Cntr=0.3,0.1

Type RM Length L Ch R = 1 ,10461   ,410,410,410
BEGIN DESCRIPTION:
Mapping XS e1c3a6a2
END DESCRIPTION:
XS GIS Cut Line= 3
      2783114.83     10073615.49      2782901.29     10073993.95
      2782946.43     10074778.71
#Sta/Elev= 30
    4729 1617.77  4748.2  1617.1  4753.9 1617.64  4769.8 1616.78  4775.6 1617.54
  4791.5 1617.16  4797.2 1617.85  4838.6 1616.34  4899.8 1614.71  4915.7 1613.17
  4990.8 1610.31  4993.6 1609.83  4996.3 1609.33  4999.6 1609.83  5034.1 1611.44
  5061.5 1611.55  5083.2 1610.92    5115 1611.77  5142.4 1611.69  5158.3 1612.38
  5199.9 1611.88  5303.6 1612.07  5423.8 1615.78  5549.3 1618.53  5714.2 1620.89
  5804.4 1622.62  5824.4 1623.62  5884.5 1623.39  5903.4 1624.02  5949.6 1624.83
#Mann= 5 ,-1 , 0
    4729     .05       0  4838.6     .16       0  4993.6     .07       0
  4999.6     .16       0  5903.4      .1       0
Bank Sta=4993.6,4999.6
XS Rating Curve= 0 ,0
Exp/Cntr=0.3,0.1

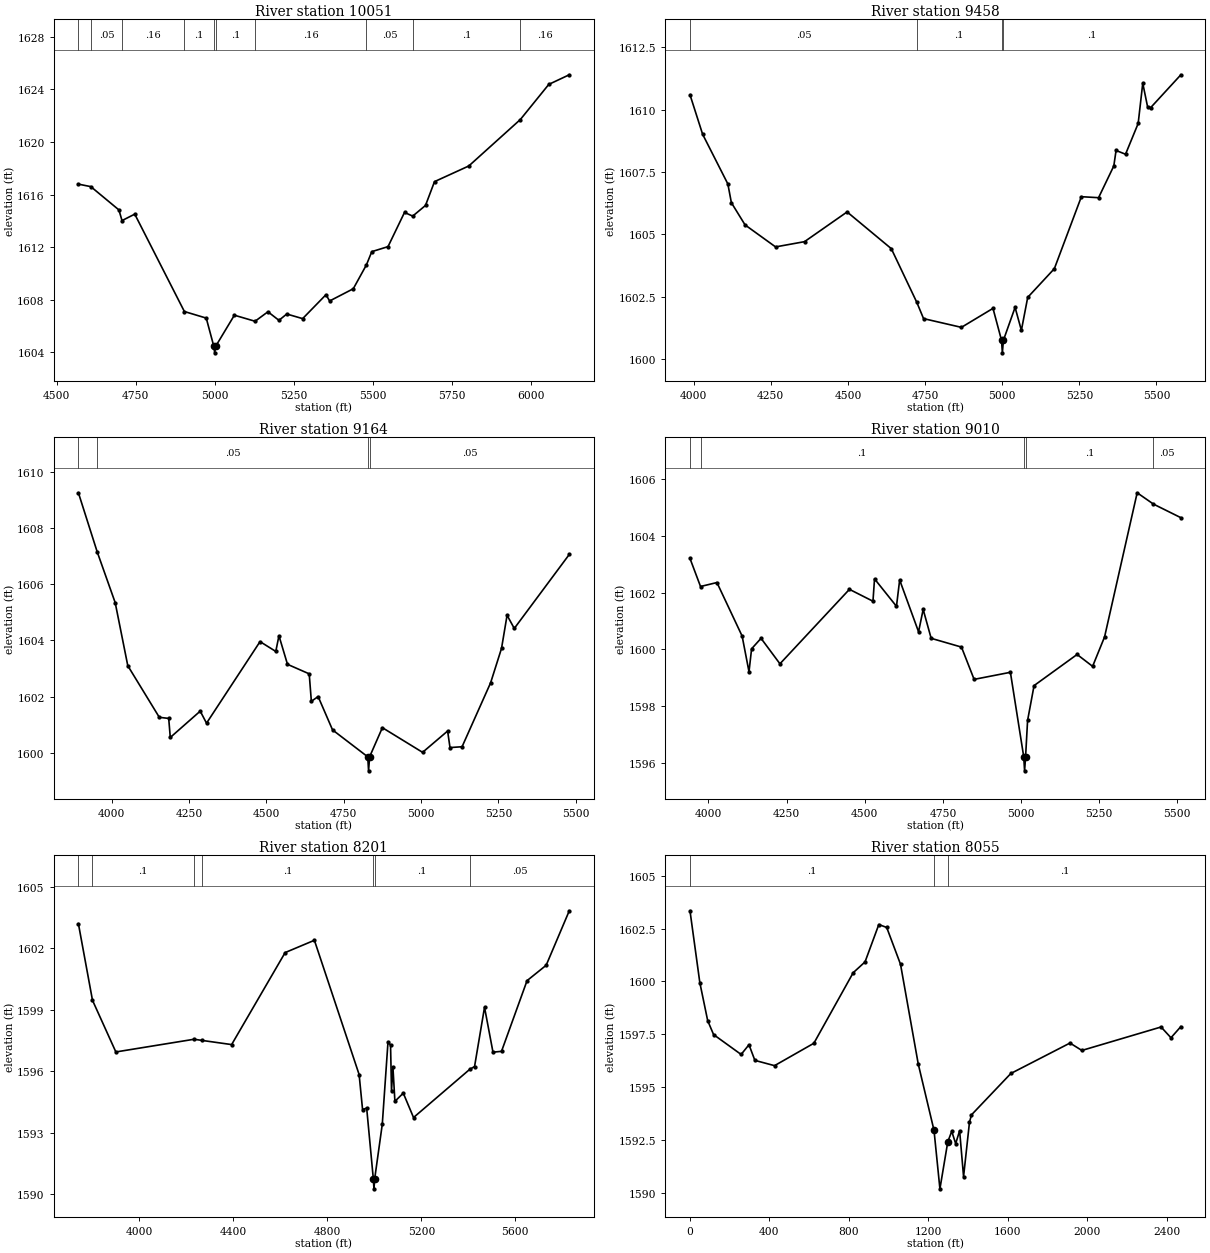
Type RM Length L Ch R = 1 ,10051   ,593,593,593
BEGIN DESCRIPTION:
KIEHNE CREEK 10.0
END DESCRIPTION:
XS GIS Cut Line= 4
      2783206.24     10073544.06      2782852.05     10073516.29
      2782150.66     10073703.79       2781954.3     10074132.79
#Sta/Elev= 30
  4569.1 1616.79  4608.4  1616.6  4697.3 1614.83  4707.1 1614.02  4747.4 1614.51
  4904.4 1607.11  4973.6 1606.61  4997.5 1604.47  5000.3 1603.97  5003.5 1604.47
  5062.6 1606.83    5128 1606.37  5168.8 1607.09  5203.6 1606.44  5228.3 1606.92
  5278.6 1606.57  5352.5 1608.39  5363.9 1607.91  5438.8 1608.84  5480.5 1610.66
  5497.4 1611.66  5548.7 1612.04  5600.9 1614.64  5626.8 1614.36  5667.3 1615.17
  5695.8 1616.98  5804.3 1618.17  5967.4  1621.7  6057.4 1624.37  6122.2  1625.1
#Mann= 10 ,-1 , 0
  4569.1      .1       0  4608.4     .05       0  4707.1     .16       0
  4904.4      .1       0  4997.5     .07       0  5003.5      .1       0
    5128     .16       0  5480.5     .05       0  5626.8      .1       0
  5967.4     .16       0
Bank Sta=4997.5,5003.5
XS Rating Curve= 0 ,0
Exp/Cntr=0.3,0.1

Type RM Length L Ch R = 1 ,9458    ,294,294,294
BEGIN DESCRIPTION:
KIEHNE CREEK 9.0
END DESCRIPTION:
XS GIS Cut Line= 2
      2783678.47     10073176.01      2782123.18     10072842.74
#Sta/Elev= 30
  3988.4 1610.59  4029.3 1609.01  4111.1 1607.02  4122.5 1606.27  4166.9 1605.38
  4265.7  1604.5  4359.5 1604.71  4497.5  1605.9  4640.7 1604.43  4723.4 1602.28
  4745.2 1601.63  4867.9 1601.28  4970.2 1602.04  4997.9 1600.76  5000.6 1600.26
  5003.9 1600.76  5041.8 1602.08  5062.2 1601.16  5082.7 1602.48  5169.1 1603.63
  5256.6 1606.51  5312.3 1606.47  5361.7 1607.74    5369 1608.36  5399.7 1608.21
  5440.6 1609.44  5455.5 1611.05  5471.3  1610.1  5481.5 1610.08    5579 1611.39
#Mann= 4 ,-1 , 0
  3988.4     .05       0  4723.4      .1       0  4997.9     .07       0
  5003.9      .1       0
Bank Sta=4997.9,5003.9
XS Rating Curve= 0 ,0
Exp/Cntr=0.3,0.1

Type RM Length L Ch R = 1 ,9164    ,154,154,154
BEGIN DESCRIPTION:
Mapping XS 28b37d23
END DESCRIPTION:
XS GIS Cut Line= 3
      2783825.39     10072983.28      2783128.77     10072853.07
      2782325.81     10072499.34
#Sta/Elev= 30
  3892.7 1609.27  3953.5 1607.16  4011.6 1605.35  4052.3  1603.1  4154.1 1601.26
  4184.5 1601.22  4189.6 1600.54  4286.3 1601.48  4306.7 1601.05  4479.6 1603.96
  4530.5 1603.61  4540.7 1604.17  4568.3 1603.15  4638.5 1602.81  4645.4 1601.83
  4667.3    1602  4713.9 1600.81  4827.6 1599.85  4830.3 1599.35  4833.6 1599.85
  4874.9 1600.89  5004.8 1600.01  5085.7 1600.77  5093.4 1600.18  5132.4 1600.21
  5224.6 1602.49  5259.9 1603.72  5277.8  1604.9  5301.1 1604.43  5478.8 1607.07
#Mann= 4 ,-1 , 0
  3892.7     .16       0  3953.5     .05       0  4827.6     .04       0
  4833.6     .05       0
Bank Sta=4827.6,4833.6
XS Rating Curve= 0 ,0
Exp/Cntr=0.3,0.1

Type RM Length L Ch R = 1 ,9010    ,809,809,809
BEGIN DESCRIPTION:
Mapping XS 3b927438
END DESCRIPTION:
XS GIS Cut Line= 4
      2783884.01     10072761.93      2783057.15     10072657.76
       2782733.8     10072573.12      2782377.91     10072384.33
#Sta/Elev= 30
  3940.8 1603.21  3974.5 1602.22    4027 1602.36  4107.6 1600.47  4129.6 1599.21
  4137.9 1600.02  4168.1 1600.39  4228.6 1599.49  4450.9 1602.12  4526.2  1601.7
  4531.2 1602.49  4601.4 1601.52  4611.6 1602.45  4672.1 1600.62  4686.8 1601.41
  4712.4 1600.39  4809.4 1600.08  4849.8 1598.94  4965.9 1599.19  5008.5 1596.21
  5011.3 1595.71  5014.5 1596.21  5020.9 1597.49  5041.6 1598.72  5179.3 1599.82
  5228.9  1599.4  5267.2 1600.44  5371.5 1605.53  5423.6 1605.13  5511.3 1604.65
#Mann= 5 ,-1 , 0
  3940.8     .05       0  3974.5      .1       0  5008.5     .07       0
  5014.5      .1       0  5423.6     .05       0
Bank Sta=5008.5,5014.5
XS Rating Curve= 0 ,0
Exp/Cntr=0.3,0.1

Type RM Length L Ch R = 1 ,8201    ,190,190,190
BEGIN DESCRIPTION:
KIEHNE CREEK 8.0
END DESCRIPTION:
XS GIS Cut Line= 4
      2783890.36     10072764.67      2783287.54     10071964.18
      2782983.94     10071844.54      2782345.93     10072258.59
#Sta/Elev= 30
  3740.6 1603.21  3800.6 1599.47    3900 1596.95  4232.9 1597.57  4268.7 1597.51
  4392.7 1597.31  4620.4  1601.8  4744.9  1602.4  4935.2 1595.85  4949.9 1594.14
  4967.4 1594.21  4995.6 1590.77  4998.4 1590.27  5001.6 1590.77  5033.8 1593.42
  5058.2 1597.45    5069 1597.28  5073.1 1595.06  5079.1 1596.21  5087.5 1594.54
  5123.2 1594.94  5166.8 1593.75  5405.8  1596.1  5426.5 1596.24  5468.9 1599.13
  5504.9 1596.94  5541.2 1596.98  5649.9 1600.43  5731.2 1601.18  5829.6 1603.84
#Mann= 7 ,-1 , 0
  3740.6     .05       0  3800.6      .1       0  4232.9     .16       0
  4268.7      .1       0  4995.6     .07       0  5001.6      .1       0
  5405.8     .05       0
Bank Sta=4995.6,5001.6
XS Rating Curve= 0 ,0
Exp/Cntr=0.3,0.1

Type RM Length L Ch R = 1 ,8055    ,259,259,259
XS GIS Cut Line= 4
     2783892.898    10072765.807     2783420.357    10071907.376
     2782651.791    10071383.636     2782109.457    10071609.867
#Sta/Elev= 30
       0 1603.34   49.52 1599.94   89.13 1598.14  118.84 1597.48  257.49 1596.54
   297.1    1597  326.81 1596.26  425.84 1596.01  623.91 1597.07  822.04 1600.41
  881.59 1600.92  951.06 1602.69  990.76 1602.55 1060.23 1600.81 1149.55 1596.09
 1228.95 1592.95 1258.72 1590.18 1298.42 1592.41 1318.27  1592.9 1338.12 1592.32
 1357.97 1592.93 1377.82 1590.76 1407.59 1593.33 1417.52 1593.68 1616.01 1595.64
 1913.84 1597.08 1973.67 1596.73 2372.54 1597.84  2422.4 1597.33 2472.26 1597.86
#Mann= 3 , 0 , 0
       0      .1       0 1228.95     .07       0 1298.42      .1       0
Bank Sta=1228.95,1298.42
XS Rating Curve= 0 ,0
Exp/Cntr=0.3,0.1

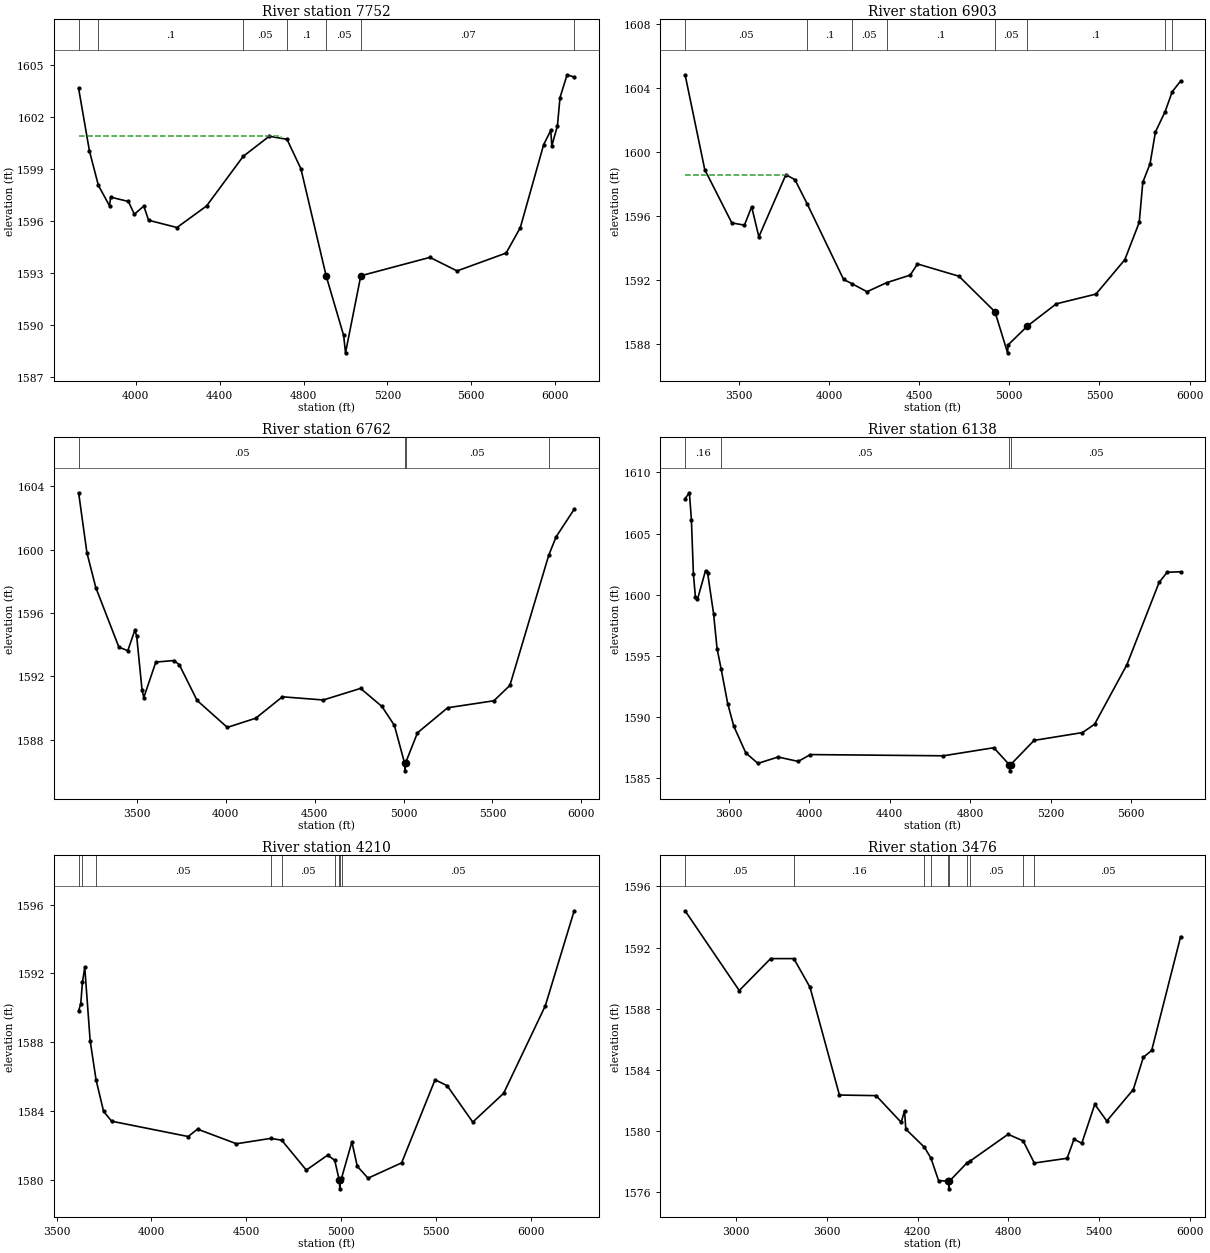
Type RM Length L Ch R = 1 ,7752    ,849,849,849
BEGIN DESCRIPTION:
Mapping XS 0768a656
END DESCRIPTION:
XS GIS Cut Line= 3
      2783898.04     10072770.48      2783482.78     10071912.67
      2783093.99     10070556.85
#Sta/Elev= 30
  3727.4 1603.65  3778.8 1600.06  3821.5 1598.07  3874.7 1596.89  3880.2 1597.39
    3965 1597.14  3993.2  1596.4  4038.3 1596.88  4060.9 1596.06  4196.4 1595.64
  4337.5 1596.88  4512.3 1599.74  4636.7  1600.9  4721.3 1600.72  4787.7 1599.02
  4908.2 1592.84  4991.4 1589.42  5000.3 1588.42  5073.2 1592.86  5402.9 1593.92
  5532.4 1593.14  5766.4 1594.17  5833.9 1595.63  5945.5 1600.42  5979.2 1601.23
  5984.4 1600.35  6010.9 1601.49  6023.4 1603.13  6057.1 1604.44  6090.9 1604.31
#Mann= 7 ,-1 , 0
  3727.4     .05       0  3821.5      .1       0  4512.3     .05       0
  4721.3      .1       0  4908.2     .05       0  5073.2     .07       0
  6090.9      .1       0
#XS Ineff= 2 , 0
         4691.83 1600.92
Permanent Ineff=
       F       F
Bank Sta=4908.2,5073.2
XS Rating Curve= 0 ,0
Exp/Cntr=0.3,0.1

Type RM Length L Ch R = 1 ,6903    ,141,141,141
BEGIN DESCRIPTION:
Mapping XS 08553a2c
END DESCRIPTION:
XS GIS Cut Line= 2
      2783901.48     10072792.87      2783927.76      10070043.9
#Sta/Elev= 30
  3201.3 1604.85  3310.4 1598.91  3460.5 1595.57  3530.5 1595.43  3570.5 1596.58
  3610.5  1594.7  3760.5 1598.59  3810.5 1598.28  3879.2 1596.75  4080.5 1592.03
  4125.7 1591.77  4210.5 1591.26  4320.3 1591.83  4450.3  1592.3  4490.5    1593
  4720.5 1592.23  4920.5    1590  4990.3 1587.43  4993.5 1587.93  5100.5 1589.11
  5260.5  1590.5  5480.5 1591.11  5640.5 1593.26  5720.6  1595.6  5740.6 1598.12
  5780.6 1599.27  5810.6 1601.27  5863.9 1602.53  5903.7 1603.79  5950.4 1604.46
#Mann= 8 ,-1 , 0
  3201.3     .05       0  3879.2      .1       0  4125.7     .05       0
  4320.3      .1       0  4920.5     .05       0  5100.5      .1       0
  5863.9     .05       0  5903.7      .1       0
#XS Ineff= 1 ,-1
  3201.3 3775.99 1598.55
Permanent Ineff=
       F
Bank Sta=4920.5,5100.5
XS Rating Curve= 0 ,0
Exp/Cntr=0.3,0.1

Type RM Length L Ch R = 1 ,6762    ,624,624,624
BEGIN DESCRIPTION:
Mapping XS d0fa00d8
END DESCRIPTION:
XS GIS Cut Line= 2
      2784009.86     10072740.33      2784032.85     10069952.02
#Sta/Elev= 30
  3171.5 1603.58  3218.1  1599.8  3268.1  1597.6  3398.1 1593.84  3448.1 1593.62
  3488.1 1594.92  3498.1 1594.54  3528.1 1591.17  3538.1 1590.66  3605.9  1592.9
  3708.1    1593  3738.1 1592.73  3838.1 1590.48  4008.1 1588.78  4168.1 1589.36
  4318.1 1590.71  4548.1 1590.51  4758.1 1591.24  4878.2  1590.1  4948.2 1588.91
  5005.2 1586.54  5007.9 1586.04  5011.2 1586.54  5078.2 1588.44  5248.2 1590.02
  5508.2 1590.46  5598.2 1591.43  5816.8 1599.64  5858.2  1600.8  5959.9 1602.54
#Mann= 4 ,-1 , 0
  3171.5     .05       0  5005.2     .04       0  5011.2     .05       0
  5816.8      .1       0
Bank Sta=5005.2,5011.2
XS Rating Curve= 0 ,0
Exp/Cntr=0.3,0.1

Type RM Length L Ch R = 1 ,6138    ,1928,1928,1928
BEGIN DESCRIPTION:
Mapping XS 93671e62
END DESCRIPTION:
XS GIS Cut Line= 2
      2784683.13     10072425.02      2784535.45     10069966.95
#Sta/Elev= 30
  3383.7 1607.87    3405 1608.34    3415 1606.15  3425.1 1601.67  3435.1 1599.79
  3445.1 1599.62  3485.2 1601.97  3495.2 1601.82  3525.2 1598.46  3542.5  1595.6
  3563.3 1593.89  3595.4  1591.1  3625.4 1589.26  3685.5 1587.06  3745.6 1586.21
  3845.8 1586.73    3946 1586.37  4006.1 1586.93  4667.3 1586.83  4917.7 1587.49
  4994.9  1586.1  4997.6  1585.6  5000.9  1586.1  5118.1 1588.09  5358.5 1588.73
  5418.6 1589.41  5578.9 1594.27  5739.2 1601.01  5779.3 1601.84  5846.2 1601.88
#Mann= 4 ,-1 , 0
  3383.7     .16       0  3563.3     .05       0  4994.9    .035       0
  5000.9     .05       0
Bank Sta=4994.9,5000.9
XS Rating Curve= 0 ,0
Exp/Cntr=0.3,0.1

Type RM Length L Ch R = 1 ,4210    ,734,734,734
BEGIN DESCRIPTION:
Mapping XS 1ad23822
END DESCRIPTION:
XS GIS Cut Line= 2
      2786765.36     10071702.51      2785004.98     10069771.35
#Sta/Elev= 30
  3616.1 1589.83  3627.5 1590.24  3636.1 1591.49  3648.4 1592.35  3676.8 1588.09
  3708.1 1585.81  3747.7 1583.98  3790.3 1583.41  4193.7 1582.52    4243 1582.95
  4448.4  1582.1  4628.5 1582.41  4686.8 1582.31  4816.6 1580.57  4929.5 1581.44
  4966.5 1581.14  4990.6 1579.98  4993.4 1579.48  4996.6 1579.98  5003.2 1580.13
  5057.1 1582.21  5085.5 1580.79  5142.3  1580.1  5319.3 1580.99  5495.7 1585.82
  5559.8 1585.47  5694.3 1583.36  5857.1 1585.03  6076.7 1590.11  6229.2 1595.64
#Mann= 9 ,-1 , 0
  3616.1     .16       0  3636.1      .1       0  3708.1     .05       0
  4628.5      .1       0  4686.8     .05       0  4966.5      .1       0
  4990.6     .07       0  4996.6      .1       0  5003.2     .05       0
Bank Sta=4990.6,4996.6
XS Rating Curve= 0 ,0
Exp/Cntr=0.3,0.1

Type RM Length L Ch R = 1 ,3476    ,360,360,360
BEGIN DESCRIPTION:
Mapping XS 15c55c38
END DESCRIPTION:
XS GIS Cut Line= 3
      2787963.25     10071300.22      2787514.13     10070700.79
      2785225.05     10069630.14
#Sta/Elev= 30
  2662.5 1594.41  3020.5 1589.19  3227.9 1591.28  3381.3 1591.28  3488.4  1589.4
  3682.7 1582.35  3925.6 1582.31  4091.2 1580.56  4113.3 1581.32  4121.6 1580.12
    4245 1578.93  4288.1 1578.21  4338.2 1576.75  4403.8 1576.71  4406.5 1576.21
  4409.8 1576.71    4528 1577.93  4542.9    1578  4797.7 1579.78  4897.3 1579.35
  4971.3  1577.9  5188.1 1578.21  5233.8 1579.46    5285 1579.19  5370.9 1581.74
  5450.4 1580.65  5625.7 1582.71    5692 1584.82  5747.2 1585.27  5938.6 1592.72
#Mann= 10 ,-1 , 0
  2662.5     .05       0  3381.3     .16       0    4245      .1       0
  4288.1     .05       0  4403.8     .03       0  4409.8     .05       0
    4528      .1       0  4542.9     .05       0  4897.3      .1       0
  4971.3     .05       0
Bank Sta=4403.8,4409.8
XS Rating Curve= 0 ,0
Exp/Cntr=0.3,0.1