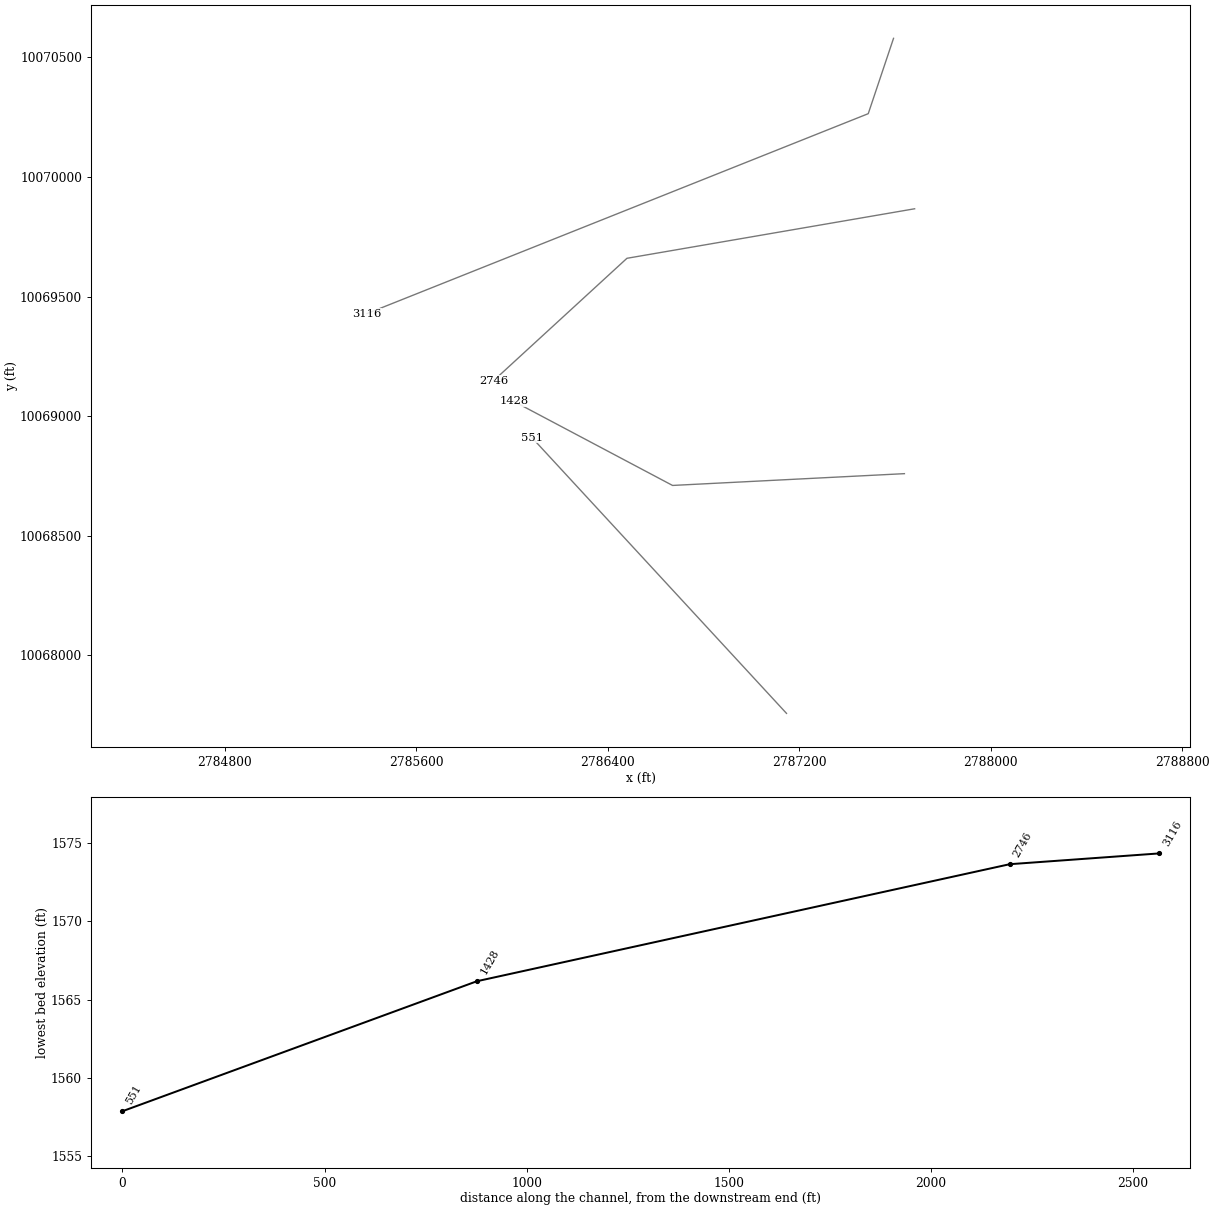
HEC-RAS study KIEHNE CREEK.prj: KIEHNE CREEK Base Level Engineering

--- KIEHNE CREEK.g01 (geometry) --- (continued)

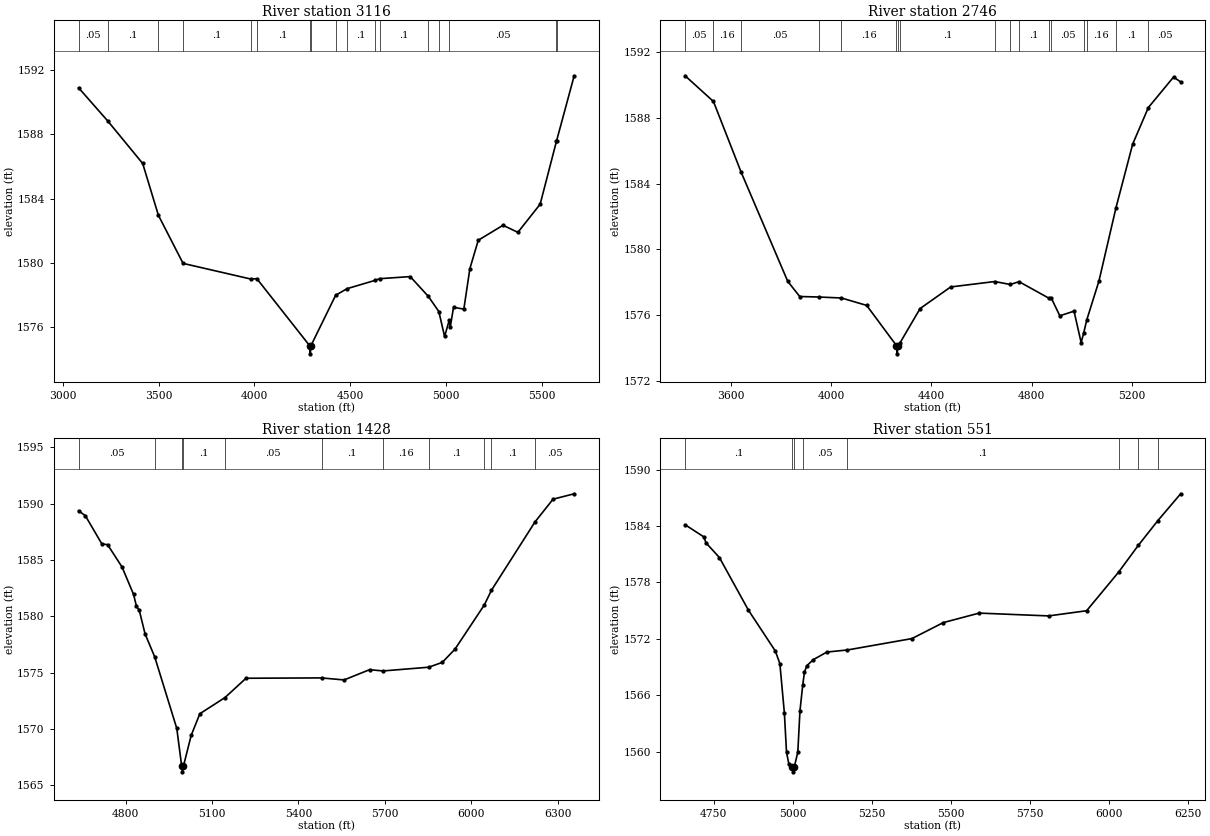
Type RM Length L Ch R = 1 ,3116    ,370,370,370
BEGIN DESCRIPTION:
Mapping XS 55957a57
END DESCRIPTION:
XS GIS Cut Line= 3
      2787593.48     10070578.77      2787487.85     10070263.99
       2785393.5     10069428.74
#Sta/Elev= 30
  3082.8 1590.88  3235.6 1588.81  3417.2 1586.18  3499.2 1582.96  3628.1 1579.97
    3981    1579  4013.2 1579.02  4289.2 1574.85    4292 1574.35  4295.2 1574.85
  4424.5 1577.99    4484  1578.4  4631.5 1578.92  4654.2 1579.02  4813.7 1579.15
  4908.4 1577.92  4963.1 1576.98  4993.1 1575.43  5017.6 1576.44  5022.7 1576.01
  5039.8 1577.24  5093.7 1577.13  5125.2 1579.65    5169 1581.41  5298.2 1582.34
  5375.8  1581.9    5492 1583.65  5577.1 1587.56  5577.4 1587.57  5669.6 1591.63
#Mann= 17 ,-1 , 0
  3082.8     .05       0  3235.6      .1       0  3499.2     .16       0
  3628.1      .1       0    3981     .16       0  4013.2      .1       0
  4289.2     .07       0  4295.2      .1       0  4424.5     .05       0
    4484      .1       0  4631.5     .05       0  4654.2      .1       0
  4908.4     .05       0  4963.1      .1       0  5017.6     .05       0
  5577.1      .1       0  5577.4     .05       0
Bank Sta=4289.2,4295.2
XS Rating Curve= 0 ,0
Exp/Cntr=0.3,0.1

Type RM Length L Ch R = 1 ,2746    ,1318,1318,1318
BEGIN DESCRIPTION:
Mapping XS 20374db8
END DESCRIPTION:
XS GIS Cut Line= 3
      2787681.63      10069866.6       2786479.6     10069659.69
       2785923.1     10069149.02
#Sta/Elev= 30
  3418.5 1590.54  3531.5 1588.98  3641.5  1584.7  3827.6 1578.06  3875.4 1577.14
  3951.1 1577.11  4041.8 1577.05  4142.2  1576.6  4260.9 1574.16  4263.7 1573.66
  4266.9 1574.16  4275.2 1574.33  4355.2 1576.41    4477 1577.72  4652.8 1578.05
  4714.3 1577.87  4749.6 1578.04    4867 1577.05  4878.4 1577.03  4911.9 1575.97
  4968.6 1576.25    4997 1574.34  5007.2 1574.93  5019.6 1575.73  5067.9 1578.08
    5136 1582.54  5202.3 1586.39  5264.8 1588.61  5365.1 1590.46  5393.5 1590.17
#Mann= 17 ,-1 , 0
  3418.5     .05       0  3531.5     .16       0  3641.5     .05       0
  3951.1      .1       0  4041.8     .16       0  4260.9    .035       0
  4266.9     .16       0  4275.2      .1       0  4652.8     .05       0
  4714.3     .16       0  4749.6      .1       0    4867     .16       0
  4878.4     .05       0  5007.2      .1       0  5019.6     .16       0
    5136      .1       0  5264.8     .05       0
Bank Sta=4260.9,4266.9
XS Rating Curve= 0 ,0
Exp/Cntr=0.3,0.1

Type RM Length L Ch R = 1 ,1428    ,877,877,877
BEGIN DESCRIPTION:
Mapping XS 903d44a1
END DESCRIPTION:
XS GIS Cut Line= 3
      2787638.94     10068759.81      2786670.08     10068710.55
      2786006.63     10069061.98
#Sta/Elev= 30
    4637 1589.36  4660.4 1588.92  4717.6 1586.42  4737.6 1586.35  4787.7 1584.37
  4827.7 1581.94  4837.7 1580.89  4847.7 1580.51  4867.8 1578.42  4901.2 1576.39
  4977.9 1570.03  4994.9 1566.68  4997.7 1566.18  5000.9 1566.68    5028 1569.43
    5058 1571.34  5145.5 1572.78  5218.2 1574.49  5480.5 1574.52  5558.7 1574.34
  5647.3 1575.25  5694.2 1575.14  5852.8 1575.47  5899.9  1575.9  5943.9 1577.07
  6045.9    1581  6070.6  1582.3  6221.8 1588.37  6284.6 1590.39  6357.9 1590.87
#Mann= 11 ,-1 , 0
    4637     .05       0  4901.2      .1       0  4994.9     .07       0
  5000.9      .1       0  5145.5     .05       0  5480.5      .1       0
  5694.2     .16       0  5852.8      .1       0  6045.9     .05       0
  6070.6      .1       0  6221.8     .05       0
Bank Sta=4994.9,5000.9
XS Rating Curve= 0 ,0
Exp/Cntr=0.3,0.1

Type RM Length L Ch R = 1 ,551     ,0,0,0
BEGIN DESCRIPTION:
KIEHNE CREEK 8.1
END DESCRIPTION:
XS GIS Cut Line= 2
      2787146.27     10067758.15      2786083.81     10068909.15
#Sta/Elev= 30
  4659.9 1584.13  4719.1 1582.84  4725.9 1582.21  4768.4 1580.64  4860.3 1575.04
  4945.3  1570.7  4959.5 1569.36  4973.7 1564.13  4980.5 1559.93  4987.8 1558.73
    4999 1558.37  5001.8 1557.87    5005 1558.37  5016.2 1559.98    5023 1564.36
  5031.9 1567.14  5037.2 1568.46  5044.6 1569.15  5065.5  1569.8  5108.1  1570.6
  5172.9 1570.82  5376.8 1572.03  5476.1 1573.73  5589.5 1574.74  5808.9 1574.44
  5929.1 1574.99  6029.9 1579.08  6092.3 1581.93  6153.6 1584.54  6226.3 1587.42
#Mann= 8 ,-1 , 0
  4659.9      .1       0    4999     .07       0    5005      .1       0
  5031.9     .05       0  5172.9      .1       0  6029.9     .05       0
  6092.3      .1       0  6153.6     .05       0
Bank Sta=4999,5005
XS Rating Curve= 0 ,0
Exp/Cntr=0.3,0.1

Chan Stop Cuts=-1
Use User Specified Reach Order=0
Composite Channel Slope=5