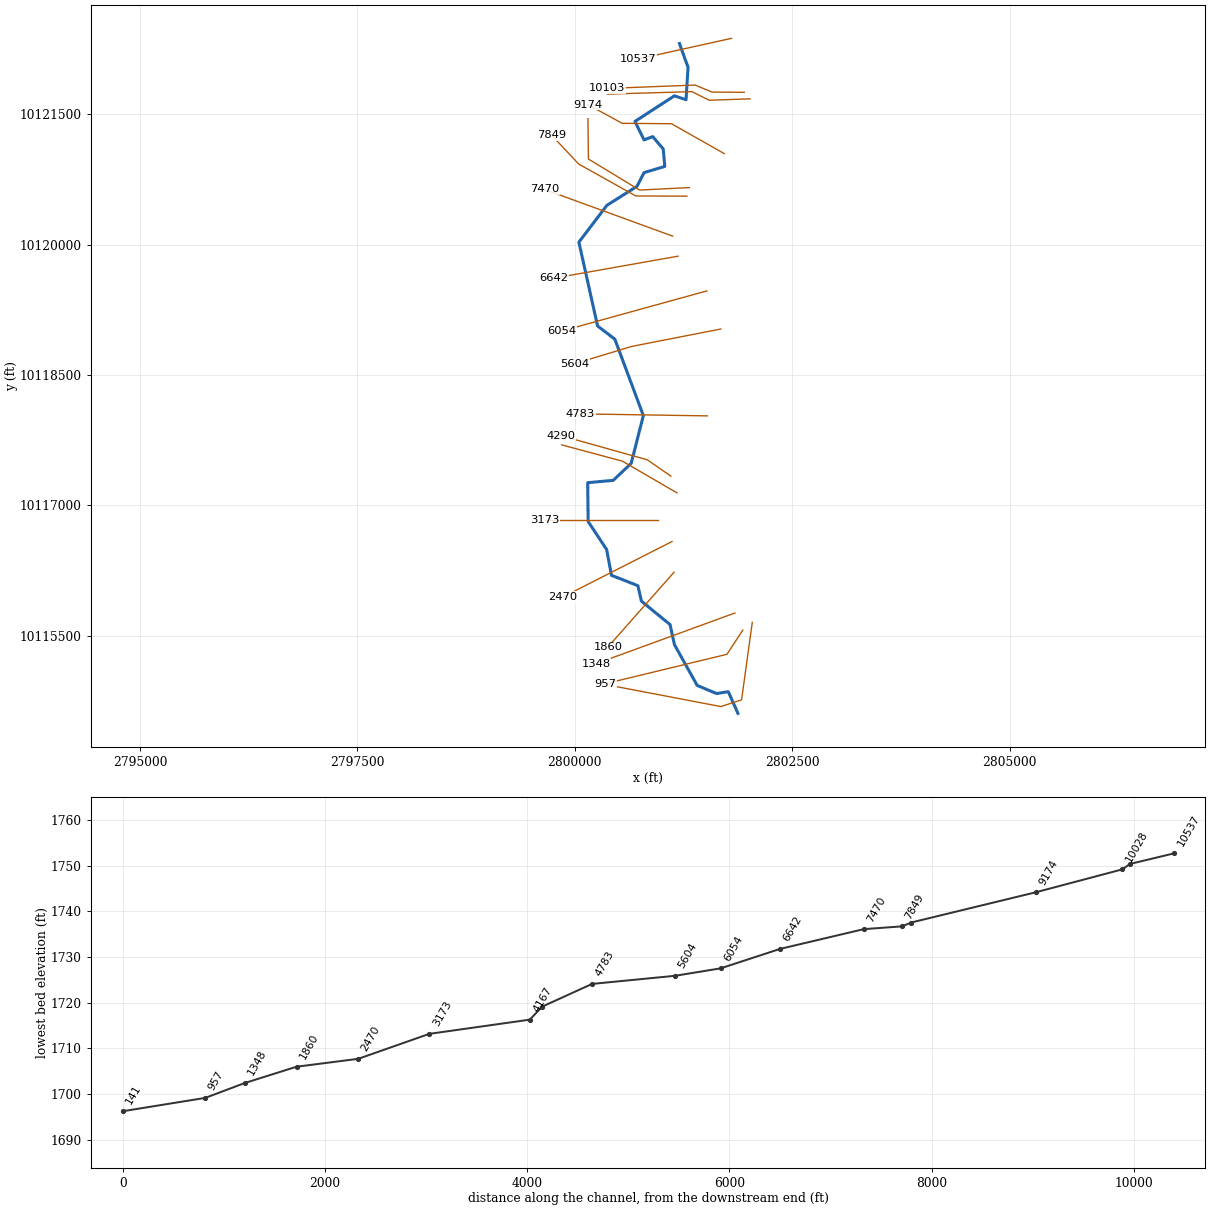
--- KNOTT BRANCH.prj (project) ---

Proj Title=KNOTT BRANCH Base Level Engineering
Current Plan=p01
Default Exp/Contr=0.3,0.1
English Units
Geom File=g01
Flow File=f01
Plan File=p01
Y Axis Title=Elevation
X Axis Title(PF)=Main Channel Distance
X Axis Title(XS)=Station
BEGIN DESCRIPTION:
KNOTT BRANCH
END DESCRIPTION:
DSS Export Rating Curves= 0
DSS Export Rating Curve Sorted= 0
DSS Export Volume Flow Curves= 0
DXF OffsetX= 0
DXF OffsetY= 0
DXF ScaleX= 1
DXF ScaleY= 10

--- KNOTT BRANCH.p01 (plan) ---

Plan Title=Multiple Run
Short Identifier=Multiple
Geom File=g01
Flow File=f01
Subcritical Flow
K Sum by GR= 0
Std Step Tol= 0.01
Critical Tol= 0.01
Num of Std Step Trials= 20
Max Error Tol= 0.3
Flow Tol Ratio= 0.001
Split Flow NTrial= 30
Split Flow Tol= 0.02
Split Flow Ratio= 0.02
Log Output Level= 0
Friction Slope Method= 1
Unsteady Friction Slope Method= 2
Unsteady Bridges Friction Slope Method= 1
Parabolic Critical Depth
Global Vel Dist=  1 , 1 , 1
Global Log Level= 0
CheckData=True
Encroach Param= -1, 0, 0, 0
BEGIN DESCRIPTION:
Multiple Run
END DESCRIPTION:

--- KNOTT BRANCH.f01 (steady flow) ---

Flow Title=Multiple
Program Version=4.10
Number of Profiles= 7
Profile Names=10-year,25-year,50-year,1pct_min,100-year,1pct_plu,500-year
River Rch & RM=KNOTT BRANCH,Reach-1         ,10537
     879    1272    1612    1495    2022    2735    3193
River Rch & RM=KNOTT BRANCH,Reach-1         ,10103
    1156    1692    2162    2017    2728    3690    4367
River Rch & RM=KNOTT BRANCH,Reach-1         ,6054
    1316    1932    2472    2309    3122    4222    5006
Boundary for River Rch & Prof#=KNOTT BRANCH,Reach-1         , 1
Up Type= 0
Dn Type= 3
Dn Slope=0.0054
Boundary for River Rch & Prof#=KNOTT BRANCH,Reach-1         , 2
Up Type= 0
Dn Type= 3
Dn Slope=0.0054
Boundary for River Rch & Prof#=KNOTT BRANCH,Reach-1         , 3
Up Type= 0
Dn Type= 3
Dn Slope=0.0054
Boundary for River Rch & Prof#=KNOTT BRANCH,Reach-1         , 4
Up Type= 0
Dn Type= 3
Dn Slope=0.0054
Boundary for River Rch & Prof#=KNOTT BRANCH,Reach-1         , 5
Up Type= 0
Dn Type= 3
Dn Slope=0.0054
Boundary for River Rch & Prof#=KNOTT BRANCH,Reach-1         , 6
Up Type= 0
Dn Type= 3
Dn Slope=0.0054
Boundary for River Rch & Prof#=KNOTT BRANCH,Reach-1         , 7
Up Type= 0
Dn Type= 3
Dn Slope=0.0054
DSS Import GetInterval= 0
DSS Import GetPeak= 0
DSS Import FillOption= 0

--- KNOTT BRANCH.g01 (geometry) ---

Geom Title=Existing Conditions
Program Version=4.10

River Reach=KNOTT BRANCH    ,Reach-1
Reach XY= 30
      2801202.08     10122315.31      2801301.36     10122041.51
      2801278.39     10121667.79       2801144.2     10121712.88
       2800690.9     10121418.26      2800794.93     10121206.04
      2800894.96     10121243.41       2801015.8     10121102.17
      2801034.04     10120900.77      2800795.37     10120828.96
      2800714.49      10120671.5      2800368.62      10120453.3
      2800046.18     10120029.31      2800260.87      10119064.7
      2800459.41     10118912.61      2800787.41     10118033.73
      2800647.53     10117483.27      2800441.32     10117288.09
       2800147.5     10117260.92      2800152.48     10116814.31
      2800365.13     10116492.26      2800421.16     10116195.24
      2800724.51     10116075.65       2800765.7      10115897.1
       2801094.4     10115628.32      2801144.98     10115397.39
      2801406.66     10114927.76      2801629.05     10114834.62
      2801764.33     10114856.06      2801875.02     10114606.37

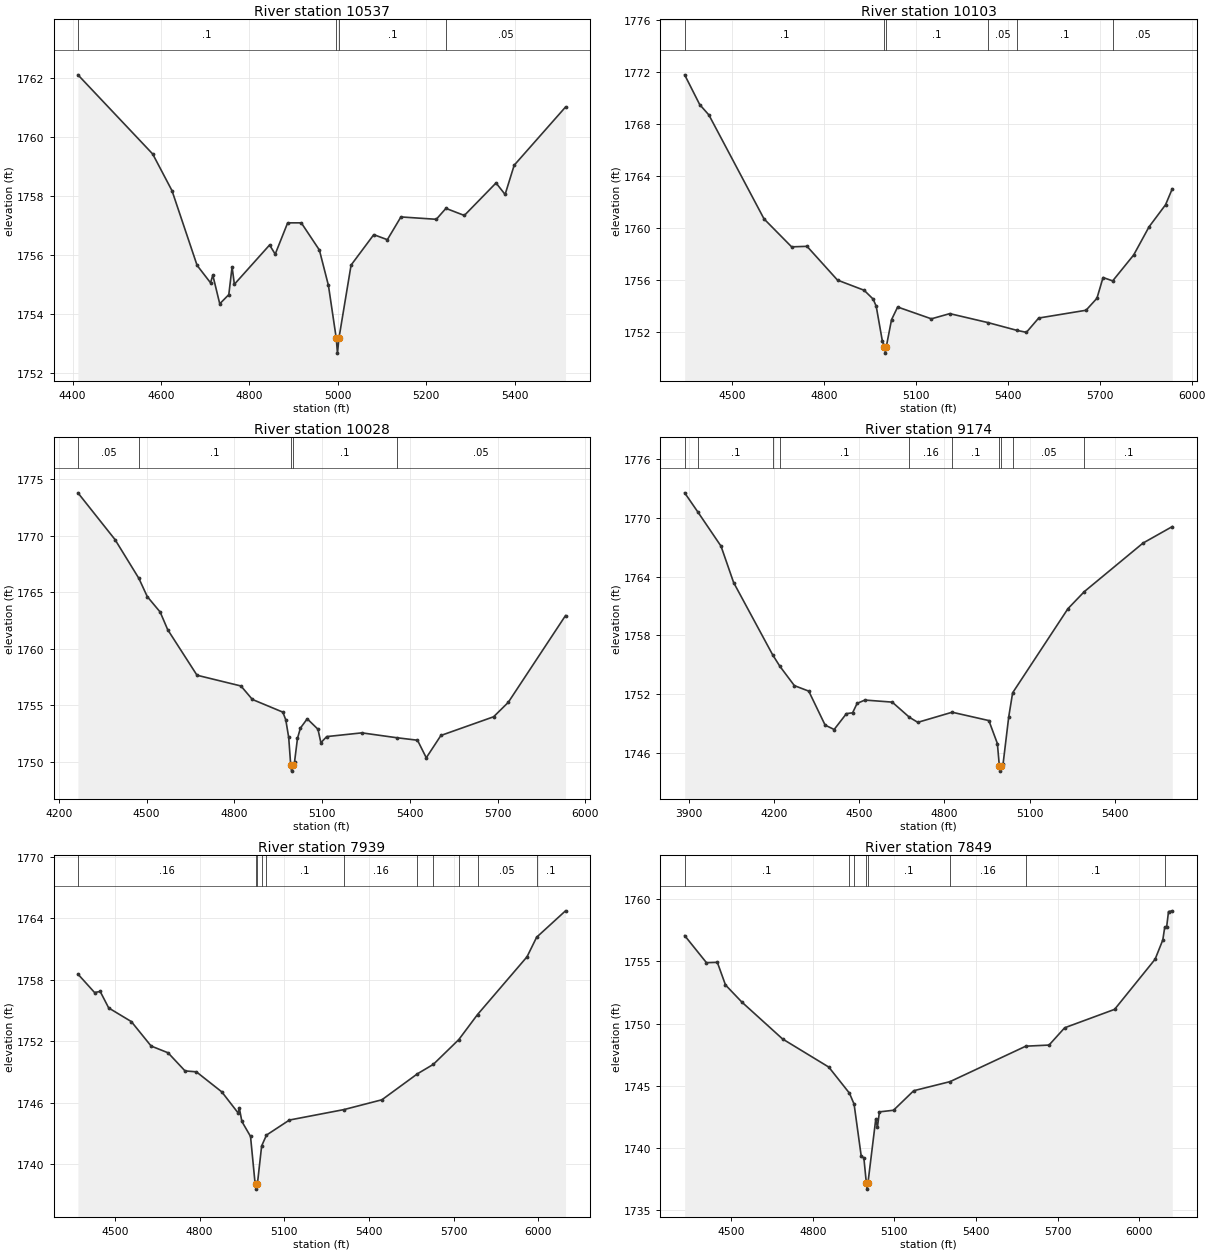
Type RM Length L Ch R = 1 ,10537   ,434,434,434
BEGIN DESCRIPTION:
KNOTT BRANCH 20.0
END DESCRIPTION:
XS GIS Cut Line= 2
       2801801.6      10122374.6      2800725.07     10122136.23
#Sta/Elev= 30
  4412.2  1762.1  4581.3 1759.42  4624.9 1758.18  4681.7 1755.65  4712.1 1755.06
  4717.2 1755.32  4732.9 1754.35  4753.4 1754.66  4760.8  1755.6    4766 1755.01
  4845.6 1756.34  4858.3 1756.03  4886.5 1757.09  4917.3 1757.09  4958.2 1756.17
  4978.7 1754.97  4996.4 1753.18  4999.1 1752.68  5002.4 1753.18  5029.9 1755.66
  5081.2 1756.69  5111.9 1756.52  5142.6 1757.29  5222.6 1757.21  5244.4 1757.58
    5286 1757.34  5357.7 1758.44  5378.2 1758.05  5398.7 1759.04  5514.8 1761.01
#Mann= 4 ,-1 , 0
  4412.2      .1       0  4996.4     .07       0  5002.4      .1       0
  5244.4     .05       0
Bank Sta=4996.4,5002.4
XS Rating Curve= 0 ,0
Exp/Cntr=0.3,0.1

Type RM Length L Ch R = 1 ,10103   ,75,75,75
BEGIN DESCRIPTION:
Mapping XS cc27fb13
END DESCRIPTION:
XS GIS Cut Line= 4
      2801947.58     10121753.54      2801577.76     10121756.14
      2801382.45     10121836.87      2800372.77     10121797.84
#Sta/Elev= 30
  4345.1 1771.79  4394.2  1769.5  4424.2  1768.7  4604.2  1760.7  4694.2 1758.55
  4744.5 1758.59    4844 1755.99  4930.8 1755.21  4960.3 1754.53  4970.3 1753.98
  4990.3 1751.31  4997.3 1750.87  5000.1 1750.37  5003.3 1750.87  5020.3 1752.94
  5040.3 1753.92  5150.4 1753.01  5210.5 1753.41  5335.1 1752.72    5430 1752.12
  5460.6 1751.97  5500.7 1753.07  5655.2 1753.67  5690.8 1754.59  5710.8 1756.19
  5742.2 1755.93  5810.9 1757.93  5860.9 1760.09  5914.8 1761.79  5936.7 1763.02
#Mann= 6 ,-1 , 0
  4345.1      .1       0  4997.3     .07       0  5003.3      .1       0
  5335.1     .05       0    5430      .1       0  5742.2     .05       0
Bank Sta=4997.3,5003.3
XS Rating Curve= 0 ,0
Exp/Cntr=0.3,0.1

Type RM Length L Ch R = 1 ,10028   ,854,854,854
BEGIN DESCRIPTION:
KNOTT BRANCH 19.0
END DESCRIPTION:
XS GIS Cut Line= 4
      2802015.23     10121678.02      2801543.91     10121662.39
      2801345.99     10121761.35      2800372.77     10121732.73
#Sta/Elev= 30
  4265.3 1773.77  4392.1 1769.64  4473.7 1766.21  4502.2 1764.61  4546.4 1763.24
  4572.2 1761.68  4672.3 1757.66  4822.5 1756.71  4861.6 1755.52  4965.7  1754.4
  4975.7 1753.72  4985.7 1752.17  4992.7 1749.69  4995.4 1749.19  4998.7 1749.69
  5005.7 1750.01  5015.7 1752.08  5025.7 1752.99    5049 1753.81  5085.7 1752.89
  5095.7  1751.7  5115.7 1752.24  5235.8 1752.57    5355 1752.14  5425.9 1751.92
  5455.9 1750.37  5505.9 1752.34    5686 1753.99    5736 1755.26  5931.8 1762.93
#Mann= 5 ,-1 , 0
  4265.3     .05       0  4473.7      .1       0  4992.7     .07       0
  4998.7      .1       0    5355     .05       0
Bank Sta=4992.7,4998.7
XS Rating Curve= 0 ,0
Exp/Cntr=0.3,0.1

Type RM Length L Ch R = 1 ,9174    ,1235,1235,1235
BEGIN DESCRIPTION:
KNOTT BRANCH 18.0
END DESCRIPTION:
XS GIS Cut Line= 4
       2801718.4      10121047.8      2801111.62     10121391.56
      2800543.91     10121396.77       2800148.1      10121612.9
#Sta/Elev= 30
  3885.9 1772.53  3933.2 1770.54  4013.8  1767.1  4058.2 1763.39  4195.9 1756.01
    4221 1754.86    4272 1752.89  4322.6 1752.33  4380.2 1748.87    4412 1748.42
  4455.3 1750.04  4476.9 1750.12  4492.8 1751.08  4520.2 1751.42  4616.4 1751.21
  4677.1 1749.66  4706.4 1749.15  4827.3 1750.18  4956.5 1749.33  4986.5 1746.99
  4993.5 1744.68  4996.2 1744.18  4999.5 1744.68  5006.5  1744.9  5026.5 1749.72
  5040.2 1752.16  5234.9 1760.73  5292.6 1762.47    5499 1767.41    5602 1769.09
#Mann= 10 ,-1 , 0
  3885.9     .16       0  3933.2      .1       0  4195.9     .16       0
    4221      .1       0  4677.1     .16       0  4827.3      .1       0
  4993.5     .07       0  4999.5      .1       0  5040.2     .05       0
  5292.6      .1       0
Bank Sta=4993.5,4999.5
XS Rating Curve= 0 ,0
Exp/Cntr=0.3,0.1

Type RM Length L Ch R = 1 ,7939    ,90,90,90
BEGIN DESCRIPTION:
KNOTT BRANCH 17.0
END DESCRIPTION:
XS GIS Cut Line= 4
      2801317.31     10120657.18      2800744.43     10120628.54
      2800155.89     10120985.31      2800150.69     10121450.04
#Sta/Elev= 30
  4369.3 1758.55  4428.2 1756.75  4448.2 1756.85  4478.3 1755.24  4558.4 1753.91
  4628.5 1751.52  4688.5 1750.86  4748.6 1749.09  4788.7    1749  4878.8 1747.04
  4936.4 1744.99    4941 1745.44  4949.9 1744.15  4980.5 1742.69    4996 1738.28
  4998.8 1738.04  5001.6 1737.54  5004.8 1738.04  5019.9 1741.76    5037 1742.82
  5118.2 1744.29  5311.2 1745.31  5445.8 1746.27  5571.7 1748.81  5627.8 1749.73
    5718 1752.15  5784.4  1754.6  5959.6 1760.24  5993.6 1762.15  6095.9 1764.73
#Mann= 11 ,-1 , 0
  4369.3     .16       0  4998.8     .07       0  5004.8     .16       0
  5019.9     .05       0    5037      .1       0  5311.2     .16       0
  5571.7      .1       0  5627.8     .05       0    5718      .1       0
  5784.4     .05       0  5993.6      .1       0
Bank Sta=4998.8,5004.8
XS Rating Curve= 0 ,0
Exp/Cntr=0.3,0.1

Type RM Length L Ch R = 1 ,7849    ,379,379,379
BEGIN DESCRIPTION:
Mapping XS 6497fb36
END DESCRIPTION:
XS GIS Cut Line= 4
      2801288.71     10120558.23      2800700.16     10120560.83
      2800043.91     10120928.02      2799733.99     10121258.77
#Sta/Elev= 30
  4328.4 1757.08  4408.6  1754.9  4448.6 1754.93  4478.6 1753.11  4538.6 1751.74
  4688.6 1748.77  4858.6 1746.51  4934.7 1744.41  4951.7 1743.53    4978 1739.34
  4987.6 1739.22  4996.7  1737.2  4999.5  1736.7  5002.7  1737.2  5031.6 1742.36
  5037.4 1741.66  5044.9 1742.91  5096.7 1743.04    5171 1744.61  5304.6 1745.34
  5583.3 1748.19  5668.9 1748.28  5726.4 1749.67  5910.1 1751.15  6059.1 1755.18
  6087.4 1756.73  6094.5 1757.75  6101.5 1757.77  6108.4 1759.01  6122.2 1759.07
#Mann= 8 ,-1 , 0
  4328.4      .1       0  4934.7     .16       0  4951.7      .1       0
  4996.7     .07       0  5002.7      .1       0  5304.6     .16       0
  5583.3      .1       0  6094.5     .05       0
Bank Sta=4996.7,5002.7
XS Rating Curve= 0 ,0
Exp/Cntr=0.3,0.1

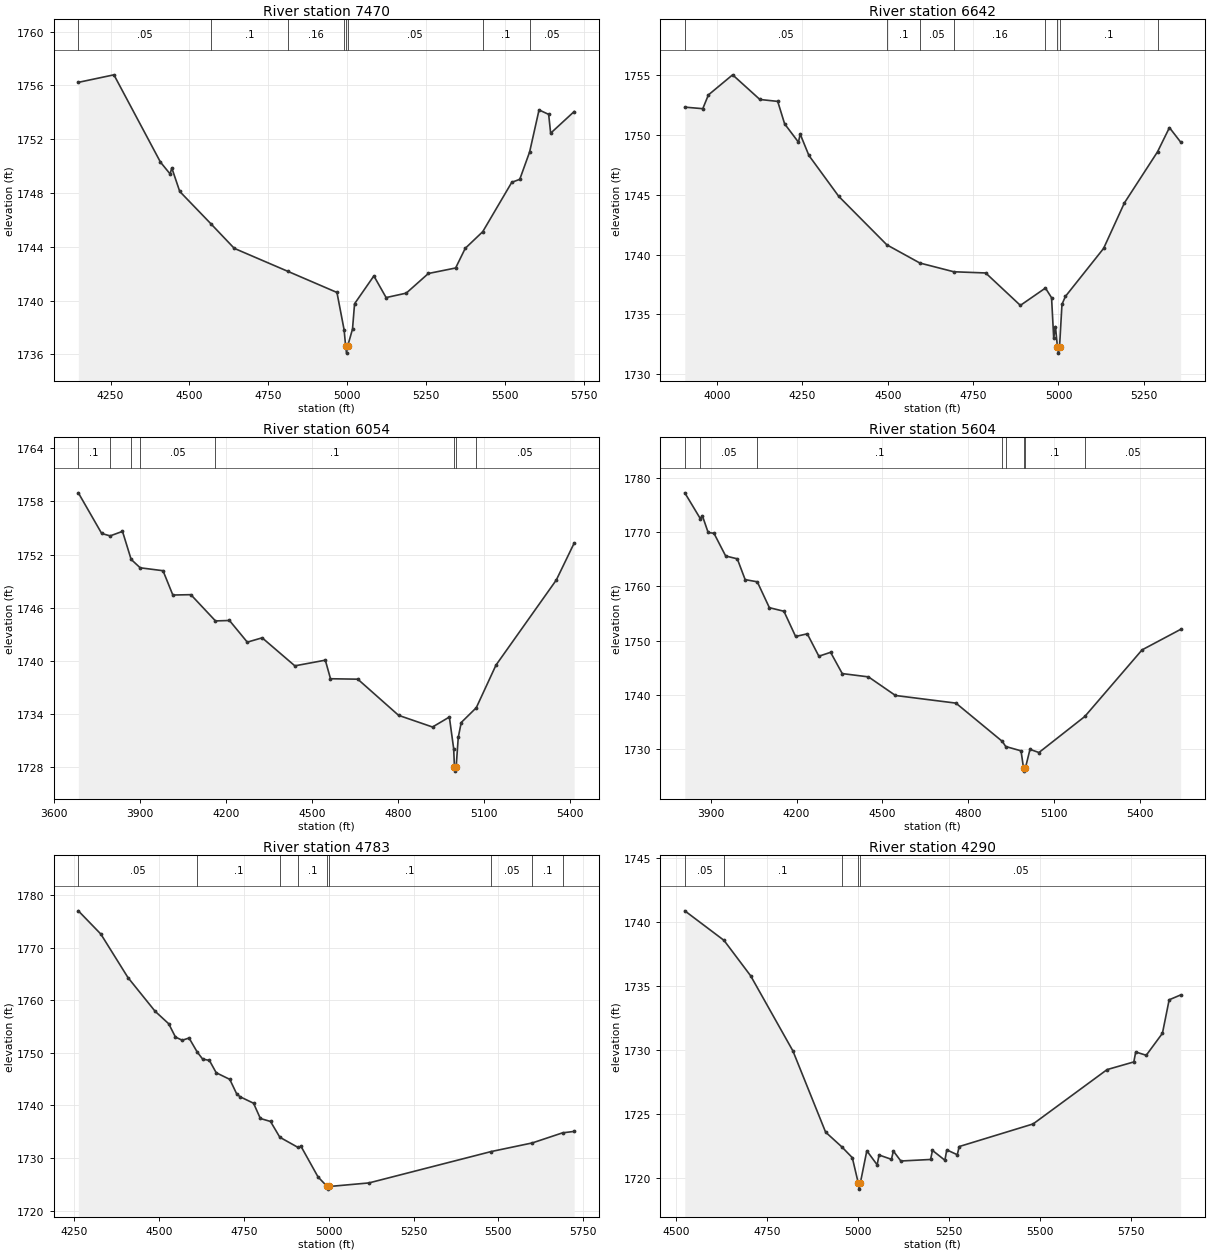
Type RM Length L Ch R = 1 ,7470    ,828,828,828
BEGIN DESCRIPTION:
KNOTT BRANCH 15.0
END DESCRIPTION:
XS GIS Cut Line= 2
      2801124.93     10120098.44       2799648.5     10120636.72
#Sta/Elev= 30
  4147.8 1756.22  4260.6 1756.78  4408.1 1750.29  4438.7 1749.41    4444 1749.86
  4469.2 1748.11  4568.2  1745.7    4642 1743.88  4810.9 1742.18  4967.5  1740.6
  4990.2 1737.82  4995.1 1736.59  4997.8 1736.09  5001.1 1736.59  5016.8 1737.88
  5023.3 1739.76  5084.5 1741.83  5123.3 1740.22  5187.1 1740.55  5257.2 1742.01
  5343.6 1742.42  5374.1 1743.88  5429.6 1745.12  5521.6 1748.79  5546.9 1749.01
  5578.2 1751.05    5608 1754.17  5638.5 1753.84  5644.8 1752.44  5719.3 1754.05
#Mann= 8 ,-1 , 0
  4147.8     .05       0  4568.2      .1       0  4810.9     .16       0
  4990.2     .05       0  4995.1    .035       0  5001.1     .05       0
  5429.6      .1       0  5578.2     .05       0
Bank Sta=4995.1,5001.1
XS Rating Curve= 0 ,0
Exp/Cntr=0.3,0.1

Type RM Length L Ch R = 1 ,6642    ,588,588,588
BEGIN DESCRIPTION:
KNOTT BRANCH 13.0
END DESCRIPTION:
XS GIS Cut Line= 2
      2801186.46     10119867.76      2799756.19       10119614.
#Sta/Elev= 30
  3905.2 1752.32  3957.9 1752.19  3974.3 1753.34  4045.3 1755.02  4125.1 1752.96
  4177.4  1752.8  4197.7 1750.92  4238.2 1749.39  4243.2 1750.07  4268.8 1748.28
  4356.3 1744.86  4497.2 1740.81  4593.9 1739.29  4693.4 1738.56  4786.7 1738.46
  4888.3 1735.75  4961.8  1737.2  4979.7 1736.39    4986    1733  4991.1 1733.98
    4997 1732.26  4999.8 1731.76    5003 1732.26  5010.2 1735.84  5020.3  1736.5
  5132.1 1740.51    5193 1744.31  5290.2 1748.59    5325 1750.61  5357.8  1749.4
#Mann= 8 ,-1 , 0
  3905.2     .05       0  4497.2      .1       0  4593.9     .05       0
  4693.4     .16       0  4961.8      .1       0    4997     .07       0
    5003      .1       0  5290.2     .05       0
Bank Sta=4997,5003
XS Rating Curve= 0 ,0
Exp/Cntr=0.3,0.1

Type RM Length L Ch R = 1 ,6054    ,450,450,450
BEGIN DESCRIPTION:
KNOTT BRANCH 12.0
END DESCRIPTION:
XS GIS Cut Line= 2
      2801517.13     10119467.89      2799848.44     10119006.51
#Sta/Elev= 30
  3683.6 1758.98  3765.2 1754.38  3794.7 1754.11  3837.8 1754.62    3868 1751.45
  3899.6  1750.5  3979.3 1750.17  4013.6 1747.42  4076.5 1747.46  4162.5 1744.49
  4211.3 1744.54  4273.6 1742.09  4325.5 1742.58  4439.6 1739.41    4546 1740.05
  4564.1 1737.95  4659.4  1737.9  4801.9 1733.81  4920.4 1732.49  4979.1 1733.62
  4994.2 1730.04  4996.9    1728  4999.6  1727.5  5002.9    1728  5010.2 1731.31
  5020.6    1733  5073.1 1734.67  5141.9 1739.49  5352.6 1749.12  5414.9 1753.29
#Mann= 8 ,-1 , 0
  3683.6      .1       0  3794.7     .05       0    3868      .1       0
  3899.6     .05       0  4162.5      .1       0  4996.9     .07       0
  5002.9      .1       0  5073.1     .05       0
Bank Sta=4996.9,5002.9
XS Rating Curve= 0 ,0
Exp/Cntr=0.3,0.1

Type RM Length L Ch R = 1 ,5604    ,821,821,821
BEGIN DESCRIPTION:
KNOTT BRANCH 11.0
END DESCRIPTION:
XS GIS Cut Line= 3
      2801678.57     10119029.57      2800655.84     10118829.64
       2799994.5     10118629.69
#Sta/Elev= 30
  3809.2 1777.31  3863.2 1772.56  3870.6 1773.08  3890.8 1769.98  3911.2 1769.83
    3952 1765.64  3992.7 1765.11  4020.1 1761.27  4062.6 1760.86  4104.8 1756.08
  4155.7 1755.42  4196.5 1750.76  4237.3 1751.25  4277.8 1747.11  4318.8 1747.83
  4359.5  1743.9  4451.2 1743.29  4545.6 1739.85  4756.9 1738.44  4919.1 1731.36
  4930.8 1730.42  4984.4 1729.62  4993.3 1726.37  4996.1 1725.87  4999.3 1726.37
  5015.7 1729.89    5047 1729.31  5207.3 1735.97  5407.4 1748.28  5542.2 1752.07
#Mann= 8 ,-1 , 0
  3809.2     .16       0  3863.2     .05       0  4062.6      .1       0
  4919.1     .05       0  4930.8      .1       0  4993.3     .07       0
  4999.3      .1       0  5207.3     .05       0
Bank Sta=4993.3,4999.3
XS Rating Curve= 0 ,0
Exp/Cntr=0.3,0.1

Type RM Length L Ch R = 1 ,4783    ,493,493,493
BEGIN DESCRIPTION:
KNOTT BRANCH 10.0
END DESCRIPTION:
XS GIS Cut Line= 2
      2801524.75      10118029.9      2800063.74     10118052.97
#Sta/Elev= 30
    4262 1777.03  4328.3 1772.61  4408.3 1764.33  4488.3 1757.92  4528.3 1755.55
  4548.3 1753.01  4568.3 1752.41  4588.3 1752.84  4612.7 1750.13  4628.3 1748.84
  4648.3 1748.57  4668.3 1746.23  4708.3 1744.97  4728.3 1742.26  4738.3 1741.67
  4778.4 1740.43  4798.4 1737.53  4828.4 1736.96  4855.8 1733.96  4908.7 1732.05
  4918.4 1732.21  4968.4 1726.41  4995.4 1724.59  4998.1 1724.09  5001.4 1724.59
  5118.4 1725.27  5478.8 1731.24  5599.9 1732.88  5689.2  1734.8  5723.2 1735.07
#Mann= 9 ,-1 , 0
    4262     .05       0  4612.7      .1       0  4855.8     .05       0
  4908.7      .1       0  4995.4     .07       0  5001.4      .1       0
  5478.8     .05       0  5599.9      .1       0  5689.2     .05       0
Bank Sta=4995.4,5001.4
XS Rating Curve= 0 ,0
Exp/Cntr=0.3,0.1

Type RM Length L Ch R = 1 ,4290    ,123,123,123
BEGIN DESCRIPTION:
Mapping XS ab3331ba
END DESCRIPTION:
XS GIS Cut Line= 3
      2801103.79     10117336.88      2800832.97     10117524.37
      2799838.15     10117803.03
#Sta/Elev= 30
  4523.4 1740.89  4631.1 1738.58  4704.3 1735.81  4820.5 1729.93  4910.3 1723.58
  4955.1 1722.42  4983.7 1721.58  4999.9 1719.62  5002.6 1719.12  5005.9 1719.62
  5023.6 1722.12    5052 1721.02  5057.2 1721.79  5091.3 1721.45  5096.5  1722.1
  5117.1 1721.32  5198.8 1721.44    5204 1722.15  5238.1 1721.38  5243.3 1722.19
  5272.2 1721.81  5277.4 1722.45  5480.6 1724.22  5683.8 1728.47  5757.3 1729.07
  5762.5 1729.85  5791.4 1729.59  5835.9 1731.31  5854.4 1733.93  5885.9 1734.31
#Mann= 5 ,-1 , 0
  4523.4     .05       0  4631.1      .1       0  4955.1     .05       0
  4999.9     .04       0  5005.9     .05       0
Bank Sta=4999.9,5005.9
XS Rating Curve= 0 ,0
Exp/Cntr=0.3,0.1

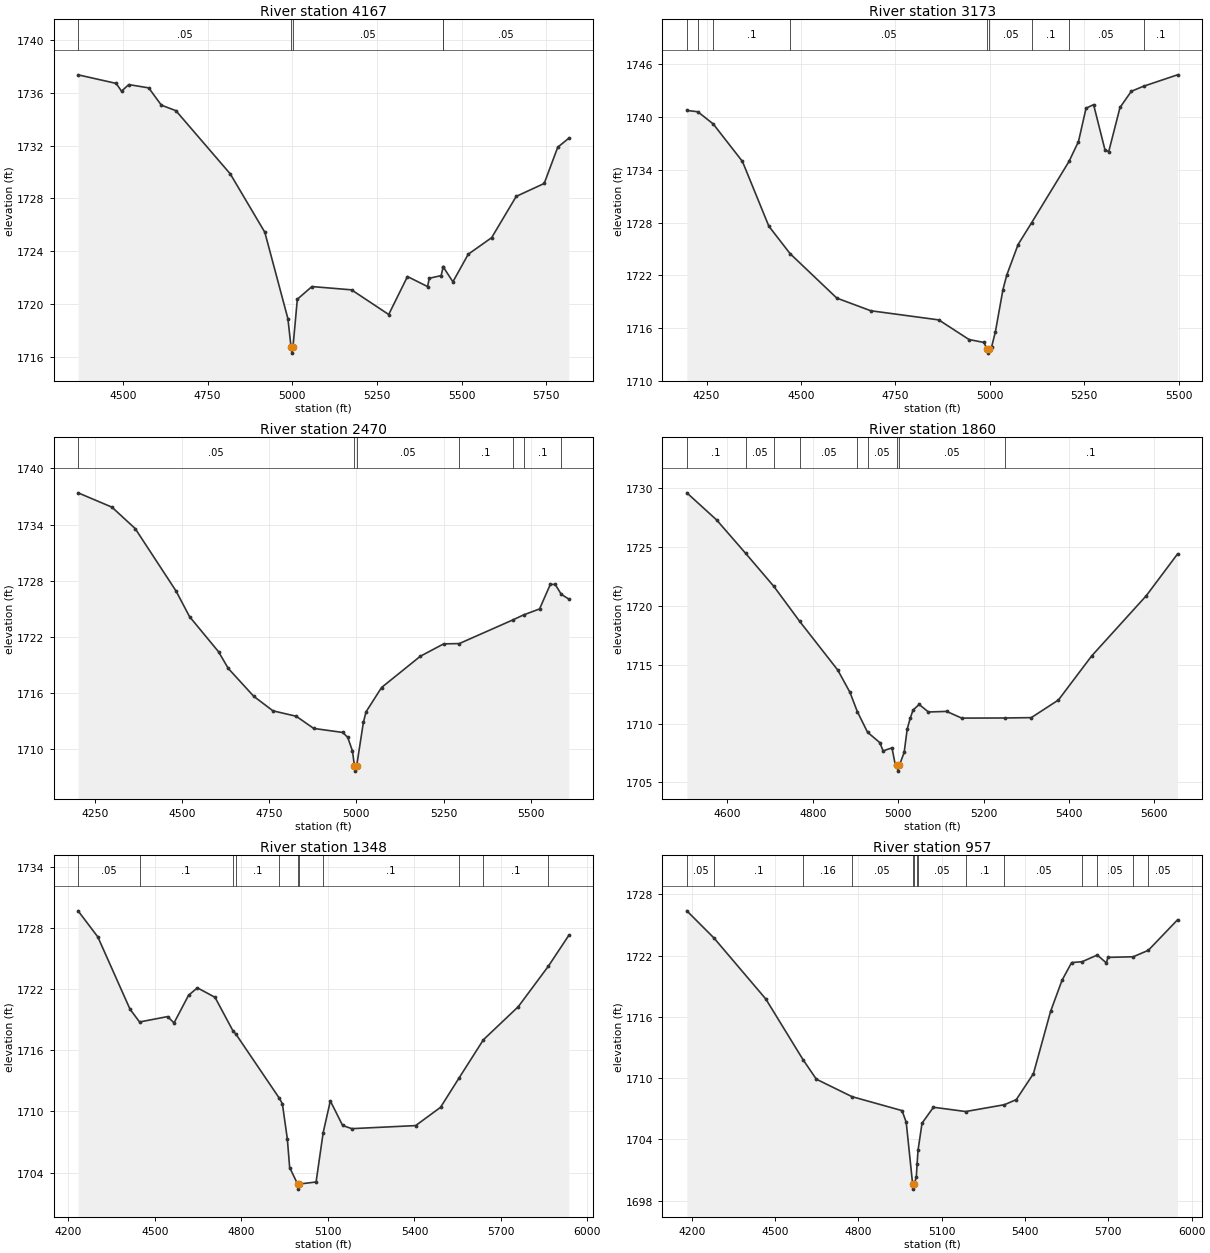
Type RM Length L Ch R = 1 ,4167    ,994,994,994
BEGIN DESCRIPTION:
KNOTT BRANCH 8.0
END DESCRIPTION:
XS GIS Cut Line= 3
      2801174.08     10117144.18      2800546.51     10117508.75
      2799848.64     10117696.24
#Sta/Elev= 30
  4367.6 1737.37  4480.1 1736.72  4495.8 1736.13  4517.3 1736.63  4576.1 1736.38
  4613.4 1735.07  4656.4 1734.65    4817 1729.85  4918.8 1725.43    4987 1718.87
  4996.1 1716.76  4998.8 1716.26  5002.1 1716.76  5014.8 1720.35  5057.9 1721.31
  5174.9 1721.06  5284.5 1719.19  5339.9 1722.07  5399.2 1721.31  5404.4 1721.94
  5439.2 1722.14  5445.4 1722.81  5445.8 1722.79    5474 1721.67  5519.2 1723.76
  5588.4 1725.02  5660.9 1728.15  5743.5 1729.13  5783.5 1731.88    5816 1732.56
#Mann= 5 ,-1 , 0
  4367.6     .05       0  4996.1     .04       0  5002.1     .05       0
  5445.4      .1       0  5445.8     .05       0
Bank Sta=4996.1,5002.1
XS Rating Curve= 0 ,0
Exp/Cntr=0.3,0.1

Type RM Length L Ch R = 1 ,3173    ,703,703,703
BEGIN DESCRIPTION:
KNOTT BRANCH 6.0
END DESCRIPTION:
XS GIS Cut Line= 2
       2800955.7      10116830.3       2799656.2      10116830.3
#Sta/Elev= 30
  4197.8 1740.76  4226.8 1740.61  4267.7 1739.22    4345 1734.96    4415 1727.59
  4471.4 1724.46    4595 1719.41    4685 1717.97    4865 1716.93    4945  1714.7
    4985 1714.36    4992 1713.65  4994.8 1713.15    4998 1713.65    5005 1713.86
    5015  1715.6    5035 1720.38    5045 1722.02    5075  1725.5  5111.1    1728
  5209.8 1734.95    5235 1737.22    5255 1741.01    5275 1741.42    5305  1736.3
    5315 1736.06    5345  1741.1    5375 1742.94  5407.2 1743.51  5497.3 1744.81
#Mann= 9 ,-1 , 0
  4197.8      .1       0  4226.8     .05       0  4267.7      .1       0
  4471.4     .05       0    4992     .03       0    4998     .05       0
  5111.1      .1       0  5209.8     .05       0  5407.2      .1       0
Bank Sta=4992,4998
XS Rating Curve= 0 ,0
Exp/Cntr=0.3,0.1

Type RM Length L Ch R = 1 ,2470    ,610,610,610
BEGIN DESCRIPTION:
KNOTT BRANCH 4.0
END DESCRIPTION:
XS GIS Cut Line= 2
      2801117.21     10116584.22      2799863.84       10115946.
#Sta/Elev= 30
  4202.3  1737.4  4299.4 1735.87  4366.1 1733.58  4482.9 1726.93  4521.8 1724.18
  4604.9 1720.43    4633 1718.64  4705.9 1715.67  4760.9 1714.12  4827.6 1713.54
  4877.7 1712.24    4961 1711.81  4975.2 1711.29  4988.9 1709.82  4994.6 1708.18
  4997.4 1707.68  5000.6 1708.18  5020.1 1712.88  5027.7 1714.01  5072.2 1716.61
  5183.4 1719.95  5250.2 1721.27  5294.9  1721.3  5449.2 1723.84  5479.1 1724.36
  5525.1    1725  5555.9 1727.62  5569.9 1727.62  5587.4 1726.56  5608.8 1726.06
#Mann= 7 ,-1 , 0
  4202.3     .05       0  4994.6    .035       0  5000.6     .05       0
  5294.9      .1       0  5449.2     .05       0  5479.1      .1       0
  5587.4     .05       0
Bank Sta=4994.6,5000.6
XS Rating Curve= 0 ,0
Exp/Cntr=0.3,0.1

Type RM Length L Ch R = 1 ,1860    ,512,512,512
BEGIN DESCRIPTION:
KNOTT BRANCH 3.0
END DESCRIPTION:
XS GIS Cut Line= 2
      2801140.32     10116230.52      2800379.02     10115369.26
#Sta/Elev= 30
  4504.8 1729.62  4574.7 1727.31  4642.4 1724.48  4708.7 1721.66  4769.1 1718.69
  4858.3 1714.55  4886.8 1712.66  4904.1 1711.02  4928.1 1709.26    4957 1708.37
  4964.5 1707.67  4985.4 1707.93    4993 1706.51  4996.7 1706.45  4999.4 1705.95
  5002.7 1706.45  5013.9 1707.54    5021 1709.52  5028.1 1710.45  5034.8 1711.15
    5049 1711.62  5070.8 1710.98  5113.4 1711.03  5148.6 1710.46  5249.1 1710.47
  5311.7  1710.5  5375.3    1712    5453 1715.74  5581.1 1720.87  5654.3 1724.42
#Mann= 9 ,-1 , 0
  4504.8      .1       0  4642.4     .05       0  4708.7      .1       0
  4769.1     .05       0  4904.1      .1       0  4928.1     .05       0
  4996.7     .03       0  5002.7     .05       0  5249.1      .1       0
Bank Sta=4996.7,5002.7
XS Rating Curve= 0 ,0
Exp/Cntr=0.3,0.1

Type RM Length L Ch R = 1 ,1348    ,391,391,391
BEGIN DESCRIPTION:
KNOTT BRANCH 2.0
END DESCRIPTION:
XS GIS Cut Line= 2
      2801840.06     10115761.42      2800241.99     10115177.52
#Sta/Elev= 30
  4233.7 1729.67  4302.2 1727.11  4413.7 1720.03  4446.9 1718.77  4544.1  1719.3
  4566.4 1718.68  4616.8 1721.39  4647.4 1722.12  4708.5 1721.19  4770.6 1717.91
  4781.2 1717.57  4931.4  1711.3  4942.1 1710.75  4959.4 1707.28  4967.3  1704.5
  4994.9 1702.88  4997.6 1702.38  5000.9 1702.88    5059 1703.08  5083.6 1707.93
  5108.4 1711.03    5151 1708.62  5182.9 1708.31  5404.1 1708.61  5490.4  1710.4
    5554 1713.25  5639.2 1717.03    5760 1720.27  5864.6 1724.25  5935.1 1727.26
#Mann= 11 ,-1 , 0
  4233.7     .05       0  4446.9      .1       0  4770.6     .05       0
  4781.2      .1       0  4931.4     .05       0  4994.9    .035       0
  5000.9     .05       0  5083.6      .1       0    5554     .05       0
  5639.2      .1       0  5864.6     .05       0
Bank Sta=4994.9,5000.9
XS Rating Curve= 0 ,0
Exp/Cntr=0.3,0.1

Type RM Length L Ch R = 1 ,957     ,816,816,816
BEGIN DESCRIPTION:
Mapping XS 6885f4ec
END DESCRIPTION:
XS GIS Cut Line= 3
       2801931.1     10115564.21      2801748.81     10115286.44
      2800354.09     10114948.59
#Sta/Elev= 30
  4181.9 1726.38  4279.9 1723.71  4466.4 1717.74  4600.9 1711.78  4648.3 1709.89
  4776.6 1708.18  4956.9 1706.81    4972 1705.68  4995.1 1699.62  4997.8 1699.12
  5001.1 1699.62  5008.4 1700.32  5011.1 1701.54  5014.6 1702.93    5029 1705.58
  5070.1 1707.14  5186.3 1706.72  5325.9 1707.39  5368.5 1707.89  5430.2 1710.43
    5492 1716.53  5533.1 1719.57  5567.7 1721.31  5605.8  1721.4  5660.1 1722.05
  5693.2 1721.27  5698.3 1721.82  5789.5 1721.88  5843.9 1722.51  5949.2  1725.5
#Mann= 14 ,-1 , 0
  4181.9     .05       0  4279.9      .1       0  4600.9     .16       0
  4776.6     .05       0  4995.1    .035       0  5001.1     .05       0
  5011.1      .1       0  5014.6     .05       0  5186.3      .1       0
  5325.9     .05       0  5605.8      .1       0  5660.1     .05       0
  5789.5      .1       0  5843.9     .05       0
Bank Sta=4995.1,5001.1
XS Rating Curve= 0 ,0
Exp/Cntr=0.3,0.1

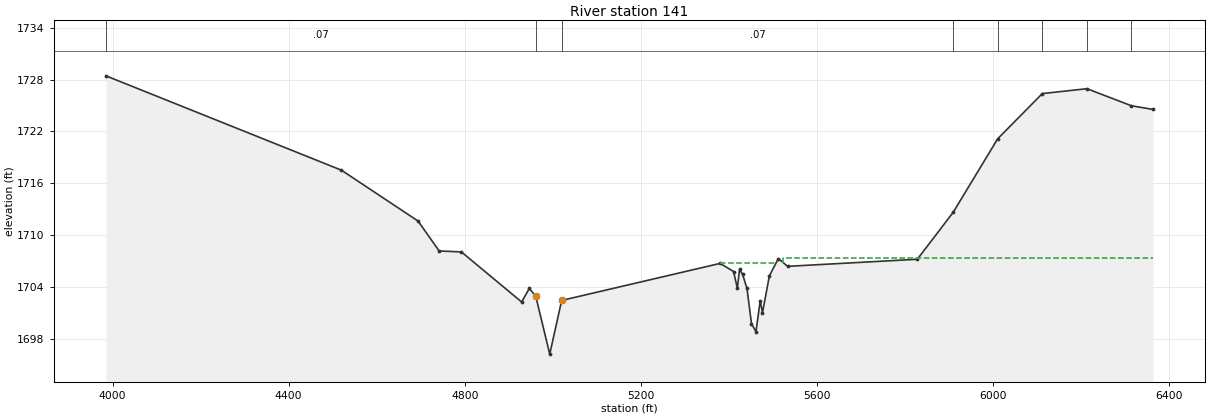
Type RM Length L Ch R = 1 ,141     ,0,0,0
BEGIN DESCRIPTION:
KNOTT BRANCH 1.0
END DESCRIPTION:
XS GIS Cut Line= 4
      2802039.99     10115653.73      2801916.96     10114761.76
      2801678.58     10114684.86       2800472.4     10114915.34
#Sta/Elev= 30
  3984.9 1728.44  4519.9 1717.51    4694 1711.62    4742 1708.15  4792.5 1708.04
  4929.4 1702.24  4946.8 1703.81  4961.4 1702.91  4993.2  1696.2  5020.3 1702.42
  5380.3 1706.71  5410.8 1705.77  5419.4 1703.83  5424.4 1706.01  5431.2 1705.45
  5441.3 1703.81  5451.5 1699.73  5461.7  1698.8  5471.4 1702.39  5476.5    1701
  5492.2 1705.27  5512.6 1707.27  5533.7 1706.37  5828.2 1707.19  5909.5 1712.61
  6010.9 1721.15  6112.2 1726.38  6213.5 1726.95  6314.8 1724.97  6363.8 1724.55
#Mann= 8 ,-1 , 0
  3984.9     .07       0  4961.4     .05       0  5020.3     .07       0
  5909.5     .05       0  6010.9      .1       0  6112.2     .05       0
  6213.5      .1       0  6314.8     .05       0
#XS Ineff= 2 ,-1
 5380.47 5504.92 1706.71 5523.54  6363.8 1707.33
Permanent Ineff=
       F       F
Bank Sta=4961.4,5020.3
XS Rating Curve= 0 ,0
Exp/Cntr=0.3,0.1

Chan Stop Cuts=-1
Use User Specified Reach Order=0
Composite Channel Slope=5