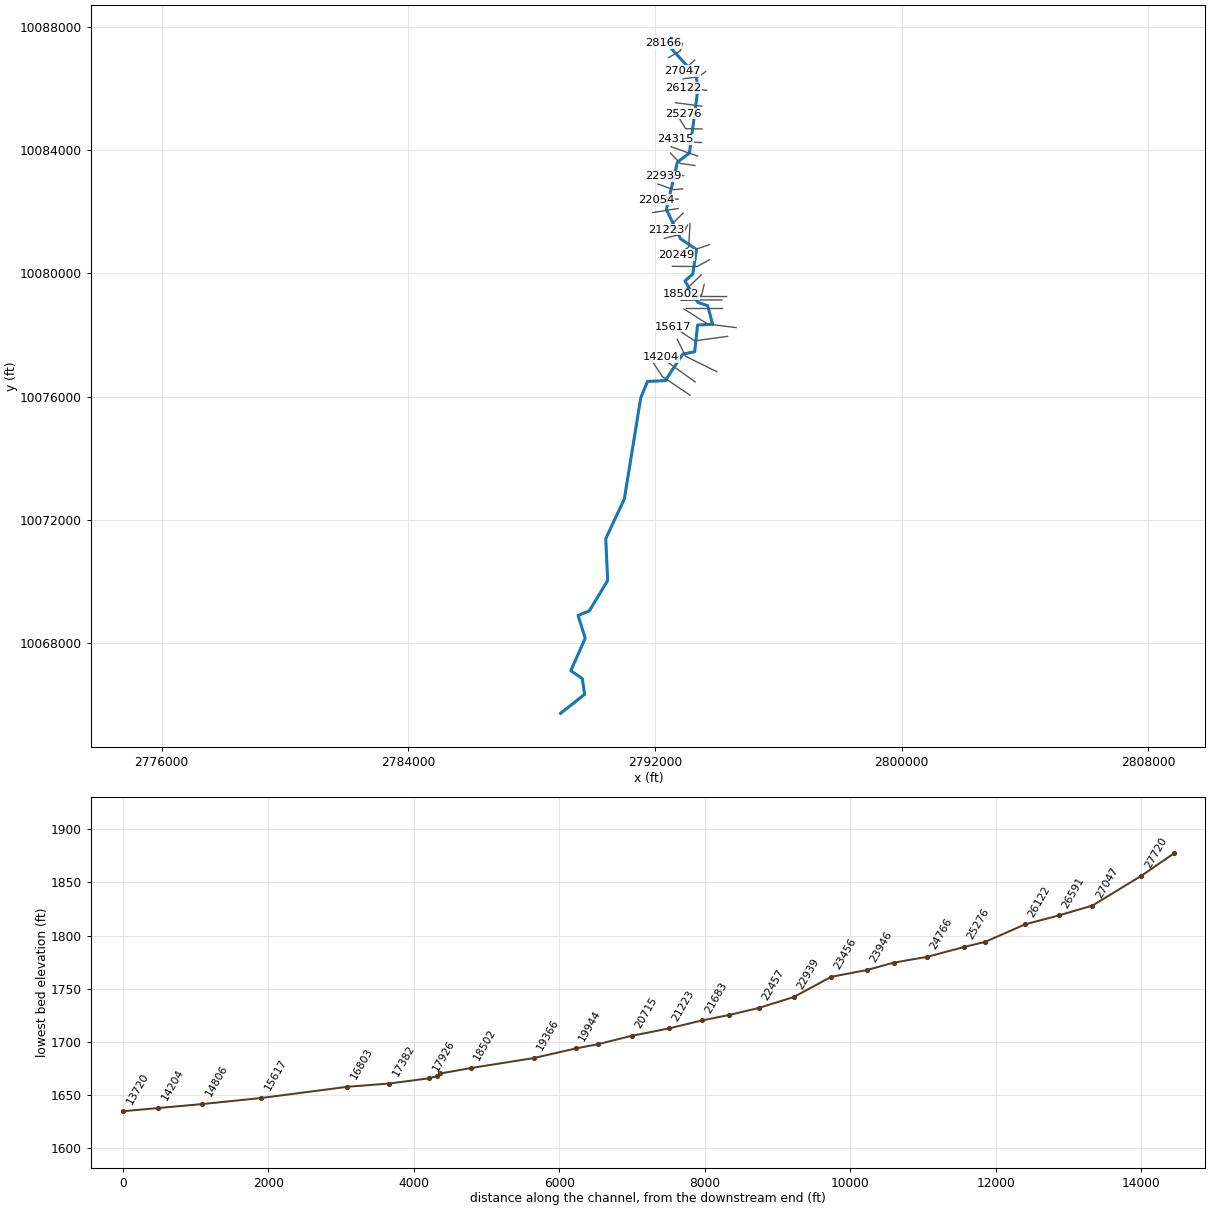
--- KUHLMAN CREEK.prj (project) ---

Proj Title=KUHLMAN CREEK Base Level Engineering
Current Plan=p01
Default Exp/Contr=0.3,0.1
English Units
Geom File=g01
Flow File=f01
Plan File=p01
Y Axis Title=Elevation
X Axis Title(PF)=Main Channel Distance
X Axis Title(XS)=Station
BEGIN DESCRIPTION:
KUHLMAN CREEK
END DESCRIPTION:
DSS Export Rating Curves= 0
DSS Export Rating Curve Sorted= 0
DSS Export Volume Flow Curves= 0
DXF OffsetX= 0
DXF OffsetY= 0
DXF ScaleX= 1
DXF ScaleY= 10

--- KUHLMAN CREEK.p01 (plan) ---

Plan Title=Multiple Run
Short Identifier=Multiple
Geom File=g01
Flow File=f01
Subcritical Flow
K Sum by GR= 0
Std Step Tol= 0.01
Critical Tol= 0.01
Num of Std Step Trials= 20
Max Error Tol= 0.3
Flow Tol Ratio= 0.001
Split Flow NTrial= 30
Split Flow Tol= 0.02
Split Flow Ratio= 0.02
Log Output Level= 0
Friction Slope Method= 1
Unsteady Friction Slope Method= 2
Unsteady Bridges Friction Slope Method= 1
Parabolic Critical Depth
Global Vel Dist=  1 , 1 , 1
Global Log Level= 0
CheckData=True
Encroach Param= -1, 0, 0, 0
BEGIN DESCRIPTION:
Multiple Run
END DESCRIPTION:

--- KUHLMAN CREEK.f01 (steady flow) ---

Flow Title=Multiple
Program Version=4.10
Number of Profiles= 7
Profile Names=10-year,25-year,50-year,1pct_min,100-year,1pct_plu,500-year
River Rch & RM=KUHLMAN CREEK,Reach-1         ,28166
     686     985    1241    1148    1553    2100    2436
River Rch & RM=KUHLMAN CREEK,Reach-1         ,19944
     873    1268    1613    1502    2032    2748    3236
River Rch & RM=KUHLMAN CREEK,Reach-1         ,17382
    1344    2000    2585    2443    3304    4469    5422
River Rch & RM=KUHLMAN CREEK,Reach-1         ,14806
    1696    2535    3284    3105    4199    5679    6901
River Rch & RM=KUHLMAN CREEK,Reach-1         ,1729
    2032    3065    3992    3795    5132    6940    8524
Boundary for River Rch & Prof#=KUHLMAN CREEK,Reach-1         , 1
Up Type= 0
Dn Type= 3
Dn Slope=0.0055
Boundary for River Rch & Prof#=KUHLMAN CREEK,Reach-1         , 2
Up Type= 0
Dn Type= 3
Dn Slope=0.0055
Boundary for River Rch & Prof#=KUHLMAN CREEK,Reach-1         , 3
Up Type= 0
Dn Type= 3
Dn Slope=0.0055
Boundary for River Rch & Prof#=KUHLMAN CREEK,Reach-1         , 4
Up Type= 0
Dn Type= 3
Dn Slope=0.0055
Boundary for River Rch & Prof#=KUHLMAN CREEK,Reach-1         , 5
Up Type= 0
Dn Type= 3
Dn Slope=0.0055
Boundary for River Rch & Prof#=KUHLMAN CREEK,Reach-1         , 6
Up Type= 0
Dn Type= 3
Dn Slope=0.0055
Boundary for River Rch & Prof#=KUHLMAN CREEK,Reach-1         , 7
Up Type= 0
Dn Type= 3
Dn Slope=0.0055
DSS Import GetInterval= 0
DSS Import GetPeak= 0
DSS Import FillOption= 0

--- KUHLMAN CREEK.g01 (geometry) ---

Geom Title=Existing Conditions
Program Version=4.10

River Reach=KUHLMAN CREEK   ,Reach-1
Reach XY= 30
      2792534.05     10087625.37      2792501.92      10087320.4
      2793323.63     10086426.69      2793398.54     10086034.27
      2793115.77     10083904.84      2792725.69     10083607.25
      2792369.65     10082074.23      2792826.29     10081127.48
      2793344.06     10080776.54      2793225.86     10079984.81
      2792970.85     10079755.08      2793388.62     10079063.57
      2793708.47     10078953.73      2793867.39     10078353.52
       2793381.9     10078327.87      2793287.23     10077463.68
      2792895.09     10077380.26      2792334.37     10076524.56
      2791756.38     10076497.89      2791536.89     10075962.96
      2791006.58     10072689.51      2790401.98     10071399.05
      2790465.78     10070044.68      2789868.89     10069058.25
      2789504.71     10068907.55      2789736.63      10068169.4
      2789269.06     10067119.01      2789641.97     10066862.64
      2789716.71     10066352.22      2788938.47     10065733.73

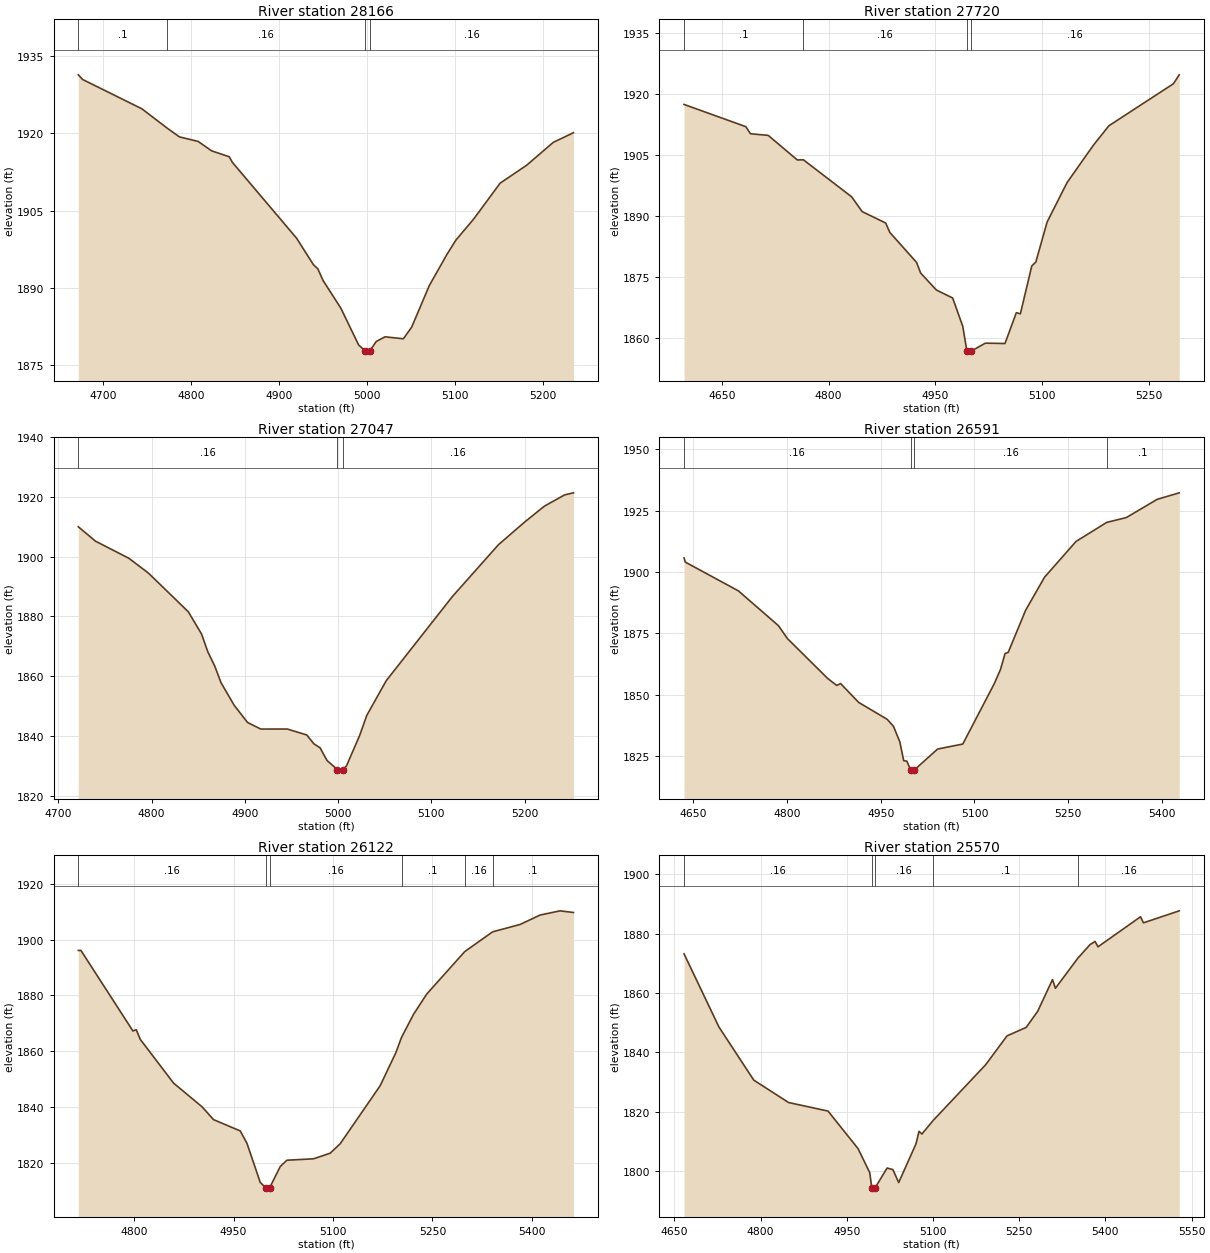
Type RM Length L Ch R = 1 ,28166   ,446,446,446
BEGIN DESCRIPTION:
UNT050 IN NNOGR 22.0
END DESCRIPTION:
XS GIS Cut Line= 3
      2792810.42     10087599.64      2792664.55     10087509.34
      2792275.63     10087467.67
#Sta/Elev= 30
  4671.7 1931.39  4676.7 1930.48    4744 1924.78    4773 1920.99  4786.6 1919.33
  4807.8 1918.45  4823.2 1916.62  4843.3 1915.46  4846.7  1914.4  4919.8 1899.63
  4938.8 1894.51  4943.9 1893.69  4949.9  1891.4  4970.1 1886.03  4990.2  1878.9
  4997.2  1877.8    5000  1877.3  5003.2  1877.8  5010.3 1879.56  5020.3 1880.47
  5041.1 1880.09  5050.5 1882.34  5070.6 1890.44  5090.7 1896.51  5100.8 1899.27
  5120.9 1903.34  5151.1 1910.34  5181.3 1913.83  5211.4 1918.26  5234.4 1920.14
#Mann= 4 ,-1 , 0
  4671.7      .1       0    4773     .16       0  4997.2     .07       0
  5003.2     .16       0
Bank Sta=4997.2,5003.2
XS Rating Curve= 0 ,0
Exp/Cntr=0.3,0.1

Type RM Length L Ch R = 1 ,27720   ,673,673,673
BEGIN DESCRIPTION:
UNT050 IN NNOGR 21.0
END DESCRIPTION:
XS GIS Cut Line= 3
      2792890.85     10087456.82      2792817.94     10087215.95
       2792431.3     10086997.98
#Sta/Elev= 30
  4597.1 1917.43  4683.9 1911.96  4690.4 1910.22  4715.3 1909.82  4756.2 1903.78
  4764.8 1903.81  4832.5 1894.71  4847.3 1891.07  4880.3 1888.27  4886.1 1885.96
  4923.7 1878.58  4929.4 1875.97  4951.5 1871.79  4974.4 1869.83  4988.6 1862.86
  4994.4 1856.77  4997.1 1856.27  5000.4 1856.77  5020.3 1858.72  5047.9 1858.64
  5063.8 1866.21  5069.5 1865.94  5085.5  1877.7  5091.2 1878.67  5107.1 1888.53
  5135.1 1898.22  5172.1 1907.41  5193.8 1912.18  5284.4 1922.51  5292.6 1924.71
#Mann= 4 ,-1 , 0
  4597.1      .1       0  4764.8     .16       0  4994.4     .07       0
  5000.4     .16       0
Bank Sta=4994.4,5000.4
XS Rating Curve= 0 ,0
Exp/Cntr=0.3,0.1

Type RM Length L Ch R = 1 ,27047   ,456,456,456
BEGIN DESCRIPTION:
UNT050 IN NNOGR 20.0
END DESCRIPTION:
XS GIS Cut Line= 2
      2793289.55     10086919.06      2792893.75     10086564.93
#Sta/Elev= 30
  4721.4 1910.04  4739.9 1905.21  4775.8 1899.46  4796.8 1894.47  4839.4 1881.57
  4853.6 1874.11  4860.3 1868.18  4867.8 1863.34  4874.5  1857.8  4888.7 1850.19
  4902.9  1844.5  4917.1 1842.28  4945.6 1842.29  4966.5  1840.3    4974 1837.36
  4980.7 1836.01  4988.2 1831.74  4999.4 1828.69  5002.1 1828.19  5005.4 1828.69
  5009.1 1829.97  5023.3 1840.25  5030.8 1846.85  5051.7 1858.49  5122.8 1886.73
  5172.1 1904.05  5200.5 1911.72  5221.4 1916.96  5243.1 1920.73  5252.5 1921.41
#Mann= 3 ,-1 , 0
  4721.4     .16       0  4999.4     .07       0  5005.4     .16       0
Bank Sta=4999.4,5005.4
XS Rating Curve= 0 ,0
Exp/Cntr=0.3,0.1

Type RM Length L Ch R = 1 ,26591   ,469,469,469
BEGIN DESCRIPTION:
UNT050 IN NNOGR 19.0
END DESCRIPTION:
XS GIS Cut Line= 3
      2793643.71     10086551.01      2793421.49      10086377.4
      2792914.53     10086314.89
#Sta/Elev= 30
    4635 1905.72    4637 1904.03    4722 1892.33  4786.2 1878.17  4800.7 1872.89
  4864.9 1856.74  4879.4 1853.89  4885.7 1854.63  4914.7 1846.96  4960.4 1840.08
  4970.4 1837.21  4980.5 1830.94  4986.7 1823.28  4991.7 1823.11  4997.7 1819.54
  5000.4 1819.04  5003.7 1819.54    5041 1828.02  5081.3 1830.05  5131.6 1854.55
  5141.7 1860.41    5149 1866.86    5154 1867.33    5182  1884.5  5212.2 1897.89
  5262.6 1912.43  5311.6 1920.15  5343.2 1922.14  5392.5 1929.54  5427.8 1932.19
#Mann= 4 ,-1 , 0
    4635     .16       0  4997.7     .07       0  5003.7     .16       0
  5311.6      .1       0
Bank Sta=4997.7,5003.7
XS Rating Curve= 0 ,0
Exp/Cntr=0.3,0.1

Type RM Length L Ch R = 1 ,26122   ,552,552,552
BEGIN DESCRIPTION:
UNT050 IN NNOGR 18.0
END DESCRIPTION:
XS GIS Cut Line= 2
      2793671.49      10085939.9       2792928.4     10086016.29
#Sta/Elev= 30
  4715.7 1896.12  4719.7 1896.12  4798.1 1867.23  4803.1 1867.69  4809.2 1864.22
  4859.5 1848.52  4902.3 1840.05  4919.8 1835.42    4960 1831.38  4970.1 1826.96
  4990.2 1812.91  4998.4    1811  5001.2  1810.5  5004.4    1811  5020.3 1818.59
  5030.4 1820.87  5070.6 1821.38  5095.6 1823.38  5110.8 1826.78  5171.1  1847.6
  5194.7 1859.42  5203.3 1864.92  5221.4  1873.2  5241.5 1880.52  5298.7 1895.71
  5340.7 1902.79  5382.2 1905.44  5412.4 1908.82  5442.5 1910.33  5462.7 1909.73
#Mann= 6 ,-1 , 0
  4715.7     .16       0  4998.4     .07       0  5004.4     .16       0
  5203.3      .1       0  5298.7     .16       0  5340.7      .1       0
Bank Sta=4998.4,5004.4
XS Rating Curve= 0 ,0
Exp/Cntr=0.3,0.1

Type RM Length L Ch R = 1 ,25570   ,294,294,294
BEGIN DESCRIPTION:
UNT050 IN NNOGR 17.0
END DESCRIPTION:
XS GIS Cut Line= 2
      2793518.73     10085426.01      2792664.53     10085537.12
#Sta/Elev= 30
    4667 1873.16  4727.8 1848.51  4788.3 1830.66  4848.8 1823.12  4917.5 1820.24
  4969.8 1807.58    4990 1799.53  4993.6 1794.47  4996.4 1793.97  4999.6 1794.47
  5020.2 1801.07  5030.3 1800.55  5040.4 1796.19  5070.6 1809.26  5075.7 1813.42
  5080.8 1812.52  5100.5 1817.11  5191.7 1835.84  5228.9 1845.56  5262.2  1848.4
  5282.4 1853.89    5308 1864.51    5313 1861.57  5351.9 1871.65  5373.2 1876.26
    5382 1877.33  5387.1 1875.53  5461.1 1885.64  5466.2  1883.6  5528.4 1887.64
#Mann= 5 ,-1 , 0
    4667     .16       0  4993.6     .07       0  4999.6     .16       0
  5100.5      .1       0  5351.9     .16       0
Bank Sta=4993.6,4999.6
XS Rating Curve= 0 ,0
Exp/Cntr=0.3,0.1

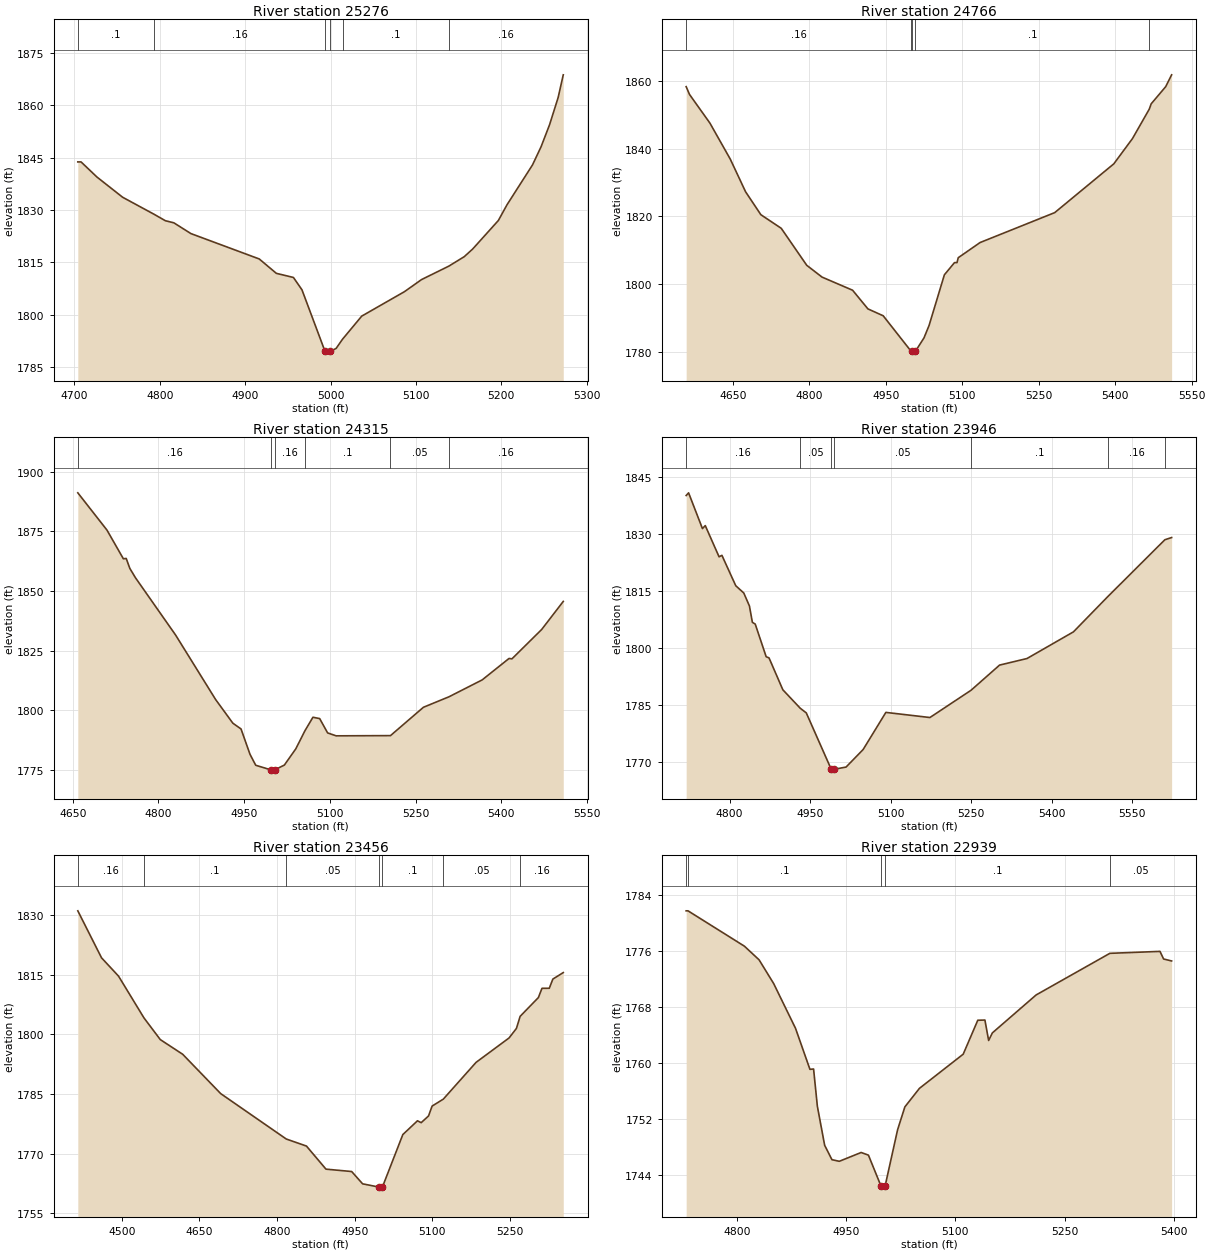
Type RM Length L Ch R = 1 ,25276   ,510,510,510
BEGIN DESCRIPTION:
UNT050 IN NNOGR 16.0
END DESCRIPTION:
XS GIS Cut Line= 2
      2793490.95     10085182.95      2792922.45     10085182.95
#Sta/Elev= 30
    4704 1843.77  4707.8 1843.77  4726.5 1839.43  4756.5 1833.66    4793 1828.83
  4806.5 1826.95  4816.5 1826.34  4836.5 1823.26  4916.5    1816  4936.5 1811.89
  4956.5 1810.71  4966.5 1807.18  4993.5 1789.56  4996.2 1789.06  4999.5 1789.56
  5006.5 1790.41    5014 1793.04  5036.5 1799.65  5086.5 1806.64  5106.5  1810.1
  5138.4 1813.94  5156.5 1816.65  5166.5 1818.87  5196.5 1827.01  5206.5 1831.46
  5236.5 1842.92  5246.5  1848.1  5256.5 1854.44  5266.5 1862.19  5272.5 1868.69
#Mann= 6 ,-1 , 0
    4704      .1       0    4793     .16       0  4993.5     .07       0
  4999.5     .16       0    5014      .1       0  5138.4     .16       0
Bank Sta=4993.5,4999.5
XS Rating Curve= 0 ,0
Exp/Cntr=0.3,0.1

Type RM Length L Ch R = 1 ,24766   ,451,451,451
BEGIN DESCRIPTION:
UNT050 IN NNOGR 15.0
END DESCRIPTION:
XS GIS Cut Line= 3
      2793524.95     10084687.31      2792993.72     10084695.12
      2792772.92     10085053.58
#Sta/Elev= 30
  4558.4 1858.24  4564.9 1855.95  4604.9 1847.52  4644.9  1836.9  4674.9 1827.29
  4704.9 1820.53  4744.9 1816.52  4794.9 1805.63  4824.9 1802.15  4884.9 1798.28
  4914.9 1792.79  4944.9 1790.76  4999.4 1780.36  5001.9 1780.26  5004.7 1779.76
  5007.9 1780.26  5024.9 1784.24  5034.9 1787.91  5064.9 1802.82  5084.8 1806.42
  5089.7 1806.42  5092.1 1807.86    5135 1812.33  5281.4 1821.14  5397.3 1835.51
    5434 1842.97  5466.9 1851.63  5470.6 1853.18  5499.1 1858.24  5510.7 1861.72
#Mann= 5 ,-1 , 0
  4558.4     .16       0  4999.4      .1       0  5001.9     .07       0
  5007.9      .1       0  5466.9     .16       0
Bank Sta=5001.9,5007.9
XS Rating Curve= 0 ,0
Exp/Cntr=0.3,0.1

Type RM Length L Ch R = 1 ,24315   ,369,369,369
BEGIN DESCRIPTION:
UNT050 IN NNOGR 14.0
END DESCRIPTION:
XS GIS Cut Line= 3
      2793509.39      10084244.6      2793090.07     10084265.43
      2792668.16     10084346.17
#Sta/Elev= 30
  4658.9 1891.17  4709.9 1875.55  4738.6 1863.52  4743.6 1863.64  4749.9 1859.49
  4759.9 1855.51    4830 1831.54  4900.1 1804.47  4930.2 1794.56  4944.5 1792.15
  4960.2 1781.52  4970.2 1776.93  4997.2 1774.97    5000 1774.47  5003.2 1774.97
  5020.3 1777.01  5040.3 1783.81  5056.4 1791.44  5070.3 1797.06  5082.1  1796.5
    5096 1790.49  5110.9 1789.27    5206 1789.36  5263.6 1801.24  5308.4 1805.65
  5366.4 1812.72  5413.4 1821.71  5418.5 1821.55  5470.5 1833.86  5508.3 1845.63
#Mann= 6 ,-1 , 0
  4658.9     .16       0  4997.2     .07       0  5003.2     .16       0
  5056.4      .1       0    5206     .05       0  5308.4     .16       0
Bank Sta=4997.2,5003.2
XS Rating Curve= 0 ,0
Exp/Cntr=0.3,0.1

Type RM Length L Ch R = 1 ,23946   ,490,490,490
BEGIN DESCRIPTION:
UNT050 IN NNOGR 13.0
END DESCRIPTION:
XS GIS Cut Line= 2
      2793379.81     10083807.96      2792525.69     10084106.55
#Sta/Elev= 30
    4719 1840.03  4723.5 1840.74  4749.3 1831.33  4754.6 1832.11  4780.3  1823.9
  4785.6 1824.29  4811.4 1816.29  4826.4 1814.36  4836.9 1810.95  4842.4 1806.65
  4847.7 1806.19  4868.1 1797.59  4873.4 1797.29  4899.2 1788.89  4931.5 1784.05
  4942.9  1782.8  4989.3 1767.98  4992.1 1767.48  4995.3 1767.98    5017 1768.55
  5048.8 1773.16  5091.2 1782.94  5173.3 1781.59  5249.9 1788.76  5303.1 1795.39
  5354.2 1797.12  5440.8 1804.14  5505.1 1813.46  5611.2 1828.39  5623.8 1828.97
#Mann= 7 ,-1 , 0
    4719     .16       0  4931.5     .05       0  4989.3    .035       0
  4995.3     .05       0  5249.9      .1       0  5505.1     .16       0
  5611.2     .05       0
Bank Sta=4989.3,4995.3
XS Rating Curve= 0 ,0
Exp/Cntr=0.3,0.1

Type RM Length L Ch R = 1 ,23456   ,517,517,517
BEGIN DESCRIPTION:
UNT050 IN NNOGR 12.0
END DESCRIPTION:
XS GIS Cut Line= 3
      2793296.46      10083502.4      2792824.27      10083564.9
      2792504.82     10083898.24
#Sta/Elev= 30
    4415 1831.01  4460.8 1819.21  4493.7  1814.6  4542.8 1804.11  4574.4 1798.65
  4617.7 1794.96  4691.1 1785.08  4817.8 1773.67  4856.8  1771.9  4894.5  1766.1
  4944.2  1765.5  4965.3 1762.41  4997.5 1761.58  5000.3 1761.08  5003.5 1761.58
    5043 1774.79  5071.3 1778.25  5078.5 1777.78  5092.7 1779.47  5099.6 1781.95
  5121.2 1783.69  5184.5 1792.93  5248.3 1799.07  5262.5 1801.46  5269.7  1804.5
  5304.9 1809.21  5311.9 1811.54    5326 1811.55  5332.9 1813.86    5353 1815.49
#Mann= 7 ,-1 , 0
    4415     .16       0  4542.8      .1       0  4817.8     .05       0
  4997.5    .035       0  5003.5      .1       0  5121.2     .05       0
  5269.7     .16       0
Bank Sta=4997.5,5003.5
XS Rating Curve= 0 ,0
Exp/Cntr=0.3,0.1

Type RM Length L Ch R = 1 ,22939   ,482,482,482
BEGIN DESCRIPTION:
UNT050 IN NNOGR 11.0
END DESCRIPTION:
XS GIS Cut Line= 2
      2792928.44     10083176.01      2792262.61     10083148.27
#Sta/Elev= 30
  4730.4  1781.8  4732.9  1781.8  4810.4 1776.74  4830.5 1774.79  4850.5  1771.4
  4880.5    1765  4900.3 1759.13  4905.3 1759.18  4910.5 1753.84  4920.5 1748.27
  4930.5 1746.21  4940.6 1745.98  4970.6 1747.24  4980.6 1746.86  4997.6  1742.5
  5000.4    1742  5003.6  1742.5  5020.6 1750.48  5030.6 1753.76  5050.6 1756.41
  5110.7  1761.3  5130.7 1766.15  5140.5 1766.18  5145.6 1763.26  5150.7 1764.34
  5210.8 1769.77    5312 1775.72  5380.8    1776  5385.8 1774.91  5396.8 1774.63
#Mann= 5 ,-1 , 0
  4730.4     .05       0  4732.9      .1       0  4997.6     .07       0
  5003.6      .1       0    5312     .05       0
Bank Sta=4997.6,5003.6
XS Rating Curve= 0 ,0
Exp/Cntr=0.3,0.1

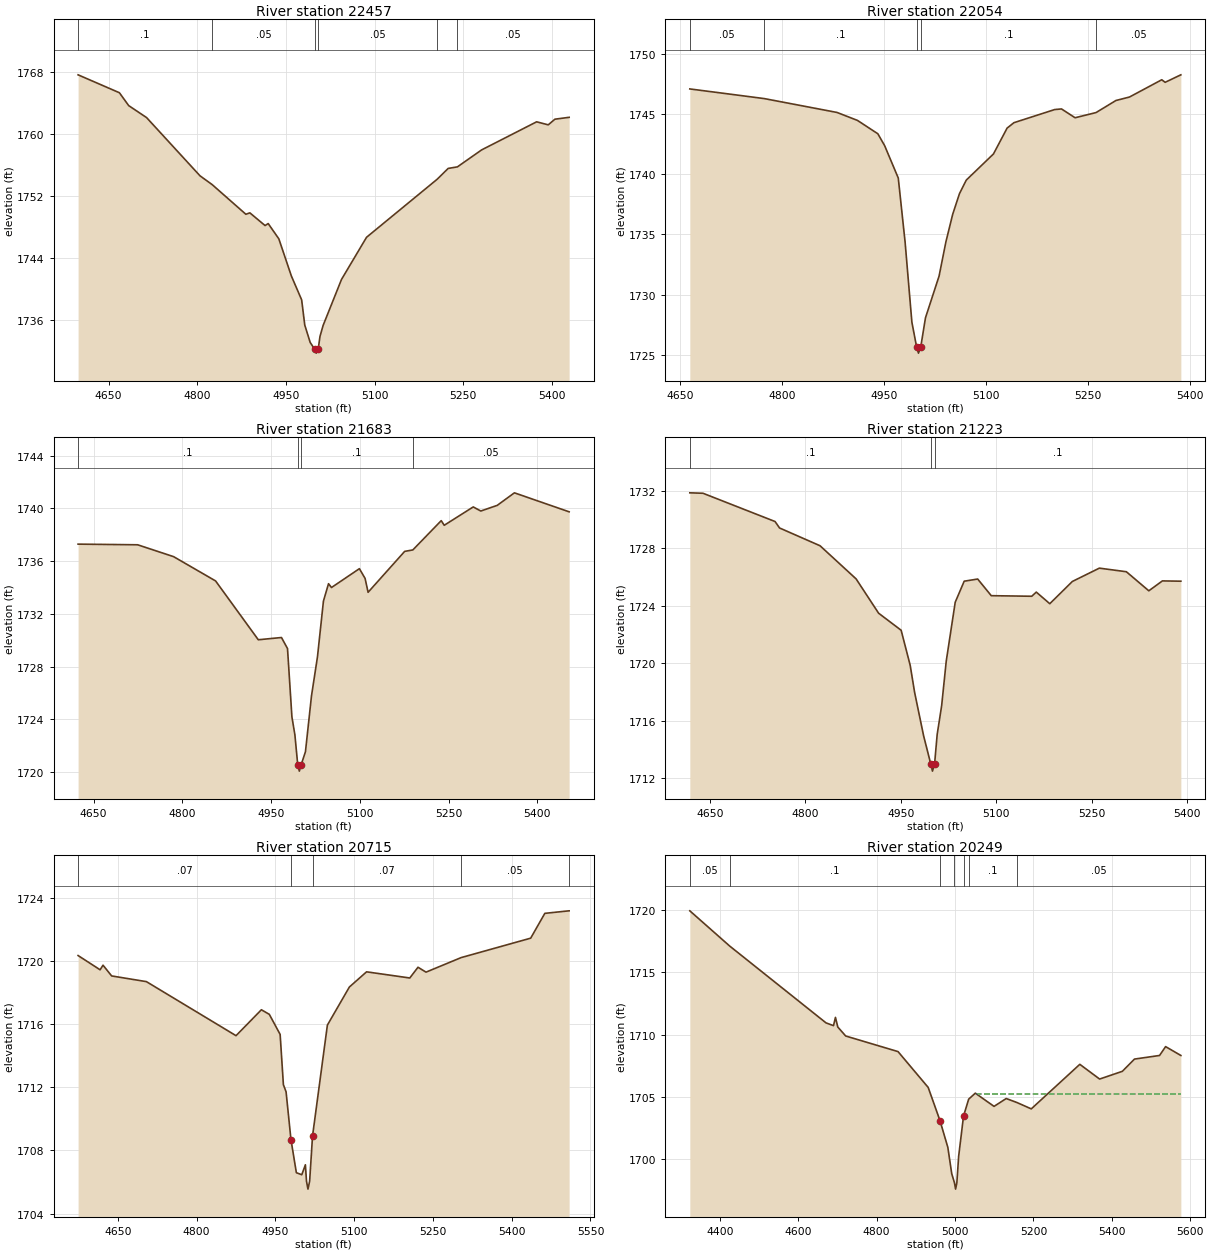
Type RM Length L Ch R = 1 ,22457   ,403,403,403
BEGIN DESCRIPTION:
UNT050 IN NNOGR 10.0
END DESCRIPTION:
XS GIS Cut Line= 3
      2792893.69     10082745.45      2792608.99     10082717.67
      2792095.14     10082898.22
#Sta/Elev= 30
  4598.5 1767.61  4668.4  1765.3  4684.1 1763.64  4714.3  1762.1  4804.7 1754.59
  4825.2 1753.46  4882.3 1749.63  4889.1 1749.81  4914.8 1748.17  4920.1 1748.43
  4938.1 1746.46  4959.3 1741.67  4976.7 1738.59    4982 1735.33  4991.1 1733.11
  4998.7 1732.22  5001.4 1731.72  5004.7 1732.22  5007.7 1733.87    5013 1735.29
  5044.1 1741.22  5086.5 1746.66  5205.9 1754.14  5224.6 1755.54  5240.2 1755.74
  5281.2 1757.93  5374.2 1761.55  5393.9 1761.16  5405.2 1761.89  5429.2 1762.13
#Mann= 6 ,-1 , 0
  4598.5      .1       0  4825.2     .05       0  4998.7    .035       0
  5004.7     .05       0  5205.9      .1       0  5240.2     .05       0
Bank Sta=4998.7,5004.7
XS Rating Curve= 0 ,0
Exp/Cntr=0.3,0.1

Type RM Length L Ch R = 1 ,22054   ,371,371,371
BEGIN DESCRIPTION:
UNT050 IN NNOGR 9.0
END DESCRIPTION:
XS GIS Cut Line= 2
      2792754.88     10082412.12      2792033.01     10082398.24
#Sta/Elev= 30
    4664 1747.07  4773.4 1746.27  4880.4 1745.12  4910.5 1744.46  4940.5 1743.35
  4950.5 1742.36  4970.5 1739.68  4980.5 1734.39  4990.5 1727.73  4997.5 1725.66
  5000.2 1725.16  5003.5 1725.66  5010.5 1728.09  5030.5 1731.55  5040.5 1734.38
  5050.5 1736.67  5060.5 1738.39  5070.5 1739.51  5110.5 1741.68  5130.5 1743.82
  5140.5 1744.27  5200.5 1745.36  5210.5 1745.41  5230.5 1744.68  5261.3 1745.11
  5290.5 1746.11  5310.5  1746.4  5357.9 1747.83  5362.9 1747.62    5386 1748.24
#Mann= 5 ,-1 , 0
    4664     .05       0  4773.4      .1       0  4997.5     .07       0
  5003.5      .1       0  5261.3     .05       0
Bank Sta=4997.5,5003.5
XS Rating Curve= 0 ,0
Exp/Cntr=0.3,0.1

Type RM Length L Ch R = 1 ,21683   ,460,460,460
BEGIN DESCRIPTION:
UNT050 IN NNOGR 8.0
END DESCRIPTION:
XS GIS Cut Line= 2
      2792747.92     10082106.57      2791928.48     10081974.62
#Sta/Elev= 30
  4623.9 1737.28  4724.6 1737.23  4785.4 1736.33  4856.3 1734.49  4928.5 1730.03
  4967.7  1730.2  4977.9 1729.36  4985.3 1724.19  4990.4 1722.81  4995.1 1720.57
  4997.9 1720.07  5001.1 1720.57  5008.2 1721.54  5018.4 1725.77  5028.5 1728.73
  5038.6 1732.96  5047.2 1734.28  5052.2 1733.99  5099.4 1735.42    5109 1734.68
  5114.1 1733.63  5175.9 1736.73  5189.7 1736.84  5237.7 1739.06  5242.8 1738.71
  5291.8  1740.1  5304.6 1739.79  5332.4 1740.22  5361.4 1741.17  5453.9 1739.73
#Mann= 4 ,-1 , 0
  4623.9      .1       0  4995.1     .07       0  5001.1      .1       0
  5189.7     .05       0
Bank Sta=4995.1,5001.1
XS Rating Curve= 0 ,0
Exp/Cntr=0.3,0.1

Type RM Length L Ch R = 1 ,21223   ,508,508,508
BEGIN DESCRIPTION:
UNT050 IN NNOGR 7.0
END DESCRIPTION:
XS GIS Cut Line= 2
      2792907.64     10081953.81      2792358.99     10081412.12
#Sta/Elev= 30
  4618.7 1731.88  4639.4 1731.85  4752.5 1729.88  4759.6 1729.43  4823.2 1728.19
  4879.8 1725.88  4915.1 1723.49  4950.5  1722.3  4964.7 1719.86  4971.7 1717.96
  4985.8 1714.94    4997 1712.98  4999.7 1712.48    5003 1712.98  5007.1 1715.04
  5014.1 1717.04  5021.3 1720.14  5035.4 1724.25  5049.5 1725.72  5070.7 1725.87
    5092 1724.71  5155.6 1724.67  5162.7 1724.96  5183.9 1724.15  5219.3  1725.7
  5261.7 1726.63  5304.1 1726.38  5339.4 1725.05  5360.7 1725.74  5389.7 1725.72
#Mann= 3 ,-1 , 0
  4618.7      .1       0    4997     .07       0    5003      .1       0
Bank Sta=4997,5003
XS Rating Curve= 0 ,0
Exp/Cntr=0.3,0.1

Type RM Length L Ch R = 1 ,20715   ,466,466,466
BEGIN DESCRIPTION:
UNT050 IN NNOGR 6.0
END DESCRIPTION:
XS GIS Cut Line= 3
      2793053.42     10081564.85      2792907.61     10081287.12
      2792303.44     10081141.29
#Sta/Elev= 30
  4574.2 1720.33  4616.1 1719.43  4621.7 1719.72  4638.1 1719.04  4704.3 1718.68
    4875 1715.26  4923.3  1716.9  4938.4 1716.61    4959 1715.34  4965.2 1712.16
  4970.3 1711.71  4979.6 1708.69  4989.9 1706.59  5000.2 1706.46  5007.1 1707.09
  5009.2 1706.05    5012 1705.55  5015.2 1706.05  5020.7 1708.91    5049 1715.93
  5090.9 1718.34  5123.6  1719.3  5205.9 1718.91  5221.6 1719.59  5236.8 1719.28
  5303.7  1720.2  5436.2 1721.43  5463.1    1723  5509.1 1723.16  5509.4 1723.16
#Mann= 5 ,-1 , 0
  4574.2     .07       0  4979.6     .05       0  5020.7     .07       0
  5303.7     .05       0  5509.1      .1       0
Bank Sta=4979.6,5020.7
XS Rating Curve= 0 ,0
Exp/Cntr=0.3,0.1

Type RM Length L Ch R = 1 ,20249   ,305,305,305
BEGIN DESCRIPTION:
UNT050 IN NNOGR 5.0
END DESCRIPTION:
XS GIS Cut Line= 3
      2793136.77     10081620.43      2793088.16     10080849.62
      2792678.45     10080599.62
#Sta/Elev= 30
  4323.7 1719.92  4425.3  1717.1  4671.1 1710.94  4690.1 1710.72  4695.1 1711.38
  4701.1 1710.61  4721.2 1709.89  4854.7 1708.64  4931.6 1705.77  4961.7 1703.11
  4981.7 1700.97  4991.7 1698.85  4998.7 1698.12  5001.5 1697.62  5004.7 1698.12
  5009.3 1700.25  5021.8 1703.48  5034.9 1704.83  5051.8 1705.31  5099.6 1704.25
  5130.6 1704.88  5157.9 1704.56  5194.5 1704.05  5318.3 1707.62  5368.8 1706.44
  5426.8 1707.06  5457.7 1708.04  5521.7 1708.33  5537.1 1709.04    5576 1708.33
#Mann= 7 ,-1 , 0
  4323.7     .05       0  4425.3      .1       0  4961.7     .05       0
  4998.7    .035       0  5021.8     .05       0  5034.9      .1       0
  5157.9     .05       0
#XS Ineff= 2 , 0
                         5053.34         1705.28
Permanent Ineff=
       F       F
Bank Sta=4961.7,5021.8
XS Rating Curve= 0 ,0
Exp/Cntr=0.3,0.1

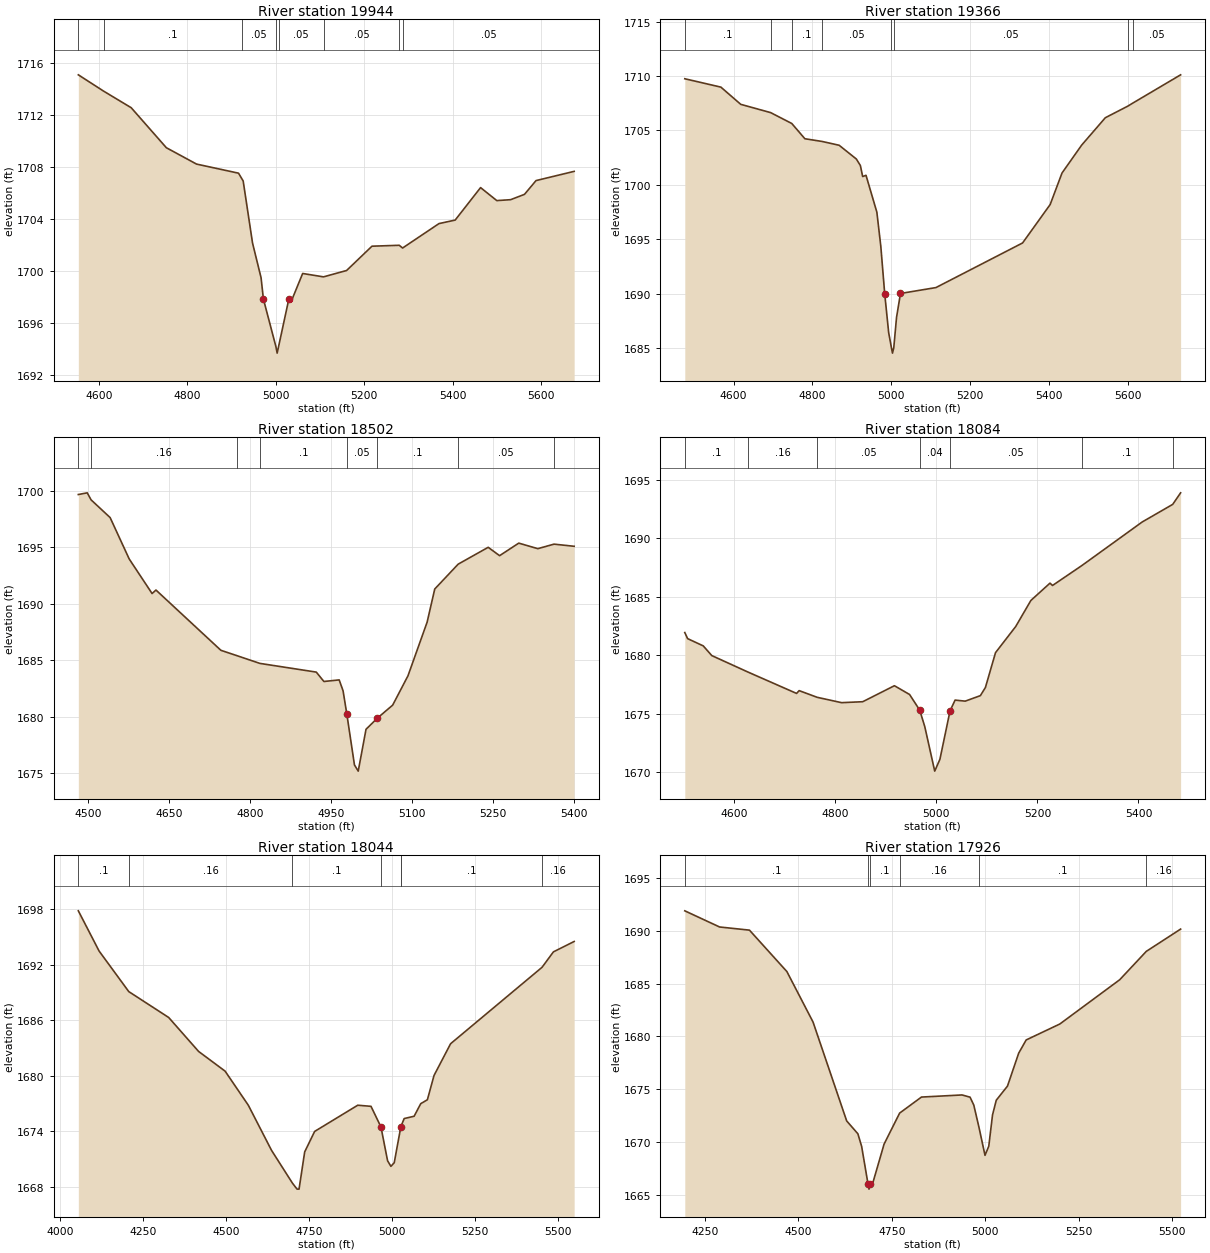
Type RM Length L Ch R = 1 ,19944   ,578,578,578
BEGIN DESCRIPTION:
UNT050 IN NNOGR 4.0
END DESCRIPTION:
XS GIS Cut Line= 2
      2793761.75     10080932.94      2792699.24     10080571.83
#Sta/Elev= 30
  4553.1 1715.07  4610.1 1713.82  4672.7 1712.54  4752.3 1709.46  4820.6  1708.2
  4915.7  1707.5  4923.9 1707.03  4926.2  1706.9  4947.4 1702.12  4966.7 1699.45
    4972 1697.81  5000.3 1694.15  5003.1 1693.65  5006.3 1694.15  5029.4 1697.79
  5034.7 1697.61  5060.8 1699.78    5108 1699.52  5160.3 1700.01  5217.7 1701.88
  5279.4 1701.95    5287 1701.74  5369.4 1703.62    5406 1703.89  5463.5 1706.39
  5500.2 1705.39  5531.5 1705.46  5562.9 1705.87    5589 1706.93  5675.3 1707.64
#Mann= 8 ,-1 , 0
  4553.1     .05       0  4610.1      .1       0  4923.9     .05       0
  5000.3    .035       0  5006.3     .05       0    5108     .05       0
  5279.4      .1       0    5287     .05       0
Bank Sta=4972,5029.4
XS Rating Curve= 0 ,0
Exp/Cntr=0.3,0.1

Type RM Length L Ch R = 1 ,19366   ,864,864,864
BEGIN DESCRIPTION:
UNT050 IN NNOGR 3.0
END DESCRIPTION:
XS GIS Cut Line= 3
      2793768.71     10080446.84      2793365.94     10080224.62
      2792567.38     10080231.56
#Sta/Elev= 30
  4476.2 1709.75  4567.8 1708.98  4618.2  1707.4  4694.1 1706.64  4747.8 1705.64
    4781 1704.24  4824.9 1703.99    4868 1703.64  4911.6 1702.38  4921.9 1701.78
  4927.7 1700.77  4936.2 1700.88  4963.7  1697.5  4973.7 1694.39  4983.7 1689.99
  4993.7 1686.44  5000.7 1685.05  5003.4 1684.55  5006.7 1685.05  5013.7 1687.84
  5023.7 1690.03  5113.7 1690.57  5333.7 1694.67  5403.7  1698.2  5433.7 1701.09
  5483.7 1703.66  5543.7 1706.17  5600.5 1707.23  5612.8  1707.5  5734.8 1710.11
#Mann= 8 ,-1 , 0
  4476.2      .1       0  4694.1     .16       0  4747.8      .1       0
  4824.9     .05       0  5000.7    .035       0  5006.7     .05       0
  5600.5      .1       0  5612.8     .05       0
Bank Sta=4983.7,5023.7
XS Rating Curve= 0 ,0
Exp/Cntr=0.3,0.1

Type RM Length L Ch R = 1 ,18502   ,418,418,418
BEGIN DESCRIPTION:
UNT050 IN NNOGR 2.0
END DESCRIPTION:
XS GIS Cut Line= 2
      2793504.81     10079960.71      2792845.14     10079321.87
#Sta/Elev= 30
  4481.9 1699.66  4498.4 1699.81  4505.5 1699.19  4540.8 1697.62  4576.1 1693.96
  4618.5  1690.9  4625.7 1691.21  4745.9 1685.88  4775.3 1685.41  4818.2 1684.72
  4922.6 1683.95  4936.7 1683.12    4965 1683.26  4972.2  1682.3  4979.2 1680.23
  4993.3 1675.74  5000.3 1675.19  5014.7 1678.89  5035.8 1679.88  5064.1 1681.03
  5092.4 1683.62  5127.9 1688.37    5142  1691.3  5185.4  1693.5    5241 1694.99
  5262.1 1694.25  5297.6 1695.36  5332.9 1694.87  5362.9 1695.27  5400.2 1695.08
#Mann= 8 ,-1 , 0
  4481.9     .05       0  4505.5     .16       0  4775.3      .1       0
  4818.2      .1       0  4979.2     .05       0  5035.8      .1       0
  5185.4     .05       0  5362.9      .1       0
Bank Sta=4979.2,5035.8
XS Rating Curve= 0 ,0
Exp/Cntr=0.3,0.1

Type RM Length L Ch R = 1 ,18084   ,40,40,40
BEGIN DESCRIPTION:
UNT050 IN NNOGR 1.0
END DESCRIPTION:
XS GIS Cut Line= 3
      2793596.32      10079649.2      2793511.69     10079297.64
      2792892.28     10079282.48
#Sta/Elev= 30
  4502.2 1681.94  4507.8 1681.42  4538.7  1680.8  4555.6 1679.97  4627.2 1678.56
  4723.4 1676.73  4728.5 1676.97    4764  1676.4  4812.4 1675.94  4854.3 1676.02
    4917 1677.39    4947 1676.64  4967.1  1675.3  4977.1 1673.89  4996.8 1670.08
  5007.1  1671.1  5027.1 1675.24  5037.1 1676.16  5057.1 1676.07  5087.1 1676.54
  5097.1 1677.24  5117.1 1680.22  5157.1 1682.46  5187.1 1684.69  5224.9 1686.17
  5229.9 1685.97  5287.8 1687.67  5407.2  1691.4  5467.7 1692.91  5483.4  1693.9
#Mann= 7 ,-1 , 0
  4502.2      .1       0  4627.2     .16       0    4764     .05       0
  4967.1     .04       0  5027.1     .05       0  5287.8      .1       0
  5467.7     .16       0
Bank Sta=4967.1,5027.1
XS Rating Curve= 0 ,0
Exp/Cntr=0.3,0.1

Type RM Length L Ch R = 1 ,18044   ,118,118,118
BEGIN DESCRIPTION:
KUHLMAN CREEK 29.0
END DESCRIPTION:
XS GIS Cut Line= 2
      2794321.11     10079252.06      2792825.92      10079256.4
#Sta/Elev= 30
  4053.9  1697.8  4116.5 1693.46    4206 1689.08  4326.5 1686.28  4416.5 1682.62
  4496.5 1680.49  4566.5 1676.81  4636.5 1671.94  4699.5  1668.4  4713.5 1667.75
  4719.5 1667.75  4736.5 1671.77  4766.5 1673.98  4896.5 1676.81  4936.5 1676.69
  4966.5 1674.46  4986.5 1670.81  4996.5 1670.21  5006.5  1670.6  5026.5 1674.49
  5027.7  1674.6  5036.5 1675.37  5066.5 1675.62  5086.5 1676.98  5106.5  1677.4
  5126.5 1680.02  5176.5 1683.45  5452.2  1691.7  5486.6 1693.37  5549.1 1694.49
#Mann= 7 ,-1 , 0
  4053.9      .1       0    4206     .16       0  4699.5      .1       0
  4966.5     .04       0  5026.5     .05       0  5027.7      .1       0
  5452.2     .16       0
Bank Sta=4966.5,5026.5
XS Rating Curve= 0 ,0
Exp/Cntr=0.3,0.1

Type RM Length L Ch R = 1 ,17926   ,544,544,544
BEGIN DESCRIPTION:
Mapping XS 6fb45d85
END DESCRIPTION:
XS GIS Cut Line= 3
      2794171.46     10079139.22      2793531.22     10079141.39
      2792845.48     10079124.03
#Sta/Elev= 30
  4196.3 1691.89  4289.3 1690.36  4369.3 1690.06  4469.3 1686.14  4539.3 1681.36
  4629.3 1671.99  4659.3 1670.77  4669.3 1669.58  4686.3 1666.03    4689 1665.53
  4692.3 1666.03  4699.3 1666.13  4729.3 1669.79  4770.9 1672.73  4829.3 1674.25
  4937.9 1674.45  4959.3 1674.24  4969.3 1673.49  4983.3 1671.36  4999.3 1668.73
  5009.4  1669.6  5019.4 1672.56  5029.4 1673.95  5059.4 1675.29  5089.4 1678.41
  5109.4 1679.66  5199.4 1681.17  5359.5 1685.36  5430.7 1688.05  5522.5 1690.16
#Mann= 6 ,-1 , 0
  4196.3      .1       0  4686.3     .07       0  4692.3      .1       0
  4770.9     .16       0  4983.3      .1       0  5430.7     .16       0
Bank Sta=4686.3,4692.3
XS Rating Curve= 0 ,0
Exp/Cntr=0.3,0.1

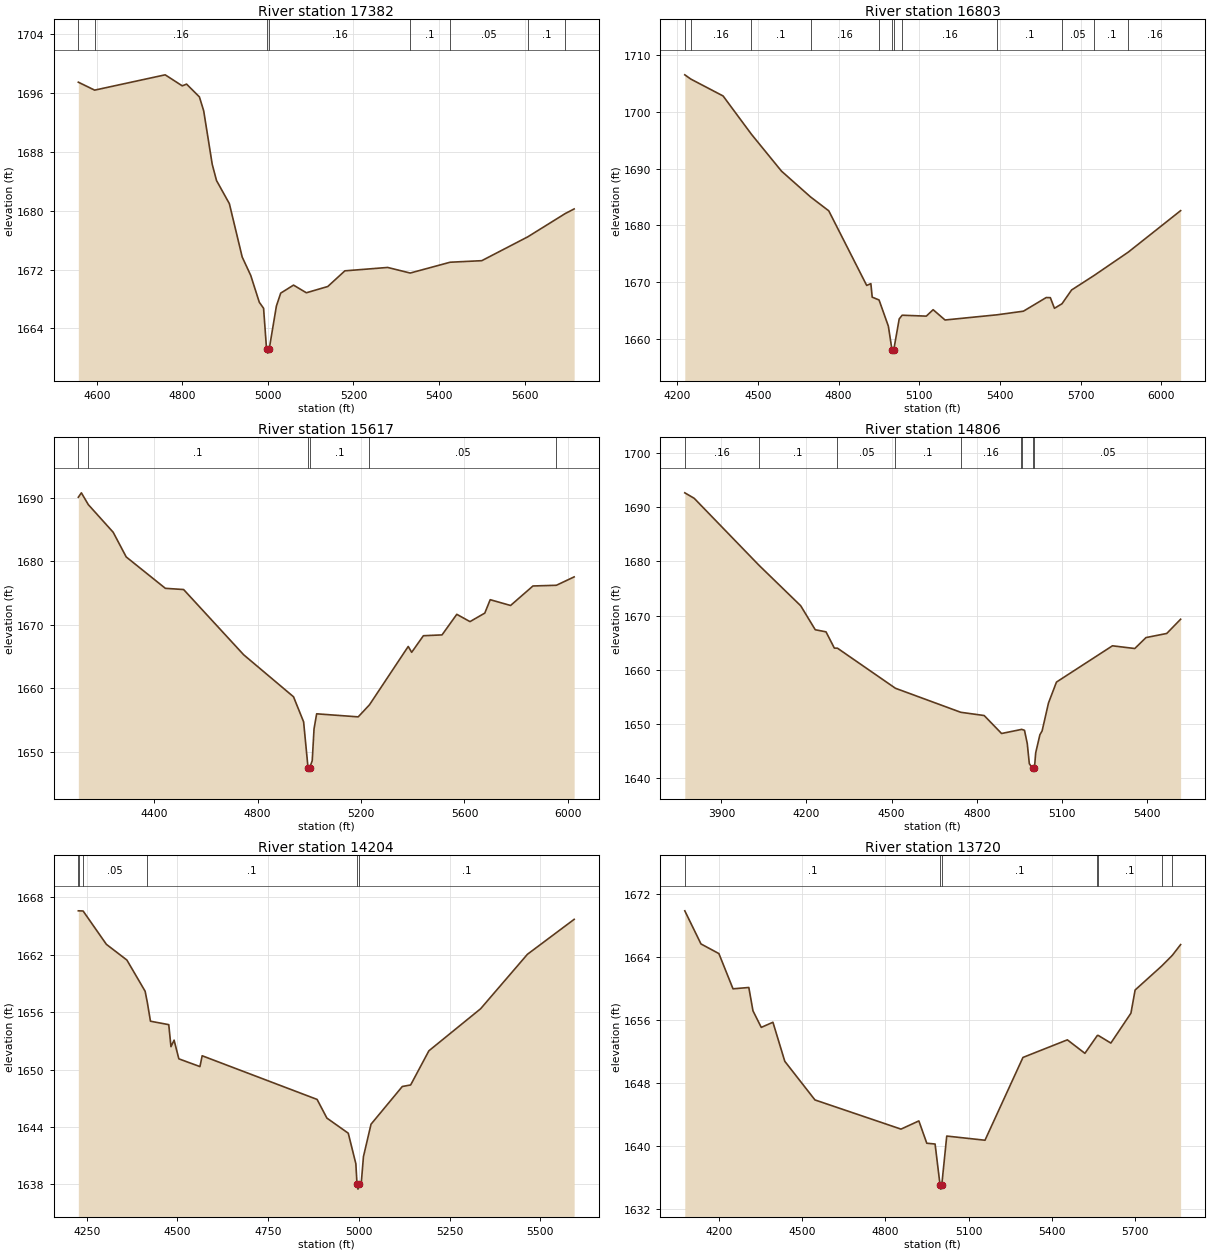
Type RM Length L Ch R = 1 ,17382   ,579,579,579
BEGIN DESCRIPTION:
KUHLMAN CREEK 28.0
END DESCRIPTION:
XS GIS Cut Line= 2
      2794171.48      10078877.4      2793012.58      10078877.4
#Sta/Elev= 30
  4556.9 1697.45    4595 1696.37  4759.9 1698.45  4799.9 1696.95  4809.9 1697.19
  4839.9 1695.45  4849.9 1693.56  4869.9 1686.28  4879.9 1684.09  4909.9 1680.95
  4939.9  1673.7  4959.9 1671.19  4979.9 1667.55  4989.9 1666.73  4996.9 1661.14
  4999.7 1660.64  5002.9 1661.14  5019.9 1667.05  5029.9 1668.79  5059.9 1669.88
  5089.9 1668.84  5139.9 1669.69  5179.9 1671.82  5279.9 1672.28  5332.6 1671.52
    5426 1672.99  5499.9  1673.2  5607.4 1676.44  5694.9  1679.6  5715.8 1680.23
#Mann= 8 ,-1 , 0
  4556.9      .1       0    4595     .16       0  4996.9     .07       0
  5002.9     .16       0  5332.6      .1       0    5426     .05       0
  5607.4      .1       0  5694.9     .16       0
Bank Sta=4996.9,5002.9
XS Rating Curve= 0 ,0
Exp/Cntr=0.3,0.1

Type RM Length L Ch R = 1 ,16803   ,1186,1186,1186
BEGIN DESCRIPTION:
KUHLMAN CREEK 27.0
END DESCRIPTION:
XS GIS Cut Line= 3
      2794629.88     10078245.45      2793713.16     10078356.56
      2792936.07     10078849.18
#Sta/Elev= 30
    4228  1706.5  4250.8 1705.74  4370.4 1702.78  4475.8 1696.04  4587.4 1689.56
  4695.4 1685.02  4763.3 1682.57  4904.3 1669.44  4919.8 1669.76  4924.8 1667.38
  4950.3 1666.88  4984.9 1662.27  4998.6 1658.03  5001.4 1657.53  5004.6 1658.03
  5025.2 1663.55  5036.2  1664.2  5125.9 1664.04  5151.3 1665.17  5195.6 1663.36
  5390.2 1664.28  5487.1 1664.91  5571.8 1667.31  5587.1 1667.29  5602.4 1665.42
  5630.5 1666.22  5666.1 1668.64  5750.6 1671.22  5876.8  1675.3  6071.5  1682.6
#Mann= 12 ,-1 , 0
    4228      .1       0  4250.8     .16       0  4475.8      .1       0
  4695.4     .16       0  4950.3      .1       0  4998.6     .07       0
  5004.6      .1       0  5036.2     .16       0  5390.2      .1       0
  5630.5     .05       0  5750.6      .1       0  5876.8     .16       0
Bank Sta=4998.6,5004.6
XS Rating Curve= 0 ,0
Exp/Cntr=0.3,0.1

Type RM Length L Ch R = 1 ,15617   ,811,811,811
BEGIN DESCRIPTION:
KUHLMAN CREEK 25.0
END DESCRIPTION:
XS GIS Cut Line= 3
       2794352.1     10077960.74      2793282.61      10077814.9
      2792583.44      10078278.7
#Sta/Elev= 30
  4106.1 1690.06  4117.9 1690.75  4144.8 1688.89    4241 1684.54  4291.4 1680.66
  4442.8 1675.72  4513.5 1675.53  4745.6 1665.27  4938.7 1658.65  4977.7 1654.71
  4994.9 1647.45  4997.7 1646.95  5000.9 1647.45  5011.1  1648.6  5018.1 1653.61
  5028.2 1655.97    5189 1655.49  5232.6 1657.39  5382.5 1666.57  5395.9 1665.65
  5441.1 1668.26  5513.3 1668.39  5570.4 1671.63  5621.5 1670.48  5678.7 1671.82
  5699.7 1673.93  5778.5 1673.02  5865.1 1676.09  5955.8  1676.2  6024.5 1677.52
#Mann= 6 ,-1 , 0
  4106.1     .16       0  4144.8      .1       0  4994.9     .07       0
  5000.9      .1       0  5232.6     .05       0  5955.8      .1       0
Bank Sta=4994.9,5000.9
XS Rating Curve= 0 ,0
Exp/Cntr=0.3,0.1

Type RM Length L Ch R = 1 ,14806   ,602,602,602
BEGIN DESCRIPTION:
KUHLMAN CREEK 24.0
END DESCRIPTION:
XS GIS Cut Line= 3
      2794004.84     10076814.89      2792990.94      10077314.9
      2792720.52     10077869.61
#Sta/Elev= 30
  3771.1 1692.67  3804.2 1691.66  4032.4  1679.3  4179.6 1671.81  4230.9 1667.38
  4268.8 1666.99  4298.2 1663.99  4309.2 1663.97  4513.4 1656.57  4743.7 1652.13
  4826.3 1651.53  4887.6 1648.21  4955.5 1648.94  4958.1 1648.98  4968.4  1648.8
  4978.2 1646.35  4985.4 1642.64  4997.4 1641.76  5000.2 1641.26  5003.4 1641.76
  5007.9 1644.64  5022.7 1647.98  5030.5 1648.69    5053 1653.85  5081.1 1657.71
  5278.4 1664.41  5357.1 1663.91  5396.6 1665.93  5469.8 1666.69  5518.7 1669.32
#Mann= 9 ,-1 , 0
  3771.1     .16       0  4032.4      .1       0  4309.2     .05       0
  4513.4      .1       0  4743.7     .16       0  4955.5      .1       0
  4958.1     .05       0  4997.4    .035       0  5003.4     .05       0
Bank Sta=4997.4,5003.4
XS Rating Curve= 0 ,0
Exp/Cntr=0.3,0.1

Type RM Length L Ch R = 1 ,14204   ,484,484,484
BEGIN DESCRIPTION:
KUHLMAN CREEK 23.0
END DESCRIPTION:
XS GIS Cut Line= 2
      2793303.41     10076481.58      2792193.87     10077279.06
#Sta/Elev= 30
  4227.1 1666.58  4228.6 1666.58  4240.3 1666.56  4304.4 1663.08  4360.9 1661.44
  4411.2 1658.18  4417.1 1657.04  4425.9 1655.05  4476.3 1654.69  4482.4 1652.39
    4491 1653.07  4504.1 1651.12  4562.2 1650.31  4568.4 1651.44  4885.1 1646.88
  4912.1 1644.93    4971 1643.35  4991.9 1640.16  4995.1 1638.01  4997.8 1637.51
  5001.1 1638.01  5006.6 1638.05  5012.8  1640.9  5033.7 1644.29  5119.9 1648.23
  5142.9 1648.39  5193.2 1651.96  5335.7 1656.35  5464.7 1662.04  5593.5 1665.69
#Mann= 6 ,-1 , 0
  4227.1      .1       0  4228.6     .16       0  4240.3     .05       0
  4417.1      .1       0  4995.1     .07       0  5001.1      .1       0
Bank Sta=4995.1,5001.1
XS Rating Curve= 0 ,0
Exp/Cntr=0.3,0.1

Type RM Length L Ch R = 1 ,13720   ,1007,1007,1007
BEGIN DESCRIPTION:
KUHLMAN CREEK 22.0
END DESCRIPTION:
XS GIS Cut Line= 3
      2793136.75     10076051.02      2792233.99     10076662.12
      2791852.76     10077244.37
#Sta/Elev= 30
  4077.6 1669.83  4135.9 1665.63  4200.4 1664.41  4251.3 1659.94  4308.2 1660.11
  4323.2 1657.15  4353.1 1655.05  4395.1  1655.7  4437.8 1650.75  4546.5 1645.85
  4856.4 1642.15  4920.8 1643.19  4949.3 1640.36  4979.2 1640.26  4997.2 1635.04
    5000 1634.54  5003.2 1635.04  5021.2 1641.27    5159 1640.74  5295.8 1651.24
  5455.7 1653.47  5518.9 1651.76  5563.8 1654.03    5567 1654.03  5612.4 1653.06
  5684.7 1656.85  5699.8 1659.79  5795.5 1662.83  5833.6 1664.18  5863.7 1665.55
#Mann= 7 ,-1 , 0
  4077.6      .1       0  4997.2     .07       0  5003.2      .1       0
  5563.8     .05       0    5567      .1       0  5795.5     .05       0
  5833.6      .1       0
Bank Sta=4997.2,5003.2
XS Rating Curve= 0 ,0
Exp/Cntr=0.3,0.1