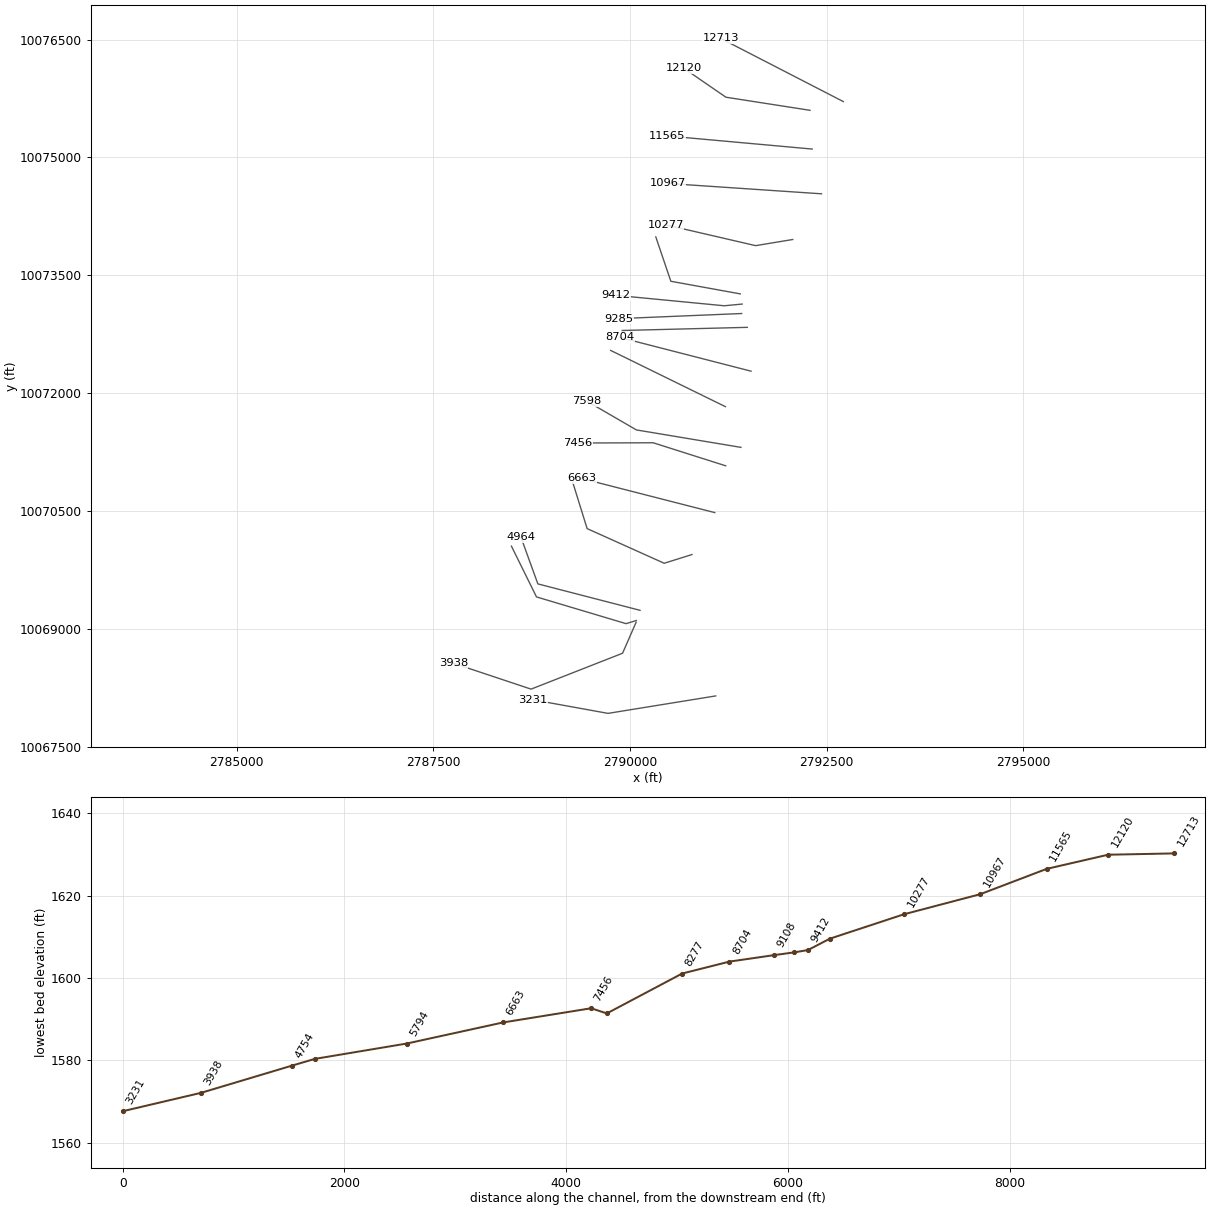
HEC-RAS study KUHLMAN CREEK.prj: KUHLMAN CREEK Base Level Engineering

--- KUHLMAN CREEK.g01 (geometry) --- (continued)

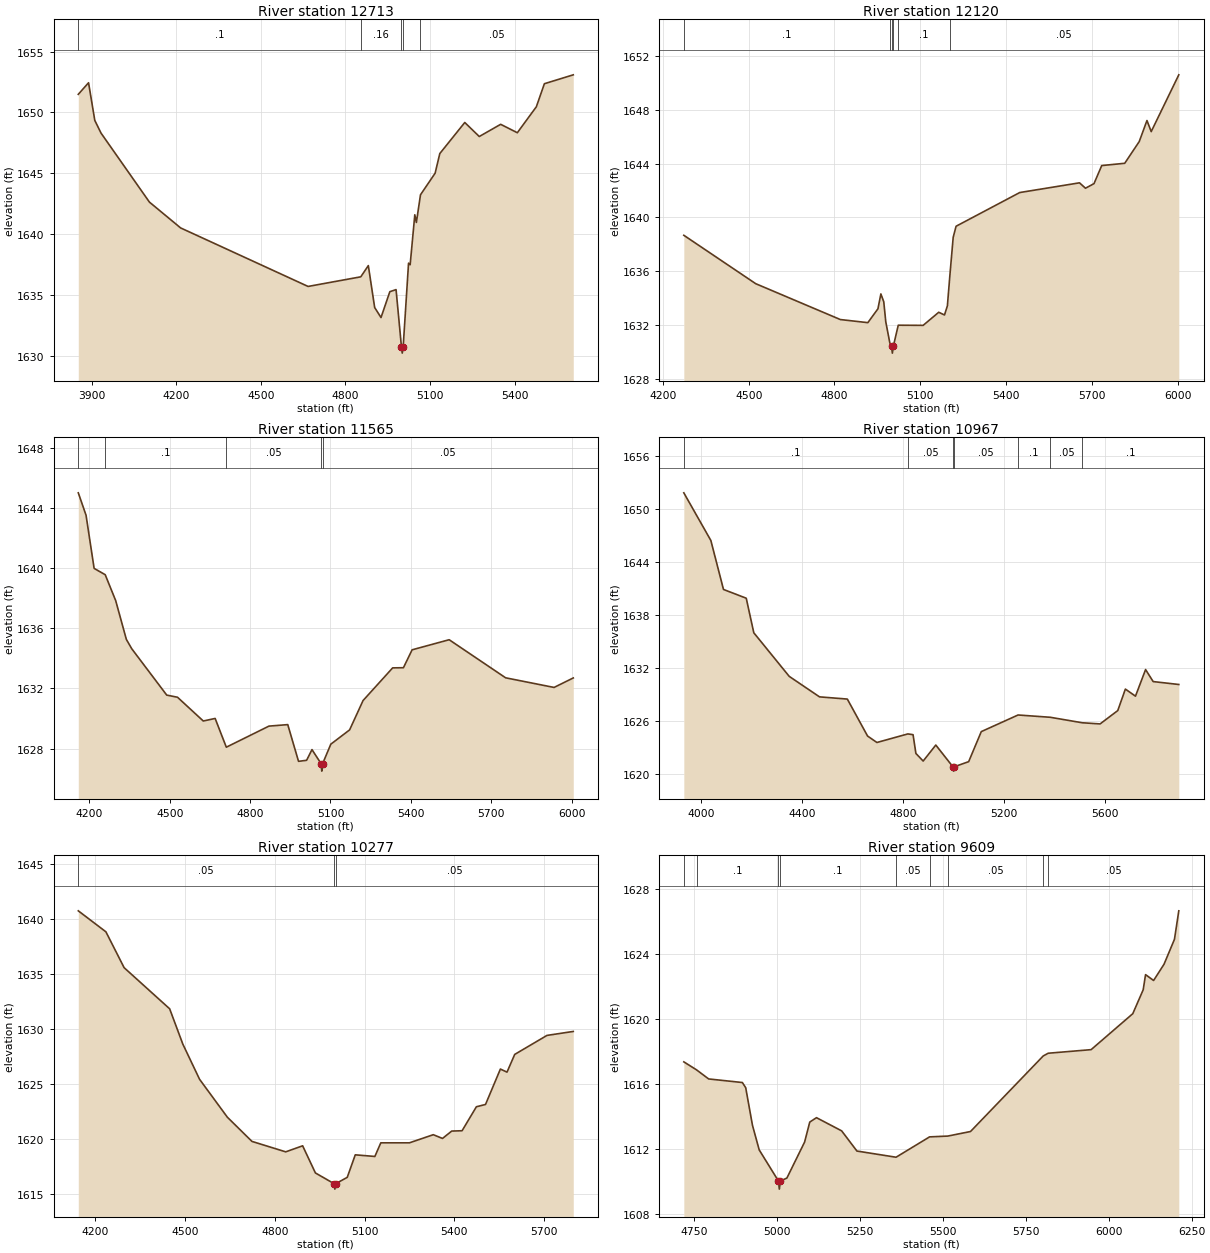
Type RM Length L Ch R = 1 ,12713   ,593,593,593
BEGIN DESCRIPTION:
KUHLMAN CREEK 20.0
END DESCRIPTION:
XS GIS Cut Line= 2
      2792713.21     10075710.71      2791152.07     10076515.56
#Sta/Elev= 30
  3851.9 1651.49  3888.3 1652.44  3910.5 1649.35  3932.6 1648.31  4104.3 1642.65
  4215.1 1640.53  4667.3 1635.73  4854.3 1636.52  4881.1 1637.44  4903.6    1634
  4926.1 1633.18  4957.4  1635.3  4979.5 1635.47  4998.7 1630.76  5001.4 1630.26
  5004.7 1630.76  5023.8 1637.64  5029.5 1637.51    5046 1641.61  5051.6 1640.98
  5066.2 1643.25  5118.1 1645.02  5134.7 1646.63  5223.3 1649.18  5274.8 1648.03
  5350.7 1649.03  5409.8 1648.34  5477.3 1650.47  5505.8 1652.36  5608.3 1653.09
#Mann= 5 ,-1 , 0
  3851.9      .1       0  4854.3     .16       0  4998.7     .07       0
  5004.7     .16       0  5066.2     .05       0
Bank Sta=4998.7,5004.7
XS Rating Curve= 0 ,0
Exp/Cntr=0.3,0.1

Type RM Length L Ch R = 1 ,12120   ,555,555,555
BEGIN DESCRIPTION:
KUHLMAN CREEK 19.0
END DESCRIPTION:
XS GIS Cut Line= 3
      2792289.51     10075599.62      2791220.11     10075766.29
      2790685.35     10076134.36
#Sta/Elev= 30
    4273 1638.68  4524.5 1635.09  4820.6 1632.43  4916.7  1632.2  4952.1 1633.23
  4962.3 1634.33  4972.4 1633.75  4979.5 1632.26  4993.6  1630.7  4999.8 1630.44
  5002.5 1629.94  5005.8 1630.44  5023.1 1632.01  5110.2    1632  5164.7 1632.97
  5184.9 1632.77    5195 1633.45  5203.4 1635.63  5215.3 1638.53  5225.4 1639.35
  5448.1 1641.85  5657.1 1642.57  5678.1 1642.17  5707.8 1642.51  5734.9 1643.85
  5815.4 1644.02  5866.1 1645.63  5893.1 1647.19    5908 1646.37  6004.5 1650.58
#Mann= 6 ,-1 , 0
    4273      .1       0  4993.6     .16       0  4999.8     .07       0
  5005.8     .16       0  5023.1      .1       0  5203.4     .05       0
Bank Sta=4999.8,5005.8
XS Rating Curve= 0 ,0
Exp/Cntr=0.3,0.1

Type RM Length L Ch R = 1 ,11565   ,598,598,598
BEGIN DESCRIPTION:
KUHLMAN CREEK 17.0
END DESCRIPTION:
XS GIS Cut Line= 2
      2792317.28     10075106.57      2790477.01     10075273.23
#Sta/Elev= 30
  4158.6 1644.99  4187.6  1643.5  4217.7 1639.97  4259.1 1639.55  4298.2 1637.83
  4338.1 1635.25  4358.2 1634.63  4488.8 1631.55  4528.9 1631.41  4625.2 1629.83
  4669.5    1630  4711.2 1628.09  4870.3 1629.49  4940.6 1629.59  4980.8 1627.15
  5010.9 1627.22    5031 1627.93  5064.8    1627  5067.6  1626.5  5070.8    1627
  5101.3 1628.29  5171.5 1629.24  5221.7 1631.19  5332.2 1633.36  5372.4 1633.37
  5404.8 1634.56  5543.1 1635.23  5753.9  1632.7  5934.7 1632.06  6006.4 1632.69
#Mann= 5 ,-1 , 0
  4158.6     .05       0  4259.1      .1       0  4711.2     .05       0
  5064.8    .035       0  5070.8     .05       0
Bank Sta=5064.8,5070.8
XS Rating Curve= 0 ,0
Exp/Cntr=0.3,0.1

Type RM Length L Ch R = 1 ,10967   ,690,690,690
BEGIN DESCRIPTION:
KUHLMAN CREEK 16.0
END DESCRIPTION:
XS GIS Cut Line= 2
      2792435.38     10074537.12      2790477.02     10074669.07
#Sta/Elev= 30
  3931.5 1651.84  4038.7 1646.45  4088.8 1640.91    4179 1639.92    4209 1636.01
  4349.4 1631.08  4469.6 1628.76  4579.9 1628.51  4660.1 1624.33  4697.2  1623.6
  4820.1 1624.57  4840.5 1624.48  4851.8 1622.36  4880.6  1621.5  4930.7 1623.31
  4998.3 1620.86  5001.1 1620.36  5004.3 1620.86    5061 1621.43  5111.1 1624.83
  5256.9 1626.71  5384.9 1626.45  5511.6 1625.83  5582.2  1625.7  5652.3 1627.21
  5682.4 1629.64  5722.5 1628.84  5762.6 1631.85  5792.6 1630.49  5894.3 1630.16
#Mann= 7 ,-1 , 0
  3931.5      .1       0  4820.1     .05       0  4998.3    .035       0
  5004.3     .05       0  5256.9      .1       0  5384.9     .05       0
  5511.6      .1       0
Bank Sta=4998.3,5004.3
XS Rating Curve= 0 ,0
Exp/Cntr=0.3,0.1

Type RM Length L Ch R = 1 ,10277   ,668,668,668
BEGIN DESCRIPTION:
KUHLMAN CREEK 14.0
END DESCRIPTION:
XS GIS Cut Line= 3
      2792069.52     10073955.56      2791598.14     10073877.43
      2790452.92     10074142.92
#Sta/Elev= 30
  4143.9 1640.78  4236.2 1638.87    4297 1635.61  4449.1 1631.87  4493.1 1628.66
    4549 1625.46  4641.9 1622.01    4724 1619.81  4836.9 1618.86  4893.3 1619.41
    4936 1616.94  4998.2 1615.97  5000.9 1615.47  5004.2 1615.97  5042.3 1616.54
  5069.1 1618.59  5134.6 1618.44  5154.4 1619.68    5250 1619.68  5329.7 1620.42
  5360.5 1620.08  5391.3 1620.75  5425.9 1620.78  5473.7 1622.96  5504.2 1623.17
  5553.9 1626.39    5576 1626.11  5601.7 1627.72  5709.5 1629.45  5797.3 1629.81
#Mann= 3 ,-1 , 0
  4143.9     .05       0  4998.2    .035       0  5004.2     .05       0
Bank Sta=4998.2,5004.2
XS Rating Curve= 0 ,0
Exp/Cntr=0.3,0.1

Type RM Length L Ch R = 1 ,9609    ,197,197,197
BEGIN DESCRIPTION:
KUHLMAN CREEK 12.0
END DESCRIPTION:
XS GIS Cut Line= 3
       2791402.2     10073263.63      2790519.73     10073424.08
      2790328.44     10073988.72
#Sta/Elev= 30
    4718 1617.37  4756.3 1616.88  4792.9 1616.32  4894.6  1616.1  4904.7 1615.78
  4925.1 1613.47  4945.4 1611.96  5003.4 1610.05  5006.1 1609.55  5009.4 1610.05
  5028.9 1610.23  5082.3 1612.44  5097.9 1613.67  5118.2 1613.94  5194.1 1613.13
  5240.2 1611.89  5358.2 1611.51  5459.3 1612.76  5514.4 1612.81  5582.8 1613.09
    5802 1617.73  5817.1  1617.9  5946.6 1618.12  6072.3 1620.33  6103.7  1621.8
  6110.8 1622.73  6135.1 1622.37  6166.6 1623.37    6198  1624.9  6211.1 1626.65
#Mann= 9 ,-1 , 0
    4718     .05       0  4756.3      .1       0  5003.4     .07       0
  5009.4      .1       0  5358.2     .05       0  5459.3      .1       0
  5514.4     .05       0    5802      .1       0  5817.1     .05       0
Bank Sta=5003.4,5009.4
XS Rating Curve= 0 ,0
Exp/Cntr=0.3,0.1

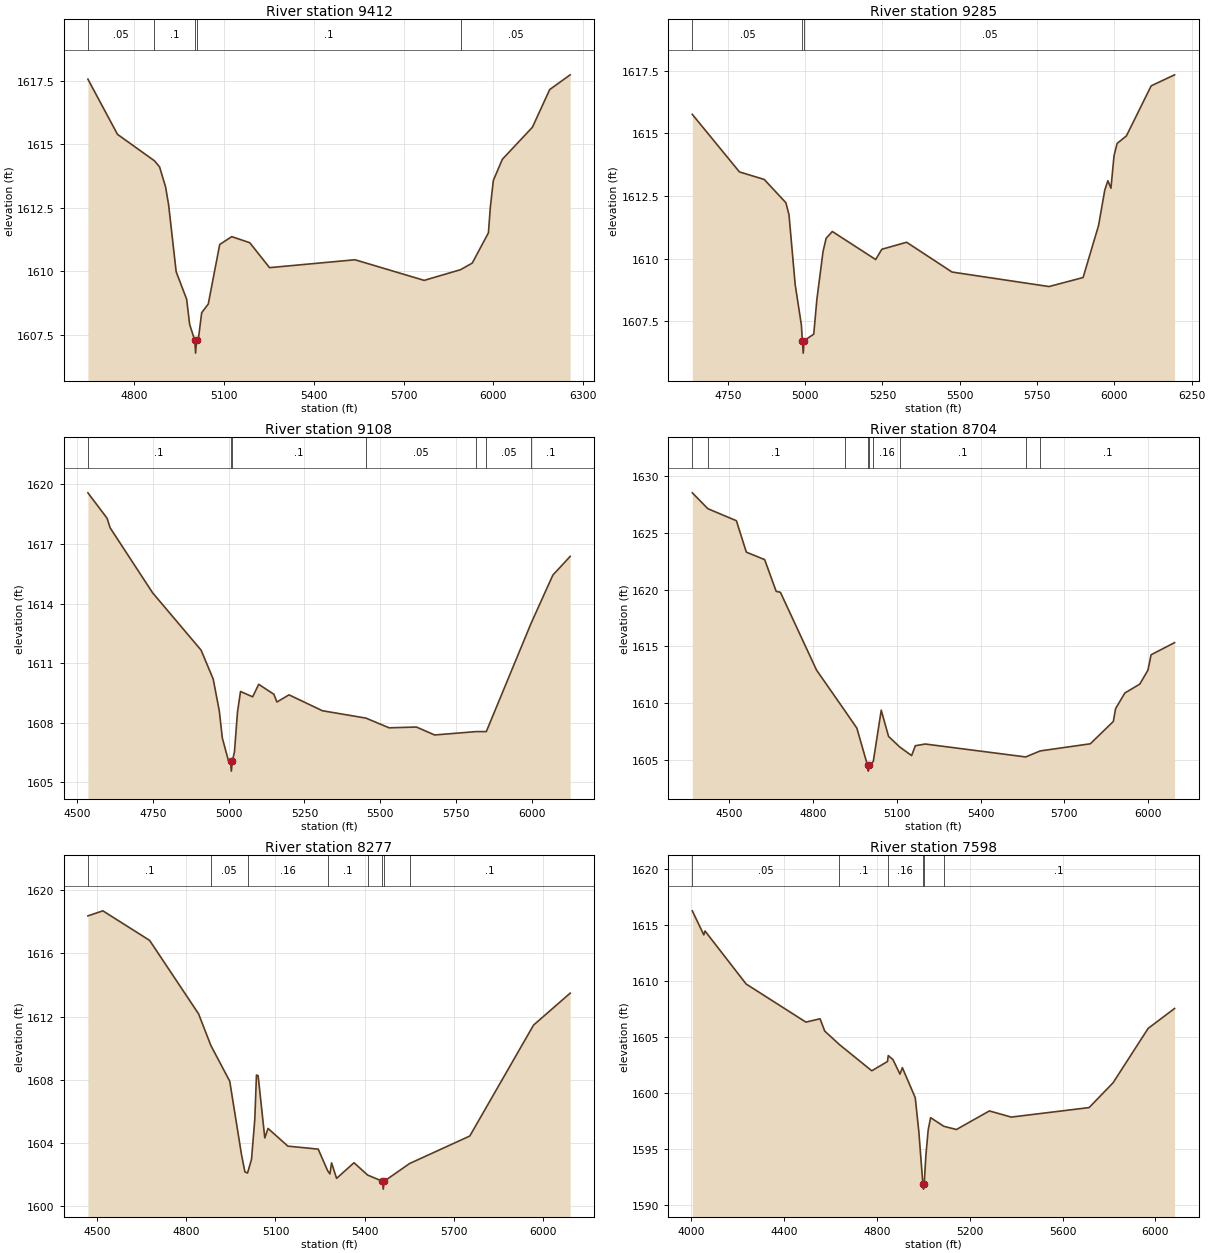
Type RM Length L Ch R = 1 ,9412    ,127,127,127
BEGIN DESCRIPTION:
Mapping XS 1893a92b
END DESCRIPTION:
XS GIS Cut Line= 3
      2791426.91     10073134.03      2791198.58     10073112.43
      2789822.91     10073245.06
#Sta/Elev= 30
  4645.4 1617.56  4744.3 1615.39  4867.9 1614.35  4884.9 1614.11    4905 1613.32
  4915.1 1612.62  4940.3 1609.99  4975.3 1608.91  4985.4 1607.92  5002.5 1607.29
  5005.2 1606.79  5008.5 1607.29  5015.5 1607.44  5025.6 1608.38  5047.6 1608.72
  5085.8 1611.06    5126 1611.37  5186.3 1611.13  5252.3 1610.15  5537.9 1610.46
    5769 1609.65  5890.5 1610.07  5929.7 1610.33  5983.7 1611.52    5990 1612.52
  6000.1 1613.58  6030.2 1614.41  6130.7 1615.67  6188.4 1617.15  6256.8 1617.73
#Mann= 5 ,-1 , 0
  4645.4     .05       0  4867.9      .1       0  5002.5     .07       0
  5008.5      .1       0  5890.5     .05       0
Bank Sta=5002.5,5008.5
XS Rating Curve= 0 ,0
Exp/Cntr=0.3,0.1

Type RM Length L Ch R = 1 ,9285    ,177,177,177
BEGIN DESCRIPTION:
Mapping XS fc5bc3fd
END DESCRIPTION:
XS GIS Cut Line= 2
      2791420.79     10073013.69      2789862.93     10072948.91
#Sta/Elev= 30
  4635.4 1615.76  4787.9 1613.46  4867.9 1613.16    4938 1612.23    4948 1611.75
    4968 1608.96    4988 1607.35  4991.2 1606.72    4994 1606.22  4997.2 1606.72
  5028.1 1606.98  5038.1 1608.36  5058.1 1610.28  5068.1 1610.81  5088.1 1611.08
  5228.2 1609.96  5248.2 1610.37  5328.3 1610.65  5475.1 1609.46  5788.7 1608.88
  5898.8 1609.24  5948.9 1611.32  5968.9 1612.73  5978.9 1613.11  5988.9 1612.81
  5998.9 1614.11  6008.9  1614.6  6038.9  1614.9    6119  1616.9  6194.6 1617.34
#Mann= 3 ,-1 , 0
  4635.4     .05       0  4991.2     .04       0  4997.2     .05       0
Bank Sta=4991.2,4997.2
XS Rating Curve= 0 ,0
Exp/Cntr=0.3,0.1

Type RM Length L Ch R = 1 ,9108    ,404,404,404
BEGIN DESCRIPTION:
Mapping XS f4570e50
END DESCRIPTION:
XS GIS Cut Line= 2
       2791491.7     10072837.81      2789901.51     10072797.74
#Sta/Elev= 30
  4535.6 1619.58  4598.9  1618.3  4608.9 1617.82  4748.9 1614.55    4909 1611.66
    4949  1610.2    4969  1608.6    4979 1607.24    4999  1606.1    5006 1606.07
  5008.7 1605.57    5012 1606.07    5019 1606.54    5029 1608.54    5039 1609.58
    5079 1609.31    5099 1609.94    5149 1609.44    5159 1609.05    5199 1609.41
  5309.1 1608.61  5452.5 1608.24  5529.2 1607.75  5619.2 1607.79  5679.2 1607.39
  5816.3 1607.56  5849.7 1607.56  5997.6 1613.02  6069.3 1615.44  6126.3 1616.38
#Mann= 7 ,-1 , 0
  4535.6      .1       0    5006     .07       0    5012      .1       0
  5452.5     .05       0  5816.3      .1       0  5849.7     .05       0
  5997.6      .1       0
Bank Sta=5006,5012
XS Rating Curve= 0 ,0
Exp/Cntr=0.3,0.1

Type RM Length L Ch R = 1 ,8704    ,427,427,427
BEGIN DESCRIPTION:
KUHLMAN CREEK 11.0
END DESCRIPTION:
XS GIS Cut Line= 2
      2791539.59     10072280.16      2789865.98     10072710.72
#Sta/Elev= 30
  4366.9 1628.53  4422.7 1627.13  4524.9 1626.07  4560.5  1623.3  4626.2 1622.64
  4667.5 1619.84  4682.6 1619.76  4812.1  1612.9  4912.3 1609.36  4956.6 1607.78
  4994.9 1604.49  4997.7 1603.99  5000.9 1604.49  5015.4 1604.84  5043.9 1609.36
  5070.2 1607.05  5110.6 1606.11  5152.8 1605.36  5166.1 1606.23  5201.6 1606.38
  5561.6 1605.24  5613.3 1605.77    5793  1606.4  5875.6 1608.37  5883.6  1609.5
  5916.9 1610.88  5970.2 1611.66  5999.5 1612.89  6010.9 1614.25    6095 1615.32
#Mann= 9 ,-1 , 0
  4366.9     .05       0  4422.7      .1       0  4912.3     .05       0
  4994.9    .035       0  5000.9     .05       0  5015.4     .16       0
  5110.6      .1       0  5561.6     .05       0  5613.3      .1       0
Bank Sta=4994.9,5000.9
XS Rating Curve= 0 ,0
Exp/Cntr=0.3,0.1

Type RM Length L Ch R = 1 ,8277    ,679,679,679
BEGIN DESCRIPTION:
KUHLMAN CREEK 10.0
END DESCRIPTION:
XS GIS Cut Line= 2
       2791213.2     10071828.77      2789754.87     10072544.04
#Sta/Elev= 30
  4468.3 1618.38  4518.7  1618.7  4676.1 1616.83  4841.1 1612.18  4882.4 1610.18
    4946 1607.92  4985.4  1603.3  4997.1 1602.18  5005.9 1602.11  5019.3 1602.97
  5030.4  1605.5    5036 1608.31  5041.6 1608.27  5064.1 1604.33    5075 1604.93
  5141.9 1603.81    5244 1603.62  5275.9 1602.25  5283.4 1602.05    5289 1602.75
  5305.9 1601.77  5364.6 1602.76  5410.5 1601.98  5460.3 1601.59  5463.1 1601.09
  5466.3 1601.59  5551.8 1602.71  5754.5 1604.45  5969.3 1611.47  6092.6 1613.49
#Mann= 8 ,-1 , 0
  4468.3      .1       0  4882.4     .05       0  5005.9     .16       0
  5275.9      .1       0  5410.5     .16       0  5460.3    .035       0
  5466.3     .16       0  5551.8      .1       0
Bank Sta=5460.3,5466.3
XS Rating Curve= 0 ,0
Exp/Cntr=0.3,0.1

Type RM Length L Ch R = 1 ,7598    ,142,142,142
BEGIN DESCRIPTION:
KUHLMAN CREEK 9.0
END DESCRIPTION:
XS GIS Cut Line= 3
       2791411.5      10071310.4      2790081.57     10071532.57
      2789449.94     10071899.23
#Sta/Elev= 30
  4004.1 1616.29  4053.7 1614.14  4058.8 1614.49    4236 1609.75  4493.8 1606.34
  4554.7 1606.64  4574.9 1605.54  4638.4 1604.33  4777.7 1601.99  4845.5 1602.82
  4848.7 1603.35    4869 1602.99  4899.3 1601.69  4909.5 1602.27  4965.1 1599.58
  4980.5 1596.55  4997.8 1591.91  5000.5 1591.41  5003.8 1591.91  5010.9 1594.43
  5020.8  1596.7  5031.2  1597.8  5087.9 1597.03  5142.4 1596.74  5284.6  1598.4
    5379 1597.85  5714.5  1598.7  5817.8 1600.92  5968.9 1605.78  6082.8 1607.56
#Mann= 6 ,-1 , 0
  4004.1     .05       0  4638.4      .1       0  4845.5     .16       0
  4997.8     .07       0  5003.8     .16       0  5087.9      .1       0
Bank Sta=4997.8,5003.8
XS Rating Curve= 0 ,0
Exp/Cntr=0.3,0.1

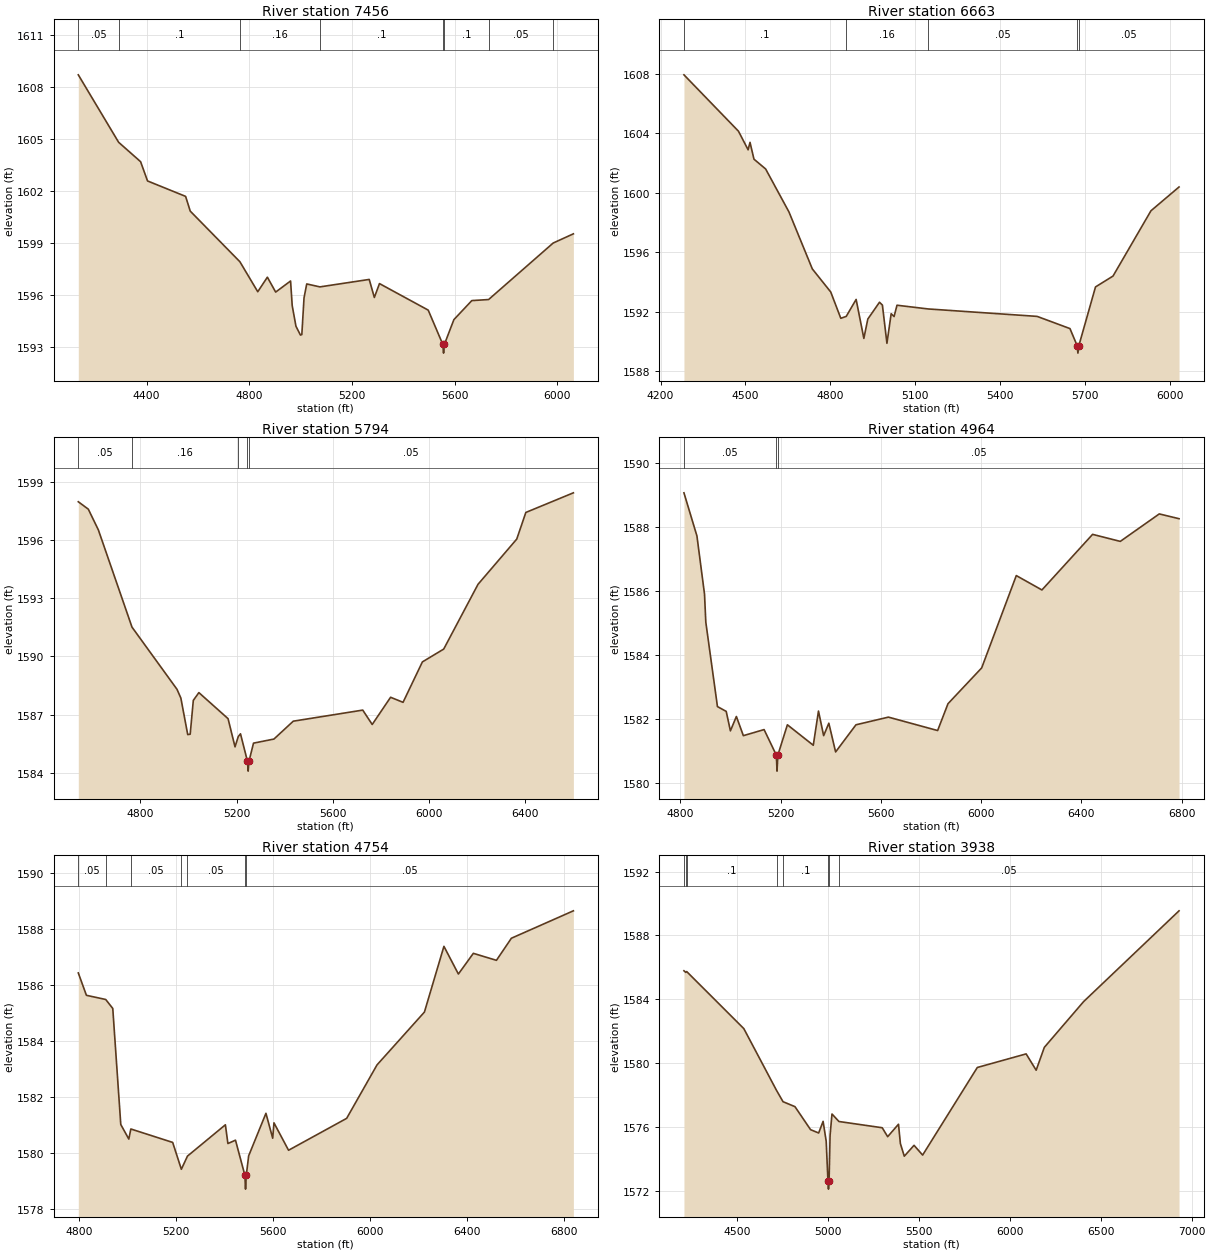
Type RM Length L Ch R = 1 ,7456    ,793,793,793
BEGIN DESCRIPTION:
Mapping XS f8478531
END DESCRIPTION:
XS GIS Cut Line= 3
      2791217.14     10071075.88      2790294.48     10071369.03
      2789332.59     10071365.95
#Sta/Elev= 30
  4133.4 1608.71  4290.6 1604.82  4376.3  1603.7  4403.3 1602.59  4551.7  1601.7
  4569.8 1600.85  4763.4 1597.93    4833  1596.2  4870.5 1597.04  4902.8 1596.18
  4960.9 1596.82  4967.3  1595.4  4981.9 1594.21  4999.5  1593.7  5004.8 1593.73
  5013.4 1595.85  5023.9 1596.65  5075.3 1596.48  5267.5 1596.91  5287.5 1595.87
  5307.5 1596.67  5497.5 1595.14  5554.5 1593.16  5557.3 1592.66  5560.5 1593.16
  5597.5 1594.59  5667.5 1595.69  5732.9 1595.75  5984.7 1599.01  6063.4 1599.54
#Mann= 8 ,-1 , 0
  4133.4     .05       0  4290.6      .1       0  4763.4     .16       0
  5075.3      .1       0  5554.5     .07       0  5560.5      .1       0
  5732.9     .05       0  5984.7      .1       0
Bank Sta=5554.5,5560.5
XS Rating Curve= 0 ,0
Exp/Cntr=0.3,0.1

Type RM Length L Ch R = 1 ,6663    ,869,869,869
BEGIN DESCRIPTION:
KUHLMAN CREEK 8.0
END DESCRIPTION:
XS GIS Cut Line= 2
      2791078.28     10070480.35      2789382.32     10070915.13
#Sta/Elev= 30
  4282.8 1607.93  4475.6 1604.14  4509.7 1602.89  4516.4 1603.39  4530.4 1602.26
  4571.7  1601.6  4654.2 1598.71  4736.8 1594.88  4801.9 1593.33  4837.5 1591.56
  4856.7 1591.69  4891.7 1592.83    4919 1590.21    4933 1591.51  4974.3 1592.64
  4984.6 1592.45  5000.6 1589.88  5015.6 1591.87  5025.9 1591.68  5036.2 1592.44
  5146.4 1592.19  5531.7 1591.69  5647.9 1590.87  5673.3 1589.72    5676 1589.22
  5679.3 1589.72  5738.2 1593.67  5800.1  1594.4  5934.3 1598.79  6033.6 1600.39
#Mann= 5 ,-1 , 0
  4282.8      .1       0  4856.7     .16       0  5146.4     .05       0
  5673.3     .07       0  5679.3     .05       0
Bank Sta=5673.3,5679.3
XS Rating Curve= 0 ,0
Exp/Cntr=0.3,0.1

Type RM Length L Ch R = 1 ,5794    ,830,830,830
BEGIN DESCRIPTION:
KUHLMAN CREEK 7.0
END DESCRIPTION:
XS GIS Cut Line= 4
      2790788.17     10069946.54      2790435.38     10069835.73
      2789455.18     10070276.71       2789273.3     10070862.41
#Sta/Elev= 30
    4542 1597.96  4583.6 1597.58  4625.5 1596.51  4765.2 1591.51  4952.3 1588.31
  4968.3 1587.86  4996.9 1585.98  5007.1    1586  5020.1 1587.74  5043.2 1588.14
  5164.5  1586.8  5193.5 1585.35    5207 1585.88  5216.2 1586.02  5245.3  1584.6
  5248.1  1584.1  5251.3  1584.6  5270.3 1585.54  5355.2 1585.75  5435.6 1586.67
  5724.4 1587.24  5763.7  1586.5  5840.1  1587.9  5891.9 1587.64  5972.3 1589.72
  6060.9 1590.38  6203.4 1593.71  6364.5 1596.04  6402.3 1597.41  6599.9 1598.42
#Mann= 5 ,-1 , 0
    4542     .05       0  4765.2     .16       0    5207     .05       0
  5245.3     .07       0  5251.3     .05       0
Bank Sta=5245.3,5251.3
XS Rating Curve= 0 ,0
Exp/Cntr=0.3,0.1

Type RM Length L Ch R = 1 ,4964    ,210,210,210
BEGIN DESCRIPTION:
KUHLMAN CREEK 6.0
END DESCRIPTION:
XS GIS Cut Line= 3
      2790127.83     10069236.85      2788828.79     10069573.18
      2788613.12      10070167.8
#Sta/Elev= 30
  4814.6 1589.08  4866.4 1587.73  4896.6 1585.91  4901.8 1585.03  4948.2 1582.39
  4983.1 1582.24  4999.9 1581.63  5023.7 1582.08  5051.5 1581.48  5134.2 1581.67
  5183.1 1580.87  5185.8 1580.37  5189.1 1580.87  5227.1 1581.82  5330.4 1581.18
  5351.1 1582.25  5371.7 1581.48  5392.4 1581.87  5419.4 1580.97  5500.6 1581.82
    5630 1582.06  5826.3 1581.64  5867.6 1582.48  6001.9  1583.6    6140 1586.49
  6242.2 1586.04  6444.3 1587.78  6554.7 1587.56  6710.2 1588.42    6789 1588.27
#Mann= 3 ,-1 , 0
  4814.6     .05       0  5183.1    .035       0  5189.1     .05       0
Bank Sta=5183.1,5189.1
XS Rating Curve= 0 ,0
Exp/Cntr=0.3,0.1

Type RM Length L Ch R = 1 ,4754    ,816,816,816
BEGIN DESCRIPTION:
Mapping XS dae7b72a
END DESCRIPTION:
XS GIS Cut Line= 4
      2790080.31     10069107.08       2789950.1     10069067.15
      2788811.21     10069407.43      2788492.61     10070053.29
#Sta/Elev= 30
  4795.7 1586.43  4829.2 1585.63    4909 1585.48  4938.1 1585.16  4971.2 1581.01
  5004.4 1580.49  5012.7 1580.85  5185.6 1580.37  5221.4 1579.41  5246.6 1579.88
  5403.3    1581  5413.7 1580.33    5445 1580.45  5483.7  1579.2  5486.5  1578.7
  5489.7  1579.2  5499.4 1579.89  5570.8 1581.41  5598.7 1580.52  5603.9 1581.07
  5664.2 1580.09  5904.2 1581.23  6029.5 1583.14  6225.4 1585.03    6306 1587.38
  6365.7 1586.39  6427.5 1587.13  6522.9 1586.88  6584.6 1587.67  6840.7 1588.65
#Mann= 7 ,-1 , 0
  4795.7     .05       0    4909      .1       0  5012.7     .05       0
  5221.4      .1       0  5246.6     .05       0  5483.7     .07       0
  5489.7     .05       0
Bank Sta=5483.7,5489.7
XS Rating Curve= 0 ,0
Exp/Cntr=0.3,0.1

Type RM Length L Ch R = 1 ,3938    ,707,707,707
BEGIN DESCRIPTION:
KUHLMAN CREEK 5.0
END DESCRIPTION:
XS GIS Cut Line= 4
      2790078.47      10069085.6      2789905.69     10068690.68
      2788742.39       10068234.      2787752.72     10068563.89
#Sta/Elev= 30
  4206.7 1585.79  4216.9 1585.69  4221.9 1585.74  4536.2 1582.17  4715.9 1578.31
  4751.8  1577.6  4817.4 1577.29  4903.4 1575.85  4947.9 1575.64  4972.3 1576.37
  4989.3 1575.13  4999.1 1572.63  5001.9 1572.13  5005.1 1572.63  5010.8 1575.51
  5021.2 1576.83  5059.4 1576.36  5297.7 1575.97  5327.5 1575.41  5387.1 1576.19
  5397.5 1574.98    5419 1574.19  5472.7 1574.87  5519.9 1574.26  5820.8 1579.74
  6089.4 1580.59  6144.6 1579.57  6189.6    1581  6405.6 1583.86  6930.7 1589.54
#Mann= 8 ,-1 , 0
  4206.7      .1       0  4216.9     .05       0  4221.9      .1       0
  4715.9     .05       0  4751.8      .1       0  4999.1     .07       0
  5005.1      .1       0  5059.4     .05       0
Bank Sta=4999.1,5005.1
XS Rating Curve= 0 ,0
Exp/Cntr=0.3,0.1

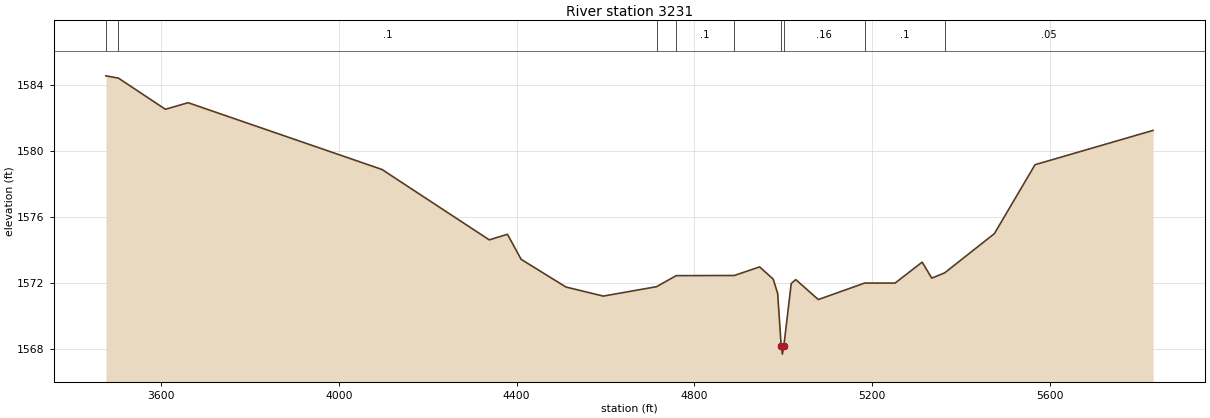
Type RM Length L Ch R = 1 ,3231    ,517,517,517
BEGIN DESCRIPTION:
KUHLMAN CREEK 4.0
END DESCRIPTION:
XS GIS Cut Line= 3
       2791090.6      10068147.6      2789720.55     10067925.43
      2788767.12     10068098.22
#Sta/Elev= 30
  3475.5 1584.54  3503.8  1584.4  3609.4 1582.51  3660.5 1582.91  4096.9 1578.86
  4338.4 1574.59  4379.3 1574.93  4410.1 1573.41    4511 1571.73    4595 1571.18
  4714.8 1571.75  4759.1 1572.42  4889.8 1572.43  4946.9 1572.95  4977.4 1572.21
  4987.5 1571.34  4995.4 1568.16  4998.2 1567.66  5001.4 1568.16    5018 1571.94
  5028.2 1572.18    5079 1570.97  5183.1 1571.97  5251.8 1571.97  5312.7 1573.24
  5334.3 1572.27  5363.5 1572.59  5475.3 1574.97  5566.8 1579.15  5832.4 1581.23
#Mann= 9 ,-1 , 0
  3475.5     .05       0  3503.8      .1       0  4714.8     .05       0
  4759.1      .1       0  4889.8     .16       0  4995.4     .07       0
  5001.4     .16       0  5183.1      .1       0  5363.5     .05       0
Bank Sta=4995.4,5001.4
XS Rating Curve= 0 ,0
Exp/Cntr=0.3,0.1