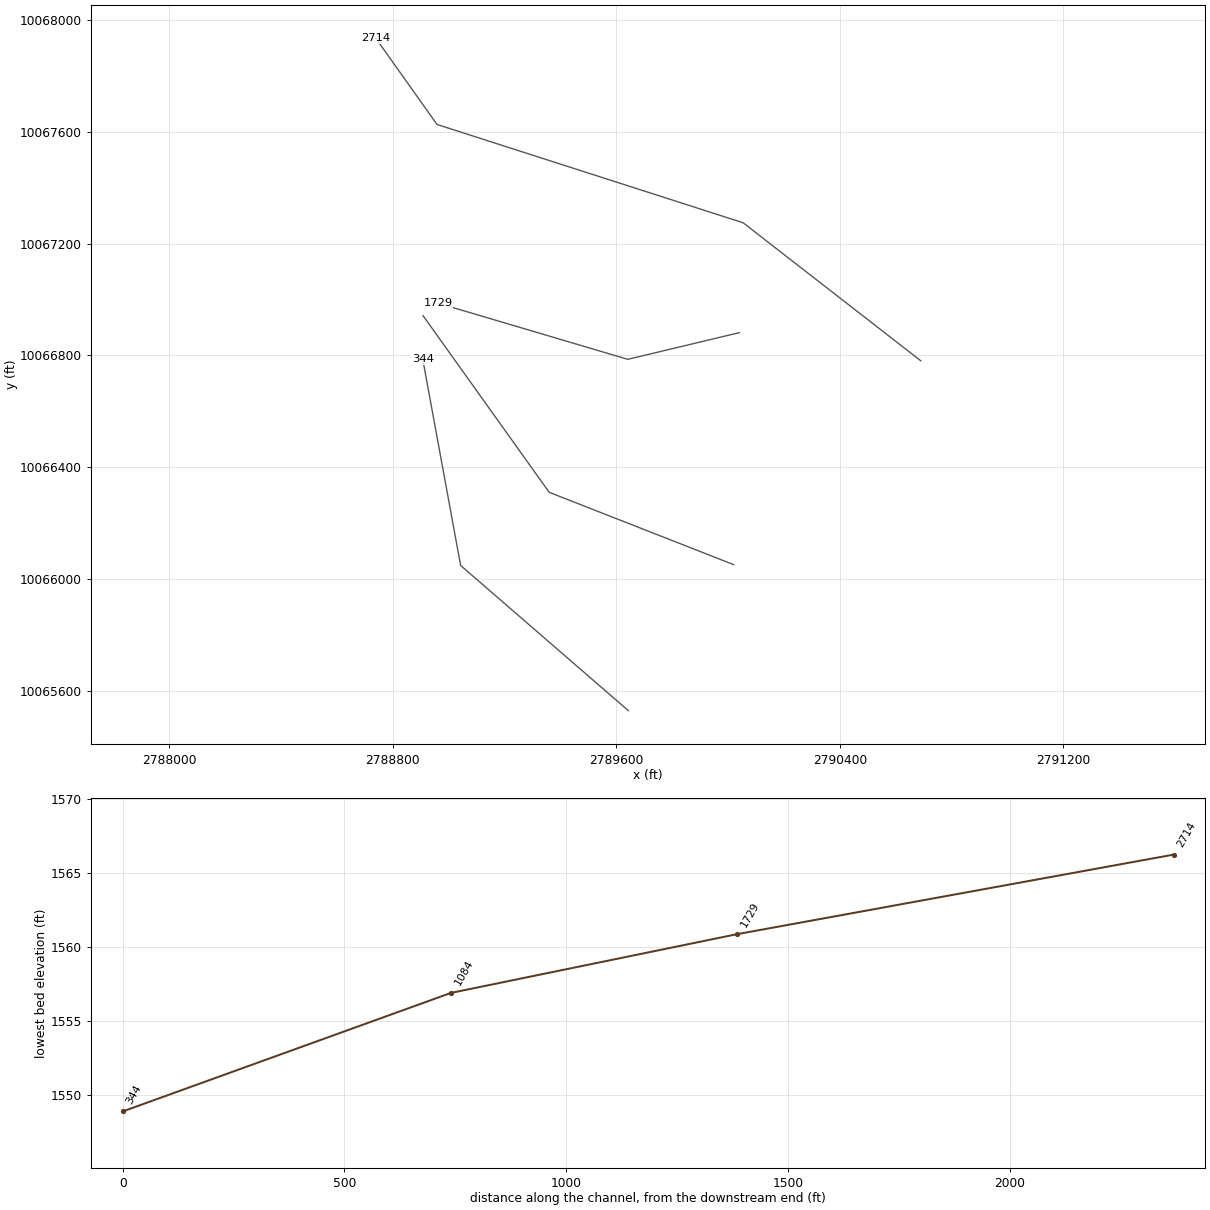
HEC-RAS study KUHLMAN CREEK.prj: KUHLMAN CREEK Base Level Engineering

--- KUHLMAN CREEK.g01 (geometry) --- (continued)

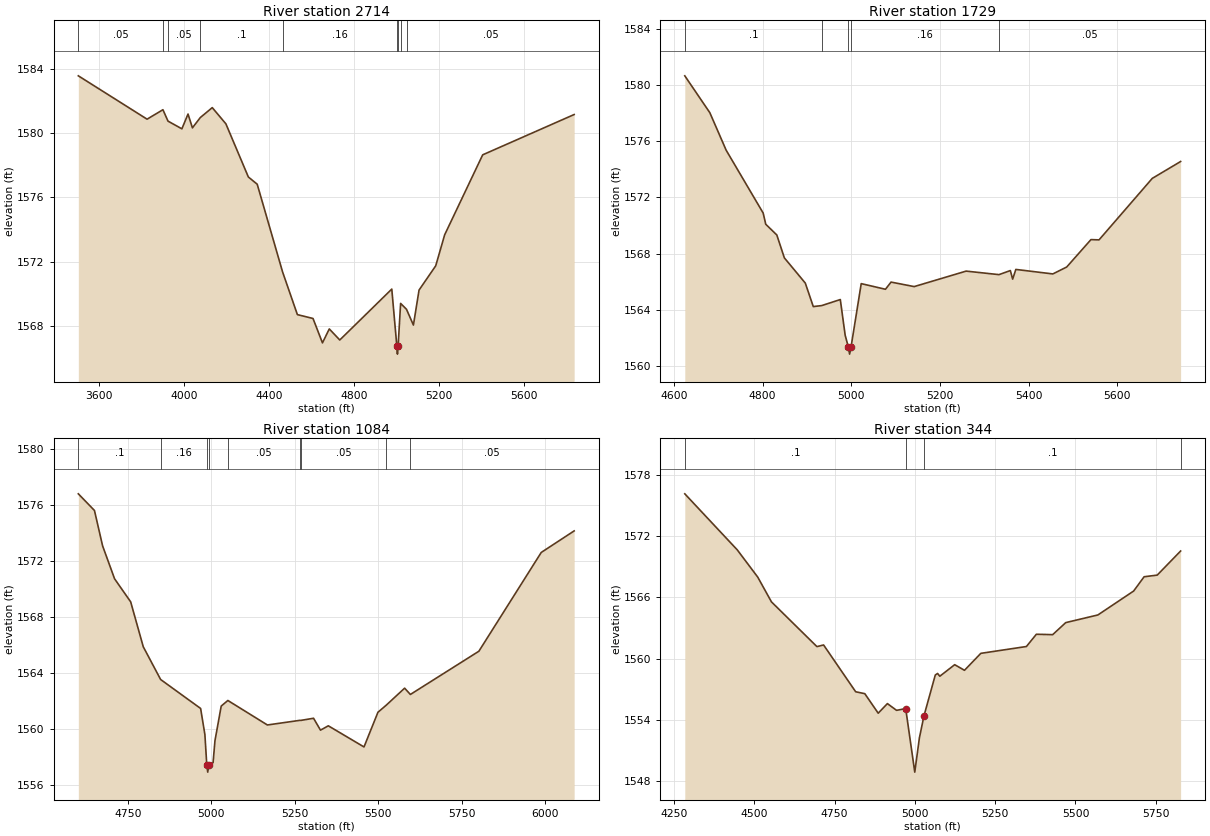
Type RM Length L Ch R = 1 ,2714    ,985,985,985
BEGIN DESCRIPTION:
KUHLMAN CREEK 3.0
END DESCRIPTION:
XS GIS Cut Line= 4
      2790689.48     10066780.63       2790053.8     10067274.36
      2788958.39     10067626.12      2788739.32     10067934.66
#Sta/Elev= 30
    3501 1583.57  3824.6 1580.87  3899.2 1581.46    3923 1580.75  3988.4 1580.27
  4017.3 1581.19  4038.1 1580.33    4075 1580.97  4131.4 1581.59  4195.6 1580.58
  4301.3 1577.27    4343 1576.82  4462.6 1571.35  4532.1  1568.7  4605.6 1568.46
  4650.1 1566.94  4682.2 1567.81  4731.6 1567.12  4976.4 1570.29  5000.2 1566.74
    5003 1566.24  5006.2 1566.74    5018  1569.4  5045.7 1569.03  5078.2 1568.05
  5104.8 1570.23  5183.2 1571.74  5225.3 1573.67  5404.3 1578.65  5834.8 1581.16
#Mann= 9 ,-1 , 0
    3501     .05       0  3899.2      .1       0    3923     .05       0
    4075      .1       0  4462.6     .16       0  5000.2     .07       0
  5006.2     .16       0    5018      .1       0  5045.7     .05       0
Bank Sta=5000.2,5006.2
XS Rating Curve= 0 ,0
Exp/Cntr=0.3,0.1

Type RM Length L Ch R = 1 ,1729    ,645,645,645
BEGIN DESCRIPTION:
KUHLMAN CREEK 2.0
END DESCRIPTION:
XS GIS Cut Line= 3
       2790040.4     10066881.39      2789641.07      10066785.9
      2788961.97     10066986.86
#Sta/Elev= 30
  4624.4 1580.64  4680.9 1578.02  4717.8 1575.35  4801.2 1570.89  4807.1 1570.09
    4832 1569.33  4849.1  1567.7  4896.3 1565.91  4914.3 1564.24  4933.4 1564.31
  4975.3 1564.74  4986.3  1562.2  4993.5 1561.36  4996.3 1560.86  4999.5 1561.36
  5022.5 1565.87  5077.2 1565.47  5089.8 1565.98    5142 1565.66  5259.2 1566.76
  5333.4 1566.51    5359  1566.8  5364.2 1566.19  5371.4 1566.88  5454.8 1566.56
  5486.1 1567.05  5540.9    1569  5559.1 1568.98  5679.2 1573.35  5743.2 1574.55
#Mann= 5 ,-1 , 0
  4624.4      .1       0  4933.4     .16       0  4993.5     .07       0
  4999.5     .16       0  5333.4     .05       0
Bank Sta=4993.5,4999.5
XS Rating Curve= 0 ,0
Exp/Cntr=0.3,0.1

Type RM Length L Ch R = 1 ,1084    ,740,740,740
BEGIN DESCRIPTION:
Mapping XS 971b5ce9
END DESCRIPTION:
XS GIS Cut Line= 3
      2790019.51     10066051.53      2789359.82     10066310.21
      2788908.43     10066942.15
#Sta/Elev= 30
  4601.6 1576.78  4649.9 1575.59  4674.3 1573.06  4710.1 1570.71  4758.4 1569.06
  4796.1 1565.85  4848.1 1563.51  4967.9 1561.44  4980.7 1559.58  4986.4 1557.39
  4989.2 1556.89  4992.4 1557.39  5005.2 1557.56  5010.9 1559.14  5029.6 1561.61
  5049.5 1562.01  5167.9 1560.26    5265 1560.59  5268.9 1560.59  5306.2 1560.74
    5327 1559.89  5350.4  1560.2  5457.3 1558.69  5499.1 1561.17  5523.7 1561.67
    5579 1562.89  5596.2 1562.44  5801.4 1565.53  5988.2 1572.59  6086.8 1574.13
#Mann= 9 ,-1 , 0
  4601.6      .1       0  4848.1     .16       0  4986.4     .07       0
  4992.4     .16       0  5049.5     .05       0    5265      .1       0
  5268.9     .05       0  5523.7     .16       0  5596.2     .05       0
Bank Sta=4986.4,4992.4
XS Rating Curve= 0 ,0
Exp/Cntr=0.3,0.1

Type RM Length L Ch R = 1 ,344     ,0,0,0
BEGIN DESCRIPTION:
KUHLMAN CREEK 1.0
END DESCRIPTION:
XS GIS Cut Line= 3
      2789643.46     10065528.74      2789042.98     10066048.49
      2788907.56     10066785.47
#Sta/Elev= 30
  4283.9 1576.13  4447.3 1570.64  4510.9 1567.98  4553.7 1565.55  4695.2 1561.17
    4716 1561.33  4815.8 1556.75  4844.3 1556.56    4886 1554.65  4914.6 1555.59
  4943.1 1554.93  4971.6  1555.1  4999.8 1548.88  5014.3 1552.25  5028.6 1554.41
  5063.7 1558.39  5070.8 1558.54  5077.8 1558.27  5124.1  1559.4  5154.6 1558.85
  5205.4 1560.51  5347.4 1561.18  5378.3 1562.38  5429.1 1562.34  5469.8 1563.52
  5569.9 1564.27  5681.1 1566.61  5713.8 1568.01  5754.5 1568.17  5827.4 1570.53
#Mann= 4 ,-1 , 0
  4283.9      .1       0  4971.6     .05       0  5028.6      .1       0
  5827.4     .05       0
Bank Sta=4971.6,5028.6
XS Rating Curve= 0 ,0
Exp/Cntr=0.3,0.1

Chan Stop Cuts=-1
Use User Specified Reach Order=0
Composite Channel Slope=5