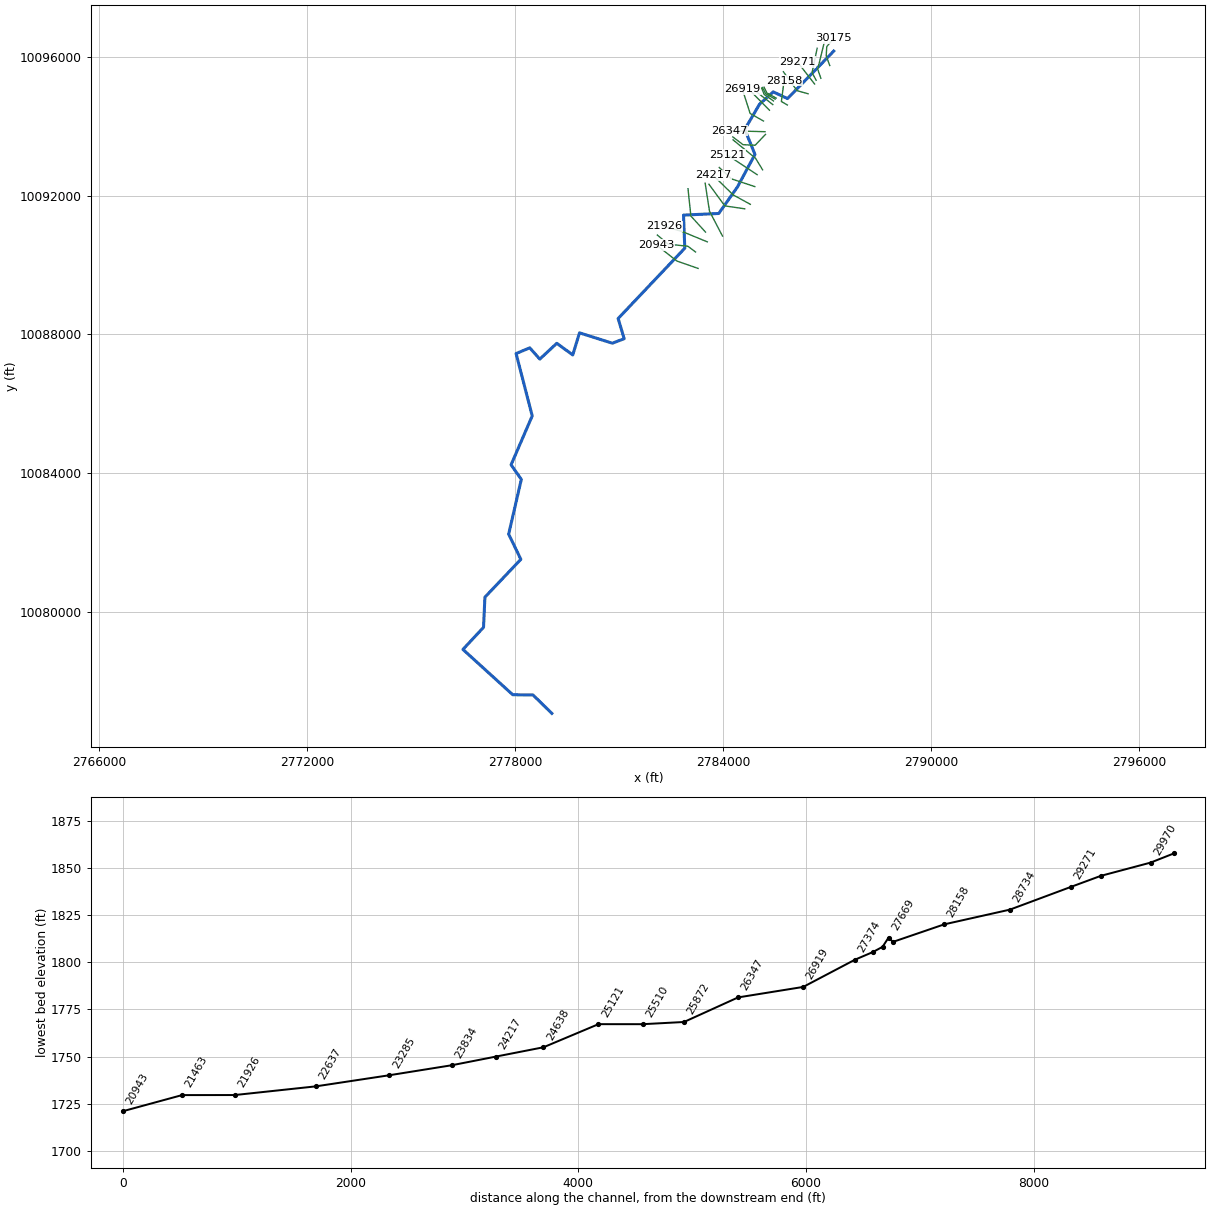
--- MARSCHALL CREEK.prj (project) ---

Proj Title=MARSCHALL CREEK Base Level Engineering
Current Plan=p01
Default Exp/Contr=0.3,0.1
English Units
Geom File=g01
Flow File=f01
Plan File=p01
Y Axis Title=Elevation
X Axis Title(PF)=Main Channel Distance
X Axis Title(XS)=Station
BEGIN DESCRIPTION:
MARSCHALL CREEK
END DESCRIPTION:
DSS Export Rating Curves= 0
DSS Export Rating Curve Sorted= 0
DSS Export Volume Flow Curves= 0
DXF OffsetX= 0
DXF OffsetY= 0
DXF ScaleX= 1
DXF ScaleY= 10

--- MARSCHALL CREEK.p01 (plan) ---

Plan Title=Multiple Run
Short Identifier=Multiple
Geom File=g01
Flow File=f01
Subcritical Flow
K Sum by GR= 0
Std Step Tol= 0.01
Critical Tol= 0.01
Num of Std Step Trials= 20
Max Error Tol= 0.3
Flow Tol Ratio= 0.001
Split Flow NTrial= 30
Split Flow Tol= 0.02
Split Flow Ratio= 0.02
Log Output Level= 0
Friction Slope Method= 1
Unsteady Friction Slope Method= 2
Unsteady Bridges Friction Slope Method= 1
Parabolic Critical Depth
Global Vel Dist=  1 , 1 , 1
Global Log Level= 0
CheckData=True
Encroach Param= -1, 0, 0, 0
BEGIN DESCRIPTION:
Multiple Run
END DESCRIPTION:

--- MARSCHALL CREEK.f01 (steady flow) ---

Flow Title=Multiple
Program Version=4.10
Number of Profiles= 7
Profile Names=10-year,25-year,50-year,1pct_min,100-year,1pct_plu,500-year
River Rch & RM=MARSCHALL CREEK,Reach-1         ,30175
     761    1098    1390    1290    1745    2359    2758
River Rch & RM=MARSCHALL CREEK,Reach-1         ,25510
    1183    1753    2258    2129    2880    3894    4701
River Rch & RM=MARSCHALL CREEK,Reach-1         ,23285
    1744    2619    3403    3230    4368    5907    7230
River Rch & RM=MARSCHALL CREEK,Reach-1         ,14409
    2780    4268    5630    5416    7325    9906   12462
River Rch & RM=MARSCHALL CREEK,Reach-1         ,13229
    3014    4623    6072    5851    7913   10702   13421
River Rch & RM=MARSCHALL CREEK,Reach-1         ,4892
    3024    4633    6101    5856    7919   10710   13409
River Rch & RM=MARSCHALL CREEK,Reach-1         ,3668
    4128    6376    8443    8138   11006   14884   18798
Boundary for River Rch & Prof#=MARSCHALL CREEK,Reach-1         , 1
Up Type= 0
Dn Type= 3
Dn Slope=0.0036
Boundary for River Rch & Prof#=MARSCHALL CREEK,Reach-1         , 2
Up Type= 0
Dn Type= 3
Dn Slope=0.0036
Boundary for River Rch & Prof#=MARSCHALL CREEK,Reach-1         , 3
Up Type= 0
Dn Type= 3
Dn Slope=0.0036
Boundary for River Rch & Prof#=MARSCHALL CREEK,Reach-1         , 4
Up Type= 0
Dn Type= 3
Dn Slope=0.0036
Boundary for River Rch & Prof#=MARSCHALL CREEK,Reach-1         , 5
Up Type= 0
Dn Type= 3
Dn Slope=0.0036
Boundary for River Rch & Prof#=MARSCHALL CREEK,Reach-1         , 6
Up Type= 0
Dn Type= 3
Dn Slope=0.0036
Boundary for River Rch & Prof#=MARSCHALL CREEK,Reach-1         , 7
Up Type= 0
Dn Type= 3
Dn Slope=0.0036
DSS Import GetInterval= 0
DSS Import GetPeak= 0
DSS Import FillOption= 0

--- MARSCHALL CREEK.g01 (geometry) ---

Geom Title=Existing Conditions
Program Version=4.10

River Reach=MARSCHALL CREEK ,Reach-1
Reach XY= 30
      2787183.49     10096168.69      2785851.18     10094799.74
      2785437.86     10094992.56      2785043.39     10094636.26
      2784618.34     10093912.73      2784911.53     10093189.05
      2784409.65     10092254.14      2783867.55     10091485.94
      2782851.49     10091438.97      2782888.47     10090484.81
      2780966.42     10088456.55       2781140.2     10087874.44
       2780798.5      10087744.8       2779852.4     10088043.56
      2779657.22     10087406.39       2779196.6     10087741.71
      2778707.25     10087286.17      2778417.31      10087611.1
      2778022.92      10087446.6      2778488.59     10085648.65
      2777879.05     10084238.49      2778173.82     10083817.07
      2777809.16     10082238.57      2778160.51     10081511.86
      2777124.31     10080420.34      2777084.18      10079550.9
      2776490.52     10078913.48      2777926.63     10077607.38
      2778511.61     10077599.94       2779054.5     10077069.62

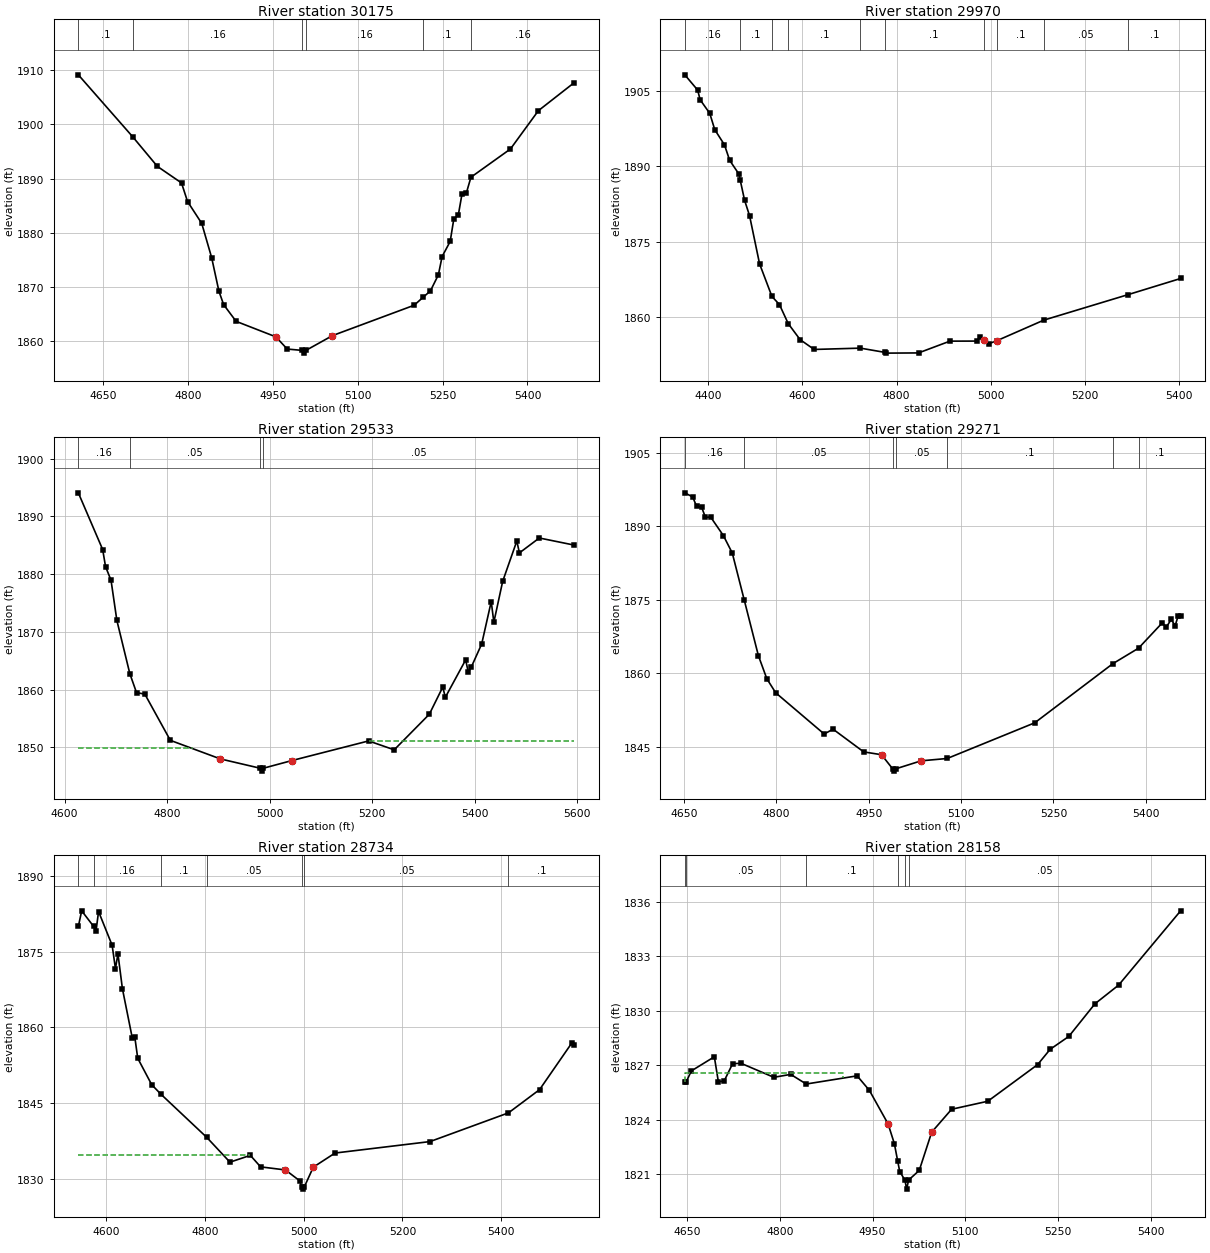
Type RM Length L Ch R = 1 ,30175   ,205,205,205
BEGIN DESCRIPTION:
Mapping XS 608cf993
END DESCRIPTION:
XS GIS Cut Line= 4
      2787068.73     10095752.62      2786966.74     10096028.21
      2786981.93      10096297.3      2787184.68     10096536.71
#Sta/Elev= 30
  4605.5 1909.12  4701.9 1897.67  4745.3 1892.24    4788 1889.19  4798.7 1885.76
  4823.8 1881.73  4841.3 1875.43  4854.2 1869.22  4862.6 1866.74  4884.6 1863.67
    4955 1860.81    4975 1858.56    5002 1858.31  5004.8 1857.81    5008 1858.31
  5055.1 1861.04  5199.6 1866.64  5215.5 1868.12  5228.2 1869.26  5242.4 1872.24
    5249 1875.61  5263.3 1878.41  5269.8  1882.6  5277.6 1883.23  5284.1 1887.09
  5291.9 1887.33    5300 1890.24  5369.9 1895.45  5419.3 1902.51  5482.6 1907.67
#Mann= 6 ,-1 , 0
  4605.5      .1       0  4701.9     .16       0    5002     .07       0
    5008     .16       0  5215.5      .1       0    5300     .16       0
Bank Sta=4955,5055.1
XS Rating Curve= 0 ,0
Exp/Cntr=0.3,0.1

Type RM Length L Ch R = 1 ,29970   ,437,437,437
BEGIN DESCRIPTION:
Mapping XS b00841a8
END DESCRIPTION:
XS GIS Cut Line= 3
      2786812.67     10095383.65      2786721.52     10095646.26
      2786905.65     10096400.11
#Sta/Elev= 30
  4349.9 1908.14  4377.2 1905.12  4382.5 1903.19  4402.9 1900.51  4413.6 1897.26
  4434.2 1894.25  4445.3 1891.17  4465.3  1888.4  4467.7 1887.25    4477 1883.25
  4487.6 1880.18  4508.8 1870.65  4535.1 1864.17  4551.1 1862.55  4569.8 1858.77
  4595.1 1855.59  4624.9 1853.65  4723.2 1853.91  4774.6 1853.08  4776.7 1852.92
  4846.7 1852.96  4913.5  1855.3  4971.7 1855.31  4976.8  1856.1  4985.6 1855.48
  4995.9 1854.78  5013.4 1855.39  5113.1 1859.47  5292.3 1864.53  5403.9 1867.73
#Mann= 10 ,-1 , 0
  4349.9     .16       0  4467.7      .1       0  4535.1     .05       0
  4569.8      .1       0  4723.2     .16       0  4774.6      .1       0
  4985.6     .07       0  5013.4      .1       0  5113.1     .05       0
  5292.3      .1       0
#Block Obstruct= 2 , 0
         4964.12 1854.78
Bank Sta=4985.6,5013.4
XS Rating Curve= 0 ,0
Exp/Cntr=0.3,0.1

Type RM Length L Ch R = 1 ,29533   ,262,262,262
BEGIN DESCRIPTION:
MARSCHALL CREEK 58.0
END DESCRIPTION:
XS GIS Cut Line= 3
      2786675.94     10095327.27      2786558.76     10095548.61
      2786706.02     10096250.27
#Sta/Elev= 30
  4626.9 1894.08  4674.4 1884.26    4680  1881.3  4690.7 1878.94  4702.1 1871.98
  4727.3 1862.79  4740.4 1859.49  4756.7 1859.22  4806.4 1851.22  4904.2    1848
  4981.8 1846.39  4984.5 1845.89  4987.8 1846.39  5043.6 1847.72  5193.3 1851.12
  5243.2 1849.58  5311.7 1855.74  5337.9 1860.44    5343 1858.68  5382.6 1865.15
  5387.7 1863.04  5393.5 1863.89  5413.9 1867.91  5432.5 1875.25  5437.6 1871.67
  5454.8 1878.74  5482.4 1885.73  5487.5 1883.68  5526.3 1886.26  5594.3 1885.03
#Mann= 4 ,-1 , 0
  4626.9     .16       0  4727.3     .05       0  4981.8     .04       0
  4987.8     .05       0
#XS Ineff= 2 , 0
         4849.59 1849.89 5193.42         1851.12
Permanent Ineff=
       F       F
Bank Sta=4904.2,5043.6
XS Rating Curve= 0 ,0
Exp/Cntr=0.3,0.1

Type RM Length L Ch R = 1 ,29271   ,537,537,537
BEGIN DESCRIPTION:
MARSCHALL CREEK 57.0
END DESCRIPTION:
XS GIS Cut Line= 2
      2786631.98     10095219.43      2786137.22     10095854.81
#Sta/Elev= 30
  4651.2 1896.83    4664 1895.99  4670.4 1894.06  4678.5  1893.9  4684.8  1891.8
    4693 1891.92  4713.8 1888.12  4728.3 1884.55  4747.6 1875.03  4770.7 1863.62
  4784.4  1858.9  4798.8 1856.04  4877.6 1847.62    4892 1848.61  4941.8 1843.97
  4970.7  1843.4  4988.6 1840.55  4991.3 1840.05  4994.6 1840.55    5035 1842.15
  5077.4 1842.63  5219.6 1849.91  5346.5 1861.98  5388.1 1865.13  5426.7  1870.3
  5433.1  1869.4  5441.2 1870.99  5447.6 1869.72  5452.7  1871.8  5456.5  1871.8
#Mann= 7 ,-1 , 0
  4651.2     .16       0  4747.6     .05       0  4988.6     .04       0
  4994.6     .05       0  5077.4      .1       0  5346.5     .05       0
  5388.1      .1       0
Bank Sta=4970.7,5035
XS Rating Curve= 0 ,0
Exp/Cntr=0.3,0.1

Type RM Length L Ch R = 1 ,28734   ,576,576,576
BEGIN DESCRIPTION:
MARSCHALL CREEK 56.0
END DESCRIPTION:
XS GIS Cut Line= 3
      2786444.47     10094938.17      2786126.79      10095026.7
      2785730.95     10095573.59
#Sta/Elev= 30
  4543.1    1880  4549.9  1883.1  4574.1 1880.01  4578.9 1879.07  4584.1 1882.96
  4611.6 1876.28  4618.3 1871.67  4623.4 1874.57  4632.4 1867.69  4652.5 1857.88
  4657.6 1858.06  4663.5 1853.89  4691.8 1848.66  4710.3 1846.79  4803.4 1838.22
  4850.4 1833.31  4891.7 1834.66  4912.5 1832.38  4962.8 1831.77  4992.2 1829.59
  4995.4 1828.47  4998.1 1827.97  5001.4 1828.47  5019.3 1832.32  5063.4 1835.12
  5255.9 1837.39  5414.9 1843.08  5477.9 1847.68  5542.9 1856.87    5548 1856.52
#Mann= 7 ,-1 , 0
  4543.1      .1       0  4574.1     .16       0  4710.3      .1       0
  4803.4     .05       0  4995.4     .04       0  5001.4     .05       0
  5414.9      .1       0
#XS Ineff= 2 , 0
         4891.21 1834.72
Permanent Ineff=
       F       F
Bank Sta=4962.8,5019.3
XS Rating Curve= 0 ,0
Exp/Cntr=0.3,0.1

Type RM Length L Ch R = 1 ,28158   ,451,451,451
BEGIN DESCRIPTION:
MARSCHALL CREEK 55.0
END DESCRIPTION:
XS GIS Cut Line= 3
      2785845.56     10094615.23      2785673.66      10094714.2
      2785751.79     10095313.18
#Sta/Elev= 30
  4646.1 1826.09  4648.5 1826.08  4656.6 1826.68  4693.9 1827.46  4700.4 1826.09
  4709.7 1826.12  4723.5 1827.08  4737.1  1827.1  4790.2 1826.33  4817.5 1826.49
  4842.6 1825.96    4925 1826.41  4944.8 1825.61  4975.1 1823.76  4985.2 1822.68
  4990.5 1821.74  4993.9 1821.14  5002.3 1820.67  5005.1 1820.17  5008.3 1820.67
  5025.5  1821.2  5045.7 1823.31  5077.9 1824.57  5136.4 1825.01  5217.1 1827.03
  5237.3 1827.87  5267.5 1828.58  5309.9 1830.38  5348.2 1831.41  5448.5  1835.5
#Mann= 6 ,-1 , 0
  4646.1      .1       0  4648.5     .05       0  4842.6      .1       0
  4990.5     .05       0  5002.3    .035       0  5008.3     .05       0
#XS Ineff= 2 , 0
         4902.55 1826.54
Permanent Ineff=
       F       F
Bank Sta=4975.1,5045.7
XS Rating Curve= 0 ,0
Exp/Cntr=0.3,0.1

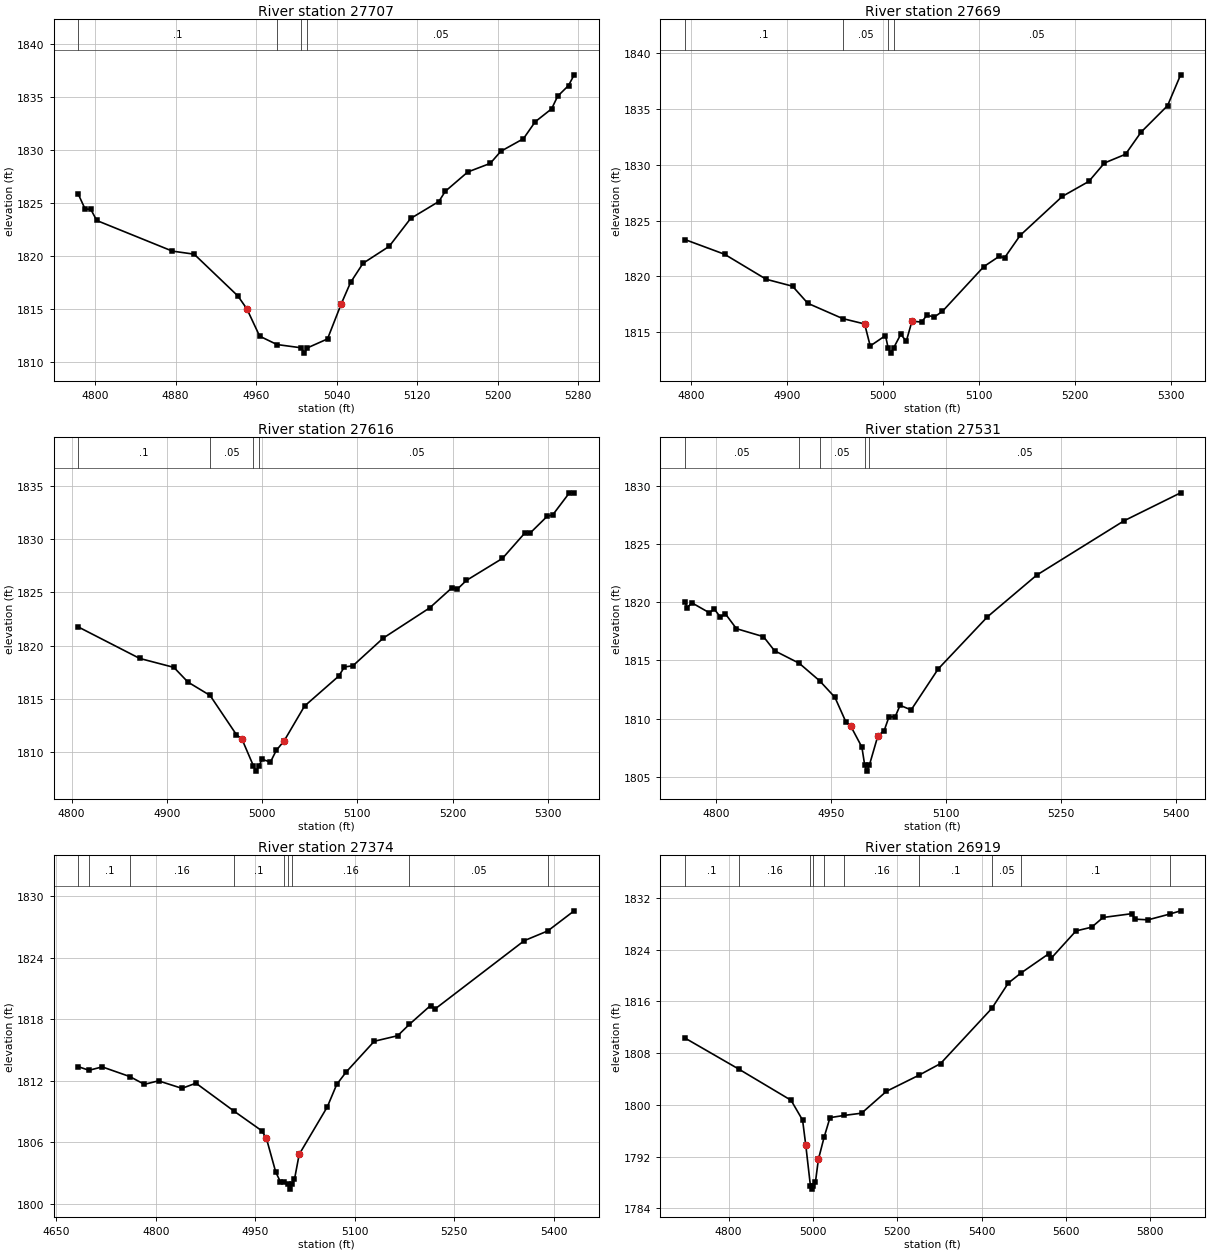
Type RM Length L Ch R = 1 ,27707   ,38,38,38
BEGIN DESCRIPTION:
MARSCHALL CREEK 54.0
END DESCRIPTION:
XS GIS Cut Line= 3
      2785524.46     10094812.78      2785254.95     10094963.81
      2785173.29     10095128.43
#Sta/Elev= 30
  4783.4 1825.84  4790.1 1824.46  4795.8 1824.42  4801.7 1823.37  4876.8 1820.48
  4898.5 1820.19  4941.9 1816.25  4950.8 1815.04  4963.6 1812.45  4980.8 1811.66
  5005.1 1811.35  5007.8 1810.85  5011.1 1811.35    5031 1812.19  5044.6 1815.49
  5053.9 1817.52  5066.3 1819.33  5092.3 1820.93  5113.6 1823.56  5141.6 1825.16
  5148.1 1826.13  5170.4 1827.95  5192.7 1828.76  5203.2  1829.9  5225.7 1831.09
  5237.4 1832.69  5253.7 1833.91  5259.7  1835.1  5270.5 1836.11  5276.1 1837.12
#Mann= 4 ,-1 , 0
  4783.4      .1       0  4980.8     .05       0  5005.1    .035       0
  5011.1     .05       0
Bank Sta=4950.8,5044.6
XS Rating Curve= 0 ,0
Exp/Cntr=0.3,0.1

Type RM Length L Ch R = 1 ,27669   ,53,53,53
BEGIN DESCRIPTION:
Mapping XS 38ea44c0
END DESCRIPTION:
XS GIS Cut Line= 3
      2785494.51     10094785.44       2785222.4     10094939.07
      2785126.03     10095118.78
#Sta/Elev= 30
  4793.4 1823.31  4834.8 1821.99  4878.2 1819.75  4905.6 1819.13  4921.5  1817.6
  4957.9 1816.23  4980.7 1815.75  4986.5 1813.78  5002.4 1814.71  5005.1 1813.64
  5007.9 1813.14  5011.1 1813.64  5018.3 1814.82  5024.1 1814.21    5030    1816
    5040 1815.92  5045.7 1816.55    5053 1816.36  5061.6 1816.87  5104.9 1820.89
  5120.8  1821.8  5126.5 1821.68  5142.7 1823.68  5186.6 1827.17  5214.2 1828.51
  5230.5 1830.16  5252.4 1830.94  5268.6 1832.92  5296.2 1835.29  5309.8 1838.05
#Mann= 4 ,-1 , 0
  4793.4      .1       0  4957.9     .05       0  5005.1    .035       0
  5011.1     .05       0
Bank Sta=4980.7,5030
XS Rating Curve= 0 ,0
Exp/Cntr=0.3,0.1

Type RM Length L Ch R = 1 ,27616   ,85,85,85
BEGIN DESCRIPTION:
Mapping XS 48aaf818
END DESCRIPTION:
XS GIS Cut Line= 3
      2785446.35     10094732.04      2785182.03     10094914.33
      2785103.91     10095097.92
#Sta/Elev= 30
  4807.1 1821.76  4871.5 1818.81  4907.4 1817.97  4922.2 1816.59  4945.4 1815.34
    4973 1811.67    4979 1811.22  4990.9 1808.74  4993.7 1808.24  4996.9 1808.74
    5000 1809.35  5008.8 1809.09  5014.9 1810.18  5023.2 1811.08  5044.6 1814.34
  5080.5 1817.15  5086.5 1818.01  5095.4 1818.12  5127.3 1820.72    5176 1823.55
  5199.7 1825.46  5205.1 1825.31  5214.5 1826.12  5252.4 1828.19    5276 1830.58
  5281.4 1830.56  5299.6 1832.16  5305.1 1832.26  5322.7 1834.34  5327.7 1834.34
#Mann= 4 ,-1 , 0
  4807.1      .1       0  4945.4     .05       0  4990.9    .035       0
  4996.9     .05       0
Bank Sta=4979,5023.2
XS Rating Curve= 0 ,0
Exp/Cntr=0.3,0.1

Type RM Length L Ch R = 1 ,27531   ,157,157,157
BEGIN DESCRIPTION:
Mapping XS bf691294
END DESCRIPTION:
XS GIS Cut Line= 2
      2785425.54     10094626.56      2784916.42       10095025.
#Sta/Elev= 30
  4759.6 1820.05  4762.7 1819.56    4769 1819.96  4791.6 1819.11    4798 1819.43
  4806.1 1818.73  4812.4 1819.03  4826.9 1817.74  4862.2 1817.05  4876.6 1815.84
  4908.8 1814.76  4935.4 1813.25  4955.3 1811.83  4969.7  1809.7  4976.1 1809.33
  4990.5 1807.54  4994.2 1805.97  4996.9 1805.47  5000.2 1805.97  5011.4 1808.52
  5019.5 1808.95  5025.8 1810.14  5033.9 1810.15  5040.3 1811.14  5054.7 1810.74
    5090 1814.27  5154.2 1818.76  5218.4 1822.35  5332.3 1827.03  5406.1 1829.44
#Mann= 5 ,-1 , 0
  4759.6     .05       0  4908.8     .16       0  4935.4     .05       0
  4994.2    .035       0  5000.2     .05       0
Bank Sta=4976.1,5011.4
XS Rating Curve= 0 ,0
Exp/Cntr=0.3,0.1

Type RM Length L Ch R = 1 ,27374   ,455,455,455
BEGIN DESCRIPTION:
MARSCHALL CREEK 53.0
END DESCRIPTION:
XS GIS Cut Line= 2
      2785329.89     10094464.23      2784803.87     10094995.46
#Sta/Elev= 30
  4683.1 1813.36  4699.2 1813.01  4719.1 1813.34  4760.6  1812.4  4782.7 1811.64
    4804 1811.98  4839.3 1811.25  4860.5 1811.75  4918.2 1809.01  4959.5 1807.12
  4966.6 1806.39  4980.7 1803.09  4987.8 1802.13  4992.6  1802.1    4999 1801.92
  5001.7 1801.42    5005 1801.92    5009 1802.37  5016.1 1804.81  5058.5 1809.44
  5072.7 1811.63  5086.8 1812.83  5129.3 1815.84  5164.6 1816.38  5182.1 1817.48
  5214.1 1819.32  5221.2    1819  5355.5 1825.65  5390.9  1826.6  5430.7 1828.56
#Mann= 9 ,-1 , 0
  4683.1     .05       0  4699.2      .1       0  4760.6     .16       0
  4918.2      .1       0  4992.6     .16       0    4999     .07       0
    5005     .16       0  5182.1     .05       0  5390.9      .1       0
Bank Sta=4966.6,5016.1
XS Rating Curve= 0 ,0
Exp/Cntr=0.3,0.1

Type RM Length L Ch R = 1 ,26919   ,572,572,572
BEGIN DESCRIPTION:
MARSCHALL CREEK 52.0
END DESCRIPTION:
XS GIS Cut Line= 3
      2785158.02     10094151.71      2784772.62     10094370.45
      2784548.67     10095068.35
#Sta/Elev= 30
  4696.2 1810.35  4824.8 1805.51  4948.2 1800.71  4975.6 1797.64  4983.2 1793.73
  4994.2 1787.46    4997 1786.96  5000.2 1787.46  5006.1 1788.07  5013.1 1791.56
  5026.6 1794.98  5040.6 1798.02  5074.9 1798.37  5115.5 1798.71  5174.4 1802.09
    5252  1804.6  5302.9 1806.39  5424.4 1814.92  5463.5 1818.84  5493.9 1820.41
  5559.8 1823.39  5565.1 1822.67  5624.1 1826.91  5661.4 1827.49  5688.3 1828.99
  5757.8 1829.59  5763.1 1828.73  5795.2 1828.63    5846 1829.51  5872.3 1830.02
#Mann= 10 ,-1 , 0
  4696.2      .1       0  4824.8     .16       0  4994.2     .07       0
  5000.2     .16       0  5026.6      .1       0  5074.9     .16       0
    5252      .1       0  5424.4     .05       0  5493.9      .1       0
    5846     .05       0
Bank Sta=4983.2,5013.1
XS Rating Curve= 0 ,0
Exp/Cntr=0.3,0.1

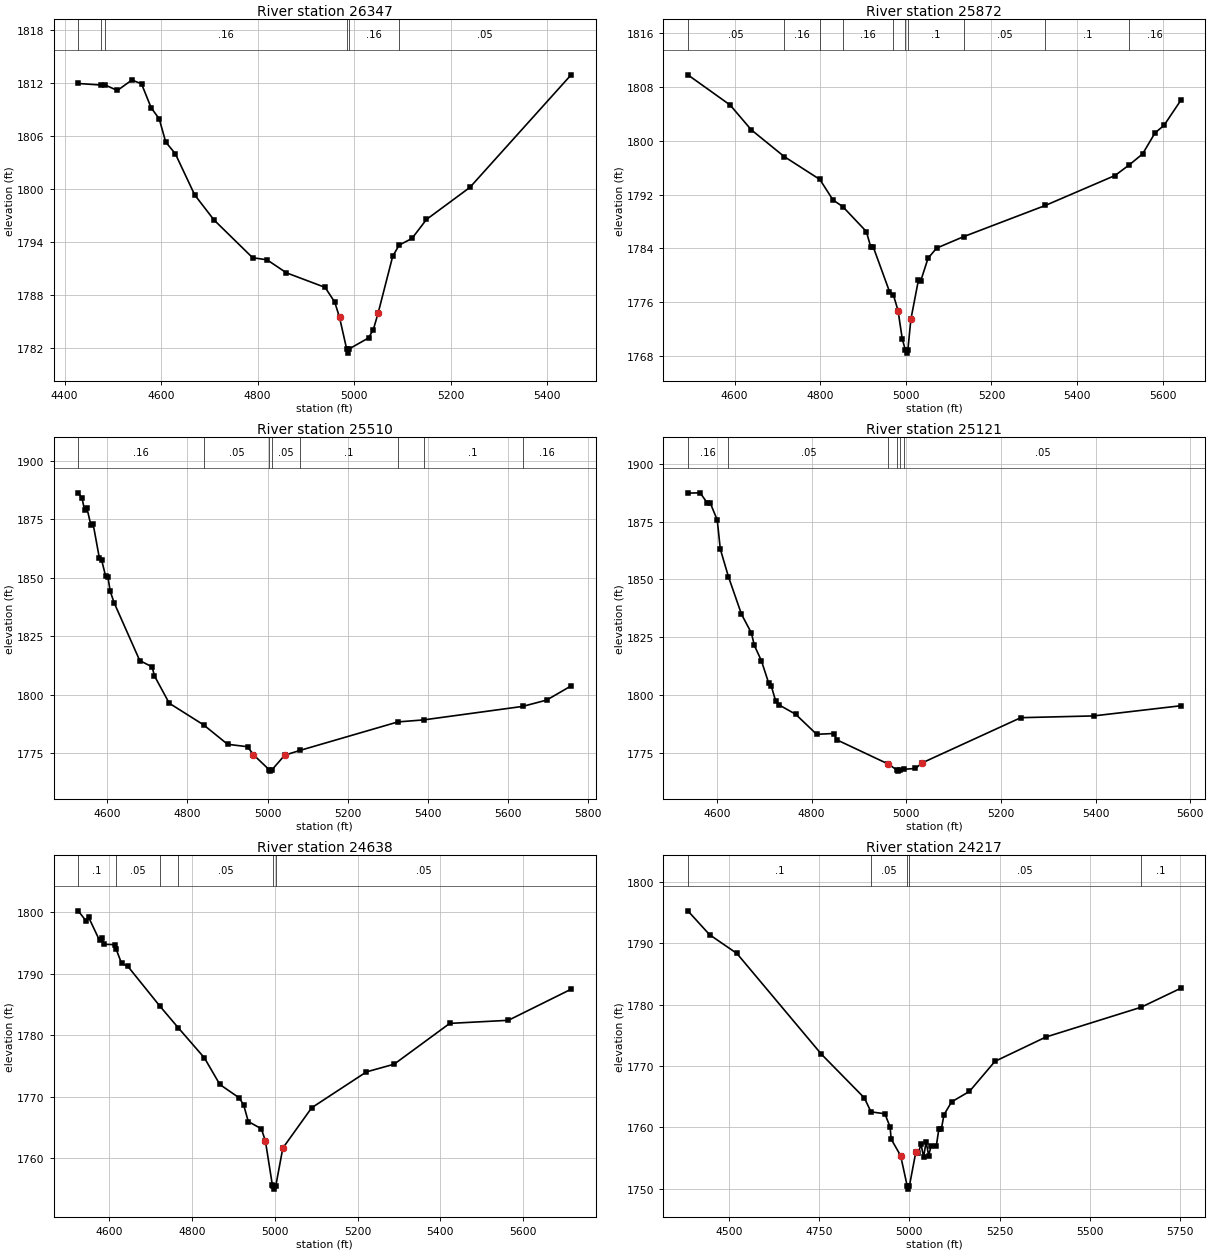
Type RM Length L Ch R = 1 ,26347   ,475,475,475
BEGIN DESCRIPTION:
MARSCHALL CREEK 51.0
END DESCRIPTION:
XS GIS Cut Line= 2
      2785199.67     10093844.41       2784178.9     10093870.45
#Sta/Elev= 30
  4428.3 1811.95  4476.3 1811.77    4483  1811.8  4509.5 1811.16  4539.5 1812.34
  4559.5 1811.91  4579.5 1809.19  4596.1 1807.95  4609.6 1805.32  4629.6 1803.98
  4669.6 1799.33  4709.6 1796.49  4789.6 1792.21  4819.6 1791.97  4859.6  1790.5
  4939.7 1788.85  4959.7 1787.19  4969.7 1785.44  4984.3  1781.9    4987  1781.4
  4990.3  1781.9  5029.7 1783.12  5039.7 1784.07  5049.7 1785.95  5079.7 1792.35
  5093.1 1793.64  5119.7 1794.39  5149.7 1796.54  5239.8 1800.18  5449.4 1812.93
#Mann= 6 ,-1 , 0
  4428.3     .05       0  4476.3      .1       0    4483     .16       0
  4984.3     .07       0  4990.3     .16       0  5093.1     .05       0
Bank Sta=4969.7,5049.7
XS Rating Curve= 0 ,0
Exp/Cntr=0.3,0.1

Type RM Length L Ch R = 1 ,25872   ,362,362,362
BEGIN DESCRIPTION:
MARSCHALL CREEK 50.0
END DESCRIPTION:
XS GIS Cut Line= 4
      2785215.34     10093766.29      2784918.46     10093453.79
       2784569.5     10093469.41      2784273.05     10093693.05
#Sta/Elev= 30
  4490.6 1809.84  4589.4 1805.34  4638.7 1801.65  4715.7 1797.66  4799.1 1794.24
  4829.7 1791.19  4852.7 1790.19  4907.7 1786.48  4918.2 1784.13  4924.1 1784.13
  4961.7 1777.54  4970.8 1777.05  4981.7  1774.7  4991.7 1770.45  4998.7 1768.86
  5001.5 1768.36  5004.7 1768.86  5011.7 1773.39  5029.5  1779.3  5034.5 1779.07
  5051.8  1782.5  5071.8 1784.01    5135 1785.72  5325.9 1790.37  5488.6 1794.83
  5522.4 1796.44  5553.1 1798.05  5582.2 1801.19  5603.1  1802.3  5642.3 1806.03
#Mann= 10 ,-1 , 0
  4490.6     .05       0  4715.7     .16       0  4799.1     .05       0
  4852.7     .16       0  4970.8      .1       0  4998.7     .07       0
  5004.7      .1       0    5135     .05       0  5325.9      .1       0
  5522.4     .16       0
Bank Sta=4981.7,5011.7
XS Rating Curve= 0 ,0
Exp/Cntr=0.3,0.1

Type RM Length L Ch R = 1 ,25510   ,389,389,389
BEGIN DESCRIPTION:
MARSCHALL CREEK 49.0
END DESCRIPTION:
XS GIS Cut Line= 3
      2785132.01     10092745.43      2784928.87     10093078.79
      2784278.65     10093609.37
#Sta/Elev= 30
  4527.4 1886.42  4537.1 1884.02  4543.4 1878.98  4549.3 1879.85  4558.9 1872.63
  4564.7 1873.05  4580.2  1858.5    4586 1857.57  4595.6 1850.87  4601.5 1850.35
  4607.4  1844.2    4617 1839.35  4680.9 1814.58  4711.8 1811.84  4717.7 1807.98
  4754.5  1796.3  4840.5 1786.98  4900.1  1778.7  4949.9 1777.65  4964.3 1774.27
  5004.4  1767.7  5007.1  1767.2  5010.4  1767.7  5042.6 1774.03  5080.4 1776.06
  5324.9 1788.28  5388.8 1789.14  5635.8 1794.92  5695.9 1797.63    5757 1803.71
#Mann= 8 ,-1 , 0
  4527.4     .16       0  4840.5     .05       0  5004.4     .04       0
  5010.4     .05       0  5080.4      .1       0  5324.9     .05       0
  5388.8      .1       0  5635.8     .16       0
Bank Sta=4964.3,5042.6
XS Rating Curve= 0 ,0
Exp/Cntr=0.3,0.1

Type RM Length L Ch R = 1 ,25121   ,483,483,483
BEGIN DESCRIPTION:
MARSCHALL CREEK 48.0
END DESCRIPTION:
XS GIS Cut Line= 2
      2784975.73     10092604.84      2784105.95     10093177.75
#Sta/Elev= 30
  4538.6 1887.27  4564.6 1887.39  4579.6 1883.02  4585.6 1883.16  4600.7 1875.69
  4607.2 1863.11  4624.3 1851.23  4651.9 1834.98    4673 1826.82    4679 1821.55
    4694 1814.89  4709.1 1805.43  4715.1 1803.81  4724.2 1797.48  4730.2 1795.93
  4766.3 1791.79  4810.7 1783.12  4846.7 1783.45  4853.7  1780.7  4962.1 1770.26
  4962.2 1770.25  4980.2 1767.71  4982.9 1767.21  4986.2 1767.71  4995.1    1768
  5019.3 1768.36  5034.4 1770.84  5242.1 1790.29  5395.8 1791.05  5580.1 1795.44
#Mann= 6 ,-1 , 0
  4538.6     .16       0  4624.3     .05       0  4962.2     .16       0
  4980.2    .035       0  4986.2     .16       0  4995.1     .05       0
Bank Sta=4962.1,5034.4
XS Rating Curve= 0 ,0
Exp/Cntr=0.3,0.1

Type RM Length L Ch R = 1 ,24638   ,421,421,421
BEGIN DESCRIPTION:
MARSCHALL CREEK 47.0
END DESCRIPTION:
XS GIS Cut Line= 3
        2784908.     10092261.09      2784230.96     10092485.04
      2783882.74     10092812.47
#Sta/Elev= 30
  4524.7 1800.22  4544.5 1798.51  4549.8 1799.19  4576.2 1795.42  4581.5 1795.86
  4587.4 1794.78  4613.2 1794.72  4616.1 1794.04  4629.5 1791.67  4644.9 1791.17
  4721.6 1784.76  4766.3 1781.21  4829.7  1776.3    4867 1771.97  4913.9 1769.79
  4924.5 1768.65  4935.7 1765.95  4967.4 1764.76  4977.1 1762.77  4993.9 1755.61
  4996.1 1755.45  4998.9 1754.95  5002.1 1755.45  5019.2 1761.63    5089 1768.19
  5221.2 1774.02  5288.1 1775.27  5422.5 1781.91  5564.1 1782.41  5715.8 1787.47
#Mann= 6 ,-1 , 0
  4524.7      .1       0  4616.1     .05       0  4721.6      .1       0
  4766.3     .05       0  4996.1     .04       0  5002.1     .05       0
Bank Sta=4977.1,5019.2
XS Rating Curve= 0 ,0
Exp/Cntr=0.3,0.1

Type RM Length L Ch R = 1 ,24217   ,383,383,383
BEGIN DESCRIPTION:
MARSCHALL CREEK 46.0
END DESCRIPTION:
XS GIS Cut Line= 3
      2784777.83     10091750.66      2784283.04     10092021.49
      2783710.09     10092584.03
#Sta/Elev= 30
  4385.6 1795.25  4445.8 1791.37  4521.7 1788.31  4755.9 1771.93  4875.1 1764.81
  4893.5 1762.54  4932.1 1762.23  4946.5 1760.08  4949.4 1758.12  4975.7 1755.41
    4994 1750.47  4996.7 1749.97    5000 1750.47  5018.1 1756.07  5025.2 1755.88
  5032.3 1757.32  5039.4 1755.17  5046.4 1757.67  5053.5 1755.44  5060.5 1757.06
  5074.7 1757.02  5081.8 1759.75  5088.8 1759.81    5096 1762.07  5117.1 1764.17
  5166.6 1765.87  5237.3 1770.76  5378.7 1774.72  5642.5 1779.56  5752.6 1782.65
#Mann= 5 ,-1 , 0
  4385.6      .1       0  4893.5     .05       0    4994     .04       0
    5000     .05       0  5642.5      .1       0
Bank Sta=4975.7,5018.1
XS Rating Curve= 0 ,0
Exp/Cntr=0.3,0.1

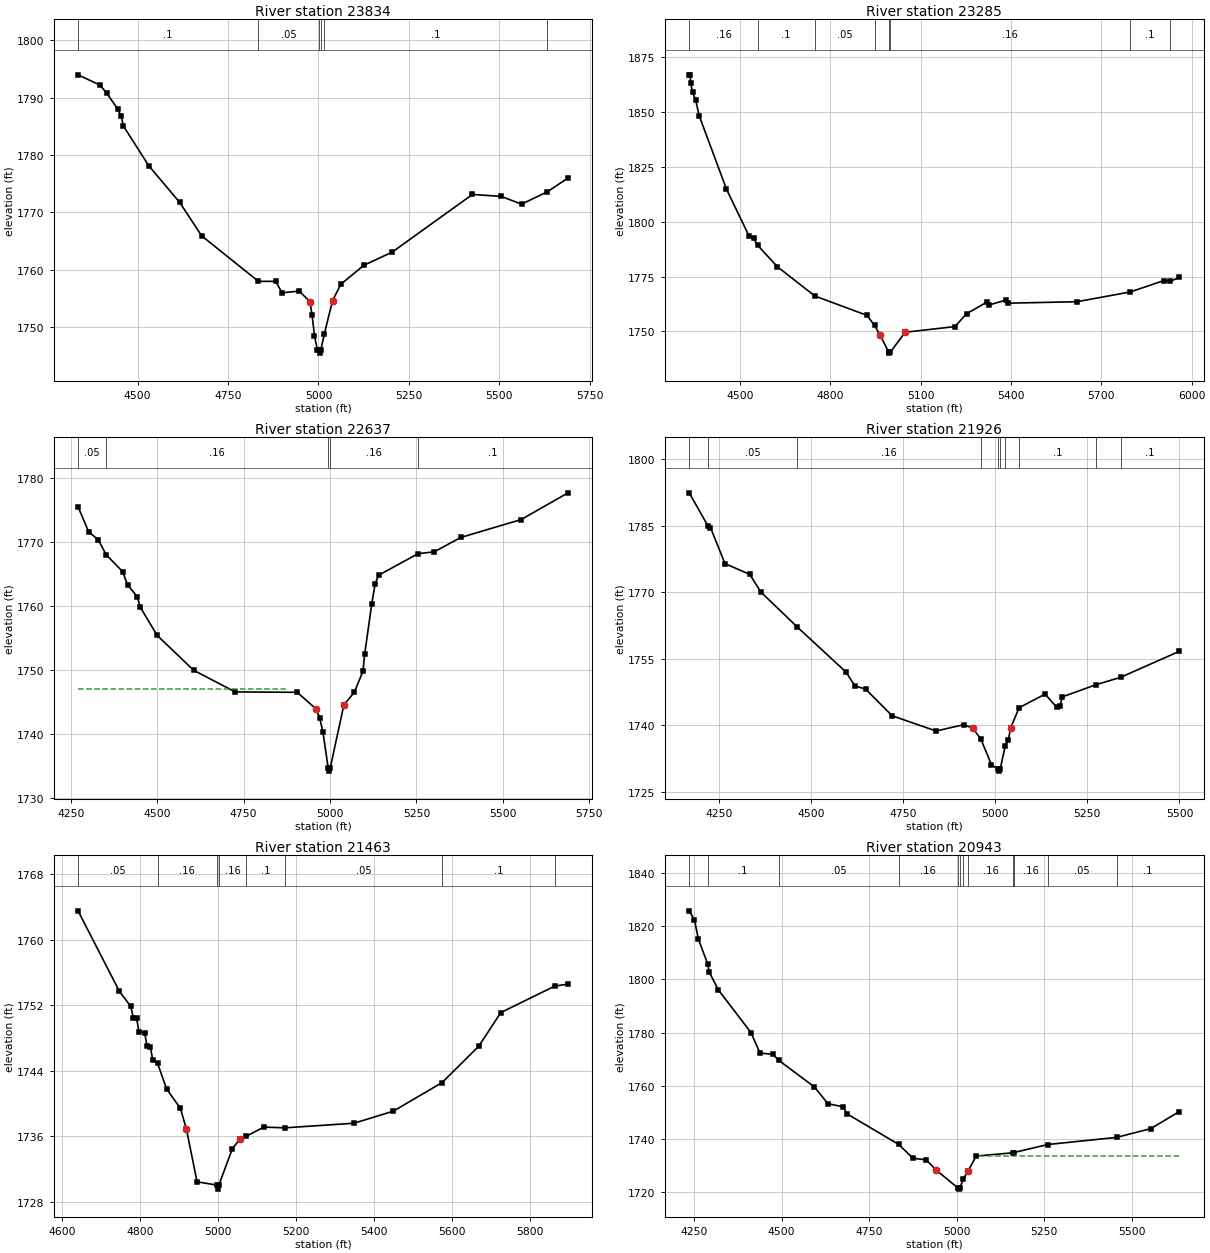
Type RM Length L Ch R = 1 ,23834   ,549,549,549
BEGIN DESCRIPTION:
MARSCHALL CREEK 45.0
END DESCRIPTION:
XS GIS Cut Line= 3
      2784616.42     10091620.45      2784043.46     10091703.79
      2783585.14     10092328.76
#Sta/Elev= 30
  4335.5 1793.97  4396.1 1792.18  4414.3 1790.81  4444.6 1788.06  4454.7 1786.73
  4461.1 1785.02  4531.2 1778.09  4616.4 1771.72    4677 1765.89  4833.9 1757.95
  4881.8 1757.95  4899.3 1755.95  4946.9 1756.25  4976.2 1754.41  4982.4 1752.01
  4988.8 1748.44    4997 1745.99  5000.2 1745.93    5003 1745.43  5006.2 1745.93
  5016.4 1748.84  5038.7 1754.57  5061.8 1757.45  5125.2 1760.74  5203.9 1763.06
  5425.4 1773.11  5504.9 1772.76  5561.3 1771.42  5632.6 1773.57  5689.5 1775.98
#Mann= 6 ,-1 , 0
  4335.5      .1       0  4833.9     .05       0  5000.2     .04       0
  5006.2     .05       0  5016.4      .1       0  5632.6     .16       0
Bank Sta=4976.2,5038.7
XS Rating Curve= 0 ,0
Exp/Cntr=0.3,0.1

Type RM Length L Ch R = 1 ,23285   ,648,648,648
BEGIN DESCRIPTION:
MARSCHALL CREEK 44.0
END DESCRIPTION:
XS GIS Cut Line= 3
      2783975.74       10090834.      2783600.75     10091552.74
      2783475.85     10092359.35
#Sta/Elev= 30
  4331.7 1866.85  4334.2 1866.85  4336.8 1863.11  4342.7    1859  4353.3  1855.2
  4365.2 1848.08  4455.5 1814.79    4530 1793.53  4545.7 1792.41  4558.8 1789.23
  4624.7 1779.44    4749 1766.12  4921.9 1757.33  4947.2 1752.71  4966.1 1748.22
  4993.9 1740.62  4996.6 1740.12  4999.9 1740.62  5048.8 1749.63  5214.2 1752.21
  5252.5 1758.05  5320.6 1763.37  5325.6 1761.96  5383.6 1764.28  5388.7 1762.86
    5619 1763.53    5796 1767.96  5908.1 1773.18  5928.9 1772.81  5958.6  1774.6
#Mann= 8 ,-1 , 0
  4331.7     .16       0  4558.8      .1       0    4749     .05       0
  4947.2     .16       0  4993.9     .07       0  4999.9     .16       0
    5796      .1       0  5928.9     .16       0
Bank Sta=4966.1,5048.8
XS Rating Curve= 0 ,0
Exp/Cntr=0.3,0.1

Type RM Length L Ch R = 1 ,22637   ,711,711,711
BEGIN DESCRIPTION:
MARSCHALL CREEK 43.0
END DESCRIPTION:
XS GIS Cut Line= 3
      2783486.16     10090948.58      2783064.29     10091412.12
      2782980.96     10092198.55
#Sta/Elev= 30
  4270.9 1775.53  4301.4 1771.63  4329.8 1770.33  4351.8 1768.06    4400 1765.38
  4414.2 1763.31  4442.6 1761.45    4450 1759.91  4499.4 1755.44  4605.4 1749.96
  4725.7 1746.58  4904.9 1746.52  4959.6 1743.92  4969.7 1742.57  4979.7 1740.25
  4994.6  1734.7  4997.4  1734.2  5000.6  1734.7  5040.1 1744.57  5070.2 1746.51
  5095.3 1749.83  5100.4 1752.55  5120.5 1760.27  5130.6  1763.5  5140.6 1764.82
  5254.7 1768.19  5301.5 1768.48  5378.5 1770.73  5552.9 1773.52  5688.5  1777.7
#Mann= 5 ,-1 , 0
  4270.9     .05       0  4351.8     .16       0  4994.6     .07       0
  5000.6     .16       0  5254.7      .1       0
#XS Ineff= 2 , 0
          4868.5  1747.1
Permanent Ineff=
       F       F
Bank Sta=4959.6,5040.1
XS Rating Curve= 0 ,0
Exp/Cntr=0.3,0.1

Type RM Length L Ch R = 1 ,21926   ,463,463,463
BEGIN DESCRIPTION:
MARSCHALL CREEK 41.0
END DESCRIPTION:
XS GIS Cut Line= 3
      2783538.29     10090667.31      2782803.87     10090969.41
      2782288.22     10091115.25
#Sta/Elev= 30
  4169.2 1792.38  4220.6 1784.83    4227 1784.54  4266.3 1776.41  4333.6 1773.98
  4363.6 1770.01  4462.6 1762.11  4594.8 1751.95  4618.8 1748.84  4648.1 1748.09
    4720 1742.09  4839.4 1738.65  4915.1 1740.09  4938.7  1739.3    4961 1736.83
  4989.7 1731.02  5007.5  1730.1  5010.3  1729.6  5013.5  1730.1  5026.8  1735.2
  5035.4 1736.65  5041.7 1739.32  5064.9 1743.92  5135.2 1746.97  5166.4 1744.05
  5176.4 1744.31  5181.6 1746.34  5272.6 1749.07  5340.3 1750.76  5499.2 1756.61
#Mann= 10 ,-1 , 0
  4169.2      .1       0  4220.6     .05       0  4462.6     .16       0
    4961      .1       0  5007.5     .07       0  5013.5      .1       0
  5026.8     .16       0  5064.9      .1       0  5272.6     .16       0
  5340.3      .1       0
#XS Ineff= 2 , 0
         4911.18    1740    5132         1746.77
Permanent Ineff=
       F       F
Bank Sta=4938.7,5041.7
XS Rating Curve= 0 ,0
Exp/Cntr=0.3,0.1

Type RM Length L Ch R = 1 ,21463   ,520,520,520
BEGIN DESCRIPTION:
MARSCHALL CREEK 40.0
END DESCRIPTION:
XS GIS Cut Line= 4
       2783198.8     10090375.46       2782977.7     10090540.22
      2782408.87     10090601.15      2782096.37     10090863.74
#Sta/Elev= 30
  4641.7 1763.53  4747.9 1753.69  4777.1 1751.86  4783.3 1750.49  4791.7 1750.45
  4797.9 1748.79  4812.5 1748.66  4818.7    1747  4827.1 1746.91  4833.3 1745.29
  4845.4 1744.94  4868.8 1741.79  4904.2 1739.42  4919.6 1736.87  4946.8 1730.46
  4996.8 1730.07  4999.5 1729.57  5002.8 1730.07  5037.4 1734.52  5057.5 1735.73
  5072.1    1736  5117.8 1737.14  5171.8 1737.05  5349.1 1737.61  5449.7 1739.08
  5575.2 1742.58  5669.3 1747.03  5725.3 1751.11  5863.9 1754.35  5897.7 1754.58
#Mann= 8 ,-1 , 0
  4641.7     .05       0  4845.4     .16       0  4996.8     .07       0
  5002.8     .16       0  5072.1      .1       0  5171.8     .05       0
  5575.2      .1       0  5863.9     .05       0
Bank Sta=4919.6,5057.5
XS Rating Curve= 0 ,0
Exp/Cntr=0.3,0.1

Type RM Length L Ch R = 1 ,20943   ,407,407,407
BEGIN DESCRIPTION:
MARSCHALL CREEK 39.0
END DESCRIPTION:
XS GIS Cut Line= 3
      2783272.66     10089901.69      2782658.04     10090115.24
      2782069.52     10090578.77
#Sta/Elev= 30
  4235.8 1825.84  4250.8 1822.42    4262 1815.19  4288.6 1805.85  4293.2 1802.72
  4318.9 1796.08  4412.3 1779.98  4438.1 1772.24  4474.5 1771.82  4491.8 1769.52
  4593.6 1759.49  4631.9 1753.19  4674.3 1752.05    4687 1749.35    4834 1737.87
  4875.4 1732.63    4913 1732.03  4941.9 1728.13    5003 1721.51  5005.8 1721.01
    5009 1721.51  5018.9 1724.77  5032.8 1727.94  5055.7 1733.47  5161.4  1734.7
  5163.6 1734.79  5259.8 1737.81  5456.7  1740.5  5554.5 1743.79  5635.6 1750.21
#Mann= 12 ,-1 , 0
  4235.8     .16       0  4288.6      .1       0  4491.8     .05       0
    4834     .16       0    5003     .07       0    5009     .16       0
  5018.9     .05       0  5032.8     .16       0  5161.4     .05       0
  5163.6     .16       0  5259.8     .05       0  5456.7      .1       0
#XS Ineff= 2 , 0
                          5062.9         1733.58
Permanent Ineff=
       F       F
Bank Sta=4941.9,5032.8
XS Rating Curve= 0 ,0
Exp/Cntr=0.3,0.1