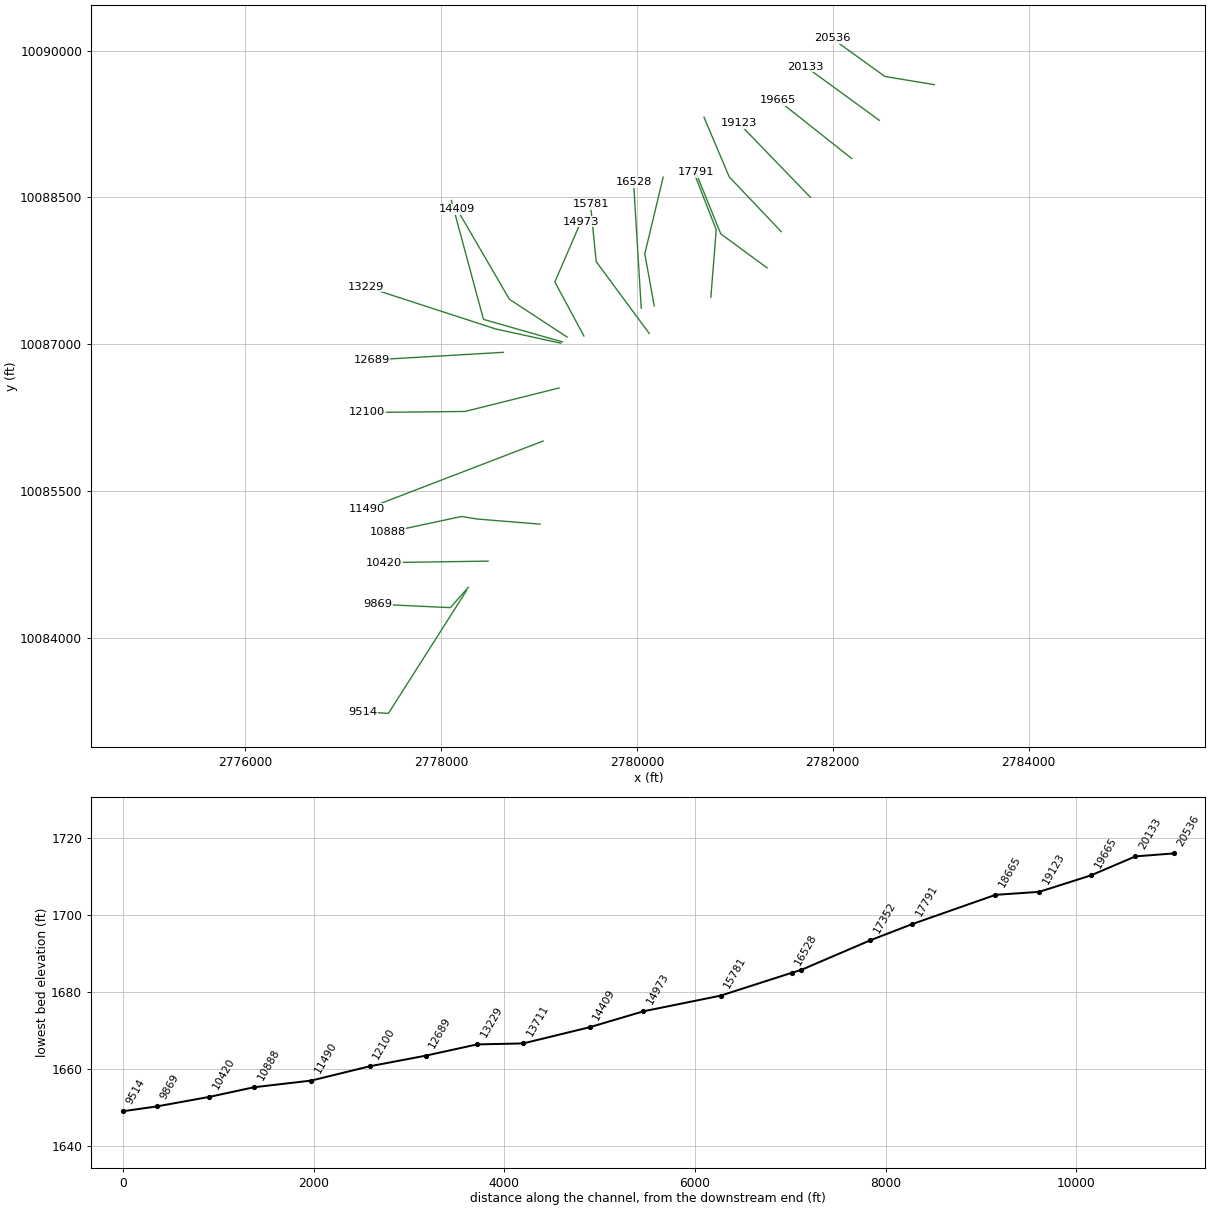
HEC-RAS study MARSCHALL CREEK.prj: MARSCHALL CREEK Base Level Engineering

--- MARSCHALL CREEK.g01 (geometry) --- (continued)

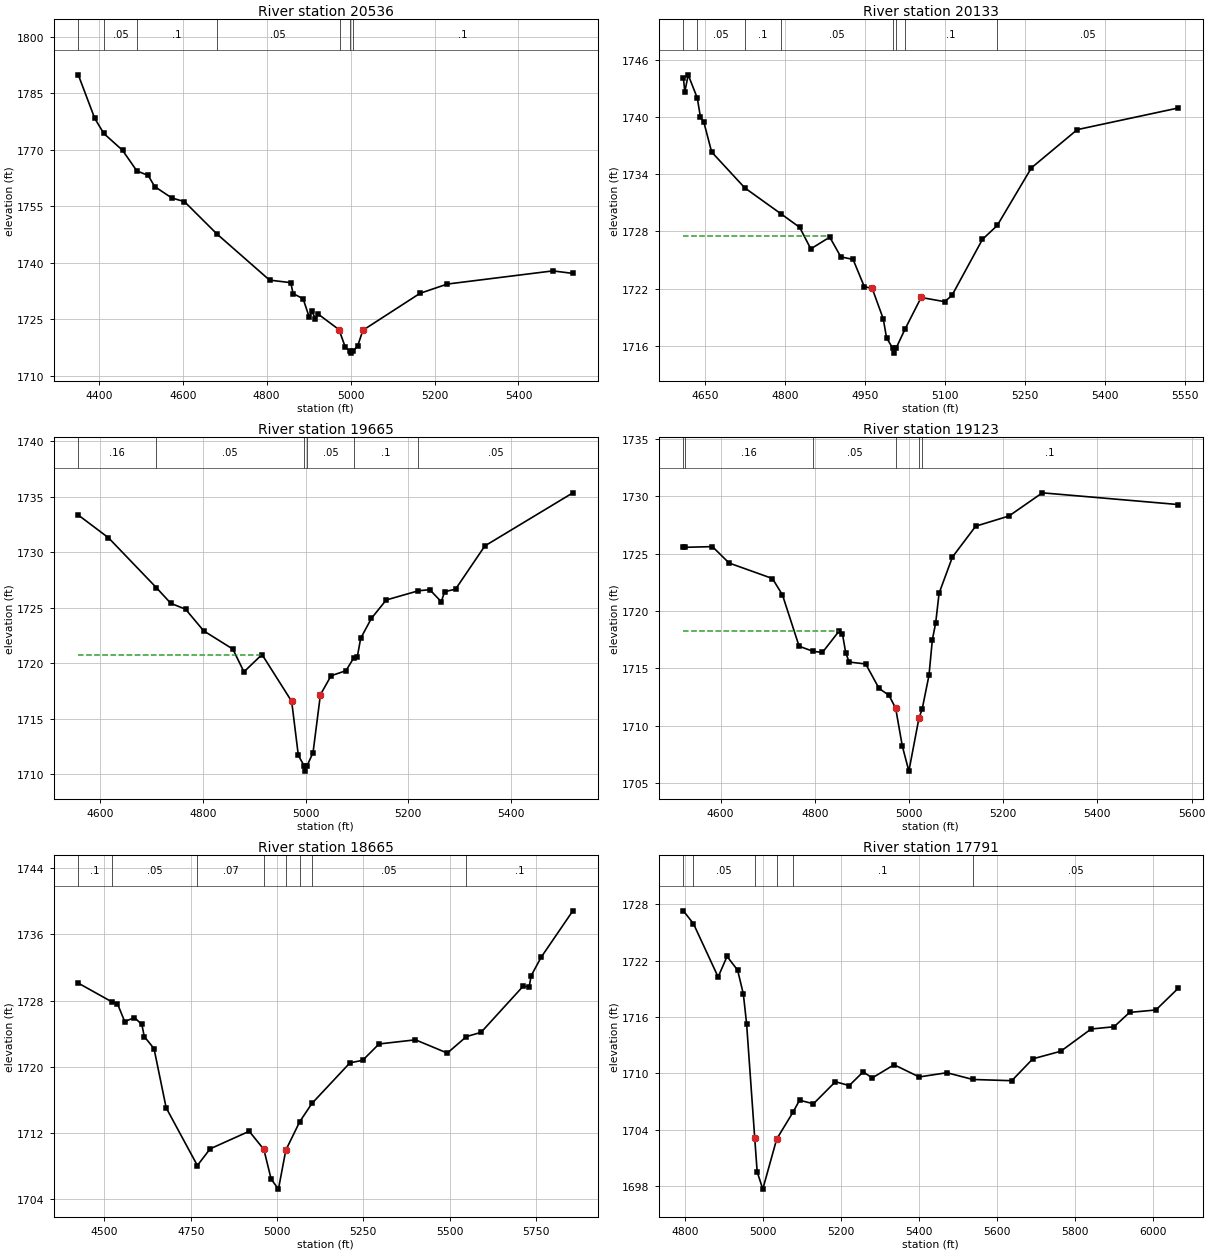
Type RM Length L Ch R = 1 ,20536   ,403,403,403
BEGIN DESCRIPTION:
MARSCHALL CREEK 38.0
END DESCRIPTION:
XS GIS Cut Line= 3
      2783038.23      10089651.7      2782533.04     10089735.04
      2781992.38     10090124.93
#Sta/Elev= 30
  4351.1 1789.96  4390.3  1778.4  4411.9 1774.38  4456.5 1769.92  4490.7 1764.43
  4517.6 1763.23  4533.3 1760.27  4573.7 1757.26  4604.2 1756.26  4681.1 1747.72
  4806.9 1735.42  4857.6 1734.74  4862.9 1731.85  4886.9 1730.47  4901.6 1725.53
  4907.8 1727.11  4916.3 1725.16  4922.5 1726.41  4972.8 1722.23  4973.6 1721.92
  4987.5 1717.55  4999.2 1716.52    5002 1716.02  5005.2 1716.52  5016.7 1717.84
  5029.3 1722.09  5165.5 1731.91  5230.5 1734.37    5482 1737.87  5529.7  1737.2
#Mann= 7 ,-1 , 0
  4351.1      .1       0  4411.9     .05       0  4490.7      .1       0
  4681.1     .05       0  4973.6      .1       0  4999.2     .07       0
  5005.2      .1       0
Bank Sta=4972.8,5029.3
XS Rating Curve= 0 ,0
Exp/Cntr=0.3,0.1

Type RM Length L Ch R = 1 ,20133   ,468,468,468
BEGIN DESCRIPTION:
MARSCHALL CREEK 37.0
END DESCRIPTION:
XS GIS Cut Line= 2
      2782475.72     10089287.14      2781725.73     10089834.01
#Sta/Elev= 30
  4608.8 1744.09  4611.5 1742.61  4617.8  1744.4  4634.9 1741.97  4640.9 1739.94
  4647.1 1739.47  4661.8 1736.32    4724 1732.56  4792.5 1729.82  4827.1 1728.42
  4847.9 1726.17  4883.5  1727.4  4904.3 1725.33  4927.2 1725.07  4948.4  1722.2
    4963 1722.05  4983.9 1718.84  4990.1 1716.85  5001.8 1715.75  5004.5 1715.25
  5007.8 1715.75    5025 1717.79    5055 1721.08    5099 1720.64  5112.8 1721.29
  5170.1 1727.17  5197.8 1728.62    5262 1734.66    5348 1738.66    5537 1740.92
#Mann= 8 ,-1 , 0
  4608.8      .1       0  4634.9     .05       0    4724      .1       0
  4792.5     .05       0  5001.8     .04       0  5007.8     .05       0
    5025      .1       0  5197.8     .05       0
#XS Ineff= 2 , 0
         4878.32 1727.52
Permanent Ineff=
       F       F
Bank Sta=4963,5055
XS Rating Curve= 0 ,0
Exp/Cntr=0.3,0.1

Type RM Length L Ch R = 1 ,19665   ,542,542,542
BEGIN DESCRIPTION:
MARSCHALL CREEK 36.0
END DESCRIPTION:
XS GIS Cut Line= 2
      2782194.48     10088896.51      2781439.27     10089495.47
#Sta/Elev= 30
  4556.7 1733.36  4615.4 1731.32  4708.9 1726.82    4737 1725.41  4765.8 1724.88
  4801.1 1722.93  4857.9 1721.29  4879.6 1719.24  4914.8  1720.8  4972.6 1716.58
  4985.6 1711.71  4996.7  1710.8  4999.5  1710.3  5002.7  1710.8  5014.2 1711.96
  5028.6 1717.18  5049.4 1718.89  5078.3 1719.34  5093.4 1720.48  5100.4 1720.57
  5107.1 1722.26  5127.9 1724.05  5156.8 1725.71  5219.6 1726.54  5241.7 1726.64
  5264.2 1725.55  5270.6 1726.46  5291.9 1726.68  5349.1 1730.58  5520.6 1735.36
#Mann= 6 ,-1 , 0
  4556.7     .16       0  4708.9     .05       0  4996.7     .04       0
  5002.7     .05       0  5093.4      .1       0  5219.6     .05       0
#XS Ineff= 2 , 0
         4913.16 1720.79
Permanent Ineff=
       F       F
Bank Sta=4972.6,5028.6
XS Rating Curve= 0 ,0
Exp/Cntr=0.3,0.1

Type RM Length L Ch R = 1 ,19123   ,458,458,458
BEGIN DESCRIPTION:
MARSCHALL CREEK 35.0
END DESCRIPTION:
XS GIS Cut Line= 2
      2781772.65     10088500.64      2781043.46     10089255.87
#Sta/Elev= 30
  4521.2 1725.54    4524 1725.54  4582.8  1725.6  4618.3 1724.17  4710.2 1722.82
  4731.5 1721.39  4766.8 1716.92  4796.6 1716.47  4816.4 1716.38  4851.7 1718.24
  4858.9 1717.97  4865.8 1716.34    4873 1715.54  4908.2 1715.37  4936.5 1713.24
  4957.6 1712.64  4971.8 1711.51  4985.9 1708.21  4999.8 1706.03  5021.4 1710.69
  5027.9 1711.41  5042.5 1714.38  5049.7  1717.5  5056.7 1718.94  5063.9 1721.53
  5092.2 1724.69  5141.6 1727.38  5212.3 1728.27  5283.1 1730.29    5571 1729.27
#Mann= 6 ,-1 , 0
  4521.2      .1       0    4524     .16       0  4796.6     .05       0
  4971.8     .04       0  5021.4     .05       0  5027.9      .1       0
#XS Ineff= 2 , 0
         4851.87 1718.26
Permanent Ineff=
       F       F
Bank Sta=4971.8,5021.4
XS Rating Curve= 0 ,0
Exp/Cntr=0.3,0.1

Type RM Length L Ch R = 1 ,18665   ,874,874,874
BEGIN DESCRIPTION:
MARSCHALL CREEK 34.0
END DESCRIPTION:
XS GIS Cut Line= 3
      2781474.75     10088149.71      2780943.52     10088709.59
      2780685.77     10089318.81
#Sta/Elev= 30
  4424.1  1730.1  4520.6 1727.86  4537.6 1727.62  4558.7 1725.46    4587 1725.94
  4608.4 1725.11  4615.3 1723.66  4643.6  1722.2  4678.8 1715.06  4769.2  1708.1
  4806.2 1710.11  4919.5 1712.23  4961.9 1710.04    4983 1706.46  5004.2 1705.25
  5025.5 1709.94  5065.8 1713.38  5101.3 1715.59  5211.3 1720.48  5248.3 1720.79
  5295.7 1722.76  5401.3 1723.26  5493.6 1721.66  5548.9 1723.65  5591.3 1724.16
  5712.7  1729.7    5731 1729.69  5736.4 1730.98  5765.6 1733.23  5857.4 1738.82
#Mann= 8 ,-1 , 0
  4424.1      .1       0  4520.6     .05       0  4769.2     .07       0
  4961.9    .035       0  5025.5     .05       0  5065.8      .1       0
  5101.3     .05       0  5548.9      .1       0
#XS Ineff= 2 , 0
          4920.9 1710.71
Permanent Ineff=
       F       F
Bank Sta=4961.9,5025.5
XS Rating Curve= 0 ,0
Exp/Cntr=0.3,0.1

Type RM Length L Ch R = 1 ,17791   ,439,439,439
BEGIN DESCRIPTION:
Mapping XS e5ffad25
END DESCRIPTION:
XS GIS Cut Line= 3
       2781330.3     10087779.97      2780857.22     10088127.19
      2780601.14     10088758.72
#Sta/Elev= 30
    4796 1727.32  4821.9 1725.94  4885.1 1720.27    4908 1722.46    4935    1721
  4949.7 1718.47  4958.1 1715.29    4979 1703.06  4985.2  1699.5  4999.6 1697.65
  5035.3 1702.99  5077.1 1705.85  5093.9 1707.13  5129.5 1706.75  5185.8  1709.1
  5221.3 1708.69  5257.2 1710.16  5279.9  1709.5  5336.3 1710.91  5400.7 1709.61
  5471.7 1710.06  5538.3 1709.34  5638.1 1709.21    5692 1711.54  5763.8 1712.35
  5841.5 1714.72  5900.4 1714.96  5940.2 1716.49  6007.6 1716.75  6064.3 1719.04
#Mann= 6 ,-1 , 0
    4796      .1       0  4821.9     .05       0    4979     .04       0
  5035.3     .05       0  5077.1      .1       0  5538.3     .05       0
#XS Ineff= 2 , 0
                         5337.66         1710.85
Permanent Ineff=
       F       F
Bank Sta=4979,5035.3
XS Rating Curve= 0 ,0
Exp/Cntr=0.3,0.1

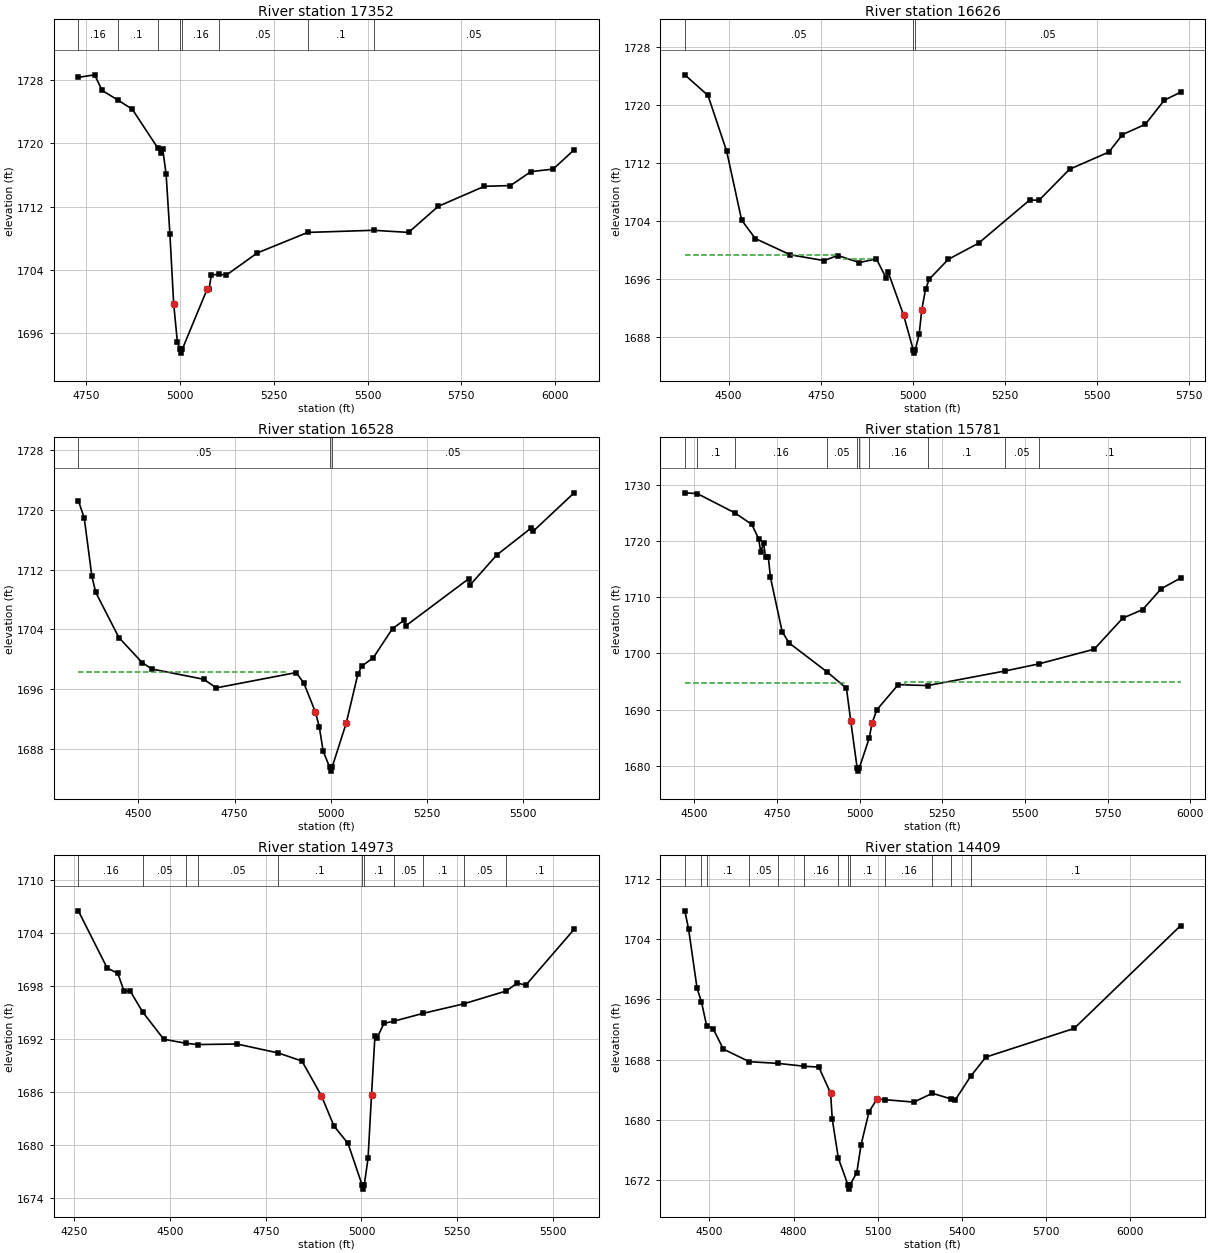
Type RM Length L Ch R = 1 ,17352   ,726,726,726
BEGIN DESCRIPTION:
MARSCHALL CREEK 32.0
END DESCRIPTION:
XS GIS Cut Line= 3
      2780756.02     10087480.46      2780810.71     10088170.52
      2780581.54     10088756.48
#Sta/Elev= 30
  4729.2 1728.35  4772.6 1728.67  4792.7 1726.69  4834.1 1725.49  4872.9 1724.32
    4941  1719.4  4949.1 1718.81  4954.1 1719.29  4963.2 1716.06  4973.2 1708.54
  4983.3 1699.68  4993.3 1694.79  5000.3 1693.94  5003.1 1693.44  5006.3 1693.94
  5072.6 1701.55  5077.6 1701.56  5083.6 1703.32  5103.6 1703.42  5123.7 1703.32
  5206.1 1706.12  5340.5 1708.72    5516 1708.99  5609.4 1708.72  5688.2 1712.02
  5811.4 1714.56  5880.9 1714.65  5935.2 1716.41  5994.9 1716.74  6050.6 1719.19
#Mann= 8 ,-1 , 0
  4729.2     .16       0  4834.1      .1       0    4941     .16       0
  5000.3     .07       0  5006.3     .16       0  5103.6     .05       0
  5340.5      .1       0    5516     .05       0
Bank Sta=4983.3,5072.6
XS Rating Curve= 0 ,0
Exp/Cntr=0.3,0.1

Type RM Length L Ch R = 1 ,16626   ,98,98,98
BEGIN DESCRIPTION:
MARSCHALL CREEK 31.0
END DESCRIPTION:
XS GIS Cut Line= 3
      2780177.89     10087391.89      2780081.54     10087923.13
      2780269.05     10088707.01
#Sta/Elev= 30
    4381 1724.19  4443.9 1721.34  4494.7 1713.63  4535.3 1704.11  4572.4 1701.56
  4667.4 1699.32  4758.9 1698.52  4796.3 1699.22  4854.8 1698.25  4901.2 1698.75
  4927.9 1696.06  4933.1 1696.91  4975.1 1690.96  5000.8 1686.23  5003.5 1685.73
  5006.8 1686.23  5017.2 1688.35  5024.3 1691.73  5034.6  1694.6  5044.9 1695.97
  5096.2 1698.69  5178.6 1700.93  5316.7 1706.87  5343.1 1706.88  5425.4 1711.14
  5532.1 1713.52  5569.1 1715.93    5631 1717.35  5682.4 1720.67  5726.9  1721.8
#Mann= 3 ,-1 , 0
    4381     .05       0  5000.8     .04       0  5006.8     .05       0
#XS Ineff= 2 ,-1
    4381 4795.77 1699.24 4810.09 4901.06 1698.75
Permanent Ineff=
       F       F
Bank Sta=4975.1,5024.3
XS Rating Curve= 0 ,0
Exp/Cntr=0.3,0.1

Type RM Length L Ch R = 1 ,16528   ,747,747,747
BEGIN DESCRIPTION:
Mapping XS 054f7527
END DESCRIPTION:
XS GIS Cut Line= 2
      2780045.08     10087368.48      2779966.96     10088654.91
#Sta/Elev= 30
  4343.8 1721.28  4359.1 1718.95  4379.1  1711.1  4389.1 1708.96  4449.2 1702.91
  4509.4 1699.56  4534.9 1698.69  4669.7 1697.31  4702.6 1696.16  4910.1 1698.21
  4930.1 1696.78  4960.2 1692.89  4970.2 1690.92  4980.2 1687.66  4997.3 1685.49
    5000 1684.99  5003.3 1685.49  5040.3 1691.46  5070.4    1698  5080.4 1699.07
  5110.5  1700.2  5160.6 1704.12  5190.5 1705.22  5195.5  1704.5  5358.1 1710.78
  5363.1 1710.01  5431.1 1713.97  5520.7 1717.59  5525.7 1717.15  5632.6 1722.32
#Mann= 3 ,-1 , 0
  4343.8     .05       0  4997.3     .04       0  5003.3     .05       0
#XS Ineff= 2 , 0
         4885.27 1698.22
Permanent Ineff=
       F       F
Bank Sta=4960.2,5040.3
XS Rating Curve= 0 ,0
Exp/Cntr=0.3,0.1

Type RM Length L Ch R = 1 ,15781   ,808,808,808
BEGIN DESCRIPTION:
MARSCHALL CREEK 30.0
END DESCRIPTION:
XS GIS Cut Line= 3
       2780126.8     10087110.03      2779585.12     10087844.41
      2779527.83     10088427.77
#Sta/Elev= 30
  4471.9 1728.53  4509.7 1728.39  4622.7 1724.98  4674.4 1722.92  4695.2 1720.35
  4701.4 1718.04  4709.9 1719.56  4716.1 1717.14  4724.5 1717.06  4730.7 1713.53
  4766.2 1703.84  4787.1 1701.84  4902.1 1696.68  4960.5 1693.79  4973.5 1687.95
    4993 1679.55  4995.7 1679.05    4999 1679.55  5029.2 1684.89  5037.7 1687.53
  5052.3 1689.95  5117.1 1694.43  5205.8 1694.26  5440.3 1696.86    5543 1698.13
  5709.3 1700.73  5795.7 1706.25    5856 1707.77  5912.1 1711.49  5970.6 1713.38
#Mann= 10 ,-1 , 0
  4471.9     .05       0  4509.7      .1       0  4622.7     .16       0
  4902.1     .05       0    4993    .035       0    4999     .05       0
  5029.2     .16       0  5205.8      .1       0  5440.3     .05       0
    5543      .1       0
#XS Ineff= 2 , 0
         4951.64 1694.74 5138.45         1694.85
Permanent Ineff=
       F       F
Bank Sta=4973.5,5037.7
XS Rating Curve= 0 ,0
Exp/Cntr=0.3,0.1

Type RM Length L Ch R = 1 ,14973   ,564,564,564
BEGIN DESCRIPTION:
MARSCHALL CREEK 29.0
END DESCRIPTION:
XS GIS Cut Line= 3
       2779460.1     10087084.04      2779163.25     10087636.08
      2779428.47     10088249.72
#Sta/Elev= 30
  4260.3 1706.48  4335.7    1700  4363.3 1699.41  4379.5 1697.42  4395.8  1697.4
  4428.6 1695.02  4483.4 1691.95  4541.6 1691.49  4572.3 1691.35  4674.9 1691.41
  4783.1 1690.39  4844.5 1689.48  4895.4 1685.55  4928.1 1682.13  4964.8 1680.16
  5001.4 1675.49  5004.1 1674.99  5007.4 1675.49  5017.2  1678.5  5026.2 1685.66
  5035.2 1692.35  5040.7  1692.1  5058.7 1693.75  5084.6 1693.99  5160.1 1694.87
  5266.6 1695.95  5377.3  1697.4  5407.5 1698.31  5429.2 1698.06  5555.6 1704.39
#Mann= 11 ,-1 , 0
  4260.3     .16       0  4428.6     .05       0  4541.6      .1       0
  4572.3     .05       0  4783.1      .1       0  5001.4     .07       0
  5007.4      .1       0  5084.6     .05       0  5160.1      .1       0
  5266.6     .05       0  5377.3      .1       0
Bank Sta=4895.4,5026.2
XS Rating Curve= 0 ,0
Exp/Cntr=0.3,0.1

Type RM Length L Ch R = 1 ,14409   ,698,698,698
BEGIN DESCRIPTION:
MARSCHALL CREEK 28.0
END DESCRIPTION:
XS GIS Cut Line= 3
      2779288.27     10087073.56      2778699.71     10087458.99
      2778163.97     10088379.62
#Sta/Elev= 30
  4411.9 1707.72  4425.5 1705.29  4455.7 1697.45  4471.3 1695.65  4489.8 1692.52
  4512.9 1692.11  4549.1 1689.41  4642.2 1687.73  4743.6 1687.51  4838.3 1687.13
  4889.8 1687.02    4932 1683.57    4938  1680.1  4959.8 1674.93  4994.4 1671.35
  4997.1 1670.85  5000.4 1671.35  5025.5 1673.04  5040.6 1676.72  5069.1  1681.1
  5097.8  1682.8  5126.3  1682.7    5229 1682.38    5295 1683.55    5362 1682.79
  5375.5  1682.6  5431.4 1685.79  5485.6 1688.34  5800.8 1692.14  6180.6 1705.76
#Mann= 13 ,-1 , 0
  4411.9     .16       0  4471.3     .05       0  4489.8      .1       0
  4642.2     .05       0  4743.6      .1       0  4838.3     .16       0
  4959.8      .1       0  4994.4     .07       0  5000.4      .1       0
  5126.3     .16       0    5295      .1       0    5362     .16       0
  5431.4      .1       0
Bank Sta=4932,5097.8
XS Rating Curve= 0 ,0
Exp/Cntr=0.3,0.1

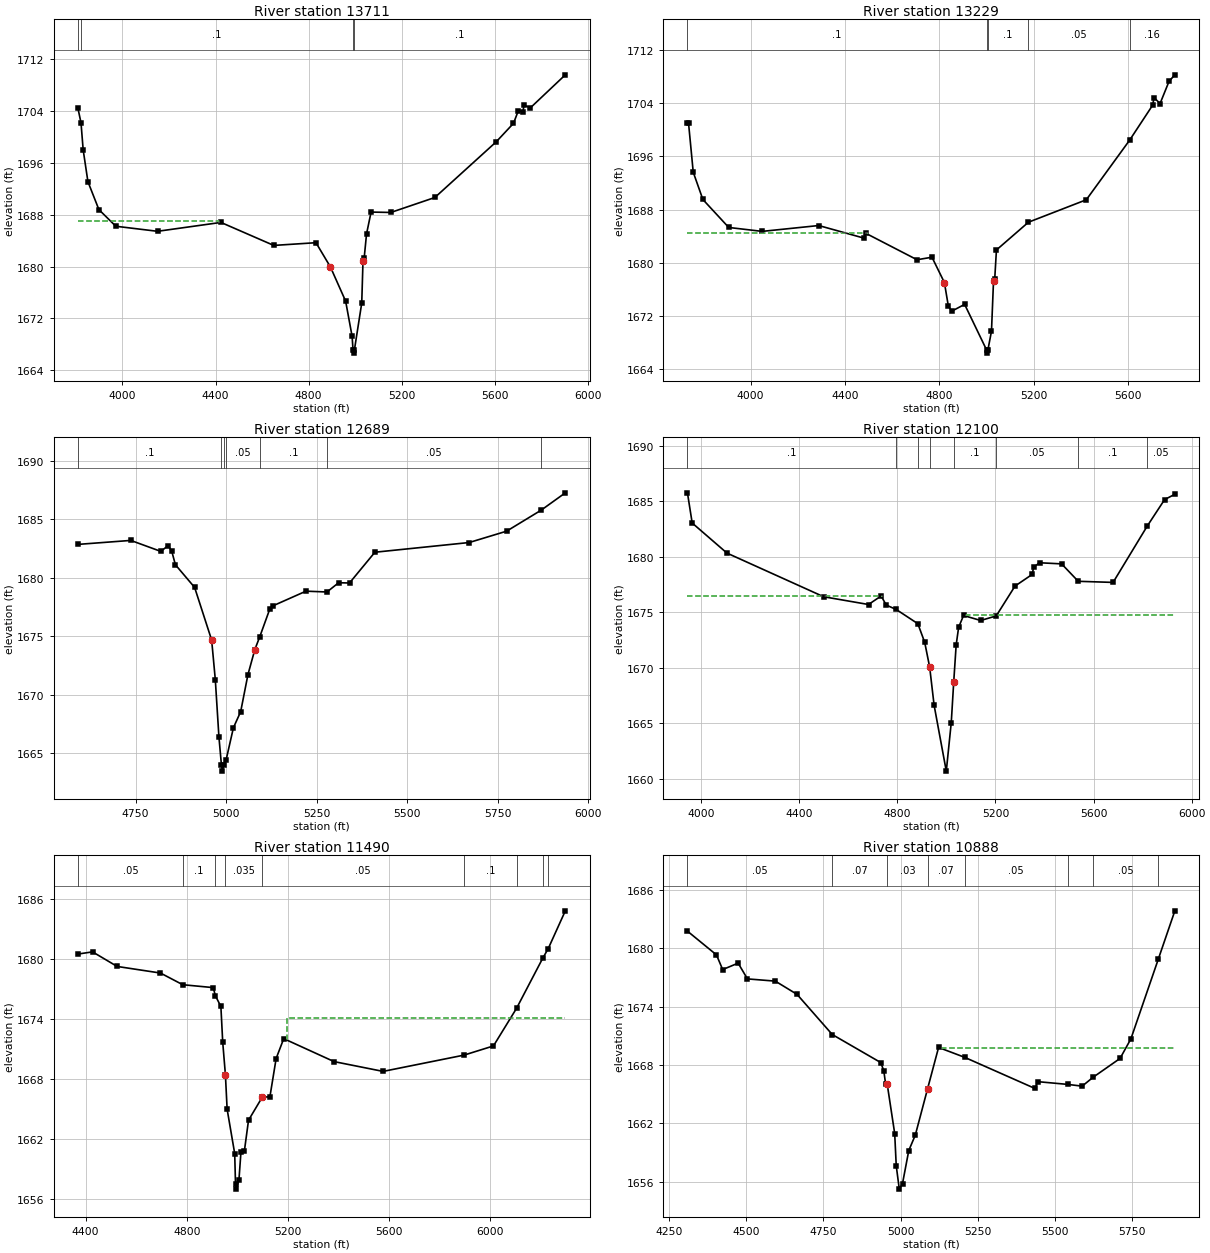
Type RM Length L Ch R = 1 ,13711   ,482,482,482
BEGIN DESCRIPTION:
MARSCHALL CREEK 27.0
END DESCRIPTION:
XS GIS Cut Line= 3
      2779239.77     10087023.83      2778434.67     10087253.86
      2778107.03     10088468.95
#Sta/Elev= 30
  3808.4 1704.47  3821.7  1702.2    3831 1698.03  3851.4 1693.12  3898.6  1688.8
  3971.4 1686.23  4150.8 1685.45  4423.4 1686.82  4650.6 1683.27    4832 1683.69
  4894.2 1679.94  4959.6 1674.66  4987.4 1669.23  4991.3 1667.14    4994 1666.64
  4997.3 1667.14  5028.8 1674.37  5034.2 1680.83  5039.4 1681.37  5049.5 1685.06
    5069 1688.42    5154 1688.36  5343.2 1690.67  5607.1 1699.27  5681.3 1702.12
    5702 1704.06  5721.7 1703.93  5726.9 1704.93  5753.8 1704.51  5904.2 1709.61
#Mann= 4 ,-1 , 0
  3808.4     .16       0  3821.7      .1       0  4991.3     .07       0
  4997.3      .1       0
#XS Ineff= 2 , 0
         4415.19 1687.02
Permanent Ineff=
       F       F
Bank Sta=4894.2,5034.2
XS Rating Curve= 0 ,0
Exp/Cntr=0.3,0.1

Type RM Length L Ch R = 1 ,13229   ,540,540,540
BEGIN DESCRIPTION:
MARSCHALL CREEK 26.0
END DESCRIPTION:
XS GIS Cut Line= 3
      2779222.46      10087010.8      2778558.37     10087156.21
      2777238.89      10087585.9
#Sta/Elev= 30
    3732 1701.05  3736.6 1701.05  3756.6 1693.63  3797.5 1689.52  3907.2 1685.31
    4049 1684.72  4288.9  1685.6  4482.3 1683.69  4487.6 1684.45  4705.8 1680.45
  4769.3 1680.83  4821.9 1677.02  4838.7 1673.47  4853.4 1672.71  4907.8 1673.73
  5000.6 1666.89  5003.3 1666.39  5006.6 1666.89  5021.7  1669.7  5030.3 1677.25
  5035.5  1677.6  5042.7 1681.92  5178.4  1686.1  5423.9 1689.48  5607.6 1698.45
  5705.3 1703.72  5711.2 1704.85  5736.8 1703.97    5775 1707.32  5799.5 1708.29
#Mann= 5 ,-1 , 0
    3732      .1       0  5000.6     .07       0  5006.6      .1       0
  5178.4     .05       0  5607.6     .16       0
#XS Ineff= 2 , 0
         4497.05 1684.49
Permanent Ineff=
       F       F
Bank Sta=4821.9,5030.3
XS Rating Curve= 0 ,0
Exp/Cntr=0.3,0.1

Type RM Length L Ch R = 1 ,12689   ,589,589,589
BEGIN DESCRIPTION:
MARSCHALL CREEK 25.0
END DESCRIPTION:
XS GIS Cut Line= 2
      2778637.18     10086917.33      2777293.45      10086839.2
#Sta/Elev= 30
  4590.7 1682.85  4736.7 1683.19  4819.8 1682.25  4839.8 1682.75  4849.9 1682.26
  4859.9 1681.11    4913 1679.17    4960 1674.67  4970.1 1671.29  4980.1 1666.39
  4987.1 1663.96  4989.8 1663.46  4993.1 1663.96  5000.1 1664.44  5020.1 1667.17
  5040.2 1668.55  5060.2 1671.71  5079.3 1673.86  5093.1 1674.97  5120.3  1677.3
  5130.3 1677.61  5220.5 1678.85  5278.5 1678.78  5310.6 1679.57  5340.7 1679.55
  5410.8 1682.18  5671.2 1683.01  5774.5 1683.98  5870.1 1685.78  5936.7 1687.26
#Mann= 7 ,-1 , 0
  4590.7      .1       0  4987.1     .07       0  4993.1      .1       0
  5000.1     .05       0  5093.1      .1       0  5278.5     .05       0
  5870.1      .1       0
#XS Ineff= 2 , 0
         4839.03 1682.69
Permanent Ineff=
       F       F
Bank Sta=4960,5079.3
XS Rating Curve= 0 ,0
Exp/Cntr=0.3,0.1

Type RM Length L Ch R = 1 ,12100   ,610,610,610
BEGIN DESCRIPTION:
MARSCHALL CREEK 24.0
END DESCRIPTION:
XS GIS Cut Line= 3
      2779204.96     10086552.75      2778246.58     10086313.16
      2777246.61     10086302.74
#Sta/Elev= 30
  3943.6 1685.76    3963 1683.04  4104.9 1680.33    4499  1676.4  4682.1  1675.7
  4733.7 1676.47  4754.3 1675.65  4795.3 1675.25  4883.3 1673.97  4911.3 1672.29
  4931.5 1670.06  4949.6 1666.63  4999.3 1660.69  5019.6 1665.07  5029.6 1668.72
  5039.6 1672.06  5049.6 1673.64  5069.6 1674.71  5139.6 1674.26  5202.9 1674.67
  5279.6 1677.36  5349.6 1678.41  5355.6 1679.06  5379.6 1679.46  5469.6 1679.36
  5537.5 1677.79  5679.6 1677.69    5819 1682.77  5889.6 1685.15  5931.5 1685.63
#Mann= 8 ,-1 , 0
  3943.6      .1       0  4795.3     .16       0  4883.3      .1       0
  4931.5     .07       0  5029.6      .1       0  5202.9     .05       0
  5537.5      .1       0    5819     .05       0
#XS Ineff= 2 , 0
         4736.08 1676.46 5081.53         1674.77
Permanent Ineff=
       F       F
Bank Sta=4931.5,5029.6
XS Rating Curve= 0 ,0
Exp/Cntr=0.3,0.1

Type RM Length L Ch R = 1 ,11490   ,602,602,602
BEGIN DESCRIPTION:
MARSCHALL CREEK 23.0
END DESCRIPTION:
XS GIS Cut Line= 2
      2779043.43     10086011.07      2777242.87     10085318.94
#Sta/Elev= 30
  4369.5 1680.53  4427.4 1680.75  4524.8 1679.29  4696.2 1678.63  4784.4 1677.46
  4905.3 1677.17  4913.1 1676.38  4935.3 1675.28  4942.6  1671.7  4953.3 1668.42
    4960    1665    4990 1660.55  4993.2 1657.49  4995.9 1656.99  5006.9 1657.94
  5014.6 1660.66  5028.3 1660.81  5044.7 1663.89  5099.3 1666.21  5129.3 1666.23
    5154 1670.07    5184 1672.06  5383.3 1669.76  5577.3 1668.78  5897.5 1670.41
    6014 1671.33  6105.5  1675.1  6209.4 1680.13  6230.5 1681.06  6298.5 1684.86
#Mann= 9 ,-1 , 0
  4369.5     .05       0  4784.4      .1       0  4913.1     .05       0
  4953.3    .035       0  5099.3     .05       0  5897.5      .1       0
  6105.5     .05       0  6209.4      .1       0  6230.5     .05       0
#XS Ineff= 2 , 0
                         5198.43         1674.08
Permanent Ineff=
       F       F
Bank Sta=4953.3,5099.3
XS Rating Curve= 0 ,0
Exp/Cntr=0.3,0.1

Type RM Length L Ch R = 1 ,10888   ,468,468,468
BEGIN DESCRIPTION:
MARSCHALL CREEK 21.0
END DESCRIPTION:
XS GIS Cut Line= 4
      2779012.16     10085162.12      2778371.58      10085214.2
      2778210.12     10085240.24      2777454.93     10085078.79
#Sta/Elev= 30
  4309.4 1681.78  4403.4 1679.34  4423.5 1677.83  4473.6 1678.49  4503.7 1676.87
    4594 1676.64  4664.3 1675.28  4778.4 1671.15  4935.2 1668.27  4945.2 1667.44
  4951.1 1666.08  4956.2 1666.08  4980.6 1660.97  4985.6 1657.65  4995.5 1655.25
  5005.9 1655.82  5026.2 1659.22  5047.4 1660.81  5086.9 1665.55  5122.7 1669.82
  5206.7 1668.81  5434.3 1665.61  5444.6  1666.3  5540.9 1666.02  5587.7 1665.84
    5623 1666.75  5710.4 1668.69  5745.5  1670.7  5834.5 1678.92  5887.9 1683.87
#Mann= 8 ,-1 , 0
  4309.4     .05       0  4778.4     .07       0  4956.2     .03       0
  5086.9     .07       0  5206.7     .05       0  5540.9      .1       0
    5623     .05       0  5834.5      .1       0
#XS Ineff= 2 , 0
                         5134.77         1669.77
Permanent Ineff=
       F       F
Bank Sta=4956.2,5086.9
XS Rating Curve= 0 ,0
Exp/Cntr=0.3,0.1

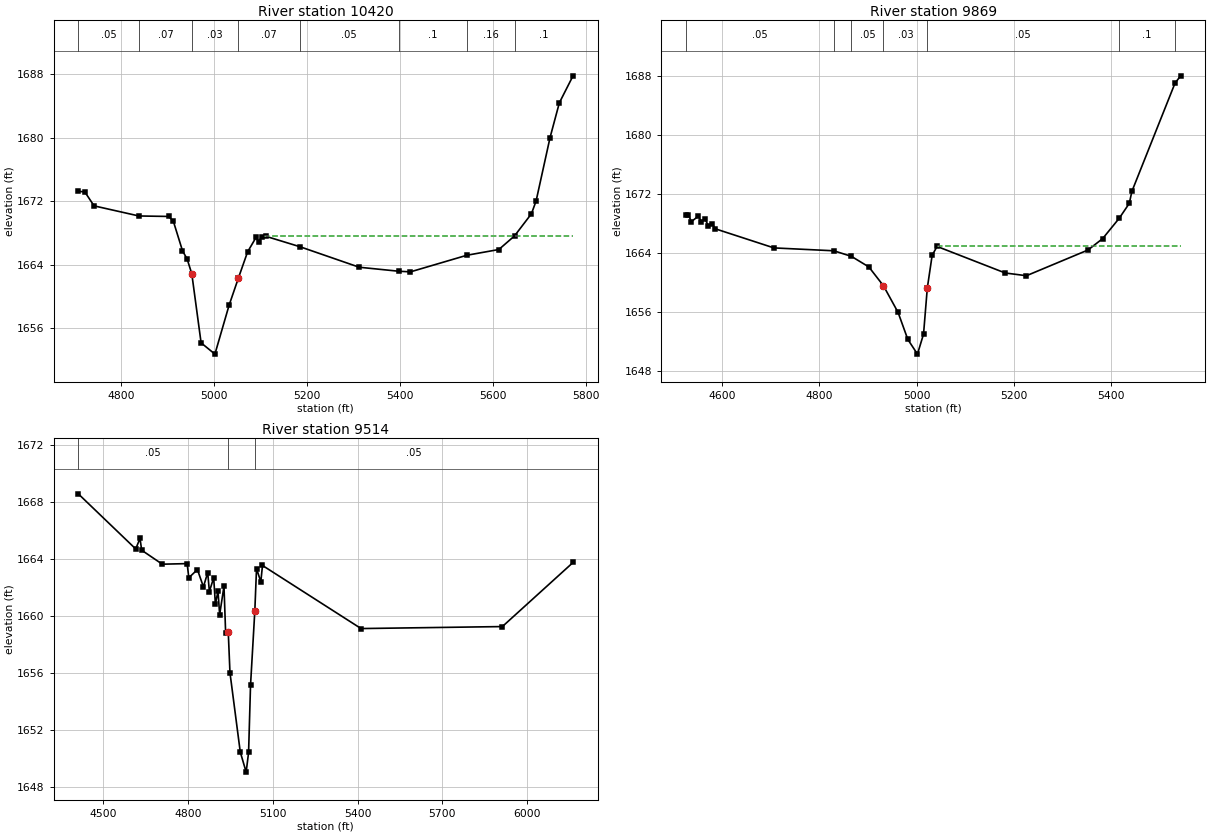
Type RM Length L Ch R = 1 ,10420   ,551,551,551
BEGIN DESCRIPTION:
MARSCHALL CREEK 20.0
END DESCRIPTION:
XS GIS Cut Line= 2
      2778482.42     10084784.24      2777419.03     10084769.05
#Sta/Elev= 30
  4707.9 1673.23  4721.9 1673.16  4741.9  1671.4  4838.2 1670.13  4901.9 1670.07
  4911.9 1669.53  4931.9 1665.76  4941.9 1664.71  4951.9 1662.86  4971.9 1654.17
  5001.6 1652.75  5031.9 1658.87  5051.9 1662.29  5071.9 1665.62  5090.3 1667.46
  5095.3 1666.84  5101.9 1667.52  5111.9 1667.56  5184.4 1666.26  5311.9 1663.68
  5396.3 1663.18  5421.9  1663.1  5543.3 1665.19  5611.9 1665.91  5645.6 1667.62
    5682 1670.41    5692 1672.02    5722    1680    5742 1684.37  5771.4 1687.76
#Mann= 8 ,-1 , 0
  4707.9     .05       0  4838.2     .07       0  4951.9     .03       0
  5051.9     .07       0  5184.4     .05       0  5396.3      .1       0
  5543.3     .16       0  5645.6      .1       0
#XS Ineff= 2 , 0
                         5108.45         1667.67
Permanent Ineff=
       F       F
Bank Sta=4951.9,5051.9
XS Rating Curve= 0 ,0
Exp/Cntr=0.3,0.1

Type RM Length L Ch R = 1 ,9869    ,355,355,355
BEGIN DESCRIPTION:
MARSCHALL CREEK 19.0
END DESCRIPTION:
XS GIS Cut Line= 3
      2778280.57      10084517.3      2778096.13     10084308.98
      2777358.28     10084343.71
#Sta/Elev= 30
  4525.7 1669.16    4531 1669.16  4536.8 1668.23    4551 1668.96  4557.7 1668.23
  4565.2 1668.56  4571.9 1667.67  4579.4 1667.96  4586.1 1667.26  4706.6 1664.67
  4829.6 1664.28  4865.7 1663.53  4901.7 1662.09  4931.7 1659.54  4961.8 1655.92
  4981.8 1652.26  5001.6 1650.27  5014.1 1652.99  5021.8 1659.21  5031.8 1663.67
  5041.9 1664.87    5182 1661.27  5225.6  1660.9  5352.2 1664.39  5382.2 1665.93
  5416.3 1668.69    5437 1670.71  5442.3 1672.33  5531.1 1687.03  5542.6    1688
#Mann= 7 ,-1 , 0
  4525.7     .05       0  4829.6      .1       0  4865.7     .05       0
  4931.7     .03       0  5021.8     .05       0  5416.3      .1       0
  5531.1     .05       0
#XS Ineff= 2 , 0
                         5043.61         1664.94
Permanent Ineff=
       F       F
Bank Sta=4931.7,5021.8
XS Rating Curve= 0 ,0
Exp/Cntr=0.3,0.1

Type RM Length L Ch R = 1 ,9514    ,103,103,103
BEGIN DESCRIPTION:
MARSCHALL CREEK 17.0
END DESCRIPTION:
XS GIS Cut Line= 3
      2778261.06     10084482.59       2777464.3     10083228.93
      2777198.68     10083244.55
#Sta/Elev= 30
  4411.2 1668.56  4614.5 1664.69  4629.7 1665.43  4635.7  1664.6  4708.5 1663.62
  4796.6 1663.66  4802.5 1662.67    4833 1663.24  4854.2 1662.03  4869.4 1663.03
  4875.3  1661.7  4890.6 1662.67  4896.5 1660.82  4905.8 1661.72  4911.7 1660.07
    4927 1662.08  4932.9 1658.77  4942.2 1658.83  4948.2    1656  4984.6 1650.44
  5005.5 1649.02  5014.1  1650.4    5021 1655.13  5036.2 1660.35  5042.2 1663.31
  5057.4 1662.38  5063.3 1663.53  5412.3  1659.1  5912.5 1659.24  6162.7 1663.74
#Mann= 3 , 0 , 0
  4411.2     .05       0  4942.2     .03       0  5036.2     .05       0
#XS Ineff= 2 , 0
                         5042.95         1663.25
Permanent Ineff=
       F       F
Bank Sta=4942.2,5036.2
XS Rating Curve= 0 ,0
Exp/Cntr=0.3,0.1