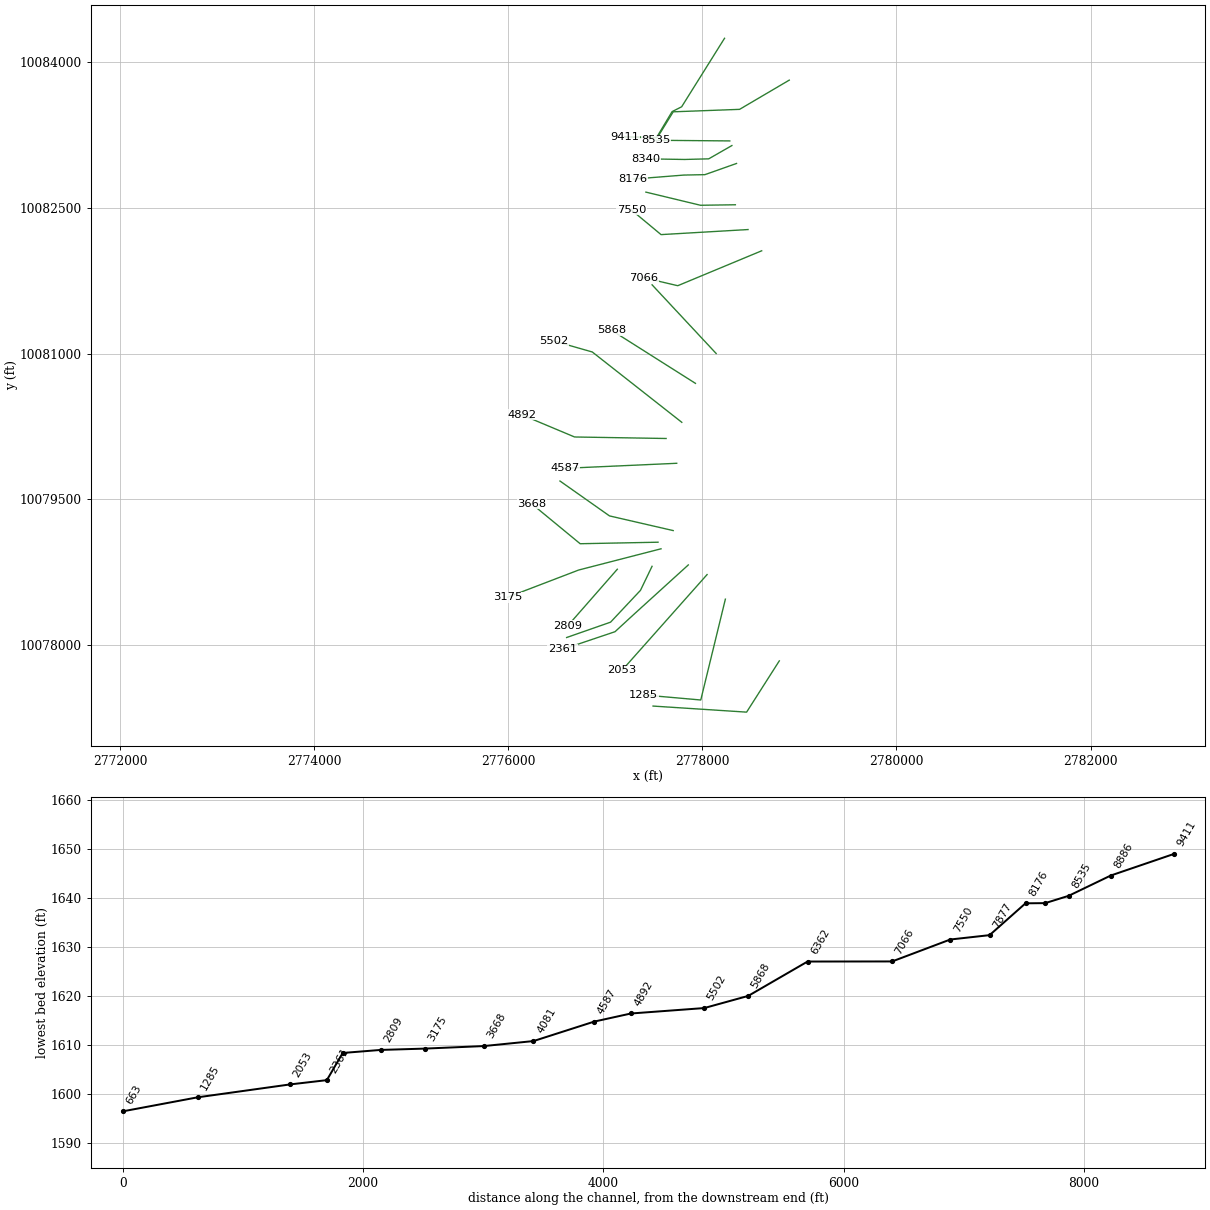
HEC-RAS study MARSCHALL CREEK.prj: MARSCHALL CREEK Base Level Engineering

--- MARSCHALL CREEK.g01 (geometry) --- (continued)

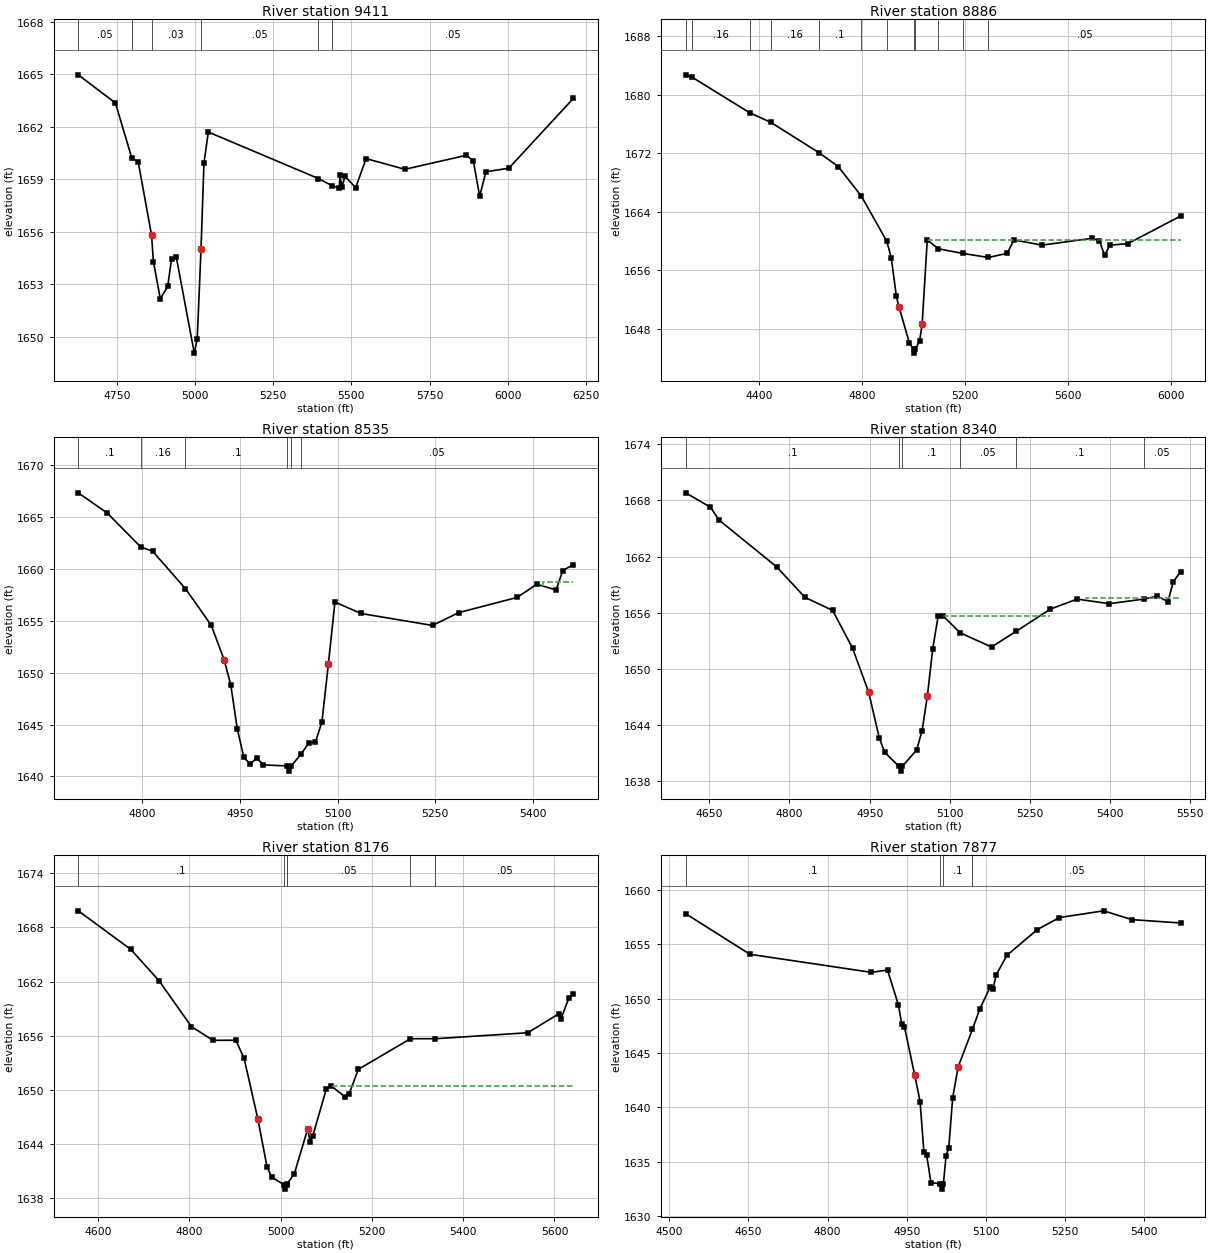
Type RM Length L Ch R = 1 ,9411    ,525,525,525
BEGIN DESCRIPTION:
MARSCHALL CREEK 18.0
END DESCRIPTION:
XS GIS Cut Line= 5
      2778228.65     10084245.85      2777787.03     10083540.73
      2777688.26     10083490.65      2777529.51     10083225.65
      2777199.27     10083233.98
#Sta/Elev= 30
  4627.2 1664.97  4745.9 1663.36  4798.4  1660.2  4818.5 1660.01  4861.4  1655.8
  4867.3 1654.29  4889.3 1652.17  4912.9 1652.87  4925.1 1654.43  4940.4 1654.55
  4997.9 1649.06  5007.3 1649.88  5019.4 1655.01  5028.8 1659.92  5042.7  1661.7
  5394.7 1659.04  5437.6 1658.64  5461.2 1658.49  5463.4 1659.23    5469 1658.57
    5480 1659.16  5513.7 1658.52  5546.9 1660.18    5671 1659.57  5867.4 1660.37
  5889.9 1660.03  5909.9 1658.02  5929.9 1659.43    6003 1659.63  6209.2 1663.62
#Mann= 6 ,-1 , 0
  4627.2     .05       0  4798.4      .1       0  4861.4     .03       0
  5019.4     .05       0  5394.7      .1       0  5437.6     .05       0
#XS Ineff= 2 , 0
                         5043.07         1661.69
Permanent Ineff=
       F       F
Bank Sta=4861.4,5019.4
XS Rating Curve= 0 ,0
Exp/Cntr=0.3,0.1

Type RM Length L Ch R = 1 ,8886    ,351,351,351
BEGIN DESCRIPTION:
Mapping XS 41d8265b
END DESCRIPTION:
XS GIS Cut Line= 5
      2778895.27     10083814.86      2778383.57     10083514.09
      2777699.93     10083488.79      2777535.91     10083222.42
      2777203.03     10083227.62
#Sta/Elev= 30
  4114.6 1682.74  4139.9 1682.41  4363.2 1677.56  4445.3 1676.24  4632.7 1672.09
  4708.2 1670.17  4797.8 1666.12  4896.4 1659.95  4913.4 1657.74  4933.4 1652.44
  4943.4    1651  4983.4 1646.11  5000.5 1645.16  5003.2 1644.66  5006.5 1645.16
  5023.5 1646.32  5033.5 1648.58  5053.5 1660.16    5096 1658.94  5192.2  1658.3
  5290.8 1657.75  5363.7 1658.31  5390.5 1660.15    5499 1659.44  5694.2 1660.37
  5722.5 1660.03  5742.5 1658.02  5762.5 1659.43  5832.5 1659.64    6038 1663.42
#Mann= 12 ,-1 , 0
  4114.6      .1       0  4139.9     .16       0  4363.2      .1       0
  4445.3     .16       0  4632.7      .1       0  4797.8     .16       0
  4896.4      .1       0  5000.5     .07       0  5006.5      .1       0
    5096     .05       0  5192.2      .1       0  5290.8     .05       0
#XS Ineff= 2 , 0
                         5056.82         1660.13
Permanent Ineff=
       F       F
Bank Sta=4943.4,5033.5
XS Rating Curve= 0 ,0
Exp/Cntr=0.3,0.1

Type RM Length L Ch R = 1 ,8535    ,195,195,195
BEGIN DESCRIPTION:
MARSCHALL CREEK 16.0
END DESCRIPTION:
XS GIS Cut Line= 2
      2778282.79     10083189.19      2777522.21     10083195.69
#Sta/Elev= 30
  4701.7 1667.31    4746 1665.37  4797.6  1662.1    4816 1661.68  4866.4 1658.08
    4906 1654.55    4926 1651.19    4936 1648.81    4946 1644.58    4956 1641.83
    4966 1641.19    4976 1641.78    4986 1641.11    5023 1641.01  5025.8 1640.51
    5029 1641.01  5044.2 1642.18    5056 1643.23    5066 1643.29    5076 1645.24
    5086 1650.84    5096 1656.79    5136 1655.69    5246 1654.54    5286 1655.77
    5376 1657.24    5406  1658.5    5436 1657.96    5446 1659.83  5462.3 1660.39
#Mann= 6 ,-1 , 0
  4701.7      .1       0  4797.6     .16       0  4866.4      .1       0
    5023     .07       0    5029      .1       0  5044.2     .05       0
#XS Ineff= 2 ,-1
 5097.71  5364.9  1656.7 5415.32  5462.3 1658.71
Permanent Ineff=
       F       F
Bank Sta=4926,5086
XS Rating Curve= 0 ,0
Exp/Cntr=0.3,0.1

Type RM Length L Ch R = 1 ,8340    ,164,164,164
BEGIN DESCRIPTION:
Mapping XS 592d2caf
END DESCRIPTION:
XS GIS Cut Line= 4
      2778304.45     10083141.44      2778065.75     10083004.73
      2777816.18     10082998.22      2777414.66     10083004.73
#Sta/Elev= 30
  4605.7 1668.82  4652.2 1667.28    4668 1665.91  4775.9  1660.9  4829.1 1657.62
  4880.8 1656.23  4918.1 1652.18  4948.1 1647.49  4968.1 1642.57  4978.1 1641.03
  5005.1 1639.52  5007.9 1639.02  5011.1 1639.52  5038.1  1641.3  5048.1 1643.34
  5058.1 1647.08  5068.1 1652.14  5078.1 1655.58  5088.1  1655.6  5119.7 1653.82
  5178.1 1652.31  5223.8 1653.98  5288.2 1656.37  5338.2 1657.44  5398.2 1656.95
    5463 1657.44  5488.2 1657.75  5508.2 1657.18  5518.2 1659.29    5532 1660.39
#Mann= 6 ,-1 , 0
  4605.7      .1       0  5005.1     .07       0  5011.1      .1       0
  5119.7     .05       0  5223.8      .1       0    5463     .05       0
#XS Ineff= 2 ,-1
 5086.58 5287.62 1655.64 5354.42    5532 1657.55
Permanent Ineff=
       F       F
Bank Sta=4948.1,5058.1
XS Rating Curve= 0 ,0
Exp/Cntr=0.3,0.1

Type RM Length L Ch R = 1 ,8176    ,299,299,299
BEGIN DESCRIPTION:
MARSCHALL CREEK 15.0
END DESCRIPTION:
XS GIS Cut Line= 4
      2778352.18     10082956.98      2778026.69     10082841.97
      2777809.67     10082837.63      2777288.88      10082796.4
#Sta/Elev= 30
  4556.6 1669.84  4671.7 1665.56  4733.5 1662.09  4804.5    1657  4851.9 1655.48
  4901.8 1655.49    4920 1653.47    4950 1646.76  4970.1 1641.48  4980.1 1640.32
  5007.1 1639.48  5009.8 1638.98  5013.1 1639.48  5013.6 1639.51  5030.1 1640.71
  5059.4 1645.67  5064.4 1644.23  5070.1 1644.82  5100.1 1650.09  5110.1 1650.46
  5140.1 1649.24  5150.2 1649.56  5170.2 1652.26  5284.4 1655.66  5339.3 1655.66
  5541.4 1656.32  5609.2 1658.41  5614.2 1657.84  5631.7  1660.2  5641.3  1660.6
#Mann= 6 ,-1 , 0
  4556.6      .1       0  5007.1     .07       0  5013.1      .1       0
  5013.6     .05       0  5284.4      .1       0  5339.3     .05       0
#XS Ineff= 2 , 0
                         5111.46         1650.47
Permanent Ineff=
       F       F
Bank Sta=4950,5059.4
XS Rating Curve= 0 ,0
Exp/Cntr=0.3,0.1

Type RM Length L Ch R = 1 ,7877    ,327,327,327
BEGIN DESCRIPTION:
Mapping XS 5da7a32a
END DESCRIPTION:
XS GIS Cut Line= 3
      2778340.28     10082531.91      2777980.96      10082526.7
      2777418.49     10082662.11
#Sta/Elev= 30
  4531.1 1657.83  4652.9 1654.09    4883 1652.43  4913.6 1652.64  4934.2 1649.43
  4940.6 1647.65  4945.7  1647.4    4965    1643  4975.3 1640.54  4982.5 1635.91
  4987.7 1635.62  4995.9 1633.08  5013.5 1632.98  5016.2 1632.48  5019.5 1632.98
  5024.5 1635.56  5029.6 1636.25    5037 1640.88  5047.3  1643.7  5074.4 1647.18
  5088.5 1649.07  5108.3 1651.09  5113.5 1650.89  5119.3 1652.18  5139.9    1654
  5197.3 1656.36  5239.3 1657.47  5323.1 1658.09  5376.5 1657.28    5469 1656.97
#Mann= 4 ,-1 , 0
  4531.1      .1       0  5013.5     .07       0  5019.5      .1       0
  5074.4     .05       0
Bank Sta=4965,5047.3
XS Rating Curve= 0 ,0
Exp/Cntr=0.3,0.1

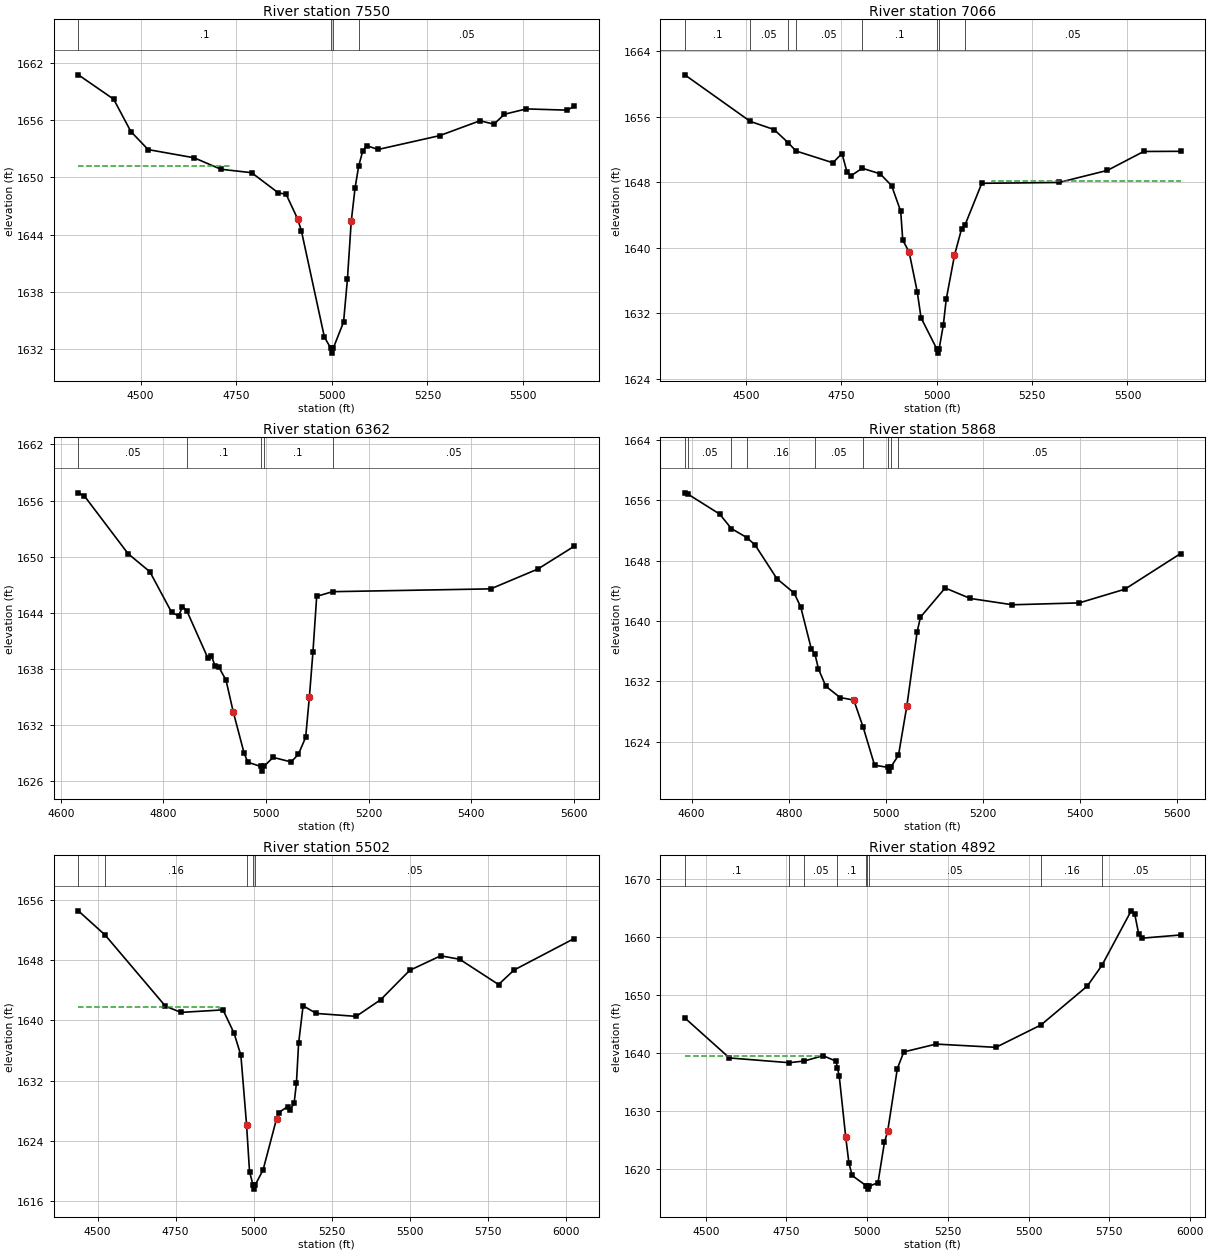
Type RM Length L Ch R = 1 ,7550    ,484,484,484
BEGIN DESCRIPTION:
MARSCHALL CREEK 14.0
END DESCRIPTION:
XS GIS Cut Line= 3
      2778470.57      10082276.7      2777574.71     10082224.62
      2777268.05      10082479.3
#Sta/Elev= 30
  4337.5 1660.74  4429.8 1658.19  4474.8  1654.8  4519.9 1652.91  4640.1 1652.05
  4710.2 1650.85  4790.4 1650.49  4860.5 1648.37  4880.5 1648.24  4910.6 1645.66
  4920.6 1644.39  4980.7 1633.26  4997.7 1632.09  5000.5 1631.59  5003.7 1632.09
  5030.8 1634.85  5040.8 1639.31  5050.8 1645.38  5060.8 1648.88  5070.2 1651.17
  5080.9 1652.76  5090.9 1653.33  5120.9 1652.92  5281.9 1654.37  5387.3 1655.93
  5423.8 1655.57  5451.1 1656.61  5508.4 1657.17  5615.2 1657.04  5633.5 1657.44
#Mann= 4 ,-1 , 0
  4337.5      .1       0  4997.7     .07       0  5003.7      .1       0
  5070.2     .05       0
#XS Ineff= 2 , 0
         4730.19 1651.16
Permanent Ineff=
       F       F
Bank Sta=4910.6,5050.8
XS Rating Curve= 0 ,0
Exp/Cntr=0.3,0.1

Type RM Length L Ch R = 1 ,7066    ,704,704,704
BEGIN DESCRIPTION:
MARSCHALL CREEK 13.0
END DESCRIPTION:
XS GIS Cut Line= 3
       2778611.2     10082057.97      2777746.58     10081698.58
      2777392.97     10081781.78
#Sta/Elev= 30
  4339.7 1661.13  4511.5 1655.43  4573.8 1654.44  4610.1 1652.85  4631.2 1651.82
  4727.8 1650.38  4751.7 1651.51    4765 1649.22  4775.5  1648.8  4804.8 1649.71
  4851.6 1649.03  4881.8 1647.58  4905.6 1644.45    4911 1640.91  4927.5  1639.5
  4949.1 1634.58  4958.8 1631.44  5000.3 1627.61    5003 1627.11  5006.3 1627.61
  5017.3 1630.54  5024.9 1633.68  5046.6 1639.07    5065 1642.27    5074 1642.75
  5118.1 1647.87  5320.4 1647.97  5447.5 1649.45  5542.5 1651.76  5639.3 1651.78
#Mann= 8 ,-1 , 0
  4339.7      .1       0  4511.5     .05       0  4610.1      .1       0
  4631.2     .05       0  4804.8      .1       0  5000.3     .07       0
  5006.3      .1       0    5074     .05       0
#XS Ineff= 2 , 0
         4827.64 1649.19 5144.07         1648.15
Permanent Ineff=
       F       F
Bank Sta=4927.5,5046.6
XS Rating Curve= 0 ,0
Exp/Cntr=0.3,0.1

Type RM Length L Ch R = 1 ,6362    ,494,494,494
BEGIN DESCRIPTION:
MARSCHALL CREEK 11.0
END DESCRIPTION:
XS GIS Cut Line= 2
      2778142.39     10081000.68      2777482.34     10081707.51
#Sta/Elev= 30
    4634 1656.82    4646 1656.47    4731 1650.32  4773.5 1648.39    4816 1644.05
  4829.7 1643.67  4837.1 1644.67  4845.5 1644.23  4886.4  1639.2  4893.7 1639.39
  4900.6 1638.34  4907.9 1638.22  4922.1  1636.8  4936.2 1633.41  4957.2 1629.04
  4964.6 1628.04  4989.9 1627.59  4992.6 1627.09  4995.9 1627.59  5013.9 1628.56
  5049.1 1628.07  5063.2 1628.89  5077.4  1630.7  5084.7 1635.04  5091.6 1639.81
  5098.9 1645.76  5129.8 1646.26  5438.4 1646.56  5530.3 1648.68  5601.1 1651.11
#Mann= 5 ,-1 , 0
    4634     .05       0  4845.5      .1       0  4989.9     .07       0
  4995.9      .1       0  5129.8     .05       0
Bank Sta=4936.2,5084.7
XS Rating Curve= 0 ,0
Exp/Cntr=0.3,0.1

Type RM Length L Ch R = 1 ,5868    ,366,366,366
BEGIN DESCRIPTION:
MARSCHALL CREEK 10.0
END DESCRIPTION:
XS GIS Cut Line= 2
       2777928.9     10080693.35      2777065.52     10081239.47
#Sta/Elev= 30
  4585.9 1657.01  4593.3  1656.8  4657.7 1654.19  4681.8 1652.27  4713.4 1651.08
  4730.6  1650.1  4775.7 1645.61  4811.2  1643.7  4824.7 1641.87  4846.7 1636.26
    4854 1635.64  4861.2 1633.65  4876.4 1631.34  4905.9 1629.84  4934.1  1629.5
  4953.5 1625.88  4976.9 1620.86    5004 1620.57  5006.7 1620.07    5010 1620.57
  5026.2 1622.18  5043.4 1628.71  5064.6 1638.55  5071.5 1640.51  5122.3 1644.38
    5174 1642.99  5260.9 1642.15  5398.6  1642.4  5492.7 1644.22  5607.5 1648.95
#Mann= 9 ,-1 , 0
  4585.9      .1       0  4593.3     .05       0  4681.8      .1       0
  4713.4     .16       0    4854     .05       0  4953.5      .1       0
    5004     .07       0    5010      .1       0  5026.2     .05       0
#XS Ineff= 2 , 0
                         5123.38         1644.35
Permanent Ineff=
       F       F
Bank Sta=4934.1,5043.4
XS Rating Curve= 0 ,0
Exp/Cntr=0.3,0.1

Type RM Length L Ch R = 1 ,5502    ,610,610,610
BEGIN DESCRIPTION:
MARSCHALL CREEK 9.0
END DESCRIPTION:
XS GIS Cut Line= 3
      2777788.22     10080292.35      2776866.37     10081016.29
      2776465.35     10081130.86
#Sta/Elev= 30
  4438.5 1654.53  4524.5 1651.31  4717.8 1641.87  4767.5 1641.05  4902.2 1641.38
  4937.5 1638.31  4959.5 1635.35  4977.7 1626.15  4987.2 1619.92  4998.7 1618.09
  5001.4 1617.59  5004.7 1618.09  5030.6 1620.13  5073.9 1626.94  5080.3 1627.74
  5109.2 1628.53  5115.6 1628.04    5130 1628.97  5137.5 1631.64  5144.5 1636.93
  5158.9 1641.93  5201.1 1640.91  5328.9 1640.52  5407.5 1642.73  5500.6 1646.63
    5600 1648.56  5660.8  1648.1  5785.3 1644.75    5835 1646.67  6027.7 1650.85
#Mann= 5 ,-1 , 0
  4438.5      .1       0  4524.5     .16       0  4977.7     .05       0
  4998.7    .035       0  5004.7     .05       0
#XS Ineff= 2 , 0
         4888.02  1641.7 5165.03         1641.76
Permanent Ineff=
       F       F
Bank Sta=4977.7,5073.9
XS Rating Curve= 0 ,0
Exp/Cntr=0.3,0.1

Type RM Length L Ch R = 1 ,4892    ,305,305,305
BEGIN DESCRIPTION:
MARSCHALL CREEK 8.0
END DESCRIPTION:
XS GIS Cut Line= 3
      2777626.78     10080125.66      2776684.08     10080141.29
      2776137.19     10080370.46
#Sta/Elev= 30
  4435.2 1645.99  4573.5 1639.09  4759.2 1638.27  4805.6 1638.57  4863.6 1639.48
  4903.6 1638.53  4907.9 1637.41  4913.6 1635.93  4933.6 1625.48  4943.6 1620.95
  4953.6 1618.83  4997.6 1617.04  5000.6 1616.98  5003.3 1616.48  5006.6 1616.98
  5033.6  1617.6  5053.6 1624.54  5063.6 1626.47  5093.6 1637.27  5113.6 1640.13
  5213.6 1641.48  5398.8 1640.92  5538.5 1644.78  5682.1 1651.49  5727.2 1655.05
  5817.8 1664.45  5828.7 1663.93    5841 1660.49  5850.3 1659.73    5971 1660.29
#Mann= 9 ,-1 , 0
  4435.2      .1       0  4759.2     .16       0  4805.6     .05       0
  4907.9      .1       0  4997.6     .05       0  5000.6    .035       0
  5006.6     .05       0  5538.5     .16       0  5727.2     .05       0
#XS Ineff= 2 , 0
         4862.08 1639.47 5212.05         1641.35
Permanent Ineff=
       F       F
Bank Sta=4933.6,5063.6
XS Rating Curve= 0 ,0
Exp/Cntr=0.3,0.1

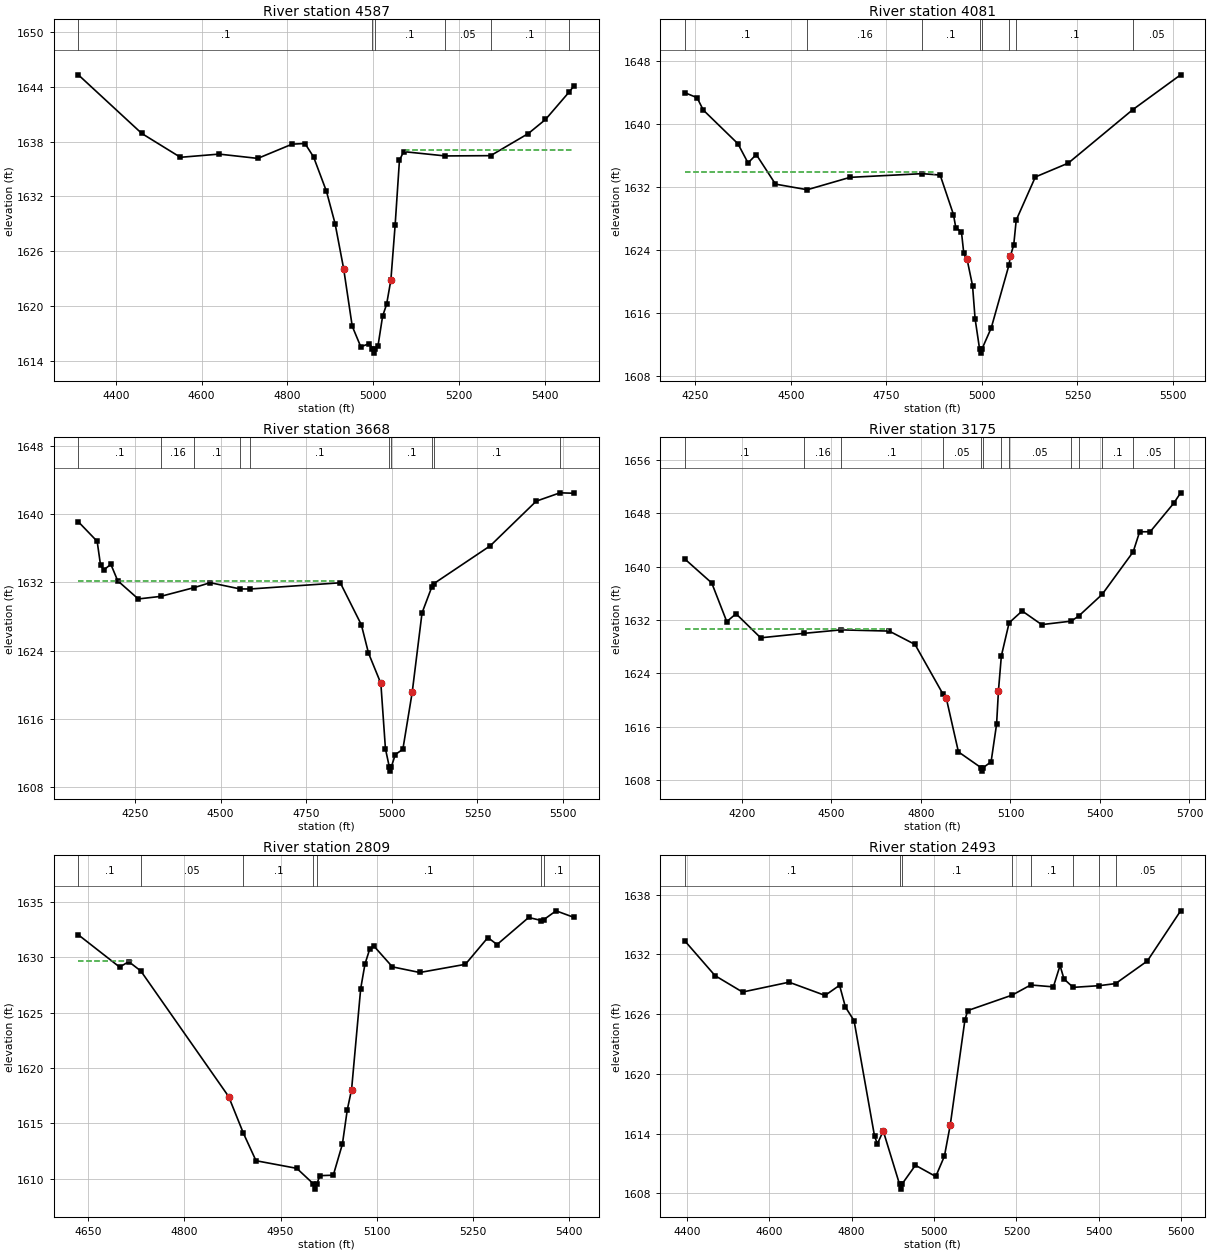
Type RM Length L Ch R = 1 ,4587    ,506,506,506
BEGIN DESCRIPTION:
MARSCHALL CREEK 7.0
END DESCRIPTION:
XS GIS Cut Line= 2
      2777736.21     10079870.45      2776581.68     10079818.45
#Sta/Elev= 30
  4312.5  1645.3  4460.4 1638.88  4550.5 1636.27  4640.6 1636.62  4730.7 1636.15
  4810.8 1637.71  4840.8 1637.78  4860.8 1636.31  4890.8 1632.55  4910.9 1629.02
  4930.9 1624.08  4950.9 1617.78  4970.9 1615.52  4990.9 1615.88  4997.9 1615.33
  5000.7 1614.83  5003.9 1615.33    5011 1615.63  5021.7 1618.87    5031 1620.17
    5041 1622.84    5051  1628.9    5061 1635.96    5071 1636.89  5167.8 1636.42
  5273.5 1636.45  5361.3 1638.87  5401.4 1640.41  5456.7 1643.43  5468.2 1644.12
#Mann= 6 ,-1 , 0
  4312.5      .1       0  4997.9     .07       0  5003.9      .1       0
  5167.8     .05       0  5273.5      .1       0  5456.7     .05       0
#XS Ineff= 2 , 0
         4839.95 1637.74 5077.41         1637.03
Permanent Ineff=
       F       F
Bank Sta=4930.9,5041
XS Rating Curve= 0 ,0
Exp/Cntr=0.3,0.1

Type RM Length L Ch R = 1 ,4081    ,413,413,413
BEGIN DESCRIPTION:
MARSCHALL CREEK 6.0
END DESCRIPTION:
XS GIS Cut Line= 3
      2777699.75     10079177.73      2777043.46     10079328.79
      2776533.28     10079687.99
#Sta/Elev= 30
  4222.5 1643.92  4254.6 1643.29  4270.8 1641.72  4361.5 1637.44    4388    1635
  4409.5 1636.07  4459.8 1632.31  4542.9  1631.6  4654.8 1633.17  4843.7 1633.64
  4890.7 1633.46  4925.5 1628.45  4931.6 1626.78  4946.4 1626.24  4952.5 1623.52
  4961.2 1622.74  4975.4 1619.43  4982.1 1615.21  4993.9 1611.35  4996.7 1610.85
  4999.9 1611.35  5024.4 1614.06  5070.8 1622.05  5074.5 1623.18  5083.2 1624.59
  5089.7 1627.74  5139.8 1633.22    5226 1634.98  5394.5 1641.76  5519.9 1646.19
#Mann= 8 ,-1 , 0
  4222.5      .1       0  4542.9     .16       0  4843.7      .1       0
  4993.9     .07       0  4999.9      .1       0  5070.8     .05       0
  5089.7      .1       0  5394.5     .05       0
#XS Ineff= 2 , 0
          4875.7 1633.91
Permanent Ineff=
       F       F
Bank Sta=4961.2,5074.5
XS Rating Curve= 0 ,0
Exp/Cntr=0.3,0.1

Type RM Length L Ch R = 1 ,3668    ,493,493,493
BEGIN DESCRIPTION:
MARSCHALL CREEK 5.0
END DESCRIPTION:
XS GIS Cut Line= 3
      2777543.49     10079057.95      2776741.37     10079042.33
      2776242.46     10079452.89
#Sta/Elev= 30
  4084.3 1639.13  4139.3 1636.83  4149.3    1634  4159.3 1633.49  4179.3 1634.13
  4199.3  1632.2  4259.4 1630.06  4324.6 1630.36  4423.2  1631.4  4469.4 1631.97
  4556.6 1631.24    4586 1631.23  4849.5 1631.96  4911.1 1627.02  4931.9  1623.7
    4968 1620.14  4981.4 1612.46  4992.7 1610.33  4995.5 1609.83  4998.7 1610.33
  5010.1 1611.78  5032.3 1612.39  5059.6 1619.09  5088.3 1628.42  5116.7 1631.45
  5122.4 1631.85  5287.7 1636.31  5421.9 1641.55  5491.3 1642.53  5532.7 1642.48
#Mann= 10 ,-1 , 0
  4084.3      .1       0  4324.6     .16       0  4423.2      .1       0
  4556.6     .16       0    4586      .1       0  4992.7     .07       0
  4998.7      .1       0  5116.7     .05       0  5122.4      .1       0
  5491.3     .16       0
#XS Ineff= 2 , 0
         4831.96  1632.2
Permanent Ineff=
       F       F
Bank Sta=4968,5059.6
XS Rating Curve= 0 ,0
Exp/Cntr=0.3,0.1

Type RM Length L Ch R = 1 ,3175    ,366,366,366
BEGIN DESCRIPTION:
MARSCHALL CREEK 4.0
END DESCRIPTION:
XS GIS Cut Line= 3
      2777574.74     10078990.25      2776725.75     10078771.49
      2775992.41     10078490.64
#Sta/Elev= 30
  4008.3 1641.15  4098.6 1637.55    4149 1631.75    4180 1632.93  4262.6 1629.32
  4407.9 1629.99  4531.2 1630.51  4693.4 1630.33    4780 1628.32    4874 1620.85
    4885 1620.22  4925.5  1612.2  5001.9 1609.81  5004.7 1609.31  5007.9 1609.81
    5035 1610.71  5053.4 1616.35  5059.7  1621.4  5069.4  1626.6  5095.4 1631.57
  5139.1 1633.35  5204.5  1631.3  5303.3 1631.82    5328 1632.56  5407.3 1635.84
  5511.2 1642.22  5532.9 1645.23  5568.3 1645.24  5647.6 1649.54  5670.3 1651.08
#Mann= 13 ,-1 , 0
  4008.3      .1       0  4407.9     .16       0  4531.2      .1       0
    4874     .05       0  5001.9    .035       0  5007.9     .05       0
  5069.4      .1       0  5095.4     .05       0  5303.3      .1       0
    5328     .05       0  5407.3      .1       0  5511.2     .05       0
  5647.6      .1       0
#XS Ineff= 2 , 0
         4690.77 1630.62 5142.24         1632.91
Permanent Ineff=
       F       F
Bank Sta=4885,5059.7
XS Rating Curve= 0 ,0
Exp/Cntr=0.3,0.1

Type RM Length L Ch R = 1 ,2809    ,316,316,316
BEGIN DESCRIPTION:
Mapping XS dae2402a
END DESCRIPTION:
XS GIS Cut Line= 2
      2777123.91     10078779.47      2776614.27     10078198.27
#Sta/Elev= 30
  4634.7 1632.05  4699.1 1629.13  4713.3 1629.62  4732.1 1628.78    4869 1617.42
  4892.1 1614.09  4911.7 1611.61  4975.3 1610.92  5000.7 1609.54  5003.5 1609.04
  5006.7 1609.54  5011.3 1610.26  5032.2  1610.3  5046.4 1613.12    5054 1616.22
  5060.7 1618.05  5074.9 1627.18  5081.6 1629.41  5089.1 1630.78  5095.8 1631.01
  5124.3 1629.15    5167 1628.64  5238.1 1629.38  5273.2  1631.8  5287.5 1631.17
  5336.8 1633.62  5356.7 1633.34    5360 1633.41  5379.5 1634.22  5407.7 1633.62
#Mann= 7 ,-1 , 0
  4634.7      .1       0  4732.1     .05       0  4892.1      .1       0
  5000.7     .07       0  5006.7      .1       0  5356.7     .05       0
    5360      .1       0
#XS Ineff= 2 , 0
         4717.88 1629.66 5097.05          1630.9
Permanent Ineff=
       F       F
Bank Sta=4869,5060.7
XS Rating Curve= 0 ,0
Exp/Cntr=0.3,0.1

Type RM Length L Ch R = 1 ,2493    ,132,132,132
BEGIN DESCRIPTION:
Mapping XS 258c6bb9
END DESCRIPTION:
XS GIS Cut Line= 4
      2777481.97     10078809.83      2777362.62     10078562.46
      2777054.46     10078234.77      2776602.15     10078076.78
#Sta/Elev= 30
  4394.9 1633.36  4468.3 1629.87    4535 1628.22    4648 1629.21  4735.4 1627.88
  4770.6  1628.9  4784.8 1626.71  4805.8 1625.34  4855.6 1613.72  4862.5 1612.97
  4876.6 1614.27  4916.1 1608.92  4918.9 1608.42  4922.1 1608.92  4954.7 1610.82
  5004.1 1609.69  5025.1 1611.73  5039.3 1614.87  5074.9 1625.42  5081.8 1626.36
  5189.4 1627.91  5234.6 1628.93  5289.6 1628.74  5305.8 1630.89  5315.4 1629.53
  5337.6 1628.69  5400.9 1628.86  5440.6 1629.07  5517.7 1631.34  5598.5 1636.38
#Mann= 8 ,-1 , 0
  4394.9      .1       0  4916.1     .07       0  4922.1      .1       0
  5189.4     .05       0  5234.6      .1       0  5337.6     .05       0
  5400.9      .1       0  5440.6     .05       0
Bank Sta=4876.6,5039.3
XS Rating Curve= 0 ,0
Exp/Cntr=0.3,0.1

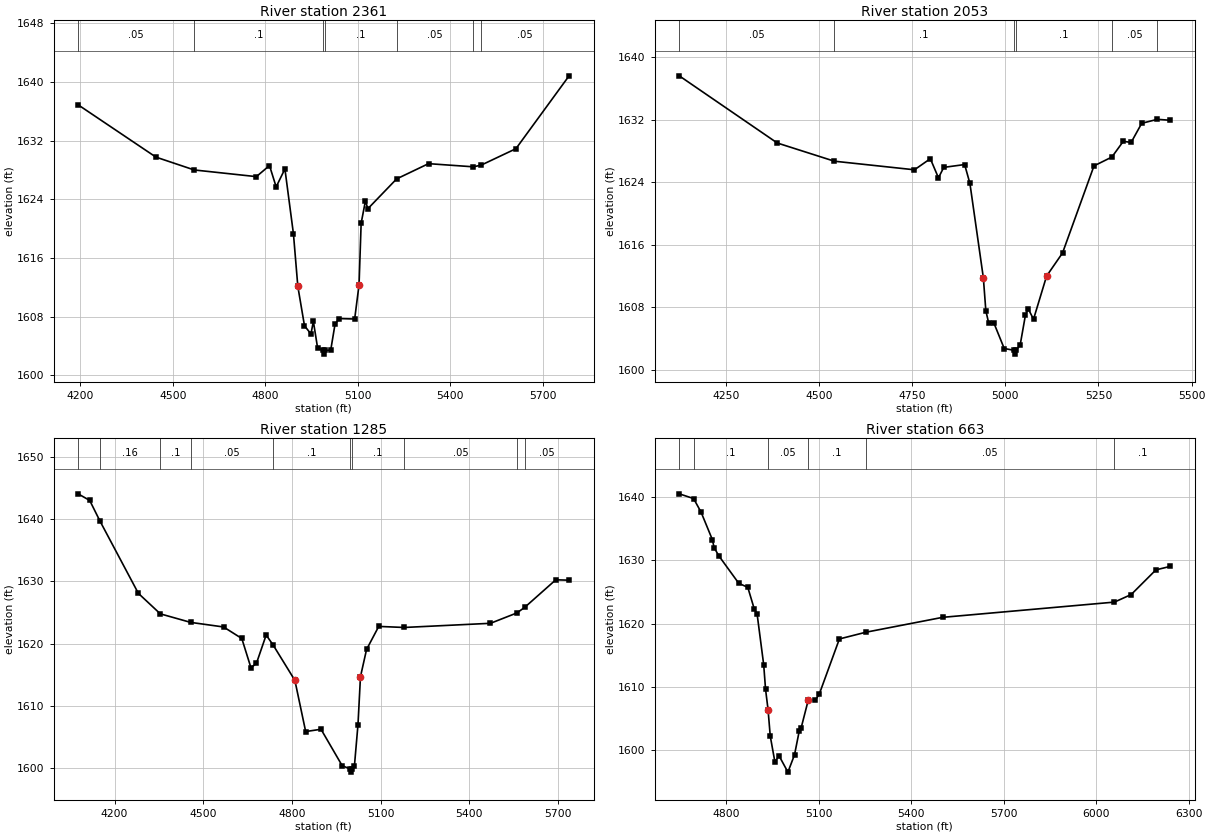
Type RM Length L Ch R = 1 ,2361    ,308,308,308
BEGIN DESCRIPTION:
MARSCHALL CREEK 3.0
END DESCRIPTION:
XS GIS Cut Line= 4
      2777855.39     10078824.02      2777292.88      10078313.6
      2777100.17     10078136.51      2776558.51     10077954.22
#Sta/Elev= 30
  4192.4 1636.88    4445 1629.74  4569.2 1627.99  4770.7 1627.08  4813.3 1628.59
  4834.9 1625.68  4863.3 1628.13    4891 1619.27  4905.2 1612.11  4926.8 1606.74
  4947.8 1605.62  4955.6 1607.34  4969.4  1603.7  4987.3 1603.37  4990.1 1602.87
  4993.3 1603.37  5011.9 1603.41  5025.9 1606.96  5039.7 1607.72  5089.6 1607.66
  5103.8 1612.33  5110.6 1620.72  5124.7 1623.81  5132.1 1622.69  5225.7 1626.77
  5329.2 1628.85  5474.3 1628.42  5499.5 1628.64  5612.7 1630.89  5785.2 1640.83
#Mann= 7 ,-1 , 0
  4192.4     .05       0  4569.2      .1       0  4987.3     .07       0
  4993.3      .1       0  5225.7     .05       0  5474.3      .1       0
  5499.5     .05       0
Bank Sta=4905.2,5103.8
XS Rating Curve= 0 ,0
Exp/Cntr=0.3,0.1

Type RM Length L Ch R = 1 ,2053    ,768,768,768
BEGIN DESCRIPTION:
MARSCHALL CREEK 2.0
END DESCRIPTION:
XS GIS Cut Line= 2
       2778048.7     10078724.65      2777173.66     10077740.24
#Sta/Elev= 30
  4125.5 1637.62  4388.4 1629.02  4541.5 1626.69  4756.4 1625.59    4799 1627.01
  4820.8 1624.56    4835  1625.9    4891 1626.26  4905.2 1623.84  4941.2 1611.77
  4947.9 1607.54  4955.4    1606  4969.6 1605.96  4997.2 1602.71  5022.6 1602.49
  5025.4 1601.99  5028.6 1602.49  5039.9 1603.14  5054.1 1606.99  5061.6 1607.79
  5075.8 1606.46  5110.9 1611.99  5153.6 1614.94    5238 1626.09  5285.9 1627.22
  5316.7 1629.24  5337.6 1629.09    5366 1631.54  5407.9 1632.05  5442.6 1631.93
#Mann= 6 ,-1 , 0
  4125.5     .05       0  4541.5      .1       0  5022.6     .07       0
  5028.6      .1       0  5285.9     .05       0  5407.9      .1       0
Bank Sta=4941.2,5110.9
XS Rating Curve= 0 ,0
Exp/Cntr=0.3,0.1

Type RM Length L Ch R = 1 ,1285    ,622,622,622
BEGIN DESCRIPTION:
Mapping XS 13becaba
END DESCRIPTION:
XS GIS Cut Line= 3
      2778237.28     10078471.86       2777983.8     10077433.63
      2777393.53     10077485.71
#Sta/Elev= 30
  4076.4 1644.09  4115.7 1643.03  4149.9 1639.76  4280.4 1628.09  4354.6  1624.8
  4456.9 1623.43  4568.6 1622.69  4630.3 1620.84  4661.2 1616.14  4679.7 1616.83
  4712.7 1621.39  4735.8 1619.83  4809.9 1614.11  4846.4 1605.88  4898.3 1606.25
    4970 1600.39  4997.9 1599.86  5000.7 1599.36  5003.9 1599.86  5011.2 1600.27
  5023.4    1607  5031.8  1614.7  5052.4 1619.07  5093.6 1622.78  5179.5 1622.61
  5471.7 1623.28  5561.3 1624.95  5588.2 1625.87  5692.6 1630.27  5737.7 1630.21
#Mann= 10 ,-1 , 0
  4076.4      .1       0  4149.9     .16       0  4354.6      .1       0
  4456.9     .05       0  4735.8      .1       0  4997.9     .07       0
  5003.9      .1       0  5179.5     .05       0  5561.3      .1       0
  5588.2     .05       0
#XS Ineff= 2 , 0
         4713.16 1621.19
Permanent Ineff=
       F       F
Bank Sta=4809.9,5031.8
XS Rating Curve= 0 ,0
Exp/Cntr=0.3,0.1

Type RM Length L Ch R = 1 ,663     ,0,0,0
BEGIN DESCRIPTION:
MARSCHALL CREEK 1.0
END DESCRIPTION:
XS GIS Cut Line= 3
      2778792.82     10077836.39      2778456.02     10077308.63
      2777492.11     10077371.04
#Sta/Elev= 30
  4647.6 1640.53  4694.1 1639.78  4718.4 1637.62  4754.8  1633.3  4760.7 1632.01
  4775.9 1630.72  4840.6 1626.37  4869.8 1625.74    4891 1622.28  4899.9 1621.56
  4921.4 1613.48  4927.4  1609.6  4935.5 1606.39  4942.6 1602.21  4957.8 1598.08
    4971  1599.1  4999.9  1596.5  5021.3 1599.24  5036.5 1602.97  5042.5 1603.44
  5065.9  1607.9  5088.1 1607.84  5101.5 1608.83  5166.8 1617.57  5252.3 1618.63
  5501.7 1620.99  6058.6  1623.4    6113  1624.6  6193.1  1628.5  6239.6 1629.05
#Mann= 6 ,-1 , 0
  4647.6     .05       0  4694.1      .1       0  4935.5     .05       0
  5065.9      .1       0  5252.3     .05       0  6058.6      .1       0
Bank Sta=4935.5,5065.9
XS Rating Curve= 0 ,0
Exp/Cntr=0.3,0.1

Chan Stop Cuts=-1
Use User Specified Reach Order=0
Composite Channel Slope=5