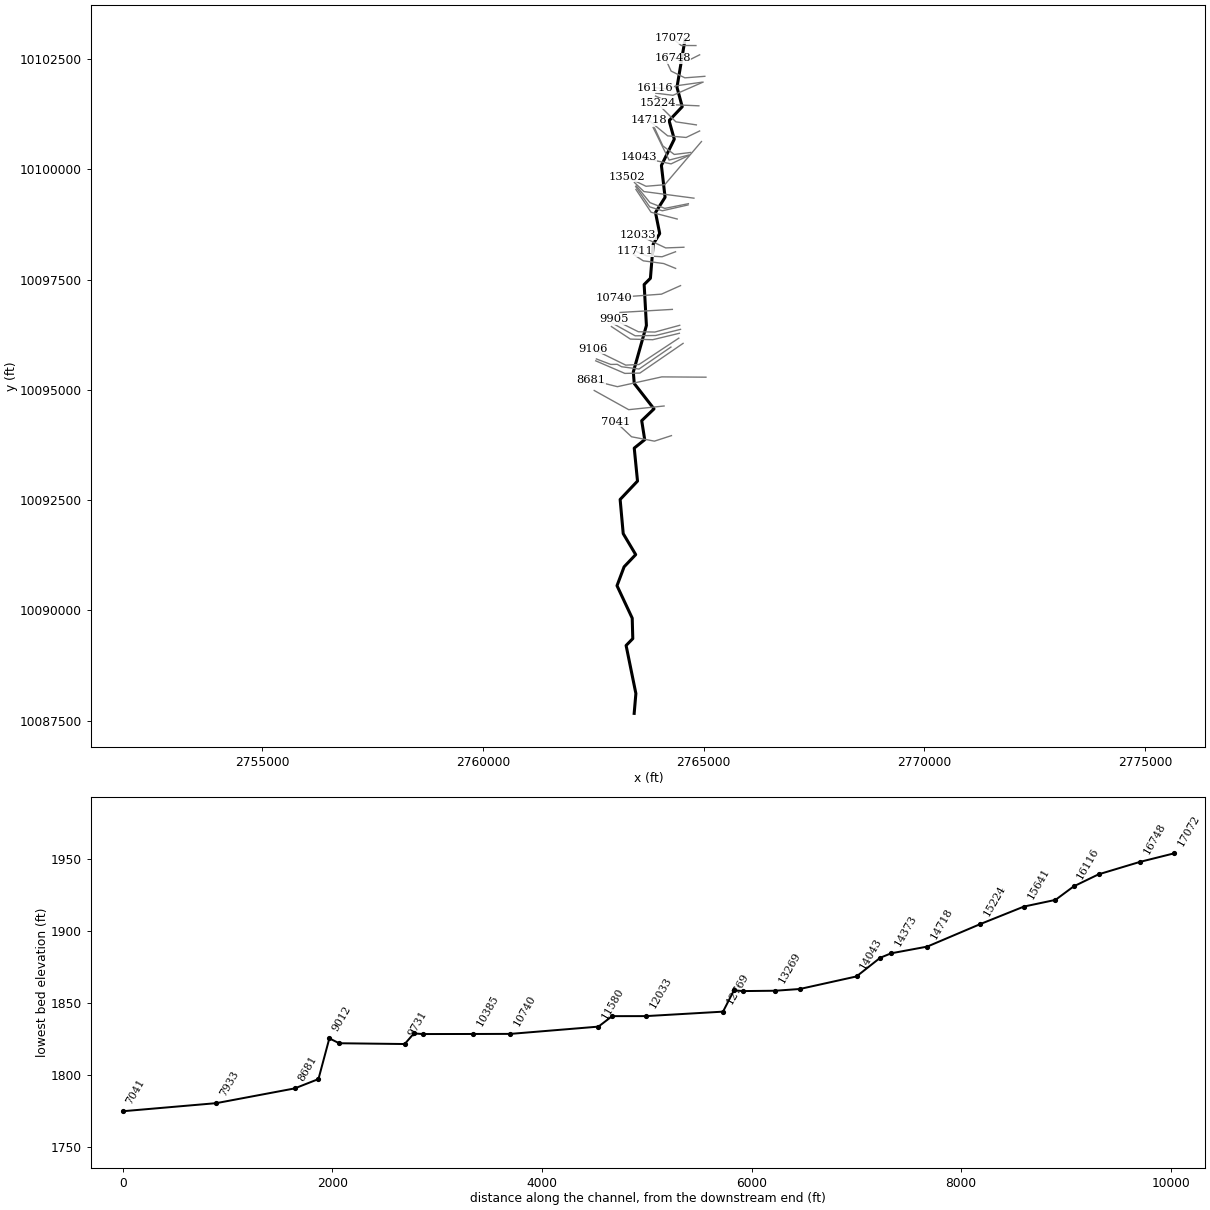
--- MAYER CREEK.prj (project) ---

Proj Title=MAYER CREEK Base Level Engineering
Current Plan=p01
Default Exp/Contr=0.3,0.1
English Units
Geom File=g01
Flow File=f01
Plan File=p01
BEGIN DESCRIPTION:
MAYER CREEK
END DESCRIPTION:

--- MAYER CREEK.p01 (plan) ---

Plan Title=Multiple Run
Short Identifier=Multiple
Geom File=g01
Flow File=f01
Subcritical Flow
K Sum by GR= 0
Std Step Tol= 0.01
Critical Tol= 0.01
Num of Std Step Trials= 20
Max Error Tol= 0.3
Flow Tol Ratio= 0.001
Split Flow NTrial= 30
Split Flow Tol= 0.02
Split Flow Ratio= 0.02
Log Output Level= 0
Friction Slope Method= 1
Unsteady Friction Slope Method= 2
Unsteady Bridges Friction Slope Method= 1
Parabolic Critical Depth
Global Vel Dist=  1 , 1 , 1
Global Log Level= 0
CheckData=True
Encroach Param= -1, 0, 0, 0
BEGIN DESCRIPTION:
Multiple Run
END DESCRIPTION:

--- MAYER CREEK.f01 (steady flow) ---

Flow Title=Multiple
Number of Profiles=7
Profile Names=10-year,25-year,50-year,1pct_min,100-year,1pct_plu,500-year
River Rch & RM= MAYER CREEK,Reach-1,17072
     214     284     339     299     404     546     573
River Rch & RM= MAYER CREEK,Reach-1,16116
     608     866    1088    1002    1355    1832    2109
River Rch & RM= MAYER CREEK,Reach-1,13269
    1451    2162    2795    2640    3571    4829    5855
Boundary for River Rch & Prof#=MAYER CREEK,Reach-1,1
Up Type=0
Dn Type=3
Dn Slope=0.005
Boundary for River Rch & Prof#=MAYER CREEK,Reach-1,2
Up Type=0
Dn Type=3
Dn Slope=0.005
Boundary for River Rch & Prof#=MAYER CREEK,Reach-1,3
Up Type=0
Dn Type=3
Dn Slope=0.005
Boundary for River Rch & Prof#=MAYER CREEK,Reach-1,4
Up Type=0
Dn Type=3
Dn Slope=0.005
Boundary for River Rch & Prof#=MAYER CREEK,Reach-1,5
Up Type=0
Dn Type=3
Dn Slope=0.005
Boundary for River Rch & Prof#=MAYER CREEK,Reach-1,6
Up Type=0
Dn Type=3
Dn Slope=0.005
Boundary for River Rch & Prof#=MAYER CREEK,Reach-1,7
Up Type=0
Dn Type=3
Dn Slope=0.005

--- MAYER CREEK.g01 (geometry) ---

Geom Title=Existing Conditions

River Reach=MAYER CREEK,Reach-1
Reach XY= 30
      2764579.83     10102941.05      2764398.36     10101860.24
      2764517.28     10101419.36      2764219.50     10101103.78
      2764337.46     10100683.77      2764045.57     10100087.56
      2764128.69     10099365.95      2763911.59     10099020.97
      2764007.22     10098543.51      2763859.71     10098303.76
      2763796.42     10097529.56      2763654.68     10097387.42
      2763705.78     10096458.70      2763408.99     10095405.32
      2763430.08     10095143.08      2763878.05     10094568.25
      2763599.28     10094300.07      2763666.97     10093869.60
      2763430.10     10093678.24      2763504.02     10092930.86
      2763110.48     10092513.83      2763180.14     10091739.29
      2763462.96     10091263.59      2763200.25     10090986.88
      2763039.55     10090558.60      2763384.20     10089823.05
      2763396.94     10089359.00      2763245.58     10089202.60
      2763467.22     10088113.75      2763428.47     10087663.73

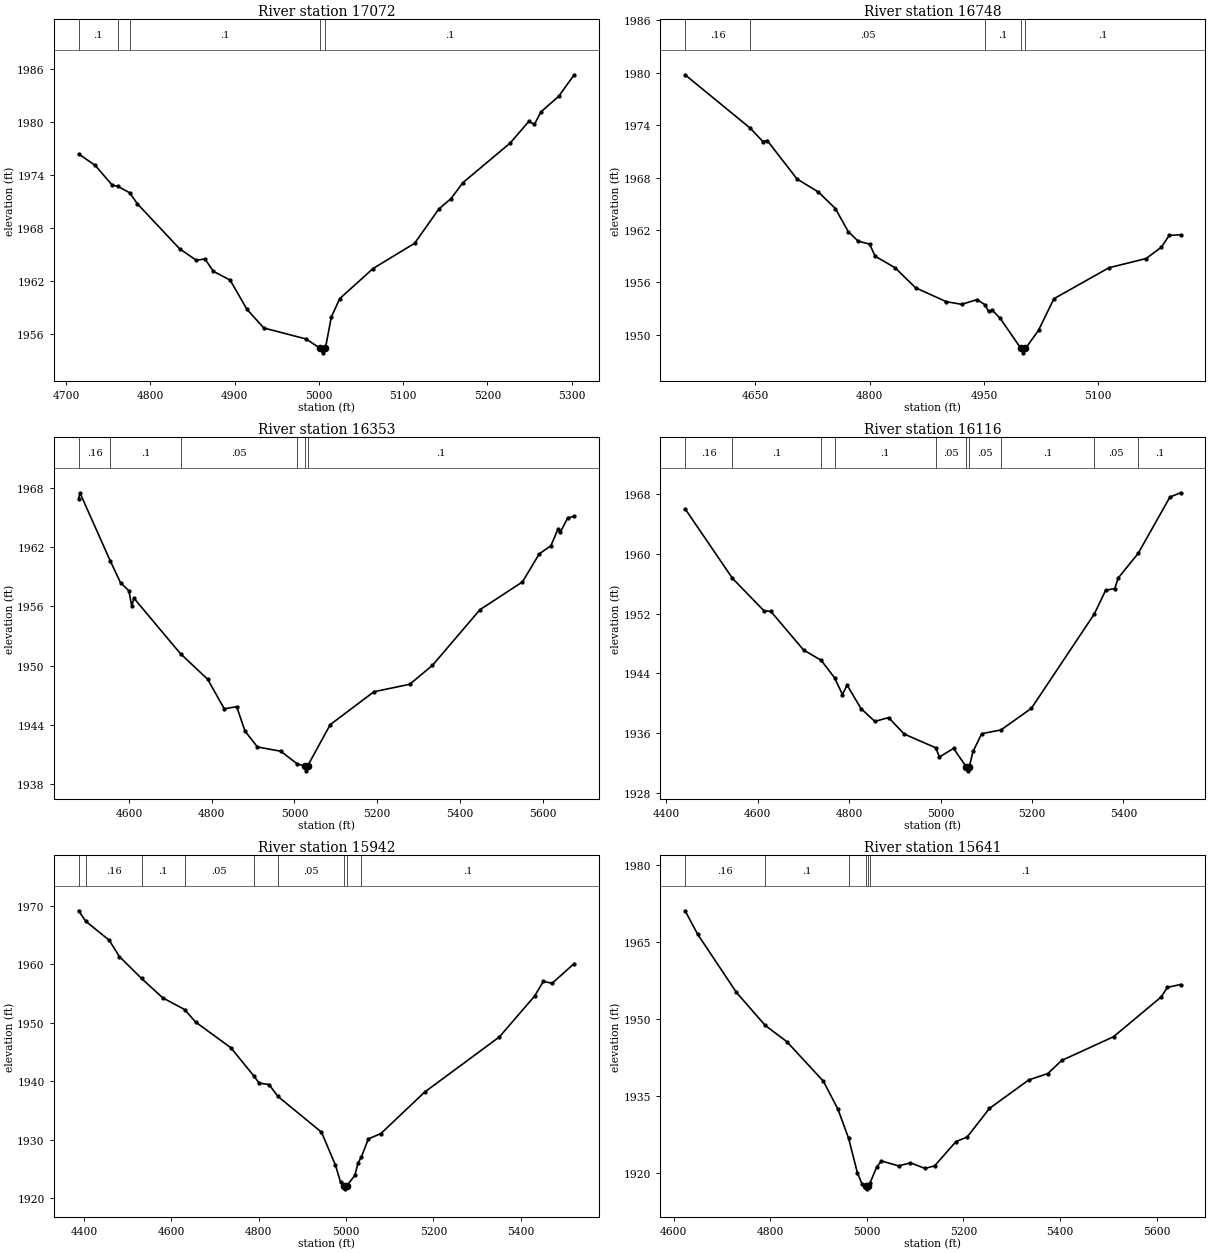
Type RM Length L Ch R = 1,17072,324,324,324
BEGIN DESCRIPTION:
MAYER CREEK 37.0
END DESCRIPTION:
XS GIS Cut Line= 3
      2764828.22     10102806.15      2764494.91     10102807.88
      2764298.41     10102969.91
#Sta/Elev= 30
  4714.9 1976.34  4734.7 1975.03  4754.7 1972.81  4761.1 1972.69  4775.5 1971.94
  4784.7 1970.69  4834.7 1965.61  4854.7 1964.30  4864.7 1964.47  4874.7 1963.07
  4894.7 1962.06  4914.7 1958.75  4934.7 1956.65  4984.7 1955.41  5001.7 1954.34
  5004.4 1953.84  5007.7 1954.34  5014.7 1957.88  5024.7 1959.97  5064.2 1963.37
  5113.7 1966.24  5142.3 1970.11  5156.7 1971.28  5171.0 1973.10  5227.0 1977.57
  5249.2 1980.03  5255.7 1979.67  5263.5 1981.10  5284.4 1982.84  5302.9 1985.29
#Mann=5,-1,0
  4714.9     0.1       0  4761.1    0.16       0  4775.5     0.1       0
  5001.7    0.07       0  5007.7     0.1       0
Bank Sta=5001.7,5007.7
Exp/Cntr=0.3,0.1

Type RM Length L Ch R = 1,16748,395,395,395
BEGIN DESCRIPTION:
Mapping XS 6288381f
END DESCRIPTION:
XS GIS Cut Line= 3
      2764911.60     10102596.09      2764665.05     10102472.81
      2764293.56     10102521.42
#Sta/Elev= 30
  4557.8 1979.76  4643.6 1973.63  4660.0 1972.11  4665.6 1972.24  4704.7 1967.84
  4732.7 1966.35  4755.0 1964.46  4771.8 1961.83  4784.9 1960.73  4799.8 1960.39
  4807.3 1959.00  4833.4 1957.68  4860.3 1955.39  4900.6 1953.80  4920.8 1953.50
  4940.9 1954.04  4951.2 1953.46  4956.1 1952.69  4961.1 1952.81  4971.2 1951.91
  4998.5 1948.45  5001.2 1947.95  5004.5 1948.45  5021.6 1950.53  5041.8 1954.14
  5113.9 1957.68  5162.8 1958.74  5182.7 1960.03  5193.1 1961.38  5208.1 1961.46
#Mann=5,-1,0
  4557.8    0.16       0  4643.6    0.05       0  4951.2     0.1       0
  4998.5    0.07       0  5004.5     0.1       0
Bank Sta=4998.5,5004.5
Exp/Cntr=0.3,0.1

Type RM Length L Ch R = 1,16353,237,237,237
BEGIN DESCRIPTION:
MAYER CREEK 36.0
END DESCRIPTION:
XS GIS Cut Line= 4
      2765029.58     10102108.73      2764578.18     10102074.01
      2764265.68     10102226.79      2764099.01     10102587.90
#Sta/Elev= 30
  4478.2 1966.92  4481.3 1967.52  4554.7 1960.61  4579.6 1958.39  4599.7 1957.59
  4606.7 1956.01  4611.7 1956.84  4724.7 1951.19  4790.2 1948.61  4830.4 1945.61
  4860.4 1945.83  4880.5 1943.35  4910.6 1941.74  4967.0 1941.31  5007.4 1940.00
  5026.0 1939.82  5028.7 1939.32  5032.0 1939.82  5086.5 1944.00  5192.2 1947.34
  5278.8 1948.10  5333.9 1950.02  5448.6 1955.66  5551.4 1958.48  5591.8 1961.31
  5620.2 1962.15  5637.7 1963.87  5643.2 1963.53  5660.6 1964.96  5676.5 1965.14
#Mann=6,-1,0
  4478.2    0.16       0  4554.7     0.1       0  4724.7    0.05       0
  5007.4     0.1       0  5026.0   0.035       0  5032.0     0.1       0
Bank Sta=5026,5032
Exp/Cntr=0.3,0.1

Type RM Length L Ch R = 1,16116,174,174,174
BEGIN DESCRIPTION:
Mapping XS 8c89e011
END DESCRIPTION:
XS GIS Cut Line= 4
      2764959.52     10101974.51      2764390.90     10101895.51
      2764190.38     10101822.59      2763895.20     10101852.11
#Sta/Elev= 30
  4441.0 1966.02  4544.5 1956.73  4613.7 1952.37  4628.6 1952.30  4700.3 1947.13
  4738.8 1945.76  4768.0 1943.42  4785.3 1941.18  4795.4 1942.45  4825.7 1939.31
  4856.0 1937.59  4886.3 1938.10  4920.3 1935.90  4989.4 1934.06  4997.3 1932.83
  5028.3 1933.98  5056.5 1931.48  5059.3 1930.98  5062.5 1931.48  5070.9 1933.57
  5090.1 1935.95  5132.1 1936.45  5198.6 1939.34  5336.4 1951.97  5361.0 1955.12
  5381.1 1955.36  5388.4 1956.75  5432.2 1960.06  5501.7 1967.59  5525.1 1968.16
#Mann=10,-1,0
  4441.0    0.16       0  4544.5     0.1       0  4738.8    0.05       0
  4768.0     0.1       0  4989.4    0.05       0  5056.5   0.035       0
  5062.5    0.05       0  5132.1     0.1       0  5336.4    0.05       0
  5432.2     0.1       0
Bank Sta=5056.5,5062.5
Exp/Cntr=0.3,0.1

Type RM Length L Ch R = 1,15942,301,301,301
BEGIN DESCRIPTION:
MAYER CREEK 35.0
END DESCRIPTION:
XS GIS Cut Line= 3
      2764987.89     10101976.78      2764307.35     10101678.18
      2763918.44     10101726.79
#Sta/Elev= 30
  4387.5 1969.17  4403.9 1967.37  4457.6 1964.13  4480.9 1961.34  4531.6 1957.59
  4579.9 1954.29  4630.2 1952.28  4655.4 1950.14  4736.4 1945.72  4789.1 1940.89
  4801.1 1939.69  4823.7 1939.44  4843.9 1937.42  4943.8 1931.30  4975.5 1925.70
  4987.5 1922.73  4995.4 1922.10  4998.2 1921.60  5001.4 1922.10  5020.2 1923.90
  5027.7 1926.07  5034.9 1926.99  5051.1 1930.14  5079.9 1931.06  5179.9 1938.14
  5351.3 1947.59  5431.9 1954.57  5452.0 1957.08  5472.2 1956.77  5522.6 1960.14
#Mann=9,-1,0
  4387.5     0.1       0  4403.9    0.16       0  4531.6     0.1       0
  4630.2    0.05       0  4789.1     0.1       0  4843.9    0.05       0
  4995.4   0.035       0  5001.4    0.05       0  5034.9     0.1       0
Bank Sta=4995.4,5001.4
Exp/Cntr=0.3,0.1

Type RM Length L Ch R = 1,15641,417,417,417
BEGIN DESCRIPTION:
MAYER CREEK 34.0
END DESCRIPTION:
XS GIS Cut Line= 3
      2764894.69     10101439.71      2764350.40     10101463.15
      2763911.92     10101661.63
#Sta/Elev= 30
  4623.7 1971.13  4649.9 1966.53  4730.0 1955.23  4789.4 1948.82  4834.2 1945.65
  4910.2 1937.91  4940.2 1932.48  4962.3 1926.81  4980.3 1920.15  4990.3 1917.86
  4997.3 1917.47  5000.0 1916.97  5003.3 1917.47  5007.0 1918.20  5020.3 1921.19
  5030.3 1922.40  5065.6 1921.44  5090.4 1922.03  5120.4 1920.95  5140.4 1921.45
  5184.6 1926.17  5207.7 1927.06  5253.9 1932.63  5335.3 1938.18  5374.9 1939.43
  5403.4 1941.97  5510.9 1946.60  5609.7 1954.36  5622.3 1956.21  5649.8 1956.77
#Mann=6,-1,0
  4623.7    0.16       0  4789.4     0.1       0  4962.3    0.16       0
  4997.3    0.07       0  5003.3    0.16       0  5007.0     0.1       0
Bank Sta=4997.3,5003.3
Exp/Cntr=0.3,0.1

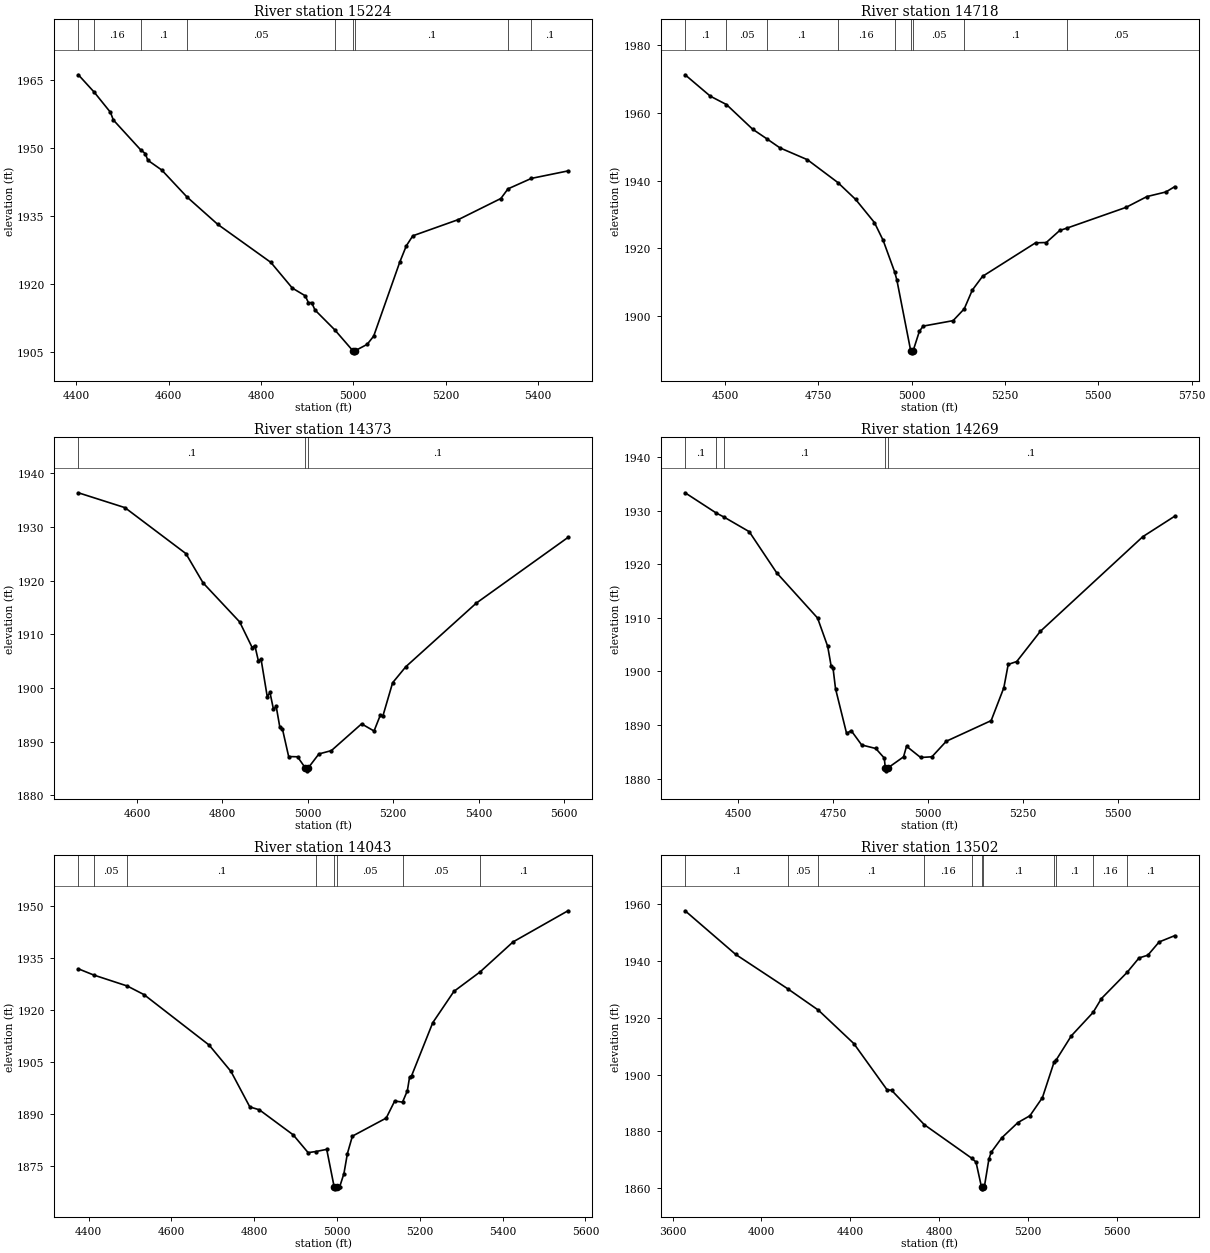
Type RM Length L Ch R = 1,15224,506,506,506
BEGIN DESCRIPTION:
MAYER CREEK 33.0
END DESCRIPTION:
XS GIS Cut Line= 3
      2764837.39     10101007.42      2764373.84     10101076.43
      2763953.34     10101494.33
#Sta/Elev= 30
  4404.0 1966.21  4438.5 1962.36  4473.7 1957.91  4479.8 1956.24  4538.9 1949.66
  4549.1 1948.82  4554.6 1947.34  4584.9 1945.17  4639.3 1939.25  4706.2 1933.18
  4821.4 1924.78  4867.8 1919.12  4895.8 1917.41  4902.8 1915.90  4909.9 1915.90
  4917.0 1914.27  4959.6 1909.92  4998.8 1905.31  5001.6 1904.81  5004.8 1905.31
  5030.1 1906.68  5044.3 1908.50  5100.8 1924.83  5115.0 1928.43  5129.1 1930.65
  5228.1 1934.24  5320.0 1938.89  5335.5 1941.02  5386.2 1943.33  5465.5 1944.98
#Mann=9,-1,0
  4404.0     0.1       0  4438.5    0.16       0  4538.9     0.1       0
  4639.3    0.05       0  4959.6     0.1       0  4998.8    0.07       0
  5004.8     0.1       0  5335.5    0.05       0  5386.2     0.1       0
Bank Sta=4998.8,5004.8
Exp/Cntr=0.3,0.1

Type RM Length L Ch R = 1,14718,345,345,345
BEGIN DESCRIPTION:
MAYER CREEK 32.0
END DESCRIPTION:
XS GIS Cut Line= 4
      2764911.57     10100869.38      2764605.61     10100722.26
      2764187.64     10100758.72      2763760.20     10101109.51
#Sta/Elev= 30
  4392.7 1971.27  4460.3 1964.95  4503.6 1962.48  4573.5 1955.22  4610.9 1952.43
  4646.9 1949.69  4720.4 1946.20  4801.9 1939.47  4849.8 1934.46  4900.0 1927.65
  4923.4 1922.39  4954.5 1912.98  4960.2 1910.65  4997.4 1889.69  5000.1 1889.19
  5003.4 1889.69  5020.4 1895.53  5030.5 1897.08  5110.8 1898.69  5140.7 1902.18
  5162.3 1907.72  5189.6 1911.76  5331.8 1921.67  5360.4 1921.75  5396.5 1925.31
  5414.7 1925.96  5574.2 1932.13  5630.2 1935.32  5681.1 1936.68  5704.7 1938.25
#Mann=9,-1,0
  4392.7     0.1       0  4503.6    0.05       0  4610.9     0.1       0
  4801.9    0.16       0  4954.5    0.05       0  4997.4   0.035       0
  5003.4    0.05       0  5140.7     0.1       0  5414.7    0.05       0
Bank Sta=4997.4,5003.4
Exp/Cntr=0.3,0.1

Type RM Length L Ch R = 1,14373,104,104,104
BEGIN DESCRIPTION:
Mapping XS 824bfa09
END DESCRIPTION:
XS GIS Cut Line= 4
      2764708.52     10100382.43      2764337.38     10100336.85
      2764078.27     10100530.86      2763889.46     10100938.43
#Sta/Elev= 30
  4462.4 1936.40  4571.5 1933.63  4714.3 1925.06  4754.6 1919.59  4840.3 1912.31
  4869.5 1907.54  4875.8 1907.91  4884.1 1905.05  4890.4 1905.35  4904.9 1898.36
  4911.2 1899.17  4919.5 1895.99  4925.8 1896.56  4934.1 1892.79  4940.4 1892.36
  4955.0 1887.21  4975.8 1887.16  4994.4 1885.04  4997.1 1884.54  5000.4 1885.04
  5025.8 1887.69  5055.0 1888.31  5125.8 1893.30  5155.0 1891.97  5170.1 1895.00
  5175.6 1894.74  5198.5 1900.97  5229.3 1903.95  5394.6 1915.83  5609.2 1928.07
#Mann=3,-1,0
  4462.4     0.1       0  4994.4    0.07       0  5000.4     0.1       0
Bank Sta=4994.4,5000.4
Exp/Cntr=0.3,0.1

Type RM Length L Ch R = 1,14269,226,226,226
BEGIN DESCRIPTION:
Mapping XS f2ef9548
END DESCRIPTION:
XS GIS Cut Line= 3
      2764671.99     10100325.12      2764220.20     10100209.24
      2763858.20     10100947.56
#Sta/Elev= 30
  4361.0 1933.33  4443.0 1929.55  4463.1 1928.81  4529.8 1926.07  4602.1 1918.39
  4709.6 1909.96  4736.3 1904.66  4745.2 1901.06  4750.4 1900.58  4756.9 1896.77
  4786.0 1888.43  4798.2 1888.94  4825.7 1886.27  4862.8 1885.61  4885.3 1883.82
  4887.9 1881.94  4890.7 1881.44  4893.9 1881.94  4935.9 1884.05  4943.8 1886.03
  4980.9 1883.93  5010.6 1884.06  5048.4 1886.96  5166.5 1890.81  5199.9 1896.95
  5211.4 1901.30  5233.9 1901.84  5295.8 1907.46  5565.7 1925.14  5649.7 1928.96
#Mann=5,-1,0
  4361.0     0.1       0  4443.0    0.05       0  4463.1     0.1       0
  4887.9    0.07       0  4893.9     0.1       0
Bank Sta=4887.9,4893.9
Exp/Cntr=0.3,0.1

Type RM Length L Ch R = 1,14043,541,541,541
BEGIN DESCRIPTION:
MAYER CREEK 31.0
END DESCRIPTION:
XS GIS Cut Line= 3
      2764653.81     10100308.21      2764264.47     10100123.31
      2763528.76     10100276.96
#Sta/Elev= 30
  4375.1 1931.89  4412.3 1930.10  4493.4 1926.93  4533.8 1924.45  4691.0 1909.92
  4743.8 1902.32  4789.3 1892.10  4812.3 1891.27  4894.0 1884.06  4930.1 1878.93
  4948.7 1879.25  4975.0 1879.87  4993.1 1869.00  4995.9 1868.50  4999.1 1869.00
  5006.4 1869.11  5016.6 1872.91  5025.0 1878.68  5037.0 1883.68  5118.7 1888.89
  5139.2 1893.80  5158.1 1893.48  5169.8 1896.76  5175.0 1900.60  5180.1 1901.10
  5231.1 1916.36  5282.2 1925.38  5345.4 1930.99  5425.2 1939.65  5557.7 1948.61
#Mann=8,-1,0
  4375.1     0.1       0  4412.3    0.05       0  4493.4     0.1       0
  4948.7    0.05       0  4993.1    0.07       0  4999.1    0.05       0
  5158.1    0.05       0  5345.4     0.1       0
Bank Sta=4993.1,4999.1
Exp/Cntr=0.3,0.1

Type RM Length L Ch R = 1,13502,233,233,233
BEGIN DESCRIPTION:
MAYER CREEK 30.0
END DESCRIPTION:
XS GIS Cut Line= 4
      2764953.19     10100629.58      2764119.85     10099650.40
      2763696.23     10099615.68      2763252.65     10099830.54
#Sta/Elev= 30
  3656.4 1957.69  3884.1 1942.32  4119.0 1930.19  4256.5 1922.69  4415.6 1910.95
  4564.9 1894.71  4585.8 1894.48  4733.4 1882.35  4945.8 1870.60  4965.6 1869.23
  4990.7 1860.29  4993.5 1859.79  4996.7 1860.29  5003.8 1860.77  5023.8 1870.29
  5033.9 1872.65  5082.0 1877.78  5154.3 1883.13  5208.4 1885.53  5264.6 1891.91
  5316.6 1904.31  5327.2 1905.25  5394.8 1913.67  5492.7 1921.91  5530.3 1926.80
  5645.2 1935.96  5699.5 1941.09  5739.1 1942.05  5789.8 1946.71  5860.1 1948.93
#Mann=11,-1,0
  3656.4     0.1       0  4119.0    0.05       0  4256.5     0.1       0
  4733.4    0.16       0  4945.8     0.1       0  4990.7    0.07       0
  4996.7     0.1       0  5316.6    0.05       0  5327.2     0.1       0
  5492.7    0.16       0  5645.2     0.1       0
Bank Sta=4990.7,4996.7
Exp/Cntr=0.3,0.1

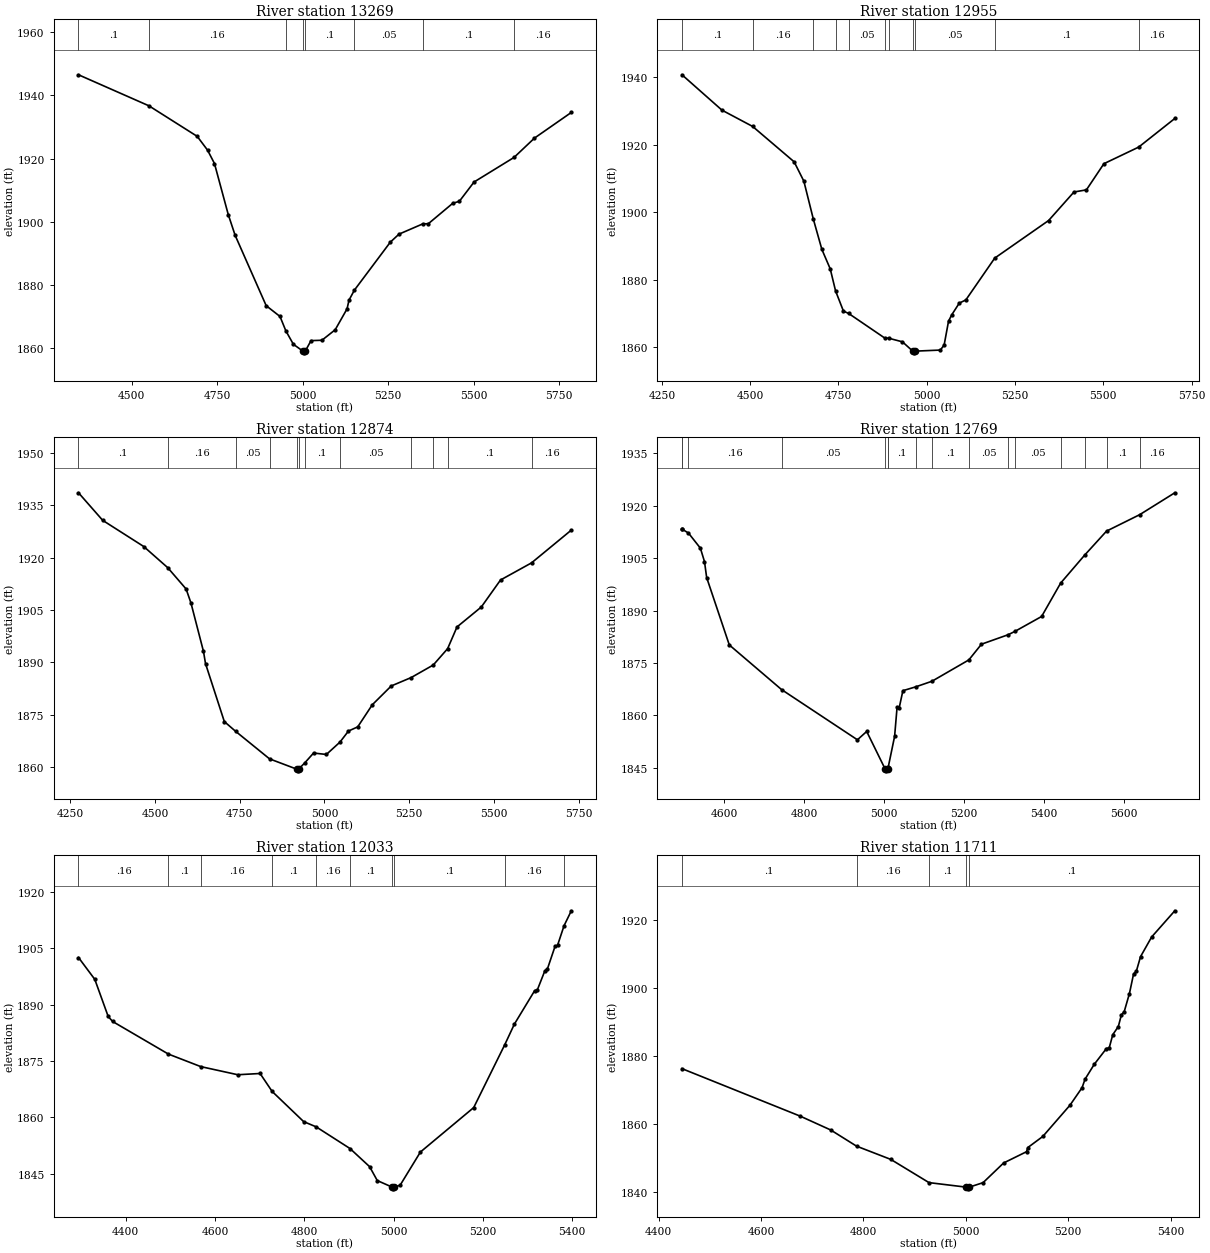
Type RM Length L Ch R = 1,13269,314,314,314
BEGIN DESCRIPTION:
Mapping XS 0fc94579
END DESCRIPTION:
XS GIS Cut Line= 3
      2764782.65     10099345.90      2763648.82     10099495.76
      2763433.98     10099701.57
#Sta/Elev= 30
  4344.0 1946.53  4549.9 1936.72  4691.2 1927.05  4721.4 1922.70  4741.6 1918.47
  4782.0 1902.30  4802.1 1895.75  4892.9 1873.50  4933.3 1870.09  4950.4 1865.54
  4972.4 1861.29  5000.9 1859.09  5003.6 1858.59  5006.9 1859.09  5024.0 1862.45
  5055.9 1862.57  5094.7 1865.89  5129.4 1872.51  5135.0 1875.24  5150.7 1878.40
  5256.0 1893.61  5281.3 1896.13  5350.9 1899.38  5367.0 1899.42  5438.4 1905.88
  5457.8 1906.52  5500.8 1912.62  5617.8 1920.40  5677.5 1926.51  5785.2 1934.62
#Mann=8,-1,0
  4344.0     0.1       0  4549.9    0.16       0  4950.4     0.1       0
  5000.9    0.07       0  5006.9     0.1       0  5150.7    0.05       0
  5350.9     0.1       0  5617.8    0.16       0
Bank Sta=5000.9,5006.9
Exp/Cntr=0.3,0.1

Type RM Length L Ch R = 1,12955,81,81,81
BEGIN DESCRIPTION:
MAYER CREEK 29.0
END DESCRIPTION:
XS GIS Cut Line= 4
      2764656.89     10099220.38      2764123.03     10099114.05
      2763786.66     10099244.25      2763476.32     10099624.04
#Sta/Elev= 30
  4306.8 1940.73  4420.0 1930.25  4506.9 1925.42  4624.4 1914.94  4651.9 1909.21
  4678.7 1897.98  4702.9 1888.99  4726.6 1883.22  4741.7 1876.69  4764.0 1870.70
  4778.4 1870.03  4880.3 1862.77  4892.9 1862.65  4931.1 1861.60  4960.3 1858.84
  4963.0 1858.34  4966.3 1858.84  5038.3 1859.16  5049.1 1860.63  5061.6 1867.74
  5070.5 1869.57  5091.9 1873.06  5110.7 1874.03  5192.4 1886.41  5345.0 1897.55
  5416.8 1906.00  5452.0 1906.63  5501.5 1914.38  5600.0 1919.30  5702.3 1927.78
#Mann=11,-1,0
  4306.8     0.1       0  4506.9    0.16       0  4678.7    0.05       0
  4741.7    0.16       0  4778.4    0.05       0  4880.3    0.16       0
  4892.9    0.05       0  4960.3   0.035       0  4966.3    0.05       0
  5192.4     0.1       0  5600.0    0.16       0
Bank Sta=4960.3,4966.3
Exp/Cntr=0.3,0.1

Type RM Length L Ch R = 1,12874,105,105,105
BEGIN DESCRIPTION:
Mapping XS d99863ad
END DESCRIPTION:
XS GIS Cut Line= 4
      2764648.23     10099192.18      2764066.60     10099059.79
      2763780.15     10099148.77      2763463.40     10099608.69
#Sta/Elev= 30
  4273.9 1938.58  4345.4 1930.68  4466.5 1923.19  4537.2 1917.14  4591.6 1911.02
  4605.9 1907.02  4642.9 1893.13  4648.9 1889.65  4704.4 1873.05  4737.6 1870.27
  4837.9 1862.37  4917.8 1859.44  4920.6 1858.94  4923.8 1859.44  4941.2 1861.15
  4967.9 1864.04  5005.7 1863.63  5045.9 1867.18  5070.9 1870.34  5098.2 1871.53
  5141.2 1877.86  5197.2 1883.25  5255.9 1885.65  5321.2 1889.25  5363.6 1893.93
  5391.3 1900.15  5463.0 1905.86  5519.8 1913.60  5611.4 1918.51  5728.8 1927.89
#Mann=12,-1,0
  4273.9     0.1       0  4537.2    0.16       0  4737.6    0.05       0
  4837.9    0.16       0  4917.8    0.07       0  4923.8    0.16       0
  4941.2     0.1       0  5045.9    0.05       0  5255.9     0.1       0
  5321.2    0.05       0  5363.6     0.1       0  5611.4    0.16       0
Bank Sta=4917.8,4923.8
Exp/Cntr=0.3,0.1

Type RM Length L Ch R = 1,12769,736,736,736
BEGIN DESCRIPTION:
MAYER CREEK 28.0
END DESCRIPTION:
XS GIS Cut Line= 3
      2764402.97     10098873.16      2763810.53     10099027.24
      2763467.64     10099543.74
#Sta/Elev= 30
  4494.5 1913.24  4495.6 1913.24  4510.6 1912.20  4540.5 1907.86  4550.8 1904.00
  4556.2 1899.44  4612.8 1880.14  4743.4 1867.36  4933.1 1852.97  4956.3 1855.36
  5002.5 1844.58  5005.2 1844.08  5008.5 1844.58  5010.4 1845.28  5026.1 1853.97
  5032.2 1862.23  5037.4 1862.04  5046.8 1867.04  5078.4 1868.12  5119.3 1869.73
  5211.7 1875.85  5243.2 1880.35  5310.3 1883.08  5326.4 1883.99  5393.6 1888.29
  5441.2 1897.85  5501.2 1905.86  5555.9 1912.74  5639.0 1917.46  5726.6 1923.72
#Mann=16,-1,0
  4494.5    0.16       0  4495.6     0.1       0  4510.6    0.16       0
  4743.4    0.05       0  5002.5   0.035       0  5008.5    0.05       0
  5010.4     0.1       0  5078.4    0.05       0  5119.3     0.1       0
  5211.7    0.05       0  5310.3     0.1       0  5326.4    0.05       0
  5441.2     0.1       0  5501.2    0.05       0  5555.9     0.1       0
  5639.0    0.16       0
Bank Sta=5002.5,5008.5
Exp/Cntr=0.3,0.1

Type RM Length L Ch R = 1,12033,322,322,322
BEGIN DESCRIPTION:
MAYER CREEK 27.0
END DESCRIPTION:
XS GIS Cut Line= 3
      2764554.91     10098232.97      2764142.56     10098217.78
      2763517.57     10098512.91
#Sta/Elev= 30
  4294.4 1902.51  4330.9 1896.70  4360.9 1886.83  4370.9 1885.49  4495.8 1876.82
  4568.3 1873.49  4651.1 1871.33  4701.1 1871.66  4728.1 1866.89  4798.7 1858.86
  4826.7 1857.47  4902.5 1851.70  4946.4 1846.88  4963.6 1843.18  4996.1 1841.48
  4998.8 1840.98  5002.1 1841.48  5014.7 1841.93  5060.2 1850.77  5179.6 1862.60
  5248.9 1879.26  5270.7 1884.80  5316.2 1893.72  5321.7 1893.78  5339.0 1899.00
  5344.5 1899.42  5361.8 1905.50  5367.3 1905.74  5382.0 1910.99  5398.2 1914.94
#Mann=10,-1,0
  4294.4    0.16       0  4495.8     0.1       0  4568.3    0.16       0
  4728.1     0.1       0  4826.7    0.16       0  4902.5     0.1       0
  4996.1    0.07       0  5002.1     0.1       0  5248.9    0.16       0
  5382.0     0.1       0
Bank Sta=4996.1,5002.1
Exp/Cntr=0.3,0.1

Type RM Length L Ch R = 1,11711,131,131,131
BEGIN DESCRIPTION:
Mapping XS 24fcf80b
END DESCRIPTION:
XS GIS Cut Line= 4
      2764365.57     10098130.80      2764060.47     10098017.06
      2763713.82     10098036.92      2763446.74     10098148.80
#Sta/Elev= 30
  4445.6 1876.32  4676.3 1862.36  4736.0 1858.28  4786.5 1853.52  4853.4 1849.62
  4928.0 1842.79  5000.6 1841.46  5003.3 1840.96  5006.6 1841.46  5033.6 1842.78
  5073.7 1848.57  5118.4 1851.88  5121.0 1853.11  5150.2 1856.37  5203.2 1865.55
  5226.9 1870.72  5232.7 1873.22  5250.7 1877.60  5274.5 1882.25  5279.9 1882.44
  5286.9 1886.33  5297.7 1888.71  5303.7 1892.16  5309.1 1893.05  5319.4 1898.43
  5327.5 1904.20  5332.9 1905.00  5341.1 1909.28  5362.8 1915.07  5408.0 1922.77
#Mann=5,-1,0
  4445.6     0.1       0  4786.5    0.16       0  4928.0     0.1       0
  5000.6    0.07       0  5006.6     0.1       0
Bank Sta=5000.6,5006.6
Exp/Cntr=0.3,0.1

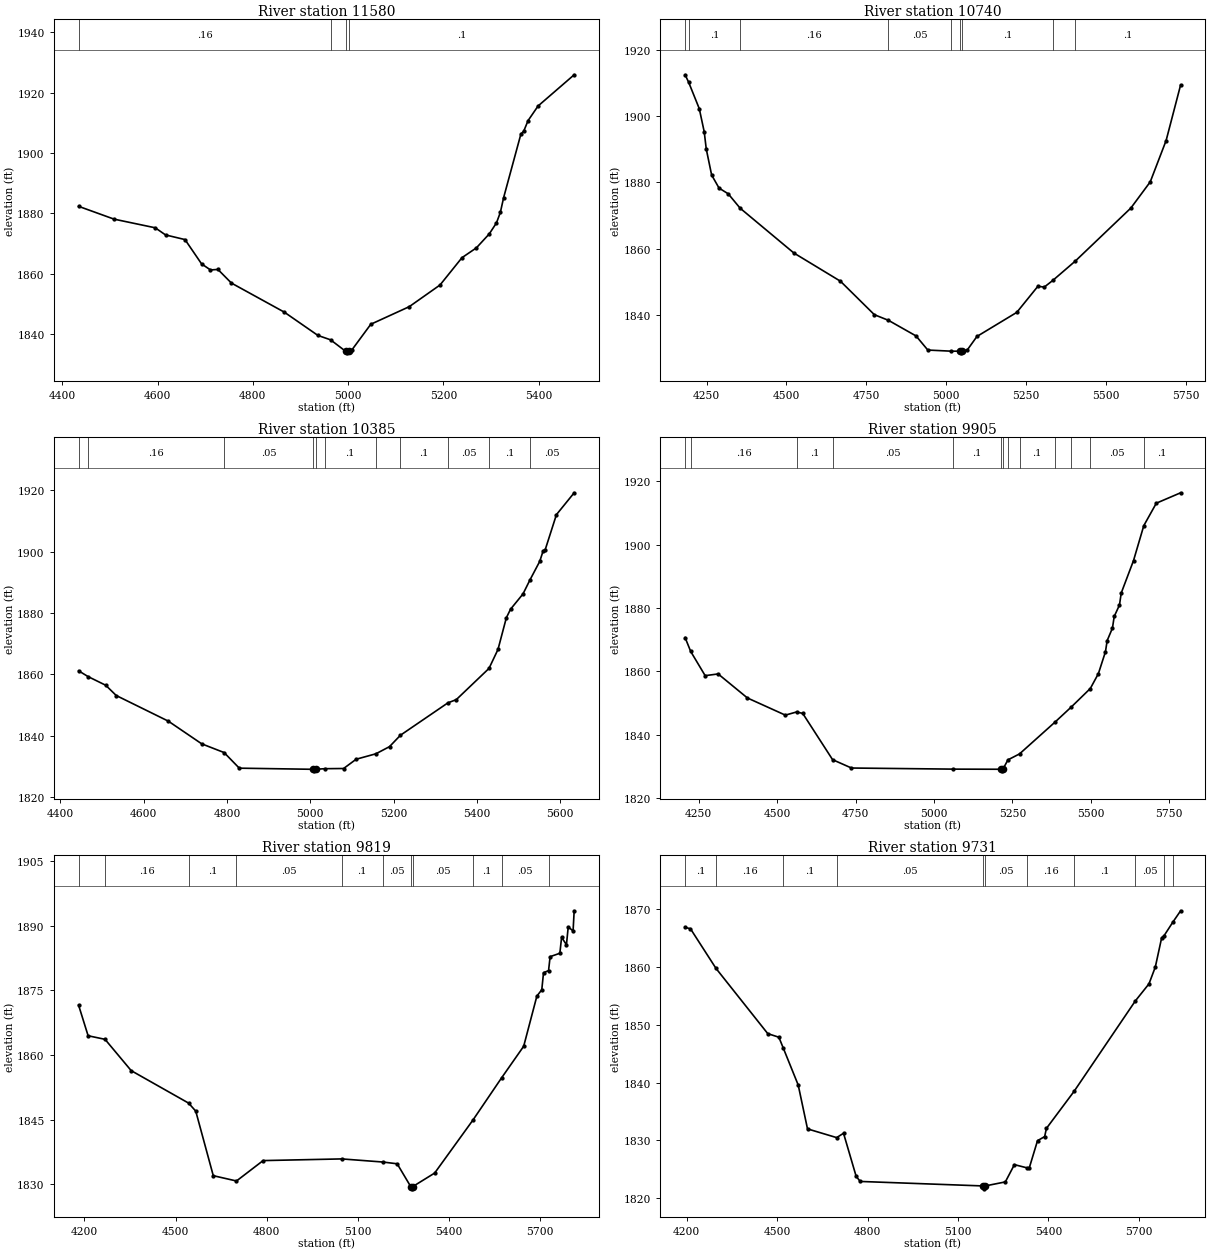
Type RM Length L Ch R = 1,11580,840,840,840
BEGIN DESCRIPTION:
MAYER CREEK 25.0
END DESCRIPTION:
XS GIS Cut Line= 4
      2764367.39     10097753.46      2764096.58     10097863.59
      2763634.37     10097924.98      2763398.98     10098079.51
#Sta/Elev= 30
  4434.3 1882.28  4508.7 1878.03  4595.1 1875.16  4616.7 1872.80  4657.6 1871.25
  4692.4 1863.19  4711.1 1861.18  4726.7 1861.35  4755.0 1856.83  4866.0 1847.19
  4936.6 1839.46  4963.1 1838.01  4994.9 1834.19  4997.6 1833.69  5000.9 1834.19
  5007.2 1834.51  5047.6 1843.17  5128.3 1849.00  5192.9 1856.19  5239.0 1865.25
  5269.2 1868.50  5296.3 1873.14  5311.4 1876.79  5319.6 1880.29  5326.4 1885.16
  5362.6 1906.21  5368.6 1907.20  5377.7 1910.71  5398.8 1915.57  5474.5 1925.91
#Mann=4,-1,0
  4434.3    0.16       0  4963.1     0.1       0  4994.9    0.07       0
  5000.9     0.1       0
Bank Sta=4994.9,5000.9
Exp/Cntr=0.3,0.1

Type RM Length L Ch R = 1,10740,355,355,355
BEGIN DESCRIPTION:
MAYER CREEK 24.0
END DESCRIPTION:
XS GIS Cut Line= 3
      2764478.92     10097362.74      2764047.07     10097169.60
      2762973.18     10097091.50
#Sta/Elev= 30
  4183.0 1912.44  4194.2 1910.17  4227.3 1902.24  4242.8 1895.26  4249.2 1890.07
  4266.0 1882.23  4289.2 1878.29  4317.9 1876.57  4355.1 1872.24  4523.1 1858.74
  4668.9 1850.23  4775.0 1840.14  4818.9 1838.45  4905.3 1833.74  4942.1 1829.49
  5015.6 1829.15  5042.7 1829.15  5045.4 1828.65  5048.7 1829.15  5065.8 1829.56
  5095.8 1833.59  5220.3 1840.84  5286.3 1848.70  5306.4 1848.47  5333.4 1850.50
  5403.5 1856.31  5577.1 1872.28  5637.7 1880.16  5687.4 1892.63  5732.8 1909.40
#Mann=9,-1,0
  4183.0    0.16       0  4194.2     0.1       0  4355.1    0.16       0
  4818.9    0.05       0  5015.6     0.1       0  5042.7   0.033       0
  5048.7     0.1       0  5333.4    0.05       0  5403.5     0.1       0
Bank Sta=5042.7,5048.7
Exp/Cntr=0.3,0.1

Type RM Length L Ch R = 1,10385,480,480,480
BEGIN DESCRIPTION:
MAYER CREEK 23.0
END DESCRIPTION:
XS GIS Cut Line= 2
      2764293.49     10096824.01      2763105.91     10096754.56
#Sta/Elev= 30
  4444.1 1861.19  4466.9 1859.30  4509.2 1856.48  4534.4 1853.14  4659.5 1844.78
  4739.6 1837.39  4793.3 1834.55  4829.8 1829.46  5007.1 1829.09  5009.8 1828.59
  5013.1 1829.09  5034.7 1829.29  5080.2 1829.35  5110.3 1832.37  5157.8 1834.15
  5190.4 1836.48  5216.7 1840.20  5330.6 1850.75  5350.7 1851.80  5429.2 1861.97
  5450.8 1868.15  5470.9 1878.49  5480.9 1881.26  5510.9 1886.26  5527.8 1890.88
  5551.0 1896.85  5559.2 1900.27  5564.2 1900.68  5591.1 1912.09  5633.7 1919.22
#Mann=11,-1,0
  4444.1     0.1       0  4466.9    0.16       0  4793.3    0.05       0
  5007.1   0.033       0  5013.1    0.05       0  5034.7     0.1       0
  5157.8    0.05       0  5216.7     0.1       0  5330.6    0.05       0
  5429.2     0.1       0  5527.8    0.05       0
Bank Sta=5007.1,5013.1
Exp/Cntr=0.3,0.1

Type RM Length L Ch R = 1,9905,86,86,86
BEGIN DESCRIPTION:
Mapping XS 5d40b209
END DESCRIPTION:
XS GIS Cut Line= 4
      2764460.12     10096462.90      2763897.62     10096310.12
      2763522.62     10096317.07      2762967.04     10096594.86
#Sta/Elev= 30
  4206.9 1870.64  4224.8 1866.25  4270.8 1858.61  4312.2 1859.15  4405.5 1851.56
  4526.3 1846.14  4562.0 1847.13  4581.7 1846.69  4676.9 1832.07  4737.1 1829.43
  5061.7 1829.08  5213.5 1829.04  5216.3 1828.54  5219.5 1829.04  5235.7 1832.01
  5272.6 1833.89  5385.4 1843.91  5438.0 1848.75  5498.2 1854.55  5524.0 1859.27
  5546.4 1866.16  5551.9 1869.69  5568.7 1873.63  5574.3 1877.30  5591.1 1880.93
  5596.7 1884.71  5635.8 1894.95  5668.6 1906.00  5708.5 1913.09  5786.0 1916.38
#Mann=13,-1,0
  4206.9     0.1       0  4224.8    0.16       0  4562.0     0.1       0
  4676.9    0.05       0  5061.7     0.1       0  5213.5   0.033       0
  5219.5     0.1       0  5235.7    0.05       0  5272.6     0.1       0
  5385.4    0.05       0  5438.0     0.1       0  5498.2    0.05       0
  5668.6     0.1       0
Bank Sta=5213.5,5219.5
Exp/Cntr=0.3,0.1

Type RM Length L Ch R = 1,9819,88,88,88
BEGIN DESCRIPTION:
Mapping XS 8cad73ea
END DESCRIPTION:
XS GIS Cut Line= 4
      2764478.76     10096370.88      2763916.29     10096232.00
      2763451.01     10096225.05      2762938.07     10096509.25
#Sta/Elev= 30
  4180.9 1871.54  4212.1 1864.48  4267.8 1863.65  4353.9 1856.39  4542.9 1848.86
  4566.4 1847.00  4624.1 1832.03  4700.5 1830.80  4788.1 1835.53  5047.0 1835.92
  5181.8 1835.20  5229.4 1834.79  5274.2 1829.48  5277.0 1828.98  5280.2 1829.48
  5352.8 1832.64  5478.7 1844.92  5573.3 1854.74  5645.8 1862.04  5689.3 1873.69
  5705.4 1875.14  5711.1 1879.10  5727.7 1879.59  5732.8 1882.82  5764.9 1883.61
  5770.6 1887.31  5786.6 1885.59  5792.4 1889.72  5808.4 1888.78  5812.0 1893.46
#Mann=11,-1,0
  4180.9     0.1       0  4267.8    0.16       0  4542.9     0.1       0
  4700.5    0.05       0  5047.0     0.1       0  5181.8    0.05       0
  5274.2   0.033       0  5280.2    0.05       0  5478.7     0.1       0
  5573.3    0.05       0  5727.7     0.1       0
Bank Sta=5274.2,5280.2
Exp/Cntr=0.3,0.1

Type RM Length L Ch R = 1,9731,625,625,625
BEGIN DESCRIPTION:
MAYER CREEK 22.0
END DESCRIPTION:
XS GIS Cut Line= 4
      2764453.14     10096282.34      2763849.01     10096136.51
      2763342.07     10096150.40      2762912.51     10096434.46
#Sta/Elev= 30
  4195.0 1866.88  4212.8 1866.65  4297.7 1859.77  4469.2 1848.49  4506.0 1847.87
  4520.8 1845.97  4570.2 1839.59  4601.0 1832.00  4697.6 1830.49  4720.5 1831.24
  4762.4 1823.78  4775.9 1822.90  5184.2 1822.12  5186.9 1821.62  5190.2 1822.12
  5257.2 1822.82  5287.2 1825.81  5330.0 1825.24  5336.3 1825.20  5363.9 1829.96
  5387.5 1830.66  5393.5 1832.09  5485.2 1838.50  5688.3 1854.15  5733.6 1857.11
  5754.6 1860.02  5775.7 1865.10  5782.8 1865.38  5813.6 1867.86  5838.6 1869.76
#Mann=11,-1,0
  4195.0     0.1       0  4297.7    0.16       0  4520.8     0.1       0
  4697.6    0.05       0  5184.2   0.033       0  5190.2    0.05       0
  5330.0    0.16       0  5485.2     0.1       0  5688.3    0.05       0
  5782.8     0.1       0  5813.6    0.05       0
Bank Sta=5184.2,5190.2
Exp/Cntr=0.3,0.1

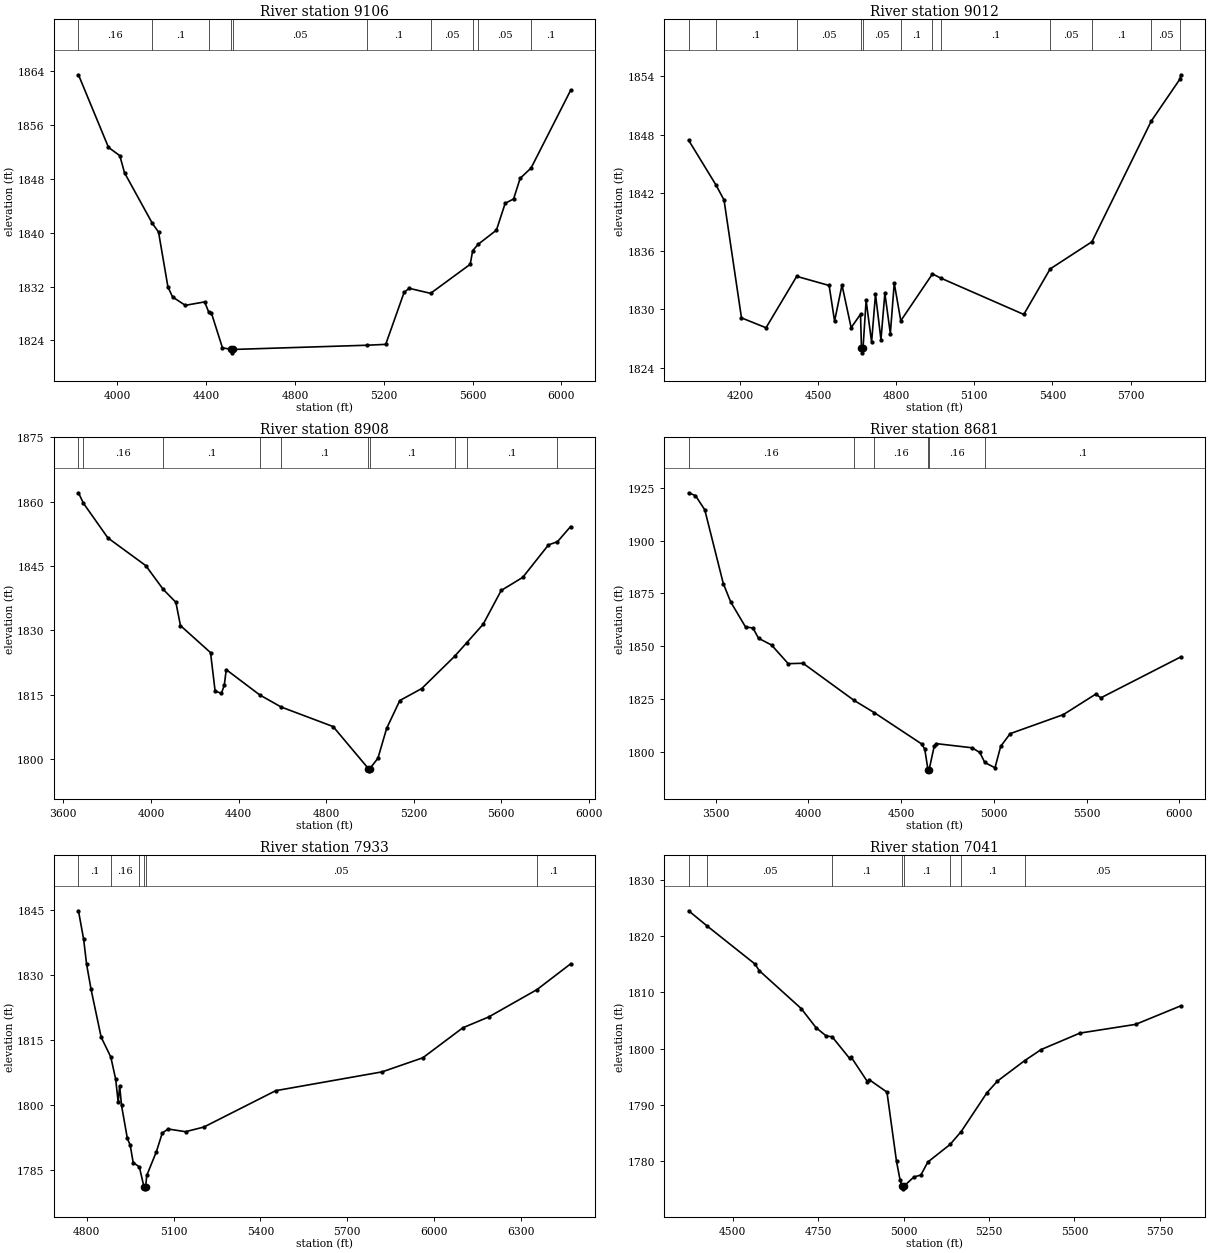
Type RM Length L Ch R = 1,9106,94,94,94
BEGIN DESCRIPTION:
MAYER CREEK 21.0
END DESCRIPTION:
XS GIS Cut Line= 4
      2764439.31     10096171.25      2763536.51     10095574.01
      2763237.90     10095560.12      2762487.94     10095928.16
#Sta/Elev= 30
  3824.4 1863.48  3959.6 1852.69  4010.7 1851.46  4031.8 1848.92  4157.2 1841.40
  4185.1 1840.11  4227.4 1831.95  4248.4 1830.46  4305.6 1829.22  4392.9 1829.73
  4411.5 1828.18  4423.0 1828.10  4472.9 1822.91  4513.3 1822.66  4516.0 1822.16
  4519.3 1822.66  5123.5 1823.29  5208.3 1823.42  5291.1 1831.14  5313.6 1831.75
  5410.5 1831.00  5589.0 1835.32  5600.1 1837.35  5625.6 1838.31  5707.0 1840.39
  5746.4 1844.38  5784.4 1845.03  5813.9 1848.09  5863.2 1849.63  6041.2 1861.17
#Mann=10,-1,0
  3824.4    0.16       0  4157.2     0.1       0  4411.5    0.05       0
  4513.3   0.033       0  4519.3    0.05       0  5123.5     0.1       0
  5410.5    0.05       0  5600.1     0.1       0  5625.6    0.05       0
  5863.2     0.1       0
Bank Sta=4513.3,4519.3
Exp/Cntr=0.3,0.1

Type RM Length L Ch R = 1,9012,104,104,104
BEGIN DESCRIPTION:
Mapping XS 7d659a65
END DESCRIPTION:
XS GIS Cut Line= 6
      2764260.89     10095969.64      2763538.68     10095471.32
      2763143.28     10095523.68      2763045.78     10095577.84
      2762897.73     10095576.04      2762572.22     10095700.13
#Sta/Elev= 30
  4003.3 1847.41  4107.1 1842.86  4139.1 1841.27  4206.1 1829.14  4300.3 1828.12
  4418.2 1833.41  4542.6 1832.47  4563.5 1828.80  4592.0 1832.52  4627.1 1828.13
  4663.1 1829.51  4666.8 1826.04  4669.5 1825.54  4672.8 1826.04  4684.6 1830.94
  4705.6 1826.64  4720.6 1831.56  4741.6 1826.90  4756.6 1831.67  4777.6 1827.52
  4792.6 1832.71  4817.7 1828.84  4939.3 1833.66  4972.1 1833.22  5289.9 1829.49
  5391.0 1834.17  5551.5 1836.97  5779.4 1849.39  5888.9 1853.69  5892.7 1854.15
#Mann=12,-1,0
  4003.3    0.16       0  4107.1     0.1       0  4418.2    0.05       0
  4666.8    0.07       0  4672.8    0.05       0  4817.7     0.1       0
  4939.3    0.05       0  4972.1     0.1       0  5391.0    0.05       0
  5551.5     0.1       0  5779.4    0.05       0  5888.9     0.1       0
Bank Sta=4666.8,4672.8
Exp/Cntr=0.3,0.1

Type RM Length L Ch R = 1,8908,227,227,227
BEGIN DESCRIPTION:
MAYER CREEK 20.0
END DESCRIPTION:
XS GIS Cut Line= 4
      2764536.52     10096053.18      2763557.35     10095379.57
      2763217.07     10095372.62      2762557.34     10095657.35
#Sta/Elev= 30
  3669.1 1862.08  3691.6 1859.66  3803.4 1851.57  3976.6 1845.11  4056.1 1839.58
  4113.9 1836.57  4134.9 1831.14  4272.2 1824.85  4293.2 1815.84  4322.2 1815.40
  4335.1 1817.29  4343.9 1820.88  4496.7 1815.00  4594.2 1812.19  4832.0 1807.62
  4993.5 1797.81  4996.3 1797.31  4999.5 1797.81  5036.5 1800.24  5076.5 1807.22
  5136.5 1813.69  5236.6 1816.48  5386.4 1823.97  5442.6 1827.18  5517.0 1831.45
  5599.4 1839.32  5697.9 1842.38  5815.4 1849.94  5856.5 1850.69  5916.5 1854.22
#Mann=10,-1,0
  3669.1     0.1       0  3691.6    0.16       0  4056.1     0.1       0
  4496.7    0.05       0  4594.2     0.1       0  4993.5    0.07       0
  4999.5     0.1       0  5386.4    0.05       0  5442.6     0.1       0
  5856.5    0.05       0
Bank Sta=4993.5,4999.5
Exp/Cntr=0.3,0.1

Type RM Length L Ch R = 1,8681,748,748,748
BEGIN DESCRIPTION:
MAYER CREEK 19.0
END DESCRIPTION:
XS GIS Cut Line= 4
      2765055.34     10095286.67      2764055.30     10095293.61
      2763048.36     10095071.39      2762444.21     10095224.17
#Sta/Elev= 30
  3353.6 1922.68  3390.5 1921.33  3440.5 1914.62  3540.5 1879.63  3580.5 1870.90
  3660.5 1859.03  3700.5 1858.57  3730.5 1853.68  3800.5 1850.51  3890.5 1841.65
  3970.5 1841.84  4245.3 1824.26  4355.3 1818.40  4609.9 1803.60  4626.9 1801.17
  4644.4 1791.33  4647.1 1790.83  4650.4 1791.33  4678.1 1802.53  4688.4 1803.74
  4882.3 1801.76  4923.9 1799.54  4950.7 1794.79  5005.8 1792.28  5036.5 1802.44
  5087.7 1808.46  5374.5 1817.49  5549.8 1827.24  5576.7 1825.44  6008.0 1844.86
#Mann=6,-1,0
  3353.6    0.16       0  4245.3     0.1       0  4355.3    0.16       0
  4644.4    0.07       0  4650.4    0.16       0  4950.7     0.1       0
Bank Sta=4644.4,4650.4
Exp/Cntr=0.3,0.1

Type RM Length L Ch R = 1,7933,892,892,892
BEGIN DESCRIPTION:
MAYER CREEK 18.0
END DESCRIPTION:
XS GIS Cut Line= 3
      2764106.41     10094633.29      2763304.31     10094549.96
      2762523.29     10094984.72
#Sta/Elev= 30
  4771.5 1844.74  4789.5 1838.12  4799.6 1832.40  4815.1 1826.60  4849.9 1815.58
  4883.1 1811.04  4900.1 1805.89  4908.8 1800.56  4913.8 1804.39  4920.2 1799.87
  4940.4 1792.24  4950.4 1790.66  4960.5 1786.66  4981.8 1785.67  4997.7 1781.11
  5000.4 1780.61  5003.7 1781.11  5007.4 1783.69  5040.9 1789.21  5061.0 1793.47
  5081.1 1794.41  5141.4 1793.79  5204.7 1794.86  5453.1 1803.25  5820.7 1807.59
  5961.3 1810.84  6099.6 1817.76  6188.8 1820.25  6354.9 1826.53  6471.8 1832.50
#Mann=6,-1,0
  4771.5     0.1       0  4883.1    0.16       0  4981.8    0.05       0
  4997.7   0.035       0  5003.7    0.05       0  6354.9     0.1       0
Bank Sta=4997.7,5003.7
Exp/Cntr=0.3,0.1

Type RM Length L Ch R = 1,7041,710,710,710
BEGIN DESCRIPTION:
MAYER CREEK 16.0
END DESCRIPTION:
XS GIS Cut Line= 4
      2764273.03     10093961.41      2763887.64     10093836.41
      2763369.41     10093935.37      2762999.62     10094281.72
#Sta/Elev= 30
  4371.6 1824.56  4425.0 1821.88  4565.6 1815.07  4578.1 1813.89  4700.7 1807.14
  4744.3 1803.72  4773.7 1802.26  4791.3 1802.10  4842.3 1798.25  4847.3 1798.44
  4894.4 1794.11  4899.5 1794.46  4951.6 1792.24  4979.5 1779.90  4989.7 1776.66
  4995.6 1775.50  4998.3 1775.00  5001.6 1775.50  5030.4 1777.11  5050.7 1777.46
  5071.2 1779.78  5136.2 1782.91  5168.7 1785.21  5244.2 1792.14  5274.8 1794.21
  5354.3 1797.85  5402.7 1799.83  5516.0 1802.76  5678.7 1804.31  5811.0 1807.62
#Mann=8,-1,0
  4371.6     0.1       0  4425.0    0.05       0  4791.3     0.1       0
  4995.6    0.07       0  5001.6     0.1       0  5136.2    0.16       0
  5168.7     0.1       0  5354.3    0.05       0
Bank Sta=4995.6,5001.6
Exp/Cntr=0.3,0.1