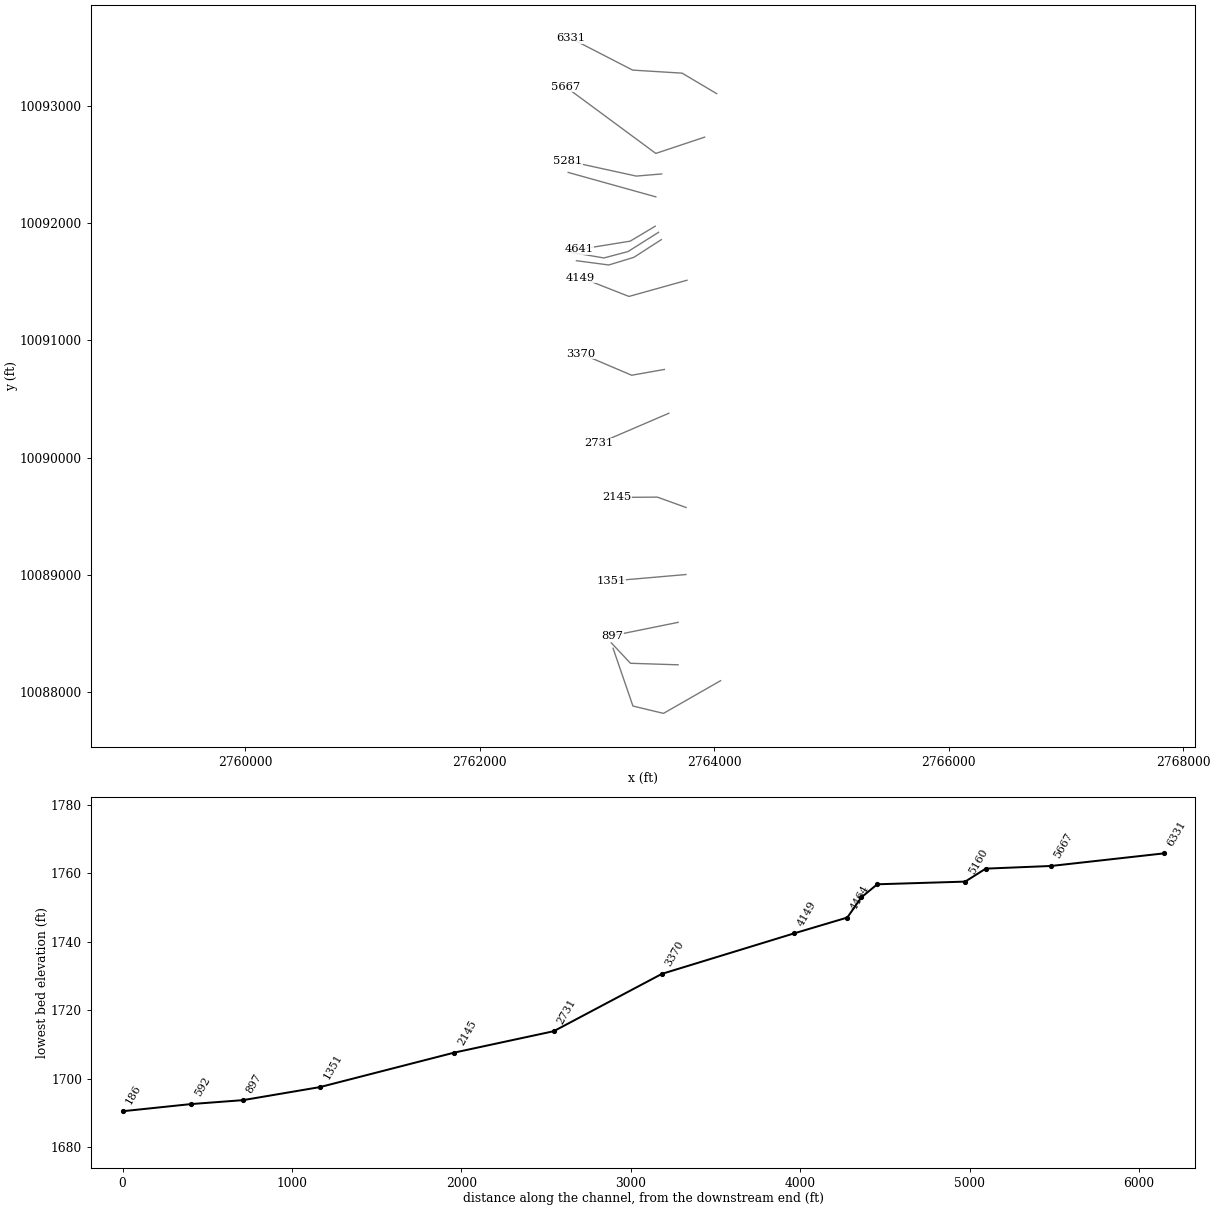
HEC-RAS study MAYER CREEK.prj: MAYER CREEK Base Level Engineering

--- MAYER CREEK.g01 (geometry) --- (continued)

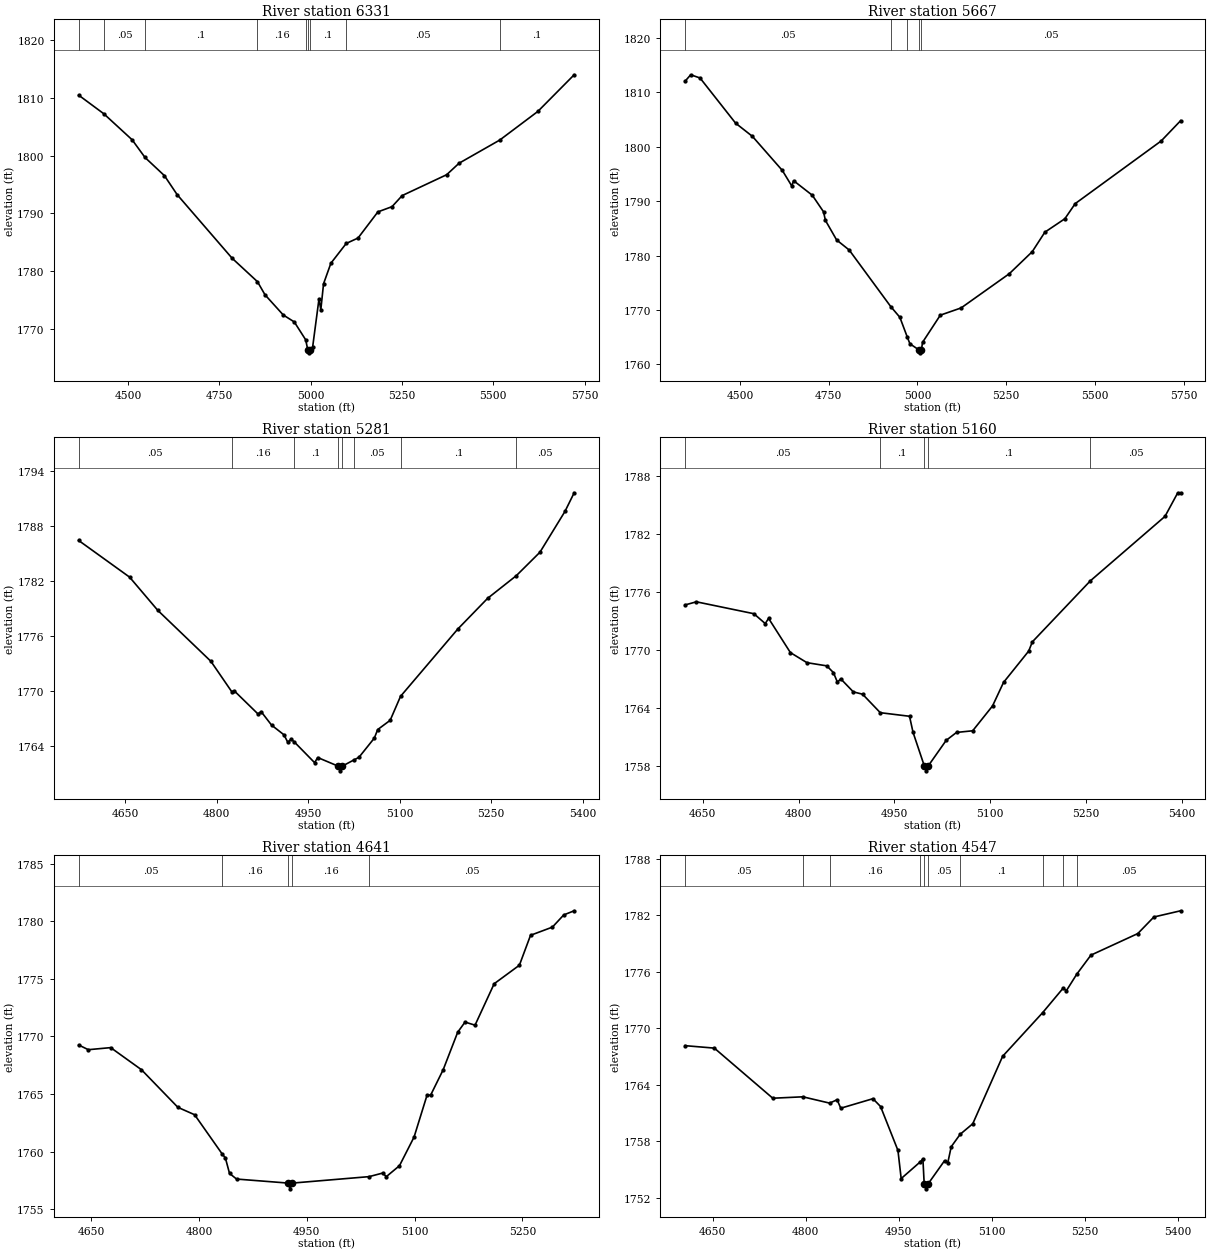
Type RM Length L Ch R = 1,6331,664,664,664
BEGIN DESCRIPTION:
MAYER CREEK 14.0
END DESCRIPTION:
XS GIS Cut Line= 4
      2764020.43     10093104.66      2763726.18     10093279.12
      2763304.31     10093305.16      2762778.29     10093575.99
#Sta/Elev= 30
  4365.1 1810.47  4434.0 1807.24  4511.5 1802.73  4546.8 1799.66  4599.9 1796.51
  4634.8 1793.21  4785.0 1782.20  4854.6 1778.12  4875.2 1775.85  4925.3 1772.34
  4955.4 1771.14  4986.6 1768.04  4992.4 1766.28  4995.2 1765.78  4998.4 1766.28
  5005.5 1766.72  5023.0 1775.13  5028.0 1773.25  5035.5 1777.76  5055.6 1781.32
  5097.6 1784.75  5129.9 1785.69  5184.2 1790.22  5222.9 1791.13  5250.7 1793.05
  5372.5 1796.67  5406.4 1798.66  5517.8 1802.68  5622.0 1807.64  5721.5 1814.00
#Mann=9,-1,0
  4365.1     0.1       0  4434.0    0.05       0  4546.8     0.1       0
  4854.6    0.16       0  4986.6     0.1       0  4992.4    0.07       0
  4998.4     0.1       0  5097.6    0.05       0  5517.8     0.1       0
Bank Sta=4992.4,4998.4
Exp/Cntr=0.3,0.1

Type RM Length L Ch R = 1,5667,386,386,386
BEGIN DESCRIPTION:
MAYER CREEK 13.0
END DESCRIPTION:
XS GIS Cut Line= 3
      2763918.44     10092733.73      2763501.79     10092594.84
      2762732.20     10093163.37
#Sta/Elev= 30
  4345.5 1812.07  4361.3 1813.25  4387.6 1812.66  4487.8 1804.35  4535.2 1801.92
  4619.5 1795.65  4645.9 1792.81  4651.2 1793.77  4703.9 1791.09  4735.5 1788.05
  4740.8 1786.47  4772.4 1782.87  4807.8 1781.02  4924.8 1770.62  4950.5 1768.65
  4971.2 1765.05  4978.9 1763.77  5005.2 1762.61  5008.0 1762.11  5011.2 1762.61
  5014.4 1764.04  5064.5 1769.04  5123.1 1770.37  5258.8 1776.66  5323.4 1780.71
  5359.0 1784.30  5415.3 1786.77  5444.6 1789.56  5686.7 1801.08  5741.5 1804.81
#Mann=5,-1,0
  4345.5    0.05       0  4924.8    0.16       0  4971.2    0.05       0
  5005.2   0.035       0  5011.2    0.05       0
Bank Sta=5005.2,5011.2
Exp/Cntr=0.3,0.1

Type RM Length L Ch R = 1,5281,121,121,121
BEGIN DESCRIPTION:
Mapping XS d81dc71d
END DESCRIPTION:
XS GIS Cut Line= 3
      2763551.67     10092419.74      2763335.56     10092401.52
      2762753.69     10092528.80
#Sta/Elev= 30
  4573.4 1786.41  4656.9 1782.42  4703.2 1778.80  4790.3 1773.25  4824.5 1769.94
  4828.7 1770.03  4867.5 1767.52  4872.6 1767.78  4889.7 1766.31  4910.1 1765.25
  4916.4 1764.43  4921.6 1764.78  4926.5 1764.51  4960.3 1762.22  4965.4 1762.78
  4999.3 1761.83  5002.0 1761.33  5005.3 1761.83  5024.3 1762.50  5033.0 1762.80
  5058.3 1764.90  5063.7 1765.82  5084.2 1766.83  5101.2 1769.44  5195.0 1776.76
  5244.0 1780.11  5291.1 1782.58  5329.8 1785.13  5370.8 1789.57  5385.9 1791.60
#Mann=8,-1,0
  4573.4    0.05       0  4824.5    0.16       0  4926.5     0.1       0
  4999.3    0.07       0  5005.3     0.1       0  5024.3    0.05       0
  5101.2     0.1       0  5291.1    0.05       0
Bank Sta=4999.3,5005.3
Exp/Cntr=0.3,0.1

Type RM Length L Ch R = 1,5160,519,519,519
BEGIN DESCRIPTION:
MAYER CREEK 11.0
END DESCRIPTION:
XS GIS Cut Line= 2
      2763502.23     10092224.43      2762754.82     10092432.77
#Sta/Elev= 30
  4622.3 1774.69  4640.0 1775.01  4730.0 1773.78  4747.8 1772.76  4753.0 1773.30
  4787.2 1769.76  4813.1 1768.72  4844.2 1768.39  4854.6 1767.69  4860.8 1766.70
  4866.0 1767.05  4885.7 1765.70  4900.2 1765.46  4927.9 1763.55  4973.7 1763.18
  4979.2 1761.52  4996.9 1758.04  4999.7 1757.54  5002.9 1758.04  5031.1 1760.69
  5047.3 1761.51  5072.6 1761.68  5103.7 1764.25  5120.9 1766.68  5160.3 1769.92
  5166.0 1770.87  5256.7 1777.17  5373.7 1783.84  5393.7 1786.28  5398.2 1786.28
#Mann=5,-1,0
  4622.3    0.05       0  4927.9     0.1       0  4996.9    0.07       0
  5002.9     0.1       0  5256.7    0.05       0
Bank Sta=4996.9,5002.9
Exp/Cntr=0.3,0.1

Type RM Length L Ch R = 1,4641,94,94,94
BEGIN DESCRIPTION:
Mapping XS 8233d876
END DESCRIPTION:
XS GIS Cut Line= 3
      2763497.02     10091974.44      2763283.47     10091846.83
      2762848.59     10091776.52
#Sta/Elev= 30
  4632.7 1769.26  4646.2 1768.85  4677.3 1769.03  4720.1 1767.11  4770.8 1763.84
  4794.0 1763.20  4832.6 1759.77  4836.8 1759.45  4842.6 1758.10  4852.4 1757.61
  4924.1 1757.26  4926.8 1756.76  4930.1 1757.26  5036.7 1757.82  5055.6 1758.13
  5060.7 1757.82  5079.0 1758.77  5099.3 1761.26  5117.3 1764.89  5122.4 1764.91
  5139.8 1767.11  5160.0 1770.37  5170.2 1771.25  5184.1 1770.98  5210.7 1774.58
  5245.8 1776.19  5261.3 1778.79  5291.7 1779.50  5307.5 1780.56  5322.0 1780.92
#Mann=5,-1,0
  4632.7    0.05       0  4832.6    0.16       0  4924.1    0.07       0
  4930.1    0.16       0  5036.7    0.05       0
Bank Sta=4924.1,4930.1
Exp/Cntr=0.3,0.1

Type RM Length L Ch R = 1,4547,83,83,83
BEGIN DESCRIPTION:
Mapping XS 1a697159
END DESCRIPTION:
XS GIS Cut Line= 4
      2763525.63     10091922.33      2763265.24     10091758.29
      2763059.51     10091703.60      2762786.03     10091750.48
#Sta/Elev= 30
  4605.8 1768.14  4652.9 1767.88  4747.0 1762.56  4795.5 1762.71  4838.6 1762.04
  4850.6 1762.40  4856.5 1761.50  4908.3 1762.51  4920.6 1761.68  4948.6 1757.02
  4953.8 1754.03  4984.5 1755.80  4988.8 1756.11  4990.9 1753.44  4993.7 1752.94
  4996.9 1753.44  5023.7 1755.93  5028.9 1755.71  5034.4 1757.41  5048.8 1758.73
  5069.1 1759.85  5117.2 1767.01  5181.6 1771.64  5214.6 1774.24  5219.9 1773.98
  5236.6 1775.73  5259.4 1777.75  5334.9 1780.04  5360.8 1781.80  5403.9 1782.46
#Mann=10,-1,0
  4605.8    0.05       0  4795.5     0.1       0  4838.6    0.16       0
  4984.5    0.05       0  4990.9   0.035       0  4996.9    0.05       0
  5048.8     0.1       0  5181.6    0.05       0  5214.6     0.1       0
  5236.6    0.05       0
Bank Sta=4990.9,4996.9
Exp/Cntr=0.3,0.1

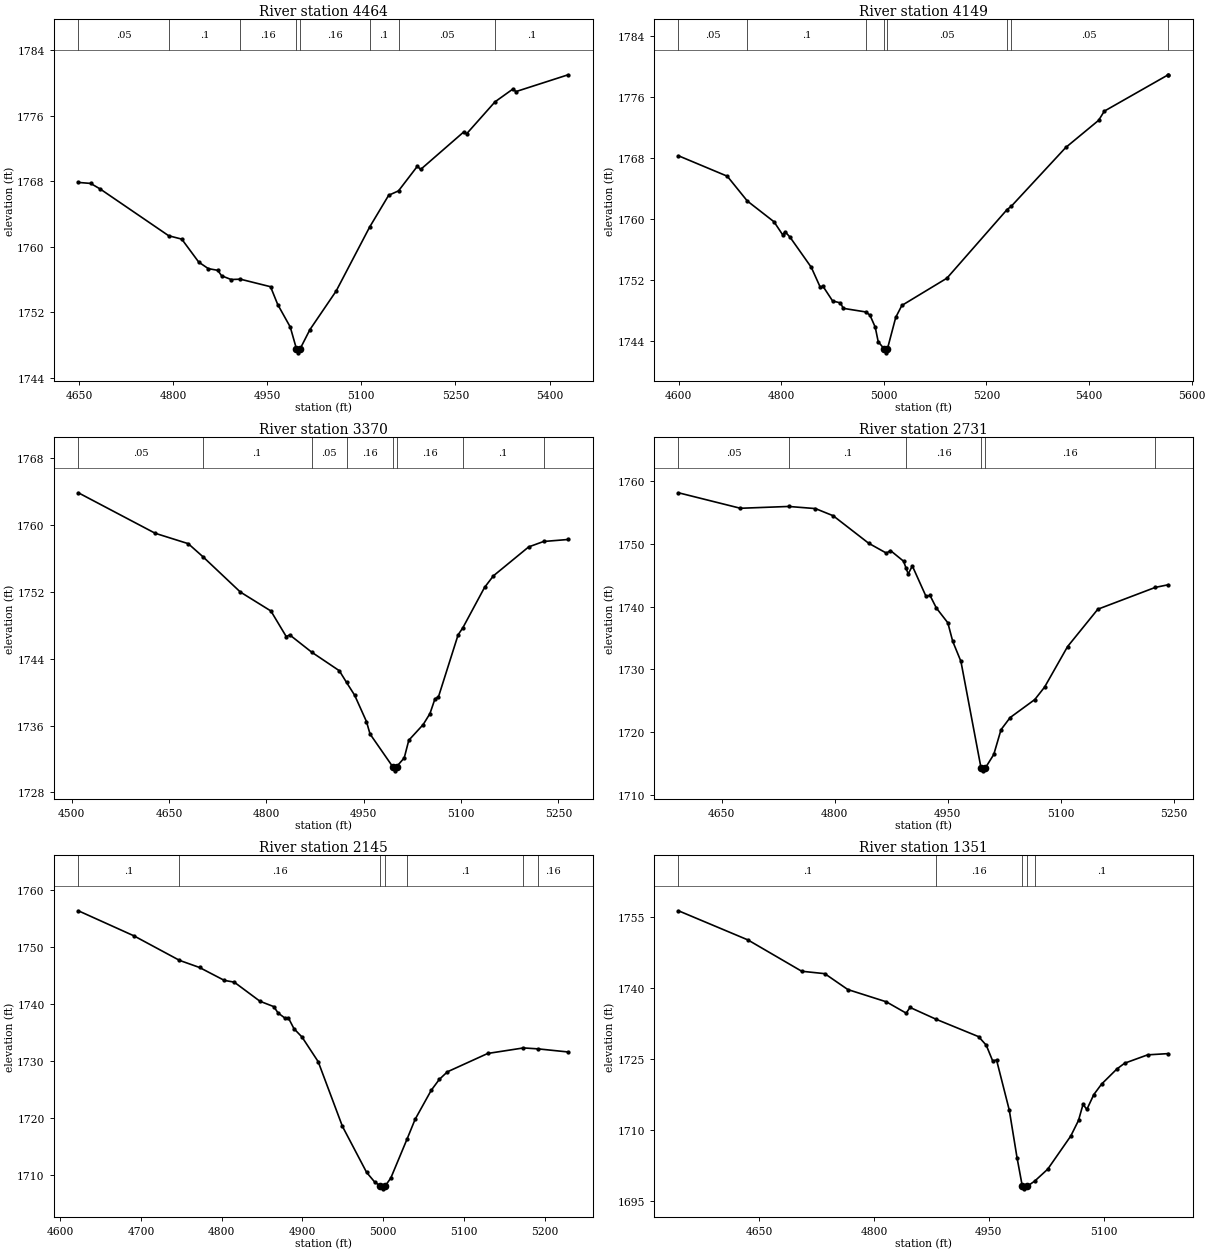
Type RM Length L Ch R = 1,4464,315,315,315
BEGIN DESCRIPTION:
Mapping XS 4b942d09
END DESCRIPTION:
XS GIS Cut Line= 4
      2763549.12     10091859.86      2763314.72     10091708.81
      2763101.18     10091643.71      2762825.18     10091680.16
#Sta/Elev= 30
  4649.1 1767.84  4668.7 1767.72  4683.9 1767.04  4793.1 1761.33  4813.9 1760.92
  4841.0 1758.11  4856.2 1757.32  4871.3 1757.11  4877.3 1756.45  4892.5 1755.99
  4907.3 1756.03  4955.4 1755.11  4966.8 1752.94  4986.8 1750.19  4996.6 1747.54
  4999.4 1747.04  5002.6 1747.54  5018.1 1749.87  5059.9 1754.58  5113.2 1762.38
  5143.6 1766.27  5159.3 1766.81  5189.4 1769.82  5194.5 1769.42  5262.9 1773.98
  5268.0 1773.79  5313.1 1777.68  5341.4 1779.23  5346.5 1778.93  5429.6 1780.98
#Mann=8,-1,0
  4649.1    0.05       0  4793.1     0.1       0  4907.3    0.16       0
  4996.6    0.07       0  5002.6    0.16       0  5113.2     0.1       0
  5159.3    0.05       0  5313.1     0.1       0
Bank Sta=4996.6,5002.6
Exp/Cntr=0.3,0.1

Type RM Length L Ch R = 1,4149,779,779,779
BEGIN DESCRIPTION:
MAYER CREEK 9.0
END DESCRIPTION:
XS GIS Cut Line= 3
      2763767.84     10091513.50      2763273.06     10091375.48
      2762862.51     10091536.58
#Sta/Elev= 30
  4599.7 1768.26  4694.8 1765.58  4733.8 1762.33  4785.9 1759.60  4802.5 1757.92
  4807.7 1758.28  4817.1 1757.58  4858.6 1753.62  4876.1 1751.00  4881.3 1751.14
  4900.1 1749.21  4915.4 1748.95  4920.9 1748.24  4964.4 1747.77  4972.8 1747.36
  4983.2 1745.77  4989.0 1743.86  5000.9 1742.90  5003.7 1742.40  5006.9 1742.90
  5023.2 1747.06  5035.1 1748.62  5123.0 1752.20  5240.3 1761.21  5248.2 1761.62
  5354.6 1769.35  5418.6 1772.91  5429.8 1774.12  5553.0 1778.84  5554.4 1778.89
#Mann=8,-1,0
  4599.7    0.05       0  4733.8     0.1       0  4964.4    0.05       0
  5000.9   0.035       0  5006.9    0.05       0  5240.3     0.1       0
  5248.2    0.05       0  5553.0     0.1       0
Bank Sta=5000.9,5006.9
Exp/Cntr=0.3,0.1

Type RM Length L Ch R = 1,3370,639,639,639
BEGIN DESCRIPTION:
MAYER CREEK 8.0
END DESCRIPTION:
XS GIS Cut Line= 3
      2763575.15     10090753.08      2763296.49     10090703.60
      2762862.51     10090888.11
#Sta/Elev= 30
  4510.5 1763.87  4629.0 1759.02  4679.8 1757.78  4702.4 1756.22  4760.1 1751.99
  4807.2 1749.72  4830.8 1746.66  4836.2 1746.86  4869.9 1744.80  4912.6 1742.57
  4923.7 1741.17  4936.2 1739.64  4954.4 1736.49  4959.9 1735.00  4994.8 1731.09
  4997.6 1730.59  5000.8 1731.09  5012.6 1732.14  5019.6 1734.25  5041.7 1736.12
  5052.2 1737.44  5059.9 1739.20  5065.3 1739.44  5095.6 1746.87  5102.8 1747.70
  5136.3 1752.54  5150.0 1753.93  5204.3 1757.39  5227.3 1758.04  5265.1 1758.28
#Mann=8,-1,0
  4510.5    0.05       0  4702.4     0.1       0  4869.9    0.05       0
  4923.7    0.16       0  4994.8    0.07       0  5000.8    0.16       0
  5102.8     0.1       0  5227.3    0.05       0
Bank Sta=4994.8,5000.8
Exp/Cntr=0.3,0.1

Type RM Length L Ch R = 1,2731,586,586,586
BEGIN DESCRIPTION:
MAYER CREEK 6.0
END DESCRIPTION:
XS GIS Cut Line= 2
      2763612.86     10090379.55      2763015.69     10090122.63
#Sta/Elev= 30
  4592.5 1758.15  4674.7 1755.68  4738.7 1755.97  4774.3 1755.63  4797.8 1754.49
  4844.9 1750.11  4868.5 1748.53  4873.9 1748.94  4891.2 1747.25  4894.7 1746.10
  4897.4 1745.21  4902.9 1746.49  4921.0 1741.65  4926.4 1741.78  4934.8 1739.78
  4950.0 1737.43  4956.5 1734.47  4967.4 1731.27  4994.0 1714.33  4996.8 1713.83
  5000.0 1714.33  5011.0 1716.44  5020.6 1720.39  5032.7 1722.32  5065.4 1725.19
  5078.5 1727.19  5108.9 1733.63  5149.1 1739.59  5225.4 1743.07  5242.6 1743.49
#Mann=6,-1,0
  4592.5    0.05       0  4738.7     0.1       0  4894.7    0.16       0
  4994.0    0.07       0  5000.0    0.16       0  5225.4    0.05       0
Bank Sta=4994,5000
Exp/Cntr=0.3,0.1

Type RM Length L Ch R = 1,2145,794,794,794
BEGIN DESCRIPTION:
MAYER CREEK 5.0
END DESCRIPTION:
XS GIS Cut Line= 3
      2763760.01     10089576.01      2763515.24     10089664.54
      2763168.84     10089661.93
#Sta/Elev= 30
  4622.5 1756.33  4691.3 1751.94  4747.8 1747.64  4772.6 1746.39  4803.3 1744.13
  4815.6 1743.82  4847.5 1740.47  4864.6 1739.53  4869.9 1738.42  4878.4 1737.52
  4882.8 1737.52  4889.6 1735.66  4899.6 1734.19  4919.6 1729.88  4949.6 1718.55
  4979.6 1710.47  4989.6 1708.78  4996.6 1708.09  4999.3 1707.59  5002.6 1708.09
  5009.6 1709.50  5029.9 1716.39  5039.6 1719.76  5059.6 1724.86  5069.6 1726.77
  5079.6 1728.10  5129.6 1731.32  5173.9 1732.29  5192.3 1732.12  5229.2 1731.58
#Mann=7,-1,0
  4622.5     0.1       0  4747.8    0.16       0  4996.6    0.07       0
  5002.6    0.16       0  5029.9     0.1       0  5173.9    0.05       0
  5192.3    0.16       0
Bank Sta=4996.6,5002.6
Exp/Cntr=0.3,0.1

Type RM Length L Ch R = 1,1351,454,454,454
BEGIN DESCRIPTION:
MAYER CREEK 3.0
END DESCRIPTION:
XS GIS Cut Line= 2
      2763758.76     10089004.57      2763121.66     10088949.17
#Sta/Elev= 30
  4544.8 1756.31  4635.4 1750.15  4705.7 1743.52  4735.8 1743.01  4765.9 1739.65
  4816.1 1737.06  4842.1 1734.66  4847.1 1735.87  4881.4 1733.35  4936.6 1729.69
  4946.6 1727.89  4955.0 1724.57  4960.1 1724.75  4976.7 1714.16  4986.8 1704.12
  4993.8 1698.00  4996.5 1697.50  4999.8 1698.00  5010.0 1699.15  5026.9 1701.66
  5057.0 1708.67  5067.1 1711.97  5073.0 1715.36  5078.0 1714.30  5087.1 1717.44
  5097.2 1719.65  5117.2 1722.85  5127.3 1724.07  5157.4 1725.84  5184.3 1726.10
#Mann=5,-1,0
  4544.8     0.1       0  4881.4    0.16       0  4993.8    0.07       0
  4999.8    0.16       0  5010.0     0.1       0
Bank Sta=4993.8,4999.8
Exp/Cntr=0.3,0.1

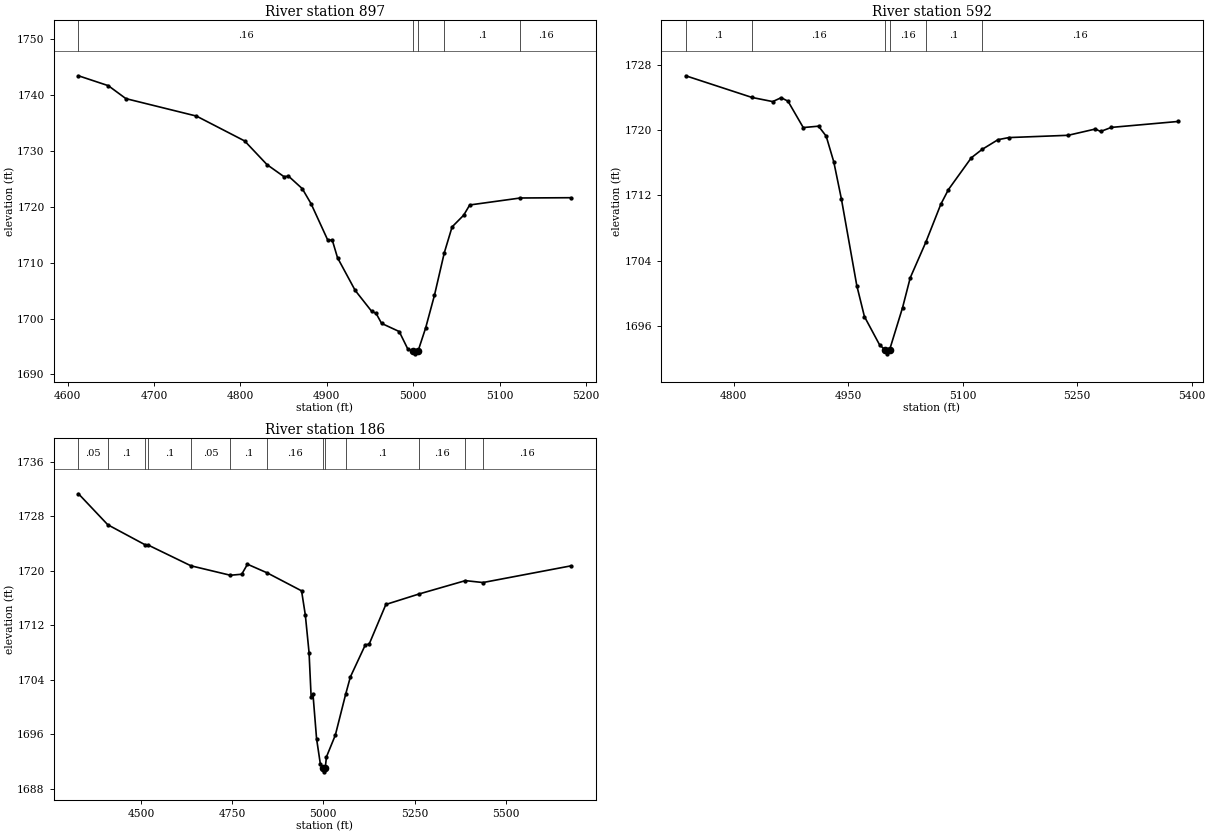
Type RM Length L Ch R = 1,897,305,305,305
BEGIN DESCRIPTION:
MAYER CREEK 2.0
END DESCRIPTION:
XS GIS Cut Line= 2
      2763692.30     10088596.82      2763133.73     10088483.73
#Sta/Elev= 30
  4612.6 1743.45  4647.1 1741.68  4667.5 1739.36  4749.1 1736.24  4804.9 1731.79
  4830.8 1727.55  4850.5 1725.39  4855.6 1725.50  4871.6 1723.25  4881.8 1720.55
  4901.2 1714.01  4906.3 1714.06  4912.4 1710.89  4932.8 1705.05  4951.9 1701.30
  4957.0 1700.94  4963.4 1699.14  4983.8 1697.68  4994.0 1694.47  4999.6 1694.19
  5002.4 1693.69  5005.6 1694.19  5014.4 1698.33  5024.6 1704.18  5036.0 1711.79
  5045.0 1716.41  5058.4 1718.50  5065.4 1720.33  5124.0 1721.58  5182.5 1721.63
#Mann=5,-1,0
  4612.6    0.16       0  4999.6    0.07       0  5005.6    0.16       0
  5036.0     0.1       0  5124.0    0.16       0
Bank Sta=4999.6,5005.6
Exp/Cntr=0.3,0.1

Type RM Length L Ch R = 1,592,406,406,406
BEGIN DESCRIPTION:
Mapping XS 9739ad41
END DESCRIPTION:
XS GIS Cut Line= 3
      2763692.31     10088234.85      2763286.08     10088247.87
      2763122.73     10088421.59
#Sta/Elev= 30
  4737.4 1726.70  4824.1 1724.04  4851.3 1723.53  4862.4 1724.01  4871.3 1723.58
  4891.3 1720.34  4911.3 1720.51  4921.3 1719.29  4931.3 1716.12  4941.3 1711.55
  4961.4 1700.94  4971.4 1697.13  4991.4 1693.63  4998.4 1693.05  5001.1 1692.55
  5004.4 1693.05  5021.4 1698.24  5031.4 1701.89  5051.9 1706.28  5071.4 1710.91
  5081.4 1712.72  5111.4 1716.63  5125.4 1717.65  5146.3 1718.85  5160.5 1719.11
  5238.2 1719.39  5273.8 1720.16  5280.7 1719.86  5294.8 1720.36  5382.3 1721.09
#Mann=6,-1,0
  4737.4     0.1       0  4824.1    0.16       0  4998.4    0.07       0
  5004.4    0.16       0  5051.9     0.1       0  5125.4    0.16       0
Bank Sta=4998.4,5004.4
Exp/Cntr=0.3,0.1

Type RM Length L Ch R = 1,186,0,0,0
BEGIN DESCRIPTION:
MAYER CREEK 1.0
END DESCRIPTION:
XS GIS Cut Line= 4
      2764054.28     10088099.42      2763567.33     10087820.79
      2763306.91     10087883.29      2763137.65     10088375.45
#Sta/Elev= 30
  4329.0 1731.30  4409.3 1726.75  4511.1 1723.82  4520.2 1723.76  4637.1 1720.72
  4745.2 1719.33  4776.3 1719.48  4792.1 1720.95  4846.1 1719.68  4940.3 1717.04
  4950.6 1713.49  4960.8 1707.98  4966.5 1701.47  4971.6 1701.84  4981.4 1695.32
  4991.7 1691.62  4999.0 1690.95  5001.7 1690.45  5005.0 1690.95  5008.5 1692.65
  5032.8 1695.84  5061.0 1701.83  5074.0 1704.39  5115.1 1709.12  5125.4 1709.20
  5171.3 1715.04  5262.3 1716.58  5389.2 1718.54  5437.3 1718.26  5678.3 1720.71
#Mann=13,-1,0
  4329.0    0.05       0  4409.3     0.1       0  4511.1    0.05       0
  4520.2     0.1       0  4637.1    0.05       0  4745.2     0.1       0
  4846.1    0.16       0  4999.0    0.07       0  5005.0    0.16       0
  5061.0     0.1       0  5262.3    0.16       0  5389.2     0.1       0
  5437.3    0.16       0
Bank Sta=4999,5005
Exp/Cntr=0.3,0.1

Chan Stop Cuts=-1