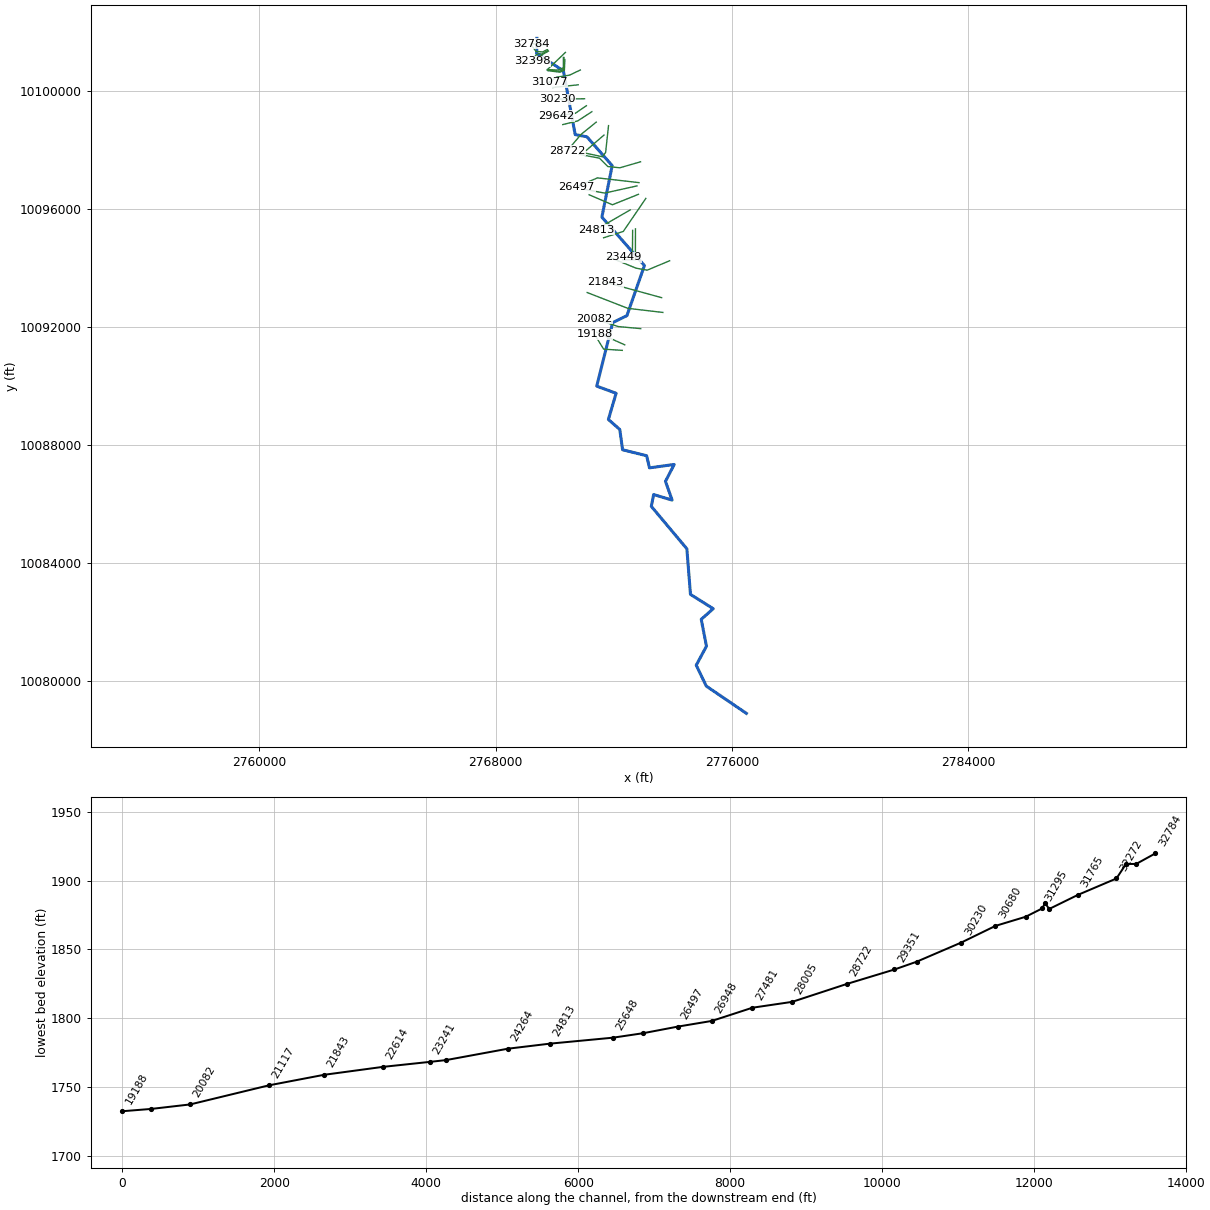
--- MIDDLE CREEK.prj (project) ---

Proj Title=MIDDLE CREEK Base Level Engineering
Current Plan=p01
Default Exp/Contr=0.3,0.1
English Units
Geom File=g01
Flow File=f01
Plan File=p01
Y Axis Title=Elevation
X Axis Title(PF)=Main Channel Distance
X Axis Title(XS)=Station
BEGIN DESCRIPTION:
MIDDLE CREEK
END DESCRIPTION:
DSS Export Rating Curves= 0
DSS Export Rating Curve Sorted= 0
DSS Export Volume Flow Curves= 0
DXF OffsetX= 0
DXF OffsetY= 0
DXF ScaleX= 1
DXF ScaleY= 10

--- MIDDLE CREEK.p01 (plan) ---

Plan Title=Multiple Run
Short Identifier=Multiple
Geom File=g01
Flow File=f01
Subcritical Flow
K Sum by GR= 0
Std Step Tol= 0.01
Critical Tol= 0.01
Num of Std Step Trials= 20
Max Error Tol= 0.3
Flow Tol Ratio= 0.001
Split Flow NTrial= 30
Split Flow Tol= 0.02
Split Flow Ratio= 0.02
Log Output Level= 0
Friction Slope Method= 1
Unsteady Friction Slope Method= 2
Unsteady Bridges Friction Slope Method= 1
Parabolic Critical Depth
Global Vel Dist=  1 , 1 , 1
Global Log Level= 0
CheckData=True
Encroach Param= -1, 0, 0, 0
BEGIN DESCRIPTION:
Multiple Run
END DESCRIPTION:

--- MIDDLE CREEK.f01 (steady flow) ---

Flow Title=Multiple
Number of Profiles=7
Profile Names=10-year,25-year,50-year,1pct_min,100-year,1pct_plu,500-year
River Rch & RM= MIDDLE CREEK,Reach-1,32784
     641     919    1157    1069    1446    1956    2265
River Rch & RM= MIDDLE CREEK,Reach-1,26948
    1201    1782    2297    2168    2932    3965    4795
River Rch & RM= MIDDLE CREEK,Reach-1,26045
    1620    2427    3148    2984    4035    5457    6660
River Rch & RM= MIDDLE CREEK,Reach-1,18369
    1946    2932    3818    3628    4906    6635    8145
River Rch & RM= MIDDLE CREEK,Reach-1,12492
    2069    3108    4038    3826    5174    6998    8540
Boundary for River Rch & Prof#=MIDDLE CREEK,Reach-1,1
Up Type=0
Dn Type=3
Dn Slope=0.005
Boundary for River Rch & Prof#=MIDDLE CREEK,Reach-1,2
Up Type=0
Dn Type=3
Dn Slope=0.005
Boundary for River Rch & Prof#=MIDDLE CREEK,Reach-1,3
Up Type=0
Dn Type=3
Dn Slope=0.005
Boundary for River Rch & Prof#=MIDDLE CREEK,Reach-1,4
Up Type=0
Dn Type=3
Dn Slope=0.005
Boundary for River Rch & Prof#=MIDDLE CREEK,Reach-1,5
Up Type=0
Dn Type=3
Dn Slope=0.005
Boundary for River Rch & Prof#=MIDDLE CREEK,Reach-1,6
Up Type=0
Dn Type=3
Dn Slope=0.005
Boundary for River Rch & Prof#=MIDDLE CREEK,Reach-1,7
Up Type=0
Dn Type=3
Dn Slope=0.005

--- MIDDLE CREEK.g01 (geometry) ---

Geom Title=Existing Conditions
Program Version=4.10

River Reach=MIDDLE CREEK    ,Reach-1
Reach XY= 30
      2769397.62     10101772.62      2769389.54     10101260.86
      2770293.71      10100671.8      2770692.12     10098512.95
      2771089.43     10098438.02      2771944.75     10097462.42
      2771596.47     10095717.93      2773036.88     10094077.95
      2772443.23      10092381.1      2771962.76     10092146.67
      2771421.51     10089994.98      2772078.44     10089752.73
      2771816.95     10088866.18      2772201.65     10088527.34
      2772297.57     10087840.27      2773111.05     10087638.15
       2773208.6     10087227.86      2774045.15     10087342.24
      2773749.57     10086770.63      2773975.18     10086135.13
      2773348.91     10086323.48      2773269.87     10085923.73
        2774474.     10084486.52      2774596.27     10082942.88
      2775366.16     10082458.03      2774960.47     10082097.94
      2775137.87     10081188.64      2774791.04     10080545.02
      2775131.81     10079837.02      2776490.52     10078913.48

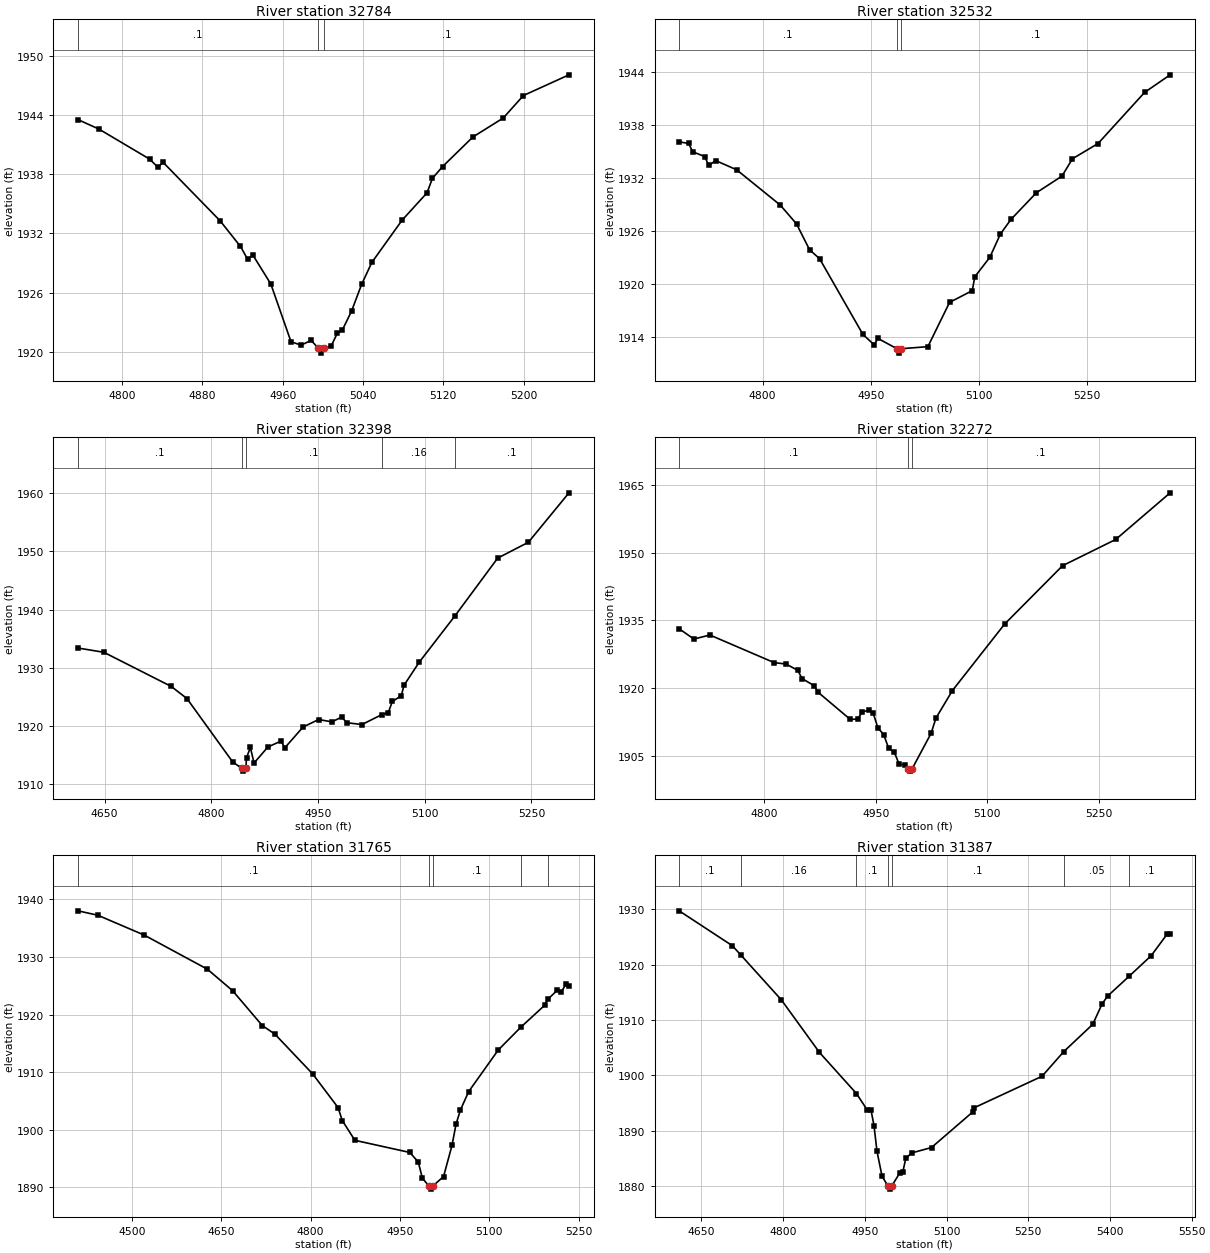
Type RM Length L Ch R = 1 ,32784   ,252,252,252
BEGIN DESCRIPTION:
MIDDLE CREEK 71.0
END DESCRIPTION:
XS GIS Cut Line= 2
      2769689.28     10101539.29      2769203.34     10101594.83
#Sta/Elev= 30
  4756.1 1943.54    4777 1942.58  4827.4 1939.54  4835.8 1938.71  4840.9 1939.21
  4897.8 1933.27    4918 1930.68  4925.2 1929.37  4930.2 1929.83  4948.2 1926.88
  4968.3 1921.03  4978.3 1920.68  4988.4 1921.16  4995.5 1920.37  4998.2 1919.87
  5001.5 1920.37  5008.5 1920.63  5014.5  1921.9  5019.5 1922.22  5028.7 1924.15
  5038.7 1926.85  5048.8 1929.06    5079 1933.35  5103.8 1936.12  5109.2 1937.59
  5119.3 1938.78  5149.5 1941.78  5179.7  1943.7  5199.8 1945.98  5245.2 1948.08
#Mann= 3 ,-1 , 0
  4756.1      .1       0  4995.5     .07       0  5001.5      .1       0
Bank Sta=4995.5,5001.5
XS Rating Curve= 0 ,0
Exp/Cntr=0.3,0.1

Type RM Length L Ch R = 1 ,32532   ,134,134,134
BEGIN DESCRIPTION:
Mapping XS c705084a
END DESCRIPTION:
XS GIS Cut Line= 4
      2769753.69     10101395.52       2769591.2     10101312.76
      2769367.07     10101327.81      2769203.38     10101548.56
#Sta/Elev= 30
  4684.1 1936.07  4697.3 1935.89  4702.9 1934.95  4719.6 1934.41  4725.2  1933.4
  4734.9 1933.95    4764 1932.91  4824.6 1928.92  4847.1  1926.8  4865.2 1923.88
  4879.2 1922.86  4939.3 1914.31    4955 1913.13    4960 1913.87  4986.5  1912.7
  4989.2  1912.2  4992.5  1912.7  5029.5 1912.93  5059.6 1917.93  5091.1 1919.26
  5094.7 1920.83  5115.5 1923.02  5130.1 1925.64  5144.8  1927.3  5180.2 1930.32
  5215.7  1932.2  5230.3 1934.16  5265.8 1935.88  5330.5 1941.66  5365.9 1943.64
#Mann= 3 ,-1 , 0
  4684.1      .1       0  4986.5     .07       0  4992.5      .1       0
Bank Sta=4986.5,4992.5
XS Rating Curve= 0 ,0
Exp/Cntr=0.3,0.1

Type RM Length L Ch R = 1 ,32398   ,126,126,126
BEGIN DESCRIPTION:
MIDDLE CREEK 70.0
END DESCRIPTION:
XS GIS Cut Line= 6
      2769761.19     10101359.41       2769556.6     10101237.55
      2769476.88      10101255.6      2769442.28     10101251.09
      2769356.54     10101199.95      2769235.27     10100997.84
#Sta/Elev= 30
  4612.5 1933.37  4648.8 1932.64  4743.7 1926.75  4765.7 1924.67  4829.9 1913.77
  4842.5 1912.67  4845.2 1912.17  4848.5 1912.67  4849.5 1914.48  4854.9 1916.25
    4860 1913.56  4879.5 1916.32  4898.1 1917.36  4903.2 1916.17    4929 1919.77
  4950.9 1921.06  4969.6 1920.65  4983.3 1921.49  4990.3 1920.51  5011.7 1920.19
  5039.8 1921.91  5048.7 1922.24  5054.5 1924.17  5067.1 1925.15  5070.8 1926.94
  5092.2 1930.92  5142.7 1938.94  5202.6 1948.86  5245.7 1951.58  5302.8  1960.1
#Mann= 5 ,-1 , 0
  4612.5      .1       0  4842.5     .07       0  4848.5      .1       0
  5039.8     .16       0  5142.7      .1       0
Bank Sta=4842.5,4848.5
XS Rating Curve= 0 ,0
Exp/Cntr=0.3,0.1

Type RM Length L Ch R = 1 ,32272   ,507,507,507
BEGIN DESCRIPTION:
Mapping XS 1be8e308
END DESCRIPTION:
XS GIS Cut Line= 3
      2769788.27     10101339.85      2769568.64     10101214.99
      2769257.24     10100951.73
#Sta/Elev= 30
  4685.7 1933.15  4705.5 1930.87  4727.1 1931.76  4813.6 1925.64  4829.4 1925.34
  4845.3 1923.94    4851 1922.12  4866.9 1920.58  4872.7 1919.07  4915.9 1913.07
    4926 1913.16  4931.8 1914.72  4941.7 1915.16  4946.6  1914.5  4953.1 1911.19
  4960.9 1909.69  4967.4 1906.72  4975.2 1905.77  4981.7 1903.12  4989.4 1903.05
    4993 1902.12  4995.7 1901.62    4999 1902.12  5024.6 1909.99  5031.1 1913.36
  5053.2 1919.45  5123.4 1934.17  5201.4 1947.11  5272.9 1952.92  5346.1 1963.25
#Mann= 3 ,-1 , 0
  4685.7      .1       0    4993     .07       0    4999      .1       0
Bank Sta=4993,4999
XS Rating Curve= 0 ,0
Exp/Cntr=0.3,0.1

Type RM Length L Ch R = 1 ,31765   ,378,378,378
BEGIN DESCRIPTION:
MIDDLE CREEK 68.0
END DESCRIPTION:
XS GIS Cut Line= 2
      2770362.93     10101296.26      2769766.71     10100727.77
#Sta/Elev= 30
  4409.7 1938.03  4443.1 1937.26  4520.8 1933.82  4626.8 1927.89  4669.2 1924.15
  4718.9  1918.1    4740 1916.62  4803.5 1909.69    4846 1903.86  4853.2 1901.59
  4874.3 1898.16  4966.5 1896.05  4980.6  1894.4  4987.5  1891.6  4998.7 1890.18
  5001.4 1889.68  5004.7 1890.18  5023.1 1891.87  5037.2 1897.26  5044.1    1901
  5051.4 1903.44  5065.3 1906.64  5114.9 1913.86  5152.6  1917.8  5192.6 1921.61
  5197.6 1922.63    5214 1924.24  5220.9 1923.97  5228.1 1925.25  5233.5 1924.89
#Mann= 5 ,-1 , 0
  4409.7      .1       0  4998.7     .07       0  5004.7      .1       0
  5152.6     .05       0  5197.6      .1       0
Bank Sta=4998.7,5004.7
XS Rating Curve= 0 ,0
Exp/Cntr=0.3,0.1

Type RM Length L Ch R = 1 ,31387   ,54,54,54
BEGIN DESCRIPTION:
Mapping XS eadefb9f
END DESCRIPTION:
XS GIS Cut Line= 4
      2770293.03     10101121.28      2770290.86     10100773.01
      2770111.82     10100697.05      2769753.72     10100716.59
#Sta/Elev= 30
  4609.1 1929.74  4706.7 1923.44  4722.2 1921.77  4796.7 1913.65  4866.7 1904.14
  4934.7  1896.7  4954.5 1893.72  4961.4 1893.72  4966.9 1890.85  4972.3 1886.28
  4981.7 1881.72    4993 1879.93  4995.7 1879.43    4999 1879.93  5014.2 1882.36
  5019.6 1882.48  5025.2 1884.99    5036 1885.97  5072.4 1886.95  5148.8 1893.44
    5151 1894.15  5275.4 1899.84  5315.3  1904.3  5368.4 1909.22  5385.6 1912.91
  5395.6 1914.32  5435.2 1917.91  5475.7 1921.63  5505.6 1925.61  5510.5 1925.61
#Mann= 7 ,-1 , 0
  4609.1      .1       0  4722.2     .16       0  4934.7      .1       0
    4993     .07       0    4999      .1       0  5315.3     .05       0
  5435.2      .1       0
Bank Sta=4993,4999
XS Rating Curve= 0 ,0
Exp/Cntr=0.3,0.1

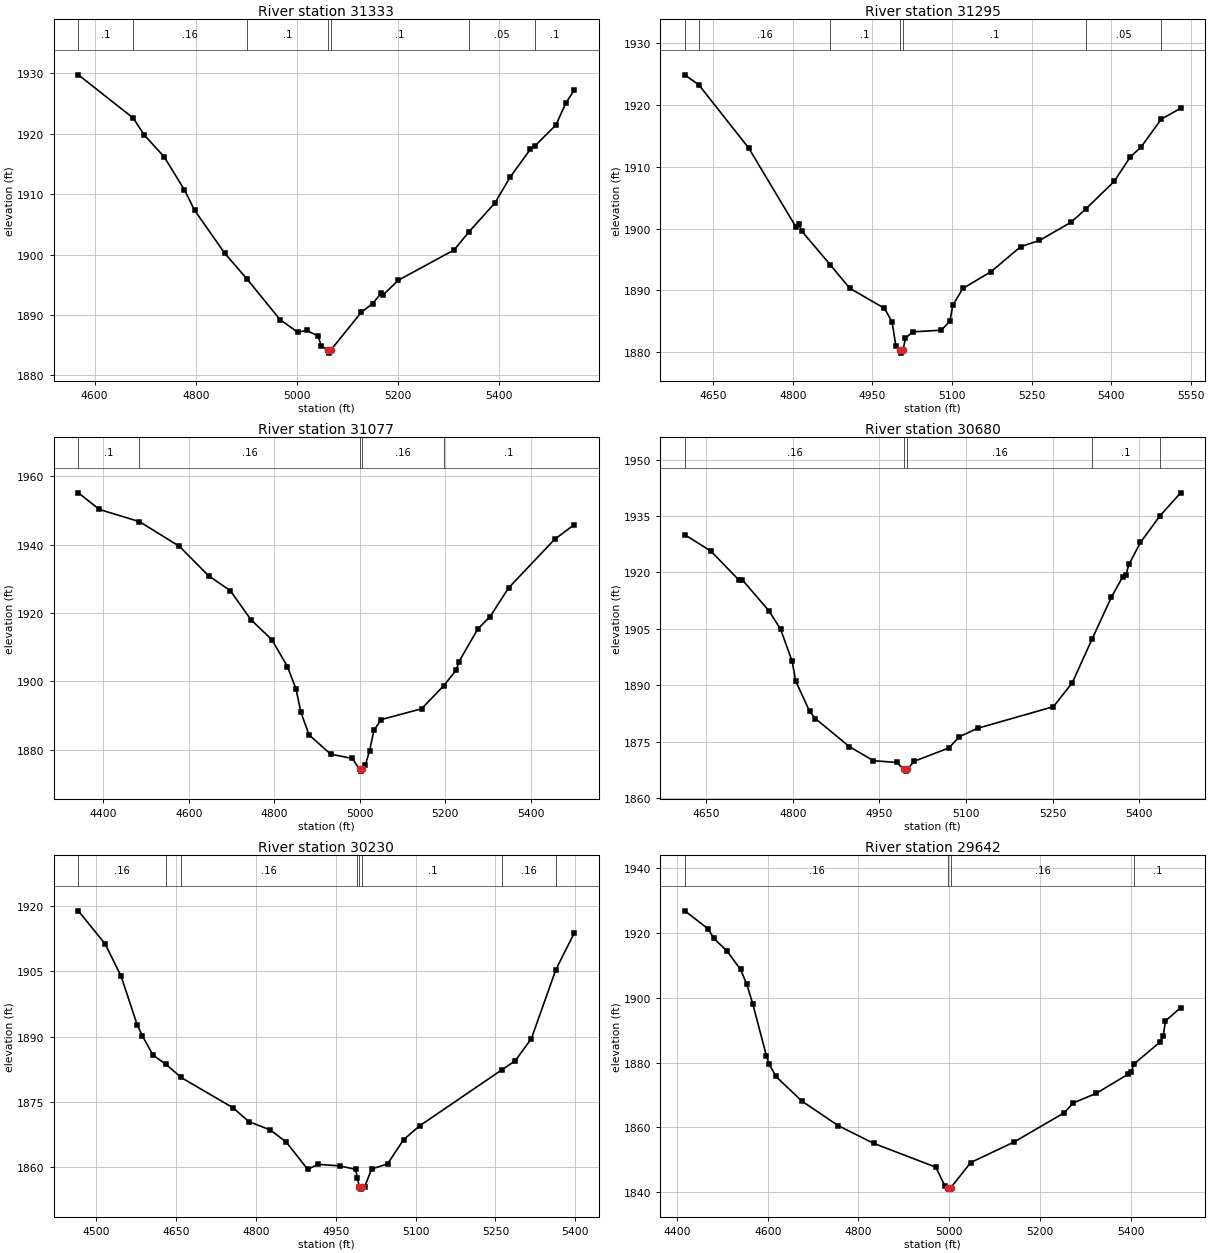
Type RM Length L Ch R = 1 ,31333   ,38,38,38
BEGIN DESCRIPTION:
Mapping XS a8ae04dc
END DESCRIPTION:
XS GIS Cut Line= 4
      2770311.47     10101123.51      2770303.88     10100720.93
      2770157.39     10100654.74       2769742.6     10100701.31
#Sta/Elev= 30
  4567.8 1929.73  4676.5 1922.57  4697.6 1919.84  4737.6 1916.16  4777.6 1910.71
  4797.6 1907.35  4857.6 1900.19  4901.3 1895.97  4966.6 1889.25    5002 1887.14
  5019.6 1887.46  5042.2  1886.5  5048.2 1884.89  5061.2 1884.19  5063.9 1883.69
  5067.2 1884.19  5127.9 1890.49  5150.3  1891.9  5166.2 1893.56  5171.2 1893.35
  5200.6 1895.74  5311.3 1900.77  5340.1 1903.72  5391.8 1908.53  5421.9 1912.79
  5462.2 1917.44  5470.7 1917.95  5512.5 1921.42  5532.6 1925.15  5548.6 1927.15
#Mann= 7 ,-1 , 0
  4567.8      .1       0  4676.5     .16       0  4901.3      .1       0
  5061.2     .07       0  5067.2      .1       0  5340.1     .05       0
  5470.7      .1       0
Bank Sta=5061.2,5067.2
XS Rating Curve= 0 ,0
Exp/Cntr=0.3,0.1

Type RM Length L Ch R = 1 ,31295   ,218,218,218
BEGIN DESCRIPTION:
Mapping XS 19dbe84a
END DESCRIPTION:
XS GIS Cut Line= 4
      2770342.94     10101054.07      2770326.66     10100687.29
      2770172.58     10100626.52      2769774.34     10100675.36
#Sta/Elev= 30
  4596.5  1924.9  4623.2 1923.25    4717 1913.03  4806.1 1900.23  4811.1 1900.76
  4817.1 1899.56  4870.9  1894.1  4907.1 1890.34  4972.5 1887.09    4987 1884.88
    4994 1881.03  5001.7 1880.33  5004.5 1879.83  5007.7 1880.33  5012.1 1882.25
  5026.2 1883.28  5079.9 1883.54    5096 1885.04  5101.4 1887.63  5120.4 1890.31
  5173.7 1893.04  5229.3 1897.08  5264.4 1898.07  5324.8 1901.06  5352.6 1903.24
  5405.4 1907.65  5435.7  1911.6  5455.8 1913.18  5494.2 1917.74  5530.5 1919.47
#Mann= 7 ,-1 , 0
  4596.5      .1       0  4623.2     .16       0  4870.9      .1       0
  5001.7     .07       0  5007.7      .1       0  5352.6     .05       0
  5494.2      .1       0
Bank Sta=5001.7,5007.7
XS Rating Curve= 0 ,0
Exp/Cntr=0.3,0.1

Type RM Length L Ch R = 1 ,31077   ,397,397,397
BEGIN DESCRIPTION:
Mapping XS 5ea57170
END DESCRIPTION:
XS GIS Cut Line= 4
      2770866.81     10100700.54      2770501.26     10100526.05
      2770060.52     10100456.85      2769806.34     10100282.38
#Sta/Elev= 30
  4341.8 1955.19  4391.1 1950.32  4484.8 1946.76  4578.2 1939.53  4646.2 1930.93
  4697.1 1926.58  4745.6 1918.04  4794.6 1912.17  4830.7 1904.36  4850.9 1897.76
  4862.3 1890.98  4881.3 1884.36  4931.9 1878.72  4982.4 1877.45  4999.8 1874.25
  5002.5 1873.75  5005.8 1874.25  5012.9 1875.51    5023 1879.77  5033.1 1885.71
  5050.1 1888.83  5144.5    1892  5195.8 1898.68  5225.4 1903.29  5231.9 1905.78
  5276.2 1915.39  5304.7 1918.96  5347.9 1927.35  5455.5 1941.57  5501.3 1945.86
#Mann= 5 ,-1 , 0
  4341.8      .1       0  4484.8     .16       0  4999.8     .07       0
  5005.8     .16       0  5195.8      .1       0
Bank Sta=4999.8,5005.8
XS Rating Curve= 0 ,0
Exp/Cntr=0.3,0.1

Type RM Length L Ch R = 1 ,30680   ,450,450,450
BEGIN DESCRIPTION:
MIDDLE CREEK 66.0
END DESCRIPTION:
XS GIS Cut Line= 2
      2770793.51     10100199.02      2769939.26     10100108.73
#Sta/Elev= 30
  4612.9 1930.01  4658.2 1925.64  4707.1 1917.88  4712.1 1918.08  4758.7 1909.76
  4778.9 1904.84    4799 1896.29  4804.9 1891.14  4829.1 1883.03  4839.2 1881.09
  4897.8 1873.66  4939.7 1869.89    4980 1869.43  4992.6 1867.62  4995.4 1867.12
  4998.6 1867.62  5010.1 1869.72  5070.5  1873.3  5088.4 1876.26  5120.8 1878.54
  5251.5 1884.27  5284.1  1890.6  5318.7 1902.32    5352 1913.42  5371.9 1918.89
    5377 1919.21  5382.2  1922.1  5402.3 1927.97  5436.6 1935.12  5471.9 1941.16
#Mann= 5 ,-1 , 0
  4612.9     .16       0  4992.6     .07       0  4998.6     .16       0
  5318.7      .1       0  5436.6     .05       0
Bank Sta=4992.6,4998.6
XS Rating Curve= 0 ,0
Exp/Cntr=0.3,0.1

Type RM Length L Ch R = 1 ,30230   ,588,588,588
BEGIN DESCRIPTION:
MIDDLE CREEK 65.0
END DESCRIPTION:
XS GIS Cut Line= 2
      2771008.77     10099726.79      2770078.17      10099712.9
#Sta/Elev= 30
    4467 1918.83  4517.3 1911.23  4547.3 1903.83  4577.3 1892.75  4587.3 1890.11
  4607.3 1885.71  4631.7 1883.62  4659.9 1880.61  4757.3 1873.66  4787.3 1870.47
  4827.3 1868.57  4857.3  1865.8  4897.4 1859.55  4917.4 1860.68  4957.4 1860.33
  4987.4 1859.54  4990.9 1857.52  4994.4  1855.5  4997.1    1855  5000.4  1855.5
  5004.6 1855.54  5017.4 1859.62  5047.4 1860.78  5077.4 1866.33  5107.4 1869.49
  5262.8 1882.43  5287.4 1884.47  5317.4 1889.52  5363.4 1905.36  5397.7 1913.68
#Mann= 8 ,-1 , 0
    4467     .16       0  4631.7      .1       0  4659.9     .16       0
  4990.9      .1       0  4994.4     .07       0  5000.4      .1       0
  5262.8     .16       0  5363.4      .1       0
Bank Sta=4994.4,5000.4
XS Rating Curve= 0 ,0
Exp/Cntr=0.3,0.1

Type RM Length L Ch R = 1 ,29642   ,291,291,291
BEGIN DESCRIPTION:
MIDDLE CREEK 64.0
END DESCRIPTION:
XS GIS Cut Line= 3
      2771071.27      10099490.7      2770696.23     10099233.73
      2770064.28     10099143.45
#Sta/Elev= 30
  4417.1 1926.68  4468.3 1921.16  4481.1  1918.2  4510.2 1914.29    4540 1908.63
  4553.8 1904.04  4567.1 1897.98  4596.9  1882.1    4603 1879.54  4617.9 1875.72
  4675.1 1868.13  4755.3 1860.57  4833.1 1855.14  4970.5 1847.78  4990.7 1841.94
  4997.8 1841.53  5000.5 1841.03  5003.8 1841.53  5047.4 1849.22  5142.2 1855.48
  5253.3  1864.5  5273.5 1867.56    5324  1870.5  5394.8 1876.44  5400.9  1877.2
  5407.7 1879.59  5465.5 1886.39  5471.6 1888.09  5476.7 1892.78  5510.1 1896.88
#Mann= 4 ,-1 , 0
  4417.1     .16       0  4997.8     .07       0  5003.8     .16       0
  5407.7      .1       0
Bank Sta=4997.8,5003.8
XS Rating Curve= 0 ,0
Exp/Cntr=0.3,0.1

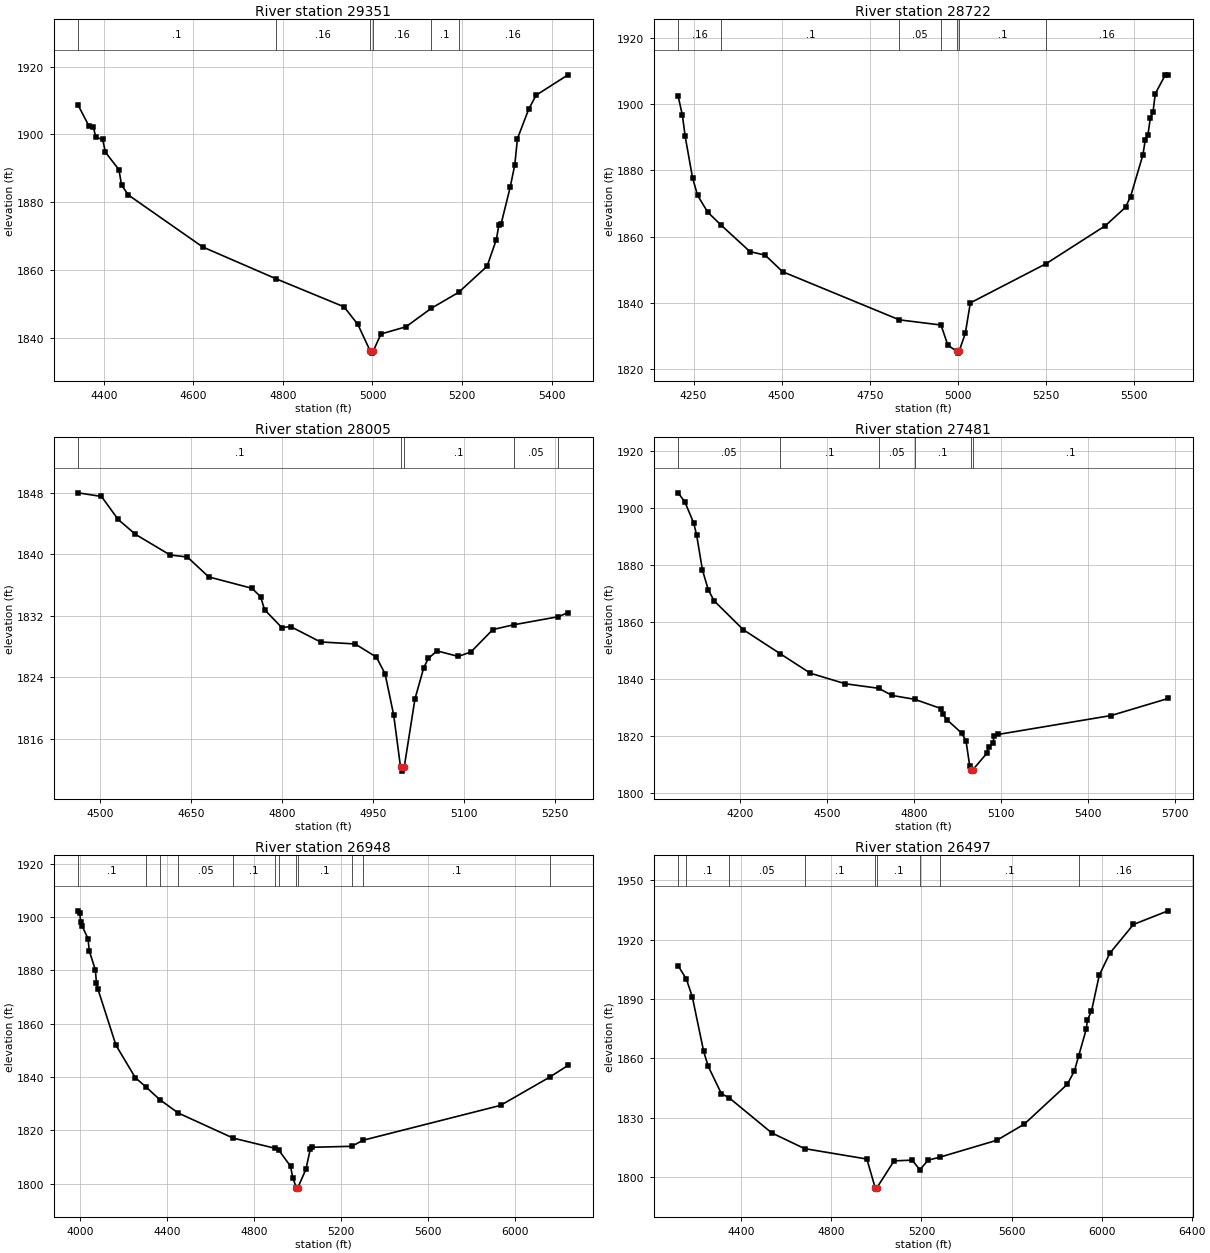
Type RM Length L Ch R = 1 ,29351   ,629,629,629
BEGIN DESCRIPTION:
MIDDLE CREEK 63.0
END DESCRIPTION:
XS GIS Cut Line= 3
      2771258.76     10099289.31      2770779.57     10098976.79
      2770273.04     10098851.89
#Sta/Elev= 30
  4342.7 1908.72  4367.5 1902.38  4376.6 1902.27  4382.6 1899.12  4397.7 1898.57
  4403.7 1894.77  4433.9 1889.62  4439.9 1885.03    4455 1882.12    4621 1866.76
  4784.9 1857.35  4936.5 1849.07  4967.4 1843.85  4995.3 1835.89  4998.1 1835.39
  5001.3 1835.89  5018.9 1841.05  5074.7 1843.17  5131.6 1848.67  5192.3 1853.35
  5255.8 1861.07  5276.4  1868.9  5282.1 1873.24  5287.2 1873.64  5307.3 1884.37
  5317.6 1891.02  5323.6 1898.78  5348.5 1907.41  5365.1 1911.59  5436.5 1917.63
#Mann= 6 ,-1 , 0
  4342.7      .1       0  4784.9     .16       0  4995.3     .07       0
  5001.3     .16       0  5131.6      .1       0  5192.3     .16       0
Bank Sta=4995.3,5001.3
XS Rating Curve= 0 ,0
Exp/Cntr=0.3,0.1

Type RM Length L Ch R = 1 ,28722   ,717,717,717
BEGIN DESCRIPTION:
MIDDLE CREEK 62.0
END DESCRIPTION:
XS GIS Cut Line= 3
      2771404.54      10098935.1      2770890.68     10098518.46
      2770418.44     10097962.88
#Sta/Elev= 30
  4206.2  1902.4  4218.4  1896.6  4226.3 1890.19  4247.1 1877.79  4261.5  1872.4
  4290.3 1867.35  4329.2 1863.34  4410.2 1855.45  4453.3 1854.39  4502.9 1849.38
  4834.4 1834.86  4952.3 1833.31  4971.9 1827.24  4997.5 1825.33  5000.3 1824.83
  5003.5 1825.33  5021.4  1830.8  5035.6 1839.98  5250.7 1851.81    5419 1863.27
  5476.1 1868.83  5490.4 1872.06  5525.5 1884.64  5532.1 1889.15  5539.8 1890.73
  5546.3  1895.6  5554.1 1897.51  5560.6  1903.1  5589.2 1908.77  5596.9 1908.76
#Mann= 7 ,-1 , 0
  4206.2     .16       0  4329.2      .1       0  4834.4     .05       0
  4952.3      .1       0  4997.5     .07       0  5003.5      .1       0
  5250.7     .16       0
Bank Sta=4997.5,5003.5
XS Rating Curve= 0 ,0
Exp/Cntr=0.3,0.1

Type RM Length L Ch R = 1 ,28005   ,524,524,524
BEGIN DESCRIPTION:
MIDDLE CREEK 60.0
END DESCRIPTION:
XS GIS Cut Line= 2
      2771668.47     10098497.64      2771057.34     10097969.84
#Sta/Elev= 30
  4464.2 1847.98  4502.8 1847.51  4530.3 1844.52  4558.8 1842.59  4615.8 1839.91
  4644.4 1839.64  4679.5 1837.06  4750.8 1835.58    4765 1834.49  4771.6  1832.8
  4800.1 1830.47  4814.4 1830.61  4863.8 1828.61  4920.8 1828.35  4955.9 1826.64
  4970.2 1824.47  4984.4 1819.11  4995.7 1812.33  4998.4 1811.83  5001.7 1812.33
  5019.5 1821.23  5033.8 1825.23  5041.4 1826.46  5055.7 1827.45  5090.8 1826.73
  5111.7 1827.31  5147.8 1830.22  5182.1 1830.84  5255.8 1831.89  5271.7 1832.42
#Mann= 5 ,-1 , 0
  4464.2      .1       0  4995.7     .07       0  5001.7      .1       0
  5182.1     .05       0  5255.8      .1       0
Bank Sta=4995.7,5001.7
XS Rating Curve= 0 ,0
Exp/Cntr=0.3,0.1

Type RM Length L Ch R = 1 ,27481   ,533,533,533
BEGIN DESCRIPTION:
MIDDLE CREEK 59.0
END DESCRIPTION:
XS GIS Cut Line= 4
      2771821.24      10098817.1      2771724.01     10097914.29
      2771619.85     10097761.51      2771036.53     10097886.51
#Sta/Elev= 30
  3987.2 1905.36  4010.7 1902.13  4040.9 1894.77  4050.9 1890.64  4071.1 1878.27
  4091.2 1871.29  4111.3 1867.41  4211.9 1857.27  4338.6 1848.87  4443.2 1841.97
  4563.9 1838.26  4679.3 1836.66  4724.8 1834.16  4803.7 1832.78  4895.2 1829.49
  4899.1  1827.7    4914 1825.67  4964.8 1820.92  4979.8 1818.28  4992.7 1809.38
  4997.7 1808.06  5000.5 1807.56  5003.7 1808.06  5051.6 1813.81  5057.6 1815.89
  5072.6 1817.48  5076.9 1819.75  5091.8 1820.47  5480.4  1827.1  5676.7 1833.09
#Mann= 6 ,-1 , 0
  3987.2     .05       0  4338.6      .1       0  4679.3     .05       0
  4803.7      .1       0  4997.7     .07       0  5003.7      .1       0
Bank Sta=4997.7,5003.7
XS Rating Curve= 0 ,0
Exp/Cntr=0.3,0.1

Type RM Length L Ch R = 1 ,26948   ,451,451,451
BEGIN DESCRIPTION:
MIDDLE CREEK 58.0
END DESCRIPTION:
XS GIS Cut Line= 5
      2772905.93     10097592.12      2772205.43       10097389.
      2771799.18     10097430.67      2771515.32     10097714.52
      2770812.81     10097847.22
#Sta/Elev= 30
    3991 1902.33  3998.4 1901.44  4003.6 1898.08  4009.2 1896.68  4037.1 1891.88
  4042.3 1887.42  4070.7 1880.14  4075.9 1875.11  4082.1 1873.08  4165.4 1851.93
  4254.2 1839.78  4303.5 1836.27  4367.7 1831.47  4451.6 1826.51  4704.9 1817.08
  4895.7  1813.3  4913.8 1812.64  4968.6 1806.54  4978.7 1802.17  4995.8 1798.45
  4998.5 1797.95  5001.8 1798.45    5039 1805.32  5059.1 1812.85  5069.1 1813.65
    5250 1814.01  5302.5 1816.29  5934.6 1829.36  6162.2 1840.03  6245.1 1844.36
#Mann= 12 ,-1 , 0
    3991      .1       0  4303.5     .05       0  4367.7      .1       0
  4451.6     .05       0  4704.9      .1       0  4895.7     .05       0
  4913.8      .1       0  4995.8     .07       0  5001.8      .1       0
    5250     .05       0  5302.5      .1       0  6162.2     .05       0
Bank Sta=4995.8,5001.8
XS Rating Curve= 0 ,0
Exp/Cntr=0.3,0.1

Type RM Length L Ch R = 1 ,26497   ,452,452,452
BEGIN DESCRIPTION:
MIDDLE CREEK 57.0
END DESCRIPTION:
XS GIS Cut Line= 3
       2772851.3     10096886.39      2771447.62     10097047.85
      2770747.11     10096745.78
#Sta/Elev= 30
  4119.5 1906.75  4156.1 1900.08  4182.7 1890.98  4233.1  1863.4  4253.2  1855.9
  4311.8 1842.04    4346 1839.99  4535.1 1822.24  4680.9 1814.28  4957.8    1809
  4995.1 1794.29  4997.8 1793.79  5001.1 1794.29  5078.6 1808.08  5159.1 1808.44
  5193.1 1803.56  5229.6 1808.43    5283 1809.99  5534.7 1818.49  5656.6 1826.64
  5847.3 1846.74  5879.2 1853.51  5898.4 1861.21  5931.6 1874.55  5937.1 1879.39
  5955.2 1883.79  5989.6 1901.94  6036.6 1913.08  6141.6 1927.63  6295.3 1934.52
#Mann= 9 ,-1 , 0
  4119.5     .16       0  4156.1      .1       0    4346     .05       0
  4680.9      .1       0  4995.1     .07       0  5001.1      .1       0
  5193.1     .05       0    5283      .1       0  5898.4     .16       0
Bank Sta=4995.1,5001.1
XS Rating Curve= 0 ,0
Exp/Cntr=0.3,0.1

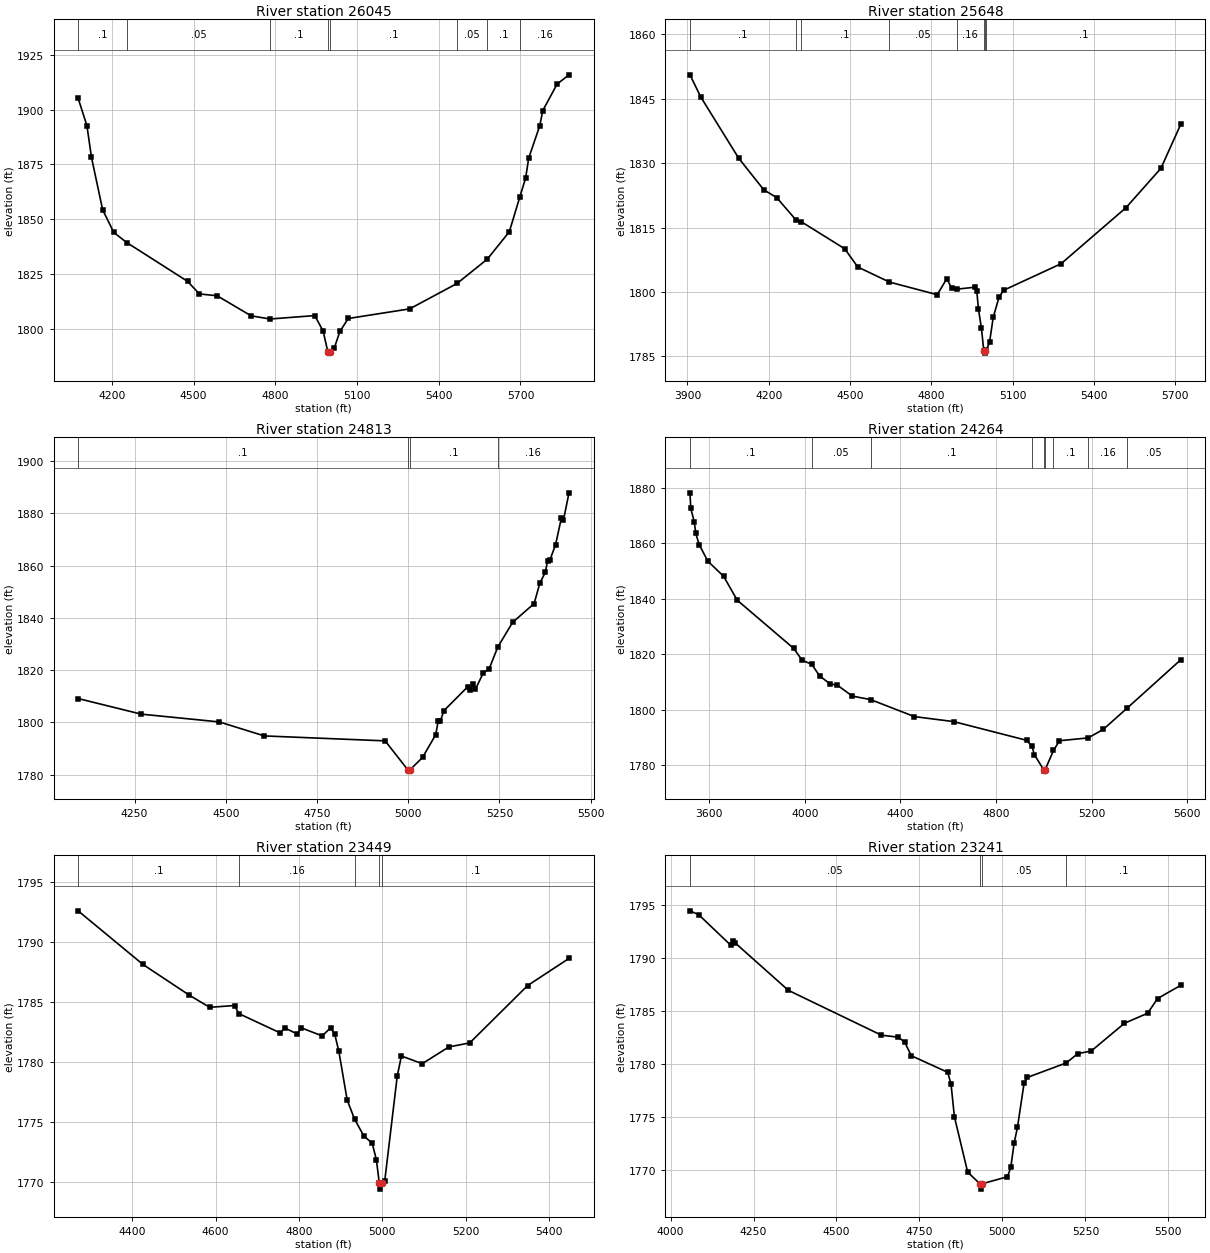
Type RM Length L Ch R = 1 ,26045   ,397,397,397
BEGIN DESCRIPTION:
MIDDLE CREEK 56.0
END DESCRIPTION:
XS GIS Cut Line= 3
      2772786.48     10096775.39      2771689.29     10096532.34
      2771023.09     10096657.26
#Sta/Elev= 30
  4076.4 1905.23  4108.7 1892.75  4125.6 1878.24  4166.5 1854.34  4207.5 1844.02
  4255.2 1839.41    4478 1821.75  4521.6    1816  4586.5 1815.18  4711.4 1806.03
  4780.7 1804.58    4945 1806.14  4975.7 1799.08  4993.2 1789.53  4995.9 1789.03
  4999.2 1789.53  5016.7 1791.35  5037.2 1798.92  5067.9 1804.81  5293.4  1809.2
    5467 1820.76    5578 1831.83  5658.9 1844.32  5697.6 1860.19    5719  1868.9
  5730.1 1877.88  5770.8 1892.67  5781.8 1899.56  5834.3 1911.62    5878 1915.85
#Mann= 8 ,-1 , 0
  4076.4      .1       0  4255.2     .05       0  4780.7      .1       0
  4993.2     .07       0  4999.2      .1       0    5467     .05       0
    5578      .1       0  5697.6     .16       0
Bank Sta=4993.2,4999.2
XS Rating Curve= 0 ,0
Exp/Cntr=0.3,0.1

Type RM Length L Ch R = 1 ,25648   ,835,835,835
BEGIN DESCRIPTION:
MIDDLE CREEK 55.0
END DESCRIPTION:
XS GIS Cut Line= 3
      2772835.15     10096490.69      2771953.18     10096136.51
      2771162.45     10096476.39
#Sta/Elev= 30
  3909.4  1850.6  3948.9 1845.47    4089 1831.19  4181.8 1823.81  4229.1 1822.01
    4301 1816.76  4318.7 1816.43  4480.3 1810.08  4528.6 1805.83  4645.4 1802.32
  4821.7 1799.38  4856.7  1803.1  4875.8 1800.83  4892.8 1800.66  4962.1 1801.14
  4967.5 1800.26  4973.8 1795.98  4984.7 1791.57  4993.5 1786.27  4996.3 1785.77
  4999.5 1786.27  5002.2 1786.41  5014.6 1788.26  5028.2 1794.11    5050 1798.88
  5067.2 1800.43  5278.6  1806.6    5518 1819.65  5646.8 1828.81  5720.5 1839.14
#Mann= 8 ,-1 , 0
  3909.4      .1       0    4301     .05       0  4318.7      .1       0
  4645.4     .05       0  4892.8     .16       0  4993.5     .07       0
  4999.5     .16       0  5002.2      .1       0
Bank Sta=4993.5,4999.5
XS Rating Curve= 0 ,0
Exp/Cntr=0.3,0.1

Type RM Length L Ch R = 1 ,24813   ,549,549,549
BEGIN DESCRIPTION:
MIDDLE CREEK 53.0
END DESCRIPTION:
XS GIS Cut Line= 2
      2772557.37     10095962.92      2771392.07     10095290.09
#Sta/Elev= 30
  4095.1 1809.17  4268.1  1803.2  4482.1 1800.22  4605.6 1794.86  4936.8 1792.97
  4998.9 1781.89  5001.6 1781.39  5004.9 1781.89  5039.2 1786.61  5075.3 1795.31
  5082.3 1800.59    5088 1800.51    5098 1804.54  5162.7 1813.61  5168.5 1812.35
  5178.5 1814.68  5184.2 1812.68  5205.8    1819  5221.6 1820.44  5245.4 1828.83
  5286.2 1838.33  5345.1  1845.5  5360.8 1853.31  5375.6 1857.41  5382.4 1861.99
  5388.2 1862.12  5403.9 1868.01  5419.7 1878.16  5425.5 1877.35  5440.7 1887.89
#Mann= 4 ,-1 , 0
  4095.1      .1       0  4998.9     .07       0  5004.9      .1       0
  5245.4     .16       0
Bank Sta=4998.9,5004.9
XS Rating Curve= 0 ,0
Exp/Cntr=0.3,0.1

Type RM Length L Ch R = 1 ,24264   ,815,815,815
BEGIN DESCRIPTION:
MIDDLE CREEK 52.0
END DESCRIPTION:
XS GIS Cut Line= 3
      2773085.14     10096351.81      2772321.23     10095233.73
      2771655.03     10095018.61
#Sta/Elev= 30
  3519.4 1878.31  3522.8 1872.66  3537.7 1867.73  3543.7 1863.62  3558.6 1859.45
  3594.5 1853.58  3660.3 1848.13  3717.1 1839.51  3953.5 1822.08  3989.4 1817.74
  4028.5  1816.4  4062.1 1812.13  4105.9 1809.24  4134.7 1808.89  4198.7 1804.86
  4275.4 1803.59  4458.8 1797.44  4623.3 1795.63    4929 1788.86  4950.8 1786.66
  4960.5  1783.7  4999.5 1778.24  5002.3 1777.74  5005.5 1778.24  5040.6  1785.2
  5065.6 1788.72  5185.6 1789.75  5248.6  1792.8  5347.4  1800.4  5573.6 1818.02
#Mann= 9 ,-1 , 0
  3519.4      .1       0  4028.5     .05       0  4275.4      .1       0
  4950.8     .16       0  4999.5     .07       0  5005.5     .16       0
  5040.6      .1       0  5185.6     .16       0  5347.4     .05       0
Bank Sta=4999.5,5005.5
XS Rating Curve= 0 ,0
Exp/Cntr=0.3,0.1

Type RM Length L Ch R = 1 ,23449   ,208,208,208
BEGIN DESCRIPTION:
MIDDLE CREEK 50.0
END DESCRIPTION:
XS GIS Cut Line= 3
      2772637.72     10095269.22      2772629.91      10094391.6
      2772331.95     10094357.92
#Sta/Elev= 30
  4270.1  1792.6  4425.6 1788.14  4535.6 1785.61  4585.6 1784.57  4645.6 1784.72
  4655.4 1784.05  4755.6 1782.43  4765.6 1782.86  4795.6 1782.35  4805.6 1782.86
  4855.6 1782.19  4875.6 1782.86  4885.6 1782.35  4895.6  1780.9  4915.6 1776.85
  4933.2 1775.27  4955.6 1773.86  4975.6 1773.26  4985.6 1771.89  4992.6 1769.94
  4995.4 1769.44  4998.6 1769.94  5005.6 1770.11  5035.6 1778.83  5045.6 1780.52
  5095.6 1779.88  5159.3 1781.27  5209.6 1781.61  5348.4 1786.38  5447.6 1788.64
#Mann= 5 ,-1 , 0
  4270.1      .1       0  4655.4     .16       0  4933.2      .1       0
  4992.6     .07       0  4998.6      .1       0
Bank Sta=4992.6,4998.6
XS Rating Curve= 0 ,0
Exp/Cntr=0.3,0.1

Type RM Length L Ch R = 1 ,23241   ,627,627,627
BEGIN DESCRIPTION:
Mapping XS 5120d574
END DESCRIPTION:
XS GIS Cut Line= 3
      2772733.86     10095320.28       2772730.6     10094273.55
      2772298.34     10094273.55
#Sta/Elev= 30
  4058.6 1794.45  4085.1 1794.08  4182.2 1791.18  4187.2  1791.6  4195.1 1791.41
  4355.1 1786.94  4635.2 1782.71  4685.2 1782.52  4705.2 1782.08  4725.2 1780.77
  4835.2  1779.2  4845.2 1778.07  4855.2 1775.02  4895.2 1769.78  4932.2 1768.67
  4934.9 1768.17  4938.2 1768.67  5015.2 1769.34  5025.2 1770.22  5035.2 1772.52
  5045.2 1773.99  5065.2 1778.17  5075.2 1778.72  5191.7 1780.08  5227.5 1780.97
  5267.5 1781.21  5367.5 1783.83  5437.5 1784.78  5467.5 1786.17  5537.6 1787.42
#Mann= 4 ,-1 , 0
  4058.6     .05       0  4932.2     .04       0  4938.2     .05       0
  5191.7      .1       0
Bank Sta=4932.2,4938.2
XS Rating Curve= 0 ,0
Exp/Cntr=0.3,0.1

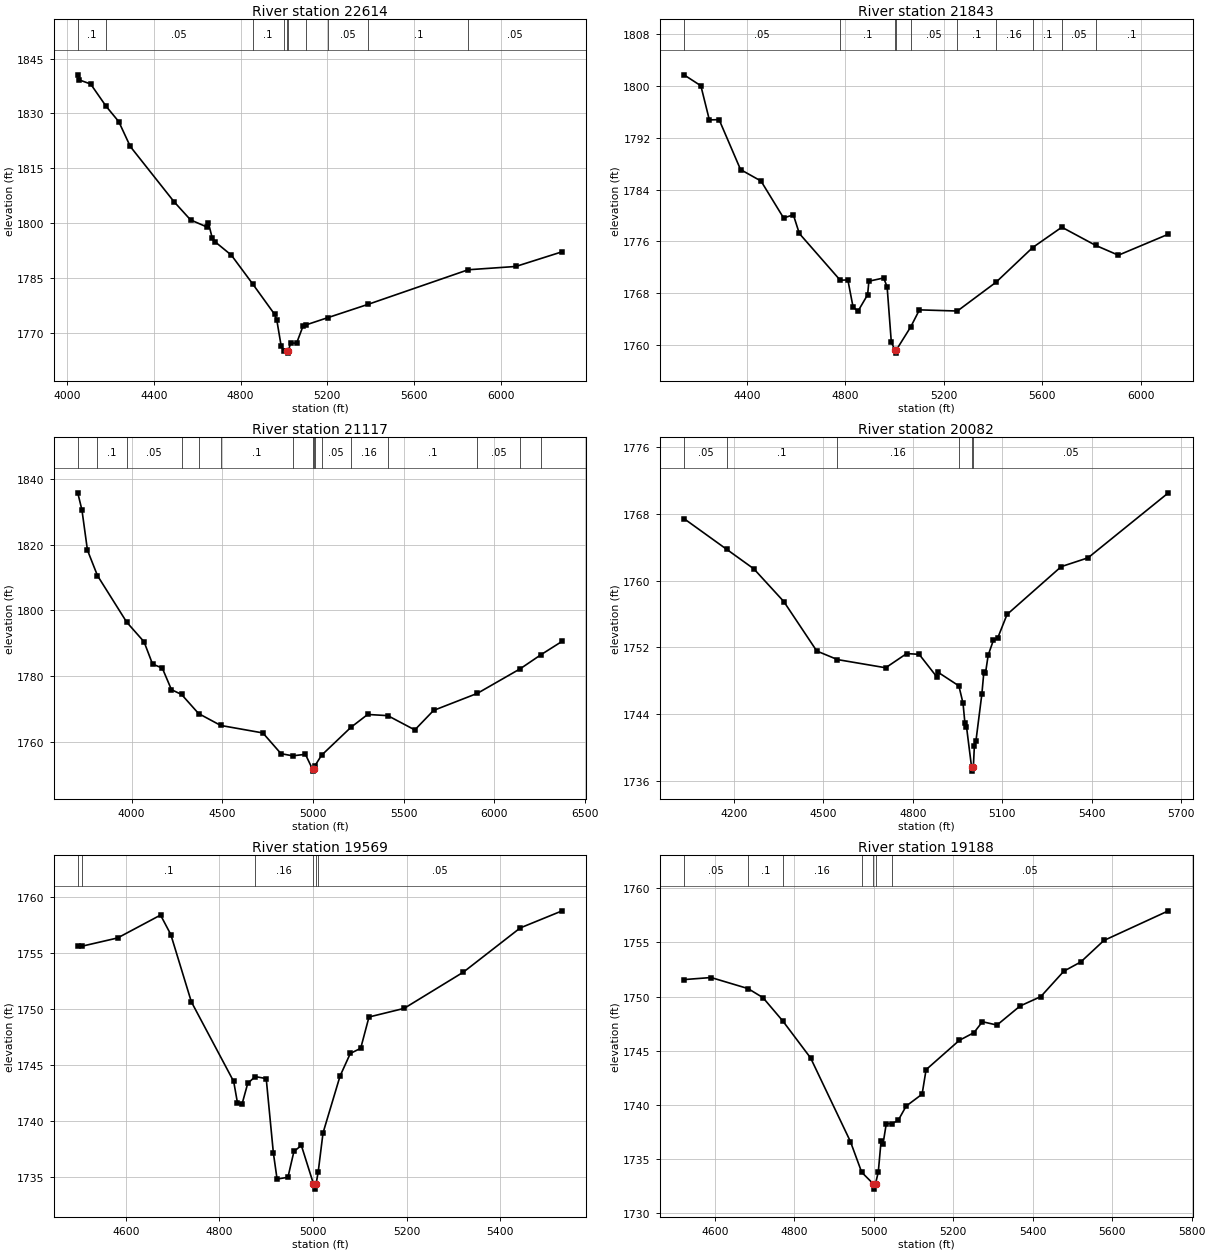
Type RM Length L Ch R = 1 ,22614   ,771,771,771
BEGIN DESCRIPTION:
MIDDLE CREEK 49.0
END DESCRIPTION:
XS GIS Cut Line= 4
      2773890.64     10094240.66      2773126.79     10093921.23
      2772751.79     10093990.68      2771802.93     10094378.53
#Sta/Elev= 30
  4048.7 1840.56  4055.1 1839.18  4108.1 1838.05  4179.3 1831.97  4237.9 1827.76
    4291 1820.97  4492.2 1805.91    4569  1800.9  4645.8 1798.93  4651.2 1800.11
  4668.9 1795.96  4680.5 1794.99  4757.3 1791.26  4854.8 1783.46  4956.3 1775.12
  4966.5 1773.63  4986.8 1766.48  4999.9 1765.17  5014.3 1764.98  5017.1 1764.48
  5020.3 1764.98  5030.1 1767.26    5058 1767.19  5088.5 1771.98  5101.1 1772.19
  5202.3 1774.18  5389.5 1777.85  5849.5 1787.27  6069.3 1788.17  6283.1 1792.19
#Mann= 10 ,-1 , 0
  4048.7      .1       0  4179.3     .05       0  4854.8      .1       0
  4999.9     .05       0  5014.3    .035       0  5020.3     .05       0
  5101.1      .1       0  5202.3     .05       0  5389.5      .1       0
  5849.5     .05       0
Bank Sta=5014.3,5020.3
XS Rating Curve= 0 ,0
Exp/Cntr=0.3,0.1

Type RM Length L Ch R = 1 ,21843   ,726,726,726
BEGIN DESCRIPTION:
MIDDLE CREEK 47.0
END DESCRIPTION:
XS GIS Cut Line= 2
      2773619.89     10092990.67      2771724.03     10093511.51
#Sta/Elev= 30
  4145.4 1801.76  4213.9 1800.07  4248.4 1794.79    4288 1794.83    4375 1787.11
    4458 1785.34  4549.7 1779.63  4589.4 1780.11  4613.5 1777.23  4779.6    1770
  4810.6 1770.05  4831.3 1765.93  4851.1 1765.18  4890.7 1767.75  4895.9 1769.85
  4955.8 1770.35  4969.9 1768.99  4986.9 1760.43  5001.4 1759.23  5004.1 1758.73
  5007.4 1759.23  5065.8 1762.79    5101 1765.42    5255 1765.24  5411.9 1769.69
  5560.8 1775.06    5679  1778.2  5815.8  1775.4  5908.5 1773.87  6111.5 1777.12
#Mann= 10 ,-1 , 0
  4145.4     .05       0  4779.6      .1       0  5001.4     .07       0
  5007.4      .1       0  5065.8     .05       0    5255      .1       0
  5411.9     .16       0  5560.8      .1       0    5679     .05       0
  5815.8      .1       0
Bank Sta=5001.4,5007.4
XS Rating Curve= 0 ,0
Exp/Cntr=0.3,0.1

Type RM Length L Ch R = 1 ,21117   ,1035,1035,1035
BEGIN DESCRIPTION:
MIDDLE CREEK 45.0
END DESCRIPTION:
XS GIS Cut Line= 3
      2773661.48     10092490.68      2772474.01     10092629.57
      2771098.99      10093164.3
#Sta/Elev= 30
  3703.5 1835.82  3726.7 1830.54  3756.9 1818.36  3812.2  1810.6  3973.6 1796.41
    4069 1790.45  4115.7 1783.68  4169.7 1782.43    4220 1775.87  4275.8 1774.41
  4369.7 1768.59  4491.9 1764.97  4724.1 1762.69  4824.1 1756.38  4888.4 1755.72
  4958.7 1756.18  4998.6 1751.56  5001.3 1751.06  5004.6 1751.56  5010.6 1752.64
  5047.8  1755.9  5209.4 1764.39    5302 1768.32    5413 1767.96  5561.9 1763.61
  5665.4 1769.55  5906.9 1774.75  6142.7 1782.22  6257.4 1786.51  6374.4  1790.6
#Mann= 16 ,-1 , 0
  3703.5     .05       0  3812.2      .1       0  3973.6     .05       0
  4275.8      .1       0  4369.7     .05       0  4491.9      .1       0
  4888.4     .16       0  4998.6     .07       0  5004.6     .16       0
  5010.6      .1       0  5047.8     .05       0  5209.4     .16       0
    5413      .1       0  5906.9     .05       0  6142.7      .1       0
  6257.4     .05       0
Bank Sta=4998.6,5004.6
XS Rating Curve= 0 ,0
Exp/Cntr=0.3,0.1

Type RM Length L Ch R = 1 ,20082   ,513,513,513
BEGIN DESCRIPTION:
MIDDLE CREEK 43.0
END DESCRIPTION:
XS GIS Cut Line= 3
      2772911.48     10091942.07      2772154.57     10092011.51
      2771335.16     10092282.33
#Sta/Elev= 30
  4033.3 1767.45  4176.3 1763.77  4267.3 1761.43  4367.7 1757.51  4478.2 1751.58
  4547.7 1750.55  4709.1 1749.57  4779.4 1751.27  4821.3 1751.18  4879.5 1748.52
  4884.7 1749.03  4954.4  1747.4  4968.3 1745.32  4974.7 1742.92  4979.9 1742.52
  4996.9 1737.68  4999.7 1737.18  5002.9 1737.68  5006.4 1740.24  5011.7 1740.83
  5031.5 1746.44  5038.1 1749.06  5043.4 1748.89  5052.6 1751.08  5069.9 1752.85
  5084.2 1753.11  5115.8 1755.96  5297.2 1761.69  5387.2 1762.75  5656.4 1770.54
#Mann= 6 ,-1 , 0
  4033.3     .05       0  4176.3      .1       0  4547.7     .16       0
  4954.4     .05       0  4996.9     .04       0  5002.9     .05       0
Bank Sta=4996.9,5002.9
XS Rating Curve= 0 ,0
Exp/Cntr=0.3,0.1

Type RM Length L Ch R = 1 ,19569   ,381,381,381
BEGIN DESCRIPTION:
MIDDLE CREEK 42.0
END DESCRIPTION:
XS GIS Cut Line= 2
      2772369.89     10091393.44      2771425.44     10091817.05
#Sta/Elev= 30
  4497.5 1755.67    4507 1755.64  4582.5 1756.37  4674.4 1758.42  4696.3 1756.68
  4740.2 1750.66  4830.7 1743.53  4838.8 1741.61  4848.4 1741.49  4860.7 1743.36
  4876.6 1743.97  4900.2 1743.79  4915.5 1737.13  4923.4  1734.8  4946.6 1734.96
  4959.4 1737.27  4975.3 1737.81  5000.9  1734.4  5003.7  1733.9  5006.9  1734.4
  5011.3 1735.45  5021.6 1738.93    5058 1744.02  5079.9 1746.04  5102.1  1746.5
  5119.8  1749.3  5194.8 1750.07  5321.7 1753.32    5443 1757.27  5532.6  1758.8
#Mann= 6 ,-1 , 0
  4497.5     .05       0    4507      .1       0  4876.6     .16       0
  5000.9     .07       0  5006.9     .16       0  5011.3     .05       0
Bank Sta=5000.9,5006.9
XS Rating Curve= 0 ,0
Exp/Cntr=0.3,0.1

Type RM Length L Ch R = 1 ,19188   ,512,512,512
BEGIN DESCRIPTION:
MIDDLE CREEK 41.0
END DESCRIPTION:
XS GIS Cut Line= 3
      2772286.53     10091205.95      2771654.57     10091247.62
      2771349.02     10091747.61
#Sta/Elev= 30
  4522.1 1751.57  4590.3 1751.76  4683.3 1750.74    4721  1749.9    4771 1747.74
  4840.9 1744.33  4941.1 1736.61  4969.4 1733.78  4998.2 1732.72    5001 1732.22
  5004.2 1732.72  5011.2  1733.8  5018.3  1736.7  5023.3 1736.43  5031.3 1738.26
  5046.2 1738.28  5061.3 1738.57  5081.4 1739.89  5121.5 1740.99  5131.5 1743.25
  5215.2 1745.96    5252 1746.67  5273.3 1747.68    5310 1747.37  5368.1 1749.13
  5420.3    1750  5478.4 1752.35    5521  1753.2    5579 1755.18  5741.4 1757.92
#Mann= 7 ,-1 , 0
  4522.1     .05       0  4683.3      .1       0    4771     .16       0
  4969.4      .1       0  4998.2     .07       0  5004.2      .1       0
  5046.2     .05       0
Bank Sta=4998.2,5004.2
XS Rating Curve= 0 ,0
Exp/Cntr=0.3,0.1