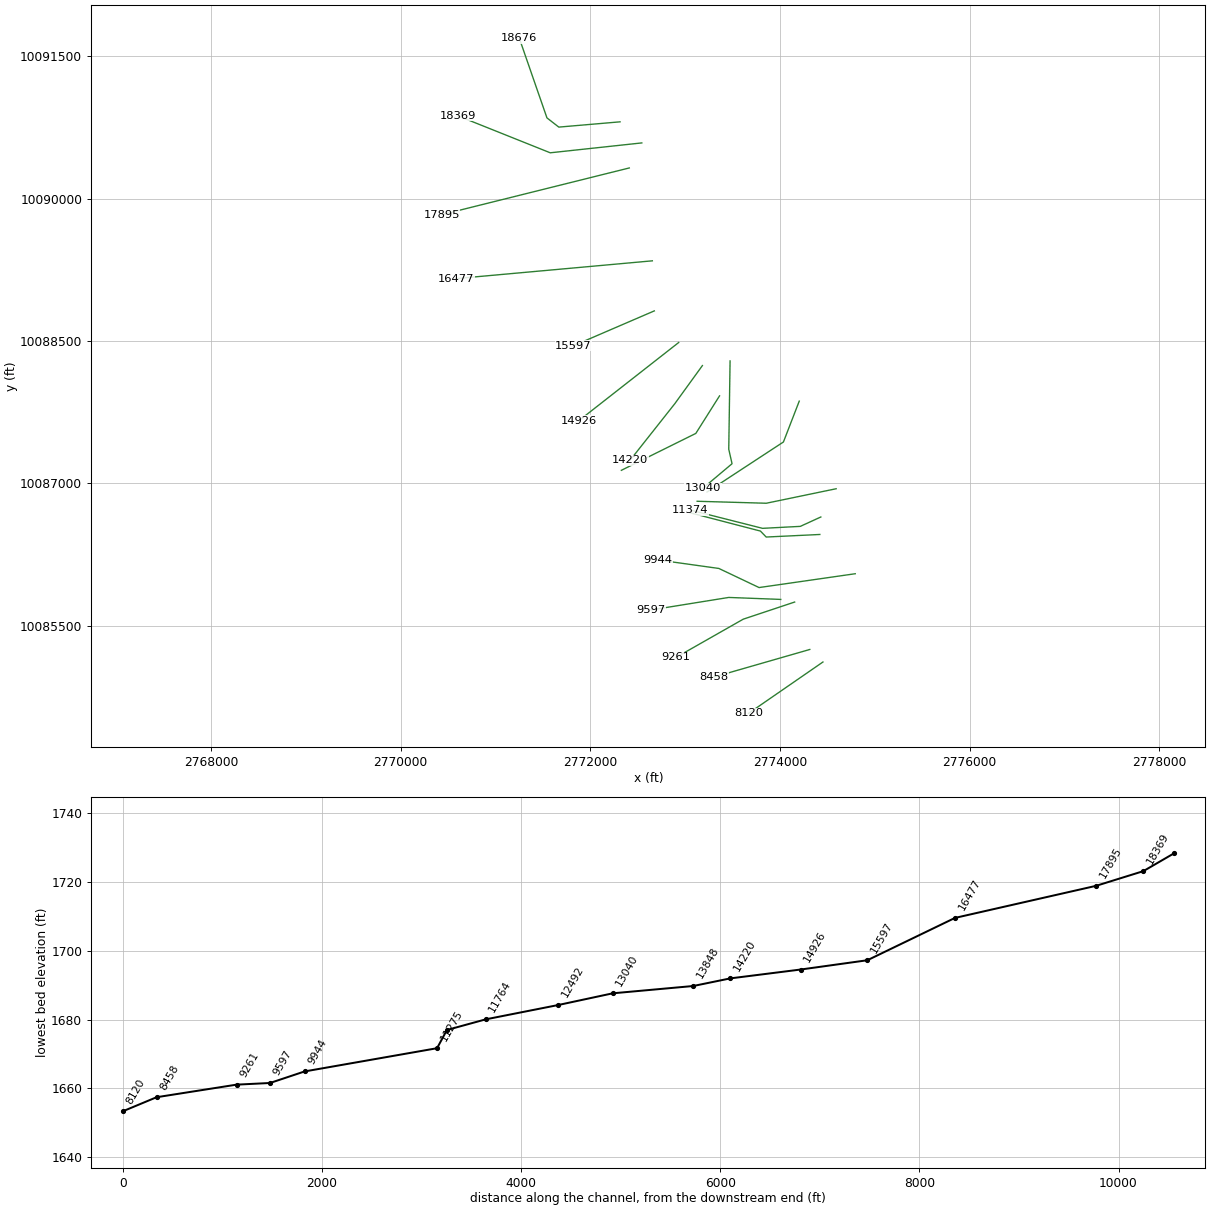
HEC-RAS study MIDDLE CREEK.prj: MIDDLE CREEK Base Level Engineering

--- MIDDLE CREEK.g01 (geometry) --- (continued)

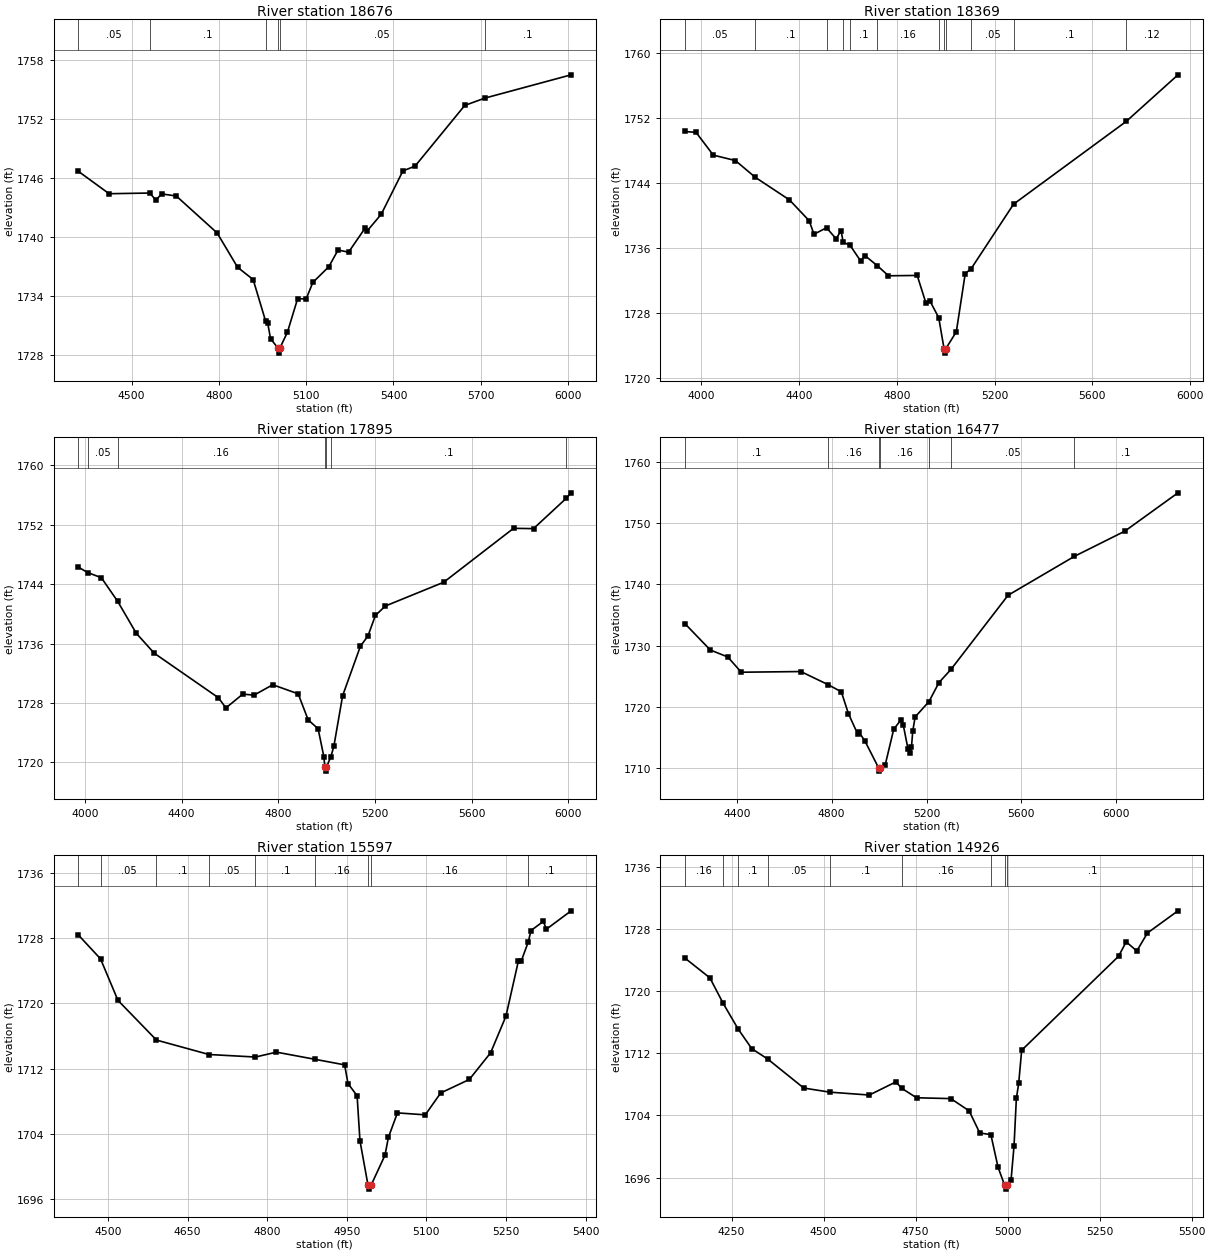
Type RM Length L Ch R = 1 ,18676   ,307,307,307
BEGIN DESCRIPTION:
MIDDLE CREEK 40.0
END DESCRIPTION:
XS GIS Cut Line= 4
      2772314.33     10090810.13      2771668.46     10090754.57
      2771543.46     10090851.79      2771252.37     10091690.39
#Sta/Elev= 30
  4316.3 1746.73  4422.6 1744.44  4562.5 1744.51  4583.1 1743.79  4603.2 1744.42
  4653.4 1744.21  4793.9 1740.45  4864.2 1736.96  4917.7 1735.71  4960.8 1731.46
  4967.7  1731.3  4977.4  1729.7  5003.4 1728.73  5006.2 1728.23  5009.4 1728.73
  5035.4 1730.35  5070.7 1733.78  5099.6 1733.73  5122.9 1735.42  5177.9 1737.02
  5209.4 1738.71  5245.8  1738.5  5302.7 1740.95    5308  1740.6  5357.9 1742.35
  5432.5 1746.76  5474.3 1747.25  5645.1 1753.42  5713.8 1754.16  6010.6 1756.53
#Mann= 6 ,-1 , 0
  4316.3     .05       0  4562.5      .1       0  4960.8     .05       0
  5003.4     .04       0  5009.4     .05       0  5713.8      .1       0
Bank Sta=5003.4,5009.4
XS Rating Curve= 0 ,0
Exp/Cntr=0.3,0.1

Type RM Length L Ch R = 1 ,18369   ,474,474,474
BEGIN DESCRIPTION:
MIDDLE CREEK 39.0
END DESCRIPTION:
XS GIS Cut Line= 3
      2772543.44      10090587.9      2771578.18     10090483.73
      2770605.94     10090872.63
#Sta/Elev= 30
  3933.1  1750.3  3978.3 1750.19  4048.7  1747.4  4139.3 1746.73  4220.3 1744.68
  4360.5  1741.9    4441 1739.35  4461.1 1737.68  4512.4 1738.48  4551.6 1737.12
  4571.8 1738.12  4580.5 1736.71    4609 1736.31  4652.2 1734.39  4669.1 1735.07
  4720.9  1733.8    4766 1732.58  4883.6 1732.62  4918.6 1729.29    4936 1729.47
  4971.7 1727.43  4993.7 1723.58  4996.5 1723.08  4999.7 1723.58  5043.7  1725.7
  5080.2 1732.85  5104.2 1733.44  5278.2 1741.38    5739 1751.53  5951.1 1757.26
#Mann= 12 ,-1 , 0
  3933.1     .05       0  4220.3      .1       0  4512.4     .05       0
  4580.5     .16       0    4609      .1       0  4720.9     .16       0
  4971.7      .1       0  4993.7     .07       0  4999.7      .1       0
  5104.2     .05       0  5278.2      .1       0    5739     .12       0
Bank Sta=4993.7,4999.7
XS Rating Curve= 0 ,0
Exp/Cntr=0.3,0.1

Type RM Length L Ch R = 1 ,17895   ,1418,1418,1418
BEGIN DESCRIPTION:
MIDDLE CREEK 38.0
END DESCRIPTION:
XS GIS Cut Line= 2
      2772411.48       10090324.      2770432.86     10089831.08
#Sta/Elev= 30
  3972.5  1746.3  4011.5 1745.56  4068.4 1744.86  4135.8 1741.68  4212.6 1737.39
  4286.9  1734.7  4552.7  1728.7  4583.6 1727.33  4653.4 1729.19  4699.9 1729.05
  4777.3 1730.45  4882.5 1729.23  4923.7 1725.73    4965 1724.52  4988.9 1720.75
  4992.9 1719.32  4995.6 1718.82  4998.9 1719.32  5017.6 1720.74  5030.2 1722.18
  5066.4 1728.97  5140.1 1735.65  5171.1 1737.01    5202 1739.78  5243.2 1741.05
  5484.5 1744.25  5773.5 1751.51  5856.1 1751.47  5991.4 1755.55  6011.6 1756.29
#Mann= 7 ,-1 , 0
  3972.5      .1       0  4011.5     .05       0  4135.8     .16       0
  4992.9     .07       0  4998.9     .16       0  5017.6      .1       0
  5991.4     .05       0
Bank Sta=4992.9,4998.9
XS Rating Curve= 0 ,0
Exp/Cntr=0.3,0.1

Type RM Length L Ch R = 1 ,16477   ,880,880,880
BEGIN DESCRIPTION:
MIDDLE CREEK 35.0
END DESCRIPTION:
XS GIS Cut Line= 2
      2772654.54     10089344.84      2770585.12     10089157.34
#Sta/Elev= 30
    4182 1733.58  4288.5 1729.29  4362.2 1728.15    4419 1725.66  4670.1 1725.77
    4785 1723.63  4840.8 1722.46  4870.9 1718.87  4910.3 1715.52  4915.4 1715.87
  4941.2 1714.35  4998.4    1710  5001.2  1709.5  5004.4    1710    5026 1710.55
  5061.7 1716.35  5091.8 1717.85  5101.8 1717.07  5121.9 1713.11  5131.6  1712.4
  5136.6 1713.48    5142 1716.07    5152 1718.35  5210.4 1720.87  5252.4 1723.97
    5303 1726.12  5543.6 1738.23  5823.3 1744.59  6035.6  1748.7  6259.9 1754.97
#Mann= 7 ,-1 , 0
    4182      .1       0    4785     .16       0  4998.4     .07       0
  5004.4     .16       0  5210.4      .1       0    5303     .05       0
  5823.3      .1       0
Bank Sta=4998.4,5004.4
XS Rating Curve= 0 ,0
Exp/Cntr=0.3,0.1

Type RM Length L Ch R = 1 ,15597   ,671,671,671
BEGIN DESCRIPTION:
MIDDLE CREEK 33.0
END DESCRIPTION:
XS GIS Cut Line= 2
      2772675.38     10088817.06      2771822.31     10088449.47
#Sta/Elev= 30
  4443.9  1728.4    4486 1725.45  4518.8 1720.36  4591.4 1715.49  4690.3 1713.72
    4778 1713.41  4817.5 1714.01    4891 1713.12    4946 1712.45  4952.3 1710.16
  4969.5 1708.66  4974.9 1703.14    4990 1697.71  4992.8 1697.21    4996 1697.71
    5022 1701.36  5028.5 1703.56  5045.5 1706.56    5098 1706.32    5127    1709
    5181 1710.66  5221.1 1713.93    5250 1718.42  5273.6 1725.23    5279 1725.21
  5292.2 1727.55  5297.1 1728.92  5320.6 1730.05  5326.1 1729.08  5372.8 1731.34
#Mann= 9 ,-1 , 0
  4443.9     .16       0    4486     .05       0  4591.4      .1       0
  4690.3     .05       0    4778      .1       0    4891     .16       0
    4990     .07       0    4996     .16       0  5292.2      .1       0
Bank Sta=4990,4996
XS Rating Curve= 0 ,0
Exp/Cntr=0.3,0.1

Type RM Length L Ch R = 1 ,14926   ,706,706,706
BEGIN DESCRIPTION:
MIDDLE CREEK 31.0
END DESCRIPTION:
XS GIS Cut Line= 2
      2772932.33     10088483.72      2771877.69     10087658.05
#Sta/Elev= 30
  4123.5 1724.21    4191 1721.68  4227.2 1718.39  4267.9 1715.09  4304.9 1712.57
  4348.4 1711.23    4446 1707.51  4517.1 1706.98  4624.2 1706.61  4696.5  1708.3
  4712.1 1707.48  4752.5 1706.26  4845.7 1706.15  4895.4 1704.58  4924.3 1701.73
  4954.5 1701.52    4974 1697.33  4991.9 1695.01  4994.6 1694.51  4997.9 1695.01
  5009.3 1695.66  5017.4 1700.03  5023.8 1706.18  5030.1 1708.12  5038.2 1712.37
  5301.4 1724.45  5322.2 1726.31  5351.1 1725.14    5380 1727.45  5462.9  1730.3
#Mann= 9 ,-1 , 0
  4123.5     .16       0  4227.2     .05       0  4267.9      .1       0
  4348.4     .05       0  4517.1      .1       0  4712.1     .16       0
  4954.5      .1       0  4991.9     .07       0  4997.9      .1       0
Bank Sta=4991.9,4997.9
XS Rating Curve= 0 ,0
Exp/Cntr=0.3,0.1

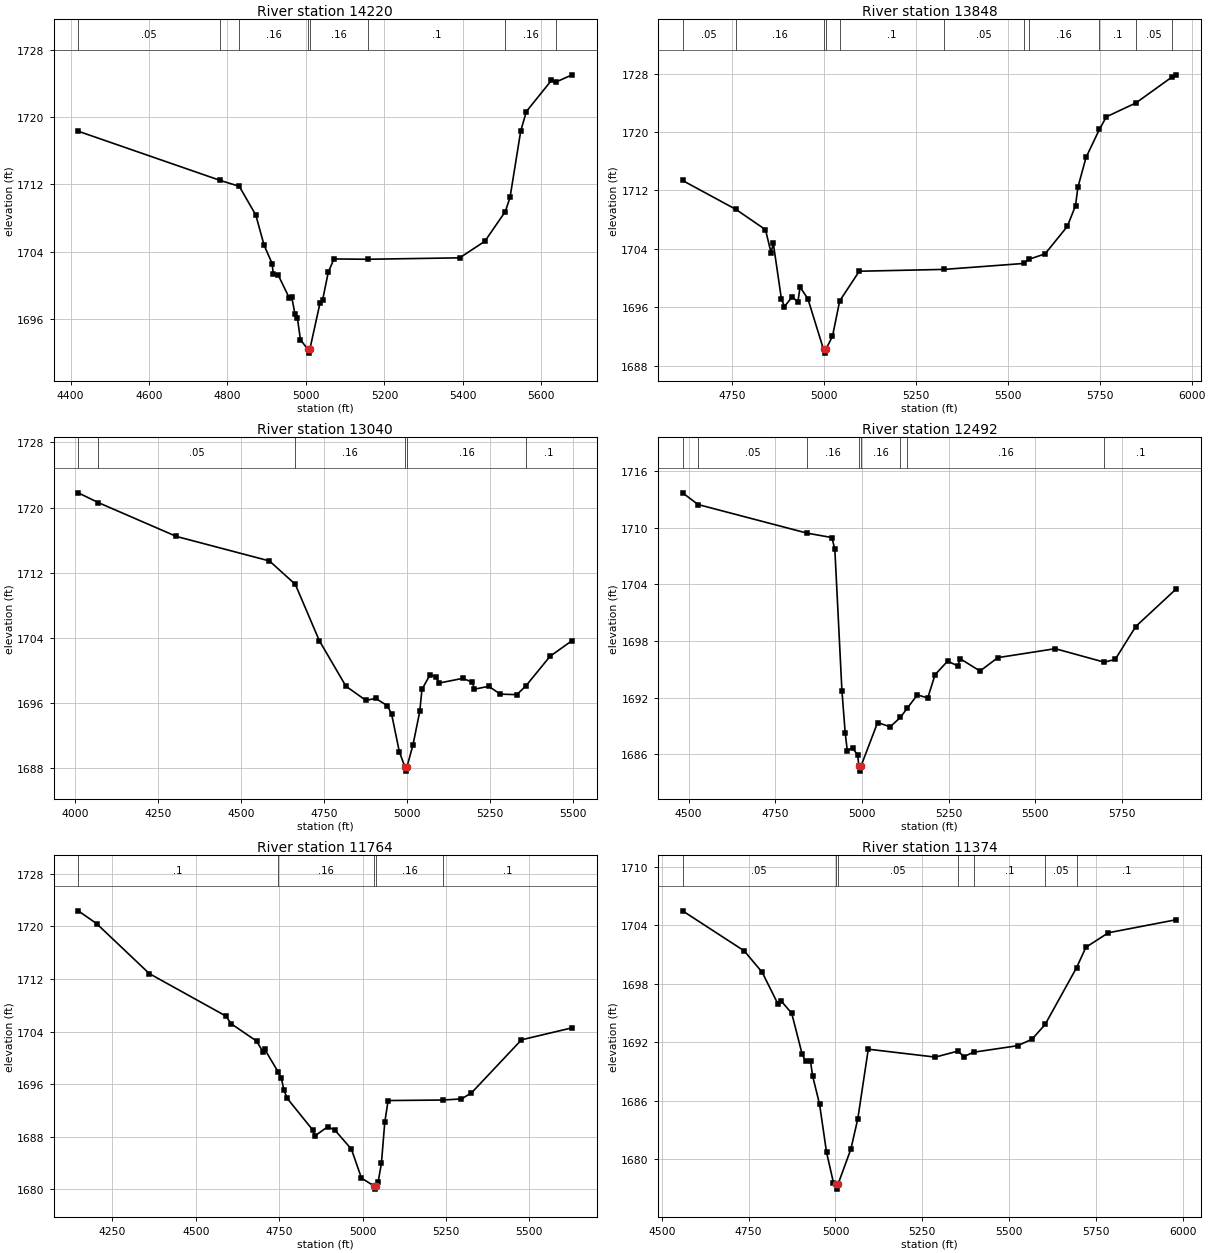
Type RM Length L Ch R = 1 ,14220   ,372,372,372
BEGIN DESCRIPTION:
MIDDLE CREEK 30.0
END DESCRIPTION:
XS GIS Cut Line= 3
      2773182.37     10088240.71      2772890.68      10087837.9
      2772418.45     10087240.67
#Sta/Elev= 30
  4419.7  1718.3    4782 1712.45  4830.1 1711.76  4872.4 1708.33  4893.3 1704.77
  4914.1 1702.56  4916.5 1701.37  4928.7 1701.28  4957.6 1698.49  4963.9 1698.58
    4972 1696.61  4978.4 1696.06  4986.1 1693.53  5004.2 1692.44    5007 1691.94
  5010.2 1692.44  5036.1 1697.93  5042.5 1698.24  5056.9 1701.54  5071.4 1703.13
  5157.4 1703.09  5391.9 1703.26  5456.1 1705.23  5508.2 1708.76  5520.2 1710.43
  5547.4 1718.31  5561.8 1720.64  5625.9 1724.35  5637.7 1724.15  5678.4    1725
#Mann= 8 ,-1 , 0
  4419.7     .05       0    4782      .1       0  4830.1     .16       0
  5004.2     .07       0  5010.2     .16       0  5157.4      .1       0
  5508.2     .16       0  5637.7      .1       0
Bank Sta=5004.2,5010.2
XS Rating Curve= 0 ,0
Exp/Cntr=0.3,0.1

Type RM Length L Ch R = 1 ,13848   ,808,808,808
BEGIN DESCRIPTION:
MIDDLE CREEK 34.0
END DESCRIPTION:
XS GIS Cut Line= 3
      2773362.91     10087921.24       2773112.9      10087525.4
      2772328.16      10087136.5
#Sta/Elev= 30
  4614.5 1713.36  4759.5 1709.41  4840.2 1706.63  4855.5 1703.45  4861.4  1704.8
  4883.6 1697.13  4891.9 1696.11  4913.1 1697.44  4928.4 1696.72  4934.3 1698.77
  4955.5 1697.18  4998.3 1690.23  5001.1 1689.73  5004.3 1690.23  5022.5 1692.02
  5042.2 1696.88  5095.5 1700.94  5326.8 1701.19  5542.4    1702    5558 1702.59
    5601 1703.31  5661.6 1707.07    5684 1709.91  5690.3  1712.4  5712.6 1716.51
  5749.1 1720.37  5768.1 1722.08  5848.2 1723.97  5946.2 1727.51  5958.5 1727.82
#Mann= 11 ,-1 , 0
  4614.5     .05       0  4759.5     .16       0  4998.3     .07       0
  5004.3     .16       0  5042.2      .1       0  5326.8     .05       0
  5542.4      .1       0    5558     .16       0  5749.1      .1       0
  5848.2     .05       0  5946.2      .1       0
Bank Sta=4998.3,5004.3
XS Rating Curve= 0 ,0
Exp/Cntr=0.3,0.1

Type RM Length L Ch R = 1 ,13040   ,548,548,548
BEGIN DESCRIPTION:
MIDDLE CREEK 28.0
END DESCRIPTION:
XS GIS Cut Line= 4
      2773474.01     10088289.29      2773460.12     10087358.73
      2773494.85     10087205.96      2773189.27     10086948.99
#Sta/Elev= 30
  4010.4 1721.81  4070.8 1720.61    4306 1716.45    4586 1713.44  4663.9 1710.56
    4736 1703.65  4816.1 1698.05  4876.1 1696.31  4906.1 1696.54  4941.1 1695.64
  4953.7 1694.62    4977 1689.99  4993.8 1688.11  4996.6 1687.61  4999.8 1688.11
    5018 1690.83  5038.5 1694.95    5045 1697.65  5069.3 1699.44  5088.1 1699.23
  5096.3 1698.43    5168 1699.01  5196.6 1698.53  5203.1 1697.68    5246 1698.03
  5281.2 1697.07  5330.6 1697.01  5357.8 1698.08  5430.7 1701.72    5497 1703.65
#Mann= 6 ,-1 , 0
  4010.4      .1       0  4070.8     .05       0  4663.9     .16       0
  4993.8     .07       0  4999.8     .16       0  5357.8      .1       0
Bank Sta=4993.8,4999.8
XS Rating Curve= 0 ,0
Exp/Cntr=0.3,0.1

Type RM Length L Ch R = 1 ,12492   ,728,728,728
BEGIN DESCRIPTION:
MIDDLE CREEK 27.0
END DESCRIPTION:
XS GIS Cut Line= 3
      2774203.19      10087865.7      2774036.51     10087435.12
      2773230.93     10086907.32
#Sta/Elev= 30
  4482.6 1713.69  4527.4 1712.45  4841.9 1709.42  4913.6 1708.95    4922  1707.7
  4942.4 1692.75    4952 1688.21  4957.9 1686.39    4973 1686.67  4988.1 1685.89
  4991.1 1684.71  4993.9 1684.21  4997.1 1684.71  5045.4 1689.36  5081.6  1688.9
  5111.1  1689.9  5130.8 1690.87  5159.9 1692.28  5190.1 1691.97  5211.2 1694.43
  5247.4 1695.86  5276.7 1695.36  5283.6 1696.12  5340.8 1694.81  5392.1 1696.23
  5557.9 1697.18  5699.5 1695.75    5731 1696.05  5790.1 1699.53  5907.4 1703.53
#Mann= 8 ,-1 , 0
  4482.6      .1       0  4527.4     .05       0  4841.9     .16       0
  4991.1     .07       0  4997.1     .16       0  5111.1     .05       0
  5130.8     .16       0  5699.5      .1       0
Bank Sta=4991.1,4997.1
XS Rating Curve= 0 ,0
Exp/Cntr=0.3,0.1

Type RM Length L Ch R = 1 ,11764   ,390,390,390
BEGIN DESCRIPTION:
MIDDLE CREEK 26.0
END DESCRIPTION:
XS GIS Cut Line= 3
      2774592.09     10086942.07      2773855.96     10086789.29
      2773126.78     10086810.12
#Sta/Elev= 30
  4147.3 1722.34  4202.1 1720.41  4360.5  1712.8  4590.2 1706.35    4606 1705.18
  4682.1 1702.55  4701.2 1700.94  4706.3 1701.33  4746.3 1697.91  4756.5 1696.93
  4763.8 1695.18    4774 1693.85  4851.6 1688.98  4856.7 1688.12  4895.3 1689.52
  4916.6 1689.05  4966.6 1686.13  4996.7 1681.74  5033.7 1680.55  5036.4 1680.05
  5039.7 1680.55  5046.7 1681.11  5056.7 1683.98  5066.7 1690.18  5076.7 1693.51
  5242.1 1693.59  5296.8 1693.76  5326.8 1694.67  5476.8 1702.74  5628.6 1704.56
#Mann= 5 ,-1 , 0
  4147.3      .1       0  4746.3     .16       0  5033.7     .07       0
  5039.7     .16       0  5242.1      .1       0
Bank Sta=5033.7,5039.7
XS Rating Curve= 0 ,0
Exp/Cntr=0.3,0.1

Type RM Length L Ch R = 1 ,11374   ,99,99,99
BEGIN DESCRIPTION:
Mapping XS 8a48fd5d
END DESCRIPTION:
XS GIS Cut Line= 4
      2774430.97     10086644.48       2774214.8     10086545.51
      2773816.37     10086524.68      2773055.94     10086717.39
#Sta/Elev= 30
  4559.9  1705.5  4737.5 1701.39    4789  1699.2    4834 1695.98    4844 1696.25
  4874.1 1694.99  4904.1  1690.8  4914.1 1690.07  4928.3 1690.06  4934.2 1688.57
  4954.2 1685.67  4974.2 1680.76  4994.3  1677.6  5001.3 1677.46    5004 1676.96
  5007.3 1677.46  5044.3 1681.06  5064.3 1684.18  5094.4 1691.31  5287.3  1690.5
    5352 1691.11  5369.8 1690.56  5397.6    1691  5524.6 1691.67  5565.8 1692.34
  5603.4 1693.85    5694 1699.68  5720.6 1701.76  5785.3 1703.25  5981.1 1704.59
#Mann= 7 ,-1 , 0
  4559.9     .05       0  5001.3     .04       0  5007.3     .05       0
    5352     .16       0  5397.6      .1       0  5603.4     .05       0
    5694      .1       0
Bank Sta=5001.3,5007.3
XS Rating Curve= 0 ,0
Exp/Cntr=0.3,0.1

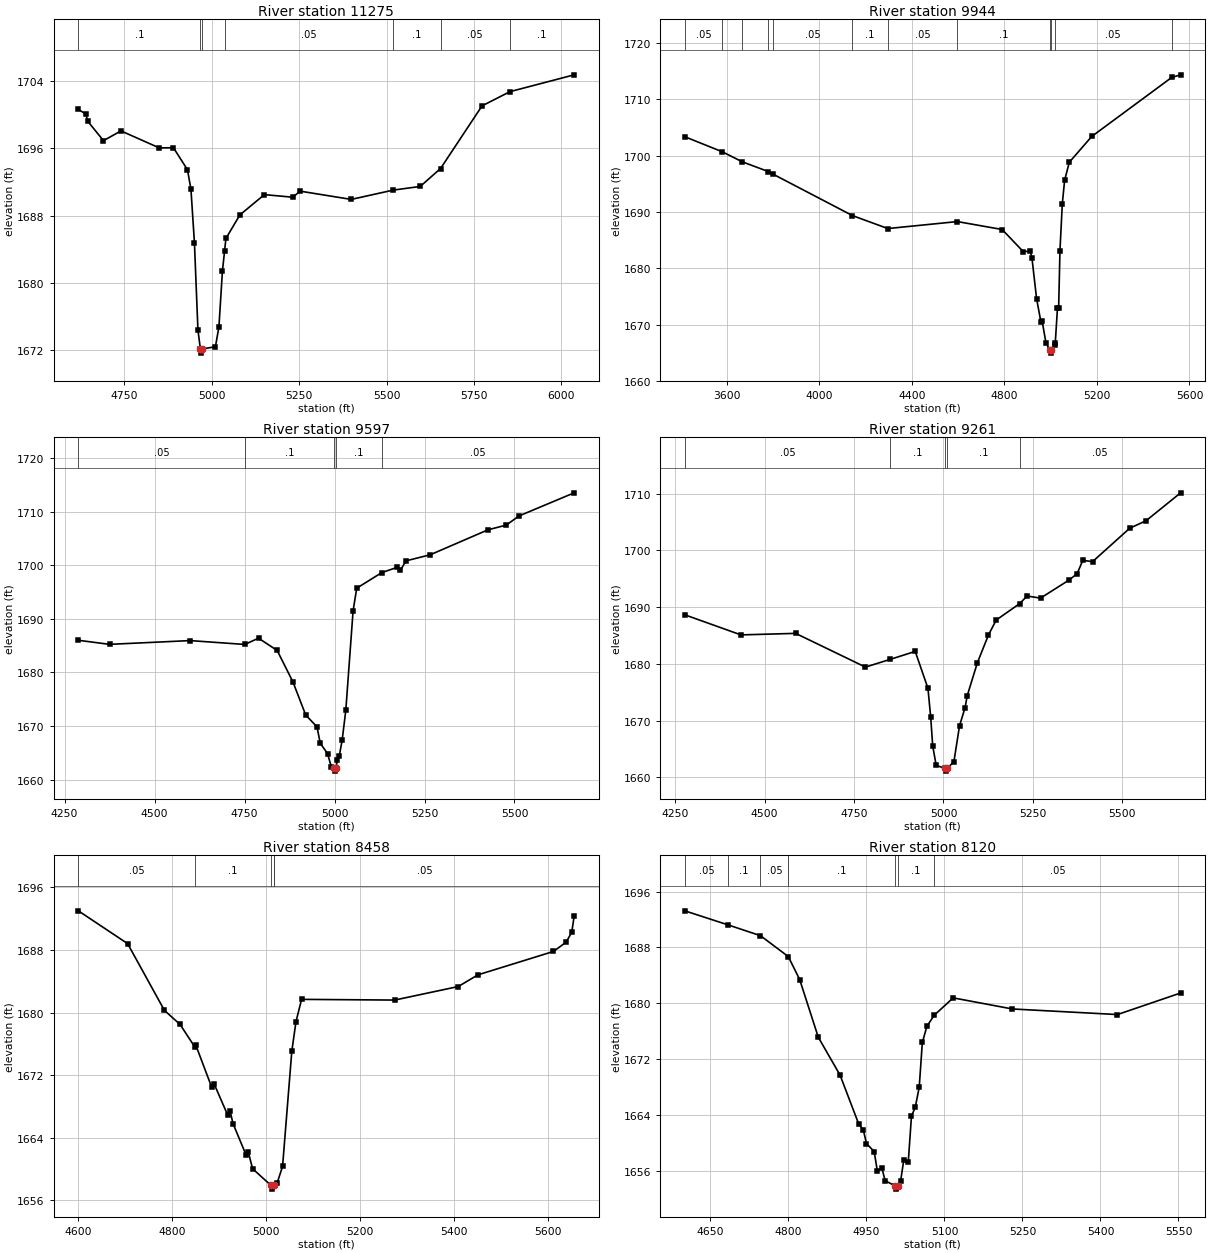
Type RM Length L Ch R = 1 ,11275   ,1331,1331,1331
BEGIN DESCRIPTION:
MIDDLE CREEK 25.0
END DESCRIPTION:
XS GIS Cut Line= 4
      2774420.38     10086459.98      2773854.74     10086433.01
      2773793.97     10086495.95       2773053.3     10086688.69
#Sta/Elev= 30
  4617.9 1700.62  4639.5 1700.07  4644.5 1699.23  4689.9 1696.91  4739.9 1698.07
  4849.6 1696.05  4890.1 1696.07  4930.2 1693.46  4940.2 1691.14  4950.2 1684.78
  4960.2 1674.42  4967.2 1672.17    4970 1671.67  4973.2 1672.17  5010.3 1672.43
  5020.3  1674.8  5030.3 1681.41  5036.4 1683.78  5040.3 1685.29  5080.3 1688.09
  5150.4  1690.5  5231.5 1690.19  5252.9 1690.91    5399 1689.93  5518.3 1691.03
  5596.4 1691.47  5654.6  1693.6  5773.3 1701.04  5853.2 1702.73    6037 1704.73
#Mann= 7 ,-1 , 0
  4617.9      .1       0  4967.2     .07       0  4973.2      .1       0
  5036.4     .05       0  5518.3      .1       0  5654.6     .05       0
  5853.2      .1       0
Bank Sta=4967.2,4973.2
XS Rating Curve= 0 ,0
Exp/Cntr=0.3,0.1

Type RM Length L Ch R = 1 ,9944    ,347,347,347
BEGIN DESCRIPTION:
MIDDLE CREEK 24.0
END DESCRIPTION:
XS GIS Cut Line= 4
      2774793.45     10086046.23      2773779.57      10085900.4
      2773355.96     10086101.79      2772711.78     10086191.84
#Sta/Elev= 30
    3418 1703.38  3580.8 1700.69  3666.1 1698.93  3778.9 1697.19  3799.9 1696.72
    4143 1689.36  4295.9 1687.06  4596.4  1688.3  4790.1 1686.89  4880.9 1682.98
  4911.4 1683.03  4918.9 1681.85  4939.1 1674.58  4957.9 1670.43  4962.9 1670.65
  4979.5 1666.75  4996.7 1665.42  4999.5 1664.92  5002.7 1665.42  5016.6 1666.43
  5019.9 1666.79  5029.3  1672.9  5034.4 1672.96  5040.1 1683.15  5050.2 1691.45
  5060.3 1695.65  5080.5 1698.84  5177.3 1703.42    5523 1713.91  5561.8 1714.38
#Mann= 12 ,-1 , 0
    3418     .05       0  3580.8      .1       0  3666.1     .05       0
  3778.9      .1       0  3799.9     .05       0    4143      .1       0
  4295.9     .05       0  4596.4      .1       0  4996.7     .07       0
  5002.7      .1       0  5016.6     .05       0    5523      .1       0
Bank Sta=4996.7,5002.7
XS Rating Curve= 0 ,0
Exp/Cntr=0.3,0.1

Type RM Length L Ch R = 1 ,9597    ,336,336,336
BEGIN DESCRIPTION:
MIDDLE CREEK 21.0
END DESCRIPTION:
XS GIS Cut Line= 3
      2774008.72      10085775.4      2773460.12     10085796.23
      2772642.05     10085664.51
#Sta/Elev= 30
  4288.2 1686.01  4374.8 1685.25  4598.7 1685.95  4750.7 1685.23  4788.8  1686.4
  4840.6 1684.11  4884.4 1678.24  4919.9 1672.06  4951.3 1669.83  4960.4 1666.77
  4980.7 1664.83  4990.8 1662.43  4997.9 1662.07  5000.7 1661.57  5003.9 1662.07
  5008.1 1663.74  5013.2 1664.41  5021.2 1667.36  5031.3  1672.9  5051.6 1691.51
  5061.7 1695.74  5131.3 1698.65  5173.1 1699.61  5183.3 1699.11  5198.7 1700.85
  5265.6 1701.97  5426.3 1706.64    5477 1707.52  5512.9 1709.24  5665.8 1713.55
#Mann= 5 ,-1 , 0
  4288.2     .05       0  4750.7      .1       0  4997.9     .07       0
  5003.9      .1       0  5131.3     .05       0
Bank Sta=4997.9,5003.9
XS Rating Curve= 0 ,0
Exp/Cntr=0.3,0.1

Type RM Length L Ch R = 1 ,9261    ,803,803,803
BEGIN DESCRIPTION:
MIDDLE CREEK 20.0
END DESCRIPTION:
XS GIS Cut Line= 3
      2774154.59     10085747.63       2773612.9     10085567.07
       2772904.6     10085164.31
#Sta/Elev= 30
  4277.1 1688.63  4434.1 1685.09  4586.9 1685.36  4781.9 1679.42  4850.7 1680.77
  4921.1 1682.18  4956.7 1675.68  4964.3 1670.66    4970 1665.53  4979.7 1662.09
  5004.5 1661.59  5007.3 1661.09  5010.5 1661.59  5029.2 1662.74    5045 1669.09
  5060.3 1672.25  5066.6  1674.4  5094.8 1680.18  5125.7 1685.06  5147.4  1687.7
  5212.7 1690.59  5233.8 1691.94  5271.3 1691.57    5352 1694.79  5373.7 1695.89
  5389.5 1698.22  5416.9    1698  5520.4 1703.87  5566.4 1705.21  5662.9 1710.12
#Mann= 5 ,-1 , 0
  4277.1     .05       0  4850.7      .1       0  5004.5     .07       0
  5010.5      .1       0  5212.7     .05       0
Bank Sta=5004.5,5010.5
XS Rating Curve= 0 ,0
Exp/Cntr=0.3,0.1

Type RM Length L Ch R = 1 ,8458    ,338,338,338
BEGIN DESCRIPTION:
MIDDLE CREEK 19.0
END DESCRIPTION:
XS GIS Cut Line= 2
      2774314.25     10085247.61       2773301.9     10084956.39
#Sta/Elev= 30
  4601.3 1692.99    4706  1688.8  4784.2 1680.27  4817.4 1678.48  4848.3 1675.64
  4851.1  1675.8  4884.8 1670.43    4890 1670.86  4918.5 1666.91  4923.7 1667.42
  4929.9 1665.82  4957.4 1661.84  4962.6 1662.13  4971.5 1660.05  5010.1 1657.94
  5012.9 1657.44  5016.1 1657.94    5018    1658  5023.5 1658.19  5035.2 1660.34
  5054.8 1675.04  5063.7 1678.83  5075.6 1681.68  5273.3 1681.59  5408.5 1683.32
  5450.2 1684.81  5610.7  1687.8  5637.5 1688.98  5649.6 1690.25  5654.7 1692.31
#Mann= 5 ,-1 , 0
  4601.3     .05       0  4848.3      .1       0  5010.1     .07       0
  5016.1      .1       0    5018     .05       0
Bank Sta=5010.1,5016.1
XS Rating Curve= 0 ,0
Exp/Cntr=0.3,0.1

Type RM Length L Ch R = 1 ,8120    ,544,544,544
BEGIN DESCRIPTION:
MIDDLE CREEK 18.0
END DESCRIPTION:
XS GIS Cut Line= 2
      2774453.17     10085115.67      2773668.46     10084574.02
#Sta/Elev= 30
  4600.7 1693.24  4683.7 1691.23  4746.2 1689.68  4799.7 1686.69  4821.6  1683.4
  4857.4 1675.13  4899.3  1669.7  4935.2 1662.69    4944 1661.85  4950.1  1659.9
  4964.9 1658.75    4971 1655.96  4979.8 1656.39  4985.9 1654.58  5004.4 1653.87
  5007.2 1653.37  5010.4 1653.87  5015.6 1654.47  5021.7 1657.49  5030.5  1657.3
  5036.6 1663.83  5043.9  1665.1  5051.5 1667.96  5057.5 1674.39  5066.3  1676.7
  5080.2 1678.27  5116.8 1680.77  5230.6 1679.18  5432.7 1678.38  5554.2 1681.47
#Mann= 7 ,-1 , 0
  4600.7     .05       0  4683.7      .1       0  4746.2     .05       0
  4799.7      .1       0  5004.4     .07       0  5010.4      .1       0
  5080.2     .05       0
Bank Sta=5004.4,5010.4
XS Rating Curve= 0 ,0
Exp/Cntr=0.3,0.1