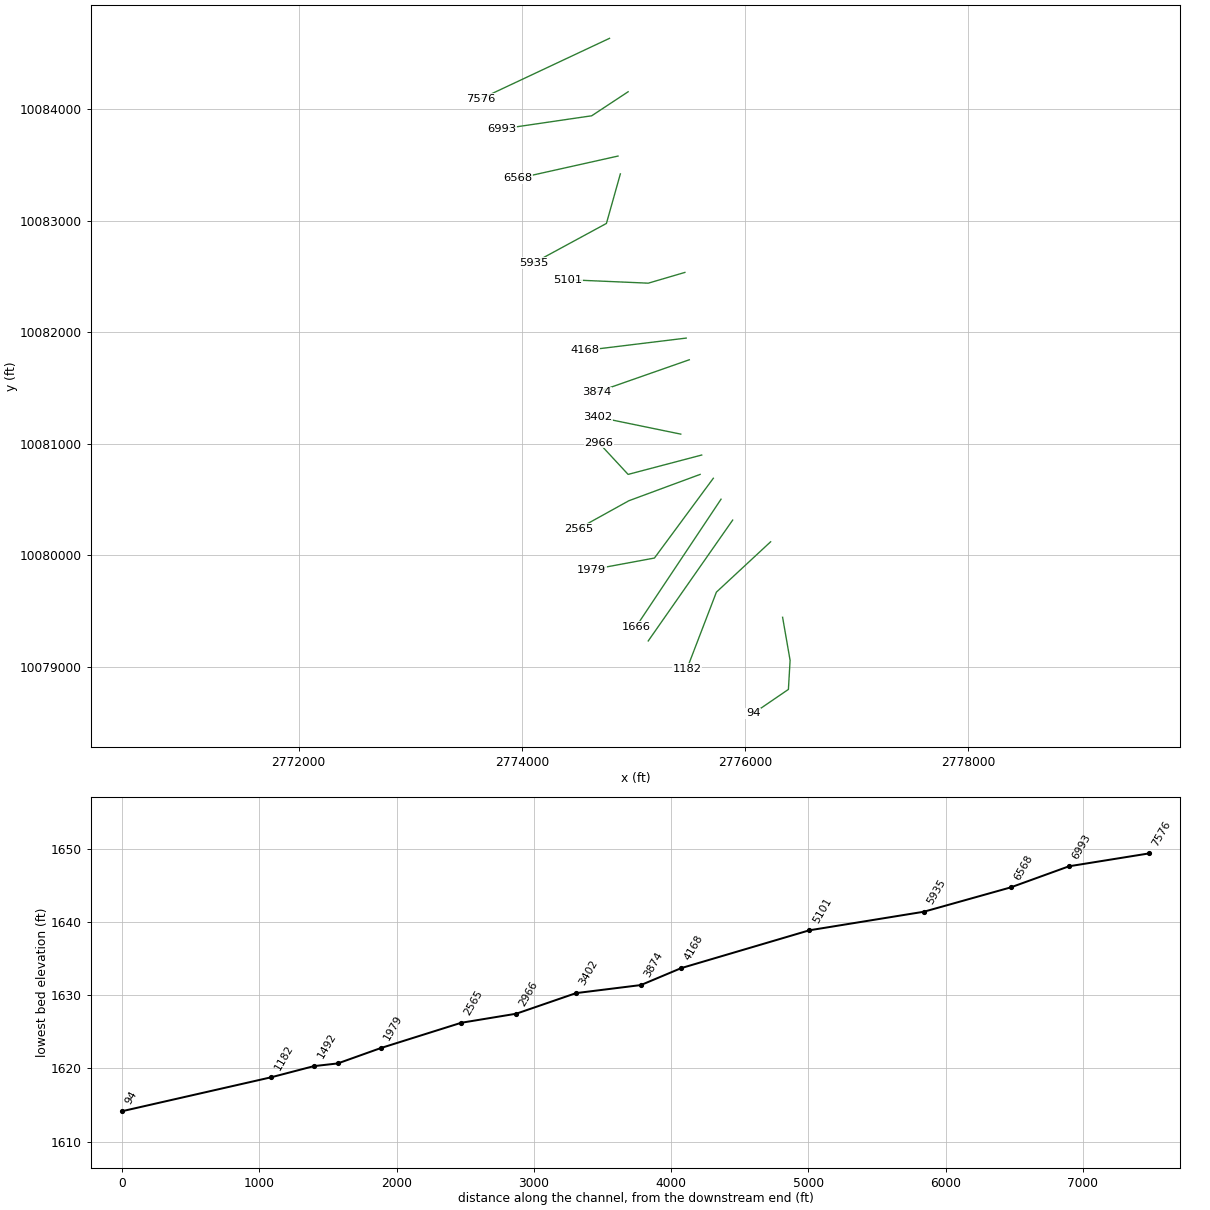
HEC-RAS study MIDDLE CREEK.prj: MIDDLE CREEK Base Level Engineering

--- MIDDLE CREEK.g01 (geometry) --- (continued)

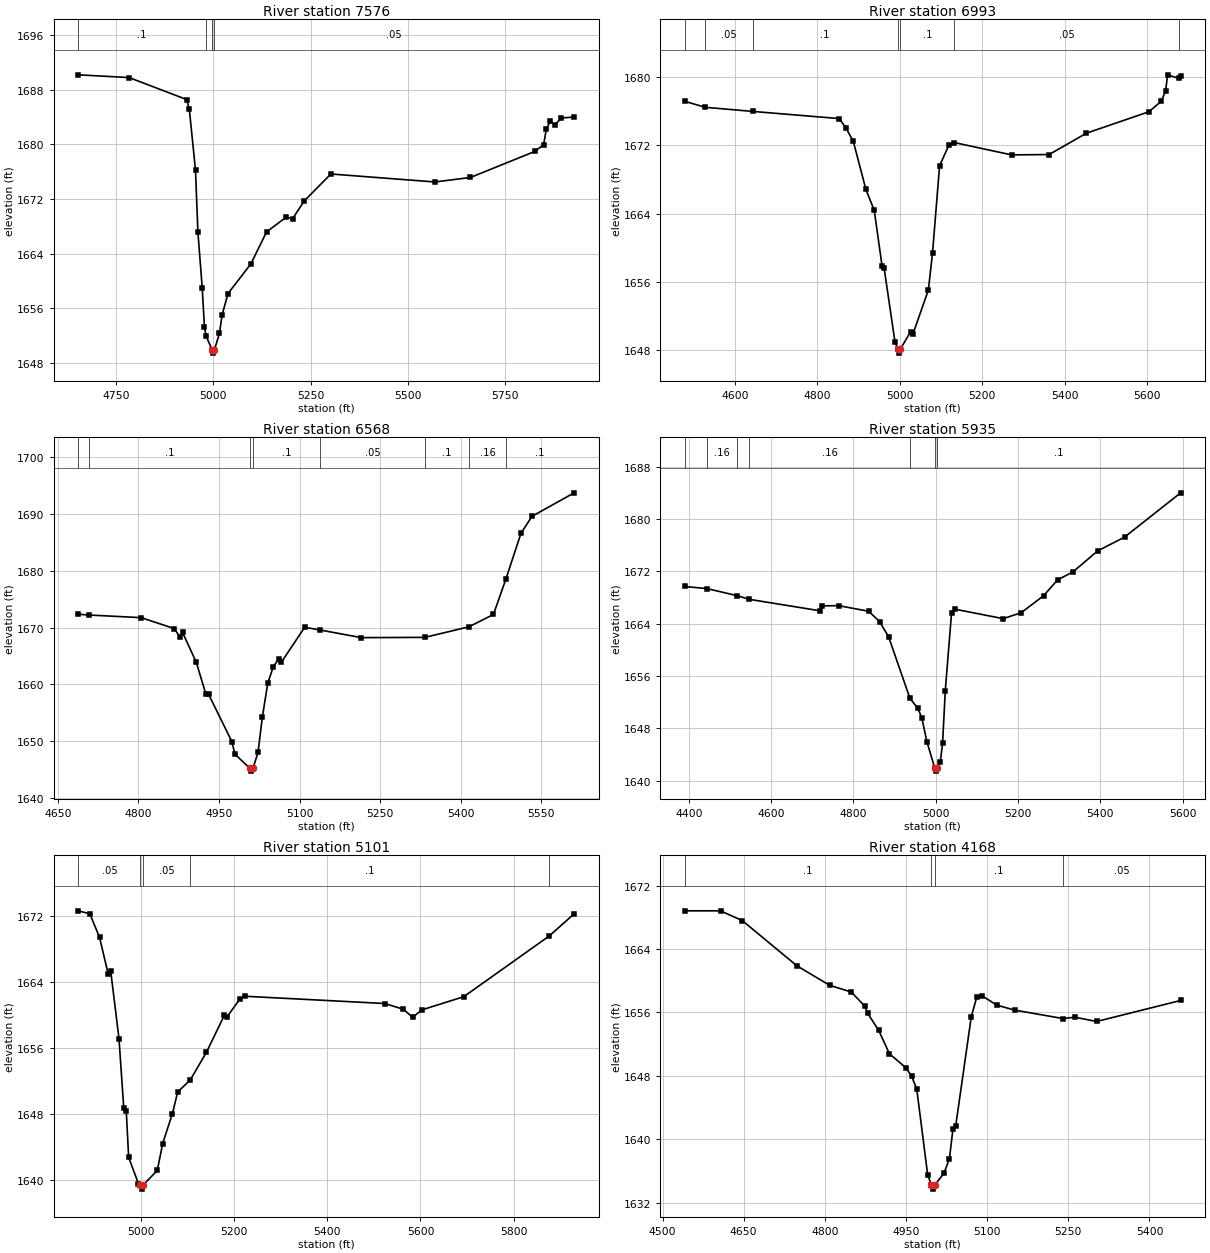
Type RM Length L Ch R = 1 ,7576    ,583,583,583
BEGIN DESCRIPTION:
MIDDLE CREEK 16.0
END DESCRIPTION:
XS GIS Cut Line= 2
      2774786.49      10084636.5      2773633.71     10084094.83
#Sta/Elev= 30
  4653.4  1690.2  4783.8  1689.8  4931.6 1686.58  4938.5 1685.16  4954.4 1676.21
  4960.6 1667.13  4971.6 1659.02  4977.3 1653.31  4981.7  1651.9  4997.1 1649.92
  4999.8 1649.42  5003.1 1649.92  5015.8  1652.3  5022.9 1655.07  5037.9 1658.15
  5096.8 1662.51  5136.9 1667.18    5188 1669.37  5203.7  1669.1  5233.6 1671.71
  5302.1 1675.67  5569.5  1674.5  5660.7 1675.16  5825.9 1678.97  5848.7 1679.98
  5855.5 1682.22    5866 1683.41  5877.6 1682.86  5894.3 1683.87  5927.1 1684.02
#Mann= 4 ,-1 , 0
  4653.4      .1       0  4981.7     .05       0  4997.1    .035       0
  5003.1     .05       0
Bank Sta=4997.1,5003.1
XS Rating Curve= 0 ,0
Exp/Cntr=0.3,0.1

Type RM Length L Ch R = 1 ,6993    ,425,425,425
BEGIN DESCRIPTION:
MIDDLE CREEK 15.0
END DESCRIPTION:
XS GIS Cut Line= 3
      2774953.14     10084157.32      2774626.79     10083942.07
      2773822.32     10083824.17
#Sta/Elev= 30
  4477.8 1677.13  4527.2 1676.43  4642.2 1675.95  4852.7 1675.11  4868.7 1674.05
    4887 1672.44  4917.6 1666.81  4937.8 1664.37  4956.8 1657.87  4961.9 1657.59
  4988.3 1648.92  4995.4 1648.16  4998.2 1647.66  5001.4 1648.16  5026.7 1650.19
  5031.7 1649.88  5069.2 1655.04  5079.3 1659.35  5096.5 1669.59  5119.7 1672.07
  5132.4  1672.3  5271.3 1670.86  5362.3  1670.9  5453.2  1673.4  5604.8 1675.91
  5635.2 1677.15  5645.3 1678.39  5650.3 1680.23    5677 1679.82  5681.8 1680.08
#Mann= 7 ,-1 , 0
  4477.8      .1       0  4527.2     .05       0  4642.2      .1       0
  4995.4     .07       0  5001.4      .1       0  5132.4     .05       0
    5677      .1       0
Bank Sta=4995.4,5001.4
XS Rating Curve= 0 ,0
Exp/Cntr=0.3,0.1

Type RM Length L Ch R = 1 ,6568    ,633,633,633
BEGIN DESCRIPTION:
MIDDLE CREEK 14.0
END DESCRIPTION:
XS GIS Cut Line= 2
      2774862.91     10083580.96      2773961.76     10083379.93
#Sta/Elev= 30
  4688.1 1672.33  4708.6 1672.19  4805.4 1671.73  4866.8 1669.81    4877 1668.36
  4882.1 1669.14  4907.8 1663.88  4925.6 1658.28  4930.7 1658.26  4974.2 1649.92
  4979.5 1647.78  5007.3 1645.27    5010 1644.77  5013.3 1645.27  5022.7 1648.05
  5030.8 1654.29    5041 1660.29  5051.3 1663.11  5061.1 1664.48  5066.2 1663.89
  5109.6 1670.05  5137.8 1669.57  5215.2 1668.22  5333.5 1668.27  5415.3 1670.12
  5461.1 1672.29  5484.4 1678.54  5512.3 1686.53  5532.8 1689.53  5611.4 1693.66
#Mann= 8 ,-1 , 0
  4688.1     .05       0  4708.6      .1       0  5007.3     .07       0
  5013.3      .1       0  5137.8     .05       0  5333.5      .1       0
  5415.3     .16       0  5484.4      .1       0
Bank Sta=5007.3,5013.3
XS Rating Curve= 0 ,0
Exp/Cntr=0.3,0.1

Type RM Length L Ch R = 1 ,5935    ,834,834,834
BEGIN DESCRIPTION:
MIDDLE CREEK 13.0
END DESCRIPTION:
XS GIS Cut Line= 3
      2774883.74     10083421.25      2774758.73     10082976.79
      2774105.93     10082622.61
#Sta/Elev= 30
  4390.5 1669.67  4444.2 1669.35  4517.8 1668.26  4547.6  1667.7  4719.5 1665.95
  4724.7 1666.71    4764 1666.74  4837.3 1665.88  4863.7  1664.3  4885.5 1661.99
  4937.3 1652.58  4956.8 1651.03  4966.3 1649.55  4978.6 1645.94  4997.5 1641.94
  5000.3 1641.44  5003.5 1641.94    5011 1642.78  5016.7 1645.69  5023.2 1653.72
  5038.5 1665.67  5045.9 1666.21    5164 1664.75  5207.8 1665.67    5262 1668.25
  5296.2  1670.7  5333.2 1671.89  5393.1  1675.1  5458.7 1677.22  5594.9 1683.99
#Mann= 7 ,-1 , 0
  4390.5     .05       0  4444.2     .16       0  4517.8     .05       0
  4547.6     .16       0  4937.3      .1       0  4997.5     .07       0
  5003.5      .1       0
Bank Sta=4997.5,5003.5
XS Rating Curve= 0 ,0
Exp/Cntr=0.3,0.1

Type RM Length L Ch R = 1 ,5101    ,933,933,933
BEGIN DESCRIPTION:
MIDDLE CREEK 10.0
END DESCRIPTION:
XS GIS Cut Line= 3
       2775462.2      10082537.7      2775134.07     10082441.34
      2774411.83     10082472.52
#Sta/Elev= 30
  4865.2 1672.59  4889.9 1672.23  4910.8 1669.37  4929.5  1664.9  4934.7 1665.31
  4952.5 1657.13  4962.8 1648.68  4968.1 1648.39  4973.3 1642.74  4994.2 1639.58
  4998.4  1639.4  5001.2  1638.9  5004.4  1639.4  5034.8 1641.16  5046.3 1644.42
  5067.1 1648.01  5078.6 1650.66  5105.6 1652.12  5140.1 1655.44  5178.8 1659.94
    5184 1659.71  5212.8 1661.97  5222.8 1662.25  5523.1 1661.37  5563.1 1660.68
  5583.1  1659.7  5603.2  1660.6  5693.2  1662.2  5876.7 1669.55  5930.1 1672.23
#Mann= 5 ,-1 , 0
  4865.2     .05       0  4998.4    .035       0  5004.4     .05       0
  5105.6      .1       0  5876.7     .05       0
Bank Sta=4998.4,5004.4
XS Rating Curve= 0 ,0
Exp/Cntr=0.3,0.1

Type RM Length L Ch R = 1 ,4168    ,294,294,294
BEGIN DESCRIPTION:
MIDDLE CREEK 9.0
END DESCRIPTION:
XS GIS Cut Line= 2
      2775473.97     10081949.01      2774564.33     10081837.91
#Sta/Elev= 30
  4541.2 1668.81  4607.2 1668.81  4647.5 1667.58  4748.2 1661.89  4808.7 1659.43
    4849 1658.57  4873.8  1656.8  4879.2 1655.88  4899.3 1653.78  4919.5 1650.78
  4949.7 1649.04  4960.4 1647.97  4969.9 1646.35    4990 1635.57  4997.1 1634.23
  4999.8 1633.73  5003.1 1634.23  5020.2 1635.73  5030.3 1637.57  5036.9 1641.36
  5041.9 1641.69  5070.6 1655.43  5080.7 1657.91  5090.8 1658.08  5118.4 1656.91
  5151.2 1656.29  5240.4 1655.23    5262  1655.4  5302.3 1654.86  5457.6 1657.51
#Mann= 4 ,-1 , 0
  4541.2      .1       0  4997.1     .07       0  5003.1      .1       0
  5240.4     .05       0
Bank Sta=4997.1,5003.1
XS Rating Curve= 0 ,0
Exp/Cntr=0.3,0.1

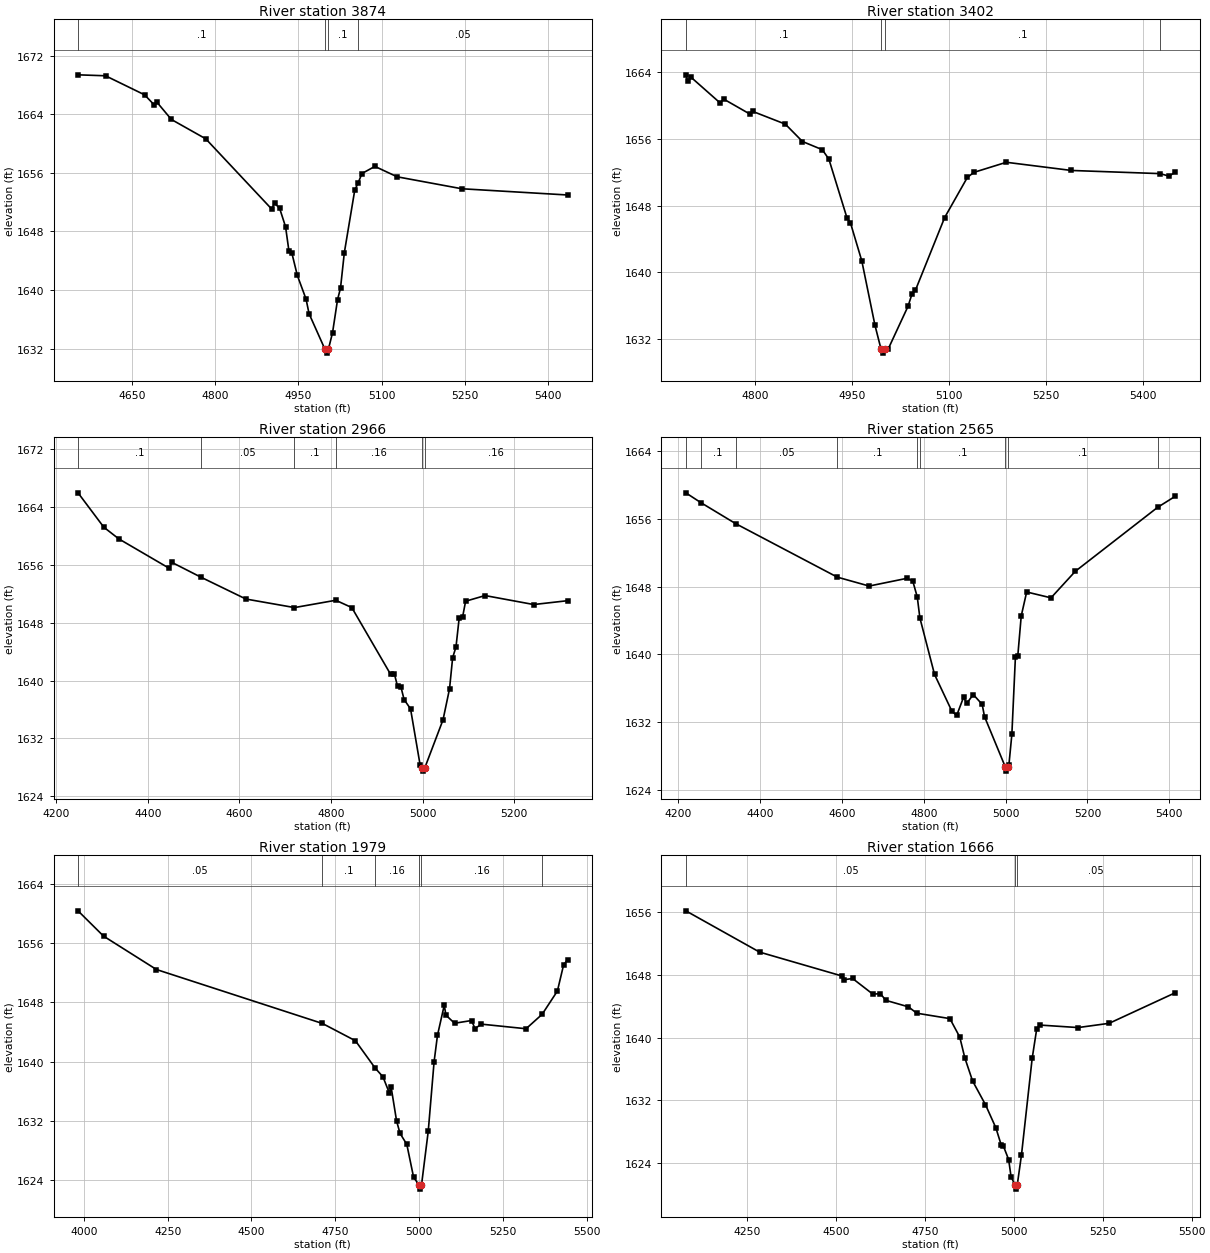
Type RM Length L Ch R = 1 ,3874    ,472,472,472
BEGIN DESCRIPTION:
MIDDLE CREEK 8.0
END DESCRIPTION:
XS GIS Cut Line= 2
      2775501.79     10081754.57      2774668.46      10081462.9
#Sta/Elev= 30
  4552.4 1669.37    4602 1669.24  4672.5 1666.64  4689.8 1665.27  4695.1  1665.6
  4720.8 1663.28  4782.8 1660.64  4901.7 1651.06  4906.9 1651.87  4916.1 1651.14
  4926.7 1648.65  4932.7 1645.39    4938 1645.08  4947.9 1642.02  4963.7 1638.77
  4969.1 1636.79  4997.9 1631.91  5000.7 1631.41  5003.9 1631.91  5011.5 1634.22
  5020.5 1638.72  5025.8 1640.27  5032.7 1645.11  5051.5 1653.64  5057.6 1654.63
  5064.5 1655.91  5087.8 1656.88    5128 1655.46  5244.6 1653.83  5435.3 1652.98
#Mann= 4 ,-1 , 0
  4552.4      .1       0  4997.9     .07       0  5003.9      .1       0
  5057.6     .05       0
Bank Sta=4997.9,5003.9
XS Rating Curve= 0 ,0
Exp/Cntr=0.3,0.1

Type RM Length L Ch R = 1 ,3402    ,436,436,436
BEGIN DESCRIPTION:
MIDDLE CREEK 7.0
END DESCRIPTION:
XS GIS Cut Line= 2
       2775425.4      10081087.9      2774682.94     10081240.56
#Sta/Elev= 30
  4692.5 1663.66  4695.6 1662.87  4700.7 1663.36  4745.9 1660.27    4751 1660.76
  4791.2 1658.98  4796.3 1659.27  4846.6 1657.75  4873.1 1655.67  4903.8 1654.69
    4914 1653.56  4942.2 1646.48  4947.3 1645.95    4965 1641.36  4985.4 1633.64
  4994.7 1630.81  4997.4 1630.31  5000.7 1630.81  5005.9 1630.81  5036.5 1635.91
  5042.9 1637.44    5048 1637.84  5093.3 1646.56  5128.4 1651.36  5138.5 1651.97
  5188.8 1653.18  5289.5  1652.2  5427.1 1651.82  5440.6 1651.52  5450.5    1652
#Mann= 4 ,-1 , 0
  4692.5      .1       0  4994.7     .07       0  5000.7      .1       0
  5427.1     .05       0
Bank Sta=4994.7,5000.7
XS Rating Curve= 0 ,0
Exp/Cntr=0.3,0.1

Type RM Length L Ch R = 1 ,2966    ,401,401,401
BEGIN DESCRIPTION:
MIDDLE CREEK 6.0
END DESCRIPTION:
XS GIS Cut Line= 3
      2775612.92      10080900.4      2774953.18     10080726.79
      2774690.59     10081010.11
#Sta/Elev= 30
  4247.6 1665.93  4303.9 1661.18  4336.4 1659.58  4447.1 1655.49  4452.2 1656.33
  4515.5 1654.29  4614.1 1651.26  4720.1 1650.08  4810.2 1651.09  4845.2 1650.08
  4929.7 1640.88  4938.3 1640.87  4945.1 1639.19  4952.4 1639.12  4959.3 1637.38
  4973.4 1636.09  4994.4  1628.3  4998.8 1627.99  5001.5 1627.49  5004.8 1627.99
  5044.3 1634.58  5058.5 1638.86  5065.3 1643.16  5072.6 1644.65  5079.5 1648.61
  5086.8 1648.71  5093.6 1650.96  5136.1 1651.74  5242.2  1650.5  5316.1 1651.03
#Mann= 6 ,-1 , 0
  4247.6      .1       0  4515.5     .05       0  4720.1      .1       0
  4810.2     .16       0  4998.8     .07       0  5004.8     .16       0
Bank Sta=4998.8,5004.8
XS Rating Curve= 0 ,0
Exp/Cntr=0.3,0.1

Type RM Length L Ch R = 1 ,2565    ,586,586,586
BEGIN DESCRIPTION:
MIDDLE CREEK 5.0
END DESCRIPTION:
XS GIS Cut Line= 3
      2775598.99     10080726.78      2774960.12     10080490.68
      2774508.73     10080240.68
#Sta/Elev= 30
    4218 1659.06  4254.6 1657.91  4339.8 1655.43  4588.4 1649.12  4666.3 1648.07
  4758.7 1648.98  4772.9 1648.67    4784 1646.78  4790.3 1644.33  4826.2 1637.65
  4868.9 1633.29  4880.4 1632.82  4897.3 1634.97  4904.9 1634.23  4920.9 1635.28
  4942.7 1634.12  4948.4 1632.68  4999.2 1626.75    5002 1626.25  5005.2 1626.75
    5008 1626.94  5015.3 1630.58    5024 1639.73  5029.7 1639.79  5038.2 1644.54
  5051.5 1647.37    5111 1646.68  5170.5 1649.81  5371.5 1657.34  5415.1 1658.66
#Mann= 9 ,-1 , 0
    4218     .05       0  4254.6      .1       0  4339.8     .05       0
  4588.4      .1       0    4784     .16       0  4790.3      .1       0
  4999.2     .07       0  5005.2      .1       0  5371.5     .16       0
Bank Sta=4999.2,5005.2
XS Rating Curve= 0 ,0
Exp/Cntr=0.3,0.1

Type RM Length L Ch R = 1 ,1979    ,313,313,313
BEGIN DESCRIPTION:
MIDDLE CREEK 4.0
END DESCRIPTION:
XS GIS Cut Line= 3
      2775717.08     10080692.08      2775189.29     10079976.79
      2774626.78     10079872.62
#Sta/Elev= 30
  3982.4 1660.34  4058.5 1656.93  4216.5 1652.42  4711.9 1645.14  4810.3 1642.81
  4868.9 1639.14  4892.5 1637.94  4911.7 1635.74  4916.8 1636.57  4933.2 1631.97
  4943.4 1630.32  4963.7 1628.82    4984 1624.37  5001.4 1623.29  5004.1 1622.79
  5007.4 1623.29  5027.6 1630.59  5045.1 1639.98  5055.2 1643.55  5075.4  1647.6
  5080.5 1646.26  5106.1 1645.17  5156.9 1645.54  5167.1 1644.46  5186.3 1645.05
  5319.6 1644.43  5367.6 1646.38  5413.1 1649.52  5431.5 1653.03  5443.4 1653.75
#Mann= 6 ,-1 , 0
  3982.4     .05       0  4711.9      .1       0  4868.9     .16       0
  5001.4     .07       0  5007.4     .16       0  5367.6      .1       0
Bank Sta=5001.4,5007.4
XS Rating Curve= 0 ,0
Exp/Cntr=0.3,0.1

Type RM Length L Ch R = 1 ,1666    ,174,174,174
BEGIN DESCRIPTION:
Mapping XS 8d4dc8da
END DESCRIPTION:
XS GIS Cut Line= 2
       2775786.5     10080504.55      2775023.07      10079359.4
#Sta/Elev= 30
  4077.9 1656.14  4285.4 1650.88  4516.8 1647.84  4523.6 1647.37  4546.8 1647.52
  4603.9 1645.52    4625  1645.6    4640 1644.74  4703.8 1643.91  4727.1  1643.1
  4820.3 1642.41  4848.1 1640.06  4862.3 1637.41  4884.1 1634.47  4920.2 1631.46
  4949.5 1628.51  4964.5 1626.33  4970.5  1626.2  4985.5 1624.46  4992.3 1622.28
  5003.6 1621.19  5006.3 1620.69  5009.6 1621.19  5021.6 1625.05  5051.6 1637.33
  5064.4 1641.09  5072.7 1641.59  5180.8 1641.27    5268 1641.81  5454.2 1645.71
#Mann= 3 ,-1 , 0
  4077.9     .05       0  5003.6     .04       0  5009.6     .05       0
Bank Sta=5003.6,5009.6
XS Rating Curve= 0 ,0
Exp/Cntr=0.3,0.1

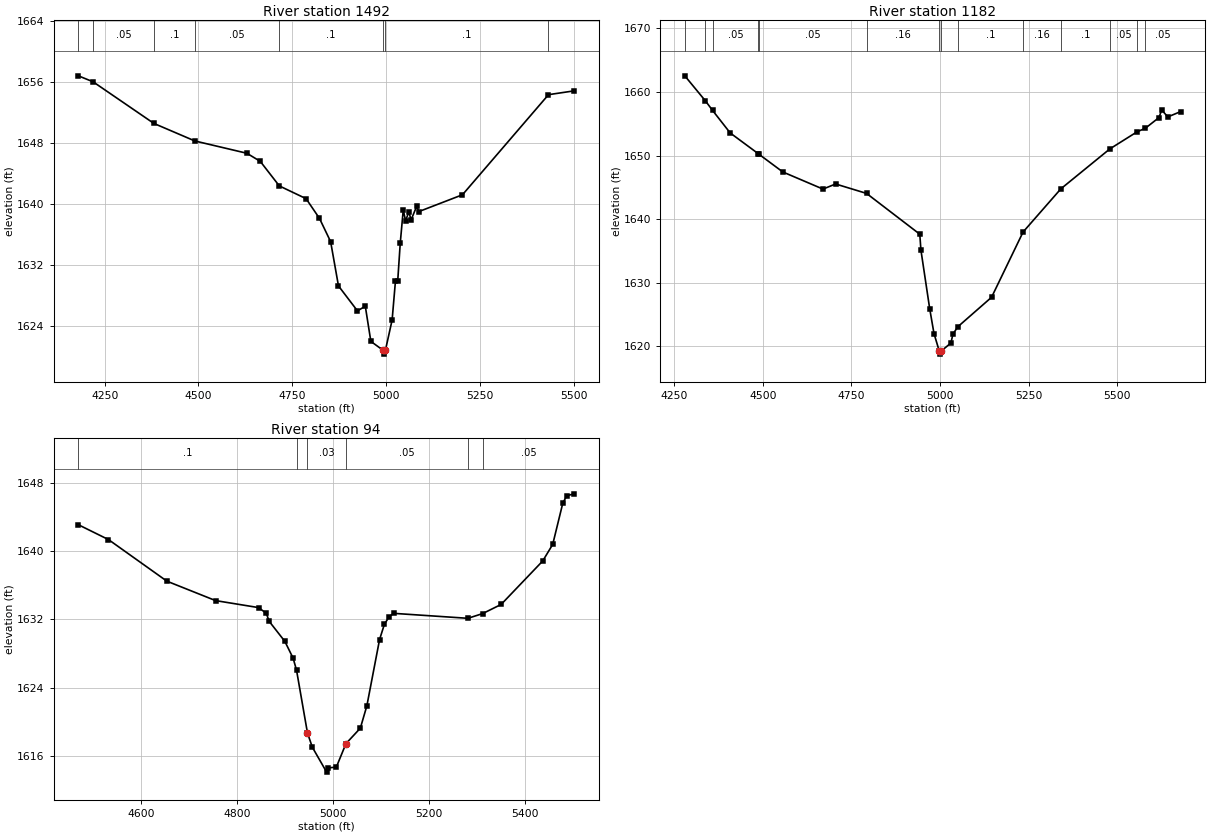
Type RM Length L Ch R = 1 ,1492    ,310,310,310
BEGIN DESCRIPTION:
MIDDLE CREEK 3.0
END DESCRIPTION:
XS GIS Cut Line= 2
      2775890.66     10080317.04      2775133.71      10079233.7
#Sta/Elev= 30
  4179.9  1656.8  4219.1 1656.02  4381.3 1650.56  4490.6 1648.26  4629.1 1646.65
  4664.8 1645.59  4715.6 1642.37  4786.9  1640.7  4822.7 1638.11  4852.4 1635.06
  4873.3 1629.26  4923.9 1625.99  4944.8  1626.6  4959.6 1621.99  4992.4 1620.82
  4995.1 1620.32  4998.4 1620.82  5016.3  1624.8  5025.1 1629.86  5031.2  1629.9
  5037.9 1634.84    5046 1639.25  5052.1 1637.79  5060.8 1638.95  5066.9 1637.93
  5081.7 1639.68  5087.8 1639.01  5203.8 1641.21  5433.1 1654.33  5501.5 1654.83
#Mann= 8 ,-1 , 0
  4179.9      .1       0  4219.1     .05       0  4381.3      .1       0
  4490.6     .05       0  4715.6      .1       0  4992.4     .07       0
  4998.4      .1       0  5433.1     .05       0
Bank Sta=4992.4,4998.4
XS Rating Curve= 0 ,0
Exp/Cntr=0.3,0.1

Type RM Length L Ch R = 1 ,1182    ,1088,1088,1088
BEGIN DESCRIPTION:
MIDDLE CREEK 2.0
END DESCRIPTION:
XS GIS Cut Line= 3
      2776230.96     10080122.63      2775744.85     10079671.23
      2775480.95     10078983.72
#Sta/Elev= 30
  4279.5 1662.54  4337.9 1658.59  4357.8 1657.11  4407.7 1653.56  4487.2 1650.29
  4489.5 1650.19  4556.2 1647.43  4669.6 1644.74  4705.3 1645.54  4792.6 1644.06
  4942.9 1637.65  4946.1 1635.16  4970.8 1625.97    4983 1622.04  4997.8  1619.3
  5000.6  1618.8  5003.8  1619.3  5030.8 1620.55  5036.6 1621.97  5050.9 1623.13
  5145.6 1627.74  5234.5 1637.99  5341.2 1644.78  5479.4 1651.05  5556.4 1653.74
  5579.7  1654.3  5618.4 1655.99  5625.7 1657.19  5643.1 1656.08  5679.3 1656.92
#Mann= 14 ,-1 , 0
  4279.5     .05       0  4337.9     .16       0  4357.8     .05       0
  4487.2     .16       0  4489.5     .05       0  4792.6     .16       0
  4997.8     .07       0  5003.8     .16       0  5050.9      .1       0
  5234.5     .16       0  5341.2      .1       0  5479.4     .05       0
  5556.4      .1       0  5579.7     .05       0
Bank Sta=4997.8,5003.8
XS Rating Curve= 0 ,0
Exp/Cntr=0.3,0.1

Type RM Length L Ch R = 1 ,94      ,0,0,0
BEGIN DESCRIPTION:
MIDDLE CREEK 1.0
END DESCRIPTION:
XS GIS Cut Line= 4
      2776338.32     10079445.71      2776405.59     10079059.42
       2776390.4       10078799.      2776075.72     10078584.15
#Sta/Elev= 30
    4469 1643.07  4531.9 1641.33  4653.7 1636.47  4755.2  1634.2  4845.1 1633.38
  4861.1  1632.7  4866.8 1631.79  4899.7 1629.43  4916.9 1627.47    4924 1626.08
  4946.9 1618.71    4957 1617.06  4986.8 1614.15    4990 1614.65    5007 1614.73
  5027.1 1617.48  5057.1 1619.29  5070.7  1621.9  5097.2 1629.65  5107.2 1631.42
  5117.1 1632.31  5126.4 1632.71  5281.4 1632.13  5312.1 1632.68  5350.7 1633.75
  5437.4 1638.83  5458.3 1640.77  5479.3 1645.59  5487.6 1646.46    5503 1646.68
#Mann= 6 ,-1 , 0
    4469      .1       0    4924     .05       0  4946.9     .03       0
  5027.1     .05       0  5281.4      .1       0  5312.1     .05       0
Bank Sta=4946.9,5027.1
XS Rating Curve= 0 ,0
Exp/Cntr=0.3,0.1

Chan Stop Cuts=-1
Use User Specified Reach Order=0
Composite Channel Slope=5