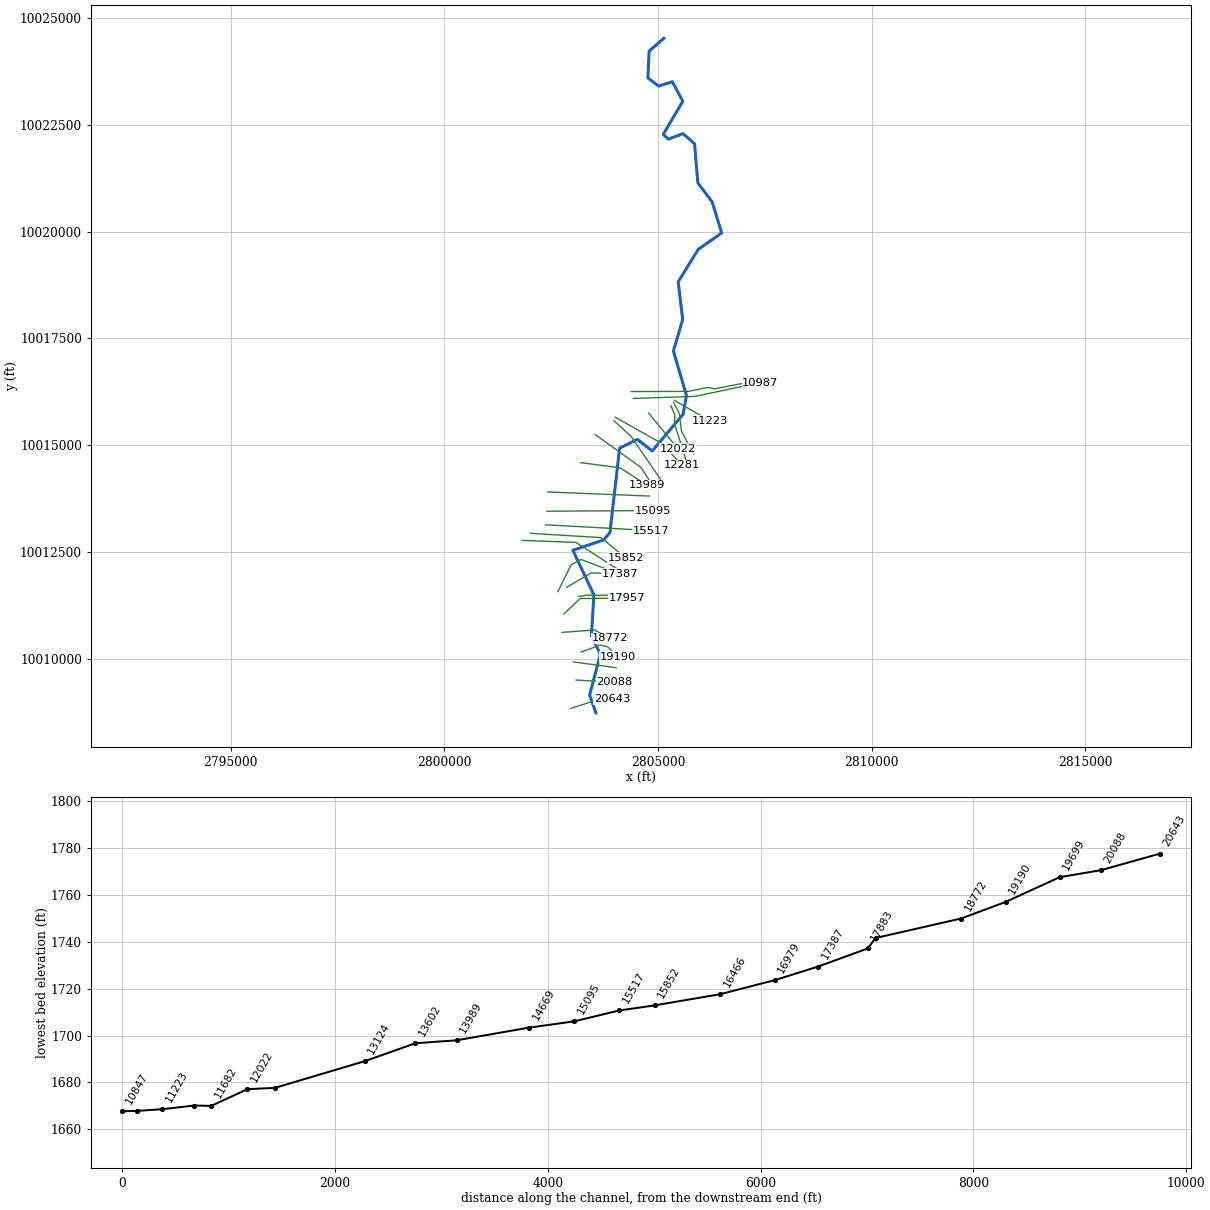
--- MIDDLE FORK HUNTERS CREEK.prj (project) ---

Proj Title=MIDDLE FORK HUNTERS CREEK Base Level Engineering
Current Plan=p01
Default Exp/Contr=0.3,0.1
English Units
Geom File=g01
Flow File=f01
Plan File=p01
Y Axis Title=Elevation
X Axis Title(PF)=Main Channel Distance
X Axis Title(XS)=Station
BEGIN DESCRIPTION:
yMIDDLE FORK HUNTERS CREEK
END DESCRIPTION:
DSS Export Rating Curves= 0
DSS Export Rating Curve Sorted= 0
DSS Export Volume Flow Curves= 0
DXF OffsetX= 0
DXF OffsetY= 0
DXF ScaleX= 1
DXF ScaleY= 10

--- MIDDLE FORK HUNTERS CREEK.p01 (plan) ---

Plan Title=Multiple Run
Short Identifier=Multiple
Geom File=g01
Flow File=f01
Subcritical Flow
K Sum by GR= 0
Std Step Tol= 0.01
Critical Tol= 0.01
Num of Std Step Trials= 20
Max Error Tol= 0.3
Flow Tol Ratio= 0.001
Split Flow NTrial= 30
Split Flow Tol= 0.02
Split Flow Ratio= 0.02
Log Output Level= 0
Friction Slope Method= 1
Unsteady Friction Slope Method= 2
Unsteady Bridges Friction Slope Method= 1
Parabolic Critical Depth
Global Vel Dist=  1 , 1 , 1
Global Log Level= 0
CheckData=True
Encroach Param= -1, 0, 0, 0
BEGIN DESCRIPTION:
Multiple Run
END DESCRIPTION:

--- MIDDLE FORK HUNTERS CREEK.f01 (steady flow) ---

Flow Title=Multiple
Program Version=4.10
Number of Profiles= 7
Profile Names=10-year,25-year,50-year,1pct_min,100-year,1pct_plu,500-year
River Rch & RM=MIDDLE FORK HUNT,Reach-1         ,20643
     453     631     781     710     960    1298    1451
River Rch & RM=MIDDLE FORK HUNT,Reach-1         ,17957
     989    1447    1848    1730    2339    3163    3759
River Rch & RM=MIDDLE FORK HUNT,Reach-1         ,16466
    1743    2607    3379    3198    4325    5849    7117
River Rch & RM=MIDDLE FORK HUNT,Reach-1         ,10987
    2514    3821    5006    4782    6467    8746   10848
River Rch & RM=MIDDLE FORK HUNT,Reach-1         ,9473
    2514    3821    5006    4782    6467    8746   10848
River Rch & RM=MIDDLE FORK HUNT,Reach-1         ,5777
    2606    3957    5181    4946    6688    9045   11201
Boundary for River Rch & Prof#=MIDDLE FORK HUNT,Reach-1         , 1
Up Type= 0
Dn Type= 3
Dn Slope=0.00671
Boundary for River Rch & Prof#=MIDDLE FORK HUNT,Reach-1         , 2
Up Type= 0
Dn Type= 3
Dn Slope=0.00671
Boundary for River Rch & Prof#=MIDDLE FORK HUNT,Reach-1         , 3
Up Type= 0
Dn Type= 3
Dn Slope=0.00671
Boundary for River Rch & Prof#=MIDDLE FORK HUNT,Reach-1         , 4
Up Type= 0
Dn Type= 3
Dn Slope=0.00671
Boundary for River Rch & Prof#=MIDDLE FORK HUNT,Reach-1         , 5
Up Type= 0
Dn Type= 3
Dn Slope=0.00671
Boundary for River Rch & Prof#=MIDDLE FORK HUNT,Reach-1         , 6
Up Type= 0
Dn Type= 3
Dn Slope=0.00671
Boundary for River Rch & Prof#=MIDDLE FORK HUNT,Reach-1         , 7
Up Type= 0
Dn Type= 3
Dn Slope=0.00671
DSS Import GetInterval= 0
DSS Import GetPeak= 0
DSS Import FillOption= 0

--- MIDDLE FORK HUNTERS CREEK.g01 (geometry) ---

Geom Title=Existing Conditions
Program Version=4.10

River Reach=MIDDLE FORK HUNT,Reach-1
Reach XY= 30
      2803545.34      10008739.6      2803397.99     10009161.73
      2803649.09     10010108.51      2803440.42     10010559.38
      2803499.49     10011500.98      2803006.24     10012545.13
      2803726.34     10012787.41      2803874.06     10012960.84
      2804099.23     10014933.42      2804517.86     10015139.97
      2804860.97     10014868.33      2805584.78     10015725.26
      2805664.69     10016166.22      2805358.62     10017206.37
      2805576.41     10017944.22      2805470.16     10018823.64
      2805939.39     10019583.95      2806487.95     10019968.15
      2806264.83     10020697.07      2805930.85       10021139.
      2805852.94     10022056.12      2805582.48     10022291.88
      2805238.31     10022163.17      2805121.16     10022274.89
      2805579.01     10023048.76      2805334.56     10023505.79
      2805013.94     10023403.83      2804761.35     10023594.94
      2804791.09     10024222.66      2805134.11     10024521.59

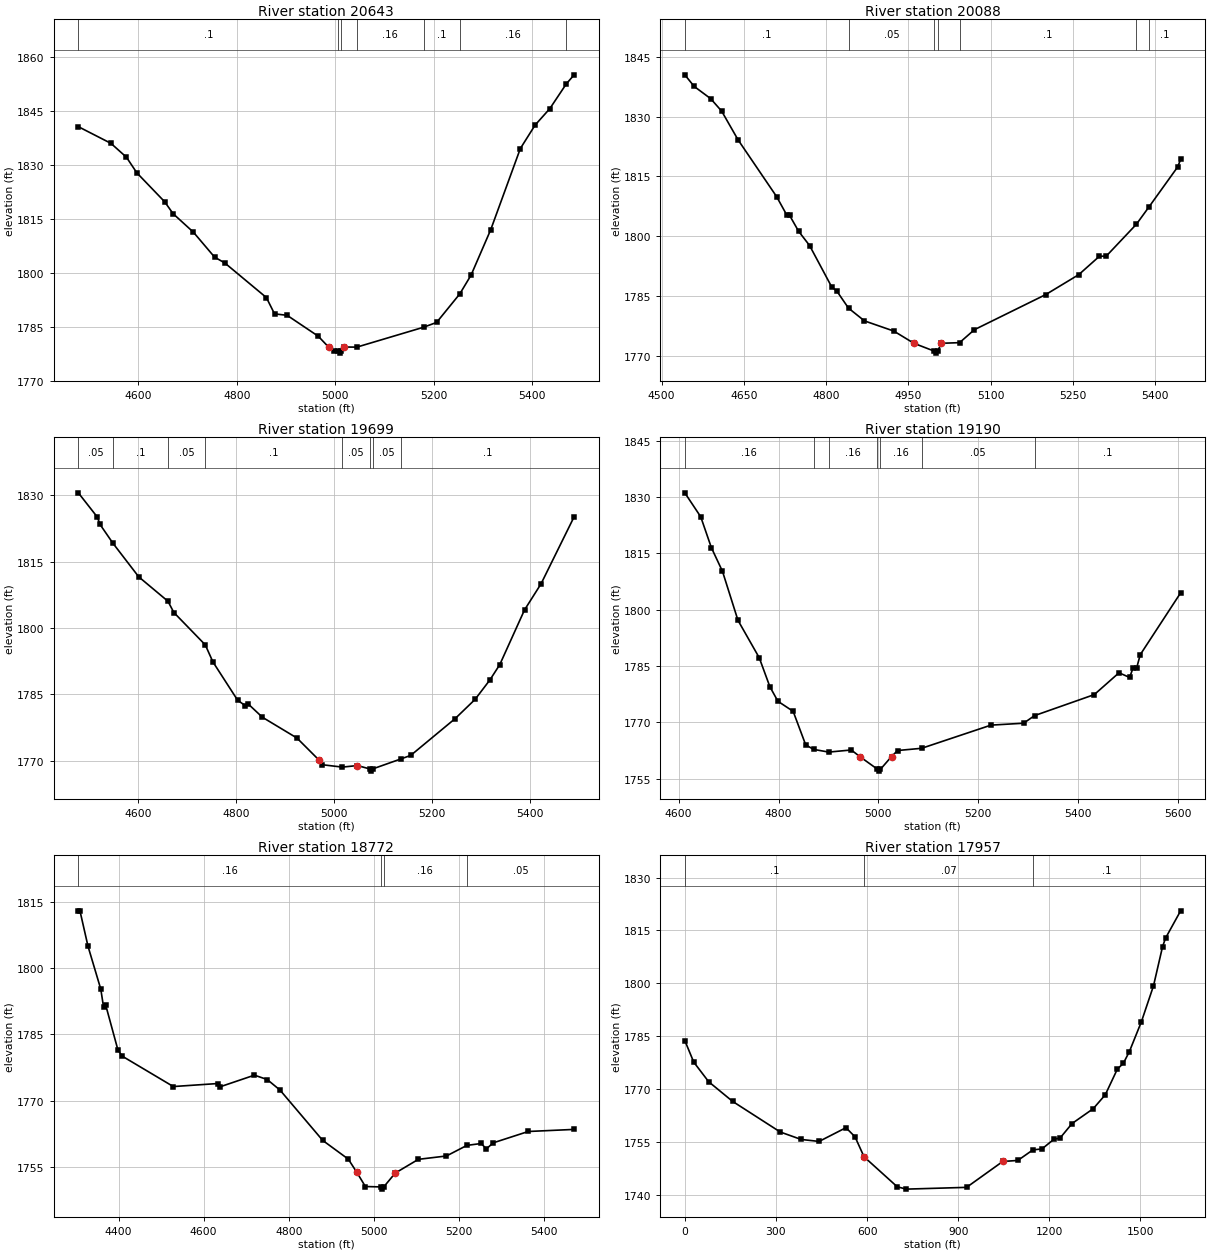
Type RM Length L Ch R = 1 ,20643   ,555,555,555
BEGIN DESCRIPTION:
MIDDLE FORK HUNTERS CREEK 44.0
END DESCRIPTION:
XS GIS Cut Line= 3
      2802955.56      10008844.7      2803619.62     10009061.71
      2803927.77     10009066.05
#Sta/Elev= 30
  4478.4 1840.66  4544.6 1836.02  4576.1 1832.16  4597.2 1827.82  4653.7 1819.77
  4670.8 1816.46  4712.2 1811.29    4755 1804.38  4775.9 1802.74  4860.2 1793.13
  4876.8 1788.59  4902.3 1788.19  4965.4 1782.39  4986.4 1779.38    4997  1778.2
  5006.6 1778.17  5009.4 1777.67  5012.6 1778.17    5018 1779.37  5043.9 1779.34
  5179.4 1784.87  5205.9 1786.21    5253 1794.15  5275.9 1799.38  5315.9 1812.04
  5375.9 1834.57  5405.9  1841.1  5435.9  1845.7  5469.4 1852.59  5485.2 1855.08
#Mann= 7 ,-1 , 0
  4478.4      .1       0  5006.6     .07       0  5012.6      .1       0
  5043.9     .16       0  5179.4      .1       0    5253     .16       0
  5469.4      .1       0
Bank Sta=4986.4,5018
XS Rating Curve= 0 ,0
Exp/Cntr=0.3,0.1

Type RM Length L Ch R = 1 ,20088   ,389,389,389
BEGIN DESCRIPTION:
MIDDLE FORK HUNTERS CREEK 43.0
END DESCRIPTION:
XS GIS Cut Line= 2
      2803081.37     10009508.76      2803983.81     10009461.04
#Sta/Elev= 30
  4542.4 1840.47  4559.5 1837.56  4589.6 1834.48  4609.6 1831.35  4639.6 1824.12
  4709.7  1809.9  4728.5 1805.21  4733.5 1805.16  4749.8  1801.2  4769.8 1797.62
  4809.9 1787.28  4819.9 1786.09  4840.8 1781.89  4869.9 1778.69  4923.3 1776.14
  4960.1 1773.06  4997.1  1771.1  4999.9  1770.6  5003.1  1771.1  5010.1 1773.07
  5043.2 1773.23  5070.2 1776.48  5200.4 1785.31  5260.5 1790.31    5298 1794.91
  5310.6 1794.96  5365.5 1802.96  5388.7 1807.36  5440.7 1817.34  5446.1 1819.25
#Mann= 7 ,-1 , 0
  4542.4      .1       0  4840.8     .05       0  4997.1    .035       0
  5003.1     .05       0  5043.2      .1       0  5365.5     .16       0
  5388.7      .1       0
Bank Sta=4960.1,5010.1
XS Rating Curve= 0 ,0
Exp/Cntr=0.3,0.1

Type RM Length L Ch R = 1 ,19699   ,509,509,509
BEGIN DESCRIPTION:
MIDDLE FORK HUNTERS CREEK 42.0
END DESCRIPTION:
XS GIS Cut Line= 2
       2803016.3     10009934.11      2804018.91     10009799.56
#Sta/Elev= 30
  4477.7 1830.55  4516.7 1825.03  4521.7 1823.44  4548.4 1819.13    4601 1811.54
  4660.5 1806.03  4672.6 1803.48  4736.7 1796.16  4752.3  1792.3  4802.8 1783.62
  4818.4 1782.41  4823.4 1782.88  4853.2 1779.79  4923.8 1775.08  4969.2 1770.05
  4974.3 1769.06  5016.3 1768.51  5047.2 1768.86  5072.2  1768.1  5074.9  1767.6
  5078.2  1768.1  5135.6 1770.35  5155.9 1771.16  5246.7  1779.5  5287.1 1783.82
  5317.3 1788.21  5337.5 1791.68    5388 1804.06  5421.8 1809.98  5489.3 1825.15
#Mann= 8 ,-1 , 0
  4477.7     .05       0  4548.4      .1       0  4660.5     .05       0
  4736.7      .1       0  5016.3     .05       0  5072.2     .07       0
  5078.2     .05       0  5135.6      .1       0
Bank Sta=4969.2,5047.2
XS Rating Curve= 0 ,0
Exp/Cntr=0.3,0.1

Type RM Length L Ch R = 1 ,19190   ,418,418,418
BEGIN DESCRIPTION:
MIDDLE FORK HUNTERS CREEK 41.0
END DESCRIPTION:
XS GIS Cut Line= 4
      2803198.57     10010164.13      2803645.66     10010329.07
      2803823.61     10010285.67      2804057.11     10010047.84
#Sta/Elev= 30
  4612.3 1831.13  4644.2 1824.75  4665.5 1816.53  4687.8 1810.21  4718.8 1797.17
  4761.4 1787.21  4782.7 1779.49  4798.8 1775.62  4829.3 1772.94  4854.4 1764.02
  4870.2 1762.81  4900.5 1762.09  4945.7 1762.65  4963.9 1760.79  4998.2 1757.52
    5001 1757.02  5004.2 1757.52  5026.3  1760.9  5038.5 1762.51  5086.6  1763.1
  5225.5 1769.27  5290.9 1769.78  5312.7  1771.8  5432.4  1777.4  5481.9 1783.21
  5503.1 1781.97  5510.2 1784.54  5517.2 1784.47  5524.4 1788.02  5605.3 1804.49
#Mann= 7 ,-1 , 0
  4612.3     .16       0  4870.2     .05       0  4900.5     .16       0
  4998.2     .07       0  5004.2     .16       0  5086.6     .05       0
  5312.7      .1       0
Bank Sta=4963.9,5026.3
XS Rating Curve= 0 ,0
Exp/Cntr=0.3,0.1

Type RM Length L Ch R = 1 ,18772   ,804,804,804
BEGIN DESCRIPTION:
MIDDLE FORK HUNTERS CREEK 40.0
END DESCRIPTION:
XS GIS Cut Line= 3
      2802755.86     10010624.21      2803511.11     10010680.63
      2803871.37     10010489.65
#Sta/Elev= 30
  4305.6 1813.01  4309.4 1813.01  4328.3 1804.99  4358.4 1795.25  4364.9 1791.18
  4369.9 1791.66  4398.5 1781.53  4408.5  1780.1  4528.8  1773.2  4634.5 1773.89
  4639.5 1773.17  4719.4 1775.78  4749.4 1774.79  4779.5  1772.4  4879.8    1761
    4940 1756.75    4960 1753.76  4980.1 1750.55  5017.2 1750.46  5019.9 1749.96
  5023.2 1750.46  5050.3  1753.6  5104.6 1756.71  5170.6 1757.47  5218.7 1759.87
  5252.4  1760.3  5264.3 1759.07  5280.6 1760.45  5362.9 1763.02  5470.7 1763.49
#Mann= 4 ,-1 , 0
  4305.6     .16       0  5017.2     .07       0  5023.2     .16       0
  5218.7     .05       0
Bank Sta=4960,5050.3
XS Rating Curve= 0 ,0
Exp/Cntr=0.3,0.1

Type RM Length L Ch R = 1 ,17957   ,74,74,74
BEGIN DESCRIPTION:
MIDDLE FORK HUNTERS CREEK 39.0
END DESCRIPTION:
XS GIS Cut Line= 3
     2802796.266    10011058.237     2803179.182    10011417.418
      2804278.14    10011426.533
#Sta/Elev= 30
       01783.78529.474151777.65478.597721772.099157.19541766.536314.39091757.831
383.16391755.725442.11221755.167530.53471759.064560.30691756.478590.07921750.805
699.24431742.308729.0166 1741.64927.4985 1742.141046.5881749.4831096.2081749.775
1145.8291752.7711175.601 1753.041215.2971755.8031235.1461756.1151274.8421760.252
1344.3111764.4431384.0071768.3841423.7031775.6511443.5521777.325  1463.41780.638
1503.0961789.1441542.7931799.2911572.5651810.3831582.4891812.8271632.1091820.568
#Mann= 3 ,-1 , 0
       0      .1       0590.0792     .07       01145.829      .1       0
Bank Sta=590.0792,1046.588
XS Rating Curve= 0 ,0
Exp/Cntr=0.3,0.1

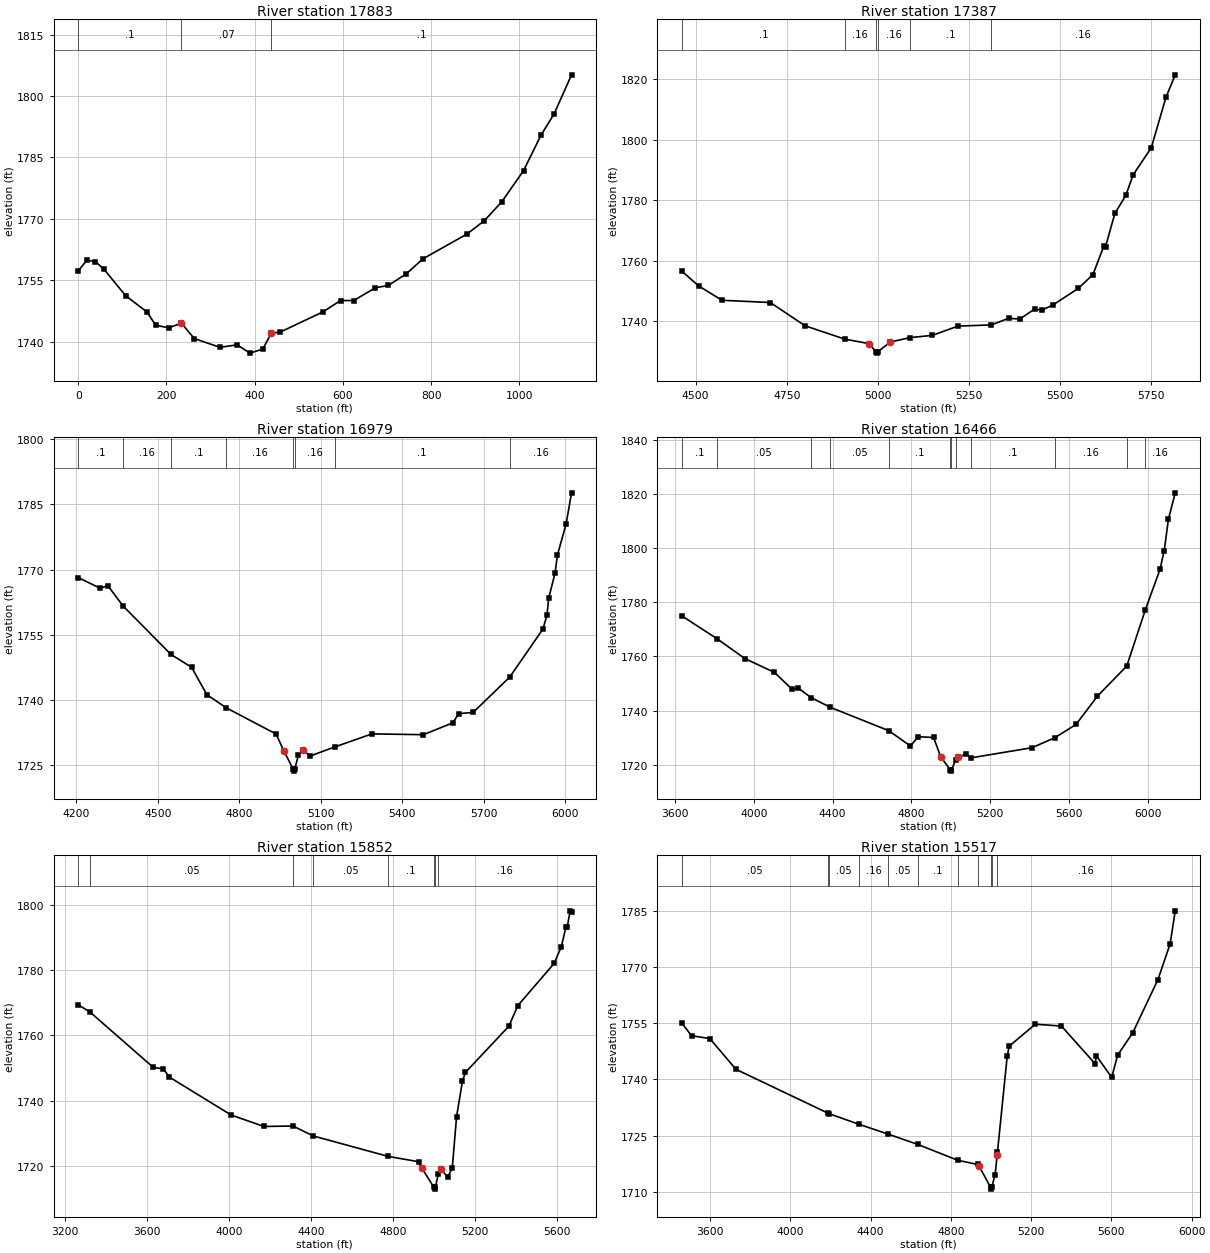
Type RM Length L Ch R = 1 ,17883   ,467,467,467
BEGIN DESCRIPTION:
MIDDLE FORK HUNTERS CREEK 38.0
END DESCRIPTION:
XS GIS Cut Line= 4
     2803133.505    10011461.883     2803335.432    10011496.846
     2803654.442    10011491.637     2804256.004    10011508.564
#Sta/Elev= 30
       01757.25119.50752 1759.8739.015051759.53758.522571757.654107.29141751.233
156.06021747.205175.5677 1743.99 204.8291743.358234.04151744.469263.15621740.728
321.38581738.587360.20551739.197389.32031737.172 418.4351738.167437.84491742.092
457.2547 1742.28555.14051747.277594.62941750.026624.24611750.022673.60721753.132
703.22391753.734742.71281756.482782.20171760.271 880.9241766.259920.45871769.529
959.99331774.1481009.4121781.7741048.9461790.4321078.5971795.6291118.1321805.179
#Mann= 3 ,-1 , 0
       0      .1       0234.0415     .07       0437.8449      .1       0
Bank Sta=234.0415,437.8449
XS Rating Curve= 0 ,0
Exp/Cntr=0.3,0.1

Type RM Length L Ch R = 1 ,17387   ,408,408,408
BEGIN DESCRIPTION:
MIDDLE FORK HUNTERS CREEK 37.0
END DESCRIPTION:
XS GIS Cut Line= 3
      2802855.72     10011674.55      2803432.98     10012017.44
      2804113.97     10011991.41
#Sta/Elev= 30
  4462.4 1756.51    4508 1751.67  4572.3  1746.9  4704.8 1746.16  4800.3 1738.46
  4909.4 1734.04  4975.6 1732.58    4994 1729.93  4996.8 1729.43    5000 1729.93
  5034.1  1733.1  5088.6 1734.57  5149.3  1735.3  5219.4 1738.37  5310.3 1738.75
  5358.1 1740.91  5389.5 1740.72  5429.5    1744  5449.5 1743.65  5479.5 1745.31
  5549.6 1750.84  5589.6  1755.4  5619.1 1764.71  5624.2 1764.63  5649.7 1775.61
  5679.7 1781.55  5699.7 1788.34  5749.7 1797.35  5789.8 1813.99  5815.3 1821.43
#Mann= 6 ,-1 , 0
  4462.4      .1       0  4909.4     .16       0    4994     .07       0
    5000     .16       0  5088.6      .1       0  5310.3     .16       0
Bank Sta=4975.6,5034.1
XS Rating Curve= 0 ,0
Exp/Cntr=0.3,0.1

Type RM Length L Ch R = 1 ,16979   ,513,513,513
BEGIN DESCRIPTION:
MIDDLE FORK HUNTERS CREEK 36.0
END DESCRIPTION:
XS GIS Cut Line= 4
      2802656.07     10011579.07      2802964.23     10012204.07
      2803198.61     10012329.94       2803997.2     10012026.13
#Sta/Elev= 30
  4206.4 1768.16  4287.5  1765.7  4315.5 1766.31    4371 1761.67  4548.1 1750.48
  4624.1 1747.52  4680.4 1741.22  4752.6 1738.17  4935.3 1732.18  4964.8 1728.16
  4998.1 1724.14  5000.8 1723.64  5004.1 1724.14  5017.3 1727.24  5032.9 1728.49
  5061.2 1727.12  5151.2  1729.2  5288.7 1732.21    5478 1732.02  5586.4 1734.75
  5607.8 1736.86  5661.3 1737.15    5796 1745.27  5918.1 1756.29  5933.1 1759.45
  5939.5 1763.37  5963.2 1769.26  5971.6 1773.31  6003.7 1780.47  6023.7 1787.65
#Mann= 8 ,-1 , 0
  4206.4      .1       0    4371     .16       0  4548.1      .1       0
  4752.6     .16       0  4998.1     .07       0  5004.1     .16       0
  5151.2      .1       0    5796     .16       0
Bank Sta=4964.8,5032.9
XS Rating Curve= 0 ,0
Exp/Cntr=0.3,0.1

Type RM Length L Ch R = 1 ,16466   ,614,614,614
BEGIN DESCRIPTION:
MIDDLE FORK HUNTERS CREEK 35.0
END DESCRIPTION:
XS GIS Cut Line= 3
      2801818.44     10012776.99      2803077.08     10012729.24
      2804127.45     10012056.48
#Sta/Elev= 30
    3634 1774.94  3812.9 1766.49  3954.3 1759.19  4104.4 1754.08  4194.4 1747.83
  4224.5 1748.36  4289.5 1744.82  4388.4  1741.2  4685.1 1732.58  4794.9 1726.94
  4834.9 1730.33    4913 1730.08  4949.4 1722.86  4997.9 1718.15  5000.7 1717.65
  5003.9 1718.15  5024.8 1721.69  5037.3 1722.82  5079.6 1723.94  5103.9 1722.56
  5412.7 1726.29  5528.8 1729.97  5636.8 1734.89  5745.8 1745.34  5894.6 1756.44
  5988.3 1777.05  6063.7 1792.18  6084.9 1799.06  6106.5 1810.71  6140.9 1820.38
#Mann= 12 ,-1 , 0
    3634      .1       0  3812.9     .05       0  4289.5      .1       0
  4388.4     .05       0  4685.1      .1       0  4997.9     .07       0
  5003.9      .1       0  5024.8     .16       0  5103.9      .1       0
  5528.8     .16       0  5894.6      .1       0  5988.3     .16       0
Bank Sta=4949.4,5037.3
XS Rating Curve= 0 ,0
Exp/Cntr=0.3,0.1

Type RM Length L Ch R = 1 ,15852   ,335,335,335
BEGIN DESCRIPTION:
MIDDLE FORK HUNTERS CREEK 34.0
END DESCRIPTION:
XS GIS Cut Line= 3
      2802013.67     10012941.92      2803663.02     10012842.09
      2804248.97     10012364.65
#Sta/Elev= 30
    3263 1769.36  3321.9 1767.05  3628.5 1750.22  3678.6  1749.7  3708.6 1747.18
  4009.2  1735.6  4169.5 1732.08  4311.2 1732.22  4410.3 1729.18  4775.6 1722.92
  4924.8 1721.28  4939.1 1719.47    5000 1713.39  5002.8 1712.89    5006 1713.39
  5021.3 1717.63  5031.8 1719.13    5067 1716.55  5089.2 1719.48    5110 1735.07
  5138.8 1746.01  5153.1 1748.62  5365.7 1762.81  5408.8 1769.08  5586.1    1782
  5621.3 1787.15  5643.6 1793.05  5650.1 1793.13  5664.4 1798.12  5671.2 1797.82
#Mann= 8 ,-1 , 0
    3263      .1       0  3321.9     .05       0  4311.2     .16       0
  4410.3     .05       0  4775.6      .1       0    5000     .07       0
    5006      .1       0  5021.3     .16       0
Bank Sta=4939.1,5031.8
XS Rating Curve= 0 ,0
Exp/Cntr=0.3,0.1

Type RM Length L Ch R = 1 ,15517   ,422,422,422
BEGIN DESCRIPTION:
MIDDLE FORK HUNTERS CREEK 33.0
END DESCRIPTION:
XS GIS Cut Line= 2
      2802369.58     10013141.57       2804824.8      10013007.1
#Sta/Elev= 30
  3459.3 1754.98  3507.2 1751.64  3598.4 1750.87  3728.6 1742.67  4189.1 1730.93
  4191.8 1730.84  4343.8 1727.97  4486.4 1725.39  4634.8 1722.63  4834.1  1718.4
  4933.1 1717.28  4940.4 1716.86  4997.5  1711.2  5000.2  1710.7  5003.5  1711.2
  5020.5 1714.58  5030.5  1719.8  5032.2  1720.6  5080.6 1746.17  5090.6 1748.85
  5220.8 1754.71    5351 1754.21  5519.5 1744.12  5524.5 1746.32  5601.4 1740.52
  5631.4  1746.5    5706 1752.38  5831.7 1766.58  5892.6 1776.12  5918.2 1784.96
#Mann= 11 ,-1 , 0
  3459.3     .05       0  4189.1     .16       0  4191.8     .05       0
  4343.8     .16       0  4486.4     .05       0  4634.8      .1       0
  4834.1     .16       0  4933.1      .1       0  4997.5     .07       0
  5003.5      .1       0  5032.2     .16       0
Bank Sta=4940.4,5030.5
XS Rating Curve= 0 ,0
Exp/Cntr=0.3,0.1

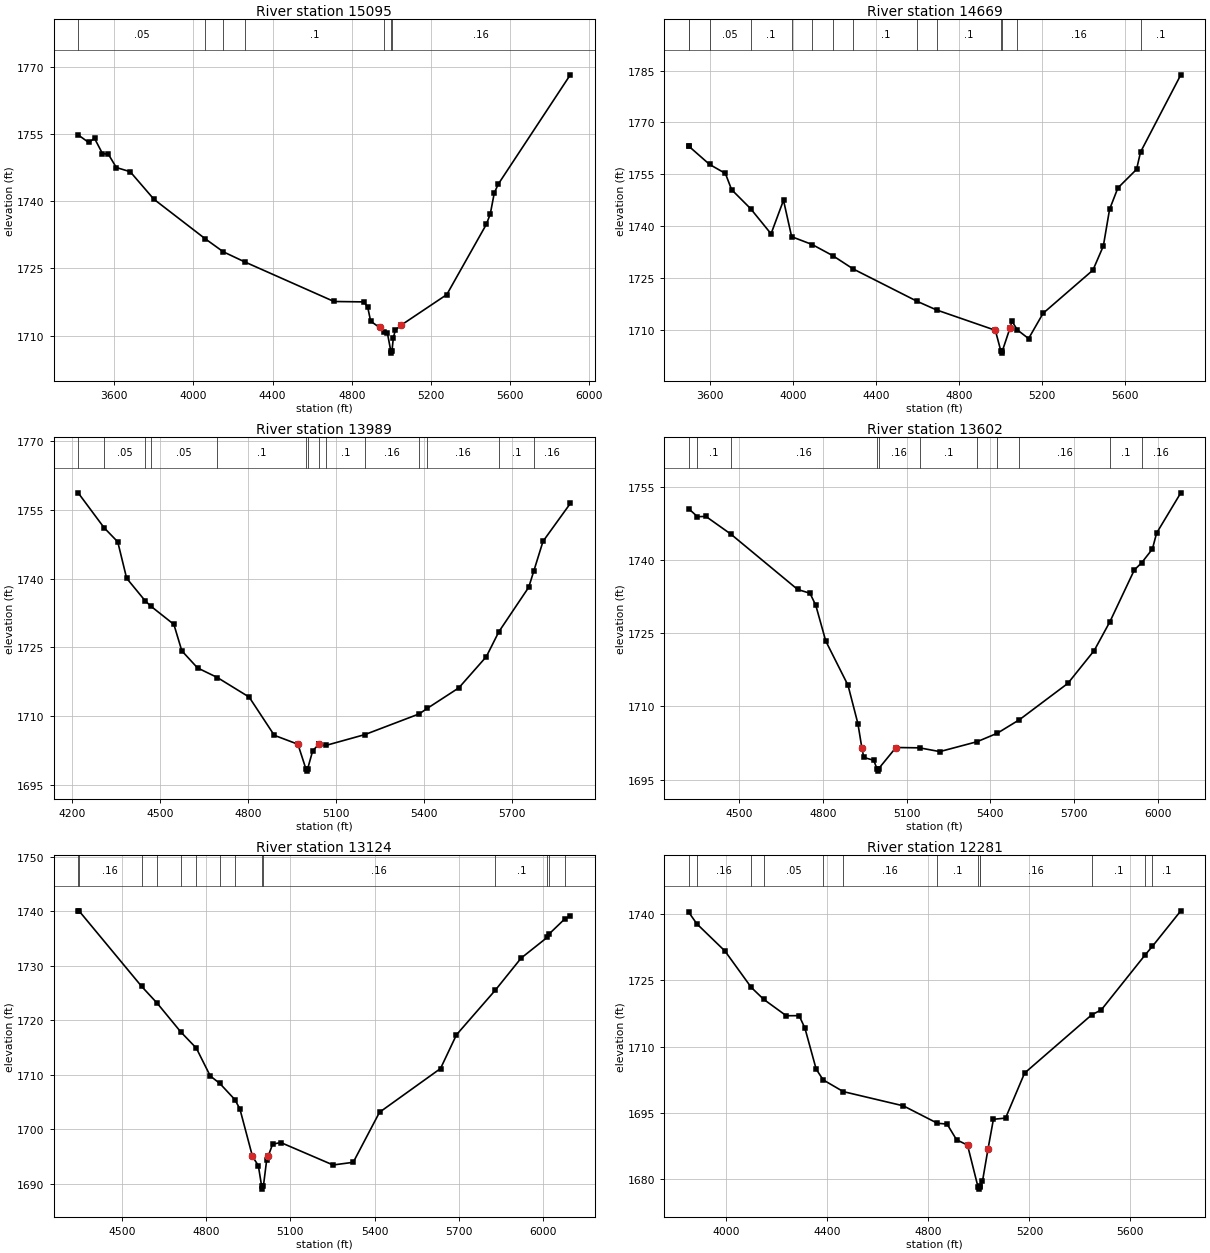
Type RM Length L Ch R = 1 ,15095   ,426,426,426
BEGIN DESCRIPTION:
MIDDLE FORK HUNTERS CREEK 32.0
END DESCRIPTION:
XS GIS Cut Line= 2
      2802395.61     10013458.41      2804882.65     10013475.77
#Sta/Elev= 30
  3417.2 1754.85  3470.1 1753.16  3500.1 1754.06  3540.1 1750.67  3570.1 1750.51
  3610.1 1747.55  3680.1 1746.62  3800.1 1740.46    4059 1731.64  4150.5 1728.72
  4259.9 1726.44  4710.1 1717.61  4860.1 1717.52  4880.1 1716.42  4895.4 1713.21
  4940.1  1711.8  4962.4 1710.89  4980.1 1710.52  4997.1 1706.57  4999.8 1706.07
  5003.1 1706.57  5010.1 1709.51  5020.1 1711.21  5050.1 1712.34  5280.1 1719.15
  5480.1 1734.86  5500.1  1737.2  5520.1 1741.86  5540.1 1743.83  5904.3 1768.27
#Mann= 7 ,-1 , 0
  3417.2     .05       0    4059      .1       0  4150.5     .05       0
  4259.9      .1       0  4962.4     .16       0  4997.1     .07       0
  5003.1     .16       0
Bank Sta=4940.1,5050.1
XS Rating Curve= 0 ,0
Exp/Cntr=0.3,0.1

Type RM Length L Ch R = 1 ,14669   ,680,680,680
BEGIN DESCRIPTION:
MIDDLE FORK HUNTERS CREEK 31.0
END DESCRIPTION:
XS GIS Cut Line= 2
      2802421.73      10013909.8      2804791.51     10013814.31
#Sta/Elev= 30
  3495.6 1763.33  3497.3 1763.09  3596.2 1757.89  3672.5 1755.28  3702.5  1750.6
    3794 1745.11  3892.7 1737.84  3952.7 1747.53  3991.8 1737.01  4090.7 1734.75
  4189.6 1731.55  4288.5 1727.69  4597.8 1718.31  4690.3 1715.85  4973.5 1709.98
  5000.6 1703.88  5003.3 1703.38  5006.6 1703.88  5043.6 1710.53  5053.6 1712.59
  5079.7 1710.08  5133.7 1707.58  5203.7 1714.89  5443.9 1727.36    5494 1734.32
    5524 1744.91    5564 1751.08  5654.1 1756.46  5673.1 1761.44  5867.3 1783.76
#Mann= 14 ,-1 , 0
  3495.6     .05       0  3497.3     .16       0  3596.2     .05       0
    3794      .1       0  3991.8     .16       0  4090.7      .1       0
  4189.6     .16       0  4288.5      .1       0  4597.8     .05       0
  4690.3      .1       0  5000.6     .07       0  5006.6      .1       0
  5079.7     .16       0  5673.1      .1       0
Bank Sta=4973.5,5043.6
XS Rating Curve= 0 ,0
Exp/Cntr=0.3,0.1

Type RM Length L Ch R = 1 ,13989   ,387,387,387
BEGIN DESCRIPTION:
MIDDLE FORK HUNTERS CREEK 30.0
END DESCRIPTION:
XS GIS Cut Line= 3
      2803194.31     10014595.56      2804110.07     10014474.04
      2804748.09     10014066.05
#Sta/Elev= 30
  4219.3 1758.76  4307.9 1751.14  4354.6 1748.05  4384.9 1740.11  4447.6 1735.23
    4467 1734.04  4546.3 1730.03  4573.4 1724.26    4627 1720.53  4694.8 1718.43
  4803.4 1714.16  4889.3 1705.81    4970 1703.86  4997.2 1698.49    5000 1697.99
  5003.2 1698.49  5020.4 1702.42  5040.6 1703.81  5043.5 1703.86  5065.3  1703.6
  5198.8 1705.97  5384.3 1710.49    5412  1711.7  5519.6 1716.17  5613.5 1722.98
  5656.2 1728.41  5758.4 1738.14  5775.5 1741.64  5807.2 1748.17  5900.4 1756.43
#Mann= 14 ,-1 , 0
  4219.3     .16       0  4307.9     .05       0  4447.6      .1       0
    4467     .05       0  4694.8      .1       0  4997.2     .07       0
  5003.2      .1       0  5043.5     .16       0  5065.3      .1       0
  5198.8     .16       0  5384.3      .1       0    5412     .16       0
  5656.2      .1       0  5775.5     .16       0
Bank Sta=4970,5040.6
XS Rating Curve= 0 ,0
Exp/Cntr=0.3,0.1

Type RM Length L Ch R = 1 ,13602   ,478,478,478
BEGIN DESCRIPTION:
MIDDLE FORK HUNTERS CREEK 29.0
END DESCRIPTION:
XS GIS Cut Line= 3
      2803524.13     10015255.29      2804600.52     10014482.72
      2804839.25     10014113.77
#Sta/Elev= 30
  4318.2 1750.48  4349.8 1748.84  4379.9  1748.9  4469.5 1745.27    4709 1733.93
  4753.2 1733.16  4774.1 1730.66  4809.7 1723.37  4889.5  1714.3  4925.1 1706.42
    4939 1701.52    4946 1699.53  4981.6 1698.94  4993.3 1697.22  4996.1 1696.72
  4999.3 1697.22  5061.4 1701.56    5146 1701.49  5218.6 1700.72  5352.4 1702.75
  5424.5 1704.48    5504 1707.25  5677.7  1714.7  5772.2 1721.43  5828.6 1727.35
  5915.9 1737.92  5942.6 1739.43  5980.7 1742.21  5995.8 1745.48  6082.6 1753.73
#Mann= 11 ,-1 , 0
  4318.2     .05       0  4349.8      .1       0  4469.5     .16       0
  4993.3     .07       0  4999.3     .16       0    5146      .1       0
  5352.4     .16       0  5424.5      .1       0    5504     .16       0
  5828.6      .1       0  5942.6     .16       0
Bank Sta=4939,5061.4
XS Rating Curve= 0 ,0
Exp/Cntr=0.3,0.1

Type RM Length L Ch R = 1 ,13124   ,843,843,843
BEGIN DESCRIPTION:
MIDDLE FORK HUNTERS CREEK 28.0
END DESCRIPTION:
XS GIS Cut Line= 3
      2803966.87     10015576.44      2804370.48     10015207.54
      2805051.92      10014213.6
#Sta/Elev= 30
  4344.8  1740.1  4347.7  1740.1  4570.7 1726.24  4626.2 1723.15  4709.9  1717.9
  4765.5 1714.91    4815 1709.81    4849 1708.44  4902.5 1705.48  4920.5 1703.77
  4965.3 1695.06  4986.2 1693.35  4998.1 1689.55  5000.9 1689.05  5004.1 1689.55
    5016 1694.43  5022.1 1695.21    5037 1697.29    5066  1697.6  5252.2 1693.48
    5324 1693.97  5417.6 1703.15  5634.7 1711.17  5691.5 1717.36  5829.4 1725.52
  5921.7 1731.43  6014.8 1735.24  6021.6 1735.87  6076.9 1738.61  6096.7 1739.18
#Mann= 14 ,-1 , 0
  4344.8     .05       0  4347.7     .16       0  4570.7     .05       0
  4626.2     .16       0  4709.9     .05       0  4765.5      .1       0
    4849     .05       0  4902.5     .16       0  4998.1     .07       0
  5004.1     .16       0  5829.4      .1       0  6014.8     .16       0
  6021.6      .1       0  6076.9     .16       0
Bank Sta=4965.3,5022.1
XS Rating Curve= 0 ,0
Exp/Cntr=0.3,0.1

Type RM Length L Ch R = 1 ,12281   ,259,259,259
BEGIN DESCRIPTION:
MIDDLE FORK HUNTERS CREEK 27.0
END DESCRIPTION:
XS GIS Cut Line= 3
      2803997.26     10015658.91      2805090.97     10015042.61
      2805559.73     10014530.44
#Sta/Elev= 30
  3850.1 1740.47  3882.5 1737.81    3994 1731.64    4098 1723.41  4147.1 1720.71
  4236.8 1716.98  4287.7    1717  4310.6 1714.18  4355.3 1704.87    4383 1702.44
  4462.8 1699.78  4700.6 1696.56  4835.5 1692.61  4873.9 1692.42  4911.5 1688.86
  4954.8 1687.66  4996.3 1678.18  4999.1 1677.68  5002.3 1678.18  5004.5 1678.43
    5014 1679.43  5035.7 1686.67  5057.4 1693.51  5105.5 1693.78  5180.9 1703.98
  5446.3 1717.16  5484.9 1718.32    5659  1730.8  5687.6 1732.74  5799.8 1740.76
#Mann= 13 ,-1 , 0
  3850.1     .05       0  3882.5     .16       0    4098      .1       0
  4147.1     .05       0    4383      .1       0  4462.8     .16       0
  4835.5      .1       0  4996.3     .07       0  5002.3      .1       0
  5004.5     .16       0  5446.3      .1       0    5659     .16       0
  5687.6      .1       0
Bank Sta=4954.8,5035.7
XS Rating Curve= 0 ,0
Exp/Cntr=0.3,0.1

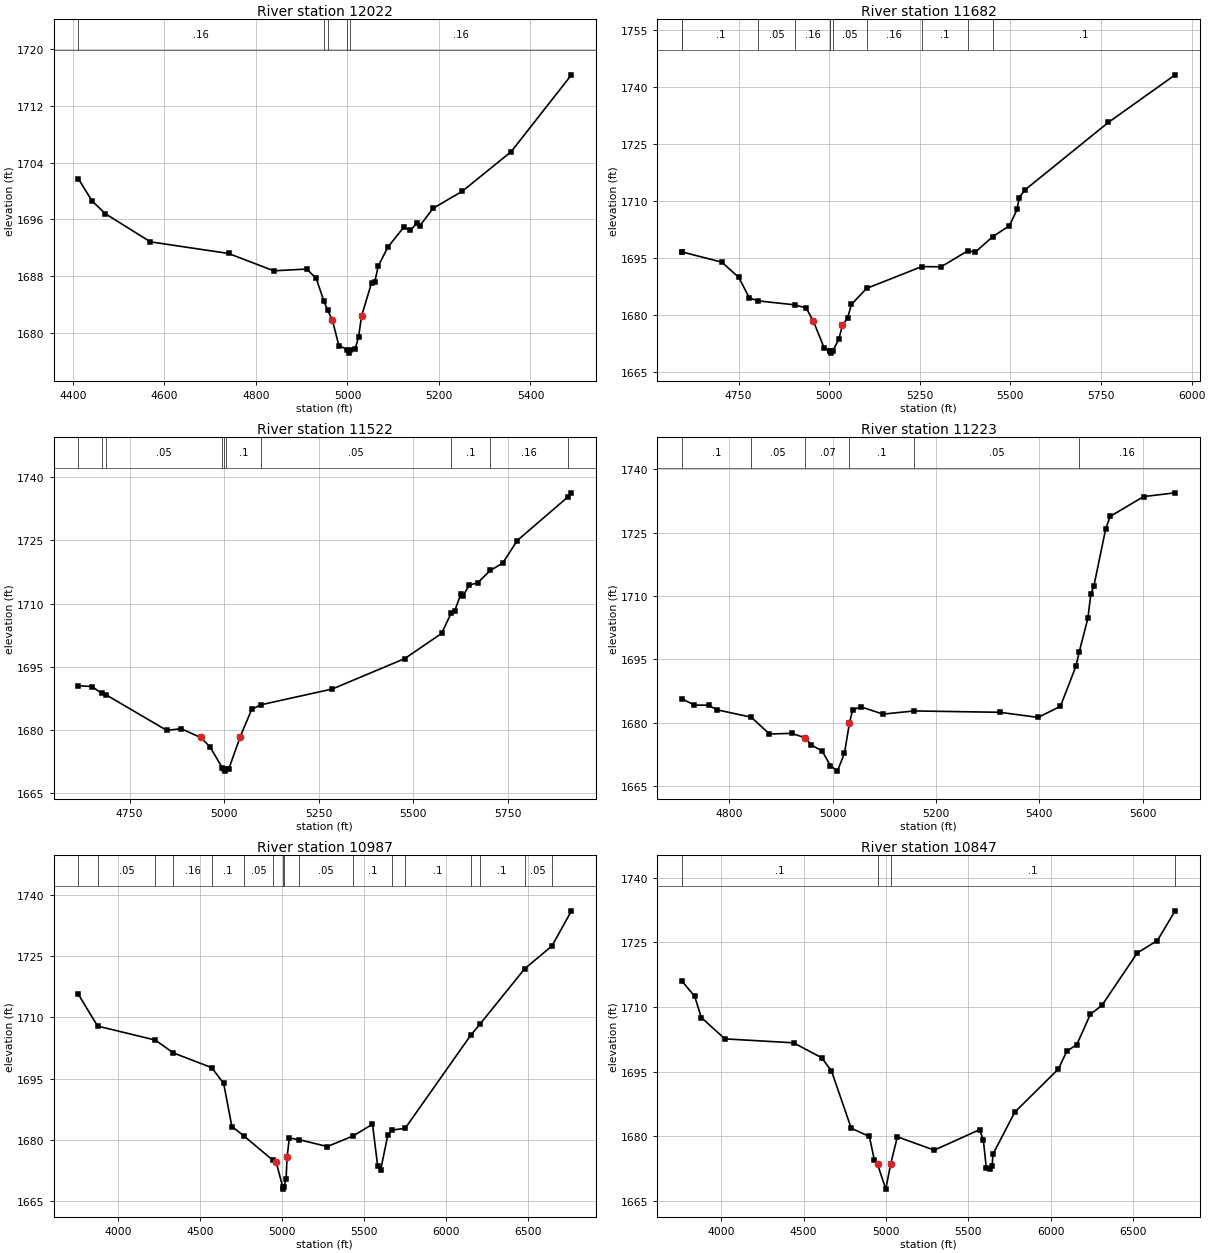
Type RM Length L Ch R = 1 ,12022   ,340,340,340
BEGIN DESCRIPTION:
MIDDLE FORK HUNTERS CREEK 26.0
END DESCRIPTION:
XS GIS Cut Line= 2
       2804782.8     10015750.09      2805467.79      10014917.7
#Sta/Elev= 30
  4411.6 1701.77  4441.7 1698.62  4470.4 1696.82  4569.4 1692.83  4740.1 1691.19
  4839.1 1688.74  4910.9 1688.99  4931.7 1687.68  4948.5 1684.46  4956.5 1683.21
  4966.8 1681.84  4981.2 1678.19  4999.6 1677.62  5002.4 1677.12  5005.6 1677.62
  5016.4 1677.64  5024.2 1679.34  5030.7 1682.33  5052.9 1687.09  5059.4  1687.1
  5067.3 1689.41  5088.1 1692.07  5123.2 1694.91  5137.6 1694.44  5151.9 1695.48
  5158.4 1695.11  5187.1 1697.56  5250.9 1699.97  5357.8 1705.56  5489.6 1716.41
#Mann= 5 ,-1 , 0
  4411.6     .16       0  4948.5     .05       0  4956.5     .16       0
  4999.6     .07       0  5005.6     .16       0
Bank Sta=4966.8,5030.7
XS Rating Curve= 0 ,0
Exp/Cntr=0.3,0.1

Type RM Length L Ch R = 1 ,11682   ,160,160,160
BEGIN DESCRIPTION:
Mapping XS fe462126
END DESCRIPTION:
XS GIS Cut Line= 4
      2805299.31     10015928.01      2805390.45     10015715.35
      2805390.45     10015489.66      2805663.25     10014627.97
#Sta/Elev= 30
  4593.6 1696.59  4594.7 1696.59  4703.6 1693.93  4750.6 1689.91  4779.8 1684.49
  4804.9 1683.72  4904.6  1682.7  4936.6 1681.87  4956.6 1678.33  4986.6 1671.27
    5003 1670.51  5003.6 1670.49  5006.3 1669.99  5009.6 1670.49  5026.6 1673.64
  5036.6 1677.37  5050.7 1679.21  5061.4 1682.81  5103.1 1687.01  5255.3 1692.75
  5308.6 1692.69  5382.7 1696.92    5403 1696.56  5450.7 1700.59  5497.4 1703.51
  5518.4  1707.8  5524.1 1710.91  5539.4 1712.87  5770.1 1730.67  5954.5  1743.2
#Mann= 11 ,-1 , 0
  4593.6     .05       0  4594.7      .1       0  4804.9     .05       0
  4904.6     .16       0    5003     .05       0  5003.6     .07       0
  5009.6     .05       0  5103.1     .16       0  5255.3      .1       0
  5382.7     .16       0  5450.7      .1       0
Bank Sta=4956.6,5036.6
XS Rating Curve= 0 ,0
Exp/Cntr=0.3,0.1

Type RM Length L Ch R = 1 ,11522   ,299,299,299
BEGIN DESCRIPTION:
Mapping XS e327ba6c
END DESCRIPTION:
XS GIS Cut Line= 4
      2805364.42     10015997.45      2805498.96     10015745.74
       2805546.7     10015337.75       2805828.8     10014799.59
#Sta/Elev= 30
    4614 1690.45  4650.5 1690.27    4676 1688.65  4686.5 1688.36    4848 1679.84
  4886.2 1680.24  4937.4 1678.15  4961.8    1676  4994.6 1670.99  4999.1 1670.65
  5001.9 1670.15  5005.1 1670.65  5012.2 1670.73  5042.4 1678.37  5072.6 1684.85
  5097.2 1685.93  5285.7 1689.68    5477 1696.91  5574.4 1702.89  5599.9 1707.75
  5609.3 1708.31  5625.8 1712.37  5631.4 1711.88  5647.8 1714.41  5669.9 1714.92
  5702.9 1717.86  5736.1 1719.62  5774.5 1724.99  5907.6  1735.3  5917.8 1736.33
#Mann= 10 ,-1 , 0
    4614     .05       0    4676      .1       0  4686.5     .05       0
  4994.6      .1       0  4999.1     .07       0  5005.1      .1       0
  5097.2     .05       0  5599.9      .1       0  5702.9     .16       0
  5907.6      .1       0
Bank Sta=4937.4,5042.4
XS Rating Curve= 0 ,0
Exp/Cntr=0.3,0.1

Type RM Length L Ch R = 1 ,11223   ,236,236,236
BEGIN DESCRIPTION:
MIDDLE FORK HUNTERS CREEK 25.0
END DESCRIPTION:
XS GIS Cut Line= 2
      2805377.46     10016053.88      2806204.94     10015577.32
#Sta/Elev= 30
  4707.9 1685.69  4732.1 1684.19  4759.6 1684.17  4775.4 1683.09  4842.2 1681.33
  4877.5 1677.35  4920.6 1677.51  4946.7 1676.44  4957.9 1674.81  4979.5 1673.33
  4995.3  1669.9  5008.9 1668.57  5022.6 1672.79  5032.2 1679.88  5038.4 1683.05
  5054.2 1683.78  5097.3 1682.06  5157.8 1682.81  5322.9 1682.49  5397.6 1681.28
  5440.7 1683.91  5470.7 1693.37  5477.2 1696.84  5493.8  1704.7  5499.6  1710.5
  5505.4 1712.33  5528.4 1725.93    5537 1728.83  5601.6 1733.52  5662.8 1734.41
#Mann= 6 ,-1 , 0
  4707.9      .1       0  4842.2     .05       0  4946.7     .07       0
  5032.2      .1       0  5157.8     .05       0  5477.2     .16       0
Bank Sta=4946.7,5032.2
XS Rating Curve= 0 ,0
Exp/Cntr=0.3,0.1

Type RM Length L Ch R = 1 ,10987   ,140,140,140
BEGIN DESCRIPTION:
MIDDLE FORK HUNTERS CREEK 24.0
END DESCRIPTION:
XS GIS Cut Line= 3
       2804422.6      10016097.3       2805859.2     10016145.04
      2807394.52     10016465.99
#Sta/Elev= 30
  3757.8 1715.73  3875.7 1707.88  4227.1 1704.44  4338.4 1701.28  4571.2 1697.67
  4644.2  1693.8  4694.2 1683.23  4769.9 1680.83  4944.7 1674.93  4964.3 1674.48
  5004.3 1668.36    5007 1667.86  5010.3 1668.36  5024.4 1670.24 5030.47 1675.63
  5044.4 1680.41  5105.5 1679.98  5276.2 1678.31  5433.4 1680.92  5551.1 1683.79
  5582.7 1673.49  5601.1 1672.62    5644 1681.03  5667.7 1682.35  5750.1 1682.78
  6149.5 1705.62    6205 1708.29    6478 1721.93  6644.8 1727.55  6763.7 1736.16
#Mann= 17 ,-1 , 0
  3757.8      .1       0  3875.7     .05       0  4227.1      .1       0
  4338.4     .16       0  4571.2      .1       0  4769.9     .05       0
  4944.7      .1       0  5004.3     .07       0  5010.3      .1       0
  5105.5     .05       0  5433.4      .1       0  5667.7     .16       0
  5750.1      .1       0  6149.5     .16       0    6205      .1       0
    6478     .05       0  6644.8      .1       0
#XS Ineff= 1 ,-1
 5541.97 5794.131681.269
Permanent Ineff=
       F
Bank Sta=4964.3,5030.47
XS Rating Curve= 0 ,0
Exp/Cntr=0.3,0.1

Type RM Length L Ch R = 1 ,10847   ,188,188,188
BEGIN DESCRIPTION:
Mapping XS 2492b371
END DESCRIPTION:
XS GIS Cut Line= 5
      2804370.47     10016257.89      2805707.29     10016262.23
      2806163.02     10016353.38      2806327.95     10016322.99
      2807334.21     10016518.17
#Sta/Elev= 30
  3761.1 1716.04  3839.1 1712.42  3879.1 1707.53  4022.3 1702.58  4439.1 1701.66
  4609.1 1698.21  4669.1 1695.13  4789.1 1681.83  4899.1 1679.92  4929.1 1674.53
  4949.1 1673.44  4998.8 1667.69  5029.1 1673.62  5069.1 1679.84  5292.9 1676.74
  5568.2 1681.49    5591 1679.12  5608.9 1672.66  5629.2 1672.32    5644 1673.04
  5649.6 1675.82  5781.8 1685.57  6046.7 1695.58  6097.6 1699.71  6158.7 1701.27
  6240.2 1708.25  6311.5 1710.39  6525.4 1722.53  6647.7 1725.42  6755.4 1732.31
#Mann= 4 ,-1 , 0
  3761.1      .1       0  4949.1     .07       0  5029.1      .1       0
  6755.4      .1       0
#XS Ineff= 1 ,-1
 5573.32 5744.45 1677.55
Permanent Ineff=
       F
Bank Sta=4949.1,5029.1
XS Rating Curve= 0 ,0
Exp/Cntr=0.3,0.1