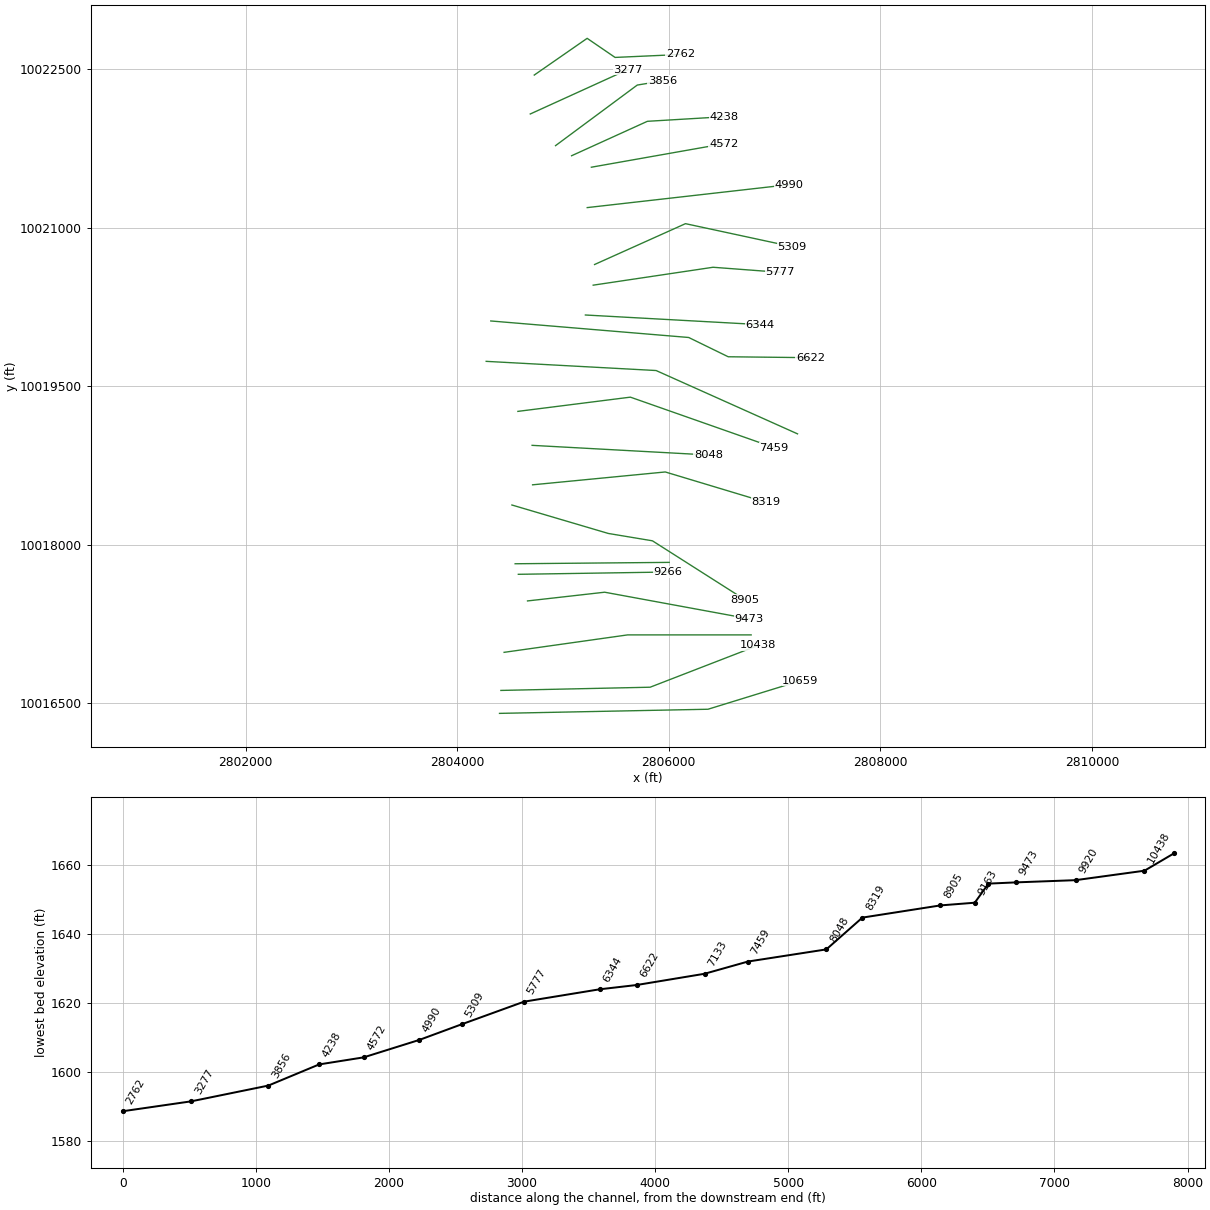
HEC-RAS study MIDDLE FORK HUNTERS CREEK.prj: MIDDLE FORK HUNTERS CREEK Base Level Engineering

--- MIDDLE FORK HUNTERS CREEK.g01 (geometry) --- (continued)

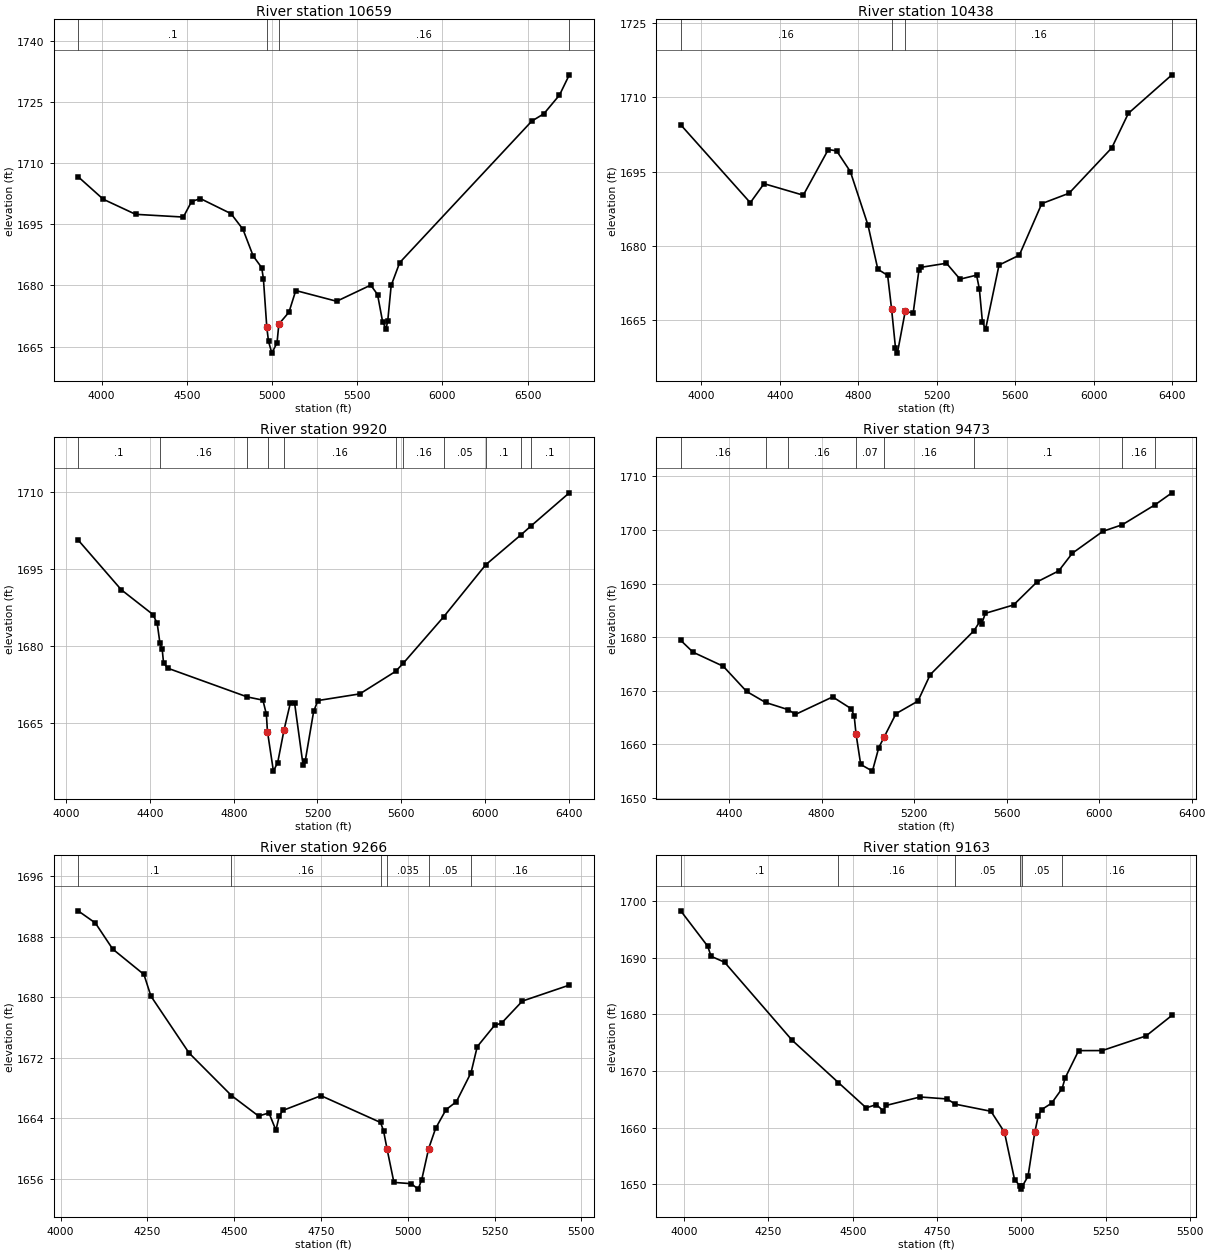
Type RM Length L Ch R = 1 ,10659   ,221,221,221
BEGIN DESCRIPTION:
Mapping XS 34484397
END DESCRIPTION:
XS GIS Cut Line= 3
      2804400.91     10016405.46      2806371.35     10016444.52
      2807243.57     10016713.57
#Sta/Elev= 30
  3861.6 1706.62  4009.2  1701.1  4199.2  1697.4  4479.3 1696.73  4527.8 1700.53
  4579.3 1701.26  4759.3 1697.56  4829.3 1693.74  4889.4 1687.19  4939.4 1684.33
  4949.4 1681.63  4969.4 1669.69  4979.4 1666.26  4999.1 1663.38  5029.4 1665.91
  5040.1 1670.49  5099.4 1673.41  5139.4 1678.72  5379.5 1676.09  5579.5 1680.05
  5619.5 1677.74  5649.5 1671.01  5669.5 1669.34  5679.5 1671.34  5699.5 1679.96
  5749.5 1685.56  6525.3 1720.26  6595.8 1722.04  6687.5 1726.62  6745.2 1731.59
#Mann= 4 ,-1 , 0
  3861.6      .1       0  4969.4     .07       0  5040.1     .16       0
  6745.2     .16       0
#XS Ineff= 1 ,-1
 5591.48 5740.591675.475
Permanent Ineff=
       F
Bank Sta=4969.4,5040.1
XS Rating Curve= 0 ,0
Exp/Cntr=0.3,0.1

Type RM Length L Ch R = 1 ,10438   ,518,518,518
BEGIN DESCRIPTION:
MIDDLE FORK HUNTERS CREEK 23.0
END DESCRIPTION:
XS GIS Cut Line= 3
      2804413.85     10016622.47      2805824.48     10016652.85
      2806843.95     10017047.63
#Sta/Elev= 30
  3895.3 1704.43    4250 1688.71    4320 1692.55  4520.1 1690.23  4647.7 1699.44
  4690.1 1699.17  4760.1 1694.99  4850.1 1684.18  4900.2 1675.29  4950.2 1674.06
  4970.2 1667.29  4990.2 1659.43  4999.9 1658.37  5040.2 1666.87  5080.2  1666.4
    5110 1675.19  5120.2 1675.68  5250.2  1676.5  5319.2 1673.29  5403.6  1674.1
  5417.8 1671.32  5433.6 1664.57  5449.9 1663.26    5518 1676.13  5621.5 1678.13
    5736 1688.53    5875 1690.62    6093 1699.78  6177.4 1706.74  6399.5 1714.51
#Mann= 4 ,-1 , 0
  3895.3     .16       0  4970.2     .07       0  5040.2     .16       0
  6399.5      .1       0
#XS Ineff= 1 ,-1
 5276.36 5533.211674.148
Permanent Ineff=
       F
Bank Sta=4970.2,5040.2
XS Rating Curve= 0 ,0
Exp/Cntr=0.3,0.1

Type RM Length L Ch R = 1 ,9920    ,447,447,447
BEGIN DESCRIPTION:
MIDDLE FORK HUNTERS CREEK 22.0
END DESCRIPTION:
XS GIS Cut Line= 3
      2804444.27     10016982.72       2805611.8     10017147.65
      2806779.38     10017147.65
#Sta/Elev= 30
  4056.5 1700.73  4262.7 1691.02  4414.2 1686.18  4434.4 1684.45  4447.3 1680.65
  4458.3 1679.37  4464.7 1676.76  4484.9 1675.71  4865.3  1670.1  4939.4 1669.48
    4956 1666.73    4961 1663.36  4961.6 1663.24  4989.6 1655.63  5010.1 1657.31
  5040.4 1663.68  5070.7 1668.95  5090.9 1668.89  5131.3 1656.81  5141.4 1657.57
  5181.8 1667.28    5202  1669.4  5402.3  1670.7  5572.9 1675.08  5609.2 1676.64
  5803.4 1685.76  6003.9 1695.89    6173 1701.76  6220.4 1703.47  6403.2 1709.93
#Mann= 11 ,-1 , 0
  4056.5      .1       0  4447.3     .16       0  4865.3      .1       0
  4961.6     .07       0  5040.4     .16       0  5572.9      .1       0
  5609.2     .16       0  5803.4     .05       0  6003.9      .1       0
    6173     .05       0  6220.4      .1       0
#XS Ineff= 1 ,-1
  5087.6 5224.231667.459
Permanent Ineff=
       F
Bank Sta=4961,5040.4
XS Rating Curve= 0 ,0
Exp/Cntr=0.3,0.1

Type RM Length L Ch R = 1 ,9473    ,207,207,207
BEGIN DESCRIPTION:
MIDDLE FORK HUNTERS CREEK 21.0
END DESCRIPTION:
XS GIS Cut Line= 3
      2804665.67     10017468.83      2805394.79     10017551.29
      2806761.94     10017299.56
#Sta/Elev= 30
  4190.8  1679.4  4243.9 1677.19  4374.8 1674.56  4475.4 1669.87  4557.4 1667.81
  4656.2 1666.45  4686.7 1665.57  4847.8 1668.84    4929 1666.61  4941.1  1665.2
  4948.6    1662    4969 1656.24  5019.6 1654.99  5047.2 1659.38  5070.7 1661.38
  5121.5 1665.71  5216.5 1668.06  5269.5 1672.99  5458.8  1681.2  5486.7 1683.08
  5491.8 1682.42  5507.9 1684.44  5629.9    1686  5731.6 1690.31  5825.2 1692.36
  5884.1 1695.66  6016.3 1699.75  6100.5 1700.98  6243.2 1704.74  6314.7 1706.93
#Mann= 8 ,-1 , 0
  4190.8     .16       0  4557.4      .1       0  4656.2     .16       0
  4948.6     .07       0  5070.7     .16       0  5458.8      .1       0
  6100.5     .16       0  6243.2      .1       0
Bank Sta=4948.6,5070.7
XS Rating Curve= 0 ,0
Exp/Cntr=0.3,0.1

Type RM Length L Ch R = 1 ,9266    ,103,103,103
BEGIN DESCRIPTION:
Mapping XS c7c9f171
END DESCRIPTION:
XS GIS Cut Line= 2
      2804578.77     10017720.56       2805993.6     10017742.26
#Sta/Elev= 30
  4050.4 1691.45  4100.1 1689.84  4150.1 1686.39  4240.1 1683.03  4260.1 1680.17
  4370.1 1672.64  4492.2 1667.01  4570.2  1664.3  4600.2 1664.71  4620.2 1662.43
  4630.2 1664.35  4640.2 1665.04  4750.2 1666.99  4921.6 1663.45  4930.2 1662.37
  4940.2 1659.98  4960.2 1655.52  5010.2 1655.35    5030 1654.63  5040.2 1655.86
  5060.2 1659.99  5080.2 1662.66  5110.2 1665.14  5140.2  1666.2  5182.4 1670.05
  5200.2 1673.48  5250.2  1676.3  5270.2 1676.59  5330.2 1679.51  5465.4 1681.62
#Mann= 6 ,-1 , 0
  4050.4      .1       0  4492.2     .16       0  4921.6     .05       0
  4940.2    .035       0  5060.2     .05       0  5182.4     .16       0
Bank Sta=4940.2,5060.2
XS Rating Curve= 0 ,0
Exp/Cntr=0.3,0.1

Type RM Length L Ch R = 1 ,9163    ,258,258,258
BEGIN DESCRIPTION:
MIDDLE FORK HUNTERS CREEK 20.0
END DESCRIPTION:
XS GIS Cut Line= 2
      2804548.48     10017820.39      2806005.12      10017833.4
#Sta/Elev= 30
  3989.7 1698.33  4069.7 1692.07  4079.7 1690.29  4119.7 1689.24  4319.7 1675.46
  4457.6 1667.93  4539.7 1663.48  4569.7 1664.05  4589.7 1662.99  4599.7 1663.92
  4699.7  1665.4  4779.7 1665.05  4803.8 1664.13  4909.7 1662.87  4949.7 1659.18
  4979.7 1650.79  4996.7  1649.6  4999.5  1649.1  5002.7  1649.6  5019.7 1651.39
  5039.7 1659.13  5049.7 1661.98  5059.7 1663.15  5089.7 1664.31  5120.8  1666.9
  5129.7 1668.75  5169.7  1673.6  5239.7 1673.61  5369.7  1676.2  5446.4 1679.83
#Mann= 6 ,-1 , 0
  3989.7      .1       0  4457.6     .16       0  4803.8     .05       0
  4996.7    .035       0  5002.7     .05       0  5120.8     .16       0
Bank Sta=4949.7,5039.7
XS Rating Curve= 0 ,0
Exp/Cntr=0.3,0.1

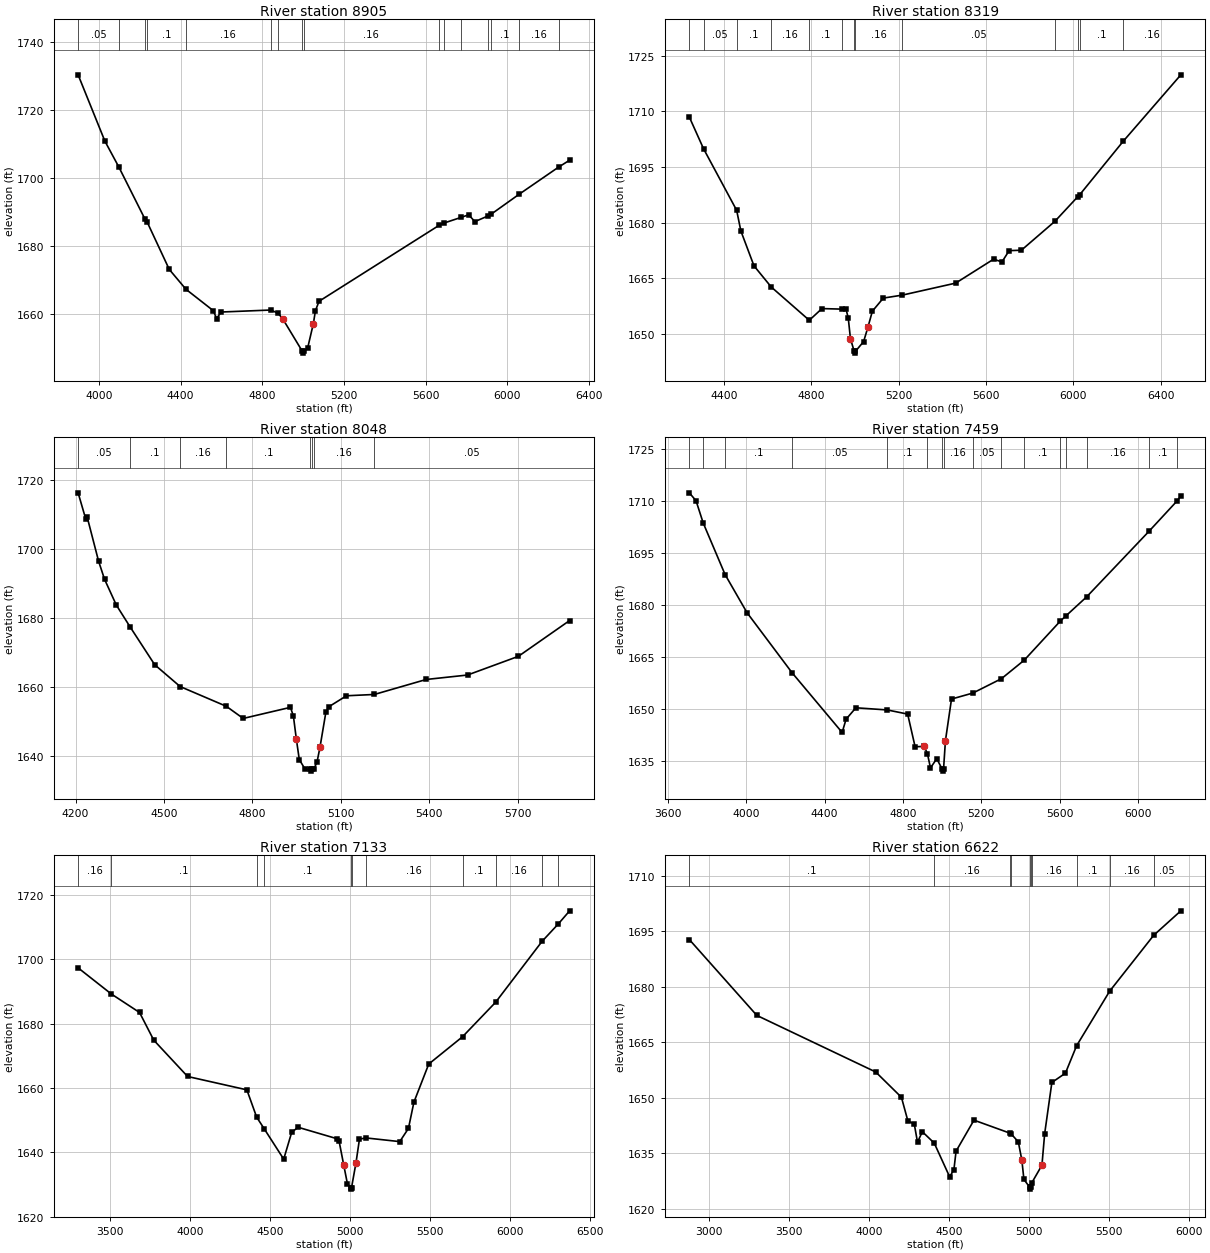
Type RM Length L Ch R = 1 ,8905    ,586,586,586
BEGIN DESCRIPTION:
MIDDLE FORK HUNTERS CREEK 19.0
END DESCRIPTION:
XS GIS Cut Line= 4
      2804518.06     10018375.94      2805429.51     10018106.85
      2805846.18      10018037.4      2806718.55     10017481.87
#Sta/Elev= 30
    3898 1730.39  4029.1 1710.84  4097.9 1703.15  4224.6 1687.94  4237.1 1686.85
  4344.4    1673  4426.1 1667.15  4559.8 1660.85  4576.2 1658.51  4598.4 1660.44
  4841.5 1661.03  4877.4 1660.08  4900.4 1658.39  4996.4 1648.82  4999.1 1648.32
  5002.4 1648.82    5022 1649.81    5050 1657.02  5060.2 1660.85  5077.8 1663.61
  5664.8 1685.97  5691.1 1686.71    5775 1688.38  5810.5 1689.11    5841  1687.1
  5904.1 1688.75  5919.8 1689.25  6056.7 1695.13  6251.5  1703.2    6305 1705.22
#Mann= 16 ,-1 , 0
    3898     .05       0  4097.9      .1       0  4224.6     .05       0
  4237.1      .1       0  4426.1     .16       0  4841.5      .1       0
  4877.4     .16       0  4996.4     .07       0  5002.4     .16       0
  5664.8      .1       0  5691.1     .16       0    5775      .1       0
  5904.1     .16       0  5919.8      .1       0  6056.7     .16       0
  6251.5      .1       0
Bank Sta=4900.4,5050
XS Rating Curve= 0 ,0
Exp/Cntr=0.3,0.1

Type RM Length L Ch R = 1 ,8319    ,271,271,271
BEGIN DESCRIPTION:
MIDDLE FORK HUNTERS CREEK 18.0
END DESCRIPTION:
XS GIS Cut Line= 3
       2804713.4     10018566.92      2805967.71     10018688.45
       2806918.2     10018401.99
#Sta/Elev= 30
    4240 1708.49    4305 1699.96    4457 1683.32  4476.2 1677.76  4536.4 1668.34
  4615.4 1662.64  4789.9 1653.65  4847.9 1656.81  4941.1 1656.66  4958.4 1656.61
  4968.5 1654.27  4978.5  1648.7  4995.6 1645.29  4998.3 1644.79  5001.6 1645.29
  5038.8  1647.9  5058.9 1651.84    5079 1656.11  5129.2 1659.64  5216.9 1660.45
  5460.8 1663.68  5634.7 1670.14  5672.9 1669.39  5705.9 1672.44  5762.1 1672.56
  5915.4 1680.34  6019.8 1686.95  6030.1 1687.58  6228.6 1701.94  6492.9 1719.88
#Mann= 13 ,-1 , 0
    4240      .1       0    4305     .05       0    4457      .1       0
  4615.4     .16       0  4789.9      .1       0  4941.1     .16       0
  4995.6     .07       0  5001.6     .16       0  5216.9     .05       0
  5915.4      .1       0  6019.8     .16       0  6030.1      .1       0
  6228.6     .16       0
Bank Sta=4978.5,5058.9
XS Rating Curve= 0 ,0
Exp/Cntr=0.3,0.1

Type RM Length L Ch R = 1 ,8048    ,589,589,589
BEGIN DESCRIPTION:
MIDDLE FORK HUNTERS CREEK 17.0
END DESCRIPTION:
XS GIS Cut Line= 2
      2804708.98     10018940.18      2806374.59      10018849.1
#Sta/Elev= 30
  4208.7 1716.35  4234.3 1708.82  4239.3 1709.36  4278.3 1696.47  4298.3 1691.28
  4338.4 1683.77  4384.5 1677.52  4468.6 1666.46  4554.9 1660.13  4711.6  1654.4
    4769 1650.87  4929.3 1654.09  4939.3 1651.58  4949.3 1644.89  4959.3 1638.94
  4979.3  1636.1  4996.4 1636.08  4999.1 1635.58  5002.4 1636.08  5009.4 1636.32
  5019.4 1638.18  5029.4 1642.45  5049.4 1652.61  5059.5 1654.26  5119.5 1657.45
    5214 1657.83    5390 1662.18  5530.2 1663.47  5702.9  1668.9  5876.8 1679.29
#Mann= 8 ,-1 , 0
  4208.7     .05       0  4384.5      .1       0  4554.9     .16       0
  4711.6      .1       0  4996.4     .07       0  5002.4      .1       0
  5009.4     .16       0    5214     .05       0
Bank Sta=4949.3,5029.4
XS Rating Curve= 0 ,0
Exp/Cntr=0.3,0.1

Type RM Length L Ch R = 1 ,7459    ,326,326,326
BEGIN DESCRIPTION:
MIDDLE FORK HUNTERS CREEK 16.0
END DESCRIPTION:
XS GIS Cut Line= 3
      2804574.48     10019261.36      2805637.85     10019395.91
      2806994.55     10018919.11
#Sta/Elev= 30
  3709.2 1712.41  3743.5 1710.12  3779.9 1703.73  3892.1 1688.78  4003.7 1677.82
  4233.5 1660.49  4489.6 1643.22  4509.5 1647.04  4559.7 1650.35  4720.4 1649.72
  4824.1 1648.53  4862.1 1639.11  4908.9 1639.18  4924.9 1637.11  4940.7 1632.99
  4972.5 1635.64  5001.3 1632.56    5004 1632.06  5007.3 1632.56    5017 1640.84
    5048 1652.87  5157.4 1654.61  5303.1 1658.75  5419.3 1664.09  5603.6 1675.38
  5631.7 1676.85  5737.8 1682.36  6056.4  1701.3  6201.5 1710.17  6219.1 1711.51
#Mann= 16 ,-1 , 0
  3709.2      .1       0  3779.9     .05       0  3892.1      .1       0
  4233.5     .05       0  4720.4      .1       0  4924.9     .16       0
  5001.3     .07       0  5007.3     .16       0  5157.4     .05       0
  5303.1     .16       0  5419.3      .1       0  5603.6     .16       0
  5631.7      .1       0  5737.8     .16       0  6056.4      .1       0
  6201.5     .16       0
Bank Sta=4908.9,5017
XS Rating Curve= 0 ,0
Exp/Cntr=0.3,0.1

Type RM Length L Ch R = 1 ,7133    ,511,511,511
BEGIN DESCRIPTION:
MIDDLE FORK HUNTERS CREEK 15.0
END DESCRIPTION:
XS GIS Cut Line= 3
      2804274.97     10019734.45       2805880.9     10019647.65
      2807217.68      10019048.7
#Sta/Elev= 30
    3300 1697.39  3507.5 1689.26  3684.1  1683.5  3772.9 1674.89  3984.5 1663.58
    4355 1659.42  4416.3 1650.92    4464 1647.26  4585.4 1637.85  4635.4 1646.22
  4675.5 1647.77  4916.6 1644.24  4931.5 1643.49  4960.4  1636.1  4983.4 1630.26
  5003.6 1629.02  5006.3 1628.52  5009.6 1629.02  5037.1 1636.64    5059 1644.07
  5098.8 1644.46    5311 1643.31  5365.3 1647.42  5399.5 1655.59  5492.2 1667.45
  5703.5 1675.95  5910.1 1686.67  6200.9 1705.65  6302.4 1711.07  6373.1 1715.14
#Mann= 11 ,-1 , 0
    3300     .16       0  3507.5      .1       0  4416.3     .16       0
    4464      .1       0  5003.6     .07       0  5009.6      .1       0
  5098.8     .16       0  5703.5      .1       0  5910.1     .16       0
  6200.9      .1       0  6302.4     .16       0
Bank Sta=4960.4,5037.1
XS Rating Curve= 0 ,0
Exp/Cntr=0.3,0.1

Type RM Length L Ch R = 1 ,6622    ,278,278,278
BEGIN DESCRIPTION:
MIDDLE FORK HUNTERS CREEK 14.0
END DESCRIPTION:
XS GIS Cut Line= 4
      2804318.42     10020116.39      2806189.06     10019960.15
      2806562.32     10019777.85      2807339.23     10019769.17
#Sta/Elev= 30
  2879.7  1692.7  3301.2  1672.2  4043.8 1656.91  4204.3 1650.08  4244.5  1643.7
  4284.6 1642.82  4304.7 1637.94  4334.8 1640.78  4409.3 1637.69  4505.4 1628.59
    4532 1630.51  4545.5 1635.52  4657.3  1643.9  4881.6 1640.39  4888.8 1640.22
  4934.3 1638.03  4956.5 1633.04  4969.2 1627.88  5005.7 1625.76  5008.4 1625.26
  5011.7 1625.76  5019.4 1627.04  5081.8 1631.73  5098.8 1640.25  5143.8 1654.08
  5228.4 1656.59  5298.3 1664.01  5504.4 1678.73  5779.5 1693.84  5949.2 1700.46
#Mann= 10 ,-1 , 0
  2879.7      .1       0  4409.3     .16       0  4881.6     .05       0
  4888.8      .1       0  5005.7     .07       0  5011.7      .1       0
  5019.4     .16       0  5298.3      .1       0  5504.4     .16       0
  5779.5     .05       0
Bank Sta=4956.5,5081.8
XS Rating Curve= 0 ,0
Exp/Cntr=0.3,0.1

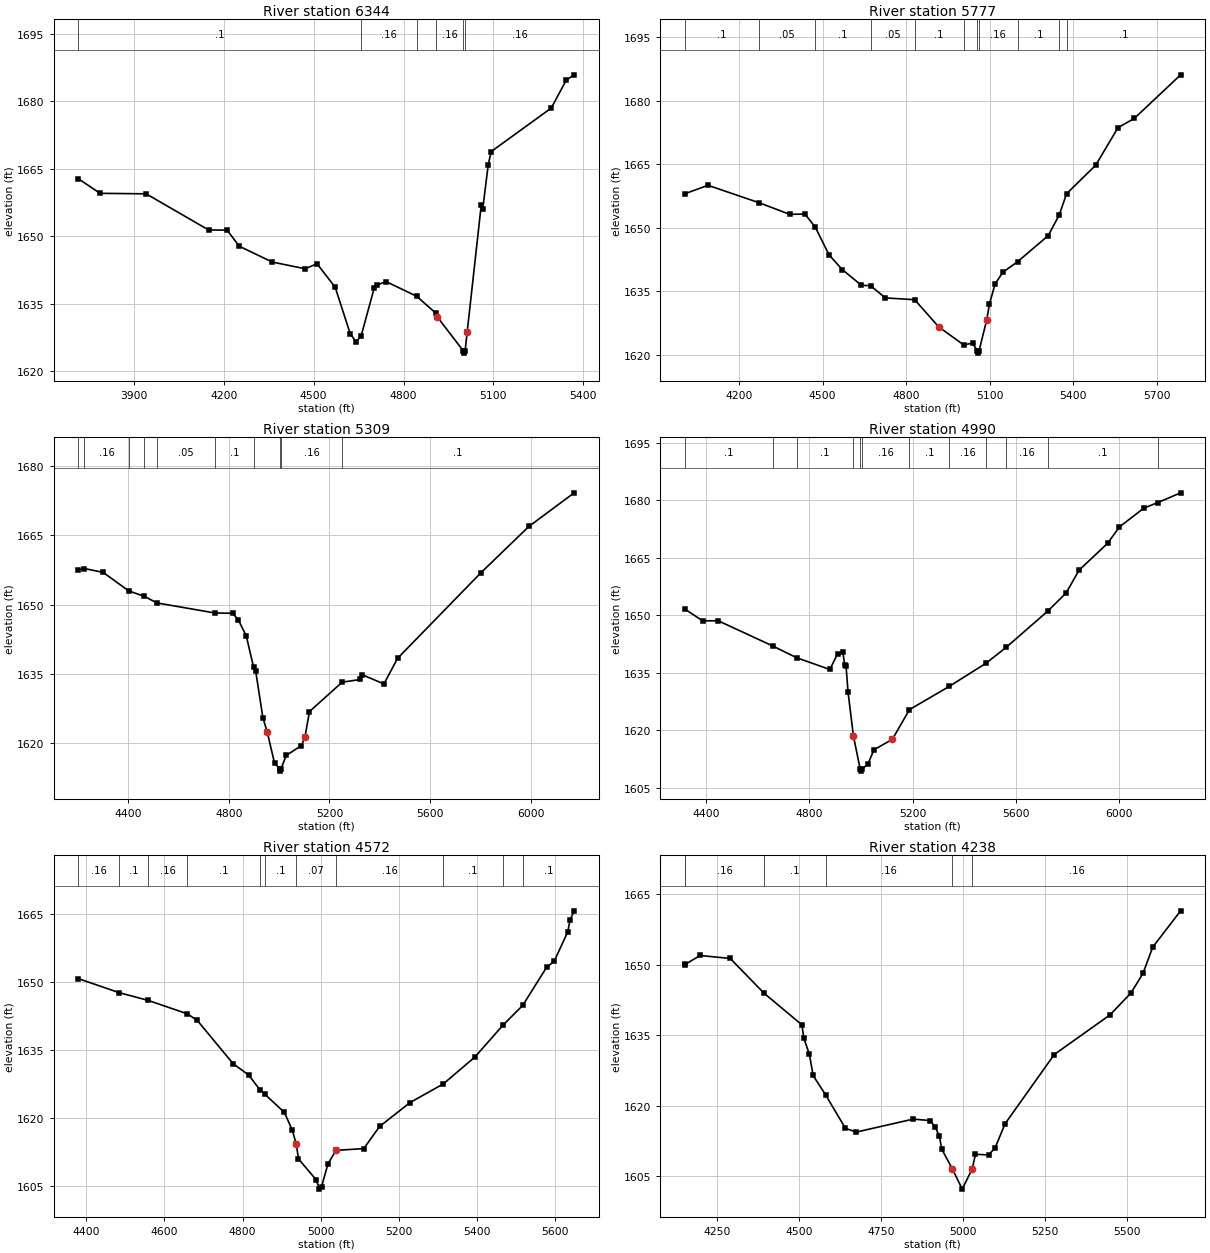
Type RM Length L Ch R = 1 ,6344    ,567,567,567
BEGIN DESCRIPTION:
MIDDLE FORK HUNTERS CREEK 13.0
END DESCRIPTION:
XS GIS Cut Line= 2
      2805212.54     10020172.82      2806864.83     10020081.75
#Sta/Elev= 30
  3714.7 1662.79  3787.3 1659.54    3941 1659.43  4149.3  1651.4  4211.4 1651.36
  4251.4  1647.8  4361.6 1644.27  4471.8 1642.77  4511.3 1643.89  4571.9 1638.67
    4622 1628.35    4642 1626.48  4658.9 1627.93  4702.3 1638.53  4712.1 1639.19
  4742.2 1639.91  4843.7 1636.67  4906.9 1632.96  4912.4 1632.09  4999.6 1624.52
  5002.3 1624.02  5005.6 1624.52  5012.6  1628.8  5059.3 1656.89  5064.3 1655.99
  5082.7  1665.9  5092.7 1668.83    5293 1678.49  5343.1 1684.69  5369.5 1685.88
#Mann= 6 ,-1 , 0
  3714.7      .1       0  4658.9     .16       0  4843.7      .1       0
  4906.9     .16       0  4999.6     .07       0  5005.6     .16       0
Bank Sta=4912.4,5012.6
XS Rating Curve= 0 ,0
Exp/Cntr=0.3,0.1

Type RM Length L Ch R = 1 ,5777    ,468,468,468
BEGIN DESCRIPTION:
MIDDLE FORK HUNTERS CREEK 12.0
END DESCRIPTION:
XS GIS Cut Line= 3
      2805286.32     10020454.94       2806419.1     10020624.21
      2807052.74     10020576.47
#Sta/Elev= 30
  4005.2 1658.07  4088.3 1660.08  4272.5 1655.95  4381.5 1653.23    4437 1653.27
    4474 1650.17    4523 1643.68  4570.4 1640.19  4639.6 1636.46  4672.7 1636.36
  4725.3 1633.48  4830.7 1633.06  4917.4 1626.62  5007.2 1622.37  5038.7 1622.81
  5055.9 1620.94  5058.7 1620.44  5061.9 1620.94  5089.3 1628.22  5099.4 1632.04
  5119.6 1636.78  5147.7 1639.55  5200.5 1642.04  5310.4 1648.19  5349.8 1653.05
  5376.6 1658.11  5480.9 1664.81  5561.1 1673.69  5619.5 1675.87    5786 1686.17
#Mann= 11 ,-1 , 0
  4005.2      .1       0  4272.5     .05       0    4474      .1       0
  4672.7     .05       0  4830.7      .1       0  5007.2     .16       0
  5055.9     .07       0  5061.9     .16       0  5200.5      .1       0
  5349.8     .16       0  5376.6      .1       0
Bank Sta=4917.4,5089.3
XS Rating Curve= 0 ,0
Exp/Cntr=0.3,0.1

Type RM Length L Ch R = 1 ,5309    ,319,319,319
BEGIN DESCRIPTION:
MIDDLE FORK HUNTERS CREEK 11.0
END DESCRIPTION:
XS GIS Cut Line= 3
      2805299.34     10020650.27      2806158.68     10021036.54
      2807164.52     10020819.76
#Sta/Elev= 30
    4202  1657.5    4226 1657.83  4300.5    1657  4402.8 1652.97  4464.7  1651.8
    4514 1650.38  4745.3 1648.19    4815 1648.13  4837.4 1646.77  4869.8  1643.2
  4898.4 1636.48  4906.9 1635.65  4935.6 1625.52  4953.2 1622.31  4981.9 1615.65
    5002  1614.4  5004.8  1613.9    5008  1614.4  5028.2 1617.29  5089.1 1619.45
  5103.1 1621.36  5120.8 1626.81  5250.8 1633.19  5323.3 1633.77  5328.4 1634.85
  5416.8 1632.81  5471.3 1638.37    5801 1656.84  5993.1 1666.96  6173.1 1674.25
#Mann= 10 ,-1 , 0
    4202      .1       0    4226     .16       0  4402.8     .05       0
  4464.7      .1       0    4514     .05       0  4745.3      .1       0
  4898.4     .16       0    5002     .07       0    5008     .16       0
  5250.8      .1       0
Bank Sta=4953.2,5103.1
XS Rating Curve= 0 ,0
Exp/Cntr=0.3,0.1

Type RM Length L Ch R = 1 ,4990    ,418,418,418
BEGIN DESCRIPTION:
MIDDLE FORK HUNTERS CREEK 10.0
END DESCRIPTION:
XS GIS Cut Line= 2
      2805229.84     10021188.44      2807139.54     10021405.45
#Sta/Elev= 30
  4317.1 1651.64  4386.2 1648.56  4446.6 1648.58  4659.6 1641.95  4750.3 1638.95
  4879.3 1635.87  4909.5 1639.99  4929.6 1640.44  4937.2 1636.98  4942.2 1636.75
  4949.8 1630.05  4970.6 1618.57  4997.1 1609.86  4999.8 1609.36  5003.1 1609.86
  5026.7 1611.16  5050.4 1614.95  5121.3 1617.62    5188  1625.4  5341.6 1631.44
  5483.6 1637.45  5562.7 1641.63  5724.1  1651.1  5795.2 1655.83  5845.5 1661.78
  5956.2 1668.79    6002 1673.06  6097.1 1677.98  6151.2 1679.42  6239.1 1681.95
#Mann= 12 ,-1 , 0
  4317.1      .1       0  4659.6     .16       0  4750.3      .1       0
  4970.6     .16       0  4997.1     .07       0  5003.1     .16       0
    5188      .1       0  5341.6     .16       0  5483.6      .1       0
  5562.7     .16       0  5724.1      .1       0  6151.2     .05       0
Bank Sta=4970.6,5121.3
XS Rating Curve= 0 ,0
Exp/Cntr=0.3,0.1

Type RM Length L Ch R = 1 ,4572    ,334,334,334
BEGIN DESCRIPTION:
MIDDLE FORK HUNTERS CREEK 9.0
END DESCRIPTION:
XS GIS Cut Line= 2
      2805268.95     10021570.39       2806518.9     10021791.74
#Sta/Elev= 30
  4379.6  1650.7    4484 1647.61  4558.3  1645.9  4657.8 1642.97  4683.8 1641.52
  4775.9 1631.95  4815.8 1629.45  4844.7 1626.17  4856.6 1625.26  4907.2 1621.21
  4927.5 1617.26  4937.7  1614.2  4943.2 1610.97  4988.4 1606.38    4997 1604.31
  5002.3 1604.86  5018.9 1609.92  5039.2 1612.85  5110.3 1613.24  5150.9 1618.12
  5228.7 1623.38  5314.1  1627.5  5394.7 1633.41  5466.8 1640.44  5517.3  1644.8
  5578.5  1653.2  5597.8  1654.5  5632.5    1661  5638.4  1663.6    5649 1665.64
#Mann= 11 ,-1 , 0
  4379.6     .16       0    4484      .1       0  4558.3     .16       0
  4657.8      .1       0  4844.7     .16       0  4856.6      .1       0
  4937.7     .07       0  5039.2     .16       0  5314.1      .1       0
  5466.8     .16       0  5517.3      .1       0
Bank Sta=4937.7,5039.2
XS Rating Curve= 0 ,0
Exp/Cntr=0.3,0.1

Type RM Length L Ch R = 1 ,4238    ,382,382,382
BEGIN DESCRIPTION:
MIDDLE FORK HUNTERS CREEK 8.0
END DESCRIPTION:
XS GIS Cut Line= 3
      2805082.32     10021678.91      2805798.44     10022004.42
      2806523.31     10022047.82
#Sta/Elev= 30
    4152 1649.97  4153.1 1650.06  4198.6 1651.96  4290.6 1651.33  4393.1 1643.98
  4509.4 1637.21  4514.9 1634.42  4532.2 1630.94  4543.5 1626.44  4581.7  1622.3
  4642.1  1615.2    4675  1614.4  4848.8 1617.16  4900.5 1616.85  4916.7  1615.4
    4929 1613.47  4935.9 1610.78  4968.7 1606.53  4998.5 1602.27  5028.8 1606.55
  5038.8 1609.68  5078.9 1609.54  5098.9 1611.05    5129 1616.16  5279.3  1630.9
  5449.6 1639.34  5513.7 1644.03  5549.8 1648.14  5579.8 1653.75  5664.8 1661.46
#Mann= 6 ,-1 , 0
    4152      .1       0  4153.1     .16       0  4393.1      .1       0
  4581.7     .16       0  4968.7     .07       0  5028.8     .16       0
Bank Sta=4968.7,5028.8
XS Rating Curve= 0 ,0
Exp/Cntr=0.3,0.1

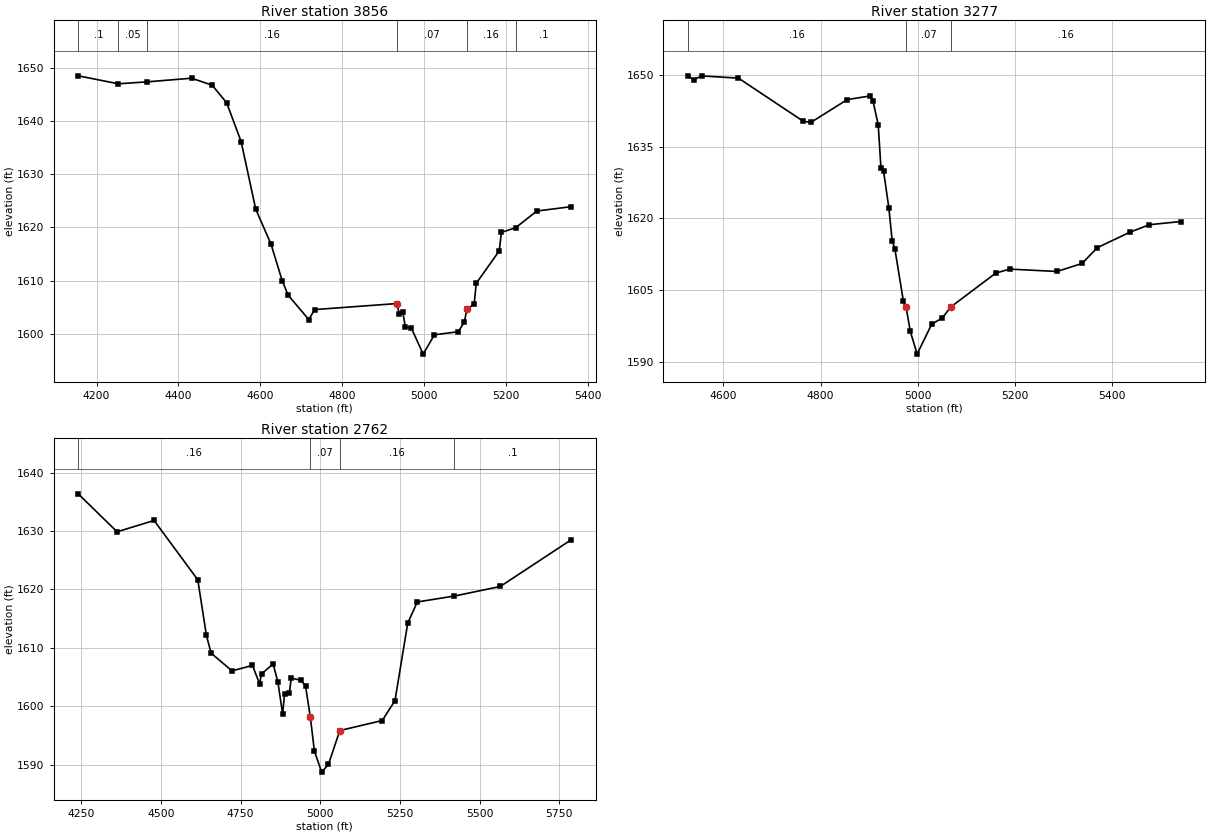
Type RM Length L Ch R = 1 ,3856    ,579,579,579
BEGIN DESCRIPTION:
MIDDLE FORK HUNTERS CREEK 7.0
END DESCRIPTION:
XS GIS Cut Line= 3
       2804930.4      10021774.4      2805702.95      10022347.3
      2805941.68     10022386.37
#Sta/Elev= 30
  4155.3 1648.55  4253.4 1647.05  4324.1 1647.42  4432.1  1648.1  4482.2 1646.79
  4517.6 1643.49  4553.1 1636.13  4588.6 1623.44    4626 1616.84  4653.3 1609.95
  4667.9 1607.23    4718 1602.66  4732.6 1604.53  4932.9 1605.66  4939.1 1603.76
  4947.5 1604.15  4953.8 1601.22  4968.4 1601.05  4997.4 1596.14  5024.7 1599.78
  5083.2 1600.36  5097.8  1602.2    5104 1604.55  5121.8 1605.59  5126.9 1609.48
  5183.1 1615.59  5188.2 1619.06  5223.3 1619.96  5274.7 1623.09    5359 1623.91
#Mann= 6 ,-1 , 0
  4155.3      .1       0  4253.4     .05       0  4324.1     .16       0
  4932.9     .07       0    5104     .16       0  5223.3      .1       0
Bank Sta=4932.9,5104
XS Rating Curve= 0 ,0
Exp/Cntr=0.3,0.1

Type RM Length L Ch R = 1 ,3277    ,515,515,515
BEGIN DESCRIPTION:
MIDDLE FORK HUNTERS CREEK 6.0
END DESCRIPTION:
XS GIS Cut Line= 2
      2804691.67     10022073.86      2805614.85     10022494.28
#Sta/Elev= 30
  4526.4 1649.87  4538.8 1649.09  4555.8 1649.85    4631 1649.39  4764.6 1640.33
  4780.3 1640.14  4854.9  1644.9    4901 1645.64  4907.5 1644.69  4918.5 1639.59
  4924.1 1630.56  4929.6 1629.86  4940.4 1622.17  4947.1 1615.37  4952.6 1613.69
  4970.2 1602.67  4975.7 1601.49  4984.4 1596.37  4998.5 1591.58  5028.3 1597.82
  5050.3 1599.17  5067.9 1601.47  5160.1 1608.54  5188.6 1609.39  5286.3 1608.89
  5337.9 1610.58    5369 1613.87  5435.6 1617.09  5476.3 1618.69  5540.8 1619.35
#Mann= 3 , 0 , 0
  4526.4     .16       0  4975.7     .07       0  5067.9     .16       0
Bank Sta=4975.7,5067.9
XS Rating Curve= 0 ,0
Exp/Cntr=0.3,0.1

Type RM Length L Ch R = 1 ,2762    ,446,446,446
BEGIN DESCRIPTION:
MIDDLE FORK HUNTERS CREEK 5.0
END DESCRIPTION:
XS GIS Cut Line= 4
      2804729.31      10022441.9      2805229.31     10022789.12
       2805493.2     10022608.56      2806111.29     10022636.34
#Sta/Elev= 30
  4240.5 1636.35  4362.5 1629.85  4478.6 1631.79  4615.7 1621.63  4642.8  1612.1
  4657.6 1609.07  4723.1 1606.04  4787.3 1606.98  4809.5 1603.84  4815.6 1605.53
  4852.1 1607.22    4867 1604.16  4881.9 1598.66    4888  1602.1  4902.9 1602.23
    4909  1604.8  4938.8 1604.45  4953.7 1603.47  4968.6 1598.22  4981.5 1592.34
  5004.2 1588.71  5025.5 1590.02  5061.3 1595.83  5194.3 1597.54  5234.3 1600.93
  5274.4 1614.22  5304.4 1617.84  5420.6 1618.85  5564.7 1620.49  5787.7  1628.5
#Mann= 4 ,-1 , 0
  4240.5     .16       0  4968.6     .07       0  5061.3     .16       0
  5420.6      .1       0
Bank Sta=4968.6,5061.3
XS Rating Curve= 0 ,0
Exp/Cntr=0.3,0.1