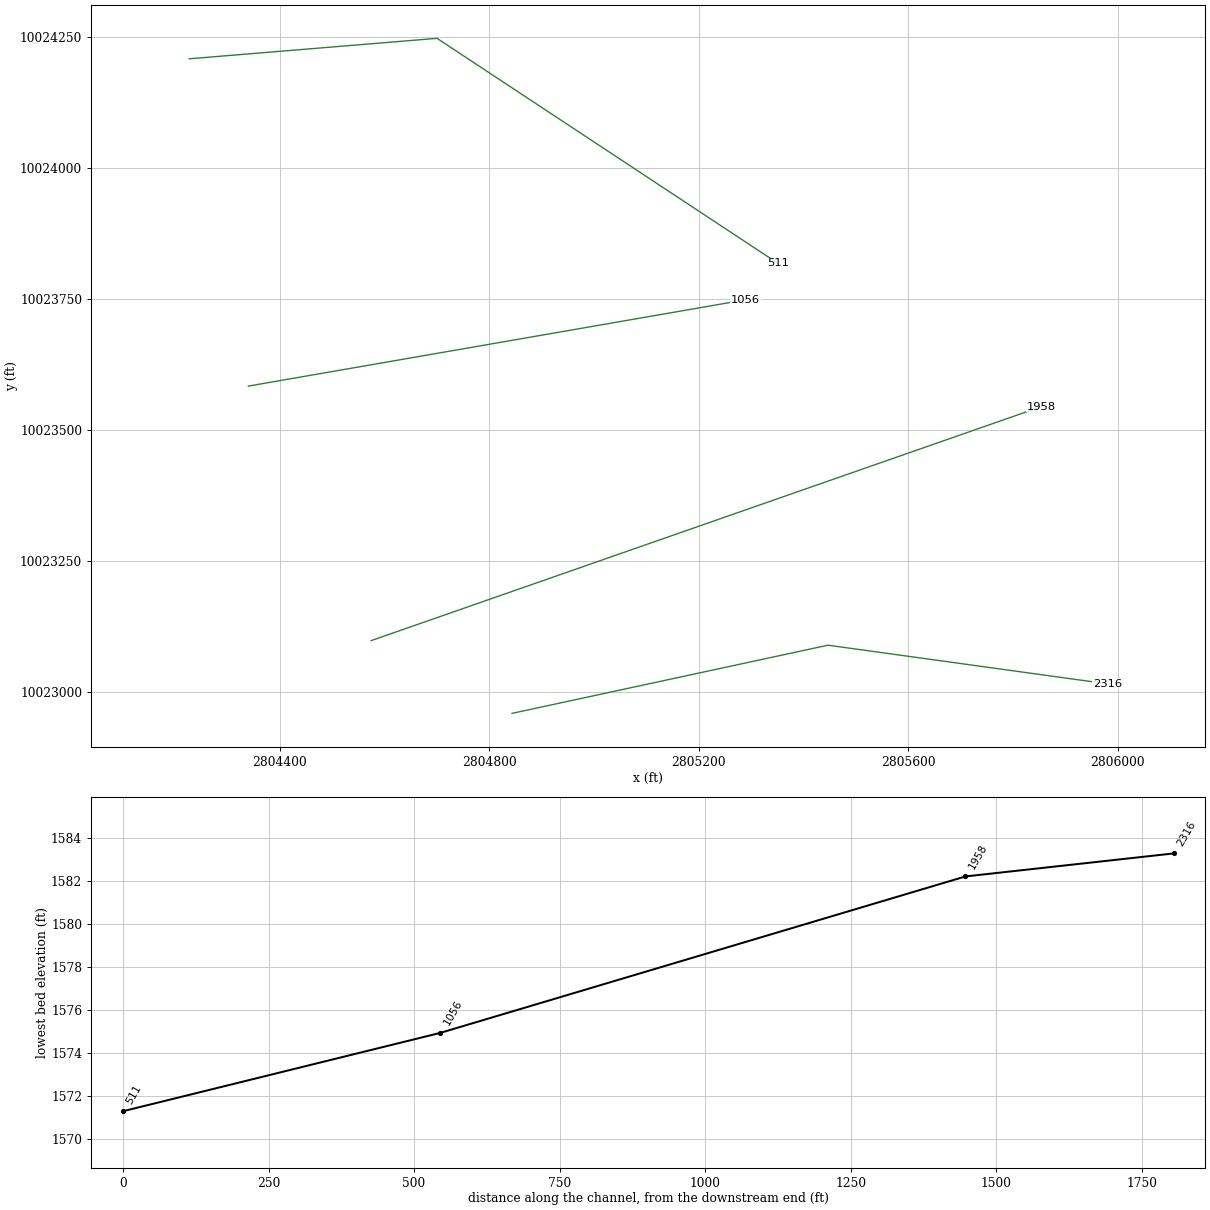
HEC-RAS study MIDDLE FORK HUNTERS CREEK.prj: MIDDLE FORK HUNTERS CREEK Base Level Engineering

--- MIDDLE FORK HUNTERS CREEK.g01 (geometry) --- (continued)

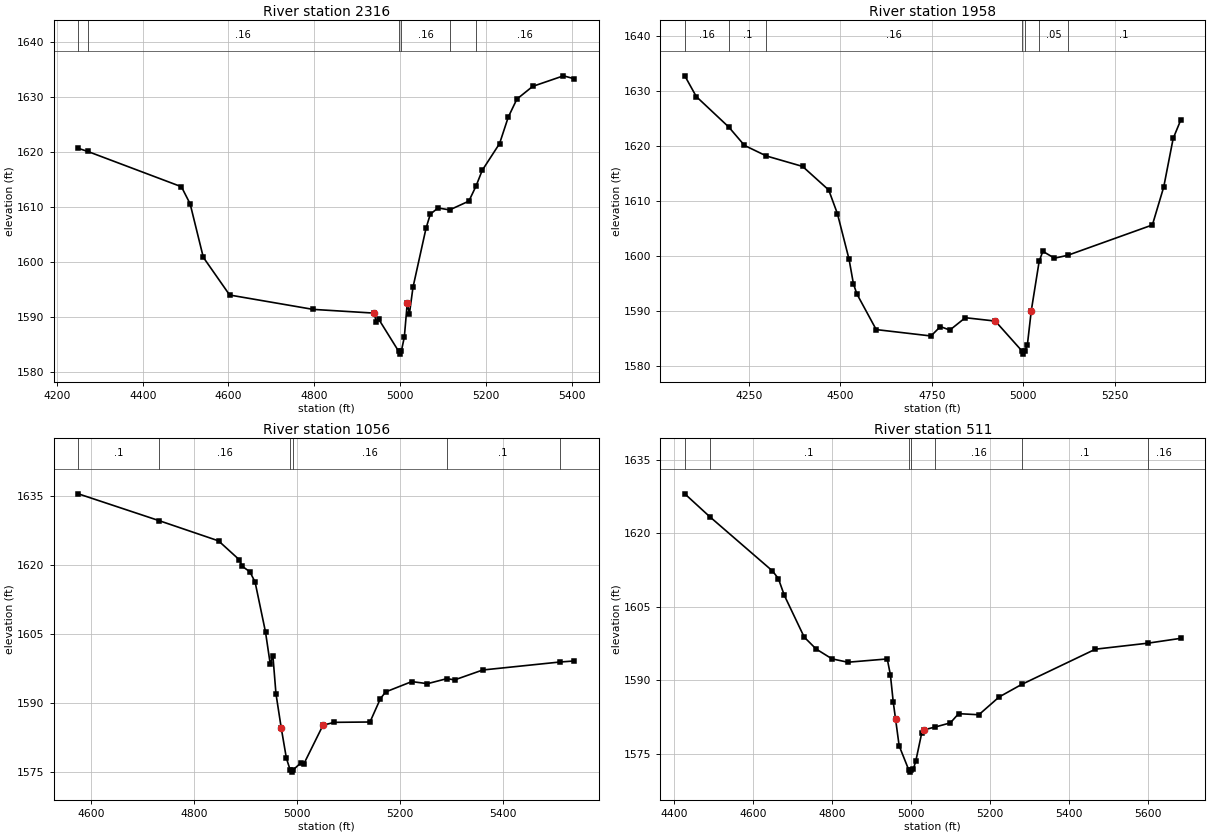
Type RM Length L Ch R = 1 ,2316    ,358,358,358
BEGIN DESCRIPTION:
MIDDLE FORK HUNTERS CREEK 4.0
END DESCRIPTION:
XS GIS Cut Line= 3
      2804843.62     10022959.29      2805446.87     10023089.49
      2805980.75      10023015.7
#Sta/Elev= 30
  4249.9 1620.72  4272.1 1620.15  4490.2 1613.74  4510.6 1610.62  4541.3  1600.9
  4602.7 1594.04  4797.1 1591.43  4939.3 1590.75    4945 1589.08    4950 1589.68
  4996.9 1583.79  4999.6 1583.29  5002.9 1583.79    5010 1586.37  5016.8 1592.54
  5021.9 1590.64  5030.2 1595.44  5060.5 1606.15  5070.6 1608.75  5088.7 1609.88
  5115.6 1609.52  5160.5 1611.12  5177.2 1613.86  5191.7 1616.73  5232.1 1621.59
  5252.3 1626.39  5272.5 1629.68  5309.3 1631.99  5381.1 1633.91    5406 1633.38
#Mann= 6 ,-1 , 0
  4249.9      .1       0  4272.1     .16       0  4996.9     .07       0
  5002.9     .16       0  5115.6      .1       0  5177.2     .16       0
Bank Sta=4939.3,5016.8
XS Rating Curve= 0 ,0
Exp/Cntr=0.3,0.1

Type RM Length L Ch R = 1 ,1958    ,902,902,902
BEGIN DESCRIPTION:
MIDDLE FORK HUNTERS CREEK 3.0
END DESCRIPTION:
XS GIS Cut Line= 2
      2804574.49     10023098.17      2805854.13     10023544.96
#Sta/Elev= 30
  4074.8 1632.81  4106.2 1629.04    4195  1623.5  4237.9 1620.16  4297.9 1618.24
  4396.8 1616.34  4468.2 1612.06  4492.1 1607.73  4523.9 1599.44  4535.7 1595.02
  4545.1 1593.17    4598 1586.68  4747.8 1585.52  4773.5 1587.23  4799.3 1586.59
  4841.6 1588.84  4923.5 1588.23  4997.5 1582.72  5000.3 1582.22  5003.5 1582.72
  5011.1 1583.81    5022 1590.14  5043.5 1599.09  5053.5 1600.91  5085.3 1599.66
  5121.4 1600.18    5353  1605.7    5384  1612.6  5409.8 1621.42  5430.2 1624.72
#Mann= 7 ,-1 , 0
  4074.8     .16       0    4195      .1       0  4297.9     .16       0
  4997.5     .07       0  5003.5     .16       0  5043.5     .05       0
  5121.4      .1       0
Bank Sta=4923.5,5022
XS Rating Curve= 0 ,0
Exp/Cntr=0.3,0.1

Type RM Length L Ch R = 1 ,1056    ,545,545,545
BEGIN DESCRIPTION:
MIDDLE FORK HUNTERS CREEK 2.0
END DESCRIPTION:
XS GIS Cut Line= 2
      2804340.07     10023584.27      2805289.29     10023748.98
#Sta/Elev= 30
  4575.7 1635.42  4733.2 1629.57  4848.1  1625.2  4888.7 1621.07    4894 1619.69
    4909 1618.48  4919.1 1616.27  4939.4 1605.38  4948.6 1598.41  4953.7 1600.29
  4959.7 1591.98  4969.9 1584.58    4980 1577.95  4987.2 1575.45  4989.9 1574.95
  4993.2 1575.45  5008.3 1576.98  5013.4 1576.63  5051.1 1585.15  5073.1 1585.77
  5142.4 1585.84  5162.7 1590.93  5172.9 1592.38  5223.6 1594.62  5254.1 1594.17
  5291.8 1595.26  5306.8 1594.99  5361.4 1597.14  5510.8 1598.87  5539.1  1599.1
#Mann= 6 ,-1 , 0
  4575.7      .1       0  4733.2     .16       0  4987.2     .07       0
  4993.2     .16       0  5291.8      .1       0  5510.8     .16       0
Bank Sta=4969.9,5051.1
XS Rating Curve= 0 ,0
Exp/Cntr=0.3,0.1

Type RM Length L Ch R = 1 ,511     ,0,0,0
BEGIN DESCRIPTION:
MIDDLE FORK HUNTERS CREEK 1.0
END DESCRIPTION:
XS GIS Cut Line= 3
      2804227.29     10024209.28      2804700.35     10024248.34
      2805351.37     10023818.67
#Sta/Elev= 30
  4427.6 1628.06  4490.4 1623.42  4649.5 1612.33  4664.3 1610.79  4679.6 1607.33
  4729.8 1598.84  4759.9 1596.42    4800 1594.41  4840.2 1593.72  4939.9 1594.39
  4947.9 1591.14    4955 1585.65    4961  1582.1    4970 1576.68  4994.1 1571.81
  4996.8 1571.31  5000.1 1571.81  5006.2 1572.01  5012.2 1573.59  5027.2 1579.32
  5033.2 1579.94  5061.2 1580.51  5099.5 1581.35  5120.5 1583.23  5171.7 1583.01
  5222.9 1586.63  5280.2  1589.2  5466.7 1596.38  5599.9 1597.61  5682.3 1598.59
#Mann= 7 ,-1 , 0
  4427.6     .16       0  4490.4      .1       0  4994.1     .07       0
  5000.1      .1       0  5061.2     .16       0  5280.2      .1       0
  5599.9     .16       0
Bank Sta=4961,5033.2
XS Rating Curve= 0 ,0
Exp/Cntr=0.3,0.1

Chan Stop Cuts=-1
Use User Specified Reach Order=0
Composite Channel Slope=5