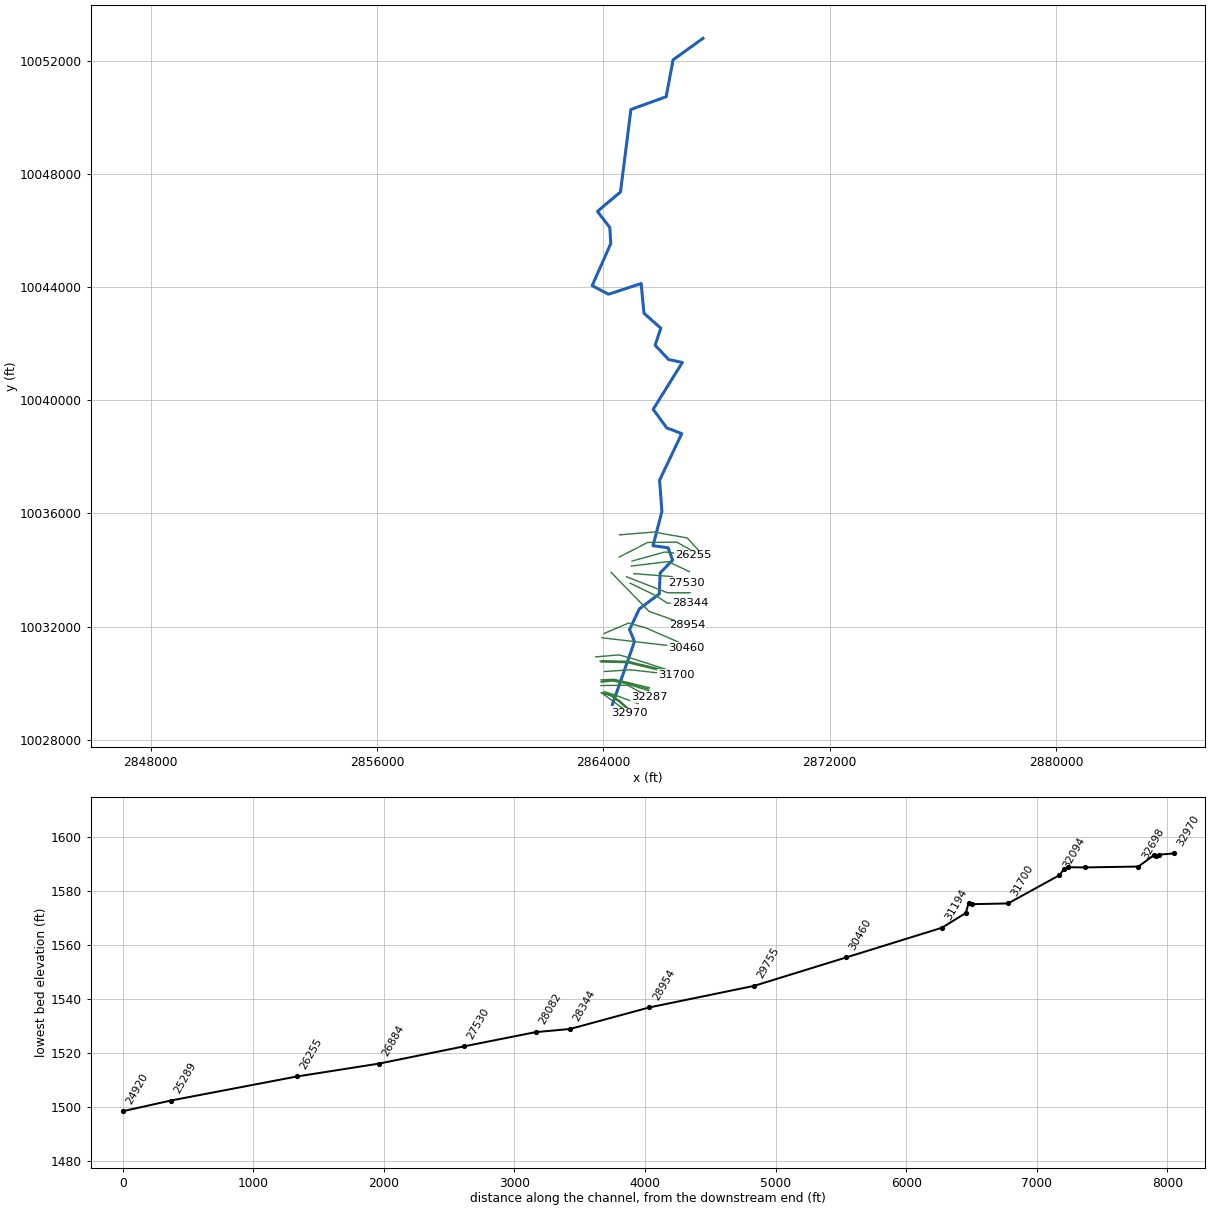
--- MIDDLE FORK ROCKY CREEK.prj (project) ---

Proj Title=MIDDLE FORK ROCKY CREEK Base Level Engineering
Current Plan=p01
Default Exp/Contr=0.3,0.1
English Units
Geom File=g01
Flow File=f01
Plan File=p01
Y Axis Title=Elevation
X Axis Title(PF)=Main Channel Distance
X Axis Title(XS)=Station
BEGIN DESCRIPTION:
MIDDLE FORK ROCKY CREEK
END DESCRIPTION:
DSS Export Rating Curves= 0
DSS Export Rating Curve Sorted= 0
DSS Export Volume Flow Curves= 0
DXF OffsetX= 0
DXF OffsetY= 0
DXF ScaleX= 1
DXF ScaleY= 10

--- MIDDLE FORK ROCKY CREEK.p01 (plan) ---

Plan Title=Multiple Run
Short Identifier=Multiple
Geom File=g01
Flow File=f01
Subcritical Flow
K Sum by GR= 0
Std Step Tol= 0.01
Critical Tol= 0.01
Num of Std Step Trials= 20
Max Error Tol= 0.3
Flow Tol Ratio= 0.001
Split Flow NTrial= 30
Split Flow Tol= 0.02
Split Flow Ratio= 0.02
Log Output Level= 0
Friction Slope Method= 1
Unsteady Friction Slope Method= 2
Unsteady Bridges Friction Slope Method= 1
Parabolic Critical Depth
Global Vel Dist=  1 , 1 , 1
Global Log Level= 0
CheckData=True
Encroach Param= -1, 0, 0, 0
BEGIN DESCRIPTION:
Multiple Run
END DESCRIPTION:

--- MIDDLE FORK ROCKY CREEK.f01 (steady flow) ---

Flow Title=Multiple
Program Version=4.10
Number of Profiles= 7
Profile Names=10-year,25-year,50-year,1pct_min,100-year,1pct_plu,500-year
River Rch & RM=MIDDLE FORK ROCK,Reach-1         ,32970
     978    1426    1817    1697    2295    3103    3669
River Rch & RM=MIDDLE FORK ROCK,Reach-1         ,30460
    1701    2555    3323    3159    4273    5779    7093
River Rch & RM=MIDDLE FORK ROCK,Reach-1         ,28954
    1802    2699    3503    3321    4491    6073    7412
River Rch & RM=MIDDLE FORK ROCK,Reach-1         ,23088
    2591    3942    5168    4943    6685    9041   11236
River Rch & RM=MIDDLE FORK ROCK,Reach-1         ,19241
    2655    4024    5262    5018    6786    9177   11336
River Rch & RM=MIDDLE FORK ROCK,Reach-1         ,11727
    2815    4271    5589    5332    7211    9752   12057
River Rch & RM=MIDDLE FORK ROCK,Reach-1         ,8182
    4367    6743    8928    8607   11639   15741   19873
River Rch & RM=MIDDLE FORK ROCK,Reach-1         ,4454
    4494    6933    9174    8837   11951   16162   20371
Boundary for River Rch & Prof#=MIDDLE FORK ROCK,Reach-1         , 1
Up Type= 0
Dn Type= 1
Dn Known WS=1375.54
Boundary for River Rch & Prof#=MIDDLE FORK ROCK,Reach-1         , 2
Up Type= 0
Dn Type= 1
Dn Known WS=1377.67
Boundary for River Rch & Prof#=MIDDLE FORK ROCK,Reach-1         , 3
Up Type= 0
Dn Type= 1
Dn Known WS=1378.89
Boundary for River Rch & Prof#=MIDDLE FORK ROCK,Reach-1         , 4
Up Type= 0
Dn Type= 1
Dn Known WS=1378.77
Boundary for River Rch & Prof#=MIDDLE FORK ROCK,Reach-1         , 5
Up Type= 0
Dn Type= 1
Dn Known WS=1380.04
Boundary for River Rch & Prof#=MIDDLE FORK ROCK,Reach-1         , 6
Up Type= 0
Dn Type= 1
Dn Known WS=1381.31
Boundary for River Rch & Prof#=MIDDLE FORK ROCK,Reach-1         , 7
Up Type= 0
Dn Type= 1
Dn Known WS=1382.41
DSS Import GetInterval= 0
DSS Import GetPeak= 0
DSS Import FillOption= 0

--- MIDDLE FORK ROCKY CREEK.g01 (geometry) ---

Geom Title=Existing Conditions
Program Version=4.10

River Reach=MIDDLE FORK ROCK,Reach-1
Reach XY= 30
      2864316.35     10029245.14      2865097.01     10031469.25
      2864921.78     10031892.24      2865267.76     10032623.18
      2865972.72     10033151.43      2866004.58     10033900.65
      2866446.71     10034349.56      2866284.73     10034785.78
      2865752.41     10034858.79      2866066.92     10036066.87
      2865983.83     10037176.72      2866767.72     10038823.31
      2866234.38     10039027.68      2865758.58     10039683.44
      2866789.24     10041340.76      2866299.42     10041446.13
      2865828.26     10041948.84      2866025.98     10042552.61
      2865432.94     10043080.87      2865331.97     10044130.46
      2864178.47     10043753.73      2863600.94     10044054.76
      2864258.15     10045543.14      2864225.96      10046112.7
      2863787.97     10046682.49      2864602.16     10047370.85
      2864971.05     10050287.56      2866218.23     10050739.72
      2866461.08     10052042.64      2867518.47     10052803.73

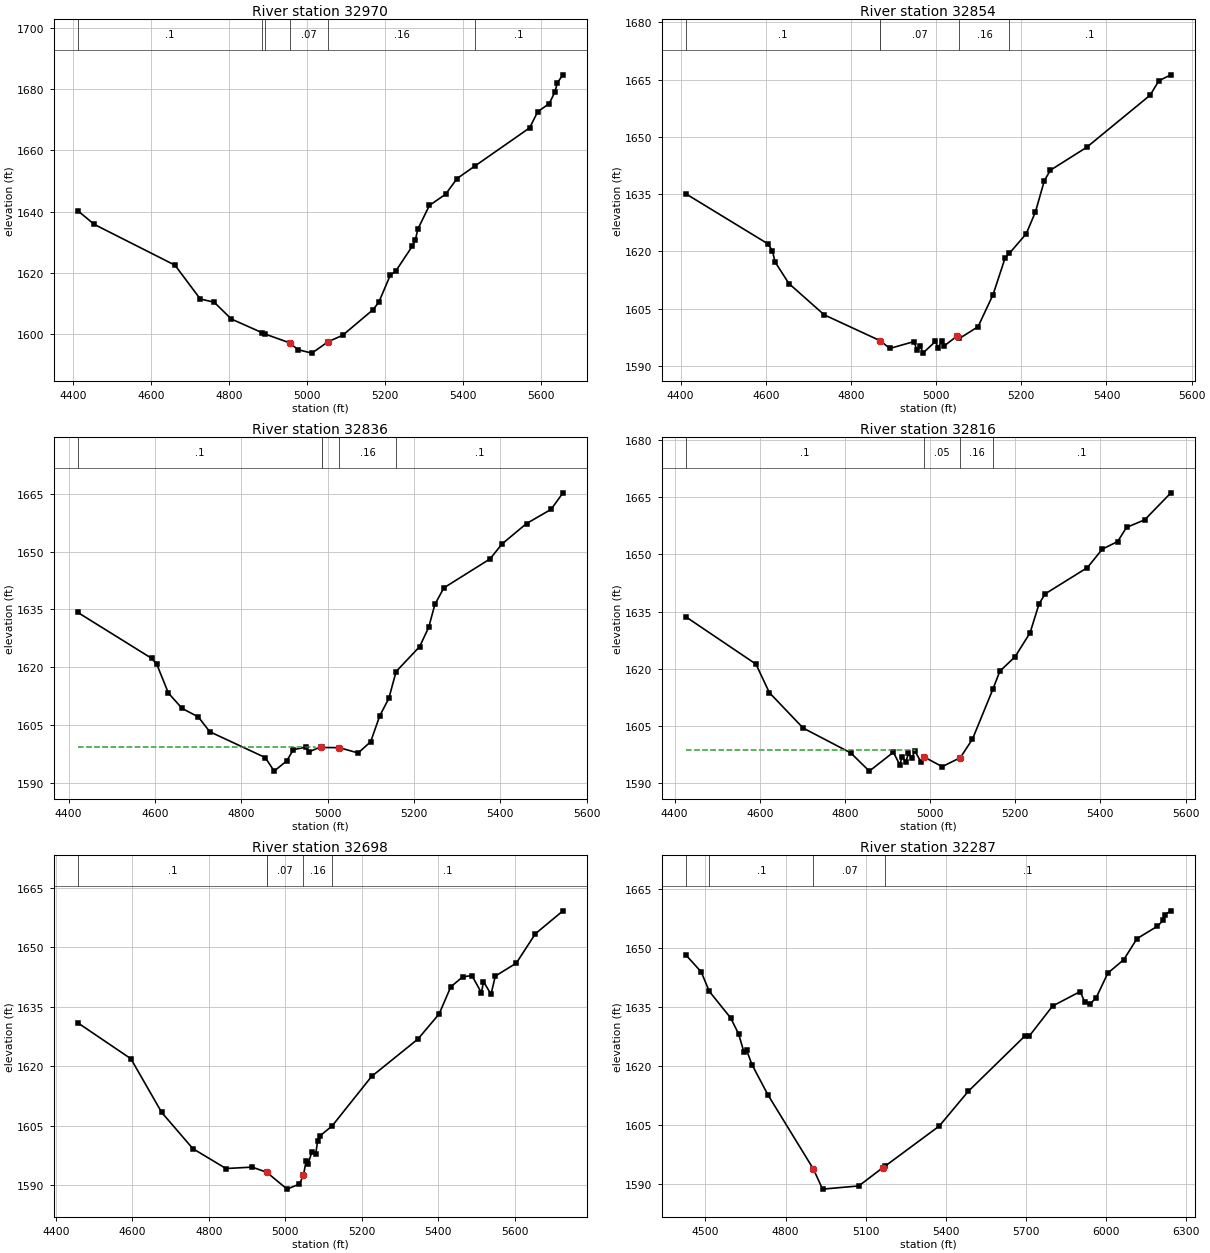
Type RM Length L Ch R = 1 ,32970   ,116,116,116
BEGIN DESCRIPTION:
MIDDLE FORK ROCKY CREEK 68.0
END DESCRIPTION:
XS GIS Cut Line= 2
      2863920.56     10029664.75      2864924.13     10028929.47
#Sta/Elev= 30
  4411.7 1640.28  4454.1 1635.83    4661 1622.51  4725.8 1611.48  4761.4 1610.44
  4805.3 1604.96  4885.1 1600.44  4892.4 1600.03  4954.6 1597.19  4976.7 1594.93
    5012 1593.82  5053.9 1597.57  5090.9 1599.64  5168.9 1608.01  5183.6 1610.43
  5212.9 1619.23  5227.3 1620.65  5269.3 1628.69  5276.9 1630.61  5283.9 1634.35
  5313.3 1642.02    5355 1645.69  5384.3 1650.81  5430.3 1654.91  5570.3 1667.34
  5591.2 1672.64  5620.5 1675.24  5635.2 1679.07  5641.4 1682.06  5655.8 1684.65
#Mann= 6 ,-1 , 0
  4411.7      .1       0  4885.1     .05       0  4892.4     .16       0
  4954.6     .07       0  5053.9     .16       0  5430.3      .1       0
Bank Sta=4954.6,5053.9
XS Rating Curve= 0 ,0
Exp/Cntr=0.3,0.1

Type RM Length L Ch R = 1 ,32854   ,18,18,18
BEGIN DESCRIPTION:
MIDDLE FORK ROCKY CREEK 67.0
END DESCRIPTION:
XS GIS Cut Line= 4
      2863964.11     10029641.26      2864275.66     10029544.45
      2864582.74     10029316.58      2864903.67      10029029.4
#Sta/Elev= 30
    4412 1635.09  4605.1 1621.96  4615.5 1620.11  4621.7 1617.22  4654.3 1611.57
  4737.1 1603.38  4868.9 1596.58  4891.2 1594.58  4948.2 1596.38  4954.4 1594.18
  4962.8 1595.24  4968.8 1593.35  4998.3 1596.41  5004.5 1594.72  5012.9 1596.48
  5019.1 1595.26  5048.4 1597.76  5054.6 1597.19  5098.4 1600.27  5133.7  1608.7
  5162.1 1618.33  5172.2 1619.52  5211.5 1624.61  5233.2 1630.35  5254.1 1638.54
  5268.3 1641.26  5353.5 1647.26  5502.3 1660.89  5523.2 1664.71  5551.3 1666.24
#Mann= 5 ,-1 , 0
    4412      .1       0  4868.9     .05       0  4868.9     .07       0
  5054.6     .16       0  5172.2      .1       0
Bank Sta=4868.9,5048.4
XS Rating Curve= 0 ,0
Exp/Cntr=0.3,0.1

Type RM Length L Ch R = 1 ,32836   ,20,20,20
BEGIN DESCRIPTION:
Mapping XS 2f434942
END DESCRIPTION:
XS GIS Cut Line= 4
      2863985.53     10029654.05      2864290.23     10029555.09
      2864626.16     10029307.69      2864914.33     10029050.68
#Sta/Elev= 30
  4421.3 1634.23  4592.6 1622.29  4604.4 1620.72  4631.1 1613.29    4663 1609.29
  4700.3  1607.1    4727 1603.24  4855.5 1596.53  4876.1 1593.01  4905.6 1595.71
  4920.3 1598.58  4949.6 1599.25  4955.8 1597.97  4985.1 1599.37  4987.4 1599.15
  5026.8 1599.11  5070.7 1597.72  5099.6 1600.65  5120.8 1607.41  5141.7  1611.9
  5158.5 1618.87  5213.1 1625.36    5234 1630.35  5248.3  1636.3  5269.2 1640.62
  5376.2 1648.14  5403.8 1652.01  5460.6 1657.32  5517.5    1661    5545  1665.3
#Mann= 5 ,-1 , 0
  4421.3      .1       0  4987.4     .07       0  4987.4     .05       0
  5026.8     .16       0  5158.5      .1       0
#XS Ineff= 2 , 0
         4971.62 1599.21
Permanent Ineff=
       T       T
Bank Sta=4985.1,5026.8
XS Rating Curve= 0 ,0
Exp/Cntr=0.3,0.1

Type RM Length L Ch R = 1 ,32816   ,118,118,118
BEGIN DESCRIPTION:
MIDDLE FORK ROCKY CREEK 66.0
END DESCRIPTION:
XS GIS Cut Line= 4
        2864001.     10029660.79      2864312.55     10029563.98
      2864619.63     10029336.11      2864940.72     10029048.79
#Sta/Elev= 30
  4426.2 1633.62  4591.1 1621.19  4622.5 1613.72  4701.9 1604.42  4813.7  1597.9
  4857.3 1593.12  4913.9 1598.08  4928.5 1594.83  4934.7 1596.88  4943.1 1595.53
  4949.3 1597.77  4957.7  1596.6  4963.9 1598.47  4978.6 1595.53  4984.8  1596.9
  5028.6  1594.3  5071.1 1596.66  5099.6 1601.52    5148 1614.74  5163.9 1619.34
  5199.8 1623.15  5234.9 1629.42  5255.8 1636.95    5270 1639.61  5369.5 1646.52
  5404.6 1651.37  5440.5 1653.36  5461.4 1657.06  5504.1 1659.06  5565.7 1666.14
#Mann= 4 ,-1 , 0
  4426.2      .1       0  4984.8     .05       0  5071.1     .16       0
    5148      .1       0
#XS Ineff= 2 , 0
         4963.65  1598.6
Permanent Ineff=
       T       T
Bank Sta=4984.8,5071.1
XS Rating Curve= 0 ,0
Exp/Cntr=0.3,0.1

Type RM Length L Ch R = 1 ,32698   ,411,411,411
BEGIN DESCRIPTION:
MIDDLE FORK ROCKY CREEK 65.0
END DESCRIPTION:
XS GIS Cut Line= 3
      2864029.27     10029699.84       2864374.3     10029591.34
      2865224.27     10029274.77
#Sta/Elev= 30
  4457.1 1630.96    4596 1621.88  4676.4 1608.34  4757.9 1599.19  4844.6 1594.16
  4913.1 1594.52  4951.3 1593.21  5004.4 1588.96  5036.7 1590.25  5047.3 1592.54
  5054.1 1596.07  5059.4 1595.37  5068.7 1598.22  5079.1 1597.77  5084.4 1601.19
    5090 1602.38    5122  1604.9  5225.4 1617.42  5346.7 1626.87    5402  1633.2
  5432.4 1640.04  5463.5 1642.56  5487.7  1642.9  5512.7 1638.53    5518 1641.38
  5537.7 1638.16  5548.9 1642.76  5603.7 1646.02  5653.7 1653.45  5725.8 1659.24
#Mann= 5 ,-1 , 0
  4457.1      .1       0  4951.3     .05       0  4951.3     .07       0
  5047.3     .16       0    5122      .1       0
Bank Sta=4951.3,5047.3
XS Rating Curve= 0 ,0
Exp/Cntr=0.3,0.1

Type RM Length L Ch R = 1 ,32287   ,126,126,126
BEGIN DESCRIPTION:
MIDDLE FORK ROCKY CREEK 64.0
END DESCRIPTION:
XS GIS Cut Line= 3
      2863910.65     10029913.34      2864855.24     10029923.28
       2865620.9     10029505.65
#Sta/Elev= 30
  4426.4 1648.28  4484.2 1643.95  4514.2 1639.02  4594.2 1632.25  4624.2 1628.18
  4644.2 1623.53  4654.2    1624  4674.2 1620.36  4734.2 1612.62  4904.2 1593.77
  4938.7 1588.64  5074.3 1589.45  5164.3  1594.1  5174.3 1594.57  5375.7  1604.7
  5483.9 1613.51  5696.6 1627.64  5712.7 1627.61    5800 1635.25  5903.5 1638.94
  5919.6  1636.4  5941.5 1635.85  5963.3 1637.38    6007 1643.63  6066.8 1647.07
  6116.1 1652.41  6192.1 1655.55  6213.9 1657.05  6219.6 1658.51  6243.2 1659.49
#Mann= 4 ,-1 , 0
  4426.4      .1       0  4514.2      .1       0  4904.2     .07       0
  5174.3      .1       0
Bank Sta=4904.2,5164.3
XS Rating Curve= 0 ,0
Exp/Cntr=0.3,0.1

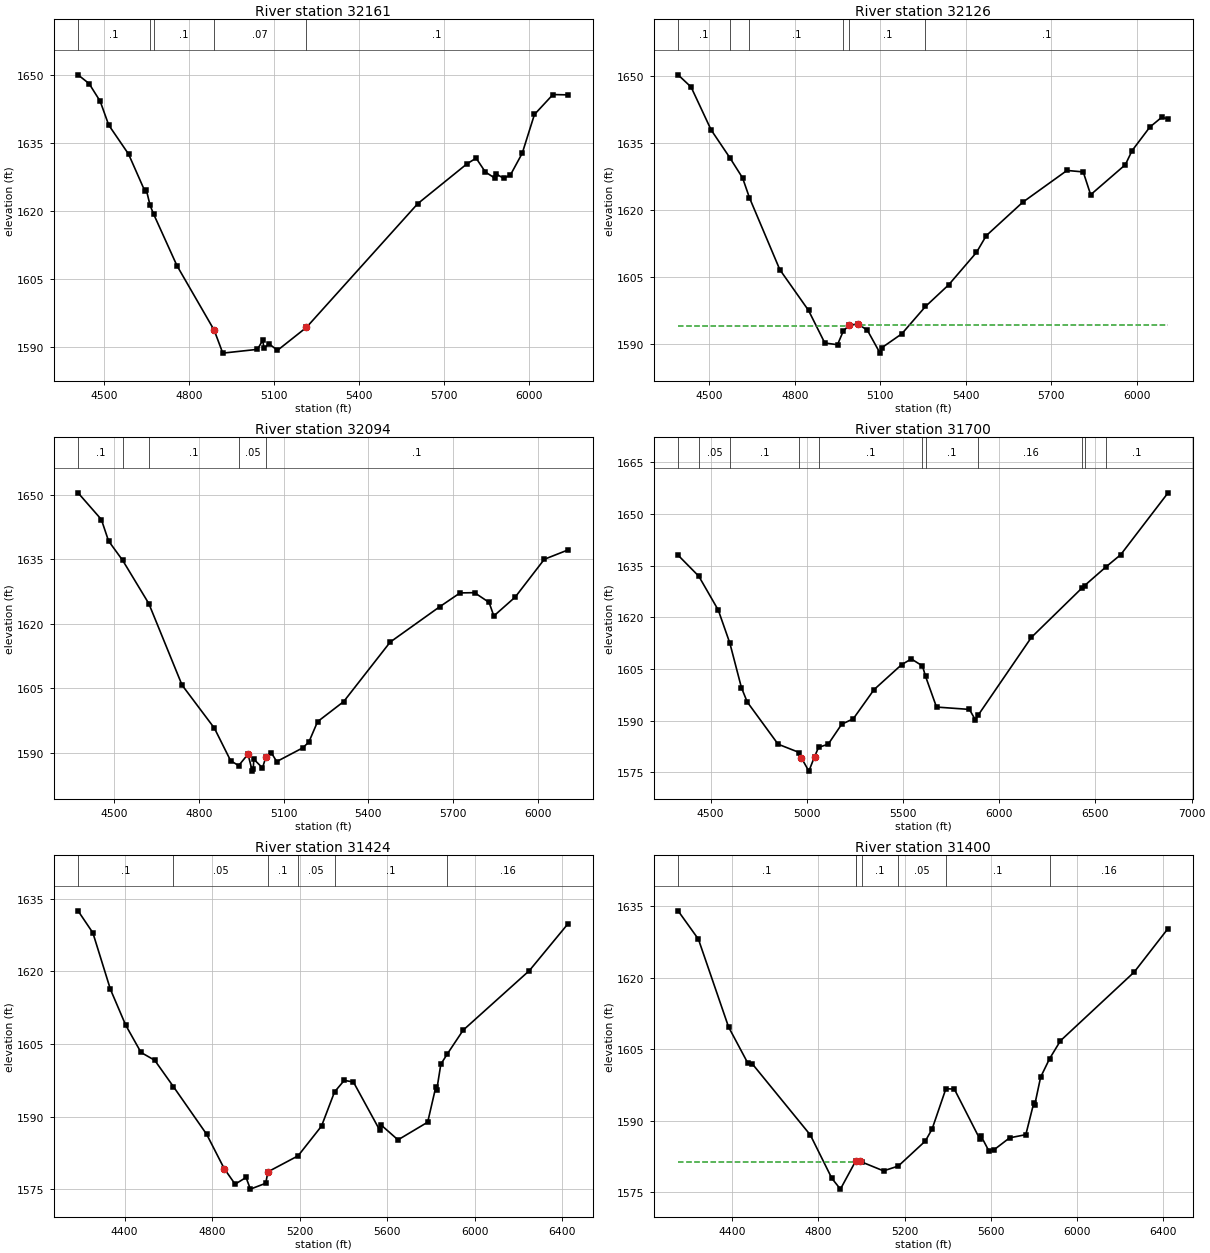
Type RM Length L Ch R = 1 ,32161   ,35,35,35
BEGIN DESCRIPTION:
MIDDLE FORK ROCKY CREEK 63.0
END DESCRIPTION:
XS GIS Cut Line= 4
      2863920.69      10030035.3      2864324.72     10030075.15
      2864763.12     10029992.12      2865602.58      10029732.4
#Sta/Elev= 30
  4408.6 1649.93  4447.6    1648  4486.8 1644.12  4516.9 1638.89  4587.2 1632.48
  4644.9 1624.32  4649.9 1624.63    4663 1621.23  4675.6  1619.3  4758.1 1607.95
  4889.6 1593.76  4919.9 1588.72  5042.3 1589.55  5060.8 1591.51  5065.9 1589.79
    5083 1590.79  5113.1 1589.33  5215.3 1594.37  5608.6 1621.59  5782.1 1630.33
  5814.8 1631.61  5847.4 1628.56    5880 1627.25  5885.2 1628.15  5912.6 1627.15
  5936.3 1627.93  5977.8 1632.69  6020.9 1641.21  6086.2 1645.59  6139.5 1645.52
#Mann= 5 ,-1 , 0
  4408.6      .1       0    4663     .05       0  4675.6      .1       0
  4889.6     .07       0  5215.3      .1       0
Bank Sta=4889.6,5215.3
XS Rating Curve= 0 ,0
Exp/Cntr=0.3,0.1

Type RM Length L Ch R = 1 ,32126   ,32,32,32
BEGIN DESCRIPTION:
Mapping XS c0ba4ff1
END DESCRIPTION:
XS GIS Cut Line= 5
      2863923.04     10030070.71      2864232.94     10030099.36
      2864347.52     10030107.17      2864779.81     10030016.02
      2865600.14     10029789.46
#Sta/Elev= 30
  4390.6 1650.27  4436.2 1647.54  4506.5 1637.93  4571.9 1631.72    4617 1627.16
    4641 1622.72  4747.5 1606.61  4848.3 1597.47  4905.3 1590.17  4949.9 1589.79
  4969.8 1592.79  4990.6 1594.19    5022  1594.4  5054.6 1593.04  5099.1  1587.9
  5104.4 1589.07  5175.3 1592.22  5258.5 1598.35  5340.1 1603.22  5437.4 1610.47
  5471.7 1614.22  5599.4  1621.7    5755 1628.84  5811.9 1628.51    5838  1623.4
  5959.7 1630.13  5983.3 1633.28  6045.5 1638.55    6087 1640.74  6109.5 1640.41
#Mann= 6 ,-1 , 0
  4390.6      .1       0  4571.9     .05       0    4641      .1       0
  4969.8     .05       0  4990.6      .1       0  5258.5      .1       0
#XS Ineff= 2 , 0
         4980.08 1593.97 5036.51         1594.13
Permanent Ineff=
       T       T
Bank Sta=4990.6,5022
XS Rating Curve= 0 ,0
Exp/Cntr=0.3,0.1

Type RM Length L Ch R = 1 ,32094   ,394,394,394
BEGIN DESCRIPTION:
MIDDLE FORK ROCKY CREEK 62.0
END DESCRIPTION:
XS GIS Cut Line= 4
      2863920.57     10030115.42      2864378.64     10030133.87
      2864751.91     10030049.24      2865619.95     10029836.57
#Sta/Elev= 30
  4372.4 1650.46    4455 1644.26  4480.4 1639.28  4530.6 1634.75  4623.1 1624.71
  4740.6 1605.79  4855.2 1595.77  4912.7 1588.21  4941.1 1587.07  4974.2 1589.72
  4989.4 1585.79  4992.7 1586.29  4994.8 1588.56  5025.5 1586.54  5037.9 1589.16
  5056.3 1590.11  5075.9 1588.01  5167.3 1591.17  5189.6 1592.53  5220.6 1597.29
    5313 1601.95  5477.7 1615.78  5652.8 1623.98    5725  1627.2  5776.3 1627.26
  5827.8    1625  5844.6 1621.84  5920.5 1626.25  6023.4 1635.02  6107.3 1637.19
#Mann= 5 ,-1 , 0
  4372.4      .1       0  4530.6     .05       0  4623.1      .1       0
  4941.1     .05       0  5037.9      .1       0
Bank Sta=4974.2,5037.9
XS Rating Curve= 0 ,0
Exp/Cntr=0.3,0.1

Type RM Length L Ch R = 1 ,31700   ,276,276,276
BEGIN DESCRIPTION:
MIDDLE FORK ROCKY CREEK 61.0
END DESCRIPTION:
XS GIS Cut Line= 3
      2864029.95     10030410.51      2864944.73     10030470.17
      2866564.46      10030291.3
#Sta/Elev= 30
    4331 1637.99  4438.6  1631.9    4540 1622.05  4600.1 1612.46  4660.2 1599.57
  4690.3  1595.4  4850.6 1583.15  4960.8 1580.73  4970.9 1579.26  5010.7 1575.33
  5040.1 1579.51  5061.1 1582.22  5111.2 1583.15  5181.3 1588.94  5241.4 1590.51
  5349.5 1598.99  5492.9 1606.24  5543.2 1607.88    5601 1605.86    5617 1602.84
    5674 1593.92  5845.1 1593.24  5875.2 1590.26  5891.9 1591.68  6166.9 1614.13
  6432.5 1628.61  6443.7 1629.18  6556.2 1634.67  6631.1 1638.13  6877.3 1656.09
#Mann= 11 ,-1 , 0
    4331      .1       0  4438.6     .05       0  4600.1      .1       0
  4960.8     .05       0  5061.1      .1       0    5601     .05       0
    5617      .1       0  5891.9     .16       0  6432.5      .1       0
  6443.7     .16       0  6556.2      .1       0
Bank Sta=4970.9,5040.1
XS Rating Curve= 0 ,0
Exp/Cntr=0.3,0.1

Type RM Length L Ch R = 1 ,31424   ,24,24,24
BEGIN DESCRIPTION:
MIDDLE FORK ROCKY CREEK 60.0
END DESCRIPTION:
XS GIS Cut Line= 4
      2863920.64     10030747.52      2864623.98     10030729.75
      2864855.23     10030724.19      2866123.64     10030416.81
#Sta/Elev= 30
    4187 1632.46  4254.8 1627.92  4334.9 1616.28  4404.9 1608.88  4474.9 1603.25
  4537.5 1601.64    4623  1596.2    4775 1586.37    4855 1579.31  4905.1 1576.08
  4955.1 1577.47  4974.8 1575.06  5045.1 1576.27  5055.1 1578.63    5193 1581.93
  5300.1 1588.06  5359.5  1595.1    5404 1597.49  5445.8 1597.16  5566.1 1587.23
  5571.2 1588.34  5649.7 1585.22  5785.4 1588.87  5822.1 1596.04  5827.2  1595.6
  5845.5 1600.82  5874.9 1602.92  5947.5 1607.84  6250.5 1620.14    6427  1629.8
#Mann= 6 ,-1 , 0
    4187      .1       0    4623     .05       0  5055.1      .1       0
    5193     .05       0  5359.5      .1       0  5874.9     .16       0
Bank Sta=4855,5055.1
XS Rating Curve= 0 ,0
Exp/Cntr=0.3,0.1

Type RM Length L Ch R = 1 ,31400   ,24,24,24
BEGIN DESCRIPTION:
Mapping XS ae4d236a
END DESCRIPTION:
XS GIS Cut Line= 4
      2863884.02     10030773.84      2864170.44     10030763.42
      2864873.56     10030747.79      2866123.54     10030440.51
#Sta/Elev= 30
  4147.5 1634.06    4242 1628.11  4382.1 1609.69  4472.1 1602.06  4492.2 1601.96
  4762.2 1587.02  4862.2 1577.92    4902 1575.66  4972.3 1581.51  4992.3 1581.52
  5002.3 1581.33  5102.3 1579.49  5170.9  1580.5  5296.4 1585.74  5327.8 1588.24
  5392.1 1596.72  5431.3 1596.66  5550.8 1586.09  5555.9 1586.77  5592.3 1583.64
  5616.2 1583.93  5688.2 1586.42  5763.6 1587.09    5800 1593.65  5805.2 1593.39
  5832.4 1599.16  5874.3 1603.05  5924.7  1606.8  6267.3 1621.21  6424.6 1630.35
#Mann= 7 ,-1 , 0
  4147.5      .1       0  4972.3     .05       0  4972.3     .05       0
  5002.3      .1       0  5170.9     .05       0  5392.1      .1       0
  5874.3     .16       0
#XS Ineff= 2 , 0
         4969.48 1581.39  5002.7          1581.3
Permanent Ineff=
       T       T
Bank Sta=4972.3,4992.3
XS Rating Curve= 0 ,0
Exp/Cntr=0.3,0.1

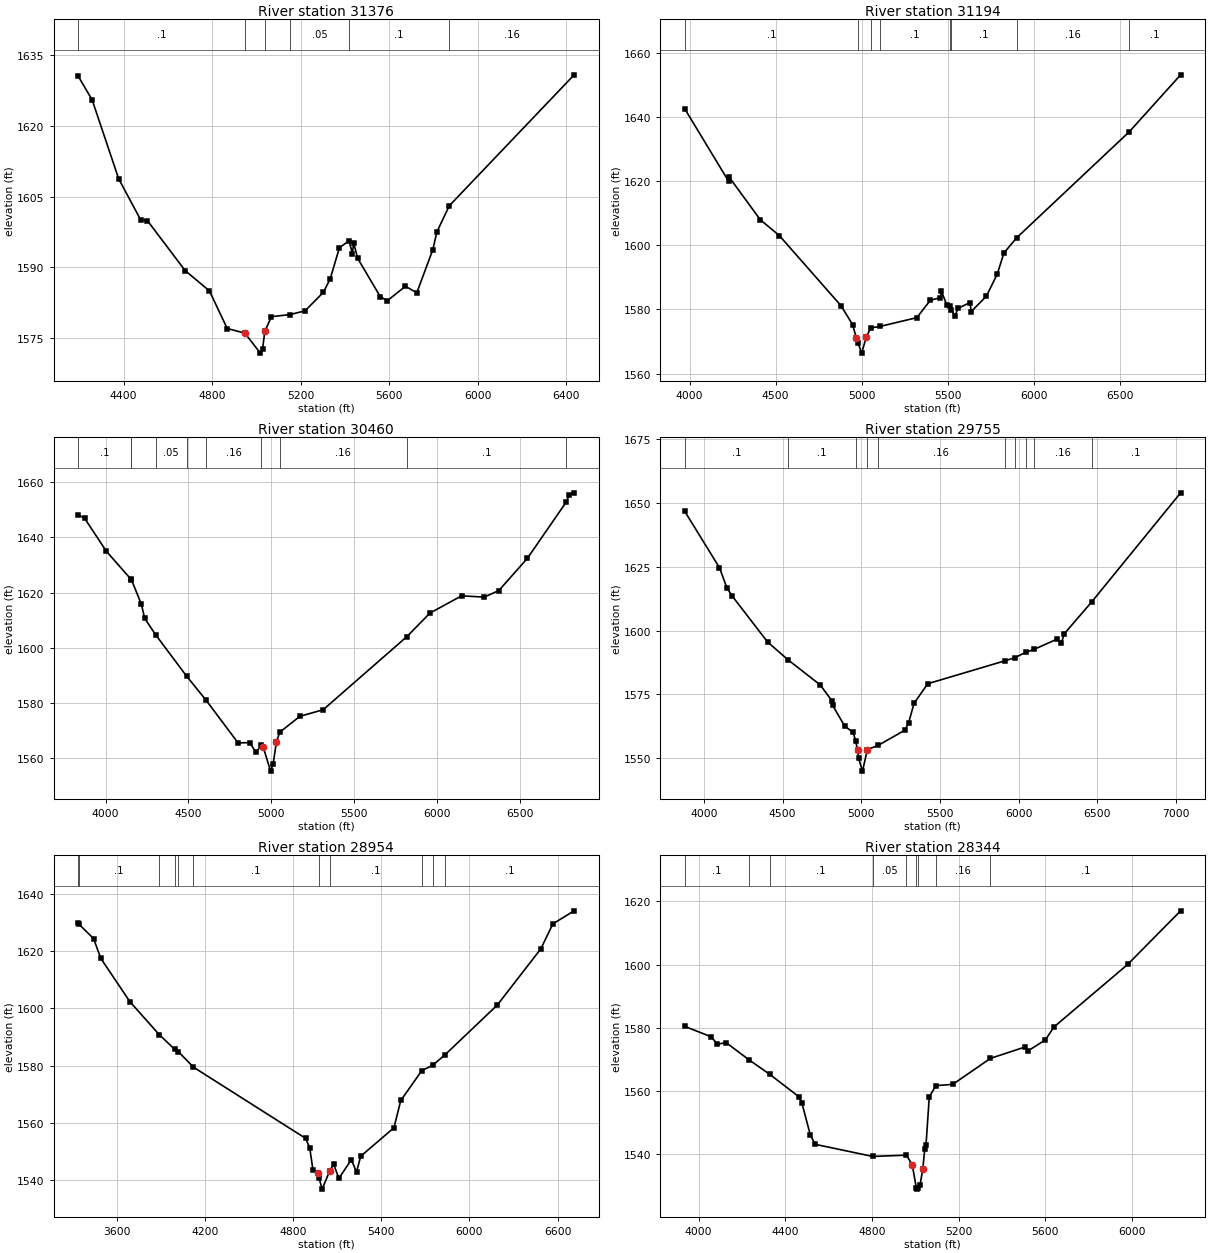
Type RM Length L Ch R = 1 ,31376   ,182,182,182
BEGIN DESCRIPTION:
MIDDLE FORK ROCKY CREEK 59.0
END DESCRIPTION:
XS GIS Cut Line= 4
      2863936.23     10030794.18      2864639.61     10030776.41
      2864870.86     10030770.85      2866139.32     10030463.46
#Sta/Elev= 30
  4195.4 1630.55  4257.7 1625.58  4377.7  1608.8  4477.7 1600.03  4507.7 1599.91
  4677.8 1589.32  4787.8    1585  4867.9 1577.01  4947.9 1576.03  5017.6 1571.78
  5027.9 1572.75  5037.9 1576.39  5067.9 1579.52  5151.5 1579.97  5219.8 1580.76
  5302.8 1584.71  5333.6 1587.59  5374.8 1594.15  5418.1 1595.64    5434 1592.94
  5439.1 1595.26  5457.1 1591.94  5559.4 1583.79  5590.9  1582.9  5673.2 1585.97
  5724.6  1584.6  5796.7 1593.72  5815.4 1597.53  5871.4 1603.08  6435.5 1630.89
#Mann= 6 ,-1 , 0
  4195.4      .1       0  4947.9     .05       0  5037.9      .1       0
  5151.5     .05       0  5418.1      .1       0  5871.4     .16       0
Bank Sta=4947.9,5037.9
XS Rating Curve= 0 ,0
Exp/Cntr=0.3,0.1

Type RM Length L Ch R = 1 ,31194   ,734,734,734
BEGIN DESCRIPTION:
MIDDLE FORK ROCKY CREEK 58.0
END DESCRIPTION:
XS GIS Cut Line= 4
      2863721.72     10030927.57      2864556.94     10030997.17
      2865123.71     10030838.07      2866504.65       10030391.
#Sta/Elev= 30
  3972.6 1642.55  4226.4 1620.01  4231.4 1621.17  4410.9 1607.96  4521.2 1603.04
  4879.4 1581.15  4947.3 1575.21  4968.1 1571.08  4978.5 1569.53    4999 1566.36
  5026.1 1571.28  5051.2 1574.25  5104.4 1574.67  5319.5 1577.43    5398 1582.84
  5456.9 1583.69  5462.2  1585.7  5494.2 1581.29    5510  1581.2  5520.2 1579.81
    5541 1577.93  5558.2 1580.29  5627.5 1582.14  5635.6 1579.34  5723.5 1584.13
  5787.5 1591.16  5824.8 1597.58  5898.2 1602.29  6552.8 1635.41  6850.9 1653.17
#Mann= 8 ,-1 , 0
  3972.6      .1       0  4978.5     .05       0  5051.2     .05       0
  5104.4      .1       0    5510     .05       0  5520.2      .1       0
  5898.2     .16       0  6552.8      .1       0
Bank Sta=4968.1,5026.1
XS Rating Curve= 0 ,0
Exp/Cntr=0.3,0.1

Type RM Length L Ch R = 1 ,30460   ,705,705,705
BEGIN DESCRIPTION:
MIDDLE FORK ROCKY CREEK 57.0
END DESCRIPTION:
XS GIS Cut Line= 2
      2863940.49     10031603.71      2866913.49      10031255.7
#Sta/Elev= 30
  3835.8 1648.21  3873.8 1646.92  4004.9    1635  4153.2 1624.88  4156.1 1624.73
  4216.4 1615.81  4236.5 1610.66  4304.3  1604.6  4489.8 1589.74  4607.1 1581.04
  4800.3 1565.59  4870.8 1565.69  4908.4 1562.13  4941.3 1564.77  4951.3  1564.2
  4996.4 1555.37  5011.8 1557.99  5031.9 1566.03    5052 1569.47  5173.3 1575.22
  5313.8  1577.6    5819 1604.07  5958.2 1612.59  6149.5 1618.85  6286.2 1618.39
  6374.5 1620.77  6546.1 1632.38    6780  1652.7  6800.9 1655.51  6829.1 1656.15
#Mann= 10 ,-1 , 0
  3835.8      .1       0  4153.2     .05       0  4156.1      .1       0
  4304.3     .05       0  4489.8      .1       0  4607.1     .16       0
  4941.3     .07       0    5052     .16       0    5819      .1       0
    6780     .05       0
Bank Sta=4951.3,5031.9
XS Rating Curve= 0 ,0
Exp/Cntr=0.3,0.1

Type RM Length L Ch R = 1 ,29755   ,801,801,801
BEGIN DESCRIPTION:
MIDDLE FORK ROCKY CREEK 55.0
END DESCRIPTION:
XS GIS Cut Line= 4
      2864019.97     10031752.85      2864885.07     10032120.77
      2865451.84     10031971.62      2866943.38     10031325.28
#Sta/Elev= 30
  3877.8  1646.7  4098.1 1624.66  4145.4 1616.74  4180.4 1613.42  4403.5 1595.55
  4532.6 1588.59    4738  1578.7  4814.4 1572.36    4817 1570.71  4893.8 1562.54
  4947.2 1560.09  4964.6 1556.57  4976.5 1553.01  4982.4  1549.9  5007.3 1544.87
  5038.5 1553.34  5106.8 1554.96  5276.4 1560.92  5299.8 1563.67    5335 1571.46
  5422.1 1579.14  5910.4 1588.09  5975.1 1589.34  6043.6 1591.42  6096.2 1592.57
    6243 1596.61  6272.2 1595.28    6290 1598.73  6463.5 1611.17  7029.5    1654
#Mann= 10 ,-1 , 0
  3877.8      .1       0  4532.6      .1       0  4964.6     .07       0
  5038.5      .1       0  5106.8     .16       0  5910.4      .1       0
  5975.1     .16       0  6043.6      .1       0  6096.2     .16       0
  6463.5      .1       0
Bank Sta=4976.5,5038.5
XS Rating Curve= 0 ,0
Exp/Cntr=0.3,0.1

Type RM Length L Ch R = 1 ,28954   ,610,610,610
BEGIN DESCRIPTION:
MIDDLE FORK ROCKY CREEK 53.0
END DESCRIPTION:
XS GIS Cut Line= 3
      2864268.58     10033920.51      2865610.93     10032538.39
      2866973.22     10032051.15
#Sta/Elev= 30
  3339.5 1629.71    3344 1629.33  3443.3 1624.34  3492.7 1617.39  3690.7  1602.3
  3889.2 1590.87  3995.8 1585.65  4019.8 1584.91  4122.1 1579.49  4885.8 1554.64
  4914.1 1551.29  4935.4 1543.74  4970.7 1542.53  4977.9 1540.64  4998.7 1536.92
  5048.6 1543.16  5076.9 1545.59  5112.2 1540.66    5197  1547.2  5232.3 1542.87
  5260.6 1548.39  5486.6 1558.32  5533.4 1567.85  5676.7 1578.28  5749.2  1580.1
    5836 1583.87  6189.3 1601.11  6486.4 1620.77  6568.1 1629.47    6713 1634.02
#Mann= 11 ,-1 , 0
  3339.5     .05       0    3344      .1       0  3889.2     .05       0
  3995.8      .1       0  4019.8     .05       0  4122.1      .1       0
  4977.9     .05       0  5048.6      .1       0  5676.7      .1       0
  5749.2     .16       0    5836      .1       0
Bank Sta=4970.7,5048.6
XS Rating Curve= 0 ,0
Exp/Cntr=0.3,0.1

Type RM Length L Ch R = 1 ,28344   ,262,262,262
BEGIN DESCRIPTION:
MIDDLE FORK ROCKY CREEK 52.0
END DESCRIPTION:
XS GIS Cut Line= 4
      2864944.74     10033532.72      2865869.46     10033085.27
      2866257.25     10032826.75      2867052.75     10032846.63
#Sta/Elev= 30
  3936.1 1580.42  4058.5 1577.12  4086.6 1574.76  4126.2 1575.32  4233.9 1569.78
  4327.7 1565.28  4462.4 1558.19  4476.2 1556.33  4515.8    1546  4538.4  1543.1
  4803.6 1539.27  4959.2 1539.68  4986.2 1536.64  5004.7 1529.43  5007.5 1528.93
  5010.7 1529.43  5022.3 1530.31  5034.8 1535.24  5043.8  1541.5  5049.8 1542.95
  5064.8 1558.14  5095.7 1561.69    5173 1562.07  5347.4 1570.31  5507.3 1573.91
  5520.7 1572.68  5600.7 1576.15  5640.7 1580.25  5980.8 1600.03  6225.2 1616.99
#Mann= 9 ,-1 , 0
  3936.1      .1       0  4233.9     .05       0  4327.7      .1       0
  4803.6     .05       0  4959.2      .1       0  5004.7     .07       0
  5010.7      .1       0  5095.7     .16       0  5347.4      .1       0
Bank Sta=4986.2,5034.8
XS Rating Curve= 0 ,0
Exp/Cntr=0.3,0.1

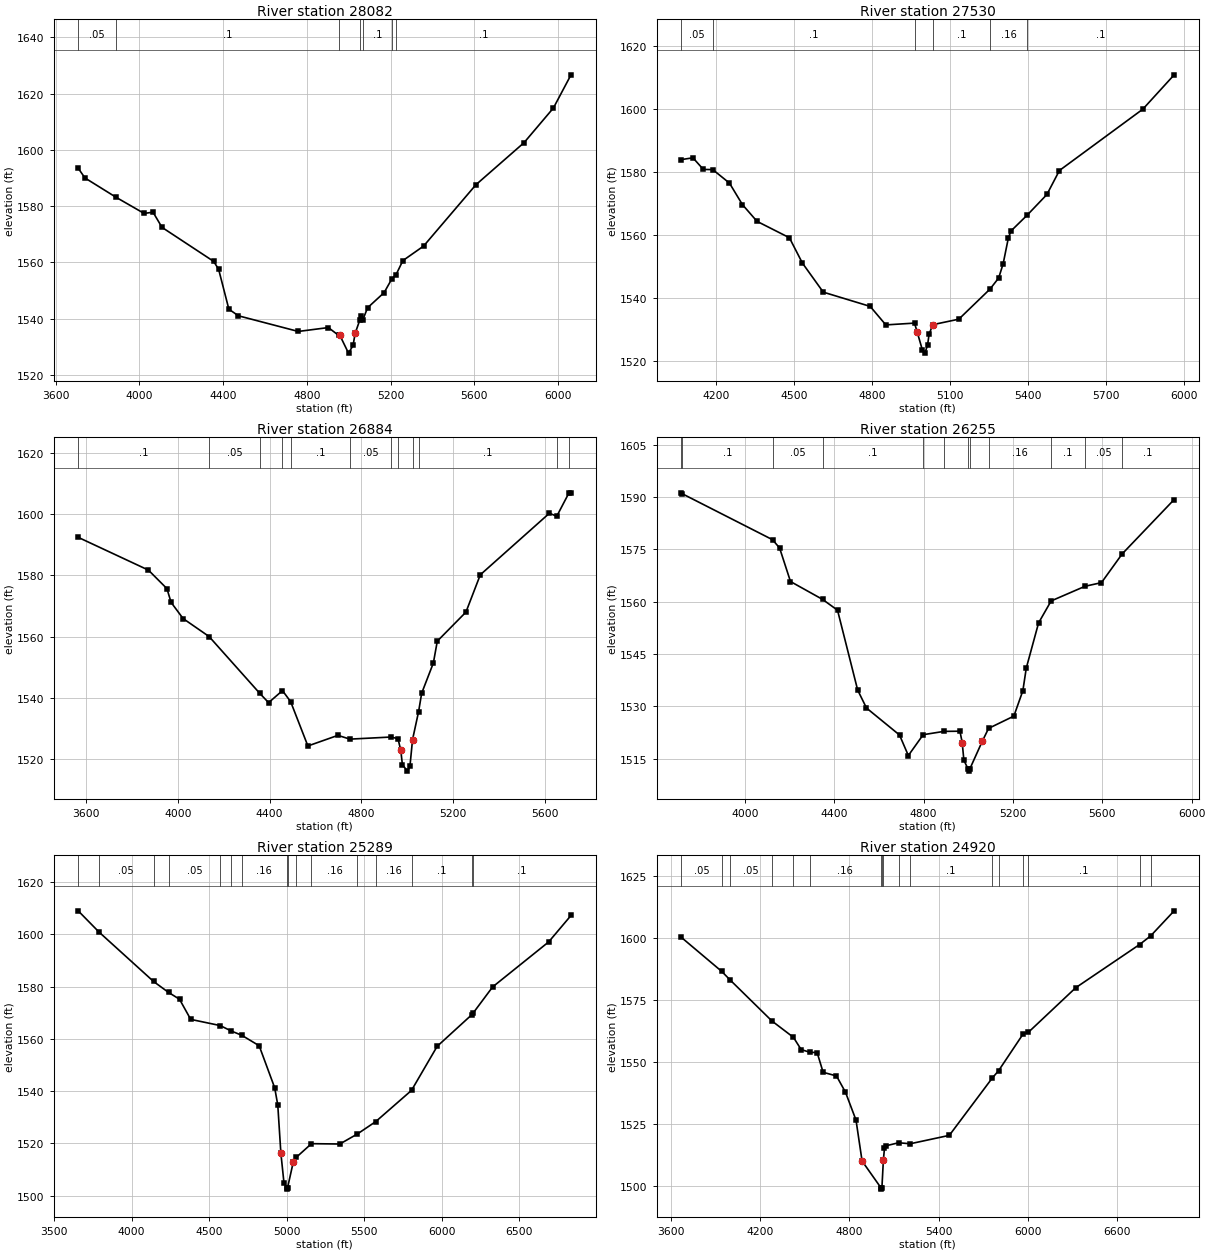
Type RM Length L Ch R = 1 ,28082   ,552,552,552
BEGIN DESCRIPTION:
MIDDLE FORK ROCKY CREEK 51.0
END DESCRIPTION:
XS GIS Cut Line= 3
      2864815.44     10033761.43      2866267.19     10033194.65
      2867062.63     10033194.65
#Sta/Elev= 30
  3707.9 1593.47  3740.4    1590  3888.8 1583.14  4022.8 1577.41  4065.4 1577.84
  4108.3 1572.45  4355.2 1560.36  4378.7 1557.56  4427.6 1543.39  4473.3 1541.04
    4759 1535.48  4902.9 1536.86  4951.9 1534.08  4957.2 1534.18  4999.1 1527.78
  5020.8 1530.51  5030.7 1534.77    5053 1539.53  5060.5 1541.14  5066.6 1539.49
  5090.4 1543.91  5169.2 1549.28  5206.6 1554.22  5225.4 1555.54  5258.8 1560.65
  5357.6  1565.8  5607.6 1587.59  5837.6 1602.55  5977.6 1614.84  6061.8 1626.64
#Mann= 7 ,-1 , 0
  3707.9     .05       0  3888.8      .1       0  4951.9     .05       0
    5053     .05       0  5066.6      .1       0  5206.6     .16       0
  5225.4      .1       0
Bank Sta=4957.2,5030.7
XS Rating Curve= 0 ,0
Exp/Cntr=0.3,0.1

Type RM Length L Ch R = 1 ,27530   ,646,646,646
BEGIN DESCRIPTION:
MIDDLE FORK ROCKY CREEK 50.0
END DESCRIPTION:
XS GIS Cut Line= 3
      2865074.03      10033870.8      2866386.51     10033771.36
      2866923.42     10033552.63
#Sta/Elev= 30
  4065.3    1584  4109.9 1584.57    4150 1580.87  4186.1 1580.82  4250.3 1576.54
  4300.4 1569.68  4356.5 1564.37  4480.9 1559.17  4531.1  1551.1  4611.3 1541.87
  4791.8 1537.34    4852 1531.46  4962.3 1532.03  4972.3 1529.31  4992.4 1523.54
  5002.2 1522.49  5012.4 1524.96  5018.4 1528.48  5032.5 1531.53  5132.8 1533.28
  5253.1 1542.87  5286.1 1546.37  5303.3 1550.88  5323.3 1559.05  5333.4 1561.31
  5395.5 1566.32  5471.7 1572.91  5519.8 1580.53  5840.8 1600.03  5961.3 1610.94
#Mann= 6 ,-1 , 0
  4065.3     .05       0  4186.1      .1       0  4962.3     .07       0
  5032.5      .1       0  5253.1     .16       0  5395.5      .1       0
Bank Sta=4972.3,5032.5
XS Rating Curve= 0 ,0
Exp/Cntr=0.3,0.1

Type RM Length L Ch R = 1 ,26884   ,629,629,629
BEGIN DESCRIPTION:
MIDDLE FORK ROCKY CREEK 49.0
END DESCRIPTION:
XS GIS Cut Line= 3
      2864984.47     10034139.27      2866287.08     10034298.36
      2867042.79     10033940.39
#Sta/Elev= 30
  3565.2 1592.44  3871.5 1581.74  3952.1  1575.7  3970.2 1571.22  4022.6 1565.94
  4135.8 1560.08  4356.9 1541.53  4395.3  1538.5  4455.8 1542.43  4491.4 1538.83
  4566.6 1524.37  4697.6 1527.83  4749.9  1526.6    4928 1527.28  4959.4 1526.76
  4971.6 1522.93  4978.6 1518.28  5000.5 1516.16  5011.5 1517.74  5022.9 1526.46
  5049.3  1535.6  5062.6 1541.56  5113.6 1551.44  5130.8 1558.57  5255.6 1568.04
  5318.3 1580.22  5619.5  1600.3  5651.6 1599.32  5704.8 1606.94  5713.7 1606.96
#Mann= 12 ,-1 , 0
  3565.2      .1       0  4135.8     .05       0  4356.9      .1       0
  4455.8     .05       0  4491.4      .1       0  4749.9     .05       0
    4928      .1       0  4959.4     .05       0  5022.9     .05       0
  5049.3      .1       0  5651.6     .05       0  5704.8      .1       0
Bank Sta=4971.6,5022.9
XS Rating Curve= 0 ,0
Exp/Cntr=0.3,0.1

Type RM Length L Ch R = 1 ,26255   ,966,966,966
BEGIN DESCRIPTION:
MIDDLE FORK ROCKY CREEK 47.0
END DESCRIPTION:
XS GIS Cut Line= 3
      2865014.33     10034318.25      2866167.76     10034636.44
      2867172.01     10034527.06
#Sta/Elev= 30
    3715 1591.22  3719.2 1590.95  4123.4 1577.77    4155 1575.39  4203.7 1565.78
  4347.2 1560.66  4414.3 1557.56  4504.5 1534.65    4544  1529.5  4691.9 1521.76
  4731.4 1515.87  4797.9 1521.85    4891  1522.8  4962.5 1522.85  4972.6 1519.58
  4980.1 1514.51  4999.8  1511.9  5002.5  1511.4  5005.8  1511.9  5063.1 1520.05
  5090.7 1523.66  5203.9 1527.18  5244.2 1534.47  5259.5 1540.96  5314.6 1553.91
  5370.7 1560.21  5522.7 1564.42  5596.2 1565.46  5688.9  1573.7  5921.7  1589.3
#Mann= 12 ,-1 , 0
    3715     .05       0  3719.2      .1       0  4123.4     .05       0
  4347.2      .1       0  4797.9     .16       0    4891      .1       0
  4999.8     .07       0  5005.8      .1       0  5090.7     .16       0
  5370.7      .1       0  5522.7     .05       0  5688.9      .1       0
Bank Sta=4972.6,5063.1
XS Rating Curve= 0 ,0
Exp/Cntr=0.3,0.1

Type RM Length L Ch R = 1 ,25289   ,369,369,369
BEGIN DESCRIPTION:
MIDDLE FORK ROCKY CREEK 45.0
END DESCRIPTION:
XS GIS Cut Line= 4
      2864556.94     10034457.46      2865561.22     10034974.51
      2866595.32     10034984.46        2867479.     10034488.01
#Sta/Elev= 30
  3655.3 1609.04  3789.5 1600.92  4141.3 1581.99  4237.8 1577.81  4308.6  1575.2
  4380.7 1567.49  4570.9 1565.12  4642.1 1563.04  4710.1  1561.4  4822.1  1557.4
  4922.1 1541.32  4942.1 1534.73  4962.1 1516.24  4982.1 1504.88  4999.1 1503.01
  5001.9 1502.51  5005.1 1503.01  5042.1  1512.9  5060.8 1514.65  5159.4 1519.91
  5342.1 1519.78  5455.3 1523.62  5573.7 1528.36  5804.3 1540.31  5969.8 1557.18
  6194.1 1569.33    6203 1570.01  6327.3 1579.91  6688.4 1597.13  6832.6 1607.26
#Mann= 16 ,-1 , 0
  3655.3     .16       0  3789.5     .05       0  4141.3      .1       0
  4237.8     .05       0  4570.9     .16       0  4642.1     .05       0
  4710.1     .16       0  4999.1     .07       0  5005.1     .16       0
  5060.8      .1       0  5159.4     .16       0  5455.3      .1       0
  5573.7     .16       0  5804.3      .1       0  6194.1     .05       0
    6203      .1       0
Bank Sta=4962.1,5042.1
XS Rating Curve= 0 ,0
Exp/Cntr=0.3,0.1

Type RM Length L Ch R = 1 ,24920   ,826,826,826
BEGIN DESCRIPTION:
MIDDLE FORK ROCKY CREEK 44.0
END DESCRIPTION:
XS GIS Cut Line= 4
      2864566.91     10035242.99      2865779.97     10035342.42
      2866963.23     10035133.61      2867569.15     10034468.09
#Sta/Elev= 30
    3668 1600.06  3940.2 1586.32  3993.8 1583.04  4277.9 1566.35  4422.8 1559.75
    4475  1554.8    4532 1553.77  4582.6 1553.57  4622.7 1545.66  4712.8 1544.18
  4773.3 1537.62  4844.3 1526.36  4885.1 1509.87  5012.6 1499.05  5015.4 1498.55
  5018.6 1499.05  5028.5  1510.3  5035.9    1515  5046.1 1516.02  5130.9 1517.25
  5209.2 1516.84  5472.6 1520.23  5760.7 1543.26  5804.3  1546.3  5969.3 1561.09
  6005.1 1561.79  6323.9 1579.76    6754 1597.18  6827.6 1600.61  6986.7 1610.76
#Mann= 17 ,-1 , 0
    3668     .05       0  3940.2      .1       0  3993.8     .05       0
  4277.9      .1       0  4422.8     .05       0    4532     .16       0
  5012.6     .07       0  5018.6     .16       0  5028.5      .1       0
  5130.9     .16       0  5209.2      .1       0  5760.7     .16       0
  5804.3      .1       0  5969.3     .05       0  6005.1      .1       0
    6754     .05       0  6827.6      .1       0
Bank Sta=4885.1,5028.5
XS Rating Curve= 0 ,0
Exp/Cntr=0.3,0.1