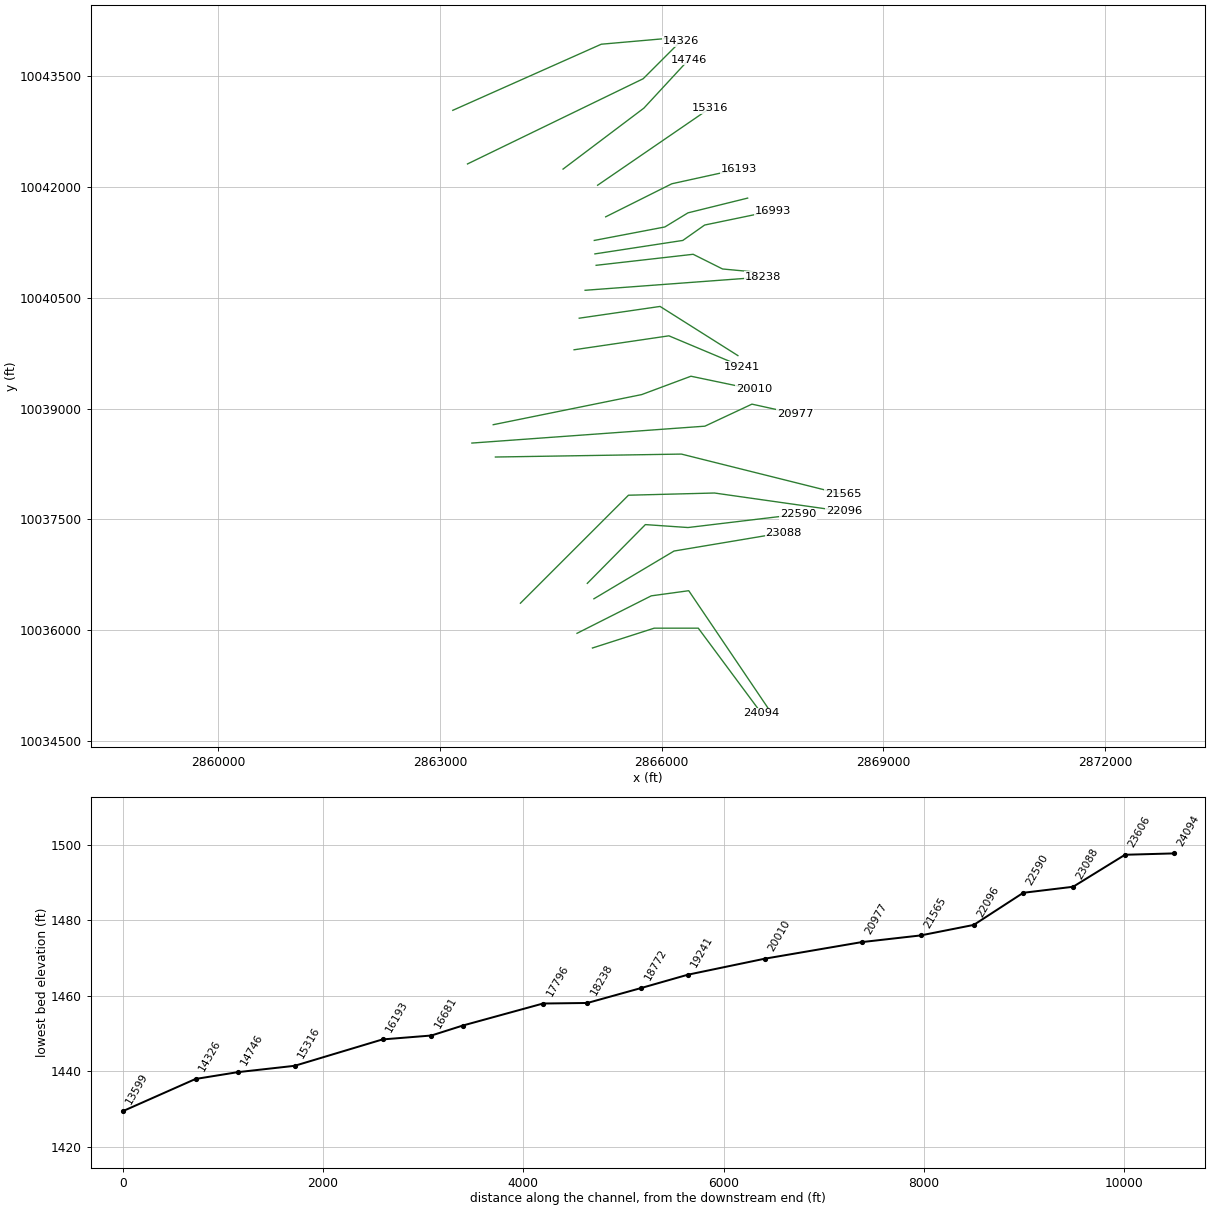
HEC-RAS study MIDDLE FORK ROCKY CREEK.prj: MIDDLE FORK ROCKY CREEK Base Level Engineering

--- MIDDLE FORK ROCKY CREEK.g01 (geometry) --- (continued)

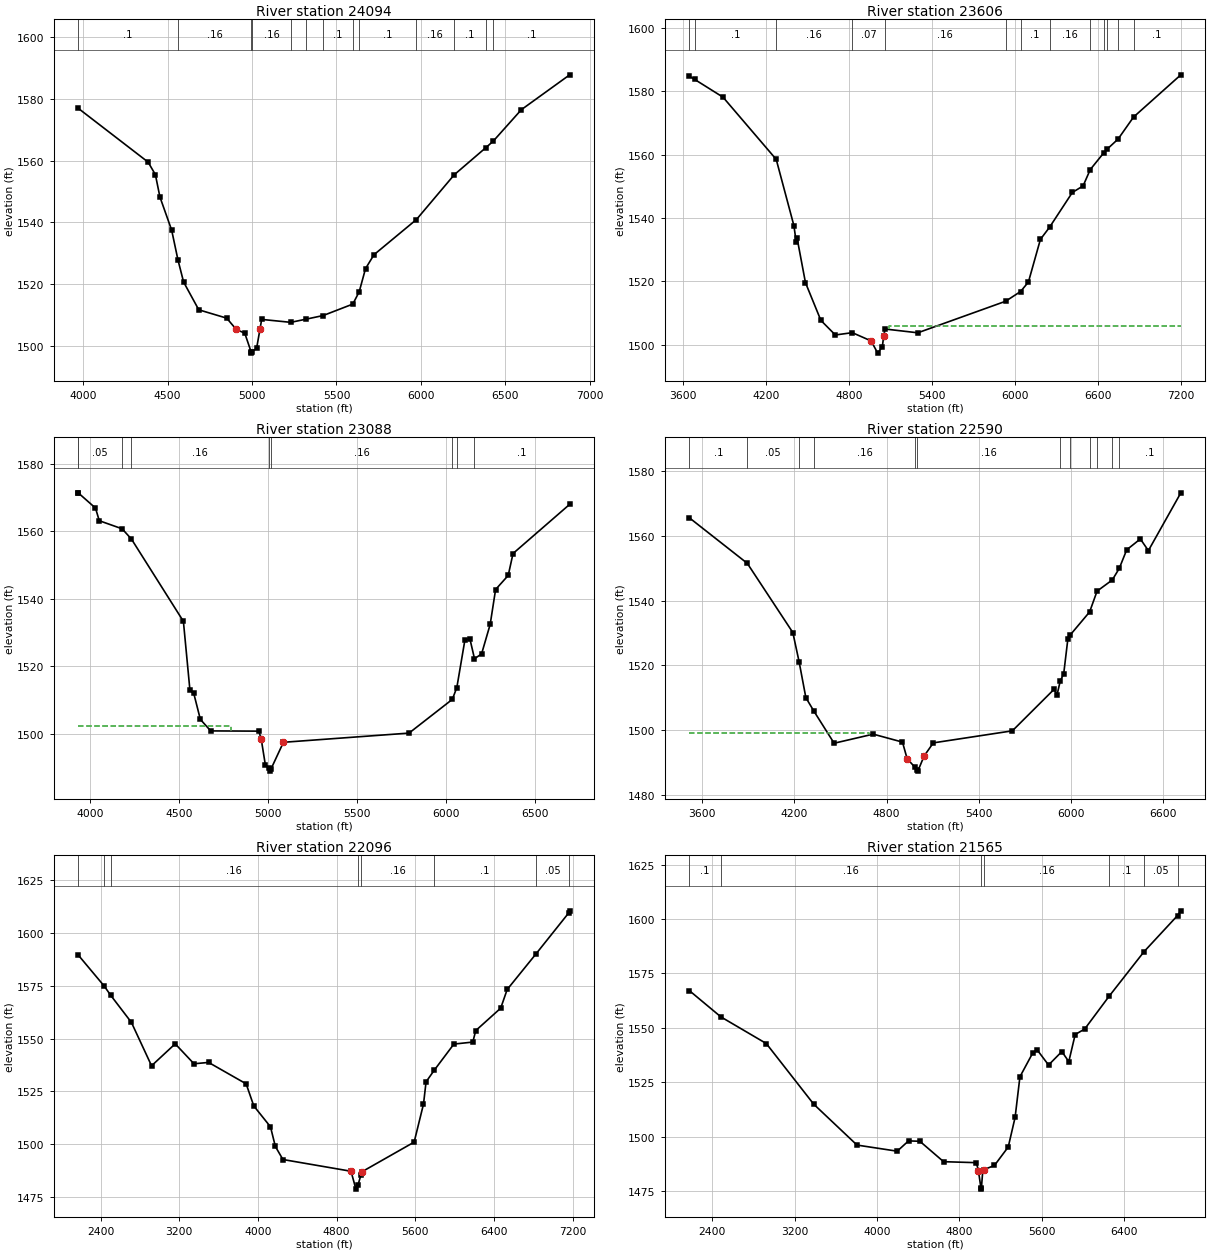
Type RM Length L Ch R = 1 ,24094   ,488,488,488
BEGIN DESCRIPTION:
MIDDLE FORK ROCKY CREEK 42.0
END DESCRIPTION:
XS GIS Cut Line= 4
      2865064.04     10035760.04      2865899.29     10036028.51
      2866495.89     10036028.51      2867351.03     10034875.06
#Sta/Elev= 30
  3970.5 1576.92  4384.8 1559.48  4427.9 1555.43  4454.7 1548.21  4524.2 1537.47
  4561.5 1527.84  4594.9 1520.68  4684.7  1511.7  4849.9    1509    4907 1505.33
    4957 1504.13    4994 1498.18  4996.8 1497.68    5000 1498.18    5027 1499.22
    5047  1505.4    5057 1508.59  5229.3 1507.64  5319.3 1508.66  5421.1 1509.84
  5596.6 1513.55  5634.4 1517.54  5671.8 1525.02  5721.9 1529.52  5973.3 1540.91
  6197.1 1555.39  6383.7 1564.14  6427.5 1566.24  6594.2 1576.44  6880.3 1587.72
#Mann= 13 ,-1 , 0
  3970.5      .1       0  4561.5     .16       0    4994     .07       0
    5000     .16       0  5229.3      .1       0  5319.3     .16       0
  5421.1      .1       0  5596.6     .16       0  5634.4      .1       0
  5973.3     .16       0  6197.1      .1       0  6383.7     .05       0
  6427.5      .1       0
Bank Sta=4907,5047
XS Rating Curve= 0 ,0
Exp/Cntr=0.3,0.1

Type RM Length L Ch R = 1 ,23606   ,518,518,518
BEGIN DESCRIPTION:
MIDDLE FORK ROCKY CREEK 41.0
END DESCRIPTION:
XS GIS Cut Line= 4
       2864855.2     10035958.89      2865859.52     10036466.02
      2866366.63     10036535.62       2867440.5     10034944.69
#Sta/Elev= 30
  3643.7 1584.76  3681.5 1583.77  3887.8 1578.13  4272.7 1558.49  4400.6 1537.58
  4417.3  1532.4  4422.9  1533.8  4484.2 1519.58  4595.7 1507.66  4700.4 1503.05
  4823.1 1503.78  4959.5 1501.17  5006.9 1497.32  5040.3 1499.32  5050.4 1502.76
  5060.4 1504.93    5297 1503.74  5932.4  1513.7  6040.2 1516.76  6097.3 1519.76
  6184.2 1533.25    6250 1537.05    6415 1548.04  6492.9 1550.12  6544.8 1555.28
  6640.7 1560.46  6665.2 1561.65  6746.1 1564.91  6857.8 1571.85  7200.1 1585.19
#Mann= 13 ,-1 , 0
  3643.7     .16       0  3681.5      .1       0  4272.7     .16       0
  4823.1     .07       0  5060.4     .16       0  5932.4     .16       0
  6040.2      .1       0    6250     .16       0  6544.8      .1       0
  6640.7     .16       0  6665.2      .1       0  6746.1     .05       0
  6857.8      .1       0
#XS Ineff= 2 , 0
                         5090.04         1506.03
Permanent Ineff=
       T       T
Bank Sta=4959.5,5050.4
XS Rating Curve= 0 ,0
Exp/Cntr=0.3,0.1

Type RM Length L Ch R = 1 ,23088   ,498,498,498
BEGIN DESCRIPTION:
MIDDLE FORK ROCKY CREEK 40.0
END DESCRIPTION:
XS GIS Cut Line= 3
      2865083.91     10036426.23      2866167.76     10037072.56
      2867649.32     10037321.14
#Sta/Elev= 30
  3933.4 1571.45  3933.9 1571.45    4031 1566.93  4052.4 1563.17  4180.9 1560.77
  4233.4 1557.71  4525.4  1533.3  4562.3 1512.78  4583.7 1511.92  4620.7  1504.2
  4679.1 1500.78  4949.7 1500.71  4963.3 1498.27  4986.6 1490.59  5008.1 1489.84
  5013.7 1488.84  5016.9 1489.34  5087.9  1497.4  5794.3 1500.13  6037.7 1510.14
  6063.1 1513.66  6108.6 1527.82  6136.6  1528.1  6162.4  1522.2  6202.3 1523.65
  6250.6 1532.41    6281 1542.75    6352 1546.93  6379.1 1553.44  6697.6 1568.03
#Mann= 9 ,-1 , 0
  3933.4     .16       0  3933.9     .05       0  4180.9      .1       0
  4233.4     .16       0  5008.1     .07       0  5016.9     .16       0
  6037.7      .1       0  6063.1     .05       0  6162.4      .1       0
#XS Ineff= 2 , 0
         4795.44 1502.26
Permanent Ineff=
       T       T
Bank Sta=4963.3,5087.9
XS Rating Curve= 0 ,0
Exp/Cntr=0.3,0.1

Type RM Length L Ch R = 1 ,22590   ,494,494,494
BEGIN DESCRIPTION:
MIDDLE FORK ROCKY CREEK 39.0
END DESCRIPTION:
XS GIS Cut Line= 4
      2864994.42     10036635.03      2865779.97     10037430.52
      2866356.68     10037390.75      2867848.21     10037569.73
#Sta/Elev= 30
  3516.5 1565.63  3893.9 1551.53  4190.2 1530.12  4231.2 1521.04    4275 1509.97
  4327.8 1505.76  4458.9 1495.87  4713.2 1498.68  4903.6 1496.22  4933.7 1491.13
  4983.8 1488.46  5000.9 1487.74  5003.6 1487.24    5044 1491.88  5104.1 1495.98
  5618.8 1499.71  5889.2 1512.52  5909.3 1510.86  5929.5 1514.98  5952.8 1517.42
  5979.8 1528.15    5995 1529.36  6121.3  1536.5  6169.8 1542.93  6268.7 1546.38
    6314 1549.95  6362.6 1555.71  6451.4 1559.07  6503.6 1555.46  6714.8 1573.34
#Mann= 12 ,-1 , 0
  3516.5      .1       0  3893.9     .05       0  4231.2      .1       0
  4327.8     .16       0  4983.8     .07       0  5000.9     .16       0
  5929.5      .1       0    5995     .16       0  6121.3      .1       0
  6169.8     .16       0  6268.7     .05       0    6314      .1       0
#XS Ineff= 2 , 0
         4687.97    1499
Permanent Ineff=
       T       T
Bank Sta=4933.7,5044
XS Rating Curve= 0 ,0
Exp/Cntr=0.3,0.1

Type RM Length L Ch R = 1 ,22096   ,531,531,531
BEGIN DESCRIPTION:
MIDDLE FORK ROCKY CREEK 38.0
END DESCRIPTION:
XS GIS Cut Line= 4
      2864089.63     10036366.62      2865551.27     10037828.26
      2866714.65     10037858.09      2868464.06     10037609.59
#Sta/Elev= 30
  2171.1 1589.58  2438.7 1574.69  2500.6 1570.56  2712.7 1557.65  2917.8  1537.1
  3158.2 1547.49  3349.1 1538.05  3497.6 1538.69  3879.4 1528.56  3957.2  1518.1
  4126.9 1508.22  4176.4 1498.93  4253.5 1492.74  4945.6 1487.19  4995.4 1478.73
  5015.6 1480.53  5045.6 1485.25  5055.6 1486.91  5587.6 1500.98  5682.7 1518.98
  5708.8  1529.5  5791.5 1534.97  5991.6 1547.37    6184 1548.32  6213.8 1553.75
  6467.7 1564.37  6533.5  1573.2  6829.1  1590.2  7158.7 1609.42  7168.9 1610.43
#Mann= 8 ,-1 , 0
  2171.1      .1       0  2438.7     .05       0  2500.6     .16       0
  5015.6     .07       0  5045.6     .16       0  5791.5      .1       0
  6829.1     .05       0  7158.7      .1       0
Bank Sta=4945.6,5055.6
XS Rating Curve= 0 ,0
Exp/Cntr=0.3,0.1

Type RM Length L Ch R = 1 ,21565   ,588,588,588
BEGIN DESCRIPTION:
MIDDLE FORK ROCKY CREEK 37.0
END DESCRIPTION:
XS GIS Cut Line= 3
      2863751.51     10038345.31      2866267.19     10038385.09
      2868453.02     10037838.63
#Sta/Elev= 30
  2178.7 1567.12  2485.7 1555.02  2925.8  1542.8  3385.8 1514.96  3805.9 1496.17
  4195.9 1493.36  4305.9 1498.09  4415.9 1497.91    4646 1488.54  4963.6 1488.09
  4984.6 1484.25  5009.7 1475.94    5013 1476.44  5025.9 1484.27  5036.2 1484.89
  5139.2  1486.8  5273.2 1495.29  5339.8 1508.88  5386.6 1527.53  5510.3 1538.41
  5551.6 1540.02  5664.5 1532.93  5793.3 1539.11  5860.8 1534.49  5922.6 1546.92
  6015.4 1549.48  6252.5 1564.55  6590.6 1584.97  6915.6 1601.55  6947.8 1603.73
#Mann= 7 ,-1 , 0
  2178.7      .1       0  2485.7     .16       0    5013     .07       0
  5036.2     .16       0  6252.5      .1       0  6590.6     .05       0
  6915.6      .1       0
Bank Sta=4984.6,5036.2
XS Rating Curve= 0 ,0
Exp/Cntr=0.3,0.1

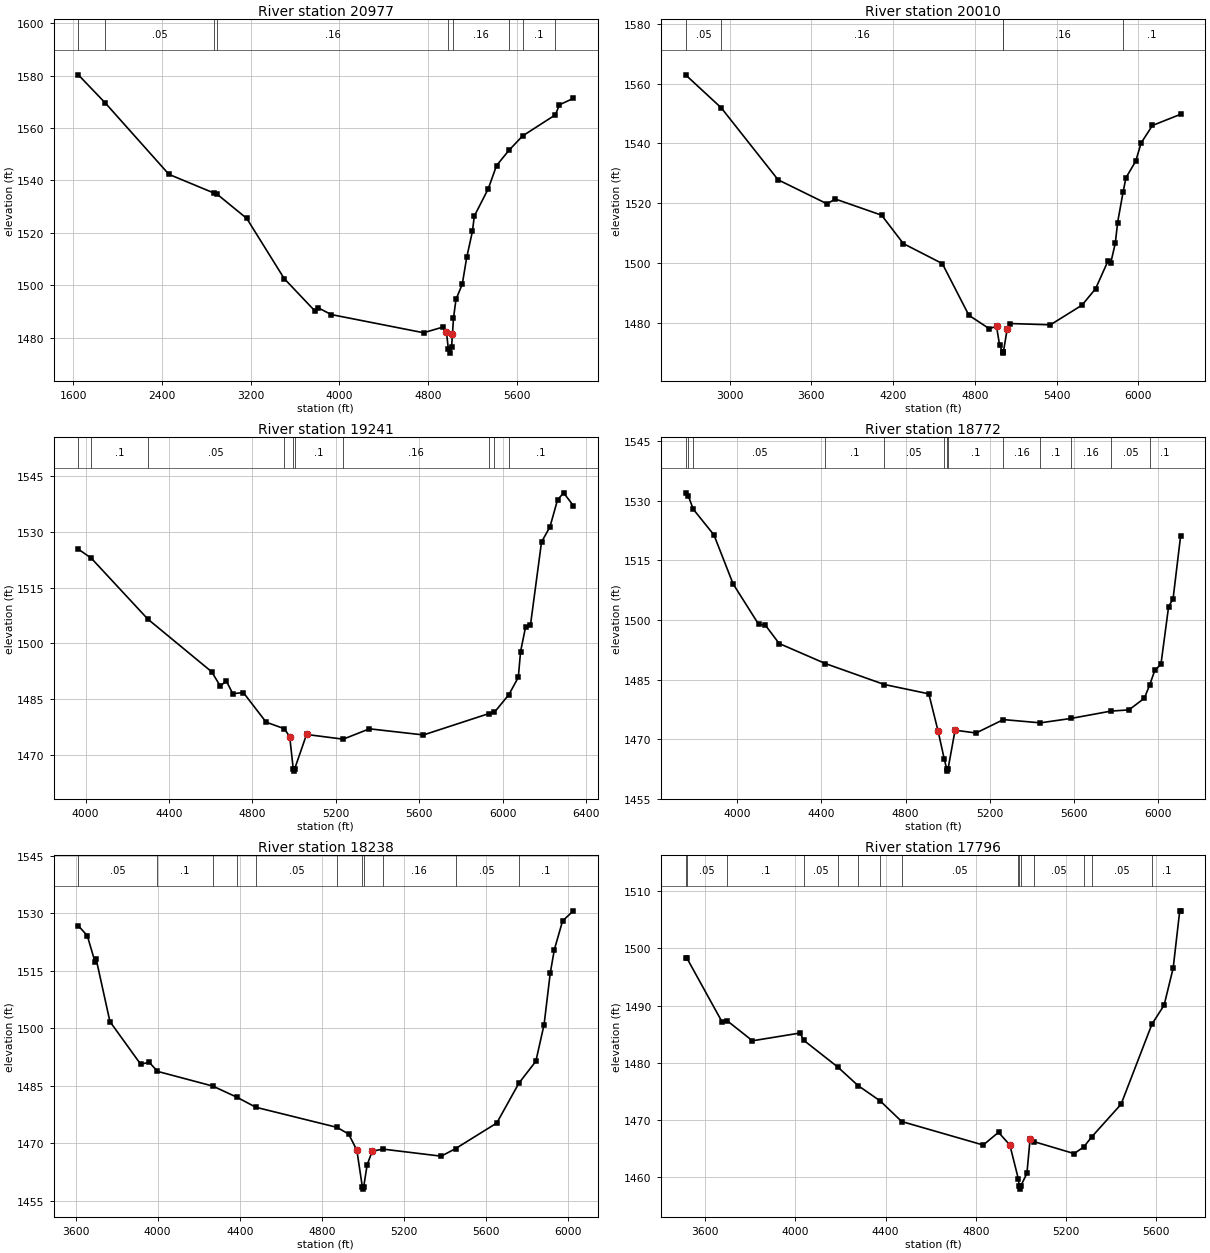
Type RM Length L Ch R = 1 ,20977   ,967,967,967
BEGIN DESCRIPTION:
MIDDLE FORK ROCKY CREEK 36.0
END DESCRIPTION:
XS GIS Cut Line= 4
      2863433.31     10038534.23      2866585.38     10038762.93
      2867221.76     10039061.23       2867808.4     10038931.97
#Sta/Elev= 30
  1646.4 1580.26  1888.2  1569.6  2463.7 1542.32  2871.6 1535.16  2894.8 1534.86
  3165.5 1525.51  3503.2 1502.57  3781.8 1490.15  3807.2 1491.49  3927.5 1488.87
  4759.7 1481.94  4931.7 1484.07    4966  1482.1  4983.3 1475.62  4997.7 1474.17
  5011.7 1476.47    5020 1481.28    5029 1487.42  5051.8 1494.63  5108.5 1500.47
  5148.6 1510.66  5199.8 1520.55  5217.1 1526.43  5342.3 1536.78  5417.6 1545.68
  5528.8 1551.46  5652.2 1556.96    5948 1565.01  5984.2 1568.83  6110.3 1571.29
#Mann= 9 ,-1 , 0
  1646.4      .1       0  1888.2     .05       0  2871.6     .16       0
  2894.8     .16       0  4983.3     .07       0    5029     .16       0
  5528.8     .05       0  5652.2      .1       0    5948     .05       0
Bank Sta=4966,5020
XS Rating Curve= 0 ,0
Exp/Cntr=0.3,0.1

Type RM Length L Ch R = 1 ,20010   ,769,769,769
BEGIN DESCRIPTION:
MIDDLE FORK ROCKY CREEK 35.0
END DESCRIPTION:
XS GIS Cut Line= 4
      2863721.74     10038782.83      2865730.25      10039190.5
      2866396.46     10039439.08      2867251.59      10039260.1
#Sta/Elev= 30
  2677.2 1562.99  2939.2 1551.93  3356.4 1527.83    3716 1519.78  3775.9  1521.4
  4116.1 1515.98  4275.9 1506.46  4561.6 1499.78  4756.8 1482.46  4906.2 1477.97
  4959.6 1478.78  4982.7 1472.36  5004.6 1470.28  5007.4 1469.78  5010.6 1470.28
    5038 1477.84  5055.6  1479.7  5355.4 1479.26  5586.9 1485.84  5686.8 1491.34
  5776.5 1500.49  5797.4 1499.83  5831.5 1506.56  5848.5  1513.5  5889.3 1523.85
  5909.8 1528.51  5981.4 1534.06  6021.1 1540.15  6103.9 1546.02  6311.4 1549.78
#Mann= 5 ,-1 , 0
  2677.2     .05       0  2939.2     .16       0  5004.6     .07       0
  5010.6     .16       0  5889.3      .1       0
Bank Sta=4959.6,5038
XS Rating Curve= 0 ,0
Exp/Cntr=0.3,0.1

Type RM Length L Ch R = 1 ,19241   ,469,469,469
BEGIN DESCRIPTION:
MIDDLE FORK ROCKY CREEK 33.0
END DESCRIPTION:
XS GIS Cut Line= 3
      2864815.43     10039797.04      2866098.16     10039985.97
      2867091.99     10039568.56
#Sta/Elev= 30
  3965.1 1525.34  4026.8 1522.94  4298.8 1506.48    4605 1492.29  4645.4 1488.51
  4675.7 1489.76    4706 1486.38  4756.6 1486.71  4865.8 1478.73    4953 1476.96
    4979 1474.83  4996.2 1466.03  4998.9 1465.53  5002.2 1466.03  5059.8 1475.41
  5235.6 1474.14  5361.4 1476.93  5620.7 1475.28  5934.5 1481.04  5960.5 1481.36
  6030.5 1486.17  6075.5 1490.82  6086.3 1497.75  6110.1 1504.31  6133.8 1504.91
  6186.8 1527.27  6227.3 1531.35  6263.5 1538.62  6292.7 1540.52  6339.6 1537.05
#Mann= 10 ,-1 , 0
  3965.1     .16       0  4026.8      .1       0  4298.8     .05       0
    4953      .1       0  4996.2     .07       0  5002.2      .1       0
  5235.6     .16       0  5934.5      .1       0  5960.5     .05       0
  6030.5      .1       0
Bank Sta=4979,5059.8
XS Rating Curve= 0 ,0
Exp/Cntr=0.3,0.1

Type RM Length L Ch R = 1 ,18772   ,534,534,534
BEGIN DESCRIPTION:
MIDDLE FORK ROCKY CREEK 32.0
END DESCRIPTION:
XS GIS Cut Line= 3
      2864885.06     10040224.61      2865978.84      10040383.7
      2867031.84     10039718.13
#Sta/Elev= 30
  3755.6 1532.02  3769.2 1531.14  3792.1  1527.9  3890.4 1521.42  3981.4 1509.09
  4102.6 1498.93  4134.8  1498.7  4199.9  1494.1    4420 1489.04  4699.3 1483.78
  4910.7 1481.43  4955.1 1471.97    4984 1465.02  4995.9 1462.48  4998.6 1461.98
  5001.9 1462.48  5035.3 1472.28  5135.3 1471.58  5264.9 1474.95  5440.2 1474.13
    5587 1475.25  5775.8 1477.09  5861.1 1477.39    5934 1480.32  5959.3 1483.64
  5984.3 1487.41  6012.9 1488.84  6049.3 1503.37  6070.5 1505.33  6106.6 1521.27
#Mann= 13 ,-1 , 0
  3755.6     .05       0  3769.2      .1       0  3792.1     .05       0
    4420      .1       0  4699.3     .05       0    4984      .1       0
  4995.9     .07       0  5001.9      .1       0  5264.9     .16       0
  5440.2      .1       0    5587     .16       0  5775.8     .05       0
  5959.3      .1       0
Bank Sta=4955.1,5035.3
XS Rating Curve= 0 ,0
Exp/Cntr=0.3,0.1

Type RM Length L Ch R = 1 ,18238   ,442,442,442
BEGIN DESCRIPTION:
MIDDLE FORK ROCKY CREEK 31.0
END DESCRIPTION:
XS GIS Cut Line= 2
      2864964.66     10040602.46      2867370.91     10040781.44
#Sta/Elev= 30
  3613.3 1526.71  3657.2 1524.12  3695.1  1517.2  3700.1 1518.08  3767.5 1501.72
  3917.9 1490.56  3958.1 1491.16  3999.3 1488.74  4268.6 1484.91  4386.4    1482
  4478.9 1479.38  4873.7 1474.15  4930.7 1472.41  4970.8 1468.21  4997.9 1458.54
  5000.7 1458.04  5003.9 1458.54    5021 1464.36    5046 1467.94  5098.3 1468.47
    5382 1466.63  5451.8  1468.6  5652.7 1475.27    5761  1485.7  5843.2 1491.37
  5883.4 1500.95  5913.4 1514.35  5933.5  1520.5  5973.6 1527.98  6026.2  1530.6
#Mann= 11 ,-1 , 0
  3613.3     .05       0  3999.3      .1       0  4268.6     .05       0
  4386.4      .1       0  4478.9     .05       0  4873.7      .1       0
  4997.9     .07       0  5003.9      .1       0  5098.3     .16       0
  5451.8     .05       0    5761      .1       0
Bank Sta=4970.8,5046
XS Rating Curve= 0 ,0
Exp/Cntr=0.3,0.1

Type RM Length L Ch R = 1 ,17796   ,803,803,803
BEGIN DESCRIPTION:
MIDDLE FORK ROCKY CREEK 30.0
END DESCRIPTION:
XS GIS Cut Line= 4
       2865113.8     10040940.53      2866426.29     10041089.68
      2866824.02     10040890.81      2867251.56     10040851.04
#Sta/Elev= 30
  3512.8 1498.24  3519.1 1498.25  3673.7  1487.2  3696.6 1487.35  3809.4 1483.83
  4020.7 1485.19  4035.9 1483.94  4187.7 1479.24  4277.2 1476.01    4376 1473.31
  4470.8 1469.72  4832.3 1465.61  4900.3 1467.83  4950.6  1465.6  4987.9 1459.73
  4992.3  1458.4  4995.1  1457.9  4998.3  1458.4  5026.2 1460.67  5040.1 1466.63
  5058.4 1466.19  5235.7 1464.11  5278.3 1465.28  5313.9 1467.05  5443.6 1472.74
  5580.4 1486.73  5634.4 1490.06  5674.6 1496.54  5703.7 1506.55  5707.8 1506.55
#Mann= 15 ,-1 , 0
  3512.8      .1       0  3519.1     .05       0  3696.6      .1       0
  4035.9     .05       0  4187.7      .1       0  4277.2     .05       0
    4376      .1       0  4470.8     .05       0  4987.9      .1       0
  4992.3     .07       0  4998.3      .1       0  5058.4     .05       0
  5278.3     .16       0  5313.9     .05       0  5580.4      .1       0
Bank Sta=4950.6,5040.1
XS Rating Curve= 0 ,0
Exp/Cntr=0.3,0.1

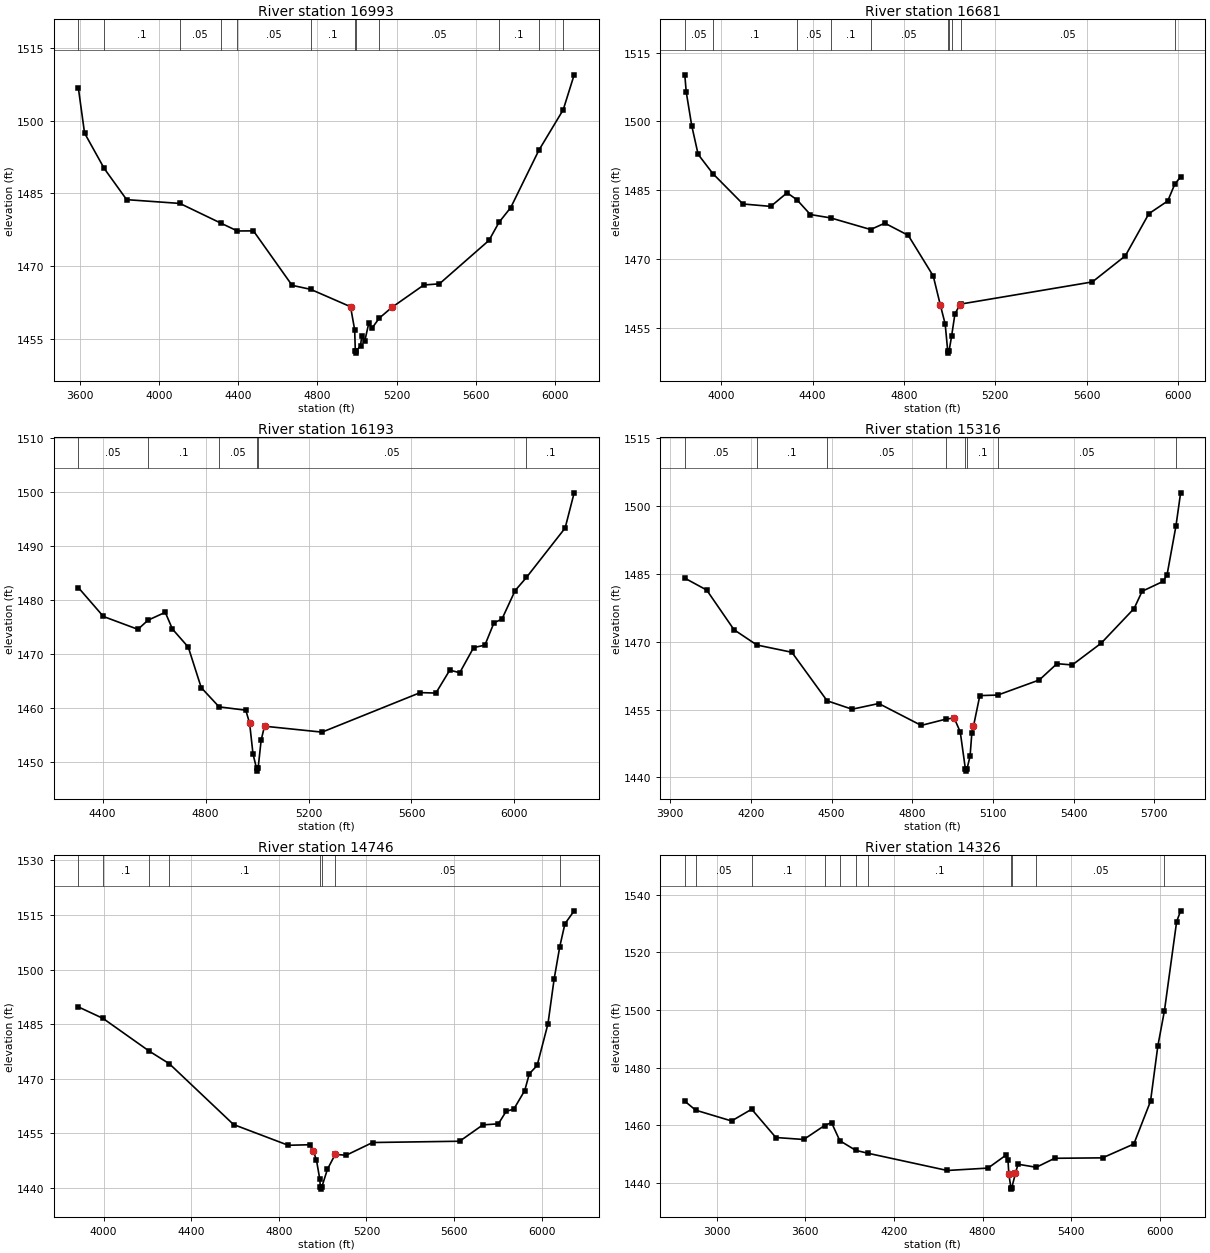
Type RM Length L Ch R = 1 ,16993   ,312,312,312
BEGIN DESCRIPTION:
MIDDLE FORK ROCKY CREEK 28.0
END DESCRIPTION:
XS GIS Cut Line= 4
      2865097.41     10041095.01      2866286.61     10041277.29
      2866581.75     10041485.63      2867501.89      10041676.6
#Sta/Elev= 30
  3592.7 1506.77  3624.1 1497.43  3723.4 1490.13  3836.6  1483.7  4105.6 1482.92
  4310.7 1478.89    4396 1477.24  4477.1 1477.26  4672.2 1466.03  4766.3  1465.2
  4967.5 1461.62  4988.4 1456.83  4991.5 1452.55  4994.3 1452.05  4997.5 1452.55
    5018 1453.59  5024.1 1455.62  5038.9 1454.47  5059.8 1458.27  5074.6 1457.13
  5112.5 1459.26  5175.8 1461.47  5337.5  1466.1  5416.3 1466.34  5666.9 1475.31
  5717.2 1479.02  5776.7 1482.08  5918.1 1493.85  6041.6 1502.24  6096.8 1509.44
#Mann= 12 ,-1 , 0
  3592.7     .05       0  3723.4      .1       0  4105.6     .05       0
  4310.7      .1       0    4396     .05       0  4766.3      .1       0
  4991.5     .07       0  4997.5      .1       0  5112.5     .05       0
  5717.2      .1       0  5918.1     .05       0  6041.6      .1       0
Bank Sta=4967.5,5175.8
XS Rating Curve= 0 ,0
Exp/Cntr=0.3,0.1

Type RM Length L Ch R = 1 ,16681   ,488,488,488
BEGIN DESCRIPTION:
Mapping XS a6a5c975
END DESCRIPTION:
XS GIS Cut Line= 4
      2865088.74      10041277.3      2866043.56     10041459.59
      2866356.06     10041650.56      2867163.34     10041850.21
#Sta/Elev= 30
  3841.1 1510.19  3847.3 1506.46  3871.4  1499.1  3899.4 1492.83  3963.5 1488.64
  4095.3 1481.99  4217.2 1481.46  4288.8 1484.43  4332.2 1482.89  4390.6 1479.68
  4479.2 1478.95  4654.4 1476.41  4716.4  1477.8    4819 1475.14  4928.4 1466.26
  4959.3 1459.95  4980.6 1455.77  4991.7 1449.92  4994.5 1449.42  4997.7 1449.92
  5008.8 1453.14  5023.2 1457.97  5044.5 1459.94  5048.2 1460.13  5624.8 1464.97
    5769 1470.66  5872.1 1479.87  5954.5 1482.64  5985.2 1486.28    6011 1487.95
#Mann= 10 ,-1 , 0
  3841.1     .05       0  3963.5      .1       0  4332.2     .05       0
  4479.2      .1       0  4654.4     .05       0  4991.7    .035       0
  4997.7     .05       0  5008.8      .1       0  5048.2     .05       0
  5985.2      .1       0
Bank Sta=4959.3,5044.5
XS Rating Curve= 0 ,0
Exp/Cntr=0.3,0.1

Type RM Length L Ch R = 1 ,16193   ,877,877,877
BEGIN DESCRIPTION:
MIDDLE FORK ROCKY CREEK 26.0
END DESCRIPTION:
XS GIS Cut Line= 3
      2865243.05      10041596.8      2866137.93     10042044.24
      2867042.73      10042243.1
#Sta/Elev= 30
  4305.4 1482.37  4402.8 1477.02    4537 1474.64  4576.1 1476.33  4643.2 1477.79
  4671.1 1474.69  4732.6 1471.35    4783 1463.84  4852.5 1460.28  4956.2 1459.66
  4971.1 1457.24  4984.2 1451.56    4998 1448.88  5000.7 1448.38    5004 1448.88
  5015.8  1454.1  5028.9  1456.7  5252.5  1455.6  5634.1 1462.92    5695 1462.84
    5749 1467.09  5787.6  1466.6  5841.6 1471.26  5885.4 1471.71  5920.8 1475.86
  5951.5 1476.52  6002.7  1481.8  6046.7 1484.24  6197.2  1493.4  6232.3 1499.92
#Mann= 6 ,-1 , 0
  4305.4     .05       0  4576.1      .1       0  4852.5     .05       0
    4998    .035       0    5004     .05       0  6046.7      .1       0
Bank Sta=4971.1,5028.9
XS Rating Curve= 0 ,0
Exp/Cntr=0.3,0.1

Type RM Length L Ch R = 1 ,15316   ,570,570,570
BEGIN DESCRIPTION:
MIDDLE FORK ROCKY CREEK 25.0
END DESCRIPTION:
XS GIS Cut Line= 2
      2865133.69     10042024.38      2866654.26     10043067.91
#Sta/Elev= 30
    3954 1484.06  4035.5 1481.43    4137 1472.66  4222.1 1469.28  4352.2 1467.67
  4483.4 1456.94  4576.3 1455.08  4675.4 1456.34  4833.4  1451.5  4925.3 1452.89
  4955.9 1453.15  4978.6 1450.03  4997.6 1441.89  5000.3 1441.39  5003.6 1441.89
    5015 1444.68  5021.5 1449.72  5027.6 1451.29  5051.3 1458.09  5118.1 1458.21
  5272.6 1461.55  5338.3 1465.15  5395.1 1464.87  5502.7 1469.68  5625.2 1477.35
    5655 1481.16  5732.8 1483.34  5747.7  1484.8  5780.7 1495.55  5798.2 1502.93
#Mann= 8 ,-1 , 0
    3954     .05       0  4222.1      .1       0  4483.4     .05       0
  4925.3      .1       0  4997.6     .07       0  5003.6      .1       0
  5118.1     .05       0  5780.7      .1       0
Bank Sta=4955.9,5027.6
XS Rating Curve= 0 ,0
Exp/Cntr=0.3,0.1

Type RM Length L Ch R = 1 ,14746   ,420,420,420
BEGIN DESCRIPTION:
MIDDLE FORK ROCKY CREEK 23.0
END DESCRIPTION:
XS GIS Cut Line= 3
      2864666.31     10042243.11      2865760.08     10043068.41
       2866366.6     10043724.64
#Sta/Elev= 30
  3884.4 1489.74  3996.8 1486.59  4208.2 1477.59  4299.9 1474.13    4593 1457.44
  4842.8 1451.74  4942.7 1451.89  4957.2 1450.19  4971.8 1447.61  4986.4 1442.57
  4989.6  1440.2  4992.4  1439.7  4995.6  1440.2  5021.8 1445.17  5057.2 1449.24
  5107.1    1449  5227.9  1452.5  5625.3 1452.85  5731.3 1457.34  5802.2 1457.63
  5837.4 1461.03  5873.1 1461.71  5922.4 1466.75  5943.4 1471.36  5979.1 1473.66
  6028.5 1485.06  6056.8 1497.39  6082.6 1506.31  6106.1 1512.57  6148.2 1516.12
#Mann= 8 ,-1 , 0
  3884.4     .05       0  3996.8      .1       0  4208.2     .05       0
  4299.9      .1       0  4989.6     .07       0  4995.6      .1       0
  5057.2     .05       0  6082.6      .1       0
Bank Sta=4957.2,5057.2
XS Rating Curve= 0 ,0
Exp/Cntr=0.3,0.1

Type RM Length L Ch R = 1 ,14326   ,727,727,727
BEGIN DESCRIPTION:
MIDDLE FORK ROCKY CREEK 24.0
END DESCRIPTION:
XS GIS Cut Line= 3
      2863373.66     10042312.71      2865750.14     10043466.14
      2866257.27     10043973.28
#Sta/Elev= 30
  2783.2 1468.41  2856.6  1465.3    3100 1461.55  3236.3 1465.62  3399.9 1455.81
  3588.9 1455.12  3729.7 1459.96    3777 1460.98  3833.5 1454.69  3940.9 1451.36
    4026 1450.32    4561 1444.37  4837.3  1445.2  4956.1 1449.59  4972.7 1447.84
  4978.3  1443.1  4992.3  1438.4    4995  1437.9  4998.3  1438.4  5023.4 1443.47
  5040.4 1446.54  5164.1 1445.48  5288.7  1448.6  5612.8 1448.75    5825 1453.55
  5938.1  1468.4  5987.6 1487.55  6032.5 1499.83  6114.9 1530.68    6142 1534.45
#Mann= 11 ,-1 , 0
  2783.2      .1       0  2856.6     .05       0  3236.3      .1       0
  3729.7     .05       0  3833.5      .1       0  3940.9     .05       0
    4026      .1       0  4992.3     .07       0  4998.3      .1       0
  5164.1     .05       0  6032.5      .1       0
Bank Sta=4978.3,5023.4
XS Rating Curve= 0 ,0
Exp/Cntr=0.3,0.1

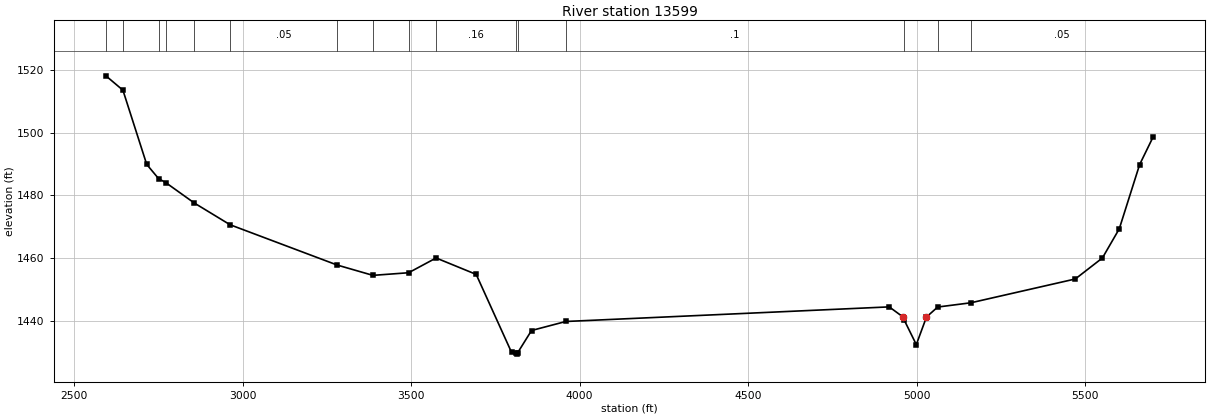
Type RM Length L Ch R = 1 ,13599   ,1872,1872,1872
BEGIN DESCRIPTION:
MIDDLE FORK ROCKY CREEK 22.0
END DESCRIPTION:
XS GIS Cut Line= 3
      2863174.77     10043038.56      2865183.37     10043933.48
      2866088.24     10044013.03
#Sta/Elev= 30
  2594.4 1518.18  2644.9  1513.6  2715.5 1489.91  2750.9 1485.35  2772.1 1484.09
  2856.8 1477.58  2962.8 1470.65  3280.8 1457.78  3386.8 1454.49  3492.7 1455.33
  3574.2 1460.04  3693.2  1454.8    3798 1429.94  3810.6 1429.85  3813.4 1429.35
  3816.6 1429.85  3857.4 1436.89  3959.2 1439.77  4918.9 1444.43  4959.1 1441.26
  4963.9 1440.09  4999.2 1432.39  5029.3 1441.19  5062.5 1444.38  5161.2 1445.74
    5471 1453.34  5551.4 1460.04  5601.5 1469.36  5661.8 1489.84  5701.7 1498.64
#Mann= 16 ,-1 , 0
  2594.4      .1       0  2644.9     .16       0  2750.9      .1       0
  2772.1     .16       0  2856.8      .1       0  2962.8     .05       0
  3280.8      .1       0  3386.8     .05       0  3492.7      .1       0
  3574.2     .16       0  3810.6     .07       0  3816.6     .16       0
  3959.2      .1       0  4963.9     .16       0  5062.5      .1       0
  5161.2     .05       0
#XS Ineff= 1 ,-1
 3618.26 4019.09 1439.77
Permanent Ineff=
       T
Bank Sta=4959.1,5029.3
XS Rating Curve= 0 ,0
Exp/Cntr=0.3,0.1