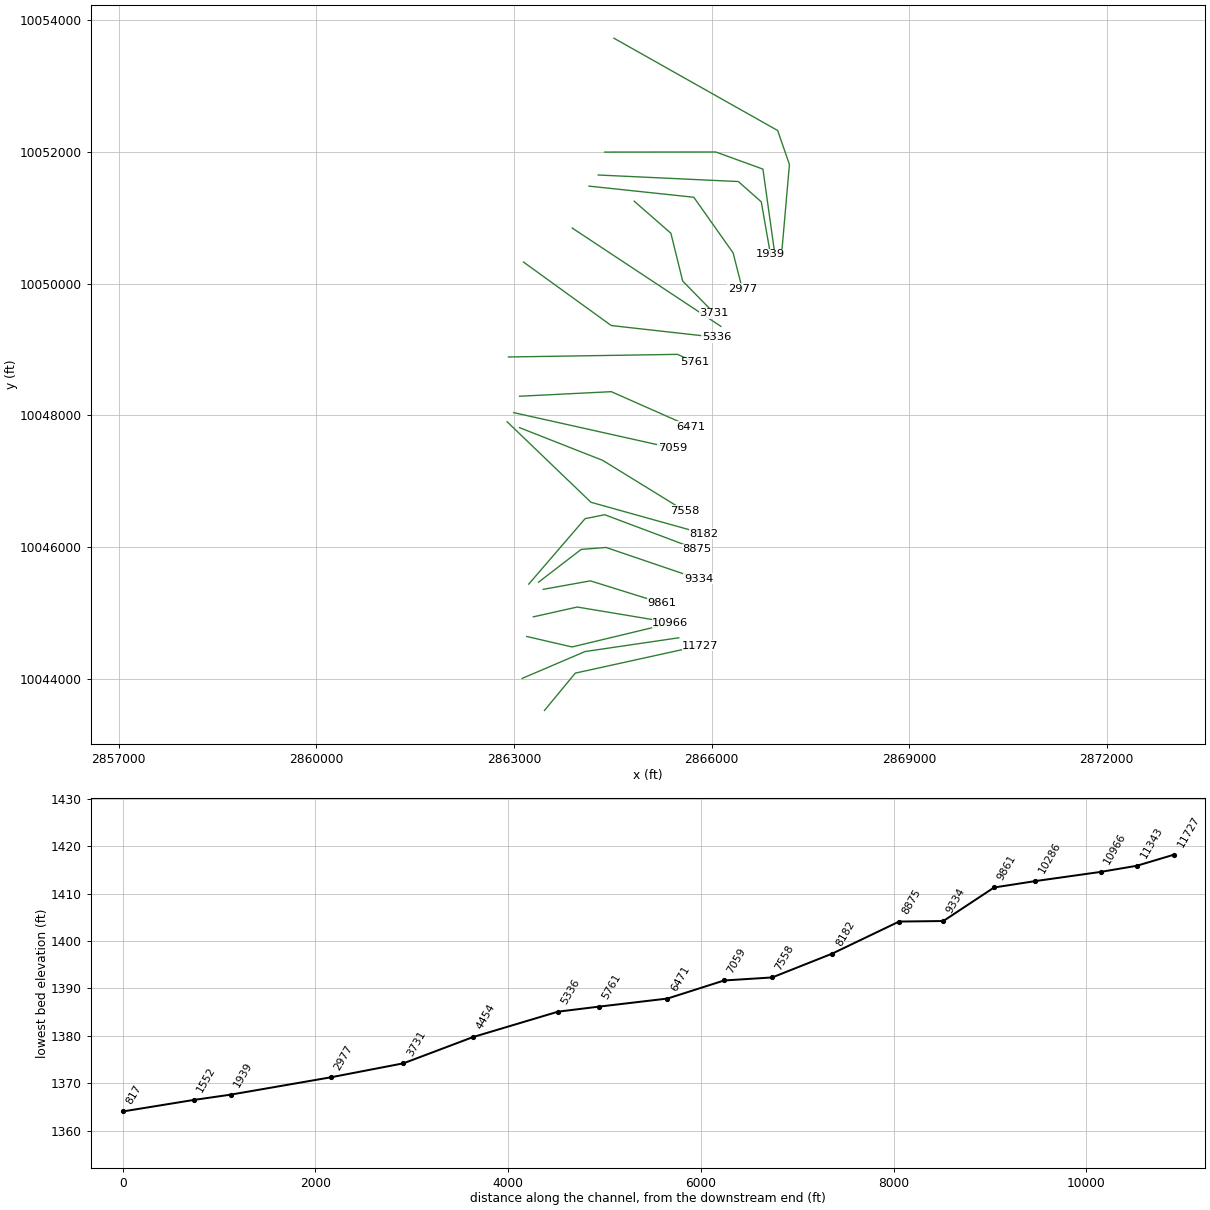
HEC-RAS study MIDDLE FORK ROCKY CREEK.prj: MIDDLE FORK ROCKY CREEK Base Level Engineering

--- MIDDLE FORK ROCKY CREEK.g01 (geometry) --- (continued)

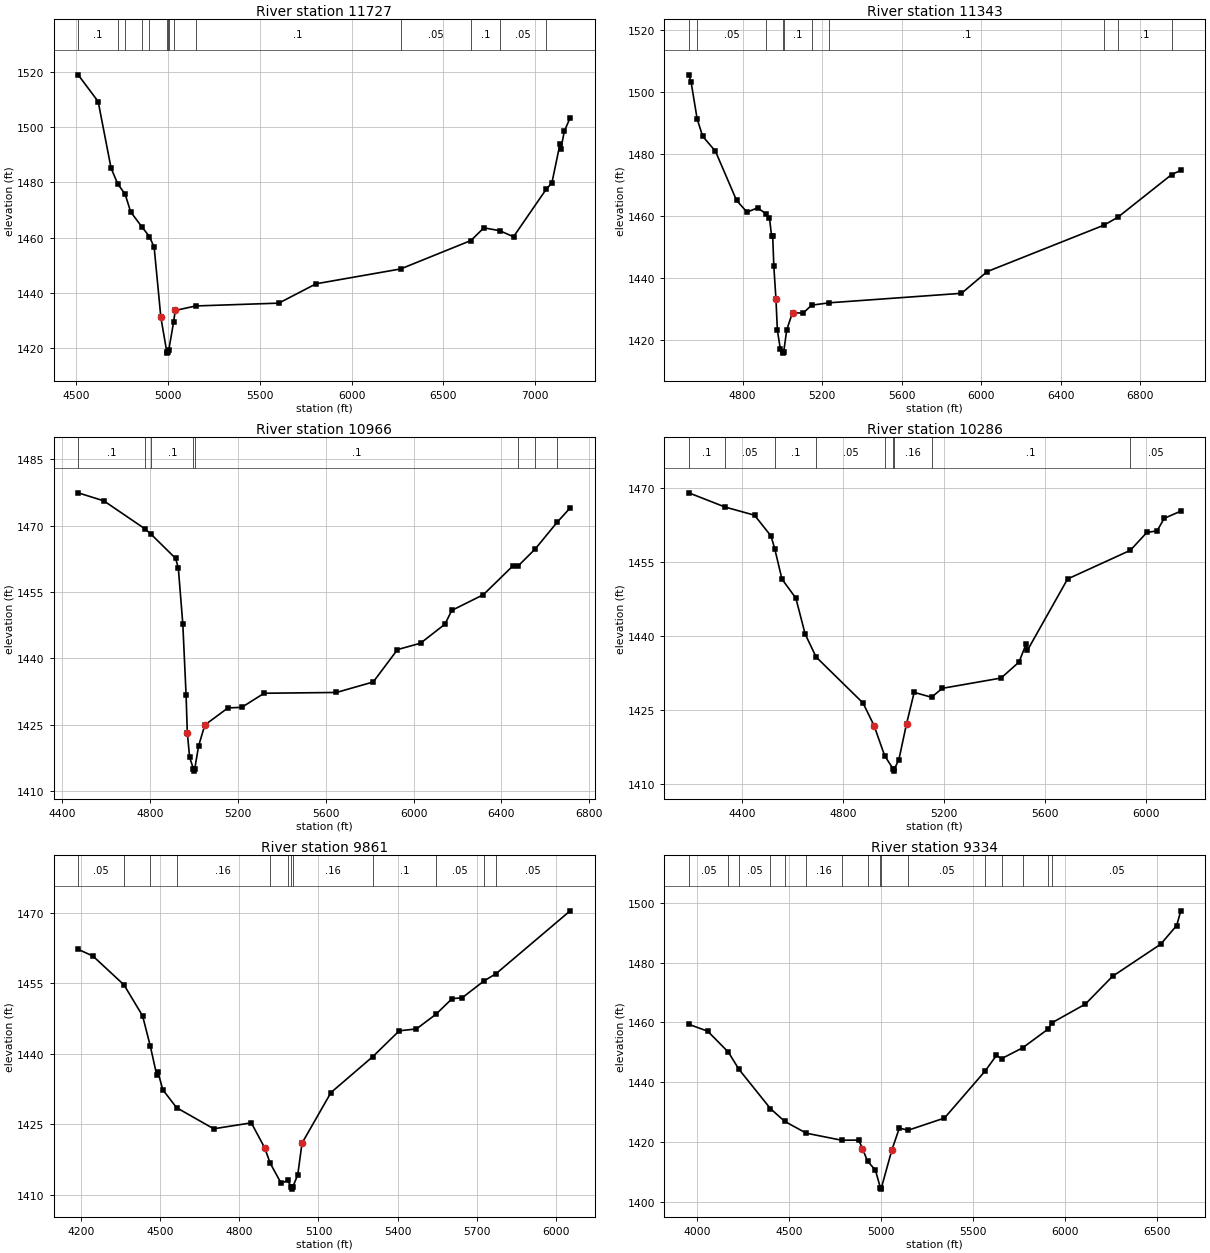
Type RM Length L Ch R = 1 ,11727   ,384,384,384
BEGIN DESCRIPTION:
MIDDLE FORK ROCKY CREEK 21.0
END DESCRIPTION:
XS GIS Cut Line= 3
      2863463.16     10043515.86       2863930.5     10044082.63
      2865829.72     10044500.26
#Sta/Elev= 30
  4511.4 1518.95  4620.4 1509.28  4690.7 1485.16  4727.2 1479.44  4767.5 1475.68
  4797.5 1469.32  4857.1 1464.02  4899.6 1460.39  4925.2 1456.58  4961.8 1431.13
  4993.9 1418.68  4996.7 1418.18  4999.9 1418.68  5004.5 1419.17  5031.8 1429.62
  5039.9 1433.63  5151.9 1435.26  5603.9 1436.28  5807.1 1443.29  6267.4 1448.66
  6650.3 1458.96  6720.6 1463.55  6807.1 1462.51  6882.1 1460.31  7059.5 1477.47
  7091.2 1479.88    7135 1493.86  7140.1 1492.13  7158.6 1498.51  7190.6 1503.43
#Mann= 14 ,-1 , 0
  4511.4      .1       0  4727.2     .05       0  4767.5      .1       0
  4857.1     .05       0  4899.6      .1       0  4993.9     .07       0
  4999.9      .1       0  5004.5     .16       0  5031.8     .05       0
  5151.9      .1       0  6267.4     .05       0  6650.3      .1       0
  6807.1     .05       0  7059.5      .1       0
Bank Sta=4961.8,5039.9
XS Rating Curve= 0 ,0
Exp/Cntr=0.3,0.1

Type RM Length L Ch R = 1 ,11343   ,377,377,377
BEGIN DESCRIPTION:
MIDDLE FORK ROCKY CREEK 20.0
END DESCRIPTION:
XS GIS Cut Line= 3
      2863125.07     10044003.08      2864079.65     10044410.76
      2865501.51     10044619.57
#Sta/Elev= 30
    4529 1505.59  4540.8  1503.2    4571 1491.39  4598.8 1485.79  4663.2 1480.94
  4769.5 1465.08  4822.2  1461.3  4874.8  1462.7  4919.7  1460.7    4935 1459.34
  4945.6 1453.62  4951.1 1453.69  4956.8 1443.86  4967.6  1433.2  4974.7 1423.15
  4989.4 1417.31  5000.7 1416.35  5003.4 1415.85  5006.7 1416.35  5021.9 1423.38
  5050.9 1428.95  5103.5 1428.72  5147.1 1431.31  5235.7 1432.08  5900.8 1435.14
  6030.2 1442.14    6617  1457.1  6687.5 1459.67  6957.5  1473.4  7004.1 1474.79
#Mann= 10 ,-1 , 0
    4529      .1       0    4571     .05       0  4919.7      .1       0
  5000.7     .07       0  5006.7      .1       0  5147.1     .05       0
  5235.7      .1       0    6617     .05       0  6687.5      .1       0
  6957.5     .05       0
Bank Sta=4967.6,5050.9
XS Rating Curve= 0 ,0
Exp/Cntr=0.3,0.1

Type RM Length L Ch R = 1 ,10966   ,680,680,680
BEGIN DESCRIPTION:
MIDDLE FORK ROCKY CREEK 19.0
END DESCRIPTION:
XS GIS Cut Line= 3
      2863194.66     10044639.47      2863880.79     10044480.37
       2865372.3     10044838.33
#Sta/Elev= 30
  4474.5 1477.38  4591.3 1475.57  4778.3 1469.25  4806.8 1468.01  4917.6 1462.59
  4930.1 1460.46  4950.6 1447.78  4965.4 1431.84  4971.1 1423.23  4981.4 1417.73
  4998.9 1415.05  5001.7 1414.55  5004.9 1415.05  5022.5 1420.24  5050.7 1424.96
  5155.9 1428.82  5218.7 1428.95  5320.4 1432.13  5649.5 1432.31  5816.9 1434.68
  5927.2 1441.99    6032 1443.43  6143.1 1447.73    6174 1450.83    6318 1454.39
  6451.7 1460.86  6476.3 1460.88    6554 1464.72  6654.4  1470.8  6712.7 1473.97
#Mann= 8 ,-1 , 0
  4474.5      .1       0  4778.3     .05       0  4806.8      .1       0
  4998.9     .07       0  5004.9      .1       0  6476.3     .05       0
    6554      .1       0  6654.4     .05       0
Bank Sta=4971.1,5050.7
XS Rating Curve= 0 ,0
Exp/Cntr=0.3,0.1

Type RM Length L Ch R = 1 ,10286   ,425,425,425
BEGIN DESCRIPTION:
MIDDLE FORK ROCKY CREEK 18.0
END DESCRIPTION:
XS GIS Cut Line= 3
      2863294.14     10044937.76      2863960.33     10045086.91
      2865211.29     10044878.42
#Sta/Elev= 30
  4188.3 1469.08  4332.5 1466.19  4448.9 1464.54  4514.3 1460.32  4529.1 1457.72
  4557.7 1451.58  4612.9  1447.7  4649.6 1440.44  4693.1 1435.77  4879.2 1426.43
  4922.8 1421.86  4964.9 1415.75  4997.9 1413.11  5000.6 1412.61  5003.9 1413.11
  5021.2 1414.92  5051.6 1422.19    5082 1428.59  5150.7  1427.6  5193.5 1429.41
  5426.7  1431.5  5497.6 1434.74    5526 1438.41  5531.1 1437.13  5690.3  1451.6
  5938.8 1457.41  6004.5 1461.03  6045.1 1461.37  6073.5  1463.9  6139.2 1465.37
#Mann= 9 ,-1 , 0
  4188.3      .1       0  4332.5     .05       0  4529.1      .1       0
  4693.1     .05       0  4964.9     .16       0  4997.9     .07       0
  5003.9     .16       0  5150.7      .1       0  5938.8     .05       0
Bank Sta=4922.8,5051.6
XS Rating Curve= 0 ,0
Exp/Cntr=0.3,0.1

Type RM Length L Ch R = 1 ,9861    ,527,527,527
BEGIN DESCRIPTION:
MIDDLE FORK ROCKY CREEK 17.0
END DESCRIPTION:
XS GIS Cut Line= 3
       2863443.3     10045355.39       2864159.2     10045484.65
      2865243.02     10045146.57
#Sta/Elev= 30
  4190.2 1462.21  4246.3 1460.78  4363.9 1454.65  4434.2 1448.08  4463.4 1441.65
  4487.7 1435.52  4492.8 1436.06  4510.5  1432.4  4562.9 1428.57  4703.5 1424.09
  4845.8 1425.35  4896.6 1420.03  4917.1  1416.8  4958.8 1412.51  4983.2 1413.11
  4997.1 1411.77  4999.8 1411.27  5003.1 1411.77  5021.7 1414.33  5037.8 1421.04
  5147.4 1431.79  5305.4  1439.4  5405.8  1444.9  5470.9  1445.3  5544.9 1448.42
  5606.1 1451.74  5643.9 1451.91  5725.6 1455.45    5773 1457.07    6053 1470.39
#Mann= 12 ,-1 , 0
  4190.2     .05       0  4363.9      .1       0  4463.4     .05       0
  4562.9     .16       0  4917.1     .05       0  4983.2     .16       0
  4997.1     .07       0  5003.1     .16       0  5305.4      .1       0
  5544.9     .05       0  5725.6      .1       0    5773     .05       0
Bank Sta=4896.6,5037.8
XS Rating Curve= 0 ,0
Exp/Cntr=0.3,0.1

Type RM Length L Ch R = 1 ,9334    ,459,459,459
BEGIN DESCRIPTION:
MIDDLE FORK ROCKY CREEK 15.0
END DESCRIPTION:
XS GIS Cut Line= 4
      2863373.64     10045464.73      2864019.99     10045961.93
      2864397.84     10045991.76      2865799.84     10045514.48
#Sta/Elev= 30
  3955.2 1459.35    4058 1457.04  4170.4 1450.04  4227.7 1444.31  4399.4 1431.13
  4476.6 1426.87  4594.5 1422.91  4786.6 1420.56  4879.5 1420.61  4899.5 1417.73
  4928.1 1413.46  4969.8 1410.61  4996.8  1404.7  4999.6  1404.2  5002.8  1404.7
    5060 1417.41  5100.2 1424.63    5148 1423.91  5345.5 1427.98  5566.5  1443.7
  5627.8 1448.92  5656.8 1447.88  5770.4 1451.48  5908.4 1457.72  5930.6 1459.88
  6111.6 1466.11  6259.5 1475.41  6521.4 1486.16  6608.1  1492.4  6630.7 1497.32
#Mann= 16 ,-1 , 0
  3955.2     .05       0  4170.4      .1       0  4227.7     .05       0
  4399.4      .1       0  4476.6     .05       0  4594.5     .16       0
  4786.6     .05       0  4928.1     .16       0  4996.8     .07       0
  5002.8     .16       0    5148     .05       0  5566.5     .16       0
  5656.8      .1       0  5770.4     .05       0  5908.4      .1       0
  5930.6     .05       0
Bank Sta=4899.5,5060
XS Rating Curve= 0 ,0
Exp/Cntr=0.3,0.1

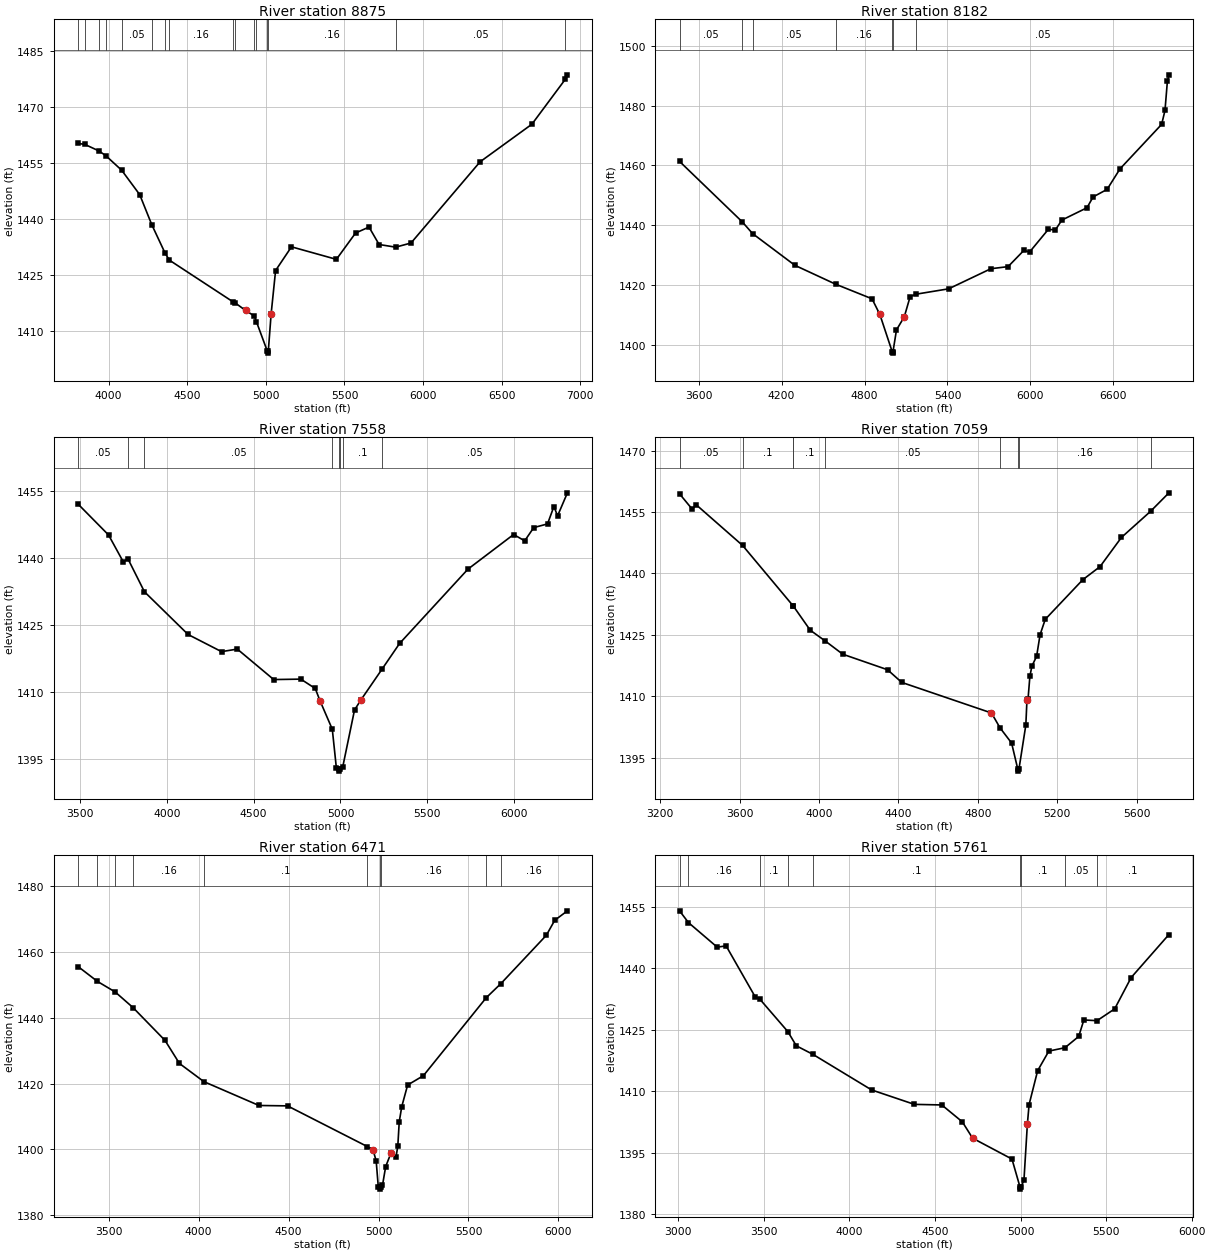
Type RM Length L Ch R = 1 ,8875    ,693,693,693
BEGIN DESCRIPTION:
MIDDLE FORK ROCKY CREEK 14.0
END DESCRIPTION:
XS GIS Cut Line= 4
       2863224.5      10045434.9      2864079.65     10046429.27
      2864377.95     10046488.93      2865779.96     10045961.93
#Sta/Elev= 30
    3805 1460.32  3848.7 1460.04  3938.9 1458.28  3983.4 1456.97    4083 1453.11
  4197.4 1446.59  4274.4 1438.51  4359.6 1430.84  4385.8 1429.03  4791.5 1417.83
  4803.6 1417.59  4871.1 1415.53  4926.2 1414.05  4940.2  1412.5  5009.6 1404.59
  5012.4 1404.09  5015.6 1404.59  5033.5 1414.57    5062 1426.24    5163 1432.59
  5448.8 1429.23  5570.8 1436.29  5656.3 1437.89  5720.4 1433.21  5825.6  1432.5
  5923.4 1433.61  6362.9 1455.38  6692.6 1465.46  6905.2 1477.51  6918.5  1478.7
#Mann= 16 ,-1 , 0
    3805     .05       0  3848.7      .1       0  3938.9     .05       0
  3983.4      .1       0    4083     .05       0  4274.4      .1       0
  4359.6     .05       0  4385.8     .16       0  4791.5      .1       0
  4803.6     .05       0  4926.2      .1       0  4940.2     .16       0
  5009.6     .07       0  5015.6     .16       0  5825.6     .05       0
  6905.2      .1       0
Bank Sta=4871.1,5033.5
XS Rating Curve= 0 ,0
Exp/Cntr=0.3,0.1

Type RM Length L Ch R = 1 ,8182    ,624,624,624
BEGIN DESCRIPTION:
MIDDLE FORK ROCKY CREEK 13.0
END DESCRIPTION:
XS GIS Cut Line= 3
      2862896.39     10047900.88      2864169.14     10046677.85
      2865879.36     10046200.58
#Sta/Elev= 30
  3461.7 1461.36  3915.7 1441.16  3990.2 1437.25  4295.8 1426.67  4590.4 1420.37
  4854.3 1415.48    4911 1410.24  5000.1 1397.84  5002.8 1397.34  5006.1 1397.84
  5031.4 1405.11  5087.7 1409.46  5130.1  1416.2  5171.6 1417.01  5408.7 1418.81
  5714.1 1425.52  5838.7 1426.22  5952.9 1431.64  5994.4  1431.1  6129.4 1438.64
  6181.3 1438.51    6228 1441.77  6409.3 1445.87  6453.8 1449.49    6555 1452.01
  6648.5 1458.87  6949.6 1473.72  6973.8 1478.35  6991.1 1488.07  7002.4 1490.26
#Mann= 7 ,-1 , 0
  3461.7     .05       0  3915.7      .1       0  3990.2     .05       0
  4590.4     .16       0  5000.1     .07       0  5006.1     .16       0
  5171.6     .05       0
Bank Sta=4911,5087.7
XS Rating Curve= 0 ,0
Exp/Cntr=0.3,0.1

Type RM Length L Ch R = 1 ,7558    ,499,499,499
BEGIN DESCRIPTION:
MIDDLE FORK ROCKY CREEK 12.0
END DESCRIPTION:
XS GIS Cut Line= 3
      2863085.27     10047811.41      2864348.12     10047314.22
      2865590.95     10046548.64
#Sta/Elev= 30
  3489.5 1452.17  3665.4 1445.23  3750.9 1439.15  3776.3 1439.94  3871.8 1432.51
  4123.1 1422.93  4315.4 1419.09  4406.4 1419.66    4616 1412.83  4771.8 1412.93
  4855.1 1410.83  4882.3 1408.08  4953.1  1401.7  4976.9  1392.9  4989.3 1392.81
    4992 1392.31  4995.3 1392.81  5013.3 1393.26    5081 1406.01  5117.2 1408.23
  5238.8 1415.13  5340.4 1420.92    5734 1437.58  5996.7 1445.34  6060.5 1443.92
  6112.6 1446.89  6191.9 1447.71  6228.6 1451.61  6249.8 1449.52  6306.4 1454.68
#Mann= 8 ,-1 , 0
  3489.5     .05       0  3776.3      .1       0  3871.8     .05       0
  4953.1     .16       0  4989.3     .07       0  4995.3     .16       0
  5013.3      .1       0  5238.8     .05       0
Bank Sta=4882.3,5117.2
XS Rating Curve= 0 ,0
Exp/Cntr=0.3,0.1

Type RM Length L Ch R = 1 ,7059    ,588,588,588
BEGIN DESCRIPTION:
MIDDLE FORK ROCKY CREEK 11.0
END DESCRIPTION:
XS GIS Cut Line= 2
      2862995.86     10048040.08      2865402.08     10047503.16
#Sta/Elev= 30
  3297.4 1459.44  3361.5 1455.67    3382 1456.74  3615.1 1446.82  3868.9  1432.1
  3871.3 1431.96  3955.8 1426.11  4032.3 1423.44  4119.7 1420.24  4345.2 1416.45
  4416.9 1413.35  4868.8 1405.88    4912 1402.24  4970.2 1398.54  5001.3 1392.17
    5004 1391.67  5007.3 1392.17  5041.9 1402.92  5047.7 1409.15  5052.9 1409.23
  5062.4 1414.88  5072.6 1417.34  5096.3 1419.74  5113.6    1425  5139.8 1428.77
  5328.9 1438.45  5415.8 1441.65  5523.4 1448.77    5670 1455.15  5762.8 1459.68
#Mann= 9 ,-1 , 0
  3297.4     .05       0  3615.1      .1       0  3868.9     .05       0
  3871.3      .1       0  4032.3     .05       0    4912     .16       0
  5001.3     .07       0  5007.3     .16       0    5670      .1       0
Bank Sta=4868.8,5047.7
XS Rating Curve= 0 ,0
Exp/Cntr=0.3,0.1

Type RM Length L Ch R = 1 ,6471    ,710,710,710
BEGIN DESCRIPTION:
MIDDLE FORK ROCKY CREEK 10.0
END DESCRIPTION:
XS GIS Cut Line= 3
      2863085.35     10048288.68      2864477.39     10048358.28
      2865690.49     10047821.33
#Sta/Elev= 30
  3329.6 1455.62  3437.7 1451.08  3536.3 1447.87  3634.9 1443.14  3813.3 1433.12
  3893.4 1426.11  4029.2 1420.58  4335.5 1413.32  4494.2  1413.2  4938.7 1400.79
    4970 1399.75    4987 1396.43  4998.7 1388.58  5005.9 1388.36  5008.6 1387.86
  5011.9 1388.36    5022 1388.99  5039.8 1394.72  5068.6 1398.75  5097.4 1397.62
  5107.3 1401.03  5115.2 1408.38  5129.2 1412.98  5161.8 1419.55  5249.5 1422.39
  5599.1 1446.14  5680.7 1450.44  5932.9 1465.13  5979.5 1469.69    6050 1472.57
#Mann= 10 ,-1 , 0
  3329.6     .16       0  3437.7     .05       0  3536.3      .1       0
  3634.9     .16       0  4029.2      .1       0  4938.7     .16       0
  5005.9     .07       0  5011.9     .16       0  5599.1     .05       0
  5680.7     .16       0
Bank Sta=4970,5068.6
XS Rating Curve= 0 ,0
Exp/Cntr=0.3,0.1

Type RM Length L Ch R = 1 ,5761    ,425,425,425
BEGIN DESCRIPTION:
MIDDLE FORK ROCKY CREEK 9.0
END DESCRIPTION:
XS GIS Cut Line= 3
      2862916.31     10048885.28      2865481.67     10048925.05
      2865750.18     10048805.71
#Sta/Elev= 30
  3007.7    1454  3059.9 1451.13  3227.7 1445.15  3279.9 1445.45  3449.9 1433.02
  3477.7 1432.43  3640.7 1424.55  3689.9  1421.1  3786.8 1419.02    4130 1410.34
    4380 1406.82    4540 1406.68  4660.1 1402.56  4720.1 1398.58  4950.1 1393.49
  4997.1 1386.66  4999.8 1386.16  5003.1 1386.66  5020.1 1388.36  5040.1 1402.02
  5050.1 1406.78  5100.1 1415.03  5165.5 1419.81  5259.6 1420.63  5340.1 1423.38
  5370.1  1427.4  5447.1 1427.22  5550.2  1430.1  5646.5 1437.74  5867.2 1448.22
#Mann= 9 ,-1 , 0
  3007.7      .1       0  3059.9     .16       0  3477.7      .1       0
  3640.7     .16       0  3786.8      .1       0  4997.1     .07       0
  5003.1      .1       0  5259.6     .05       0  5447.1      .1       0
Bank Sta=4720.1,5040.1
XS Rating Curve= 0 ,0
Exp/Cntr=0.3,0.1

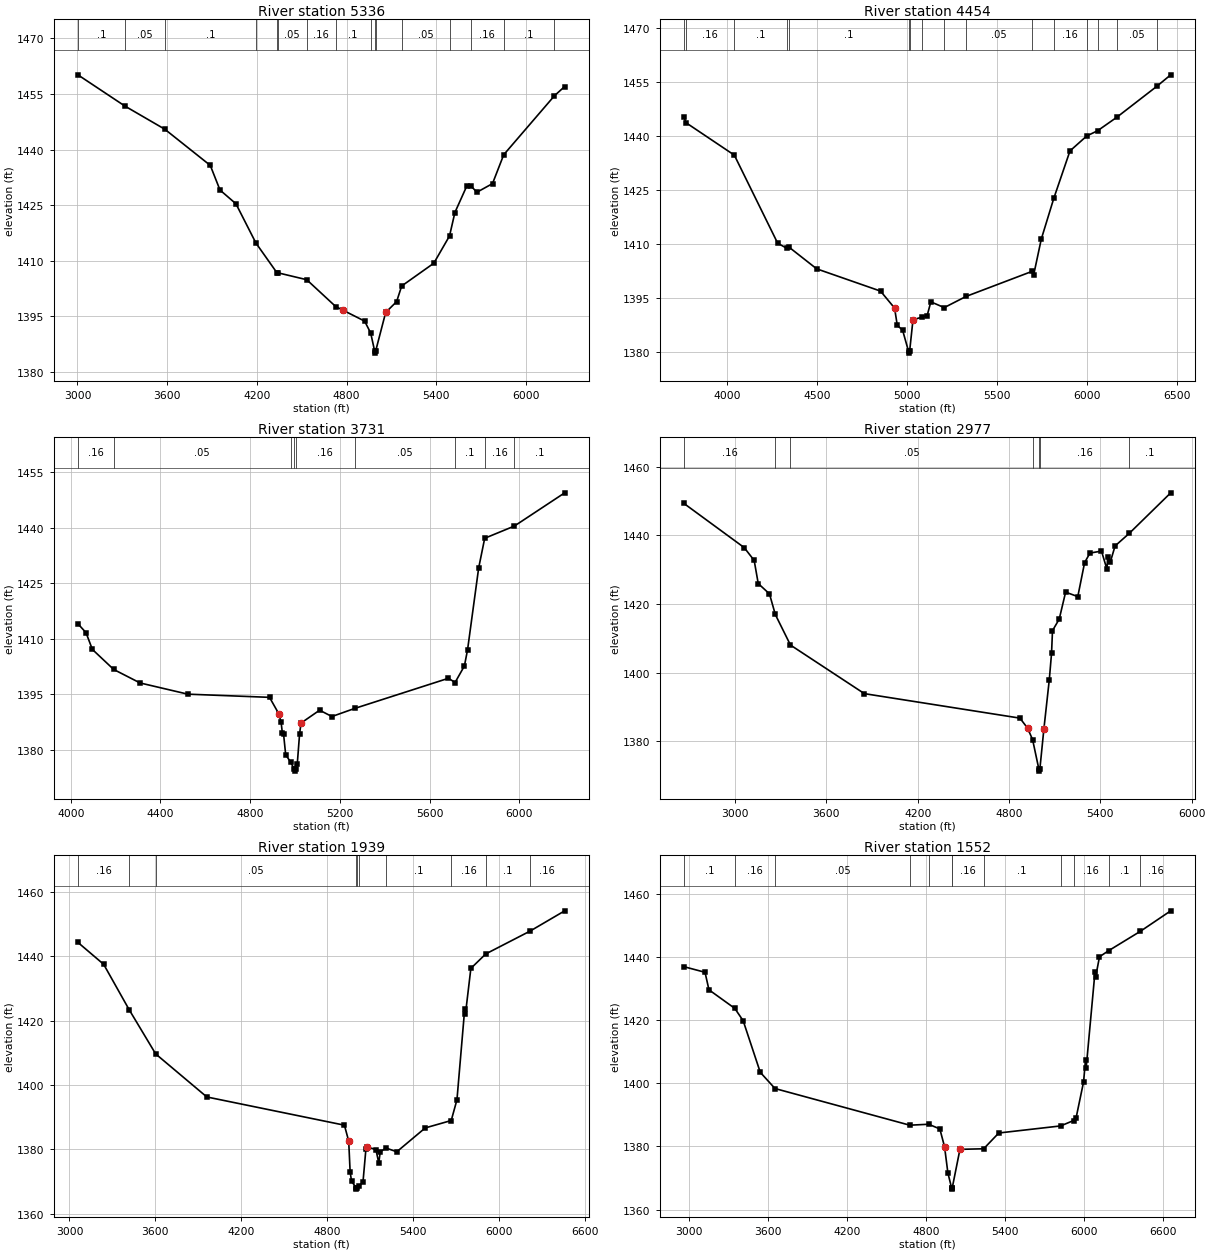
Type RM Length L Ch R = 1 ,5336    ,882,882,882
BEGIN DESCRIPTION:
MIDDLE FORK ROCKY CREEK 8.0
END DESCRIPTION:
XS GIS Cut Line= 3
      2863144.94     10050327.09      2864477.39     10049362.56
       2866078.3     10049183.57
#Sta/Elev= 30
    3003 1460.19  3318.4 1451.74    3584 1445.52  3888.5 1435.75  3953.5  1429.1
  4060.2 1425.39  4193.8  1414.8  4333.1 1406.85  4340.8 1406.77  4533.4 1404.91
    4727 1397.68  4773.6 1396.73  4920.7 1393.74  4961.3 1390.52  4988.1  1385.6
  4990.9  1385.1  4994.1  1385.6  5061.5 1396.07  5134.7    1399  5168.5 1403.21
  5383.5 1409.36  5488.6 1416.72  5524.4 1423.04  5604.9 1430.27  5631.5 1430.24
  5671.3  1428.5    5776 1430.84    5851 1438.63  6190.6 1454.56  6258.8 1457.04
#Mann= 16 ,-1 , 0
    3003      .1       0  3318.4     .05       0    3584      .1       0
  4193.8     .16       0  4333.1      .1       0  4340.8     .05       0
  4533.4     .16       0    4727      .1       0  4961.3     .16       0
  4988.1     .07       0  4994.1     .16       0  5168.5     .05       0
  5488.6      .1       0  5631.5     .16       0    5851      .1       0
  6190.6     .16       0
Bank Sta=4773.6,5061.5
XS Rating Curve= 0 ,0
Exp/Cntr=0.3,0.1

Type RM Length L Ch R = 1 ,4454    ,723,723,723
BEGIN DESCRIPTION:
MIDDLE FORK ROCKY CREEK 6.0
END DESCRIPTION:
XS GIS Cut Line= 2
      2863884.51     10050843.38      2866141.45     10049350.33
#Sta/Elev= 30
  3758.4 1445.29  3769.6 1443.69  4038.7 1434.68  4279.5 1410.26  4329.8 1408.85
  4343.5 1409.12  4496.2 1403.14  4851.3 1396.96  4929.5 1392.25  4944.5 1387.46
  4974.1 1386.11  5007.1 1380.25  5009.9 1379.75  5013.1 1380.25  5031.8    1389
  5083.7 1389.77    5110 1390.06  5131.1 1393.98  5205.5 1392.38  5327.3 1395.49
  5692.5 1402.41  5702.9 1401.52    5745 1411.38  5814.3 1422.66  5904.5 1435.85
  5997.8    1440  6057.8 1441.44  6165.2  1445.2  6386.2 1453.73  6464.5 1456.96
#Mann= 16 ,-1 , 0
  3758.4      .1       0  3769.6     .16       0  4038.7      .1       0
  4329.8     .16       0  4343.5      .1       0  5007.1     .07       0
  5013.1      .1       0  5083.7     .16       0  5205.5      .1       0
  5327.3     .05       0  5692.5      .1       0  5814.3     .16       0
  5997.8     .05       0  6057.8      .1       0  6165.2     .05       0
  6386.2      .1       0
Bank Sta=4929.5,5031.8
XS Rating Curve= 0 ,0
Exp/Cntr=0.3,0.1

Type RM Length L Ch R = 1 ,3731    ,754,754,754
BEGIN DESCRIPTION:
MIDDLE FORK ROCKY CREEK 5.0
END DESCRIPTION:
XS GIS Cut Line= 4
      2864825.44     10051251.77      2865382.23     10050764.57
      2865561.22     10050038.71       2866038.5     10049551.48
#Sta/Elev= 30
    4032 1414.08  4068.1 1411.67  4096.6 1407.13  4191.4 1401.72  4309.2 1398.06
  4521.8 1395.03    4886 1394.17  4927.2 1389.74  4937.5 1387.52  4943.4 1384.45
  4948.5  1384.3  4958.1 1378.63  4980.4 1376.63  4996.3 1374.71  4999.1 1374.21
  5002.3 1374.71  5009.6 1376.06  5019.9 1384.19  5026.3 1387.21  5109.3 1390.69
  5164.1 1388.98  5265.2 1391.16  5683.6 1399.33  5712.9 1398.18  5754.4 1402.64
  5768.5 1406.99  5818.1 1429.17    5845  1437.2  5977.2  1440.5  6201.5 1449.49
#Mann= 9 ,-1 , 0
    4032     .16       0  4191.4     .05       0  4980.4     .16       0
  4996.3     .07       0  5002.3     .16       0  5265.2     .05       0
  5712.9      .1       0    5845     .16       0  5977.2      .1       0
Bank Sta=4927.2,5026.3
XS Rating Curve= 0 ,0
Exp/Cntr=0.3,0.1

Type RM Length L Ch R = 1 ,2977    ,1038,1038,1038
BEGIN DESCRIPTION:
MIDDLE FORK ROCKY CREEK 4.0
END DESCRIPTION:
XS GIS Cut Line= 4
      2864139.35     10051480.49      2865730.25     10051311.46
      2866326.85     10050466.27      2866466.06     10049919.41
#Sta/Elev= 30
  2663.7 1449.34  3059.5 1436.47  3125.4 1432.72  3152.1 1425.97    3226 1422.95
  3264.2 1416.95  3363.9 1408.03  3849.5 1393.86  4871.4 1386.72  4921.8 1383.81
  4954.9 1380.44  4996.4 1371.76  4999.1 1371.26  5002.4 1371.76    5029 1383.55
  5064.7 1397.97  5079.4 1405.67  5085.6 1412.24  5129.8  1415.6  5171.8 1423.47
  5251.8 1422.16  5296.6 1432.08  5331.7 1434.86  5407.5 1435.44  5443.3 1430.13
  5448.4 1433.79  5465.8 1432.29  5496.8 1436.94  5590.1 1440.61  5862.4 1452.43
#Mann= 7 ,-1 , 0
  2663.7     .16       0  3264.2      .1       0  3363.9     .05       0
  4954.9     .16       0  4996.4     .07       0  5002.4     .16       0
  5590.1      .1       0
Bank Sta=4921.8,5029
XS Rating Curve= 0 ,0
Exp/Cntr=0.3,0.1

Type RM Length L Ch R = 1 ,1939    ,387,387,387
BEGIN DESCRIPTION:
MIDDLE FORK ROCKY CREEK 3.0
END DESCRIPTION:
XS GIS Cut Line= 4
      2864278.53     10051649.53       2866406.4      10051550.1
      2866754.42     10051241.85      2866893.34     10050448.01
#Sta/Elev= 30
  3058.9 1444.32    3239  1437.5  3417.4 1423.37  3602.5 1409.64  3959.8 1396.26
  4920.9 1387.49  4950.9 1382.55  4960.9 1372.97  4970.9 1370.05    5002 1368.11
  5004.8 1367.61    5008 1368.11    5025 1368.49    5051 1369.97    5071 1380.01
    5081 1380.73  5141.1  1379.9  5161.1 1375.74  5171.1 1379.18  5211.1 1380.39
  5286.8 1379.22  5485.7 1386.64  5667.2 1388.94  5707.2 1395.39  5761.6 1423.76
  5766.7 1422.11  5804.4 1436.24  5908.4 1440.73  6217.7 1447.82  6459.9 1454.13
#Mann= 10 ,-1 , 0
  3058.9     .16       0  3417.4      .1       0  3602.5     .05       0
    5002    .035       0    5008     .05       0    5025     .16       0
  5211.1      .1       0  5667.2     .16       0  5908.4      .1       0
  6217.7     .16       0
Bank Sta=4950.9,5081
XS Rating Curve= 0 ,0
Exp/Cntr=0.3,0.1

Type RM Length L Ch R = 1 ,1552    ,735,735,735
BEGIN DESCRIPTION:
MIDDLE FORK ROCKY CREEK 2.0
END DESCRIPTION:
XS GIS Cut Line= 4
      2864377.99     10051997.55      2866063.41     10051999.32
      2866779.55     10051738.91       2866953.1     10050497.42
#Sta/Elev= 30
  2959.7 1436.94  3120.2 1435.16  3150.2 1429.61  3346.5 1423.73  3410.2 1419.82
  3540.2 1403.48  3652.4 1398.34  4676.9 1386.73  4820.2 1387.03  4905.4 1385.55
  4941.3  1379.9  4966.6 1371.61  4994.2 1366.98  4996.9 1366.48  5000.2 1366.98
  5058.3 1379.08  5238.5 1379.26  5353.6 1384.26  5823.7  1386.5  5922.4 1388.21
  5941.7 1389.14    5998 1400.41  6013.2 1407.45  6018.2    1405  6084.7 1435.15
  6089.7 1433.64  6119.2 1440.08  6188.5    1442  6429.1 1448.12  6660.7 1454.63
#Mann= 12 ,-1 , 0
  2959.7      .1       0  3346.5     .16       0  3652.4     .05       0
  4676.9      .1       0  4820.2     .16       0  4994.2     .07       0
  5000.2     .16       0  5238.5      .1       0  5823.7     .05       0
  5922.4     .16       0  6188.5      .1       0  6429.1     .16       0
Bank Sta=4941.3,5058.3
XS Rating Curve= 0 ,0
Exp/Cntr=0.3,0.1

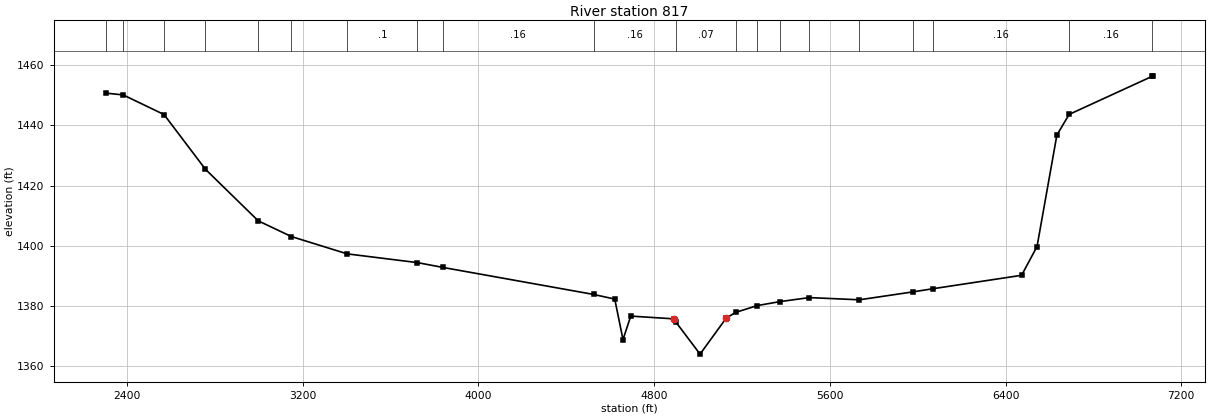
Type RM Length L Ch R = 1 ,817     ,0,0,0
BEGIN DESCRIPTION:
MIDDLE FORK ROCKY CREEK 1.0
END DESCRIPTION:
XS GIS Cut Line= 4
      2864517.18     10053727.68        2867003.     10052325.68
      2867181.98     10051808.62      2867062.76     10050447.52
#Sta/Elev= 30
  2304.1 1450.67  2382.7 1450.08  2568.8 1443.56  2757.4 1425.39  2997.8 1408.28
  3148.5 1403.08  3402.7 1397.33  3722.3 1394.43  3838.4 1392.83  4524.3 1383.87
  4620.8 1382.32  4658.3 1368.88  4693.6 1376.68  4890.8 1375.76  4900.2 1374.59
  5009.1 1364.06  5127.8 1375.97  5170.7  1377.9  5269.6 1380.17  5372.1 1381.48
  5506.9 1382.82  5734.6 1382.09    5978 1384.71  6071.6 1385.79    6473 1390.22
  6543.3 1399.77  6633.6 1436.74  6689.5 1443.61  7068.2 1456.27  7071.5 1456.41
#Mann= 20 ,-1 , 0
  2304.1     .05       0  2382.7     .05       0  2568.8      .1       0
  2757.4     .05       0  2997.8      .1       0  3148.5     .05       0
  3402.7      .1       0  3722.3     .05       0  3838.4     .16       0
  4524.3     .16       0  4900.2     .07       0  5170.7     .16       0
  5269.6      .1       0  5372.1     .16       0  5506.9      .1       0
  5734.6     .16       0    5978      .1       0  6071.6     .16       0
  6689.5     .16       0  7068.2      .1       0
Bank Sta=4890.8,5127.8
XS Rating Curve= 0 ,0
Exp/Cntr=0.3,0.1

Chan Stop Cuts=-1
Use User Specified Reach Order=0
Composite Channel Slope=5