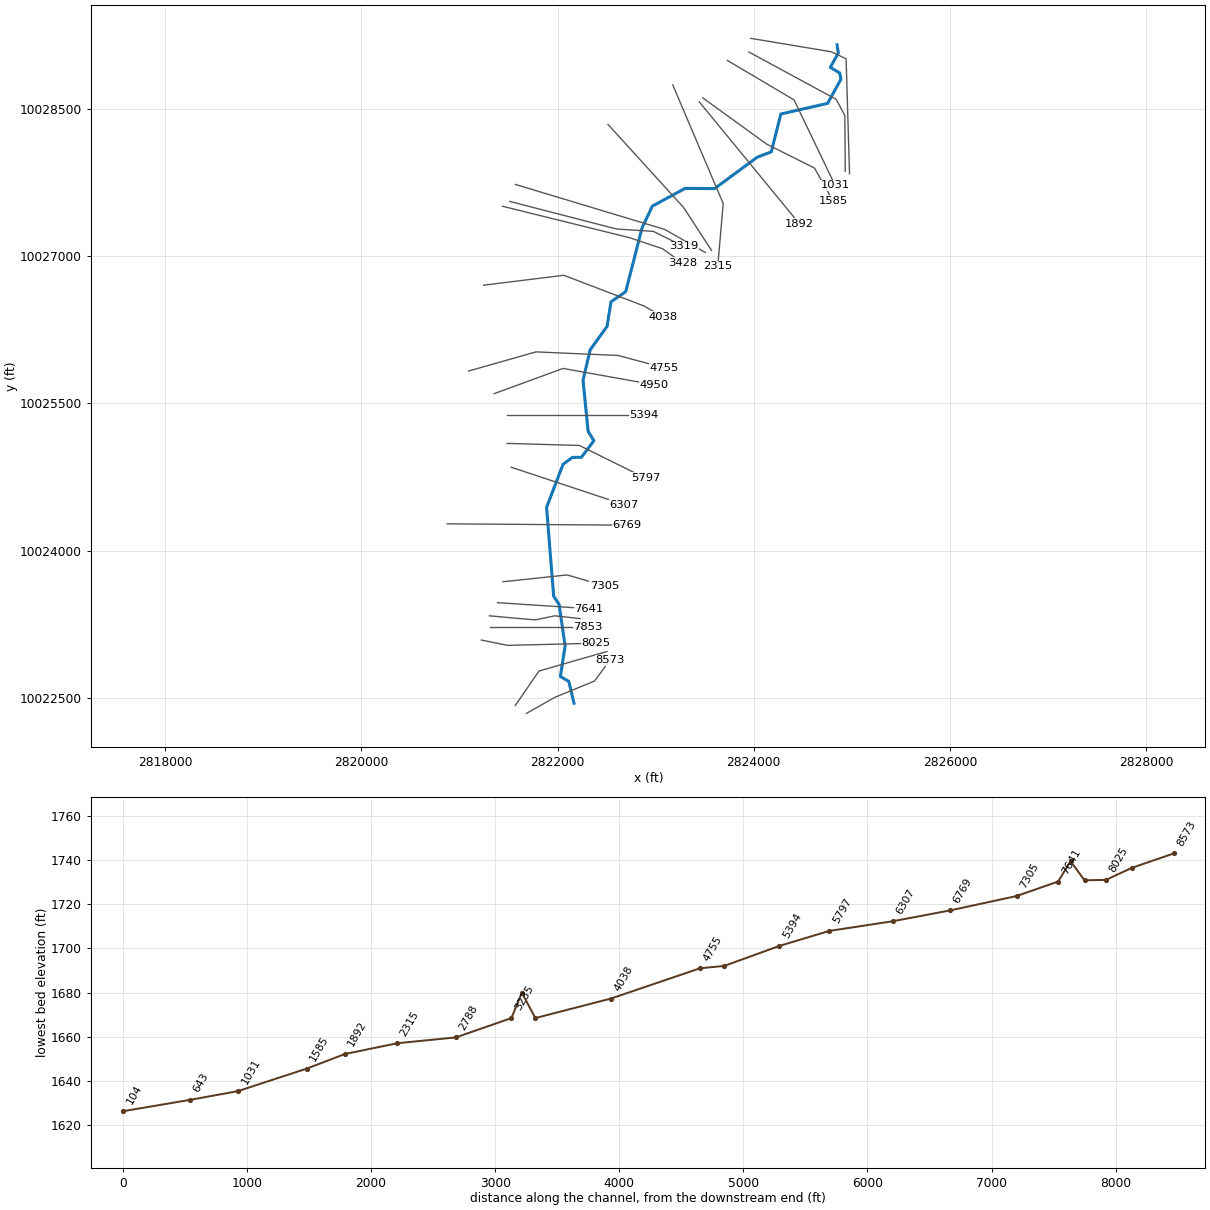
--- MIDDLE FORK THREEMILE CREEK.prj (project) ---

Proj Title=MIDDLE FORK THREEMILE CREEK Base Level Engineering
Current Plan=p01
Default Exp/Contr=0.3,0.1
English Units
Geom File=g01
Flow File=f01
Plan File=p01
BEGIN DESCRIPTION:
MIDDLE FORK THREEMILE CREEK
END DESCRIPTION:

--- MIDDLE FORK THREEMILE CREEK.p01 (plan) ---

Plan Title=Multiple Run
Short Identifier=Multiple
Geom File=g01
Flow File=f01
Subcritical Flow
K Sum by GR= 0
Std Step Tol= 0.01
Critical Tol= 0.01
Num of Std Step Trials= 20
Max Error Tol= 0.3
Flow Tol Ratio= 0.001
Split Flow NTrial= 30
Split Flow Tol= 0.02
Split Flow Ratio= 0.02
Log Output Level= 0
Friction Slope Method= 1
Unsteady Friction Slope Method= 2
Unsteady Bridges Friction Slope Method= 1
Parabolic Critical Depth
Global Vel Dist=  1 , 1 , 1
Global Log Level= 0
CheckData=True
Encroach Param= -1, 0, 0, 0
BEGIN DESCRIPTION:
Multiple Run
END DESCRIPTION:

--- MIDDLE FORK THREEMILE CREEK.f01 (steady flow) ---

Flow Title=Multiple
Number of Profiles=7
Profile Names=10-year,25-year,50-year,1pct_min,100-year,1pct_plu,500-year
River Rch & RM= MIDDLE FORK THRE,Reach-1,8573
     938    1373    1755    1643    2222    3005    3576
River Rch & RM= MIDDLE FORK THRE,Reach-1,7853
    1410    2105    2724    2579    3488    4718    5743
River Rch & RM= MIDDLE FORK THRE,Reach-1,4038
    1547    2313    2998    2840    3840    5194    6330
Boundary for River Rch & Prof#=MIDDLE FORK THRE,Reach-1,1
Up Type=0
Dn Type=3
Dn Slope=0.005
Boundary for River Rch & Prof#=MIDDLE FORK THRE,Reach-1,2
Up Type=0
Dn Type=3
Dn Slope=0.005
Boundary for River Rch & Prof#=MIDDLE FORK THRE,Reach-1,3
Up Type=0
Dn Type=3
Dn Slope=0.005
Boundary for River Rch & Prof#=MIDDLE FORK THRE,Reach-1,4
Up Type=0
Dn Type=3
Dn Slope=0.005
Boundary for River Rch & Prof#=MIDDLE FORK THRE,Reach-1,5
Up Type=0
Dn Type=3
Dn Slope=0.005
Boundary for River Rch & Prof#=MIDDLE FORK THRE,Reach-1,6
Up Type=0
Dn Type=3
Dn Slope=0.005
Boundary for River Rch & Prof#=MIDDLE FORK THRE,Reach-1,7
Up Type=0
Dn Type=3
Dn Slope=0.005

--- MIDDLE FORK THREEMILE CREEK.g01 (geometry) ---

Geom Title=Existing Conditions

River Reach=MIDDLE FORK THRE,Reach-1
Reach XY= 30
      2822168.22     10022444.56      2822114.62     10022667.87
      2822029.07     10022717.48      2822077.13     10023027.36
      2822016.68     10023450.00      2821960.97     10023533.71
      2821888.47     10024440.55      2822056.53     10024879.91
      2822149.85     10024949.50      2822244.25     10024951.64
      2822370.67     10025120.57      2822311.81     10025214.64
      2822259.92     10025736.65      2822332.89     10026046.64
      2822504.84     10026285.23      2822545.00     10026535.64
      2822694.81     10026637.99      2822861.32     10027288.94
      2822966.08     10027510.22      2823299.73     10027690.87
      2823600.88     10027689.28      2824035.52     10028009.25
      2824178.16     10028063.52      2824275.47     10028449.03
      2824751.92     10028557.18      2824887.80     10028803.67
      2824875.17     10028867.03      2824779.59     10028924.16
      2824861.22     10029070.46      2824848.47     10029153.73

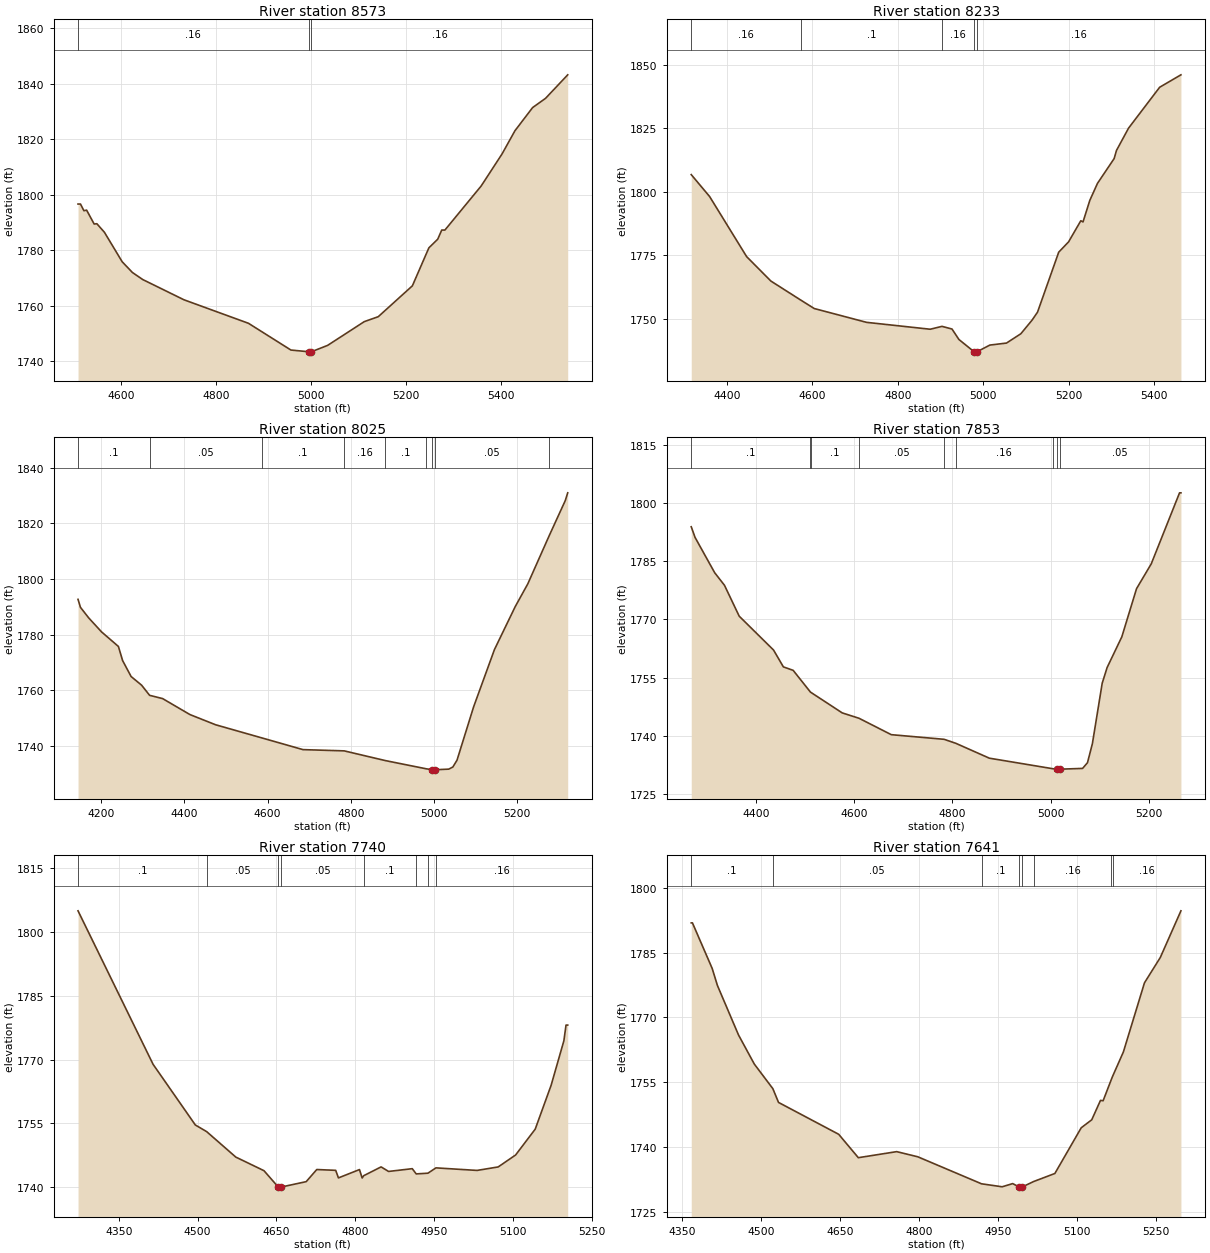
Type RM Length L Ch R = 1,8573,340,340,340
BEGIN DESCRIPTION:
MIDDLE FORK THREEMILE CREEK 17.0
END DESCRIPTION:
XS GIS Cut Line= 4
      2821684.39     10022341.67      2821970.82     10022504.41
      2822377.07     10022671.08      2822533.32     10022883.32
#Sta/Elev= 30
  4508.7 1796.66  4513.9 1796.66  4521.1 1794.26  4526.8 1794.47  4542.7 1789.47
  4548.4 1789.58  4564.3 1786.51  4601.8 1775.88  4623.4 1772.02  4645.1 1769.49
  4731.9 1762.21  4868.0 1753.74  4957.4 1744.12  4994.7 1743.51  4997.5 1743.01
  5000.7 1743.51  5034.8 1745.80  5112.1 1754.35  5141.5 1756.12  5213.4 1767.23
  5248.2 1780.90  5266.8 1784.00  5275.3 1787.30  5282.0 1787.30  5358.4 1803.16
  5402.3 1814.66  5429.6 1823.04  5466.8 1831.37  5494.1 1834.70  5540.8 1843.16
#Mann=3,-1,0
  4508.7    0.16       0  4994.7    0.07       0  5000.7    0.16       0
Bank Sta=4994.7,5000.7
Exp/Cntr=0.3,0.1

Type RM Length L Ch R = 1,8233,208,208,208
BEGIN DESCRIPTION:
Mapping XS 824715dd
END DESCRIPTION:
XS GIS Cut Line= 4
      2821569.78     10022422.38      2821810.67     10022772.64
      2822134.89     10022866.39      2822503.39     10022971.86
#Sta/Elev= 30
  4316.7 1806.75  4359.7 1798.12  4446.3 1774.46  4503.1 1764.83  4574.5 1757.18
  4604.6 1754.01  4727.0 1748.57  4875.9 1745.86  4903.5 1746.99  4926.9 1745.94
  4943.1 1741.82  4978.9 1736.95  4981.7 1736.45  4984.9 1736.95  5015.5 1739.62
  5054.4 1740.41  5088.0 1744.08  5114.2 1749.43  5127.0 1752.57  5176.6 1776.20
  5199.7 1780.27  5228.3 1788.58  5233.5 1788.13  5249.4 1796.61  5267.3 1803.30
  5306.3 1813.06  5311.9 1816.31  5340.0 1825.04  5412.8 1841.15  5462.6 1846.05
#Mann=5,-1,0
  4316.7    0.16       0  4574.5     0.1       0  4903.5    0.16       0
  4978.9    0.07       0  4984.9    0.16       0
Bank Sta=4978.9,4984.9
Exp/Cntr=0.3,0.1

Type RM Length L Ch R = 1,8025,172,172,172
BEGIN DESCRIPTION:
Mapping XS 0a78c1d6
END DESCRIPTION:
XS GIS Cut Line= 3
      2821223.40     10023089.05      2821490.36     10023034.79
      2822394.38     10023056.47
#Sta/Elev= 30
  4144.4 1792.70  4150.3 1789.82  4170.0 1786.05  4201.0 1781.00  4241.4 1775.79
  4251.6 1770.70  4272.0 1764.98  4297.1 1761.89  4316.4 1758.24  4347.7 1757.06
  4413.3 1751.33  4474.9 1747.67  4587.0 1742.91  4685.0 1738.74  4784.1 1738.29
  4882.7 1734.81  4981.3 1731.85  4996.1 1731.52  4998.9 1731.02  5002.1 1731.52
  5035.1 1731.73  5045.1 1732.50  5055.1 1734.95  5095.1 1754.15  5145.1 1774.68
  5195.1 1790.12  5225.2 1798.26  5277.0 1815.68  5315.2 1828.14  5321.1 1830.94
#Mann=9,-1,0
  4144.4     0.1       0  4316.4    0.05       0  4587.0     0.1       0
  4784.1    0.16       0  4882.7     0.1       0  4981.3    0.05       0
  4996.1   0.033       0  5002.1    0.05       0  5277.0    0.16       0
Bank Sta=4996.1,5002.1
Exp/Cntr=0.3,0.1

Type RM Length L Ch R = 1,7853,113,113,113
BEGIN DESCRIPTION:
Mapping XS 509bc017
END DESCRIPTION:
XS GIS Cut Line= 2
      2821310.64     10023217.88      2822308.94     10023217.88
#Sta/Elev= 30
  4267.6 1793.91  4275.4 1791.16  4315.4 1782.05  4335.4 1778.80  4365.4 1770.83
  4435.4 1762.09  4455.4 1757.75  4475.4 1756.85  4510.7 1751.23  4511.1 1751.20
  4575.4 1745.87  4609.7 1744.48  4675.4 1740.25  4783.2 1739.05  4807.0 1738.02
  4875.4 1734.18  5004.3 1731.47  5012.4 1731.34  5015.2 1730.84  5018.4 1731.34
  5065.4 1731.54  5075.4 1733.02  5085.4 1737.93  5105.4 1753.53  5115.4 1757.57
  5145.4 1765.50  5175.4 1777.93  5205.4 1784.34  5263.1 1802.67  5265.9 1802.67
#Mann=9,-1,0
  4267.6     0.1       0  4510.7    0.05       0  4511.1     0.1       0
  4609.7    0.05       0  4783.2     0.1       0  4807.0    0.16       0
  5004.3    0.05       0  5012.4    0.07       0  5018.4    0.05       0
Bank Sta=5012.4,5018.4
Exp/Cntr=0.3,0.1

Type RM Length L Ch R = 1,7740,99,99,99
BEGIN DESCRIPTION:
Mapping XS 5a6cb0b4
END DESCRIPTION:
XS GIS Cut Line= 4
      2821306.29     10023335.64      2821771.53     10023293.97
      2821972.92     10023335.64      2822229.86     10023307.86
#Sta/Elev= 30
  4272.6 1805.00  4415.3 1768.90  4495.7 1754.62  4517.2 1753.06  4572.6 1747.07
  4626.2 1743.87  4653.3 1740.03  4656.1 1739.53  4659.3 1740.03  4706.5 1741.29
  4726.6 1744.14  4762.6 1743.95  4767.8 1742.17  4807.8 1744.13  4812.9 1742.15
  4815.9 1742.69  4848.9 1744.76  4863.1 1743.69  4908.2 1744.34  4915.7 1743.11
  4938.0 1743.28  4953.2 1744.53  5031.4 1743.93  5071.6 1744.75  5104.7 1747.56
  5142.0 1753.64  5172.2 1763.94  5196.5 1774.43  5200.6 1778.12  5203.8 1778.12
#Mann=8,-1,0
  4272.6     0.1       0  4517.2    0.05       0  4653.3    0.07       0
  4659.3    0.05       0  4815.9     0.1       0  4915.7    0.16       0
  4938.0     0.1       0  4953.2    0.16       0
Bank Sta=4653.3,4659.3
Exp/Cntr=0.3,0.1

Type RM Length L Ch R = 1,7641,336,336,336
BEGIN DESCRIPTION:
Mapping XS 1cbfa184
END DESCRIPTION:
XS GIS Cut Line= 2
      2821388.77     10023469.61      2822317.59     10023408.85
#Sta/Elev= 30
  4366.7 1791.85  4369.0 1791.85  4406.5 1781.32  4416.5 1777.37  4456.6 1765.92
  4486.6 1759.20  4521.9 1753.50  4532.6 1750.33  4647.0 1742.96  4684.3 1737.55
  4757.2 1738.95  4797.3 1737.76  4918.5 1731.51  4957.7 1730.82  4977.7 1731.56
  4989.8 1730.78  4992.6 1730.28  4995.8 1730.78  5017.6 1732.04  5057.9 1733.90
  5108.0 1744.47  5128.0 1746.32  5144.6 1750.80  5149.6 1750.72  5165.1 1755.60
  5167.5 1756.33  5188.1 1762.00  5228.2 1777.99  5258.3 1783.85  5297.5 1794.64
#Mann=8,-1,0
  4366.7     0.1       0  4521.9    0.05       0  4918.5     0.1       0
  4989.8    0.07       0  4995.8     0.1       0  5017.6    0.16       0
  5165.1     0.1       0  5167.5    0.16       0
Bank Sta=4989.8,4995.8
Exp/Cntr=0.3,0.1

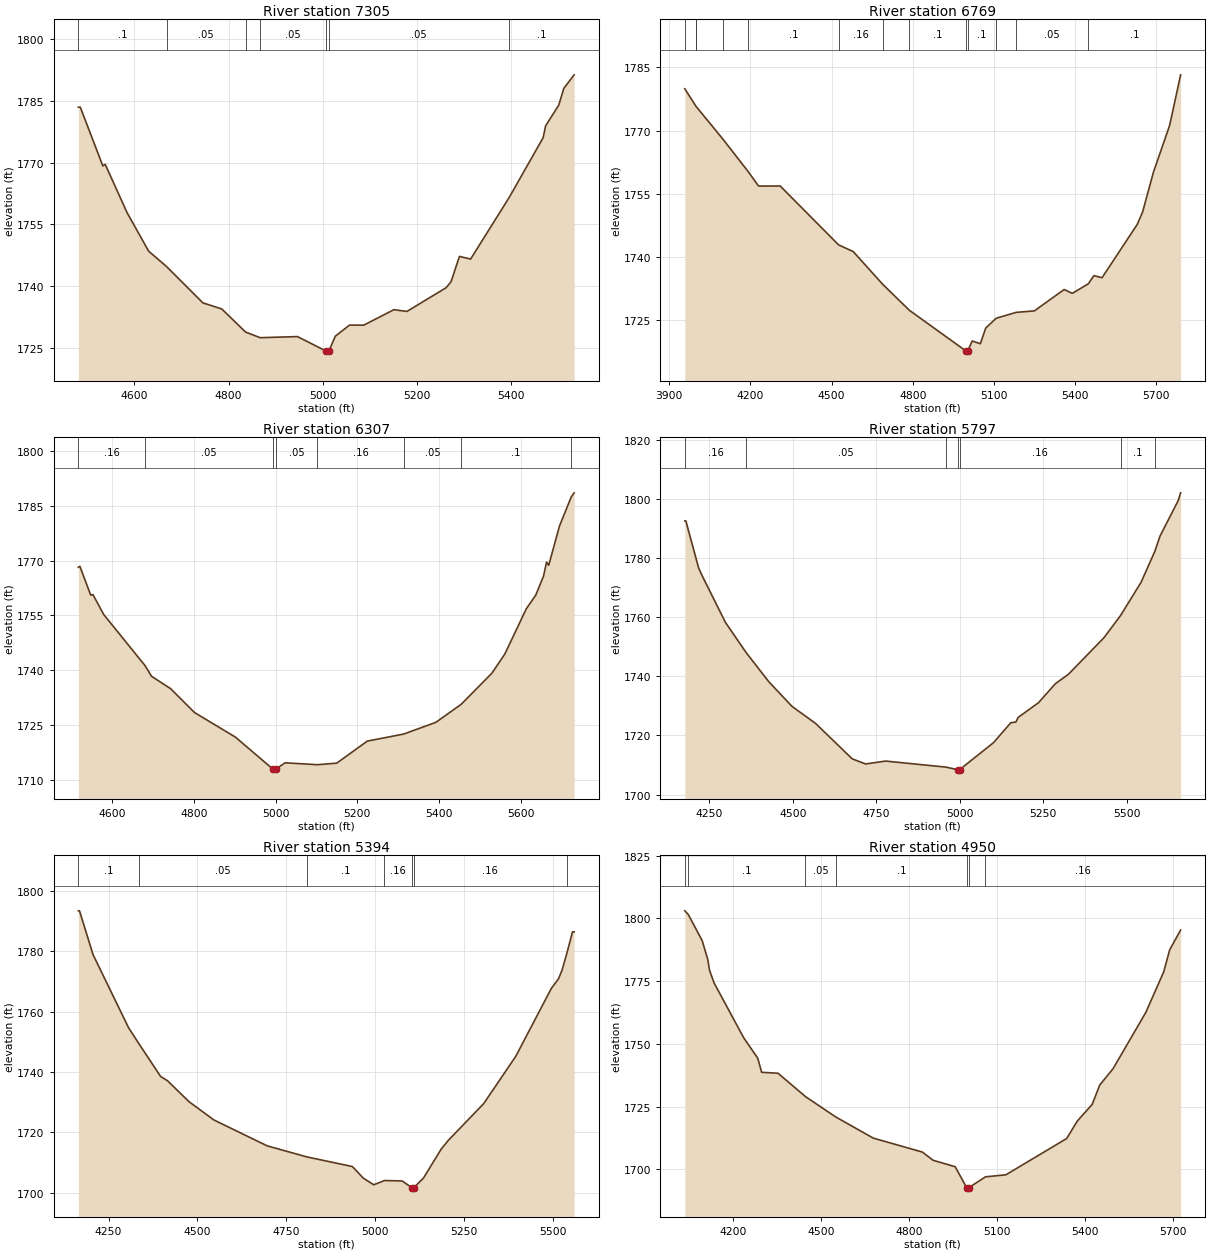
Type RM Length L Ch R = 1,7305,536,536,536
BEGIN DESCRIPTION:
MIDDLE FORK THREEMILE CREEK 16.0
END DESCRIPTION:
XS GIS Cut Line= 3
      2821445.13     10023682.86      2822097.92     10023752.31
      2822479.82     10023641.21
#Sta/Elev= 30
  4480.6 1783.45  4484.8 1783.45  4532.7 1769.19  4537.7 1769.58  4584.5 1757.77
  4630.2 1748.47  4668.3 1744.73  4745.4 1735.92  4785.6 1734.44  4836.3 1728.82
  4867.2 1727.46  4946.5 1727.73  5007.3 1724.21  5010.1 1723.71  5013.3 1724.21
  5027.0 1727.83  5057.2 1730.52  5087.3 1730.50  5151.6 1734.26  5179.3 1733.84
  5262.6 1739.60  5273.0 1741.04  5290.9 1747.20  5314.7 1746.56  5396.5 1761.49
  5468.9 1776.05  5474.1 1778.91  5502.1 1783.96  5512.8 1788.02  5534.8 1791.31
#Mann=7,-1,0
  4480.6     0.1       0  4668.3    0.05       0  4836.3     0.1       0
  4867.2    0.05       0  5007.3   0.035       0  5013.3    0.05       0
  5396.5     0.1       0
Bank Sta=5007.3,5013.3
Exp/Cntr=0.3,0.1

Type RM Length L Ch R = 1,6769,462,462,462
BEGIN DESCRIPTION:
MIDDLE FORK THREEMILE CREEK 15.0
END DESCRIPTION:
XS GIS Cut Line= 2
      2820875.71     10024273.14      2822709.06     10024259.25
#Sta/Elev= 30
  3957.1 1779.95  3998.0 1775.83  3998.2 1775.81  4098.7 1767.94  4191.6 1760.28
  4229.9 1756.85  4309.9 1756.87  4525.9 1742.89  4579.9 1741.31  4688.9 1733.54
  4787.5 1727.37  4996.9 1717.70  4999.6 1717.20  5002.9 1717.70  5019.9 1720.08
  5049.9 1719.44  5069.9 1723.15  5108.3 1725.47  5182.3 1726.87  5249.9 1727.23
  5359.9 1732.30  5389.9 1731.39  5449.2 1733.65  5469.9 1735.59  5499.9 1735.10
  5629.9 1747.73  5649.9 1750.70  5689.9 1760.13  5749.9 1771.26  5790.5 1783.26
#Mann=13,-1,0
  3957.1     0.1       0  3998.0    0.16       0  3998.2     0.1       0
  4098.7    0.16       0  4191.6     0.1       0  4525.9    0.16       0
  4688.9    0.05       0  4787.5     0.1       0  4996.9    0.07       0
  5002.9     0.1       0  5108.3    0.16       0  5182.3    0.05       0
  5449.2     0.1       0
Bank Sta=4996.9,5002.9
Exp/Cntr=0.3,0.1

Type RM Length L Ch R = 1,6307,510,510,510
BEGIN DESCRIPTION:
MIDDLE FORK THREEMILE CREEK 14.0
END DESCRIPTION:
XS GIS Cut Line= 2
      2821528.44     10024849.54      2822679.50     10024468.16
#Sta/Elev= 30
  4517.7 1768.17  4521.6 1768.42  4548.1 1760.50  4553.3 1760.71  4579.8 1755.22
  4680.7 1741.24  4696.8 1738.29  4743.5 1734.89  4801.7 1728.37  4902.0 1721.61
  4994.1 1712.80  4996.9 1712.30  5000.1 1712.80  5023.4 1714.58  5102.5 1714.06
  5149.8 1714.49  5224.3 1720.52  5313.3 1722.46  5392.1 1725.67  5454.0 1730.61
  5529.0 1739.13  5560.7 1744.38  5613.3 1756.80  5636.4 1760.53  5655.5 1765.79
  5662.8 1769.59  5668.1 1768.72  5694.5 1779.50  5723.0 1787.39  5730.3 1788.57
#Mann=8,-1,0
  4517.7    0.16       0  4680.7    0.05       0  4994.1   0.035       0
  5000.1    0.05       0  5102.5    0.16       0  5313.3    0.05       0
  5454.0     0.1       0  5723.0    0.16       0
Bank Sta=4994.1,5000.1
Exp/Cntr=0.3,0.1

Type RM Length L Ch R = 1,5797,403,403,403
BEGIN DESCRIPTION:
MIDDLE FORK THREEMILE CREEK 13.0
END DESCRIPTION:
XS GIS Cut Line= 3
      2821486.85     10025092.58      2822222.92     10025071.75
      2822894.71     10024739.32
#Sta/Elev= 30
  4176.0 1792.60  4179.3 1792.60  4217.6 1776.63  4227.6 1774.16  4297.7 1758.29
  4359.9 1748.05  4427.7 1738.21  4497.7 1729.81  4567.8 1724.10  4677.8 1712.09
  4717.8 1710.37  4777.9 1711.34  4958.4 1709.30  4993.7 1708.44  4996.4 1707.94
  4999.7 1708.44  5101.1 1717.57  5152.9 1724.31  5168.4 1724.56  5175.2 1726.14
  5235.7 1731.06  5286.7 1737.54  5325.4 1740.69  5431.8 1753.04  5481.9 1760.60
  5543.4 1771.85  5584.3 1782.23  5600.2 1787.49  5654.9 1799.55  5661.9 1802.12
#Mann=7,-1,0
  4176.0    0.16       0  4359.9    0.05       0  4958.4    0.16       0
  4993.7    0.07       0  4999.7    0.16       0  5481.9     0.1       0
  5584.3    0.16       0
Bank Sta=4993.7,4999.7
Exp/Cntr=0.3,0.1

Type RM Length L Ch R = 1,5394,444,444,444
BEGIN DESCRIPTION:
MIDDLE FORK THREEMILE CREEK 12.0
END DESCRIPTION:
XS GIS Cut Line= 2
      2821486.83     10025384.25      2822882.63     10025384.25
#Sta/Elev= 30
  4165.0 1793.48  4168.3 1793.48  4206.6 1778.90  4306.6 1754.66  4336.1 1749.30
  4396.6 1738.53  4416.6 1737.05  4476.6 1730.15  4546.6 1724.09  4696.6 1715.50
  4807.6 1711.85  4936.6 1708.63  4966.6 1704.85  4996.6 1702.58  5026.7 1703.99
  5076.6 1703.86  5103.6 1701.64  5106.4 1701.14  5109.6 1701.64  5136.6 1704.81
  5186.6 1714.44  5206.6 1717.33  5306.6 1729.58  5396.6 1745.24  5496.6 1767.75
  5516.6 1770.90  5526.6 1773.74  5539.6 1779.10  5556.2 1786.50  5560.8 1786.50
#Mann=7,-1,0
  4165.0     0.1       0  4336.1    0.05       0  4807.6     0.1       0
  5026.7    0.16       0  5103.6    0.07       0  5109.6    0.16       0
  5539.6     0.1       0
Bank Sta=5103.6,5109.6
Exp/Cntr=0.3,0.1

Type RM Length L Ch R = 1,4950,195,195,195
BEGIN DESCRIPTION:
MIDDLE FORK THREEMILE CREEK 11.0
END DESCRIPTION:
XS GIS Cut Line= 3
      2821354.82     10025599.51      2822056.25     10025856.47
      2822985.15     10025690.10
#Sta/Elev= 30
  4035.3 1802.97  4047.1 1801.52  4094.5 1791.11  4113.7 1783.59  4119.6 1779.33
  4135.0 1774.28  4236.4 1752.35  4284.1 1744.24  4297.4 1738.63  4353.1 1738.27
  4446.8 1728.96  4550.2 1720.83  4678.2 1712.41  4845.5 1706.85  4882.0 1703.58
  4957.3 1701.02  4996.7 1692.59  4999.4 1692.09  5002.7 1692.59  5060.6 1696.99
  5130.0 1697.79  5337.5 1712.26  5373.8 1719.23  5424.6 1725.88  5450.1 1733.55
  5495.7 1740.09  5607.5 1762.53  5668.4 1778.66  5688.7 1787.44  5726.0 1795.31
#Mann=7,-1,0
  4035.3    0.16       0  4047.1     0.1       0  4446.8    0.05       0
  4550.2     0.1       0  4996.7    0.07       0  5002.7     0.1       0
  5060.6    0.16       0
Bank Sta=4996.7,5002.7
Exp/Cntr=0.3,0.1

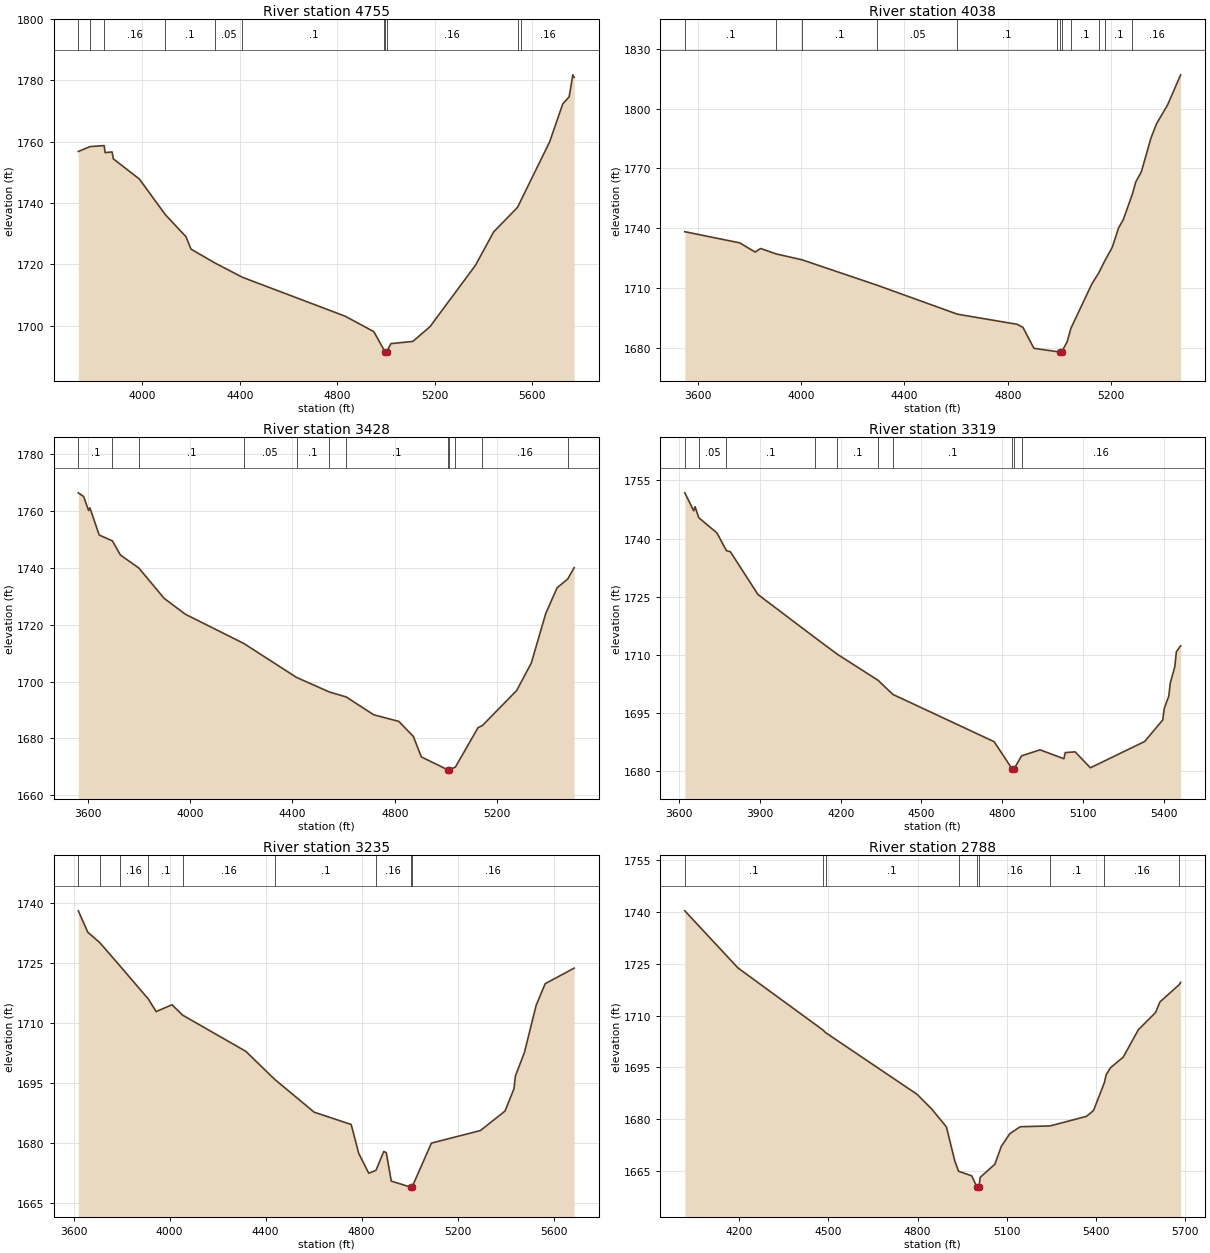
Type RM Length L Ch R = 1,4755,717,717,717
BEGIN DESCRIPTION:
MIDDLE FORK THREEMILE CREEK 10.0
END DESCRIPTION:
XS GIS Cut Line= 4
      2821093.62     10025829.89      2821781.07     10026025.19
      2822617.01     10025988.73      2823083.71     10025863.50
#Sta/Elev= 30
  3737.5 1756.83  3785.2 1758.42  3843.5 1758.75  3847.4 1756.46  3876.1 1756.67
  3881.3 1754.41  3988.1 1747.83  4094.6 1736.21  4179.2 1729.02  4200.0 1724.96
  4297.3 1720.48  4410.5 1715.79  4832.4 1703.08  4950.0 1698.05  4993.4 1691.83
  4997.1 1691.53  4999.8 1691.03  5003.1 1691.53  5020.1 1694.13  5110.2 1694.86
  5180.2 1699.63  5367.1 1719.69  5441.9 1730.60  5540.1 1738.63  5555.3 1741.13
  5671.5 1759.97  5725.3 1772.35  5751.5 1774.65  5766.7 1781.84  5772.1 1781.04
#Mann=11,-1,0
  3737.5    0.16       0  3785.2     0.1       0  3843.5    0.16       0
  4094.6     0.1       0  4297.3    0.05       0  4410.5     0.1       0
  4993.4    0.16       0  4997.1    0.07       0  5003.1    0.16       0
  5540.1     0.1       0  5555.3    0.16       0
Bank Sta=4997.1,5003.1
Exp/Cntr=0.3,0.1

Type RM Length L Ch R = 1,4038,610,610,610
BEGIN DESCRIPTION:
MIDDLE FORK THREEMILE CREEK 9.0
END DESCRIPTION:
XS GIS Cut Line= 4
      2821247.26     10026704.88      2822064.93     10026805.57
      2822880.90     10026493.07      2823074.43     10026382.49
#Sta/Elev= 30
  3549.2 1738.27  3762.0 1732.67  3821.8 1728.05  3842.6 1729.85  3903.6 1727.11
  4002.5 1724.20  4295.5 1711.36  4604.9 1696.89  4835.7 1691.82  4858.7 1690.30
  4901.5 1679.75  4990.2 1678.12  5002.3 1677.84  5005.0 1677.34  5008.3 1677.84
  5030.0 1682.96  5044.7 1689.81  5126.4 1712.20  5152.1 1717.48  5175.2 1723.46
  5204.9 1730.46  5229.6 1740.28  5246.8 1744.09  5282.8 1757.08  5295.8 1763.18
  5317.4 1768.25  5354.9 1785.30  5376.5 1792.45  5419.7 1802.03  5469.7 1816.99
#Mann=12,-1,0
  3549.2     0.1       0  3903.6    0.05       0  4002.5     0.1       0
  4295.5    0.05       0  4604.9     0.1       0  4990.2    0.16       0
  5002.3    0.07       0  5008.3    0.16       0  5044.7     0.1       0
  5152.1    0.16       0  5175.2     0.1       0  5282.8    0.16       0
Bank Sta=5002.3,5008.3
Exp/Cntr=0.3,0.1

Type RM Length L Ch R = 1,3428,109,109,109
BEGIN DESCRIPTION:
MIDDLE FORK THREEMILE CREEK 7.0
END DESCRIPTION:
XS GIS Cut Line= 4
      2821438.24     10027509.24      2822729.86     10027189.81
      2823068.83     10027076.84      2823271.56     10026932.84
#Sta/Elev= 30
  3563.8 1766.41  3584.6 1765.11  3603.8 1760.16  3609.0 1761.13  3645.3 1751.57
  3697.0 1749.50  3728.1 1744.53  3799.8 1739.98  3899.0 1729.28  3981.8 1723.69
  4210.7 1713.38  4416.1 1701.46  4543.7 1696.36  4610.1 1694.58  4717.8 1688.30
  4815.6 1685.99  4872.3 1680.69  4903.4 1673.50  5005.8 1668.99  5008.6 1668.49
  5011.8 1668.99  5036.2 1669.88  5124.8 1683.77  5141.7 1684.51  5275.7 1696.84
  5332.8 1706.50  5389.4 1723.96  5433.7 1733.01  5475.0 1736.07  5500.3 1740.09
#Mann=12,-1,0
  3563.8     0.1       0  3697.0    0.05       0  3799.8     0.1       0
  4210.7    0.05       0  4416.1     0.1       0  4543.7    0.05       0
  4610.1     0.1       0  5005.8    0.07       0  5011.8     0.1       0
  5036.2    0.05       0  5141.7    0.16       0  5475.0     0.1       0
Bank Sta=5005.8,5011.8
Exp/Cntr=0.3,0.1

Type RM Length L Ch R = 1,3319,84,84,84
BEGIN DESCRIPTION:
Mapping XS 1e1f968f
END DESCRIPTION:
XS GIS Cut Line= 4
      2821514.56     10027557.87      2822600.92     10027277.18
      2822975.27     10027253.30      2823284.41     10027100.03
#Sta/Elev= 30
  3620.8 1751.81  3654.0 1747.17  3659.1 1748.23  3672.5 1745.40  3740.4 1741.44
  3775.6 1736.86  3790.1 1736.60  3892.7 1725.55  4106.3 1714.33  4187.8 1710.12
  4339.3 1703.38  4393.8 1699.76  4770.4 1687.54  4837.6 1680.45  4840.3 1679.95
  4843.6 1680.45  4871.9 1683.89  4940.8 1685.45  5029.3 1683.15  5034.3 1684.73
  5071.0 1684.93  5127.7 1680.81  5329.4 1687.60  5396.7 1693.18  5402.3 1696.17
  5419.1 1699.34  5424.7 1702.71  5441.5 1706.93  5447.1 1710.76  5463.0 1712.31
#Mann=10,-1,0
  3620.8     0.1       0  3672.5    0.05       0  3775.6     0.1       0
  4106.3    0.05       0  4187.8     0.1       0  4339.3    0.05       0
  4393.8     0.1       0  4837.6    0.07       0  4843.6     0.1       0
  4871.9    0.16       0
Bank Sta=4837.6,4843.6
Exp/Cntr=0.3,0.1

Type RM Length L Ch R = 1,3235,447,447,447
BEGIN DESCRIPTION:
Mapping XS 172d6979
END DESCRIPTION:
XS GIS Cut Line= 3
      2821570.16     10027731.47      2823090.97     10027273.14
      2823506.17     10027037.86
#Sta/Elev= 30
  3619.7 1738.07  3659.2 1732.72  3709.8 1730.08  3793.3 1724.29  3911.0 1716.04
  3944.0 1712.88  4010.0 1714.58  4053.8 1712.00  4317.4 1702.94  4437.8 1695.93
  4602.2 1687.72  4756.4 1684.65  4787.7 1677.44  4829.5 1672.46  4859.7 1673.18
  4892.1 1677.90  4902.6 1677.59  4923.5 1670.49  5004.0 1668.98  5006.8 1668.48
  5010.0 1668.98  5090.6 1679.99  5294.8 1683.13  5397.2 1688.00  5434.7 1693.60
  5440.5 1696.77  5478.0 1702.62  5527.0 1714.44  5564.5 1719.85  5685.3 1723.74
#Mann=9,-1,0
  3619.7    0.05       0  3709.8     0.1       0  3793.3    0.16       0
  3911.0     0.1       0  4053.8    0.16       0  4437.8     0.1       0
  4859.7    0.16       0  5004.0    0.07       0  5010.0    0.16       0
Bank Sta=5004,5010
Exp/Cntr=0.3,0.1

Type RM Length L Ch R = 1,2788,473,473,473
BEGIN DESCRIPTION:
MIDDLE FORK THREEMILE CREEK 6.0
END DESCRIPTION:
XS GIS Cut Line= 3
      2822514.56     10028342.60      2823285.42     10027495.36
      2823569.85     10027058.30
#Sta/Elev= 30
  4017.1 1740.34  4195.9 1723.80  4482.2 1705.79  4490.3 1705.08  4798.0 1687.20
  4847.3 1682.94  4896.6 1677.77  4925.0 1667.84  4937.5 1664.93  4981.8 1663.60
  4999.7 1660.25  5002.5 1659.75  5005.7 1660.25  5010.2 1663.16  5059.5 1666.96
  5081.1 1672.11  5109.5 1675.78  5144.6 1677.82  5245.0 1678.05  5367.3 1680.82
  5391.2 1682.52  5427.8 1690.62  5433.4 1692.80  5448.6 1694.94  5490.8 1697.95
  5542.1 1705.93  5599.5 1710.86  5614.6 1713.97  5680.0 1719.03  5684.0 1719.63
#Mann=9,-1,0
  4017.1     0.1       0  4482.2    0.16       0  4490.3     0.1       0
  4937.5    0.16       0  4999.7    0.07       0  5005.7    0.16       0
  5245.0     0.1       0  5427.8    0.16       0  5680.0     0.1       0
Bank Sta=4999.7,5005.7
Exp/Cntr=0.3,0.1

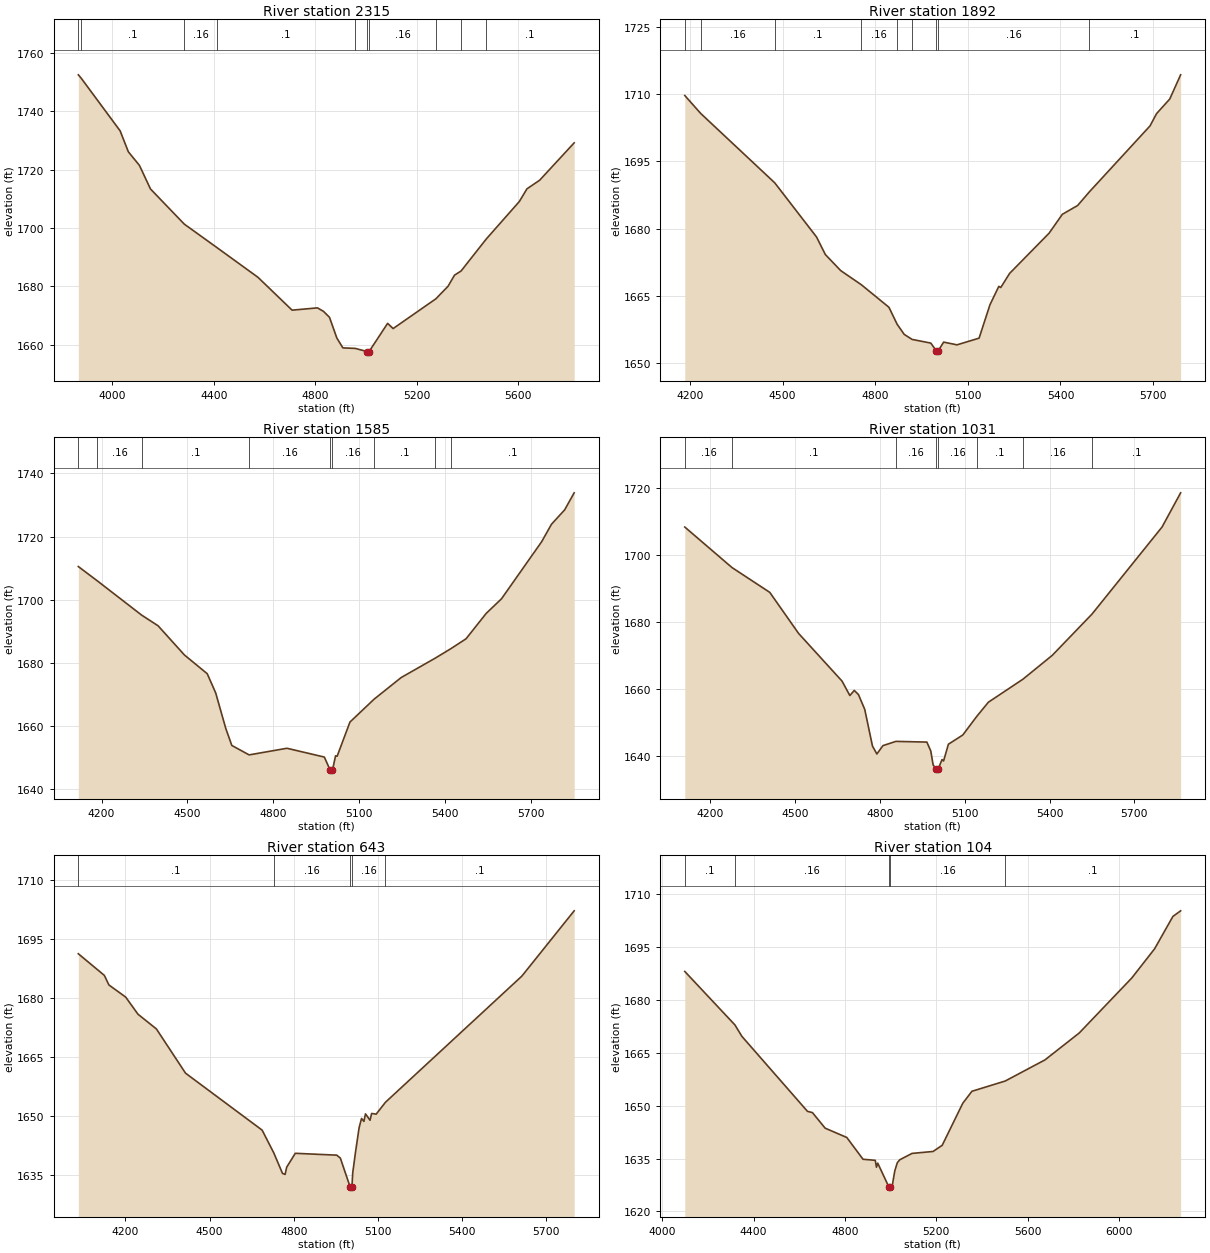
Type RM Length L Ch R = 1,2315,423,423,423
BEGIN DESCRIPTION:
MIDDLE FORK THREEMILE CREEK 5.0
END DESCRIPTION:
XS GIS Cut Line= 3
      2823174.29     10028745.40      2823688.19     10027537.03
      2823632.66     10026898.45
#Sta/Elev= 30
  3866.2 1752.53  3876.8 1751.46  4031.0 1733.31  4063.3 1726.15  4107.1 1721.46
  4150.6 1713.39  4283.5 1701.36  4411.4 1693.36  4574.2 1683.10  4708.7 1671.83
  4808.7 1672.62  4832.4 1671.42  4856.0 1669.39  4885.1 1662.27  4908.8 1658.90
  4957.8 1658.72  5005.8 1657.60  5008.5 1657.10  5011.8 1657.60  5085.1 1667.31
  5106.8 1665.52  5275.4 1675.73  5323.1 1680.01  5348.8 1683.84  5374.5 1685.25
  5473.6 1696.20  5604.2 1709.08  5634.3 1713.44  5684.5 1716.40  5820.3 1729.20
#Mann=10,-1,0
  3866.2    0.05       0  3876.8     0.1       0  4283.5    0.16       0
  4411.4     0.1       0  4957.8    0.16       0  5005.8    0.07       0
  5011.8    0.16       0  5275.4     0.1       0  5374.5    0.16       0
  5473.6     0.1       0
Bank Sta=5005.8,5011.8
Exp/Cntr=0.3,0.1

Type RM Length L Ch R = 1,1892,307,307,307
BEGIN DESCRIPTION:
MIDDLE FORK THREEMILE CREEK 4.0
END DESCRIPTION:
XS GIS Cut Line= 2
      2823445.16     10028571.73      2824464.72     10027330.22
#Sta/Elev= 30
  4182.9 1709.70  4234.6 1705.69  4474.4 1690.21  4609.7 1678.13  4638.4 1674.20
  4687.9 1670.63  4755.4 1667.44  4844.4 1662.43  4870.7 1658.67  4893.9 1656.38
  4919.5 1655.26  4980.0 1654.44  4997.8 1652.70  5000.5 1652.20  5003.8 1652.70
  5021.6 1654.66  5064.7 1654.05  5136.4 1655.54  5171.6 1662.99  5200.3 1667.10
  5206.7 1666.85  5235.4 1670.00  5363.2 1678.97  5406.2 1683.19  5455.7 1685.15
  5493.9 1688.21  5690.3 1702.92  5711.2 1705.64  5754.2 1708.92  5789.4 1714.32
#Mann=9,-1,0
  4182.9     0.1       0  4234.6    0.16       0  4474.4     0.1       0
  4755.4    0.16       0  4870.7     0.1       0  4919.5    0.16       0
  4997.8    0.07       0  5003.8    0.16       0  5493.9     0.1       0
Bank Sta=4997.8,5003.8
Exp/Cntr=0.3,0.1

Type RM Length L Ch R = 1,1585,554,554,554
BEGIN DESCRIPTION:
MIDDLE FORK THREEMILE CREEK 3.0
END DESCRIPTION:
XS GIS Cut Line= 4
      2823479.86     10028613.41      2824132.64     10028141.19
      2824618.75     10027898.14      2824806.24     10027564.81
#Sta/Elev= 30
  4118.9 1710.48  4184.3 1706.01  4340.3 1695.06  4397.4 1691.70  4489.4 1682.44
  4569.1 1676.49  4598.5 1670.44  4634.1 1659.07  4654.9 1653.75  4715.3 1650.75
  4847.5 1652.85  4978.1 1650.06  4997.5 1646.10  5000.2 1645.60  5003.5 1646.10
  5009.3 1647.09  5017.2 1650.45  5022.8 1650.33  5067.5 1661.16  5151.6 1668.40
  5246.4 1675.28  5364.3 1681.38  5419.8 1684.43  5472.9 1687.57  5543.3 1695.62
  5596.8 1700.26  5737.0 1718.36  5771.4 1723.91  5817.3 1728.46  5850.5 1733.86
#Mann=9,-1,0
  4118.9     0.1       0  4184.3    0.16       0  4340.3     0.1       0
  4715.3    0.16       0  4997.5    0.07       0  5003.5    0.16       0
  5151.6     0.1       0  5364.3    0.16       0  5419.8     0.1       0
Bank Sta=4997.5,5003.5
Exp/Cntr=0.3,0.1

Type RM Length L Ch R = 1,1031,388,388,388
BEGIN DESCRIPTION:
MIDDLE FORK THREEMILE CREEK 2.0
END DESCRIPTION:
XS GIS Cut Line= 3
      2823729.89     10028995.34      2824410.42     10028592.58
      2824827.06     10027724.57
#Sta/Elev= 30
  4109.9 1708.45  4276.7 1696.34  4410.4 1688.91  4512.3 1676.63  4666.0 1662.36
  4693.7 1658.04  4709.3 1659.57  4724.1 1658.33  4746.3 1653.90  4773.6 1642.95
  4789.2 1640.55  4810.7 1643.05  4856.6 1644.32  4966.0 1644.11  4979.8 1641.47
  4988.1 1637.33  4999.5 1635.92  5002.2 1635.42  5005.5 1635.92  5019.6 1638.88
  5025.1 1638.45  5042.2 1643.47  5093.1 1646.23  5142.5 1651.80  5183.6 1656.04
  5306.0 1662.94  5409.6 1670.07  5550.1 1682.41  5797.9 1708.47  5863.5 1718.69
#Mann=8,-1,0
  4109.9    0.16       0  4276.7     0.1       0  4856.6    0.16       0
  4999.5    0.07       0  5005.5    0.16       0  5142.5     0.1       0
  5306.0    0.16       0  5550.1     0.1       0
Bank Sta=4999.5,5005.5
Exp/Cntr=0.3,0.1

Type RM Length L Ch R = 1,643,539,539,539
BEGIN DESCRIPTION:
Mapping XS a2cc26ea
END DESCRIPTION:
XS GIS Cut Line= 4
      2823948.82     10029081.18      2824838.60     10028599.40
      2824927.58     10028434.47      2824931.91     10027867.32
#Sta/Elev= 30
  4032.6 1691.24  4125.3 1685.75  4141.5 1683.32  4201.4 1680.23  4245.2 1675.88
  4310.8 1672.14  4414.5 1660.91  4687.4 1646.44  4729.1 1640.63  4760.0 1635.44
  4769.2 1635.19  4774.9 1637.03  4805.5 1640.55  4953.3 1640.08  4966.1 1639.33
  5001.2 1631.95  5003.9 1631.45  5007.2 1631.95  5010.2 1635.62  5020.3 1640.97
  5032.9 1647.08  5041.5 1649.40  5049.9 1648.66  5055.6 1650.57  5071.8 1648.95
  5077.5 1650.67  5093.7 1650.50  5126.8 1653.52  5612.6 1685.56  5799.0 1702.15
#Mann=5,-1,0
  4032.6     0.1       0  4729.1    0.16       0  5001.2    0.07       0
  5007.2    0.16       0  5126.8     0.1       0
Bank Sta=5001.2,5007.2
Exp/Cntr=0.3,0.1

Type RM Length L Ch R = 1,104,0,0,0
BEGIN DESCRIPTION:
MIDDLE FORK THREEMILE CREEK 1.0
END DESCRIPTION:
XS GIS Cut Line= 4
      2823968.38     10029220.06      2824788.69     10029083.34
      2824940.60     10029011.72      2824975.32     10027839.81
#Sta/Elev= 30
  4098.5 1688.11  4318.2 1672.93  4348.4 1669.71  4635.9 1648.41  4657.6 1648.05
  4713.4 1643.63  4808.2 1640.99  4879.2 1634.81  4932.8 1634.50  4938.2 1632.55
  4943.7 1633.71  4993.2 1626.83  4996.0 1626.33  4999.2 1626.83  5006.5 1627.00
  5018.3 1631.49  5029.3 1633.81  5040.4 1634.67  5094.1 1636.47  5186.1 1637.02
  5226.1 1638.77  5316.2 1650.70  5356.2 1654.10  5502.3 1657.02  5676.3 1663.01
  5826.4 1670.65  6056.5 1686.25  6156.5 1694.54  6236.6 1703.72  6270.5 1705.32
#Mann=5,-1,0
  4098.5     0.1       0  4318.2    0.16       0  4993.2    0.07       0
  4999.2    0.16       0  5502.3     0.1       0
Bank Sta=4993.2,4999.2
Exp/Cntr=0.3,0.1

Chan Stop Cuts=-1