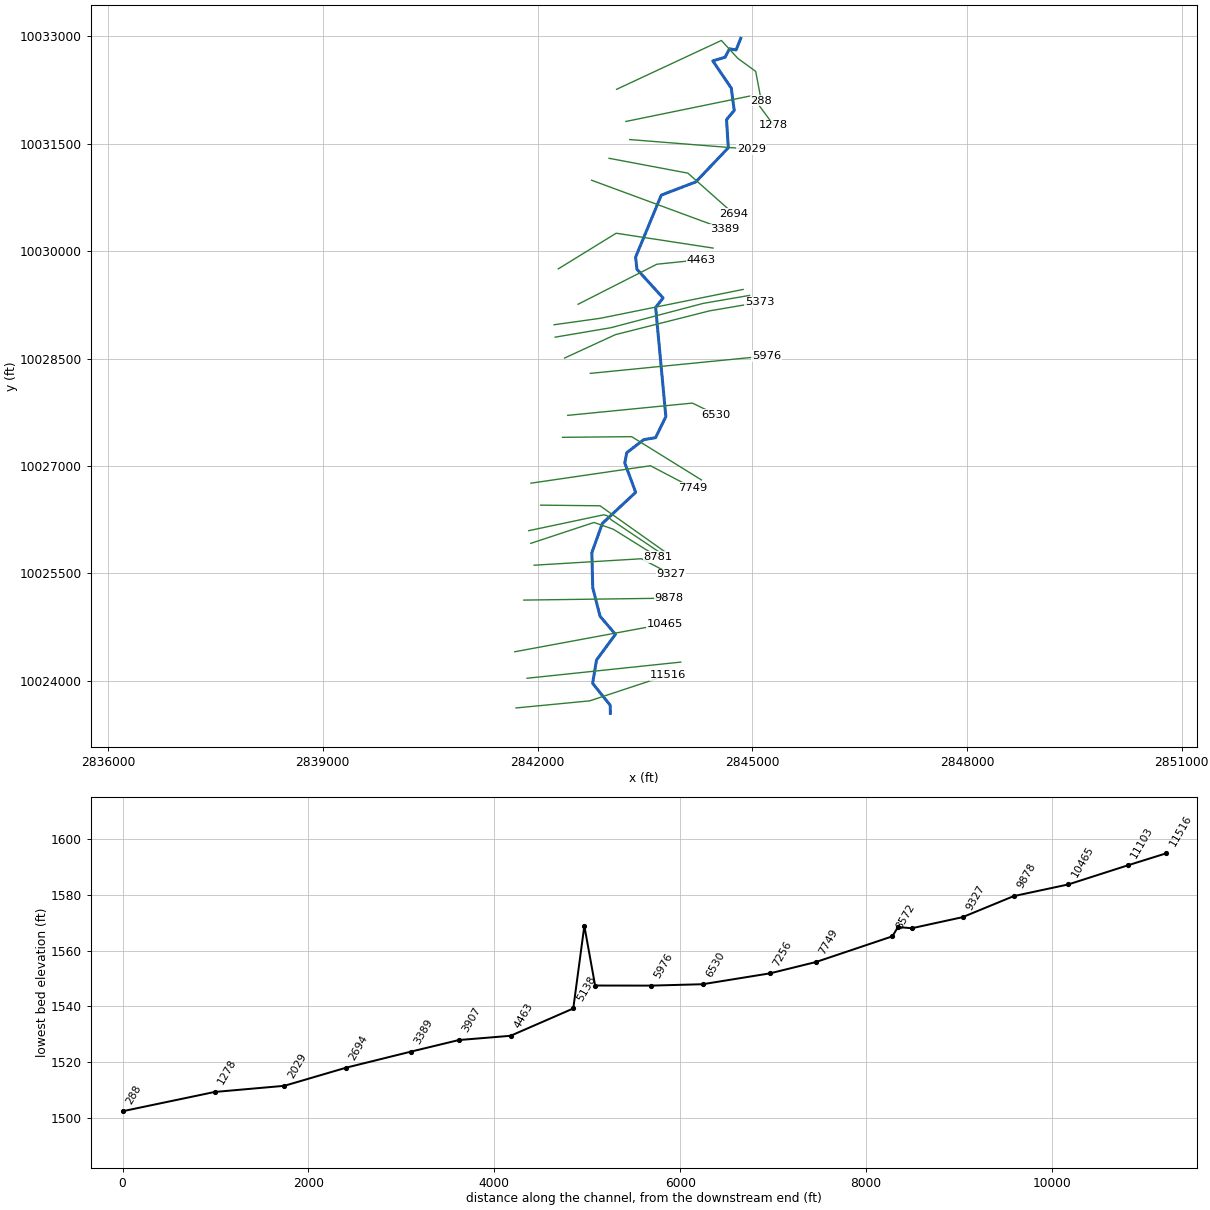
--- MIDDLE FORK WILLIAMS CREEK.prj (project) ---

Proj Title=MIDDLE FORK WILLIAMS CREEK Base Level Engineering
Current Plan=p01
Default Exp/Contr=0.3,0.1
English Units
Geom File=g01
Flow File=f01
Plan File=p01
Y Axis Title=Elevation
X Axis Title(PF)=Main Channel Distance
X Axis Title(XS)=Station
BEGIN DESCRIPTION:
MIDDLE FORK WILLIAMS CREEK
END DESCRIPTION:
DSS Export Rating Curves= 0
DSS Export Rating Curve Sorted= 0
DSS Export Volume Flow Curves= 0
DXF OffsetX= 0
DXF OffsetY= 0
DXF ScaleX= 1
DXF ScaleY= 10

--- MIDDLE FORK WILLIAMS CREEK.p01 (plan) ---

Plan Title=Multiple Run
Short Identifier=Multiple
Geom File=g01
Flow File=f01
Subcritical Flow
K Sum by GR= 0
Std Step Tol= 0.01
Critical Tol= 0.01
Num of Std Step Trials= 20
Max Error Tol= 0.3
Flow Tol Ratio= 0.001
Split Flow NTrial= 30
Split Flow Tol= 0.02
Split Flow Ratio= 0.02
Log Output Level= 0
Friction Slope Method= 1
Unsteady Friction Slope Method= 2
Unsteady Bridges Friction Slope Method= 1
Parabolic Critical Depth
Global Vel Dist=  1 , 1 , 1
Global Log Level= 0
CheckData=True
Encroach Param= -1, 0, 0, 0
BEGIN DESCRIPTION:
Multiple Run
END DESCRIPTION:

--- MIDDLE FORK WILLIAMS CREEK.f01 (steady flow) ---

Flow Title=Multiple
Program Version=4.10
Number of Profiles= 7
Profile Names=10-year,25-year,50-year,1pct_min,100-year,1pct_plu,500-year
River Rch & RM=MIDDLE FORK WILL,Reach-1         ,11516
    1711    2572    3348    3185    4308    5826    7161
River Rch & RM=MIDDLE FORK WILL,Reach-1         ,7749
    2012    3031    3948    3756    5079    6869    8442
Boundary for River Rch & Prof#=MIDDLE FORK WILL,Reach-1         , 1
Up Type= 0
Dn Type= 1
Dn Known WS=1509.68
Boundary for River Rch & Prof#=MIDDLE FORK WILL,Reach-1         , 2
Up Type= 0
Dn Type= 1
Dn Known WS=1510.68
Boundary for River Rch & Prof#=MIDDLE FORK WILL,Reach-1         , 3
Up Type= 0
Dn Type= 1
Dn Known WS=1511.45
Boundary for River Rch & Prof#=MIDDLE FORK WILL,Reach-1         , 4
Up Type= 0
Dn Type= 1
Dn Known WS=1511.33
Boundary for River Rch & Prof#=MIDDLE FORK WILL,Reach-1         , 5
Up Type= 0
Dn Type= 1
Dn Known WS=1512.21
Boundary for River Rch & Prof#=MIDDLE FORK WILL,Reach-1         , 6
Up Type= 0
Dn Type= 1
Dn Known WS=1513.18
Boundary for River Rch & Prof#=MIDDLE FORK WILL,Reach-1         , 7
Up Type= 0
Dn Type= 1
Dn Known WS=1514
DSS Import GetInterval= 0
DSS Import GetPeak= 0
DSS Import FillOption= 0

--- MIDDLE FORK WILLIAMS CREEK.g01 (geometry) ---

Geom Title=Existing Conditions
Program Version=4.10

River Reach=MIDDLE FORK WILL,Reach-1
Reach XY= 30
      2843018.09     10023544.54      2843015.69     10023657.86
      2842769.74     10023964.02      2842824.45     10024290.57
      2843088.72     10024648.83      2842873.65     10024900.58
       2842771.4      10025299.2      2842759.09     10025789.26
       2842904.7      10026196.5      2843370.97     10026632.07
      2843219.01     10027042.59      2843247.13       10027186.
      2843483.83     10027368.06      2843649.48     10027395.77
      2843792.44      10027689.9      2843649.78     10029216.58
      2843754.54     10029346.98      2843388.64     10029748.65
      2843369.94     10029917.74      2843729.07     10030783.61
      2844211.55     10030968.56      2844664.96     10031445.13
      2844640.22     10031838.15       2844747.5     10031966.31
      2844706.66     10032277.98      2844448.47     10032658.84
      2844619.93     10032709.51      2844681.91     10032827.14
      2844774.06     10032811.73      2844838.47     10032973.73

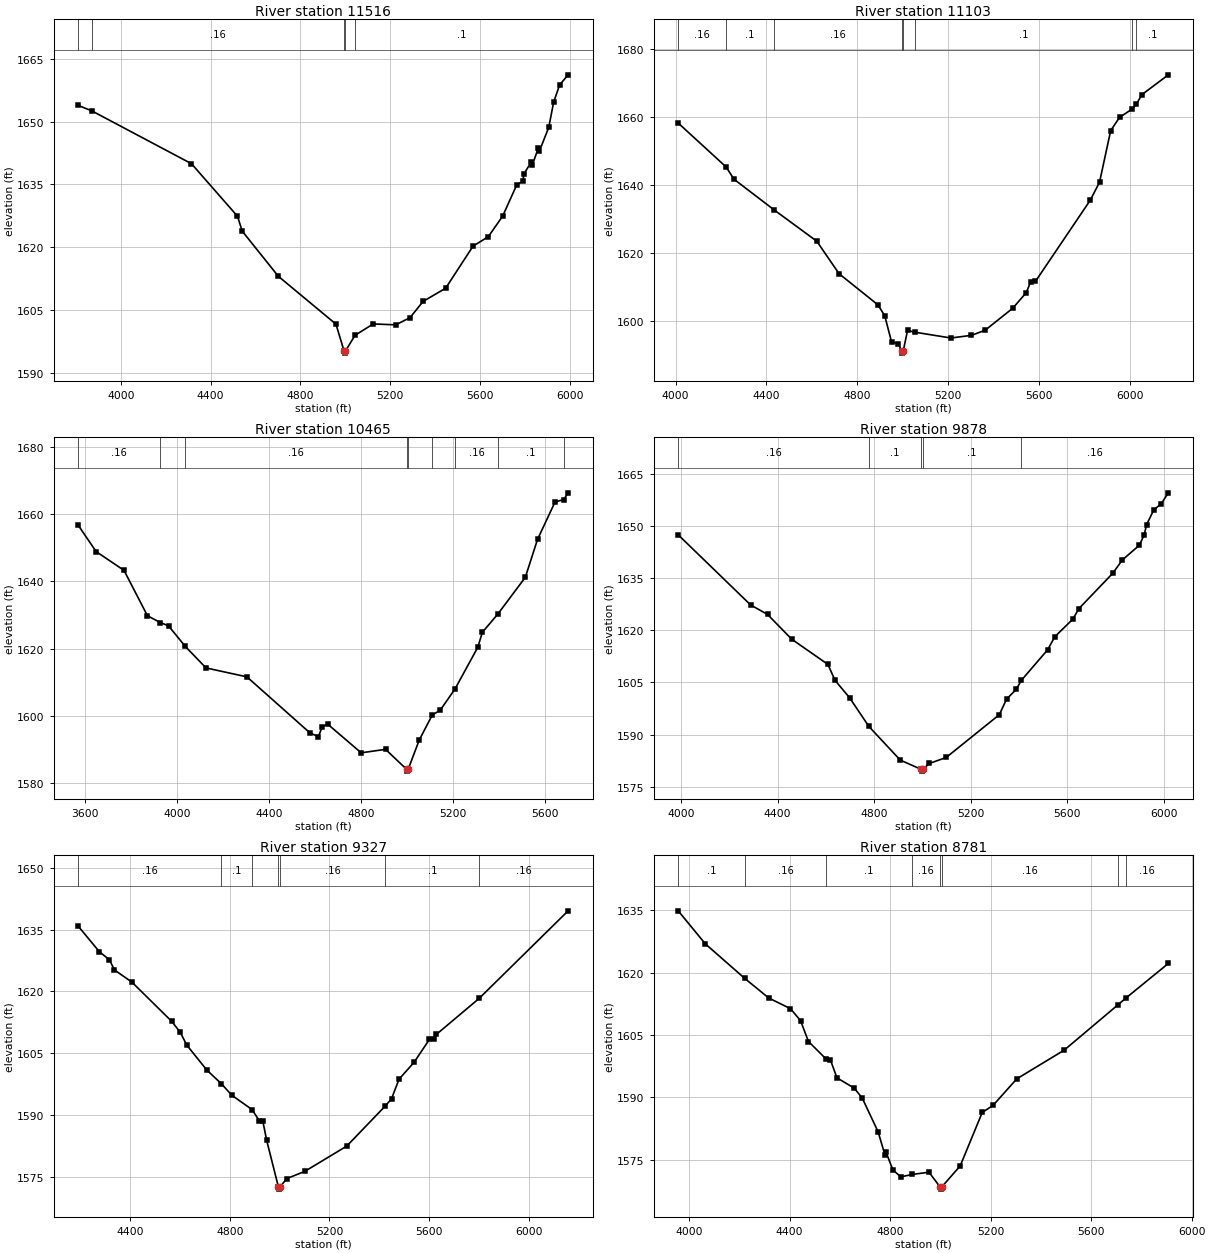
Type RM Length L Ch R = 1 ,11516   ,413,413,413
BEGIN DESCRIPTION:
MIDDLE FORK WILLIAMS CREEK 25.0
END DESCRIPTION:
XS GIS Cut Line= 3
      2841700.28     10023620.22      2842728.84     10023719.47
       2843820.5     10024080.35
#Sta/Elev= 30
  3809.8 1653.85    3870 1652.57  4315.1 1639.94  4519.7 1627.44  4541.4 1623.85
  4702.1  1613.1  4958.6  1601.7  4994.8 1595.29  4997.5 1594.79  5000.8 1595.29
  5043.8 1599.05  5124.7 1601.75  5225.1 1601.53  5288.6 1603.25  5346.8 1607.12
  5447.2 1610.26  5568.9 1620.27  5637.6 1622.57  5701.1 1627.45  5764.5 1634.96
  5790.6 1635.74  5796.3 1637.51    5828 1640.32  5833.2  1639.6  5859.7 1643.63
    5865 1642.96  5906.5 1648.61  5928.4 1654.64  5954.9 1658.73  5992.9 1661.13
#Mann= 5 ,-1 , 0
  3809.8      .1       0    3870     .16       0  4994.8     .07       0
  5000.8     .16       0  5043.8      .1       0
Bank Sta=4994.8,5000.8
XS Rating Curve= 0 ,0
Exp/Cntr=0.3,0.1

Type RM Length L Ch R = 1 ,11103   ,638,638,638
BEGIN DESCRIPTION:
MIDDLE FORK WILLIAMS CREEK 24.0
END DESCRIPTION:
XS GIS Cut Line= 2
      2841853.71     10024035.25        2844001.     10024260.81
#Sta/Elev= 30
  4011.8 1658.16  4222.4 1645.27  4257.9 1641.62  4435.5 1632.56  4622.2 1623.41
  4720.4 1613.85  4891.4  1604.7  4921.5 1601.51  4951.7 1593.77  4981.9 1593.28
  4996.6 1590.99  4999.4 1590.49  5002.6 1590.99  5022.1 1597.17  5055.7 1596.63
  5213.1 1594.94  5303.6 1595.72    5364 1597.23  5485.3 1603.68  5544.9 1608.27
  5565.1 1611.55  5585.2 1611.56  5826.5 1635.42  5867.8 1640.75    5917 1655.94
  5955.9 1659.82  6009.4  1662.2  6030.4 1663.72    6054  1666.5  6170.9 1672.35
#Mann= 8 ,-1 , 0
  4011.8     .16       0  4222.4      .1       0  4435.5     .16       0
  4996.6     .07       0  5002.6     .16       0  5055.7      .1       0
  6009.4     .16       0  6030.4      .1       0
Bank Sta=4996.6,5002.6
XS Rating Curve= 0 ,0
Exp/Cntr=0.3,0.1

Type RM Length L Ch R = 1 ,10465   ,587,587,587
BEGIN DESCRIPTION:
MIDDLE FORK WILLIAMS CREEK 23.0
END DESCRIPTION:
XS GIS Cut Line= 2
      2841682.28     10024405.17      2843774.45     10024792.94
#Sta/Elev= 30
  3571.3 1656.79  3649.8 1648.89  3770.8 1643.31  3872.5 1629.84  3928.3 1627.81
  3964.1 1626.82    4037 1620.71  4126.8 1614.33  4304.5 1611.67    4579 1594.97
    4615 1593.92  4631.8 1596.91  4655.6  1597.6  4800.6 1589.11  4906.3 1590.14
  4998.4 1584.17  5001.2 1583.67  5004.4 1584.17  5052.3 1592.87  5109.2 1600.35
  5143.8 1601.76  5208.7 1608.17  5306.5 1620.43  5326.9 1624.93  5393.6 1630.31
  5513.2 1641.25  5566.1  1652.5  5642.2 1663.63  5679.9 1664.34  5699.1 1666.34
#Mann= 9 ,-1 , 0
  3571.3     .16       0  3928.3      .1       0    4037     .16       0
  4998.4     .07       0  5004.4     .16       0  5109.2      .1       0
  5208.7     .16       0  5393.6      .1       0  5679.9     .16       0
Bank Sta=4998.4,5004.4
XS Rating Curve= 0 ,0
Exp/Cntr=0.3,0.1

Type RM Length L Ch R = 1 ,9878    ,551,551,551
BEGIN DESCRIPTION:
MIDDLE FORK WILLIAMS CREEK 21.0
END DESCRIPTION:
XS GIS Cut Line= 2
      2841808.59     10025126.95      2843838.61     10025154.02
#Sta/Elev= 30
  3988.2  1647.4  4288.1 1627.25  4358.1 1624.53  4458.1 1617.42  4608.1 1610.17
  4638.1 1605.55  4698.1 1600.58    4778 1592.33  4908.2 1582.65  4995.2 1579.99
  4997.9 1579.49  5001.2 1579.99  5028.2 1581.69  5098.2 1583.41  5318.2  1595.7
  5348.2 1600.17  5388.2 1602.97  5409.9 1605.61  5518.2 1614.34  5548.2 1618.11
  5622.6 1623.15  5648.2 1626.21  5788.2 1636.35  5828.2 1640.19  5898.2  1644.4
  5918.2 1647.34  5928.2 1650.29  5958.2 1654.59  5988.3 1656.26  6018.4 1659.47
#Mann= 5 ,-1 , 0
  3988.2     .16       0    4778      .1       0  4995.2     .07       0
  5001.2      .1       0  5409.9     .16       0
Bank Sta=4995.2,5001.2
XS Rating Curve= 0 ,0
Exp/Cntr=0.3,0.1

Type RM Length L Ch R = 1 ,9327    ,546,546,546
BEGIN DESCRIPTION:
MIDDLE FORK WILLIAMS CREEK 20.0
END DESCRIPTION:
XS GIS Cut Line= 3
      2841952.92     10025614.15      2843450.62     10025704.38
      2843863.67     10025488.88
#Sta/Elev= 30
  4191.6  1635.9  4277.3 1629.63  4317.4 1627.69  4337.4 1625.22  4407.5 1622.26
  4567.8 1612.69  4601.6 1610.06  4627.9 1606.94  4708.1 1600.89  4766.6 1597.56
  4808.3 1594.77    4890 1591.26  4918.5 1588.57  4933.2 1588.39  4948.5 1583.76
  4995.6 1572.44  4998.4 1571.94  5001.6 1572.44  5028.7 1574.49  5101.5 1576.26
  5269.8 1582.41  5424.3 1592.15  5449.4 1593.91  5479.5 1598.67  5539.6 1602.75
  5601.4 1608.34  5619.7  1608.4  5629.7 1609.57  5801.1 1618.31  6157.9 1639.58
#Mann= 7 ,-1 , 0
  4191.6     .16       0  4766.6      .1       0    4890     .16       0
  4995.6     .07       0  5001.6     .16       0  5424.3      .1       0
  5801.1     .16       0
Bank Sta=4995.6,5001.6
XS Rating Curve= 0 ,0
Exp/Cntr=0.3,0.1

Type RM Length L Ch R = 1 ,8781    ,149,149,149
BEGIN DESCRIPTION:
Mapping XS c558c29b
END DESCRIPTION:
XS GIS Cut Line= 4
      2841906.25     10025919.62      2842789.06     10026211.29
      2843057.29     10026117.54      2843682.75     10025728.24
#Sta/Elev= 30
  3956.5 1634.81  4064.2 1626.89  4220.9  1618.6  4316.9 1613.87  4403.2 1611.32
  4443.3 1608.44  4474.9 1603.43  4545.3 1599.21  4561.9 1599.06  4588.3  1594.7
  4657.1 1592.23  4688.8 1589.86  4752.3 1581.71  4778.8 1576.27    4784 1576.81
  4810.5 1572.63  4842.2 1570.92  4888.1 1571.51  4954.5 1572.04  4999.1 1568.48
  5001.9 1567.98  5005.1 1568.48  5078.7 1573.55  5166.5 1586.39  5209.5 1588.09
  5303.9 1594.46  5492.8 1601.36  5707.7 1612.29  5739.3 1613.91  5907.1 1622.17
#Mann= 8 ,-1 , 0
  3956.5      .1       0  4220.9     .16       0  4545.3      .1       0
  4888.1     .16       0  4999.1     .07       0  5005.1     .16       0
  5707.7      .1       0  5739.3     .16       0
Bank Sta=4999.1,5005.1
XS Rating Curve= 0 ,0
Exp/Cntr=0.3,0.1

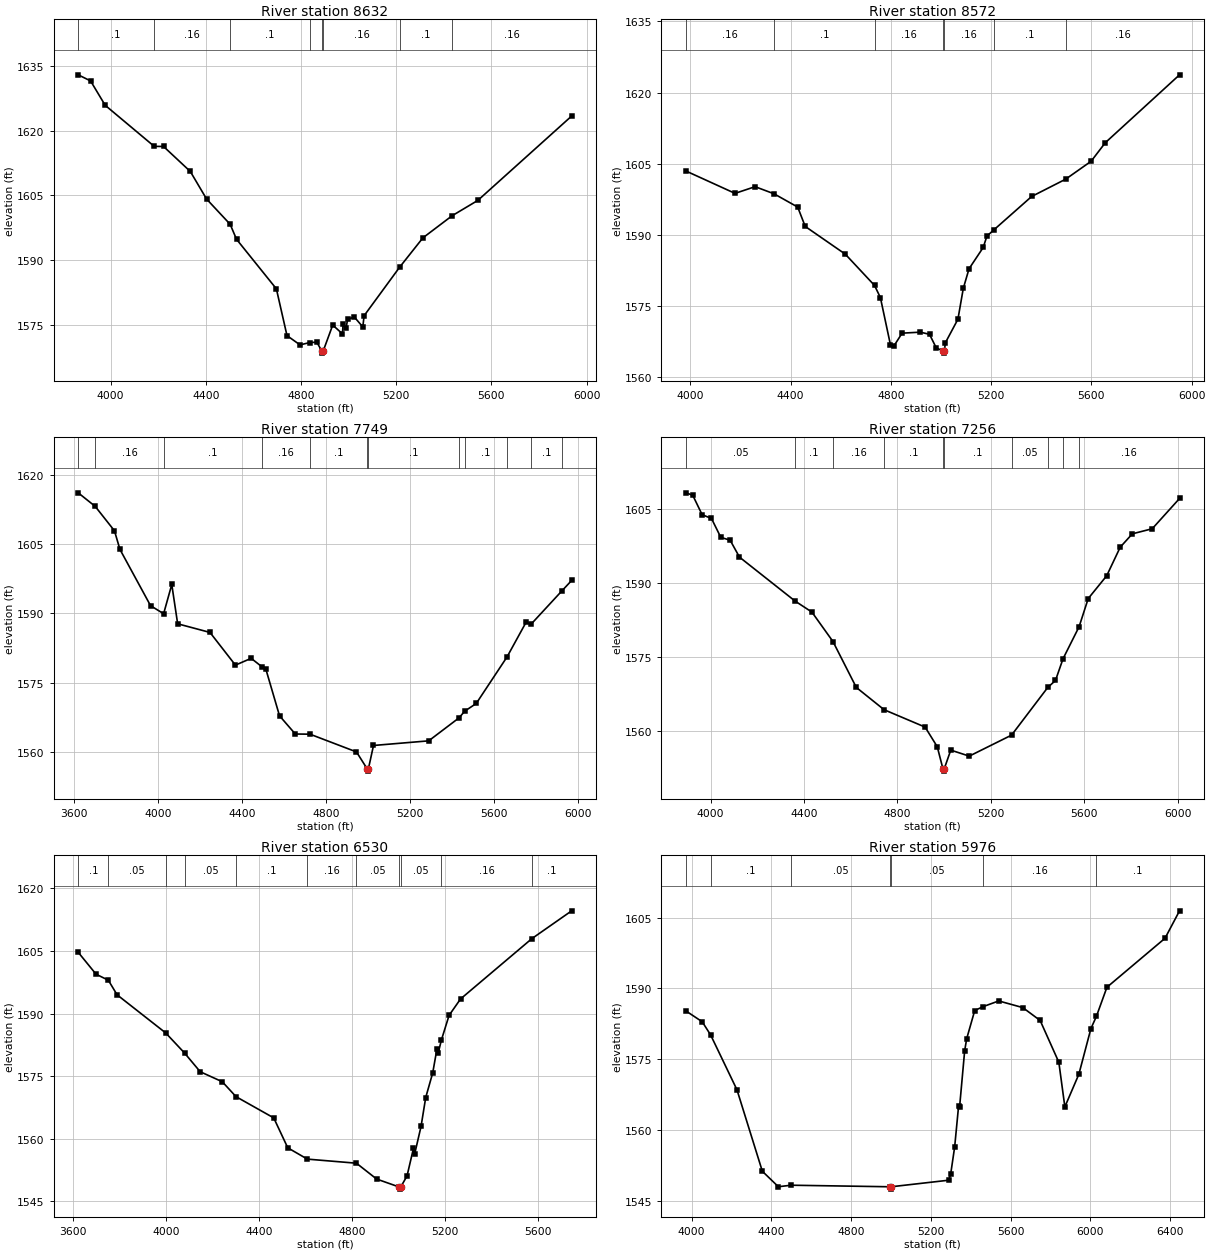
Type RM Length L Ch R = 1 ,8632    ,60,60,60
BEGIN DESCRIPTION:
Mapping XS 801eb8d4
END DESCRIPTION:
XS GIS Cut Line= 5
      2841877.64     10026096.71      2842924.47     10026318.06
      2842968.74     10026307.64      2843031.24     10026247.75
      2843754.35     10025761.34
#Sta/Elev= 30
  3863.9 1632.91  3915.8  1631.5  3977.2 1625.85  4183.3 1616.33  4222.5  1616.3
  4334.9 1610.51  4403.4 1604.11  4502.3 1598.27  4529.1 1594.79  4696.6  1583.3
  4741.2 1572.46    4796 1570.31    4836 1570.84  4866.4 1570.94  4887.4  1568.9
  4890.1  1568.4  4893.4  1568.9  4933.4 1574.91  4974.3 1572.86    4977 1575.17
  4989.1 1574.14    4996 1576.26  5024.3 1576.76  5059.8 1574.47  5065.2 1577.07
  5214.4 1588.31  5312.3 1595.12  5434.9 1600.24  5543.3 1603.81  5937.4 1623.36
#Mann= 8 ,-1 , 0
  3863.9      .1       0  4183.3     .16       0  4502.3      .1       0
    4836     .16       0  4887.4     .07       0  4893.4     .16       0
  5214.4      .1       0  5434.9     .16       0
Bank Sta=4887.4,4893.4
XS Rating Curve= 0 ,0
Exp/Cntr=0.3,0.1

Type RM Length L Ch R = 1 ,8572    ,823,823,823
BEGIN DESCRIPTION:
MIDDLE FORK WILLIAMS CREEK 18.0
END DESCRIPTION:
XS GIS Cut Line= 3
      2842043.13     10026453.23       2842873.2     10026444.21
      2843802.46      10025785.6
#Sta/Elev= 30
  3982.7 1603.46    4178 1598.76  4258.1 1600.17  4333.7 1598.67  4428.1 1595.87
  4458.1 1591.79  4618.1 1585.94  4734.8 1579.34  4758.1 1576.79  4798.1 1566.86
  4812.8 1566.65  4844.7 1569.29  4917.3  1569.5  4954.1 1569.05  4981.3 1566.15
  5007.9 1565.58  5010.6 1565.08  5013.9 1565.58    5017 1567.23  5067.5 1572.23
  5088.9 1578.73  5111.8 1582.86  5168.4 1587.36  5183.2 1589.76  5211.7  1591.1
  5361.6  1598.1  5497.4 1601.75    5599 1605.53  5655.6 1609.44  5951.8 1623.75
#Mann= 7 ,-1 , 0
  3982.7     .16       0  4333.7      .1       0  4734.8     .16       0
  5007.9     .07       0  5013.9     .16       0  5211.7      .1       0
  5497.4     .16       0
Bank Sta=5007.9,5013.9
XS Rating Curve= 0 ,0
Exp/Cntr=0.3,0.1

Type RM Length L Ch R = 1 ,7749    ,493,493,493
BEGIN DESCRIPTION:
MIDDLE FORK WILLIAMS CREEK 16.0
END DESCRIPTION:
XS GIS Cut Line= 3
      2841907.82     10026759.99      2843576.94     10027003.59
      2844163.35     10026696.85
#Sta/Elev= 30
  3621.4 1616.07  3702.2 1613.14  3793.9 1607.86  3819.8 1603.85  3965.7 1591.66
  4027.9 1589.92  4066.7 1596.24  4094.7 1587.74  4248.6 1585.87  4369.6  1578.8
  4444.7 1580.27  4497.7 1578.37  4514.7  1577.9  4579.6 1567.83  4654.6  1563.9
  4724.7 1563.86  4945.9 1560.02  4996.6 1556.37  4999.3 1555.87  5002.6 1556.37
  5026.8 1561.42  5289.5 1562.42  5434.7 1567.42  5460.6 1568.83  5515.8  1570.5
  5662.5 1580.58  5752.9 1588.06  5776.4 1587.63  5922.7 1594.82    5970 1597.12
#Mann= 12 ,-1 , 0
  3621.4      .1       0  3702.2     .16       0  4027.9      .1       0
  4497.7     .16       0  4724.7      .1       0  4996.6     .07       0
  5002.6      .1       0  5434.7     .05       0  5460.6      .1       0
  5662.5     .16       0  5776.4      .1       0  5922.7     .16       0
Bank Sta=4996.6,5002.6
XS Rating Curve= 0 ,0
Exp/Cntr=0.3,0.1

Type RM Length L Ch R = 1 ,7256    ,726,726,726
BEGIN DESCRIPTION:
MIDDLE FORK WILLIAMS CREEK 15.0
END DESCRIPTION:
XS GIS Cut Line= 3
      2842349.88     10027400.57      2843315.29     10027409.59
      2844289.67     10026805.12
#Sta/Elev= 30
  3895.4 1608.38    3924 1607.88    3964 1603.94    4004 1603.17    4044 1599.33
    4084 1598.75    4124 1595.31    4362 1586.38    4434 1584.14  4524.2 1578.15
    4624 1568.83    4743  1564.3  4918.5 1560.77  4970.5 1556.78  4994.6 1552.32
  4997.3 1551.82  5000.6 1552.32  5028.3 1556.09  5107.5 1554.87  5288.6 1559.14
  5443.7 1568.84  5476.5 1570.24  5508.7 1574.64  5577.6 1581.17  5616.6 1586.89
  5695.7 1591.52  5753.6 1597.33  5805.5 1600.05  5890.6 1601.08  6007.5 1607.23
#Mann= 10 ,-1 , 0
  3895.4     .05       0    4362      .1       0  4524.2     .16       0
    4743      .1       0  4994.6     .07       0  5000.6      .1       0
  5288.6     .05       0  5443.7      .1       0  5508.7     .05       0
  5577.6     .16       0
Bank Sta=4994.6,5000.6
XS Rating Curve= 0 ,0
Exp/Cntr=0.3,0.1

Type RM Length L Ch R = 1 ,6530    ,554,554,554
BEGIN DESCRIPTION:
MIDDLE FORK WILLIAMS CREEK 14.0
END DESCRIPTION:
XS GIS Cut Line= 3
       2842422.1     10027707.33      2844163.39     10027878.75
      2844497.18     10027716.37
#Sta/Elev= 30
  3622.8 1604.67  3699.5 1599.42  3752.1 1597.99    3790 1594.48  3998.8 1585.35
  4080.4  1580.5  4147.1 1576.05  4242.1 1573.65    4301 1570.08  4463.2 1564.99
  4523.5 1557.82  4607.7 1555.11  4818.7 1554.13  4905.3 1550.34  5002.8 1548.42
  5005.6 1547.92  5008.8 1548.42    5036 1551.06  5063.6 1557.66  5068.6 1556.27
  5096.3 1562.94  5116.4 1569.87  5146.5 1575.78  5164.9 1581.58  5169.9 1580.48
  5183.7 1583.63  5216.8 1589.56  5266.1 1593.49  5572.5 1607.94  5743.7 1614.61
#Mann= 11 ,-1 , 0
  3622.8      .1       0  3752.1     .05       0  3998.8      .1       0
  4080.4     .05       0    4301      .1       0  4607.7     .16       0
  4818.7     .05       0  5002.8    .033       0  5008.8     .05       0
  5183.7     .16       0  5572.5      .1       0
Bank Sta=5002.8,5008.8
XS Rating Curve= 0 ,0
Exp/Cntr=0.3,0.1

Type RM Length L Ch R = 1 ,5976    ,603,603,603
BEGIN DESCRIPTION:
MIDDLE FORK WILLIAMS CREEK 13.0
END DESCRIPTION:
XS GIS Cut Line= 2
      2842737.84     10028293.78      2845200.92     10028537.38
#Sta/Elev= 30
  3972.7 1585.19  4053.7 1582.91  4095.9 1580.11  4227.9 1568.49  4355.2 1551.21
  4435.6 1547.93  4499.7 1548.25  4995.3 1547.92  4998.1 1547.42  5001.3 1547.92
  5289.7 1549.31  5299.8 1550.58  5319.9 1556.38  5339.4 1564.97  5344.4 1564.75
  5370.1 1576.79  5380.2 1579.32  5420.4 1585.29  5461.7 1586.11  5540.9 1587.33
  5661.5 1585.92  5748.6 1583.19  5842.4 1574.33  5872.6 1564.86  5942.9 1571.79
  6003.2 1581.46  6030.8 1584.05  6083.6 1590.23    6375 1600.62  6447.8 1606.44
#Mann= 7 ,-1 , 0
  3972.7     .05       0  4095.9      .1       0  4499.7     .05       0
  4995.3    .033       0  5001.3     .05       0  5461.7     .16       0
  6030.8      .1       0
Bank Sta=4995.3,5001.3
XS Rating Curve= 0 ,0
Exp/Cntr=0.3,0.1

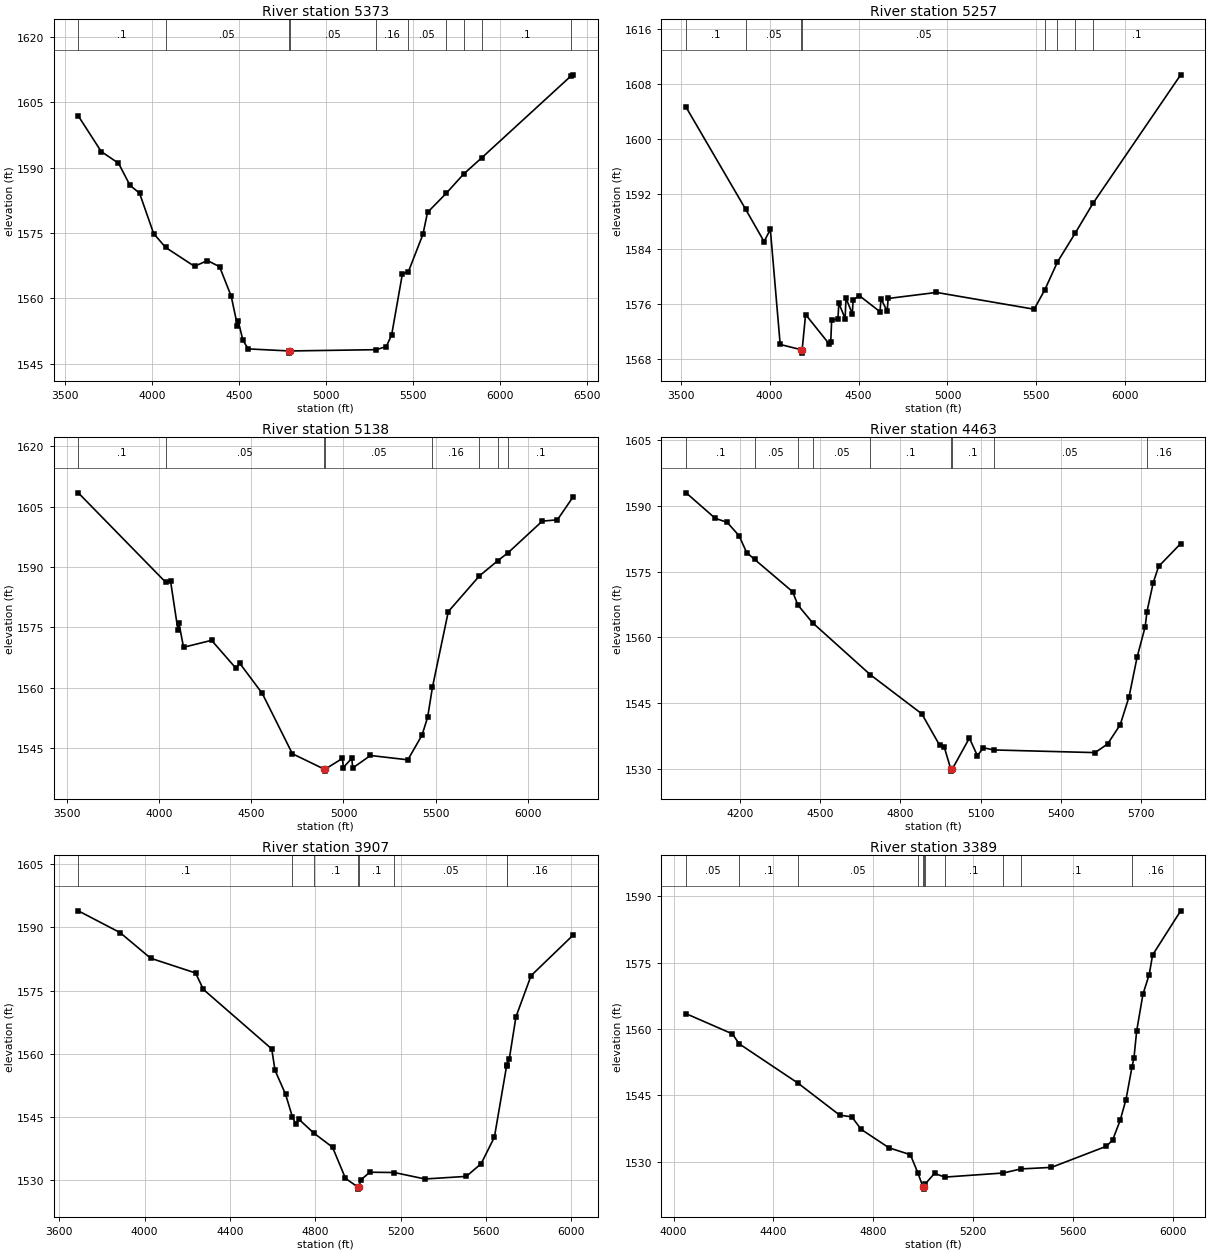
Type RM Length L Ch R = 1 ,5373    ,116,116,116
BEGIN DESCRIPTION:
MIDDLE FORK WILLIAMS CREEK 12.0
END DESCRIPTION:
XS GIS Cut Line= 4
      2842378.28     10028507.92      2843086.58     10028834.29
      2844406.02     10029167.62      2845100.49     10029285.68
#Sta/Elev= 30
  3576.1 1601.88  3708.4 1593.69  3807.5 1591.02  3873.6 1585.95  3928.6 1584.15
  4009.7 1574.88  4078.6  1571.7  4244.8 1567.36  4319.2 1568.69  4388.9 1567.28
  4455.8 1560.52  4491.7 1553.78  4496.9 1554.72  4522.9 1550.43  4553.9 1548.42
  4788.1 1547.95  4790.9 1547.45  4794.1 1547.95  5290.3 1548.24  5348.1 1548.96
    5379 1551.66  5440.9 1565.69  5474.1 1566.02  5558.8  1574.7  5585.3 1579.74
    5693 1584.12  5792.6 1588.52  5896.8 1592.25  6408.4 1610.96  6421.3  1611.3
#Mann= 10 ,-1 , 0
  3576.1      .1       0  4078.6     .05       0  4788.1    .035       0
  4794.1     .05       0  5290.3     .16       0  5474.1     .05       0
    5693      .1       0  5792.6     .16       0  5896.8      .1       0
  6408.4     .16       0
Bank Sta=4788.1,4794.1
XS Rating Curve= 0 ,0
Exp/Cntr=0.3,0.1

Type RM Length L Ch R = 1 ,5257    ,119,119,119
BEGIN DESCRIPTION:
MIDDLE FORK WILLIAMS CREEK 11.0
END DESCRIPTION:
XS GIS Cut Line= 4
      2842246.34     10028799.58      2843024.08     10028931.51
      2844315.74     10029271.79      2844961.57      10029382.9
#Sta/Elev= 30
    3531 1604.56  3865.5 1589.74  3969.3 1585.04  4004.5 1586.81  4059.8 1570.09
  4177.4 1569.33  4180.2 1568.83  4183.4 1569.33  4202.6 1574.44  4334.7 1570.18
    4344 1570.47  4349.2 1573.65  4384.4 1573.77  4389.5 1576.08  4424.7 1573.86
  4429.8 1576.81    4465 1574.56  4470.1 1576.59  4505.3 1577.17    4621 1574.84
  4626.2 1576.72  4661.4 1574.92  4666.5 1576.77  4938.3 1577.65  5487.2 1575.21
  5546.2 1577.98  5618.5 1582.08  5718.4 1586.28  5817.8 1590.59  6310.9 1609.27
#Mann= 8 ,-1 , 0
    3531      .1       0  3865.5     .05       0  4177.4    .035       0
  4183.4     .05       0  5546.2     .16       0  5618.5      .1       0
  5718.4     .05       0  5817.8      .1       0
Bank Sta=4177.4,4183.4
XS Rating Curve= 0 ,0
Exp/Cntr=0.3,0.1

Type RM Length L Ch R = 1 ,5138    ,675,675,675
BEGIN DESCRIPTION:
MIDDLE FORK WILLIAMS CREEK 10.0
END DESCRIPTION:
XS GIS Cut Line= 3
       2842232.4     10028973.18      2842878.24     10029063.46
      2844871.33     10029466.24
#Sta/Elev= 30
  3560.1 1608.42  4034.7 1586.19    4061 1586.53  4101.1 1574.37  4106.1 1576.13
  4131.7 1570.02  4283.9 1571.75  4416.5 1564.79  4436.3 1566.08  4559.3 1558.53
  4722.6 1543.56  4895.1 1539.73  4897.9 1539.23  4901.1 1539.73  4994.5 1542.39
  4999.6 1540.12  5045.2 1542.43  5050.4 1540.01  5146.7 1543.12  5349.7 1542.04
  5426.5 1548.18  5457.1 1552.62  5483.1 1560.07  5569.3 1578.89  5738.3 1587.77
  5838.1 1591.55  5894.8 1593.56  6079.4 1601.38  6161.7 1601.71  6245.6 1607.33
#Mann= 8 ,-1 , 0
  3560.1      .1       0  4034.7     .05       0  4895.1    .035       0
  4901.1     .05       0  5483.1     .16       0  5738.3      .1       0
  5838.1     .05       0  5894.8      .1       0
Bank Sta=4895.1,4901.1
XS Rating Curve= 0 ,0
Exp/Cntr=0.3,0.1

Type RM Length L Ch R = 1 ,4463    ,556,556,556
BEGIN DESCRIPTION:
MIDDLE FORK WILLIAMS CREEK 9.0
END DESCRIPTION:
XS GIS Cut Line= 3
       2842566.4     10029259.15      2843667.16     10029818.55
      2844280.67     10029881.71
#Sta/Elev= 30
  3997.9 1593.03  4107.1  1587.2  4151.6 1586.29  4196.1 1583.23  4224.6 1579.39
  4254.5 1577.81  4396.4 1570.45  4416.6 1567.37  4471.1 1563.36  4687.7 1551.46
  4880.3 1542.53  4947.1 1535.34  4963.7 1535.06  4988.6 1529.94  4991.3 1529.44
  4994.6 1529.94  5058.4 1536.99  5088.3 1532.96  5110.7 1534.79  5149.2 1534.28
  5528.9 1533.67  5575.8 1535.64    5623 1540.04  5656.2 1546.45  5686.3  1555.5
  5716.5 1562.44  5723.2  1565.9  5746.7 1572.52  5766.8 1576.21  5849.4 1581.43
#Mann= 9 ,-1 , 0
  3997.9      .1       0  4254.5     .05       0  4416.6      .1       0
  4471.1     .05       0  4687.7      .1       0  4988.6     .07       0
  4994.6      .1       0  5149.2     .05       0  5723.2     .16       0
Bank Sta=4988.6,4994.6
XS Rating Curve= 0 ,0
Exp/Cntr=0.3,0.1

Type RM Length L Ch R = 1 ,3907    ,518,518,518
BEGIN DESCRIPTION:
MIDDLE FORK WILLIAMS CREEK 8.0
END DESCRIPTION:
XS GIS Cut Line= 3
      2842290.19     10029753.67      2843098.75     10030251.62
      2844452.14      10030044.1
#Sta/Elev= 30
  3689.2 1593.94  3885.3 1588.77  4028.3  1582.7  4239.2 1579.19  4275.6  1575.3
  4596.2 1561.18  4611.7 1556.09  4660.8 1550.46  4693.1 1545.05  4709.3 1543.32
  4724.2 1544.46  4793.6 1541.21  4881.3 1537.86    4942 1530.47  4999.7 1528.42
  5002.5 1527.92  5005.7 1528.42  5012.8 1530.05    5056 1531.93  5170.8 1531.86
  5314.5 1530.33  5508.6 1530.94  5577.9 1533.95  5640.1 1540.24  5697.2  1557.1
    5698 1557.36  5709.7 1558.72  5741.2  1568.8  5812.1 1578.56    6008 1588.12
#Mann= 8 ,-1 , 0
  3689.2      .1       0  4693.1     .05       0  4793.6      .1       0
  4999.7     .07       0  5005.7      .1       0  5170.8     .05       0
  5697.2      .1       0    5698     .16       0
Bank Sta=4999.7,5005.7
XS Rating Curve= 0 ,0
Exp/Cntr=0.3,0.1

Type RM Length L Ch R = 1 ,3389    ,695,695,695
BEGIN DESCRIPTION:
MIDDLE FORK WILLIAMS CREEK 6.0
END DESCRIPTION:
XS GIS Cut Line= 2
       2842755.9     10030991.45      2844613.98     10030305.95
#Sta/Elev= 30
  4050.1 1563.44  4235.3 1558.88  4262.4 1556.64  4498.5 1547.72  4665.2 1540.49
  4713.7  1540.1  4751.2 1537.27  4862.2 1533.11  4948.2 1531.54    4979 1527.31
  4998.5 1524.25  5001.2 1523.75  5004.5 1524.25  5007.7 1524.91  5044.8 1527.31
  5085.8 1526.47  5320.1  1527.4  5391.2 1528.32  5513.1 1528.67  5732.6 1533.44
  5757.7 1534.81  5788.2  1539.3  5811.5 1544.01  5835.7 1551.39  5843.5 1553.44
  5854.4 1559.55  5879.5 1567.86  5904.6 1572.31  5918.1 1576.73  6030.6 1586.72
#Mann= 11 ,-1 , 0
  4050.1     .05       0  4262.4      .1       0  4498.5     .05       0
    4979      .1       0  4998.5     .07       0  5004.5      .1       0
  5007.7     .16       0  5085.8      .1       0  5320.1     .16       0
  5391.2      .1       0  5835.7     .16       0
Bank Sta=4998.5,5004.5
XS Rating Curve= 0 ,0
Exp/Cntr=0.3,0.1

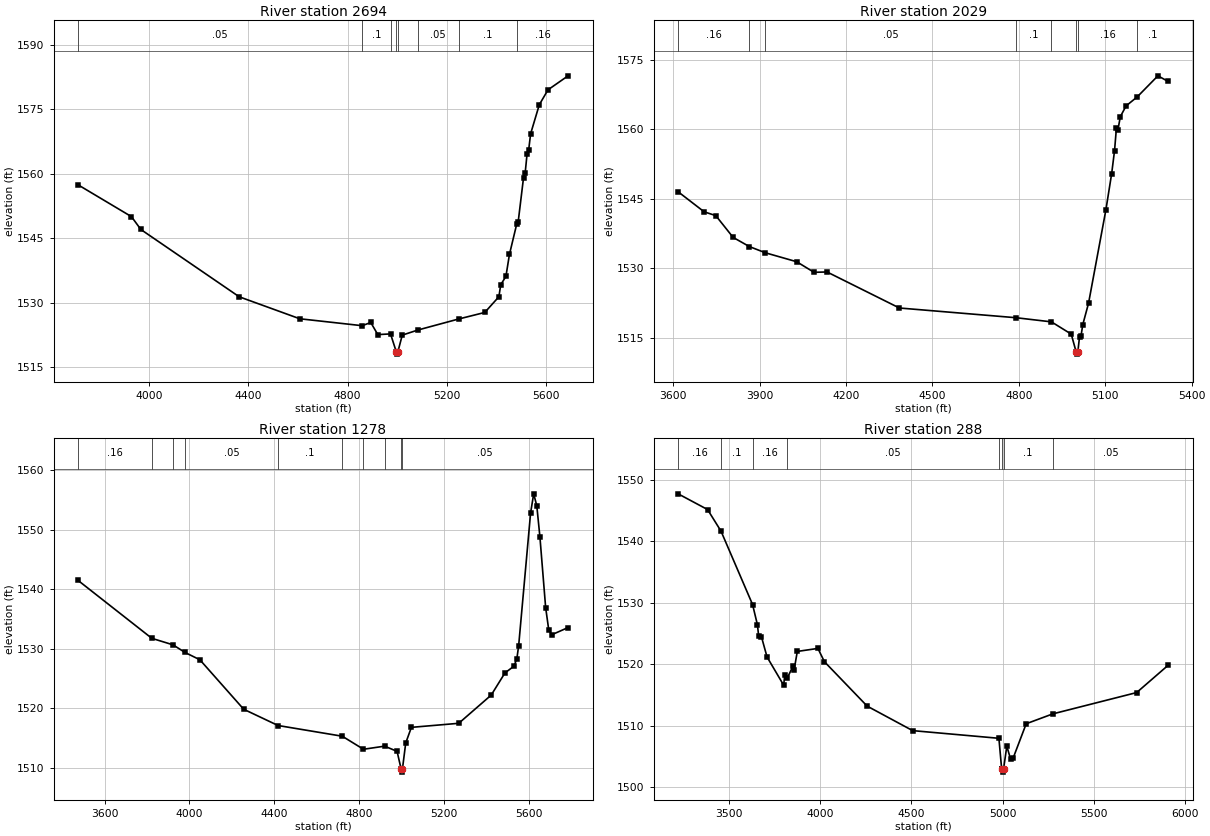
Type RM Length L Ch R = 1 ,2694    ,665,665,665
BEGIN DESCRIPTION:
MIDDLE FORK WILLIAMS CREEK 5.0
END DESCRIPTION:
XS GIS Cut Line= 3
      2842999.47     10031298.22      2844100.23      10031090.7
      2844740.85     10030522.26
#Sta/Elev= 30
  3713.1 1557.39  3928.5 1549.99  3966.5    1547  4363.3 1531.35  4607.6 1526.24
  4859.2 1524.63  4893.8 1525.38  4922.2 1522.56  4973.6 1522.72    4997 1518.52
  4999.7 1518.02    5003 1518.52  5020.9 1522.44  5084.7 1523.64  5247.8 1526.18
  5353.7 1527.71  5410.6 1531.36  5418.1 1534.16    5439 1536.09  5453.2  1541.2
    5483 1548.37  5488.4 1548.74  5510.1 1559.08  5516.8 1560.23  5524.3 1564.57
    5531 1565.59  5538.6 1569.25  5573.7 1576.02  5608.8 1579.48  5689.7 1582.73
#Mann= 8 ,-1 , 0
  3713.1     .05       0  4859.2      .1       0  4973.6     .16       0
    4997     .07       0    5003     .16       0  5084.7     .05       0
  5247.8      .1       0    5483     .16       0
Bank Sta=4997,5003
XS Rating Curve= 0 ,0
Exp/Cntr=0.3,0.1

Type RM Length L Ch R = 1 ,2029    ,751,751,751
BEGIN DESCRIPTION:
MIDDLE FORK WILLIAMS CREEK 3.0
END DESCRIPTION:
XS GIS Cut Line= 2
      2843288.22     10031559.86      2844983.93     10031424.56
#Sta/Elev= 30
  3617.3 1546.54  3707.8 1542.21    3748  1541.4  3808.2  1536.7  3864.3 1534.73
  3920.1 1533.38  4028.9 1531.45    4089 1529.17  4134.3 1529.24  4385.4 1521.47
  4790.8 1519.37  4913.2 1518.48  4981.9 1515.84  4998.9 1512.02  5001.7 1511.52
  5004.9 1512.02  5010.7 1515.26  5015.7 1515.37    5022 1517.88  5042.1 1522.52
  5102.3 1542.66  5122.3 1550.48  5132.3 1555.43  5138.8 1560.29  5143.8 1559.84
  5152.4 1562.75  5172.5 1565.07  5211.2 1567.02  5282.8 1571.55  5318.4 1570.34
#Mann= 8 ,-1 , 0
  3617.3     .16       0  3864.3      .1       0  3920.1     .05       0
  4790.8      .1       0  4913.2     .16       0  4998.9     .07       0
  5004.9     .16       0  5211.2      .1       0
Bank Sta=4998.9,5004.9
XS Rating Curve= 0 ,0
Exp/Cntr=0.3,0.1

Type RM Length L Ch R = 1 ,1278    ,990,990,990
BEGIN DESCRIPTION:
MIDDLE FORK WILLIAMS CREEK 2.0
END DESCRIPTION:
XS GIS Cut Line= 3
      2843234.08     10031812.48      2844993.44     10032173.37
      2845300.03     10031758.58
#Sta/Elev= 30
  3474.6 1541.51  3822.8 1531.78  3922.6 1530.69  3979.1 1529.41  4049.4 1528.18
  4256.1 1519.87  4418.1 1517.14  4721.2 1515.34  4821.1 1513.15  4920.9 1513.67
  4979.7  1512.8  4998.9 1509.81  5001.7 1509.31  5004.9 1509.81  5020.5  1514.2
  5047.2 1516.83  5270.6 1517.51  5423.8 1522.25  5488.6 1525.97  5531.3 1527.11
  5544.9 1528.38  5553.3 1530.55  5609.6 1552.84  5624.2 1556.05  5638.9 1554.02
  5653.5 1548.85  5680.6 1536.95  5695.2 1533.21  5709.8 1532.39  5786.4 1533.59
#Mann= 10 ,-1 , 0
  3474.6     .16       0  3822.8     .05       0  3922.6      .1       0
  3979.1     .05       0  4418.1      .1       0  4721.2     .05       0
  4821.1      .1       0  4920.9     .05       0  4998.9    .035       0
  5004.9     .05       0
Bank Sta=4998.9,5004.9
XS Rating Curve= 0 ,0
Exp/Cntr=0.3,0.1

Type RM Length L Ch R = 1 ,288     ,0,0,0
BEGIN DESCRIPTION:
MIDDLE FORK WILLIAMS CREEK 1.0
END DESCRIPTION:
XS GIS Cut Line= 5
        2843105.     10032261.84      2844568.54     10032944.13
      2844797.71     10032694.13      2845047.71     10032511.83
      2845125.83     10032100.39
#Sta/Elev= 30
  3223.5 1547.74  3384.6 1545.18  3458.2 1541.66  3630.9 1529.71  3657.6  1526.4
  3664.5 1524.51  3679.7 1524.44  3710.2 1521.16  3801.1 1516.57  3807.2 1518.23
  3821.1 1517.75  3852.9 1519.72  3858.4 1519.08  3875.8 1522.07  3988.6 1522.56
    4024  1520.4  4258.2 1513.16  4507.2 1509.17  4979.2 1507.92  4994.2 1502.94
  4998.6 1502.91  5001.3 1502.41  5004.6 1502.91  5022.5 1506.63  5043.5  1504.5
  5057.7 1504.74  5128.6 1510.29  5274.4  1511.9  5733.2 1515.37  5905.6 1519.82
#Mann= 8 ,-1 , 0
  3223.5     .16       0  3458.2      .1       0  3630.9     .16       0
  3821.1     .05       0  4979.2      .1       0  4998.6     .07       0
  5004.6      .1       0  5274.4     .05       0
Bank Sta=4998.6,5004.6
XS Rating Curve= 0 ,0
Exp/Cntr=0.3,0.1

Chan Stop Cuts=-1
Use User Specified Reach Order=0
Composite Channel Slope=5