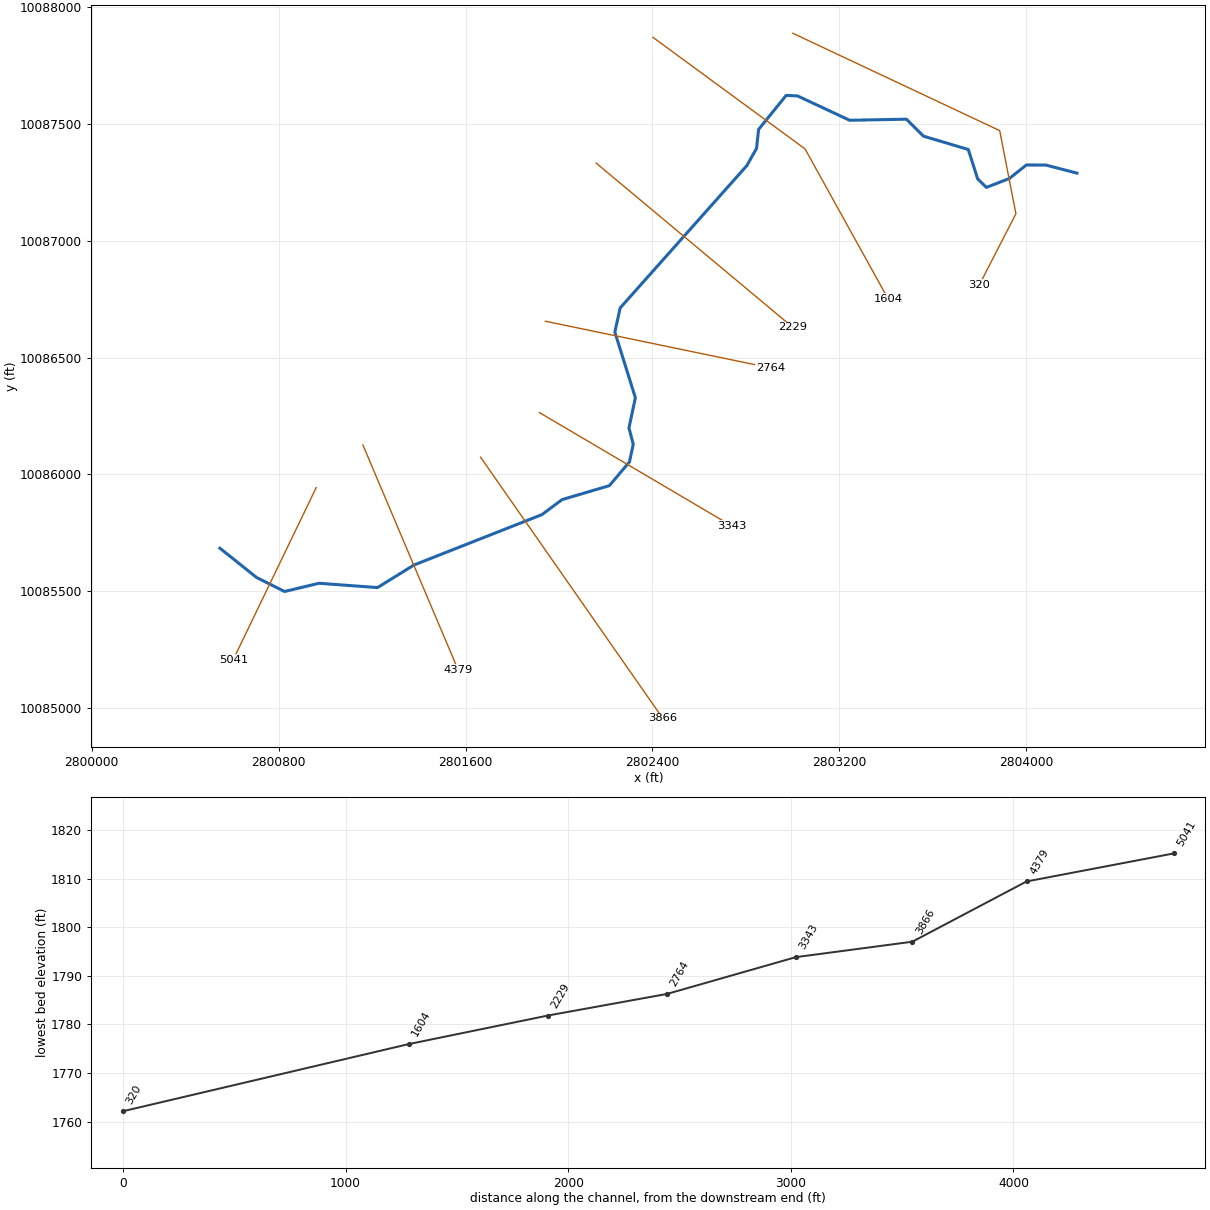
--- NORTH CAVE CREEK.prj (project) ---

Proj Title=NORTH CAVE CREEK Base Level Engineering
Current Plan=p01
Default Exp/Contr=0.3,0.1
English Units
Geom File=g01
Flow File=f01
Plan File=p01
Y Axis Title=Elevation
X Axis Title(PF)=Main Channel Distance
X Axis Title(XS)=Station
BEGIN DESCRIPTION:
NORTH CAVE CREEK
END DESCRIPTION:
DSS Export Rating Curves= 0
DSS Export Rating Curve Sorted= 0
DSS Export Volume Flow Curves= 0
DXF OffsetX= 0
DXF OffsetY= 0
DXF ScaleX= 1
DXF ScaleY= 10

--- NORTH CAVE CREEK.p01 (plan) ---

Plan Title=Multiple Run
Short Identifier=Multiple
Geom File=g01
Flow File=f01
Subcritical Flow
K Sum by GR= 0
Std Step Tol= 0.01
Critical Tol= 0.01
Num of Std Step Trials= 20
Max Error Tol= 0.3
Flow Tol Ratio= 0.001
Split Flow NTrial= 30
Split Flow Tol= 0.02
Split Flow Ratio= 0.02
Log Output Level= 0
Friction Slope Method= 1
Unsteady Friction Slope Method= 2
Unsteady Bridges Friction Slope Method= 1
Parabolic Critical Depth
Global Vel Dist=  1 , 1 , 1
Global Log Level= 0
CheckData=True
Encroach Param= -1, 0, 0, 0
BEGIN DESCRIPTION:
Multiple Run
END DESCRIPTION:

--- NORTH CAVE CREEK.f01 (steady flow) ---

Flow Title=Multiple
Program Version=4.10
Number of Profiles= 7
Profile Names=10-year,25-year,50-year,1pct_min,100-year,1pct_plu,500-year
River Rch & RM=NORTH CAVE CREEK,Reach-1         ,5041
    1104    1610    2050    1909    2582    3492    4113
Boundary for River Rch & Prof#=NORTH CAVE CREEK,Reach-1         , 1
Up Type= 0
Dn Type= 3
Dn Slope=0.0108
Boundary for River Rch & Prof#=NORTH CAVE CREEK,Reach-1         , 2
Up Type= 0
Dn Type= 3
Dn Slope=0.0108
Boundary for River Rch & Prof#=NORTH CAVE CREEK,Reach-1         , 3
Up Type= 0
Dn Type= 3
Dn Slope=0.0108
Boundary for River Rch & Prof#=NORTH CAVE CREEK,Reach-1         , 4
Up Type= 0
Dn Type= 3
Dn Slope=0.0108
Boundary for River Rch & Prof#=NORTH CAVE CREEK,Reach-1         , 5
Up Type= 0
Dn Type= 3
Dn Slope=0.0108
Boundary for River Rch & Prof#=NORTH CAVE CREEK,Reach-1         , 6
Up Type= 0
Dn Type= 3
Dn Slope=0.0108
Boundary for River Rch & Prof#=NORTH CAVE CREEK,Reach-1         , 7
Up Type= 0
Dn Type= 3
Dn Slope=0.0108
DSS Import GetInterval= 0
DSS Import GetPeak= 0
DSS Import FillOption= 0

--- NORTH CAVE CREEK.g01 (geometry) ---

Geom Title=Existing Conditions
Program Version=4.10

River Reach=NORTH CAVE CREEK,Reach-1
Reach XY= 30
      2800548.47     10085683.73      2800705.64     10085558.29
      2800825.18     10085498.52      2800972.56     10085533.73
      2801223.08      10085515.3      2801379.28     10085611.96
      2801926.83     10085827.65      2802013.23     10085891.88
      2802215.31     10085951.53       2802301.5     10086053.34
      2802317.71     10086128.95      2802299.29     10086198.49
       2802326.8     10086327.87      2802238.86      10086609.1
      2802261.77     10086712.35      2802803.58     10087321.01
      2802845.38     10087395.01      2802854.24     10087476.33
      2802972.33     10087622.09      2803021.11     10087619.73
        2803244.     10087515.51      2803487.08      10087520.2
      2803559.96      10087447.5      2803751.83     10087390.42
      2803791.95     10087264.66      2803829.22     10087228.11
       2803927.4     10087266.23      2804000.45     10087324.17
      2804083.39     10087323.91      2804216.74     10087289.33

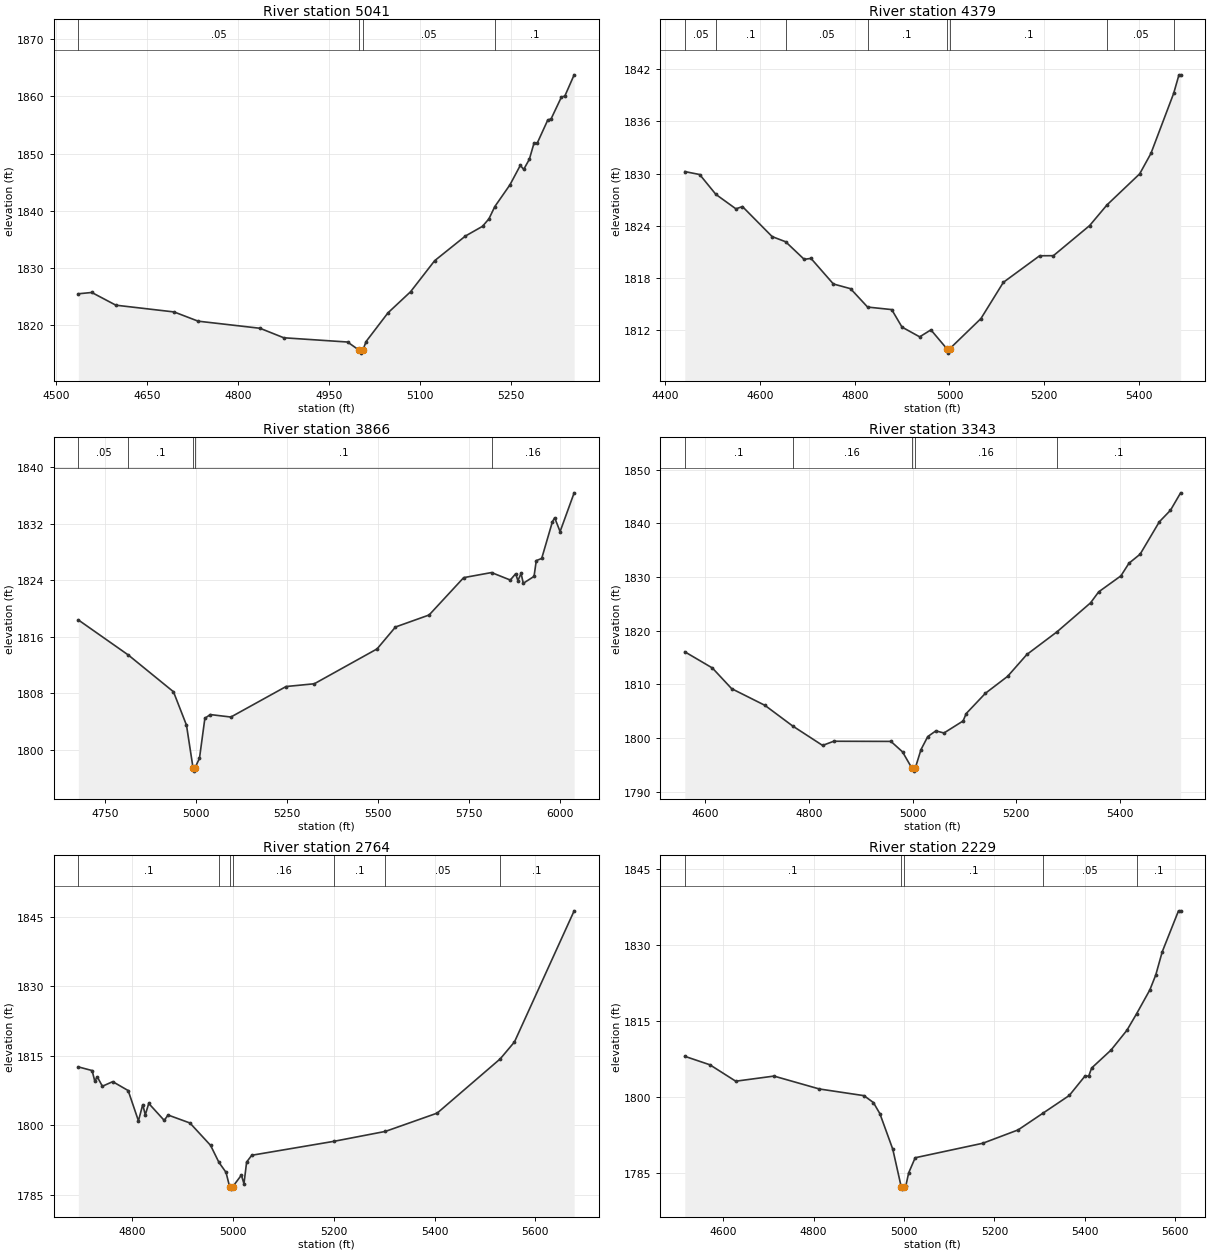
Type RM Length L Ch R = 1 ,5041    ,662,662,662
BEGIN DESCRIPTION:
NORTH CAVE CREEK 9.0
END DESCRIPTION:
XS GIS Cut Line= 2
       2800960.8     10085943.51      2800605.64      10085207.2
#Sta/Elev= 30
  4536.8 1825.52    4559 1825.75  4598.7 1823.53  4694.7 1822.35  4734.3 1820.74
  4836.3  1819.5  4875.6 1817.84  4980.7  1817.1  4999.9 1815.66  5002.6 1815.16
  5005.9 1815.66  5011.2 1817.18  5047.3 1822.19  5084.6 1825.88  5124.3  1831.3
  5175.1 1835.61  5203.2  1837.3  5213.8 1838.61  5223.5 1840.75  5248.4 1844.54
  5265.5 1847.94  5271.1 1847.24  5280.4    1849  5288.1 1851.82  5293.7 1851.89
  5310.7 1855.84  5316.3 1856.07  5333.3 1859.87  5338.9 1860.04  5354.3 1863.75
#Mann= 4 ,-1 , 0
  4536.8     .05       0  4999.9    .035       0  5005.9     .05       0
  5223.5      .1       0
Bank Sta=4999.9,5005.9
XS Rating Curve= 0 ,0
Exp/Cntr=0.3,0.1

Type RM Length L Ch R = 1 ,4379    ,513,513,513
BEGIN DESCRIPTION:
NORTH CAVE CREEK 8.0
END DESCRIPTION:
XS GIS Cut Line= 2
      2801160.45     10086125.83      2801568.45     10085162.25
#Sta/Elev= 30
  4441.4 1830.24  4472.8  1829.9    4507 1827.62  4549.3 1825.96  4563.1 1826.22
  4625.8 1822.77  4654.2 1822.18  4693.4 1820.16  4707.7 1820.27    4755 1817.33
  4791.2 1816.79  4827.2 1814.68  4878.1 1814.39  4899.8 1812.38  4937.1 1811.26
  4960.8 1812.06  4994.5 1809.89  4997.3 1809.39  5000.5 1809.89  5066.4 1813.36
  5113.7 1817.52  5190.2 1820.57  5219.3 1820.58  5295.8 1824.04  5332.4 1826.41
  5401.4 1829.98  5425.1 1832.32  5473.1 1839.22  5484.3 1841.35  5487.8 1841.35
#Mann= 8 ,-1 , 0
  4441.4     .05       0    4507      .1       0  4654.2     .05       0
  4827.2      .1       0  4994.5     .07       0  5000.5      .1       0
  5332.4     .05       0  5473.1      .1       0
Bank Sta=4994.5,5000.5
XS Rating Curve= 0 ,0
Exp/Cntr=0.3,0.1

Type RM Length L Ch R = 1 ,3866    ,523,523,523
BEGIN DESCRIPTION:
NORTH CAVE CREEK 6.0
END DESCRIPTION:
XS GIS Cut Line= 2
      2801663.94     10086073.71      2802444.34     10084955.14
#Sta/Elev= 30
  4675.6 1818.41  4813.2 1813.44  4937.3 1808.24  4973.1 1803.51    4991  1797.5
  4993.8    1797    4997  1797.5  5008.9 1798.84  5023.7 1804.48  5038.5 1805.01
  5095.2 1804.66    5247 1808.98  5324.7 1809.37  5497.4 1814.31    5548 1817.41
  5640.5 1819.11  5735.6  1824.4  5812.2 1825.12  5863.8 1824.06  5878.6 1824.95
  5884.7 1823.98  5893.5 1824.99  5899.6  1823.6  5929.2 1824.58  5935.3 1826.81
  5950.2 1827.12  5979.8 1832.33  5985.9 1832.88  6000.8 1830.92  6039.5 1836.41
#Mann= 5 ,-1 , 0
  4675.6     .05       0  4813.2      .1       0    4991     .07       0
    4997      .1       0  5812.2     .16       0
Bank Sta=4991,4997
XS Rating Curve= 0 ,0
Exp/Cntr=0.3,0.1

Type RM Length L Ch R = 1 ,3343    ,579,579,579
BEGIN DESCRIPTION:
NORTH CAVE CREEK 5.0
END DESCRIPTION:
XS GIS Cut Line= 2
      2801915.71     10086264.68      2802740.22     10085778.65
#Sta/Elev= 30
  4560.3 1816.07  4613.6 1813.05  4650.7  1809.2    4715 1806.09  4768.4 1802.25
  4826.3 1798.62  4847.8  1799.4  4958.2 1799.37  4980.6 1797.42    4999 1794.33
  5001.8 1793.83    5005 1794.33  5016.2 1797.84  5029.3 1800.27  5044.9 1801.33
  5060.6 1800.94  5097.5 1803.18  5103.5 1804.56  5140.6 1808.34  5183.5  1811.5
  5220.6 1815.57  5278.6 1819.78  5343.5 1825.19  5359.2 1827.24  5402.1 1830.22
  5417.7 1832.58  5439.2 1834.26  5476.3  1840.3  5497.8 1842.45  5517.4  1845.7
#Mann= 5 ,-1 , 0
  4560.3      .1       0  4768.4     .16       0    4999     .07       0
    5005     .16       0  5278.6      .1       0
Bank Sta=4999,5005
XS Rating Curve= 0 ,0
Exp/Cntr=0.3,0.1

Type RM Length L Ch R = 1 ,2764    ,535,535,535
BEGIN DESCRIPTION:
NORTH CAVE CREEK 4.0
END DESCRIPTION:
XS GIS Cut Line= 2
      2801941.73     10086655.32      2802904.38     10086455.86
#Sta/Elev= 30
  4693.7  1812.6    4721 1811.81  4726.2 1809.58  4731.3 1810.44  4741.4 1808.43
  4761.9 1809.42  4792.5  1807.5  4812.9 1800.97  4821.4 1804.47  4826.5 1802.27
  4833.3 1804.73    4864 1801.07  4871.6 1802.23    4915 1800.51  4955.9 1795.69
  4972.5 1792.02  4986.5 1789.88  4993.7 1786.76  4996.5 1786.26  4999.7 1786.76
    5017 1789.28  5022.1 1787.42  5027.4  1792.1  5037.6 1793.56  5200.9 1796.57
  5302.6  1798.7  5405.2 1802.64  5530.2 1814.33  5558.4 1817.97  5676.8 1846.23
#Mann= 7 ,-1 , 0
  4693.7      .1       0  4972.5     .16       0  4993.7     .07       0
  4999.7     .16       0  5200.9      .1       0  5302.6     .05       0
  5530.2      .1       0
Bank Sta=4993.7,4999.7
XS Rating Curve= 0 ,0
Exp/Cntr=0.3,0.1

Type RM Length L Ch R = 1 ,2229    ,625,625,625
BEGIN DESCRIPTION:
NORTH CAVE CREEK 3.0
END DESCRIPTION:
XS GIS Cut Line= 2
       2802158.7     10087332.43      2803000.72      10086629.3
#Sta/Elev= 30
  4514.9 1808.02  4570.4 1806.35  4627.6 1803.11  4712.2 1804.12  4812.4 1801.58
  4911.3 1800.26  4932.2  1798.9  4946.5 1796.71  4975.1 1789.68  4993.6 1782.32
  4996.4 1781.82  4999.6 1782.32  5003.7 1782.38  5010.2 1785.02  5024.6 1788.01
  5174.2 1790.87  5252.3  1793.5  5307.8 1796.83  5365.5 1800.29  5400.7 1804.17
  5408.5  1804.1    5415 1805.71  5457.9 1809.25  5493.1 1813.16  5514.7 1816.45
  5543.8 1821.12  5556.9 1824.07  5571.2 1828.64  5607.2 1836.72  5611.9 1836.72
#Mann= 5 ,-1 , 0
  4514.9      .1       0  4993.6     .07       0  4999.6      .1       0
  5307.8     .05       0  5514.7      .1       0
Bank Sta=4993.6,4999.6
XS Rating Curve= 0 ,0
Exp/Cntr=0.3,0.1

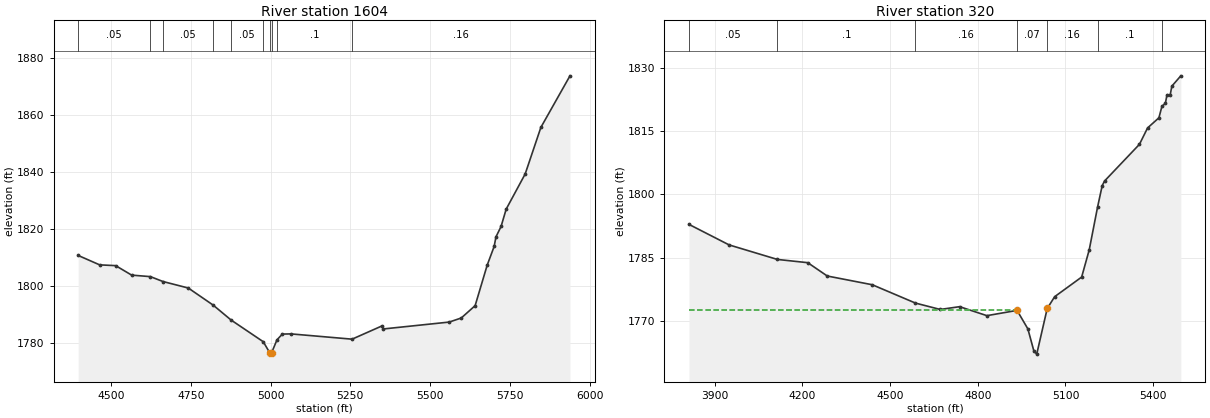
Type RM Length L Ch R = 1 ,1604    ,1284,1284,1284
BEGIN DESCRIPTION:
NORTH CAVE CREEK 2.0
END DESCRIPTION:
XS GIS Cut Line= 3
      2802401.77     10087870.61      2803052.82     10087393.17
      2803408.72     10086750.83
#Sta/Elev= 30
  4396.9 1810.59  4464.4 1807.28  4514.5 1807.01  4564.7 1803.68  4623.5 1803.15
    4663 1801.43  4742.2 1799.15  4820.1 1793.16  4876.3 1787.92  4977.1 1780.31
  4997.4 1776.45  5000.2 1775.95  5003.4 1776.45  5020.2 1780.97    5037 1782.99
  5064.1 1783.05  5255.5  1781.2  5348.3  1785.8    5354 1784.79    5560  1787.2
  5597.8 1788.63  5641.3 1792.97  5679.1 1807.18  5700.9 1813.74  5706.6 1817.11
  5722.6 1820.75  5738.6 1826.84  5798.1 1839.17  5847.4 1855.54  5938.6 1873.63
#Mann= 10 ,-1 , 0
  4396.9     .05       0  4623.5      .1       0    4663     .05       0
  4820.1     .16       0  4876.3     .05       0  4977.1     .16       0
  4997.4     .07       0  5003.4     .16       0  5020.2      .1       0
  5255.5     .16       0
Bank Sta=4997.4,5003.4
XS Rating Curve= 0 ,0
Exp/Cntr=0.3,0.1

Type RM Length L Ch R = 1 ,320     ,0,0,0
BEGIN DESCRIPTION:
NORTH CAVE CREEK 1.0
END DESCRIPTION:
XS GIS Cut Line= 4
      2803000.72     10087887.97      2803886.15      10087471.3
       2803955.6      10087115.4      2803799.36      10086811.6
#Sta/Elev= 30
  3811.9  1792.9  3949.3 1788.03  4114.3 1784.59  4218.3 1783.82    4285 1780.66
    4439 1778.59  4586.9 1774.24  4671.5 1772.73  4737.8 1773.39  4831.2 1771.26
  4934.4 1772.51  4971.4 1768.12  4991.8 1762.92  5001.7 1762.14  5037.6 1772.96
  5063.1 1775.76  5155.4 1780.41  5181.3 1786.86  5209.7 1796.95  5225.7 1802.09
  5233.7 1803.18  5353.1 1811.88  5380.9 1815.76  5419.7 1818.17  5430.1 1820.89
  5441.8  1821.6  5447.5 1823.63  5458.4 1823.62    5464 1825.67  5494.7 1828.12
#Mann= 7 ,-1 , 0
  3811.9     .05       0  4114.3      .1       0  4586.9     .16       0
  4934.4     .07       0  5037.6     .16       0  5209.7      .1       0
  5430.1     .16       0
#XS Ineff= 2 , 0
         4927.32 1772.51
Permanent Ineff=
       F       F
Bank Sta=4934.4,5037.6
XS Rating Curve= 0 ,0
Exp/Cntr=0.3,0.1

Chan Stop Cuts=-1
Use User Specified Reach Order=0
Composite Channel Slope=5