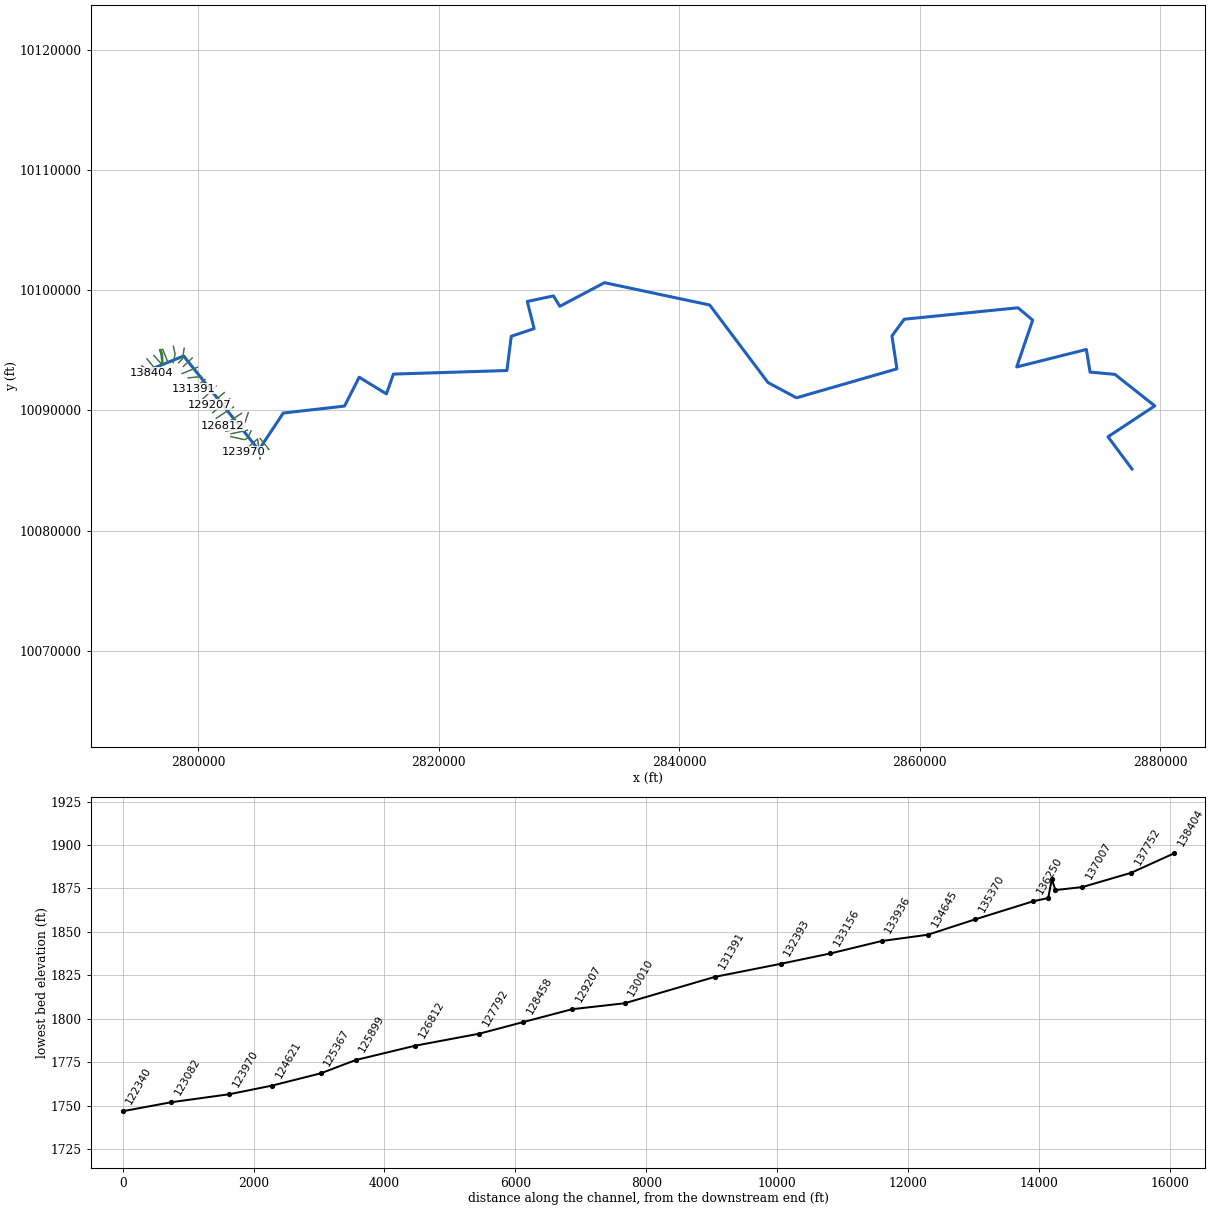
--- NORTH GRAPE CREEK.prj (project) ---

Proj Title=NORTH GRAPE CREEK Base Level Engineering
Current Plan=p01
Default Exp/Contr=0.3,0.1
English Units
Geom File=g01
Flow File=f01
Plan File=p01
Y Axis Title=Elevation
X Axis Title(PF)=Main Channel Distance
X Axis Title(XS)=Station
BEGIN DESCRIPTION:
NORTH GRAPE CREEK
END DESCRIPTION:
DSS Export Rating Curves= 0
DSS Export Rating Curve Sorted= 0
DSS Export Volume Flow Curves= 0
DXF OffsetX= 0
DXF OffsetY= 0
DXF ScaleX= 1
DXF ScaleY= 10

--- NORTH GRAPE CREEK.p01 (plan) ---

Plan Title=Multiple Run
Short Identifier=Multiple
Geom File=g01
Flow File=f01
Subcritical Flow
K Sum by GR= 0
Std Step Tol= 0.01
Critical Tol= 0.01
Num of Std Step Trials= 20
Max Error Tol= 0.3
Flow Tol Ratio= 0.001
Split Flow NTrial= 30
Split Flow Tol= 0.02
Split Flow Ratio= 0.02
Log Output Level= 0
Friction Slope Method= 1
Unsteady Friction Slope Method= 2
Unsteady Bridges Friction Slope Method= 1
Parabolic Critical Depth
Global Vel Dist=  1 , 1 , 1
Global Log Level= 0
CheckData=True
Encroach Param= -1, 0, 0, 0
BEGIN DESCRIPTION:
Multiple Run
END DESCRIPTION:

--- NORTH GRAPE CREEK.f01 (steady flow) ---

Flow Title=Multiple
Program Version=4.10
Number of Profiles= 7
Profile Names=10-year,25-year,50-year,1pct_min,100-year,1pct_plu,500-year
River Rch & RM=NORTH GRAPE CREE,Reach-1         ,138404
     717    1022    1281    1177    1592    2153    2464
River Rch & RM=NORTH GRAPE CREE,Reach-1         ,137007
    1088    1580    2007    1863    2520    3408    3989
River Rch & RM=NORTH GRAPE CREE,Reach-1         ,130010
    1449    2134    2735    2560    3463    4683    5574
River Rch & RM=NORTH GRAPE CREE,Reach-1         ,123970
    2344    3523    4579    4339    5869    7937    9684
River Rch & RM=NORTH GRAPE CREE,Reach-1         ,117462
    2425    3648    4744    4497    6082    8225   10044
River Rch & RM=NORTH GRAPE CREE,Reach-1         ,116686
    2425    3648    4744    4497    6082    8225   10044
River Rch & RM=NORTH GRAPE CREE,Reach-1         ,116116
    2997    4546    5944    5663    7658   10357   12771
River Rch & RM=NORTH GRAPE CREE,Reach-1         ,114829
    3470    5290    6943    6634    8972   12134   15057
River Rch & RM=NORTH GRAPE CREE,Reach-1         ,113468
    3470    5290    6943    6634    8972   12134   15057
River Rch & RM=NORTH GRAPE CREE,Reach-1         ,111580
    3470    5290    6943    6634    8972   12134   15057
River Rch & RM=NORTH GRAPE CREE,Reach-1         ,111078
    4035    6174    8121    7775   10515   14220   17708
River Rch & RM=NORTH GRAPE CREE,Reach-1         ,104302
    4185    6401    8419    8058   10897   14737   18342
River Rch & RM=NORTH GRAPE CREE,Reach-1         ,99341
    4232    6456    8475    8093   10945   14802   18341
River Rch & RM=NORTH GRAPE CREE,Reach-1         ,88740
    4466    6820    8960    8561   11578   15658   19423
River Rch & RM=NORTH GRAPE CREE,Reach-1         ,83538
    4498    6864    9010    8603   11635   15735   19489
River Rch & RM=NORTH GRAPE CREE,Reach-1         ,76382
    9212   14321   19047   18397   24879   33647   42621
River Rch & RM=NORTH GRAPE CREE,Reach-1         ,75546
    9212   14321   19047   18397   24879   33647   42621
River Rch & RM=NORTH GRAPE CREE,Reach-1         ,71484
   10563   16472   21957   21251   28740   38868   49429
River Rch & RM=NORTH GRAPE CREE,Reach-1         ,70442
   11003   17190   22945   22236   30072   40669   51851
River Rch & RM=NORTH GRAPE CREE,Reach-1         ,68420
   11003   17190   22945   22236   30072   40669   51851
River Rch & RM=NORTH GRAPE CREE,Reach-1         ,63901
   11141   17414   23251   22540   30483   41225   52593
River Rch & RM=NORTH GRAPE CREE,Reach-1         ,60356
   11932   18685   24982   24250   32795   44352   56723
River Rch & RM=NORTH GRAPE CREE,Reach-1         ,56881
   12404   19445   26017   25272   34178   46222   59194
River Rch & RM=NORTH GRAPE CREE,Reach-1         ,52740
   12770   20022   26795   26031   35203   47609   60982
River Rch & RM=NORTH GRAPE CREE,Reach-1         ,47807
   12923   20255   27100   26320   35595   48137   61625
River Rch & RM=NORTH GRAPE CREE,Reach-1         ,39599
   13272   20814   27859   27067   36604   49503   63416
River Rch & RM=NORTH GRAPE CREE,Reach-1         ,35251
   13325   20888   27950   27147   36713   49650   63565
River Rch & RM=NORTH GRAPE CREE,Reach-1         ,30688
   14136   22177   29692   28853   39021   52771   67622
River Rch & RM=NORTH GRAPE CREE,Reach-1         ,29725
   14136   22177   29692   28853   39021   52771   67622
River Rch & RM=NORTH GRAPE CREE,Reach-1         ,23748
   14037   21989   29411   28551   38611   52217   66772
River Rch & RM=NORTH GRAPE CREE,Reach-1         ,14917
   14503   22716   30381   29488   39880   53933   68942
River Rch & RM=NORTH GRAPE CREE,Reach-1         ,10569
   14982   23455   31359   30424   41145   55644   71067
Boundary for River Rch & Prof#=NORTH GRAPE CREE,Reach-1         , 1
Up Type= 0
Dn Type= 3
Dn Slope=0.0016
Boundary for River Rch & Prof#=NORTH GRAPE CREE,Reach-1         , 2
Up Type= 0
Dn Type= 3
Dn Slope=0.0016
Boundary for River Rch & Prof#=NORTH GRAPE CREE,Reach-1         , 3
Up Type= 0
Dn Type= 3
Dn Slope=0.0016
Boundary for River Rch & Prof#=NORTH GRAPE CREE,Reach-1         , 4
Up Type= 0
Dn Type= 3
Dn Slope=0.0016
Boundary for River Rch & Prof#=NORTH GRAPE CREE,Reach-1         , 5
Up Type= 0
Dn Type= 3
Dn Slope=0.0016
Boundary for River Rch & Prof#=NORTH GRAPE CREE,Reach-1         , 6
Up Type= 0
Dn Type= 3
Dn Slope=0.0016
Boundary for River Rch & Prof#=NORTH GRAPE CREE,Reach-1         , 7
Up Type= 0
Dn Type= 3
Dn Slope=0.0016
DSS Import GetInterval= 0
DSS Import GetPeak= 0
DSS Import FillOption= 0

--- NORTH GRAPE CREEK.g01 (geometry) ---

Geom Title=Existing Conditions
Program Version=4.10

River Reach=NORTH GRAPE CREE,Reach-1
Reach XY= 30
      2795448.47     10093183.73      2798785.11     10094525.49
      2805025.54     10086696.42      2807065.45     10089779.25
      2812157.11     10090357.03       2813378.4     10092757.81
      2815644.67     10091373.54      2816224.29     10093021.76
      2825664.12     10093319.16      2826026.29     10096170.39
      2827925.83     10096805.12      2827359.33     10099070.42
      2829535.12     10099531.58      2830063.09     10098665.37
      2833779.05     10100632.48      2842527.07     10098772.82
      2847379.51     10092314.82      2849744.79     10091047.29
      2858098.42     10093458.77      2857683.93     10096198.11
      2858709.96     10097590.13      2868168.47     10098543.73
      2869387.18     10097511.58      2868058.98      10093616.7
      2873853.22     10095073.13      2874158.76     10093187.57
      2876226.04      10092999.2      2879541.41     10090375.72
      2875652.83     10087802.56      2877644.86     10085120.76

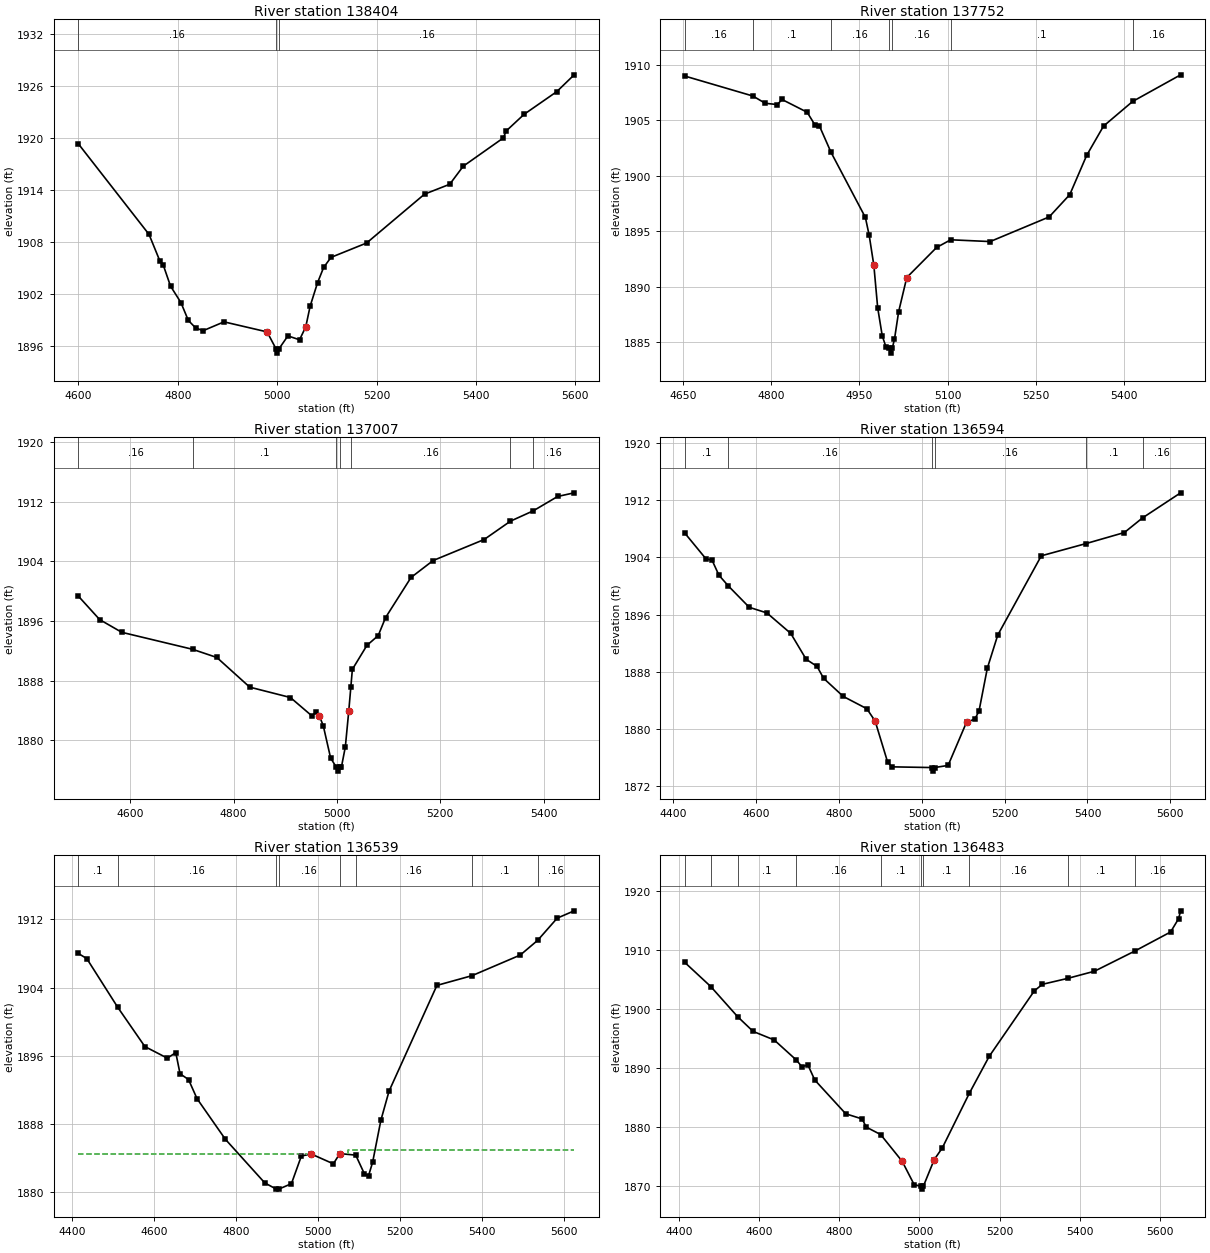
Type RM Length L Ch R = 1 ,138404  ,652,652,652
BEGIN DESCRIPTION:
NORTH GRAPE CREEK 188.0
END DESCRIPTION:
XS GIS Cut Line= 2
      2795301.05     10093703.96      2796124.62     10093140.47
#Sta/Elev= 30
  4599.8 1919.35  4742.1 1908.89  4764.3 1905.77  4770.4 1905.41  4785.3 1902.93
  4806.3 1901.02  4821.2 1898.96  4836.1 1898.09    4851 1897.78    4893  1898.8
  4979.7 1897.64  4997.6 1895.69  5000.4 1895.19  5003.6 1895.69  5021.6 1897.18
    5045 1896.73  5057.5 1898.22  5066.3  1900.6  5081.2 1903.31  5093.5 1905.08
  5108.3 1906.24    5180  1907.9  5296.6 1913.54  5347.3 1914.68  5374.4 1916.76
    5455 1920.02  5461.1 1920.84  5496.9 1922.75  5562.7 1925.37  5597.7 1927.31
#Mann= 3 ,-1 , 0
  4599.8     .16       0  4997.6     .07       0  5003.6     .16       0
Bank Sta=4979.7,5057.5
XS Rating Curve= 0 ,0
Exp/Cntr=0.3,0.1

Type RM Length L Ch R = 1 ,137752  ,745,745,745
BEGIN DESCRIPTION:
NORTH GRAPE CREEK 187.0
END DESCRIPTION:
XS GIS Cut Line= 2
      2795726.46     10094294.18      2796264.02      10093643.9
#Sta/Elev= 30
  4652.8    1909  4768.7  1907.2  4789.5 1906.55  4810.3 1906.43  4818.2 1906.89
    4861 1905.74  4874.1 1904.61    4882 1904.49  4901.7 1902.12  4960.1 1896.26
  4966.6 1894.64  4974.5 1891.94    4981 1888.13  4988.8 1885.59  4995.3 1884.57
  5000.1 1884.54  5002.9 1884.04  5006.1 1884.54  5009.6  1885.3  5016.7 1887.78
  5030.5 1890.85  5081.3 1893.56  5105.3 1894.25  5172.4 1894.09  5272.8 1896.31
  5307.9 1898.32  5336.6 1901.85  5365.3 1904.49  5414.8 1906.71  5496.5 1909.11
#Mann= 7 ,-1 , 0
  4652.8     .16       0  4768.7      .1       0  4901.7     .16       0
  5000.1     .07       0  5006.1     .16       0  5105.3      .1       0
  5414.8     .16       0
Bank Sta=4974.5,5030.5
XS Rating Curve= 0 ,0
Exp/Cntr=0.3,0.1

Type RM Length L Ch R = 1 ,137007  ,413,413,413
BEGIN DESCRIPTION:
NORTH GRAPE CREEK 186.0
END DESCRIPTION:
XS GIS Cut Line= 2
      2796308.06     10094571.96      2796941.73     10093851.48
#Sta/Elev= 30
  4499.6 1899.33    4541 1896.17  4583.7 1894.47  4720.7 1892.19  4767.7 1891.09
  4831.3 1887.11    4910 1885.72  4951.8 1883.24  4959.4 1883.79    4966 1883.25
  4973.6 1881.93  4987.8  1877.6  4999.1 1876.34  5001.8 1875.84  5005.1 1876.34
  5008.7 1876.38  5016.3  1879.1  5022.9 1883.88  5026.9 1887.09  5029.9  1889.5
  5058.1 1892.72  5079.9 1894.03  5094.1 1896.44  5143.4 1901.83  5186.1  1904.1
  5284.8 1906.92  5335.9 1909.39  5380.1 1910.78  5427.1  1912.7  5459.1 1913.19
#Mann= 7 ,-1 , 0
  4499.6     .16       0  4720.7      .1       0  4999.1     .07       0
  5005.1      .1       0  5026.9     .16       0  5335.9      .1       0
  5380.1     .16       0
Bank Sta=4966,5022.9
XS Rating Curve= 0 ,0
Exp/Cntr=0.3,0.1

Type RM Length L Ch R = 1 ,136594  ,55,55,55
BEGIN DESCRIPTION:
Mapping XS e78118ba
END DESCRIPTION:
XS GIS Cut Line= 3
        2796773.     10095042.03      2796905.38     10094642.72
      2796970.45     10093868.33
#Sta/Elev= 30
  4427.3  1907.4  4478.2 1903.81  4493.2  1903.6  4509.8  1901.5  4532.5    1900
    4583 1897.01  4625.7 1896.22  4683.3 1893.35  4720.5 1889.73  4746.7 1888.74
  4762.6 1887.07  4810.1 1884.53    4867 1882.81  4887.1 1881.08  4917.2 1875.35
  4927.3 1874.67  5024.6 1874.57  5027.4 1874.07  5030.6 1874.57  5063.4 1874.87
  5107.9 1880.92    5128 1881.36    5138 1882.47  5158.1 1888.47  5183.3 1893.12
  5288.5 1904.22  5395.7 1905.92  5489.2 1907.48  5533.1 1909.53  5625.1 1913.04
#Mann= 6 ,-1 , 0
  4427.3      .1       0  4532.5     .16       0  5024.6     .07       0
  5030.6     .16       0  5395.7      .1       0  5533.1     .16       0
Bank Sta=4887.1,5107.9
XS Rating Curve= 0 ,0
Exp/Cntr=0.3,0.1

Type RM Length L Ch R = 1 ,136539  ,56,56,56
BEGIN DESCRIPTION:
Mapping XS 251939a3
END DESCRIPTION:
XS GIS Cut Line= 3
      2796831.58     10095063.76      2796970.48     10094536.38
      2796996.52     10093872.36
#Sta/Elev= 30
  4415.1    1908  4435.8 1907.39  4510.8 1901.71  4577.5 1897.07  4632.3 1895.71
  4652.9 1896.36  4663.3 1893.88    4684  1893.2  4704.7 1890.96  4773.9 1886.19
  4870.1 1881.07  4898.2 1880.34  4904.2 1880.34  4935.1 1880.98  4959.3 1884.22
  4983.1 1884.47  5037.4 1883.31  5053.2 1884.51    5092 1884.33  5113.2 1882.13
  5123.2  1881.9  5133.2 1883.49  5153.3 1888.41  5173.3 1891.84  5290.1 1904.25
  5375.7 1905.39  5493.5 1907.81    5536 1909.54  5583.6 1912.14    5625    1913
#Mann= 8 ,-1 , 0
  4415.1      .1       0  4510.8     .16       0  4898.2     .07       0
  4904.2     .16       0  5053.2      .1       0    5092     .16       0
  5375.7      .1       0    5536     .16       0
#XS Ineff= 2 , 0
       0  4973.1  1884.5  5073.2       0 1884.88
Permanent Ineff=
       T       T
Bank Sta=4983.1,5053.2
XS Rating Curve= 0 ,0
Exp/Cntr=0.3,0.1

Type RM Length L Ch R = 1 ,136483  ,233,233,233
BEGIN DESCRIPTION:
Mapping XS c9c471df
END DESCRIPTION:
XS GIS Cut Line= 3
      2796892.35      10095065.9      2797022.56     10094666.59
       2797048.6     10093848.61
#Sta/Elev= 30
  4413.9 1907.95  4478.8 1903.86  4545.9 1898.75  4584.5 1896.26  4637.1 1894.81
  4692.6  1891.4  4706.6 1890.25  4721.2  1890.6  4738.5 1888.02  4815.9 1882.29
  4856.8 1881.42    4867 1880.04  4903.1 1878.77  4956.8 1874.24  4986.8 1870.28
  5003.8 1870.02  5006.6 1869.52  5009.8 1870.02  5036.9 1874.53  5056.9 1876.49
  5124.5 1885.76  5174.3 1892.04    5287 1903.14    5307 1904.24  5370.4 1905.25
  5437.1 1906.46  5537.3 1909.86  5627.2 1913.11  5647.2 1915.36  5652.3  1916.7
#Mann= 10 ,-1 , 0
  4413.9      .1       0  4478.8     .16       0  4545.9      .1       0
  4692.6     .16       0  4903.1      .1       0  5003.8     .07       0
  5009.8      .1       0  5124.5     .16       0  5370.4      .1       0
  5537.3     .16       0
Bank Sta=4956.8,5036.9
XS Rating Curve= 0 ,0
Exp/Cntr=0.3,0.1

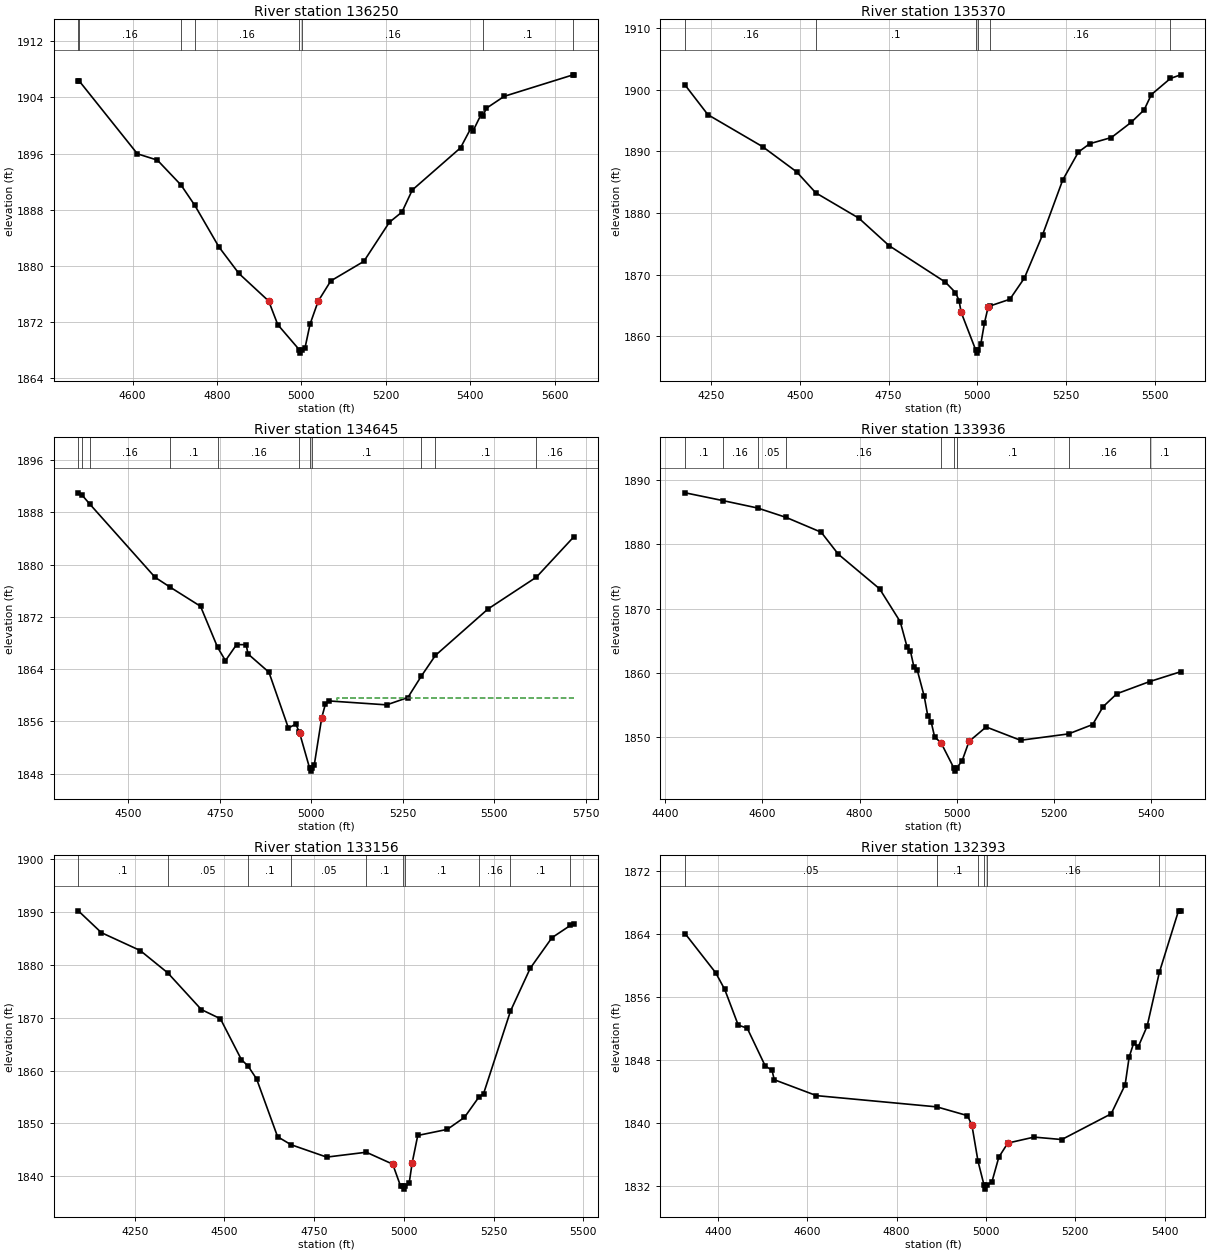
Type RM Length L Ch R = 1 ,136250  ,880,880,880
BEGIN DESCRIPTION:
NORTH GRAPE CREEK 185.0
END DESCRIPTION:
XS GIS Cut Line= 2
      2797045.89     10095084.11      2797471.22      10093990.4
#Sta/Elev= 30
  4471.5 1906.35  4473.3 1906.35  4611.4 1895.96  4658.8 1895.06  4714.9 1891.51
  4747.5 1888.62  4804.5 1882.71  4851.9 1878.93  4922.5    1875    4944 1871.64
  4994.7 1868.09  4997.4 1867.59  5000.7 1868.09  5008.4  1868.3  5020.5 1871.72
  5039.7 1874.98  5069.6 1877.87  5147.9 1880.65  5208.3 1886.21  5238.2 1887.67
  5262.7 1890.81  5376.9 1896.81  5401.4 1899.59  5406.8 1899.24    5426  1901.6
  5430.4 1901.33  5437.6 1902.42  5480.4 1904.14  5643.7  1907.2    5645  1907.2
#Mann= 8 ,-1 , 0
  4471.5      .1       0  4473.3     .16       0  4714.9      .1       0
  4747.5     .16       0  4994.7     .07       0  5000.7     .16       0
  5430.4      .1       0  5643.7     .16       0
Bank Sta=4922.5,5039.7
XS Rating Curve= 0 ,0
Exp/Cntr=0.3,0.1

Type RM Length L Ch R = 1 ,135370  ,725,725,725
BEGIN DESCRIPTION:
NORTH GRAPE CREEK 184.0
END DESCRIPTION:
XS GIS Cut Line= 3
      2797922.61     10095335.88      2798070.18      10094702.2
      2797913.92     10093972.99
#Sta/Elev= 30
  4176.9 1900.71  4240.7 1895.94  4394.7 1890.76  4490.8 1886.67  4544.8 1883.26
  4666.2 1879.15  4751.4 1874.69  4910.1 1868.77  4938.5 1867.08  4948.7 1865.78
  4954.4  1863.9  4995.7 1857.75  4998.5 1857.25  5001.7 1857.75  5010.1 1858.76
  5020.3 1862.15  5030.5 1864.69  5036.9 1864.92  5091.9 1865.99  5132.8 1869.43
  5183.9 1876.42  5240.8 1885.33  5285.1 1889.88  5316.9 1891.23  5378.2 1892.24
  5433.4 1894.68  5470.3 1896.71  5490.7  1899.2  5544.4 1901.82  5573.3 1902.41
#Mann= 6 ,-1 , 0
  4176.9     .16       0  4544.8      .1       0  4995.7     .07       0
  5001.7      .1       0  5036.9     .16       0  5544.4      .1       0
Bank Sta=4954.4,5030.5
XS Rating Curve= 0 ,0
Exp/Cntr=0.3,0.1

Type RM Length L Ch R = 1 ,134645  ,709,709,709
BEGIN DESCRIPTION:
NORTH GRAPE CREEK 183.0
END DESCRIPTION:
XS GIS Cut Line= 3
       2798825.4     10095170.99       2798686.5     10094294.22
      2798356.64     10093964.36
#Sta/Elev= 30
  4363.1    1891  4373.4 1890.65  4394.4 1889.28  4572.9 1878.06  4613.6 1876.57
  4697.2 1873.62  4743.9 1867.33  4765.3 1865.29  4795.7 1867.75  4821.9 1867.74
    4827 1866.32  4884.2 1863.52  4937.4 1854.97  4957.7 1855.58    4967 1854.36
  4967.8 1854.26  4995.2 1848.87  4997.9 1848.37  5001.2 1848.87  5008.3 1849.38
  5028.6 1856.57  5038.7 1858.67  5048.8 1859.12    5206 1858.52  5263.9 1859.64
  5301.2 1862.96  5339.2 1866.09  5483.1 1873.21  5615.5 1878.09  5717.3 1884.24
#Mann= 11 ,-1 , 0
  4363.1     .16       0  4373.4      .1       0  4394.4     .16       0
  4613.6      .1       0  4743.9     .16       0    4967      .1       0
  4995.2     .07       0  5001.2      .1       0  5301.2     .16       0
  5339.2      .1       0  5615.5     .16       0
#XS Ineff= 2 , 0
                          5070.7         1859.51
Permanent Ineff=
       F       F
Bank Sta=4967.8,5028.6
XS Rating Curve= 0 ,0
Exp/Cntr=0.3,0.1

Type RM Length L Ch R = 1 ,133936  ,780,780,780
BEGIN DESCRIPTION:
NORTH GRAPE CREEK 182.0
END DESCRIPTION:
XS GIS Cut Line= 2
       2799493.8     10094363.67      2798755.97     10093660.56
#Sta/Elev= 30
  4441.5 1888.02  4518.4 1886.82  4590.2 1885.66  4649.3 1884.19  4721.2 1881.89
  4756.4 1878.47  4841.3 1873.09  4883.8 1867.97  4897.9 1864.03  4904.8 1863.39
  4912.1 1860.88    4919 1860.39  4933.1 1856.38  4940.4 1853.35  4947.3 1852.43
  4954.5 1850.06  4967.9 1849.11    4994 1845.23  4996.7 1844.73    5000 1845.23
  5011.1 1846.33  5025.3 1849.35  5060.5  1851.6  5131.3 1849.53    5230 1850.52
  5279.7 1851.98  5301.1 1854.75  5329.5 1856.77  5396.9 1858.66  5460.7 1860.19
#Mann= 9 ,-1 , 0
  4441.5      .1       0  4518.4     .16       0  4590.2     .05       0
  4649.3     .16       0  4967.9      .1       0    4994     .07       0
    5000      .1       0    5230     .16       0  5396.9      .1       0
#XS Ineff= 2 , 0
                         5058.22          1851.1
Permanent Ineff=
       F       F
Bank Sta=4967.9,5025.3
XS Rating Curve= 0 ,0
Exp/Cntr=0.3,0.1

Type RM Length L Ch R = 1 ,133156  ,763,763,763
BEGIN DESCRIPTION:
NORTH GRAPE CREEK 181.0
END DESCRIPTION:
XS GIS Cut Line= 2
      2799927.78     10093591.07      2798652.61     10093061.92
#Sta/Elev= 30
  4092.6 1890.18  4156.8 1886.06  4265.1 1882.68    4342 1878.45  4435.4 1871.53
  4488.6 1869.79  4547.1 1862.07  4565.6 1860.86  4589.5 1858.42    4648  1847.5
  4685.2    1846  4784.8 1843.65  4895.2 1844.57  4968.8 1842.32  4990.8 1838.16
  4998.3  1838.1  5001.1  1837.6  5004.3  1838.1  5014.7 1838.73    5023 1842.55
  5038.6 1847.74    5121 1848.89  5168.8 1851.16  5209.4 1855.03  5221.9 1855.61
    5297 1871.23  5352.1 1879.33  5412.7 1885.11  5463.9 1887.42  5473.2 1887.78
#Mann= 10 ,-1 , 0
  4092.6      .1       0    4342     .05       0  4565.6      .1       0
  4685.2     .05       0  4895.2      .1       0  4998.3     .07       0
  5004.3      .1       0  5209.4     .16       0    5297      .1       0
  5463.9     .16       0
Bank Sta=4968.8,5023
XS Rating Curve= 0 ,0
Exp/Cntr=0.3,0.1

Type RM Length L Ch R = 1 ,132393  ,1002,1002,1002
BEGIN DESCRIPTION:
NORTH GRAPE CREEK 180.0
END DESCRIPTION:
XS GIS Cut Line= 2
      2800266.35     10092818.52      2799163.91     10092705.67
#Sta/Elev= 30
  4327.4 1864.03  4395.6 1859.07  4415.7 1856.96  4445.9 1852.43    4466 1852.04
  4506.2 1847.25  4521.5 1846.68  4526.5 1845.49  4620.9 1843.47  4890.3 1842.04
  4958.6 1840.93  4968.6 1839.73  4982.3 1835.13  4995.8 1832.09  4998.5 1831.59
  5001.8 1832.09  5013.3 1832.49  5028.9 1835.66    5049 1837.44  5107.6  1838.2
  5169.7 1837.89  5280.2 1841.16  5311.4 1844.85  5320.4 1848.36  5330.5 1850.15
  5340.5 1849.64  5360.7 1852.31    5388 1859.14  5430.8 1866.95  5435.6 1866.95
#Mann= 6 ,-1 , 0
  4327.4     .05       0  4890.3      .1       0  4982.3     .16       0
  4995.8     .07       0  5001.8     .16       0    5388      .1       0
Bank Sta=4968.6,5049
XS Rating Curve= 0 ,0
Exp/Cntr=0.3,0.1

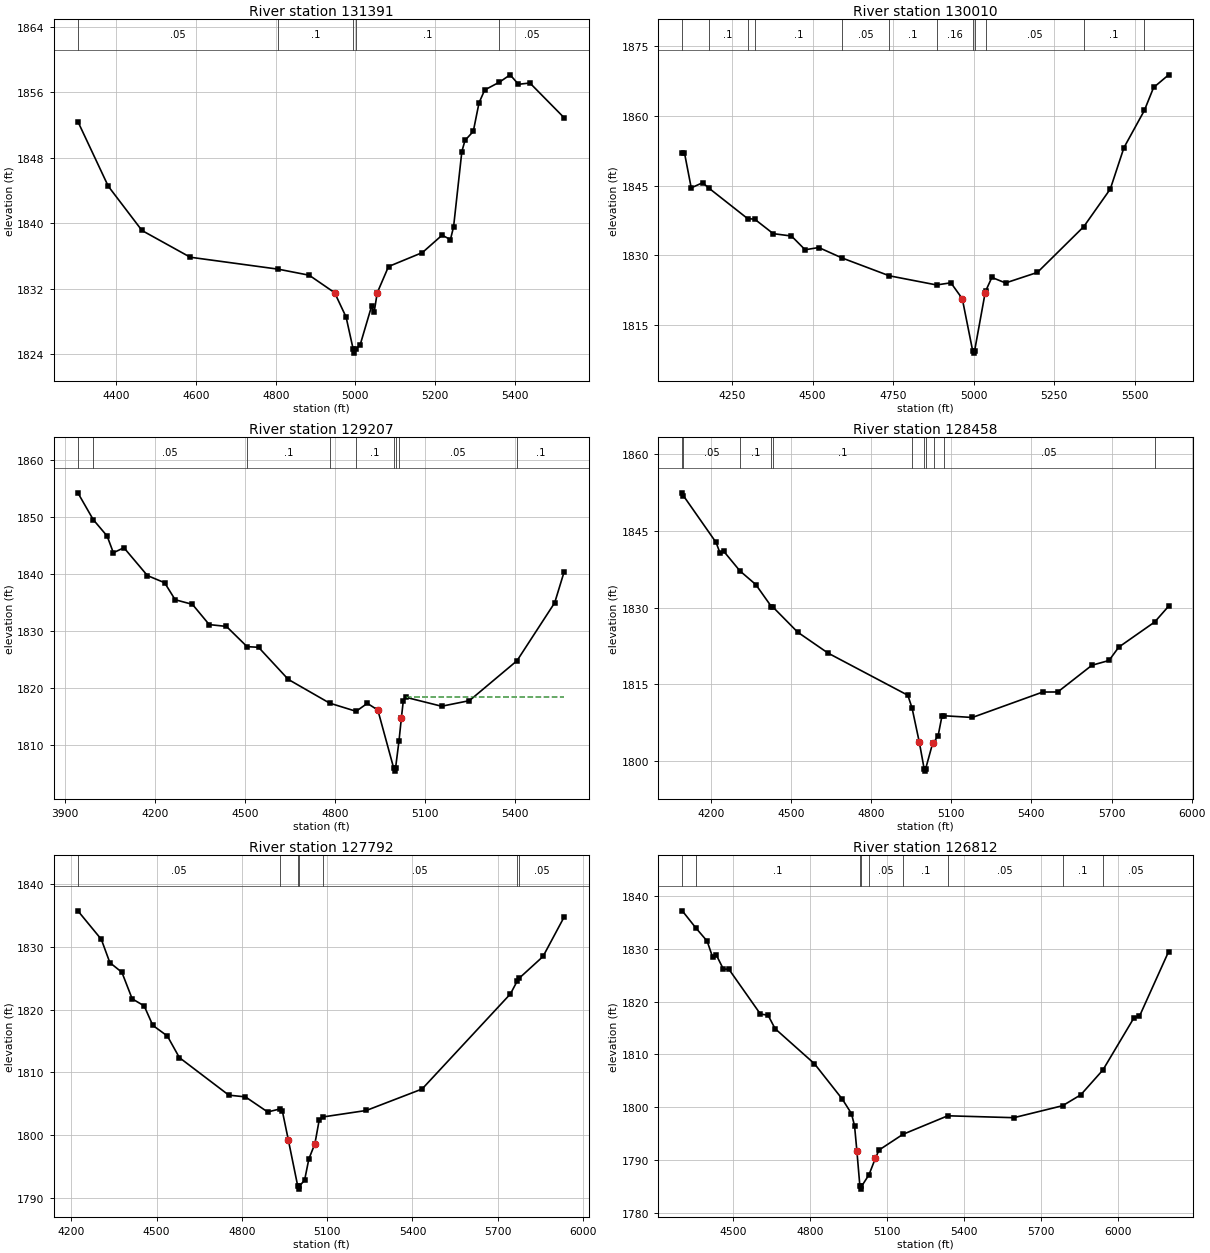
Type RM Length L Ch R = 1 ,131391  ,1381,1381,1381
BEGIN DESCRIPTION:
NORTH GRAPE CREEK 179.0
END DESCRIPTION:
XS GIS Cut Line= 2
       2800552.8     10092566.77      2799606.64     10091794.21
#Sta/Elev= 30
  4303.1 1852.45  4379.4 1844.54  4464.1 1839.12  4585.4 1835.85  4806.1 1834.39
  4884.1 1833.65    4948 1831.51  4976.7 1828.54  4994.5 1824.62  4997.3 1824.12
  5000.5 1824.62  5011.9  1825.1  5040.6 1829.83  5047.1 1829.09    5055  1831.5
  5083.3 1834.71  5168.4 1836.42  5217.9 1838.55  5238.8 1838.01  5246.7 1839.56
  5267.5 1848.78  5275.4 1850.14  5296.2 1851.24  5310.6 1854.73  5324.9 1856.31
  5361.7 1857.26  5388.8 1858.16  5409.6    1857  5438.4 1857.16  5524.6  1852.9
#Mann= 5 ,-1 , 0
  4303.1     .05       0  4806.1      .1       0  4994.5     .07       0
  5000.5      .1       0  5361.7     .05       0
Bank Sta=4948,5055
XS Rating Curve= 0 ,0
Exp/Cntr=0.3,0.1

Type RM Length L Ch R = 1 ,130010  ,803,803,803
BEGIN DESCRIPTION:
NORTH GRAPE CREEK 178.0
END DESCRIPTION:
XS GIS Cut Line= 2
      2801472.96     10092028.59      2800396.58     10090969.57
#Sta/Elev= 30
  4095.4 1852.08  4102.1 1852.08  4123.2  1844.5  4158.5  1845.6  4177.5 1844.47
  4298.3 1837.87  4320.2 1837.75  4377.8 1834.63  4434.4 1834.12  4476.8 1831.16
  4519.2 1831.64  4591.5 1829.39  4738.2 1825.55  4884.8 1823.58  4929.4 1824.04
  4964.7 1820.62    4997 1809.39  4999.8 1808.89    5003 1809.39  5035.4 1821.76
  5037.2 1822.25  5056.6  1825.2    5099 1824.01    5198 1826.28    5342 1836.15
  5424.3 1844.25  5466.7 1853.17    5530 1861.17  5558.7 1866.12  5605.4 1868.85
#Mann= 12 ,-1 , 0
  4095.4     .05       0  4177.5      .1       0  4298.3     .05       0
  4320.2      .1       0  4591.5     .05       0  4738.2      .1       0
  4884.8     .16       0    4997     .07       0    5003     .16       0
  5037.2     .05       0    5342      .1       0    5530     .05       0
Bank Sta=4964.7,5035.4
XS Rating Curve= 0 ,0
Exp/Cntr=0.3,0.1

Type RM Length L Ch R = 1 ,129207  ,749,749,749
BEGIN DESCRIPTION:
NORTH GRAPE CREEK 177.0
END DESCRIPTION:
XS GIS Cut Line= 2
      2802167.41     10091481.72      2800909.51     10090458.05
#Sta/Elev= 30
    3942 1854.29  3993.1  1849.6  4039.6 1846.71  4060.4 1843.78  4095.6 1844.66
  4173.9 1839.78  4231.3 1838.52  4266.5 1835.54    4324 1834.73    4380 1831.18
  4437.4 1830.86  4506.2 1827.31  4544.5  1827.2  4643.6 1821.57  4781.4 1817.41
  4869.9 1815.97  4907.2 1817.37  4942.3 1816.19  4995.3 1805.98  4998.1 1805.48
  5001.3 1805.98    5013 1810.85  5020.6 1814.74  5027.1 1817.75    5035 1818.44
  5154.9 1816.86  5247.6 1817.84  5406.3 1824.84    5532 1835.01  5563.8 1840.49
#Mann= 9 ,-1 , 0
    3942      .1       0  3993.1     .05       0  4506.2      .1       0
  4781.4     .05       0  4869.9      .1       0  4995.3     .07       0
  5001.3      .1       0    5013     .05       0  5406.3      .1       0
#XS Ineff= 2 , 0
                         5039.64          1818.4
Permanent Ineff=
       F       F
Bank Sta=4942.3,5020.6
XS Rating Curve= 0 ,0
Exp/Cntr=0.3,0.1

Type RM Length L Ch R = 1 ,128458  ,666,666,666
BEGIN DESCRIPTION:
NORTH GRAPE CREEK 176.0
END DESCRIPTION:
XS GIS Cut Line= 2
      2802618.78     10090960.87      2801203.85     10089815.04
#Sta/Elev= 30
  4093.1  1852.4    4097 1851.86  4219.7  1842.7  4234.1 1840.68  4247.9 1841.01
  4309.1 1837.14  4368.4 1834.48  4427.1 1830.15  4432.4 1830.09    4525 1825.19
  4638.6  1821.1  4937.5 1812.86  4953.3 1810.37  4980.6 1803.65  4998.4 1798.54
  5001.2 1798.04  5004.4 1798.54  5030.2 1803.45  5034.2 1803.62    5051 1804.98
  5065.4 1808.83  5072.2 1808.86  5178.9 1808.52  5442.7 1813.49  5498.7  1813.5
  5626.6 1818.72  5690.5 1819.65  5727.2 1822.26  5861.6 1827.17  5913.8 1830.26
#Mann= 11 ,-1 , 0
  4093.1     .16       0    4097     .05       0  4309.1      .1       0
  4427.1     .05       0  4432.4      .1       0  4953.3     .05       0
  4998.4    .035       0  5004.4     .05       0  5034.2      .1       0
  5072.2     .05       0  5861.6      .1       0
Bank Sta=4980.6,5030.2
XS Rating Curve= 0 ,0
Exp/Cntr=0.3,0.1

Type RM Length L Ch R = 1 ,127792  ,980,980,980
BEGIN DESCRIPTION:
Mapping XS e4e6dbec
END DESCRIPTION:
XS GIS Cut Line= 2
      2802922.62      10090283.8      2801491.86     10089347.31
#Sta/Elev= 30
  4223.5 1835.77    4306 1831.22    4336 1827.51  4378.3 1825.97  4414.5 1821.74
  4456.7 1820.61  4486.9 1817.51  4538.2 1815.81  4580.4 1812.37  4754.3 1806.38
  4812.6 1806.11  4890.9  1803.7  4934.4 1804.19  4942.2 1803.91  4963.3 1799.28
  4996.5  1791.9  4999.3  1791.4  5002.5  1791.9  5020.6 1792.81  5035.7 1796.22
  5056.8 1798.62  5071.9 1802.38  5085.4 1802.91  5237.7 1803.94  5433.7 1807.36
  5744.3 1822.52  5768.9 1824.63  5775.2 1825.03  5858.9 1828.49  5933.5 1834.81
#Mann= 7 ,-1 , 0
  4223.5     .05       0  4934.4      .1       0  4996.5     .07       0
  5002.5      .1       0  5085.4     .05       0  5768.9      .1       0
  5775.2     .05       0
Bank Sta=4963.3,5056.8
XS Rating Curve= 0 ,0
Exp/Cntr=0.3,0.1

Type RM Length L Ch R = 1 ,126812  ,913,913,913
BEGIN DESCRIPTION:
Mapping XS d574cd0b
END DESCRIPTION:
XS GIS Cut Line= 2
      2803591.01     10089754.28      2802002.98     10088712.95
#Sta/Elev= 30
  4300.3 1837.19  4352.8 1833.98  4397.3 1831.46  4418.4 1828.47  4433.5 1828.79
  4460.5 1826.18  4482.7  1826.1  4605.2 1817.65  4635.4 1817.41  4662.5 1814.88
  4816.3 1808.23  4924.8 1801.55    4961 1798.78    4973 1796.45  4982.1 1791.69
  4993.9 1784.98  4996.7 1784.48  4999.9 1784.98  5029.2 1787.19  5054.4 1790.34
  5068.7 1791.89  5161.9 1794.86  5336.9 1798.37  5594.8 1798.01  5785.3 1800.28
  5856.2 1802.34  5942.7 1807.05  6064.1 1816.94  6085.2  1817.2  6199.3 1829.48
#Mann= 9 ,-1 , 0
  4300.3     .05       0  4352.8      .1       0  4993.9     .07       0
  4999.9      .1       0  5029.2     .05       0  5161.9      .1       0
  5336.9     .05       0  5785.3      .1       0  5942.7     .05       0
Bank Sta=4982.1,5054.4
XS Rating Curve= 0 ,0
Exp/Cntr=0.3,0.1

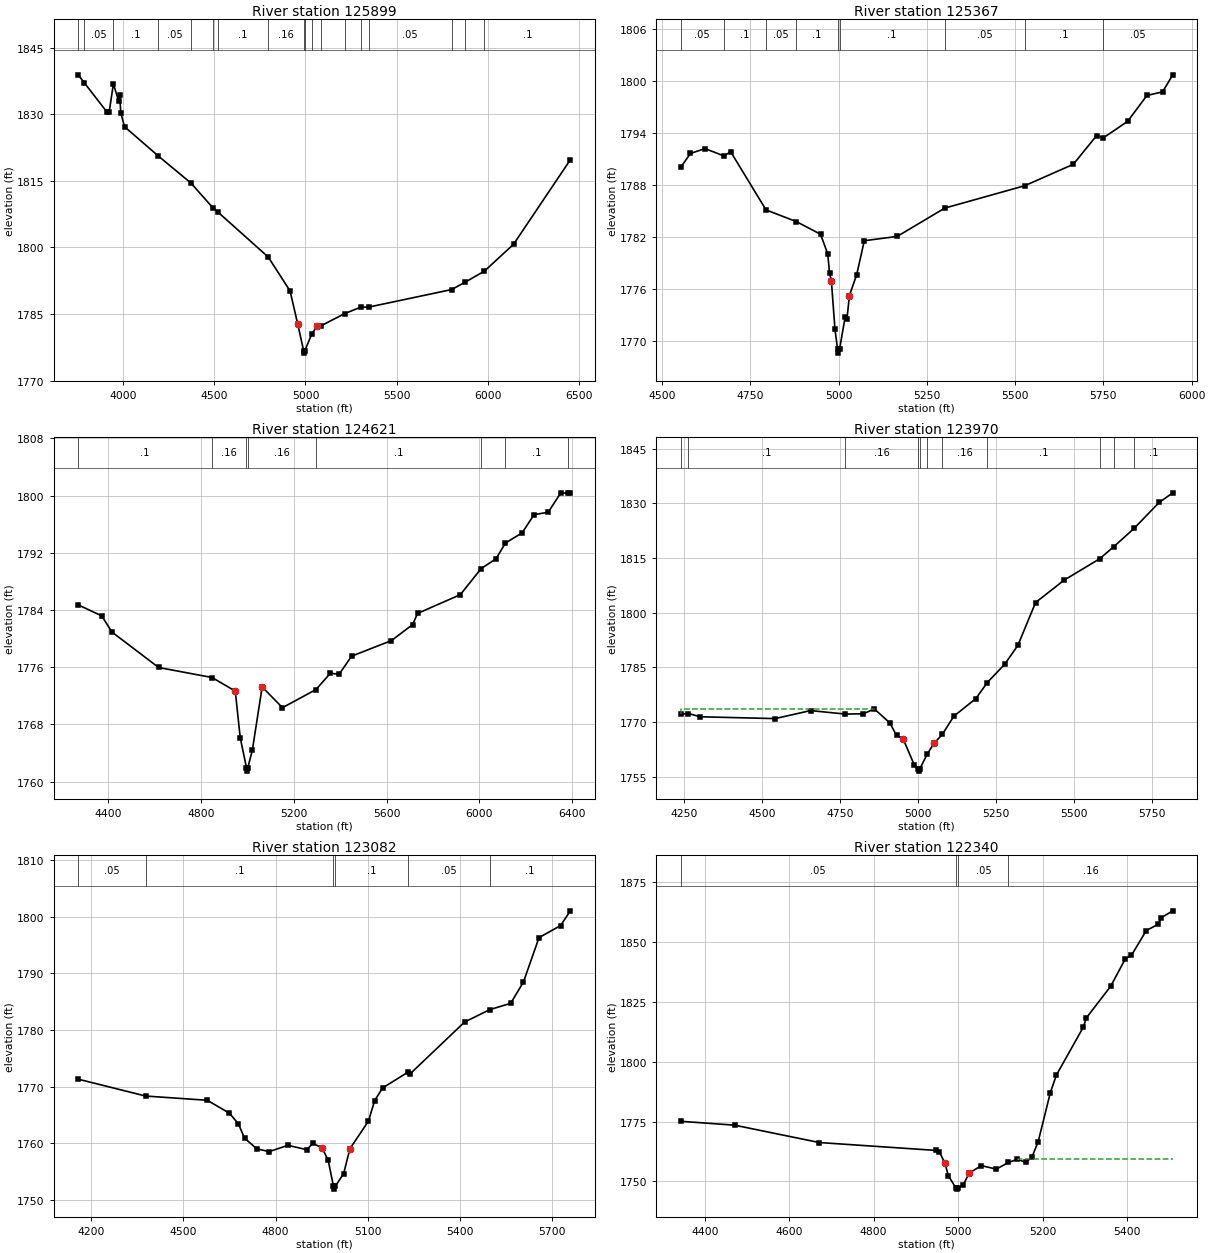
Type RM Length L Ch R = 1 ,125899  ,532,532,532
BEGIN DESCRIPTION:
Mapping XS 9865f2cb
END DESCRIPTION:
XS GIS Cut Line= 4
      2804155.26     10089815.08      2803894.83      10089033.8
      2803252.47     10088417.48       2802280.3      10088278.6
#Sta/Elev= 30
    3755 1838.89  3788.9 1837.09    3914 1830.44  3925.1 1830.54    3948 1836.86
  3977.3 1832.89  3982.5 1834.29  3988.3  1830.4  4008.9  1827.2  4193.5 1820.62
  4372.9  1814.5  4493.8 1808.89  4519.9 1807.99  4796.3 1797.82  4915.6  1790.2
    4958 1782.67  4990.2 1776.68    4993 1776.18  4996.2 1776.68  5033.7 1780.39
    5064 1782.31  5083.6 1782.31    5215 1785.09  5302.6 1786.53  5346.3 1786.55
  5800.2  1790.5  5876.5 1792.21  5980.2 1794.66  6139.5 1800.69  6450.8 1819.75
#Mann= 18 ,-1 , 0
    3755      .1       0  3788.9     .05       0    3948      .1       0
  4193.5     .05       0  4372.9      .1       0  4493.8     .05       0
  4519.9      .1       0  4796.3     .16       0  4990.2     .07       0
  4996.2     .16       0  5033.7     .05       0  5083.6      .1       0
    5215     .05       0  5302.6      .1       0  5346.3     .05       0
  5800.2      .1       0  5876.5     .05       0  5980.2      .1       0
Bank Sta=4958,5064
XS Rating Curve= 0 ,0
Exp/Cntr=0.3,0.1

Type RM Length L Ch R = 1 ,125367  ,746,746,746
BEGIN DESCRIPTION:
NORTH GRAPE CREEK 175.0
END DESCRIPTION:
XS GIS Cut Line= 2
      2804085.76     10088348.03      2802723.25     10088052.96
#Sta/Elev= 30
  4552.5 1789.99  4580.4 1791.61  4621.4 1792.17  4674.9 1791.33  4694.5 1791.79
  4794.5 1785.09  4880.4 1783.74  4948.8 1782.28  4969.2 1780.01  4974.4 1777.77
  4979.5 1776.91  4989.7 1771.31  4996.9 1769.05  4999.7 1768.55  5002.9 1769.05
  5018.5 1772.71  5023.6 1772.44  5030.6  1775.2  5051.1 1777.59  5072.8 1781.53
  5166.1 1782.03  5300.8  1785.3  5526.9 1787.88    5665 1790.36  5730.9 1793.68
  5749.8 1793.41  5818.5 1795.31  5873.4 1798.31  5917.5 1798.72  5946.6 1800.69
#Mann= 9 ,-1 , 0
  4552.5     .05       0  4674.9      .1       0  4794.5     .05       0
  4880.4      .1       0  4996.9     .07       0  5002.9      .1       0
  5300.8     .05       0  5526.9      .1       0  5749.8     .05       0
Bank Sta=4979.5,5030.6
XS Rating Curve= 0 ,0
Exp/Cntr=0.3,0.1

Type RM Length L Ch R = 1 ,124621  ,651,651,651
BEGIN DESCRIPTION:
NORTH GRAPE CREEK 174.0
END DESCRIPTION:
XS GIS Cut Line= 4
      2804389.64     10088295.98      2804120.53     10087723.04
      2803851.43      10087558.1      2802705.57     10087818.53
#Sta/Elev= 30
  4269.4 1784.73  4371.3 1783.18  4415.5 1780.92  4616.6 1775.97    4847 1774.57
  4947.4 1772.67  4968.7 1766.16  4995.6 1761.98  4998.4 1761.48  5001.6 1761.98
  5020.8 1764.37  5063.4 1773.25  5151.1 1770.35  5295.7 1772.89  5357.9 1775.17
  5395.4 1775.02  5449.1 1777.55    5621 1779.73  5712.7 1781.97  5733.8 1783.53
  5918.4 1786.15  6008.3  1789.8  6072.2 1791.16  6113.3 1793.38    6185 1794.79
  6236.3 1797.33  6297.8 1797.68  6351.6 1800.38  6381.4 1800.34  6393.1 1800.39
#Mann= 8 ,-1 , 0
  4269.4      .1       0    4847     .16       0  4995.6     .07       0
  5001.6     .16       0  5295.7      .1       0  6008.3     .05       0
  6113.3      .1       0  6381.4     .05       0
Bank Sta=4947.4,5063.4
XS Rating Curve= 0 ,0
Exp/Cntr=0.3,0.1

Type RM Length L Ch R = 1 ,123970  ,888,888,888
BEGIN DESCRIPTION:
NORTH GRAPE CREEK 172.0
END DESCRIPTION:
XS GIS Cut Line= 2
      2804910.44     10087610.17      2803729.94     10086559.87
#Sta/Elev= 30
  4237.8  1772.1    4263 1772.34  4300.4 1771.44  4541.2 1770.94  4654.9 1773.14
  4767.1 1772.18  4824.7 1772.27  4859.8 1773.59  4909.7 1769.74  4930.9 1766.31
  4951.8 1765.45  4987.7 1758.27    4999 1757.02  5001.7 1756.52    5005 1757.02
  5029.6 1761.21  5051.3 1764.15  5078.1 1766.61  5114.8 1771.59  5185.9 1776.45
  5222.1 1780.83  5277.9 1785.82  5320.5 1791.04  5377.4 1802.81  5469.4 1808.97
  5582.7 1814.79  5628.8 1818.16  5693.9 1823.17  5773.8 1830.27  5817.9 1832.92
#Mann= 11 ,-1 , 0
  4237.8     .05       0    4263      .1       0  4767.1     .16       0
    4999     .07       0    5005     .16       0  5029.6      .1       0
  5078.1     .16       0  5222.1      .1       0  5582.7     .16       0
  5628.8     .05       0  5693.9      .1       0
#XS Ineff= 2 , 0
         4860.87 1773.59
Permanent Ineff=
       F       F
Bank Sta=4951.8,5051.3
XS Rating Curve= 0 ,0
Exp/Cntr=0.3,0.1

Type RM Length L Ch R = 1 ,123082  ,742,742,742
BEGIN DESCRIPTION:
NORTH GRAPE CREEK 170.0
END DESCRIPTION:
XS GIS Cut Line= 2
      2804945.18     10087540.74      2805136.16     10085952.18
#Sta/Elev= 30
  4158.2 1771.33  4377.5 1768.35  4578.2  1767.6  4650.1 1765.31  4678.9 1763.46
  4699.1 1760.91  4739.4 1759.01  4779.6 1758.54  4840.1 1759.65  4901.7 1758.87
  4920.7    1760  4950.9  1759.2    4971 1757.01  4988.2 1752.41  4990.9 1751.91
  4994.2 1752.41  5021.4 1754.67  5041.5 1759.03    5102 1763.93  5122.1 1767.56
  5148.2 1769.79  5231.4  1772.6  5235.5 1772.17  5414.2 1781.41  5496.2 1783.61
  5564.2 1784.72  5605.6 1788.47  5656.4 1796.33  5726.4 1798.45  5758.2 1801.06
#Mann= 6 ,-1 , 0
  4158.2     .05       0  4377.5      .1       0  4988.2     .07       0
  4994.2      .1       0  5231.4     .05       0  5496.2      .1       0
Bank Sta=4950.9,5041.5
XS Rating Curve= 0 ,0
Exp/Cntr=0.3,0.1

Type RM Length L Ch R = 1 ,122340  ,949,949,949
BEGIN DESCRIPTION:
NORTH GRAPE CREEK 167.0
END DESCRIPTION:
XS GIS Cut Line= 2
      2805136.13      10087662.3       2805864.4     10086751.97
#Sta/Elev= 30
  4342.7 1775.09  4470.9 1773.46    4671 1766.21    4948  1762.9  4955.6 1762.33
  4968.8 1757.53  4976.8  1752.4  4994.6 1747.22  4997.3 1746.72  5000.6 1747.22
    5012 1748.42  5026.4 1753.44  5055.2 1756.56  5090.4 1755.08  5119.2 1757.86
    5140 1759.18  5160.9  1757.9  5175.3 1760.29  5189.7 1766.61  5218.5 1787.11
  5232.9 1794.47  5296.9 1814.55  5303.3 1818.22    5361 1831.47  5396.2 1843.03
  5410.6 1844.53  5445.8 1854.86  5474.6 1857.54    5481 1860.23  5508.5  1863.1
#Mann= 4 ,-1 , 0
  4342.7     .05       0  4994.6     .04       0  5000.6     .05       0
  5119.2     .16       0
#XS Ineff= 2 , 0
                         5141.78         1759.13
Permanent Ineff=
       F       F
Bank Sta=4968.8,5026.4
XS Rating Curve= 0 ,0
Exp/Cntr=0.3,0.1