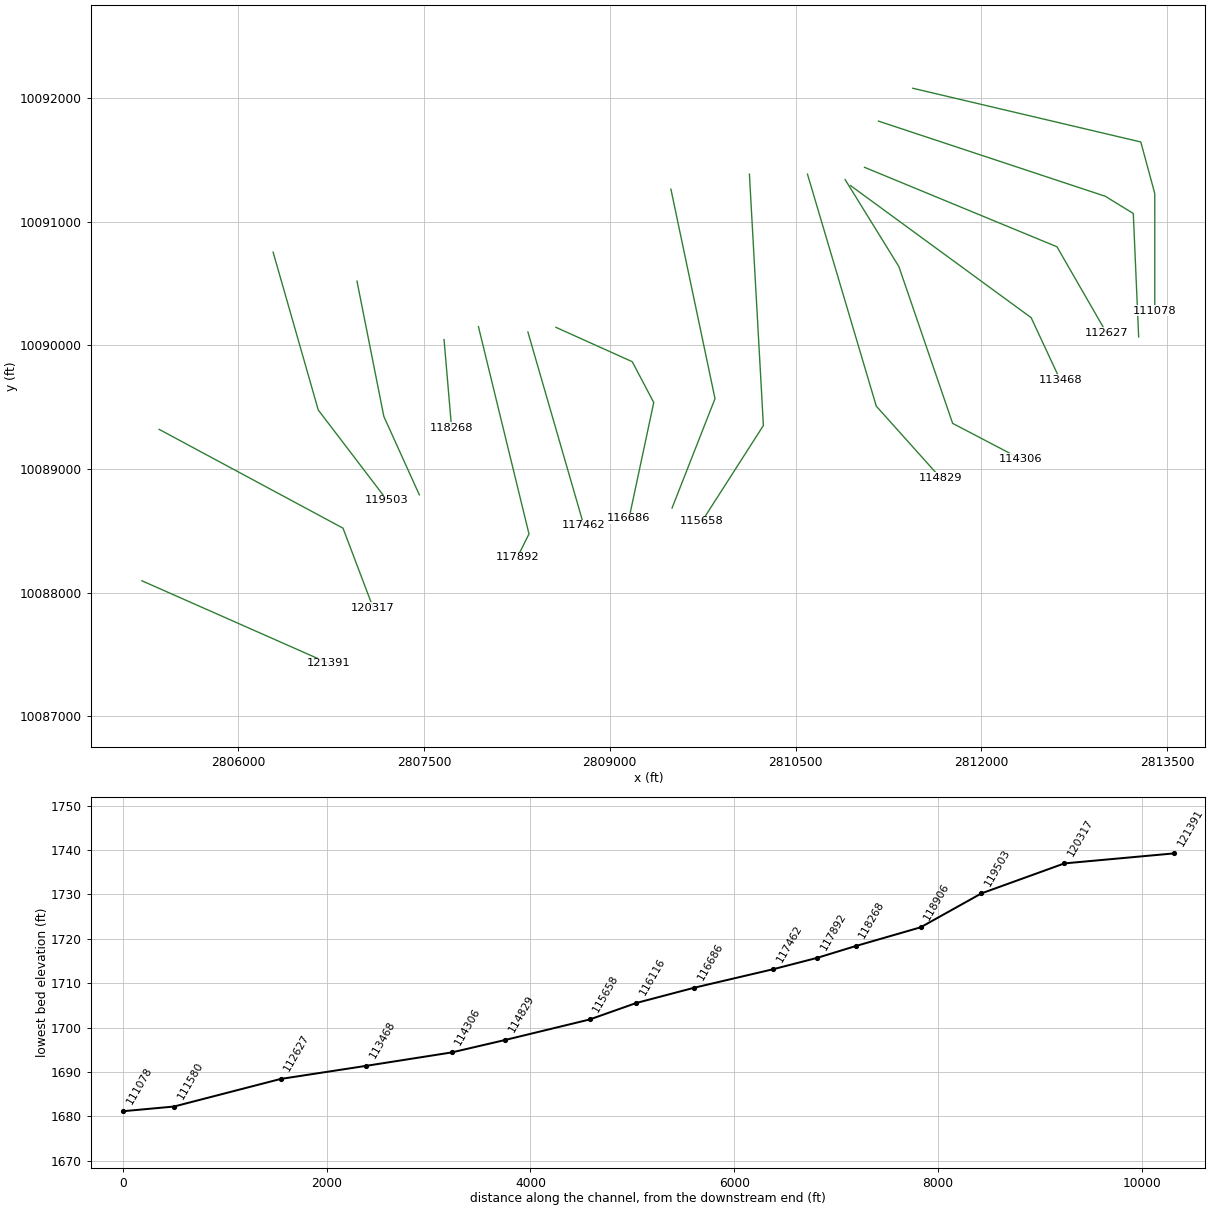
HEC-RAS study NORTH GRAPE CREEK.prj: NORTH GRAPE CREEK Base Level Engineering

--- NORTH GRAPE CREEK.g01 (geometry) --- (continued)

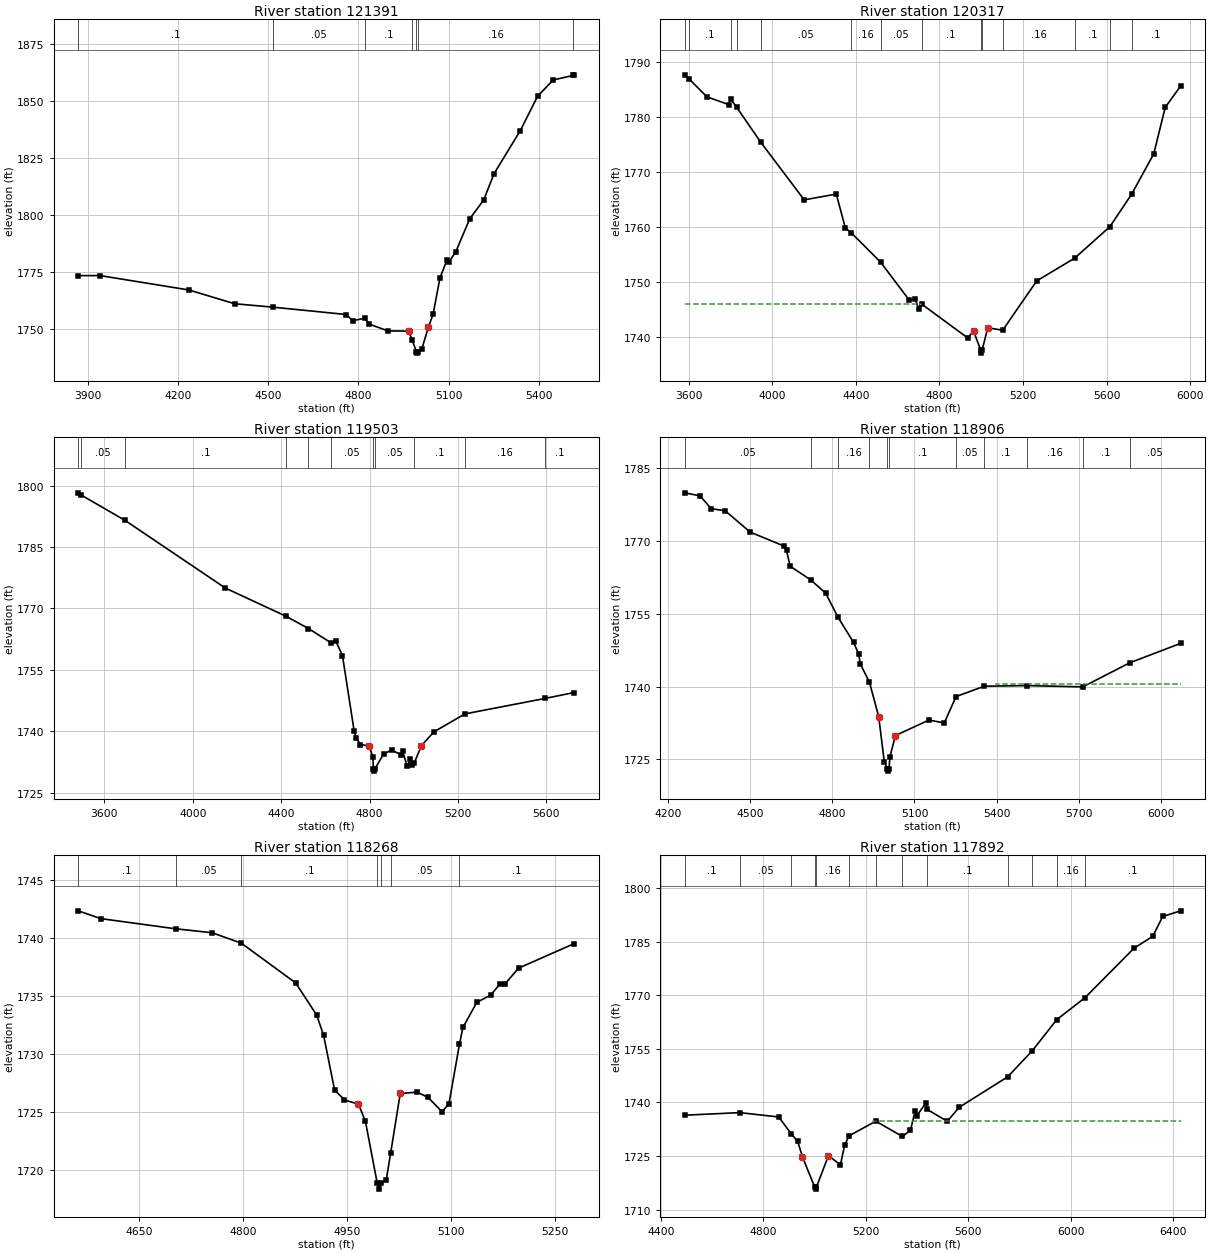
Type RM Length L Ch R = 1 ,121391  ,1074,1074,1074
BEGIN DESCRIPTION:
NORTH GRAPE CREEK 166.0
END DESCRIPTION:
XS GIS Cut Line= 2
      2805222.96      10088096.3      2806732.46      10087428.3
#Sta/Elev= 30
  3867.3 1773.25  3939.9 1773.27  4235.8 1766.95  4387.3 1760.93  4516.9  1759.4
  4759.1  1756.2    4781 1753.46  4820.6 1754.58  4835.6 1752.01  4897.5 1749.03
  4966.9 1748.89  4979.2 1744.84  4993.1 1739.76  4995.9 1739.26  4999.1 1739.76
  5010.6 1740.98  5032.5 1750.58  5048.2 1756.22  5071.4 1772.32  5094.7 1780.17
  5100.2  1779.2  5123.5 1783.57  5170.1 1798.11  5216.7 1806.41  5251.2 1817.95
  5338.6 1836.82  5396.1 1851.89  5448.1 1859.07  5515.5 1861.08    5518 1861.33
#Mann= 7 ,-1 , 0
  3867.3      .1       0  4516.9     .05       0  4820.6      .1       0
  4979.2     .16       0  4993.1     .07       0  4999.1     .16       0
  5515.5      .1       0
Bank Sta=4966.9,5032.5
XS Rating Curve= 0 ,0
Exp/Cntr=0.3,0.1

Type RM Length L Ch R = 1 ,120317  ,814,814,814
BEGIN DESCRIPTION:
NORTH GRAPE CREEK 164.0
END DESCRIPTION:
XS GIS Cut Line= 3
      2805361.89     10089320.23      2806846.22     10088521.65
      2807089.27     10087879.31
#Sta/Elev= 30
  3581.8 1787.71  3600.4 1787.03  3688.1 1783.69    3792 1782.29  3800.7 1783.33
  3829.8 1781.81  3944.6 1775.46  4153.1 1764.93  4306.5 1765.99  4350.3 1759.78
  4377.2 1758.97  4518.2  1753.6  4656.2 1746.64  4683.8 1746.95    4700 1745.14
  4714.9 1745.95  4935.3 1739.78  4963.3 1741.04  4998.1 1737.51  5000.8 1737.01
  5004.1 1737.51  5031.4 1741.63  5102.7 1741.18  5265.8 1750.18  5446.9  1754.3
  5615.8 1760.06  5719.3 1765.94  5825.5 1773.31  5880.5 1781.78  5954.1 1785.67
#Mann= 14 ,-1 , 0
  3581.8     .05       0  3600.4      .1       0  3800.7     .05       0
  3829.8      .1       0  3944.6     .05       0  4377.2     .16       0
  4518.2     .05       0  4714.9      .1       0  4998.1     .07       0
  5004.1      .1       0  5102.7     .16       0  5446.9      .1       0
  5615.8     .05       0  5719.3      .1       0
#XS Ineff= 2 , 0
         4711.95    1746
Permanent Ineff=
       F       F
Bank Sta=4963.3,5031.4
XS Rating Curve= 0 ,0
Exp/Cntr=0.3,0.1

Type RM Length L Ch R = 1 ,119503  ,597,597,597
BEGIN DESCRIPTION:
NORTH GRAPE CREEK 163.0
END DESCRIPTION:
XS GIS Cut Line= 3
      2806281.98     10090752.56      2806646.57     10089476.51
      2807201.57     10088748.06
#Sta/Elev= 30
  3482.7 1798.22  3494.6 1797.71  3694.2 1791.48  4147.8 1774.96  4422.5 1768.07
  4523.5 1765.08  4624.5 1761.63  4646.3 1762.12  4677.5 1758.47  4730.2 1740.12
  4739.9 1738.32  4758.8 1736.75  4797.8  1736.4  4814.7 1733.82  4817.4 1730.75
  4820.1 1730.25  4823.4 1730.75  4863.6 1734.41  4899.4 1735.41    4941 1734.28
  4949.3 1735.24  4970.1 1731.41  4984.6 1733.19  4990.9 1731.79  5001.6 1732.15
  5034.5 1736.44  5090.7 1739.83  5231.7 1744.23  5594.8 1748.01  5725.6 1749.45
#Mann= 11 ,-1 , 0
  3482.7      .1       0  3494.6     .05       0  3694.2      .1       0
  4422.5     .05       0  4523.5      .1       0  4624.5     .05       0
  4817.4     .04       0  4823.4     .05       0  5001.6      .1       0
  5231.7     .16       0  5594.8      .1       0
Bank Sta=4797.8,5034.5
XS Rating Curve= 0 ,0
Exp/Cntr=0.3,0.1

Type RM Length L Ch R = 1 ,118906  ,638,638,638
BEGIN DESCRIPTION:
NORTH GRAPE CREEK 161.0
END DESCRIPTION:
XS GIS Cut Line= 3
      2806959.07     10090518.19      2807176.08     10089424.42
      2807462.54     10088790.75
#Sta/Elev= 30
  4261.3 1779.98  4316.8 1779.36  4357.6 1776.72  4408.6 1776.28  4500.3 1771.88
  4622.7 1769.02  4632.9 1768.09  4645.9 1764.85  4720.8 1762.03  4775.6  1759.3
  4820.2 1754.38  4877.5 1749.13  4896.7  1746.7  4901.8 1744.74  4935.6 1740.93
  4969.3 1733.85  4989.7 1724.53  5001.1  1723.1  5003.9  1722.6  5007.1  1723.1
  5010.1 1725.51  5030.5 1729.94  5152.6 1733.12  5208.8 1732.55  5251.9 1737.98
  5355.1 1740.11  5511.6 1740.24  5714.4 1739.97  5885.9 1744.93  6071.8 1748.94
#Mann= 11 ,-1 , 0
  4261.3     .05       0  4720.8      .1       0  4820.2     .16       0
  4935.6      .1       0  5001.1     .07       0  5007.1      .1       0
  5251.9     .05       0  5355.1      .1       0  5511.6     .16       0
  5714.4      .1       0  5885.9     .05       0
#XS Ineff= 2 , 0
                         5398.31         1740.49
Permanent Ineff=
       F       F
Bank Sta=4969.3,5030.5
XS Rating Curve= 0 ,0
Exp/Cntr=0.3,0.1

Type RM Length L Ch R = 1 ,118268  ,376,376,376
BEGIN DESCRIPTION:
Mapping XS 2defe4ad
END DESCRIPTION:
XS GIS Cut Line= 2
      2807662.01     10090045.84      2807722.77     10089334.03
#Sta/Elev= 30
  4562.7 1742.37  4594.9  1741.7  4702.9 1740.82  4755.5 1740.48  4797.6 1739.58
  4875.9 1736.15  4906.1 1733.38  4916.1 1731.64  4931.9 1726.92  4946.2 1726.06
  4966.3  1725.7  4976.3 1724.23  4993.4 1718.87  4996.1 1718.37  4999.4 1718.87
  5006.4 1719.18  5012.8 1721.51  5026.5 1726.62  5050.9 1726.73  5066.6 1726.28
  5086.7 1725.05  5096.7 1725.73  5111.8 1730.85  5116.8 1732.31  5136.9 1734.48
    5157 1735.11  5169.9 1736.04    5177 1736.03  5197.1 1737.43  5277.1 1739.54
#Mann= 7 ,-1 , 0
  4562.7      .1       0  4702.9     .05       0  4797.6      .1       0
  4993.4     .07       0  4999.4      .1       0  5012.8     .05       0
  5111.8      .1       0
Bank Sta=4966.3,5026.5
XS Rating Curve= 0 ,0
Exp/Cntr=0.3,0.1

Type RM Length L Ch R = 1 ,117892  ,430,430,430
BEGIN DESCRIPTION:
NORTH GRAPE CREEK 159.0
END DESCRIPTION:
XS GIS Cut Line= 3
      2807939.79     10090149.97      2808347.77     10088474.64
      2808252.87     10088284.84
#Sta/Elev= 30
  4492.7 1736.41  4707.1 1737.13  4859.4 1735.92  4909.1 1731.15  4933.7 1729.06
    4952 1724.79  5000.4 1716.22  5003.2 1715.72  5006.4 1716.22  5053.7 1725.08
  5100.6 1722.53  5116.7 1727.94  5133.7 1730.62  5238.7 1734.73  5342.6 1730.46
    5374 1732.18  5392.6 1737.62  5397.7 1736.15  5434.3 1739.84  5439.1 1738.02
  5517.7 1734.71  5564.6 1738.63  5753.2 1747.12  5849.7 1754.43  5945.2 1763.14
  6055.6 1769.29  6247.5 1783.17  6320.1 1786.46  6359.3 1792.03  6429.2 1793.61
#Mann= 13 ,-1 , 0
  4492.7      .1       0  4707.1     .05       0  4909.1     .16       0
  5000.4     .07       0  5006.4     .16       0  5133.7     .05       0
  5238.7      .1       0  5342.6     .16       0  5439.1      .1       0
  5753.2     .16       0  5849.7      .1       0  5945.2     .16       0
  6055.6      .1       0
#XS Ineff= 2 , 0
                         5225.79         1734.71
Permanent Ineff=
       F       F
Bank Sta=4952,5053.7
XS Rating Curve= 0 ,0
Exp/Cntr=0.3,0.1

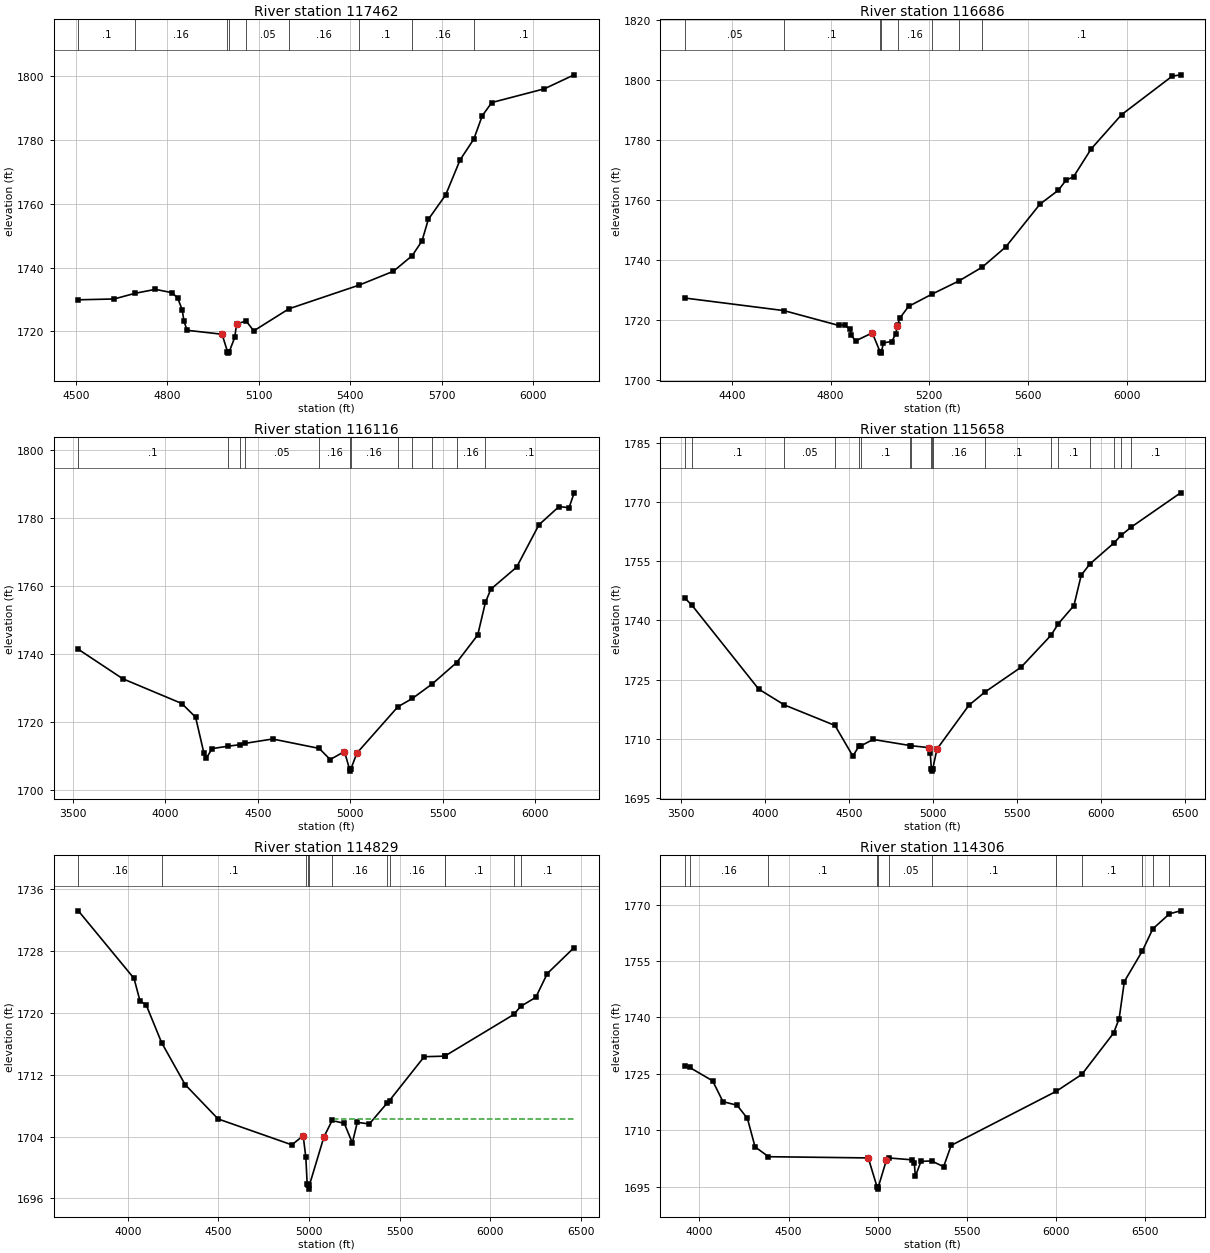
Type RM Length L Ch R = 1 ,117462  ,776,776,776
BEGIN DESCRIPTION:
NORTH GRAPE CREEK 158.0
END DESCRIPTION:
XS GIS Cut Line= 2
      2808339.08     10090106.62      2808790.47     10088544.11
#Sta/Elev= 30
  4507.7 1729.89  4625.2 1730.15    4693 1731.91  4760.5 1733.17  4814.8 1732.12
  4833.4 1730.47  4848.4 1726.78  4854.2 1723.14  4864.6 1720.33  4979.1 1719.09
  4996.9 1713.67  4999.7 1713.17  5002.9 1713.67  5020.7 1718.08  5026.9 1722.37
  5058.2 1723.22  5083.2 1720.15  5198.5 1727.07  5429.2 1734.51  5541.2 1738.84
  5602.9 1743.74  5634.9 1748.32  5655.7  1755.1  5712.7 1762.79  5759.8 1773.73
  5805.1 1780.31  5832.6 1787.59  5863.9 1791.74  6036.2 1796.04  6134.1 1800.43
#Mann= 9 ,-1 , 0
  4507.7      .1       0    4693     .16       0  4996.9     .07       0
  5002.9     .16       0  5058.2     .05       0  5198.5     .16       0
  5429.2      .1       0  5602.9     .16       0  5805.1      .1       0
Bank Sta=4979.1,5026.9
XS Rating Curve= 0 ,0
Exp/Cntr=0.3,0.1

Type RM Length L Ch R = 1 ,116686  ,570,570,570
BEGIN DESCRIPTION:
NORTH GRAPE CREEK 157.0
END DESCRIPTION:
XS GIS Cut Line= 4
      2808564.98     10090144.91      2809181.29     10089867.13
       2809354.9     10089537.27      2809155.25     10088599.78
#Sta/Elev= 30
    4210 1727.34  4611.3 1723.15  4833.5  1718.2  4856.6  1718.4  4879.8 1716.88
  4884.1 1714.91  4901.2 1713.06    4969 1715.72  5000.3 1709.49    5003 1708.99
  5006.3 1709.49    5014 1712.41  5048.1 1712.86  5063.7 1715.35  5070.7 1718.14
  5071.7  1718.4  5080.1 1720.59  5115.9 1724.55  5212.5 1728.71  5319.5 1733.01
  5414.5 1737.64  5509.3 1744.35  5647.8 1758.59  5722.5 1763.25  5753.2 1766.56
  5783.8 1767.72  5855.4 1777.02  5978.1 1788.38  6182.8 1801.19  6217.3 1801.66
#Mann= 8 ,-1 , 0
    4210     .05       0  4611.3      .1       0  5000.3     .07       0
  5006.3      .1       0  5071.7     .16       0  5212.5      .1       0
  5319.5     .05       0  5414.5      .1       0
Bank Sta=4969,5070.7
XS Rating Curve= 0 ,0
Exp/Cntr=0.3,0.1

Type RM Length L Ch R = 1 ,116116  ,458,458,458
BEGIN DESCRIPTION:
NORTH GRAPE CREEK 155.0
END DESCRIPTION:
XS GIS Cut Line= 3
       2809493.6     10091261.12      2809849.51     10089568.39
      2809502.87     10088684.47
#Sta/Elev= 30
  3530.7 1741.41  3770.6 1732.74  4090.1 1725.44  4164.3 1721.42    4209 1710.91
  4222.9 1709.38  4253.6 1712.17  4339.3 1712.88  4402.5 1713.31  4433.7 1713.74
  4580.5    1715  4832.1 1712.23  4891.5 1708.96  4968.9  1711.3  4996.5 1706.04
  4999.3 1705.54  5002.5 1706.04    5036 1710.85  5257.3 1724.48  5335.5 1726.93
  5442.9 1731.21  5574.9  1737.5  5688.8 1745.62  5730.2 1755.19  5759.5  1759.1
  5899.2 1765.61  6019.6 1778.07  6128.1 1783.43  6182.4  1783.1  6209.9 1787.48
#Mann= 12 ,-1 , 0
  3530.7      .1       0  4339.3     .05       0  4402.5      .1       0
  4433.7     .05       0  4832.1     .16       0  4996.5     .07       0
  5002.5     .16       0  5257.3      .1       0  5335.5     .16       0
  5442.9     .05       0  5574.9     .16       0  5730.2      .1       0
Bank Sta=4968.9,5036
XS Rating Curve= 0 ,0
Exp/Cntr=0.3,0.1

Type RM Length L Ch R = 1 ,115658  ,829,829,829
BEGIN DESCRIPTION:
NORTH GRAPE CREEK 154.0
END DESCRIPTION:
XS GIS Cut Line= 3
      2810127.29     10091382.61      2810240.13     10089351.37
      2809745.34      10088578.8
#Sta/Elev= 30
  3524.1 1745.64  3567.6 1743.77  3963.7  1722.6  4116.2 1718.59  4418.2 1713.38
  4524.5 1705.64  4562.3 1708.22  4570.6 1708.17  4644.7 1709.84  4866.5 1708.29
  4869.1 1708.26  4975.2 1707.78  4985.2 1706.44  4992.2 1702.32    4995 1701.82
  4998.2 1702.32  5000.4 1702.43  5025.3  1707.4  5215.6  1718.5  5310.9 1721.84
  5526.1 1728.13  5703.6 1736.19  5748.6 1739.18  5840.7 1743.74  5884.1 1751.42
  5935.6 1754.26  6077.3 1759.52  6121.4 1761.51  6181.1 1763.58  6475.9 1772.28
#Mann= 18 ,-1 , 0
  3524.1     .16       0  3567.6      .1       0  4116.2     .05       0
  4418.2      .1       0  4562.3     .16       0  4570.6      .1       0
  4866.5     .05       0  4869.1      .1       0  4992.2     .07       0
  4998.2      .1       0  5000.4     .16       0  5310.9      .1       0
  5703.6     .05       0  5748.6      .1       0  5935.6     .16       0
  6077.3      .1       0  6121.4     .16       0  6181.1      .1       0
Bank Sta=4975.2,5025.3
XS Rating Curve= 0 ,0
Exp/Cntr=0.3,0.1

Type RM Length L Ch R = 1 ,114829  ,523,523,523
BEGIN DESCRIPTION:
NORTH GRAPE CREEK 153.0
END DESCRIPTION:
XS GIS Cut Line= 3
      2810596.04     10091382.62      2811151.59     10089507.62
      2811671.23     10088927.36
#Sta/Elev= 30
  3727.7  1733.2  4034.8 1724.46  4068.1 1721.52  4101.3 1721.06    4187 1716.15
  4316.4 1710.73  4498.3 1706.28  4905.1 1702.93  4967.7  1704.1  4982.4  1701.3
  4989.8 1697.88    4996  1697.7  4998.7  1697.2    5002  1697.7  5082.4 1703.97
  5127.4 1706.08  5194.5 1705.71  5238.9 1703.18  5266.2 1705.84  5332.7 1705.63
  5431.2 1708.35  5443.9 1708.66  5635.2 1714.33  5747.2  1714.4  5748.2  1714.4
  6129.2 1719.79  6166.7 1720.83  6250.6 1722.01  6314.2 1725.09  6462.2 1728.45
#Mann= 12 ,-1 , 0
  3727.7     .16       0    4187      .1       0  4982.4     .05       0
    4996     .04       0    5002     .05       0  5127.4     .16       0
  5431.2      .1       0  5443.9     .16       0  5747.2     .05       0
  5748.2      .1       0  6129.2     .05       0  6166.7      .1       0
#XS Ineff= 2 , 0
                         5144.27         1706.27
Permanent Ineff=
       F       F
Bank Sta=4967.7,5082.4
XS Rating Curve= 0 ,0
Exp/Cntr=0.3,0.1

Type RM Length L Ch R = 1 ,114306  ,838,838,838
BEGIN DESCRIPTION:
NORTH GRAPE CREEK 151.0
END DESCRIPTION:
XS GIS Cut Line= 4
      2810899.84     10091339.24      2811333.88     10090636.09
      2811767.91     10089368.73      2812314.16      10089082.6
#Sta/Elev= 30
  3917.6 1727.21  3945.4 1726.71  4073.9 1723.16  4131.8 1717.63    4211 1716.69
    4269 1713.18  4311.9 1705.63  4387.3 1703.01  4947.3 1702.69  4997.1  1694.9
  4999.9  1694.4  5003.1  1694.9  5049.5 1702.17  5066.1 1702.67  5190.4 1702.19
  5205.9 1701.24  5211.5 1697.79  5243.2 1701.78  5303.3 1701.88  5370.1 1700.35
  5412.3 1706.01  6002.8  1720.4  6146.2 1724.89  6323.7 1735.83  6355.1 1739.66
  6384.3 1749.54  6485.8 1757.69  6544.1 1763.53  6637.6 1767.53  6700.2 1768.32
#Mann= 12 ,-1 , 0
  3917.6      .1       0  3945.4     .16       0  4387.3      .1       0
  4997.1     .07       0  5003.1      .1       0  5066.1     .05       0
  5303.3      .1       0  6002.8     .05       0  6146.2      .1       0
  6485.8     .05       0  6544.1      .1       0  6637.6     .05       0
Bank Sta=4947.3,5049.5
XS Rating Curve= 0 ,0
Exp/Cntr=0.3,0.1

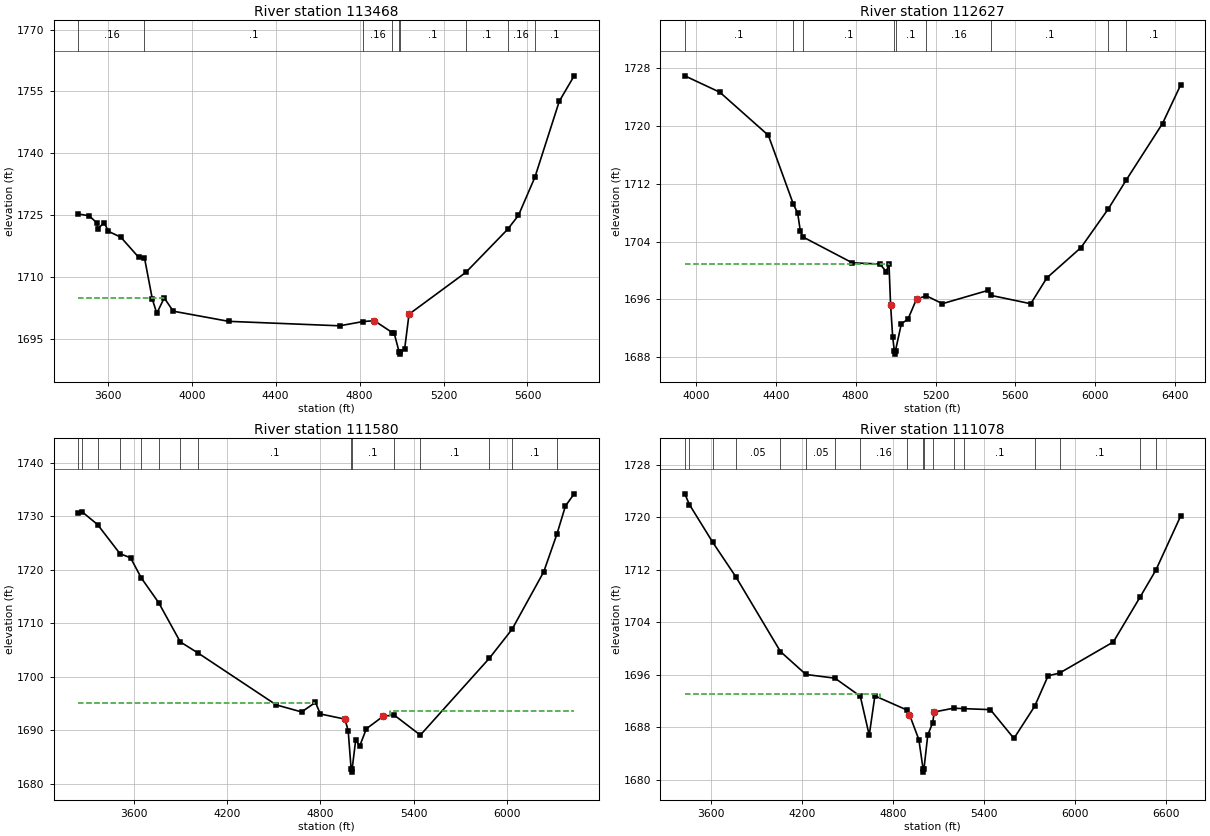
Type RM Length L Ch R = 1 ,113468  ,841,841,841
BEGIN DESCRIPTION:
NORTH GRAPE CREEK 150.0
END DESCRIPTION:
XS GIS Cut Line= 3
      2810943.48     10091290.72      2812401.78     10090223.04
      2812636.15     10089719.58
#Sta/Elev= 30
  3459.8 1725.32  3511.6 1724.89  3547.2 1723.19  3553.4 1721.77  3582.7 1723.23
  3603.5 1721.11  3662.2 1719.71  3747.9  1714.8  3774.9 1714.73  3812.7 1704.65
  3833.6 1701.28  3869.1 1704.98  3912.1 1701.78  4176.4 1699.32  4705.3 1698.24
  4816.2 1699.27  4870.4 1699.48  4956.1 1696.59  4964.6  1696.5  4988.6 1691.88
  4991.4 1691.38  4994.6 1691.88  5014.8 1692.64  5035.6 1701.05  5306.6 1711.19
  5505.3  1721.6  5557.1 1724.99  5635.7 1734.27  5751.7 1752.64  5822.5 1758.79
#Mann= 9 ,-1 , 0
  3459.8     .16       0  3774.9      .1       0  4816.2     .16       0
  4956.1      .1       0  4988.6     .04       0  4994.6      .1       0
  5306.6      .1       0  5505.3     .16       0  5635.7      .1       0
#XS Ineff= 2 , 0
         3870.46 1705.03
Permanent Ineff=
       F       F
Bank Sta=4870.4,5035.6
XS Rating Curve= 0 ,0
Exp/Cntr=0.3,0.1

Type RM Length L Ch R = 1 ,112627  ,1047,1047,1047
BEGIN DESCRIPTION:
NORTH GRAPE CREEK 149.0
END DESCRIPTION:
XS GIS Cut Line= 3
      2811056.34     10091438.29      2812610.11     10090795.95
      2813009.43     10090101.49
#Sta/Elev= 30
  3944.8 1726.92  4120.2 1724.65  4363.1 1718.69  4488.9 1709.12  4509.8 1707.94
  4522.8 1705.52  4535.5 1704.64  4783.5 1701.05    4921 1700.89  4953.4 1699.84
  4967.1 1700.87  4975.1 1695.22  4985.6 1690.78  4993.7 1688.92  4996.5 1688.42
  4999.7 1688.92  5029.2 1692.64  5061.7 1693.23  5104.9 1696.03  5153.7 1696.49
  5234.8  1695.4  5464.6 1697.25  5475.4 1696.56  5676.8 1695.39  5757.3 1698.96
  5928.3 1703.16    6066 1708.55  6155.7 1712.54  6336.5 1720.32  6427.2 1725.65
#Mann= 9 ,-1 , 0
  3944.8      .1       0  4488.9     .16       0  4535.5      .1       0
  4993.7     .07       0  4999.7      .1       0  5153.7     .16       0
  5475.4      .1       0    6066     .05       0  6155.7      .1       0
#XS Ineff= 2 , 0
         4966.05 1700.88
Permanent Ineff=
       F       F
Bank Sta=4975.1,5104.9
XS Rating Curve= 0 ,0
Exp/Cntr=0.3,0.1

Type RM Length L Ch R = 1 ,111580  ,502,502,502
BEGIN DESCRIPTION:
NORTH GRAPE CREEK 148.0
END DESCRIPTION:
XS GIS Cut Line= 4
      2811169.12     10091811.58      2813000.74     10091203.94
      2813226.43     10091065.05      2813269.79     10090067.78
#Sta/Elev= 30
  3241.5 1730.72  3265.2 1730.87  3365.8 1728.46  3509.7 1723.03    3578 1722.26
  3646.8  1718.5  3758.6 1713.89  3898.1 1706.54  4011.7 1704.48  4515.6 1694.77
  4679.3 1693.45  4768.5 1695.23  4800.1 1693.07  4958.2 1692.11  4979.2 1689.96
  4998.4  1682.7  5001.2  1682.2  5004.4  1682.7  5027.8 1688.24    5053 1687.04
  5096.5 1690.31    5205 1692.65  5275.8 1692.86  5443.9 1689.12  5887.6 1703.46
  6034.2 1708.88  6238.4 1719.63  6323.3 1726.68  6378.5 1731.95  6434.5 1734.22
#Mann= 15 ,-1 , 0
  3241.5      .1       0  3265.2     .05       0  3365.8      .1       0
  3509.7     .05       0  3646.8      .1       0  3758.6     .16       0
  3898.1     .05       0  4011.7      .1       0  4998.4     .07       0
  5004.4      .1       0  5275.8     .16       0  5443.9      .1       0
  5887.6     .05       0  6034.2      .1       0  6323.3     .05       0
#XS Ineff= 2 , 0
          4766.9 1695.21 5249.93         1693.54
Permanent Ineff=
       F       F
Bank Sta=4958.2,5205
XS Rating Curve= 0 ,0
Exp/Cntr=0.3,0.1

Type RM Length L Ch R = 1 ,111078  ,991,991,991
BEGIN DESCRIPTION:
Mapping XS 980993ad
END DESCRIPTION:
XS GIS Cut Line= 4
      2811446.78     10092077.06      2813287.01     10091643.04
      2813399.86     10091226.37      2813399.86     10090280.17
#Sta/Elev= 30
  3427.7 1723.58  3457.9 1721.95  3612.6 1716.16  3765.2 1710.89  4058.5 1699.52
  4226.3 1696.03  4417.2 1695.47  4584.7 1692.71  4643.6 1686.76  4680.8 1692.77
    4892 1690.61  4908.9  1689.9  4970.6 1686.11  4998.4 1681.64  5001.2 1681.14
  5004.4 1681.64  5029.7 1686.85  5061.9 1688.64    5072 1690.31  5199.3 1690.89
  5268.2 1690.82    5442 1690.67  5597.4 1686.28  5734.6  1691.2  5822.7 1695.83
  5898.7 1696.25  6252.7 1700.99  6430.5 1707.89    6533 1711.94  6696.3 1720.18
#Mann= 18 ,-1 , 0
  3427.7      .1       0  3457.9     .16       0  3612.6      .1       0
  3765.2     .05       0  4058.5      .1       0  4226.3     .05       0
  4417.2      .1       0  4584.7     .16       0    4892      .1       0
  4998.4     .07       0  5004.4      .1       0  5061.9     .16       0
  5199.3     .05       0  5268.2      .1       0  5734.6     .16       0
  5898.7      .1       0  6430.5     .05       0    6533      .1       0
#XS Ineff= 2 , 0
         4714.25 1693.07
Permanent Ineff=
       F       F
Bank Sta=4908.9,5072
XS Rating Curve= 0 ,0
Exp/Cntr=0.3,0.1