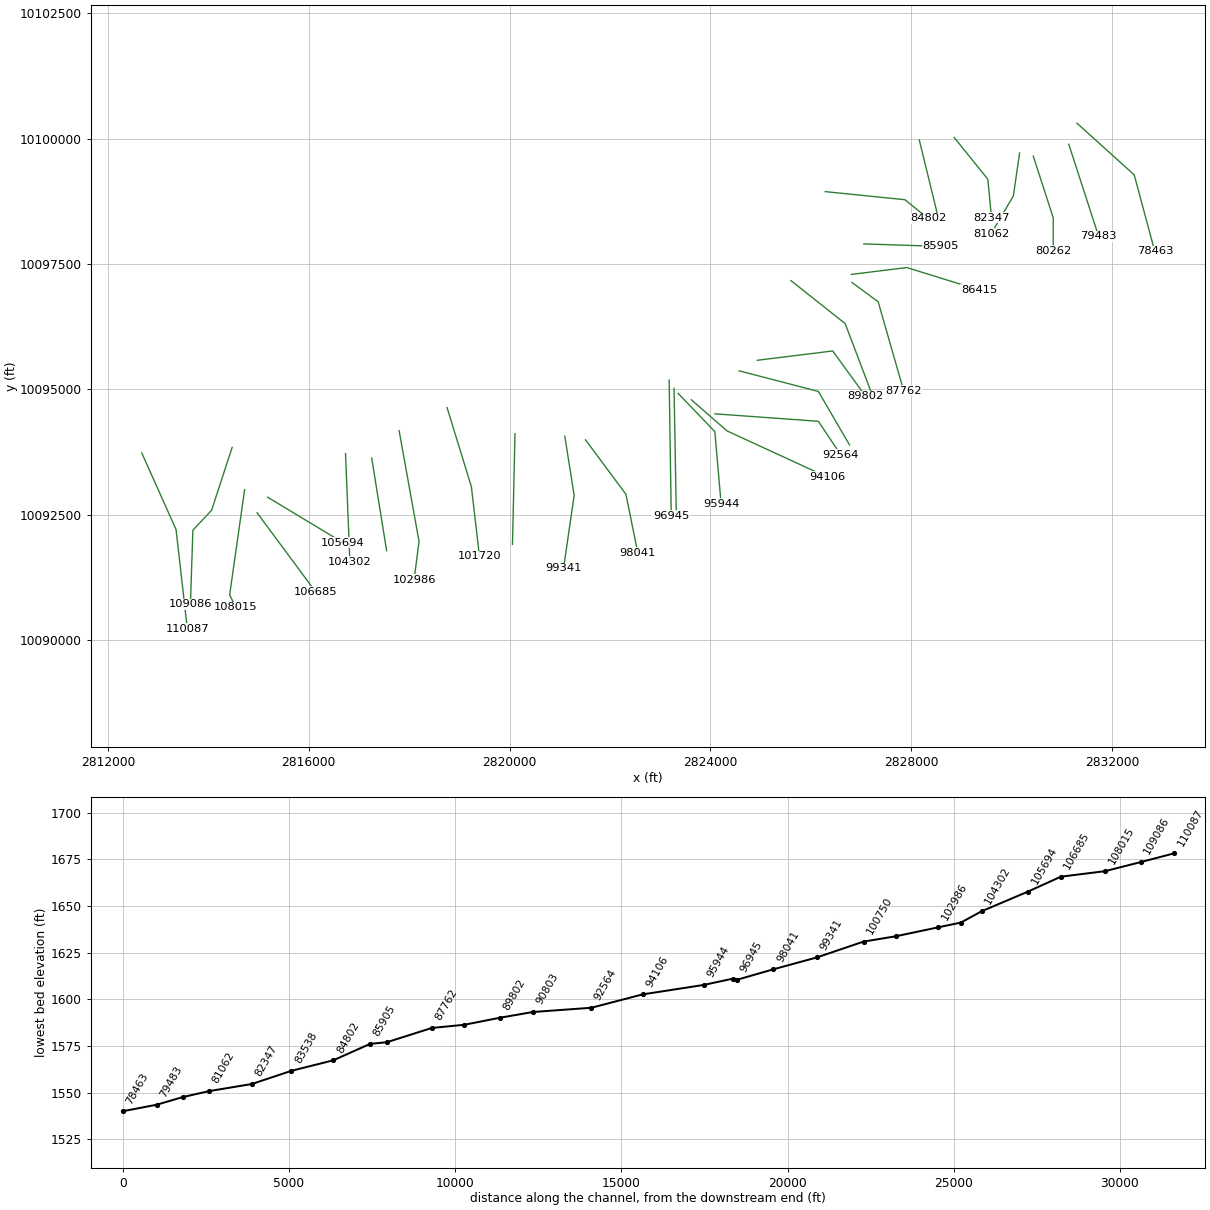
HEC-RAS study NORTH GRAPE CREEK.prj: NORTH GRAPE CREEK Base Level Engineering

--- NORTH GRAPE CREEK.g01 (geometry) --- (continued)

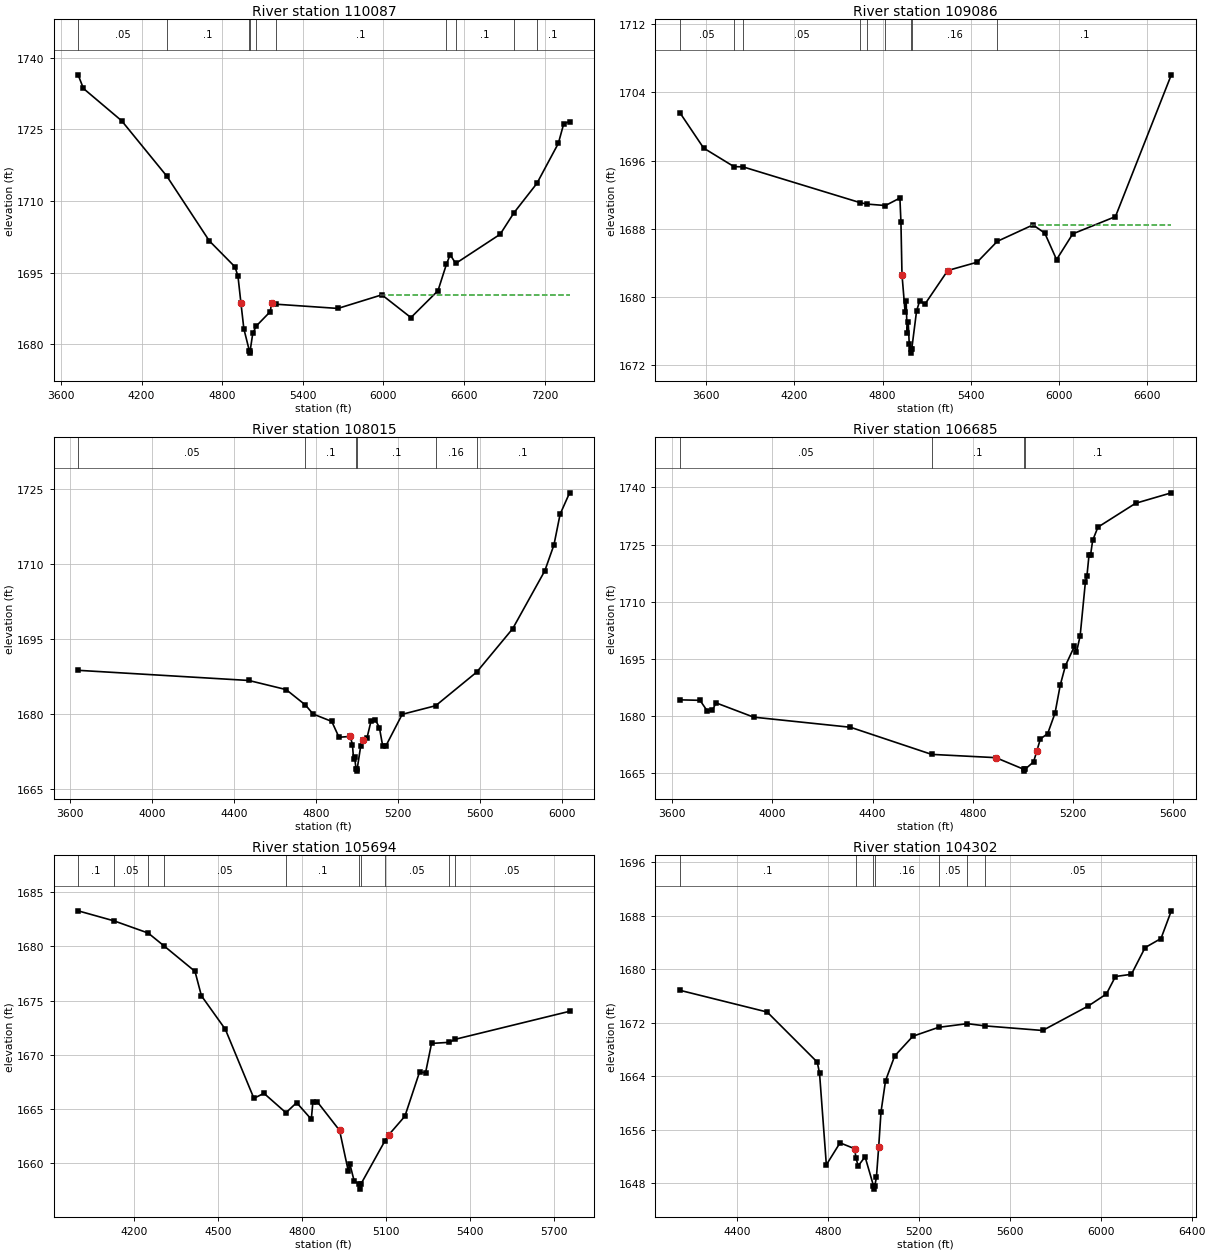
Type RM Length L Ch R = 1 ,110087  ,1001,1001,1001
BEGIN DESCRIPTION:
NORTH GRAPE CREEK 147.0
END DESCRIPTION:
XS GIS Cut Line= 3
      2812674.73      10093729.8      2813357.24     10092203.47
      2813580.61     10090230.34
#Sta/Elev= 30
    3728 1736.44  3767.5 1733.58  4052.3  1726.8  4387.7 1715.21  4704.4 1701.63
  4895.5 1696.18  4917.7 1694.22  4939.6 1688.62  4961.5 1683.19  5002.3  1678.6
  5005.1  1678.1  5008.3  1678.6    5028 1682.28  5054.8 1683.81  5158.7 1686.82
  5167.2 1688.61  5198.5 1688.36  5661.4 1687.47  5988.6 1690.32  6204.8 1685.55
  6406.1 1691.19  6468.7  1696.7  6496.7 1698.74  6537.9  1696.9    6869 1703.02
  6971.8 1707.53    7142 1713.67  7301.8 1722.07    7342 1726.19  7385.7 1726.64
#Mann= 10 ,-1 , 0
    3728     .05       0  4387.7      .1       0  5002.3     .07       0
  5008.3      .1       0  5054.8     .05       0  5198.5      .1       0
  6468.7     .16       0  6537.9      .1       0  6971.8     .16       0
    7142      .1       0
#XS Ineff= 2 , 0
                         5974.88         1690.21
Permanent Ineff=
       F       F
Bank Sta=4939.6,5167.2
XS Rating Curve= 0 ,0
Exp/Cntr=0.3,0.1

Type RM Length L Ch R = 1 ,109086  ,1071,1071,1071
BEGIN DESCRIPTION:
NORTH GRAPE CREEK 146.0
END DESCRIPTION:
XS GIS Cut Line= 4
      2814474.09     10093841.53      2814064.57     10092588.16
      2813692.29     10092191.06      2813642.65     10090714.39
#Sta/Elev= 30
  3421.9 1701.64  3583.8 1697.48  3790.3  1695.3  3850.7 1695.28  4649.1 1691.07
  4694.6 1690.91  4819.5 1690.74  4917.7 1691.62  4924.7 1688.83  4931.9 1682.63
  4952.9 1678.27  4960.2  1679.5  4967.1 1675.81  4974.4 1677.08  4981.2 1674.48
  4992.4 1673.93  4995.1 1673.43  4998.4 1673.93    5031 1678.37    5052 1679.55
  5087.7 1679.17    5243 1683.12  5442.2 1684.09  5579.6 1686.54  5822.4 1688.47
  5902.5  1687.5  5982.5  1684.4  6092.6 1687.42  6382.7 1689.44  6762.3 1706.07
#Mann= 9 ,-1 , 0
  3421.9     .05       0  3790.3      .1       0  3850.7     .05       0
  4649.1      .1       0  4694.6     .05       0  4819.5     .16       0
  4992.4     .07       0  4998.4     .16       0  5579.6      .1       0
#XS Ineff= 2 , 0
                          5811.5         1688.51
Permanent Ineff=
       F       F
Bank Sta=4931.9,5243
XS Rating Curve= 0 ,0
Exp/Cntr=0.3,0.1

Type RM Length L Ch R = 1 ,108015  ,1330,1330,1330
BEGIN DESCRIPTION:
NORTH GRAPE CREEK 145.0
END DESCRIPTION:
XS GIS Cut Line= 3
      2814722.27     10092997.71      2814424.44     10090900.49
      2814548.51     10090652.34
#Sta/Elev= 30
  3640.7 1688.73  4472.9  1686.7  4654.7 1684.88    4749 1681.79  4786.1    1680
    4877 1678.52  4912.3 1675.36  4967.9 1675.52    4978 1673.83  4983.3 1671.01
  4988.3 1671.39  4995.2 1669.09  4997.9 1668.59  5001.2 1669.09  5018.4 1673.67
  5028.5 1674.82  5048.7 1675.21  5068.9 1678.67  5089.1 1678.88  5109.3 1677.28
  5125.1 1673.68  5139.6 1673.53  5220.4 1679.94  5383.5 1681.66  5583.4 1688.37
    5759 1697.05  5915.4  1708.6  5960.1 1713.79  5990.1 1719.92  6036.4 1724.19
#Mann= 6 ,-1 , 0
  3640.7     .05       0    4749      .1       0  4995.2     .07       0
  5001.2      .1       0  5383.5     .16       0  5583.4      .1       0
Bank Sta=4967.9,5028.5
XS Rating Curve= 0 ,0
Exp/Cntr=0.3,0.1

Type RM Length L Ch R = 1 ,106685  ,991,991,991
BEGIN DESCRIPTION:
NORTH GRAPE CREEK 142.0
END DESCRIPTION:
XS GIS Cut Line= 2
      2814970.46      10092538.5      2816136.93     10090962.53
#Sta/Elev= 30
  3630.8 1684.31  3711.4 1684.18  3739.6 1681.46  3761.1 1681.61  3775.1 1683.52
  3925.4 1679.77  4311.5 1677.12  4635.4 1670.01  4891.8 1669.15  5002.3 1666.12
    5005 1665.62  5008.3 1666.12  5042.1 1668.05    5055 1670.91  5069.1 1674.04
  5098.4 1675.47  5127.6 1680.82  5148.5 1688.19  5169.3 1693.29  5204.8 1698.32
  5213.2  1696.8  5227.8 1701.07  5248.7 1715.16  5254.9 1716.76  5263.3 1722.33
  5269.5 1722.35  5277.9 1726.13  5298.8 1729.58  5449.1 1735.84  5591.5 1738.58
#Mann= 4 ,-1 , 0
  3630.8     .05       0  4635.4      .1       0  5002.3     .07       0
  5008.3      .1       0
Bank Sta=4891.8,5055
XS Rating Curve= 0 ,0
Exp/Cntr=0.3,0.1

Type RM Length L Ch R = 1 ,105694  ,1392,1392,1392
BEGIN DESCRIPTION:
NORTH GRAPE CREEK 141.0
END DESCRIPTION:
XS GIS Cut Line= 2
      2815181.44     10092848.73      2816682.95     10091942.86
#Sta/Elev= 30
  4001.3 1683.27    4130 1682.34  4251.4 1681.22  4307.7 1680.04  4418.3 1677.69
  4441.2 1675.44  4526.6 1672.35  4628.5 1665.99  4664.4 1666.45  4742.9 1664.66
  4780.9 1665.59  4833.3 1664.06  4839.1 1665.69  4854.6 1665.67  4934.2 1663.03
  4965.3 1659.28  4971.1 1659.91  4986.6 1658.33    5005 1658.12  5007.7 1657.62
    5011 1658.12  5096.5 1662.09  5108.9  1662.6  5167.2 1664.34  5219.6 1668.42
  5240.9 1668.34  5262.3 1671.05    5326 1671.15  5345.3 1671.42  5754.9 1674.01
#Mann= 10 ,-1 , 0
  4001.3      .1       0    4130     .05       0  4251.4      .1       0
  4307.7     .05       0  4742.9      .1       0    5005     .07       0
    5011      .1       0  5096.5     .05       0    5326      .1       0
  5345.3     .05       0
Bank Sta=4934.2,5108.9
XS Rating Curve= 0 ,0
Exp/Cntr=0.3,0.1

Type RM Length L Ch R = 1 ,104302  ,622,622,622
BEGIN DESCRIPTION:
NORTH GRAPE CREEK 140.0
END DESCRIPTION:
XS GIS Cut Line= 2
      2816732.57     10093717.43      2816819.42     10091558.48
#Sta/Elev= 30
  4149.8 1676.83  4533.8 1673.58    4754 1666.09    4764 1664.45    4794 1650.73
  4854.1 1654.02  4918.8 1653.14    4924 1651.76  4934.1 1650.57  4964.2 1651.94
  5001.2  1647.6  5003.9  1647.1  5007.2  1647.6  5014.2  1648.9  5024.2 1653.46
  5034.2 1658.63  5054.2 1663.31  5094.3    1667  5174.3 1669.96  5287.4 1671.29
  5413.9 1671.84  5490.9 1671.51  5744.8 1670.82    5945 1674.47    6025 1676.27
    6065 1678.89  6135.1 1679.22  6195.2 1683.21  6265.2 1684.57  6310.5 1688.71
#Mann= 7 ,-1 , 0
  4149.8      .1       0    4924     .16       0  5001.2     .07       0
  5007.2     .16       0  5287.4     .05       0  5413.9      .1       0
  5490.9     .05       0
Bank Sta=4918.8,5024.2
XS Rating Curve= 0 ,0
Exp/Cntr=0.3,0.1

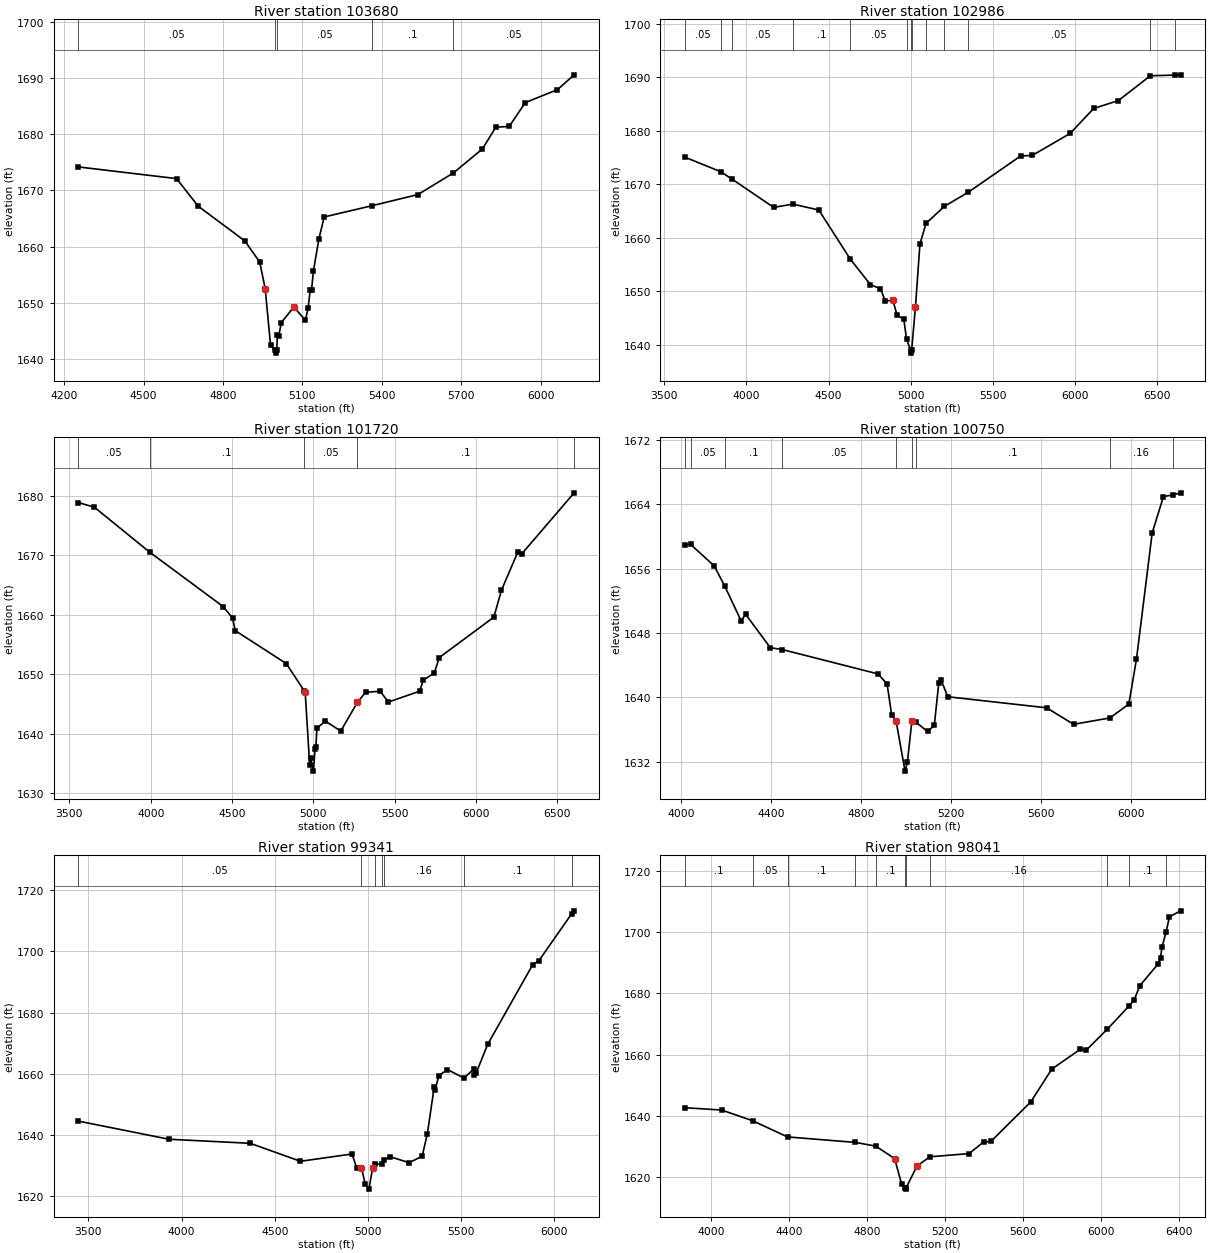
Type RM Length L Ch R = 1 ,103680  ,694,694,694
BEGIN DESCRIPTION:
NORTH GRAPE CREEK 139.0
END DESCRIPTION:
XS GIS Cut Line= 2
      2817253.76     10093630.55      2817551.58     10091781.58
#Sta/Elev= 30
  4253.8 1674.18  4624.8  1672.1  4706.4  1667.2  4882.2 1661.04    4939 1657.26
  4959.6 1652.52  4979.9 1642.44  4997.1 1641.56  4999.9 1641.06  5003.1 1641.56
  5005.9  1644.2  5010.9 1644.12  5020.4  1646.5  5067.7 1649.25  5111.5 1646.91
  5121.7 1649.07  5129.5 1652.25  5134.6 1652.26  5141.9 1655.72  5162.2 1661.33
  5182.4 1665.28  5364.8  1667.3  5536.9 1669.27  5670.4 1673.11    5780 1677.37
  5830.7 1681.25  5881.3 1681.38  5942.1 1685.62  6063.6 1687.93  6126.6 1690.56
#Mann= 5 ,-1 , 0
  4253.8     .05       0  4997.1     .04       0  5003.1     .05       0
  5364.8      .1       0  5670.4     .05       0
Bank Sta=4959.6,5067.7
XS Rating Curve= 0 ,0
Exp/Cntr=0.3,0.1

Type RM Length L Ch R = 1 ,102986  ,1266,1266,1266
BEGIN DESCRIPTION:
NORTH GRAPE CREEK 134.0
END DESCRIPTION:
XS GIS Cut Line= 3
      2817799.76     10094176.59      2818196.87     10091967.69
      2818097.62     10091198.48
#Sta/Elev= 30
  3624.4 1675.08  3844.7 1672.34  3913.1 1670.95  4165.8 1665.69  4282.5  1666.3
  4440.9  1665.2  4631.6 1656.05  4755.1 1651.26  4816.1 1650.48  4846.5 1648.13
  4890.5 1648.42  4917.7 1645.54  4958.3 1644.79  4974.7 1641.15  4999.9 1638.96
  5002.6 1638.46  5005.9 1638.96  5029.4 1647.15  5056.5 1658.84  5093.5 1662.69
  5204.3 1665.86  5350.7 1668.52  5669.5 1675.29  5741.1 1675.41    5971  1679.5
  6114.7 1684.17  6265.9 1685.66  6459.9 1690.29  6611.1 1690.41  6644.3 1690.46
#Mann= 13 ,-1 , 0
  3624.4     .05       0  3844.7      .1       0  3913.1     .05       0
  4282.5      .1       0  4631.6     .05       0  4974.7     .16       0
  4999.9     .07       0  5005.9     .16       0  5093.5     .05       0
  5204.3      .1       0  5350.7     .05       0  6459.9      .1       0
  6611.1     .05       0
Bank Sta=4890.5,5029.4
XS Rating Curve= 0 ,0
Exp/Cntr=0.3,0.1

Type RM Length L Ch R = 1 ,101720  ,970,970,970
BEGIN DESCRIPTION:
NORTH GRAPE CREEK 133.0
END DESCRIPTION:
XS GIS Cut Line= 3
      2818755.29      10094635.7      2819239.25     10093059.71
      2819400.57     10091669.87
#Sta/Elev= 30
  3554.9 1678.82  3653.6 1678.03  3993.1 1670.49  4446.1 1661.33  4503.1 1659.39
  4519.4 1657.31  4833.2 1651.77  4944.2 1647.16  4949.4 1646.98  4976.9 1634.71
  4982.2 1635.92  5000.3 1633.71  5009.6 1637.44  5014.9 1637.76  5021.5 1640.94
  5073.8  1642.1  5167.9 1640.44  5269.9 1645.24  5320.3 1646.94  5409.7 1647.13
  5461.2 1645.31  5652.5 1647.13  5675.7    1649  5743.1 1650.18  5773.3 1652.78
    6109 1659.57  6155.9  1664.1  6256.5 1670.51  6281.3 1670.22  6602.7 1680.45
#Mann= 5 ,-1 , 0
  3554.9     .05       0  3993.1      .1       0  4944.2     .05       0
  5269.9      .1       0  6602.7      .1       0
Bank Sta=4949.4,5269.9
XS Rating Curve= 0 ,0
Exp/Cntr=0.3,0.1

Type RM Length L Ch R = 1 ,100750  ,1409,1409,1409
BEGIN DESCRIPTION:
NORTH GRAPE CREEK 132.0
END DESCRIPTION:
XS GIS Cut Line= 2
       2820107.9     10094114.45       2820058.3     10091907.21
#Sta/Elev= 30
    4015 1658.94  4040.4 1659.01  4145.8 1656.34  4193.6 1653.78  4265.8 1649.51
  4285.8 1650.33  4395.8 1646.18  4448.7 1645.95  4875.9 1642.92  4915.9 1641.66
    4936 1637.85    4956 1637.05  4995.7 1630.86    5006 1631.95    5026 1637.02
  5043.1 1636.95    5096 1635.78    5126 1636.54    5146 1641.81    5156 1642.18
    5186 1640.09  5626.1 1638.72  5746.2 1636.67  5907.8 1637.46  5992.1 1639.17
  6026.2 1644.76  6096.2 1660.42  6146.3 1664.94  6187.1 1665.12  6222.8  1665.4
#Mann= 9 ,-1 , 0
    4015      .1       0  4040.4     .05       0  4193.6      .1       0
  4448.7     .05       0    4956     .04       0    5026     .05       0
  5043.1      .1       0  5907.8     .16       0  6187.1      .1       0
Bank Sta=4956,5026
XS Rating Curve= 0 ,0
Exp/Cntr=0.3,0.1

Type RM Length L Ch R = 1 ,99341   ,1300,1300,1300
BEGIN DESCRIPTION:
NORTH GRAPE CREEK 131.0
END DESCRIPTION:
XS GIS Cut Line= 3
      2821100.65     10094064.86      2821286.79     10092885.98
      2821075.83     10091434.11
#Sta/Elev= 30
  3445.9 1644.56    3933 1638.63  4368.3 1637.31    4638 1631.44  4914.5 1633.82
  4940.2 1629.19    4965 1629.38  4985.2 1624.03  5005.1 1622.35  5025.6 1629.41
  5035.8  1630.4  5075.4 1630.67    5088 1631.79  5116.6 1632.97  5220.8 1630.99
  5290.9 1633.07  5318.7 1640.41    5356 1655.84  5361.1 1654.71  5379.3 1659.33
  5426.2 1661.39  5515.6 1658.61  5566.4  1661.5  5571.5 1659.71  5581.4 1660.36
  5642.1 1669.58  5884.6 1695.66  5917.1 1696.91    6093 1712.22  6106.5  1713.2
#Mann= 7 ,-1 , 0
  3445.9     .05       0    4965     .04       0  5035.8     .05       0
  5075.4      .1       0    5088     .16       0  5515.6      .1       0
    6093     .16       0
Bank Sta=4965,5025.6
XS Rating Curve= 0 ,0
Exp/Cntr=0.3,0.1

Type RM Length L Ch R = 1 ,98041   ,1096,1096,1096
BEGIN DESCRIPTION:
NORTH GRAPE CREEK 130.0
END DESCRIPTION:
XS GIS Cut Line= 3
      2821512.63      10093993.5      2822318.17     10092906.71
      2822554.28     10091740.05
#Sta/Elev= 30
  3864.7 1642.64  4054.1 1641.88  4212.4 1638.39  4391.5  1633.1  4740.2  1631.3
  4844.4 1630.09    4941 1626.01  4976.5 1617.74  4994.3 1616.54  4997.1 1616.04
  5000.3 1616.54  5055.8 1623.61  5121.9 1626.61  5322.5 1627.64  5397.2 1631.45
  5434.8 1631.63  5638.8  1644.5  5747.1 1655.26  5893.9 1661.77  5924.5 1661.49
  6032.5 1668.35  6143.9 1675.93  6169.4 1677.84  6198.5 1682.51  6291.8 1689.59
    6305  1691.7  6312.2  1695.1  6332.7 1699.92  6350.6 1705.04  6407.8 1706.97
#Mann= 11 ,-1 , 0
  3864.7      .1       0  4212.4     .05       0  4391.5      .1       0
  4740.2     .05       0  4844.4      .1       0  4994.3     .07       0
  5000.3      .1       0  5121.9     .16       0  6032.5     .05       0
  6143.9      .1       0  6332.7     .16       0
Bank Sta=4941,5055.8
XS Rating Curve= 0 ,0
Exp/Cntr=0.3,0.1

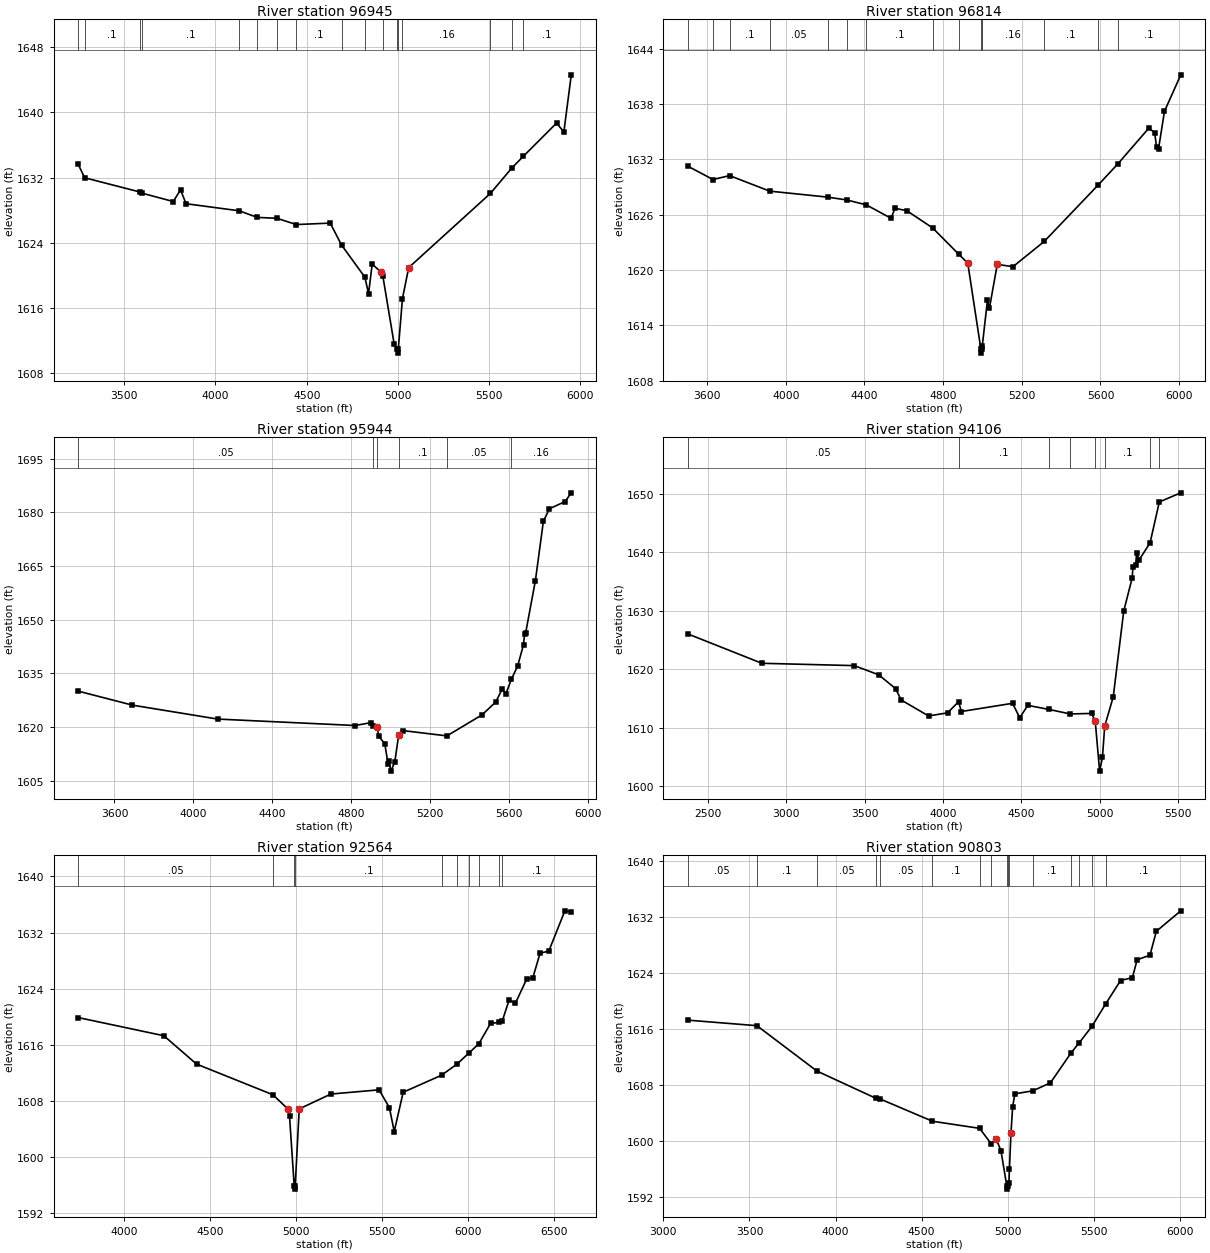
Type RM Length L Ch R = 1 ,96945   ,131,131,131
BEGIN DESCRIPTION:
NORTH GRAPE CREEK 129.0
END DESCRIPTION:
XS GIS Cut Line= 2
      2823179.28     10095184.44      2823220.95     10092483.07
#Sta/Elev= 30
  3247.9 1633.62  3283.3 1631.97  3584.7 1630.23  3595.2 1630.09  3768.7 1629.05
  3808.7 1630.49  3838.7 1628.78  4130.5 1627.91  4228.8  1627.1  4336.9 1626.99
  4442.8 1626.22  4628.8  1626.4  4690.9  1623.7  4818.5 1619.76  4838.8 1617.74
  4858.8 1621.35  4908.8 1620.36  4916.8 1619.94  4978.8 1611.58  4995.8 1610.92
  4998.6 1610.42  5001.8 1610.92  5024.6 1617.13  5058.8 1620.93  5506.5 1630.05
  5624.6 1633.19  5686.1 1634.59  5868.9 1638.69  5908.9  1637.6  5949.6 1644.62
#Mann= 17 ,-1 , 0
  3247.9     .05       0  3283.3      .1       0  3584.7     .05       0
  3595.2      .1       0  4130.5     .05       0  4228.8      .1       0
  4336.9     .05       0  4442.8      .1       0  4690.9     .05       0
  4818.5     .16       0  4916.8      .1       0  4995.8     .07       0
  5001.8      .1       0  5024.6     .16       0  5506.5      .1       0
  5624.6     .05       0  5686.1      .1       0
Bank Sta=4908.8,5058.8
XS Rating Curve= 0 ,0
Exp/Cntr=0.3,0.1

Type RM Length L Ch R = 1 ,96814   ,870,870,870
BEGIN DESCRIPTION:
Mapping XS 7a00c406
END DESCRIPTION:
XS GIS Cut Line= 2
       2823276.5     10095017.79      2823321.64      10092510.9
#Sta/Elev= 30
    3501 1631.26  3629.7 1629.81  3714.2 1630.23    3918 1628.55  4212.9  1627.9
  4311.1 1627.59  4409.4 1627.06  4535.2 1625.61  4555.2 1626.69  4615.2 1626.43
  4746.2 1624.57  4880.6 1621.69  4925.3 1620.74  4991.5  1611.5  4994.2    1611
  4997.5  1611.5  4999.1  1611.8  5025.3 1616.71  5035.3 1615.87  5075.3 1620.61
  5155.3 1620.37    5314  1623.1  5588.7 1629.22    5687 1631.47  5845.4 1635.36
  5875.4  1634.9  5885.4 1633.32  5895.4 1633.15  5925.5  1637.2  6008.3 1641.15
#Mann= 15 ,-1 , 0
    3501      .1       0  3629.7     .05       0  3714.2      .1       0
    3918     .05       0  4212.9      .1       0  4311.1     .05       0
  4409.4      .1       0  4746.2     .05       0  4880.6      .1       0
  4991.5     .07       0  4997.5      .1       0  4999.1     .16       0
    5314      .1       0  5588.7     .05       0    5687      .1       0
Bank Sta=4925.3,5075.3
XS Rating Curve= 0 ,0
Exp/Cntr=0.3,0.1

Type RM Length L Ch R = 1 ,95944   ,1838,1838,1838
BEGIN DESCRIPTION:
NORTH GRAPE CREEK 128.0
END DESCRIPTION:
XS GIS Cut Line= 3
      2823356.33     10094920.63        2824089.     10094156.71
        2824214.     10092722.73
#Sta/Elev= 30
  3416.4 1630.01  3691.4 1626.09  4122.9  1622.2  4819.2  1620.4  4899.5  1621.2
    4912 1620.37  4929.6 1620.06  4939.6 1617.42  4969.7 1615.24  4985.8 1609.77
  4990.9 1610.58  4999.6 1607.65  5019.9 1610.09    5040 1617.76  5060.1 1618.99
  5284.3  1617.5  5461.6 1623.36  5531.9 1626.97  5564.8 1630.67    5582 1629.09
  5610.5 1633.28  5642.3 1636.99  5672.4    1643  5677.6 1645.96  5682.6 1646.12
  5732.6 1660.93  5772.8 1677.43  5802.9 1680.97  5883.2    1683  5914.3 1685.44
#Mann= 6 ,-1 , 0
  3416.4     .05       0    4912      .1       0  4929.6     .07       0
    5040      .1       0  5284.3     .05       0  5610.5     .16       0
Bank Sta=4929.6,5040
XS Rating Curve= 0 ,0
Exp/Cntr=0.3,0.1

Type RM Length L Ch R = 1 ,94106   ,1542,1542,1542
BEGIN DESCRIPTION:
NORTH GRAPE CREEK 127.0
END DESCRIPTION:
XS GIS Cut Line= 3
      2823620.28     10094792.11      2824332.06      10094170.6
      2826328.59     10093250.46
#Sta/Elev= 30
  2372.3 1626.05    2845 1621.02  3434.4 1620.62  3589.3 1619.06  3698.6 1616.67
  3732.5 1614.76  3907.9 1612.02    4029 1612.55    4099 1614.45  4117.1 1612.78
  4443.3 1614.18  4489.2 1611.71  4540.6 1613.83    4676 1613.13  4811.1 1612.36
  4947.4 1612.45  4970.3 1611.12  4998.5 1602.59  5016.2 1604.93    5031 1610.29
  5085.1 1615.28  5152.1 1629.94  5205.4 1635.55  5210.9 1637.42  5228.3 1637.79
  5233.9 1639.87  5251.2 1638.73  5319.8 1641.59  5378.9 1648.59  5515.6 1650.15
#Mann= 8 ,-1 , 0
  2372.3     .05       0    4099      .1       0    4676     .05       0
  4811.1      .1       0  4970.3     .07       0    5031      .1       0
  5319.8     .05       0  5378.9      .1       0
Bank Sta=4970.3,5031
XS Rating Curve= 0 ,0
Exp/Cntr=0.3,0.1

Type RM Length L Ch R = 1 ,92564   ,1761,1761,1761
BEGIN DESCRIPTION:
NORTH GRAPE CREEK 126.0
END DESCRIPTION:
XS GIS Cut Line= 3
      2824091.25      10094511.6      2826151.24     10094362.69
      2826597.96     10093692.61
#Sta/Elev= 30
  3731.4 1619.88  4229.9 1617.29  4420.4 1613.25    4865 1608.88  4951.8 1606.86
  4961.8 1605.81  4988.9 1595.93  4991.6 1595.43  4994.9 1595.93  5018.2 1606.86
  5202.4 1608.98  5483.2 1609.58  5543.3 1607.04  5571.3 1603.64  5623.5 1609.24
  5846.7 1611.66  5935.6 1613.23    6004 1614.77    6064 1616.15    6132 1619.04
  6178.9 1619.19  6201.2 1619.46  6240.2 1622.38  6276.3  1621.9    6342 1625.34
    6378 1625.53  6420.5 1629.06  6471.2 1629.35  6564.7 1635.09  6602.1 1634.94
#Mann= 10 ,-1 , 0
  3731.4     .05       0    4865      .1       0  4988.9     .07       0
  4994.9      .1       0  5846.7     .05       0  5935.6      .1       0
    6004     .05       0    6064      .1       0  6178.9     .05       0
  6201.2      .1       0
Bank Sta=4951.8,5018.2
XS Rating Curve= 0 ,0
Exp/Cntr=0.3,0.1

Type RM Length L Ch R = 1 ,90803   ,1001,1001,1001
BEGIN DESCRIPTION:
NORTH GRAPE CREEK 125.0
END DESCRIPTION:
XS GIS Cut Line= 3
      2824575.25     10095367.84      2826151.24     10094958.33
      2826771.71     10093891.12
#Sta/Elev= 30
  3141.4 1617.25  3543.4 1616.46  3891.7 1609.99  4236.4 1606.08  4257.5 1606.02
  4562.7 1602.83  4836.3 1601.82  4902.5 1599.65  4932.3 1600.31  4960.1 1598.65
  4993.8 1593.65  4996.6 1593.15  4999.8 1593.65  5006.4 1593.99  5009.6 1596.05
  5018.3 1601.11  5028.3 1604.92  5041.1 1606.74  5145.2 1607.17  5247.6 1608.31
  5367.1 1612.57    5413 1613.97  5489.3 1616.39  5569.5 1619.62  5654.8  1622.9
  5723.5 1623.32  5750.8 1625.86  5825.3 1626.51  5862.4 1629.92  6004.2 1632.84
#Mann= 16 ,-1 , 0
  3141.4     .05       0  3543.4      .1       0  3891.7     .05       0
  4236.4      .1       0  4257.5     .05       0  4562.7      .1       0
  4836.3     .05       0  4902.5      .1       0  4993.8     .07       0
  4999.8      .1       0  5009.6     .05       0  5145.2      .1       0
  5367.1     .05       0    5413      .1       0  5489.3     .05       0
  5569.5      .1       0
Bank Sta=4932.3,5018.3
XS Rating Curve= 0 ,0
Exp/Cntr=0.3,0.1

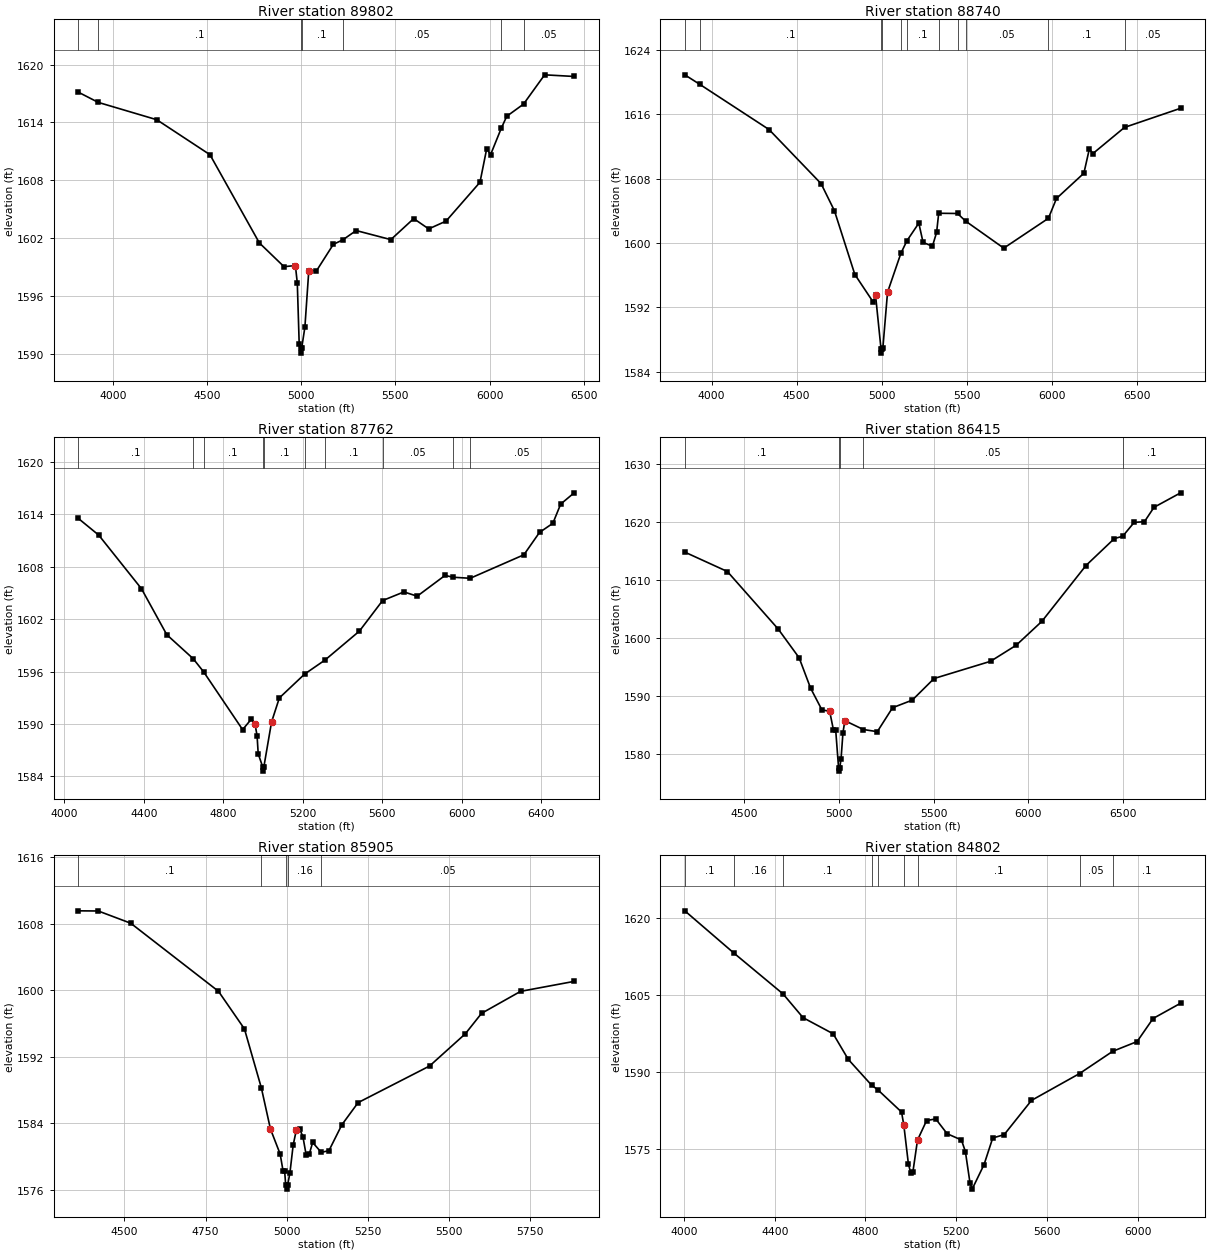
Type RM Length L Ch R = 1 ,89802   ,1062,1062,1062
BEGIN DESCRIPTION:
NORTH GRAPE CREEK 124.0
END DESCRIPTION:
XS GIS Cut Line= 3
      2824935.11      10095578.8      2826436.66     10095764.94
      2827093.88      10094859.7
#Sta/Elev= 30
  3817.4 1617.13  3923.1 1616.07  4233.9 1614.27  4516.1 1610.64  4778.1 1601.49
  4909.1 1599.02  4969.5 1599.14  4979.6 1597.32  4989.7 1591.01  4996.7 1590.55
  4999.5 1590.05  5002.7 1590.55  5019.9 1592.74  5040.6 1598.61  5080.4 1598.56
    5171 1601.34  5220.7  1601.8    5292 1602.77  5476.1 1601.83  5597.5 1604.01
  5677.1 1602.94  5769.1 1603.75  5949.2 1607.78  5984.8 1611.25  6005.6 1610.65
  6061.9 1613.37  6091.4 1614.63  6180.3 1615.89  6292.4 1618.93  6449.1 1618.76
#Mann= 7 ,-1 , 0
  3817.4     .05       0  3923.1      .1       0  4996.7     .07       0
  5002.7      .1       0  5220.7     .05       0  6061.9      .1       0
  6180.3     .05       0
Bank Sta=4969.5,5040.6
XS Rating Curve= 0 ,0
Exp/Cntr=0.3,0.1

Type RM Length L Ch R = 1 ,88740   ,978,978,978
BEGIN DESCRIPTION:
NORTH GRAPE CREEK 123.0
END DESCRIPTION:
XS GIS Cut Line= 3
      2825605.26     10097167.17      2826684.84     10096310.95
      2827230.87     10094871.43
#Sta/Elev= 30
  3842.1 1620.93    3930 1619.75    4338 1614.12  4644.1 1607.39  4722.6 1604.02
  4842.7 1596.09  4950.1 1592.68  4964.5  1593.5  4996.8 1586.81  4999.5 1586.31
  5002.8 1586.81  5007.7 1586.99    5035 1593.88  5113.8 1598.74  5149.2 1600.29
  5219.1 1602.48    5244 1600.09    5299  1599.6  5323.8 1601.33    5336 1603.71
    5447 1603.68    5494 1602.74    5719 1599.37  5981.5 1603.08  6029.2 1605.55
  6190.3 1608.69  6222.4  1611.7  6243.8 1611.14  6429.4 1614.39  6759.6 1616.77
#Mann= 11 ,-1 , 0
  3842.1     .05       0    3930      .1       0  4996.8     .07       0
  5002.8      .1       0  5113.8     .16       0  5149.2      .1       0
    5336     .05       0    5447      .1       0    5494     .05       0
  5981.5      .1       0  6429.4     .05       0
Bank Sta=4964.5,5035
XS Rating Curve= 0 ,0
Exp/Cntr=0.3,0.1

Type RM Length L Ch R = 1 ,87762   ,1347,1347,1347
BEGIN DESCRIPTION:
NORTH GRAPE CREEK 120.0
END DESCRIPTION:
XS GIS Cut Line= 3
      2826821.37     10097129.94      2827342.54     10096745.28
      2827851.32     10094970.72
#Sta/Elev= 30
  4070.6 1613.52  4173.2 1611.61  4388.3 1605.47  4515.6 1600.21  4648.1 1597.47
  4700.9 1595.96  4896.8 1589.35  4941.5 1590.57  4959.2 1589.99  4969.6 1588.66
  4975.3 1586.58  4997.8  1585.1  5000.6  1584.6  5003.8  1585.1  5042.4 1590.22
  5081.7 1592.98    5209 1595.71  5311.7 1597.32  5484.1 1600.62  5600.9 1604.12
  5708.2 1605.11  5774.9 1604.62  5915.1    1607    5955 1606.79  6041.5 1606.67
  6311.6 1609.36  6390.2 1611.92  6457.2 1612.96  6496.6 1615.16  6564.4 1616.45
#Mann= 10 ,-1 , 0
  4070.6      .1       0  4648.1     .05       0  4700.9      .1       0
  4997.8     .07       0  5003.8      .1       0    5209     .05       0
  5311.7      .1       0  5600.9     .05       0    5955      .1       0
  6041.5     .05       0
Bank Sta=4959.2,5042.4
XS Rating Curve= 0 ,0
Exp/Cntr=0.3,0.1

Type RM Length L Ch R = 1 ,86415   ,510,510,510
BEGIN DESCRIPTION:
NORTH GRAPE CREEK 118.0
END DESCRIPTION:
XS GIS Cut Line= 3
      2826808.96     10097291.29      2827913.36     10097427.79
      2829352.83     10096981.06
#Sta/Elev= 30
  4184.8 1614.78  4409.8 1611.43    4678 1601.52  4788.9 1596.55  4849.3 1591.32
  4909.8 1587.53  4950.1 1587.35  4970.2  1584.1  4982.3 1584.03  4997.5 1577.49
  5000.2 1576.99  5003.5 1577.49  5010.5 1579.12  5020.6 1583.64  5030.7  1585.7
  5128.1 1584.17    5202  1583.8  5282.6 1587.93  5386.7 1589.24    5502 1592.97
  5800.4 1595.94  5935.9 1598.71  6071.5 1602.83  6304.7 1612.47  6454.7 1617.12
  6498.5 1617.51  6559.4 1619.91  6613.6 1620.03  6664.1 1622.51  6804.8 1625.01
#Mann= 5 ,-1 , 0
  4184.8      .1       0  4997.5     .07       0  5003.5      .1       0
  5128.1     .05       0  6498.5      .1       0
Bank Sta=4950.1,5030.7
XS Rating Curve= 0 ,0
Exp/Cntr=0.3,0.1

Type RM Length L Ch R = 1 ,85905   ,1103,1103,1103
BEGIN DESCRIPTION:
NORTH GRAPE CREEK 116.0
END DESCRIPTION:
XS GIS Cut Line= 2
      2827057.11     10097899.34       2828583.5      10097849.7
#Sta/Elev= 30
  4358.1 1609.53  4419.5 1609.51  4519.5 1608.04  4789.7 1599.86  4869.7 1595.34
  4921.9 1588.24  4949.8 1583.31  4979.8 1580.29  4988.5 1578.31  4993.5 1578.28
  4996.8 1576.58  4999.5 1576.08  5002.8 1576.58  5009.8 1578.02  5019.8 1581.37
  5029.8 1583.22  5039.8 1583.31  5049.8 1582.39  5059.8  1580.2  5069.8 1580.34
  5079.8 1581.69  5106.4  1580.5  5129.9  1580.7  5169.9 1583.82  5219.9 1586.48
    5440 1590.88  5550.1 1594.75  5600.1 1597.21  5720.2 1599.85  5885.3 1601.05
#Mann= 5 ,-1 , 0
  4358.1      .1       0  4921.9     .16       0  4996.8     .07       0
  5002.8     .16       0  5106.4     .05       0
Bank Sta=4949.8,5029.8
XS Rating Curve= 0 ,0
Exp/Cntr=0.3,0.1

Type RM Length L Ch R = 1 ,84802   ,1264,1264,1264
BEGIN DESCRIPTION:
NORTH GRAPE CREEK 113.0
END DESCRIPTION:
XS GIS Cut Line= 3
       2826287.7     10098941.73      2827876.14      10098780.4
      2828334.03     10098409.14
#Sta/Elev= 30
  4003.3 1621.37  4219.5 1613.17  4436.8 1605.21  4524.8 1600.61  4657.4 1597.48
  4724.2  1592.5  4826.6 1587.51  4854.9 1586.58    4959 1582.27    4969 1579.72
  4989.1 1572.22  4999.2 1570.47  5009.2  1570.7  5029.3 1576.83  5069.5 1580.63
  5109.7 1580.94    5160 1578.06    5223 1576.85  5240.4  1574.6  5260.5 1568.58
  5270.3  1567.3  5322.7 1572.07    5361 1577.24  5411.3 1577.88  5531.9 1584.54
  5743.6 1589.75  5890.1 1594.08  5997.5 1595.97  6067.9 1600.45  6189.4 1603.42
#Mann= 9 ,-1 , 0
  4003.3      .1       0  4219.5     .16       0  4436.8      .1       0
  4826.6     .05       0  4854.9      .1       0    4969     .07       0
  5029.3      .1       0  5743.6     .05       0  5890.1      .1       0
Bank Sta=4969,5029.3
XS Rating Curve= 0 ,0
Exp/Cntr=0.3,0.1

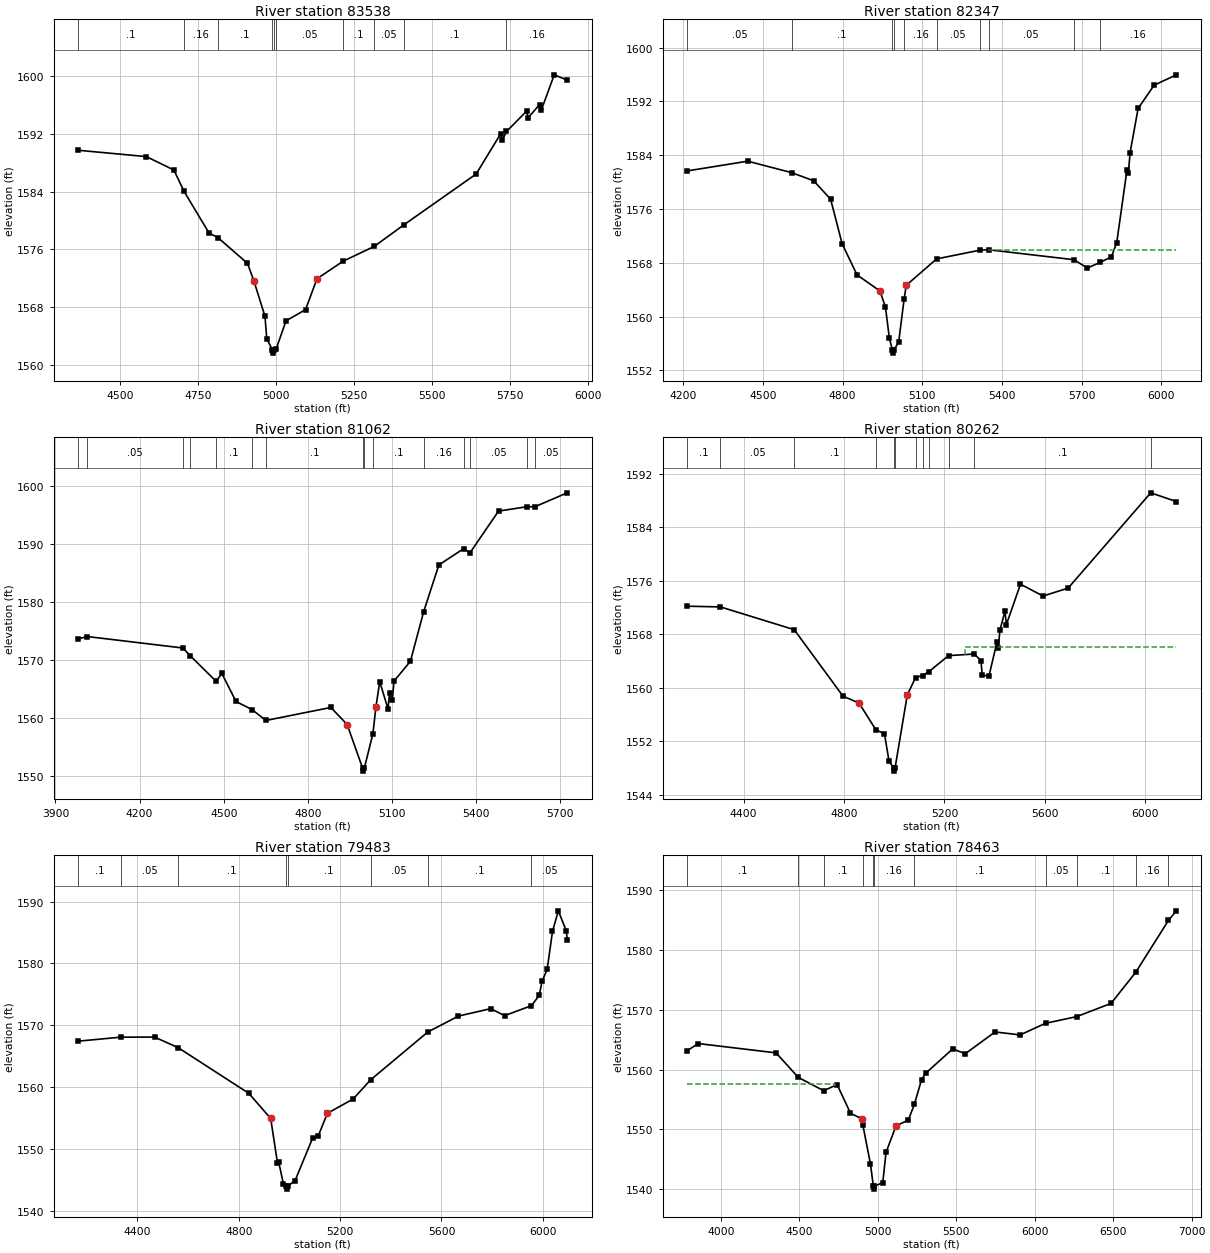
Type RM Length L Ch R = 1 ,83538   ,1191,1191,1191
BEGIN DESCRIPTION:
NORTH GRAPE CREEK 111.0
END DESCRIPTION:
XS GIS Cut Line= 2
      2828161.56     10099971.67      2828533.25     10098447.75
#Sta/Elev= 30
  4365.2 1589.75  4584.3 1588.87  4672.8 1587.01  4704.6  1584.1  4785.1  1578.3
  4814.8 1577.61  4908.6 1574.08  4929.2 1571.64  4964.7 1566.75  4970.4 1563.63
    4988 1562.14  4990.7 1561.64    4994 1562.14  5000.4 1562.19  5032.1 1566.11
  5094.9 1567.67  5131.4 1571.94  5215.4 1574.38  5315.6 1576.44  5409.6  1579.4
  5641.9 1586.46  5720.2 1592.02  5725.3 1591.12  5739.1 1592.35  5803.5 1595.16
  5808.7 1594.27  5845.2 1596.07  5850.4 1595.27  5892.1  1600.2  5933.8 1599.48
#Mann= 10 ,-1 , 0
  4365.2      .1       0  4704.6     .16       0  4814.8      .1       0
    4988     .07       0    4994      .1       0  5000.4     .05       0
  5215.4      .1       0  5315.6     .05       0  5409.6      .1       0
  5739.1     .16       0
Bank Sta=4929.2,5131.4
XS Rating Curve= 0 ,0
Exp/Cntr=0.3,0.1

Type RM Length L Ch R = 1 ,82347   ,1285,1285,1285
BEGIN DESCRIPTION:
NORTH GRAPE CREEK 110.0
END DESCRIPTION:
XS GIS Cut Line= 3
      2828856.44     10100021.37      2829526.58     10099189.91
      2829601.03      10098420.5
#Sta/Elev= 30
  4215.2 1581.67  4443.2 1583.12  4608.9 1581.41  4691.2 1580.21  4755.1 1577.47
  4798.3 1570.86  4854.4 1566.22  4940.7 1563.82  4961.5 1561.43  4975.9 1556.89
  4987.3 1555.08    4990 1554.58  4993.3 1555.08  5011.1 1556.19  5031.9 1562.67
  5039.8 1564.67    5154 1568.59  5316.9 1569.89  5349.7 1569.95  5670.9 1568.47
  5721.3 1567.23  5769.3 1568.07  5811.7  1568.9  5831.8 1571.01  5870.4 1581.83
  5875.4 1581.31  5882.1 1584.39  5912.2 1590.96  5972.5 1594.42  6056.1 1595.96
#Mann= 10 ,-1 , 0
  4215.2     .05       0  4608.9      .1       0  4987.3     .07       0
  4993.3      .1       0  5031.9     .16       0    5154     .05       0
  5316.9      .1       0  5349.7     .05       0  5670.9      .1       0
  5769.3     .16       0
#XS Ineff= 2 , 0
                          5348.8         1569.96
Permanent Ineff=
       F       F
Bank Sta=4940.7,5039.8
XS Rating Curve= 0 ,0
Exp/Cntr=0.3,0.1

Type RM Length L Ch R = 1 ,81062   ,800,800,800
BEGIN DESCRIPTION:
NORTH GRAPE CREEK 109.0
END DESCRIPTION:
XS GIS Cut Line= 3
      2830159.45     10099711.12      2830035.36     10098854.86
      2829588.86     10098098.29
#Sta/Elev= 30
  3980.7 1573.64  4013.9 1574.05  4354.6 1572.07  4379.9 1570.77    4473 1566.31
  4493.4 1567.67  4543.9 1562.82    4601 1561.42  4650.6 1559.54    4882 1561.79
  4940.1 1558.83  4995.2 1551.28  4997.9 1550.78  5001.2 1551.28  5031.9 1557.27
  5042.6 1561.89  5056.2 1566.24  5085.5 1561.57  5091.3 1564.26  5101.1 1563.04
  5106.9 1566.34  5165.5 1569.77  5212.8 1578.36  5266.9 1586.43  5355.1 1589.24
  5377.9 1588.53  5479.6 1595.74    5580 1596.49  5609.5  1596.5  5724.4  1598.9
#Mann= 15 ,-1 , 0
  3980.7      .1       0  4013.9     .05       0  4354.6      .1       0
  4379.9     .05       0    4473      .1       0    4601     .05       0
  4650.6      .1       0  4995.2     .07       0  5001.2      .1       0
  5031.9      .1       0  5212.8     .16       0  5355.1      .1       0
  5377.9     .05       0    5580      .1       0  5609.5     .05       0
Bank Sta=4940.1,5042.6
XS Rating Curve= 0 ,0
Exp/Cntr=0.3,0.1

Type RM Length L Ch R = 1 ,80262   ,779,779,779
BEGIN DESCRIPTION:
NORTH GRAPE CREEK 108.0
END DESCRIPTION:
XS GIS Cut Line= 3
      2830432.44     10099649.09      2830829.55     10098420.53
      2830829.55     10097762.88
#Sta/Elev= 30
  4175.2 1572.21  4308.1  1572.1  4601.7  1568.7    4796 1558.76    4860 1557.73
  4926.3 1553.77  4961.3 1553.12  4979.5 1549.04  4997.6 1548.05  5000.3 1547.55
  5003.6 1548.05  5052.1 1558.91    5085 1561.54  5112.8 1561.84  5138.5 1562.43
  5216.5 1564.82  5318.5 1565.06  5345.6 1564.08  5350.8 1561.89  5377.6 1561.77
  5409.6 1566.87  5414.9 1565.98  5420.9 1568.59  5441.6 1571.47  5446.9 1569.45
  5503.1  1575.5  5593.1 1573.73  5693.1 1574.92  6021.9 1589.16    6124 1587.86
#Mann= 12 ,-1 , 0
  4175.2      .1       0  4308.1     .05       0  4601.7      .1       0
  4926.3     .16       0  4997.6     .07       0  5003.6     .16       0
    5085      .1       0  5112.8     .16       0  5138.5      .1       0
  5216.5     .05       0  5318.5      .1       0  6021.9     .16       0
#XS Ineff= 2 , 0
                         5283.29         1566.13
Permanent Ineff=
       F       F
Bank Sta=4860,5052.1
XS Rating Curve= 0 ,0
Exp/Cntr=0.3,0.1

Type RM Length L Ch R = 1 ,79483   ,1020,1020,1020
BEGIN DESCRIPTION:
NORTH GRAPE CREEK 107.0
END DESCRIPTION:
XS GIS Cut Line= 2
      2831139.78     10099884.85      2831735.35     10098048.51
#Sta/Elev= 30
  4165.6 1567.42  4334.7 1568.07  4467.8 1568.08  4560.8 1566.37  4839.6 1558.98
    4926 1554.91  4952.7 1547.72    4958 1547.79  4976.3 1544.28    4987 1543.97
  4989.7 1543.47    4993 1543.97  5021.9 1544.82  5091.9 1551.77  5112.6 1551.99
  5149.8 1555.75    5251 1558.05  5320.5 1561.17  5545.8  1568.9  5666.7 1571.48
  5794.6 1572.69  5848.8 1571.55  5955.1 1573.17  5985.5 1574.82    5997 1577.14
    6017 1579.04    6038 1585.18    6061 1588.52  6092.9 1585.23  6096.1 1583.84
#Mann= 8 ,-1 , 0
  4165.6      .1       0  4334.7     .05       0  4560.8      .1       0
    4987     .07       0    4993      .1       0  5320.5     .05       0
  5545.8      .1       0  5955.1     .05       0
Bank Sta=4926,5149.8
XS Rating Curve= 0 ,0
Exp/Cntr=0.3,0.1

Type RM Length L Ch R = 1 ,78463   ,575,575,575
BEGIN DESCRIPTION:
NORTH GRAPE CREEK 105.0
END DESCRIPTION:
XS GIS Cut Line= 3
      2831301.12     10100306.74      2832442.77     10099276.78
      2832852.27     10097750.44
#Sta/Elev= 30
  3784.6 1563.15  3855.7 1564.36  4351.2  1562.8  4493.4 1558.69  4654.7 1556.47
  4740.5 1557.49  4825.7 1552.71  4896.7 1551.77  4904.2 1550.76  4952.8 1544.24
  4971.4  1540.5  4974.2    1540  4977.4  1540.5  5031.2 1541.07  5052.2 1546.15
  5115.7 1550.57  5194.1 1551.56  5233.2 1554.21  5278.6 1558.33    5307 1559.44
  5477.4 1563.47  5557.4 1562.66    5747  1566.3    5907 1565.81  6068.8 1567.75
  6267.5 1568.87  6486.4 1571.08  6643.2 1576.27  6852.4 1584.97  6902.5 1586.57
#Mann= 11 ,-1 , 0
  3784.6      .1       0  4493.4     .05       0  4654.7      .1       0
  4904.2     .16       0  4971.4     .07       0  4977.4     .16       0
  5233.2      .1       0  6068.8     .05       0  6267.5      .1       0
  6643.2     .16       0  6852.4      .1       0
#XS Ineff= 2 , 0
         4726.17 1557.57
Permanent Ineff=
       F       F
Bank Sta=4896.7,5115.7
XS Rating Curve= 0 ,0
Exp/Cntr=0.3,0.1