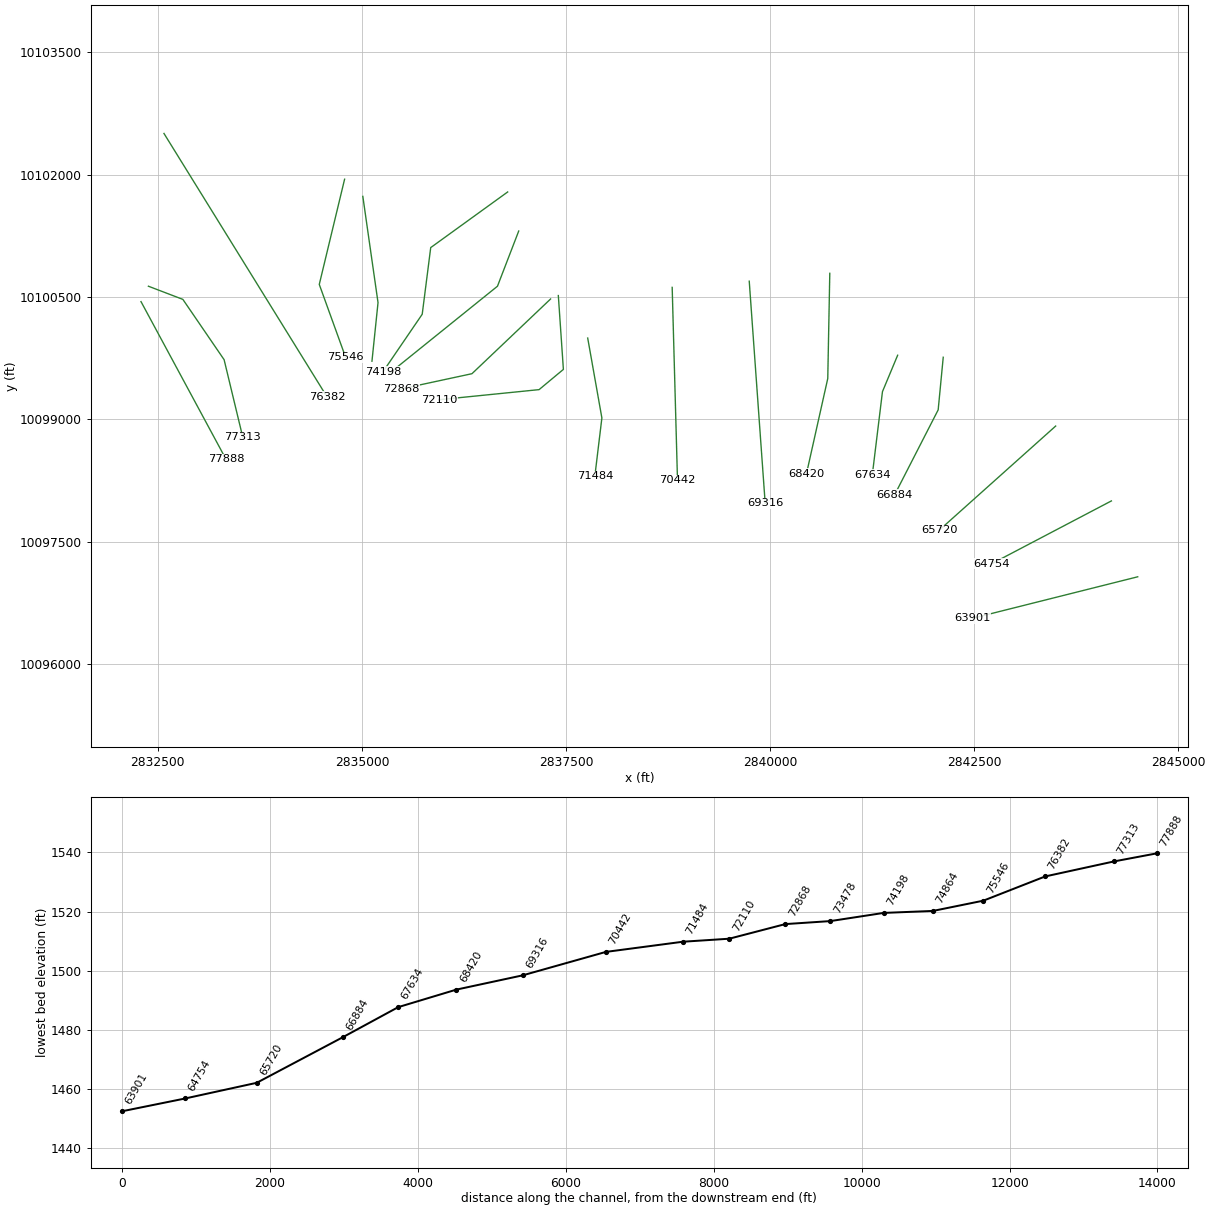
HEC-RAS study NORTH GRAPE CREEK.prj: NORTH GRAPE CREEK Base Level Engineering

--- NORTH GRAPE CREEK.g01 (geometry) --- (continued)

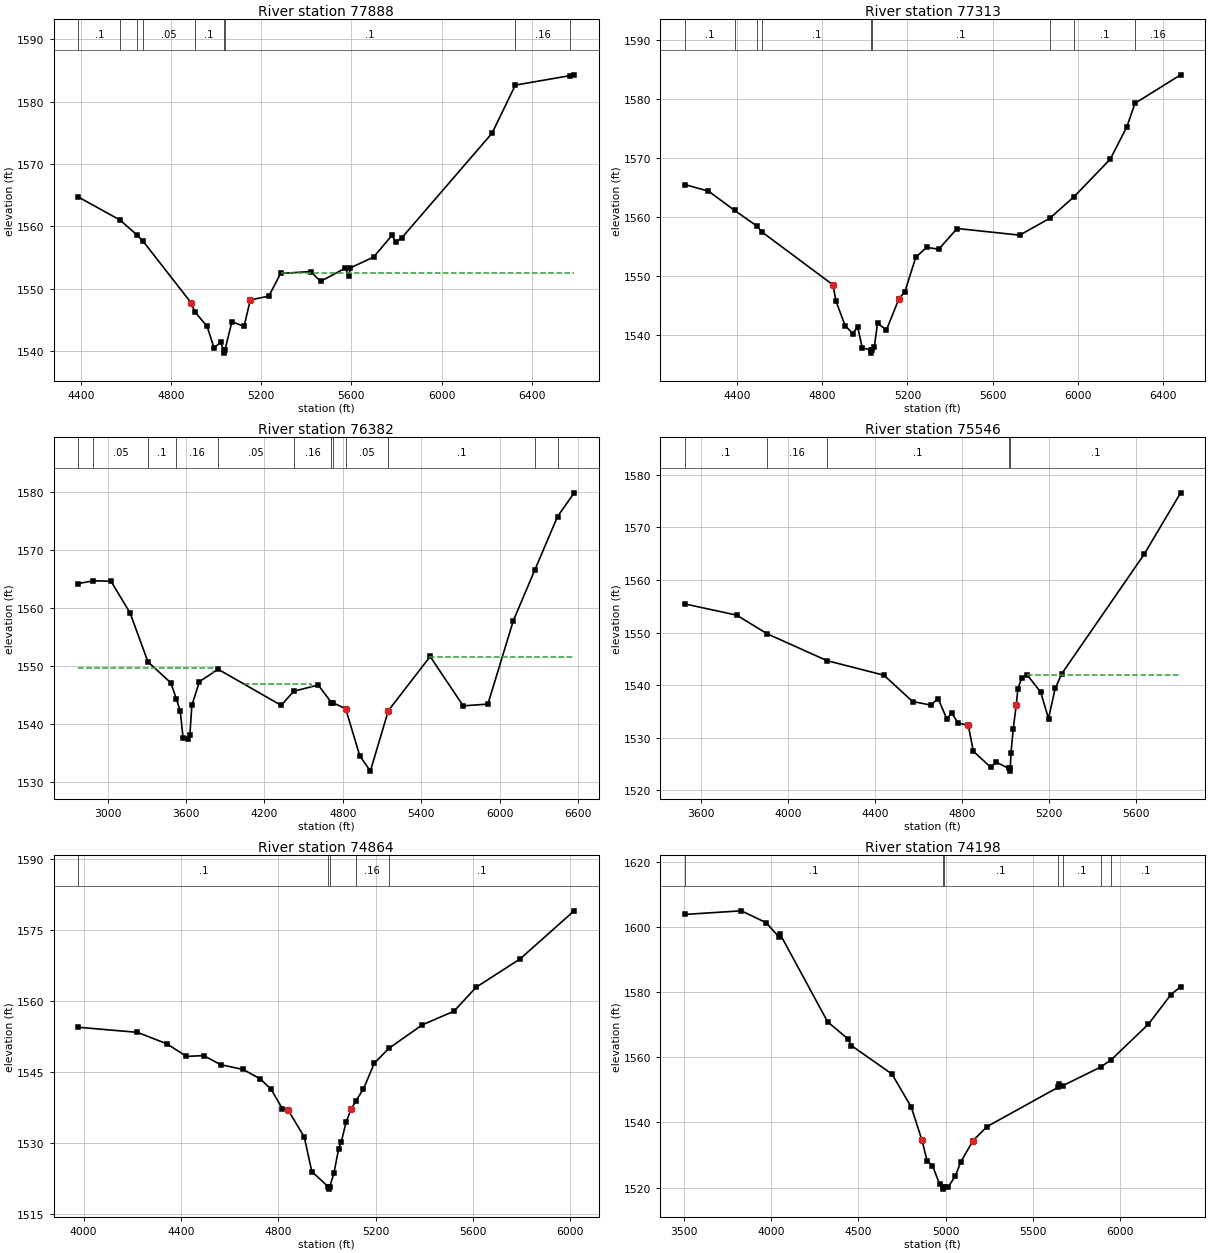
Type RM Length L Ch R = 1 ,77888   ,575,575,575
BEGIN DESCRIPTION:
NORTH GRAPE CREEK 104.0
END DESCRIPTION:
XS GIS Cut Line= 2
      2832293.86     10100443.24      2833335.89     10098508.05
#Sta/Elev= 30
  4389.4  1564.7  4575.3 1560.98  4649.8 1558.58  4676.9 1557.58  4888.6 1547.76
  4906.2 1546.26  4960.2 1543.95  4990.8  1540.5  5020.3 1541.39  5033.2 1540.15
    5036 1539.65  5039.2 1540.15  5070.3 1544.69  5124.1 1543.94  5151.7 1548.19
  5233.6 1548.79  5286.1 1552.43  5419.4 1552.74  5463.2 1551.16  5572.7 1553.28
    5589    1552  5594.6 1553.31  5698.5 1555.07  5780.4 1558.57  5796.6  1557.4
  5824.2 1558.19  6223.4 1574.94  6326.5 1582.65  6570.2 1584.18  6587.3  1584.3
#Mann= 9 ,-1 , 0
  4389.4      .1       0  4575.3     .05       0  4649.8      .1       0
  4676.9     .05       0  4906.2      .1       0  5033.2     .07       0
  5039.2      .1       0  6326.5     .16       0  6570.2      .1       0
#XS Ineff= 2 , 0
                         5287.68         1552.48
Permanent Ineff=
       F       F
Bank Sta=4888.6,5151.7
XS Rating Curve= 0 ,0
Exp/Cntr=0.3,0.1

Type RM Length L Ch R = 1 ,77313   ,931,931,931
BEGIN DESCRIPTION:
NORTH GRAPE CREEK 103.0
END DESCRIPTION:
XS GIS Cut Line= 4
       2832384.8     10100632.06      2832806.72     10100470.58
      2833311.93       10099731.        2833541.     10098778.28
#Sta/Elev= 30
    4155 1565.47    4266 1564.36  4389.2 1561.08  4491.6 1558.49  4519.1 1557.39
  4850.2  1548.5  4865.1  1545.7  4907.1 1541.61    4943 1540.25  4966.3 1541.35
  4987.7 1537.88  5026.7 1537.44  5029.4 1536.94  5032.7 1537.44  5044.6 1537.98
  5059.5 1541.98  5101.5 1540.86    5160 1546.13  5188.2 1547.36    5239 1553.15
  5289.8 1554.84  5346.7 1554.53  5433.4 1558.03    5727 1556.91  5868.7 1559.77
  5982.2 1563.42  6151.7 1569.75  6229.9 1575.24    6268 1579.22  6482.3 1584.04
#Mann= 9 ,-1 , 0
    4155      .1       0  4389.2     .16       0  4491.6     .05       0
  4519.1      .1       0  5026.7     .07       0  5032.7      .1       0
  5868.7     .05       0  5982.2      .1       0    6268     .16       0
Bank Sta=4850.2,5160
XS Rating Curve= 0 ,0
Exp/Cntr=0.3,0.1

Type RM Length L Ch R = 1 ,76382   ,836,836,836
BEGIN DESCRIPTION:
NORTH GRAPE CREEK 102.0
END DESCRIPTION:
XS GIS Cut Line= 2
      2832575.18     10102505.93      2834571.11     10099277.72
#Sta/Elev= 30
    2775 1564.16  2889.6 1564.62  3024.7 1564.57  3171.3 1559.08  3307.9 1550.68
    3483 1547.06  3525.2 1544.31  3555.4 1542.17  3577.1  1537.5  3613.3 1537.42
  3628.7 1538.07  3644.1 1543.21    3702 1547.27  3845.2  1549.4  4327.3 1543.19
  4424.1 1545.61    4611 1546.69  4712.9 1543.66  4727.2  1543.6  4821.4  1542.6
  4929.1 1534.52  5010.3 1531.86  5147.7 1542.26    5468  1551.6  5720.9  1543.1
  5910.1  1543.4  6105.1 1557.79  6269.3  1566.5  6443.1 1575.69  6570.4 1579.78
#Mann= 12 ,-1 , 0
    2775      .1       0  2889.6     .05       0  3307.9      .1       0
  3525.2     .16       0  3845.2     .05       0  4424.1     .16       0
  4712.9     .05       0  4727.2      .1       0  4821.4     .05       0
  5147.7      .1       0  6269.3     .16       0  6443.1      .1       0
#XS Ineff= 3 ,-1
    2775  3806.9 1549.62    4046 4554.48 1546.94 5462.47  6570.4 1551.54
Permanent Ineff=
       F       F       F
Bank Sta=4821.4,5147.7
XS Rating Curve= 0 ,0
Exp/Cntr=0.3,0.1

Type RM Length L Ch R = 1 ,75546   ,682,682,682
BEGIN DESCRIPTION:
NORTH GRAPE CREEK 100.0
END DESCRIPTION:
XS GIS Cut Line= 3
      2834788.13     10101944.78      2834477.89     10100654.21
      2834800.54     10099760.72
#Sta/Elev= 30
  3525.7 1555.44    3764 1553.31  3903.3 1549.78  4178.9 1544.66  4440.6 1541.89
  4571.6  1536.9  4655.5 1536.22    4689 1537.46  4730.1 1533.51  4750.7 1534.78
  4781.4 1532.79  4827.8 1532.38  4850.7 1527.45  4930.8 1524.41  4956.2 1525.37
  5014.5 1524.17  5017.2 1523.67  5020.5 1524.17  5023.7 1527.07  5034.3 1531.73
  5048.2  1536.3  5055.6  1539.3  5073.5 1541.41  5098.1 1541.96  5160.2 1538.68
  5196.2 1533.66  5226.9 1539.39  5257.6 1542.21    5635 1564.84    5803 1576.55
#Mann= 5 ,-1 , 0
  3525.7      .1       0  3903.3     .16       0  4178.9      .1       0
  5014.5     .07       0  5020.5      .1       0
#XS Ineff= 2 , 0
                         5099.58         1541.89
Permanent Ineff=
       F       F
Bank Sta=4827.8,5048.2
XS Rating Curve= 0 ,0
Exp/Cntr=0.3,0.1

Type RM Length L Ch R = 1 ,74864   ,666,666,666
BEGIN DESCRIPTION:
NORTH GRAPE CREEK 99.0
END DESCRIPTION:
XS GIS Cut Line= 3
      2835011.49     10101733.87      2835197.63     10100430.84
      2835123.33     10099712.53
#Sta/Elev= 30
  3978.3 1554.46  4220.9 1553.39  4341.4 1550.98  4422.9  1548.3  4493.6 1548.46
  4564.3 1546.53  4655.2 1545.54    4726 1543.54  4770.8 1541.34  4816.9 1537.24
  4841.5 1536.87  4907.1 1531.24  4938.1 1523.93  5005.8  1520.7  5008.5  1520.2
  5011.8  1520.7    5029 1523.57  5048.6 1528.76  5059.3 1530.18  5079.5  1534.5
  5099.7 1537.07  5118.1 1538.79  5150.2 1541.37    5195 1546.86  5255.3 1550.01
  5392.2 1554.97  5522.9 1557.87  5613.4 1562.92  5794.3 1568.93  6016.7 1579.11
#Mann= 5 ,-1 , 0
  3978.3      .1       0  5005.8     .07       0  5011.8      .1       0
  5118.1     .16       0  5255.3      .1       0
Bank Sta=4841.5,5099.7
XS Rating Curve= 0 ,0
Exp/Cntr=0.3,0.1

Type RM Length L Ch R = 1 ,74198   ,720,720,720
BEGIN DESCRIPTION:
Mapping XS cbb95eee
END DESCRIPTION:
XS GIS Cut Line= 4
      2836785.92     10101788.31      2835843.18       10101106.
      2835739.02     10100288.29      2835259.87      10099585.2
#Sta/Elev= 30
  3507.1 1603.86  3830.8 1604.97  3973.1 1601.32  4046.6  1596.9  4052.7 1597.82
    4325 1570.88  4440.2  1565.7  4461.1 1563.59  4693.3 1554.86  4804.2 1544.67
  4864.7 1534.58  4894.9 1528.14  4925.2 1526.77  4965.5 1521.07  4984.9 1520.03
  4987.7 1519.53  4990.9 1520.03  5015.9 1520.24  5056.2 1523.58  5086.4 1527.78
    5157  1534.4  5237.7 1538.73  5644.9 1550.81  5649.5  1551.8  5672.4 1551.31
  5888.6 1557.03  5949.4 1559.28  6161.1 1570.14  6289.8  1579.2    6346 1581.71
#Mann= 7 ,-1 , 0
  3507.1      .1       0  4984.9     .07       0  4990.9      .1       0
  5644.9     .16       0  5672.4      .1       0  5888.6     .16       0
  5949.4      .1       0
Bank Sta=4864.7,5157
XS Rating Curve= 0 ,0
Exp/Cntr=0.3,0.1

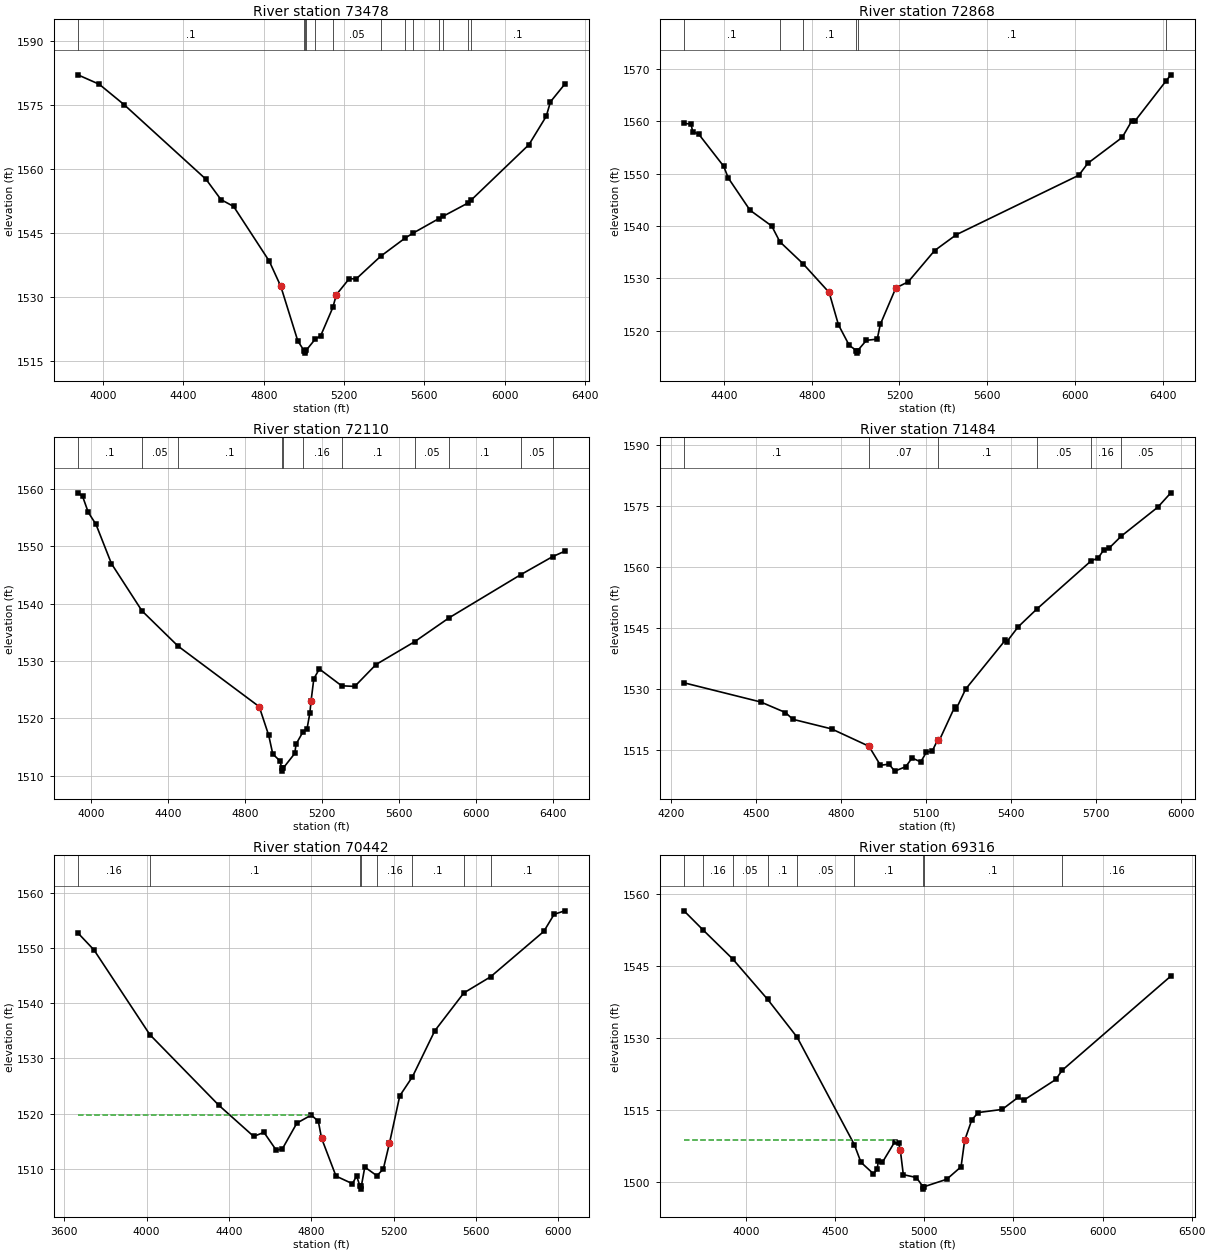
Type RM Length L Ch R = 1 ,73478   ,610,610,610
BEGIN DESCRIPTION:
NORTH GRAPE CREEK 97.0
END DESCRIPTION:
XS GIS Cut Line= 3
       2836921.3     10101309.11      2836660.89     10100632.04
      2835337.94     10099564.31
#Sta/Elev= 30
  3874.1 1581.96  3980.6 1579.75  4104.9 1574.95  4513.1 1557.46    4587 1552.73
  4650.1 1551.13  4827.6 1538.32  4885.2  1532.4  4969.9 1519.62  5002.1 1517.27
  5004.9 1516.77  5008.1 1517.27  5012.9 1517.51  5057.4 1520.09  5083.5  1520.8
  5144.4 1527.46  5161.9 1530.46  5225.8 1534.19    5261 1534.17  5381.9 1539.43
  5505.6 1543.76  5546.1 1544.93  5673.4  1548.3  5695.1 1548.86  5817.7 1551.93
  5832.7 1552.58  6121.4  1565.6  6207.7 1572.25  6228.6 1575.64  6299.6 1579.75
#Mann= 13 ,-1 , 0
  3874.1      .1       0  5002.1     .07       0  5008.1      .1       0
  5012.9     .05       0  5057.4      .1       0  5144.4     .05       0
  5381.9      .1       0  5505.6     .05       0  5546.1      .1       0
  5673.4     .05       0  5695.1      .1       0  5817.7     .16       0
  5832.7      .1       0
Bank Sta=4885.2,5161.9
XS Rating Curve= 0 ,0
Exp/Cntr=0.3,0.1

Type RM Length L Ch R = 1 ,72868   ,758,758,758
BEGIN DESCRIPTION:
NORTH GRAPE CREEK 96.0
END DESCRIPTION:
XS GIS Cut Line= 3
      2837311.94      10100475.8      2836348.39     10099559.13
      2835478.61     10099371.63
#Sta/Elev= 30
  4217.5 1559.59  4249.9 1559.41  4256.8 1558.02  4285.1 1557.49  4398.3  1551.4
  4419.4 1549.15  4518.5 1543.01  4617.6 1539.99  4654.6 1536.99  4760.5 1532.79
  4879.3 1527.32  4921.7 1521.15  4971.1 1517.22  5003.7 1516.25  5006.4 1515.75
  5009.7 1516.25  5049.1 1518.19  5098.5 1518.42  5112.7 1521.25  5183.4 1528.18
  5240.1 1529.36  5360.2 1535.31  5459.3 1538.34  6017.9 1549.68  6058.8 1551.96
  6215.5 1556.89  6259.7 1560.08  6273.7 1560.02  6414.1 1567.59  6437.2 1568.83
#Mann= 6 ,-1 , 0
  4217.5      .1       0  4654.6     .05       0  4760.5      .1       0
  5003.7     .07       0  5009.7      .1       0  6414.1     .05       0
Bank Sta=4879.3,5183.4
XS Rating Curve= 0 ,0
Exp/Cntr=0.3,0.1

Type RM Length L Ch R = 1 ,72110   ,626,626,626
BEGIN DESCRIPTION:
NORTH GRAPE CREEK 95.0
END DESCRIPTION:
XS GIS Cut Line= 4
      2837406.49     10100517.72      2837468.54     10099611.83
      2837170.71     10099363.64      2835942.86     10099239.62
#Sta/Elev= 30
  3931.6  1559.3  3955.6 1558.73  3985.7 1555.89  4025.8  1553.8    4106 1546.96
  4264.5 1538.74  4452.2 1532.59    4874 1522.04  4923.4 1517.03  4944.3  1513.8
  4980.7 1512.62    4992 1511.31  4994.8 1510.81    4998 1511.31  5058.8  1513.9
  5065.3 1515.51    5100 1517.57  5122.6 1518.23  5136.9 1520.88  5143.4 1523.04
  5157.7  1526.9  5186.4 1528.61  5302.1 1525.68  5370.3 1525.57  5480.8 1529.38
  5682.1 1533.37  5861.4 1537.54    6232 1545.02  6398.4 1548.18  6461.4 1549.12
#Mann= 11 ,-1 , 0
  3931.6      .1       0  4264.5     .05       0  4452.2      .1       0
    4992     .07       0    4998      .1       0    5100     .16       0
  5302.1      .1       0  5682.1     .05       0  5861.4      .1       0
    6232     .05       0  6398.4      .1       0
#XS Ineff= 2 , 0
                         5187.05         1528.59
Permanent Ineff=
       F       F
Bank Sta=4874,5143.4
XS Rating Curve= 0 ,0
Exp/Cntr=0.3,0.1

Type RM Length L Ch R = 1 ,71484   ,1042,1042,1042
BEGIN DESCRIPTION:
NORTH GRAPE CREEK 94.0
END DESCRIPTION:
XS GIS Cut Line= 3
      2837766.37     10099996.47      2837940.09     10099016.18
      2837853.48     10098298.55
#Sta/Elev= 30
  4245.3 1531.53  4516.2 1526.81  4603.5 1524.21  4629.4 1522.55    4766 1520.19
  4898.1 1515.92  4938.7 1511.23  4968.9  1511.5  4989.2 1509.79    5028 1510.88
  5050.4 1513.03  5080.9 1512.05  5101.2 1514.49  5121.5 1514.72  5141.1 1517.53
  5146.2 1517.31  5200.3 1525.49  5205.3 1524.99  5239.6 1529.99  5379.5 1542.03
  5384.5 1541.62  5424.6 1545.29  5490.1 1549.65  5682.8 1561.58  5706.7 1562.21
  5726.8 1564.23    5747 1564.76  5788.8 1567.64  5918.2 1574.79  5963.7  1578.3
#Mann= 6 ,-1 , 0
  4245.3      .1       0  4898.1     .07       0  5141.1      .1       0
  5490.1     .05       0  5682.8     .16       0  5788.8     .05       0
Bank Sta=4898.1,5141.1
XS Rating Curve= 0 ,0
Exp/Cntr=0.3,0.1

Type RM Length L Ch R = 1 ,70442   ,1126,1126,1126
BEGIN DESCRIPTION:
NORTH GRAPE CREEK 93.0
END DESCRIPTION:
XS GIS Cut Line= 2
      2838801.33     10100617.89      2838866.44     10098252.38
#Sta/Elev= 30
  3665.6  1552.7    3744 1549.62  4015.4  1534.3    4350 1521.55  4520.1 1515.89
  4570.1 1516.62  4630.1 1513.38  4660.1 1513.67  4730.2  1518.3  4800.2 1519.75
  4834.4 1518.62  4850.2 1515.55  4920.2 1508.71  5000.3 1507.33  5020.3 1508.74
  5037.3 1506.85    5040 1506.35  5043.3 1506.85  5060.3 1510.34    5119 1508.77
  5150.3 1509.99  5180.3 1514.68  5230.3 1523.23  5292.1 1526.69  5400.4 1534.99
  5541.8 1541.85  5671.6 1544.76  5930.6 1552.98  5980.6 1556.07    6032  1556.7
#Mann= 8 ,-1 , 0
  3665.6     .16       0  4015.4      .1       0  5037.3     .07       0
  5043.3      .1       0    5119     .16       0  5292.1      .1       0
  5541.8     .05       0  5671.6      .1       0
#XS Ineff= 2 , 0
            4804 1519.78
Permanent Ineff=
       F       F
Bank Sta=4850.2,5180.3
XS Rating Curve= 0 ,0
Exp/Cntr=0.3,0.1

Type RM Length L Ch R = 1 ,69316   ,896,896,896
BEGIN DESCRIPTION:
NORTH GRAPE CREEK 91.0
END DESCRIPTION:
XS GIS Cut Line= 2
      2839745.34     10100693.79      2839940.65     10097970.28
#Sta/Elev= 30
  3652.6 1556.45  3757.9 1552.52  3925.5 1546.42  4122.1 1537.97    4287  1530.1
  4607.7 1507.72  4645.2 1504.01  4715.4 1501.61  4735.4 1502.52  4742.6  1504.2
  4765.5 1504.02  4835.7 1508.34  4855.7 1508.04  4865.8 1506.58  4882.7 1501.44
    4956 1500.84  4993.1 1498.92  4995.8 1498.42  4999.1 1498.92  5126.4 1500.48
  5206.6 1503.08  5226.7 1508.57  5266.8 1512.86  5302.9 1514.39  5437.2 1515.04
  5527.5 1517.58  5557.5 1516.94    5738 1521.28  5772.5 1523.16  6383.1 1542.84
#Mann= 9 ,-1 , 0
  3652.6     .05       0  3757.9     .16       0  3925.5     .05       0
  4122.1      .1       0    4287     .05       0  4607.7      .1       0
  4993.1     .07       0  4999.1      .1       0  5772.5     .16       0
#XS Ineff= 2 , 0
         4843.83 1508.63
Permanent Ineff=
       F       F
Bank Sta=4865.8,5226.7
XS Rating Curve= 0 ,0
Exp/Cntr=0.3,0.1

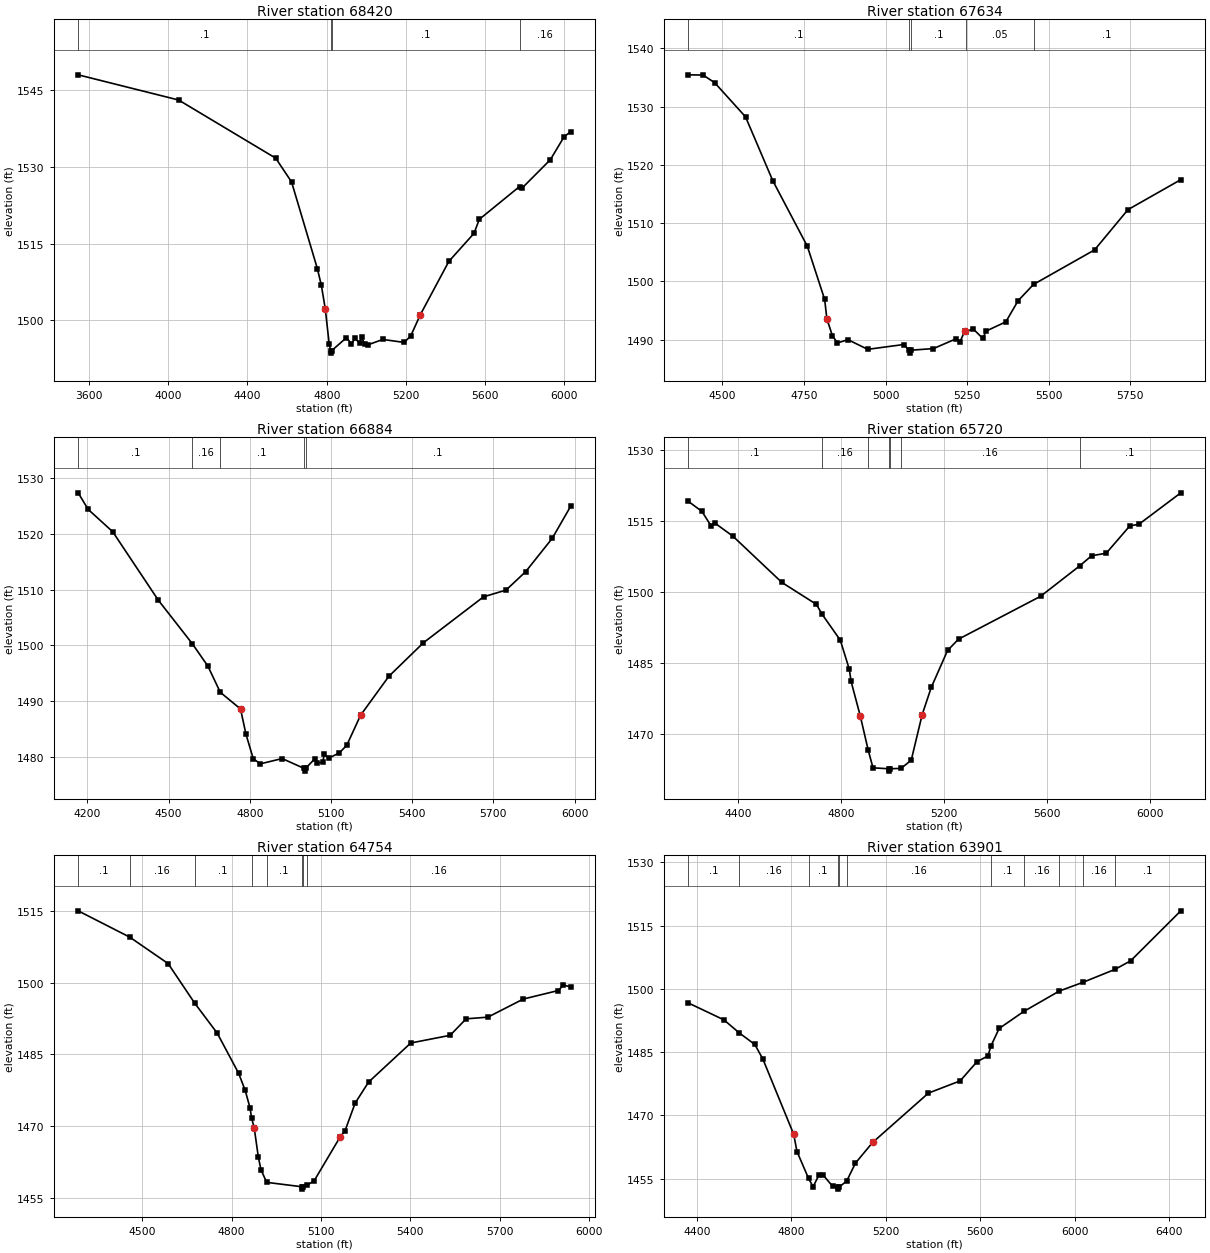
Type RM Length L Ch R = 1 ,68420   ,786,786,786
BEGIN DESCRIPTION:
Mapping XS 20639b81
END DESCRIPTION:
XS GIS Cut Line= 3
      2840732.19     10100790.71      2840707.37     10099500.14
      2840446.78      10098333.7
#Sta/Elev= 30
  3545.3 1547.96  4052.4 1543.04  4542.5 1531.68  4622.5 1527.04  4752.5 1510.13
  4772.5 1506.92  4792.5  1502.3  4812.5 1495.39  4819.5  1494.1  4822.3  1493.6
  4825.5  1494.1  4899.5 1496.62  4924.6 1495.43  4942.9 1496.46  4965.6 1495.56
  4975.9 1496.77  4991.4 1495.31  5006.6 1495.21  5083.4 1496.27  5191.1 1495.69
  5223.9 1496.95    5273 1501.14  5416.5 1511.52  5543.3 1516.99  5570.2 1519.73
  5773.3 1526.14  5785.4 1525.81  5928.8 1531.38    5998 1535.85  6031.3 1536.86
#Mann= 4 ,-1 , 0
  3545.3      .1       0  4819.5     .07       0  4825.5      .1       0
  5773.3     .16       0
Bank Sta=4792.5,5273
XS Rating Curve= 0 ,0
Exp/Cntr=0.3,0.1

Type RM Length L Ch R = 1 ,67634   ,750,750,750
BEGIN DESCRIPTION:
NORTH GRAPE CREEK 90.0
END DESCRIPTION:
XS GIS Cut Line= 3
      2841563.61     10099785.56      2841377.47     10099338.82
      2841253.42     10098321.63
#Sta/Elev= 30
  4395.9 1535.44  4441.2  1535.4  4476.7 1534.09  4571.2 1528.23  4654.4  1517.3
  4760.5 1506.02  4813.6 1496.89  4820.4 1493.56  4837.5 1490.64  4852.9 1489.43
    4885 1489.99  4945.4 1488.33  5056.3 1489.16  5071.8 1488.18  5074.5 1487.68
  5077.8 1488.18  5146.9 1488.46  5217.4 1490.17  5227.5 1489.53    5243 1491.49
  5247.4 1491.34  5267.8 1491.88    5298  1490.2  5308.1 1491.46  5368.6 1493.05
  5406.2 1496.67  5453.4 1499.47  5640.6  1505.4  5742.7  1512.3  5904.6 1517.45
#Mann= 5 ,-1 , 0
  4395.9      .1       0  5071.8     .07       0  5077.8      .1       0
  5247.4     .05       0  5453.4      .1       0
Bank Sta=4820.4,5243
XS Rating Curve= 0 ,0
Exp/Cntr=0.3,0.1

Type RM Length L Ch R = 1 ,66884   ,1164,1164,1164
BEGIN DESCRIPTION:
NORTH GRAPE CREEK 88.0
END DESCRIPTION:
XS GIS Cut Line= 3
      2842122.04     10099760.78      2842059.99     10099115.46
      2841526.39     10098073.09
#Sta/Elev= 30
    4166  1527.3  4203.2 1524.32  4293.6 1520.34  4461.9  1508.1  4587.8 1500.29
  4645.2 1496.29    4691 1491.61  4765.8 1488.62  4785.9  1484.1  4812.7 1479.74
  4838.7  1478.8  4919.7 1479.75  4999.9    1478  5002.6  1477.5  5005.9    1478
  5040.9 1479.73  5047.3 1478.91  5069.5 1479.12  5075.1 1480.52  5091.7 1479.83
  5130.5 1480.75  5158.3 1482.13  5209.4 1487.51  5313.8 1494.47  5441.4 1500.47
  5663.5 1508.69  5746.7  1509.9  5818.9 1513.18  5917.2 1519.15  5985.3 1524.89
#Mann= 5 ,-1 , 0
    4166      .1       0  4587.8     .16       0    4691      .1       0
  4999.9     .07       0  5005.9      .1       0
Bank Sta=4765.8,5209.4
XS Rating Curve= 0 ,0
Exp/Cntr=0.3,0.1

Type RM Length L Ch R = 1 ,65720   ,966,966,966
BEGIN DESCRIPTION:
NORTH GRAPE CREEK 89.0
END DESCRIPTION:
XS GIS Cut Line= 2
      2843499.47     10098916.91      2842072.91     10097639.21
#Sta/Elev= 30
  4205.8 1519.11  4258.6 1516.99  4293.7 1513.98  4307.9 1514.56  4378.9 1511.76
  4569.6 1501.97  4704.1 1497.33  4725.2 1495.31  4796.9 1489.76    4832 1483.59
  4838.7 1481.07  4874.6 1473.73  4905.3 1466.54  4923.9 1462.79  4984.5 1462.59
  4987.2 1462.09  4990.5 1462.59    5033 1462.67  5072.7  1464.4  5115.3 1474.05
  5150.5 1479.78    5214  1487.6  5256.6 1489.98  5575.9 1499.05  5727.8 1505.47
    5774 1507.61  5830.8 1508.14  5922.8 1513.93  5957.9 1514.26  6120.9 1520.91
#Mann= 7 ,-1 , 0
  4205.8      .1       0  4725.2     .16       0  4905.3      .1       0
  4984.5     .07       0  4990.5      .1       0    5033     .16       0
  5727.8      .1       0
Bank Sta=4874.6,5115.3
XS Rating Curve= 0 ,0
Exp/Cntr=0.3,0.1

Type RM Length L Ch R = 1 ,64754   ,853,853,853
BEGIN DESCRIPTION:
NORTH GRAPE CREEK 83.0
END DESCRIPTION:
XS GIS Cut Line= 2
      2844182.01     10097998.63      2842717.64     10097229.22
#Sta/Elev= 30
  4284.6 1515.06  4457.9 1509.55  4586.7 1504.02  4675.6 1495.77  4751.7 1489.45
  4823.5 1481.06  4845.6 1477.48    4862 1473.77    4867 1471.71    4876 1469.61
  4889.7 1463.54  4898.6 1460.86  4917.8 1458.22  5035.3  1457.3  5038.1  1456.8
  5041.3  1457.3    5053 1457.63  5076.8  1458.5    5165 1467.77    5181 1469.03
  5214.9  1474.8  5260.1 1479.21  5401.8 1487.39  5534.1    1489  5587.7 1492.45
  5660.7  1492.8  5779.7 1496.59  5897.6 1498.38    5914 1499.52  5938.8 1499.14
#Mann= 8 ,-1 , 0
  4284.6      .1       0  4457.9     .16       0  4675.6      .1       0
    4867     .05       0  4917.8      .1       0  5035.3     .07       0
  5041.3      .1       0    5053     .16       0
Bank Sta=4876,5165
XS Rating Curve= 0 ,0
Exp/Cntr=0.3,0.1

Type RM Length L Ch R = 1 ,63901   ,809,809,809
BEGIN DESCRIPTION:
NORTH GRAPE CREEK 82.0
END DESCRIPTION:
XS GIS Cut Line= 2
      2844504.63     10097067.92      2842482.71     10096559.34
#Sta/Elev= 30
  4364.4 1496.66  4515.1 1492.65  4579.5 1489.58    4646  1486.8  4680.1 1483.34
  4810.5  1465.5  4824.5  1461.4  4873.3 1455.04  4892.7 1453.04  4917.3 1455.81
  4933.9 1455.91    4975 1453.16  4996.8 1452.98  4999.5 1452.48  5002.8 1452.98
  5034.7 1454.37  5071.9 1458.65  5144.6 1463.55    5381 1475.27  5515.3 1478.17
  5586.6 1482.72  5632.9 1484.09  5646.1 1486.51  5680.3  1490.6  5784.6 1494.64
  5934.9 1499.48  6034.9 1501.55  6170.4 1504.62  6237.1 1506.66  6449.3 1518.52
#Mann= 11 ,-1 , 0
  4364.4      .1       0  4579.5     .16       0  4873.3      .1       0
  4996.8     .07       0  5002.8      .1       0  5034.7     .16       0
  5646.1      .1       0  5784.6     .16       0  5934.9      .1       0
  6034.9     .16       0  6170.4      .1       0
Bank Sta=4810.5,5144.6
XS Rating Curve= 0 ,0
Exp/Cntr=0.3,0.1