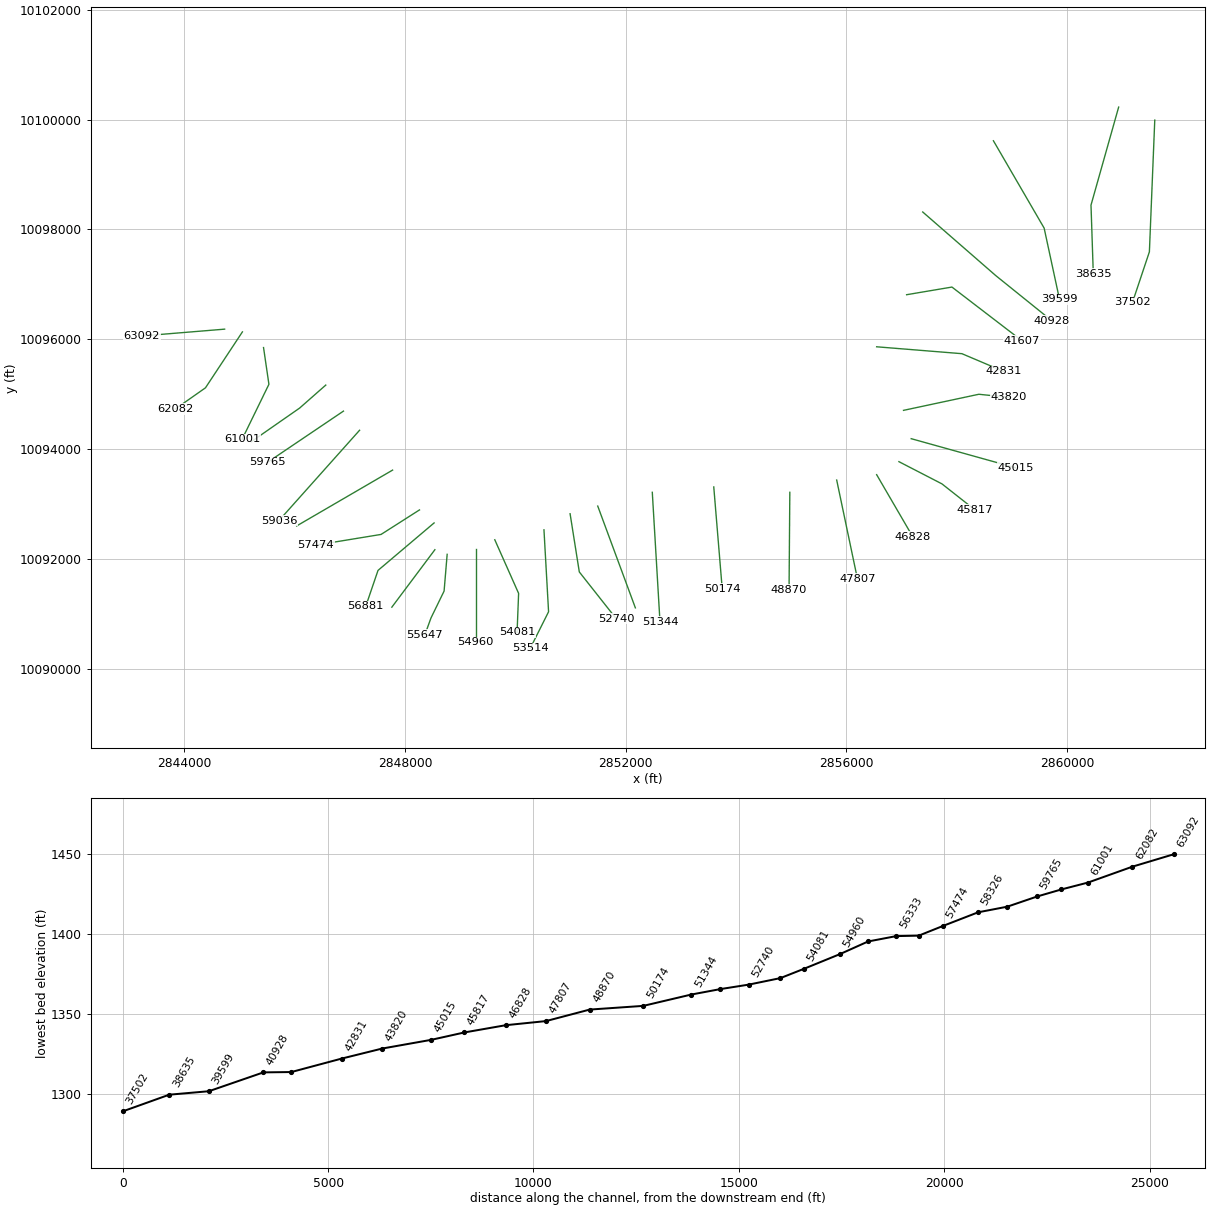
HEC-RAS study NORTH GRAPE CREEK.prj: NORTH GRAPE CREEK Base Level Engineering

--- NORTH GRAPE CREEK.g01 (geometry) --- (continued)

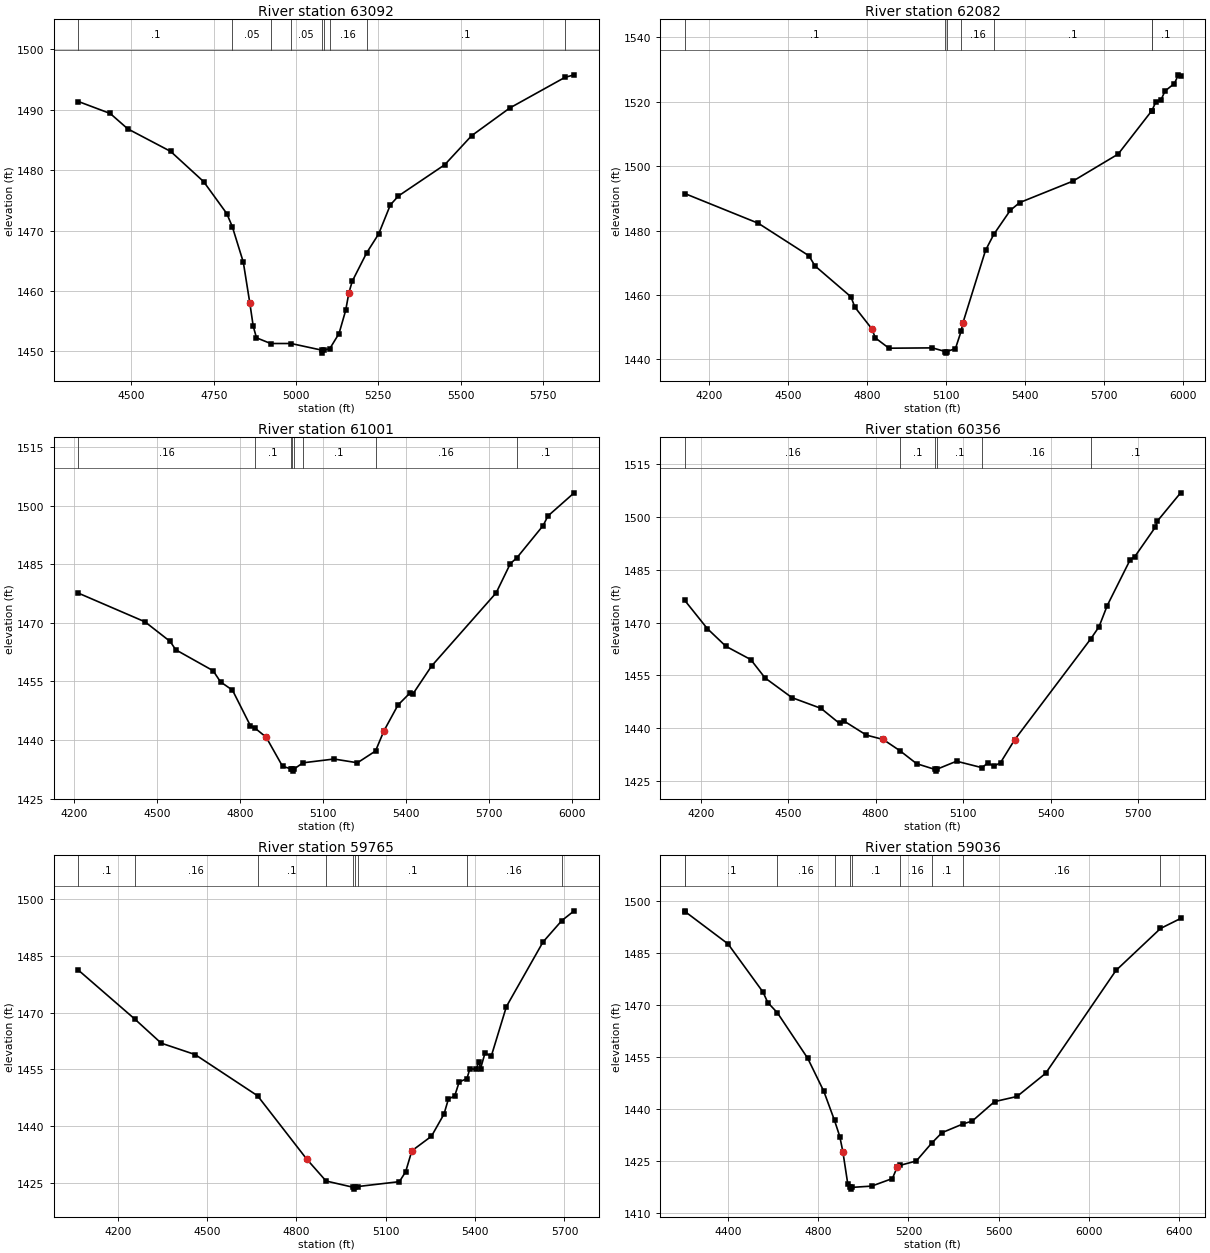
Type RM Length L Ch R = 1 ,63092   ,1010,1010,1010
BEGIN DESCRIPTION:
NORTH GRAPE CREEK 81.0
END DESCRIPTION:
XS GIS Cut Line= 2
      2844728.02     10096186.86      2843226.44     10096062.76
#Sta/Elev= 30
  4338.5 1491.33  4435.3 1489.35  4488.6 1486.81    4619 1483.08  4719.3 1478.08
  4789.6  1472.8  4806.4 1470.64  4839.8 1464.77  4859.8 1457.95  4869.9 1454.19
  4879.9 1452.26    4923 1451.32  4984.9 1451.32  5077.6 1450.23  5080.3 1449.73
  5083.6 1450.23  5102.4 1450.45  5130.7 1452.97  5150.8 1456.78  5160.7 1459.71
  5170.9 1461.62  5214.9 1466.33  5251.2 1469.44  5286.7 1474.24  5311.4 1475.72
  5451.8 1480.87  5533.5 1485.67  5649.4 1490.25  5817.2 1495.32  5845.2 1495.74
#Mann= 9 ,-1 , 0
  4338.5      .1       0  4806.4     .05       0    4923     .16       0
  4984.9     .05       0  5077.6    .035       0  5083.6     .05       0
  5102.4     .16       0  5214.9      .1       0  5817.2     .16       0
Bank Sta=4859.8,5160.7
XS Rating Curve= 0 ,0
Exp/Cntr=0.3,0.1

Type RM Length L Ch R = 1 ,62082   ,1081,1081,1081
BEGIN DESCRIPTION:
NORTH GRAPE CREEK 80.0
END DESCRIPTION:
XS GIS Cut Line= 3
      2845050.63     10096137.21      2844380.53     10095119.66
      2843834.52     10094734.97
#Sta/Elev= 30
  4106.1 1491.52  4385.7 1482.29  4578.5 1472.18  4601.2 1469.06  4738.1 1459.45
  4753.2 1456.22  4816.7  1449.6  4831.4 1446.65  4882.7 1443.48  5048.3 1443.58
  5096.5 1442.45  5099.3 1441.95  5102.5 1442.45  5135.7 1443.34  5157.8 1448.88
  5163.9 1451.29  5250.1 1473.86  5281.6 1478.84  5344.4 1486.31  5380.1 1488.71
  5582.2 1495.36  5754.6 1503.77  5881.8 1517.15  5882.5 1517.16  5897.4 1519.85
  5918.4 1520.73  5933.1 1523.38  5968.9  1525.7  5983.7  1528.4  5992.4 1528.03
#Mann= 7 ,-1 , 0
  4106.1      .1       0  5096.5     .07       0  5102.5      .1       0
  5157.8     .16       0  5281.6      .1       0  5881.8     .05       0
  5882.5      .1       0
Bank Sta=4816.7,5163.9
XS Rating Curve= 0 ,0
Exp/Cntr=0.3,0.1

Type RM Length L Ch R = 1 ,61001   ,645,645,645
BEGIN DESCRIPTION:
NORTH GRAPE CREEK 79.0
END DESCRIPTION:
XS GIS Cut Line= 3
      2845433.45     10095851.96      2845530.96     10095183.32
       2845043.4     10094180.35
#Sta/Elev= 30
  4216.7  1477.6  4457.4 1470.25  4548.4 1465.22  4568.6 1463.09  4703.5 1457.73
  4730.3 1454.87  4773.5 1452.75  4838.5  1443.6  4853.9 1443.08    4895 1440.72
  4954.2 1433.27  4983.7 1432.61    4989 1432.52  4991.8 1432.02    4995 1432.52
  5028.1 1434.15  5140.2 1435.12  5224.9 1434.16  5290.1 1437.17  5320.6 1442.34
  5371.3 1448.95  5416.4 1452.15  5425.7 1451.83  5492.4 1458.91  5725.9 1477.67
  5777.3 1485.18    5800 1486.59  5895.7 1494.91  5912.6 1497.33  6007.6 1503.28
#Mann= 8 ,-1 , 0
  4216.7     .16       0  4853.9      .1       0  4983.7     .16       0
    4989     .07       0    4995     .16       0  5028.1      .1       0
  5290.1     .16       0    5800      .1       0
Bank Sta=4895,5320.6
XS Rating Curve= 0 ,0
Exp/Cntr=0.3,0.1

Type RM Length L Ch R = 1 ,60356   ,591,591,591
BEGIN DESCRIPTION:
NORTH GRAPE CREEK 78.0
END DESCRIPTION:
XS GIS Cut Line= 3
      2846561.79     10095169.36      2846088.18     10094751.47
       2845212.2     10094139.67
#Sta/Elev= 30
  4145.5  1476.3  4222.7 1468.29  4286.2 1463.27  4371.6 1459.48  4420.9 1454.24
  4512.9 1448.65  4612.5  1445.6  4676.1 1441.31  4690.3 1442.05  4768.1 1437.99
  4825.6 1436.75  4883.4 1433.53  4940.3 1429.86  5002.7 1428.24  5005.4 1427.74
  5008.7 1428.24  5077.2 1430.56  5164.7 1428.72  5184.5 1430.09  5205.4 1429.13
  5228.1 1430.16  5276.9 1436.71  5537.8 1465.41  5565.7  1468.8    5594 1474.85
  5672.9 1487.93  5687.8 1488.69  5759.3  1497.2  5765.4 1498.84  5845.6 1506.92
#Mann= 6 ,-1 , 0
  4145.5     .16       0  4883.4      .1       0  5002.7     .07       0
  5008.7      .1       0  5164.7     .16       0  5537.8      .1       0
Bank Sta=4825.6,5276.9
XS Rating Curve= 0 ,0
Exp/Cntr=0.3,0.1

Type RM Length L Ch R = 1 ,59765   ,729,729,729
BEGIN DESCRIPTION:
NORTH GRAPE CREEK 77.0
END DESCRIPTION:
XS GIS Cut Line= 2
      2846882.23     10094695.75      2845503.25      10093762.5
#Sta/Elev= 30
  4067.5  1481.3  4256.8 1468.36  4345.7 1461.97  4459.6 1458.95  4669.4 1448.04
  4834.1 1431.31  4899.4 1425.48  4989.9 1423.83  4992.6 1423.33  4995.9 1423.83
  5006.8 1424.02  5145.6 1425.31  5166.6  1427.9  5187.6 1433.48  5253.5 1437.34
  5295.5  1443.2  5310.4  1447.2  5331.4 1447.98  5346.4 1451.68  5372.5 1452.58
  5382.3 1455.17  5403.3 1455.06  5412.2 1457.04  5418.3 1455.23  5433.2 1459.35
  5454.2  1458.5  5505.1 1471.65    5628 1488.74  5691.1  1494.4  5732.6 1496.99
#Mann= 9 ,-1 , 0
  4067.5      .1       0  4256.8     .16       0  4669.4      .1       0
  4899.4     .16       0  4989.9     .07       0  4995.9     .16       0
  5006.8      .1       0  5372.5     .16       0  5691.1     .05       0
Bank Sta=4834.1,5187.6
XS Rating Curve= 0 ,0
Exp/Cntr=0.3,0.1

Type RM Length L Ch R = 1 ,59036   ,710,710,710
BEGIN DESCRIPTION:
NORTH GRAPE CREEK 76.0
END DESCRIPTION:
XS GIS Cut Line= 2
      2847174.75     10094347.45      2845712.75     10092704.45
#Sta/Elev= 30
  4207.9 1497.18  4210.3  1496.9  4399.5 1487.65    4555 1473.74  4575.9 1470.74
  4618.3 1467.81  4753.2 1454.65  4824.3 1445.18    4872 1436.75  4895.3 1432.11
  4908.9 1427.78  4930.5 1418.56  4941.7 1417.44  4944.4 1416.94  4947.7 1417.44
  5036.7 1417.81  5128.6 1419.99  5149.9 1423.26  5161.2 1423.77  5234.8 1425.06
  5302.5 1430.17  5348.5 1433.21  5440.9 1435.71  5483.2 1436.58  5581.8 1442.17
  5681.3 1443.65  5808.4 1450.32  6120.3 1479.98  6317.9 1492.09  6407.2 1494.98
#Mann= 10 ,-1 , 0
  4207.9     .16       0  4210.3      .1       0  4618.3     .16       0
    4872      .1       0  4941.7     .07       0  4947.7      .1       0
  5161.2     .16       0  5302.5      .1       0  5440.9     .16       0
  6317.9      .1       0
Bank Sta=4908.9,5149.9
XS Rating Curve= 0 ,0
Exp/Cntr=0.3,0.1

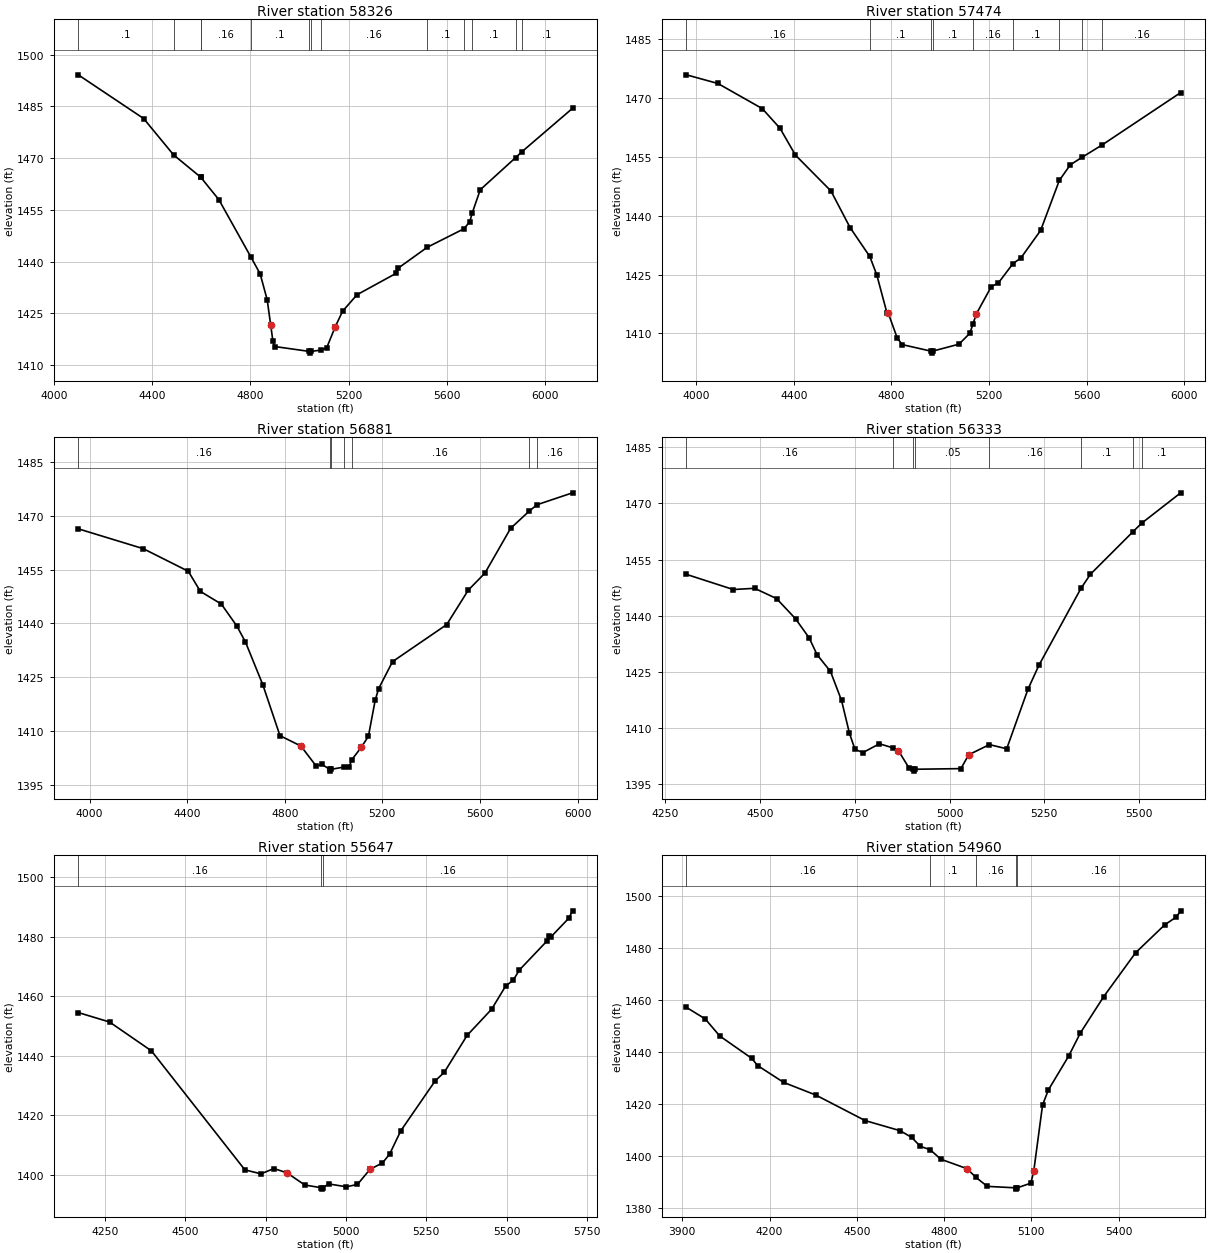
Type RM Length L Ch R = 1 ,58326   ,852,852,852
BEGIN DESCRIPTION:
NORTH GRAPE CREEK 75.0
END DESCRIPTION:
XS GIS Cut Line= 2
       2847773.8     10093623.09      2846032.93     10092606.42
#Sta/Elev= 30
  4097.6 1494.14  4364.2 1481.47  4486.3 1470.93  4596.7 1464.47  4597.6  1464.4
  4671.2 1457.93  4800.6 1441.45  4839.5 1436.42  4868.1 1428.93  4882.5 1421.59
  4891.2 1417.06  4898.2 1415.35  5039.9 1413.93  5042.7 1413.43  5045.9 1413.93
  5089.3 1414.32  5111.3 1415.04    5146 1421.12    5176 1425.61  5234.7 1430.37
  5395.1 1436.61  5400.9 1437.99  5521.1 1444.13  5670.9  1449.5  5694.3 1451.52
  5704.3 1454.03  5737.3 1460.82  5881.5 1470.13  5906.3 1471.78  6113.6 1484.43
#Mann= 13 ,-1 , 0
  4097.6      .1       0  4486.3     .16       0  4596.7      .1       0
  4597.6     .16       0  4800.6      .1       0  5039.9     .07       0
  5045.9      .1       0  5089.3     .16       0  5521.1      .1       0
  5670.9     .16       0  5704.3      .1       0  5881.5     .16       0
  5906.3      .1       0
Bank Sta=4882.5,5146
XS Rating Curve= 0 ,0
Exp/Cntr=0.3,0.1

Type RM Length L Ch R = 1 ,57474   ,593,593,593
BEGIN DESCRIPTION:
NORTH GRAPE CREEK 74.0
END DESCRIPTION:
XS GIS Cut Line= 3
      2848261.37      10092898.7      2847564.83     10092452.91
      2846382.05      10092258.1
#Sta/Elev= 30
  3960.1 1475.96  4089.1 1473.75  4270.9 1467.34  4343.5 1462.33    4407 1455.46
  4552.5 1446.31  4631.1 1436.95  4711.6  1429.6  4740.2 1424.91    4782 1415.17
  4787.1 1415.17  4823.9 1408.82  4844.2 1407.12  4962.8 1405.44  4965.6 1404.94
  4968.8 1405.44  5077.3 1407.23  5121.7 1410.01  5133.7 1412.26  5148.2 1414.93
  5209.1 1421.87    5239 1422.88  5298.4 1427.79  5330.7 1429.21  5411.8 1436.26
  5488.5 1449.03  5533.4    1453    5582 1454.93  5664.8 1458.11  5985.8 1471.43
#Mann= 9 ,-1 , 0
  3960.1     .16       0  4711.6      .1       0  4962.8     .07       0
  4968.8      .1       0  5133.7     .16       0  5298.4      .1       0
  5488.5     .16       0    5582      .1       0  5664.8     .16       0
Bank Sta=4787.1,5148.2
XS Rating Curve= 0 ,0
Exp/Cntr=0.3,0.1

Type RM Length L Ch R = 1 ,56881   ,548,548,548
BEGIN DESCRIPTION:
NORTH GRAPE CREEK 73.0
END DESCRIPTION:
XS GIS Cut Line= 3
      2848526.03     10092661.85      2847509.11     10091798.17
      2847286.23     10091143.46
#Sta/Elev= 30
  3953.7 1466.38  4220.3 1460.84  4404.8 1454.54  4454.2 1448.93  4539.9 1445.42
  4603.6 1439.29  4638.8 1434.86  4710.2 1422.91  4780.4 1408.73  4866.1 1405.84
  4929.8 1400.17  4950.7  1400.8    4984 1399.34  4986.7 1398.84    4990 1399.34
    5042 1399.97  5064.9 1400.12  5074.2 1401.97  5114.4 1405.53  5142.9 1408.56
  5170.7  1418.6  5184.6 1421.79  5241.8 1429.36  5463.7 1439.68  5552.5 1449.31
  5620.5 1454.03  5725.7 1466.51  5801.1 1471.25  5833.9 1473.09  5979.5 1476.41
#Mann= 7 ,-1 , 0
  3953.7     .16       0    4984     .07       0    4990     .16       0
    5042      .1       0  5074.2     .16       0  5801.1      .1       0
  5833.9     .16       0
Bank Sta=4866.1,5114.4
XS Rating Curve= 0 ,0
Exp/Cntr=0.3,0.1

Type RM Length L Ch R = 1 ,56333   ,686,686,686
BEGIN DESCRIPTION:
NORTH GRAPE CREEK 72.0
END DESCRIPTION:
XS GIS Cut Line= 2
      2848539.99     10092174.31      2847759.88     10091129.52
#Sta/Elev= 30
  4305.8 1451.05  4429.4 1447.01  4485.7 1447.33  4543.6 1444.59  4593.6 1439.21
  4629.5 1434.11  4650.4 1429.63  4685.8 1425.15    4715  1417.4  4735.8 1408.67
  4750.4 1404.37  4771.3  1403.5    4815 1405.85  4851.5 1404.73  4865.1 1403.99
  4893.1 1399.38  4903.8 1399.05  4906.5 1398.55  4909.8 1399.05  5029.8 1399.22
  5050.6 1402.92  5105.1 1405.63  5150.7 1404.51  5206.9 1420.44  5236.1 1426.88
  5346.5  1447.3  5371.6 1451.09    5484 1462.46  5507.4 1464.76  5609.7 1472.81
#Mann= 8 ,-1 , 0
  4305.8     .16       0  4851.5     .05       0  4903.8    .033       0
  4909.8     .05       0  5105.1     .16       0  5346.5      .1       0
    5484     .16       0  5507.4      .1       0
Bank Sta=4865.1,5050.6
XS Rating Curve= 0 ,0
Exp/Cntr=0.3,0.1

Type RM Length L Ch R = 1 ,55647   ,687,687,687
BEGIN DESCRIPTION:
NORTH GRAPE CREEK 71.0
END DESCRIPTION:
XS GIS Cut Line= 4
      2848762.87     10092090.75      2848707.14     10091422.04
      2848470.32     10090934.47      2848359.01     10090628.35
#Sta/Elev= 30
  4166.5 1454.56  4263.9 1451.38  4394.3 1441.68  4685.3 1401.66  4735.5 1400.33
  4775.6 1402.11  4815.8  1400.7  4871.7 1396.58  4921.6 1395.69  4924.3 1395.19
  4927.6 1395.69  4946.8 1396.93  5001.5 1395.97  5035.8 1396.78  5074.8 1401.85
  5113.6    1404  5135.8 1406.94  5170.6  1414.8  5277.8 1431.61  5305.9 1434.45
  5377.2 1446.89  5453.8 1455.73  5497.4 1463.53  5520.3 1465.38    5540 1468.88
  5625.1 1478.54  5632.1 1480.37  5637.4 1479.93  5693.3 1486.22  5705.3 1488.76
#Mann= 3 ,-1 , 0
  4166.5     .16       0  4921.6     .07       0  4927.6     .16       0
Bank Sta=4815.8,5074.8
XS Rating Curve= 0 ,0
Exp/Cntr=0.3,0.1

Type RM Length L Ch R = 1 ,54960   ,879,879,879
BEGIN DESCRIPTION:
NORTH GRAPE CREEK 70.0
END DESCRIPTION:
XS GIS Cut Line= 2
       2849278.3     10092188.19       2849278.3     10090488.69
#Sta/Elev= 30
  3914.2 1457.17  3978.7 1452.74  4028.7 1446.17  4138.7 1437.57  4158.7 1434.81
  4248.7  1428.3  4358.7 1423.47  4528.7 1413.63  4648.7 1409.75  4688.7 1407.16
  4718.7 1403.71  4752.2 1402.44  4788.7 1398.78  4878.7 1395.15  4909.8 1391.78
  4948.7 1388.33  5045.7 1387.77  5048.4 1387.27  5051.7 1387.77  5098.7 1389.58
  5108.7 1394.42  5138.7 1419.62  5158.7 1425.42  5228.7 1438.48  5268.7 1447.33
  5348.7 1461.26  5458.7 1478.19  5558.7 1488.91  5598.7 1491.93  5613.7  1494.3
#Mann= 5 ,-1 , 0
  3914.2     .16       0  4752.2      .1       0  4909.8     .16       0
  5045.7     .07       0  5051.7     .16       0
Bank Sta=4878.7,5108.7
XS Rating Curve= 0 ,0
Exp/Cntr=0.3,0.1

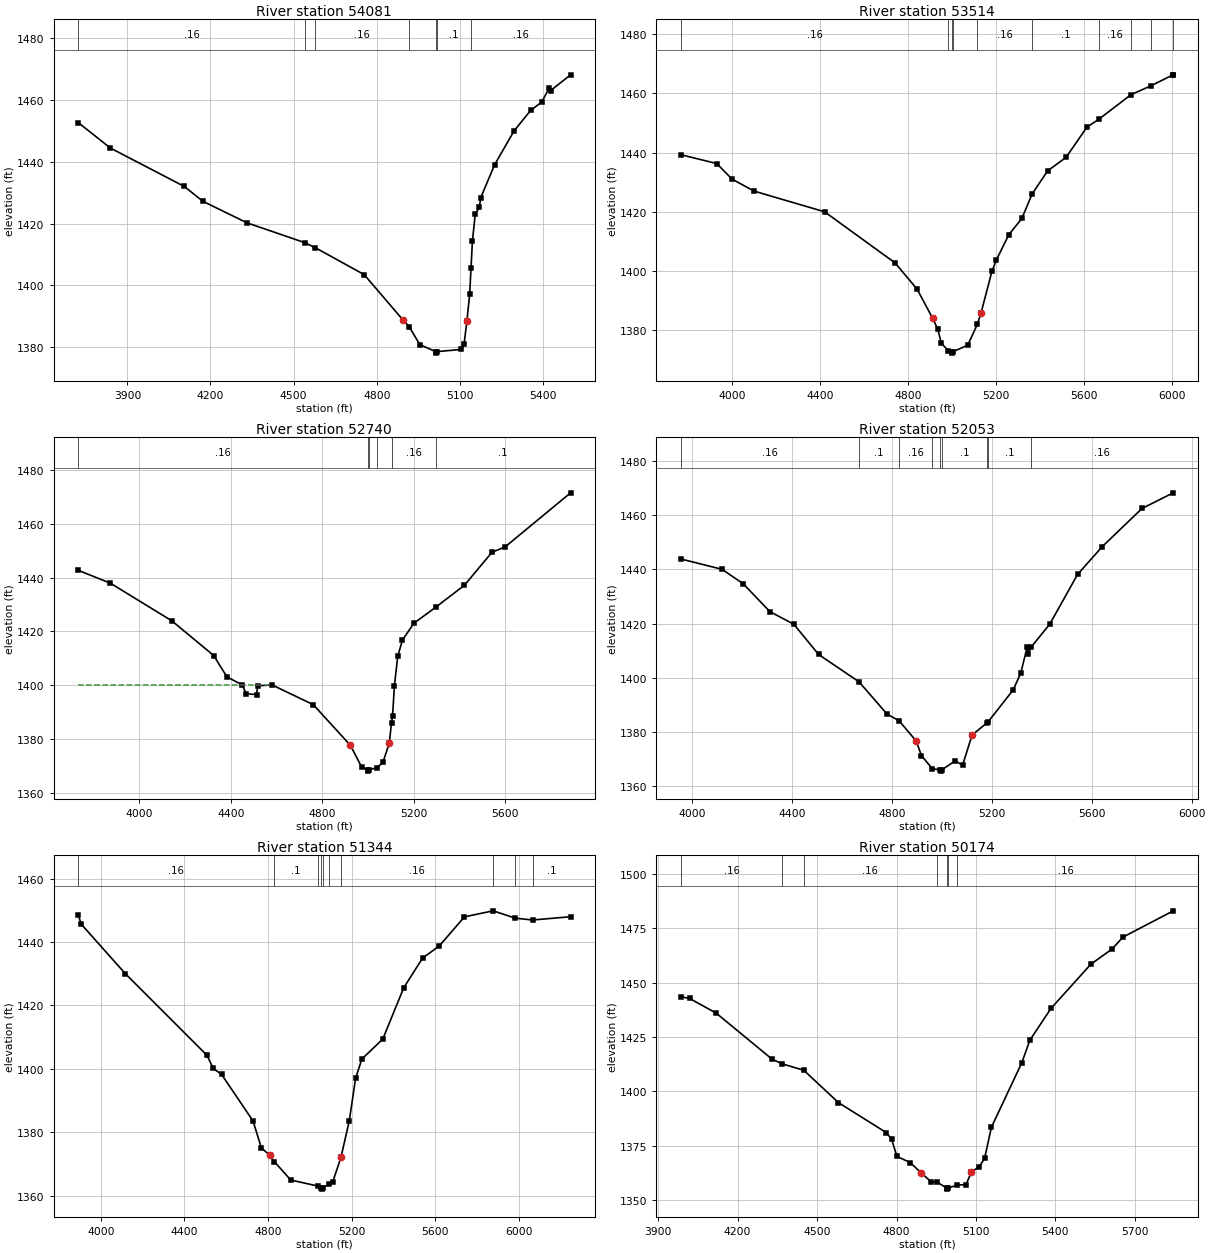
Type RM Length L Ch R = 1 ,54081   ,567,567,567
BEGIN DESCRIPTION:
NORTH GRAPE CREEK 69.0
END DESCRIPTION:
XS GIS Cut Line= 3
      2849626.58     10092355.36      2850058.42     10091380.25
      2850030.56     10090669.75
#Sta/Elev= 30
  3722.3 1452.71  3838.5 1444.46  4105.6    1432  4172.5 1427.21  4331.5 1420.25
  4539.9 1413.83  4577.9 1412.21  4754.7 1403.48  4895.4 1388.74  4917.1 1386.64
  4955.4 1380.84  5012.4 1378.56  5015.2 1378.06  5018.4 1378.56  5105.5 1379.25
  5115.5 1381.05  5125.5 1388.41  5135.5 1397.04  5140.5 1405.71  5145.5 1414.38
  5155.6 1422.96  5170.4 1425.31  5175.6 1428.39  5225.6 1439.04  5295.7 1449.99
  5355.7 1456.63  5395.7 1459.35  5423.1 1463.98  5428.1 1463.07  5499.8 1468.15
#Mann= 7 ,-1 , 0
  3722.3     .16       0  4539.9      .1       0  4577.9     .16       0
  4917.1      .1       0  5012.4     .07       0  5018.4      .1       0
  5140.5     .16       0
Bank Sta=4895.4,5125.5
XS Rating Curve= 0 ,0
Exp/Cntr=0.3,0.1

Type RM Length L Ch R = 1 ,53514   ,774,774,774
BEGIN DESCRIPTION:
NORTH GRAPE CREEK 68.0
END DESCRIPTION:
XS GIS Cut Line= 3
      2850518.13     10092536.49      2850601.71     10091045.91
      2850267.74     10090377.97
#Sta/Elev= 30
  3765.3 1439.32  3928.3 1436.34  3998.4 1431.06  4098.6 1427.02  4419.1 1420.04
  4739.6 1402.78  4839.7 1393.92  4909.9 1384.15  4933.6 1380.45  4949.9 1375.64
  4981.3 1373.19    4997 1372.81  4999.7 1372.31    5003 1372.81  5070.1 1374.98
  5113.6 1382.01  5130.2 1385.81  5180.3 1399.99  5200.3 1403.77  5256.8  1412.3
  5316.2 1417.79  5362.9 1426.06  5433.6 1433.88  5517.4 1438.44  5612.5 1448.65
  5668.4 1451.41  5812.3 1459.59  5902.3 1462.55  6003.4  1466.3    6005 1466.27
#Mann= 10 ,-1 , 0
  3765.3     .16       0  4981.3      .1       0    4997     .07       0
    5003      .1       0  5113.6     .16       0  5362.9      .1       0
  5668.4     .16       0  5812.3      .1       0  5902.3     .16       0
  6003.4      .1       0
Bank Sta=4909.9,5130.2
XS Rating Curve= 0 ,0
Exp/Cntr=0.3,0.1

Type RM Length L Ch R = 1 ,52740   ,687,687,687
BEGIN DESCRIPTION:
NORTH GRAPE CREEK 67.0
END DESCRIPTION:
XS GIS Cut Line= 3
      2850991.77     10092829.05      2851158.94     10091770.31
      2851827.63     10090920.51
#Sta/Elev= 30
  3732.7 1442.69  3873.3 1437.93    4143 1423.91  4325.5 1411.08  4382.9  1403.2
  4450.3 1400.19    4467 1396.96  4512.8 1396.59  4517.8 1399.86  4580.3 1400.19
  4760.6 1392.88  4923.1  1377.8  4972.8 1369.65  4998.7 1368.72  5001.4 1368.22
  5004.7 1368.72  5041.1 1369.54  5065.8 1371.62    5093 1378.52  5102.9 1386.14
  5107.5 1388.73  5115.5  1399.8    5130 1410.77  5150.8 1416.83  5200.5 1423.04
  5295.5 1428.95  5421.9 1437.16  5542.1 1449.37  5599.9 1451.38  5885.9 1471.42
#Mann= 6 ,-1 , 0
  3732.7     .16       0  4998.7     .07       0  5004.7     .16       0
  5041.1      .1       0  5102.9     .16       0  5295.5      .1       0
#XS Ineff= 2 , 0
         4580.51 1400.24
Permanent Ineff=
       F       F
Bank Sta=4923.1,5093
XS Rating Curve= 0 ,0
Exp/Cntr=0.3,0.1

Type RM Length L Ch R = 1 ,52053   ,709,709,709
BEGIN DESCRIPTION:
NORTH GRAPE CREEK 66.0
END DESCRIPTION:
XS GIS Cut Line= 2
      2851493.28     10092968.33      2852175.29     10091117.17
#Sta/Elev= 30
  3953.6 1443.86  4118.4 1440.05  4203.6 1434.69  4310.2  1424.4  4406.1 1419.74
  4505.5 1408.56  4667.5 1398.44  4779.1 1386.58  4828.4 1384.01  4896.3 1376.58
  4917.6 1371.18  4961.1  1366.3  4993.5 1365.94  4996.3 1365.44  4999.5 1365.94
  5052.1 1369.21  5082.5 1367.67  5120.1 1378.76  5179.3 1383.25  5184.7 1383.68
    5285 1395.47  5315.5 1401.71  5340.6 1411.19  5345.9 1408.88  5356.4 1411.22
  5431.9 1419.84  5543.1 1438.19  5642.3 1448.47  5801.1 1462.54  5926.4 1468.32
#Mann= 9 ,-1 , 0
  3953.6     .16       0  4667.5      .1       0  4828.4     .16       0
  4961.1      .1       0  4993.5     .07       0  4999.5      .1       0
  5179.3     .16       0  5184.7      .1       0  5356.4     .16       0
Bank Sta=4896.3,5120.1
XS Rating Curve= 0 ,0
Exp/Cntr=0.3,0.1

Type RM Length L Ch R = 1 ,51344   ,1170,1170,1170
BEGIN DESCRIPTION:
NORTH GRAPE CREEK 65.0
END DESCRIPTION:
XS GIS Cut Line= 2
      2852482.35     10093219.13      2852621.54     10090866.74
#Sta/Elev= 30
  3891.3  1448.6    3906 1445.63  4117.1 1430.01  4507.8 1404.25  4537.8 1400.11
  4577.9  1398.2  4728.2 1383.53  4768.2 1375.02  4808.3 1372.71  4830.8 1370.66
  4908.5 1364.91  5038.3    1363  5055.7 1362.53  5058.5 1362.03  5061.7 1362.53
  5091.3 1363.55  5108.8 1364.14  5148.8 1372.02    5189 1383.65    5219 1397.01
  5249.1 1403.08  5349.2 1409.38  5449.4 1425.58  5539.6 1434.93  5619.7 1438.76
  5739.9 1447.94  5877.3 1449.84  5983.3 1447.52  6065.9 1446.95  6247.8 1447.98
#Mann= 10 ,-1 , 0
  3891.3     .16       0  4830.8      .1       0  5038.3     .16       0
  5055.7     .07       0  5061.7     .16       0  5091.3      .1       0
  5148.8     .16       0  5877.3      .1       0  5983.3     .05       0
  6065.9      .1       0
Bank Sta=4808.3,5148.8
XS Rating Curve= 0 ,0
Exp/Cntr=0.3,0.1

Type RM Length L Ch R = 1 ,50174   ,1304,1304,1304
BEGIN DESCRIPTION:
Mapping XS 4f631ae7
END DESCRIPTION:
XS GIS Cut Line= 2
       2853596.8     10093316.66      2853750.04     10091463.88
#Sta/Elev= 30
  3985.9 1443.53  4018.9 1442.74  4119.3 1435.98    4330  1414.8  4368.7 1412.62
  4449.9 1409.68  4580.9 1394.77  4761.5 1380.97  4781.5 1377.93  4801.6 1370.02
  4851.8 1367.16  4891.9 1362.56    4932 1358.16  4952.5 1358.24  4989.2 1355.44
    4992 1354.94  4995.2 1355.44  5030.2 1356.84  5062.5 1357.01  5082.6 1362.78
  5112.7 1365.31  5132.7 1369.15  5158.2 1383.39  5273.2 1413.17  5303.3 1423.48
  5383.6 1438.21  5534.1 1458.54  5614.4 1465.54  5654.5 1470.95    5845 1483.09
#Mann= 7 ,-1 , 0
  3985.9     .16       0  4368.7      .1       0  4449.9     .16       0
  4952.5      .1       0  4989.2     .07       0  4995.2      .1       0
  5030.2     .16       0
Bank Sta=4891.9,5082.6
XS Rating Curve= 0 ,0
Exp/Cntr=0.3,0.1

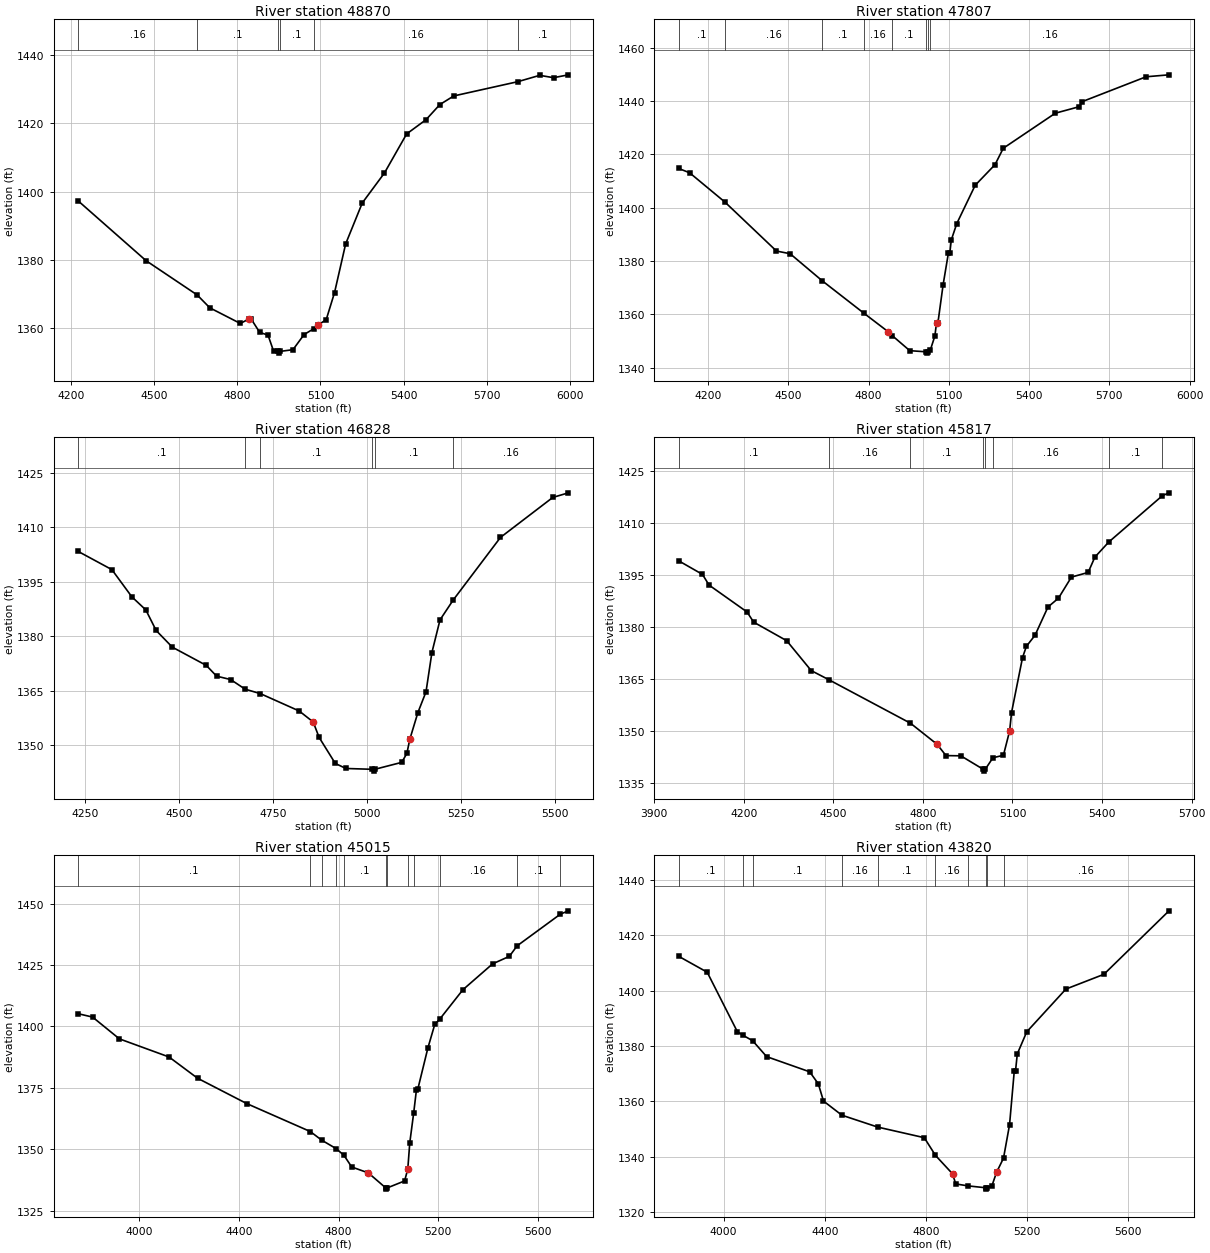
Type RM Length L Ch R = 1 ,48870   ,1063,1063,1063
BEGIN DESCRIPTION:
NORTH GRAPE CREEK 61.0
END DESCRIPTION:
XS GIS Cut Line= 2
      2854975.94     10093219.05      2854962.01      10091449.9
#Sta/Elev= 30
  4225.4 1397.28  4470.7 1379.73  4655.1 1369.68  4700.7 1365.91  4810.7 1361.33
  4840.7 1362.59  4850.7 1362.52  4880.7 1358.71  4910.7 1357.91  4930.7 1353.22
  4947.7 1353.13  4950.5 1352.63  4953.7 1353.13  5000.7 1353.64  5040.7 1358.07
  5076.1 1359.81  5090.7 1360.82  5120.7 1362.46  5150.7 1370.39  5190.7 1384.63
  5250.7 1396.65  5330.7 1405.43  5410.8 1416.88  5480.8 1421.06  5530.8  1425.5
  5580.8 1428.01  5811.7 1432.19  5890.8 1434.05  5940.8 1433.36  5994.6  1434.2
#Mann= 6 ,-1 , 0
  4225.4     .16       0  4655.1      .1       0  4947.7     .07       0
  4953.7      .1       0  5076.1     .16       0  5811.7      .1       0
Bank Sta=4840.7,5090.7
XS Rating Curve= 0 ,0
Exp/Cntr=0.3,0.1

Type RM Length L Ch R = 1 ,47807   ,979,979,979
BEGIN DESCRIPTION:
NORTH GRAPE CREEK 60.0
END DESCRIPTION:
XS GIS Cut Line= 2
       2855825.7     10093442.03      2856201.44     10091646.83
#Sta/Elev= 30
  4089.2 1414.68  4130.3 1413.06  4262.6 1402.06  4455.3 1383.71  4506.3 1382.71
  4625.9  1372.6  4781.8 1360.44  4874.1 1353.38  4888.1 1352.01  4953.9 1346.36
  5014.2 1345.94  5016.9 1345.44  5020.2 1345.94  5030.9 1346.66  5047.8  1351.9
  5053.8 1356.81  5058.9 1356.65  5078.5 1371.06  5098.6 1383.14  5103.7 1383.09
  5109.1 1387.85  5129.6    1394  5198.5 1408.37  5272.6 1416.09  5303.5 1422.24
  5498.2 1435.39  5587.9 1437.83  5599.5 1439.75  5837.6 1449.04  5923.3 1449.77
#Mann= 8 ,-1 , 0
  4089.2      .1       0  4262.6     .16       0  4625.9      .1       0
  4781.8     .16       0  4888.1      .1       0  5014.2     .07       0
  5020.2      .1       0  5030.9     .16       0
Bank Sta=4874.1,5053.8
XS Rating Curve= 0 ,0
Exp/Cntr=0.3,0.1

Type RM Length L Ch R = 1 ,46828   ,1011,1011,1011
BEGIN DESCRIPTION:
NORTH GRAPE CREEK 59.0
END DESCRIPTION:
XS GIS Cut Line= 2
      2856550.09     10093539.52      2857204.14     10092412.33
#Sta/Elev= 30
  4232.4 1403.36  4322.3 1398.33  4375.3 1390.85  4412.5 1387.24  4439.9 1381.58
  4482.9 1376.99  4573.2 1371.97  4600.5 1369.01  4637.8 1368.08  4676.3 1365.43
  4716.8  1364.2  4819.9 1359.43  4857.2  1356.4    4873 1352.14    4916 1344.98
  4944.3  1343.6  5014.8 1343.37  5017.6 1342.87  5020.8 1343.37  5092.4 1345.28
  5106.2 1347.75  5113.9 1351.62  5135.4 1358.97    5157  1364.7  5172.7 1375.52
  5194.2  1384.5  5229.5    1390  5354.9  1407.2    5494 1418.21  5535.6 1419.47
#Mann= 6 ,-1 , 0
  4232.4      .1       0  4676.3     .16       0  4716.8      .1       0
  5014.8     .07       0  5020.8      .1       0  5229.5     .16       0
Bank Sta=4857.2,5113.9
XS Rating Curve= 0 ,0
Exp/Cntr=0.3,0.1

Type RM Length L Ch R = 1 ,45817   ,802,802,802
BEGIN DESCRIPTION:
NORTH GRAPE CREEK 58.0
END DESCRIPTION:
XS GIS Cut Line= 3
       2856954.1     10093776.31      2857734.21     10093372.33
      2858333.19     10092898.72
#Sta/Elev= 30
    3982 1399.15  4061.9 1395.21  4084.1 1392.11  4211.2 1384.34  4233.4  1381.4
    4344 1376.03  4426.1 1367.39  4484.5 1364.78  4758.5 1352.17  4847.5 1346.08
  4877.4 1342.81    4927 1342.75  5002.6 1338.82  5005.3 1338.32  5008.6 1338.82
  5034.6 1342.19  5069.7  1342.9  5090.5 1349.95  5096.9 1355.27  5133.6 1371.12
  5146.6 1374.41  5175.5  1377.6  5218.8 1385.77    5254 1388.33  5297.3 1394.42
  5353.4 1395.77  5375.9  1400.2  5422.5 1404.57  5601.8 1417.95  5624.1 1418.79
#Mann= 8 ,-1 , 0
    3982      .1       0  4484.5     .16       0  4758.5      .1       0
  5002.6     .07       0  5008.6      .1       0  5034.6     .16       0
  5422.5      .1       0  5601.8     .05       0
Bank Sta=4847.5,5090.5
XS Rating Curve= 0 ,0
Exp/Cntr=0.3,0.1

Type RM Length L Ch R = 1 ,45015   ,1195,1195,1195
BEGIN DESCRIPTION:
NORTH GRAPE CREEK 54.0
END DESCRIPTION:
XS GIS Cut Line= 2
      2857176.94     10094194.25      2859071.57     10093664.87
#Sta/Elev= 30
  3754.9 1405.21  3813.1 1403.83  3920.7 1394.95  4119.9 1387.57  4234.1 1378.92
  4431.4 1368.59  4686.3  1357.2  4732.4 1353.67  4790.1 1350.23  4821.6 1347.49
  4852.5 1342.76  4919.4 1340.33  4989.1 1334.23  4991.8 1333.73  4995.1 1334.23
  5064.7 1337.07  5077.5 1341.88  5085.5 1352.63  5101.2  1364.8  5112.3 1374.26
  5117.5 1374.37  5158.2 1391.27  5185.8 1400.86  5204.9 1402.89  5298.7 1414.98
  5417.8 1425.52    5485 1428.58    5516 1432.85  5689.8 1445.78  5722.1 1447.12
#Mann= 12 ,-1 , 0
  3754.9      .1       0  4686.3     .16       0  4732.4      .1       0
  4790.1     .16       0  4821.6      .1       0  4989.1     .07       0
  4995.1      .1       0  5077.5     .16       0  5101.2      .1       0
  5204.9     .16       0    5516      .1       0  5689.8     .16       0
Bank Sta=4919.4,5077.5
XS Rating Curve= 0 ,0
Exp/Cntr=0.3,0.1

Type RM Length L Ch R = 1 ,43820   ,989,989,989
BEGIN DESCRIPTION:
NORTH GRAPE CREEK 53.0
END DESCRIPTION:
XS GIS Cut Line= 3
      2857037.67     10094709.68      2858402.88     10095002.22
      2858944.84     10094946.63
#Sta/Elev= 30
  3821.6 1412.49  3934.9 1406.71  4054.1 1385.22  4077.8 1383.84  4114.7 1381.94
  4170.1 1376.19  4340.5  1370.7  4374.7 1366.34  4395.1 1360.13  4467.9 1355.01
  4610.3  1350.7    4794 1346.88  4838.4 1340.47  4906.5 1333.75  4918.3 1330.16
  4968.4 1329.44  5036.4 1328.78  5039.2 1328.28  5042.4 1328.78  5061.5 1329.43
  5080.3 1334.39  5107.6 1339.48  5131.5 1351.54  5150.1 1370.87  5155.2 1371.05
  5162.2 1377.18  5199.6 1385.16  5354.6 1400.62  5504.9 1405.95  5762.6 1428.91
#Mann= 10 ,-1 , 0
  3821.6      .1       0  4077.8     .16       0  4114.7      .1       0
  4467.9     .16       0  4610.3      .1       0  4838.4     .16       0
  4968.4     .05       0  5036.4    .033       0  5042.4     .05       0
  5107.6     .16       0
Bank Sta=4906.5,5080.3
XS Rating Curve= 0 ,0
Exp/Cntr=0.3,0.1

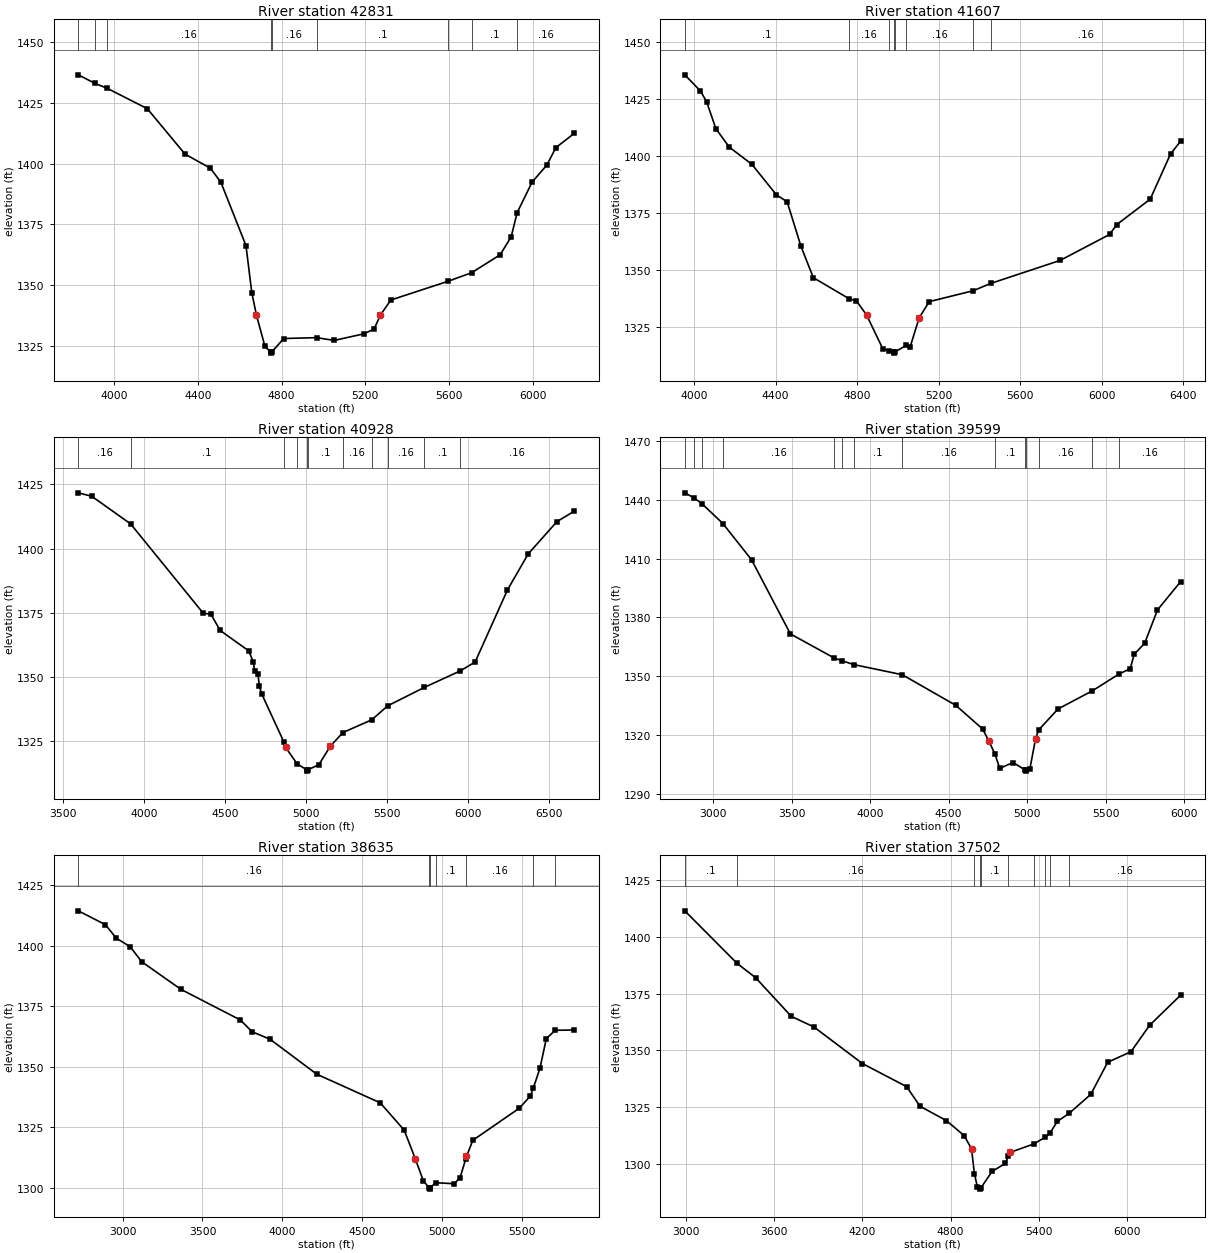
Type RM Length L Ch R = 1 ,42831   ,1224,1224,1224
BEGIN DESCRIPTION:
NORTH GRAPE CREEK 52.0
END DESCRIPTION:
XS GIS Cut Line= 3
      2856550.11     10095865.92       2858096.4     10095740.54
      2858848.65     10095420.14
#Sta/Elev= 30
  3828.6 1436.48  3906.4 1433.02  3965.3 1430.98    4158 1422.56  4338.6 1403.84
    4459  1398.1  4509.2 1392.39  4629.6 1366.23  4657.3 1346.93  4679.7 1337.57
  4719.9 1324.87    4747 1322.49  4749.7 1321.99    4753 1322.49  4810.2    1328
  4967.1 1328.36    5051 1327.21  5191.4 1329.91  5241.6 1331.87  5271.7 1337.63
  5321.8 1343.84  5594.3 1351.53  5707.7 1355.07    5844 1362.45  5896.7 1369.86
  5925.3 1379.79  5996.7 1392.35    6067 1399.35  6110.4 1406.54  6197.6 1412.36
#Mann= 9 ,-1 , 0
  3828.6     .16       0  3906.4      .1       0  3965.3     .16       0
    4747     .07       0    4753     .16       0  4967.1      .1       0
  5594.3     .16       0  5707.7      .1       0  5925.3     .16       0
Bank Sta=4679.7,5271.7
XS Rating Curve= 0 ,0
Exp/Cntr=0.3,0.1

Type RM Length L Ch R = 1 ,41607   ,679,679,679
BEGIN DESCRIPTION:
NORTH GRAPE CREEK 50.0
END DESCRIPTION:
XS GIS Cut Line= 3
      2857093.35      10096813.2      2857915.31     10096952.51
      2859182.09     10095978.06
#Sta/Elev= 30
  3954.6 1435.56  4030.8 1428.53  4061.2 1423.86  4107.1 1411.94  4172.8 1403.87
  4283.1 1396.38  4403.8    1383  4456.8 1379.87  4524.5 1360.38  4584.9 1346.66
  4760.7 1337.42  4796.5 1336.51  4846.4 1330.25  4925.2  1315.6  4957.4 1314.61
  4978.5 1314.09  4981.3 1313.59  4984.5 1314.09  5040.5 1316.95  5060.2 1316.37
  5103.7    1329  5153.6 1336.16  5368.1 1340.92  5455.8 1344.16  5795.1 1354.21
    6038 1365.59  6073.3 1369.93  6237.3 1381.06    6337 1400.88  6386.5 1406.48
#Mann= 8 ,-1 , 0
  3954.6      .1       0  4760.7     .16       0  4957.4      .1       0
  4978.5     .07       0  4984.5      .1       0  5040.5     .16       0
  5368.1      .1       0  5455.8     .16       0
Bank Sta=4846.4,5103.7
XS Rating Curve= 0 ,0
Exp/Cntr=0.3,0.1

Type RM Length L Ch R = 1 ,40928   ,1329,1329,1329
BEGIN DESCRIPTION:
NORTH GRAPE CREEK 49.0
END DESCRIPTION:
XS GIS Cut Line= 3
      2857385.95     10098317.71      2858709.35     10097161.47
      2859724.89      10096340.7
#Sta/Elev= 30
  3592.3 1421.68  3675.3 1420.33  3915.1  1409.6  4362.5 1374.94  4411.9 1374.36
  4468.8 1368.11  4645.4 1360.17  4673.9 1355.71  4681.5 1352.15  4702.4  1351.1
  4709.9 1346.59  4724.2 1343.56  4862.3 1324.69  4872.3 1322.68  4944.4 1316.17
    5004 1313.88  5006.8 1313.38    5010 1313.88  5078.2 1315.89  5149.3  1323.1
  5227.1  1328.4  5405.2 1333.36  5503.8  1338.8  5729.8 1345.96  5951.8 1352.38
  6043.7 1355.85  6243.5 1383.91  6371.4  1397.9  6548.9 1410.47  6655.4 1414.51
#Mann= 11 ,-1 , 0
  3592.3     .16       0  3915.1      .1       0  4862.3     .16       0
  4944.4      .1       0    5004     .07       0    5010      .1       0
  5227.1     .16       0  5405.2      .1       0  5503.8     .16       0
  5729.8      .1       0  5951.8     .16       0
Bank Sta=4872.3,5149.3
XS Rating Curve= 0 ,0
Exp/Cntr=0.3,0.1

Type RM Length L Ch R = 1 ,39599   ,964,964,964
BEGIN DESCRIPTION:
Mapping XS 9affa583
END DESCRIPTION:
XS GIS Cut Line= 3
      2858667.56     10099613.27      2859586.98     10098025.17
      2859865.59     10096729.63
#Sta/Elev= 30
  2818.2 1443.61  2878.6 1440.96    2928 1438.03  3060.9 1427.93  3244.3 1409.37
  3491.1 1371.63  3768.4 1359.41  3819.2 1357.95  3894.9 1355.97  4204.6 1350.79
  4545.8 1335.15  4716.1 1323.13    4757 1316.83  4796.1 1310.11  4825.1 1303.01
  4910.4    1306  4989.3  1302.1    4992  1301.6  4995.3  1302.1  5017.4  1302.6
  5053.6 1318.07  5073.3 1322.58  5196.8 1333.31  5416.6 1342.61  5584.6  1351.1
  5657.1 1353.89  5682.8 1361.25  5749.2 1366.84    5831 1383.88  5978.4 1398.29
#Mann= 14 ,-1 , 0
  2818.2      .1       0  2878.6     .16       0    2928      .1       0
  3060.9     .16       0  3768.4      .1       0  3819.2     .16       0
  3894.9      .1       0  4204.6     .16       0  4796.1      .1       0
  4989.3     .07       0  4995.3      .1       0  5073.3     .16       0
  5416.6      .1       0  5584.6     .16       0
Bank Sta=4757,5053.6
XS Rating Curve= 0 ,0
Exp/Cntr=0.3,0.1

Type RM Length L Ch R = 1 ,38635   ,1133,1133,1133
BEGIN DESCRIPTION:
NORTH GRAPE CREEK 46.0
END DESCRIPTION:
XS GIS Cut Line= 3
      2860938.25      10100226.2      2860436.75     10098443.09
      2860478.54     10097189.38
#Sta/Elev= 30
  2722.1 1414.44  2891.8 1408.71  2959.9 1403.13  3046.7 1399.63  3119.4 1393.39
  3365.6 1381.96  3737.3 1369.33  3810.6 1364.48  3923.1 1361.38  4216.3 1346.92
  4613.8 1335.09  4763.9 1323.81  4833.9 1311.88  4883.9 1302.84  4920.9 1299.93
  4923.7 1299.43  4926.9 1299.93  4960.2 1302.09  5077.5 1301.65  5114.1 1304.23
  5149.9 1311.96  5154.1 1312.97  5194.1 1319.62  5484.3 1332.83  5554.3 1337.88
  5573.9  1341.4  5614.3 1349.33  5654.4 1361.64  5710.3 1365.07  5828.8 1365.19
#Mann= 7 ,-1 , 0
  2722.1     .16       0  4920.9     .07       0  4926.9     .16       0
  4960.2      .1       0  5149.9     .16       0  5573.9      .1       0
  5710.3     .16       0
Bank Sta=4833.9,5154.1
XS Rating Curve= 0 ,0
Exp/Cntr=0.3,0.1

Type RM Length L Ch R = 1 ,37502   ,1012,1012,1012
BEGIN DESCRIPTION:
NORTH GRAPE CREEK 45.0
END DESCRIPTION:
XS GIS Cut Line= 3
        2861593.     10099989.36      2861495.48     10097593.32
        2861189.     10096673.88
#Sta/Elev= 30
  2995.2 1411.36  3350.3 1388.25  3475.8 1381.97  3718.9 1364.93  3871.6 1360.32
  4201.8  1344.2  4502.1 1334.04  4592.2 1325.46  4772.3  1319.1  4892.4 1312.52
  4942.4 1306.72  4962.2 1295.69  4982.5 1289.91  4999.5  1289.5  5002.2    1289
  5005.5  1289.5  5082.6 1296.83  5172.6  1300.3  5191.2 1303.42  5202.7 1305.11
  5366.9  1308.9  5441.4 1311.79  5474.4 1313.61  5525.3 1318.76  5606.3 1322.38
    5752 1330.64  5867.1 1344.78  6025.2 1349.42  6151.7 1361.03  6362.4 1374.28
#Mann= 10 ,-1 , 0
  2995.2      .1       0  3350.3     .16       0  4962.2      .1       0
  4999.5     .07       0  5005.5      .1       0  5191.2     .16       0
  5366.9      .1       0  5441.4     .16       0  5474.4     .05       0
  5606.3     .16       0
Bank Sta=4942.4,5202.7
XS Rating Curve= 0 ,0
Exp/Cntr=0.3,0.1