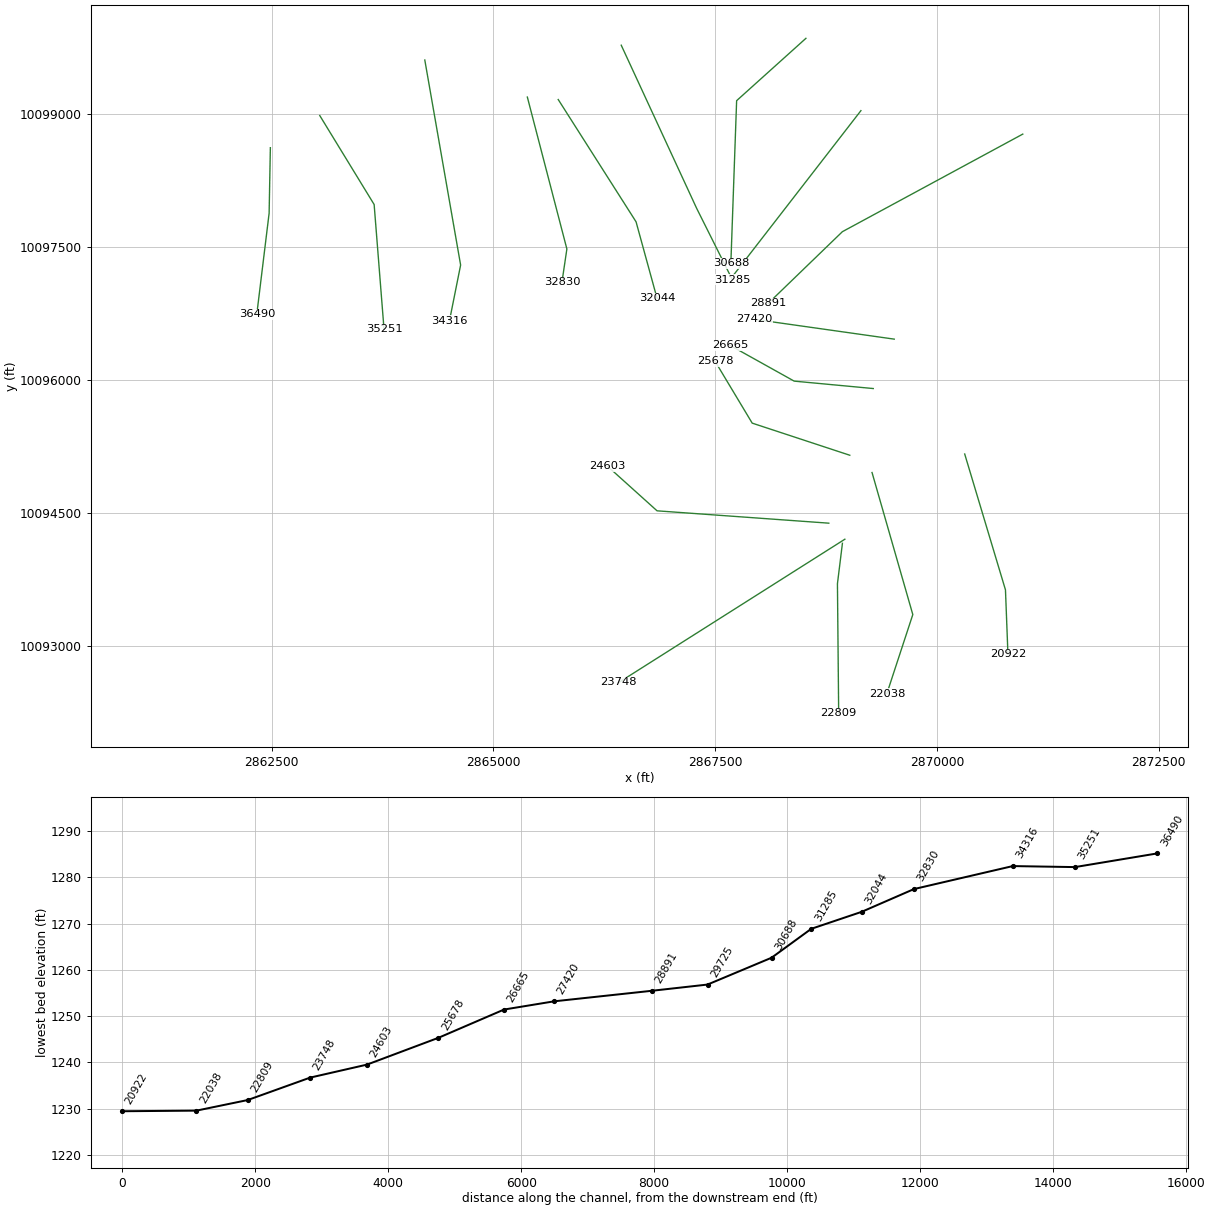
HEC-RAS study NORTH GRAPE CREEK.prj: NORTH GRAPE CREEK Base Level Engineering

--- NORTH GRAPE CREEK.g01 (geometry) --- (continued)

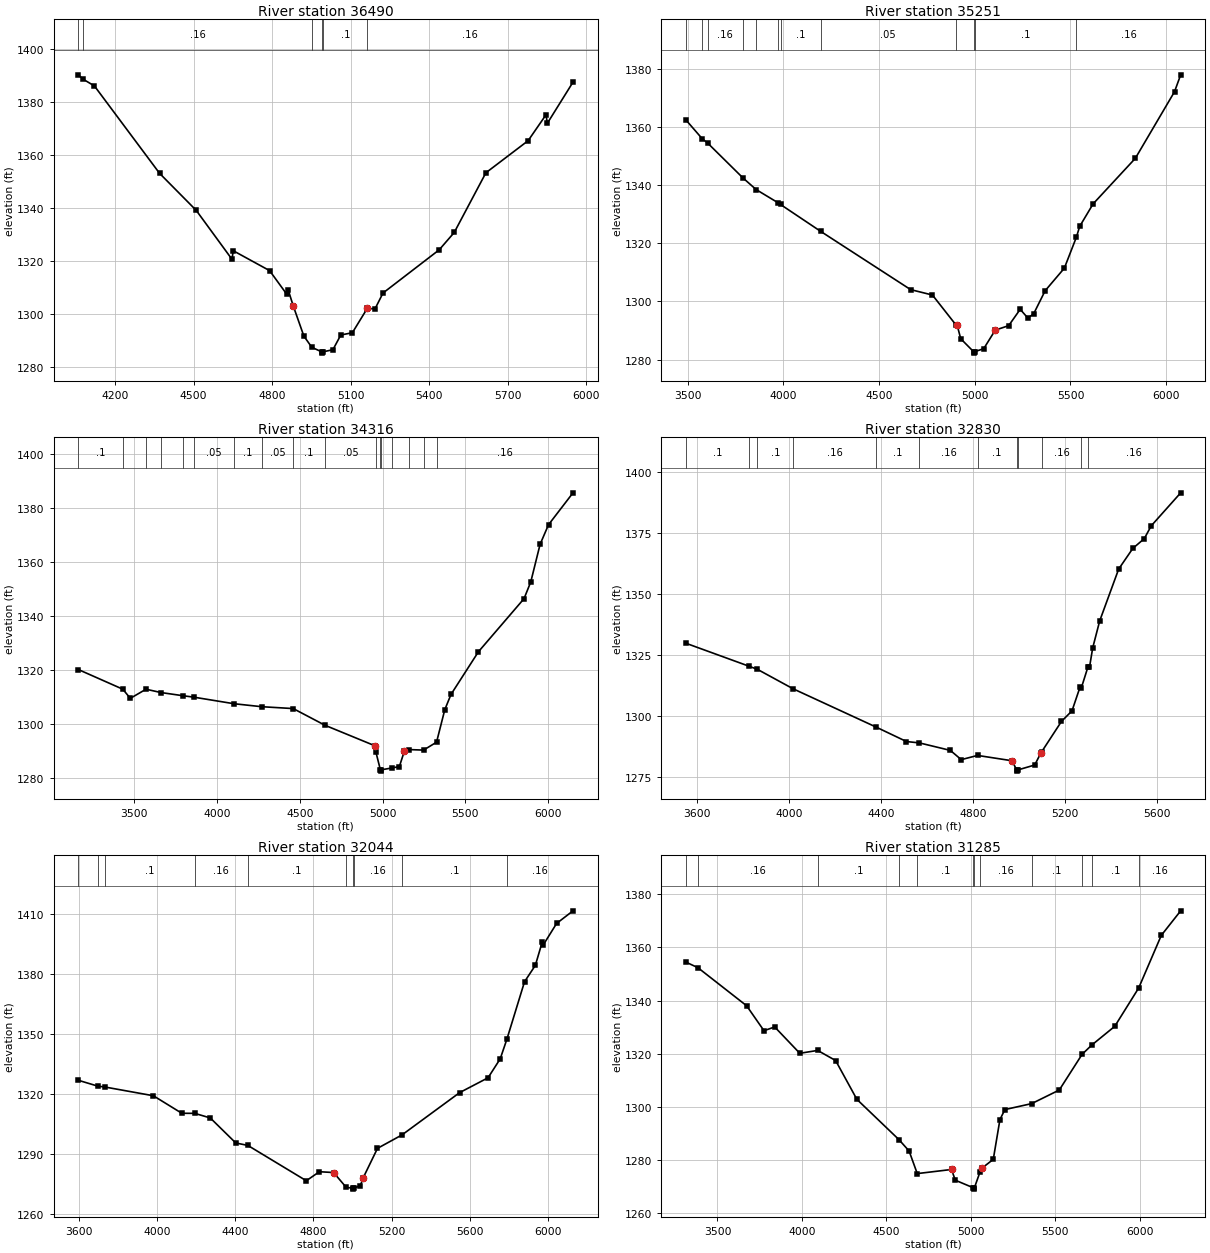
Type RM Length L Ch R = 1 ,36490   ,1239,1239,1239
BEGIN DESCRIPTION:
NORTH GRAPE CREEK 44.0
END DESCRIPTION:
XS GIS Cut Line= 3
      2862484.56     10098624.17      2862470.63     10097885.86
      2862331.32     10096743.57
#Sta/Elev= 30
  4059.7 1390.08  4078.3 1388.42  4121.4 1385.88  4370.2 1352.94  4510.2 1338.97
  4646.5 1320.56  4651.5 1323.77  4790.3 1316.27  4856.5 1307.28  4861.5 1308.93
  4880.9 1302.88  4921.2 1291.58  4951.4 1287.38  4988.7 1285.67  4991.4 1285.17
  4994.7 1285.67    5032 1286.45  5062.2 1292.01  5106.3 1292.85    5163    1302
  5164.1 1301.95  5193.2 1301.92  5223.4 1307.83  5437.8  1324.1  5495.4 1330.66
  5616.3 1353.16  5777.5 1365.25  5845.8 1375.01  5850.8 1371.79  5948.9 1387.33
#Mann= 6 ,-1 , 0
  4059.7      .1       0  4078.3     .16       0  4951.4      .1       0
  4988.7     .07       0  4994.7      .1       0  5164.1     .16       0
Bank Sta=4880.9,5163
XS Rating Curve= 0 ,0
Exp/Cntr=0.3,0.1

Type RM Length L Ch R = 1 ,35251   ,935,935,935
BEGIN DESCRIPTION:
NORTH GRAPE CREEK 41.0
END DESCRIPTION:
XS GIS Cut Line= 3
      2863041.76     10098986.42      2863654.73     10097983.38
      2863766.08     10096577.59
#Sta/Elev= 30
  3490.2 1362.35  3574.9 1355.93  3603.8  1354.4  3788.6  1342.4  3857.1 1338.43
  3972.4 1333.86  3984.5  1333.3    4194 1324.08  4664.5 1304.04  4778.5 1302.18
  4900.4 1291.98    4907 1291.97  4926.2 1287.17  4993.4 1282.71  4996.1 1282.21
  4999.4 1282.71  5046.5 1283.74  5106.7 1290.11    5177 1291.66  5237.1 1297.27
  5277.3 1294.26  5307.4 1295.72  5367.5 1303.65  5467.9 1311.42  5530.8 1322.06
  5548.1 1325.78  5618.3 1333.52    5839 1349.18  6043.7 1372.07  6075.9 1377.87
#Mann= 12 ,-1 , 0
  3490.2     .16       0  3574.9     .05       0  3603.8     .16       0
  3788.6     .05       0  3857.1      .1       0  3972.4     .05       0
  3984.5      .1       0    4194     .05       0  4900.4      .1       0
  4993.4     .07       0  4999.4      .1       0  5530.8     .16       0
Bank Sta=4907,5106.7
XS Rating Curve= 0 ,0
Exp/Cntr=0.3,0.1

Type RM Length L Ch R = 1 ,34316   ,1486,1486,1486
BEGIN DESCRIPTION:
NORTH GRAPE CREEK 40.0
END DESCRIPTION:
XS GIS Cut Line= 3
      2864225.89     10099613.29      2864629.88     10097300.78
      2864504.51     10096673.93
#Sta/Elev= 30
  3162.9 1320.07  3431.7 1312.78  3477.1 1309.39  3571.8 1312.77  3662.1 1311.54
  3793.8 1310.37  3861.4 1309.82  4102.7  1307.4  4269.1  1306.3  4460.6  1305.6
  4652.7 1299.41  4952.2 1291.86  4958.9 1289.69  4986.7 1282.93  4989.5 1282.43
  4992.7 1282.93    5058 1283.61  5101.4 1284.12  5131.8 1289.87  5157.1 1290.42
  5247.4 1290.22  5325.9 1293.15  5375.5 1305.16    5413 1310.83  5578.8 1326.66
  5854.2 1346.33  5894.9 1352.56    5951 1366.45    6002 1373.72  6149.7 1385.52
#Mann= 17 ,-1 , 0
  3162.9      .1       0  3431.7     .16       0  3571.8      .1       0
  3662.1     .05       0  3793.8      .1       0  3861.4     .05       0
  4102.7      .1       0  4269.1     .05       0  4460.6      .1       0
  4652.7     .05       0  4958.9      .1       0  4986.7     .07       0
  4992.7      .1       0    5058     .05       0  5157.1     .16       0
  5247.4     .05       0  5325.9     .16       0
Bank Sta=4952.2,5131.8
XS Rating Curve= 0 ,0
Exp/Cntr=0.3,0.1

Type RM Length L Ch R = 1 ,32830   ,786,786,786
BEGIN DESCRIPTION:
NORTH GRAPE CREEK 38.0
END DESCRIPTION:
XS GIS Cut Line= 3
      2865382.13     10099195.34      2865827.91     10097481.88
      2865772.42     10097107.27
#Sta/Elev= 30
  3553.1 1329.83  3828.2 1320.39  3863.8 1319.14  4018.5 1311.19  4380.8 1295.43
  4511.1 1289.58  4567.4 1289.02  4701.7 1285.95  4749.1 1282.16  4819.8 1283.89
  4970.4  1281.7  4989.2 1277.96    4992 1277.46  4995.2 1277.96  5068.1 1279.96
  5094.4 1284.79  5097.9 1285.31  5184.5 1297.83  5230.2 1302.15  5265.5 1312.01
  5271.3 1311.71  5298.9 1319.98  5306.1 1319.95  5320.1 1327.94  5350.5    1339
  5432.9 1360.22  5494.5  1368.7  5544.1 1372.68  5574.5 1377.95  5702.3 1391.45
#Mann= 12 ,-1 , 0
  3553.1      .1       0  3828.2     .16       0  3863.8      .1       0
  4018.5     .16       0  4380.8      .1       0  4567.4     .16       0
  4819.8      .1       0  4989.2     .07       0  4995.2      .1       0
  5097.9     .16       0  5271.3     .05       0  5298.9     .16       0
Bank Sta=4970.4,5094.4
XS Rating Curve= 0 ,0
Exp/Cntr=0.3,0.1

Type RM Length L Ch R = 1 ,32044   ,759,759,759
BEGIN DESCRIPTION:
NORTH GRAPE CREEK 37.0
END DESCRIPTION:
XS GIS Cut Line= 3
      2865730.39     10099167.51      2866608.03     10097788.35
      2866844.85     10096924.66
#Sta/Elev= 30
  3597.4 1326.89  3696.8 1323.97  3734.2 1323.51  3981.4 1319.16    4127 1310.41
    4193 1310.37  4272.6 1308.07    4403 1295.58  4464.5 1294.37  4763.7 1276.72
  4830.6 1281.23  4903.4 1280.82  4967.7 1273.42  5000.3 1273.04    5003 1272.54
  5006.3 1273.04  5039.7 1274.26  5054.9 1278.25  5127.7  1292.9    5253  1299.6
    5548 1320.73  5693.2 1328.13  5755.4 1337.59  5789.6  1347.4  5879.8 1376.09
  5935.1 1384.25  5969.6 1395.68  5974.8 1394.33  6043.7 1405.17  6127.7 1411.48
#Mann= 10 ,-1 , 0
  3597.4      .1       0  3696.8     .16       0  3734.2      .1       0
    4193     .16       0  4464.5      .1       0  4967.7     .16       0
  5000.3     .07       0  5006.3     .16       0    5253      .1       0
  5789.6     .16       0
Bank Sta=4903.4,5054.9
XS Rating Curve= 0 ,0
Exp/Cntr=0.3,0.1

Type RM Length L Ch R = 1 ,31285   ,597,597,597
BEGIN DESCRIPTION:
NORTH GRAPE CREEK 36.0
END DESCRIPTION:
XS GIS Cut Line= 3
      2866440.87     10099780.41      2867290.63     10097941.59
      2867694.03     10097134.79
#Sta/Elev= 30
  3313.5 1354.47  3384.2 1352.38  3672.6 1338.01  3775.3  1328.6  3838.6 1330.03
  3987.2 1320.09    4093 1321.17  4199.2 1317.36  4324.9 1302.73  4573.6 1287.55
    4634 1283.24  4682.3 1274.72  4885.2 1276.27  4907.2 1272.23  5014.5 1269.36
  5017.3 1268.86  5020.5 1269.36  5053.2 1275.25  5063.4 1276.68  5132.2 1280.09
  5171.6  1295.1    5201 1298.87  5359.4 1301.11  5522.8 1306.24  5658.3 1319.74
  5715.4 1323.21  5851.1 1330.26  5992.7 1344.72  6126.6 1364.58  6241.2 1373.82
#Mann= 12 ,-1 , 0
  3313.5      .1       0  3384.2     .16       0    4093      .1       0
  4573.6     .16       0  4682.3      .1       0  5014.5     .07       0
  5020.5      .1       0  5053.2     .16       0  5359.4      .1       0
  5658.3     .16       0  5715.4      .1       0  5992.7     .16       0
Bank Sta=4885.2,5063.4
XS Rating Curve= 0 ,0
Exp/Cntr=0.3,0.1

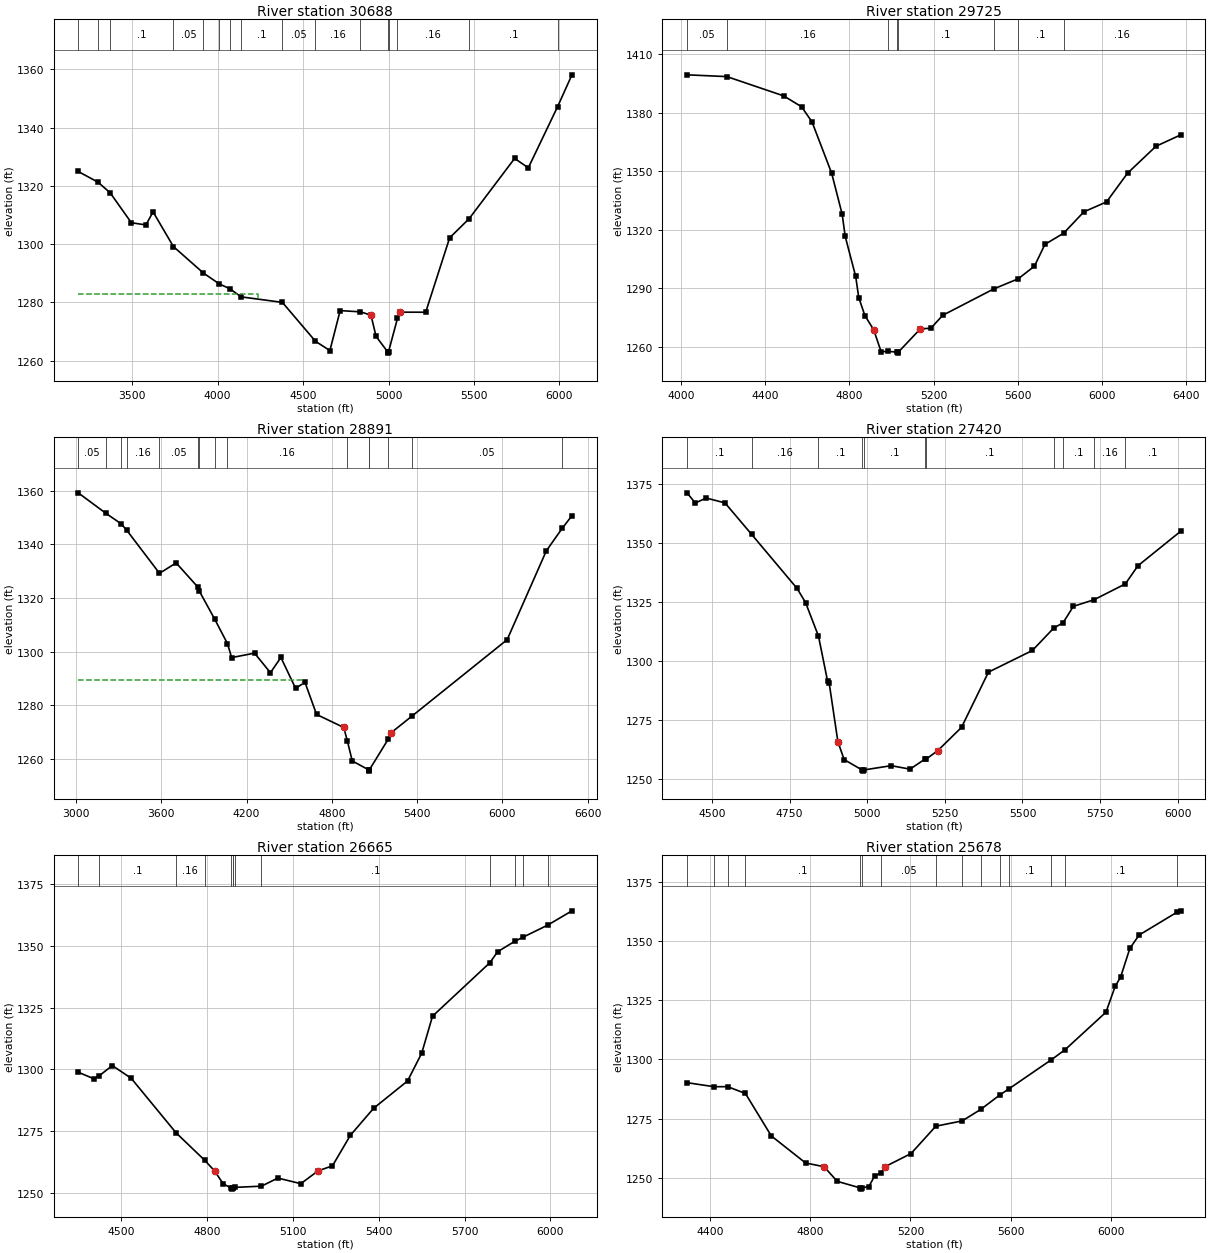
Type RM Length L Ch R = 1 ,30688   ,963,963,963
BEGIN DESCRIPTION:
Mapping XS 97c8f163
END DESCRIPTION:
XS GIS Cut Line= 3
       2868523.2     10099857.75      2867741.98     10099154.65
      2867676.87     10097318.73
#Sta/Elev= 30
  3184.9 1324.96  3299.7 1321.32  3371.1 1317.69  3495.7 1307.37  3580.9 1306.61
  3622.7  1311.1  3741.7 1299.19    3917 1290.11  4010.2 1286.36  4071.3 1284.73
  4138.1 1281.92  4379.2 1280.03  4572.9 1266.67  4657.1 1263.49  4717.1 1277.21
  4835.7 1276.78  4897.3 1275.66  4927.3 1268.34  4994.3 1263.11  4997.1 1262.61
  5000.3 1263.11  5052.4 1274.53  5067.4 1276.67  5217.5 1276.65  5357.5 1302.17
    5472 1308.78  5737.8 1329.45  5817.8 1326.21  5988.9 1347.17    6073 1358.14
#Mann= 16 ,-1 , 0
  3184.9      .1       0  3299.7     .05       0  3371.1      .1       0
  3741.7     .05       0    3917     .16       0  4010.2      .1       0
  4071.3     .16       0  4138.1      .1       0  4379.2     .05       0
  4572.9     .16       0  4835.7      .1       0  4994.3     .07       0
  5000.3      .1       0  5052.4     .16       0    5472      .1       0
  5988.9     .16       0
#XS Ineff= 2 , 0
         4236.78 1282.94
Permanent Ineff=
       F       F
Bank Sta=4897.3,5067.4
XS Rating Curve= 0 ,0
Exp/Cntr=0.3,0.1

Type RM Length L Ch R = 1 ,29725   ,834,834,834
BEGIN DESCRIPTION:
NORTH GRAPE CREEK 34.0
END DESCRIPTION:
XS GIS Cut Line= 2
      2869143.41     10099042.11      2867708.56     10097189.34
#Sta/Elev= 30
    4030  1399.5  4219.2 1398.59  4488.4 1388.72  4573.5 1383.14  4623.3 1375.36
  4716.6 1349.03  4766.4 1328.02  4780.8 1316.66  4830.6  1296.1  4845.1 1285.31
  4874.1 1276.09  4915.7 1268.86  4951.3 1257.54  4985.6 1257.72  5026.8 1257.31
  5029.6 1256.81  5032.8 1257.31  5137.6 1269.27  5187.4 1269.57  5243.5 1276.19
  5485.5 1289.71  5602.1 1294.93    5679 1301.39  5728.8 1312.56  5817.8 1318.31
  5913.5 1329.24  6021.2 1334.34  6120.8 1349.05  6255.7 1362.86  6373.4 1368.72
#Mann= 8 ,-1 , 0
    4030     .05       0  4219.2     .16       0  4985.6      .1       0
  5026.8     .07       0  5032.8      .1       0  5485.5     .05       0
  5602.1      .1       0  5817.8     .16       0
Bank Sta=4915.7,5137.6
XS Rating Curve= 0 ,0
Exp/Cntr=0.3,0.1

Type RM Length L Ch R = 1 ,28891   ,1471,1471,1471
BEGIN DESCRIPTION:
NORTH GRAPE CREEK 33.0
END DESCRIPTION:
XS GIS Cut Line= 3
      2870968.35     10098777.44      2868934.45      10097676.9
       2868098.6     10096868.91
#Sta/Elev= 30
  3015.2 1359.17  3208.5 1351.59  3318.2  1347.6  3356.5 1345.24  3587.2 1329.18
  3704.4 1333.06  3855.5 1324.15  3866.5 1322.66  3976.1 1312.06  4065.6 1302.98
  4095.2 1297.78  4256.2 1299.43  4368.1 1292.14  4441.7 1297.83  4545.4 1286.29
    4611  1288.6  4692.8 1276.59    4884 1271.74  4908.9 1266.85    4944 1259.28
  5058.7 1255.97  5061.4 1255.47  5064.7 1255.97  5199.1 1267.54    5217 1269.75
    5365    1276  6034.3 1304.45  6310.1 1337.56  6421.2  1345.9  6490.3 1350.65
#Mann= 15 ,-1 , 0
  3015.2     .05       0  3208.5     .16       0  3318.2      .1       0
  3356.5     .16       0  3587.2     .05       0  3855.5     .16       0
  3866.5     .05       0  3976.1      .1       0  4065.6     .16       0
  4908.9      .1       0  5058.7     .07       0  5064.7      .1       0
  5199.1     .16       0    5365     .05       0  6421.2      .1       0
#XS Ineff= 2 , 0
         4593.22 1289.38
Permanent Ineff=
       F       F
Bank Sta=4884,5217
XS Rating Curve= 0 ,0
Exp/Cntr=0.3,0.1

Type RM Length L Ch R = 1 ,27420   ,755,755,755
BEGIN DESCRIPTION:
NORTH GRAPE CREEK 30.0
END DESCRIPTION:
XS GIS Cut Line= 2
       2869519.5     10096464.94       2867945.4     10096687.82
#Sta/Elev= 30
  4419.9  1371.4  4446.6 1367.07  4481.5 1369.19  4542.1 1367.12    4628 1353.74
  4774.4 1330.77  4801.6 1324.79  4843.2 1310.53  4872.6 1291.36  4877.7 1290.58
  4905.7 1265.68  4925.9 1258.09  4983.5 1253.69  4986.3 1253.19  4989.5 1253.69
  5077.4 1255.51    5138 1254.03  5185.6 1258.25  5190.2 1258.32  5227.7 1261.94
  5303.8 1271.77  5390.5 1295.24  5531.9 1304.43  5601.1    1314  5630.9 1316.21
  5663.9 1323.18  5731.1 1326.02  5831.4 1332.72  5871.9 1340.42  6009.7 1355.09
#Mann= 11 ,-1 , 0
  4419.9      .1       0    4628     .16       0  4843.2      .1       0
  4983.5     .07       0  4989.5      .1       0  5185.6     .05       0
  5190.2      .1       0  5601.1     .16       0  5630.9      .1       0
  5731.1     .16       0  5831.4      .1       0
Bank Sta=4905.7,5227.7
XS Rating Curve= 0 ,0
Exp/Cntr=0.3,0.1

Type RM Length L Ch R = 1 ,26665   ,987,987,987
BEGIN DESCRIPTION:
Mapping XS 82aa873b
END DESCRIPTION:
XS GIS Cut Line= 3
      2869282.75     10095907.71      2868391.15      10095991.3
      2867666.79     10096395.27
#Sta/Elev= 30
  4350.4 1298.83  4404.9 1296.16    4424  1297.4  4469.4 1301.52  4535.5 1296.36
  4692.2 1274.25  4791.7 1263.17  4826.8  1258.8  4856.9 1253.55    4884 1251.91
  4886.8 1251.41    4890 1251.91  4891.2 1251.92  4897.7 1252.12  4990.7 1252.61
  5047.7  1255.9  5128.1 1253.62  5188.3 1258.82  5238.6 1260.85  5301.4 1273.26
  5382.5  1284.2  5500.9 1295.26  5550.5 1306.55  5588.2 1321.54  5788.6 1343.23
  5815.6 1347.67  5875.2 1351.89  5905.7 1353.65    5991 1358.49  6075.3 1364.27
#Mann= 13 ,-1 , 0
  4350.4     .05       0    4424      .1       0  4692.2     .16       0
  4791.7     .05       0    4884     .07       0    4890     .05       0
  4891.2     .16       0  4897.7     .05       0  4990.7      .1       0
  5788.6     .16       0  5875.2      .1       0  5905.7     .16       0
    5991     .05       0
Bank Sta=4826.8,5188.3
XS Rating Curve= 0 ,0
Exp/Cntr=0.3,0.1

Type RM Length L Ch R = 1 ,25678   ,1075,1075,1075
BEGIN DESCRIPTION:
NORTH GRAPE CREEK 28.0
END DESCRIPTION:
XS GIS Cut Line= 3
      2869018.06     10095155.45      2867917.51     10095517.65
       2867499.6     10096214.18
#Sta/Elev= 30
  4308.1 1290.21  4416.4  1288.5  4470.2 1288.53  4541.2 1285.65  4644.6 1267.74
  4781.4 1256.34  4855.1 1254.75  4907.8 1248.59  4999.5  1245.8  5002.2  1245.3
  5005.5  1245.8  5034.1  1246.4  5057.4 1250.93  5082.3 1252.05  5097.2 1254.69
  5202.5 1260.32  5301.3 1271.85  5406.7 1274.09  5481.2 1278.97  5555.7 1284.94
    5593  1287.6  5762.3 1299.87  5816.6 1304.05  5980.5 1319.94  6017.4  1330.9
  6038.8  1334.7  6075.8 1346.83  6112.7 1352.48  6263.9 1362.12    6279 1362.71
#Mann= 15 ,-1 , 0
  4308.1     .05       0  4416.4      .1       0  4470.2     .05       0
  4541.2      .1       0  4999.5     .07       0  5005.5      .1       0
  5082.3     .05       0  5301.3      .1       0  5406.7     .05       0
  5481.2      .1       0  5555.7     .16       0    5593      .1       0
  5762.3     .05       0  5816.6      .1       0  6263.9     .05       0
Bank Sta=4855.1,5097.2
XS Rating Curve= 0 ,0
Exp/Cntr=0.3,0.1

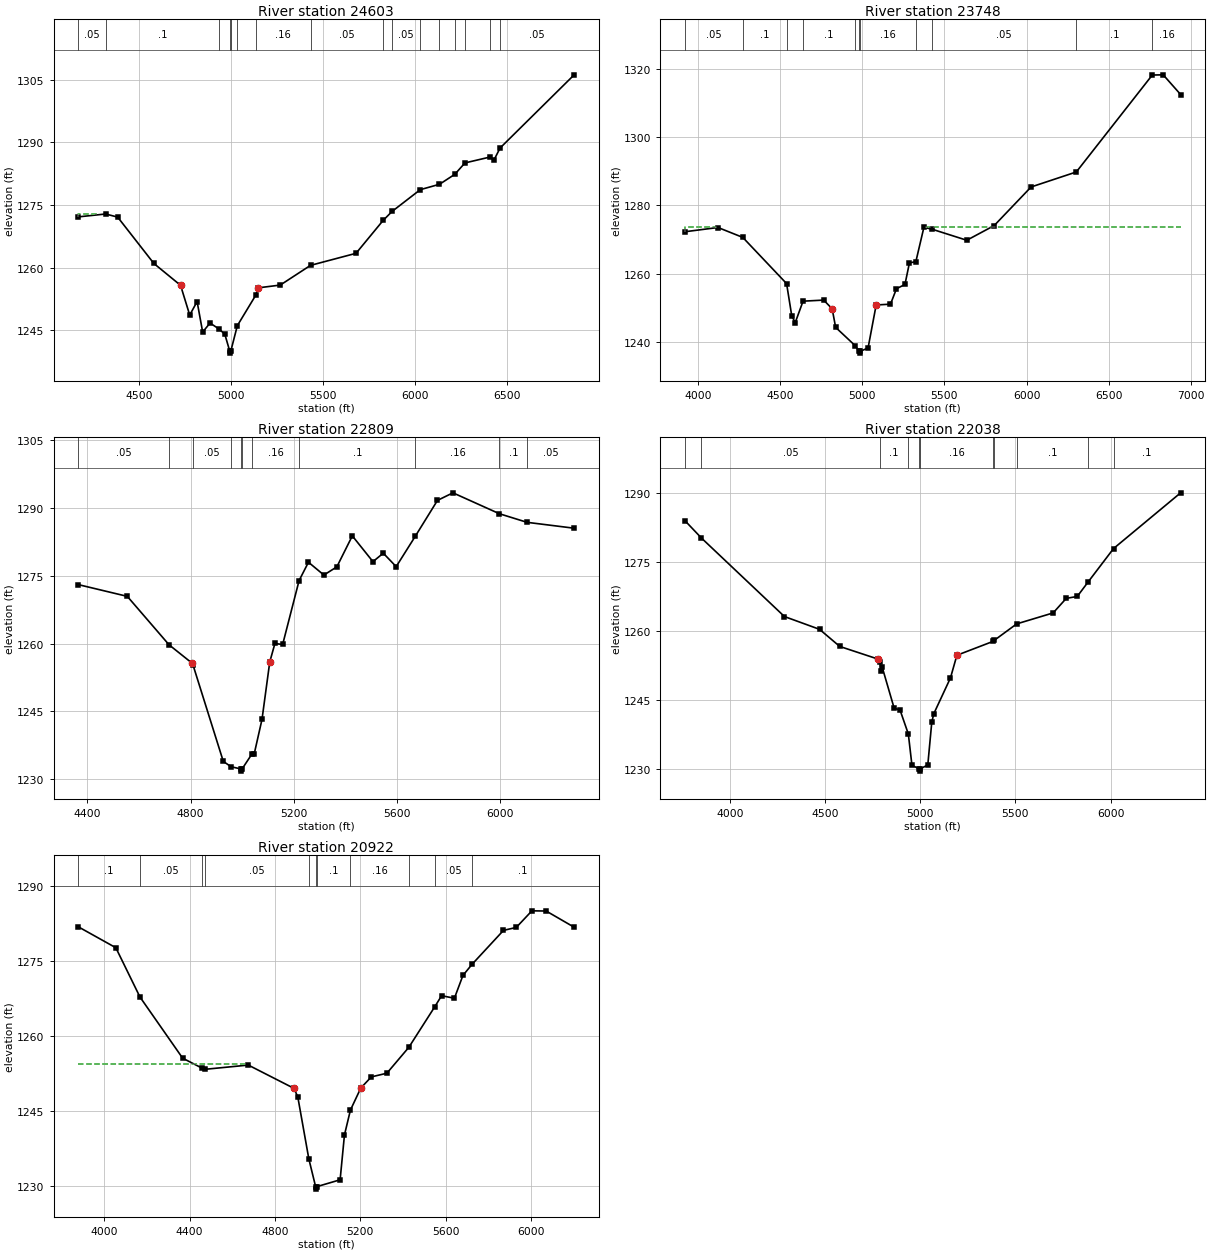
Type RM Length L Ch R = 1 ,24603   ,855,855,855
BEGIN DESCRIPTION:
NORTH GRAPE CREEK 26.0
END DESCRIPTION:
XS GIS Cut Line= 3
      2868781.22     10094389.27      2866844.85     10094528.58
       2866288.4     10095029.38
#Sta/Elev= 30
  4172.2 1272.15  4320.2 1272.84  4385.5  1272.1  4581.9 1260.99  4726.8 1255.75
  4776.5 1248.62  4816.6 1251.86  4846.7 1244.55  4886.8 1246.71  4935.6 1245.28
    4967 1244.02  4993.5    1240  4996.2  1239.5  4999.5    1240  5034.8 1246.08
  5134.1 1253.33  5147.5 1255.14  5267.8 1255.81  5431.8 1260.53  5678.8 1263.42
    5826 1271.31  5874.2 1273.45  6027.3 1278.67  6131.6 1279.96  6214.8 1282.35
  6269.7 1285.08  6407.8 1286.51  6426.3  1285.7  6460.3 1288.65  6862.2 1306.19
#Mann= 16 ,-1 , 0
  4172.2     .05       0  4320.2      .1       0  4935.6     .05       0
  4993.5    .035       0  4999.5     .05       0  5034.8      .1       0
  5134.1     .16       0  5431.8     .05       0    5826      .1       0
  5874.2     .05       0  6027.3     .16       0  6131.6     .05       0
  6214.8      .1       0  6269.7     .05       0  6407.8      .1       0
  6460.3     .05       0
#XS Ineff= 2 , 0
         4277.85  1272.8
Permanent Ineff=
       F       F
Bank Sta=4726.8,5147.5
XS Rating Curve= 0 ,0
Exp/Cntr=0.3,0.1

Type RM Length L Ch R = 1 ,23748   ,939,939,939
BEGIN DESCRIPTION:
NORTH GRAPE CREEK 25.0
END DESCRIPTION:
XS GIS Cut Line= 2
      2868962.29     10094208.16      2866413.26     10092592.38
#Sta/Elev= 30
  3919.8 1272.27  4121.9 1273.52  4272.7 1270.62  4539.4 1257.07    4571 1247.57
  4592.2 1245.65  4639.5 1251.92  4765.1 1252.24  4816.8 1249.68  4837.9 1244.25
    4957 1238.87  4980.7 1237.19  4983.4 1236.69  4986.7 1237.19  5035.4 1238.22
  5084.6 1250.81  5171.8 1251.04  5208.2 1255.57  5259.9 1256.82    5287 1263.14
  5326.2 1263.51  5375.2 1273.58  5425.5 1273.01  5636.2 1269.78  5803.1 1274.09
  6027.6  1285.4  6302.9  1289.8  6765.3 1318.22  6831.8 1318.28  6937.8 1312.51
#Mann= 11 ,-1 , 0
  3919.8     .05       0  4272.7      .1       0  4539.4     .05       0
  4639.5      .1       0    4957     .16       0  4980.7     .07       0
  4986.7     .16       0  5326.2      .1       0  5425.5     .05       0
  6302.9      .1       0  6765.3     .16       0
#XS Ineff= 2 , 0
         4108.05 1273.77 5387.71         1273.64
Permanent Ineff=
       F       F
Bank Sta=4816.8,5084.6
XS Rating Curve= 0 ,0
Exp/Cntr=0.3,0.1

Type RM Length L Ch R = 1 ,22809   ,771,771,771
BEGIN DESCRIPTION:
NORTH GRAPE CREEK 35.0
END DESCRIPTION:
XS GIS Cut Line= 3
      2868934.88     10094162.13      2868878.73     10093706.67
      2868892.66     10092243.94
#Sta/Elev= 30
  4364.8    1273  4554.6 1270.41  4716.4 1259.72  4806.5 1255.63  4809.2 1255.28
  4926.6 1233.99  4957.1  1232.8  4993.7 1232.34  4996.4 1231.84  4999.7 1232.34
  5036.7 1235.54  5046.7  1235.7  5076.7 1243.27  5106.7 1255.93  5126.7 1260.01
  5156.7 1259.79  5220.4  1273.9  5256.7 1277.94  5316.5 1275.12  5366.7 1276.92
  5426.7 1283.76  5506.7 1278.07  5546.7 1279.94  5596.7 1276.97  5671.5 1283.74
  5756.7 1291.59  5816.7 1293.26    5997 1288.64  6103.9 1286.75  6286.5 1285.45
#Mann= 11 ,-1 , 0
  4364.8     .05       0  4716.4      .1       0  4809.2     .05       0
  4957.1      .1       0  4993.7     .07       0  4999.7      .1       0
  5036.7     .16       0  5220.4      .1       0  5671.5     .16       0
    5997      .1       0  6103.9     .05       0
Bank Sta=4806.5,5106.7
XS Rating Curve= 0 ,0
Exp/Cntr=0.3,0.1

Type RM Length L Ch R = 1 ,22038   ,1116,1116,1116
BEGIN DESCRIPTION:
NORTH GRAPE CREEK 24.0
END DESCRIPTION:
XS GIS Cut Line= 3
      2869268.78     10094960.45       2869728.5      10093358.4
      2869436.28     10092467.82
#Sta/Elev= 30
  3764.1  1284.1  3851.5 1280.29  4287.4  1263.2  4471.6 1260.42    4578 1256.69
  4780.2 1253.92  4789.2 1253.38    4796 1251.45  4801.2 1252.12  4863.5 1243.26
  4894.7 1242.83  4938.1 1237.63  4957.1  1230.8  4995.7 1230.05  4998.5 1229.55
  5001.7 1230.05  5040.3 1230.91  5061.1 1240.16  5071.5 1242.02  5159.4 1249.85
  5193.1 1254.77  5382.2 1257.78  5389.1 1258.01  5507.1  1261.6  5698.6 1263.99
  5767.5 1267.16  5825.1 1267.57  5881.4 1270.68  6015.8    1278  6368.1 1290.13
#Mann= 11 ,-1 , 0
  3764.1      .1       0  3851.5     .05       0  4789.2      .1       0
  4938.1     .16       0  4995.7     .07       0  5001.7     .16       0
  5382.2      .1       0  5389.1     .16       0  5507.1      .1       0
  5881.4     .16       0  6015.8      .1       0
Bank Sta=4780.2,5193.1
XS Rating Curve= 0 ,0
Exp/Cntr=0.3,0.1

Type RM Length L Ch R = 1 ,20922   ,1178,1178,1178
BEGIN DESCRIPTION:
NORTH GRAPE CREEK 23.0
END DESCRIPTION:
XS GIS Cut Line= 3
      2870313.59     10095169.35       2870773.3     10093637.02
      2870801.16     10092912.66
#Sta/Elev= 30
  3878.5  1281.9  4054.3 1277.72  4167.4 1267.86  4367.6 1255.62  4456.1 1253.68
  4474.2  1253.4  4675.5 1254.24  4889.6 1249.58  4907.5 1247.86  4959.3 1235.45
    4991 1229.92  4993.7 1229.42    4997 1229.92  5105.9 1231.29  5126.2 1240.25
  5154.2 1245.23  5202.8 1249.64    5252 1251.87  5325.1 1252.61    5428 1257.79
  5550.3 1265.95  5581.7 1268.12  5641.7 1267.61  5681.7 1272.17  5724.3 1274.39
  5871.9 1281.19  5931.9 1281.78  6005.1  1285.1    6072 1285.06  6203.2 1281.82
#Mann= 11 ,-1 , 0
  3878.5      .1       0  4167.4     .05       0  4456.1      .1       0
  4474.2     .05       0  4959.3      .1       0    4991     .07       0
    4997      .1       0  5154.2     .16       0    5428      .1       0
  5550.3     .05       0  5724.3      .1       0
#XS Ineff= 2 , 0
         4661.63 1254.38
Permanent Ineff=
       F       F
Bank Sta=4889.6,5202.8
XS Rating Curve= 0 ,0
Exp/Cntr=0.3,0.1