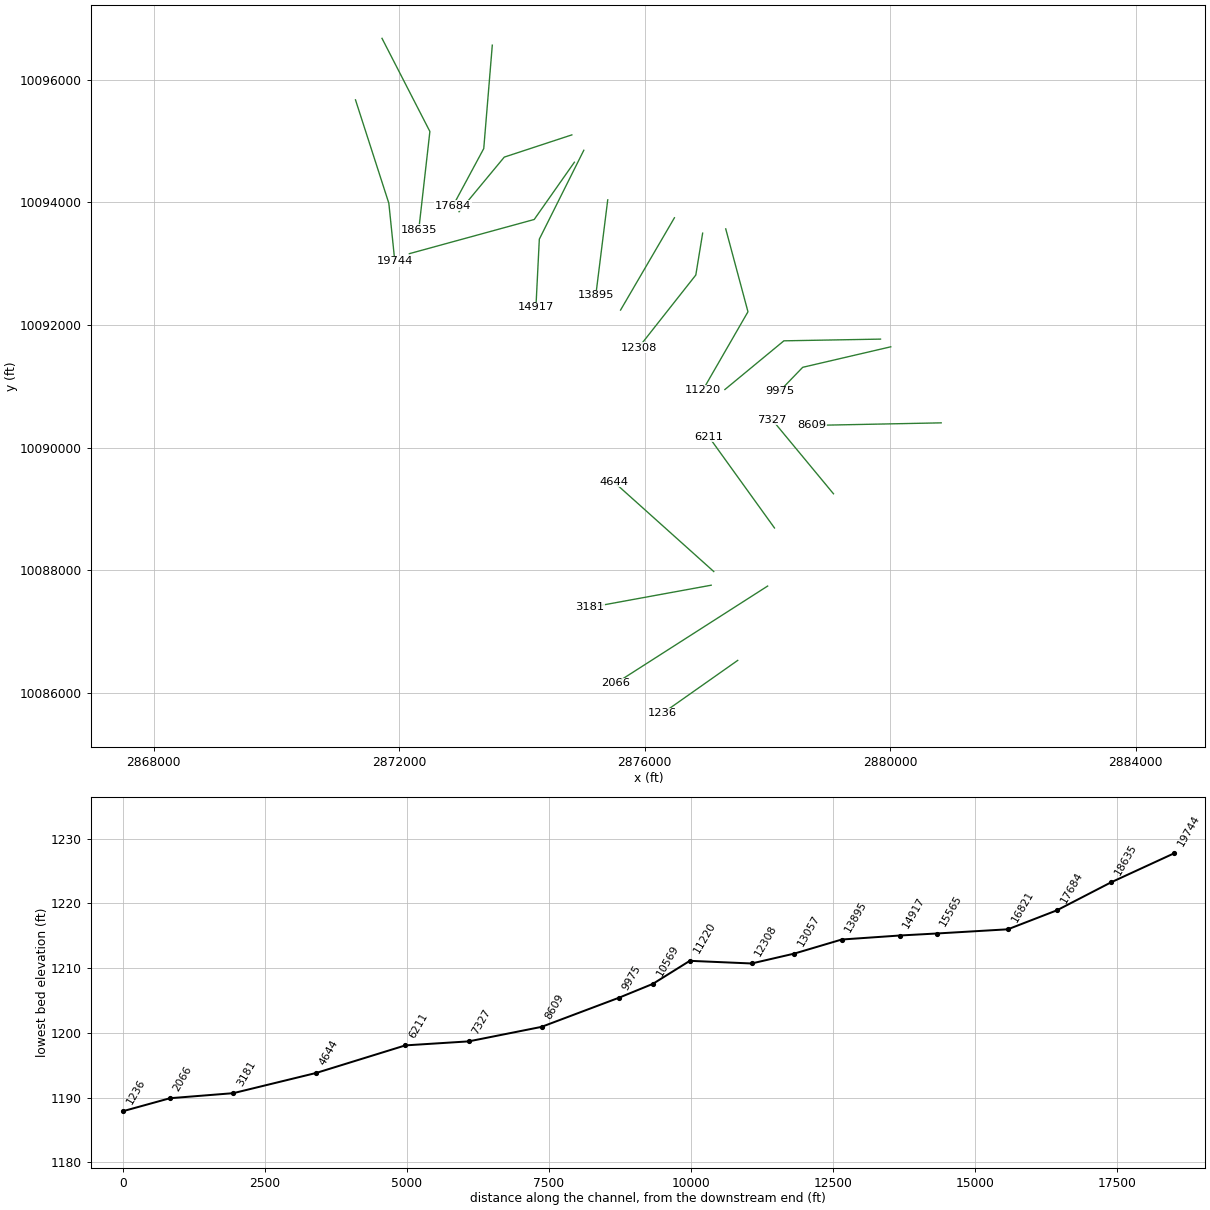
HEC-RAS study NORTH GRAPE CREEK.prj: NORTH GRAPE CREEK Base Level Engineering

--- NORTH GRAPE CREEK.g01 (geometry) --- (continued)

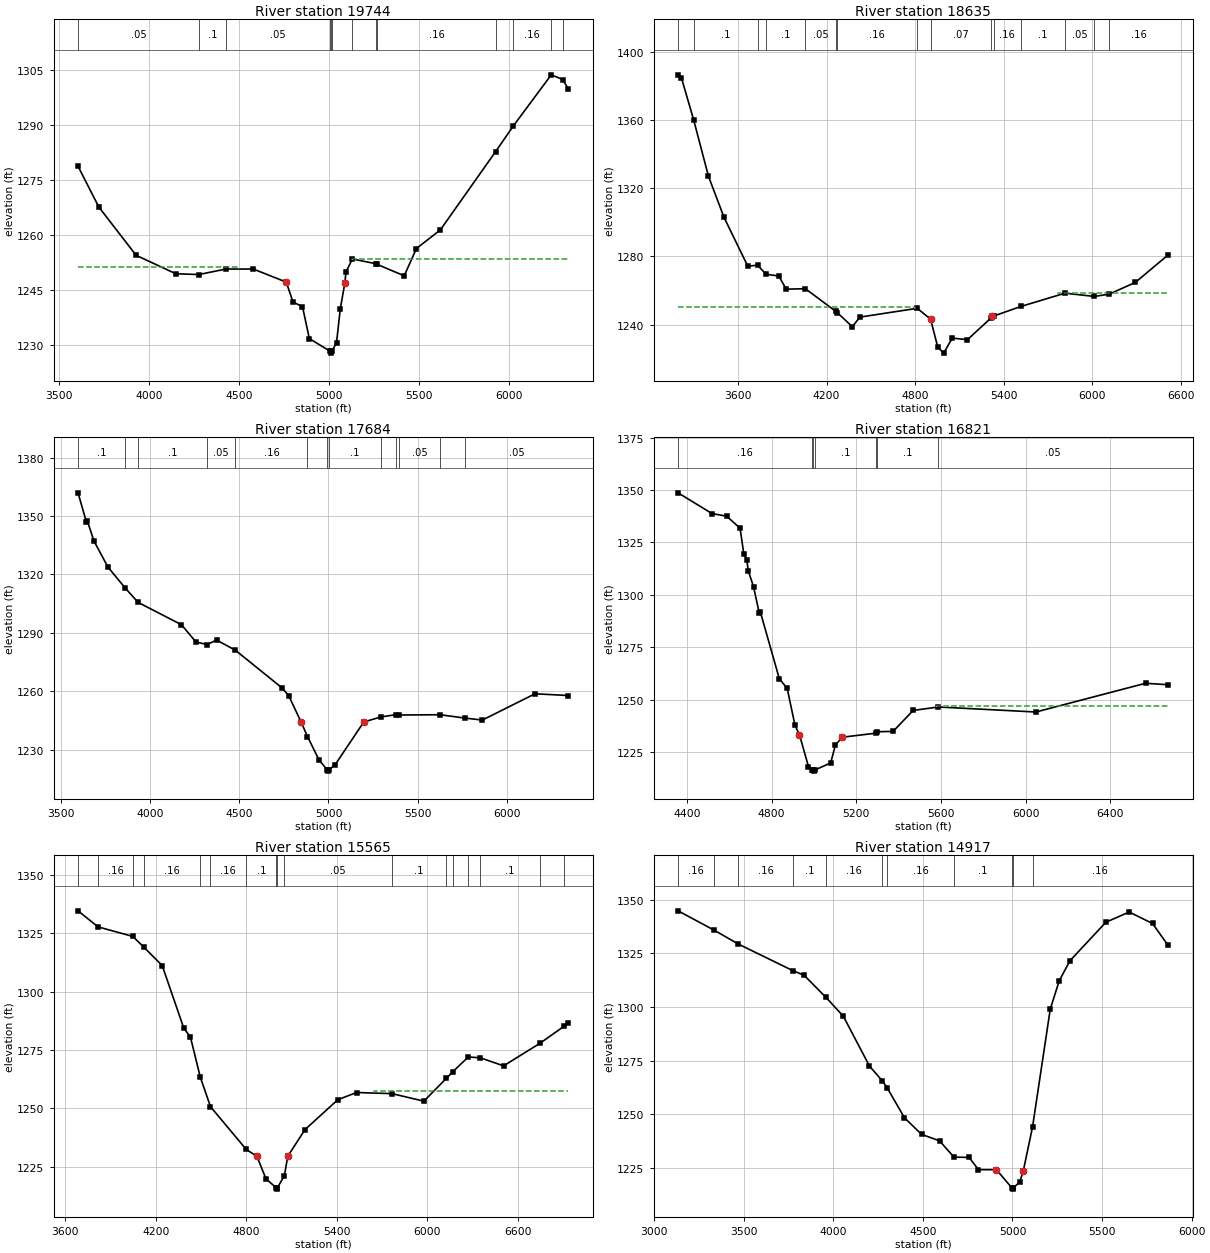
Type RM Length L Ch R = 1 ,19744   ,1109,1109,1109
BEGIN DESCRIPTION:
NORTH GRAPE CREEK 21.0
END DESCRIPTION:
XS GIS Cut Line= 3
      2871288.74     10095670.85      2871832.03     10093985.28
       2871929.5     10093038.34
#Sta/Elev= 30
  3606.2 1278.76  3721.7 1267.63  3928.9 1254.44  4149.5  1249.4  4277.6 1249.19
    4428 1250.69  4580.3 1250.69  4763.3 1247.12  4800.9 1241.65  4853.5 1240.44
  4891.6 1231.69  5008.1 1228.22  5010.8 1227.72  5014.1 1228.22  5018.9 1228.41
  5042.6 1230.55  5063.6 1239.83  5089.2 1246.95  5095.1 1249.92  5131.1 1253.44
  5264.6 1252.11  5268.6 1251.96  5418.9 1248.84  5486.6 1256.29    5620  1261.4
  5926.9 1282.78  6025.3 1289.78  6235.9 1303.74  6299.8 1302.46  6329.1 1299.99
#Mann= 13 ,-1 , 0
  3606.2     .05       0  4277.6      .1       0    4428     .05       0
  5008.1    .035       0  5014.1     .05       0  5018.9      .1       0
  5131.1     .16       0  5264.6      .1       0  5268.6     .16       0
  5926.9      .1       0  6025.3     .16       0  6235.9      .1       0
  6299.8     .16       0
#XS Ineff= 2 , 0
         4498.32 1251.22 5127.67         1253.51
Permanent Ineff=
       F       F
Bank Sta=4763.3,5089.2
XS Rating Curve= 0 ,0
Exp/Cntr=0.3,0.1

Type RM Length L Ch R = 1 ,18635   ,951,951,951
BEGIN DESCRIPTION:
NORTH GRAPE CREEK 20.0
END DESCRIPTION:
XS GIS Cut Line= 3
      2871720.56     10096673.93       2872500.7     10095155.46
       2872319.6     10093553.41
#Sta/Elev= 30
  3193.9 1386.62  3216.6 1384.86  3299.5 1360.18  3399.7  1327.1    3505 1302.97
  3666.3 1274.27  3732.2 1274.87  3790.1 1269.56  3876.5 1268.51  3926.4  1260.8
  4056.7 1261.05  4261.3 1247.81  4273.1 1246.98  4374.6 1238.72  4425.4 1244.38
    4814 1249.55  4904.4 1243.21  4953.1 1226.81  4993.1 1223.24  5051.6 1232.06
  5154.4 1231.13  5315.4 1243.99    5321 1244.91  5331.7 1244.99  5517.1 1250.66
  5815.4 1258.44    6013 1256.53  6113.7 1257.83  6291.6 1264.75  6513.3 1280.86
#Mann= 15 ,-1 , 0
  3193.9     .16       0  3299.5      .1       0  3732.2     .16       0
  3790.1      .1       0  4056.7     .05       0  4261.3      .1       0
  4273.1     .16       0    4814      .1       0  4904.4     .07       0
  5315.4      .1       0  5331.7     .16       0  5517.1      .1       0
  5815.4     .05       0    6013      .1       0  6113.7     .16       0
#XS Ineff= 2 , 0
         4802.17 1250.05 5769.76         1258.81
Permanent Ineff=
       F       F
Bank Sta=4904.4,5321
XS Rating Curve= 0 ,0
Exp/Cntr=0.3,0.1

Type RM Length L Ch R = 1 ,17684   ,863,863,863
BEGIN DESCRIPTION:
NORTH GRAPE CREEK 19.0
END DESCRIPTION:
XS GIS Cut Line= 3
      2873517.64     10096562.49      2873378.33     10094876.84
      2872876.85     10093943.53
#Sta/Elev= 30
    3594 1361.98  3641.3 1346.87  3646.3 1347.55  3683.1 1337.25  3762.2 1323.77
  3860.1 1312.91  3931.2 1305.67  4174.7 1294.18  4255.9 1285.33    4319 1283.97
  4371.8 1286.32  4477.3 1281.08  4739.5  1261.7  4776.8 1257.71    4847 1244.05
  4882.1 1236.72  4947.4 1224.62  4994.5 1219.43  4997.3 1218.93  5000.5 1219.43
  5037.7 1222.26  5198.2 1244.18  5293.4 1246.77  5379.4 1247.96  5397.4 1247.78
    5626 1247.92  5768.2 1246.17  5864.2 1245.18  6159.6 1258.69  6344.9  1257.8
#Mann= 13 ,-1 , 0
    3594      .1       0  3860.1     .16       0  3931.2      .1       0
    4319     .05       0  4477.3     .16       0  4882.1      .1       0
  4994.5     .07       0  5000.5      .1       0  5293.4     .05       0
  5379.4      .1       0  5397.4     .05       0    5626      .1       0
  5768.2     .05       0
Bank Sta=4847,5198.2
XS Rating Curve= 0 ,0
Exp/Cntr=0.3,0.1

Type RM Length L Ch R = 1 ,16821   ,1256,1256,1256
BEGIN DESCRIPTION:
NORTH GRAPE CREEK 18.0
END DESCRIPTION:
XS GIS Cut Line= 3
      2874813.22     10095099.75      2873712.66     10094737.54
       2872975.5     10093847.37
#Sta/Elev= 30
  4358.4 1348.66  4518.8 1338.76  4587.7 1337.53  4651.2  1331.8  4668.7 1319.71
    4683 1316.75  4689.8 1311.54  4714.8 1303.95  4741.3 1291.56  4746.6 1292.02
  4836.7 1260.02  4873.7 1255.47  4910.8 1237.79  4931.9  1233.3  4974.3  1218.2
  4990.5 1216.67  4997.9  1216.5  5000.6    1216  5003.9  1216.5  5079.3 1219.92
  5101.5 1228.43  5133.3 1232.16  5294.1  1234.1    5300 1234.79  5374.1 1234.94
  5468.8 1244.93  5588.4 1246.58  6048.3 1244.18  6566.7 1257.88  6672.8 1257.18
#Mann= 7 ,-1 , 0
  4358.4     .16       0  4990.5      .1       0  4997.9     .07       0
  5003.9      .1       0  5294.1     .05       0    5300      .1       0
  5588.4     .05       0
#XS Ineff= 2 , 0
                         5574.46         1246.97
Permanent Ineff=
       F       F
Bank Sta=4931.9,5133.3
XS Rating Curve= 0 ,0
Exp/Cntr=0.3,0.1

Type RM Length L Ch R = 1 ,15565   ,648,648,648
BEGIN DESCRIPTION:
NORTH GRAPE CREEK 17.0
END DESCRIPTION:
XS GIS Cut Line= 3
      2874854.99     10094653.98      2874200.24      10093720.6
      2872166.32     10093163.36
#Sta/Elev= 30
  3685.2 1334.63    3818 1327.74  4048.3 1323.67  4122.6    1319  4243.2 1311.19
  4386.1  1284.4  4430.6 1280.49  4495.6 1263.41  4563.5 1250.68  4800.4 1232.38
    4872 1229.36  4930.9 1219.81  5000.4 1215.85  5003.2 1215.35  5006.4 1215.85
  5053.3 1221.08    5076 1229.45  5190.1 1240.86  5407.8 1253.68  5532.2 1256.76
  5767.1 1256.28  5978.1 1253.05  6127.4 1262.81  6171.7 1265.75  6272.8 1271.99
  6353.8 1271.61  6506.9 1268.18  6747.9 1277.84  6906.1 1285.08  6934.2 1286.53
#Mann= 17 ,-1 , 0
  3685.2      .1       0    3818     .16       0  4048.3      .1       0
  4122.6     .16       0  4495.6      .1       0  4563.5     .16       0
  4800.4      .1       0  5000.4     .07       0  5006.4      .1       0
  5053.3     .05       0  5767.1      .1       0  6127.4     .16       0
  6171.7      .1       0  6272.8     .16       0  6353.8      .1       0
  6747.9     .16       0  6906.1      .1       0
#XS Ineff= 2 , 0
                         5645.16         1257.29
Permanent Ineff=
       F       F
Bank Sta=4872,5076
XS Rating Curve= 0 ,0
Exp/Cntr=0.3,0.1

Type RM Length L Ch R = 1 ,14917   ,1022,1022,1022
BEGIN DESCRIPTION:
NORTH GRAPE CREEK 16.0
END DESCRIPTION:
XS GIS Cut Line= 3
      2875008.22     10094848.99      2874283.82     10093400.19
      2874228.17     10092287.19
#Sta/Elev= 30
    3134 1344.88  3335.3 1335.85  3469.8  1329.4    3773 1317.03  3838.2 1314.76
  3959.4 1304.49  4056.2  1295.7    4202 1272.46  4273.3 1265.59  4300.3  1262.4
  4397.2 1248.34  4492.7 1240.59  4592.9 1237.58  4673.7 1229.96  4758.1 1229.85
  4810.3 1224.12  4910.5  1224.1  4997.6 1215.54  5000.3 1215.04  5003.6 1215.54
  5040.6 1218.35  5060.6 1223.62  5112.3 1244.17  5210.8    1299  5260.9 1312.24
    5321 1321.61  5521.2 1339.55  5651.4 1344.33  5781.5 1338.97  5868.2 1328.79
#Mann= 11 ,-1 , 0
    3134     .16       0  3335.3      .1       0  3469.8     .16       0
    3773      .1       0  3959.4     .16       0  4273.3      .1       0
  4300.3     .16       0  4673.7      .1       0  4997.6     .07       0
  5003.6      .1       0  5112.3     .16       0
Bank Sta=4910.5,5060.6
XS Rating Curve= 0 ,0
Exp/Cntr=0.3,0.1

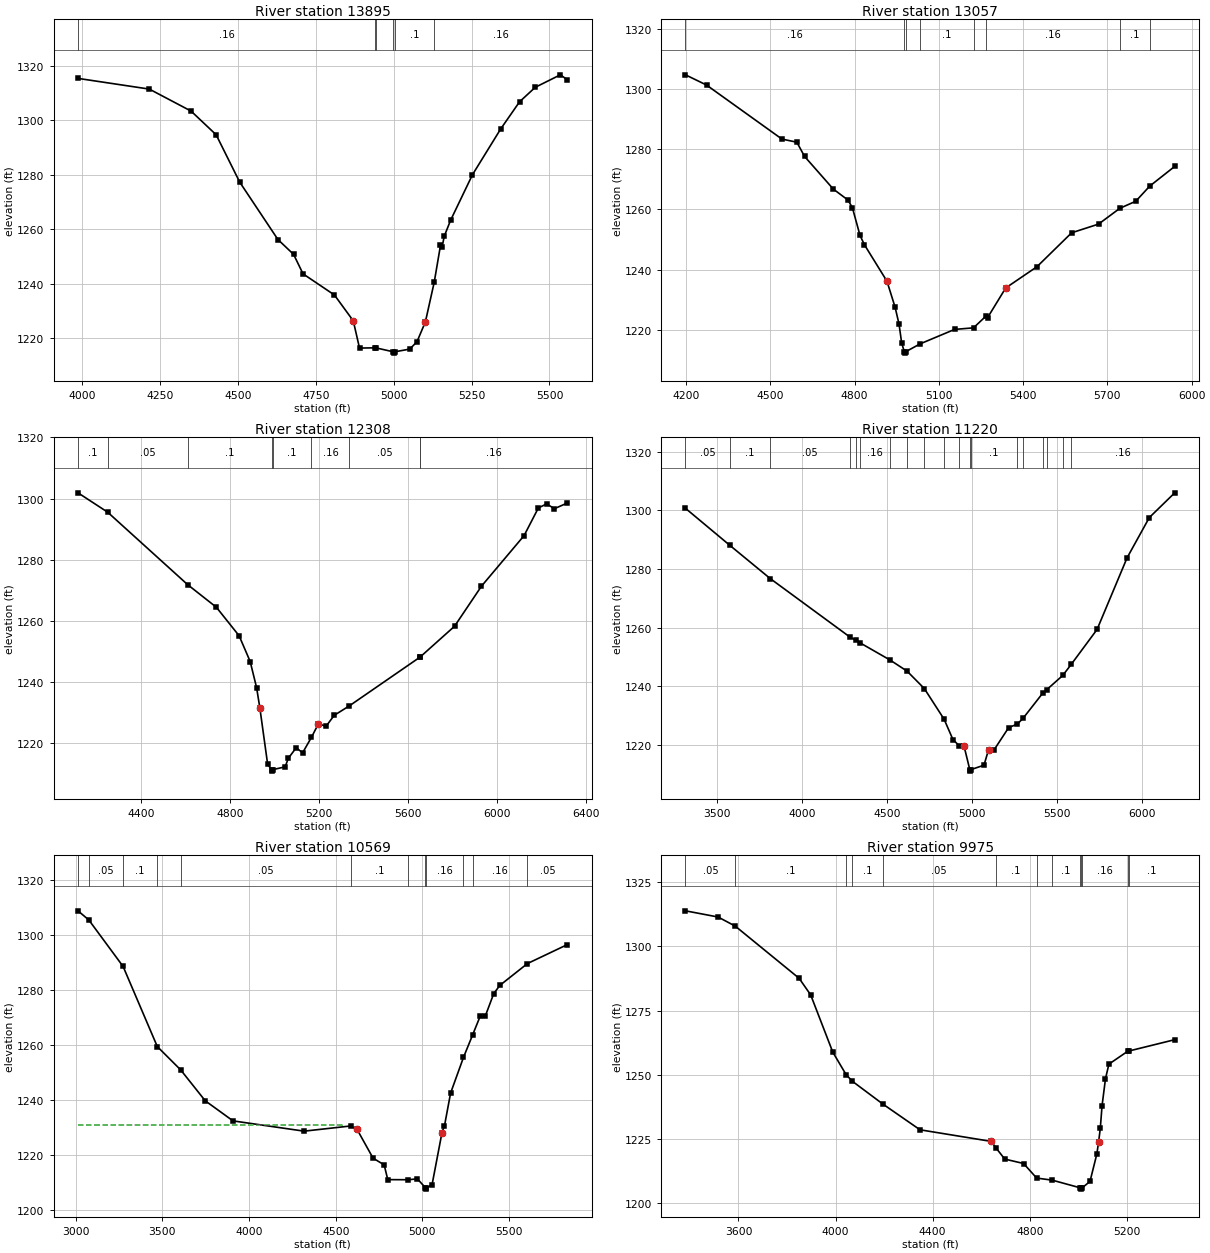
Type RM Length L Ch R = 1 ,13895   ,838,838,838
BEGIN DESCRIPTION:
NORTH GRAPE CREEK 15.0
END DESCRIPTION:
XS GIS Cut Line= 2
      2875398.27     10094040.96      2875203.36     10092481.69
#Sta/Elev= 30
  3985.7 1315.38  4214.7 1311.45  4348.8 1303.37  4429.4 1294.66    4505 1277.28
  4627.9 1256.16  4678.3 1250.69  4708.5 1243.55  4809.3 1235.79  4869.8  1226.3
  4889.9 1216.28  4939.8 1216.37  4942.4 1216.36  4997.8 1214.92  5000.5 1214.42
  5003.8 1214.92  5051.2  1215.9  5074.4 1218.59  5101.5 1225.92  5129.9  1240.5
    5150 1254.02    5155 1253.31    5162 1257.35  5182.2 1263.18  5252.7 1279.99
  5343.4 1296.81  5403.9 1306.77  5454.3  1312.1  5534.9 1316.69  5557.1 1314.93
#Mann= 6 ,-1 , 0
  3985.7     .16       0  4939.8     .05       0  4942.4      .1       0
  4997.8     .07       0  5003.8      .1       0  5129.9     .16       0
Bank Sta=4869.8,5101.5
XS Rating Curve= 0 ,0
Exp/Cntr=0.3,0.1

Type RM Length L Ch R = 1 ,13057   ,749,749,749
BEGIN DESCRIPTION:
NORTH GRAPE CREEK 14.0
END DESCRIPTION:
XS GIS Cut Line= 2
      2876484.84     10093748.43      2875607.25     10092243.98
#Sta/Elev= 30
    4198 1304.73  4272.9 1301.34  4541.5 1283.37  4594.5 1282.34  4621.8 1277.63
  4724.4 1266.75  4776.4 1263.12  4792.1 1260.62  4819.4 1251.35  4835.1 1248.25
  4915.3 1236.14  4944.4 1227.46  4958.3 1221.87  4967.5 1215.72  4976.8 1212.74
  4979.6 1212.24  4982.8 1212.74  5033.4 1215.32    5156 1220.12  5223.4 1220.64
  5266.9 1224.47  5273.4 1224.01    5338 1233.89  5449.5 1240.97  5572.7 1252.23
  5668.6 1255.12  5744.2 1260.36  5801.1 1262.72  5850.7 1267.74  5939.7 1274.29
#Mann= 8 ,-1 , 0
    4198     .16       0  4976.8     .07       0  4982.8     .16       0
  5033.4      .1       0  5223.4     .05       0  5266.9     .16       0
  5744.2      .1       0  5850.7     .16       0
Bank Sta=4915.3,5338
XS Rating Curve= 0 ,0
Exp/Cntr=0.3,0.1

Type RM Length L Ch R = 1 ,12308   ,1088,1088,1088
BEGIN DESCRIPTION:
NORTH GRAPE CREEK 13.0
END DESCRIPTION:
XS GIS Cut Line= 3
      2876944.58     10093497.74      2876833.13     10092815.11
      2875899.78       10091631.
#Sta/Elev= 30
  4115.4 1301.87  4248.7 1295.53  4608.1 1271.81  4737.5 1264.39  4839.7 1255.05
  4889.4 1246.62  4918.3 1238.06  4932.8 1231.48    4968 1212.94  4985.8 1211.22
  4988.6 1210.72  4991.8 1211.22  5046.6 1212.12  5061.1 1214.95  5096.3 1218.37
  5125.2 1216.73    5165  1221.8  5195.7 1226.15    5231 1225.45  5267.2 1228.99
  5335.7 1232.12    5651 1247.96  5653.5 1248.09  5808.2 1258.17  5929.3  1271.3
  6120.8 1287.86    6185 1296.92    6222 1298.24  6257.2 1296.69  6314.8 1298.51
#Mann= 9 ,-1 , 0
  4115.4      .1       0  4248.7     .05       0  4608.1      .1       0
  4985.8     .07       0  4991.8      .1       0    5165     .16       0
  5335.7     .05       0    5651      .1       0  5653.5     .16       0
Bank Sta=4932.8,5195.7
XS Rating Curve= 0 ,0
Exp/Cntr=0.3,0.1

Type RM Length L Ch R = 1 ,11220   ,651,651,651
BEGIN DESCRIPTION:
NORTH GRAPE CREEK 12.0
END DESCRIPTION:
XS GIS Cut Line= 3
      2877320.69     10093567.41       2877682.9     10092216.09
      2876944.57     10090934.47
#Sta/Elev= 30
  3315.2 1300.72  3576.2  1288.1  3813.6 1276.78  4283.5  1256.8  4319.3 1255.68
  4343.5 1254.82  4518.2 1249.02  4618.8 1245.22  4720.3 1239.28  4836.7 1228.82
  4888.8 1221.88  4924.9 1219.81  4953.5 1219.78  4987.8 1211.63  4990.6 1211.13
  4993.8 1211.63  5071.3 1213.16  5098.6 1218.49  5130.2 1218.34  5216.4 1225.96
  5267.8 1227.18    5302  1229.2  5418.4 1237.82  5440.8 1238.91  5534.7 1243.75
  5584.8 1247.54  5736.5 1259.42  5913.2 1283.86  6044.1 1297.58  6193.3    1306
#Mann= 19 ,-1 , 0
  3315.2     .05       0  3576.2      .1       0  3813.6     .05       0
  4283.5      .1       0  4319.3     .05       0  4343.5     .16       0
  4518.2     .05       0  4618.8     .16       0  4720.3      .1       0
  4836.7     .16       0  4924.9      .1       0  4987.8     .07       0
  4993.8      .1       0  5267.8     .05       0    5302     .16       0
  5418.4     .05       0  5440.8     .16       0  5534.7      .1       0
  5584.8     .16       0
Bank Sta=4953.5,5098.6
XS Rating Curve= 0 ,0
Exp/Cntr=0.3,0.1

Type RM Length L Ch R = 1 ,10569   ,594,594,594
BEGIN DESCRIPTION:
NORTH GRAPE CREEK 11.0
END DESCRIPTION:
XS GIS Cut Line= 3
      2879842.16     10091770.31      2878267.99     10091742.45
        2877307.     10090948.59
#Sta/Elev= 30
  3014.1 1308.63  3076.8 1305.29  3274.1 1288.43  3471.3 1259.34  3606.4 1250.85
  3747.9 1239.64  3907.9 1232.35    4318 1228.62  4585.4  1230.5    4623 1229.27
  4715.5 1218.81  4779.4 1216.38  4800.2 1211.02  4918.9 1210.98  4970.9  1211.3
  5017.4 1208.07  5020.1 1207.57  5023.4 1208.07  5055.5 1209.15  5112.9 1228.12
  5127.2 1230.57  5162.4 1242.43  5236.8 1255.42  5289.7 1263.61    5333 1270.36
  5361.7 1270.28  5411.2 1278.57  5446.3 1281.55  5605.4 1289.48    5835 1296.35
#Mann= 12 ,-1 , 0
  3014.1      .1       0  3076.8     .05       0  3274.1      .1       0
  3471.3     .16       0  3606.4     .05       0  4585.4      .1       0
  4918.9     .16       0  5017.4     .07       0  5023.4     .16       0
  5236.8     .05       0  5289.7     .16       0  5605.4     .05       0
#XS Ineff= 2 , 0
         4538.15 1230.93
Permanent Ineff=
       F       F
Bank Sta=4623,5112.9
XS Rating Curve= 0 ,0
Exp/Cntr=0.3,0.1

Type RM Length L Ch R = 1 ,9975    ,1366,1366,1366
BEGIN DESCRIPTION:
NORTH GRAPE CREEK 10.0
END DESCRIPTION:
XS GIS Cut Line= 3
      2880009.28     10091644.92      2878574.46      10091310.6
      2878198.35     10090920.55
#Sta/Elev= 30
  3381.9 1313.88  3516.2 1311.47  3586.8 1307.93  3849.9  1287.6  3897.6 1281.13
  3988.5 1258.85  4043.6 1250.04  4069.4 1247.46  4193.9 1238.66  4347.9 1228.56
  4641.8 1224.03  4660.3 1221.56    4697 1217.15  4774.6 1215.42  4828.3 1209.75
  4892.8 1208.93    5007 1205.97  5009.8 1205.94  5012.6 1205.44  5015.8 1205.94
  5048.1 1208.44  5076.3 1219.14  5083.6 1223.88  5090.5 1229.11  5097.7 1237.89
  5111.9 1248.49    5126 1254.15  5205.6 1259.29  5209.2 1259.28    5397 1263.67
#Mann= 13 ,-1 , 0
  3381.9     .05       0  3586.8      .1       0  4043.6     .05       0
  4069.4      .1       0  4193.9     .05       0  4660.3      .1       0
  4828.3     .05       0  4892.8      .1       0    5007     .16       0
  5009.8     .07       0  5015.8     .16       0  5205.6     .05       0
  5209.2      .1       0
Bank Sta=4641.8,5083.6
XS Rating Curve= 0 ,0
Exp/Cntr=0.3,0.1

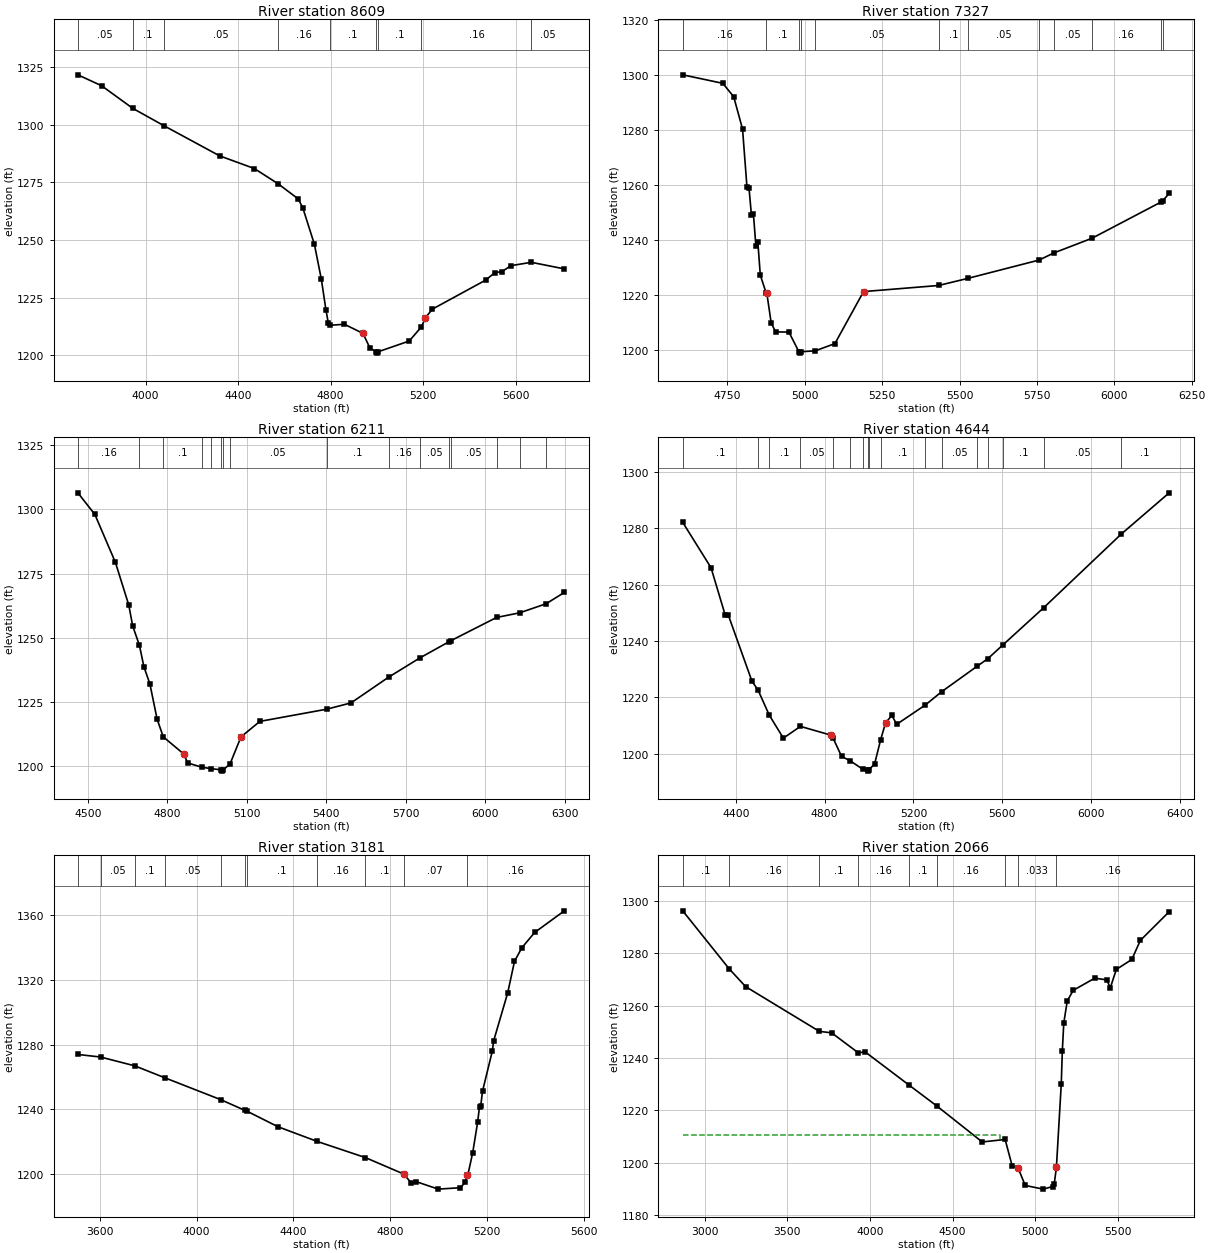
Type RM Length L Ch R = 1 ,8609    ,1282,1282,1282
BEGIN DESCRIPTION:
NORTH GRAPE CREEK 9.0
END DESCRIPTION:
XS GIS Cut Line= 2
      2880831.28     10090405.11      2878727.69     10090363.31
#Sta/Elev= 30
    3707 1321.63  3809.8 1316.89  3944.1 1307.11  4078.2 1299.62  4319.9  1286.5
    4470    1281  4572.2 1274.43    4660 1267.82    4680  1263.9    4730 1248.13
    4760 1233.01    4780 1219.62    4790 1214.14  4798.3 1213.02    4860 1213.44
  4940.1 1209.49  4970.1 1203.18  4997.1 1201.43  4999.8 1200.93  5003.1 1201.43
  5140.1 1206.18  5192.8  1212.3  5210.1 1216.24  5240.1    1220  5470.2 1232.57
  5510.2 1235.81  5541.7  1236.3  5580.2 1238.87  5668.3 1240.32    5811 1237.46
#Mann= 9 ,-1 , 0
    3707     .05       0  3944.1      .1       0  4078.2     .05       0
  4572.2     .16       0  4798.3      .1       0  4997.1     .07       0
  5003.1      .1       0  5192.8     .16       0  5668.3     .05       0
Bank Sta=4940.1,5210.1
XS Rating Curve= 0 ,0
Exp/Cntr=0.3,0.1

Type RM Length L Ch R = 1 ,7327    ,1116,1116,1116
BEGIN DESCRIPTION:
NORTH GRAPE CREEK 8.0
END DESCRIPTION:
XS GIS Cut Line= 2
      2879075.95     10089248.88      2878074.08     10090459.47
#Sta/Elev= 30
  4605.8 1300.12  4735.3 1297.02  4770.5 1292.14  4799.1 1280.34  4813.4 1259.15
  4819.9 1258.94  4827.8 1248.96  4834.3 1249.27  4842.1 1237.81  4848.6 1239.01
  4856.4 1227.14  4875.8 1220.44  4877.3  1220.7  4891.6 1209.68  4905.9 1206.44
  4948.9 1206.35  4981.1 1199.19  4983.8 1198.69  4987.1 1199.19    5034 1199.53
  5097.4 1202.16  5189.9 1221.12  5432.3 1223.34  5528.1 1225.97  5757.2 1232.62
    5805 1235.22  5928.3 1240.58  6149.4 1253.67  6155.7 1254.13  6177.2 1256.92
#Mann= 12 ,-1 , 0
  4605.8     .16       0  4875.8      .1       0  4981.1     .07       0
  4987.1      .1       0    5034     .05       0  5432.3      .1       0
  5528.1     .05       0  5757.2      .1       0    5805     .05       0
  5928.3     .16       0  6149.4      .1       0  6155.7     .16       0
Bank Sta=4877.3,5189.9
XS Rating Curve= 0 ,0
Exp/Cntr=0.3,0.1

Type RM Length L Ch R = 1 ,6211    ,1567,1567,1567
BEGIN DESCRIPTION:
NORTH GRAPE CREEK 7.0
END DESCRIPTION:
XS GIS Cut Line= 2
      2878114.76     10088691.62      2877042.75     10090181.29
#Sta/Elev= 30
  4462.7 1306.45  4526.9 1298.02  4604.4 1279.34  4654.8 1262.73  4669.5 1254.62
    4695 1247.05  4711.7 1238.77  4734.5 1232.01  4761.6 1218.32  4784.9 1211.42
  4862.2 1204.73  4876.9 1201.25  4930.1 1199.61  4964.6 1199.04    5004 1198.57
  5006.7 1198.07    5010 1198.57  5036.1  1200.7  5078.2 1211.42  5149.4 1217.44
    5401 1222.18  5493.1 1224.63  5635.3 1234.68  5752.8 1242.15  5862.8 1248.46
  5870.4 1248.89  6042.5 1257.92  6129.9 1259.73  6229.2 1263.25    6298 1267.66
#Mann= 16 ,-1 , 0
  4462.7     .16       0    4695     .05       0  4784.9      .1       0
  4930.1     .05       0  4964.6      .1       0    5004     .07       0
    5010      .1       0  5036.1     .05       0    5401      .1       0
  5635.3     .16       0  5752.8     .05       0  5862.8     .16       0
  5870.4     .05       0  6042.5      .1       0  6129.9     .05       0
  6229.2      .1       0
Bank Sta=4862.2,5078.2
XS Rating Curve= 0 ,0
Exp/Cntr=0.3,0.1

Type RM Length L Ch R = 1 ,4644    ,1463,1463,1463
BEGIN DESCRIPTION:
NORTH GRAPE CREEK 5.0
END DESCRIPTION:
XS GIS Cut Line= 2
      2877125.68     10087981.16      2875495.79     10089443.88
#Sta/Elev= 30
  4161.2 1282.11  4288.7    1266  4352.2 1249.27  4366.4 1249.21  4472.6 1225.79
  4500.7 1222.54  4550.7  1213.7  4614.3 1205.53  4691.2  1209.7  4826.9 1206.62
  4838.9 1205.42  4876.3 1199.05  4914.4 1197.52  4972.3 1194.47  4993.6 1194.32
  4996.4 1193.82  4999.6 1194.32    5025 1196.36  5052.3 1204.97  5074.4 1210.97
  5102.8 1213.57  5124.5 1210.43  5253.4 1217.29  5328.1 1222.07    5485 1230.95
  5534.5  1233.7  5603.9  1238.7  5786.8 1251.85    6135 1277.91  6351.2 1292.58
#Mann= 17 ,-1 , 0
  4161.2      .1       0  4500.7     .05       0  4550.7      .1       0
  4691.2     .05       0  4838.9      .1       0  4914.4     .05       0
  4972.3     .16       0  4993.6     .07       0  4999.6     .16       0
  5052.3      .1       0  5253.4     .16       0  5328.1     .05       0
    5485      .1       0  5534.5     .05       0  5603.9      .1       0
  5786.8     .05       0    6135      .1       0
Bank Sta=4826.9,5074.4
XS Rating Curve= 0 ,0
Exp/Cntr=0.3,0.1

Type RM Length L Ch R = 1 ,3181    ,1115,1115,1115
BEGIN DESCRIPTION:
NORTH GRAPE CREEK 3.0
END DESCRIPTION:
XS GIS Cut Line= 2
      2877083.86     10087758.28      2875105.74     10087396.09
#Sta/Elev= 30
  3509.5 1273.91  3603.2 1272.33  3744.7 1266.88  3868.3 1259.54  4100.9 1245.93
  4200.4 1239.33  4207.7 1238.93  4336.6 1229.25  4499.1 1220.15  4697.8  1210.2
  4856.9 1199.99  4887.4 1194.53  4907.8 1195.33    4999 1190.69  5090.8 1191.57
  5111.1 1194.97  5116.7 1199.12  5121.7 1199.55  5141.6 1213.15  5161.9 1231.88
  5169.8 1241.59  5174.9 1242.08  5182.2  1251.2  5222.9 1276.07  5228.1 1282.25
  5286.4 1312.01  5314.4 1331.45  5344.9 1339.85  5397.8  1349.3  5520.5 1362.68
#Mann= 11 ,-1 , 0
  3509.5      .1       0  3603.2     .05       0  3744.7      .1       0
  3868.3     .05       0  4100.9      .1       0  4200.4     .16       0
  4207.7      .1       0  4499.1     .16       0  4697.8      .1       0
  4856.9     .07       0  5116.7     .16       0
Bank Sta=4856.9,5116.7
XS Rating Curve= 0 ,0
Exp/Cntr=0.3,0.1

Type RM Length L Ch R = 1 ,2066    ,830,830,830
BEGIN DESCRIPTION:
NORTH GRAPE CREEK 2.0
END DESCRIPTION:
XS GIS Cut Line= 2
      2878003.34     10087744.37      2875523.61     10086156.23
#Sta/Elev= 30
  2866.2 1296.21  3147.5 1274.05  3246.8 1267.27  3693.4 1250.16  3767.6 1249.61
  3928.9 1241.99  3970.5 1242.33  4237.4 1229.59  4405.2 1221.63  4679.1 1207.93
  4817.8 1208.88  4860.8 1198.71  4897.2 1197.84  4939.5 1191.31  5048.3 1189.91
  5106.1 1190.91  5115.3 1192.01  5128.2 1198.19  5157.6 1230.06  5163.9 1242.49
  5172.8 1253.36    5194 1261.82  5230.3 1265.85  5360.5 1270.49  5433.2 1269.84
  5454.4 1266.77  5490.7 1273.82  5584.6 1277.62  5636.2  1284.9  5810.9 1295.88
#Mann= 9 ,-1 , 0
  2866.2      .1       0  3147.5     .16       0  3693.4      .1       0
  3928.9     .16       0  4237.4      .1       0  4405.2     .16       0
  4817.8      .1       0  4897.2    .033       0  5128.2     .16       0
#XS Ineff= 2 , 0
         4788.72 1210.52
Permanent Ineff=
       F       F
Bank Sta=4897.2,5128.2
XS Rating Curve= 0 ,0
Exp/Cntr=0.3,0.1

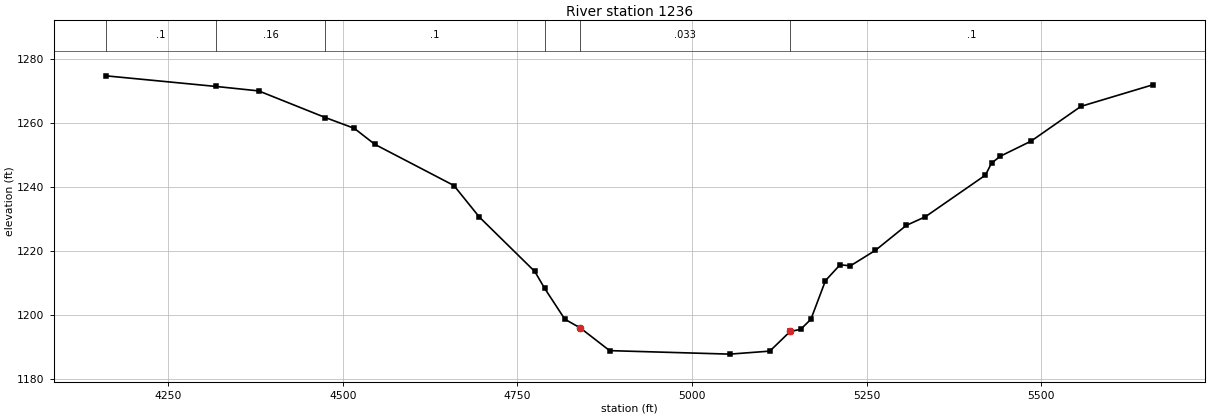
Type RM Length L Ch R = 1 ,1236    ,0,0,0
BEGIN DESCRIPTION:
NORTH GRAPE CREEK 1.0
END DESCRIPTION:
XS GIS Cut Line= 2
      2877515.74     10086532.39      2876289.84     10085668.69
#Sta/Elev= 30
  4160.6 1274.83  4318.8  1271.5  4379.4 1270.12  4474.8  1261.8  4516.2 1258.44
  4545.8 1253.42    4659 1240.56  4695.5 1230.69  4774.8 1213.71    4789 1208.42
  4817.8 1198.81  4840.1 1196.06    4882 1188.99  5054.1  1187.9  5111.4 1188.84
  5140.6    1195  5155.4 1195.62  5170.2 1198.78  5191.1 1210.87    5212 1215.81
  5226.8 1215.48  5262.6 1220.32  5306.9 1228.12    5334 1230.79  5420.2 1243.82
  5428.9 1247.58  5441.7 1249.74  5485.5 1254.43  5556.9 1265.29  5660.2 1272.05
#Mann= 6 ,-1 , 0
  4160.6      .1       0  4318.8     .16       0  4474.8      .1       0
    4789     .05       0  4840.1    .033       0  5140.6      .1       0
Bank Sta=4840.1,5140.6
XS Rating Curve= 0 ,0
Exp/Cntr=0.3,0.1

Chan Stop Cuts=-1
Use User Specified Reach Order=0
Composite Channel Slope=5