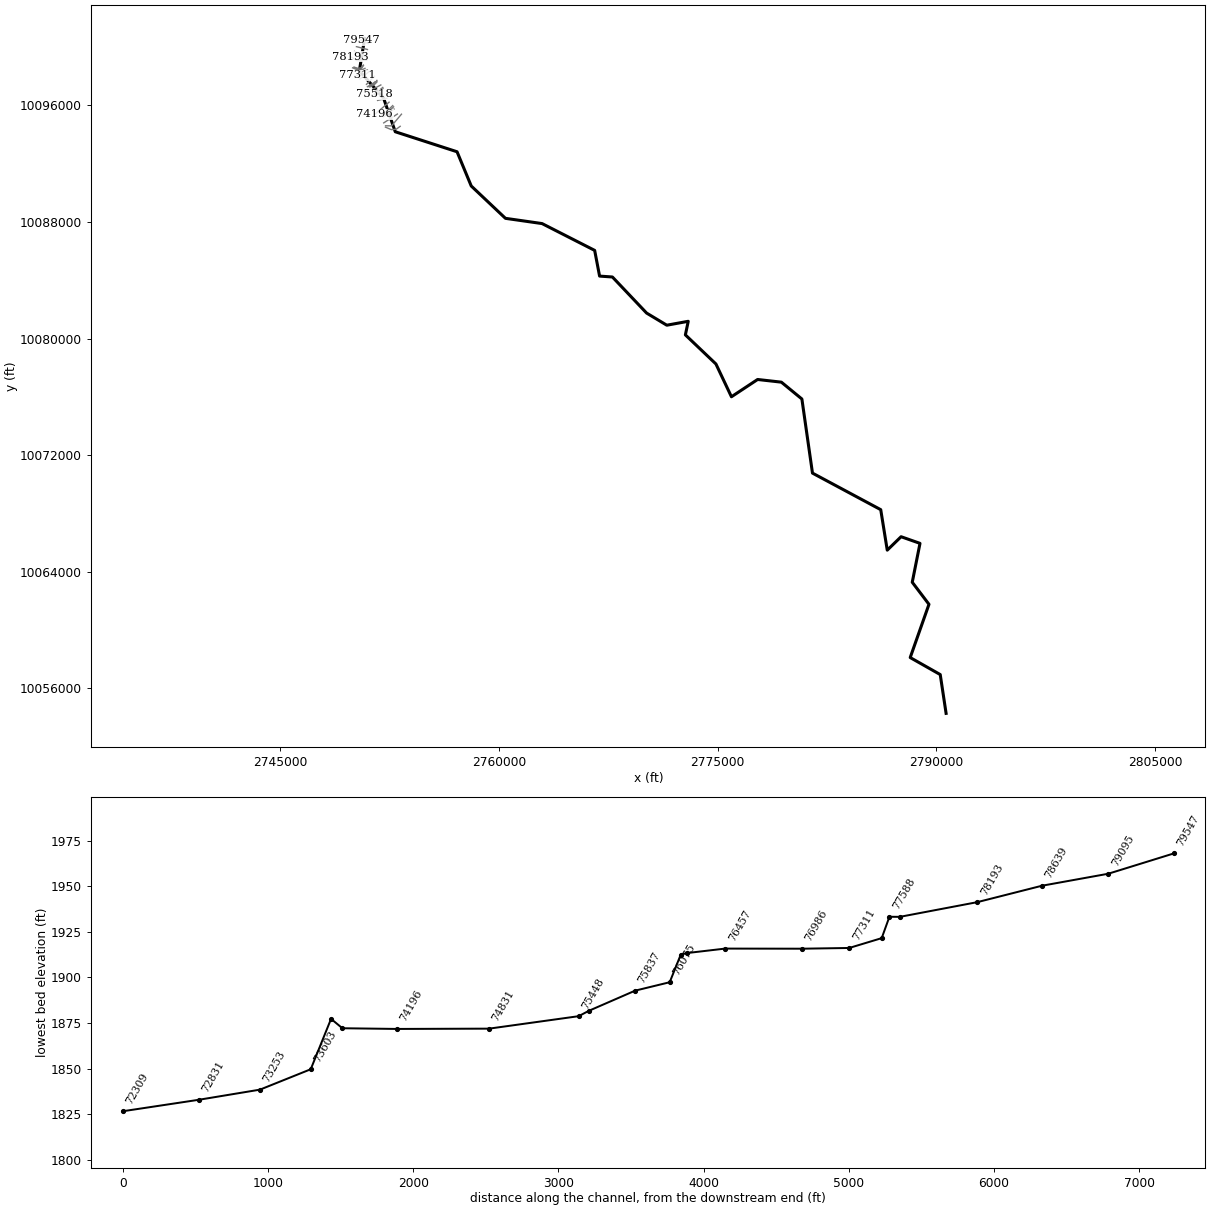
--- PALO ALTO CREEK.prj (project) ---

Proj Title=PALO ALTO CREEK Base Level Engineering
Current Plan=p01
Default Exp/Contr=0.3,0.1
English Units
Geom File=g01
Flow File=f01
Plan File=p01
Y Axis Title=Elevation
X Axis Title(PF)=Main Channel Distance
X Axis Title(XS)=Station
BEGIN DESCRIPTION:
PALO ALTO CREEK
END DESCRIPTION:
DSS Export Rating Curves= 0
DSS Export Rating Curve Sorted= 0
DSS Export Volume Flow Curves= 0
DXF OffsetX= 0
DXF OffsetY= 0
DXF ScaleX= 1
DXF ScaleY= 10

--- PALO ALTO CREEK.p01 (plan) ---

Plan Title=Multiple Run
Short Identifier=Multiple
Geom File=g01
Flow File=f01
Subcritical Flow
K Sum by GR= 0
Std Step Tol= 0.01
Critical Tol= 0.01
Num of Std Step Trials= 20
Max Error Tol= 0.3
Flow Tol Ratio= 0.001
Split Flow NTrial= 30
Split Flow Tol= 0.02
Split Flow Ratio= 0.02
Log Output Level= 0
Friction Slope Method= 1
Unsteady Friction Slope Method= 2
Unsteady Bridges Friction Slope Method= 1
Parabolic Critical Depth
Global Vel Dist=  1 , 1 , 1
Global Log Level= 0
CheckData=True
Encroach Param= -1, 0, 0, 0
BEGIN DESCRIPTION:
Multiple Run
END DESCRIPTION:

--- PALO ALTO CREEK.f01 (steady flow) ---

Flow Title=Multiple
Program Version=4.10
Number of Profiles= 7
Profile Names=10-year,25-year,50-year,1pct_min,100-year,1pct_plu,500-year
River Rch & RM=PALO ALTO CREEK,Reach-1         ,79547
     724    1044    1320    1223    1654    2237    2607
River Rch & RM=PALO ALTO CREEK,Reach-1         ,73821
    1287    1919    2481    2347    3174    4293    5218
River Rch & RM=PALO ALTO CREEK,Reach-1         ,71809
    2056    3132    4110    3938    5326    7202    8989
River Rch & RM=PALO ALTO CREEK,Reach-1         ,69045
    2283    3490    4589    4404    5955    8054   10083
River Rch & RM=PALO ALTO CREEK,Reach-1         ,64035
    2924    4512    5971    5762    7793   10539   13342
River Rch & RM=PALO ALTO CREEK,Reach-1         ,60881
    3088    4768    6311    6091    8237   11140   14104
River Rch & RM=PALO ALTO CREEK,Reach-1         ,57914
    4424    6930    9265    9023   12202   16502   21276
River Rch & RM=PALO ALTO CREEK,Reach-1         ,57402
    5051    7944   10649   10395   14057   19011   24623
River Rch & RM=PALO ALTO CREEK,Reach-1         ,55912
    5467    8603   11537   11262   15230   20597   26679
River Rch & RM=PALO ALTO CREEK,Reach-1         ,52217
    5493    8621   11540   11242   15204   20562   26525
River Rch & RM=PALO ALTO CREEK,Reach-1         ,47624
    5732    8997   12043   11730   15864   21454   27665
River Rch & RM=PALO ALTO CREEK,Reach-1         ,44679
    5779    9054   12105   11775   15924   21535   27694
River Rch & RM=PALO ALTO CREEK,Reach-1         ,40697
    5819    9107   12166   11824   15991   21625   27760
River Rch & RM=PALO ALTO CREEK,Reach-1         ,37599
    5833    9116   12166   11810   15972   21601   27666
River Rch & RM=PALO ALTO CREEK,Reach-1         ,34494
    8198   12949   17411   17018   23015   31124   40400
River Rch & RM=PALO ALTO CREEK,Reach-1         ,33567
    8198   12949   17411   17018   23015   31124   40400
River Rch & RM=PALO ALTO CREEK,Reach-1         ,33121
    8363   13207   17754   17349   23462   31730   41165
River Rch & RM=PALO ALTO CREEK,Reach-1         ,31607
    8298   13078   17556   17130   23167   31330   40525
River Rch & RM=PALO ALTO CREEK,Reach-1         ,31026
    8298   13078   17556   17130   23167   31330   40525
River Rch & RM=PALO ALTO CREEK,Reach-1         ,27420
    8302   13047   17480   17020   23018   31129   40095
River Rch & RM=PALO ALTO CREEK,Reach-1         ,26818
    8302   13047   17480   17020   23018   31129   40095
River Rch & RM=PALO ALTO CREEK,Reach-1         ,26390
    8906   13997   18754   18257   24691   33391   42987
River Rch & RM=PALO ALTO CREEK,Reach-1         ,19420
    8906   13997   18754   18257   24691   33391   42987
River Rch & RM=PALO ALTO CREEK,Reach-1         ,14011
    9443   14845   19895   19369   26195   35425   45609
River Rch & RM=PALO ALTO CREEK,Reach-1         ,7854
    9477   14894   19956   19424   26269   35525   45716
River Rch & RM=PALO ALTO CREEK,Reach-1         ,7060
    9580   15037   20129   19574   26471   35799   45975
River Rch & RM=PALO ALTO CREEK,Reach-1         ,5780
    9580   15037   20129   19574   26471   35799   45975
Boundary for River Rch & Prof#=PALO ALTO CREEK,Reach-1         , 1
Up Type= 0
Dn Type= 3
Dn Slope=0.00248
Boundary for River Rch & Prof#=PALO ALTO CREEK,Reach-1         , 2
Up Type= 0
Dn Type= 3
Dn Slope=0.00248
Boundary for River Rch & Prof#=PALO ALTO CREEK,Reach-1         , 3
Up Type= 0
Dn Type= 3
Dn Slope=0.00248
Boundary for River Rch & Prof#=PALO ALTO CREEK,Reach-1         , 4
Up Type= 0
Dn Type= 3
Dn Slope=0.00248
Boundary for River Rch & Prof#=PALO ALTO CREEK,Reach-1         , 5
Up Type= 0
Dn Type= 3
Dn Slope=0.00248
Boundary for River Rch & Prof#=PALO ALTO CREEK,Reach-1         , 6
Up Type= 0
Dn Type= 3
Dn Slope=0.00248
Boundary for River Rch & Prof#=PALO ALTO CREEK,Reach-1         , 7
Up Type= 0
Dn Type= 3
Dn Slope=0.00248
DSS Import GetInterval= 0
DSS Import GetPeak= 0
DSS Import FillOption= 0

--- PALO ALTO CREEK.g01 (geometry) ---

Geom Title=Existing Conditions
Program Version=4.10

River Reach=PALO ALTO CREEK ,Reach-1
Reach XY= 30
       2750795.2     10100602.49      2750432.43     10098371.85
      2752090.13     10096504.87      2752894.86     10094192.06
       2757131.3     10092819.27      2758104.79     10090470.19
      2760450.64     10088251.04      2762960.44     10087891.73
      2766567.68     10086051.71       2766905.2     10084287.82
      2767784.93     10084226.19      2770128.33     10081751.22
      2771514.28      10080917.7      2772984.54     10081185.63
      2772788.47     10080253.73      2774883.52     10078256.55
      2775947.04     10076007.19      2777740.97     10077193.39
      2779371.42     10077009.49      2780777.48     10075854.22
      2781503.71     10070768.68      2786184.22      10068259.7
      2786631.01     10065481.51      2787579.81     10066404.31
      2788876.23     10065947.72      2788345.44     10063279.69
      2789491.89     10061765.45      2788204.91      10058111.8
      2790264.19     10056944.72      2790666.35     10054281.87

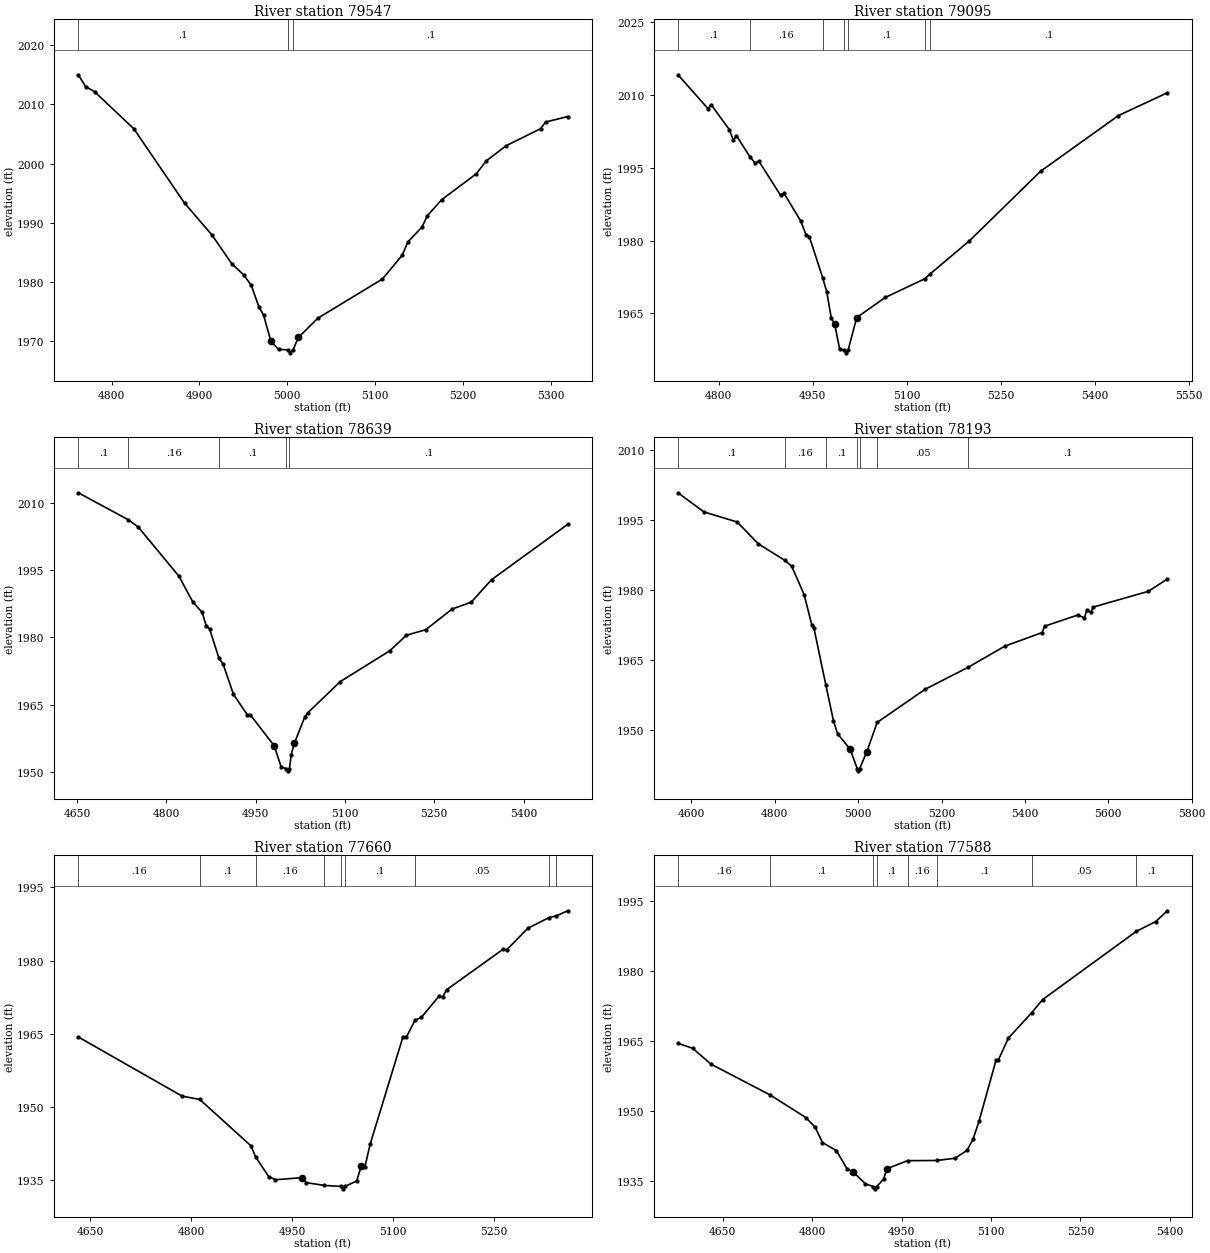
Type RM Length L Ch R = 1 ,79547   ,452,452,452
BEGIN DESCRIPTION:
PALO ALTO CREEK 134.0
END DESCRIPTION:
XS GIS Cut Line= 2
      2751045.21      10100237.2      2750545.21     10100481.99
#Sta/Elev= 30
  4762.2 2014.99  4770.5    2013  4780.8 2012.12  4825.4 2005.87    4883 1993.34
  4914.4 1987.92  4936.7 1983.11  4950.5 1981.19    4959 1979.44  4967.5 1975.88
    4973  1974.4  4981.3    1970    4990 1968.65  5000.5 1968.56  5003.3 1968.06
  5006.5 1968.56  5012.5 1970.66    5035 1973.94  5108.1 1980.51  5130.6 1984.52
  5137.1 1986.78  5153.1 1989.28  5159.4 1991.23  5175.6 1993.91    5215 1998.28
  5226.2 2000.44  5248.7    2003  5288.1 2005.89  5293.7 2007.01  5318.9 2007.94
#Mann= 3 ,-1 , 0
  4762.2      .1       0  5000.5     .07       0  5006.5      .1       0
Bank Sta=4981.3,5012.5
XS Rating Curve= 0 ,0
Exp/Cntr=0.3,0.1

Type RM Length L Ch R = 1 ,79095   ,456,456,456
BEGIN DESCRIPTION:
PALO ALTO CREEK 133.0
END DESCRIPTION:
XS GIS Cut Line= 2
      2750987.92     10099836.16      2750233.11     10100033.97
#Sta/Elev= 30
  4735.3 2014.13  4783.1 2007.18  4788.2 2007.98  4817.4 2002.81  4823.5 2000.69
  4828.6 2001.57  4849.9 1997.27  4858.7 1995.89  4863.9 1996.42  4899.1 1989.29
  4904.3 1989.76  4931.1 1984.02  4939.5 1981.21  4944.7 1980.83  4966.1 1972.33
  4972.5 1969.47  4979.9 1963.99  4985.1 1962.84  4993.2 1957.61  5000.5  1957.4
  5003.3  1956.9  5006.5  1957.4  5020.3 1964.16  5065.9  1968.3  5129.1 1972.16
  5137.4 1973.14  5199.9 1979.94  5313.6 1994.28  5437.7 2005.74  5515.6 2010.42
#Mann= 7 ,-1 , 0
  4735.3      .1       0  4849.9     .16       0  4966.1      .1       0
  5000.5     .07       0  5006.5      .1       0  5129.1     .16       0
  5137.4      .1       0
Bank Sta=4985.1,5020.3
XS Rating Curve= 0 ,0
Exp/Cntr=0.3,0.1

Type RM Length L Ch R = 1 ,78639   ,446,446,446
BEGIN DESCRIPTION:
PALO ALTO CREEK 132.0
END DESCRIPTION:
XS GIS Cut Line= 2
      2750836.84     10099357.01      2750092.76     10099705.63
#Sta/Elev= 30
  4652.4 2012.19  4736.4 2006.18  4753.1 2004.57  4821.6 1993.58  4844.4 1987.96
  4860.4 1985.57  4867.3 1982.54  4872.8 1981.93  4888.4 1975.44  4895.6 1974.04
  4912.9 1967.36  4935.8 1962.86  4941.3 1962.79  4981.4 1955.89  4992.9 1951.24
    5001 1950.83  5003.7 1950.33    5007 1950.83  5009.8 1953.93  5015.3 1956.53
  5032.6 1962.29  5038.1 1963.29  5092.3 1970.19  5175.1 1977.01  5203.4  1980.5
  5235.9 1981.73  5280.1 1986.33    5312 1987.84  5346.3 1992.85  5474.1 2005.16
#Mann= 5 ,-1 , 0
  4652.4      .1       0  4736.4     .16       0  4888.4      .1       0
    5001     .07       0    5007      .1       0
Bank Sta=4981.4,5015.3
XS Rating Curve= 0 ,0
Exp/Cntr=0.3,0.1

Type RM Length L Ch R = 1 ,78193   ,533,533,533
BEGIN DESCRIPTION:
PALO ALTO CREEK 131.0
END DESCRIPTION:
XS GIS Cut Line= 3
      2750930.65       10099107.      2750284.78     10099070.54
      2749832.59     10099340.81
#Sta/Elev= 30
  4567.9 2000.85  4630.2 1996.75  4709.9 1994.59  4760.4 1989.94  4823.8  1986.4
  4840.5 1985.15  4870.6 1979.02  4888.8 1972.58  4893.8 1971.98  4922.4 1959.76
  4940.7 1952.08  4950.7 1949.24  4980.7 1945.96  4997.8 1941.81  5000.5 1941.31
  5003.8 1941.81  5020.8 1945.37  5045.6 1951.67    5161 1958.79  5263.7 1963.47
  5351.9 1968.01  5441.4 1970.92  5447.3 1972.28    5527 1974.68  5542.6 1974.07
  5548.4 1975.66  5558.2 1975.26    5564 1976.38  5696.3 1979.75  5741.6 1982.38
#Mann= 7 ,-1 , 0
  4567.9      .1       0  4823.8     .16       0  4922.4      .1       0
  4997.8     .07       0  5003.8      .1       0  5045.6     .05       0
  5263.7      .1       0
Bank Sta=4980.7,5020.8
XS Rating Curve= 0 ,0
Exp/Cntr=0.3,0.1

Type RM Length L Ch R = 1 ,77660   ,72,72,72
BEGIN DESCRIPTION:
PALO ALTO CREEK 130.0
END DESCRIPTION:
XS GIS Cut Line= 4
      2750698.02     10098759.67      2750578.63     10098583.85
      2750307.36     10098551.29      2750077.32     10098627.25
#Sta/Elev= 30
  4632.1 1964.35  4786.5 1952.24  4812.8 1951.55  4888.8 1942.07  4896.1 1939.73
  4915.3 1935.77  4925.4 1935.11  4965.6 1935.55  4971.1 1934.53    4998 1933.95
  5023.1 1933.75  5025.8 1933.25  5029.1 1933.75  5046.2 1934.87  5053.3 1938.03
  5058.4 1937.74  5066.4 1942.46  5114.8 1964.26  5119.9 1964.26    5133 1967.78
  5142.3 1968.35  5168.8 1972.73    5174 1972.54  5179.9 1974.01    5264 1982.32
  5269.3 1982.19    5301 1986.63  5332.4 1988.81  5343.2 1989.15  5360.1  1990.2
#Mann= 9 ,-1 , 0
  4632.1     .16       0  4812.8      .1       0  4896.1     .16       0
    4998      .1       0  5023.1     .07       0  5029.1      .1       0
    5133     .05       0  5332.4      .1       0  5343.2     .05       0
Bank Sta=4965.6,5053.3
XS Rating Curve= 0 ,0
Exp/Cntr=0.3,0.1

Type RM Length L Ch R = 1 ,77588   ,53,53,53
BEGIN DESCRIPTION:
Mapping XS cf6b6d26
END DESCRIPTION:
XS GIS Cut Line= 5
      2750715.36     10098750.97      2750567.78     10098507.89
      2750502.68     10098494.87      2750316.04     10098490.53
      2750057.84      10098607.7
#Sta/Elev= 30
  4574.9 1964.43  4599.4 1963.39  4630.2 1959.99    4730 1953.35  4789.3 1948.56
  4804.8 1946.55  4817.3  1943.2  4840.7 1941.47  4858.8 1937.52  4868.8 1936.92
  4889.2 1934.38  4902.2 1933.79    4905 1933.29  4908.2 1933.79  4919.8 1935.35
  4925.3 1937.59    4960 1939.32  5009.6 1939.36  5039.9 1939.85  5059.9 1941.52
  5069.9  1943.9  5079.9 1947.72  5108.6 1960.87  5112.4 1960.87  5129.2 1965.54
  5168.3 1970.99  5186.6 1973.79    5344 1988.42  5376.5  1990.5  5395.9 1992.81
#Mann= 8 ,-1 , 0
  4574.9     .16       0    4730      .1       0  4902.2     .07       0
  4908.2      .1       0    4960     .16       0  5009.6      .1       0
  5168.3     .05       0    5344      .1       0
Bank Sta=4868.8,4925.3
XS Rating Curve= 0 ,0
Exp/Cntr=0.3,0.1

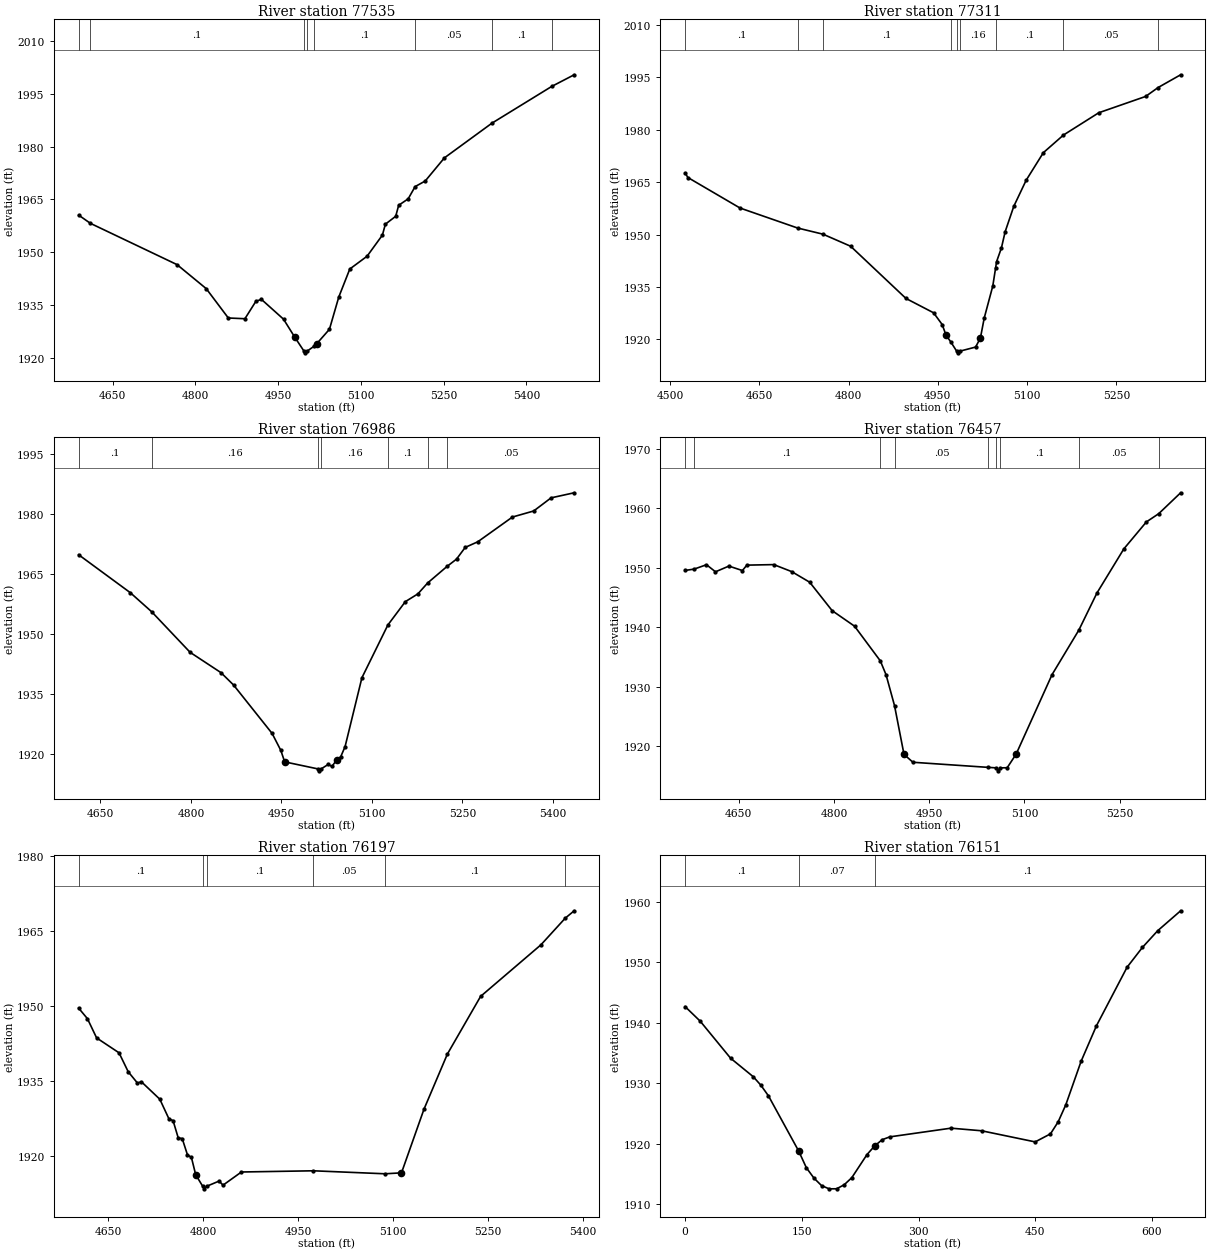
Type RM Length L Ch R = 1 ,77535   ,224,224,224
BEGIN DESCRIPTION:
Mapping XS bfca6639
END DESCRIPTION:
XS GIS Cut Line= 4
      2750817.39      10098544.8      2750615.52     10098447.13
      2750320.38     10098436.28      2749969.76     10098579.12
#Sta/Elev= 30
  4588.4 1960.58  4609.8 1958.24  4766.8 1946.55  4819.7 1939.75  4859.7 1931.44
  4889.8 1931.23  4909.8 1936.19  4919.8  1936.7  4959.8  1931.1  4979.8 1926.09
  4996.8 1922.07  4999.6 1921.57  5002.8 1922.07  5015.1 1923.44  5019.9 1924.14
    5043 1928.24  5059.9 1937.36  5079.9 1945.31  5111.2 1948.93    5139 1954.91
  5144.4 1958.01  5163.1 1960.24  5168.5 1963.36  5185.7 1965.18  5198.3 1968.65
  5216.6 1970.23  5251.4 1976.79  5337.5 1986.61    5446 1997.03  5486.6 2000.32
#Mann= 8 ,-1 , 0
  4588.4     .16       0  4609.8      .1       0  4996.8     .07       0
  5002.8      .1       0  5015.1      .1       0  5198.3     .05       0
  5337.5      .1       0    5446     .05       0
Bank Sta=4979.8,5019.9
XS Rating Curve= 0 ,0
Exp/Cntr=0.3,0.1

Type RM Length L Ch R = 1 ,77311   ,325,325,325
BEGIN DESCRIPTION:
PALO ALTO CREEK 129.0
END DESCRIPTION:
XS GIS Cut Line= 3
       2750987.9     10098429.91      2750623.32     10098336.16
      2750263.93     10098054.91
#Sta/Elev= 30
  4525.2 1967.61  4529.9  1966.3  4617.5 1957.58  4714.3 1951.86  4756.9  1950.1
  4803.4 1946.65  4896.4 1931.72  4942.8 1927.62  4957.3 1924.25  4963.7 1921.22
  4971.5 1919.35  4981.5 1916.67  4984.2 1916.17  4987.5 1916.67  5013.4 1917.82
  5021.5 1920.41  5027.9 1926.11  5042.3 1935.28  5046.9  1940.3  5048.7 1942.26
  5056.8 1946.16  5063.1 1950.81  5077.6 1958.07  5098.4 1965.53  5127.3 1973.41
  5161.1 1978.45  5220.4 1984.82  5299.1 1989.48  5320.2 1992.04    5358 1995.68
#Mann= 9 ,-1 , 0
  4525.2      .1       0  4714.3     .16       0  4756.9      .1       0
  4971.5     .16       0  4981.5     .07       0  4987.5     .16       0
  5046.9      .1       0  5161.1     .05       0  5320.2      .1       0
Bank Sta=4963.7,5021.5
XS Rating Curve= 0 ,0
Exp/Cntr=0.3,0.1

Type RM Length L Ch R = 1 ,76986   ,529,529,529
BEGIN DESCRIPTION:
PALO ALTO CREEK 128.0
END DESCRIPTION:
XS GIS Cut Line= 2
      2751102.45     10098320.51      2750462.65     10097805.55
#Sta/Elev= 30
  4613.9 1969.77  4699.5 1960.29  4734.9 1955.53  4798.7 1945.38  4849.8 1940.31
  4870.6 1937.23  4934.6 1925.11    4949 1920.88  4955.4 1918.01    5010 1916.27
  5012.7 1915.77    5016 1916.27  5027.4 1917.36  5033.8 1916.87  5041.8 1918.55
  5048.2 1919.26  5055.5 1921.82  5083.4 1939.03  5126.5 1952.23  5155.4 1958.05
  5176.2 1959.99  5192.4 1962.72  5224.5 1966.85  5240.2 1968.67  5254.6  1971.6
  5275.4    1973  5332.9 1979.19  5368.1  1980.7  5396.9 1983.98  5435.2 1985.25
#Mann= 7 ,-1 , 0
  4613.9      .1       0  4734.9     .16       0    5010     .07       0
    5016     .16       0  5126.5      .1       0  5192.4     .16       0
  5224.5     .05       0
Bank Sta=4955.4,5041.8
XS Rating Curve= 0 ,0
Exp/Cntr=0.3,0.1

Type RM Length L Ch R = 1 ,76457   ,260,260,260
BEGIN DESCRIPTION:
PALO ALTO CREEK 127.0
END DESCRIPTION:
XS GIS Cut Line= 2
      2751467.06     10098002.82      2750920.18     10097445.53
#Sta/Elev= 30
  4565.3 1949.51  4579.5 1949.73    4599 1950.47  4613.2 1949.28  4634.3 1950.24
  4655.6 1949.49  4662.6  1950.4    4705 1950.49  4733.3 1949.31  4761.6 1947.53
    4797 1942.75  4832.3 1940.14  4872.9 1934.31  4881.9 1931.99  4895.3 1926.78
  4910.2  1918.6  4924.3 1917.27  5043.3 1916.41  5055.6 1916.33  5058.4 1915.83
  5061.6 1916.33  5072.8 1916.35  5086.9 1918.64  5143.5    1932  5185.7 1939.48
  5214.2 1945.71  5256.6 1953.13  5292.1 1957.66  5311.6 1959.05  5346.1 1962.56
#Mann= 9 ,-1 , 0
  4565.3     .05       0  4579.5      .1       0  4872.9     .16       0
  4895.3     .05       0  5043.3      .1       0  5055.6    .033       0
  5061.6      .1       0  5185.7     .05       0  5311.6      .1       0
Bank Sta=4910.2,5086.9
XS Rating Curve= 0 ,0
Exp/Cntr=0.3,0.1

Type RM Length L Ch R = 1 ,76197   ,46,46,46
BEGIN DESCRIPTION:
Mapping XS 168b32c2
END DESCRIPTION:
XS GIS Cut Line= 3
      2751635.66     10097716.25      2751375.27     10097518.35
      2750984.64     10097283.98
#Sta/Elev= 30
  4603.3 1949.56  4617.2 1947.45  4631.7  1943.6  4667.1 1940.62  4681.6 1936.83
  4696.2 1934.57  4702.4 1934.83  4731.5 1931.34  4746.1 1927.36  4752.4 1927.07
  4760.6  1923.6  4766.9 1923.46  4775.2  1920.2  4781.4  1919.7  4788.2 1916.23
  4799.3 1913.91    4802 1913.41  4805.3 1913.91  4825.1 1914.96  4831.4 1914.15
  4860.4 1916.78  4974.1 1917.02  5087.3 1916.42  5113.2 1916.61  5148.7 1929.34
  5185.7 1940.38  5238.1  1951.9  5333.4 1962.22  5371.8 1967.55  5385.9 1969.03
#Mann= 6 ,-1 , 0
  4603.3      .1       0  4799.3    .033       0  4805.3      .1       0
  4974.1     .05       0  5087.3      .1       0  5371.8     .05       0
Bank Sta=4788.2,5113.2
XS Rating Curve= 0 ,0
Exp/Cntr=0.3,0.1

Type RM Length L Ch R = 1 ,76151   ,76,76,76
BEGIN DESCRIPTION:
Mapping XS 0db0d0e6
END DESCRIPTION:
XS GIS Cut Line= 3
      2751609.63     10097664.17      2751411.73      10097487.1
      2751088.81      10097294.4
#Sta/Elev= 30
       0 1942.64   19.48 1940.22   58.44 1934.11   87.66 1931.04    97.4 1929.64
  107.14 1927.88   146.1 1918.73  155.84    1916  165.58 1914.29  175.32 1913.05
  185.06 1912.51   194.8 1912.52  204.54 1913.19  214.28 1914.36  233.76 1918.17
   243.5 1919.59  253.24 1920.63  262.98  1921.1   341.7 1922.54  381.06 1922.11
  449.93 1920.27  469.61  1921.6  479.45 1923.58  489.29  1926.4  508.97  1933.6
  528.65 1939.46  568.01 1949.14  587.69 1952.41  607.37 1955.18  636.89 1958.48
#Mann= 3 , 0 , 0
       0      .1       0   146.1     .07       0   243.5      .1       0
Bank Sta=146.1,243.5
XS Rating Curve= 0 ,0
Exp/Cntr=0.3,0.1

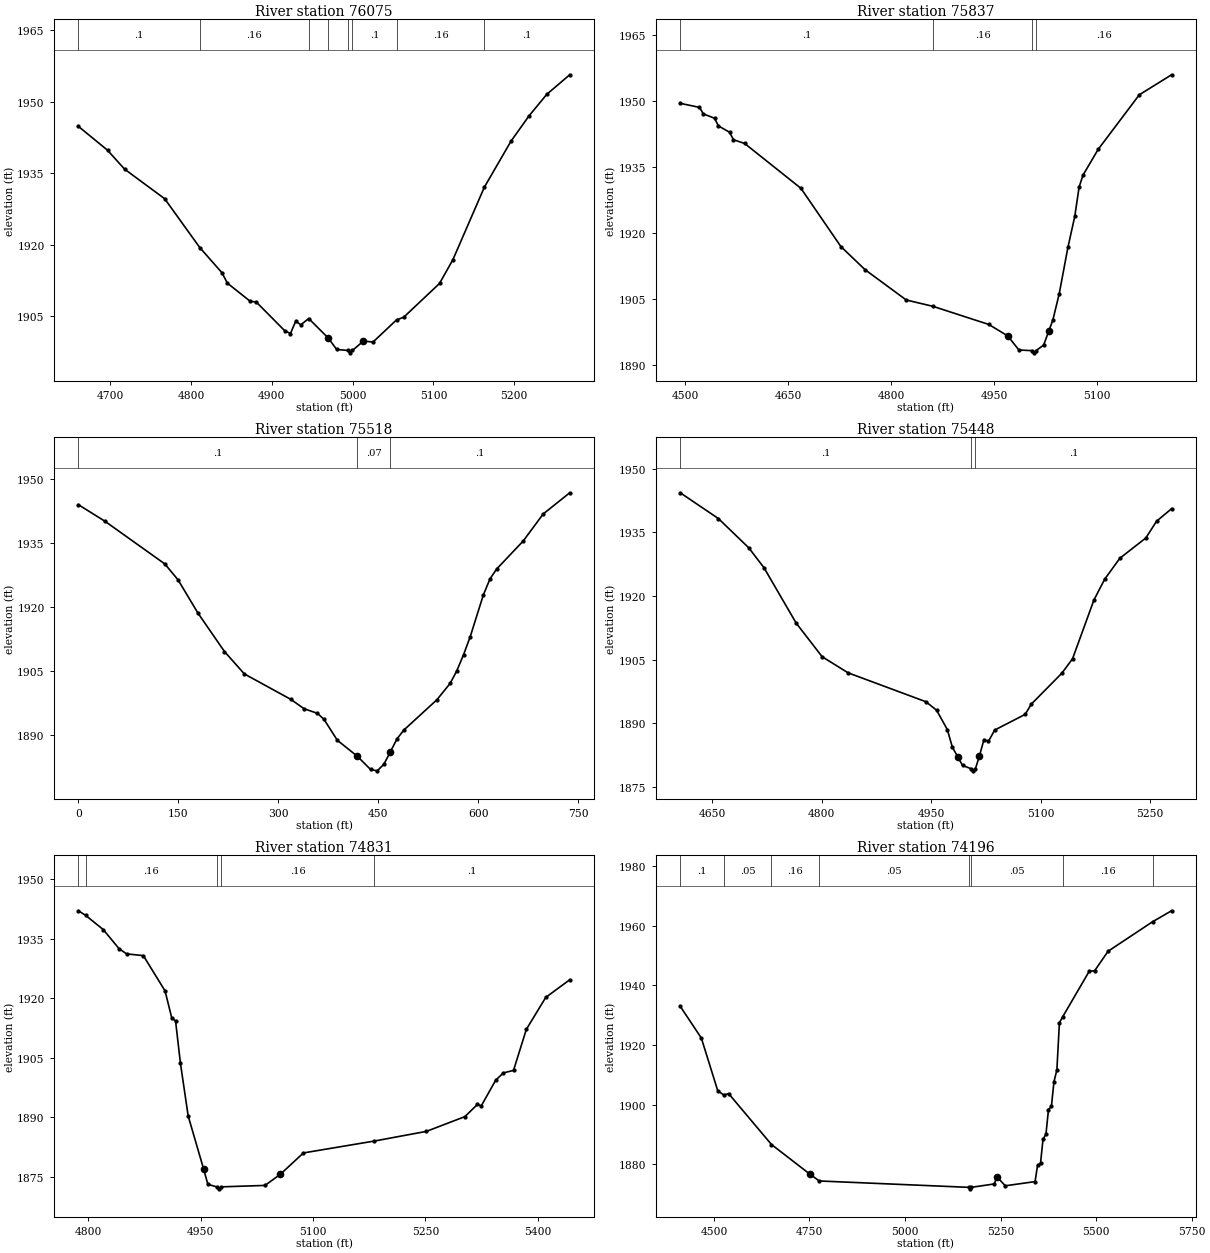
Type RM Length L Ch R = 1 ,76075   ,238,238,238
BEGIN DESCRIPTION:
Mapping XS 36bdbcea
END DESCRIPTION:
XS GIS Cut Line= 3
      2751640.89      10097612.1      2751453.39      10097419.4
      2751152.34     10097263.68
#Sta/Elev= 30
  4660.8 1944.83  4696.8 1939.84  4717.9 1935.87  4767.5 1929.67    4811 1919.42
  4838.2 1914.19  4845.2 1911.96  4873.5 1908.15  4880.7 1908.04  4915.9 1902.02
  4923.1 1901.42  4929.6 1903.99    4936 1903.25  4945.7 1904.56  4969.7  1900.5
  4980.3 1898.08  4993.8 1897.87  4996.5 1897.37  4999.8 1897.87  5013.3 1899.83
  5025.3 1899.64  5054.3 1904.27  5063.2 1904.83  5107.5 1911.91    5124 1916.87
    5163  1932.1    5196 1941.75  5218.2 1947.03  5240.3 1951.57  5268.6 1955.65
#Mann= 8 ,-1 , 0
  4660.8      .1       0    4811     .16       0  4945.7     .05       0
  4969.7      .1       0  4993.8     .07       0  4999.8      .1       0
  5054.3     .16       0    5163      .1       0
Bank Sta=4969.7,5013.3
XS Rating Curve= 0 ,0
Exp/Cntr=0.3,0.1

Type RM Length L Ch R = 1 ,75837   ,319,319,319
BEGIN DESCRIPTION:
PALO ALTO CREEK 126.0
END DESCRIPTION:
XS GIS Cut Line= 2
      2751904.56     10097403.87      2751274.33     10097065.32
#Sta/Elev= 30
  4492.9 1949.55  4520.9 1948.63  4526.5 1947.15  4542.8 1946.16  4548.5 1944.41
  4564.7 1942.97  4570.4 1941.26  4586.6 1940.42  4668.6 1930.21  4726.8 1916.95
    4762 1911.68    4822 1904.78    4861 1903.33  4942.2 1899.21  4969.8  1896.6
    4986  1893.4  5004.9 1893.25  5007.7 1892.75  5010.9 1893.25    5022  1894.5
  5029.8 1897.81  5035.5 1900.24  5044.7 1906.18  5057.4 1916.77  5067.4 1923.84
  5073.7  1930.5  5079.4 1933.21  5101.4 1939.06  5161.3 1951.49  5208.3 1956.05
#Mann= 4 ,-1 , 0
  4492.9      .1       0    4861     .16       0  5004.9     .07       0
  5010.9     .16       0
Bank Sta=4969.8,5029.8
XS Rating Curve= 0 ,0
Exp/Cntr=0.3,0.1

Type RM Length L Ch R = 1 ,75518   ,70,70,70
XS GIS Cut Line= 2
      2752039.92    10097233.754     2751468.305     10096768.91
#Sta/Elev= 30
       0  1943.9   39.87 1940.03  129.58 1930.07  149.51 1926.35  179.41 1918.57
  219.28 1909.57  249.18 1904.33  318.96 1898.38  338.89 1896.19  358.83 1895.13
  368.79 1893.69  388.73 1888.82  418.63  1885.1  438.57    1882  448.53 1881.68
   458.5 1883.19  468.47 1886.18  478.44 1889.19   488.4 1891.19  538.24 1898.31
  558.17 1902.15  568.14  1905.1  578.11  1908.8  588.08    1913  608.01 1922.85
  617.98 1926.59  627.95 1928.88  667.82 1935.43  697.72 1941.73  737.59 1946.69
#Mann= 3 , 0 , 0
       0      .1       0  418.63     .07       0  468.47      .1       0
Bank Sta=418.63,468.47
XS Rating Curve= 0 ,0
Exp/Cntr=0.3,0.1

Type RM Length L Ch R = 1 ,75448   ,617,617,617
BEGIN DESCRIPTION:
PALO ALTO CREEK 125.0
END DESCRIPTION:
XS GIS Cut Line= 2
       2752060.8     10097133.03      2751514.98     10096737.96
#Sta/Elev= 30
  4605.8 1944.36  4658.1 1938.28  4699.8 1931.37  4720.7 1926.66  4764.8  1913.6
  4800.4 1905.67    4836 1901.87  4942.7 1895.05  4957.4 1893.04  4972.1 1888.47
    4979 1884.31  4986.8 1881.92  4992.9 1880.03  5004.6 1879.24  5007.4 1878.74
  5010.6 1879.24  5016.1 1882.23  5022.3 1886.12  5028.5 1885.71    5037 1888.36
  5078.8 1892.06  5087.3 1894.49  5129.1 1901.77  5143.8 1905.18  5173.2 1919.08
  5187.9 1923.97  5208.7 1928.91  5244.3 1933.69    5259 1937.64  5279.6  1940.6
#Mann= 3 ,-1 , 0
  4605.8      .1       0  5004.6     .07       0  5010.6      .1       0
Bank Sta=4986.8,5016.1
XS Rating Curve= 0 ,0
Exp/Cntr=0.3,0.1

Type RM Length L Ch R = 1 ,74831   ,635,635,635
BEGIN DESCRIPTION:
PALO ALTO CREEK 124.0
END DESCRIPTION:
XS GIS Cut Line= 2
      2752321.19      10096487.2      2751682.05      10096341.7
#Sta/Elev= 30
  4787.1 1942.06  4796.6 1940.92  4820.4 1937.29  4841.2 1932.52  4851.4 1931.18
  4873.7 1930.75  4902.7 1921.84  4911.6 1915.03  4916.7 1914.26  4923.2 1903.59
  4933.5 1890.31    4954 1876.99  4959.8 1873.04  4971.5  1872.4  4974.3  1871.9
  4977.5  1872.4    5036 1872.76  5056.5 1875.57  5087.3 1880.96  5181.9 1883.96
  5251.4  1886.4  5302.7 1890.12  5319.4 1893.19  5324.6 1892.84  5343.7 1899.28
    5354 1901.14  5367.6 1901.79  5384.7 1912.14  5410.6  1920.2  5442.6 1924.66
#Mann= 5 ,-1 , 0
  4787.1      .1       0  4796.6     .16       0  4971.5     .07       0
  4977.5     .16       0  5181.9      .1       0
Bank Sta=4954,5056.5
XS Rating Curve= 0 ,0
Exp/Cntr=0.3,0.1

Type RM Length L Ch R = 1 ,74196   ,375,375,375
BEGIN DESCRIPTION:
PALO ALTO CREEK 123.0
END DESCRIPTION:
XS GIS Cut Line= 2
      2752469.05     10096221.51      2751490.17     10095388.41
#Sta/Elev= 30
    4412 1932.97  4467.2 1922.33  4510.1 1904.66  4525.8 1903.22  4538.6 1903.68
  4650.7 1886.61  4751.7 1876.62  4775.7 1874.38  5167.1 1872.24  5169.8 1871.74
  5173.1 1872.24  5233.8 1873.39  5240.3 1875.82  5262.3 1872.76  5340.3 1874.17
  5346.8 1879.59  5354.6 1880.36  5361.1 1888.38  5368.8 1890.08  5375.4 1898.32
  5383.1 1899.44  5389.7 1907.62  5397.4 1911.68    5404 1927.47  5412.1 1929.34
  5481.9 1944.71  5496.2  1944.9  5531.3 1951.44  5647.7 1961.34  5697.4 1965.02
#Mann= 8 ,-1 , 0
    4412      .1       0  4525.8     .05       0  4650.7     .16       0
  4775.7     .05       0  5167.1    .033       0  5173.1     .05       0
  5412.1     .16       0  5647.7      .1       0
Bank Sta=4751.7,5240.3
XS Rating Curve= 0 ,0
Exp/Cntr=0.3,0.1

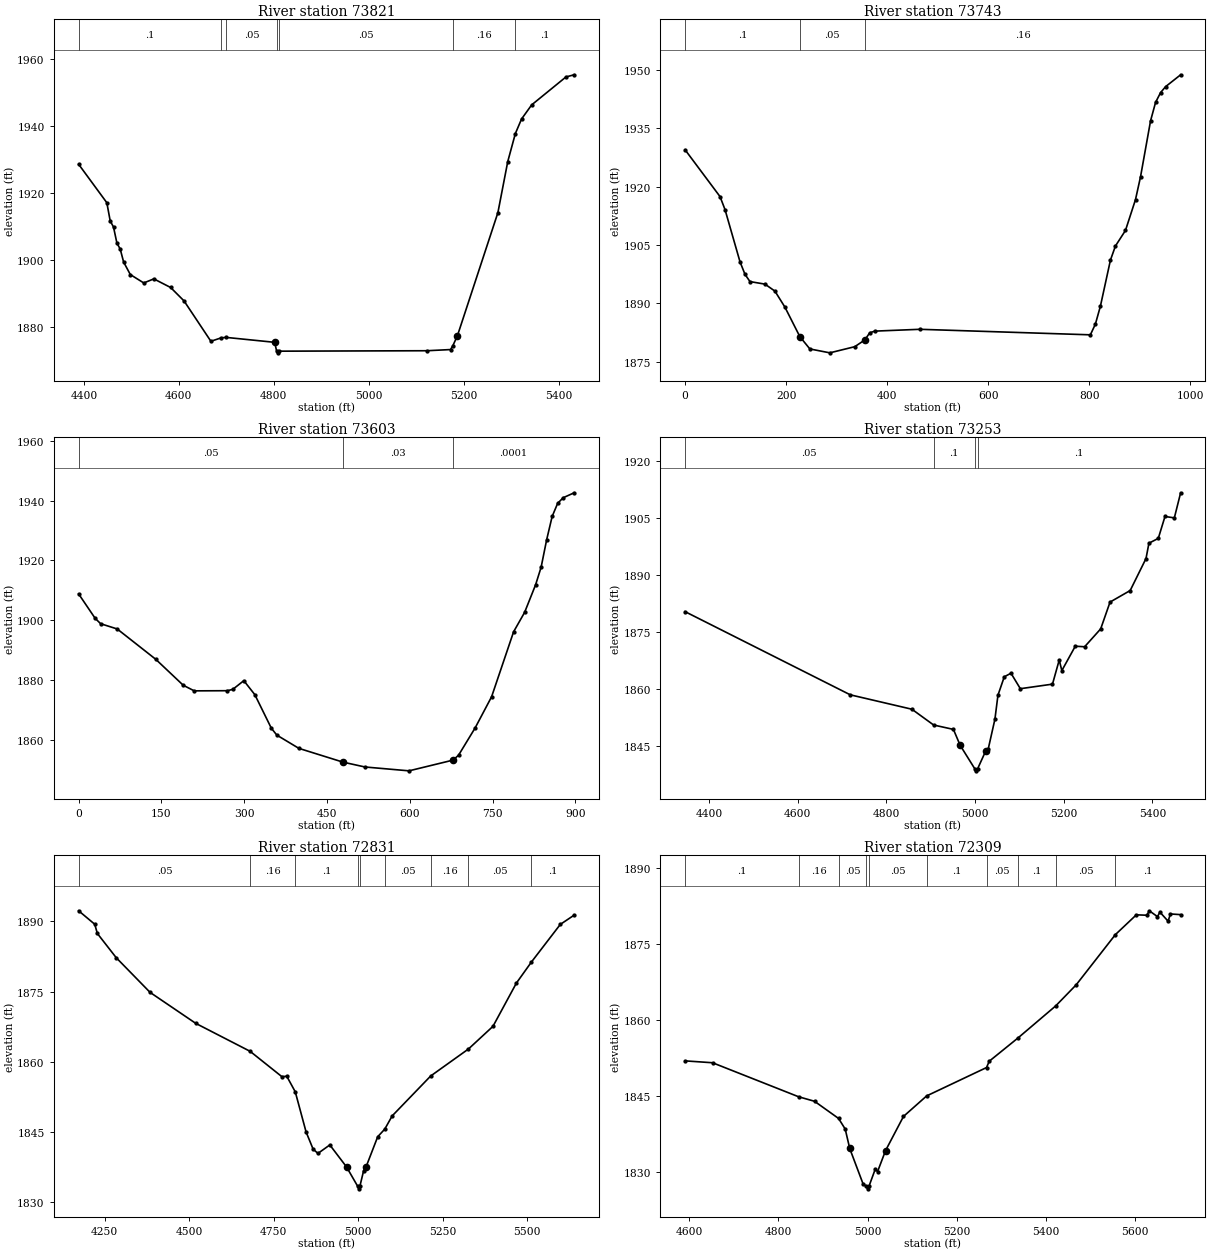
Type RM Length L Ch R = 1 ,73821   ,78,78,78
BEGIN DESCRIPTION:
PALO ALTO CREEK 122.0
END DESCRIPTION:
XS GIS Cut Line= 3
      2752719.05     10095987.14      2752390.89     10095664.19
      2751927.33     10095310.01
#Sta/Elev= 30
    4389 1928.57  4448.4 1917.06  4455.5 1911.62  4462.5 1909.77  4469.6 1904.99
  4476.6 1903.18  4483.8 1899.29  4497.9 1895.55  4526.2 1893.04  4547.4 1894.26
  4582.8 1891.68  4611.1 1887.65  4667.6 1875.58  4689.5 1876.62  4699.8 1876.74
  4801.9 1875.27  4806.1 1872.62  4808.8 1872.12  4812.1 1872.62  5122.5 1872.75
  5172.4  1873.1  5177.3 1874.27  5186.9 1877.25  5272.1 1914.07  5292.9 1929.38
  5308.9 1937.76    5322 1942.13  5343.3 1946.35  5415.5 1954.71  5432.8 1955.36
#Mann= 7 ,-1 , 0
    4389      .1       0  4689.5     .16       0  4699.8     .05       0
  4806.1    .033       0  4812.1     .05       0  5177.3     .16       0
  5308.9      .1       0
Bank Sta=4801.9,5186.9
XS Rating Curve= 0 ,0
Exp/Cntr=0.3,0.1

Type RM Length L Ch R = 1 ,73743   ,140,140,140
BEGIN DESCRIPTION:
Mapping XS 5b94b456
END DESCRIPTION:
XS GIS Cut Line= 3
      2752780.88     10095902.41      2752503.11     10095645.48
      2752010.03     10095289.56
#Sta/Elev= 30
       0 1929.44   69.13 1917.41      79 1914.07  108.63 1900.66   118.5 1897.44
  128.38 1895.57     158 1894.92  177.75 1893.12   197.5 1889.01  227.13 1881.41
  246.88 1878.26  286.38 1877.26  335.75 1878.84  355.51 1880.57  365.38 1882.41
  375.26 1882.84  464.56 1883.31  801.93 1881.89  811.85 1884.64  821.78 1889.25
  841.62 1901.09  851.54 1904.72  871.39 1908.72  891.23 1916.65  901.16  1922.5
     921 1936.88  930.92 1941.62  940.85 1944.14  950.77 1945.67  980.54 1948.72
#Mann= 3 , 0 , 0
       0      .1       0  227.13     .05       0  355.51     .16       0
Bank Sta=227.13,355.51
XS Rating Curve= 0 ,0
Exp/Cntr=0.3,0.1

Type RM Length L Ch R = 1 ,73603   ,350,350,350
BEGIN DESCRIPTION:
PALO ALTO CREEK 121.0
END DESCRIPTION:
XS GIS Cut Line= 2
      2752810.81     10095752.83      2752094.37     10095218.09
#Sta/Elev= 30
       0 1908.81   29.93 1900.65   39.91 1898.84   69.84 1897.09  139.68 1886.95
  189.56 1878.25  209.51 1876.38  269.38 1876.43  279.35 1876.88  299.31 1879.79
  319.26 1875.11  349.19 1863.88  359.17 1861.57  399.08 1857.14  478.89 1852.54
   518.8 1850.91  598.61 1849.62  678.43 1853.21  688.41 1854.85  718.34 1863.94
  748.27 1874.39  788.18 1896.15  808.13 1902.64  828.08 1911.89  838.06 1917.77
  848.04 1926.92  858.01 1934.72  867.99 1939.12  877.97 1940.99  897.92 1942.65
#Mann= 3 , 0 , 0
       0     .05       0  478.89     .03       0  678.43   .0001       0
Bank Sta=478.89,678.43
XS Rating Curve= 0 ,0
Exp/Cntr=0.3,0.1

Type RM Length L Ch R = 1 ,73253   ,422,422,422
BEGIN DESCRIPTION:
PALO ALTO CREEK 120.0
END DESCRIPTION:
XS GIS Cut Line= 2
      2753039.97     10095409.07      2752103.01     10094800.05
#Sta/Elev= 30
  4346.2 1880.28  4718.7 1858.41  4857.7 1854.62  4906.7 1850.47  4951.3 1849.32
  4966.5 1845.13  4999.7 1838.92  5002.5 1838.42  5005.7 1838.92  5023.8 1843.56
  5029.8 1844.17  5044.9 1852.01  5051.7  1858.3    5066 1863.15  5081.1 1864.09
  5102.2 1860.02  5174.7 1861.22  5189.9 1867.56  5195.8 1864.78  5226.1 1871.19
  5247.2 1871.05  5283.4 1875.75  5304.5  1882.8  5349.9 1885.83  5385.6 1894.25
  5392.2 1898.28  5413.3 1899.55  5428.4 1905.31  5449.5 1904.94  5463.7 1911.54
#Mann= 4 ,-1 , 0
  4346.2     .05       0  4906.7      .1       0  4999.7     .07       0
  5005.7      .1       0
Bank Sta=4966.5,5023.8
XS Rating Curve= 0 ,0
Exp/Cntr=0.3,0.1

Type RM Length L Ch R = 1 ,72831   ,522,522,522
BEGIN DESCRIPTION:
PALO ALTO CREEK 119.0
END DESCRIPTION:
XS GIS Cut Line= 3
      2753321.26     10095398.69      2752644.15     10094596.58
      2752227.48     10094601.79
#Sta/Elev= 30
  4172.7 1892.26  4220.4 1889.38  4228.1 1887.41  4284.1 1882.22  4384.2 1874.82
  4519.4  1868.2  4680.2 1862.23  4774.3 1856.81  4788.6 1856.91  4813.8 1853.57
  4845.7 1845.02  4866.6 1841.33  4880.9 1840.42    4916 1842.23  4965.4 1837.54
  4998.8 1833.35  5001.5 1832.85  5004.8 1833.35  5016.1 1836.74  5022.6 1837.42
  5057.7 1843.98  5078.6 1845.61  5100.6 1848.44  5214.5 1856.96  5326.3 1862.73
  5398.8 1867.57  5468.1 1876.81  5512.8 1881.33  5598.1 1889.35  5639.1 1891.33
#Mann= 9 ,-1 , 0
  4172.7     .05       0  4680.2     .16       0  4813.8      .1       0
  4998.8     .07       0  5004.8      .1       0  5078.6     .05       0
  5214.5     .16       0  5326.3     .05       0  5512.8      .1       0
Bank Sta=4965.4,5022.6
XS Rating Curve= 0 ,0
Exp/Cntr=0.3,0.1

Type RM Length L Ch R = 1 ,72309   ,500,500,500
BEGIN DESCRIPTION:
PALO ALTO CREEK 118.0
END DESCRIPTION:
XS GIS Cut Line= 4
      2753232.68     10094565.32      2752961.86     10094367.41
      2752628.53     10094336.16      2752222.87     10094507.79
#Sta/Elev= 30
  4591.1 1851.85  4652.6 1851.48  4845.3 1844.77  4881.2 1843.87  4935.1 1840.48
    4950 1838.38  4960.1 1834.55  4990.2 1827.51  4997.2 1827.08    5000 1826.58
  5003.2 1827.08  5017.4 1830.49  5022.5 1829.98  5040.4 1834.13  5080.6 1840.88
  5132.5 1844.93  5266.7 1850.53  5272.8 1851.78  5337.2 1856.37  5421.7  1862.7
  5467.7 1866.87  5555.5 1876.78  5602.5 1880.69  5626.2 1880.61  5631.6 1881.49
  5649.9 1880.33  5655.3 1881.23  5673.6 1879.44    5679 1880.86  5701.8 1880.73
#Mann= 10 ,-1 , 0
  4591.1      .1       0  4845.3     .16       0  4935.1     .05       0
  4997.2    .035       0  5003.2     .05       0  5132.5      .1       0
  5266.7     .05       0  5337.2      .1       0  5421.7     .05       0
  5555.5      .1       0
Bank Sta=4960.1,5040.4
XS Rating Curve= 0 ,0
Exp/Cntr=0.3,0.1