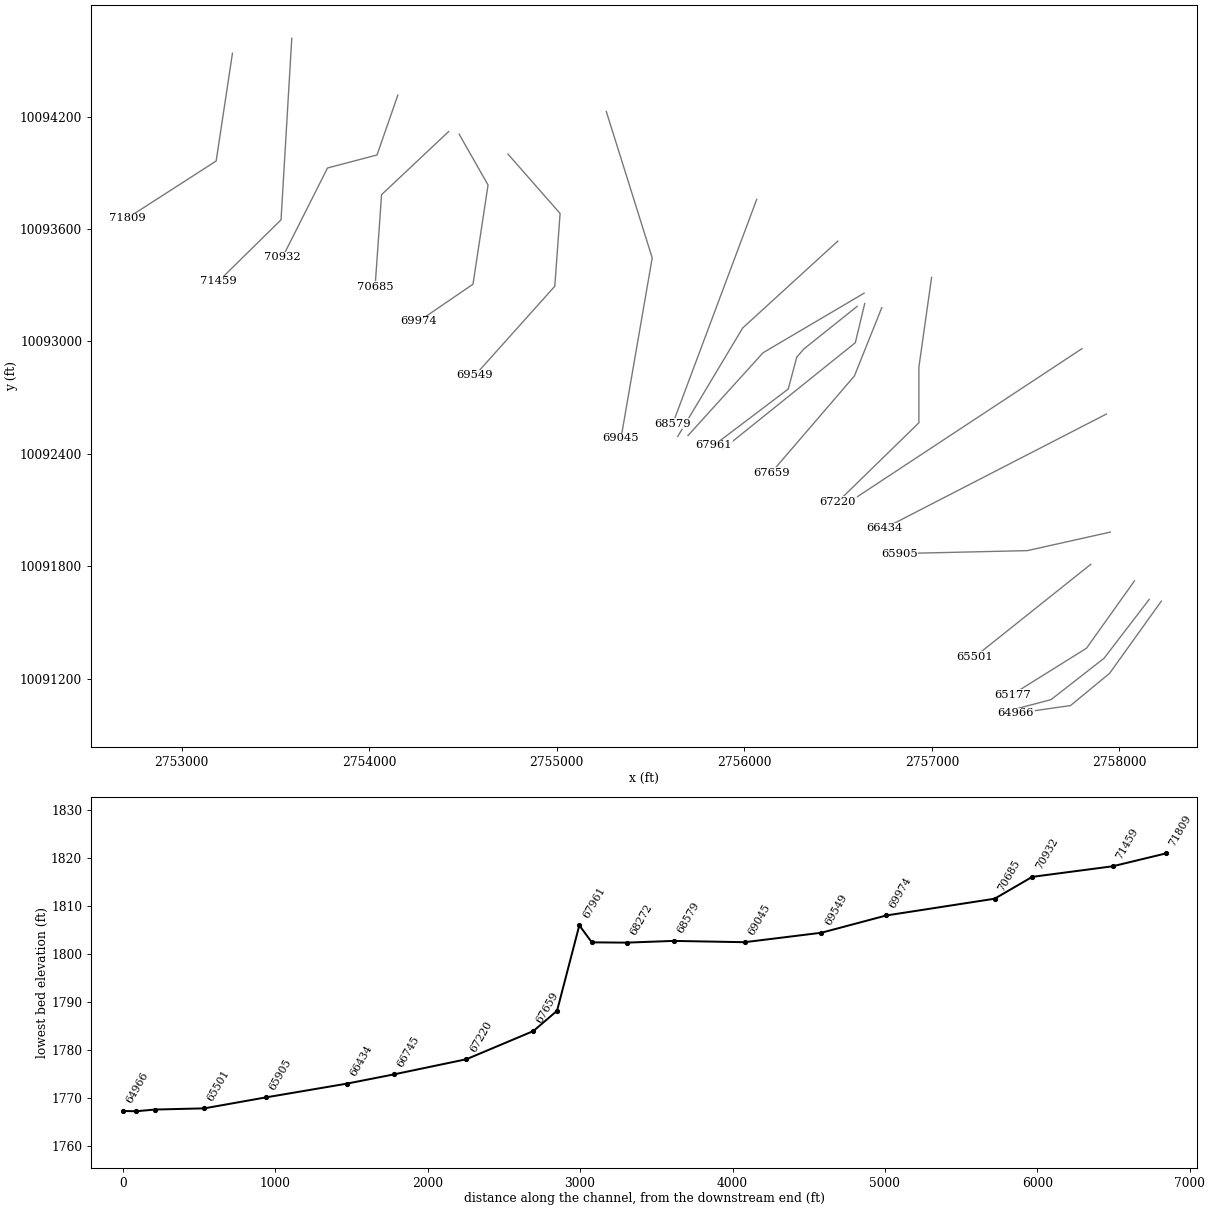
HEC-RAS study PALO ALTO CREEK.prj: PALO ALTO CREEK Base Level Engineering

--- PALO ALTO CREEK.g01 (geometry) --- (continued)

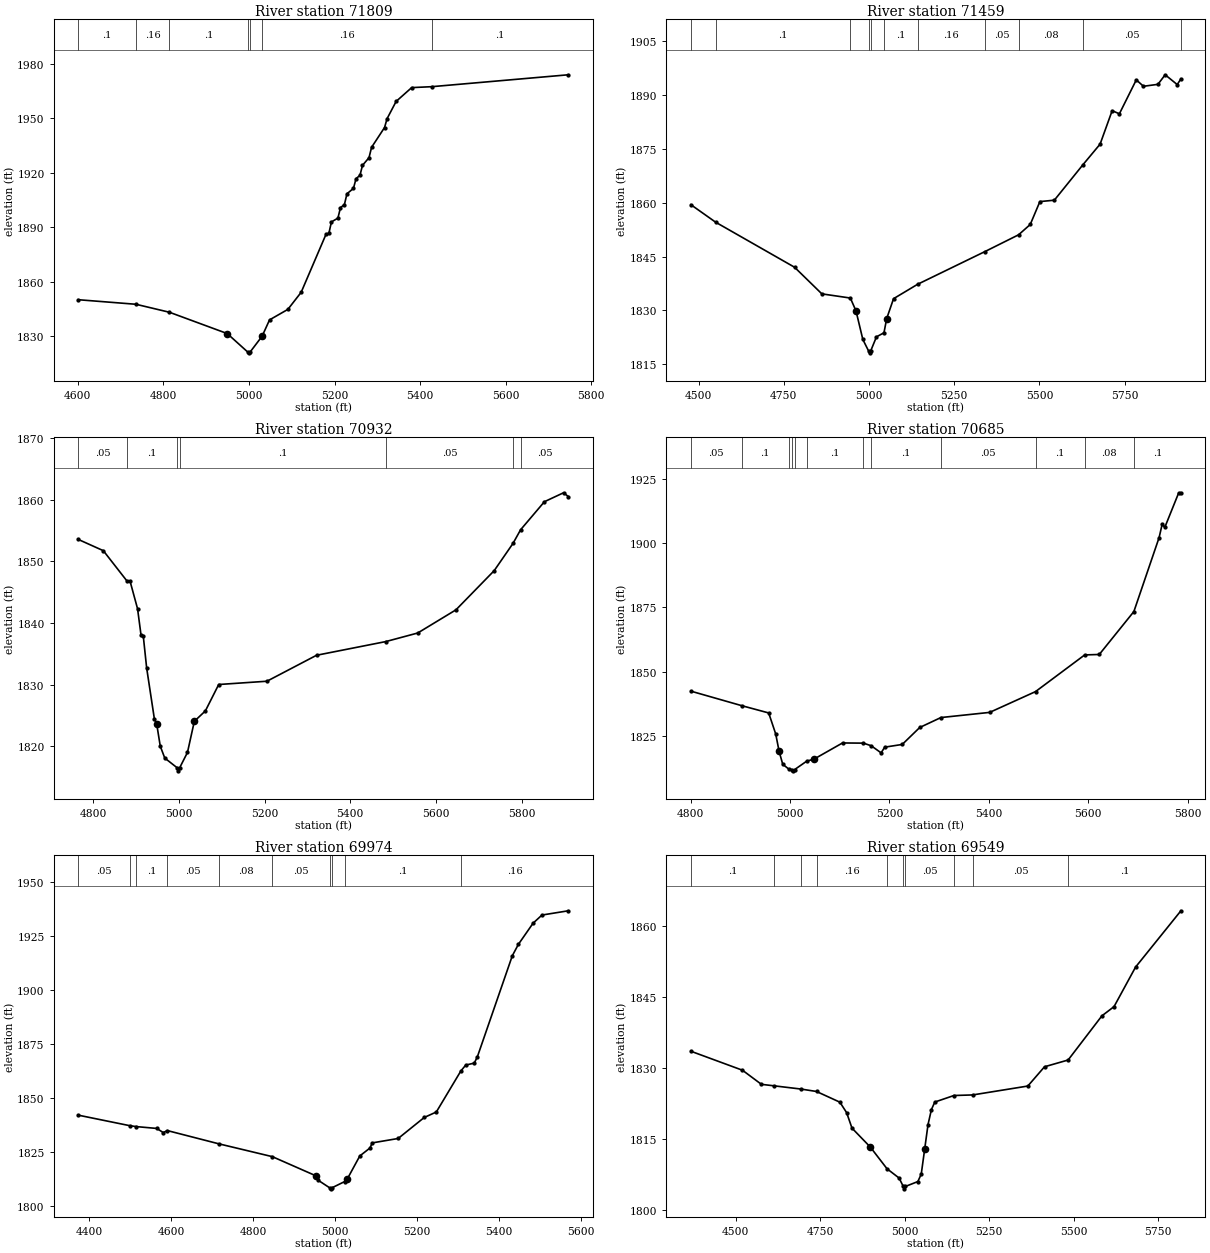
Type RM Length L Ch R = 1 ,71809   ,350,350,350
BEGIN DESCRIPTION:
PALO ALTO CREEK 117.0
END DESCRIPTION:
XS GIS Cut Line= 3
      2753270.54     10094537.72      2753183.73      10093962.6
      2752710.14     10093657.68
#Sta/Elev= 30
  4601.5 1850.11  4736.1 1847.61  4814.4 1843.21  4949.4 1831.49    4997 1821.39
  4999.7 1820.89    5003 1821.39    5031 1830.09  5048.2 1839.02    5091 1844.79
  5122.1  1854.2    5180 1886.02  5186.9 1886.67  5192.8  1892.9    5208 1895.02
  5213.9 1900.75  5223.2  1902.5  5229.1  1908.4  5244.3 1911.37  5250.3 1916.71
  5259.5 1918.54  5265.4 1924.04  5280.6 1928.25  5286.6 1933.95  5316.9 1944.84
  5322.9 1949.75    5344 1959.22  5380.3 1966.81  5427.2 1967.32  5746.4 1973.87
#Mann= 7 ,-1 , 0
  4601.5      .1       0  4736.1     .16       0  4814.4      .1       0
    4997     .07       0    5003      .1       0    5031     .16       0
  5427.2      .1       0
Bank Sta=4949.4,5031
XS Rating Curve= 0 ,0
Exp/Cntr=0.3,0.1

Type RM Length L Ch R = 1 ,71459   ,527,527,527
BEGIN DESCRIPTION:
PALO ALTO CREEK 116.0
END DESCRIPTION:
XS GIS Cut Line= 3
      2753586.86     10094617.37      2753529.57     10093648.66
      2753196.26     10093320.56
#Sta/Elev= 30
  4477.2 1859.43    4550 1854.55  4781.4 1842.03  4861.5 1834.62  4945.1 1833.46
  4961.7 1829.89  4981.7 1821.95  4998.7 1818.71  5001.5 1818.21  5004.7 1818.71
  5021.8 1822.67  5043.8 1823.79  5051.8 1827.75  5071.9 1833.28  5142.6 1837.29
  5340.1 1846.39  5438.9 1851.06  5473.1 1853.93  5501.4  1860.3  5543.8 1860.69
  5628.2 1870.61  5678.1 1876.29  5713.5  1885.6  5734.7 1884.73  5784.3 1894.17
  5805.4 1892.39  5847.8 1892.93  5869.1 1895.59  5904.4 1892.87  5915.3 1894.44
#Mann= 11 ,-1 , 0
  4477.2     .05       0    4550      .1       0  4945.1     .16       0
  4998.7     .07       0  5004.7     .16       0  5043.8      .1       0
  5142.6     .16       0  5340.1     .05       0  5438.9     .08       0
  5628.2     .05       0  5915.3     .16       0
Bank Sta=4961.7,5051.8
XS Rating Curve= 0 ,0
Exp/Cntr=0.3,0.1

Type RM Length L Ch R = 1 ,70932   ,247,247,247
BEGIN DESCRIPTION:
PALO ALTO CREEK 115.0
END DESCRIPTION:
XS GIS Cut Line= 4
      2754152.46     10094314.27      2754041.34     10093994.81
      2753777.46     10093925.37      2753537.89      10093449.7
#Sta/Elev= 30
  4765.5 1853.53  4823.8 1851.71  4879.8 1846.72    4886 1846.81  4903.7 1842.29
  4911.8 1838.02  4917.1 1837.83  4924.9  1832.7  4942.9 1824.45  4948.2 1823.68
  4956.7 1820.01  4967.2 1818.08    4996 1816.51  4998.8 1816.01    5002 1816.51
  5020.2    1819  5036.2 1824.04    5062 1825.73  5093.1 1830.01  5205.6 1830.54
  5321.4 1834.75    5483 1836.97  5557.6 1838.36  5646.9 1842.12  5736.2 1848.48
  5780.1  1852.9  5797.7  1855.1  5853.3 1859.65  5897.9  1861.1  5909.2 1860.49
#Mann= 7 ,-1 , 0
  4765.5     .05       0  4879.8      .1       0    4996     .07       0
    5002      .1       0    5483     .05       0  5780.1     .08       0
  5797.7     .05       0
Bank Sta=4948.2,5036.2
XS Rating Curve= 0 ,0
Exp/Cntr=0.3,0.1

Type RM Length L Ch R = 1 ,70685   ,711,711,711
BEGIN DESCRIPTION:
Mapping XS d0e907a3
END DESCRIPTION:
XS GIS Cut Line= 3
      2754423.25     10094119.78      2754065.65     10093783.01
      2754030.93     10093289.94
#Sta/Elev= 30
  4800.7 1842.41    4903 1836.77  4957.1 1833.95  4971.3 1825.75  4978.1    1819
  4985.4 1814.01  4997.5 1812.15  5003.4 1811.96  5006.2 1811.46  5009.4 1811.96
  5033.2 1815.17  5048.9 1816.08  5105.6 1822.29  5147.8 1822.22  5163.4 1821.19
  5183.2 1818.45  5190.5 1820.66  5225.7 1821.71  5260.9  1828.3  5303.5 1832.16
  5401.5 1834.16  5493.8 1842.24  5592.7 1856.49    5622 1856.66  5691.6 1873.34
  5742.3 1902.05  5748.7  1907.4  5753.7 1905.99  5781.8 1919.47  5786.2 1919.47
#Mann= 12 ,-1 , 0
  4800.7     .05       0    4903      .1       0  4997.5     .05       0
  5003.4     .04       0  5009.4     .05       0  5033.2      .1       0
  5147.8     .05       0  5163.4      .1       0  5303.5     .05       0
  5493.8      .1       0  5592.7     .08       0  5691.6      .1       0
Bank Sta=4978.1,5048.9
XS Rating Curve= 0 ,0
Exp/Cntr=0.3,0.1

Type RM Length L Ch R = 1 ,69974   ,425,425,425
BEGIN DESCRIPTION:
PALO ALTO CREEK 113.0
END DESCRIPTION:
XS GIS Cut Line= 4
       2754479.3     10094105.84      2754633.38     10093834.56
      2754553.09     10093305.05      2754265.34     10093108.17
#Sta/Elev= 30
    4373 1842.04  4499.1 1837.16  4514.3 1836.76  4564.4 1835.91  4580.3 1833.99
  4590.2 1834.92  4716.6 1828.76  4846.5 1822.86  4952.5 1814.03  4958.9 1811.89
  4986.3 1808.47    4989 1807.97  4992.3 1808.47  5023.4 1811.36  5029.7 1812.59
  5060.1 1823.18    5085 1826.87  5090.4 1829.22  5153.7 1831.26  5217.4 1840.98
  5246.9 1843.51  5306.7 1862.46  5318.7 1865.22  5339.6 1866.13  5347.3 1869.16
  5432.4 1915.78  5447.3 1921.08  5483.2 1930.86  5504.8 1934.61  5569.2 1936.58
#Mann= 10 ,-1 , 0
    4373     .05       0  4499.1     .08       0  4514.3      .1       0
  4590.2     .05       0  4716.6     .08       0  4846.5     .05       0
  4986.3     .04       0  4992.3     .05       0  5023.4      .1       0
  5306.7     .16       0
Bank Sta=4952.5,5029.7
XS Rating Curve= 0 ,0
Exp/Cntr=0.3,0.1

Type RM Length L Ch R = 1 ,69549   ,504,504,504
BEGIN DESCRIPTION:
PALO ALTO CREEK 112.0
END DESCRIPTION:
XS GIS Cut Line= 4
      2754739.71     10093999.51       2755017.5     10093682.65
      2754989.29      10093294.2      2754563.91     10092818.91
#Sta/Elev= 30
  4368.1 1833.45  4520.5 1829.44  4576.5 1826.46  4613.4 1826.15  4692.8 1825.47
  4739.4 1824.95  4808.5 1822.69  4828.5 1820.47  4844.3 1817.21  4898.7 1813.19
  4947.9 1808.62  4983.6 1806.66    4996 1804.88  4998.7 1804.38    5002 1804.88
  5039.1 1805.92  5049.1  1807.5  5059.1 1812.71  5069.1 1817.96  5079.2 1821.14
  5089.2 1822.72  5145.8  1824.1  5201.1 1824.22  5364.2  1826.1  5413.5 1830.17
  5483.3  1831.6  5583.2 1840.93  5619.1 1842.88  5682.7 1851.23  5816.8 1863.13
#Mann= 10 ,-1 , 0
  4368.1      .1       0  4613.4     .16       0  4692.8      .1       0
  4739.4     .16       0  4947.9     .05       0    4996     .04       0
    5002     .05       0  5145.8      .1       0  5201.1     .05       0
  5483.3      .1       0
Bank Sta=4898.7,5059.1
XS Rating Curve= 0 ,0
Exp/Cntr=0.3,0.1

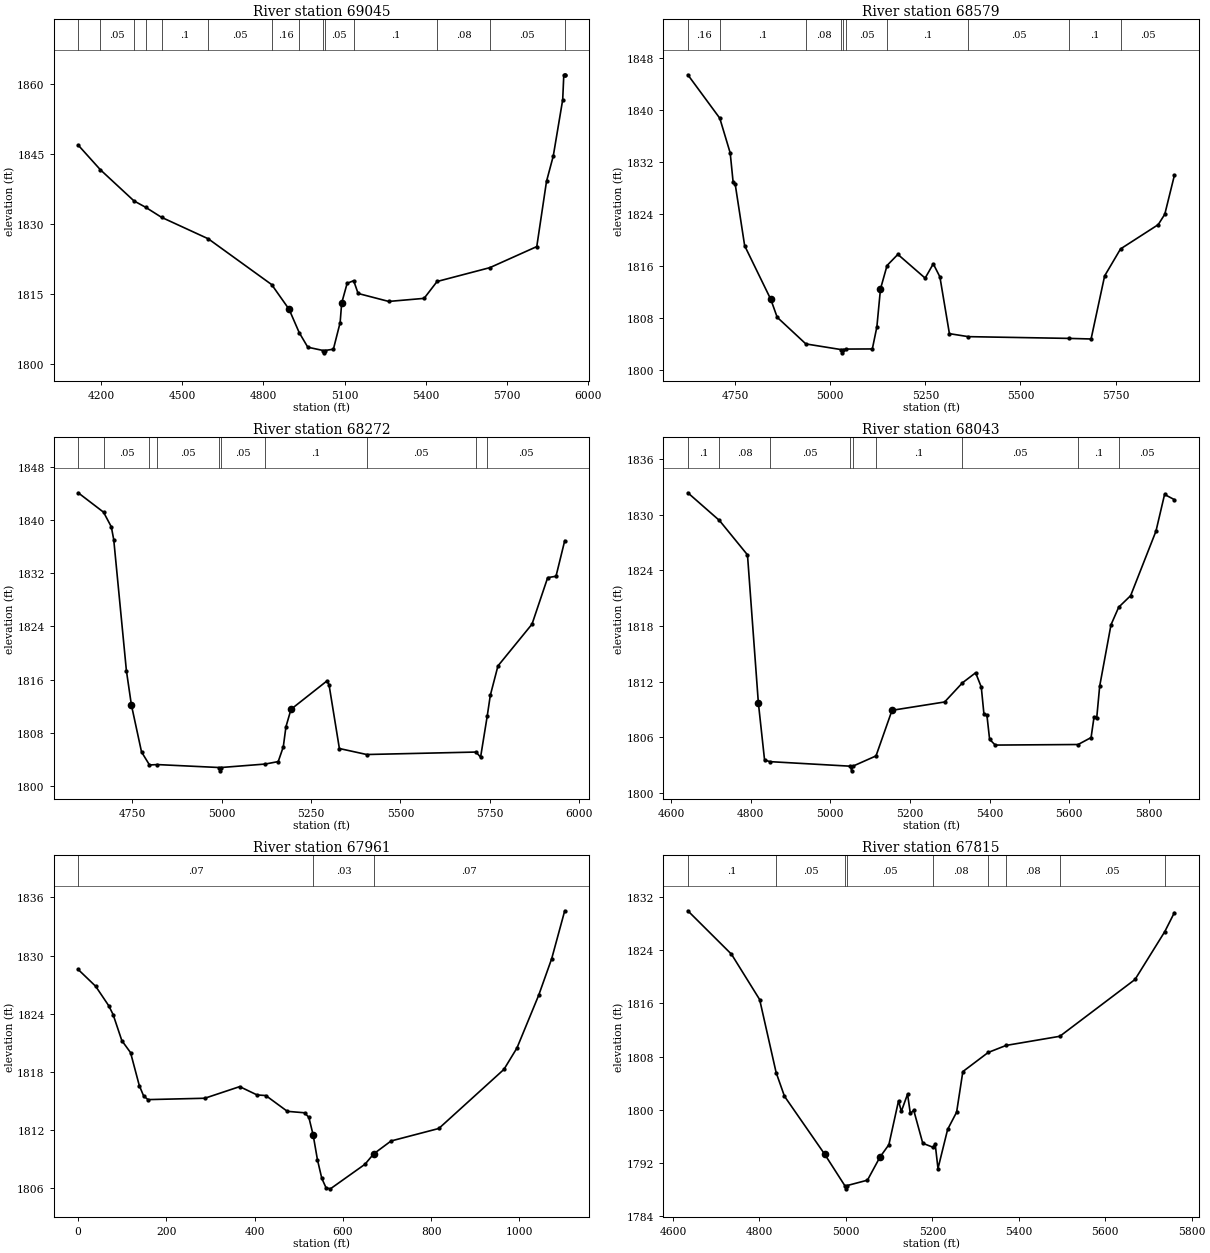
Type RM Length L Ch R = 1 ,69045   ,466,466,466
BEGIN DESCRIPTION:
PALO ALTO CREEK 111.0
END DESCRIPTION:
XS GIS Cut Line= 3
      2755263.95     10094226.78      2755508.73     10093445.54
      2755342.08     10092482.04
#Sta/Elev= 30
  4116.2 1846.99  4198.3 1841.69  4322.3 1835.01  4364.9 1833.66    4424 1831.49
  4596.6 1826.88  4830.7 1817.05  4894.9 1811.76  4932.3 1806.75    4964 1803.62
  5020.7 1802.91  5023.5 1802.41  5026.7 1802.91  5058.5 1803.19  5083.5 1808.92
    5089 1813.06  5109.3 1817.33  5133.4 1817.89  5149.8 1815.15  5262.9 1813.44
  5393.4  1814.1  5441.4 1817.72  5636.2 1820.69  5809.5 1825.21  5845.4  1839.2
  5870.4 1844.65  5905.2 1856.72  5909.3 1862.08  5912.4 1862.08  5912.7 1862.08
#Mann= 14 ,-1 , 0
  4116.2      .1       0  4198.3     .05       0  4322.3      .1       0
  4364.9     .05       0    4424      .1       0  4596.6     .05       0
  4830.7     .16       0  4932.3     .05       0  5020.7     .04       0
  5026.7     .05       0  5133.4      .1       0  5441.4     .08       0
  5636.2     .05       0  5912.4     .16       0
Bank Sta=4894.9,5089
XS Rating Curve= 0 ,0
Exp/Cntr=0.3,0.1

Type RM Length L Ch R = 1 ,68579   ,307,307,307
BEGIN DESCRIPTION:
PALO ALTO CREEK 110.0
END DESCRIPTION:
XS GIS Cut Line= 2
      2756066.03     10093758.05      2755618.12     10092560.16
#Sta/Elev= 30
  4625.7 1845.44  4709.7 1838.76  4737.1 1833.42  4744.8 1828.91  4750.2 1828.63
  4775.1 1819.15  4843.8  1810.9  4860.6 1808.15    4936 1804.05  5028.7 1803.18
  5031.5 1802.68  5034.7 1803.18  5042.7 1803.26  5110.7 1803.28  5122.6 1806.66
  5132.1  1812.5  5149.4 1816.11  5177.8 1817.82  5249.5 1814.17  5270.9 1816.37
  5288.3 1814.36  5313.3 1805.63  5362.8 1805.17  5628.2  1804.9  5685.7 1804.81
  5721.3 1814.51  5763.1 1818.66  5862.1 1822.39  5879.4 1823.99  5904.6 1829.96
#Mann= 10 ,-1 , 0
  4625.7     .16       0  4709.7      .1       0    4936     .08       0
  5028.7     .07       0  5034.7     .08       0  5042.7     .05       0
  5149.4      .1       0  5362.8     .05       0  5628.2      .1       0
  5763.1     .05       0
Bank Sta=4843.8,5132.1
XS Rating Curve= 0 ,0
Exp/Cntr=0.3,0.1

Type RM Length L Ch R = 1 ,68272   ,229,229,229
BEGIN DESCRIPTION:
PALO ALTO CREEK 109.0
END DESCRIPTION:
XS GIS Cut Line= 3
      2756498.04     10093534.86      2755991.21     10093071.53
      2755644.97     10092492.79
#Sta/Elev= 30
  4598.5 1844.06  4669.4 1841.15  4691.2 1838.95    4698 1837.01  4733.4 1817.35
  4747.4  1812.2  4775.7 1805.16    4798  1803.2    4820 1803.26  4992.3 1802.82
    4995 1802.32  4998.3 1802.82  5121.9 1803.34  5158.1 1803.71  5172.3 1805.92
  5179.7 1808.93  5193.9 1811.56  5294.3 1815.81  5300.2 1815.26  5329.2 1805.67
  5405.7 1804.77  5711.4 1805.14  5724.2 1804.37  5742.8 1810.54  5751.4 1813.65
  5772.8 1818.07  5868.1 1824.34  5911.9 1831.32  5935.2 1831.53  5959.6 1836.87
#Mann= 10 ,-1 , 0
  4598.5      .1       0  4669.4     .05       0    4798     .08       0
    4820     .05       0  4992.3    .033       0  4998.3     .05       0
  5121.9      .1       0  5405.7     .05       0  5711.4      .1       0
  5742.8     .05       0
Bank Sta=4747.4,5193.9
XS Rating Curve= 0 ,0
Exp/Cntr=0.3,0.1

Type RM Length L Ch R = 1 ,68043   ,82,82,82
BEGIN DESCRIPTION:
Mapping XS 8b0f184f
END DESCRIPTION:
XS GIS Cut Line= 3
      2756638.54     10093257.21      2756099.93      10092939.4
       2755699.7     10092497.48
#Sta/Elev= 30
  4642.1 1832.38  4721.5 1829.39  4791.9 1825.68  4819.2 1809.72  4834.8 1803.54
    4849 1803.37  5050.4 1802.88  5053.1 1802.38  5056.4 1802.88  5114.6 1803.99
  5154.8 1808.91  5286.9 1809.81  5331.7 1811.88  5364.7 1812.96  5378.9 1811.42
  5385.6  1808.5    5393  1808.4  5399.8 1805.78    5414 1805.16    5622 1805.22
  5654.6 1805.97    5662 1808.19  5668.8 1808.11  5676.2 1811.52  5704.6 1818.14
    5724 1820.04  5753.9 1821.28  5817.5 1828.24  5839.1  1832.2  5863.7 1831.64
#Mann= 9 ,-1 , 0
  4642.1      .1       0  4721.5     .08       0    4849     .05       0
  5050.4    .033       0  5056.4     .05       0  5114.6      .1       0
  5331.7     .05       0    5622      .1       0    5724     .05       0
Bank Sta=4819.2,5154.8
XS Rating Curve= 0 ,0
Exp/Cntr=0.3,0.1

Type RM Length L Ch R = 1 ,67961   ,146,146,146
BEGIN DESCRIPTION:
Mapping XS d5a74b67
END DESCRIPTION:
XS GIS Cut Line= 5
      2756601.68     10093186.92     2756317.876    10092959.876
     2756279.503    10092916.045      2756233.93    10092745.472
     2755836.795    10092444.691
#Sta/Elev= 30
       0 1828.56   39.57 1826.83   69.25 1824.82   79.14 1823.91   98.93 1821.22
  118.71 1819.98   138.5 1816.58  148.39  1815.5  158.28 1815.13  286.89 1815.27
  366.03 1816.47  405.49 1815.61  425.22 1815.55  474.01 1813.92  513.04 1813.77
   522.8  1813.3  532.55 1811.47  542.31 1808.91  552.07 1807.01  561.83 1806.02
  571.59 1805.92  650.06 1808.46  669.74 1809.53   709.1 1810.86  817.34 1812.15
  964.93 1818.25  994.45 1820.46 1043.65  1825.9 1073.17 1829.68 1102.69 1834.62
#Mann= 3 , 0 , 0
       0     .07       0  532.55     .03       0  669.74     .07       0
Bank Sta=532.55,669.74
XS Rating Curve= 0 ,0
Exp/Cntr=0.3,0.1

Type RM Length L Ch R = 1 ,67815   ,156,156,156
BEGIN DESCRIPTION:
Mapping XS 27ea856e
END DESCRIPTION:
XS GIS Cut Line= 3
      2756641.84     10093201.98      2756591.67     10092992.92
      2755882.16     10092421.98
#Sta/Elev= 30
  4634.3 1829.88  4735.3 1823.36  4800.5 1816.55  4838.6  1805.6  4857.9 1802.04
  4950.7 1793.36  4997.3 1788.64    5000 1788.14  5003.3 1788.64  5049.9 1789.44
  5078.7 1792.89  5099.5 1794.77  5121.8 1801.35  5128.3 1799.77  5142.7 1802.36
  5149.1 1799.45    5157 1799.93  5177.9 1794.98  5201.5 1794.38  5206.6 1794.88
  5213.1 1791.19  5235.4 1797.06  5256.2 1799.65  5270.6 1805.74  5329.2 1808.61
  5370.8 1809.67    5495 1811.04    5669 1819.57  5737.9 1826.76    5760  1829.6
#Mann= 9 ,-1 , 0
  4634.3      .1       0  4838.6     .05       0  4997.3     .07       0
  5003.3     .05       0  5201.5     .08       0  5329.2      .1       0
  5370.8     .08       0    5495     .05       0  5737.9      .1       0
Bank Sta=4950.7,5078.7
XS Rating Curve= 0 ,0
Exp/Cntr=0.3,0.1

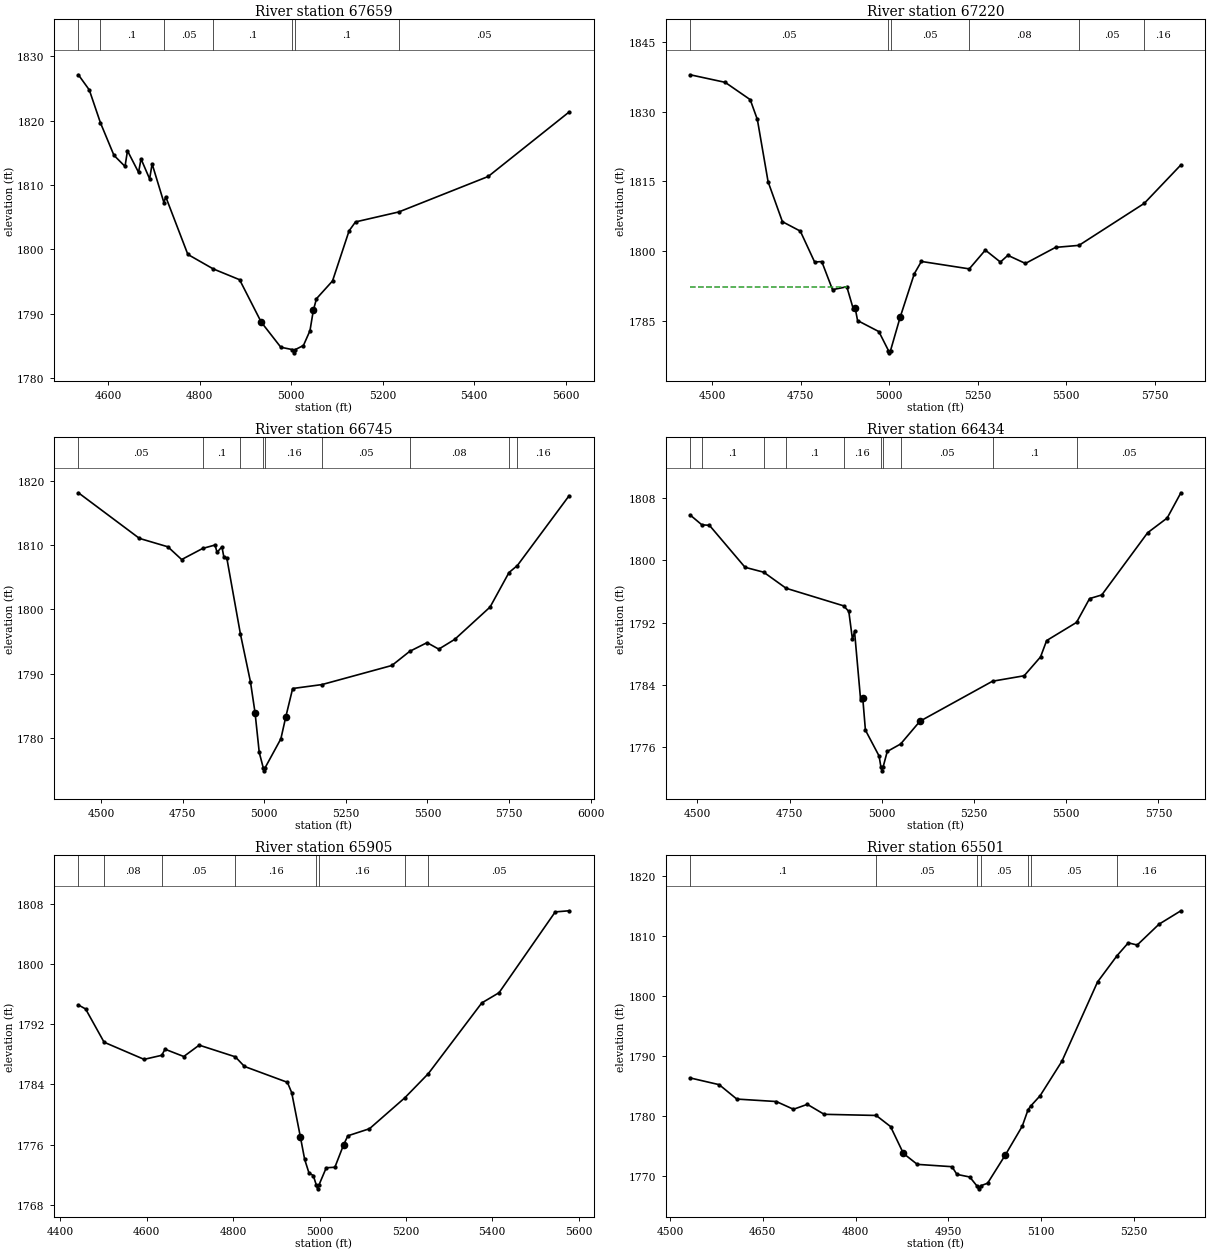
Type RM Length L Ch R = 1 ,67659   ,439,439,439
BEGIN DESCRIPTION:
PALO ALTO CREEK 108.0
END DESCRIPTION:
XS GIS Cut Line= 3
      2756732.69      10093179.9      2756586.86     10092815.33
      2756144.12     10092299.67
#Sta/Elev= 30
  4534.8 1827.11  4558.6 1824.76    4583 1819.65  4612.5  1814.6  4636.7 1812.87
  4642.1  1815.3  4666.3 1811.95  4671.7 1814.04  4690.5 1810.93  4695.9 1813.27
  4721.8 1807.23  4725.6 1808.17    4774  1799.2  4829.5 1796.95  4887.1 1795.27
  4934.4 1788.68  4977.2 1784.78  5002.7 1784.41  5005.5 1783.91  5008.7 1784.41
  5026.6 1785.05  5040.9 1787.35  5048.2 1790.49  5055.1 1792.32  5090.2 1795.08
  5126.4 1802.87  5140.4 1804.25  5235.1  1805.8  5430.4 1811.31  5607.1 1821.32
#Mann= 7 ,-1 , 0
  4534.8     .05       0    4583      .1       0  4721.8     .05       0
  4829.5      .1       0  5002.7     .07       0  5008.7      .1       0
  5235.1     .05       0
Bank Sta=4934.4,5048.2
XS Rating Curve= 0 ,0
Exp/Cntr=0.3,0.1

Type RM Length L Ch R = 1 ,67220   ,475,475,475
BEGIN DESCRIPTION:
PALO ALTO CREEK 107.0
END DESCRIPTION:
XS GIS Cut Line= 4
      2756998.32     10093341.36      2756930.61     10092862.21
      2756930.61     10092565.33      2756498.33     10092143.47
#Sta/Elev= 30
  4438.6 1837.99  4537.2 1836.36  4607.9 1832.63  4628.1 1828.35  4658.4 1814.93
  4698.8 1806.32  4749.3 1804.29  4789.7 1797.63  4809.9 1797.72  4840.2 1791.67
  4880.6 1792.29  4898.9  1787.5    4904 1787.78  4910.9 1785.01    4971 1782.63
    4998 1778.55  5000.7 1778.05    5004 1778.55    5031  1785.7    5071 1795.09
    5091 1797.75  5226.2 1796.15  5271.5  1800.2    5314 1797.62  5335.1 1799.07
  5384.7 1797.32  5469.6 1800.78  5535.8 1801.22    5720 1810.27  5823.4 1818.56
#Mann= 6 ,-1 , 0
  4438.6     .05       0    4998     .04       0    5004     .05       0
  5226.2     .08       0  5535.8     .05       0    5720     .16       0
#XS Ineff= 2 , 0
         4879.81 1792.28
Permanent Ineff=
       F       F
Bank Sta=4904,5031
XS Rating Curve= 0 ,0
Exp/Cntr=0.3,0.1

Type RM Length L Ch R = 1 ,66745   ,311,311,311
BEGIN DESCRIPTION:
PALO ALTO CREEK 106.0
END DESCRIPTION:
XS GIS Cut Line= 2
      2757800.41     10092961.17      2756545.18     10092133.03
#Sta/Elev= 30
  4430.3 1818.13  4617.3 1811.04  4704.6 1809.73  4746.8 1807.75  4811.4 1809.48
  4849.2 1810.01  4855.2 1808.87  4870.2 1809.72  4876.2 1808.14  4885.3 1807.95
  4926.9 1796.17  4957.6 1788.76  4971.7 1783.95  4984.6 1777.76  4996.7  1775.4
  4999.4  1774.9  5002.7  1775.4  5050.9 1779.88  5065.9 1783.28    5087  1787.7
  5176.8 1788.31  5391.1 1791.28  5445.8 1793.48  5498.9 1794.83  5534.8 1793.82
  5583.7 1795.34  5692.1 1800.37    5750 1805.73  5775.7 1806.82  5934.1 1817.66
#Mann= 9 ,-1 , 0
  4430.3     .05       0  4811.4      .1       0  4926.9     .16       0
  4996.7     .07       0  5002.7     .16       0  5176.8     .05       0
  5445.8     .08       0    5750     .05       0  5775.7     .16       0
Bank Sta=4971.7,5065.9
XS Rating Curve= 0 ,0
Exp/Cntr=0.3,0.1

Type RM Length L Ch R = 1 ,66434   ,529,529,529
BEGIN DESCRIPTION:
PALO ALTO CREEK 105.0
END DESCRIPTION:
XS GIS Cut Line= 2
      2757930.57     10092612.18      2756748.36     10092002.85
#Sta/Elev= 30
  4480.8 1805.81  4512.2 1804.56  4532.9 1804.49  4629.4  1799.1    4680 1798.47
  4740.6 1796.41  4896.6 1794.15  4910.7 1793.43  4920.6 1789.84  4926.2 1790.87
  4942.8 1782.02  4948.4 1782.35  4955.7 1778.19  4992.7 1774.87  4997.7 1773.46
  5000.4 1772.96  5003.7 1773.46  5014.9 1775.45  5051.2 1776.41  5103.5 1779.33
  5300.2 1784.47    5386 1785.17  5430.4 1787.59  5446.9 1789.69  5527.9 1792.02
  5563.3 1795.08  5596.4 1795.55  5720.7 1803.54  5773.7 1805.43  5810.8 1808.67
#Mann= 10 ,-1 , 0
  4480.8     .05       0  4512.2      .1       0    4680     .05       0
  4740.6      .1       0  4896.6     .16       0  4997.7     .07       0
  5003.7     .16       0  5051.2     .05       0  5300.2      .1       0
  5527.9     .05       0
Bank Sta=4948.4,5103.5
XS Rating Curve= 0 ,0
Exp/Cntr=0.3,0.1

Type RM Length L Ch R = 1 ,65905   ,404,404,404
BEGIN DESCRIPTION:
PALO ALTO CREEK 104.0
END DESCRIPTION:
XS GIS Cut Line= 3
      2757951.45       10091982.      2757508.73     10091883.04
      2756826.45     10091867.41
#Sta/Elev= 30
  4441.7 1794.55  4458.4 1794.02  4501.2  1789.6  4593.8 1787.32  4634.7 1787.86
  4642.3 1788.67  4685.7  1787.7  4721.4 1789.21    4805 1787.66  4826.2 1786.38
  4925.6 1784.27  4935.6  1782.9  4955.6 1777.05  4965.6 1774.03  4975.6 1772.22
  4985.6 1771.88  4992.6 1770.61  4995.4 1770.11  4998.6 1770.61  5015.6 1772.91
  5035.6 1772.98  5055.6 1775.94  5065.6 1777.16  5115.7  1778.1  5197.5 1782.21
  5251.9 1785.42  5375.7 1794.82  5415.7 1796.18  5545.8 1806.92  5577.8 1807.07
#Mann= 8 ,-1 , 0
  4441.7      .1       0  4501.2     .08       0  4634.7     .05       0
    4805     .16       0  4992.6     .07       0  4998.6     .16       0
  5197.5      .1       0  5251.9     .05       0
Bank Sta=4955.6,5055.6
XS Rating Curve= 0 ,0
Exp/Cntr=0.3,0.1

Type RM Length L Ch R = 1 ,65501   ,324,324,324
BEGIN DESCRIPTION:
PALO ALTO CREEK 103.0
END DESCRIPTION:
XS GIS Cut Line= 2
      2757847.29     10091810.13      2757227.47     10091315.32
#Sta/Elev= 30
  4532.8 1786.31  4579.6 1785.19  4608.1 1782.79    4672 1782.38  4699.7 1781.09
  4722.1 1781.91  4749.3 1780.25  4833.4 1780.06  4856.6 1778.21  4877.4 1773.73
  4899.8 1771.91  4955.9 1771.52  4963.9 1770.24  4984.7  1769.8  4996.1 1768.33
  4998.9 1767.83  5002.1 1768.33  5013.5 1768.77  5042.3  1773.5  5069.5 1778.27
  5078.8 1780.99  5083.1 1781.62  5098.4 1783.35  5133.6 1789.09  5191.2 1802.31
  5222.9 1806.71  5240.9 1808.83  5255.3 1808.46  5290.5 1811.93  5325.9 1814.17
#Mann= 7 ,-1 , 0
  4532.8      .1       0  4833.4     .05       0  4996.1     .04       0
  5002.1     .05       0  5078.8     .08       0  5083.1     .05       0
  5222.9     .16       0
Bank Sta=4877.4,5042.3
XS Rating Curve= 0 ,0
Exp/Cntr=0.3,0.1

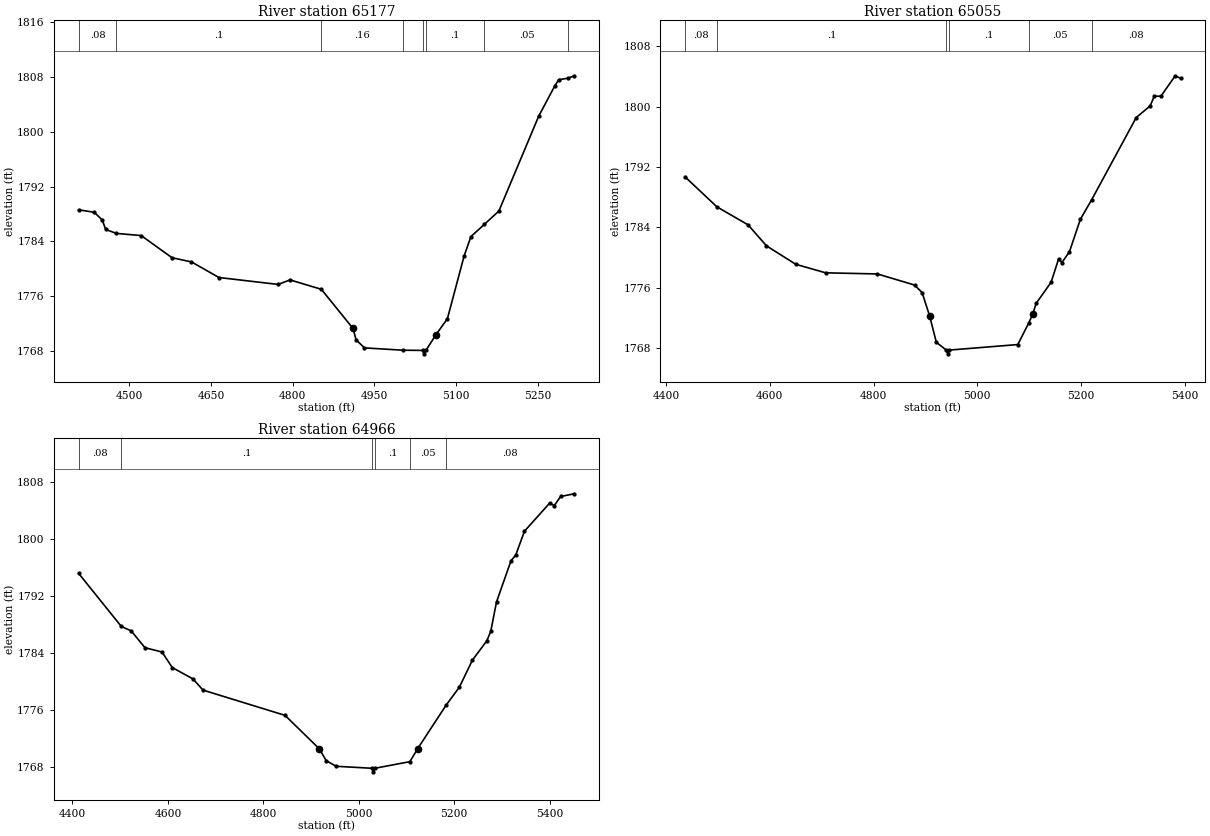
Type RM Length L Ch R = 1 ,65177   ,122,122,122
BEGIN DESCRIPTION:
Mapping XS 4d35c4b4
END DESCRIPTION:
XS GIS Cut Line= 3
      2758080.28      10091721.8      2757824.35     10091362.16
      2757427.91      10091114.6
#Sta/Elev= 30
  4407.4 1788.62  4436.1 1788.26  4450.8 1787.12    4457 1785.75  4476.8 1785.17
  4522.1 1784.86  4578.7 1781.62  4614.3 1781.01  4664.8 1778.73  4773.2 1777.72
  4795.1 1778.38  4852.5 1777.01  4910.4 1771.31  4916.3 1769.62  4931.6 1768.45
  5002.3 1768.11  5038.3 1768.08    5041 1767.58  5044.3 1768.08  5062.5 1770.35
  5083.7 1772.71  5114.4 1781.89  5126.9 1784.71  5151.7 1786.51  5178.1 1788.44
  5251.2 1802.31  5280.2 1806.65  5287.8 1807.62  5305.6 1807.86  5316.2  1808.2
#Mann= 8 ,-1 , 0
  4407.4     .08       0  4476.8      .1       0  4852.5     .16       0
  5002.3      .1       0  5038.3     .07       0  5044.3      .1       0
  5151.7     .05       0  5305.6     .16       0
Bank Sta=4910.4,5062.5
XS Rating Curve= 0 ,0
Exp/Cntr=0.3,0.1

Type RM Length L Ch R = 1 ,65055   ,89,89,89
BEGIN DESCRIPTION:
PALO ALTO CREEK 102.0
END DESCRIPTION:
XS GIS Cut Line= 4
      2758158.87     10091623.09      2757918.01     10091308.64
      2757635.35     10091087.86       2757441.6     10091036.53
#Sta/Elev= 30
  4436.8 1790.69    4498 1786.72  4558.2 1784.33  4593.6 1781.55  4650.1  1779.1
  4707.8 1777.97  4807.5 1777.82  4879.1 1776.35  4893.6 1775.36    4908 1772.29
  4921.1 1768.76  4940.3 1767.73  4943.1 1767.23  4946.3 1767.73  5078.1 1768.46
    5099 1771.29    5107 1772.51  5113.4 1773.91  5142.3 1776.72  5156.8 1779.82
  5163.1 1779.33  5177.6 1780.75  5198.7 1785.06  5220.6 1787.67  5306.3 1798.54
  5333.2  1800.1  5341.3 1801.39  5353.9 1801.38  5381.6 1804.09    5392 1803.74
#Mann= 6 ,-1 , 0
  4436.8     .08       0    4498      .1       0  4940.3     .07       0
  4946.3      .1       0    5099     .05       0  5220.6     .08       0
Bank Sta=4908,5107
XS Rating Curve= 0 ,0
Exp/Cntr=0.3,0.1

Type RM Length L Ch R = 1 ,64966   ,45,45,45
BEGIN DESCRIPTION:
Mapping XS d13a9d3c
END DESCRIPTION:
XS GIS Cut Line= 4
      2758223.35     10091613.39      2757947.32     10091227.99
      2757738.98     10091056.11      2757447.28     10091014.44
#Sta/Elev= 30
  4412.9 1795.15  4502.4  1787.7  4523.2 1787.07    4552 1784.71  4587.6 1784.11
  4609.3 1781.92  4652.7 1780.33  4673.6 1778.76  4845.6 1775.21  4917.5 1770.51
  4931.9 1768.85  4952.7 1768.06  5027.9 1767.78  5030.6 1767.28  5033.9 1767.78
  5107.3 1768.71  5123.4 1770.51    5183 1776.62  5211.2 1779.19  5238.4 1782.97
  5268.7 1785.69  5276.8 1787.01  5288.9 1791.14  5319.2 1796.91  5329.3 1797.74
  5347.5 1801.07    5400    1805  5410.1 1804.68  5423.3 1805.95  5451.7 1806.33
#Mann= 6 ,-1 , 0
  4412.9     .08       0  4502.4      .1       0  5027.9     .07       0
  5033.9      .1       0  5107.3     .05       0    5183     .08       0
Bank Sta=4917.5,5123.4
XS Rating Curve= 0 ,0
Exp/Cntr=0.3,0.1