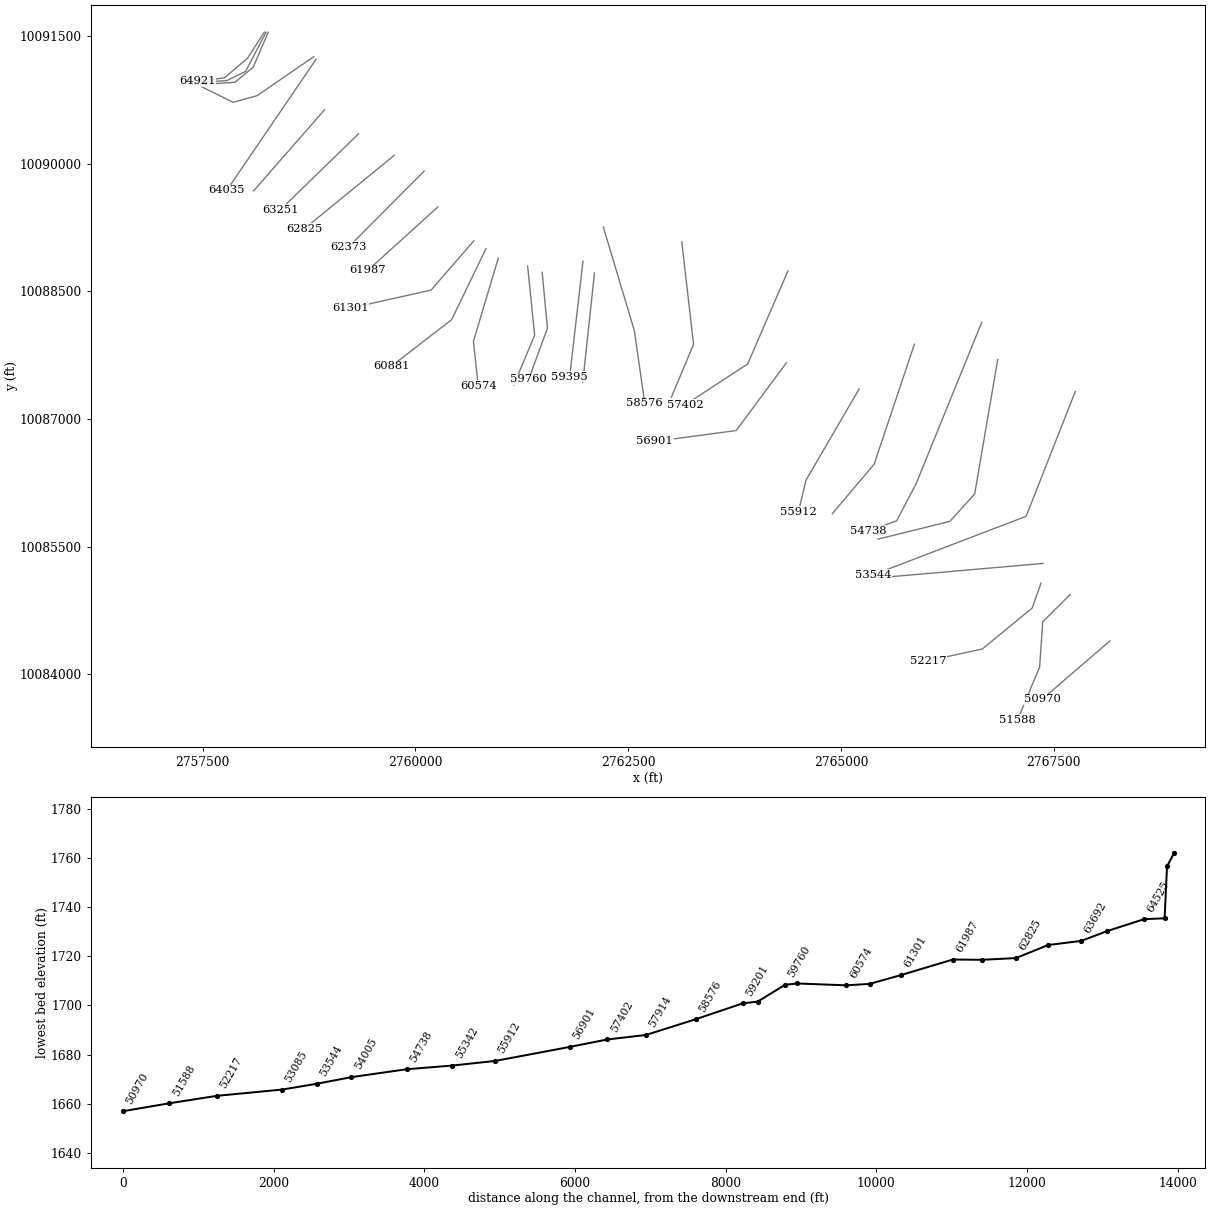
HEC-RAS study PALO ALTO CREEK.prj: PALO ALTO CREEK Base Level Engineering

--- PALO ALTO CREEK.g01 (geometry) --- (continued)

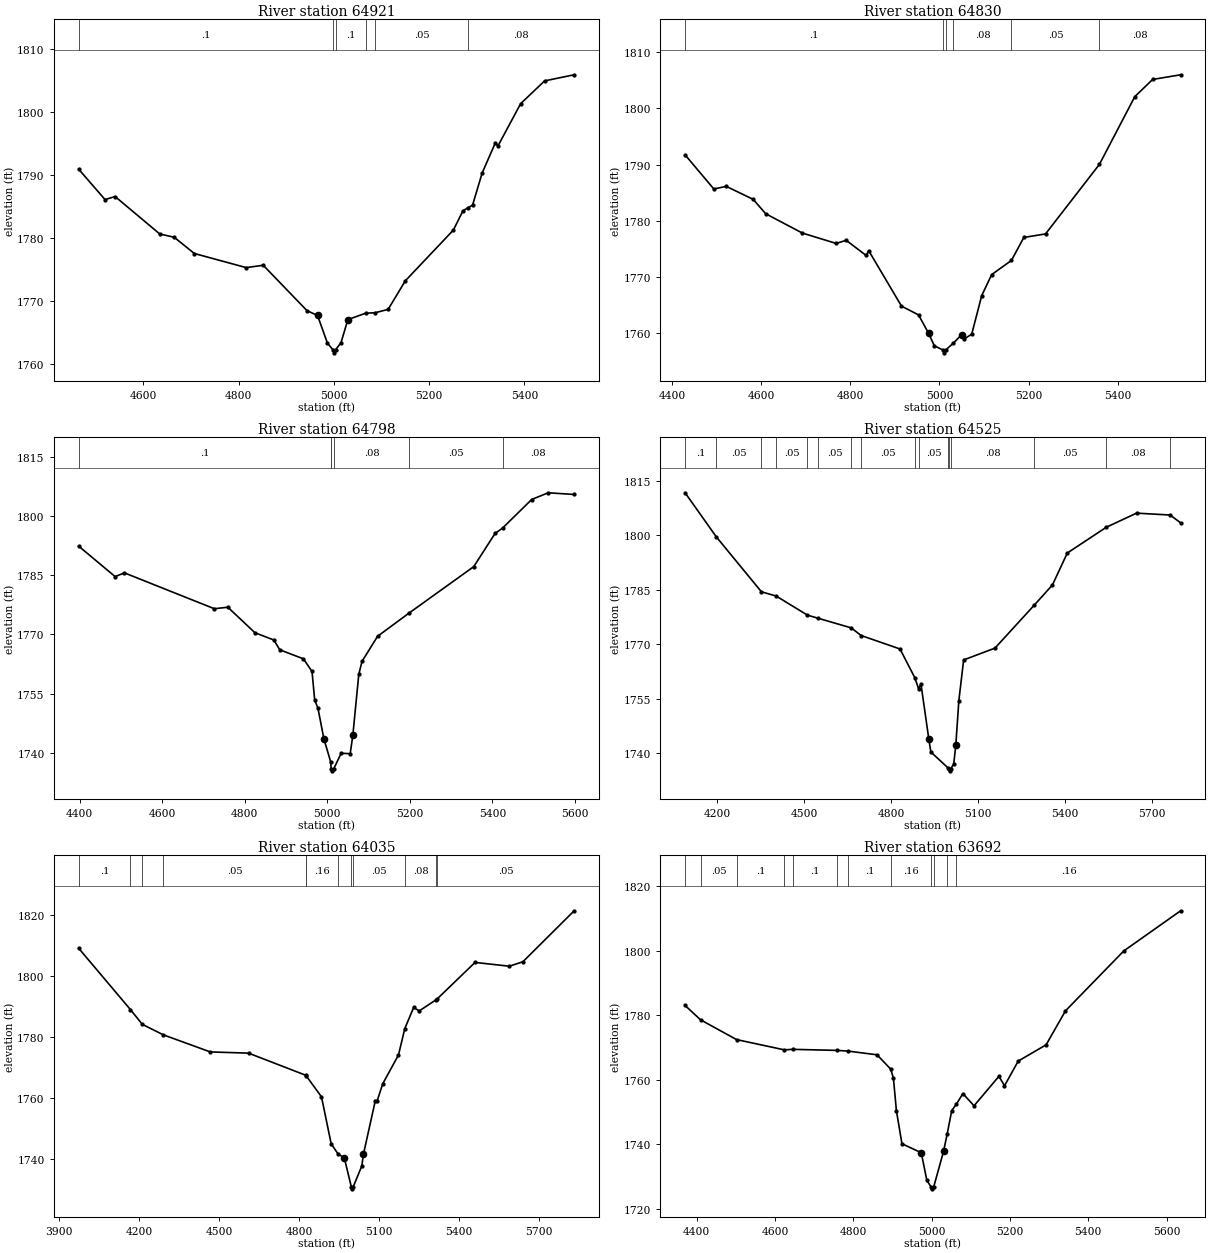
Type RM Length L Ch R = 1 ,64921   ,91,91,91
BEGIN DESCRIPTION:
Mapping XS e40175b9
END DESCRIPTION:
XS GIS Cut Line= 4
      2758223.34     10091545.66      2758025.44     10091238.41
      2757754.61     10091009.24      2757436.88     10090967.57
#Sta/Elev= 30
  4463.8 1790.99  4519.3 1786.15  4540.4 1786.64  4634.2 1780.69  4664.5 1780.17
  4706.8 1777.59  4815.7 1775.35  4851.5 1775.72  4943.4 1768.51  4965.5 1767.75
  4986.3 1763.36  4997.6 1762.31  5000.4 1761.81  5003.6 1762.31  5014.9 1763.44
  5029.2 1767.09  5066.5  1768.1  5086.4 1768.18  5113.7 1768.71  5150.1 1773.27
  5250.8 1781.31  5270.9 1784.37  5282.1 1784.89  5291.1 1785.27  5311.3 1790.39
  5339.1 1795.19  5344.2 1794.64    5392 1801.38  5442.4 1805.01  5504.5 1805.98
#Mann= 6 ,-1 , 0
  4463.8      .1       0  4997.6     .07       0  5003.6      .1       0
  5066.5     .08       0  5086.4     .05       0  5282.1     .08       0
Bank Sta=4965.5,5029.2
XS Rating Curve= 0 ,0
Exp/Cntr=0.3,0.1

Type RM Length L Ch R = 1 ,64830   ,32,32,32
BEGIN DESCRIPTION:
Mapping XS cb55f5fa
END DESCRIPTION:
XS GIS Cut Line= 4
      2758244.29     10091544.25       2758004.7      10091085.9
      2757784.64     10090976.52      2757435.69     10090955.69
#Sta/Elev= 30
  4428.9 1791.72  4493.5 1785.65  4521.2 1786.13  4581.8 1783.81    4610 1781.25
  4692.2 1777.82    4768 1775.98  4790.6 1776.53  4835.4 1773.84  4841.1 1774.69
  4914.7 1764.84    4953 1763.27  4975.4 1760.03  4988.4 1757.78  5007.8 1757.03
  5010.5 1756.53  5013.8 1757.03  5031.3 1758.26    5050 1759.78  5055.6 1758.99
  5072.4 1759.85  5094.8  1766.7  5117.2 1770.44  5161.6 1772.96  5189.3 1777.04
  5238.1 1777.67  5359.1 1790.04  5438.4 1802.06  5478.5 1805.13  5541.4 1805.96
#Mann= 6 ,-1 , 0
  4428.9      .1       0  5007.8     .07       0  5013.8      .1       0
  5031.3     .08       0  5161.6     .05       0  5359.1     .08       0
Bank Sta=4975.4,5050
XS Rating Curve= 0 ,0
Exp/Cntr=0.3,0.1

Type RM Length L Ch R = 1 ,64798   ,273,273,273
BEGIN DESCRIPTION:
Mapping XS 06707309
END DESCRIPTION:
XS GIS Cut Line= 4
      2758270.23     10091545.69      2758093.15     10091134.24
      2757879.61     10090957.16      2757405.69     10090925.91
#Sta/Elev= 30
  4397.7 1792.38  4486.1 1784.65  4508.7 1785.59  4726.4 1776.51  4759.1 1776.89
  4824.7 1770.43  4870.6 1768.58  4884.9  1766.1  4942.2 1763.81    4963 1760.61
  4969.5 1753.37  4977.4  1751.3  4991.7 1743.57    5008 1737.79  5009.5 1735.93
  5012.3 1735.43  5015.5 1735.93  5033.6 1739.88  5055.5 1739.78    5062 1744.54
  5076.3  1759.9  5084.2 1763.19  5121.8 1769.52  5199.1 1775.49  5354.7 1787.17
  5406.5  1795.6  5424.4 1796.93    5495 1804.18  5535.1 1805.89    5598 1805.46
#Mann= 6 ,-1 , 0
  4397.7      .1       0    5008     .08       0  5009.5     .07       0
  5015.5     .08       0  5199.1     .05       0  5424.4     .08       0
Bank Sta=4991.7,5062
XS Rating Curve= 0 ,0
Exp/Cntr=0.3,0.1

Type RM Length L Ch R = 1 ,64525   ,490,490,490
BEGIN DESCRIPTION:
PALO ALTO CREEK 101.0
END DESCRIPTION:
XS GIS Cut Line= 4
       2758805.6     10091258.03      2758138.94     10090799.71
      2757857.69     10090721.58      2757312.14     10090991.76
#Sta/Elev= 30
  4089.2 1811.69  4197.3  1799.5  4352.5 1784.41  4403.5 1783.23  4511.3 1777.97
  4546.2 1777.16  4662.5 1774.46  4696.5 1772.36  4830.7 1768.65  4881.8 1760.72
    4895 1757.63  4902.9 1759.05  4929.8 1743.96  4937.1 1740.26  4996.7 1735.85
  4999.5 1735.57  5002.2 1735.07  5005.5 1735.57    5016 1736.96  5023.2 1742.14
  5033.6 1754.36  5050.2 1765.63  5158.2 1768.88  5293.9 1780.73  5356.6 1786.29
  5407.9 1795.09  5542.6  1802.2  5646.8 1806.08  5762.8 1805.56  5798.9  1803.4
#Mann= 16 ,-1 , 0
  4089.2      .1       0  4197.3     .05       0  4352.5      .1       0
  4403.5     .05       0  4511.3      .1       0  4546.2     .05       0
  4662.5     .08       0  4696.5     .05       0  4881.8     .16       0
    4895     .05       0  4996.7     .08       0  4999.5     .07       0
  5005.5     .08       0  5293.9     .05       0  5542.6     .08       0
  5762.8      .1       0
Bank Sta=4929.8,5023.2
XS Rating Curve= 0 ,0
Exp/Cntr=0.3,0.1

Type RM Length L Ch R = 1 ,64035   ,343,343,343
BEGIN DESCRIPTION:
PALO ALTO CREEK 100.0
END DESCRIPTION:
XS GIS Cut Line= 2
      2758831.64     10091226.77      2757784.77     10089690.32
#Sta/Elev= 30
  3972.4    1809  4166.8  1788.9  4211.4 1784.07  4290.2 1780.64  4466.3 1775.05
  4609.9 1774.65  4824.5 1767.41  4825.8 1767.28  4883.6 1760.34  4919.9 1744.97
  4947.1 1741.49    4969 1740.43  4995.9 1730.73  4998.6 1730.23  5001.9 1730.73
  5034.8 1737.71  5040.9 1741.54  5085.6 1759.14  5091.7 1758.82  5113.5 1764.65
  5172.4 1774.04  5196.2 1782.69  5229.3  1789.6  5250.3 1788.47  5314.9  1792.2
    5318 1792.43  5459.7 1804.35  5588.4  1803.1  5639.2 1804.56  5831.6 1821.25
#Mann= 12 ,-1 , 0
  3972.4      .1       0  4166.8     .05       0  4211.4      .1       0
  4290.2     .05       0  4824.5      .1       0  4825.8     .16       0
  4947.1     .05       0  4995.9     .04       0  5001.9     .05       0
  5196.2     .08       0  5314.9     .16       0    5318     .05       0
Bank Sta=4969,5040.9
XS Rating Curve= 0 ,0
Exp/Cntr=0.3,0.1

Type RM Length L Ch R = 1 ,63692   ,441,441,441
BEGIN DESCRIPTION:
PALO ALTO CREEK 99.0
END DESCRIPTION:
XS GIS Cut Line= 2
      2758930.58     10090633.01      2758097.29     10089679.93
#Sta/Elev= 30
  4370.1 1783.03  4409.8 1778.58  4501.6 1772.47  4623.7 1769.29  4644.5 1769.45
  4759.4 1769.12  4787.3 1768.89  4860.5 1767.76  4895.2 1763.35  4902.3 1760.57
  4909.9 1750.49  4924.1 1740.21  4973.5 1737.43  4987.7 1728.88    4999 1726.75
  5001.7 1726.25    5005 1726.75  5030.4 1737.86  5039.8 1743.32  5051.3 1750.49
  5063.4  1752.5  5079.8 1755.75  5108.3 1751.97  5171.9  1761.1  5186.1 1758.17
  5221.2 1765.82  5292.4 1770.85  5341.8 1781.36  5490.8 1799.92  5636.1 1812.36
#Mann= 12 ,-1 , 0
  4370.1      .1       0  4409.8     .05       0  4501.6      .1       0
  4623.7     .05       0  4644.5      .1       0  4759.4     .05       0
  4787.3      .1       0  4895.2     .16       0    4999     .07       0
    5005     .16       0  5039.8     .05       0  5063.4     .16       0
Bank Sta=4973.5,5030.4
XS Rating Curve= 0 ,0
Exp/Cntr=0.3,0.1

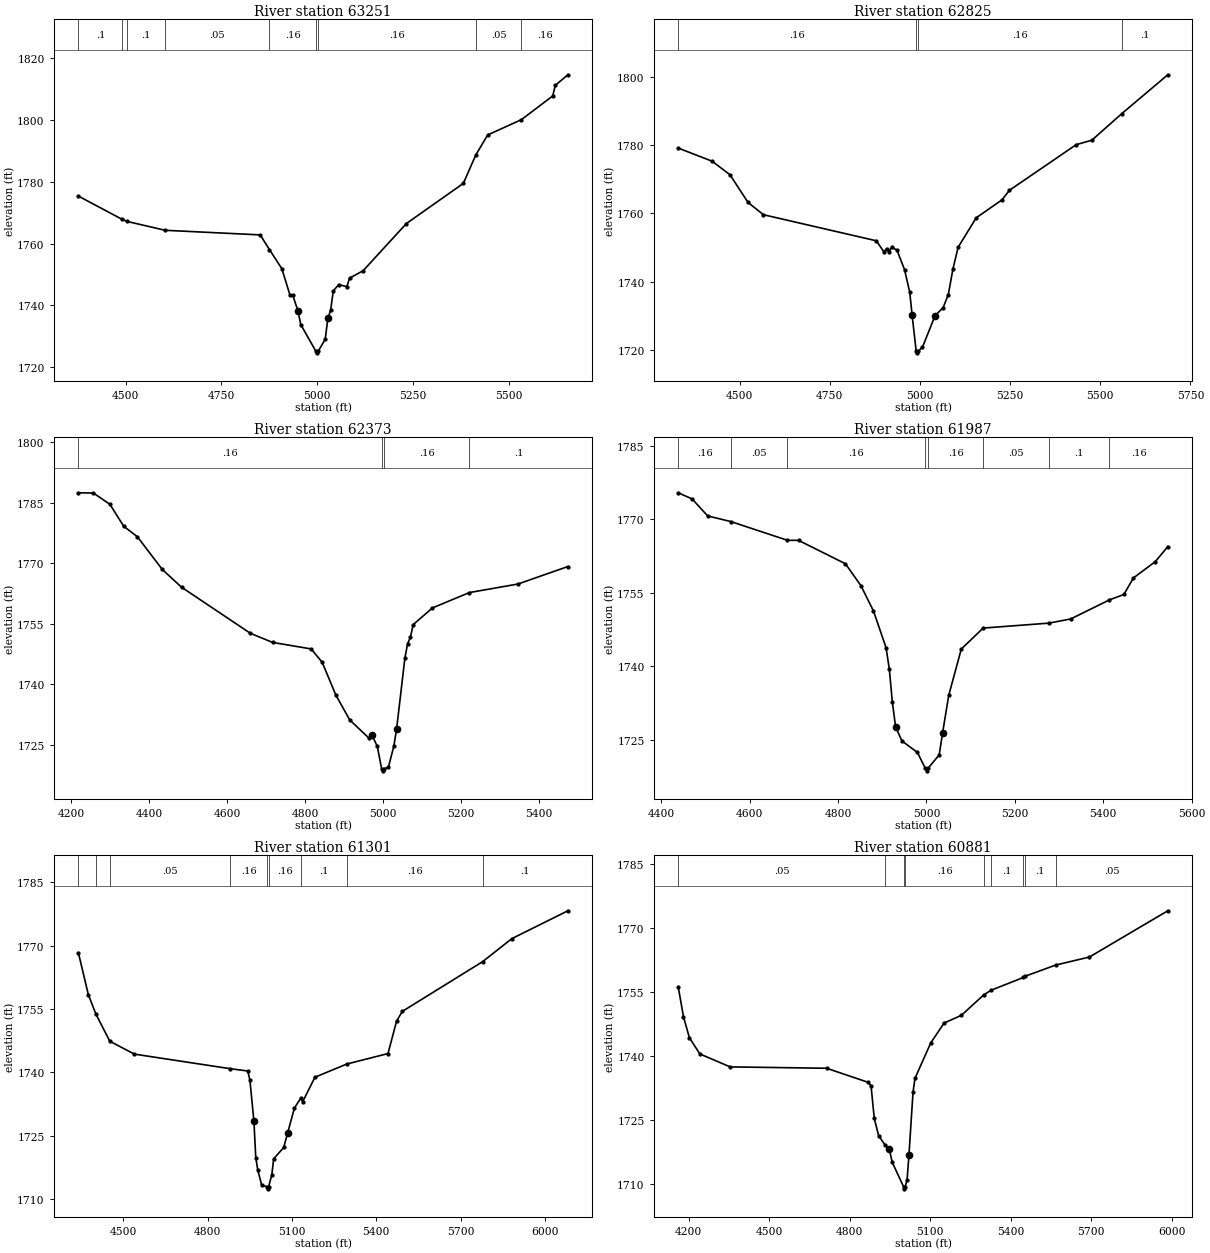
Type RM Length L Ch R = 1 ,63251   ,426,426,426
BEGIN DESCRIPTION:
PALO ALTO CREEK 98.0
END DESCRIPTION:
XS GIS Cut Line= 2
      2759331.64     10090351.78      2758414.96     10089461.14
#Sta/Elev= 30
  4376.7 1775.39  4491.5 1767.81  4503.7 1767.17  4603.5 1764.29  4851.4  1762.8
  4875.7 1758.03    4908 1751.84  4929.1 1743.34  4936.3 1743.34  4950.4 1738.01
  4957.4 1733.72  4996.9 1725.06  4999.6 1724.56  5002.9 1725.06  5021.2 1728.96
  5028.2 1735.76  5035.3 1738.32  5042.3 1744.64  5056.4 1746.68  5077.8 1746.02
  5084.7 1748.78  5120.1 1751.17  5233.2 1766.49  5381.8 1779.49  5414.5 1788.76
  5445.4  1795.2  5533.4 1800.16  5615.1 1807.84  5622.1 1811.31  5654.8 1814.71
#Mann= 9 ,-1 , 0
  4376.7      .1       0  4491.5     .05       0  4503.7      .1       0
  4603.5     .05       0  4875.7     .16       0  4996.9     .07       0
  5002.9     .16       0  5414.5     .05       0  5533.4     .16       0
Bank Sta=4950.4,5028.2
XS Rating Curve= 0 ,0
Exp/Cntr=0.3,0.1

Type RM Length L Ch R = 1 ,62825   ,452,452,452
BEGIN DESCRIPTION:
PALO ALTO CREEK 97.0
END DESCRIPTION:
XS GIS Cut Line= 2
      2759748.35     10090096.61      2758697.17     10089237.97
#Sta/Elev= 30
  4329.9 1779.09    4424 1775.25  4473.5 1771.28  4523.4 1763.21  4566.1 1759.62
  4879.2    1752    4900 1748.77  4907.9 1749.74  4914.3 1748.75  4922.2 1750.16
  4936.6 1749.21  4957.4 1743.54  4971.8 1736.95  4978.2 1730.43  4989.6 1719.76
  4992.3 1719.26  4995.6 1719.76    5007  1720.9  5042.1 1730.14  5064.4 1732.46
  5078.7  1736.3  5091.7 1743.86    5106 1750.13  5156.1 1758.72  5227.4 1763.95
  5248.2 1766.76  5433.4  1780.1  5476.5 1781.38  5559.7 1789.16  5687.2 1800.51
#Mann= 4 ,-1 , 0
  4329.9     .16       0  4989.6     .07       0  4995.6     .16       0
  5559.7      .1       0
Bank Sta=4978.2,5042.1
XS Rating Curve= 0 ,0
Exp/Cntr=0.3,0.1

Type RM Length L Ch R = 1 ,62373   ,386,386,386
BEGIN DESCRIPTION:
PALO ALTO CREEK 96.0
END DESCRIPTION:
XS GIS Cut Line= 2
      2760102.46     10089914.26      2759217.08     10089023.68
#Sta/Elev= 30
    4218 1787.47  4256.6 1787.41    4299 1784.61  4334.3 1779.19  4369.7 1776.55
  4433.3 1768.47  4482.8 1764.06  4659.6 1752.63  4716.2 1750.39  4815.2 1748.77
  4843.4 1745.48  4878.8 1737.29  4914.2 1731.17  4963.7 1726.65  4970.7 1727.51
  4984.9 1724.62    4996 1719.06  4998.8 1718.56    5002 1719.06  5013.2 1719.41
  5027.3 1724.67  5034.4 1728.93  5055.6 1746.45  5062.7 1750.11  5069.7 1751.61
  5076.8 1754.79  5126.3 1758.93    5221 1762.74  5345.5 1764.85  5473.8 1769.19
#Mann= 4 ,-1 , 0
    4218     .16       0    4996     .07       0    5002     .16       0
    5221      .1       0
Bank Sta=4970.7,5034.4
XS Rating Curve= 0 ,0
Exp/Cntr=0.3,0.1

Type RM Length L Ch R = 1 ,61987   ,686,686,686
BEGIN DESCRIPTION:
PALO ALTO CREEK 95.0
END DESCRIPTION:
XS GIS Cut Line= 2
      2760263.96     10089492.43      2759442.83     10088749.25
#Sta/Elev= 30
  4438.5 1775.37    4470 1774.11  4505.1 1770.65  4557.5  1769.5  4685.6 1765.68
  4710.6 1765.67  4816.7  1760.9  4851.8 1756.43  4880.2 1751.26  4908.6 1743.81
  4916.1 1739.38  4922.8 1732.75  4930.2 1727.67  4944.4 1724.78  4979.6 1722.42
  4997.5 1719.17  5000.3 1718.67  5003.5 1719.17  5028.9 1721.93  5036.4 1726.34
  5050.5  1734.1  5078.9 1743.51  5128.3 1747.78  5277.1 1748.79  5326.3 1749.64
    5414 1753.53  5446.6 1754.63  5468.2    1758  5517.6 1761.32    5546 1764.39
#Mann= 8 ,-1 , 0
  4438.5     .16       0  4557.5     .05       0  4685.6     .16       0
  4997.5     .07       0  5003.5     .16       0  5128.3     .05       0
  5277.1      .1       0    5414     .16       0
Bank Sta=4930.2,5036.4
XS Rating Curve= 0 ,0
Exp/Cntr=0.3,0.1

Type RM Length L Ch R = 1 ,61301   ,420,420,420
BEGIN DESCRIPTION:
PALO ALTO CREEK 94.0
END DESCRIPTION:
XS GIS Cut Line= 3
      2760687.18     10089095.66      2760183.04     10088514.86
      2759233.76      10088302.6
#Sta/Elev= 30
    4340 1768.32  4375.9  1758.3  4402.5 1753.76    4452 1747.33  4539.3 1744.28
  4881.1 1740.82  4942.8 1740.28  4950.5 1738.12  4964.7 1728.35  4971.3 1719.77
  4978.2  1716.9  4992.2 1713.26  5011.1 1712.87  5013.8 1712.37  5017.1 1712.87
  5028.3 1715.69    5035 1719.49  5070.9 1722.17  5084.3 1725.52  5108.8 1731.51
  5131.2 1733.83  5138.3 1733.02  5181.7  1738.8  5294.9 1741.93  5441.7 1744.41
  5472.4 1752.12  5492.9 1754.41    5778 1766.16  5882.3 1771.63  6081.8 1778.23
#Mann= 9 ,-1 , 0
    4340     .16       0  4402.5      .1       0    4452     .05       0
  4881.1     .16       0  5011.1     .07       0  5017.1     .16       0
  5131.2      .1       0  5294.9     .16       0    5778      .1       0
Bank Sta=4964.7,5084.3
XS Rating Curve= 0 ,0
Exp/Cntr=0.3,0.1

Type RM Length L Ch R = 1 ,60881   ,307,307,307
BEGIN DESCRIPTION:
PALO ALTO CREEK 93.0
END DESCRIPTION:
XS GIS Cut Line= 3
      2760828.65     10089001.26      2760424.78     10088166.98
      2759714.35     10087618.68
#Sta/Elev= 30
  4161.4 1756.25  4180.9 1749.21  4203.1 1744.26  4242.1 1740.46    4355 1737.42
  4714.2  1737.1  4869.7 1733.78    4880 1732.91  4891.9 1725.34  4908.1 1721.27
  4931.7 1719.09  4947.5 1718.16  4958.9    1715    5001 1709.26  5003.8 1708.76
    5007 1709.26  5014.1 1710.81  5021.1 1716.63  5036.4 1731.55  5043.7 1734.74
  5102.2 1743.03    5152 1747.73  5216.3 1749.53  5300.1 1754.36  5326.5 1755.41
  5447.1 1758.43  5452.1 1758.68  5567.8 1761.35  5693.6 1763.24  5985.7 1774.11
#Mann= 9 ,-1 , 0
  4161.4     .05       0  4931.7     .16       0    5001     .07       0
    5007     .16       0  5300.1     .05       0  5326.5      .1       0
  5447.1     .05       0  5452.1      .1       0  5567.8     .05       0
Bank Sta=4947.5,5021.1
XS Rating Curve= 0 ,0
Exp/Cntr=0.3,0.1

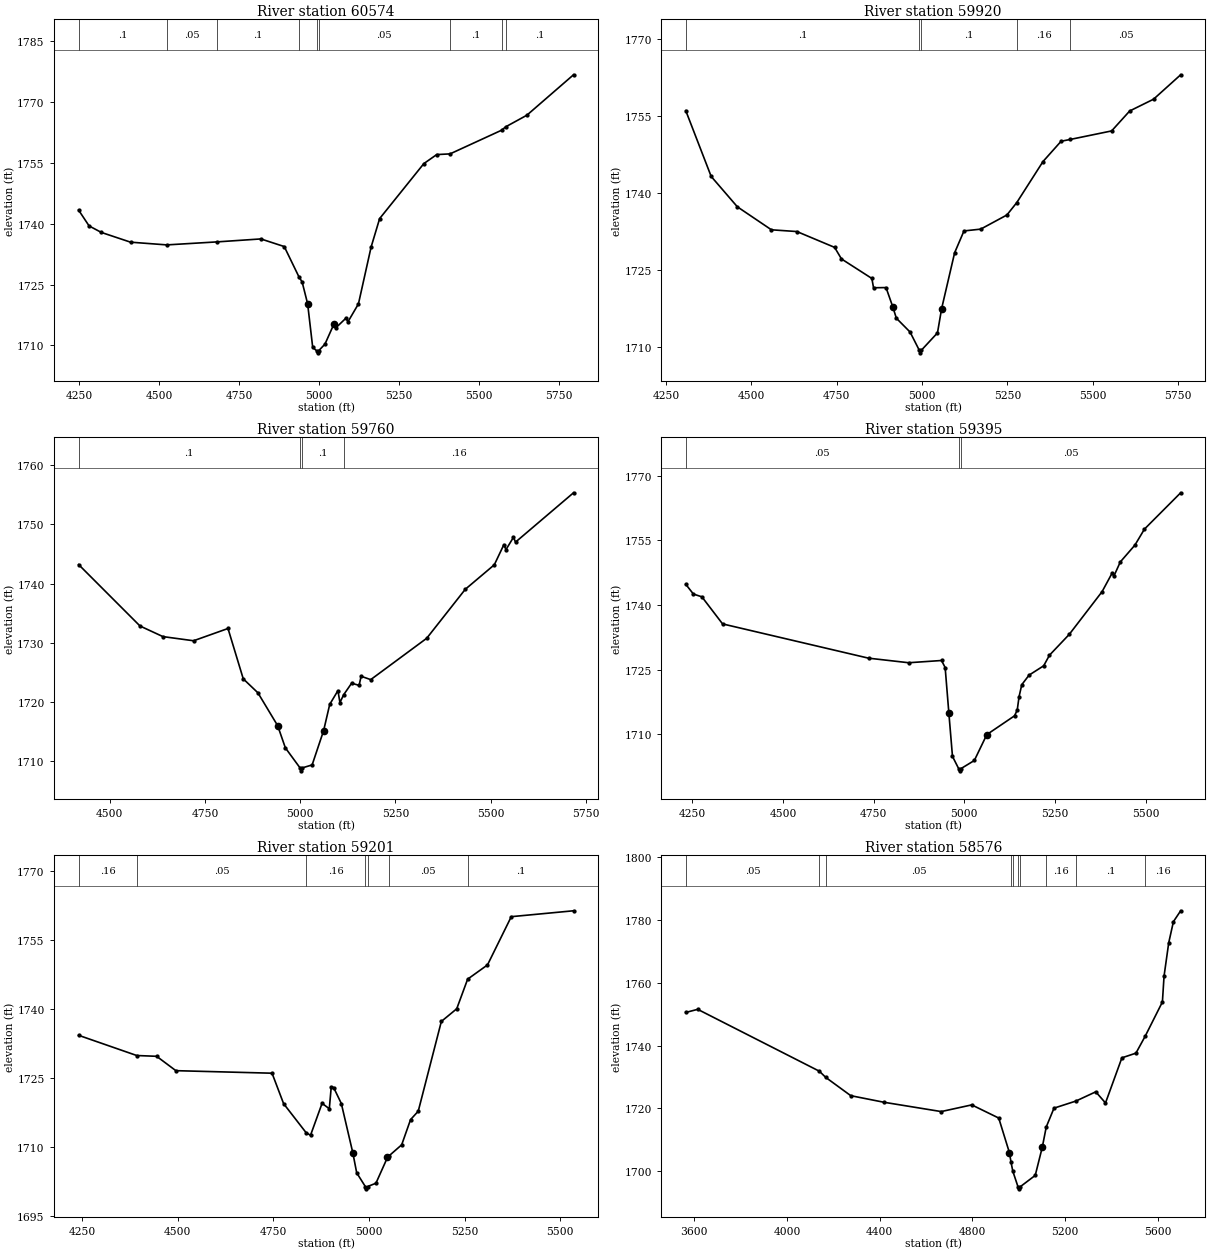
Type RM Length L Ch R = 1 ,60574   ,654,654,654
BEGIN DESCRIPTION:
PALO ALTO CREEK 92.0
END DESCRIPTION:
XS GIS Cut Line= 3
      2760973.12     10088889.25      2760681.26     10087913.45
      2760737.27     10087388.74
#Sta/Elev= 30
  4248.8 1743.34  4281.6 1739.44  4319.9 1737.84  4411.1 1735.44  4524.4 1734.77
  4681.1 1735.51  4818.2 1736.24  4891.3 1734.36  4937.5 1726.85  4947.1 1725.66
  4964.3 1720.28  4980.2 1709.53  4992.6 1708.69  4995.4 1708.19  4998.6 1708.69
  5018.5 1710.34  5046.4 1715.26  5051.6 1714.28  5084.8 1716.79    5090 1715.79
  5123.1 1720.25  5162.6 1734.23  5189.3 1741.25  5327.4 1754.79  5367.6 1757.01
  5409.3 1757.18  5570.6 1763.02  5582.8 1763.83  5649.2  1766.7    5795 1776.66
#Mann= 9 ,-1 , 0
  4248.8      .1       0  4524.4     .05       0  4681.1      .1       0
  4937.5     .05       0  4992.6     .07       0  4998.6     .05       0
  5409.3      .1       0  5570.6     .05       0  5582.8      .1       0
Bank Sta=4964.3,5046.4
XS Rating Curve= 0 ,0
Exp/Cntr=0.3,0.1

Type RM Length L Ch R = 1 ,59920   ,160,160,160
BEGIN DESCRIPTION:
PALO ALTO CREEK 90.0
END DESCRIPTION:
XS GIS Cut Line= 3
      2761318.05     10088797.86       2761400.6      10087984.2
       2761155.9     10087400.45
#Sta/Elev= 30
  4307.3 1756.04  4381.8 1743.24  4458.6 1737.33  4558.4 1732.86  4633.1 1732.52
  4743.7 1729.44  4763.8 1727.19  4852.8  1723.4  4857.8 1721.59  4894.4 1721.62
  4914.5 1717.82  4924.6 1715.67  4964.8 1712.98  4991.9 1709.43  4994.7 1708.93
  4997.9 1709.43  5045.2 1712.81  5057.4 1717.54  5095.5  1728.4  5122.9 1732.64
  5171.9 1732.99  5248.7 1735.74  5277.5 1738.14  5354.6 1746.14  5407.6 1750.08
  5434.2 1750.43  5555.7 1752.09  5608.7 1755.97  5678.6 1758.26  5758.1 1763.01
#Mann= 5 ,-1 , 0
  4307.3      .1       0  4991.9     .07       0  4997.9      .1       0
  5277.5     .16       0  5434.2     .05       0
Bank Sta=4914.5,5057.4
XS Rating Curve= 0 ,0
Exp/Cntr=0.3,0.1

Type RM Length L Ch R = 1 ,59760   ,365,365,365
BEGIN DESCRIPTION:
Mapping XS a0e29af9
END DESCRIPTION:
XS GIS Cut Line= 3
      2761489.04     10088724.18      2761550.95     10088066.75
      2761330.47     10087467.03
#Sta/Elev= 30
  4418.3 1743.22  4579.5 1732.85  4639.7 1731.06  4720.1 1730.36  4810.5 1732.43
  4850.6 1723.93    4889 1721.58    4941 1716.02  4961.1 1712.29  4999.6 1708.91
  5002.3 1708.41  5005.6 1708.91  5031.4 1709.41  5061.6 1715.21  5077.6 1719.63
  5099.1 1721.94  5104.4 1719.94  5114.3 1721.26  5135.1  1723.2  5154.7 1722.83
    5160 1724.37  5185.2  1723.8  5332.2 1730.78  5433.4 1739.04  5509.7 1743.18
  5534.8 1746.58  5540.2 1745.73    5560 1747.82  5565.3    1747  5717.6 1755.33
#Mann= 4 ,-1 , 0
  4418.3      .1       0  4999.6     .07       0  5005.6      .1       0
  5114.3     .16       0
Bank Sta=4941,5061.6
XS Rating Curve= 0 ,0
Exp/Cntr=0.3,0.1

Type RM Length L Ch R = 1 ,59395   ,194,194,194
BEGIN DESCRIPTION:
PALO ALTO CREEK 89.0
END DESCRIPTION:
XS GIS Cut Line= 2
      2761968.37     10088854.65      2761812.17     10087498.32
#Sta/Elev= 30
  4231.5 1744.79  4252.6 1742.52    4276 1741.88  4333.1  1735.6  4735.7 1727.66
  4846.5  1726.6  4937.1 1727.12  4947.1 1725.49  4957.2 1715.05  4967.3 1704.89
  4984.4 1702.04  4987.1 1701.54  4990.4 1702.04  5027.6 1703.94    5062 1709.94
  5138.4 1714.29  5145.9 1715.61    5151 1718.74  5158.5 1721.51  5178.6 1723.73
  5218.9 1725.89  5234.9 1728.35  5289.4 1733.17    5380 1743.08  5407.9 1747.41
  5412.9 1746.75  5430.3 1749.97  5470.6 1753.87  5496.9 1757.58  5596.8    1766
#Mann= 3 ,-1 , 0
  4231.5     .05       0  4984.4     .04       0  4990.4     .05       0
Bank Sta=4957.2,5062
XS Rating Curve= 0 ,0
Exp/Cntr=0.3,0.1

Type RM Length L Ch R = 1 ,59201   ,625,625,625
BEGIN DESCRIPTION:
PALO ALTO CREEK 88.0
END DESCRIPTION:
XS GIS Cut Line= 2
      2762103.78     10088716.58      2761965.76     10087430.16
#Sta/Elev= 30
  4240.8 1734.23  4392.8 1729.84  4444.8 1729.67  4495.1 1726.55  4746.5    1726
  4776.7 1719.39  4835.4  1713.1  4847.1 1712.52  4877.3 1719.46  4896.2 1718.28
  4901.2 1722.98  4907.5 1722.89  4927.6 1719.42  4957.7  1708.7  4967.8 1704.37
  4990.3 1701.39  4993.1 1700.89  4996.3 1701.39  5018.1 1702.11  5048.3 1707.72
  5051.2 1707.97  5085.4 1710.45  5108.6 1715.92  5128.7 1717.75  5189.1 1737.24
  5229.3 1739.99  5257.8 1746.42  5309.7 1749.51  5371.9 1759.99  5534.6 1761.27
#Mann= 7 ,-1 , 0
  4240.8     .16       0  4392.8     .05       0  4835.4     .16       0
  4990.3     .07       0  4996.3     .16       0  5051.2     .05       0
  5257.8      .1       0
#XS Ineff= 2 , 0
         4904.23 1722.66
Permanent Ineff=
       F       F
Bank Sta=4957.7,5048.3
XS Rating Curve= 0 ,0
Exp/Cntr=0.3,0.1

Type RM Length L Ch R = 1 ,58576   ,662,662,662
BEGIN DESCRIPTION:
PALO ALTO CREEK 87.0
END DESCRIPTION:
XS GIS Cut Line= 3
      2762207.94     10089255.73      2762572.54     10088036.93
      2762694.94     10087182.72
#Sta/Elev= 30
    3563 1750.58  3614.6 1751.57  4139.4 1731.87  4166.9  1729.9  4274.9 1724.08
  4417.7 1721.99  4665.1 1719.02  4796.8 1721.15  4913.2 1716.96  4959.6 1705.87
  4966.4 1702.83    4974 1700.03    4997 1694.92  4999.8 1694.42    5003 1694.92
  5070.7  1698.7  5101.1 1707.67  5118.2 1714.12  5151.6 1720.11  5246.2 1722.37
  5331.8 1725.31  5373.8 1721.76  5444.5 1736.13  5505.1 1737.62  5545.1 1743.03
  5619.3 1753.92  5626.4 1762.14  5646.6 1772.78  5666.8 1779.49  5698.1 1782.95
#Mann= 10 ,-1 , 0
    3563     .05       0  4139.4     .16       0  4166.9     .05       0
  4966.4     .16       0    4974     .05       0    4997    .035       0
    5003     .05       0  5118.2     .16       0  5246.2      .1       0
  5545.1     .16       0
Bank Sta=4959.6,5101.1
XS Rating Curve= 0 ,0
Exp/Cntr=0.3,0.1

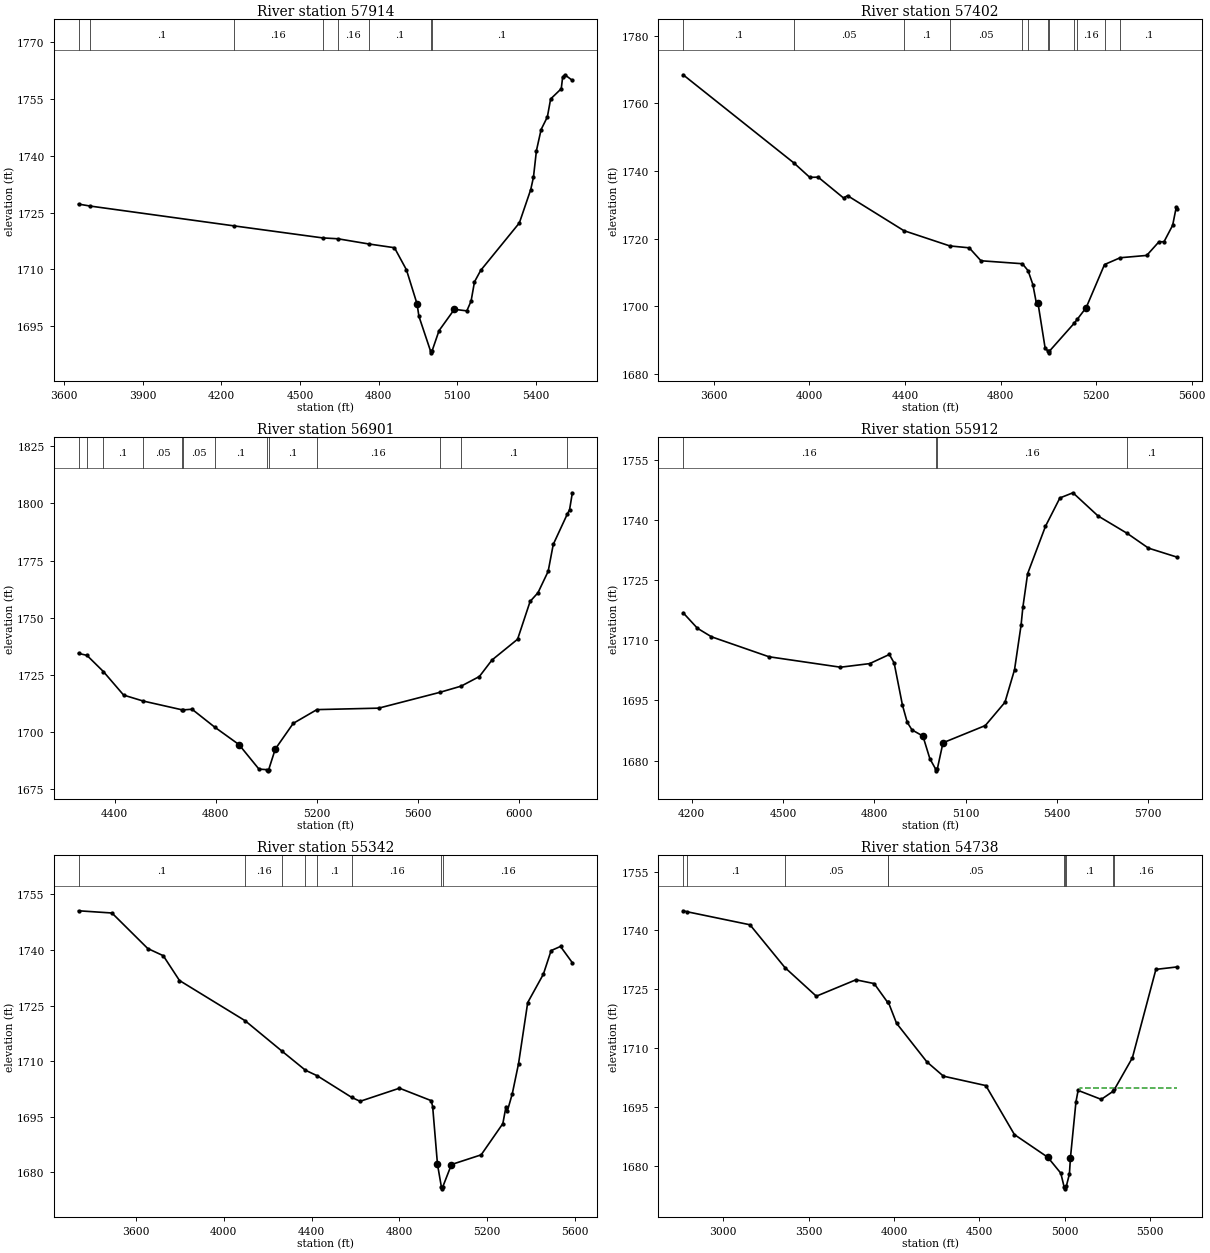
Type RM Length L Ch R = 1 ,57914   ,512,512,512
BEGIN DESCRIPTION:
PALO ALTO CREEK 86.0
END DESCRIPTION:
XS GIS Cut Line= 3
      2763129.83     10089081.19      2763267.85     10087878.08
      2763008.08     10087257.23
#Sta/Elev= 30
  3655.1 1727.24  3699.3 1726.72  4246.4 1721.51  4586.1 1718.32  4644.4 1718.09
  4762.2 1716.72  4860.4 1715.73  4906.1  1709.9  4946.7 1700.88  4953.6 1697.66
  4997.9  1688.5  5000.6    1688  5003.9  1688.5  5030.4 1693.85  5088.9 1699.48
  5136.5 1699.07  5152.7 1701.65  5165.7 1706.73  5189.5 1709.76  5336.9 1722.27
  5380.3 1731.07  5390.7 1734.34    5402 1741.34  5419.9 1746.91  5443.7 1750.22
  5456.2 1754.97  5496.7 1757.67  5502.1 1760.77  5510.4 1761.35  5539.1 1759.87
#Mann= 8 ,-1 , 0
  3655.1     .16       0  3699.3      .1       0  4246.4     .16       0
  4586.1      .1       0  4644.4     .16       0  4762.2      .1       0
  4997.9     .07       0  5003.9      .1       0
Bank Sta=4946.7,5088.9
XS Rating Curve= 0 ,0
Exp/Cntr=0.3,0.1

Type RM Length L Ch R = 1 ,57402   ,501,501,501
BEGIN DESCRIPTION:
PALO ALTO CREEK 85.0
END DESCRIPTION:
XS GIS Cut Line= 3
      2764377.24     10088740.09      2763903.26     10087646.31
      2763170.09     10087167.93
#Sta/Elev= 30
  3470.9 1768.47  3934.9 1742.37    4001 1738.12  4036.4 1738.17  4142.6 1732.01
  4159.2  1732.7  4395.1 1722.34  4587.5 1717.82  4668.8 1717.26  4717.9 1713.43
  4891.4 1712.55  4915.2 1710.49  4935.2 1706.39  4950.3 1700.75  4956.3 1701.07
  4986.5 1687.62  4998.6 1686.68  5001.4 1686.18  5004.6 1686.68  5107.9 1694.91
  5120.6 1696.06  5158.4 1699.56  5235.2 1712.31  5300.7 1714.32  5411.9 1715.01
  5463.2 1719.05  5484.3 1719.06  5520.5 1723.93  5535.6 1729.32  5538.4 1728.71
#Mann= 12 ,-1 , 0
  3470.9      .1       0  3934.9     .05       0  4395.1      .1       0
  4587.5     .05       0  4891.4      .1       0  4915.2     .16       0
  4998.6     .07       0  5004.6     .16       0  5107.9      .1       0
  5120.6     .16       0  5235.2     .05       0  5300.7      .1       0
Bank Sta=4956.3,5158.4
XS Rating Curve= 0 ,0
Exp/Cntr=0.3,0.1

Type RM Length L Ch R = 1 ,56901   ,989,989,989
BEGIN DESCRIPTION:
PALO ALTO CREEK 84.0
END DESCRIPTION:
XS GIS Cut Line= 3
      2764360.15     10087661.62      2763768.98     10086864.71
       2762813.4     10086737.13
#Sta/Elev= 30
  4256.4 1734.43  4289.7 1733.57    4355 1726.48  4434.9 1716.23  4511.5 1713.65
    4668 1709.75  4669.2 1709.75  4706.1 1710.04  4795.8 1702.23  4891.8 1694.62
  4971.1  1683.9  5003.6 1683.64  5006.3 1683.14  5009.6 1683.64  5035.8 1692.65
  5106.8 1703.86  5200.7 1709.88  5445.4 1710.52  5686.7 1717.39  5772.2 1720.14
  5844.4 1724.34  5894.1 1731.52  5995.7 1740.62  6045.3 1757.13  6076.4 1760.91
  6116.8 1770.26    6137 1782.03  6192.7 1795.29  6201.6 1797.17  6212.7 1804.58
#Mann= 13 ,-1 , 0
  4256.4      .1       0  4289.7     .16       0    4355      .1       0
  4511.5     .05       0    4668      .1       0  4669.2     .05       0
  4795.8      .1       0  5003.6     .07       0  5009.6      .1       0
  5200.7     .16       0  5686.7     .05       0  5772.2      .1       0
  6192.7     .16       0
Bank Sta=4891.8,5035.8
XS Rating Curve= 0 ,0
Exp/Cntr=0.3,0.1

Type RM Length L Ch R = 1 ,55912   ,570,570,570
BEGIN DESCRIPTION:
PALO ALTO CREEK 82.0
END DESCRIPTION:
XS GIS Cut Line= 3
      2765214.27     10087354.26      2764589.29     10086281.38
      2764500.74     10085911.57
#Sta/Elev= 30
  4172.1 1716.89  4219.1 1713.02  4265.3 1710.89    4454 1705.91    4689  1703.3
  4784.9  1704.2  4849.5 1706.48  4865.2 1704.36  4892.5 1693.83  4908.2 1689.55
  4923.9 1687.65  4959.7 1686.12  4982.6 1680.45  5001.1 1677.94  5003.9 1677.44
  5007.1 1677.94  5025.6 1684.44  5164.6 1688.74  5229.1 1694.54  5260.6 1702.67
  5282.1  1713.8  5287.9 1718.21  5303.6 1726.64  5362.3 1738.48  5409.6 1745.54
  5452.5 1746.83  5534.7 1741.06  5631.1 1736.68  5700.4 1733.02    5794 1730.78
#Mann= 4 ,-1 , 0
  4172.1     .16       0  5001.1     .07       0  5007.1     .16       0
  5631.1      .1       0
#XS Ineff= 2 , 0
         4848.85 1706.32
Permanent Ineff=
       F       F
Bank Sta=4959.7,5025.6
XS Rating Curve= 0 ,0
Exp/Cntr=0.3,0.1

Type RM Length L Ch R = 1 ,55342   ,604,604,604
BEGIN DESCRIPTION:
PALO ALTO CREEK 81.0
END DESCRIPTION:
XS GIS Cut Line= 3
      2765862.91     10087879.61      2765390.68     10086469.84
      2764898.56     10085887.62
#Sta/Elev= 30
  3338.7 1750.58  3490.8 1749.98  3653.9  1740.4  3724.6 1738.46  3798.4 1731.77
  4097.1 1720.93  4266.8 1712.64    4372 1707.57  4426.2 1706.06  4582.5 1700.25
    4621 1699.18  4800.3 1702.72  4944.9 1699.36  4951.5 1697.77  4973.5 1682.17
  4991.3 1676.07  4994.1 1675.57  4997.3 1676.07  5037.2 1682.13  5172.4 1684.74
  5271.2 1693.17  5285.5 1697.75  5292.1 1696.63  5314.1  1701.2  5342.7 1709.35
  5384.4 1725.82  5455.8 1733.48    5491 1739.84  5533.8 1740.96  5587.8 1736.56
#Mann= 8 ,-1 , 0
  3338.7      .1       0  4097.1     .16       0  4266.8      .1       0
    4372     .16       0  4426.2      .1       0  4582.5     .16       0
  4991.3     .07       0  4997.3     .16       0
Bank Sta=4973.5,5037.2
XS Rating Curve= 0 ,0
Exp/Cntr=0.3,0.1

Type RM Length L Ch R = 1 ,54738   ,733,733,733
BEGIN DESCRIPTION:
PALO ALTO CREEK 80.0
END DESCRIPTION:
XS GIS Cut Line= 4
      2766654.57     10088136.53      2765883.73     10086240.68
      2765654.57     10085803.18      2765322.34     10085685.52
#Sta/Elev= 30
  2764.8    1745    2786 1744.77  3156.4 1741.43  3361.1 1730.52  3545.1 1723.21
  3776.9 1727.39    3884 1726.43  3963.3 1721.62  3966.9  1721.7  4015.1 1716.31
  4192.8 1706.46  4289.9 1702.81  4538.2 1700.41  4705.7 1687.91    4901 1682.13
  4977.3 1678.07  4996.8 1674.57  4999.6 1674.07  5002.8 1674.57  5009.7 1674.74
  5027.8 1677.83  5033.7 1681.93  5066.2 1696.28  5078.9 1699.18  5214.3 1696.89
  5283.2 1698.93  5291.3 1699.42  5396.6 1707.48  5534.5 1730.05  5657.7 1730.67
#Mann= 10 ,-1 , 0
  2764.8     .16       0    2786      .1       0  3361.1     .05       0
  3963.3      .1       0  3966.9     .05       0  4996.8    .035       0
  5002.8     .05       0  5009.7      .1       0  5283.2     .05       0
  5291.3     .16       0
#XS Ineff= 2 , 0
                          5089.2         1699.72
Permanent Ineff=
       F       F
Bank Sta=4901,5033.7
XS Rating Curve= 0 ,0
Exp/Cntr=0.3,0.1

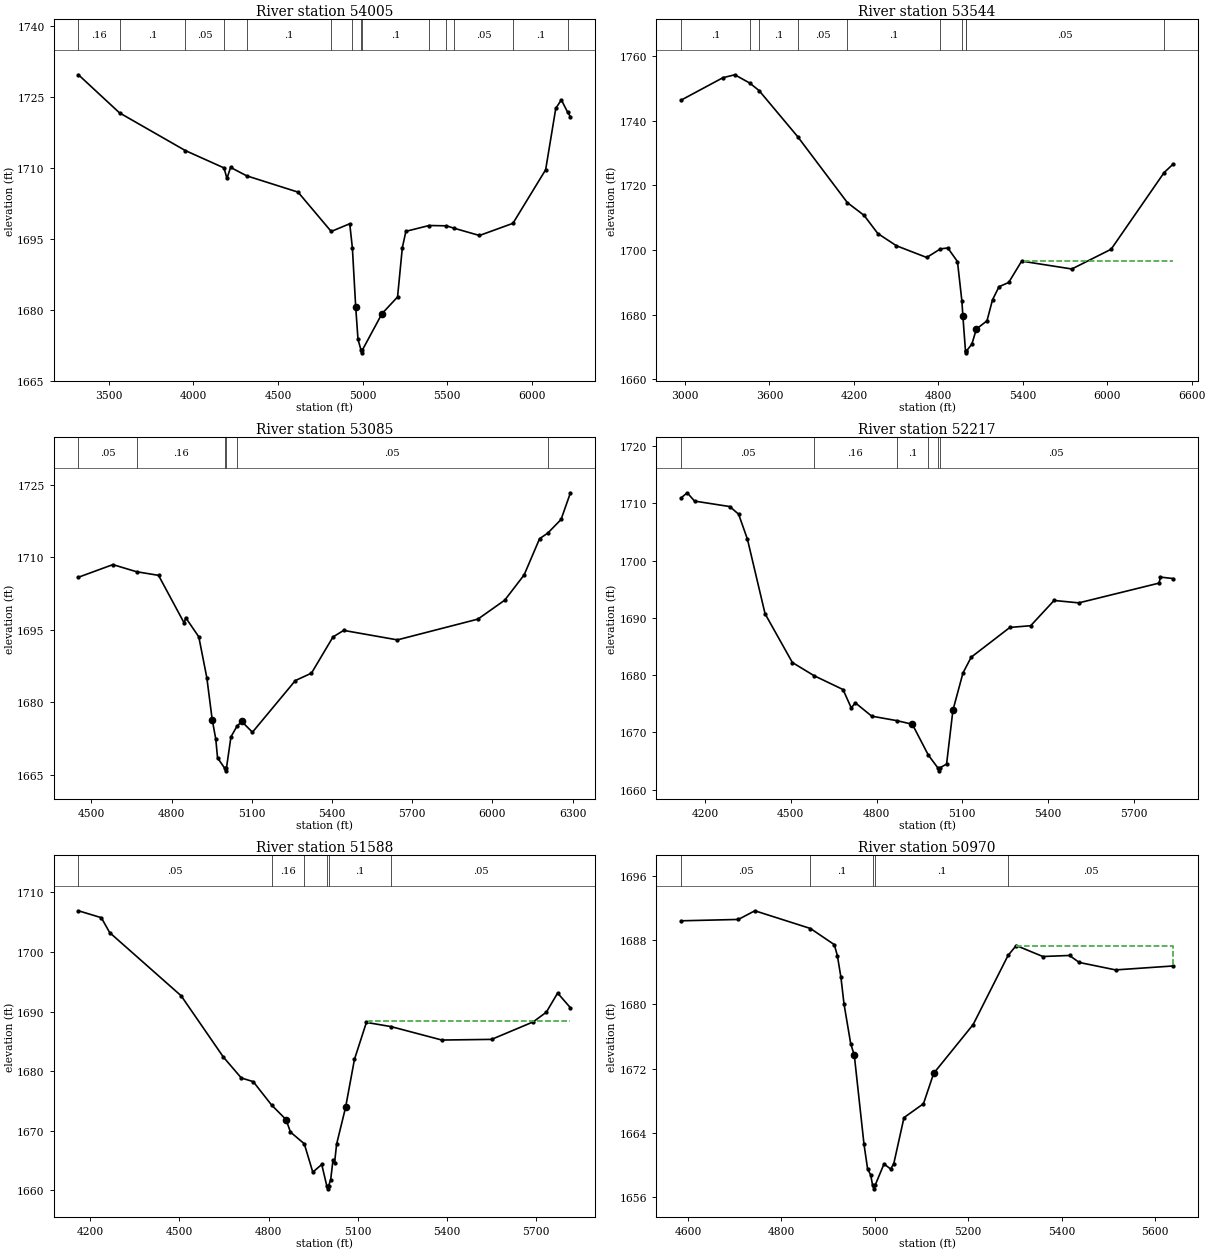
Type RM Length L Ch R = 1 ,54005   ,461,461,461
BEGIN DESCRIPTION:
PALO ALTO CREEK 79.0
END DESCRIPTION:
XS GIS Cut Line= 4
      2766842.32     10087699.76      2766571.49     10086119.92
      2766279.83       10085797.      2765436.19      10085588.7
#Sta/Elev= 30
  3321.3 1729.61    3564 1721.56  3952.9  1713.6  4181.7 1709.93  4198.6  1707.7
  4220.3 1710.04  4315.6 1708.26  4618.8 1704.82  4814.7 1696.51  4924.2 1698.14
  4939.8 1693.05  4959.4 1680.59    4973 1673.72  4991.5 1671.37  4994.3 1670.87
  4997.5 1671.37  5114.8 1679.15  5206.7 1682.67  5235.1 1693.12  5256.1 1696.54
  5393.6 1697.77  5495.5  1697.7  5543.1 1697.17  5690.7 1695.66  5888.5 1698.23
  6081.8 1709.55  6141.6 1722.51  6174.5 1724.31    6212 1721.68  6228.3 1720.75
#Mann= 14 ,-1 , 0
  3321.3     .16       0    3564      .1       0  3952.9     .05       0
  4181.7     .16       0  4315.6      .1       0  4814.7     .16       0
  4939.8      .1       0  4991.5     .07       0  4997.5      .1       0
  5393.6     .05       0  5495.5      .1       0  5543.1     .05       0
  5888.5      .1       0    6212     .16       0
Bank Sta=4959.4,5114.8
XS Rating Curve= 0 ,0
Exp/Cntr=0.3,0.1

Type RM Length L Ch R = 1 ,53544   ,459,459,459
BEGIN DESCRIPTION:
Mapping XS c99bfa55
END DESCRIPTION:
XS GIS Cut Line= 3
      2767753.78     10087323.89      2767176.53      10085856.9
        2765384.     10085171.14
#Sta/Elev= 30
  2971.8 1746.35  3270.3 1753.32  3354.2 1754.21  3459.8 1751.65  3526.5 1749.32
  3800.9 1735.05  4153.8 1714.64  4272.3 1710.71  4369.9 1705.09  4502.7 1701.29
  4717.5 1697.67    4815 1700.33  4867.4 1700.62    4936 1696.41  4967.4 1684.21
  4974.5 1679.52  4993.1 1668.66  4995.8 1668.16  4999.1 1668.66  5038.7  1670.9
  5070.2 1675.51  5145.8 1678.07  5185.1 1684.58  5231.4 1688.63  5299.9 1689.93
    5392 1696.54  5748.7 1694.11  6027.8 1700.22  6404.4 1723.95  6467.5 1726.54
#Mann= 10 ,-1 , 0
  2971.8      .1       0  3459.8     .05       0  3526.5      .1       0
  3800.9     .05       0  4153.8      .1       0    4815     .16       0
  4967.4     .05       0  4993.1    .035       0  4999.1     .05       0
  6404.4      .1       0
#XS Ineff= 2 , 0
                         5406.89         1696.49
Permanent Ineff=
       F       F
Bank Sta=4974.5,5070.2
XS Rating Curve= 0 ,0
Exp/Cntr=0.3,0.1

Type RM Length L Ch R = 1 ,53085   ,868,868,868
BEGIN DESCRIPTION:
PALO ALTO CREEK 78.0
END DESCRIPTION:
XS GIS Cut Line= 2
      2767376.83     10085303.18      2765543.47     10085143.46
#Sta/Elev= 30
  4451.6 1705.86  4580.4 1708.47  4668.8    1707  4751.1 1706.25  4847.5 1696.34
  4852.5 1697.51  4901.7 1693.54  4931.8 1685.07  4951.8 1676.43  4965.3 1672.36
  4971.9  1668.5    4999 1666.31  5001.8 1665.81    5005 1666.31  5022.1 1672.86
  5044.4 1675.02  5062.3 1676.02  5102.4  1673.8    5263 1684.49  5323.3 1686.02
  5403.6  1693.5  5443.7 1694.86  5644.5  1692.9  5945.6 1697.19    6046 1701.11
  6118.6 1706.33  6176.5 1713.84  6206.9 1714.98  6256.8 1717.81  6291.9 1723.33
#Mann= 6 ,-1 , 0
  4451.6     .05       0  4668.8     .16       0    4999     .07       0
    5005     .16       0  5044.4     .05       0  6206.9      .1       0
#XS Ineff= 2 , 0
                         5452.54         1694.66
Permanent Ineff=
       F       F
Bank Sta=4951.8,5062.3
XS Rating Curve= 0 ,0
Exp/Cntr=0.3,0.1

Type RM Length L Ch R = 1 ,52217   ,629,629,629
BEGIN DESCRIPTION:
PALO ALTO CREEK 76.0
END DESCRIPTION:
XS GIS Cut Line= 4
      2767350.38     10085070.32      2767246.58     10084778.14
      2766660.28     10084296.89      2766021.53     10084159.27
#Sta/Elev= 30
  4115.5 1710.93  4137.3 1711.83  4162.8 1710.38  4286.3 1709.42  4317.1 1708.09
    4348 1703.71  4409.7 1690.69  4505.3 1682.18  4581.2 1679.88  4682.6 1677.46
  4711.3 1674.25  4725.6 1675.14    4783 1672.81  4870.6 1672.03  4925.1  1671.4
    4981 1666.02  5014.7 1663.76  5017.4 1663.26  5020.7 1663.76    5045 1664.44
  5067.2 1673.85  5102.4 1680.36  5131.1 1683.11  5266.5 1688.31  5339.4 1688.61
  5421.2 1693.02  5507.9  1692.6  5788.5 1696.05  5793.6  1697.1  5837.5 1696.85
#Mann= 6 ,-1 , 0
  4115.5     .05       0  4581.2     .16       0  4870.6      .1       0
    4981     .05       0  5014.7    .035       0  5020.7     .05       0
Bank Sta=4925.1,5067.2
XS Rating Curve= 0 ,0
Exp/Cntr=0.3,0.1

Type RM Length L Ch R = 1 ,51588   ,618,618,618
BEGIN DESCRIPTION:
PALO ALTO CREEK 75.0
END DESCRIPTION:
XS GIS Cut Line= 4
      2767693.47     10084937.51      2767371.21      10084617.2
      2767334.76     10084085.95      2767076.96      10083468.8
#Sta/Elev= 30
  4160.4 1706.92  4237.3 1705.76  4265.6 1703.25    4506 1692.65  4648.3 1682.35
  4708.5 1678.85  4748.5 1678.24  4810.7 1674.29  4858.8 1671.88  4873.9 1669.77
  4920.4  1667.8    4949 1663.04  4979.1 1664.33  4996.1 1660.74  4998.9 1660.24
  5002.1 1660.74  5009.2 1661.76  5017.1 1665.14  5022.1 1664.52  5029.2 1667.75
  5059.3  1673.9  5089.3 1681.99  5129.4 1688.18  5211.9 1687.48  5383.4 1685.22
  5550.7 1685.33  5690.8 1688.27  5734.9 1689.89    5773 1693.11  5816.1 1690.63
#Mann= 6 ,-1 , 0
  4160.4     .05       0  4810.7     .16       0  4920.4      .1       0
  4996.1     .07       0  5002.1      .1       0  5211.9     .05       0
#XS Ineff= 2 , 0
                         5137.85         1688.46
Permanent Ineff=
       F       F
Bank Sta=4858.8,5059.3
XS Rating Curve= 0 ,0
Exp/Cntr=0.3,0.1

Type RM Length L Ch R = 1 ,50970   ,433,433,433
BEGIN DESCRIPTION:
PALO ALTO CREEK 74.0
END DESCRIPTION:
XS GIS Cut Line= 2
      2768161.49     10084393.43      2767363.16     10083706.18
#Sta/Elev= 30
    4585 1690.41  4707.7 1690.58  4743.1 1691.66  4862.2 1689.45  4913.2 1687.44
  4919.8 1686.06  4927.4 1683.36    4934 1680.04  4948.3  1675.1    4956 1673.65
  4976.8 1662.55  4984.5 1659.48  4991.1 1658.73    4995  1657.5  4997.8    1657
    5001  1657.5  5019.6  1660.1  5033.9 1659.47  5040.5 1660.13  5062.4 1665.88
  5104.1 1667.61    5126  1671.4  5210.5 1677.48  5285.2 1686.09  5302.7 1687.33
  5359.7 1685.96  5416.8 1686.09  5437.6 1685.22  5515.5 1684.29  5638.4 1684.78
#Mann= 5 ,-1 , 0
    4585     .05       0  4862.2      .1       0    4995     .07       0
    5001      .1       0  5285.2     .05       0
#XS Ineff= 2 , 0
                          5302.3         1687.21
Permanent Ineff=
       F       F
Bank Sta=4956,5126
XS Rating Curve= 0 ,0
Exp/Cntr=0.3,0.1