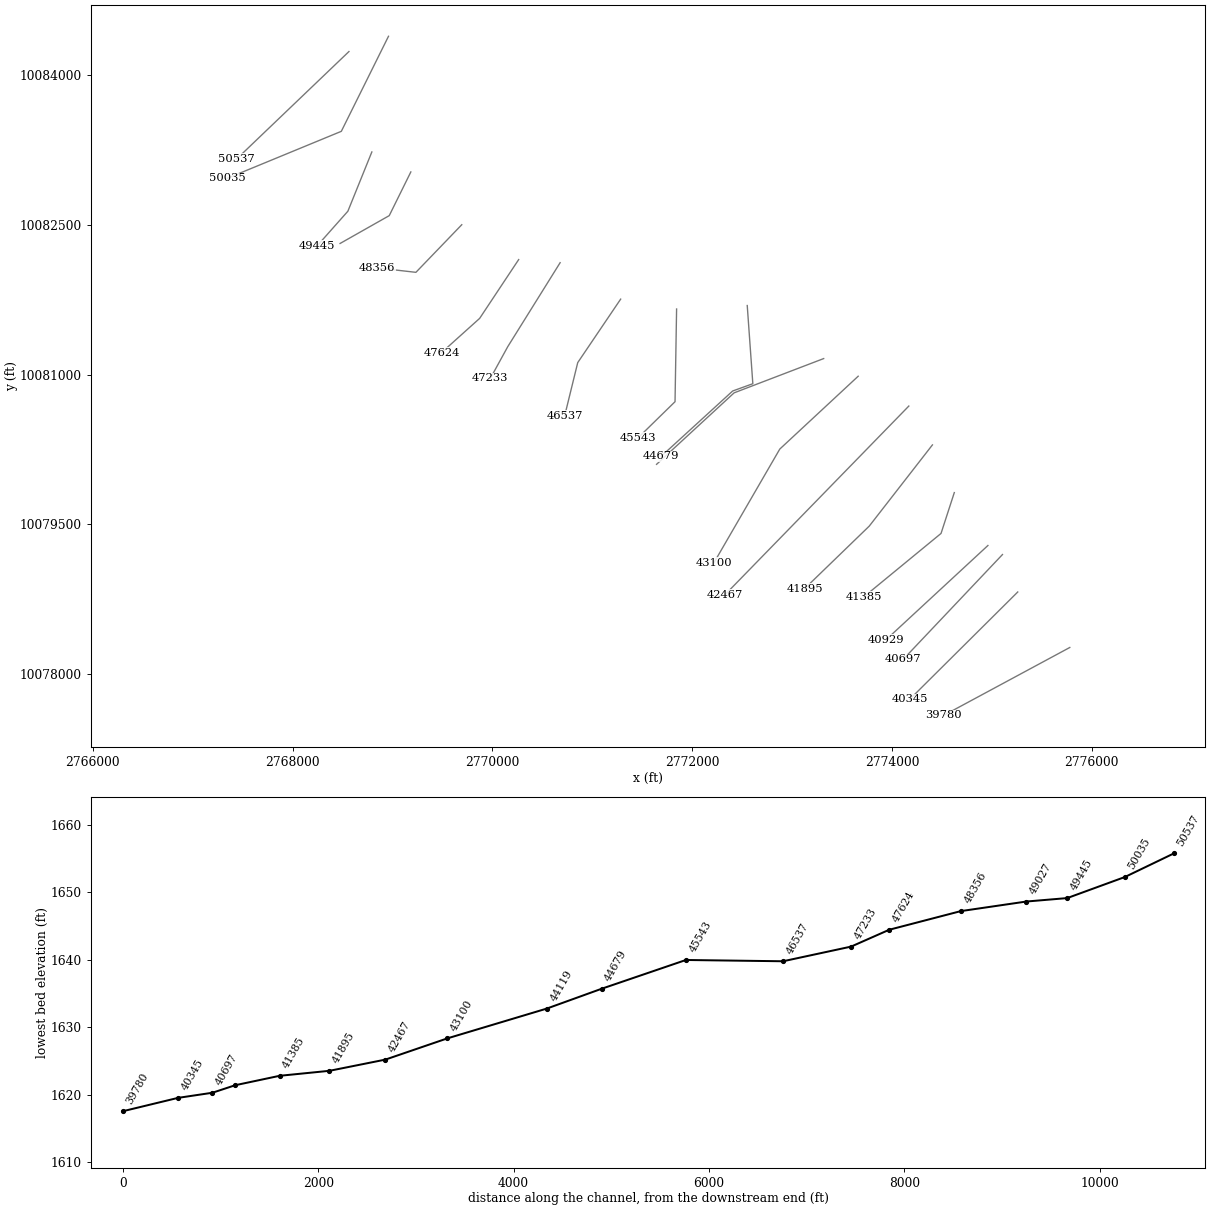
HEC-RAS study PALO ALTO CREEK.prj: PALO ALTO CREEK Base Level Engineering

--- PALO ALTO CREEK.g01 (geometry) --- (continued)

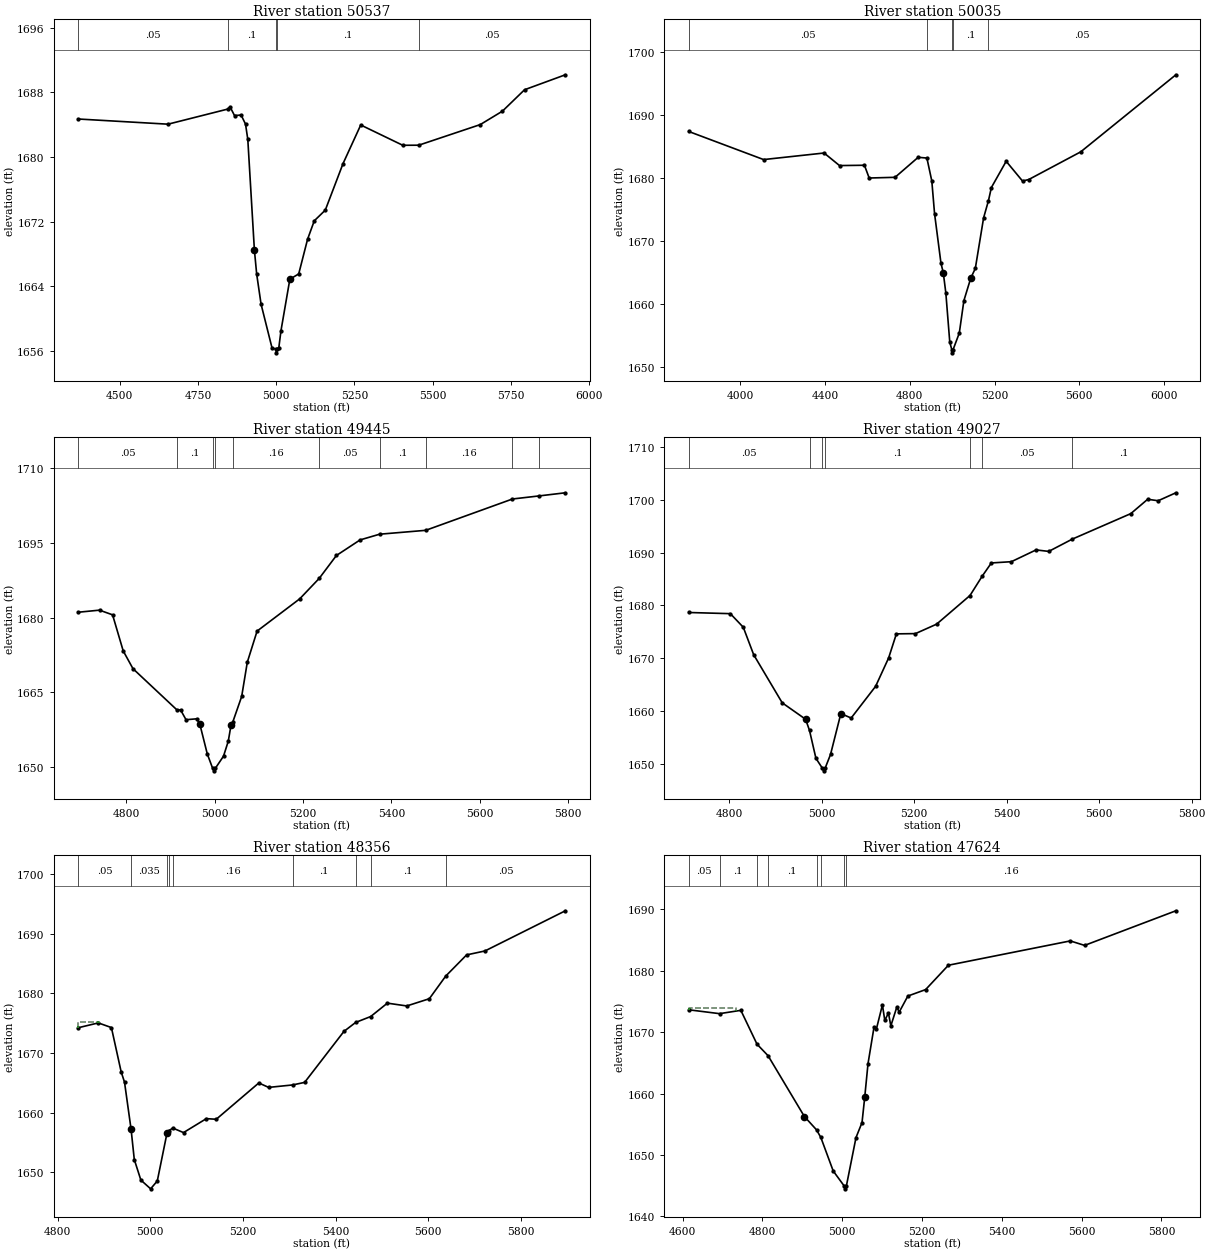
Type RM Length L Ch R = 1 ,50537   ,502,502,502
BEGIN DESCRIPTION:
PALO ALTO CREEK 73.0
END DESCRIPTION:
XS GIS Cut Line= 2
      2768564.29     10084233.74      2767440.01     10083158.04
#Sta/Elev= 30
  4367.7 1684.71  4654.6 1684.07  4844.6 1685.93  4852.8  1686.2  4866.9 1685.14
    4888  1685.2  4902.1 1684.08  4909.4 1682.18  4930.4 1668.53  4937.7 1665.54
  4951.8  1661.8  4987.1 1656.34  4998.2 1656.29    5001 1655.79  5004.2 1656.29
  5008.4 1656.41  5015.4 1658.54  5043.7  1664.9    5072 1665.55  5100.3 1669.84
  5121.7 1672.12  5156.9 1673.44  5213.5 1679.19  5270.1 1683.97  5404.4 1681.46
  5455.3 1681.47  5651.9 1684.02  5722.7 1685.68  5793.4 1688.33  5923.7 1690.18
#Mann= 5 ,-1 , 0
  4367.7     .05       0  4844.6      .1       0  4998.2     .07       0
  5004.2      .1       0  5455.3     .05       0
#XS Ineff= 2 , 0
                         5274.12         1683.75
Permanent Ineff=
       F       F
Bank Sta=4930.4,5043.7
XS Rating Curve= 0 ,0
Exp/Cntr=0.3,0.1

Type RM Length L Ch R = 1 ,50035   ,590,590,590
BEGIN DESCRIPTION:
PALO ALTO CREEK 72.0
END DESCRIPTION:
XS GIS Cut Line= 3
      2768960.12     10084386.51       2768487.9     10083435.12
      2767342.77     10082963.19
#Sta/Elev= 30
  3755.9 1687.35  4109.5  1682.9  4395.2 1683.94    4468 1681.95  4585.7    1682
  4608.1 1679.98  4730.3 1680.09  4839.6 1683.26  4880.7 1683.14  4903.9 1679.51
  4916.9 1674.33  4947.2 1666.47    4958 1664.99  4970.1 1661.79  4988.7    1654
  4998.3 1652.79    5001 1652.29  5004.3 1652.79  5033.7 1655.42  5055.4 1660.56
  5087.8 1664.12  5109.4 1665.66  5148.5 1673.67  5171.5  1676.4  5185.2 1678.47
  5255.1 1682.63  5332.3  1679.5  5361.7 1679.74    5607 1684.12  6056.6 1696.33
#Mann= 5 ,-1 , 0
  3755.9     .05       0  4880.7      .1       0  4998.3     .07       0
  5004.3      .1       0  5171.5     .05       0
Bank Sta=4958,5087.8
XS Rating Curve= 0 ,0
Exp/Cntr=0.3,0.1

Type RM Length L Ch R = 1 ,49445   ,418,418,418
BEGIN DESCRIPTION:
PALO ALTO CREEK 71.0
END DESCRIPTION:
XS GIS Cut Line= 3
      2768793.46     10083228.73      2768553.51     10082635.43
      2768246.22     10082289.08
#Sta/Elev= 30
  4690.8 1681.06    4739 1681.48  4768.6 1680.54  4792.7 1673.28  4814.8 1669.71
    4914 1661.45  4922.7  1661.4  4934.9 1659.45    4959 1659.63  4965.9 1658.65
  4983.1 1652.55  4995.2 1649.67    4998 1649.17  5001.2 1649.67  5019.8 1652.12
  5030.6 1655.14  5036.7 1658.33  5040.4 1658.89  5060.9 1664.12  5073.7 1671.03
  5095.8 1677.27  5192.3 1683.75  5236.5 1687.87  5275.4 1692.47    5329  1695.6
  5373.2 1696.75  5477.6 1697.53    5674 1703.83  5733.5 1704.44  5793.8 1705.08
#Mann= 10 ,-1 , 0
  4690.8     .05       0    4914      .1       0  4995.2     .07       0
  5001.2      .1       0  5040.4     .16       0  5236.5     .05       0
  5373.2      .1       0  5477.6     .16       0    5674      .1       0
  5733.5     .16       0
Bank Sta=4965.9,5036.7
XS Rating Curve= 0 ,0
Exp/Cntr=0.3,0.1

Type RM Length L Ch R = 1 ,49027   ,671,671,671
BEGIN DESCRIPTION:
PALO ALTO CREEK 70.0
END DESCRIPTION:
XS GIS Cut Line= 3
       2769183.7     10083028.71      2768967.57     10082591.16
      2768475.39     10082312.52
#Sta/Elev= 30
  4712.3 1678.67  4802.3 1678.45  4830.3 1675.87  4852.8 1670.66  4914.5 1661.55
    4965 1658.44  4973.5 1656.32  4987.4 1651.03  5001.3 1649.16  5004.1 1648.66
  5007.3 1649.16    5019 1651.77  5041.3 1659.51  5063.6 1658.67  5116.5 1664.68
  5144.6 1670.05  5161.4 1674.62  5202.7 1674.67  5248.4 1676.46  5320.6 1681.89
  5346.8 1685.53  5366.8 1688.06  5410.1  1688.3  5463.5 1690.53  5490.9 1690.25
  5541.9 1692.58  5668.4 1697.41  5704.9 1700.13  5727.6 1699.85  5765.9 1701.36
#Mann= 7 ,-1 , 0
  4712.3     .05       0  4973.5      .1       0  5001.3     .07       0
  5007.3      .1       0  5320.6     .16       0  5346.8     .05       0
  5541.9      .1       0
Bank Sta=4965,5041.3
XS Rating Curve= 0 ,0
Exp/Cntr=0.3,0.1

Type RM Length L Ch R = 1 ,48356   ,732,732,732
BEGIN DESCRIPTION:
PALO ALTO CREEK 69.0
END DESCRIPTION:
XS GIS Cut Line= 3
      2769693.44      10082500.2      2769234.49     10082023.67
      2768846.51     10082067.93
#Sta/Elev= 30
  4844.2 1674.22  4887.6 1675.03  4915.9 1674.25    4937 1666.82  4944.2 1665.11
  4958.4  1657.2  4965.3 1652.15  4979.5 1648.71  5000.6 1647.24    5015 1648.56
  5036.1 1656.63  5039.4 1656.95  5048.5 1657.42  5071.6 1656.66    5121    1659
  5142.3 1658.89  5234.2 1664.97  5255.5 1664.23  5307.3 1664.64  5333.2 1665.07
  5418.1 1673.61  5443.4 1675.11  5475.9  1676.1  5511.9 1678.34  5553.8 1677.87
  5602.5 1679.08  5637.9 1682.87    5683 1686.42  5722.6 1687.08  5896.3 1693.81
#Mann= 9 ,-1 , 0
  4844.2     .05       0  4958.4    .035       0  5036.1     .05       0
  5039.4      .1       0  5048.5     .16       0  5307.3      .1       0
  5443.4     .05       0  5475.9      .1       0  5637.9     .05       0
#XS Ineff= 2 , 0
         4888.51 1675.14
Permanent Ineff=
       F       F
Bank Sta=4958.4,5036.1
XS Rating Curve= 0 ,0
Exp/Cntr=0.3,0.1

Type RM Length L Ch R = 1 ,47624   ,391,391,391
BEGIN DESCRIPTION:
PALO ALTO CREEK 68.0
END DESCRIPTION:
XS GIS Cut Line= 3
      2770263.15     10082151.29      2769872.52     10081562.73
       2769489.7     10081218.98
#Sta/Elev= 30
  4615.2 1673.65  4692.4 1673.02  4745.8 1673.56  4786.3 1668.05    4814 1666.17
  4905.1 1656.26  4935.5 1654.09  4946.3 1652.85  4977.3 1647.39  5004.4 1644.98
  5007.1 1644.48  5010.4 1644.98  5034.4 1652.83  5049.5 1655.28  5056.3 1659.42
  5064.5 1664.87  5079.6 1670.84  5085.6 1670.54  5100.6 1674.44  5106.6 1671.91
  5115.7 1673.13  5121.7 1671.03  5136.7 1674.09  5142.7 1673.28  5164.4 1675.89
  5208.9 1676.94    5266 1680.91  5571.4 1684.87  5607.3 1684.14  5836.1 1689.78
#Mann= 8 ,-1 , 0
  4615.2     .05       0  4692.4      .1       0  4786.3     .05       0
    4814      .1       0  4935.5     .05       0  4946.3     .16       0
  5004.4     .07       0  5010.4     .16       0
#XS Ineff= 2 , 0
         4734.58 1673.88
Permanent Ineff=
       F       F
Bank Sta=4905.1,5056.3
XS Rating Curve= 0 ,0
Exp/Cntr=0.3,0.1

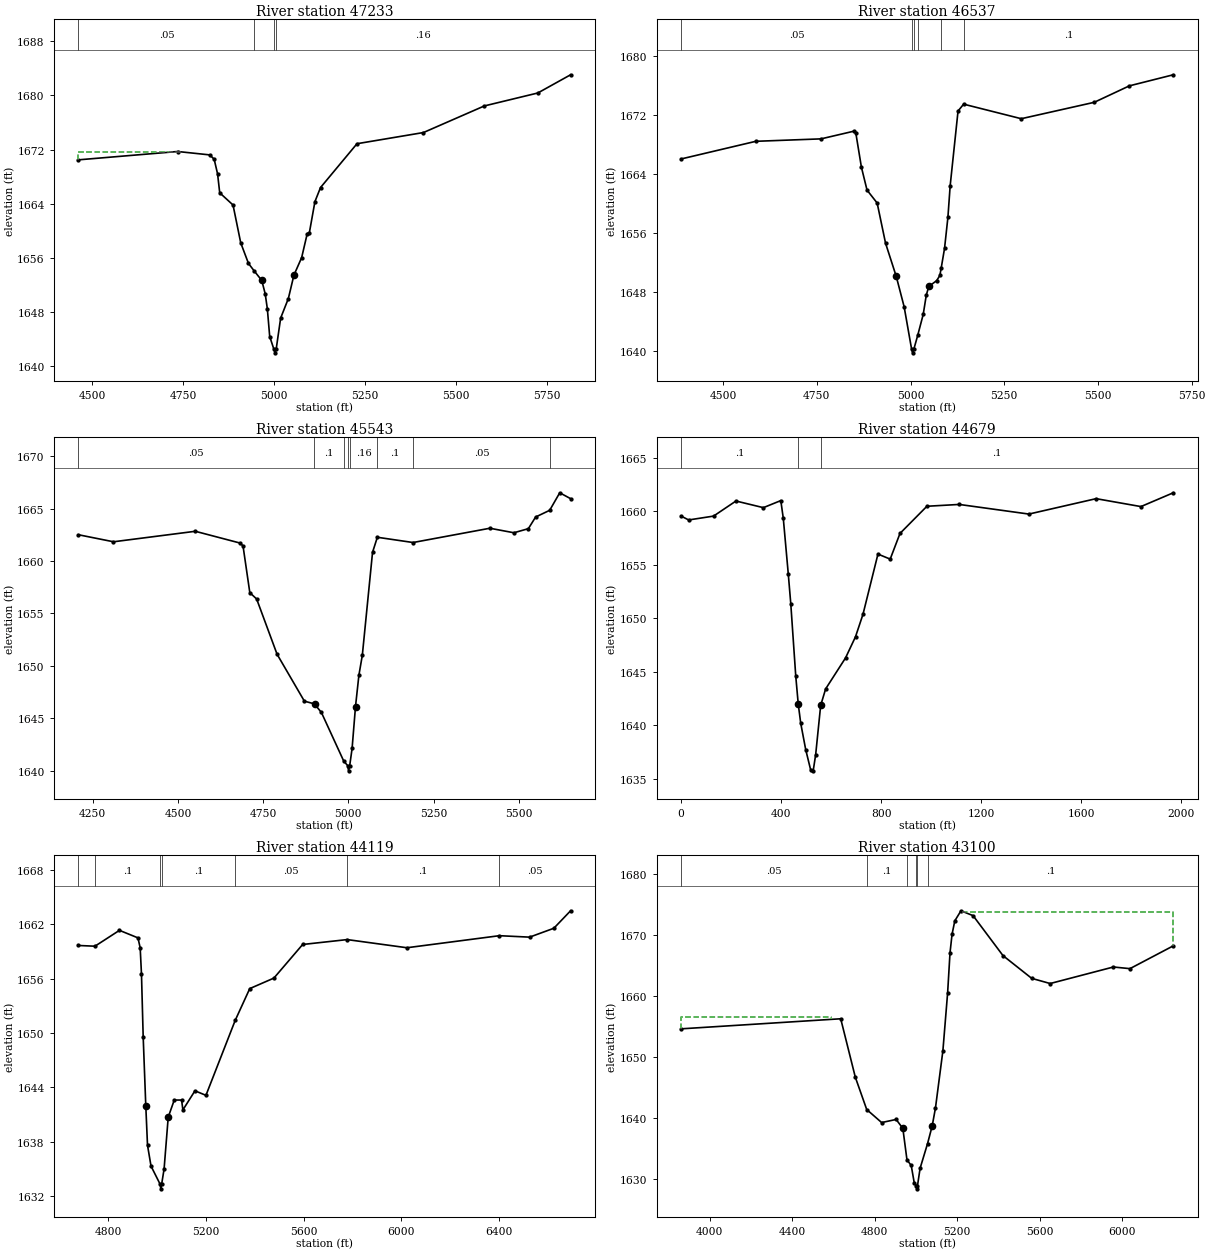
Type RM Length L Ch R = 1 ,47233   ,696,696,696
BEGIN DESCRIPTION:
PALO ALTO CREEK 67.0
END DESCRIPTION:
XS GIS Cut Line= 3
      2770678.07     10082120.16      2770153.58     10081279.15
      2769979.27     10080961.14
#Sta/Elev= 30
  4462.3 1670.48  4735.3 1671.71  4823.4 1671.21  4835.6 1670.57    4845 1668.41
  4850.9 1665.61  4887.5 1663.81  4908.7 1658.22    4930 1655.18  4946.5 1654.02
  4966.5 1652.68    4976  1650.7  4981.9 1648.49  4988.4 1644.39  5000.1 1642.48
  5002.9 1641.98  5006.1 1642.48  5018.5 1647.11  5039.7    1650    5055 1653.45
  5076.3 1656.04  5091.6 1659.58  5097.5 1659.72  5112.8 1664.31  5128.2 1666.39
  5228.5 1672.86  5411.3 1674.51  5578.9 1678.44  5725.9 1680.35  5816.1 1683.04
#Mann= 4 ,-1 , 0
  4462.3     .05       0  4946.5     .16       0  5000.1     .07       0
  5006.1     .16       0
#XS Ineff= 2 , 0
         4750.18 1671.62
Permanent Ineff=
       F       F
Bank Sta=4966.5,5055
XS Rating Curve= 0 ,0
Exp/Cntr=0.3,0.1

Type RM Length L Ch R = 1 ,46537   ,994,994,994
BEGIN DESCRIPTION:
PALO ALTO CREEK 66.0
END DESCRIPTION:
XS GIS Cut Line= 3
        2771284.     10081755.48      2770854.29     10081120.02
      2770724.14     10080589.87
#Sta/Elev= 30
    4388 1666.07  4587.3 1668.46  4761.1 1668.79  4847.9 1669.82    4854 1669.58
  4868.9 1664.95  4883.9 1661.85  4910.9  1660.1  4933.3 1654.66  4961.9 1650.15
  4982.9 1646.05  5002.8 1640.31  5005.5 1639.81  5008.8 1640.31  5019.3 1642.21
  5033.8 1645.02    5042 1647.63  5048.7  1648.8  5069.7 1649.59  5078.2 1650.29
    5082 1651.36  5090.7 1653.96  5099.7 1658.18  5105.7 1662.45  5126.7 1672.56
  5141.6 1673.49  5295.4 1671.52    5490 1673.74  5583.8 1675.97    5701 1677.47
#Mann= 6 ,-1 , 0
    4388     .05       0  5002.8    .035       0  5008.8     .05       0
  5019.3      .1       0    5082     .16       0  5141.6      .1       0
Bank Sta=4961.9,5048.7
XS Rating Curve= 0 ,0
Exp/Cntr=0.3,0.1

Type RM Length L Ch R = 1 ,45543   ,864,864,864
BEGIN DESCRIPTION:
PALO ALTO CREEK 65.0
END DESCRIPTION:
XS GIS Cut Line= 3
      2771843.87     10081656.49      2771828.24     10080728.73
       2771459.1     10080368.05
#Sta/Elev= 30
  4208.2  1662.5    4311 1661.83    4551 1662.83    4681 1661.72    4691 1661.45
    4711 1656.98    4731 1656.38    4791 1651.11  4871.1 1646.64  4898.6  1646.4
  4901.1 1646.36  4921.1 1645.56  4986.7 1640.92  4998.1  1640.5  5000.8    1640
  5004.1  1640.5  5011.1 1642.13  5021.1 1646.13  5031.1 1649.12  5041.1 1651.01
  5071.1 1660.83  5085.2 1662.26    5190 1661.76  5415.3 1663.12  5485.9 1662.69
  5528.3 1663.08  5549.6 1664.19  5590.9 1664.83  5620.4  1666.5  5652.2 1665.94
#Mann= 8 ,-1 , 0
  4208.2     .05       0  4898.6      .1       0  4986.7     .16       0
  4998.1     .07       0  5004.1     .16       0  5085.2      .1       0
    5190     .05       0  5590.9      .1       0
Bank Sta=4901.1,5021.1
XS Rating Curve= 0 ,0
Exp/Cntr=0.3,0.1

Type RM Length L Ch R = 1 ,44679   ,560,560,560
XS GIS Cut Line= 4
     2772550.988    10081691.306     2772606.977    10080908.754
     2772405.154    10080835.837     2771691.613    10080183.493
#Sta/Elev= 30
       0 1659.54   29.89 1659.18  129.52 1659.54  219.18 1660.95  328.77 1660.33
  398.51 1660.99  408.47 1659.33   428.4 1654.13  438.36 1651.36  458.29 1644.58
  468.25 1641.97  478.21 1640.17  498.14 1637.71  518.06  1635.8  528.03 1635.73
  537.99 1637.25  557.91 1641.84  577.84 1643.39  657.54 1646.29  697.39 1648.27
  727.28 1650.37  787.06 1655.99  836.01 1655.52  875.17 1657.92  982.86 1660.46
 1111.97 1660.63 1390.76 1659.73  1659.6 1661.17 1838.83 1660.43 1968.27 1661.72
#Mann= 3 , 0 , 0
       0      .1       0  468.25     .07       0  557.91      .1       0
Bank Sta=468.25,557.91
XS Rating Curve= 0 ,0
Exp/Cntr=0.3,0.1

Type RM Length L Ch R = 1 ,44119   ,1019,1019,1019
BEGIN DESCRIPTION:
PALO ALTO CREEK 64.0
END DESCRIPTION:
XS GIS Cut Line= 3
      2773316.06     10081160.37      2772419.82      10080817.5
      2771643.42     10080101.85
#Sta/Elev= 30
  4677.3 1659.66  4744.9 1659.58  4845.2 1661.33    4921  1660.5  4930.1  1659.4
  4935.4 1656.49  4942.4 1649.56  4953.1 1641.92  4960.1 1637.61  4974.5 1635.31
  5011.9  1633.3  5014.6  1632.8  5017.9  1633.3    5028 1634.99  5044.9 1640.71
  5069.6  1642.6  5099.7  1642.6    5105 1641.51  5154.4 1643.62  5199.4 1643.12
  5319.2 1651.39  5378.8  1654.9  5477.7 1656.06  5595.5 1659.77  5777.8 1660.31
  6022.5 1659.41  6401.1 1660.74  6524.9 1660.58  6624.2 1661.56  6692.8 1663.49
#Mann= 7 ,-1 , 0
  4677.3     .05       0  4744.9      .1       0  5011.9     .07       0
  5017.9      .1       0  5319.2     .05       0  5777.8      .1       0
  6401.1     .05       0
Bank Sta=4953.1,5044.9
XS Rating Curve= 0 ,0
Exp/Cntr=0.3,0.1

Type RM Length L Ch R = 1 ,43100   ,633,633,633
BEGIN DESCRIPTION:
PALO ALTO CREEK 63.0
END DESCRIPTION:
XS GIS Cut Line= 3
      2773661.54     10080983.76      2772876.79     10080254.57
      2772217.98     10079117.25
#Sta/Elev= 30
  3861.8 1654.62  4635.2 1656.27    4706 1646.69  4761.2 1641.39  4833.6 1639.25
  4903.9 1639.76  4936.4 1638.29  4956.4 1633.13    4977 1632.21  4991.8 1629.34
  5001.3 1628.88  5004.1 1628.38  5007.3 1628.88  5020.1 1631.76  5056.2  1635.8
  5078.9 1638.74  5094.6 1641.66  5130.5 1651.01  5153.5 1660.54  5165.1 1667.11
    5175 1670.14  5188.3 1672.33  5218.1 1673.98  5276.9 1673.18  5421.8 1666.63
    5561  1662.9  5650.5 1662.05    5957 1664.76  6037.3 1664.49  6247.4 1668.23
#Mann= 6 ,-1 , 0
  3861.8     .05       0  4761.2      .1       0  4956.4     .05       0
  5001.3    .035       0  5007.3     .05       0  5056.2      .1       0
#XS Ineff= 2 , 0
         4588.27 1656.63 5221.28         1673.74
Permanent Ineff=
       F       F
Bank Sta=4936.4,5078.9
XS Rating Curve= 0 ,0
Exp/Cntr=0.3,0.1

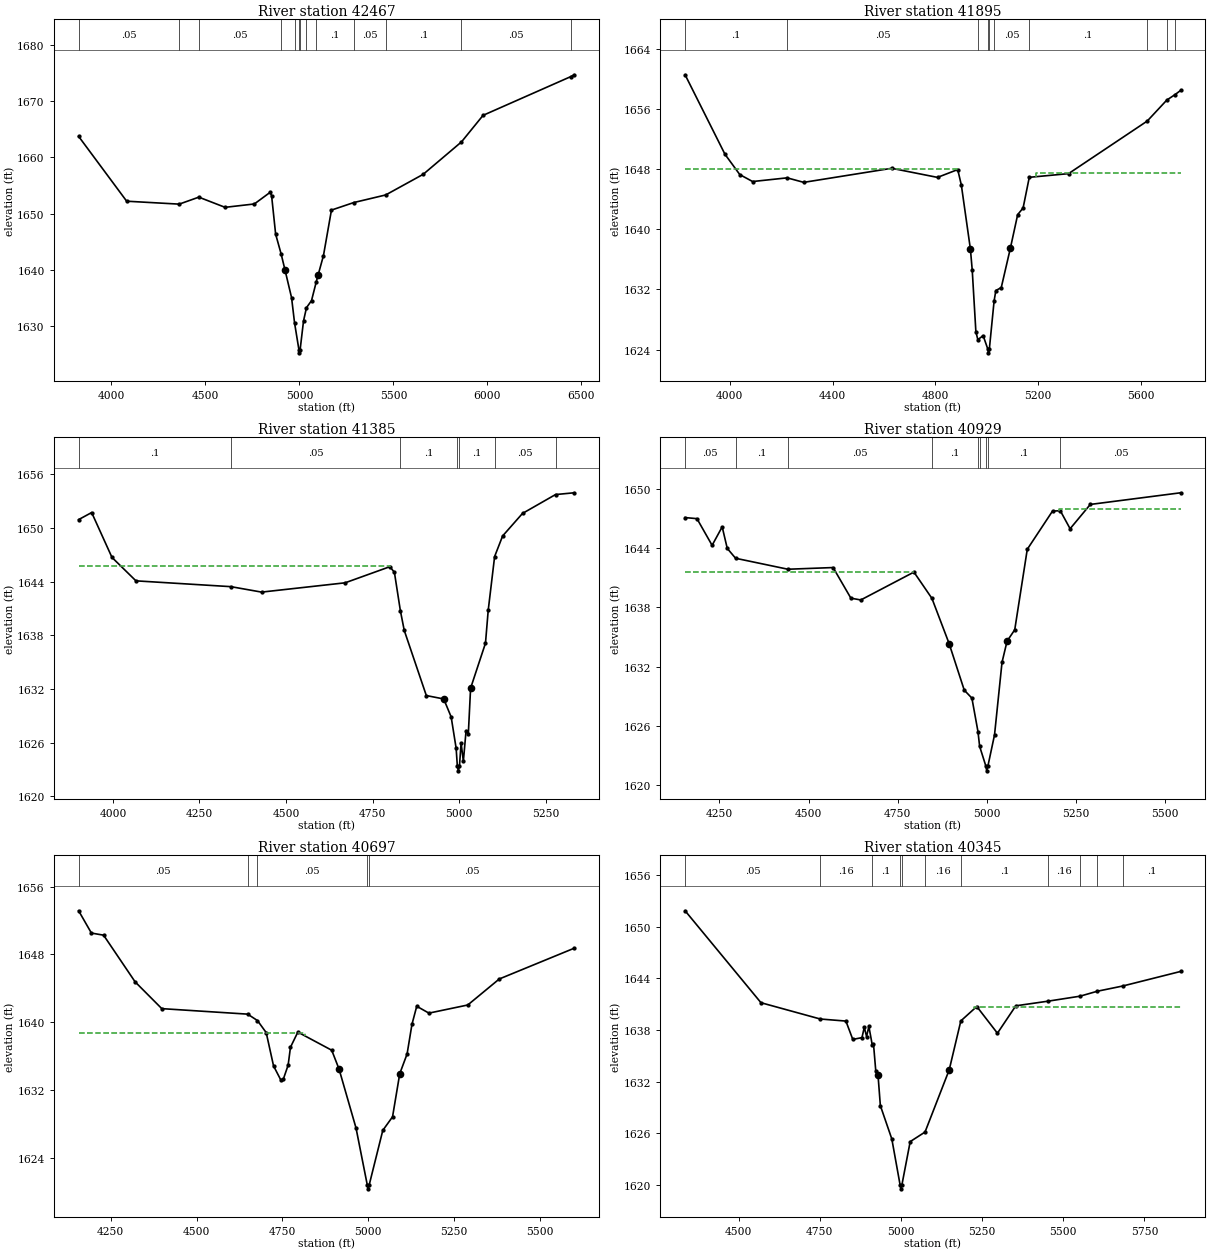
Type RM Length L Ch R = 1 ,42467   ,572,572,572
BEGIN DESCRIPTION:
PALO ALTO CREEK 62.0
END DESCRIPTION:
XS GIS Cut Line= 2
      2774168.47     10080685.13       2772329.4     10078797.49
#Sta/Elev= 30
    3826 1663.71  4081.5 1652.19  4360.9 1651.67  4465.2 1652.91  4604.9  1651.1
  4760.5  1651.7  4845.4 1653.79  4852.4 1653.12  4873.7 1646.34  4902.5 1642.87
  4923.1 1640.03  4958.5 1635.03  4974.3 1630.57  4997.8 1625.74  5000.5 1625.24
  5003.8 1625.74  5022.1 1630.93  5037.8 1633.27  5064.5 1634.52  5089.8 1637.86
  5099.8 1639.09  5128.1 1642.53  5170.5 1650.61  5289.2 1651.95  5458.9  1653.3
  5658.5 1656.97  5862.1 1662.73  5976.9 1667.45  6444.4 1674.35  6461.4 1674.66
#Mann= 13 ,-1 , 0
    3826     .05       0  4360.9      .1       0  4465.2     .05       0
  4902.5      .1       0  4974.3     .05       0  4997.8    .035       0
  5003.8     .05       0  5037.8     .16       0  5089.8      .1       0
  5289.2     .05       0  5458.9      .1       0  5862.1     .05       0
  6444.4      .1       0
Bank Sta=4923.1,5099.8
XS Rating Curve= 0 ,0
Exp/Cntr=0.3,0.1

Type RM Length L Ch R = 1 ,41895   ,510,510,510
BEGIN DESCRIPTION:
PALO ALTO CREEK 61.0
END DESCRIPTION:
XS GIS Cut Line= 3
      2774404.58     10080296.25      2773772.62     10079483.73
      2773126.78     10078858.72
#Sta/Elev= 30
  3826.4 1660.54  3981.6 1649.97  4039.3 1647.27  4089.1 1646.35  4223.4 1646.84
  4288.1 1646.24  4630.2 1648.11  4808.5  1646.9  4887.1 1647.94  4901.2 1645.89
  4936.5 1637.37  4943.6 1634.58  4957.8 1626.39  4965.4 1625.33  4986.1 1625.87
  5004.2 1624.08  5006.9 1623.58  5010.2 1624.08  5028.7 1630.47  5035.5 1631.86
  5056.6 1632.26  5092.1  1637.5  5120.4 1641.95  5141.5 1642.83  5165.6 1646.91
  5318.4  1647.4  5624.6 1654.39  5700.7 1657.18  5732.1 1657.89  5754.5 1658.46
#Mann= 10 ,-1 , 0
  3826.4      .1       0  4223.4     .05       0  4965.4      .1       0
  5004.2     .07       0  5010.2      .1       0  5028.7     .05       0
  5165.6      .1       0  5624.6     .05       0  5700.7      .1       0
  5732.1     .05       0
#XS Ineff= 2 , 0
         4884.52 1647.96 5189.84         1647.47
Permanent Ineff=
       F       F
Bank Sta=4936.5,5092.1
XS Rating Curve= 0 ,0
Exp/Cntr=0.3,0.1

Type RM Length L Ch R = 1 ,41385   ,456,456,456
BEGIN DESCRIPTION:
PALO ALTO CREEK 60.0
END DESCRIPTION:
XS GIS Cut Line= 3
      2774623.66     10079818.95      2774490.84     10079410.09
      2773717.38     10078774.65
#Sta/Elev= 30
    3901 1650.94  3938.6 1651.73  3997.3 1646.71  4066.5 1644.09  4340.7 1643.44
  4429.3 1642.83  4670.5 1643.87  4799.5 1645.67  4812.8 1645.05    4830 1640.76
  4841.2 1638.55    4905 1631.26  4955.2 1630.88  4976.7 1628.87  4991.1 1625.36
  4994.6 1623.34  4997.3 1622.84  5000.6 1623.34  5005.4 1625.96  5011.9 1623.91
  5019.8 1627.34  5026.3    1627  5032.8 1632.08  5075.8 1637.12  5083.7  1640.8
  5102.2 1646.81  5125.3 1649.11  5182.7 1651.63    5278 1653.74  5331.9 1653.94
#Mann= 7 ,-1 , 0
    3901      .1       0  4340.7     .05       0    4830      .1       0
  4994.6     .07       0  5000.6      .1       0  5102.2     .05       0
    5278      .1       0
#XS Ineff= 2 , 0
         4799.27 1645.78
Permanent Ineff=
       F       F
Bank Sta=4955.2,5032.8
XS Rating Curve= 0 ,0
Exp/Cntr=0.3,0.1

Type RM Length L Ch R = 1 ,40929   ,232,232,232
BEGIN DESCRIPTION:
Mapping XS 4b6053a2
END DESCRIPTION:
XS GIS Cut Line= 2
       2774960.1     10079289.26      2773939.27     10078344.83
#Sta/Elev= 30
  4153.6 1647.08  4186.9 1646.97  4229.4 1644.27  4257.7 1646.14  4271.9 1643.96
  4295.3 1642.96  4442.1 1641.85    4569 1642.02  4618.9 1638.92  4646.7 1638.74
  4795.8 1641.56  4846.3  1638.9  4894.5 1634.33    4937 1629.61  4958.5  1628.8
  4975.5 1625.42  4980.2 1623.92  4997.5 1621.94  5000.2 1621.44  5003.5 1621.94
    5022 1625.08    5043 1632.42  5057.2 1634.57  5078.7 1635.72  5113.9 1643.87
  5184.8 1647.74  5206.6 1647.77  5234.1 1645.95  5290.8 1648.41  5544.3 1649.59
#Mann= 9 ,-1 , 0
  4153.6     .05       0  4295.3      .1       0  4442.1     .05       0
  4846.3      .1       0  4975.5     .05       0  4980.2      .1       0
  4997.5     .07       0  5003.5      .1       0  5206.6     .05       0
#XS Ineff= 2 , 0
         4795.16 1641.56 5202.42         1647.94
Permanent Ineff=
       F       F
Bank Sta=4894.5,5057.2
XS Rating Curve= 0 ,0
Exp/Cntr=0.3,0.1

Type RM Length L Ch R = 1 ,40697   ,352,352,352
BEGIN DESCRIPTION:
PALO ALTO CREEK 59.0
END DESCRIPTION:
XS GIS Cut Line= 2
      2775105.92     10079198.98      2774113.15     10078150.66
#Sta/Elev= 30
  4156.5 1653.15  4193.7 1650.52  4229.2 1650.27  4321.1 1644.76  4398.8  1641.6
    4649 1640.95  4677.6 1640.19    4703 1638.77  4724.4 1634.84  4745.4 1633.19
  4752.7 1633.25  4766.9 1634.93  4773.7 1637.04  4795.2 1638.83  4893.9 1636.69
  4915.3 1634.46  4964.7 1627.51  4997.3 1620.83    5000 1620.33  5003.3 1620.83
  5042.7 1627.23  5071.1 1628.83  5092.1 1633.92  5113.5 1636.25  5127.7 1639.75
  5141.6 1641.88  5177.1 1641.07  5290.3 1642.03  5382.1  1645.1  5600.3 1648.73
#Mann= 5 ,-1 , 0
  4156.5     .05       0    4649     .16       0  4677.6     .05       0
  4997.3     .04       0  5003.3     .05       0
#XS Ineff= 2 , 0
         4815.11 1638.77
Permanent Ineff=
       F       F
Bank Sta=4915.3,5092.1
XS Rating Curve= 0 ,0
Exp/Cntr=0.3,0.1

Type RM Length L Ch R = 1 ,40345   ,565,565,565
BEGIN DESCRIPTION:
PALO ALTO CREEK 58.0
END DESCRIPTION:
XS GIS Cut Line= 2
      2775258.71     10078823.99      2774175.99     10077748.21
#Sta/Elev= 30
  4335.1 1651.84  4568.8 1641.17  4751.3 1639.28  4830.4 1639.04  4851.6 1636.91
  4879.9 1637.12    4887 1638.32  4894.1 1637.24  4901.1 1638.42  4911.6 1636.27
  4915.3 1636.42  4922.4 1633.25  4929.4 1632.73  4936.5 1629.23  4971.8 1625.36
  4997.1 1620.07  4999.9 1619.57  5003.1 1620.07  5028.4 1625.05  5074.1 1626.16
  5148.6 1633.38  5184.4 1639.06  5233.5 1640.73  5297.1 1637.63  5353.7 1640.81
  5453.1 1641.35  5551.8 1641.93  5604.5  1642.5  5683.2 1643.11  5861.4  1644.8
#Mann= 11 ,-1 , 0
  4335.1     .05       0  4751.3     .16       0  4911.6      .1       0
  4997.1     .07       0  5003.1      .1       0  5074.1     .16       0
  5184.4      .1       0  5453.1     .16       0  5551.8      .1       0
  5604.5     .16       0  5683.2      .1       0
#XS Ineff= 2 , 0
                         5224.06         1640.73
Permanent Ineff=
       F       F
Bank Sta=4929.4,5148.6
XS Rating Curve= 0 ,0
Exp/Cntr=0.3,0.1

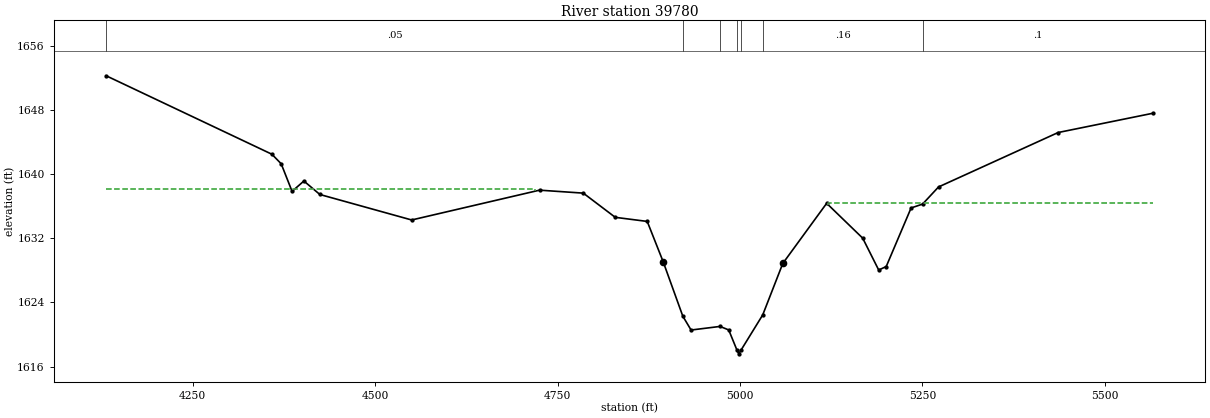
Type RM Length L Ch R = 1 ,39780   ,1068,1068,1068
BEGIN DESCRIPTION:
PALO ALTO CREEK 57.0
END DESCRIPTION:
XS GIS Cut Line= 2
      2775779.59     10078268.47      2774516.47     10077588.33
#Sta/Elev= 30
  4131.5 1652.28  4358.6 1642.49  4371.3  1641.3  4386.2 1637.86  4402.4 1639.15
  4424.3 1637.47  4550.1 1634.29  4725.3 1638.01  4785.3 1637.64  4829.1 1634.62
  4872.9 1634.11  4894.8 1629.07  4921.7 1622.28    4933 1620.56  4972.7 1621.01
  4984.6 1620.57  4995.7 1618.09  4998.4 1617.59  5001.7 1618.09  5031.2 1622.45
  5058.7 1628.87  5118.8 1636.37  5168.2 1632.02  5190.1 1628.05  5200.4 1628.48
  5234.5 1635.79  5250.2 1636.27  5272.1 1638.41    5436  1645.2  5566.1 1647.61
#Mann= 7 ,-1 , 0
  4131.5     .05       0  4921.7     .16       0  4972.7      .1       0
  4995.7     .07       0  5001.7      .1       0  5031.2     .16       0
  5250.2      .1       0
#XS Ineff= 2 , 0
         4719.71  1638.1 5121.16          1636.4
Permanent Ineff=
       F       F
Bank Sta=4894.8,5058.7
XS Rating Curve= 0 ,0
Exp/Cntr=0.3,0.1