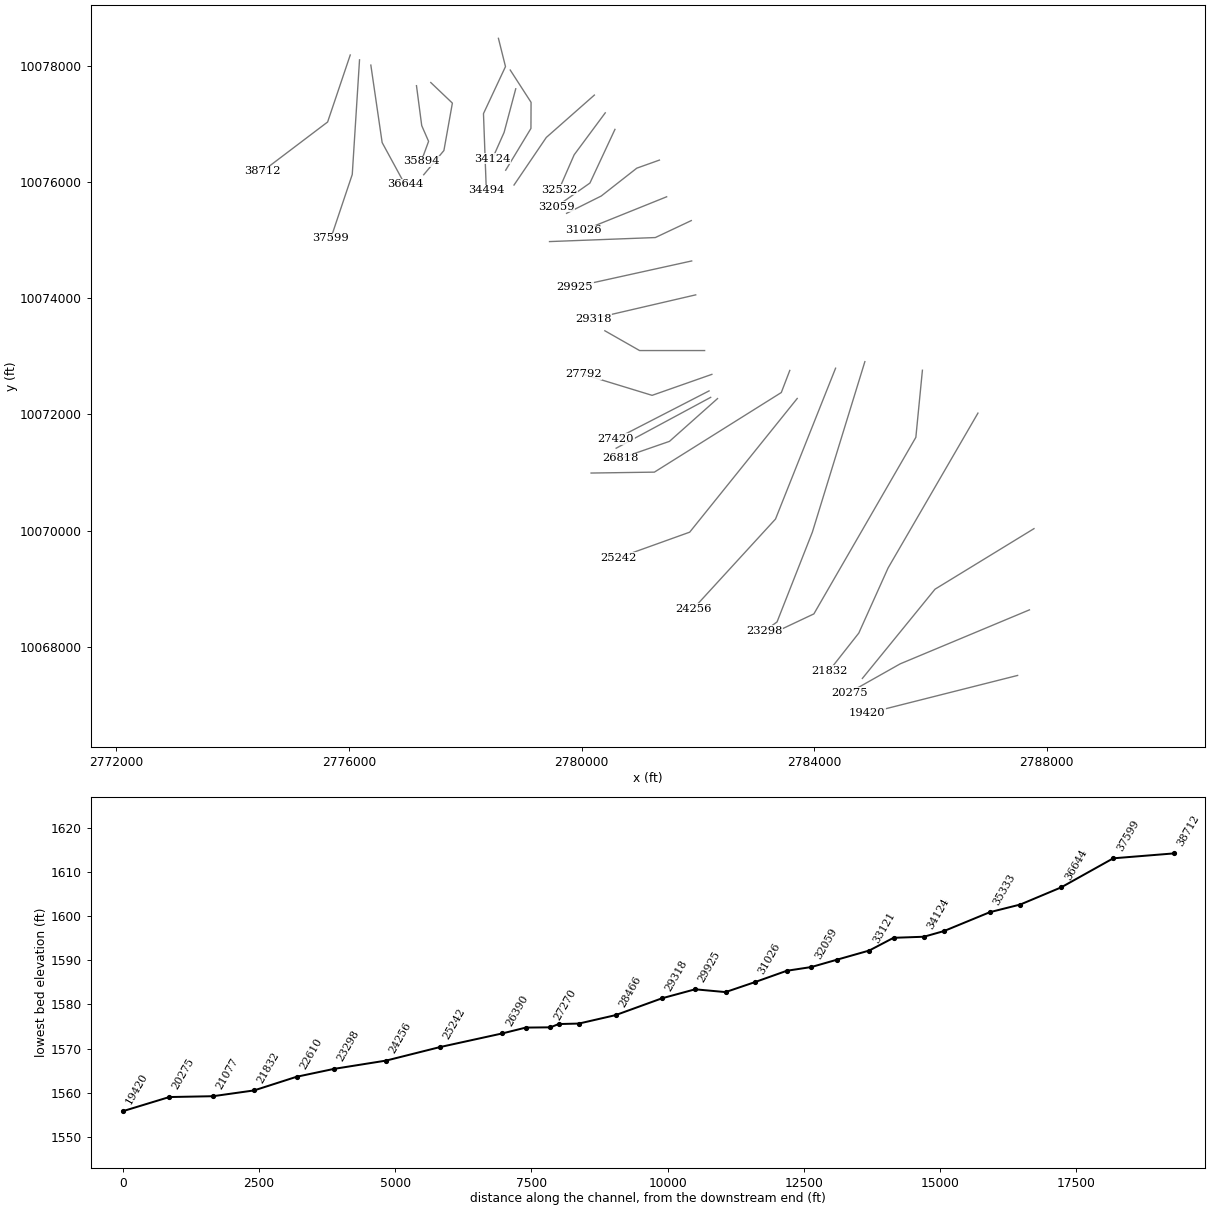
HEC-RAS study PALO ALTO CREEK.prj: PALO ALTO CREEK Base Level Engineering

--- PALO ALTO CREEK.g01 (geometry) --- (continued)

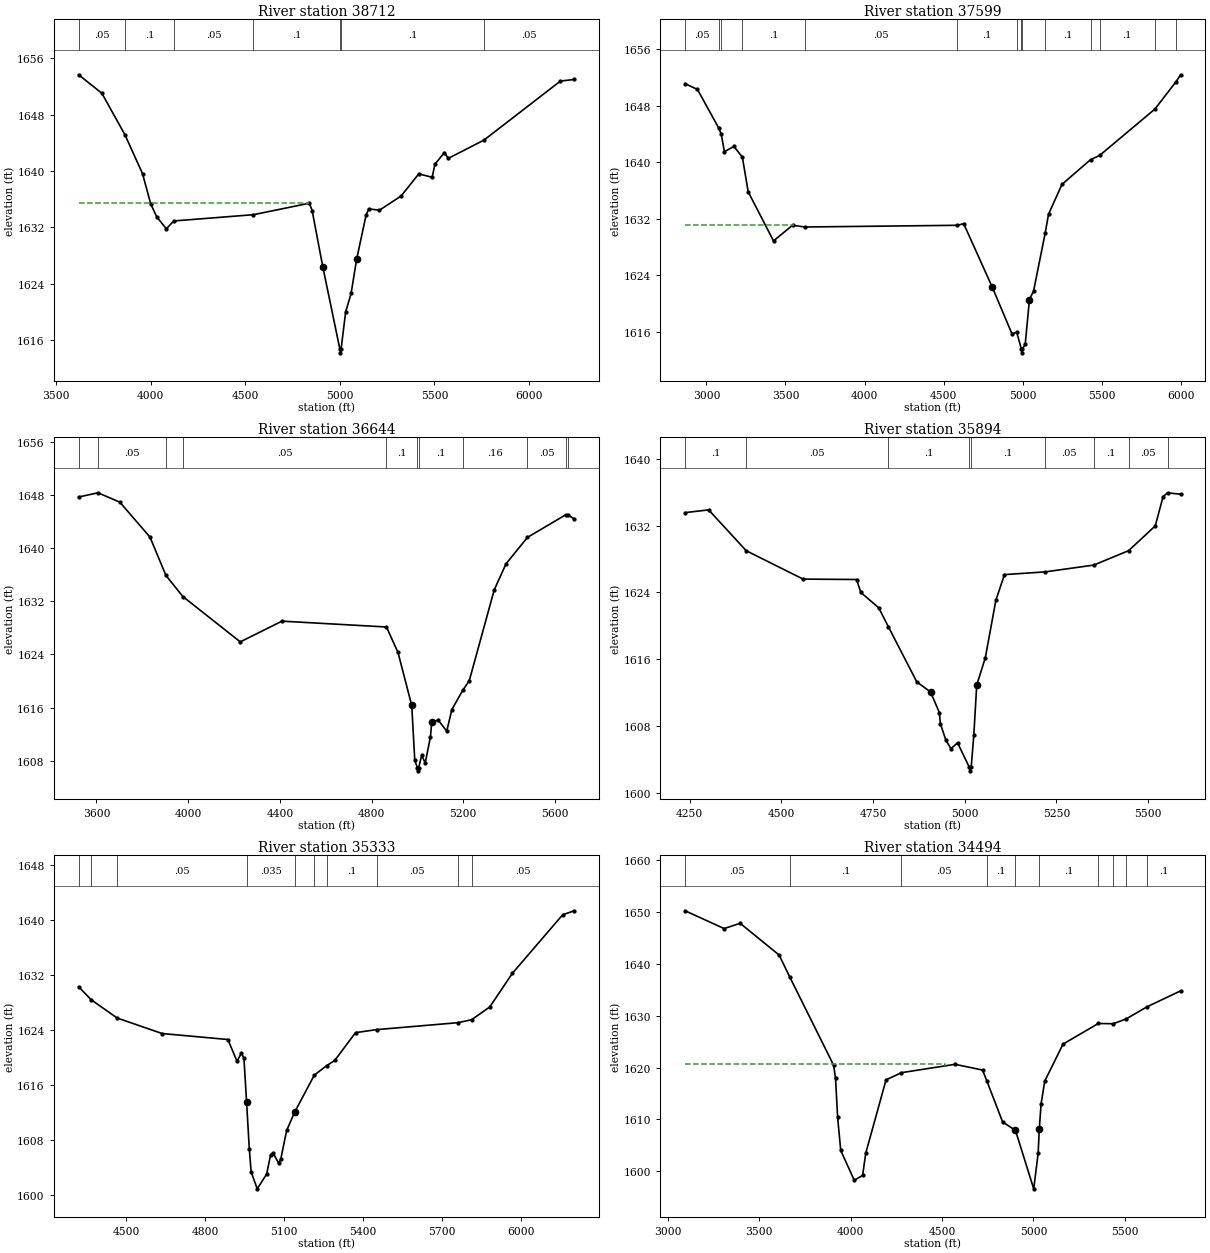
Type RM Length L Ch R = 1 ,38712   ,1113,1113,1113
BEGIN DESCRIPTION:
Mapping XS 89d2525c
END DESCRIPTION:
XS GIS Cut Line= 3
      2776022.62      10078185.1      2775633.73     10077032.34
      2774515.66     10076185.11
#Sta/Elev= 30
  3619.3 1653.65  3741.9 1651.03  3864.3 1645.12    3957 1639.61  4000.7 1635.28
  4032.3 1633.47  4082.9 1631.77  4122.3 1632.89  4543.6 1633.78    4839 1635.41
  4853.6 1634.37  4909.8  1626.4  5000.4 1614.66  5003.1 1614.16  5006.4 1614.66
  5030.7 1619.95  5059.6 1622.61  5088.7 1627.43  5138.6 1633.71  5153.2  1634.6
  5209.4 1634.42  5323.8 1636.43  5417.4 1639.58  5488.1 1639.09  5502.7 1640.95
  5552.6 1642.61  5573.4 1641.78  5761.6 1644.37  6166.3 1652.76  6238.7 1652.98
#Mann= 7 ,-1 , 0
  3619.3     .05       0  3864.3      .1       0  4122.3     .05       0
  4543.6      .1       0  5000.4     .07       0  5006.4      .1       0
  5761.6     .05       0
#XS Ineff= 2 , 0
         4838.57 1635.45
Permanent Ineff=
       F       F
Bank Sta=4909.8,5088.7
XS Rating Curve= 0 ,0
Exp/Cntr=0.3,0.1

Type RM Length L Ch R = 1 ,37599   ,955,955,955
BEGIN DESCRIPTION:
PALO ALTO CREEK 56.0
END DESCRIPTION:
XS GIS Cut Line= 3
      2776182.35     10078101.81      2776057.35     10076129.57
      2775689.29     10075032.35
#Sta/Elev= 30
  2865.3 1651.13  2943.5  1650.3  3077.8 1644.86  3094.1 1643.95  3113.9  1641.5
    3174 1642.25  3227.5 1640.73  3264.2 1635.83  3424.5 1628.88  3544.7  1631.1
  3621.7 1630.85  4587.7 1631.09  4626.9 1631.32  4807.3 1622.36    4932 1615.75
  4962.3 1615.95  4992.3 1613.55  4995.1 1613.05  4998.3 1613.55  5016.4 1614.33
  5042.6 1620.58  5068.8 1621.79  5142.4    1630  5163.5 1632.66  5248.5 1636.88
  5429.3 1640.38  5486.5 1640.97  5836.6 1647.54  5968.9 1651.38  5998.8 1652.38
#Mann= 14 ,-1 , 0
  2865.3     .05       0  3077.8      .1       0  3094.1     .05       0
  3227.5      .1       0  3621.7     .05       0  4587.7      .1       0
  4962.3     .16       0  4992.3     .07       0  4998.3     .16       0
  5142.4      .1       0  5429.3     .16       0  5486.5      .1       0
  5836.6     .05       0  5968.9      .1       0
#XS Ineff= 2 , 0
         3553.81 1631.19
Permanent Ineff=
       F       F
Bank Sta=4807.3,5042.6
XS Rating Curve= 0 ,0
Exp/Cntr=0.3,0.1

Type RM Length L Ch R = 1 ,36644   ,750,750,750
BEGIN DESCRIPTION:
PALO ALTO CREEK 55.0
END DESCRIPTION:
XS GIS Cut Line= 3
       2776376.8     10078011.47      2776571.23     10076678.18
      2776960.14     10075962.86
#Sta/Elev= 30
  3522.3 1647.69  3606.7 1648.33  3701.9 1646.92  3833.3 1641.67    3903  1635.9
    3977 1632.71  4227.4 1625.89  4409.3 1629.01  4865.1 1628.13  4915.4  1624.3
  4975.3 1616.33  4988.6 1608.06  4999.8 1606.98  5002.6 1606.48  5005.8 1606.98
    5019 1608.83  5034.1 1607.64  5056.9 1611.59  5062.7 1613.83    5091 1614.11
  5128.2 1612.45  5150.1 1615.69  5197.9 1618.61  5226.1 1620.02  5335.3 1633.73
    5387 1637.66  5480.3 1641.62    5647 1645.02  5658.5 1644.95  5683.9 1644.41
#Mann= 11 ,-1 , 0
  3522.3      .1       0  3606.7     .05       0    3903      .1       0
    3977     .05       0  4865.1      .1       0  4999.8     .07       0
  5005.8      .1       0  5197.9     .16       0  5480.3     .05       0
    5647      .1       0  5658.5     .05       0
#XS Ineff= 2 , 0
         4414.78 1628.97
Permanent Ineff=
       F       F
Bank Sta=4975.3,5062.7
XS Rating Curve= 0 ,0
Exp/Cntr=0.3,0.1

Type RM Length L Ch R = 1 ,35894   ,561,561,561
BEGIN DESCRIPTION:
PALO ALTO CREEK 53.0
END DESCRIPTION:
XS GIS Cut Line= 4
      2777161.51     10077657.39      2777251.79     10076969.84
      2777369.85     10076699.01      2777244.85     10076358.74
#Sta/Elev= 30
  4237.2 1633.56  4301.4 1633.89  4403.9 1628.99    4559 1625.59  4704.8 1625.54
  4716.5 1623.99  4765.4 1622.14  4791.4 1619.89    4869 1613.27  4906.6 1612.05
  4930.7 1609.58  4933.4 1608.25  4948.2  1606.3  4962.2 1605.26  4980.2 1605.96
  5011.5  1603.1  5014.3  1602.6  5017.5  1603.1  5024.6  1606.9  5032.5 1612.89
  5055.9 1616.15  5084.8 1623.07  5108.2 1626.13    5218 1626.45  5351.7 1627.27
  5446.8    1629  5519.4 1631.97  5540.7 1635.48  5553.2 1635.94  5588.6 1635.76
#Mann= 9 ,-1 , 0
  4237.2      .1       0  4403.9     .05       0  4791.4      .1       0
  5011.5     .07       0  5017.5      .1       0    5218     .05       0
  5351.7      .1       0  5446.8     .05       0  5553.2      .1       0
Bank Sta=4906.6,5032.5
XS Rating Curve= 0 ,0
Exp/Cntr=0.3,0.1

Type RM Length L Ch R = 1 ,35333   ,839,839,839
BEGIN DESCRIPTION:
PALO ALTO CREEK 52.0
END DESCRIPTION:
XS GIS Cut Line= 4
      2777407.38     10077711.44      2777778.94     10077357.24
      2777633.11     10076541.27      2777285.89     10076124.61
#Sta/Elev= 30
  4319.4 1630.29  4367.2  1628.4  4465.8 1625.74    4637 1623.48  4887.1 1622.61
  4921.7 1619.43  4937.9 1620.62    4948 1619.91  4958.2 1613.47  4968.4 1606.71
  4975.5 1603.33  4998.6 1600.86  5034.4    1603  5049.6 1605.82  5059.8 1606.04
  5080.1 1604.58  5088.2  1605.2  5110.6 1609.37    5141 1612.03  5215.7 1617.42
  5262.7  1618.8  5293.4 1619.56  5372.5 1623.61  5452.4 1624.05  5761.7 1625.06
  5813.9 1625.49    5883 1627.35  5968.9 1632.25  6160.3 1640.78    6204 1641.36
#Mann= 10 ,-1 , 0
  4319.4     .05       0  4367.2      .1       0  4465.8     .05       0
  4958.2    .035       0    5141      .1       0  5215.7     .05       0
  5262.7      .1       0  5452.4     .05       0  5761.7      .1       0
  5813.9     .05       0
Bank Sta=4958.2,5141
XS Rating Curve= 0 ,0
Exp/Cntr=0.3,0.1

Type RM Length L Ch R = 1 ,34494   ,370,370,370
BEGIN DESCRIPTION:
PALO ALTO CREEK 51.0
END DESCRIPTION:
XS GIS Cut Line= 4
      2778570.61     10078471.83      2778692.13     10077985.71
      2778313.66     10077176.68      2778362.27     10075860.74
#Sta/Elev= 30
  3094.3 1650.26  3307.9 1646.83  3395.6 1647.84  3608.6 1641.72  3665.9 1637.55
  3906.7 1620.47  3917.4  1617.9  3928.8 1610.39  3945.8    1604  4019.8 1598.25
  4065.5  1599.2  4082.8 1603.51  4193.7 1617.63  4278.2 1619.02  4571.6 1620.63
  4721.7 1619.52  4745.7 1617.37  4831.7 1609.49  4901.8 1607.88  5001.6  1596.6
  5025.9 1603.49  5031.9 1608.07  5041.9 1612.97  5061.9 1617.39    5162 1624.53
  5354.9 1628.51    5437 1628.46  5508.4 1629.41    5620  1631.7  5805.4 1634.81
#Mann= 10 ,-1 , 0
  3094.3     .05       0  3665.9      .1       0  4278.2     .05       0
  4745.7      .1       0  4901.8     .07       0  5031.9      .1       0
  5354.9     .05       0    5437      .1       0  5508.4     .05       0
    5620      .1       0
#XS Ineff= 2 , 0
         4515.81 1620.61
Permanent Ineff=
       F       F
Bank Sta=4901.8,5031.9
XS Rating Curve= 0 ,0
Exp/Cntr=0.3,0.1

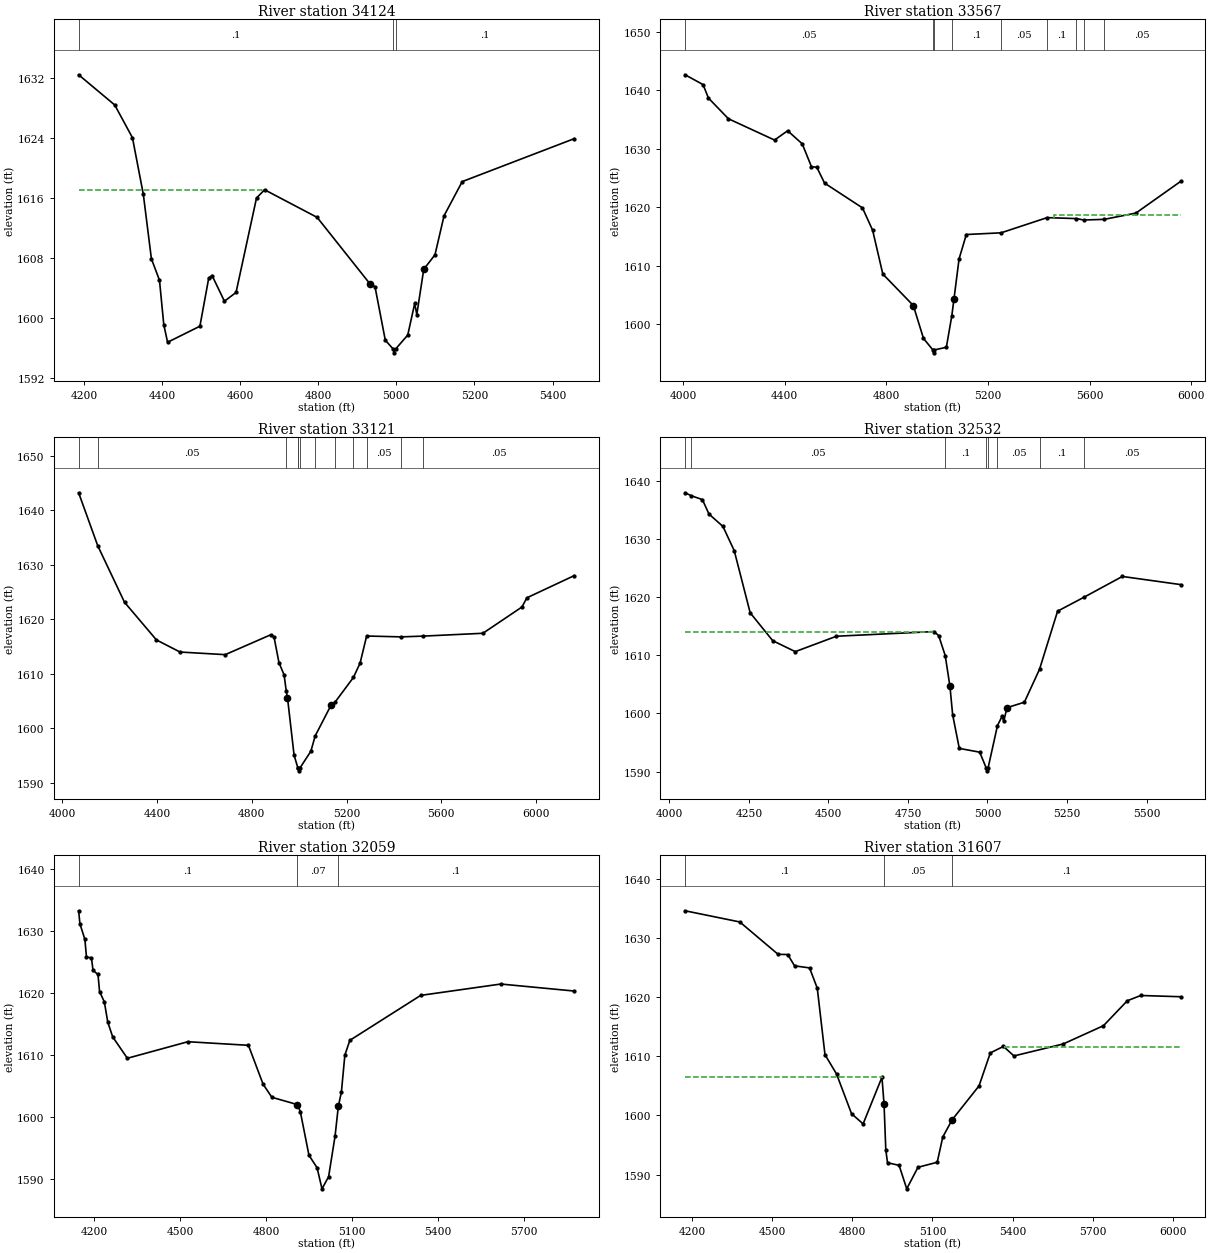
Type RM Length L Ch R = 1 ,34124   ,557,557,557
BEGIN DESCRIPTION:
PALO ALTO CREEK 50.0
END DESCRIPTION:
XS GIS Cut Line= 3
      2778868.47     10077603.76      2778668.47     10076853.73
      2778468.46     10076403.71
#Sta/Elev= 30
  4186.6 1632.38  4279.1 1628.35  4324.4 1623.99  4352.2 1616.45  4372.9 1607.85
  4393.6 1604.99  4404.6 1599.07  4414.3 1596.72  4497.1 1598.86  4519.7 1605.28
  4528.2 1605.62  4559.9 1602.19  4589.6 1603.36    4642 1615.95  4662.7 1617.05
  4797.2 1613.37  4931.8 1604.55  4945.4 1604.12  4971.7    1597    4992 1595.81
  4994.7 1595.31    4998 1595.81  5029.2 1597.68    5047 1601.89  5052.4 1600.42
  5070.2 1606.45  5098.9 1608.38  5122.2 1613.59  5168.7 1618.14  5455.3 1623.86
#Mann= 3 ,-1 , 0
  4186.6      .1       0    4992     .07       0    4998      .1       0
#XS Ineff= 2 , 0
         4656.83 1617.06
Permanent Ineff=
       F       F
Bank Sta=4931.8,5070.2
XS Rating Curve= 0 ,0
Exp/Cntr=0.3,0.1

Type RM Length L Ch R = 1 ,33567   ,446,446,446
BEGIN DESCRIPTION:
PALO ALTO CREEK 49.0
END DESCRIPTION:
XS GIS Cut Line= 4
      2778773.84      10077926.1      2779131.89     10077370.59
      2779129.72     10076921.37      2778695.69     10076203.04
#Sta/Elev= 30
    4008 1642.61  4078.7 1640.93  4099.8 1638.63  4178.4 1635.09  4359.9 1631.45
  4411.4 1633.04  4468.8  1630.8  4505.1 1626.89  4526.2  1626.8  4556.6 1624.09
  4705.8 1619.85  4745.8 1616.02  4785.8 1608.54  4905.8 1603.16  4945.8 1597.53
  4982.8 1595.57  4985.5 1595.07  4988.8 1595.57  5035.8 1596.02  5057.2 1601.41
  5065.8  1604.3  5085.8 1611.14  5114.4  1615.3  5251.1 1615.59  5432.3 1618.19
  5547.7 1618.02    5576 1617.78  5656.3 1617.89  5781.3 1618.96  5957.4 1624.38
#Mann= 9 ,-1 , 0
    4008     .05       0  4982.8    .035       0  4988.8     .05       0
  5057.2      .1       0  5251.1     .05       0  5432.3      .1       0
  5547.7     .05       0    5576      .1       0  5656.3     .05       0
#XS Ineff= 2 , 0
                          5460.7         1618.72
Permanent Ineff=
       F       F
Bank Sta=4905.8,5065.8
XS Rating Curve= 0 ,0
Exp/Cntr=0.3,0.1

Type RM Length L Ch R = 1 ,33121   ,589,589,589
BEGIN DESCRIPTION:
PALO ALTO CREEK 48.0
END DESCRIPTION:
XS GIS Cut Line= 3
      2780220.14     10077495.48      2779393.72     10076766.29
       2778838.8     10075947.79
#Sta/Elev= 30
  4069.6 1643.19  4150.1 1633.49  4263.2 1623.11  4397.9  1616.2  4497.5 1613.98
  4688.2  1613.5  4879.8 1617.14    4894 1616.75  4914.9 1612.05  4936.7 1609.77
  4945.8 1606.78  4950.9 1605.61  4978.7 1595.07  4994.8  1592.7  4997.2 1592.69
    5000 1592.19  5003.2 1592.69  5049.6 1595.79  5067.7 1598.59  5134.9 1604.25
  5151.1 1604.76  5229.3 1609.33  5257.3 1611.96  5284.9 1616.92    5430 1616.76
  5522.8  1616.9  5775.5 1617.42  5940.2 1622.24  5961.2 1623.93  6160.6 1627.99
#Mann= 12 ,-1 , 0
  4069.6      .1       0  4150.1     .05       0  4945.8      .1       0
  4994.8     .05       0  4997.2    .035       0  5003.2     .05       0
  5067.7      .1       0  5151.1     .05       0  5229.3      .1       0
  5284.9     .05       0    5430      .1       0  5522.8     .05       0
#XS Ineff= 2 , 0
         4879.69 1616.91 5290.81         1616.91
Permanent Ineff=
       F       F
Bank Sta=4950.9,5134.9
XS Rating Curve= 0 ,0
Exp/Cntr=0.3,0.1

Type RM Length L Ch R = 1 ,32532   ,473,473,473
BEGIN DESCRIPTION:
PALO ALTO CREEK 47.0
END DESCRIPTION:
XS GIS Cut Line= 3
      2780407.59     10077189.88      2779872.88     10076467.67
      2779608.99      10075863.5
#Sta/Elev= 30
  4049.4 1637.95  4069.4 1637.43  4103.7 1636.78  4124.5 1634.29  4168.4 1632.16
  4203.9 1627.99    4254 1617.31  4324.9 1612.51  4395.8 1610.63  4525.3 1613.28
    4832 1614.08  4846.7 1613.38  4867.2 1609.95  4882.1 1604.64  4890.5 1599.79
  4911.4 1593.99  4975.6 1593.34    4996 1590.63  4998.7 1590.13    5002 1590.63
  5031.4 1597.91  5045.8 1599.49  5051.2 1598.67  5061.4 1600.99    5116 1601.93
  5163.6 1607.59  5220.5 1617.59  5303.6 1619.99  5424.1 1623.56  5607.3 1622.16
#Mann= 8 ,-1 , 0
  4049.4      .1       0  4069.4     .05       0  4867.2      .1       0
    4996     .07       0    5002      .1       0  5031.4     .05       0
  5163.6      .1       0  5303.6     .05       0
#XS Ineff= 2 , 0
         4835.79 1614.01
Permanent Ineff=
       F       F
Bank Sta=4882.1,5061.4
XS Rating Curve= 0 ,0
Exp/Cntr=0.3,0.1

Type RM Length L Ch R = 1 ,32059   ,452,452,452
BEGIN DESCRIPTION:
PALO ALTO CREEK 46.0
END DESCRIPTION:
XS GIS Cut Line= 3
      2780574.28     10076905.19      2780143.72     10075981.56
      2779561.94     10075572.93
#Sta/Elev= 30
    4146 1633.29  4150.5 1631.19  4167.9 1628.67  4173.4 1625.81  4190.7 1625.72
  4196.3 1623.67  4213.6 1623.02  4219.1 1620.27  4235.9 1618.58  4247.5 1615.38
  4264.9 1612.96  4316.1 1609.51  4527.4 1612.18  4738.8  1611.6    4790 1605.33
  4820.6 1603.22  4909.9 1602.04  4919.9 1600.91  4950.1 1593.88  4978.5 1591.85
  4995.6 1588.46  5018.7 1590.42  5041.3 1596.98  5052.6 1601.75  5063.4 1604.08
  5075.4 1610.01  5092.8  1612.4  5340.2 1619.65  5619.9 1621.48    5876 1620.35
#Mann= 3 , 0 , 0
    4146      .1       0  4909.9     .07       0  5052.6      .1       0
#XS Ineff= 2 , 0
         4527.84 1612.16
Permanent Ineff=
       F       F
Bank Sta=4909.9,5052.6
XS Rating Curve= 0 ,0
Exp/Cntr=0.3,0.1

Type RM Length L Ch R = 1 ,31607   ,581,581,581
BEGIN DESCRIPTION:
PALO ALTO CREEK 45.0
END DESCRIPTION:
XS GIS Cut Line= 4
      2781338.84     10076376.87      2780949.92     10076237.97
      2780338.81     10075758.81      2779742.54     10075460.67
#Sta/Elev= 30
  4173.5 1634.58  4378.5 1632.69  4521.9 1627.22    4558 1627.19  4583.5 1625.28
  4639.7 1624.93  4668.6  1621.5  4697.5 1610.27  4740.8 1607.01    4797  1600.3
  4840.3 1598.58  4910.9 1606.46  4918.7 1601.92  4925.3  1594.2  4931.7 1592.02
  4975.1 1591.58  5003.7 1587.61  5045.8 1591.25  5117.9  1592.1  5138.7 1596.36
    5174 1599.29  5274.5    1605  5316.8 1610.57  5366.1 1611.67  5405.2 1610.06
  5589.7 1612.08  5740.7 1615.17  5830.1 1619.39  5880.4 1620.27  6029.7 1620.06
#Mann= 3 , 0 , 0
  4173.5      .1       0  4918.7     .05       0    5174      .1       0
#XS Ineff= 2 , 0
         4909.92 1606.42  5367.9          1611.6
Permanent Ineff=
       F       F
Bank Sta=4918.7,5174
XS Rating Curve= 0 ,0
Exp/Cntr=0.3,0.1

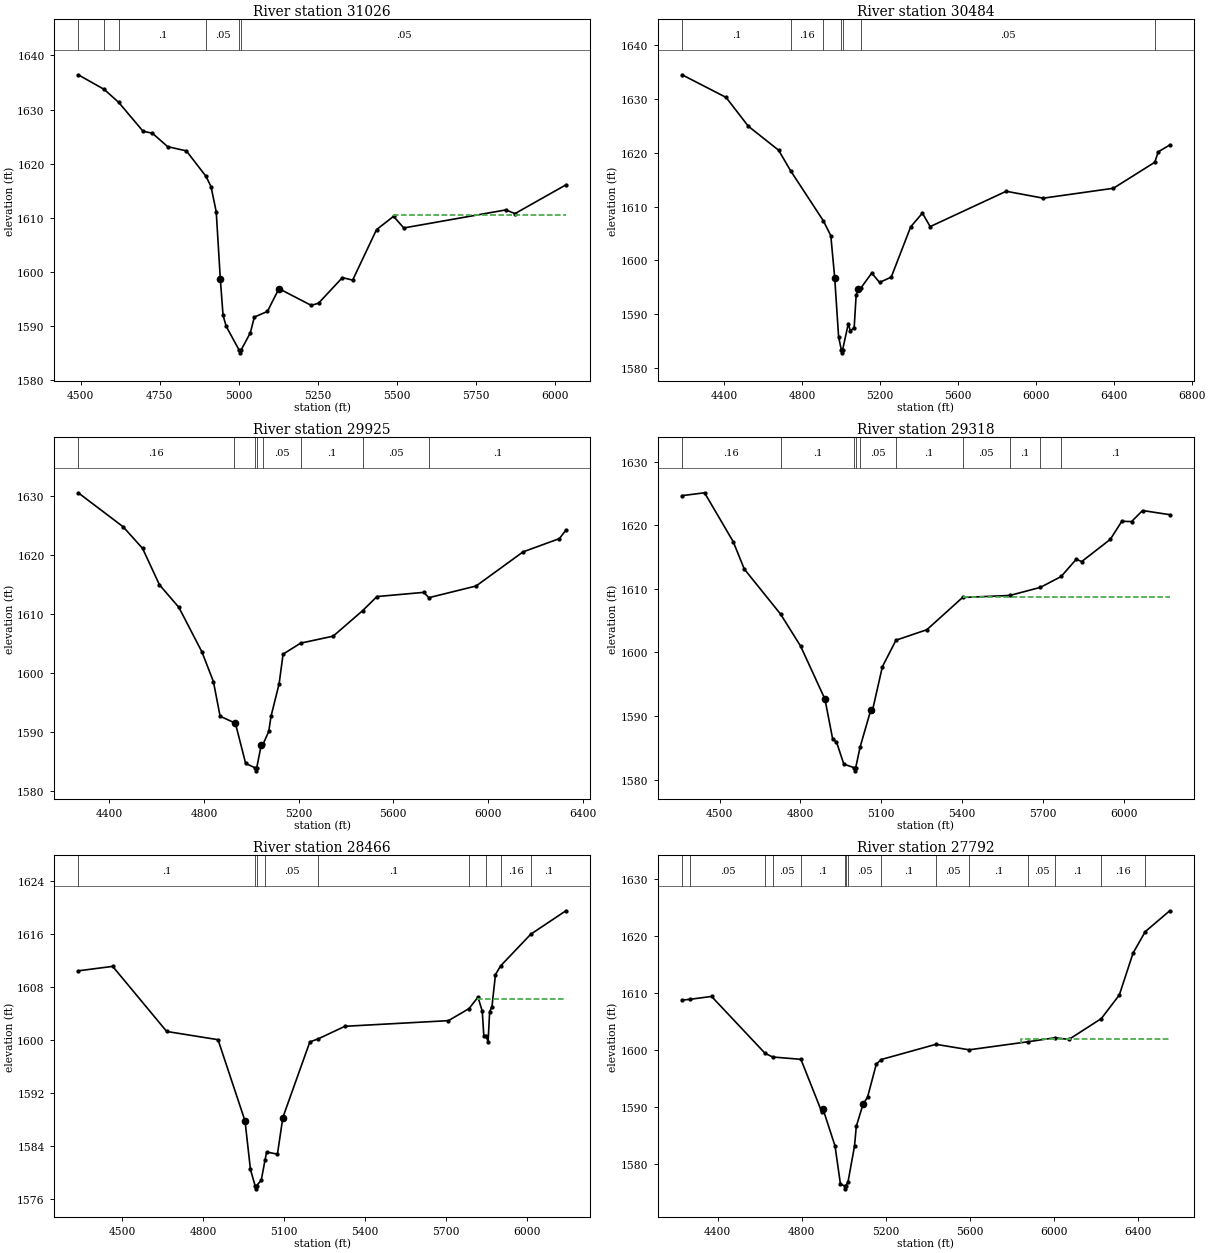
Type RM Length L Ch R = 1 ,31026   ,542,542,542
BEGIN DESCRIPTION:
PALO ALTO CREEK 44.0
END DESCRIPTION:
XS GIS Cut Line= 2
       2781463.2     10075745.47      2780033.02     10075169.23
#Sta/Elev= 30
    4492 1636.43  4574.3 1633.72  4619.8 1631.34  4696.9    1626  4726.5 1625.63
  4774.8 1623.15  4833.9 1622.37  4895.9 1617.67  4911.8 1615.78  4928.3 1611.12
  4941.3 1598.65  4949.9 1591.98  4960.1 1589.93  5000.8 1585.56  5003.6 1585.06
  5006.8 1585.56  5036.2 1588.76  5048.8 1591.67  5090.1  1592.7  5126.6 1596.92
  5228.7 1593.83  5251.8 1594.23  5327.3 1598.96  5359.6 1598.49  5435.1 1607.81
    5489 1610.28  5521.3 1608.13  5843.6 1611.46  5873.2 1610.79  6033.9 1616.09
#Mann= 6 ,-1 , 0
    4492      .1       0  4574.3     .05       0  4619.8      .1       0
  4895.9     .05       0  5000.8    .035       0  5006.8     .05       0
#XS Ineff= 2 , 0
                         5489.36         1610.45
Permanent Ineff=
       F       F
Bank Sta=4941.3,5126.6
XS Rating Curve= 0 ,0
Exp/Cntr=0.3,0.1

Type RM Length L Ch R = 1 ,30484   ,559,559,559
BEGIN DESCRIPTION:
PALO ALTO CREEK 43.0
END DESCRIPTION:
XS GIS Cut Line= 3
      2781886.77     10075335.73      2781268.72     10075044.06
      2779449.26     10074974.62
#Sta/Elev= 30
  4183.2 1634.51  4409.2  1630.3  4523.1 1624.95  4678.9 1620.48  4740.8 1616.64
  4908.3 1607.37  4946.9 1604.59  4966.9 1596.77    4987 1585.78  5001.2 1583.29
  5003.9 1582.79  5007.2 1583.29    5037 1588.24    5047 1586.86    5067  1587.5
    5077  1593.5    5087 1594.63  5101.1 1594.84  5157.1 1597.63  5197.1 1595.89
  5257.2 1596.87  5357.2 1606.23  5417.3 1608.77  5457.3 1606.27  5847.6 1612.84
  6037.7 1611.56    6398  1613.4  6610.7 1618.24  6628.2 1620.17  6687.4 1621.45
#Mann= 7 ,-1 , 0
  4183.2      .1       0  4740.8     .16       0  4908.3      .1       0
  5001.2     .07       0  5007.2      .1       0  5101.1     .05       0
  6610.7      .1       0
#XS Ineff= 2 , 0
                         5418.38          1608.4
Permanent Ineff=
       F       F
Bank Sta=4966.9,5087
XS Rating Curve= 0 ,0
Exp/Cntr=0.3,0.1

Type RM Length L Ch R = 1 ,29925   ,607,607,607
BEGIN DESCRIPTION:
PALO ALTO CREEK 42.0
END DESCRIPTION:
XS GIS Cut Line= 2
      2781893.74     10074641.29      2779881.65     10074197.24
#Sta/Elev= 30
  4268.8 1630.55  4458.5 1624.79  4540.5 1621.13  4612.1 1614.94  4693.6 1611.15
  4791.2  1603.6    4840 1598.54  4868.2 1592.68  4927.4 1591.59  4932.5 1591.54
  4976.2 1584.67  5016.9 1583.92  5019.6 1583.42  5022.9 1583.92  5042.2 1587.83
    5050 1587.96  5073.8  1590.1  5083.2 1592.64  5117.5 1598.16  5134.4  1603.2
  5208.3 1605.06  5346.1 1606.25  5470.9 1610.59  5531.1 1612.96  5728.4 1613.67
  5750.5 1612.77  5949.9 1614.75  6148.2 1620.53  6301.8 1622.78  6329.3 1624.22
#Mann= 8 ,-1 , 0
  4268.8     .16       0  4927.4      .1       0  5016.9     .07       0
  5022.9      .1       0    5050     .05       0  5208.3      .1       0
  5470.9     .05       0  5750.5      .1       0
Bank Sta=4932.5,5042.2
XS Rating Curve= 0 ,0
Exp/Cntr=0.3,0.1

Type RM Length L Ch R = 1 ,29318   ,852,852,852
BEGIN DESCRIPTION:
PALO ALTO CREEK 41.0
END DESCRIPTION:
XS GIS Cut Line= 2
      2781963.18     10074057.96      2780200.32     10073648.47
#Sta/Elev= 30
  4360.9 1624.65  4444.3  1625.1  4550.5 1617.43  4591.6 1613.12  4726.5 1606.02
  4800.8 1600.99  4891.1 1592.66  4920.1 1586.32  4933.8 1585.95  4961.2 1582.44
  4999.3 1581.89    5002 1581.39  5005.3 1581.89  5021.6 1585.13  5061.7 1591.02
  5066.8 1590.76  5104.3 1597.76  5154.8 1601.93  5269.2 1603.57  5401.9 1608.64
  5577.4 1608.96  5690.6 1610.23  5767.8 1611.94  5823.5 1614.64  5844.1 1614.29
  5950.2 1617.78  5992.9 1620.62  6028.9 1620.57  6069.9 1622.31  6170.7 1621.66
#Mann= 10 ,-1 , 0
  4360.9     .16       0  4726.5      .1       0  4999.3     .07       0
  5005.3      .1       0  5021.6     .05       0  5154.8      .1       0
  5401.9     .05       0  5577.4      .1       0  5690.6     .05       0
  5767.8      .1       0
#XS Ineff= 2 , 0
                         5402.66         1608.67
Permanent Ineff=
       F       F
Bank Sta=4891.1,5061.7
XS Rating Curve= 0 ,0
Exp/Cntr=0.3,0.1

Type RM Length L Ch R = 1 ,28466   ,674,674,674
BEGIN DESCRIPTION:
PALO ALTO CREEK 40.0
END DESCRIPTION:
XS GIS Cut Line= 3
      2782115.96     10073099.62      2780997.88     10073099.62
      2780400.69     10073439.88
#Sta/Elev= 30
  4337.8 1610.44  4465.3 1611.11  4665.3  1601.3  4855.3 1600.06  4955.3 1587.81
  4975.3 1580.52  4992.3 1578.08    4995 1577.58  4998.3 1578.08  5015.3 1578.86
  5029.6 1581.98  5035.3 1583.13  5075.3 1582.81  5095.3 1588.33  5195.3 1599.73
  5224.2 1600.15  5325.3 1602.08  5708.4 1602.93  5784.7 1604.75  5817.7 1606.47
  5833.6 1604.36  5839.3 1600.65  5847.2 1600.69  5855.2 1599.72  5860.9 1604.28
  5869.5 1605.05  5882.5 1609.87  5901.2 1611.17  6013.2 1615.96  6143.2 1619.49
#Mann= 9 ,-1 , 0
  4337.8      .1       0  4992.3     .07       0  4998.3      .1       0
  5029.6     .05       0  5224.2      .1       0  5784.7     .05       0
  5847.2      .1       0  5901.2     .16       0  6013.2      .1       0
#XS Ineff= 2 , 0
                         5812.27         1606.21
Permanent Ineff=
       F       F
Bank Sta=4955.3,5095.3
XS Rating Curve= 0 ,0
Exp/Cntr=0.3,0.1

Type RM Length L Ch R = 1 ,27792   ,372,372,372
BEGIN DESCRIPTION:
PALO ALTO CREEK 38.0
END DESCRIPTION:
XS GIS Cut Line= 3
      2782240.92     10072689.89      2781213.16     10072328.79
       2780034.9      10072689.2
#Sta/Elev= 30
  4231.3 1608.73  4269.1 1608.88  4371.7 1609.38  4626.8  1599.4  4662.7 1598.77
    4797 1598.36  4897.4 1589.05  4902.7 1589.59  4959.4 1583.18  4985.1 1576.53
  5004.6 1576.17  5007.4 1575.67  5010.6 1576.17  5021.4 1576.92  5052.3 1583.18
  5060.6 1586.61  5092.4 1590.46  5114.3 1591.74    5156 1597.53  5179.5 1598.33
  5439.6 1600.99  5597.8 1600.03  5877.9 1601.44  6006.8 1602.14  6072.9 1601.85
    6227  1605.5  6312.8 1609.64  6378.4 1616.99  6436.2 1620.73  6552.8 1624.39
#Mann= 15 ,-1 , 0
  4231.3      .1       0  4269.1     .05       0  4626.8      .1       0
  4662.7     .05       0    4797      .1       0  5004.6     .07       0
  5010.6      .1       0  5021.4     .05       0  5179.5      .1       0
  5439.6     .05       0  5597.8      .1       0  5877.9     .05       0
  6006.8      .1       0    6227     .16       0  6436.2     .05       0
#XS Ineff= 2 , 0
                         5844.62         1601.85
Permanent Ineff=
       F       F
Bank Sta=4902.7,5092.4
XS Rating Curve= 0 ,0
Exp/Cntr=0.3,0.1

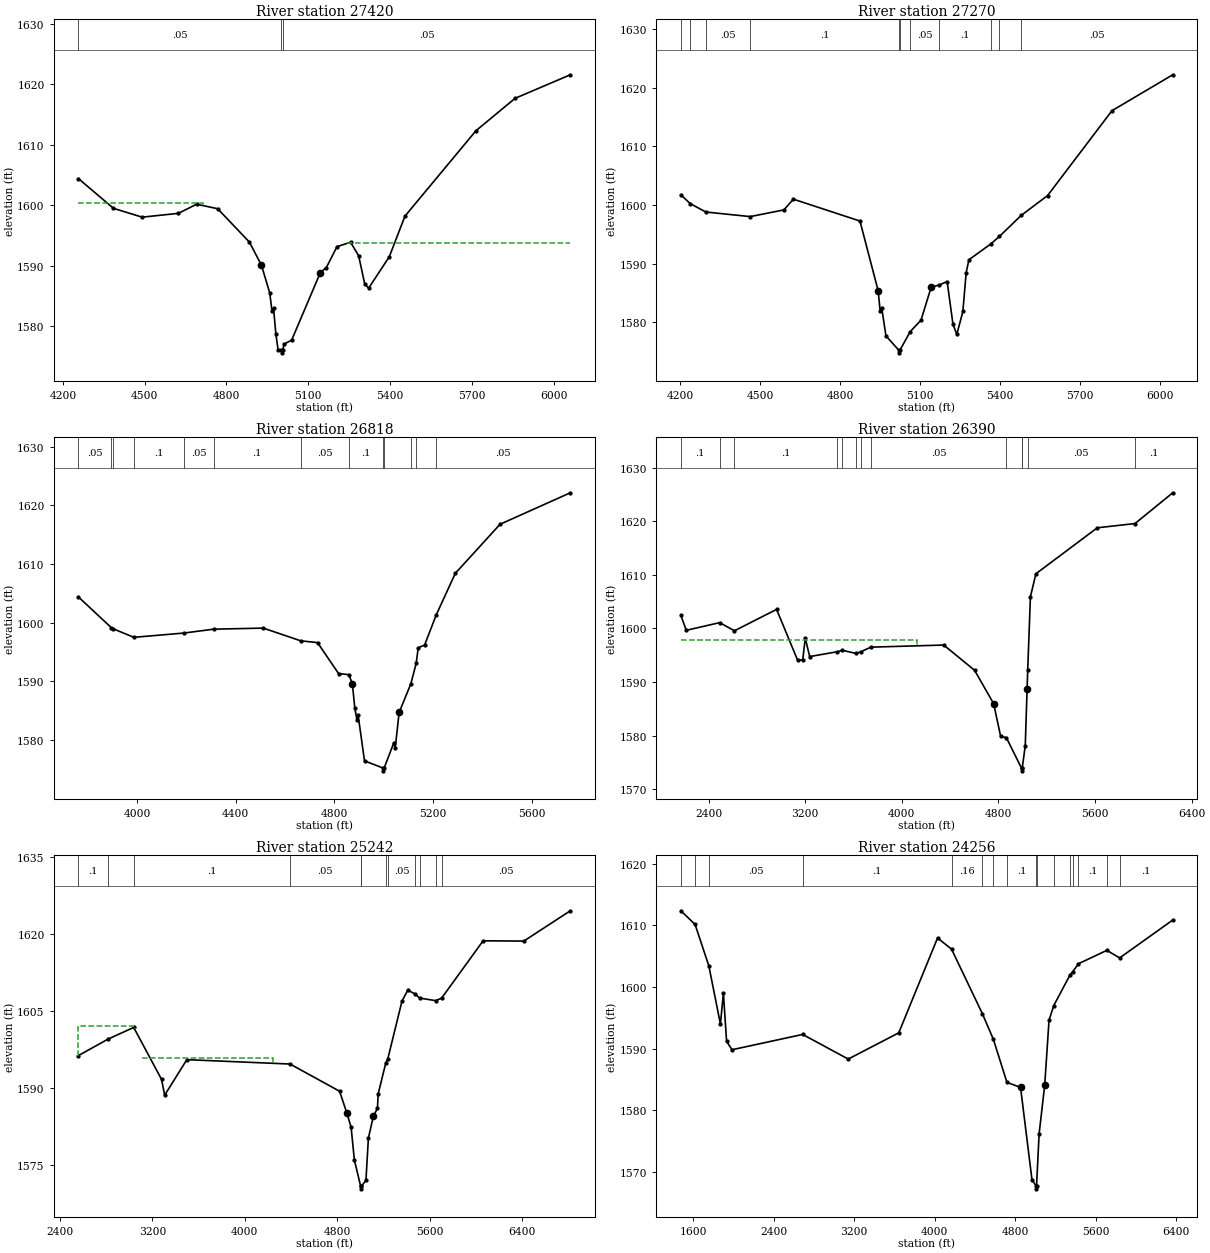
Type RM Length L Ch R = 1 ,27420   ,150,150,150
BEGIN DESCRIPTION:
PALO ALTO CREEK 39.0
END DESCRIPTION:
XS GIS Cut Line= 2
      2782192.31     10072405.17      2780588.16     10071578.78
#Sta/Elev= 30
  4256.9 1604.39  4385.4 1599.47  4490.6 1598.01  4623.6 1598.64  4690.1 1600.15
  4767.4 1599.41    4884 1593.89  4928.3 1590.06  4958.7 1585.47    4967 1582.47
  4972.6 1582.97  4981.2 1578.65  4989.2  1576.1  5000.7 1576.06  5003.4 1575.56
  5006.7 1576.06  5011.3 1577.01  5039.1 1577.66  5144.3 1588.84  5166.5 1589.68
  5205.2 1593.12  5255.2 1593.87  5284.9 1591.62  5307.4 1586.91  5321.7 1586.28
  5397.4 1591.47  5454.7 1598.18    5715  1612.3  5858.6 1617.67  6061.4 1621.57
#Mann= 3 ,-1 , 0
  4256.9     .05       0  5000.7     .04       0  5006.7     .05       0
#XS Ineff= 2 , 0
         4713.42 1600.29 5242.44          1593.7
Permanent Ineff=
       F       F
Bank Sta=4928.3,5144.3
XS Rating Curve= 0 ,0
Exp/Cntr=0.3,0.1

Type RM Length L Ch R = 1 ,27270   ,452,452,452
BEGIN DESCRIPTION:
Mapping XS f68fc835
END DESCRIPTION:
XS GIS Cut Line= 2
      2782220.12     10072294.07      2780595.12     10071419.07
#Sta/Elev= 30
  4202.1 1601.74  4236.8 1600.25  4295.8 1598.81  4462.3 1598.03  4588.7 1599.17
  4624.2    1601  4874.1 1597.27  4942.2 1585.42  4949.7 1582.03  4955.4 1582.54
  4971.6 1577.71  5018.7 1575.32  5021.5 1574.82  5024.7 1575.32  5062.5 1578.43
  5103.1 1580.38  5141.2    1586    5172 1586.38  5201.2 1586.97  5223.1 1579.67
  5237.5 1577.96  5260.2 1581.87  5272.6 1588.49  5282.9 1590.68  5364.4 1593.35
  5397.2 1594.65  5478.8 1598.22  5578.2 1601.62  5819.4 1616.06  6047.7 1622.19
#Mann= 11 ,-1 , 0
  4202.1     .05       0  4236.8      .1       0  4295.8     .05       0
  4462.3      .1       0  5018.7     .07       0  5024.7      .1       0
  5062.5     .05       0    5172      .1       0  5364.4     .05       0
  5397.2      .1       0  5478.8     .05       0
Bank Sta=4942.2,5141.2
XS Rating Curve= 0 ,0
Exp/Cntr=0.3,0.1

Type RM Length L Ch R = 1 ,26818   ,428,428,428
BEGIN DESCRIPTION:
Mapping XS a0b29110
END DESCRIPTION:
XS GIS Cut Line= 3
      2782338.15     10072273.22      2781511.77     10071537.12
      2780672.47     10071245.79
#Sta/Elev= 30
  3762.3  1604.4    3895 1599.19  3900.6 1599.02    3987 1597.52  4190.7 1598.25
  4310.5 1598.91  4512.1 1599.09  4664.2 1596.92    4732 1596.62  4817.3 1591.35
  4859.5 1591.15  4873.4 1589.58  4883.1 1585.52  4891.5  1583.5  4896.7 1584.24
  4922.6 1576.46  4996.5 1575.26  4999.2 1574.76  5002.5 1575.26  5041.8 1579.58
  5047.1 1578.62    5063 1584.71  5110.3 1589.57  5132.1 1593.06  5140.5 1595.75
  5166.3 1596.19  5213.2 1601.31  5290.8 1608.42  5472.3 1616.79  5757.4 1622.16
#Mann= 13 ,-1 , 0
  3762.3     .05       0    3895      .1       0  3900.6     .05       0
    3987      .1       0  4190.7     .05       0  4310.5      .1       0
  4664.2     .05       0  4859.5      .1       0  4996.5     .07       0
  5002.5      .1       0  5110.3     .05       0  5132.1      .1       0
  5213.2     .05       0
Bank Sta=4873.4,5063
XS Rating Curve= 0 ,0
Exp/Cntr=0.3,0.1

Type RM Length L Ch R = 1 ,26390   ,1148,1148,1148
BEGIN DESCRIPTION:
PALO ALTO CREEK 36.0
END DESCRIPTION:
XS GIS Cut Line= 4
      2783580.58     10072757.57      2783434.76     10072377.37
      2781252.46     10071007.58      2780163.95     10070991.96
#Sta/Elev= 30
  2170.5 1602.43  2215.2 1599.66  2491.7 1601.09  2614.2 1599.57  2962.9 1603.56
  3136.8 1594.09  3179.2 1594.14  3200.4  1598.2  3236.9 1594.76  3465.2 1595.66
  3507.9 1595.93  3621.3 1595.34  3663.9 1595.69    3743 1596.52  4346.8 1596.91
  4602.4  1592.2  4760.3 1585.97    4818 1579.88  4865.1 1579.65  4990.7 1573.95
  4993.4 1573.45  4996.7 1573.95  5021.8 1578.14  5037.1 1588.76    5042 1592.21
  5064.5 1605.94  5110.2 1610.21  5618.3 1618.78  5930.3 1619.57  6242.9 1625.31
#Mann= 13 ,-1 , 0
  2170.5      .1       0  2491.7     .16       0  2614.2      .1       0
  3465.2     .05       0  3507.9      .1       0  3621.3     .05       0
  3663.9      .1       0    3743     .05       0  4865.1      .1       0
  4990.7     .07       0  4996.7      .1       0    5042     .05       0
  5930.3      .1       0
#XS Ineff= 2 , 0
         4122.13  1597.9
Permanent Ineff=
       F       F
Bank Sta=4760.3,5037.1
XS Rating Curve= 0 ,0
Exp/Cntr=0.3,0.1

Type RM Length L Ch R = 1 ,25242   ,986,986,986
BEGIN DESCRIPTION:
PALO ALTO CREEK 34.0
END DESCRIPTION:
XS GIS Cut Line= 3
      2783708.33     10072274.89      2781859.35     10069974.52
      2780626.69      10069531.8
#Sta/Elev= 30
  2558.5 1596.31  2814.7 1599.51  3037.1 1601.79  3278.3 1591.67  3305.5  1588.6
  3497.5 1595.51  4391.8 1594.66  4820.7 1589.36  4884.7 1585.04  4920.7 1582.33
  4948.7 1575.98  5003.3 1570.85    5006 1570.35  5009.3 1570.85    5049 1571.99
  5070.3 1580.23  5113.1 1584.45  5148.7 1586.03  5155.1 1588.84  5220.5 1594.83
  5237.9 1595.62  5361.5 1606.93  5411.1 1609.04  5474.2 1608.32  5513.6 1607.51
  5652.1 1607.01  5704.1 1607.48    6064 1618.66  6416.9 1618.61  6819.6 1624.51
#Mann= 12 ,-1 , 0
  2558.5      .1       0  2814.7     .05       0  3037.1      .1       0
  4391.8     .05       0  5003.3    .035       0  5009.3     .05       0
  5220.5      .1       0  5237.9     .05       0  5474.2      .1       0
  5513.6     .05       0  5652.1      .1       0  5704.1     .05       0
#XS Ineff= 2 ,-1
  2558.5 3045.79 1601.99 3107.67 4246.29 1595.86
Permanent Ineff=
       F       F
Bank Sta=4884.7,5113.1
XS Rating Curve= 0 ,0
Exp/Cntr=0.3,0.1

Type RM Length L Ch R = 1 ,24256   ,958,958,958
BEGIN DESCRIPTION:
PALO ALTO CREEK 31.0
END DESCRIPTION:
XS GIS Cut Line= 3
      2784368.05     10072795.74      2783335.05     10070200.21
      2781920.15     10068655.11
#Sta/Elev= 30
  1476.6 1612.36  1617.9 1610.14  1754.6 1603.43  1869.6 1594.01  1899.3    1599
  1930.8 1591.22  1984.6 1589.84    2687 1592.32  3140.1 1588.33  3642.1 1592.58
  4027.6 1607.95  4166.5 1606.15    4473 1595.69  4582.8 1591.51  4717.4 1584.55
  4852.6 1583.74    4966 1568.78  5005.6  1567.8  5008.3  1567.3  5011.6  1567.8
    5037 1576.19  5093.1  1584.2  5135.6 1594.63  5183.1 1597.01  5342.5 1601.91
  5370.7 1602.48  5428.2 1603.78  5710.6 1605.95  5837.4 1604.72  6365.2 1610.86
#Mann= 16 ,-1 , 0
  1476.6      .1       0  1617.9     .16       0  1754.6     .05       0
    2687      .1       0  4166.5     .16       0    4473      .1       0
  4582.8     .05       0  4717.4      .1       0  5005.6     .07       0
  5011.6      .1       0  5183.1     .05       0  5342.5      .1       0
  5370.7     .05       0  5428.2      .1       0  5710.6     .16       0
  5837.4      .1       0
#XS Ineff= 2 , 0
         4036.28 1607.24
Permanent Ineff=
       F       F
Bank Sta=4852.6,5093.1
XS Rating Curve= 0 ,0
Exp/Cntr=0.3,0.1

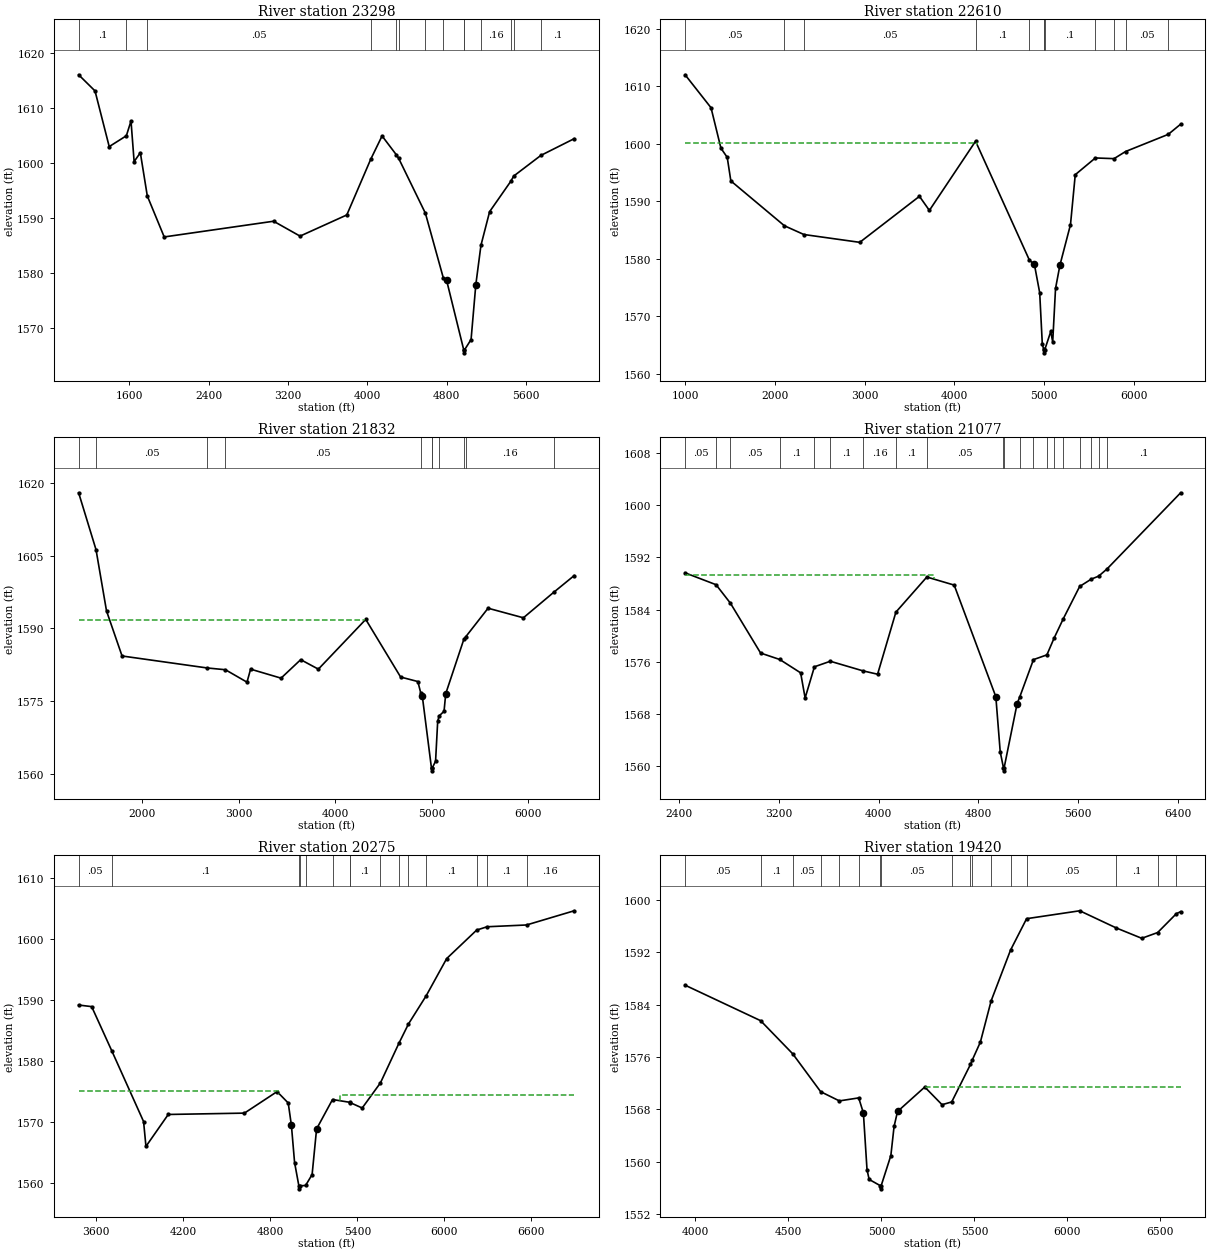
Type RM Length L Ch R = 1 ,23298   ,688,688,688
BEGIN DESCRIPTION:
PALO ALTO CREEK 30.0
END DESCRIPTION:
XS GIS Cut Line= 4
      2784871.51     10072908.54      2783968.73     10069974.52
      2783361.09     10068429.38      2783144.08     10068273.13
#Sta/Elev= 30
  1088.2 1616.02  1253.5 1613.08  1396.6 1602.95  1569.5 1604.92  1616.4 1607.61
  1647.8 1600.22  1710.5 1601.84  1780.7 1593.97  1951.2 1586.51  3054.4 1589.37
  3321.2 1586.66  3792.6 1590.51    4033 1600.61  4148.3 1604.89  4293.2 1601.44
  4315.5 1600.82  4585.2 1590.83  4766.4 1579.03  4799.5 1578.59  4972.5 1565.92
  4975.2 1565.42  4978.5 1565.92    5046 1567.84  5093.7 1577.81  5145.5 1584.98
    5233 1591.11  5446.7 1596.64    5476 1597.59  5749.2 1601.34  6085.7 1604.39
#Mann= 14 ,-1 , 0
  1088.2      .1       0  1569.5     .16       0  1780.7     .05       0
    4033      .1       0  4293.2     .16       0  4315.5      .1       0
  4585.2     .16       0  4766.4      .1       0  4972.5     .07       0
  4978.5      .1       0  5145.5     .16       0  5446.7      .1       0
    5476     .16       0  5749.2      .1       0
#XS Ineff= 2 , 0
         4141.48 1604.44
Permanent Ineff=
       F       F
Bank Sta=4799.5,5093.7
XS Rating Curve= 0 ,0
Exp/Cntr=0.3,0.1

Type RM Length L Ch R = 1 ,22610   ,778,778,778
BEGIN DESCRIPTION:
PALO ALTO CREEK 29.0
END DESCRIPTION:
XS GIS Cut Line= 4
       2785861.1     10072761.02      2785748.24     10071606.46
      2783994.77     10068568.27      2783222.86       10068204.
#Sta/Elev= 30
  1000.9 1611.97  1289.8 1606.24  1400.1 1599.21  1470.4 1597.61  1510.6 1593.52
  2107.6 1585.72  2324.7  1584.2  2947.1 1582.84    3612 1590.84  3722.8 1588.39
  4237.3 1600.42  4837.5 1579.74    4893    1579  4951.9 1574.08  4981.3 1565.08
  4996.1  1564.3  5001.4 1564.13  5004.2 1563.63  5007.4 1564.13  5075.4 1567.34
  5096.9 1565.52  5128.5 1574.83  5177.6 1578.89  5295.1 1585.92  5348.2  1594.6
  5572.3 1597.51  5780.5 1597.39  5908.9 1598.63  6384.2 1601.61  6522.4 1603.38
#Mann= 12 ,-1 , 0
  1000.9     .05       0  2107.6      .1       0  2324.7     .05       0
  4237.3      .1       0  4837.5     .16       0  4996.1      .1       0
  5001.4     .07       0  5007.4      .1       0  5572.3     .05       0
  5780.5      .1       0  5908.9     .05       0  6384.2      .1       0
#XS Ineff= 2 , 0
         4253.93 1600.16
Permanent Ineff=
       F       F
Bank Sta=4893,5177.6
XS Rating Curve= 0 ,0
Exp/Cntr=0.3,0.1

Type RM Length L Ch R = 1 ,21832   ,755,755,755
BEGIN DESCRIPTION:
PALO ALTO CREEK 28.0
END DESCRIPTION:
XS GIS Cut Line= 4
      2786815.93     10072023.09      2785270.81      10069358.2
      2784767.34     10068238.41      2784255.71     10067588.03
#Sta/Elev= 30
  1339.5    1618  1519.8 1606.24  1628.5 1593.59  1789.6 1584.28  2673.5  1581.8
  2860.8 1581.44  3084.4 1578.87  3121.7 1581.56  3437.3  1579.7    3641 1583.52
    3824 1581.56  4315.1 1591.84  4676.6 1579.93  4855.2    1579  4885.9 1576.58
  4901.5 1575.96  4996.6 1561.05  4999.3 1560.55  5002.6 1561.05  5038.8 1562.56
  5060.7 1570.77  5075.4 1571.89  5126.5 1572.85    5144 1576.49  5333.5 1587.83
  5349.2 1588.19  5582.8 1594.15  5948.9 1592.17  6262.7 1597.43  6475.2 1600.89
#Mann= 11 ,-1 , 0
  1339.5     .16       0  1519.8     .05       0  2673.5      .1       0
  2860.8     .05       0  4885.9      .1       0  4996.6     .07       0
  5002.6      .1       0  5075.4     .16       0  5333.5      .1       0
  5349.2     .16       0  6262.7      .1       0
#XS Ineff= 2 , 0
         4304.72 1591.77
Permanent Ineff=
       F       F
Bank Sta=4901.5,5144
XS Rating Curve= 0 ,0
Exp/Cntr=0.3,0.1

Type RM Length L Ch R = 1 ,21077   ,802,802,802
BEGIN DESCRIPTION:
PALO ALTO CREEK 26.0
END DESCRIPTION:
XS GIS Cut Line= 3
      2787779.48     10070035.27       2786078.1     10068993.61
      2784828.76     10067457.96
#Sta/Elev= 30
  2446.9 1589.63  2695.2 1587.81  2810.5 1584.97  3052.5 1577.32  3206.2 1576.33
  3373.6 1574.28  3409.6 1570.42  3484.1 1575.21  3611.5 1576.06  3874.7 1574.58
  3990.8 1574.07  4137.7  1583.6  4385.8 1588.99  4605.2 1587.75  4939.2 1570.62
  4974.4 1562.16  5000.1 1559.74  5002.9 1559.24  5006.1 1559.74  5110.1 1569.56
  5130.7 1570.56    5241 1576.31  5348.8 1577.04  5407.2 1579.64  5480.2 1582.58
  5611.6 1587.54  5704.1 1588.66  5763.5 1589.12  5830.7 1590.22  6421.5 1601.92
#Mann= 20 ,-1 , 0
  2446.9     .05       0  2695.2     .16       0  2810.5     .05       0
  3206.2      .1       0  3484.1     .16       0  3611.5      .1       0
  3874.7     .16       0  4137.7      .1       0  4385.8     .05       0
  5000.1     .07       0  5006.1      .1       0  5130.7     .16       0
    5241      .1       0  5348.8     .16       0  5407.2      .1       0
  5480.2     .16       0  5611.6     .16       0  5704.1      .1       0
  5763.5     .16       0  5830.7      .1       0
#XS Ineff= 2 , 0
         4445.59 1589.34
Permanent Ineff=
       F       F
Bank Sta=4939.2,5110.1
XS Rating Curve= 0 ,0
Exp/Cntr=0.3,0.1

Type RM Length L Ch R = 1 ,20275   ,855,855,855
BEGIN DESCRIPTION:
Mapping XS 26b6c2d9
END DESCRIPTION:
XS GIS Cut Line= 3
      2787701.34      10068637.7      2785479.15     10067708.89
      2784602.94      10067214.4
#Sta/Elev= 30
  3479.7  1589.2  3569.5 1588.94  3708.7 1581.66  3927.2 1570.09  3943.6 1566.01
  4097.3 1571.25  4622.1 1571.47  4847.2    1575    4924 1573.13    4946 1569.44
  4967.7 1563.37  4997.2 1559.55  4999.9 1559.05  5003.2 1559.55  5043.5  1559.6
  5088.5 1561.39  5119.4 1568.88  5229.2  1573.7  5346.5 1573.25  5349.2 1573.21
  5433.7 1572.31  5559.3 1576.43  5686.3 1582.91  5752.4 1586.09  5874.4 1590.71
  6015.8 1596.82  6222.8  1601.5  6294.7 1602.04  6565.9 1602.33  6894.3 1604.66
#Mann= 15 ,-1 , 0
  3479.7     .05       0  3708.7      .1       0  4997.2     .07       0
  5003.2      .1       0  5043.5     .05       0  5229.2      .1       0
  5346.5     .05       0  5349.2      .1       0  5559.3     .05       0
  5686.3      .1       0  5752.4     .05       0  5874.4      .1       0
  6222.8     .05       0  6294.7      .1       0  6565.9     .16       0
#XS Ineff= 2 , 0
         4862.72 1575.07  5281.8         1574.44
Permanent Ineff=
       F       F
Bank Sta=4946,5119.4
XS Rating Curve= 0 ,0
Exp/Cntr=0.3,0.1

Type RM Length L Ch R = 1 ,19420   ,1253,1253,1253
BEGIN DESCRIPTION:
PALO ALTO CREEK 25.0
END DESCRIPTION:
XS GIS Cut Line= 2
      2787497.92     10067509.35      2784914.52     10066856.56
#Sta/Elev= 30
  3944.2 1586.99  4350.3 1581.56    4523 1576.49  4673.1  1570.7  4773.7 1569.29
  4877.7 1569.75  4902.9 1567.45  4922.4 1558.77  4933.8 1557.28  4992.7 1556.34
  4995.4 1555.84  4998.7 1556.34  5050.6 1560.93  5067.9 1565.38  5086.5 1567.67
  5232.9 1571.41  5325.8 1568.71  5377.8 1569.13  5478.5 1574.86  5487.6 1575.49
    5532 1578.29  5589.9  1584.6  5694.1 1592.35  5780.5 1597.16  6066.3 1598.37
  6263.7 1595.73  6399.7 1594.16  6485.2 1595.04  6585.9 1597.93  6608.8 1598.23
#Mann= 17 ,-1 , 0
  3944.2     .05       0  4350.3      .1       0    4523     .05       0
  4673.1     .16       0  4773.7      .1       0  4877.7     .05       0
  4992.7    .035       0  4998.7     .05       0  5377.8      .1       0
  5478.5     .05       0  5487.6      .1       0  5589.9     .16       0
  5694.1      .1       0  5780.5     .05       0  6263.7      .1       0
  6485.2     .05       0  6585.9     .16       0
#XS Ineff= 2 , 0
                         5238.78         1571.48
Permanent Ineff=
       F       F
Bank Sta=4902.9,5086.5
XS Rating Curve= 0 ,0
Exp/Cntr=0.3,0.1