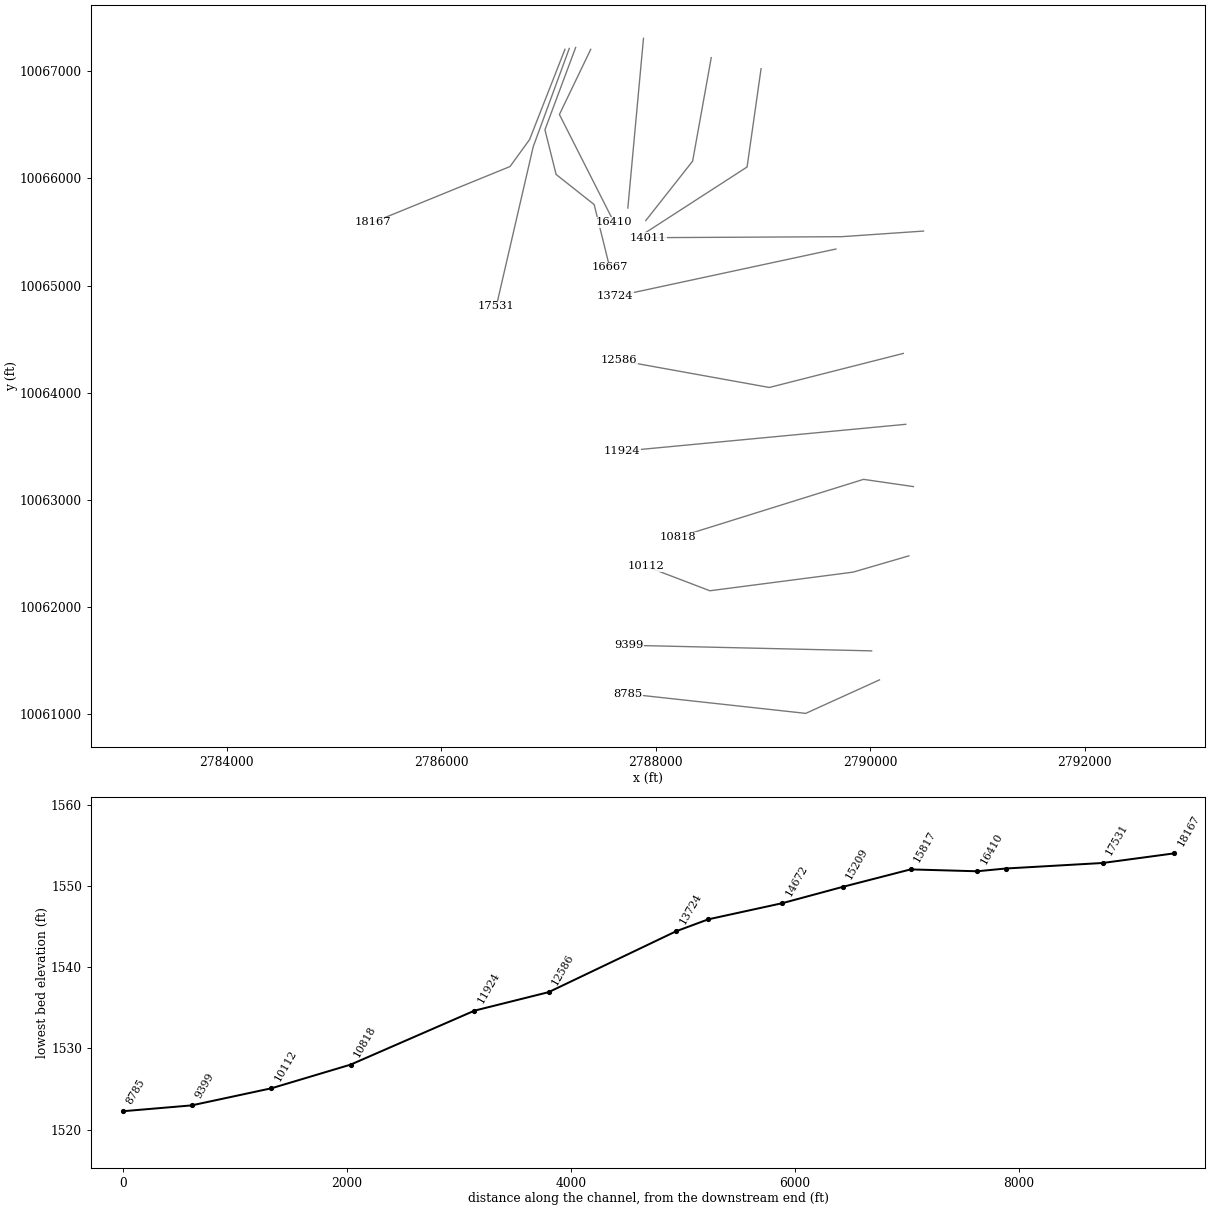
HEC-RAS study PALO ALTO CREEK.prj: PALO ALTO CREEK Base Level Engineering

--- PALO ALTO CREEK.g01 (geometry) --- (continued)

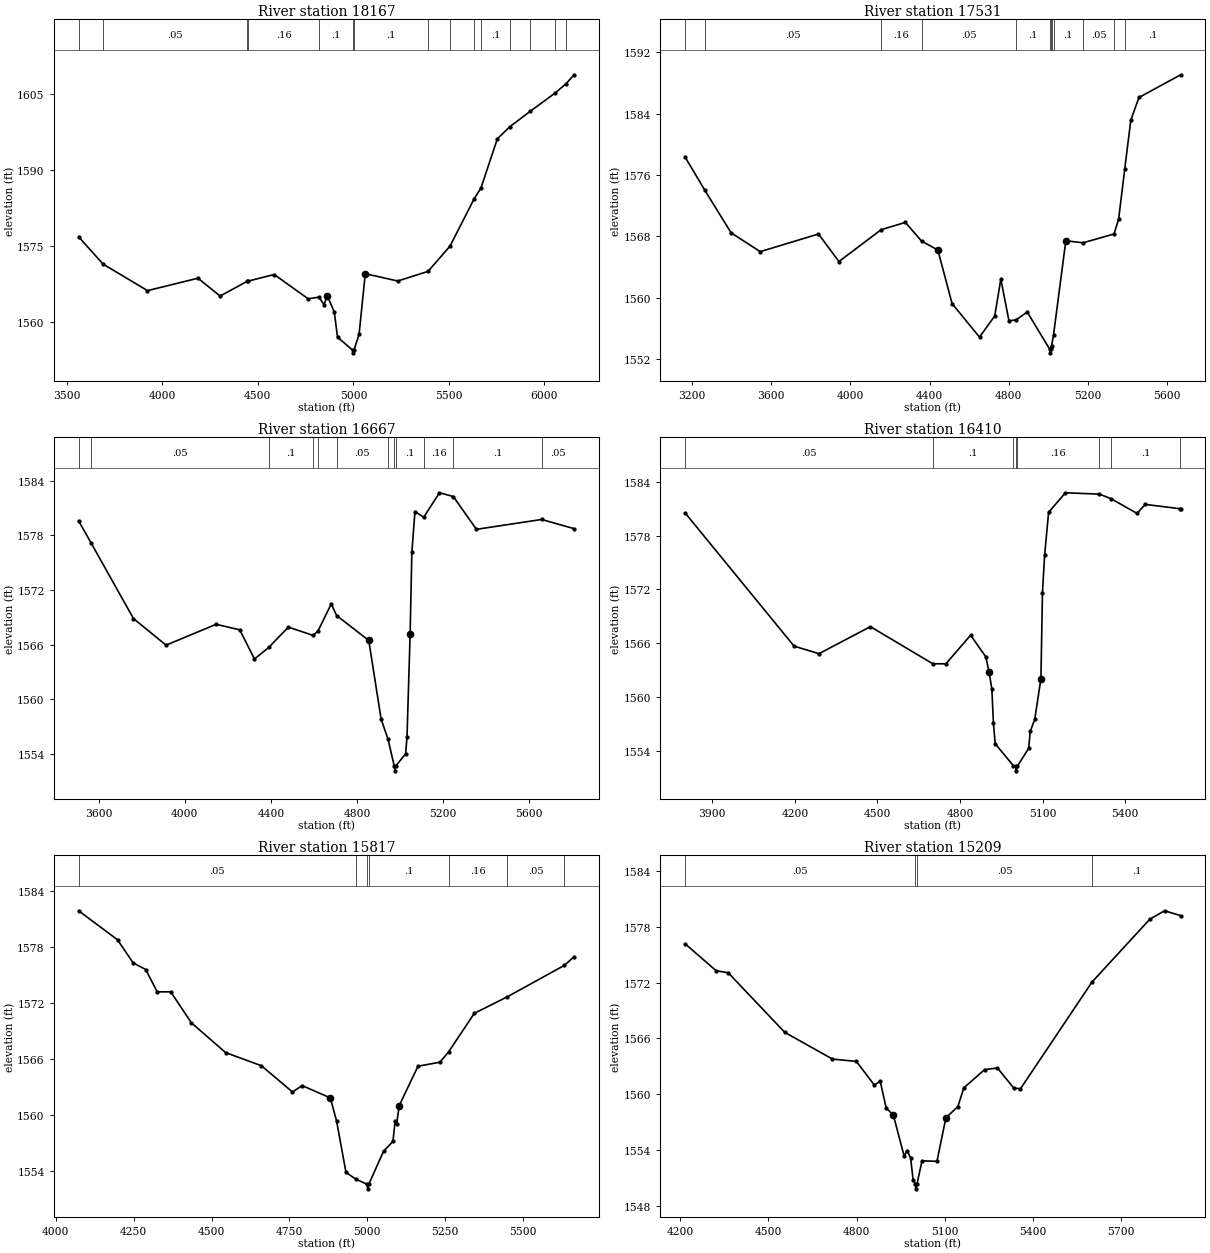
Type RM Length L Ch R = 1 ,18167   ,636,636,636
BEGIN DESCRIPTION:
Mapping XS 14523563
END DESCRIPTION:
XS GIS Cut Line= 4
      2787154.49     10067205.42      2786824.63     10066363.41
      2786642.34     10066111.67      2785366.27     10065590.83
#Sta/Elev= 30
    3562  1576.9  3689.7 1571.52  3922.4 1566.28  4186.7 1568.73  4302.3 1565.21
  4445.2 1568.14  4449.3 1568.16  4585.4 1569.46  4763.3 1564.67  4819.8    1565
  4846.1 1563.51  4863.3 1565.25  4900.1 1562.06  4916.8 1557.11  4996.7 1554.51
  4999.4 1554.01  5002.7 1554.51  5029.7 1557.66  5062.1 1569.62  5232.2 1568.18
  5390.8 1570.08  5505.5 1575.06  5632.4 1584.43  5667.2 1586.49  5753.4 1596.24
  5819.7 1598.64  5924.4 1601.63  6057.2  1605.3  6112.8  1607.1  6155.4 1608.86
#Mann= 15 ,-1 , 0
    3562      .1       0  3689.7     .05       0  4445.2      .1       0
  4449.3     .16       0  4819.8      .1       0  4996.7     .07       0
  5002.7      .1       0  5390.8     .16       0  5505.5      .1       0
  5632.4     .05       0  5667.2      .1       0  5819.7     .05       0
  5924.4      .1       0  6057.2     .05       0  6112.8      .1       0
Bank Sta=4863.3,5062.1
XS Rating Curve= 0 ,0
Exp/Cntr=0.3,0.1

Type RM Length L Ch R = 1 ,17531   ,864,864,864
BEGIN DESCRIPTION:
Mapping XS feb1d08e
END DESCRIPTION:
XS GIS Cut Line= 3
      2787194.87     10067213.56      2786858.67       10066297.
      2786514.54     10064808.44
#Sta/Elev= 30
  3164.5 1578.35  3263.5 1574.05  3397.1 1568.47  3544.3 1566.02  3838.6 1568.32
  3941.9 1564.73  4155.2 1568.88  4277.6 1569.83  4359.2  1567.4  4441.8 1566.23
  4513.6 1559.25  4652.2 1554.88  4729.2 1557.64    4760 1562.44    4801 1557.01
  4836.6 1557.12  4893.4 1558.15  5006.4 1553.33  5009.2 1552.83  5012.4 1553.33
  5016.5 1553.77  5026.3 1555.17  5088.4 1567.44  5174.9 1567.17    5332 1568.32
  5355.3 1570.27  5386.2  1576.8  5416.8 1583.16  5457.9 1586.11  5668.6 1589.07
#Mann= 12 ,-1 , 0
  3164.5      .1       0  3263.5     .05       0  4155.2     .16       0
  4359.2     .05       0  4836.6      .1       0  5006.4     .07       0
  5012.4      .1       0  5016.5     .05       0  5026.3      .1       0
  5174.9     .05       0    5332     .16       0  5386.2      .1       0
Bank Sta=4441.8,5088.4
XS Rating Curve= 0 ,0
Exp/Cntr=0.3,0.1

Type RM Length L Ch R = 1 ,16667   ,257,257,257
BEGIN DESCRIPTION:
Mapping XS 902bc20d
END DESCRIPTION:
XS GIS Cut Line= 5
      2787254.33     10067222.81      2786967.86     10066454.55
      2787072.03     10066037.89        2787427.     10065756.69
      2787571.08     10065172.36
#Sta/Elev= 30
  3506.1 1579.57  3564.8 1577.12    3761 1568.86  3912.6 1565.94  4145.5 1568.23
  4255.1 1567.62  4323.8 1564.42    4390 1565.69  4481.5 1567.92  4596.4 1567.01
  4618.9 1567.49  4680.7 1570.47  4705.6 1569.19  4855.1 1566.46  4912.8  1557.8
  4944.6 1555.63  4973.9 1552.65  4976.7 1552.15  4979.9 1552.65  5026.6 1554.03
    5033 1555.89  5047.4 1567.15  5055.5 1576.12  5069.9  1580.6  5110.4 1579.97
  5183.7 1582.66  5248.3 1582.25  5355.6 1578.65    5659 1579.73  5810.2 1578.72
#Mann= 12 ,-1 , 0
  3506.1      .1       0  3564.8     .05       0    4390      .1       0
  4596.4     .05       0  4618.9      .1       0  4705.6     .05       0
  4944.6      .1       0  4973.9     .07       0  4979.9      .1       0
  5110.4     .16       0  5248.3      .1       0    5659     .05       0
Bank Sta=4855.1,5047.4
XS Rating Curve= 0 ,0
Exp/Cntr=0.3,0.1

Type RM Length L Ch R = 1 ,16410   ,593,593,593
BEGIN DESCRIPTION:
PALO ALTO CREEK 24.0
END DESCRIPTION:
XS GIS Cut Line= 3
      2787394.98     10067205.53      2787102.81     10066597.17
      2787611.09     10065592.62
#Sta/Elev= 30
    3801 1580.52    4197 1565.69  4287.6 1564.85  4474.3 1567.86    4701 1563.73
  4748.7 1563.72  4838.4 1566.91  4893.5 1564.51  4905.6 1562.83  4915.8 1560.89
  4921.4  1557.1    4928 1554.82  4993.4  1552.4  5001.9 1552.31  5004.6 1551.81
  5007.9 1552.31  5049.5 1554.32  5055.1 1556.19  5071.7 1557.57    5094 1562.08
  5099.6 1571.64  5107.3 1575.78  5121.9 1580.59  5183.2 1582.76  5306.5 1582.61
  5348.2 1582.11  5443.6 1580.46  5472.8 1581.47  5598.5 1580.99  5601.7 1580.99
#Mann= 8 ,-1 , 0
    3801     .05       0    4701      .1       0  4993.4     .16       0
  5001.9     .07       0  5007.9     .16       0  5306.5     .05       0
  5348.2      .1       0  5598.5     .05       0
Bank Sta=4905.6,5094
XS Rating Curve= 0 ,0
Exp/Cntr=0.3,0.1

Type RM Length L Ch R = 1 ,15817   ,608,608,608
BEGIN DESCRIPTION:
PALO ALTO CREEK 23.0
END DESCRIPTION:
XS GIS Cut Line= 2
      2787886.78       10067308.      2787740.94      10065724.6
#Sta/Elev= 30
  4073.6 1581.86  4198.4 1578.75  4248.6 1576.27  4288.8 1575.56  4325.8 1573.16
  4369.1 1573.17  4435.6 1569.84  4545.3 1566.65  4660.3 1565.24  4759.8 1562.43
  4790.9 1563.11  4881.3 1561.79  4901.4  1559.3  4931.5  1553.8  4963.1 1553.08
  4998.8 1552.54  5001.5 1552.04  5004.8 1552.54    5052 1556.07  5082.1 1557.13
  5089.1 1559.27  5094.1    1559  5102.2 1560.96  5162.5 1565.19  5232.8 1565.62
  5260.6 1566.72  5343.2 1570.86  5448.2 1572.62  5632.1    1576  5663.7 1576.94
#Mann= 7 ,-1 , 0
  4073.6     .05       0  4963.1      .1       0  4998.8     .07       0
  5004.8      .1       0  5260.6     .16       0  5448.2     .05       0
  5632.1      .1       0
Bank Sta=4881.3,5102.2
XS Rating Curve= 0 ,0
Exp/Cntr=0.3,0.1

Type RM Length L Ch R = 1 ,15209   ,537,537,537
BEGIN DESCRIPTION:
PALO ALTO CREEK 22.0
END DESCRIPTION:
XS GIS Cut Line= 3
      2788518.72     10067127.43      2788345.11     10066162.12
      2787908.44     10065607.62
#Sta/Elev= 30
  4216.5 1576.15  4321.9 1573.27  4363.4 1573.04  4555.6 1566.66  4718.1 1563.79
  4799.4 1563.54  4860.4 1561.02  4880.7  1561.4    4901 1558.54  4925.3 1557.78
    4962  1553.4  4972.1 1553.97    4984 1553.21  4992.5 1550.85  4999.6 1550.38
  5002.4 1549.88  5005.6 1550.38  5022.9 1552.88  5073.7 1552.83  5104.2  1557.5
  5144.9  1558.7  5165.2 1560.71    5236 1562.66  5279.4 1562.84  5335.4 1560.67
    5358 1560.61  5601.4 1572.05  5798.9 1578.81  5848.6 1579.69  5903.1 1579.17
#Mann= 4 ,-1 , 0
  4216.5     .05       0  4999.6     .04       0  5005.6     .05       0
  5601.4      .1       0
#XS Ineff= 2 , 0
                         5273.04         1562.72
Permanent Ineff=
       F       F
Bank Sta=4925.3,5104.2
XS Rating Curve= 0 ,0
Exp/Cntr=0.3,0.1

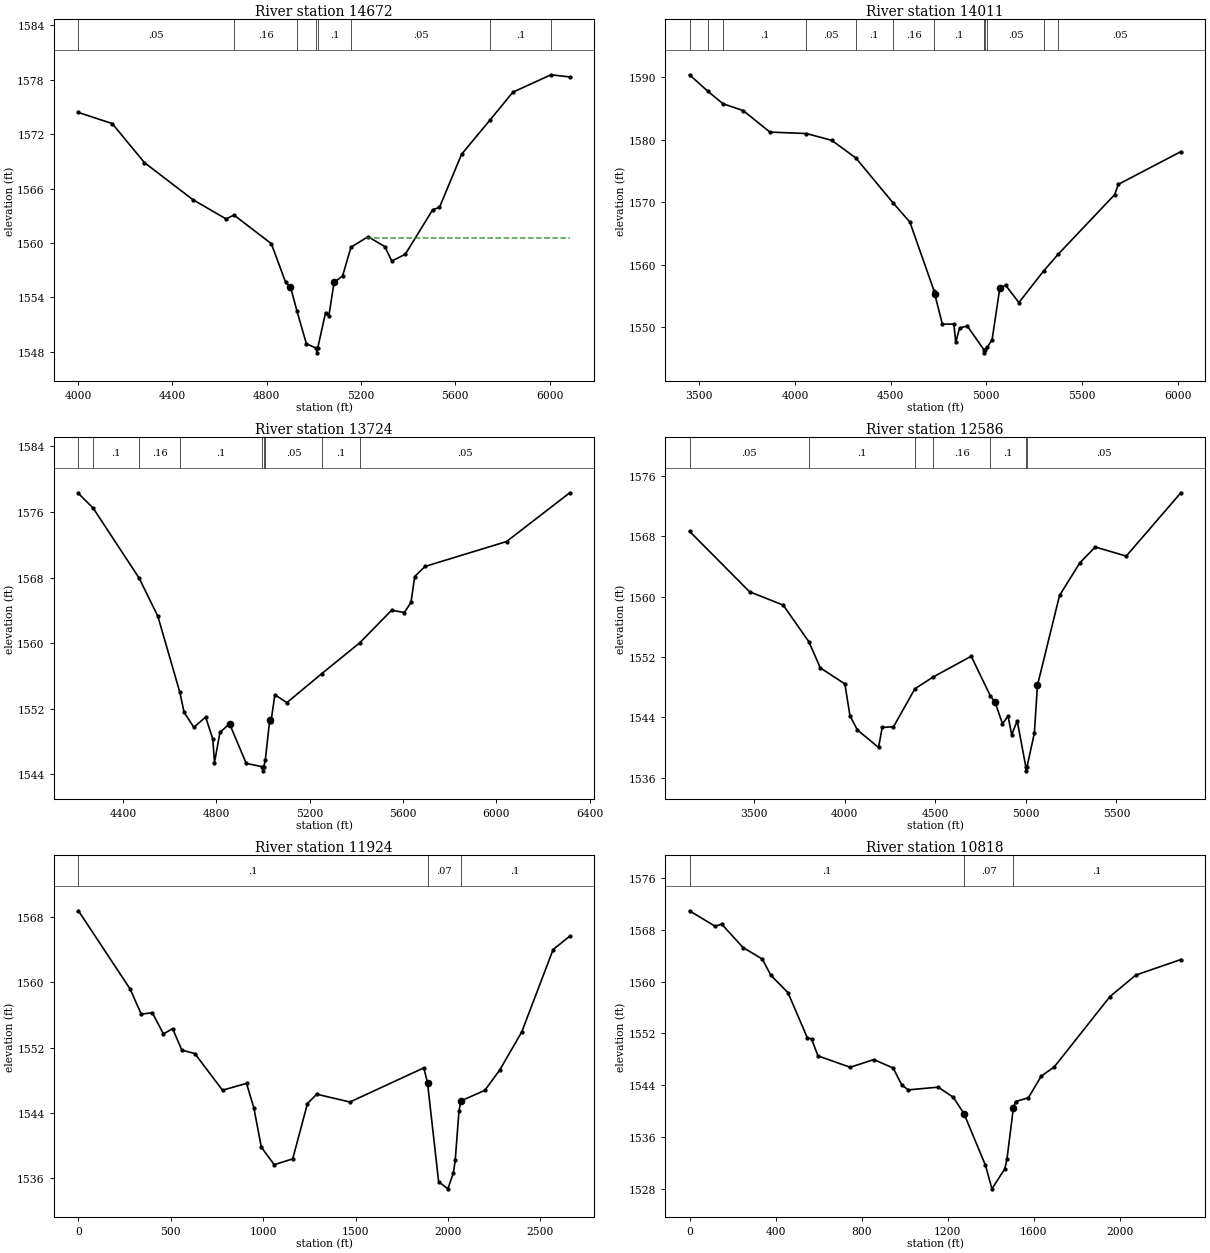
Type RM Length L Ch R = 1 ,14672   ,661,661,661
BEGIN DESCRIPTION:
PALO ALTO CREEK 21.0
END DESCRIPTION:
XS GIS Cut Line= 3
      2788983.13     10067024.09      2788852.92     10066107.43
      2787880.16       10065478.
#Sta/Elev= 30
  4001.2 1574.39  4144.5 1573.17  4281.3 1568.86  4486.4 1564.78  4627.8 1562.65
  4661.1 1563.08  4819.7 1559.92  4880.3 1555.65  4900.5 1555.18  4928.5 1552.48
  4968.1  1548.9  5010.2 1548.38    5013 1547.88  5016.2 1548.38  5049.5 1552.29
  5063.4 1551.92  5085.8 1555.64  5122.1 1556.37  5157.4 1559.53  5230.1 1560.69
  5301.6 1559.59  5330.5    1558  5387.9 1558.75  5504.1 1563.66    5533 1563.93
  5626.7 1569.78  5748.6  1573.6  5844.3 1576.63  6005.9 1578.55  6085.7 1578.31
#Mann= 8 ,-1 , 0
  4001.2     .05       0  4661.1     .16       0  4928.5      .1       0
  5010.2     .07       0  5016.2      .1       0  5157.4     .05       0
  5748.6      .1       0  6005.9     .05       0
#XS Ineff= 2 , 0
                         5221.28         1560.56
Permanent Ineff=
       F       F
Bank Sta=4900.5,5085.8
XS Rating Curve= 0 ,0
Exp/Cntr=0.3,0.1

Type RM Length L Ch R = 1 ,14011   ,287,287,287
BEGIN DESCRIPTION:
PALO ALTO CREEK 16.0
END DESCRIPTION:
XS GIS Cut Line= 3
      2790498.13     10065509.36      2789732.89      10065456.9
      2787932.15     10065447.65
#Sta/Elev= 30
  3448.8 1590.42  3545.8 1587.75  3623.9 1585.78  3729.1 1584.69  3869.4 1581.24
  4059.6 1581.01  4192.1 1579.92  4318.1  1577.1  4511.1 1569.96  4600.3 1566.84
  4727.1 1555.79  4730.3 1555.31  4770.3 1550.48  4830.3  1550.5  4840.3  1547.6
  4860.3 1549.87  4900.3 1550.19  4987.3 1546.39    4990 1545.89  4993.3 1546.39
  5003.9 1546.76  5030.3 1548.01  5070.3 1556.23  5100.3 1556.74  5170.3 1553.94
  5299.9 1559.02  5375.3 1561.67  5670.3 1571.21  5690.3 1572.88  6016.6 1578.11
#Mann= 12 ,-1 , 0
  3448.8      .1       0  3545.8     .05       0  3623.9      .1       0
  4059.6     .05       0  4318.1      .1       0  4511.1     .16       0
  4727.1      .1       0  4987.3     .07       0  4993.3      .1       0
  5003.9     .05       0  5299.9      .1       0  5375.3     .05       0
Bank Sta=4730.3,5070.3
XS Rating Curve= 0 ,0
Exp/Cntr=0.3,0.1

Type RM Length L Ch R = 1 ,13724   ,1138,1138,1138
BEGIN DESCRIPTION:
PALO ALTO CREEK 19.0
END DESCRIPTION:
XS GIS Cut Line= 2
      2789681.05     10065341.81      2787623.74      10064899.1
#Sta/Elev= 30
  4209.5 1578.27  4272.4 1576.49  4469.4 1567.94  4549.7 1563.28  4644.1 1553.98
  4662.2 1551.55  4703.9 1549.73  4754.3 1550.98    4785  1548.3  4792.3 1545.42
  4815.6  1549.1  4856.6 1550.17  4928.2 1545.33  4996.8 1544.92  4999.5 1544.42
  5002.8 1544.92  5009.8 1545.69  5028.8 1550.65  5033.9 1550.37  5050.9 1553.71
  5102.1 1552.74  5250.8 1556.26  5413.6 1560.02    5551 1564.02  5605.5 1563.74
    5634 1564.99  5649.7 1568.13    5694 1569.36  6043.1  1572.4  6313.9 1578.35
#Mann= 9 ,-1 , 0
  4209.5     .05       0  4272.4      .1       0  4469.4     .16       0
  4644.1      .1       0  4996.8     .07       0  5002.8      .1       0
  5009.8     .05       0  5250.8      .1       0  5413.6     .05       0
Bank Sta=4856.6,5028.8
XS Rating Curve= 0 ,0
Exp/Cntr=0.3,0.1

Type RM Length L Ch R = 1 ,12586   ,662,662,662
BEGIN DESCRIPTION:
PALO ALTO CREEK 18.0
END DESCRIPTION:
XS GIS Cut Line= 3
      2790309.92     10064367.67      2789060.22     10064049.84
      2787659.37     10064302.86
#Sta/Elev= 30
  3142.4 1568.65  3474.1 1560.64  3659.8 1558.87  3800.7 1554.05  3864.7 1550.56
  4000.3 1548.43  4028.4 1544.21  4069.3 1542.34  4186.1 1540.02  4206.7 1542.68
  4268.6 1542.75  4386.9 1547.79  4487.8 1549.35  4697.9  1552.1  4803.4 1546.86
    4830 1545.98  4870.6 1543.15  4901.1 1544.18  4921.4  1541.7  4951.9 1543.54
  4999.7 1537.42  5002.5 1536.92  5005.7 1537.42  5046.5 1541.91  5063.7 1548.25
  5185.6 1560.15  5297.4 1564.46  5382.9 1566.57  5553.7 1565.36  5855.4 1573.75
#Mann= 7 ,-1 , 0
  3142.4     .05       0  3800.7      .1       0  4386.9     .05       0
  4487.8     .16       0  4803.4      .1       0  4999.7     .07       0
  5005.7     .05       0
Bank Sta=4830,5063.7
XS Rating Curve= 0 ,0
Exp/Cntr=0.3,0.1

Type RM Length L Ch R = 1 ,11924   ,1106,1106,1106
XS GIS Cut Line= 2
     2790332.401    10063706.119      2787684.79    10063454.859
#Sta/Elev= 30
       0 1568.81  279.99 1559.19  339.98 1556.11  399.98 1556.28  459.98 1553.68
  509.97 1554.32  559.97 1551.68  629.97 1551.27  779.96 1546.76  909.95  1547.6
  949.95 1544.57  989.95 1539.77 1059.95 1537.61 1159.94 1538.32 1239.94 1545.12
 1289.93 1546.27 1469.92 1545.31  1869.9 1549.51  1889.9 1547.64  1949.9 1535.52
  1999.9 1534.64  2029.9  1536.6  2039.9 1538.17 2059.89 1544.15 2069.89 1545.44
 2199.89 1546.74 2279.88 1549.21 2399.88 1553.92 2569.87 1564.05 2659.86 1565.69
#Mann= 3 , 0 , 0
       0      .1       0  1889.9     .07       0 2069.89      .1       0
Bank Sta=1889.9,2069.89
XS Rating Curve= 0 ,0
Exp/Cntr=0.3,0.1

Type RM Length L Ch R = 1 ,10818   ,706,706,706
XS GIS Cut Line= 3
     2790403.654    10063124.845     2789938.635    10063192.348
     2788209.812    10062652.325
#Sta/Elev= 30
       0 1570.92  119.33 1568.52  149.16 1568.87   248.6 1565.25   338.1 1563.47
  377.88 1560.96  457.43 1558.28  547.13 1551.33  567.08 1551.12     597 1548.51
   746.6 1546.76   856.3 1547.95  946.06 1546.64  985.96 1544.04 1015.88 1543.27
  1155.5 1543.69 1225.32 1542.13 1275.18 1539.59 1374.92 1531.62 1404.84 1527.99
 1464.68 1531.08 1474.65 1532.56 1504.57 1540.49 1514.54 1541.46 1574.38 1542.06
 1634.22  1545.4 1694.06  1546.8 1953.37 1557.68 2073.05 1560.99 2282.49 1563.39
#Mann= 3 , 0 , 0
       0      .1       0 1275.18     .07       0 1504.57      .1       0
Bank Sta=1275.18,1504.57
XS Rating Curve= 0 ,0
Exp/Cntr=0.3,0.1

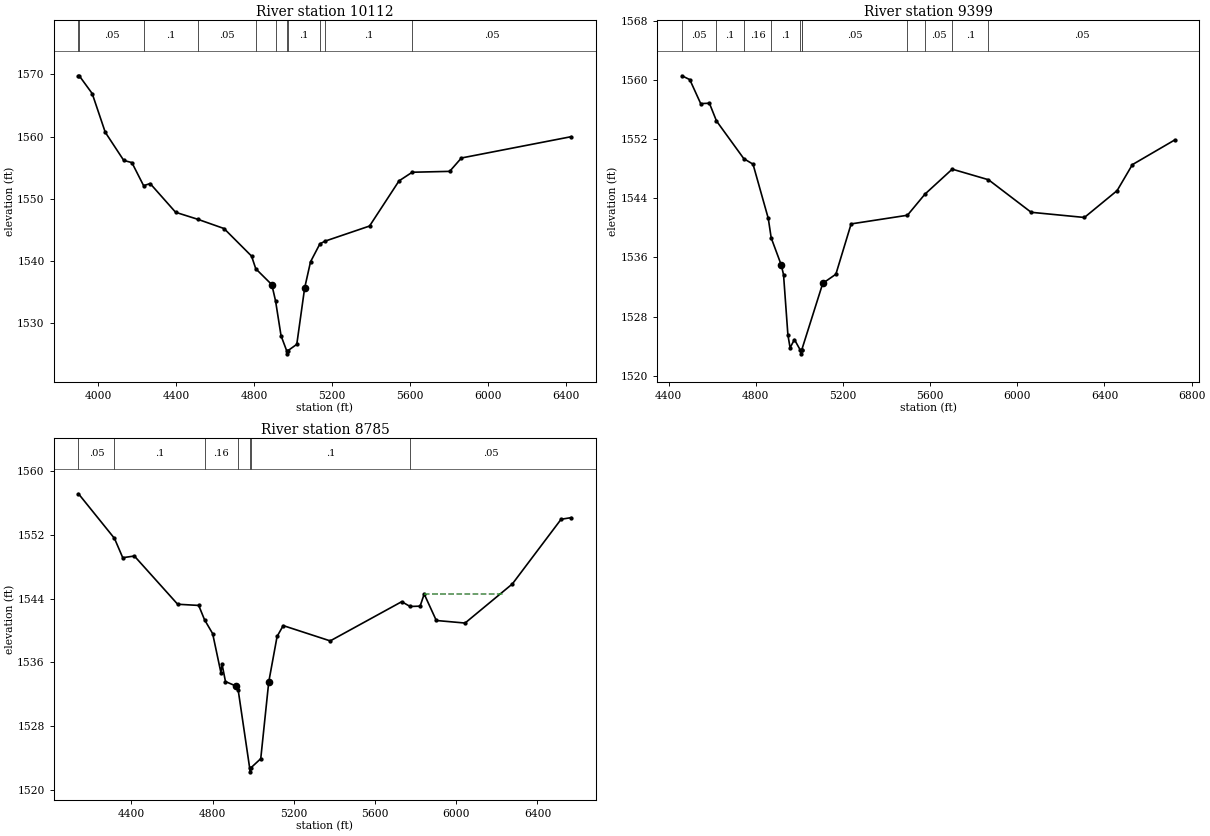
Type RM Length L Ch R = 1 ,10112   ,713,713,713
BEGIN DESCRIPTION:
PALO ALTO CREEK 15.0
END DESCRIPTION:
XS GIS Cut Line= 4
       2790361.3     10062478.29       2789840.5     10062326.39
      2788505.87     10062152.78      2787909.07     10062380.65
#Sta/Elev= 30
  3899.3 1569.79  3903.2 1569.79  3969.6 1566.93  4036.5 1560.71  4131.4 1556.18
  4173.1 1555.83  4233.2 1552.12  4266.8 1552.46  4397.4 1547.84  4511.5 1546.71
  4645.5 1545.23  4786.7  1540.8  4808.4 1538.76  4890.7  1536.2  4909.9 1533.58
    4938 1527.99  4966.8 1525.58  4969.6 1525.08  4972.8 1525.58  5018.7 1526.61
    5059 1535.66  5089.2 1539.88  5137.3 1542.77  5164.6 1543.21  5391.8 1545.63
    5543 1552.89  5610.6 1554.28  5802.7 1554.42  5862.8 1556.57  6426.5    1560
#Mann= 11 ,-1 , 0
  3899.3      .1       0  3903.2     .05       0  4233.2      .1       0
  4511.5     .05       0  4808.4     .16       0  4909.9      .1       0
  4966.8     .07       0  4972.8      .1       0  5137.3     .16       0
  5164.6      .1       0  5610.6     .05       0
Bank Sta=4890.7,5059
XS Rating Curve= 0 ,0
Exp/Cntr=0.3,0.1

Type RM Length L Ch R = 1 ,9399    ,614,614,614
BEGIN DESCRIPTION:
PALO ALTO CREEK 13.0
END DESCRIPTION:
XS GIS Cut Line= 2
      2790014.33     10061591.81      2787753.93     10061643.89
#Sta/Elev= 30
  4461.6 1560.55  4497.5 1560.03  4547.5 1556.79  4587.5 1556.84    4620 1554.44
  4745.3 1549.35  4787.6  1548.6  4857.6 1541.27    4871 1538.64  4917.6 1534.94
  4927.6 1533.66  4947.6 1525.54  4957.6 1523.79  4977.6  1524.9  5004.6 1523.47
  5007.4 1522.97  5010.6 1523.47  5011.3 1523.52  5107.6  1532.5  5167.7 1533.73
  5237.7 1540.53    5496  1541.7  5576.6 1544.56  5701.5 1547.93  5867.8  1546.5
  6063.7  1542.1    6308  1541.4    6458 1545.03    6528 1548.54  6722.6 1551.88
#Mann= 11 ,-1 , 0
  4461.6     .05       0    4620      .1       0  4745.3     .16       0
    4871      .1       0  5004.6     .07       0  5010.6      .1       0
  5011.3     .05       0    5496      .1       0  5576.6     .05       0
  5701.5      .1       0  5867.8     .05       0
Bank Sta=4917.6,5107.6
XS Rating Curve= 0 ,0
Exp/Cntr=0.3,0.1

Type RM Length L Ch R = 1 ,8785    ,931,931,931
BEGIN DESCRIPTION:
PALO ALTO CREEK 12.0
END DESCRIPTION:
XS GIS Cut Line= 3
      2790087.31     10061320.98      2789399.79     10061008.47
      2787738.37     10061190.76
#Sta/Elev= 30
    4140 1557.14  4317.2 1551.54  4357.9 1549.12  4415.1 1549.33  4628.2 1543.28
  4731.9 1543.13  4760.5 1541.34  4800.6 1539.59  4841.3 1534.69  4846.7 1535.77
  4863.7 1533.58  4916.7    1533  4926.5 1532.48  4982.7 1522.75  4985.4 1522.25
  4988.7 1522.75  5037.4  1523.9  5076.8 1533.53  5117.9 1539.24    5148  1540.6
  5379.4 1538.68  5731.5  1543.6  5772.7    1543  5822.1 1543.04  5842.2 1544.56
  5901.8 1541.24  6043.4 1540.92  6276.4 1545.83  6516.2 1553.94  6566.6 1554.15
#Mann= 7 ,-1 , 0
    4140     .05       0  4317.2      .1       0  4760.5     .16       0
  4926.5      .1       0  4982.7     .07       0  4988.7      .1       0
  5772.7     .05       0
#XS Ineff= 1 ,-1
 5844.62  6236.4 1544.53
Permanent Ineff=
       F
Bank Sta=4916.7,5076.8
XS Rating Curve= 0 ,0
Exp/Cntr=0.3,0.1