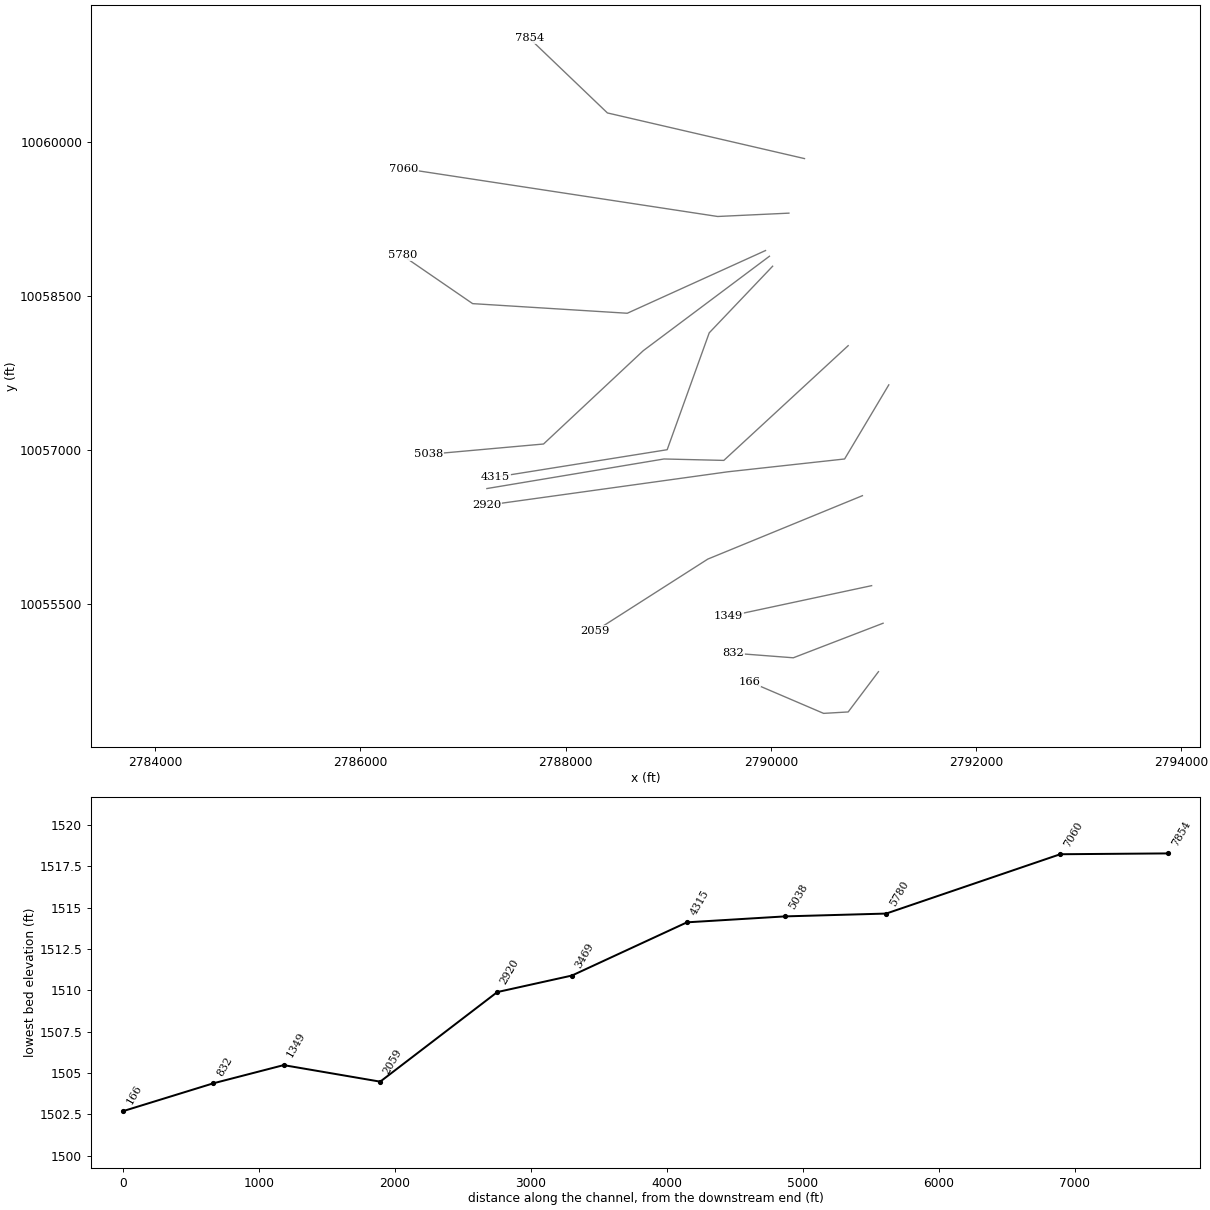
HEC-RAS study PALO ALTO CREEK.prj: PALO ALTO CREEK Base Level Engineering

--- PALO ALTO CREEK.g01 (geometry) --- (continued)

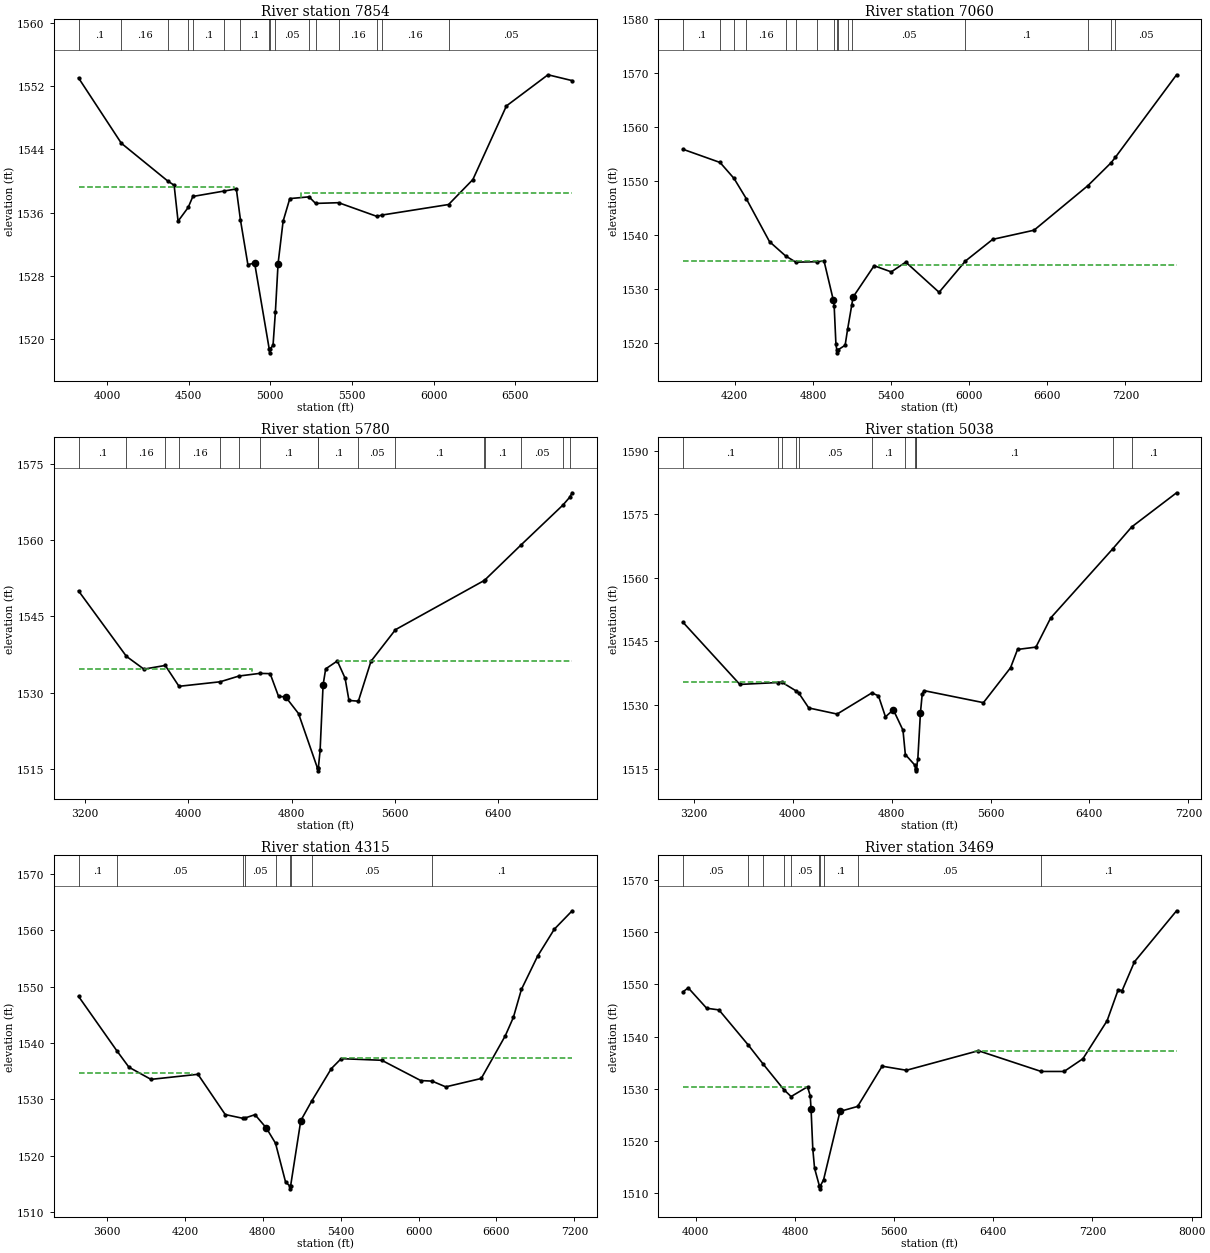
Type RM Length L Ch R = 1 ,7854    ,794,794,794
BEGIN DESCRIPTION:
PALO ALTO CREEK 11.0
END DESCRIPTION:
XS GIS Cut Line= 3
      2790328.79     10059841.58      2788408.21     10060286.46
      2787648.69     10061013.44
#Sta/Elev= 30
  3825.9 1553.05    4088 1544.79    4373    1540  4411.3 1539.48  4435.3 1534.93
  4497.3 1536.67    4526 1538.06  4718.7 1538.75  4792.2 1539.01  4817.3  1535.1
    4863 1529.42    4904 1529.66  4993.4 1518.78  4996.2 1518.28  4999.4 1518.78
  5016.9 1519.23  5031.4 1523.47  5047.7 1529.55  5078.5 1534.92  5119.6 1537.79
  5237.2 1538.01  5277.5 1537.18  5418.4 1537.27  5652.7 1535.54  5684.7 1535.71
  6091.9 1537.04  6240.7  1540.2    6446 1549.51  6700.5 1553.45  6848.7 1552.71
#Mann= 16 ,-1 , 0
  3825.9      .1       0    4088     .16       0    4373      .1       0
  4497.3     .16       0    4526      .1       0  4718.7     .16       0
  4817.3      .1       0  4993.4     .07       0  4999.4      .1       0
  5031.4     .05       0  5237.2      .1       0  5277.5     .05       0
  5418.4     .16       0  5652.7      .1       0  5684.7     .16       0
  6091.9     .05       0
#XS Ineff= 2 , 0
         4775.04 1539.27 5189.62         1538.56
Permanent Ineff=
       F       F
Bank Sta=4904,5047.7
XS Rating Curve= 0 ,0
Exp/Cntr=0.3,0.1

Type RM Length L Ch R = 1 ,7060    ,1280,1280,1280
BEGIN DESCRIPTION:
PALO ALTO CREEK 9.0
END DESCRIPTION:
XS GIS Cut Line= 3
      2790176.91      10059309.9      2789482.43     10059277.35
      2786423.03     10059743.85
#Sta/Elev= 30
  3802.1 1555.93  4087.2 1553.48  4194.7 1550.52    4288  1546.8    4467 1538.82
  4590.7 1536.17    4669 1535.02  4828.7  1535.1  4885.7 1535.23  4956.5 1528.03
  4963.5 1526.84  4976.8 1519.84  4983.9 1518.73  4986.6 1518.23  4989.9 1518.73
  5047.6 1519.64  5066.4 1522.58  5097.9 1527.01  5108.5 1528.56  5270.1 1534.36
  5401.6 1533.22  5512.9 1535.03  5768.9 1529.44    5971 1535.23  6180.5 1539.24
  6497.9 1540.94  6912.2 1549.21  7089.4 1553.43  7123.1 1554.46  7592.1 1569.72
#Mann= 16 ,-1 , 0
  3802.1      .1       0  4087.2     .16       0  4194.7      .1       0
    4288     .16       0  4590.7     .12       0    4669     .16       0
  4828.7      .1       0  4963.5     .05       0  4983.9    .035       0
  4989.9     .05       0  5066.4      .1       0  5097.9     .05       0
    5971      .1       0  6912.2     .05       0  7089.4      .1       0
  7123.1     .05       0
#XS Ineff= 2 , 0
         4874.24 1535.27 5306.53         1534.53
Permanent Ineff=
       F       F
Bank Sta=4956.5,5108.5
XS Rating Curve= 0 ,0
Exp/Cntr=0.3,0.1

Type RM Length L Ch R = 1 ,5780    ,742,742,742
BEGIN DESCRIPTION:
PALO ALTO CREEK 8.0
END DESCRIPTION:
XS GIS Cut Line= 4
      2789948.89     10058945.44      2788601.71     10058334.34
      2787094.77     10058428.09      2786408.44     10058899.52
#Sta/Elev= 30
  3150.1    1550  3520.7 1537.14  3655.8 1534.63  3821.5 1535.35  3927.8 1531.25
  4246.6 1532.14  4391.9 1533.27  4553.1 1533.79  4633.5 1533.74  4698.9 1529.25
  4752.9 1529.18  4853.1  1525.9  5000.4 1515.14  5003.1 1514.64  5006.4 1515.14
  5020.3 1518.66  5043.4 1531.52  5063.5 1534.68  5153.7 1536.23  5213.8 1532.84
  5243.8 1528.47  5316.5 1528.33  5414.2 1536.17  5603.8 1542.38  6285.6 1551.97
  6293.5 1552.09  6576.7 1559.05    6900 1566.86  6951.2 1568.36  6971.9 1569.28
#Mann= 16 ,-1 , 0
  3150.1      .1       0  3520.7     .16       0  3821.5      .1       0
  3927.8     .16       0  4246.6      .1       0  4391.9     .05       0
  4553.1      .1       0  5000.4     .07       0  5006.4      .1       0
  5316.5     .05       0  5603.8      .1       0  6285.6     .05       0
  6293.5      .1       0  6576.7     .05       0    6900      .1       0
  6951.2     .05       0
#XS Ineff= 2 , 0
         4489.72 1534.61 5157.19         1536.26
Permanent Ineff=
       F       F
Bank Sta=4752.9,5043.4
XS Rating Curve= 0 ,0
Exp/Cntr=0.3,0.1

Type RM Length L Ch R = 1 ,5038    ,723,723,723
BEGIN DESCRIPTION:
PALO ALTO CREEK 7.0
END DESCRIPTION:
XS GIS Cut Line= 4
      2789987.11     10058889.89      2788757.96     10057969.76
      2787785.74     10057060.04      2786664.22     10056959.34
#Sta/Elev= 30
  3111.9 1549.53  3572.4 1534.85  3879.7  1535.3  3909.6 1535.42    4029 1533.29
  4048.4 1532.84    4130  1529.3  4359.2 1527.86  4640.2 1532.85  4693.6 1532.16
  4750.3 1527.21  4813.8 1528.87  4891.9 1524.05    4911 1518.31  4986.1 1515.88
  4994.9 1514.97  4997.7 1514.47  5000.9 1514.97  5012.1 1517.33  5033.1 1528.15
  5047.3  1532.5  5061.5 1533.39  5542.6 1530.55  5761.9 1538.78  5818.6  1543.1
  5967.1 1543.65  6086.5 1550.52    6588 1566.81  6741.7 1571.99  7104.8 1580.05
#Mann= 12 ,-1 , 0
  3111.9      .1       0  3879.7     .05       0  3909.6      .1       0
    4029     .16       0  4048.4     .05       0  4640.2      .1       0
    4911     .05       0  4986.1      .1       0  4994.9     .07       0
  5000.9      .1       0    6588     .05       0  6741.7      .1       0
#XS Ineff= 3 ,-1
  3111.9 3945.09 1535.41 4040.22 4643.96 1532.79  5068.4  7104.8 1533.27
Permanent Ineff=
       F       F       F
Bank Sta=4813.8,5033.1
XS Rating Curve= 0 ,0
Exp/Cntr=0.3,0.1

Type RM Length L Ch R = 1 ,4315    ,846,846,846
BEGIN DESCRIPTION:
PALO ALTO CREEK 6.0
END DESCRIPTION:
XS GIS Cut Line= 4
      2790018.35     10058792.64      2789400.32     10058143.37
       2788990.6     10057004.48      2787316.95     10056737.12
#Sta/Elev= 30
  3381.4 1548.29  3675.4 1538.66  3769.5 1535.71  3939.3 1533.55    4301 1534.45
  4511.2  1527.3  4647.4 1526.63  4663.3 1526.69  4740.4 1527.28  4827.2 1524.93
  4898.5  1522.2  4975.5 1515.34  5008.5 1514.61  5011.3 1514.11  5014.5 1514.61
    5093 1526.23  5175.5 1529.64  5328.1 1535.46  5403.9 1537.23  5716.5 1536.94
  6016.9 1533.34    6104 1533.24  6209.3 1532.22  6482.7 1533.71  6667.8 1541.29
  6729.9 1544.54    6792 1549.52  6916.1 1555.41  7045.4 1560.22    7183 1563.49
#Mann= 9 ,-1 , 0
  3381.4      .1       0  3675.4     .05       0  4647.4      .1       0
  4663.3     .05       0  4898.5      .1       0  5008.5     .07       0
  5014.5      .1       0  5175.5     .05       0    6104      .1       0
#XS Ineff= 2 , 0
         4257.56 1534.61 5409.31         1537.33
Permanent Ineff=
       F       F
Bank Sta=4827.2,5093
XS Rating Curve= 0 ,0
Exp/Cntr=0.3,0.1

Type RM Length L Ch R = 1 ,3469    ,549,549,549
BEGIN DESCRIPTION:
PALO ALTO CREEK 5.0
END DESCRIPTION:
XS GIS Cut Line= 4
      2790754.47     10058018.36      2789542.69     10056900.32
      2788959.35     10056914.21      2787233.62       10056626.
#Sta/Elev= 30
  3896.4 1548.58  3939.3 1549.35  4087.9 1545.45  4187.1 1545.13  4422.6 1538.44
  4544.9 1534.73  4711.1 1529.86    4769 1528.55  4901.6 1530.42  4923.2 1528.71
    4930 1526.19  4944.2 1518.47  4958.3 1514.84  4997.9 1511.39  5000.6 1510.89
  5003.9 1511.39  5031.1 1512.63  5163.6 1525.71  5305.7 1526.66  5503.3 1534.36
  5699.4 1533.58  6279.9 1537.32  6786.3 1533.35  6971.1 1533.35  7123.1 1535.79
  7318.1 1543.06    7407 1548.96  7439.6 1548.84  7538.8 1554.34  7878.3  1564.1
#Mann= 10 ,-1 , 0
  3896.4     .05       0  4422.6      .1       0  4544.9     .05       0
  4711.1      .1       0    4769     .05       0  4997.9    .035       0
  5003.9     .05       0  5031.1      .1       0  5305.7     .05       0
  6786.3      .1       0
#XS Ineff= 2 , 0
         4894.25 1530.43 6252.99         1537.31
Permanent Ineff=
       F       F
Bank Sta=4930,5163.6
XS Rating Curve= 0 ,0
Exp/Cntr=0.3,0.1

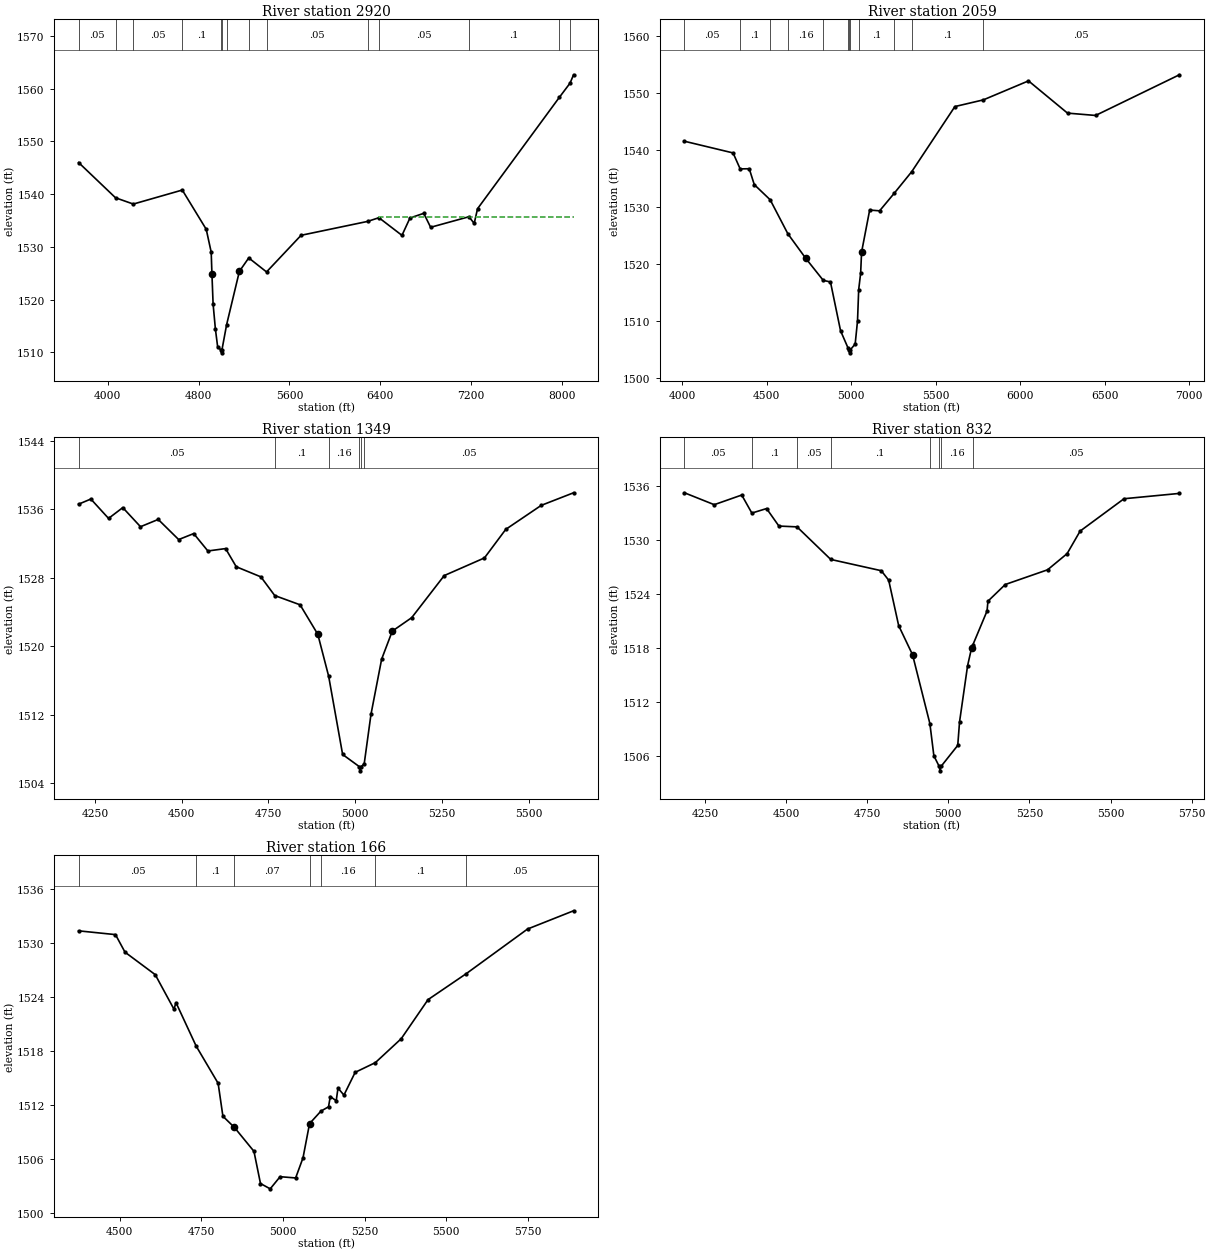
Type RM Length L Ch R = 1 ,2920    ,861,861,861
BEGIN DESCRIPTION:
PALO ALTO CREEK 4.0
END DESCRIPTION:
XS GIS Cut Line= 4
      2791150.32     10057636.42      2790719.77     10056914.21
      2789580.88     10056789.21      2787231.86     10056463.05
#Sta/Elev= 30
  3743.5    1546  4068.7 1539.31  4225.2 1538.12  4656.4 1540.78  4867.3 1533.33
    4911 1528.99  4917.6 1524.79  4927.7 1519.16  4947.8 1514.44  4967.9 1511.01
  4999.1 1510.39  5001.9 1509.89  5005.1 1510.39  5046.8 1515.24  5159.1 1525.35
  5241.6  1527.9  5398.3 1525.24  5702.3 1532.19  6288.7 1534.83  6387.8 1535.53
  6590.6 1532.18  6661.3 1535.48  6782.5 1536.36    6843 1533.71  7179.9 1535.71
  7226.7 1534.45  7256.2 1537.24  7976.5 1558.37  8070.2 1561.05  8101.6 1562.65
#Mann= 14 ,-1 , 0
  3743.5     .05       0  4068.7      .1       0  4225.2     .05       0
  4656.4      .1       0  4999.1     .07       0  5005.1      .1       0
  5046.8     .05       0  5241.6      .1       0  5398.3     .05       0
  6288.7      .1       0  6387.8     .05       0  7179.9      .1       0
  7976.5     .05       0  8070.2      .1       0
#XS Ineff= 2 , 0
                         6386.32         1535.71
Permanent Ineff=
       F       F
Bank Sta=4917.6,5159.1
XS Rating Curve= 0 ,0
Exp/Cntr=0.3,0.1

Type RM Length L Ch R = 1 ,2059    ,710,710,710
BEGIN DESCRIPTION:
PALO ALTO CREEK 3.0
END DESCRIPTION:
XS GIS Cut Line= 3
      2790893.37     10056556.56      2789386.44     10055938.51
      2788290.47     10055237.93
#Sta/Elev= 30
  4013.7 1541.56  4301.6 1539.51  4343.5 1536.71  4397.3 1536.74    4427 1533.96
  4521.1  1531.3  4625.8 1525.34  4732.3 1521.01  4835.4 1517.17  4877.9  1516.9
  4937.7 1508.34  4980.8  1505.4  4988.8 1504.97  4991.5 1504.47  4994.8 1504.97
  5024.2 1506.02  5038.1 1510.07    5045 1515.55  5056.6 1518.43  5062.1 1522.12
    5110  1529.5  5168.8 1529.36  5254.5 1532.41  5359.3 1536.24  5614.4 1547.64
  5782.7 1548.81    6050 1552.14  6280.9 1546.49  6447.1 1546.08  6943.2 1553.21
#Mann= 12 ,-1 , 0
  4013.7     .05       0  4343.5      .1       0  4521.1     .05       0
  4625.8     .16       0  4835.4      .1       0  4980.8     .16       0
  4988.8     .07       0  4994.8     .16       0    5045      .1       0
  5254.5     .05       0  5359.3      .1       0  5782.7     .05       0
Bank Sta=4732.3,5062.1
XS Rating Curve= 0 ,0
Exp/Cntr=0.3,0.1

Type RM Length L Ch R = 1 ,1349    ,517,517,517
BEGIN DESCRIPTION:
PALO ALTO CREEK 2.0
END DESCRIPTION:
XS GIS Cut Line= 2
        2790983.     10055679.66      2789587.19     10055381.05
#Sta/Elev= 30
  4202.5 1536.58  4237.8 1537.18  4288.9 1534.92  4329.9 1536.18    4381 1533.95
  4432.1  1534.8  4491.1 1532.45  4534.4 1533.15  4575.3 1531.12  4626.4  1531.4
  4657.1 1529.28  4728.2  1528.1  4768.1 1525.92  4841.2 1524.84  4892.3  1521.4
  4923.6 1516.51  4963.9 1507.38  5011.7 1505.97  5014.5 1505.47  5017.7 1505.97
  5026.1 1506.28  5045.7 1512.07  5076.4  1518.5  5107.1 1521.77  5163.1 1523.34
  5256.9 1528.25  5372.9 1530.31  5434.3 1533.64  5536.6 1536.44  5629.9 1537.91
#Mann= 6 ,-1 , 0
  4202.5     .05       0  4768.1      .1       0  4923.6     .16       0
  5011.7     .07       0  5017.7     .16       0  5026.1     .05       0
Bank Sta=4892.3,5107.1
XS Rating Curve= 0 ,0
Exp/Cntr=0.3,0.1

Type RM Length L Ch R = 1 ,832     ,666,666,666
BEGIN DESCRIPTION:
Mapping XS 3680e903
END DESCRIPTION:
XS GIS Cut Line= 3
      2791094.74      10055313.5      2790219.77     10054976.71
      2789633.25     10055021.82
#Sta/Elev= 30
  4186.5  1535.2  4278.4 1533.88  4363.1 1534.95  4394.3 1532.95  4439.7 1533.45
  4477.7 1531.51  4533.5 1531.42  4637.5 1527.81  4793.3 1526.56  4816.1 1525.51
  4846.9 1520.47  4889.7 1517.24  4943.1 1509.61  4955.4 1506.04  4971.7 1504.87
  4974.4 1504.37  4977.7 1504.87    5029 1507.19  5034.6 1509.81  5059.3 1516.02
  5071.9 1518.03  5075.9 1518.36  5119.3 1522.09  5122.1 1523.18  5175.5 1525.03
  5305.9 1526.66  5366.1 1528.45  5406.2 1530.95  5541.6 1534.54  5712.3 1535.13
#Mann= 8 ,-1 , 0
  4186.5     .05       0  4394.3      .1       0  4533.5     .05       0
  4637.5      .1       0  4943.1     .16       0  4971.7     .07       0
  4977.7     .16       0  5075.9     .05       0
Bank Sta=4889.7,5071.9
XS Rating Curve= 0 ,0
Exp/Cntr=0.3,0.1

Type RM Length L Ch R = 1 ,166     ,0,0,0
BEGIN DESCRIPTION:
PALO ALTO CREEK 1.0
END DESCRIPTION:
XS GIS Cut Line= 4
      2791049.65     10054841.32      2790754.49     10054448.93
      2790514.91     10054435.04       2789793.1     10054743.89
#Sta/Elev= 30
  4374.1 1531.36  4487.1 1530.94  4516.2 1528.99  4608.8 1526.49  4666.2 1522.65
  4672.4 1523.38  4734.3 1518.54  4801.5 1514.41  4816.1 1510.75  4851.5  1509.5
  4911.2 1506.85  4931.2 1503.27    4961 1502.68  4991.3 1504.03  5038.9 1503.89
  5061.5 1506.13  5081.5 1509.93  5116.4 1511.32  5139.6  1511.8    5145 1512.94
  5163.2 1512.47  5168.6 1513.88  5186.8  1513.1  5221.2 1515.63  5283.1 1516.71
  5362.3 1519.37  5444.4 1523.71  5561.5  1526.6  5749.2 1531.56  5890.2 1533.59
#Mann= 7 ,-1 , 0
  4374.1     .05       0  4734.3      .1       0  4851.5     .07       0
  5081.5     .05       0  5116.4     .16       0  5283.1      .1       0
  5561.5     .05       0
Bank Sta=4851.5,5081.5
XS Rating Curve= 0 ,0
Exp/Cntr=0.3,0.1

Chan Stop Cuts=-1
Use User Specified Reach Order=0
Composite Channel Slope=5