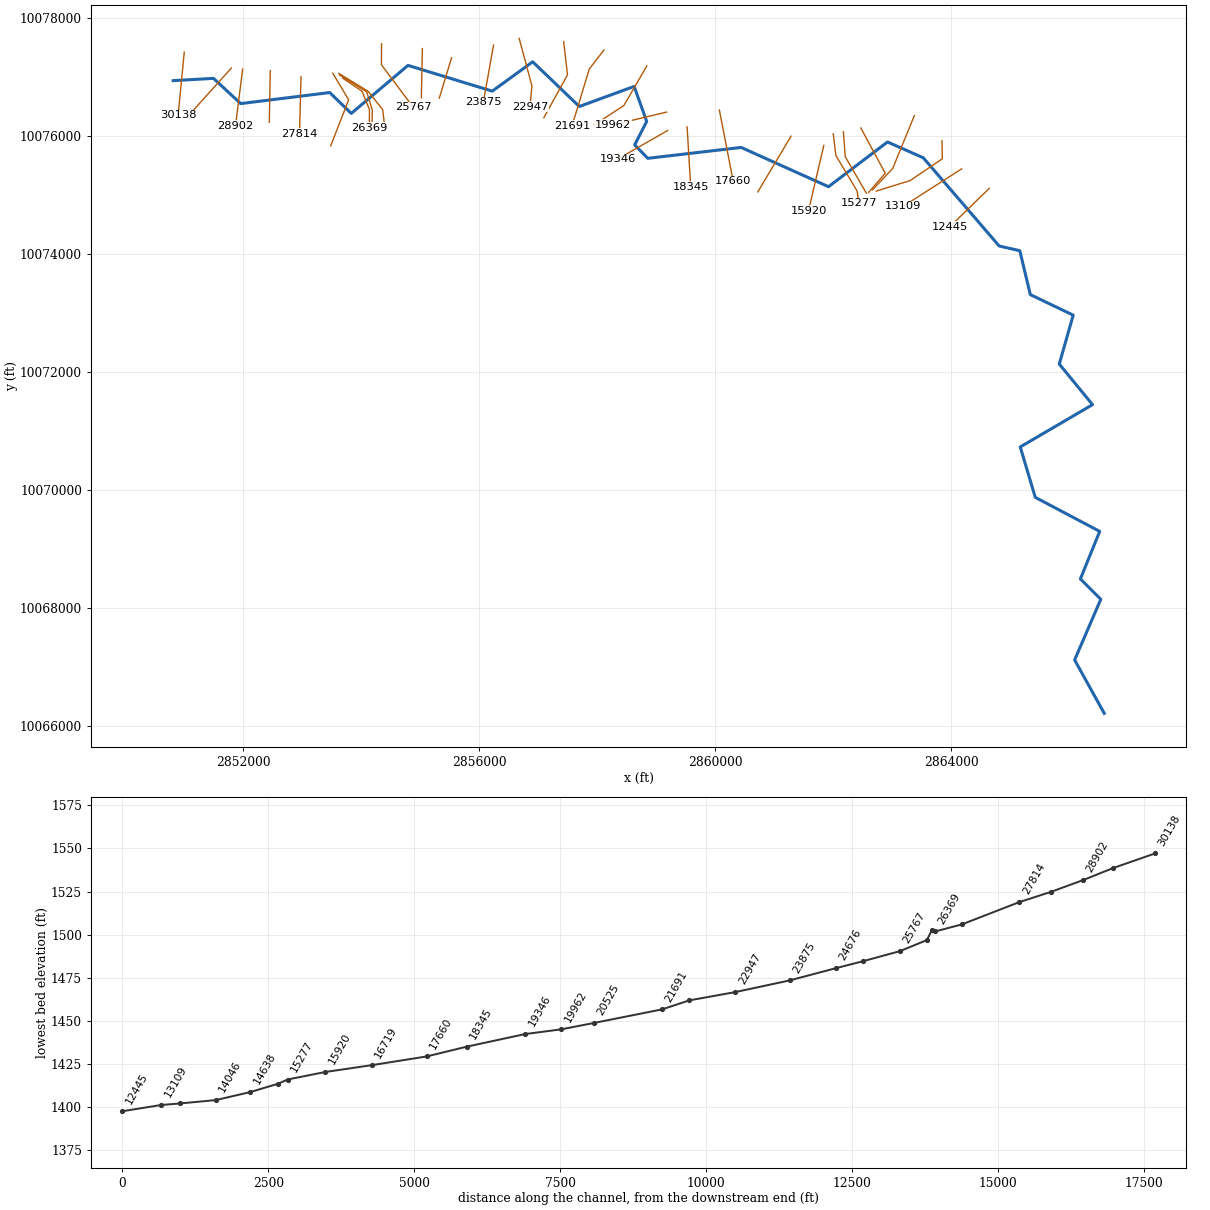
--- POST OAK CREEK.prj (project) ---

Proj Title=POST OAK CREEK Base Level Engineering
Current Plan=p01
Default Exp/Contr=0.3,0.1
English Units
Geom File=g01
Flow File=f01
Plan File=p01
Y Axis Title=Elevation
X Axis Title(PF)=Main Channel Distance
X Axis Title(XS)=Station
BEGIN DESCRIPTION:
POST OAK CREEK
END DESCRIPTION:
DSS Export Rating Curves= 0
DSS Export Rating Curve Sorted= 0
DSS Export Volume Flow Curves= 0
DXF OffsetX= 0
DXF OffsetY= 0
DXF ScaleX= 1
DXF ScaleY= 10

--- POST OAK CREEK.p01 (plan) ---

Plan Title=Multiple Run
Short Identifier=Multiple
Geom File=g01
Flow File=f01
Subcritical Flow
K Sum by GR= 0
Std Step Tol= 0.01
Critical Tol= 0.01
Num of Std Step Trials= 20
Max Error Tol= 0.3
Flow Tol Ratio= 0.001
Split Flow NTrial= 30
Split Flow Tol= 0.02
Split Flow Ratio= 0.02
Log Output Level= 0
Friction Slope Method= 1
Unsteady Friction Slope Method= 2
Unsteady Bridges Friction Slope Method= 1
Parabolic Critical Depth
Global Vel Dist=  1 , 1 , 1
Global Log Level= 0
CheckData=True
Encroach Param= -1, 0, 0, 0
BEGIN DESCRIPTION:
Multiple Run
END DESCRIPTION:

--- POST OAK CREEK.f01 (steady flow) ---

Flow Title=Multiple
Program Version=4.10
Number of Profiles= 7
Profile Names=10-year,25-year,50-year,1pct_min,100-year,1pct_plu,500-year
River Rch & RM=POST OAK CREEK,Reach-1         ,30138
     869    1263    1607    1498    2025    2739    3229
River Rch & RM=POST OAK CREEK,Reach-1         ,29419
    1416    2105    2717    2565    3468    4691    5675
River Rch & RM=POST OAK CREEK,Reach-1         ,20525
    1721    2573    3333    3154    4265    5768    7016
River Rch & RM=POST OAK CREEK,Reach-1         ,14046
    2083    3137    4083    3878    5244    7092    8692
River Rch & RM=POST OAK CREEK,Reach-1         ,9514
    2457    3721    4863    4635    6268    8476   10461
Boundary for River Rch & Prof#=POST OAK CREEK,Reach-1         , 1
Up Type= 0
Dn Type= 3
Dn Slope=0.011
Boundary for River Rch & Prof#=POST OAK CREEK,Reach-1         , 2
Up Type= 0
Dn Type= 3
Dn Slope=0.011
Boundary for River Rch & Prof#=POST OAK CREEK,Reach-1         , 3
Up Type= 0
Dn Type= 3
Dn Slope=0.011
Boundary for River Rch & Prof#=POST OAK CREEK,Reach-1         , 4
Up Type= 0
Dn Type= 3
Dn Slope=0.011
Boundary for River Rch & Prof#=POST OAK CREEK,Reach-1         , 5
Up Type= 0
Dn Type= 3
Dn Slope=0.011
Boundary for River Rch & Prof#=POST OAK CREEK,Reach-1         , 6
Up Type= 0
Dn Type= 3
Dn Slope=0.011
Boundary for River Rch & Prof#=POST OAK CREEK,Reach-1         , 7
Up Type= 0
Dn Type= 3
Dn Slope=0.011
DSS Import GetInterval= 0
DSS Import GetPeak= 0
DSS Import FillOption= 0

--- POST OAK CREEK.g01 (geometry) ---

Geom Title=Existing Conditions
Program Version=4.10

River Reach=POST OAK CREEK  ,Reach-1
Reach XY= 30
      2850808.47     10076943.73      2851492.25     10076981.87
      2851953.88     10076554.37      2853462.64     10076741.56
        2853828.     10076387.67      2854789.48      10077201.9
       2856218.5     10076765.77       2856903.1     10077263.32
      2857693.61     10076505.31      2858623.18     10076845.32
      2858836.28     10076252.01      2858632.55     10075854.62
      2858853.94     10075626.66      2860437.06     10075811.02
      2861918.33     10075145.44      2862918.47     10075903.73
      2863524.84     10075635.38      2864811.65     10074140.45
      2865160.96     10074060.28      2865339.48     10073316.17
      2866066.38     10072967.74       2865830.1     10072139.19
      2866394.24     10071450.73      2865168.76     10070733.86
      2865422.74     10069879.86      2866515.61     10069302.43
      2866188.26     10068496.65      2866534.35     10068150.85
      2866090.52      10067123.7      2866592.76     10066217.23

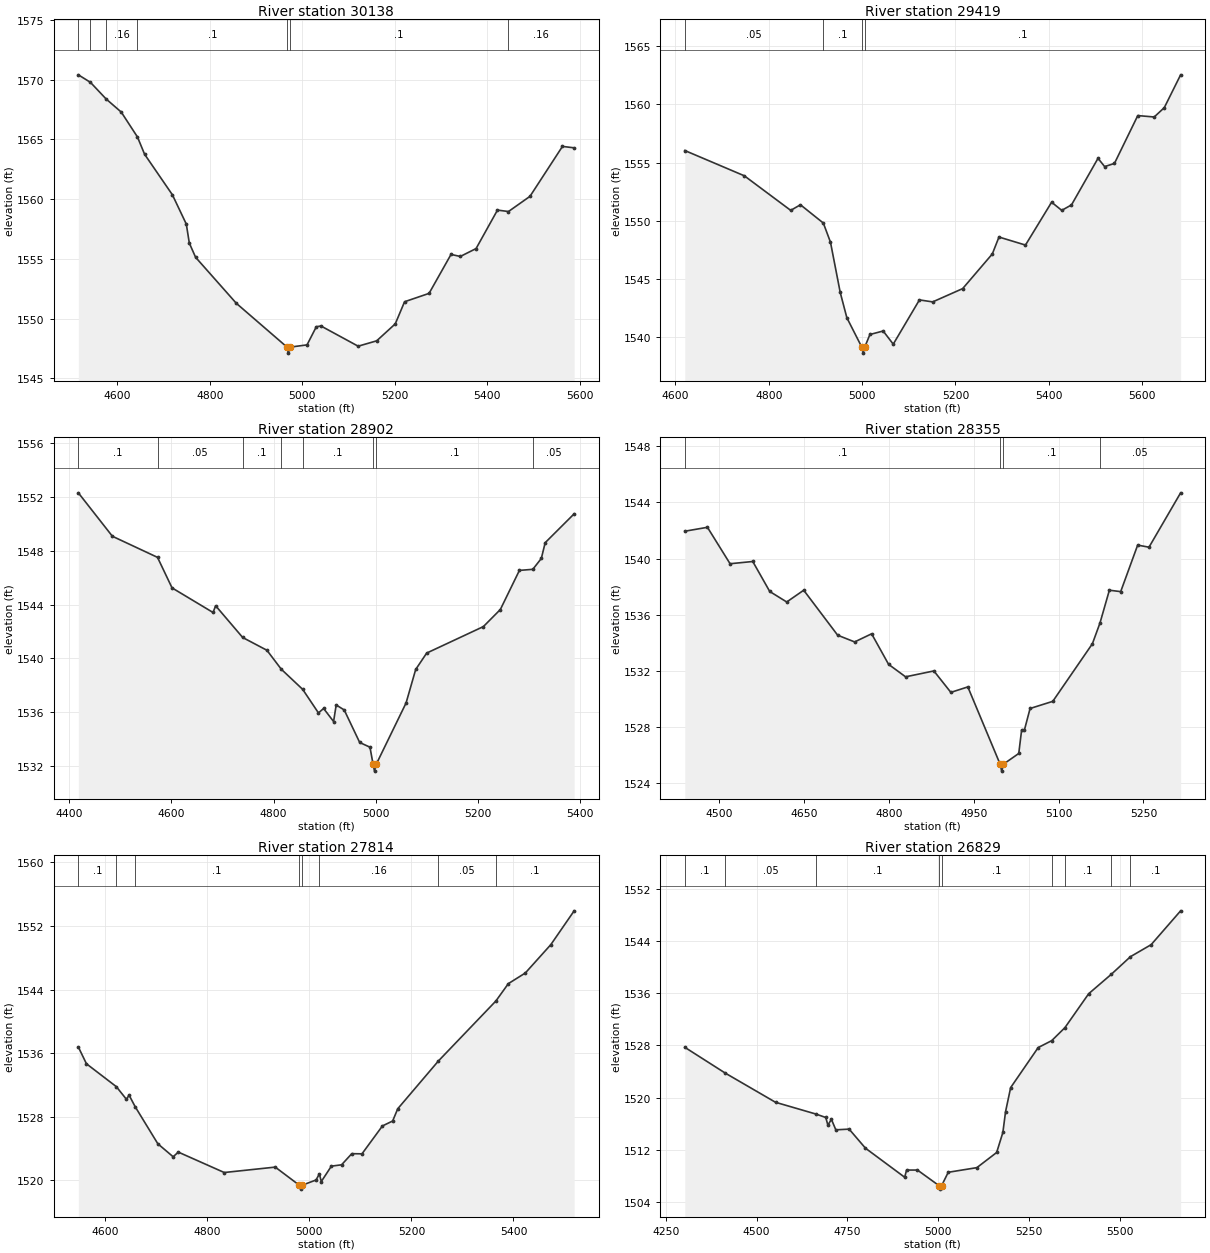
Type RM Length L Ch R = 1 ,30138   ,719,719,719
BEGIN DESCRIPTION:
POST OAK CREEK 59.0
END DESCRIPTION:
XS GIS Cut Line= 2
      2850996.92     10077426.23      2850892.76      10076358.6
#Sta/Elev= 30
  4515.3 1570.41  4541.5 1569.78  4575.4 1568.39  4608.2 1567.29  4643.2 1565.21
  4658.7 1563.76  4718.8 1560.37  4748.9 1557.92  4755.4 1556.33    4769 1555.14
  4857.1 1551.29  4966.9 1547.62  4969.7 1547.12  4972.9 1547.62  5010.1 1547.81
  5030.2 1549.33  5040.3 1549.39  5120.7  1547.7  5160.8 1548.15    5201 1549.57
  5221.1 1551.42  5274.1 1552.12  5321.6 1555.38  5341.7 1555.21  5375.8 1555.87
  5422.1 1559.09  5445.9 1558.97  5492.4 1560.24  5562.7 1564.42    5588  1564.3
#Mann= 7 ,-1 , 0
  4515.3      .1       0  4541.5     .05       0  4575.4     .16       0
  4643.2      .1       0  4966.9     .07       0  4972.9      .1       0
  5445.9     .16       0
Bank Sta=4966.9,4972.9
XS Rating Curve= 0 ,0
Exp/Cntr=0.3,0.1

Type RM Length L Ch R = 1 ,29419   ,517,517,517
BEGIN DESCRIPTION:
POST OAK CREEK 58.0
END DESCRIPTION:
XS GIS Cut Line= 2
      2851795.51     10077157.11      2851084.39     10076367.94
#Sta/Elev= 30
  4620.2 1556.03  4747.7 1553.86  4847.1 1550.89    4868 1551.37    4917  1549.8
  4932.3 1548.16  4953.2 1543.84  4967.4 1541.67  4999.6 1539.13  5002.3 1538.63
  5005.6 1539.13  5016.8 1540.23  5045.2 1540.53  5066.8  1539.4  5122.9  1543.2
  5151.3 1543.03  5215.5 1544.17  5279.1 1547.15  5293.3  1548.6  5350.1 1547.91
  5406.1 1551.59  5427.8 1550.89  5448.7 1551.36  5505.5 1555.36  5519.7 1554.65
  5540.7 1554.92  5590.7 1559.03  5625.9 1558.91  5647.5 1559.71  5682.5 1562.53
#Mann= 4 ,-1 , 0
  4620.2     .05       0    4917      .1       0  4999.6     .07       0
  5005.6      .1       0
Bank Sta=4999.6,5005.6
XS Rating Curve= 0 ,0
Exp/Cntr=0.3,0.1

Type RM Length L Ch R = 1 ,28902   ,547,547,547
BEGIN DESCRIPTION:
POST OAK CREEK 57.0
END DESCRIPTION:
XS GIS Cut Line= 2
       2851986.5     10077139.77      2851865.13     10076177.49
#Sta/Elev= 30
  4418.1 1552.32  4484.7 1549.09    4573 1547.52  4601.4 1545.25  4681.6 1543.42
  4686.7 1543.92  4739.6 1541.56    4787 1540.61  4815.1  1539.2    4857  1537.7
  4887.8 1535.95  4897.9 1536.28  4917.4 1535.31  4922.5 1536.54  4938.2 1536.17
  4968.5 1533.75  4988.6  1533.4  4994.7 1532.12  4997.5 1531.62  5000.7 1532.12
  5059.2 1536.69    5078 1539.18  5099.5  1540.4  5210.4 1542.37  5243.6 1543.64
  5280.9 1546.55  5307.1 1546.63  5323.8 1547.44  5331.3 1548.61    5388 1550.76
#Mann= 8 ,-1 , 0
  4418.1      .1       0    4573     .05       0  4739.6      .1       0
  4815.1     .05       0    4857      .1       0  4994.7     .07       0
  5000.7      .1       0  5307.1     .05       0
Bank Sta=4994.7,5000.7
XS Rating Curve= 0 ,0
Exp/Cntr=0.3,0.1

Type RM Length L Ch R = 1 ,28355   ,541,541,541
BEGIN DESCRIPTION:
POST OAK CREEK 56.0
END DESCRIPTION:
XS GIS Cut Line= 2
      2852455.25     10077113.76      2852437.91     10076237.83
#Sta/Elev= 30
  4439.6 1541.95  4479.6 1542.23  4519.6 1539.63  4559.7 1539.79  4589.7 1537.65
  4619.7  1536.9  4649.7 1537.74  4709.7 1534.53  4739.7 1534.05  4769.7 1534.63
  4799.7 1532.45  4829.7 1531.56  4879.7 1531.98  4909.7 1530.45  4939.7 1530.84
  4996.7 1525.33  4999.5 1524.83  5002.7 1525.33  5029.7 1526.09  5034.8 1527.78
  5039.8 1527.78  5049.7  1529.3  5089.8 1529.81  5159.8 1533.92  5173.2  1535.4
  5189.8 1537.74  5209.8 1537.64  5239.8 1540.96  5259.8 1540.81  5315.7 1544.69
#Mann= 4 ,-1 , 0
  4439.6      .1       0  4996.7     .07       0  5002.7      .1       0
  5173.2     .05       0
Bank Sta=4996.7,5002.7
XS Rating Curve= 0 ,0
Exp/Cntr=0.3,0.1

Type RM Length L Ch R = 1 ,27814   ,985,985,985
BEGIN DESCRIPTION:
POST OAK CREEK 55.0
END DESCRIPTION:
XS GIS Cut Line= 2
      2852976.09     10077009.58      2852950.06     10076038.03
#Sta/Elev= 30
  4547.1 1536.78    4563 1534.67  4621.6 1531.79  4641.5 1530.19  4646.5 1530.73
  4658.4 1529.28    4703  1524.6    4733 1522.97    4743 1523.56  4833.1 1520.99
  4933.1 1521.67  4980.1  1519.4  4982.9  1518.9  4986.1  1519.4  5013.1 1520.05
  5019.6 1520.83  5023.3 1519.85  5043.1 1521.79  5063.1 1521.96  5083.1 1523.36
  5103.1 1523.34  5143.2 1526.85  5163.2 1527.47  5173.2 1529.01  5252.9 1535.02
  5365.6 1542.57    5390 1544.75  5423.3 1546.09  5473.3 1549.66    5519 1553.91
#Mann= 8 ,-1 , 0
  4547.1      .1       0  4621.6     .16       0  4658.4      .1       0
  4980.1     .07       0  4986.1      .1       0  5019.6     .16       0
  5252.9     .05       0  5365.6      .1       0
Bank Sta=4980.1,4986.1
XS Rating Curve= 0 ,0
Exp/Cntr=0.3,0.1

Type RM Length L Ch R = 1 ,26829   ,460,460,460
BEGIN DESCRIPTION:
POST OAK CREEK 53.0
END DESCRIPTION:
XS GIS Cut Line= 3
      2853514.26     10077070.36      2853783.38     10076618.94
      2853479.78     10075838.25
#Sta/Elev= 30
  4302.7 1527.69  4413.9 1523.74  4552.1 1519.27  4663.7 1517.46  4690.3 1516.94
  4696.1 1515.77  4705.8 1516.66  4717.9 1515.05  4754.5 1515.16  4799.4 1512.24
  4907.2 1507.79  4912.5 1508.89  4942.4 1508.89  5002.5 1506.47  5005.3 1505.97
  5008.5 1506.47    5027 1508.55  5105.7 1509.26  5160.1 1511.58  5177.2 1514.65
  5184.6 1517.84  5198.6 1521.52  5274.3 1527.65  5311.5 1528.71  5347.8  1530.7
  5413.2  1535.9  5475.3 1538.87    5528 1541.57  5584.9 1543.41  5665.9 1548.59
#Mann= 9 ,-1 , 0
  4302.7      .1       0  4413.9     .05       0  4663.7      .1       0
  5002.5     .07       0  5008.5      .1       0  5311.5     .05       0
  5347.8      .1       0  5475.3     .05       0    5528      .1       0
Bank Sta=5002.5,5008.5
XS Rating Curve= 0 ,0
Exp/Cntr=0.3,0.1

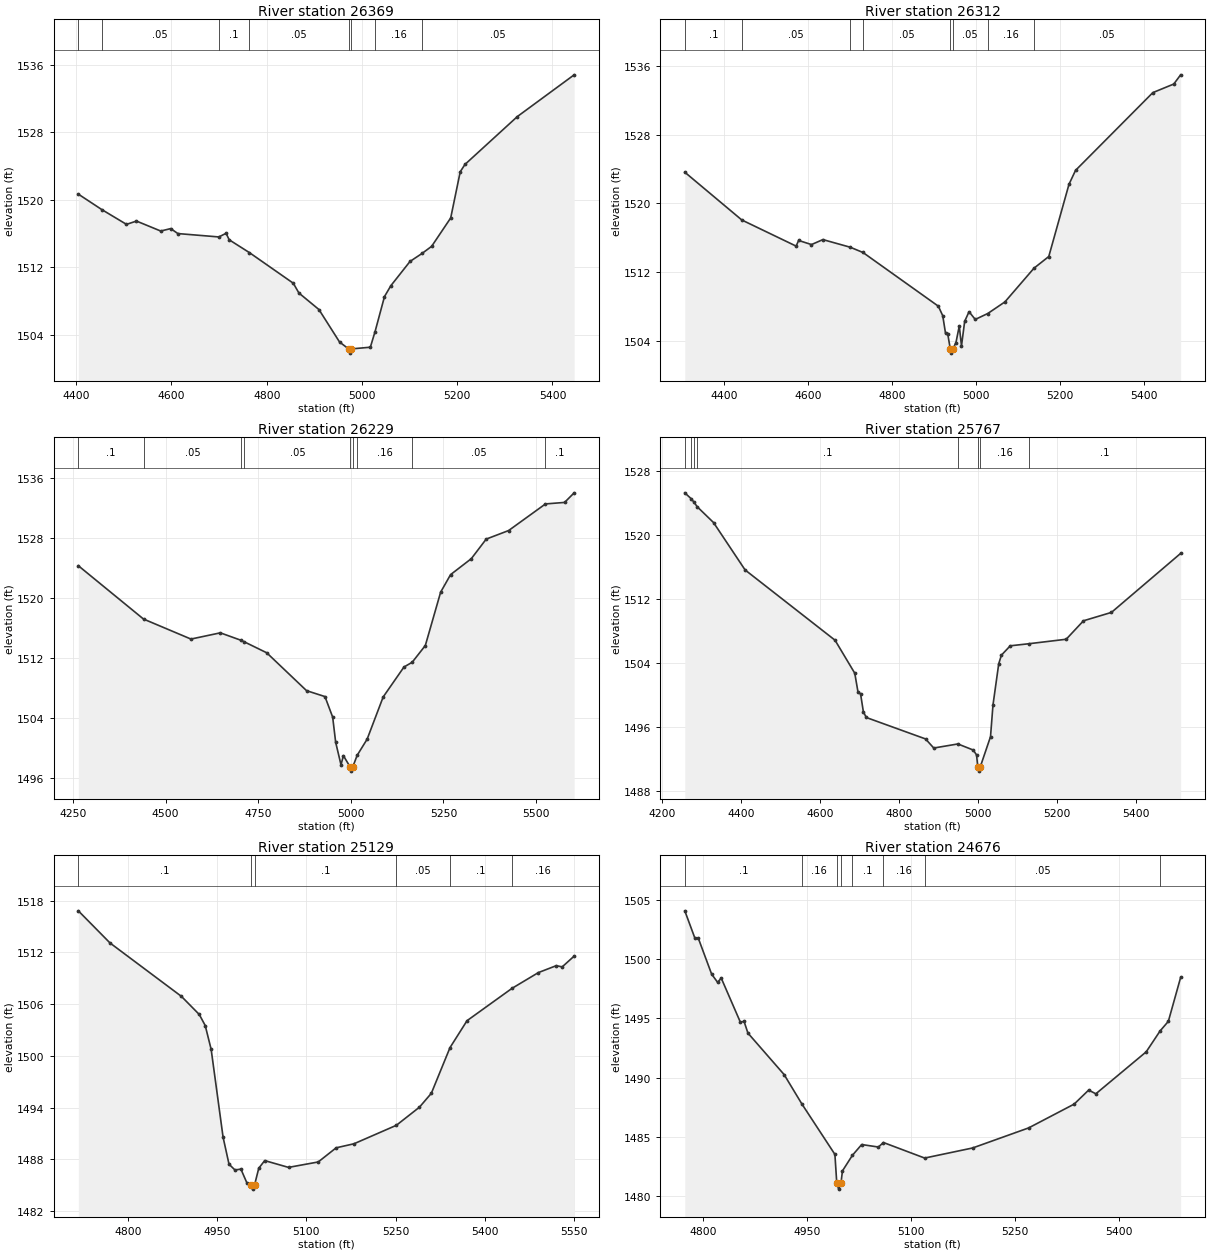
Type RM Length L Ch R = 1 ,26369   ,57,57,57
BEGIN DESCRIPTION:
Mapping XS 9336ed1d
END DESCRIPTION:
XS GIS Cut Line= 4
      2853681.56     10076986.57      2854010.32     10076764.14
      2854136.19     10076452.73      2854134.02     10076144.56
#Sta/Elev= 30
  4404.5 1520.67  4453.5 1518.85  4505.6 1517.09  4526.6 1517.48  4577.5  1516.3
  4598.5 1516.59  4613.4    1516  4699.5  1515.6  4714.7 1516.03  4721.3 1515.26
  4763.8 1513.74  4855.8 1510.12  4867.6 1508.96  4909.7    1507  4952.9 1503.16
  4971.9 1502.34  4974.6 1501.84  4977.9 1502.34  5017.6 1502.54  5027.5 1504.39
  5047.3 1508.54  5060.7 1509.83  5100.9  1512.7    5126 1513.64  5146.3 1514.49
  5186.3 1517.85  5206.3 1523.32  5216.3 1524.19  5326.3 1529.86  5445.5  1534.8
#Mann= 8 ,-1 , 0
  4404.5      .1       0  4453.5     .05       0  4699.5      .1       0
  4763.8     .05       0  4971.9    .035       0  4977.9     .05       0
  5027.5     .16       0    5126     .05       0
Bank Sta=4971.9,4977.9
XS Rating Curve= 0 ,0
Exp/Cntr=0.3,0.1

Type RM Length L Ch R = 1 ,26312   ,83,83,83
BEGIN DESCRIPTION:
Mapping XS 3a1ec25b
END DESCRIPTION:
XS GIS Cut Line= 4
      2853629.42     10077039.78      2854089.53     10076754.38
      2854185.02     10076441.88      2854177.45     10076127.47
#Sta/Elev= 30
  4305.4 1523.63  4441.4 1518.07    4571 1515.03  4576.9 1515.69  4607.6 1515.21
  4634.8 1515.79  4700.1  1514.9  4730.4 1514.29  4910.2 1508.04  4920.7 1506.93
  4927.3 1504.89  4932.6 1504.81  4938.6 1503.08  4941.4 1502.58  4944.6 1503.08
  4952.1 1503.78  4960.1 1505.73  4965.4 1503.42    4973 1506.28  4983.4  1507.4
  4998.2  1506.5  5028.1 1507.19    5069 1508.54  5138.3 1512.46  5173.6 1513.82
  5221.8 1522.22  5237.4 1523.84  5421.8 1532.89  5471.8 1533.89  5488.1 1534.96
#Mann= 8 ,-1 , 0
  4305.4      .1       0  4441.4     .05       0  4700.1      .1       0
  4730.4     .05       0  4938.6    .035       0  4944.6     .05       0
  5028.1     .16       0  5138.3     .05       0
Bank Sta=4938.6,4944.6
XS Rating Curve= 0 ,0
Exp/Cntr=0.3,0.1

Type RM Length L Ch R = 1 ,26229   ,462,462,462
BEGIN DESCRIPTION:
POST OAK CREEK 51.0
END DESCRIPTION:
XS GIS Cut Line= 4
      2853614.48     10077067.37      2854115.78     10076761.37
      2854361.01     10076451.04      2854402.16     10076097.97
#Sta/Elev= 30
  4264.4 1524.25  4440.3 1517.14  4568.4 1514.47  4647.7  1515.3  4703.9  1514.3
  4712.8 1514.09  4772.9 1512.64  4880.4 1507.59  4930.1  1506.8  4950.9 1504.06
    4959  1500.7  4973.4  1497.7  4979.8 1498.93  4998.7 1497.36  5001.4 1496.86
  5004.7 1497.36    5017 1498.97  5043.9 1501.12  5087.2 1506.75  5143.3 1510.74
  5165.6 1511.38    5201 1513.61  5242.3 1520.72  5269.1 1523.06  5325.1 1525.19
  5365.3  1527.8  5425.8 1528.94  5525.3 1532.49  5576.8 1532.69  5602.7 1533.97
#Mann= 9 ,-1 , 0
  4264.4      .1       0  4440.3     .05       0  4703.9      .1       0
  4712.8     .05       0  4998.7    .035       0  5004.7     .05       0
    5017     .16       0  5165.6     .05       0  5525.3      .1       0
Bank Sta=4998.7,5004.7
XS Rating Curve= 0 ,0
Exp/Cntr=0.3,0.1

Type RM Length L Ch R = 1 ,25767   ,638,638,638
BEGIN DESCRIPTION:
POST OAK CREEK 50.0
END DESCRIPTION:
XS GIS Cut Line= 3
      2854341.47     10077566.51       2854339.3     10077212.76
      2854879.67      10076490.1
#Sta/Elev= 30
    4257 1525.26  4273.9 1524.49  4280.8 1524.05  4288.6 1523.51  4329.8 1521.54
  4409.8 1515.61  4637.6 1506.82  4687.6 1502.69  4695.9  1500.3  4702.2 1500.13
  4709.4 1497.86  4716.8 1497.15  4866.8 1494.47  4887.7 1493.33  4948.8 1493.84
  4987.7 1493.08  4996.1 1492.47  4999.3 1490.94  5002.1 1490.44  5005.3 1490.94
  5031.5 1494.75  5037.7  1498.7  5052.3 1503.87  5059.1 1504.95  5081.5 1506.12
  5128.9 1506.38  5223.2 1506.94    5267 1509.25  5337.9  1510.3  5513.1 1517.68
#Mann= 8 ,-1 , 0
    4257     .16       0  4273.9      .1       0  4280.8     .16       0
  4288.6      .1       0  4948.8     .16       0  4999.3     .07       0
  5005.3     .16       0  5128.9      .1       0
Bank Sta=4999.3,5005.3
XS Rating Curve= 0 ,0
Exp/Cntr=0.3,0.1

Type RM Length L Ch R = 1 ,25129   ,453,453,453
BEGIN DESCRIPTION:
POST OAK CREEK 49.0
END DESCRIPTION:
XS GIS Cut Line= 2
      2855033.38     10077486.99      2855016.02     10076653.67
#Sta/Elev= 30
  4716.6 1516.81  4769.9 1513.08  4889.9 1506.89  4919.9 1504.79  4929.9 1503.51
  4939.9 1500.74  4959.9 1490.57  4969.9 1487.43  4979.9 1486.76  4989.9 1486.86
  4999.9 1485.27  5006.9 1485.04  5009.7 1484.54  5012.9 1485.04  5019.9 1486.96
  5029.9 1487.85  5069.9 1487.06  5119.9 1487.69    5150 1489.33    5180  1489.8
  5251.2 1491.94    5290 1494.04    5310 1495.65  5341.4 1500.95    5370 1504.07
  5445.6 1507.82    5490 1509.65    5520 1510.45    5530 1510.31  5550.1 1511.56
#Mann= 6 ,-1 , 0
  4716.6      .1       0  5006.9     .07       0  5012.9      .1       0
  5251.2     .05       0  5341.4      .1       0  5445.6     .16       0
Bank Sta=5006.9,5012.9
XS Rating Curve= 0 ,0
Exp/Cntr=0.3,0.1

Type RM Length L Ch R = 1 ,24676   ,801,801,801
BEGIN DESCRIPTION:
POST OAK CREEK 48.0
END DESCRIPTION:
XS GIS Cut Line= 2
      2855528.17     10077330.76      2855320.39     10076646.82
#Sta/Elev= 30
  4773.6 1504.08    4788  1501.8  4793.2 1501.75  4812.3 1498.74  4820.9 1498.05
  4826.1 1498.41  4853.7 1494.69    4859 1494.76  4864.6 1493.77  4916.8 1490.27
  4942.2 1487.81    4990 1483.54  4992.7 1481.11  4995.4 1480.61  4998.7 1481.11
  5000.9 1482.15  5015.2 1483.46  5028.6 1484.37  5052.7 1484.16    5060 1484.54
  5119.4 1483.23  5188.5 1484.08  5269.2 1485.77  5334.9 1487.78  5355.8 1488.96
  5366.2 1488.65  5438.8 1492.19  5458.8 1493.95  5470.7 1494.76  5488.4 1498.46
#Mann= 8 ,-1 , 0
  4773.6      .1       0  4942.2     .16       0  4992.7     .07       0
  4998.7     .16       0  5015.2      .1       0    5060     .16       0
  5119.4     .05       0  5458.8     .16       0
Bank Sta=4992.7,4998.7
XS Rating Curve= 0 ,0
Exp/Cntr=0.3,0.1

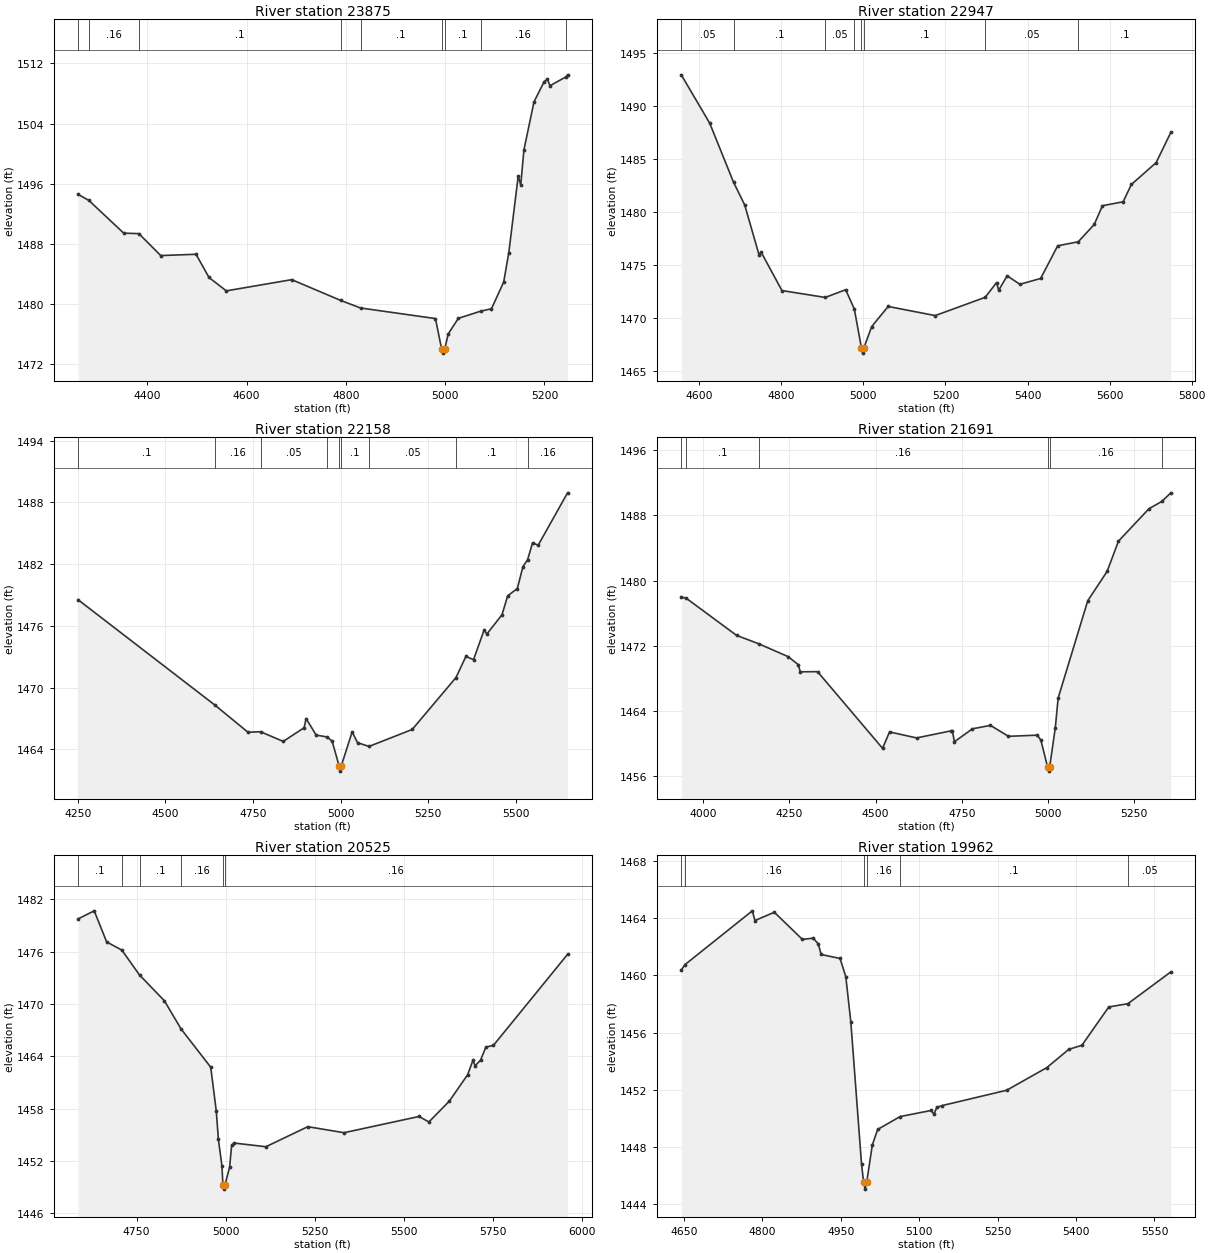
Type RM Length L Ch R = 1 ,23875   ,928,928,928
BEGIN DESCRIPTION:
POST OAK CREEK 46.0
END DESCRIPTION:
XS GIS Cut Line= 2
      2856239.97     10077547.72      2856066.65     10076577.17
#Sta/Elev= 30
  4260.6 1494.57  4282.4 1493.76  4352.7  1489.4  4383.1 1489.34  4427.2 1486.42
  4498.3 1486.59  4524.4  1483.5  4559.2 1481.72    4691 1483.21  4789.9 1480.44
  4829.5 1479.44  4980.5 1478.03    4993 1473.93  4995.8 1473.43    4999 1473.93
  5006.2 1475.99  5026.5 1478.06  5071.3 1479.01  5093.3 1479.34  5117.9  1482.9
  5128.1 1486.78  5147.1    1497  5152.2 1495.81  5158.6 1500.48  5178.9 1506.88
  5199.2 1509.55    5206 1509.89  5211.1 1509.03  5243.4 1510.21  5246.5 1510.48
#Mann= 9 ,-1 , 0
  4260.6     .05       0  4282.4     .16       0  4383.1      .1       0
  4789.9     .05       0  4829.5      .1       0    4993     .07       0
    4999      .1       0  5071.3     .16       0  5243.4      .1       0
Bank Sta=4993,4999
XS Rating Curve= 0 ,0
Exp/Cntr=0.3,0.1

Type RM Length L Ch R = 1 ,22947   ,789,789,789
BEGIN DESCRIPTION:
POST OAK CREEK 45.0
END DESCRIPTION:
XS GIS Cut Line= 3
        2856674.     10077660.61      2856891.02     10076853.31
      2856856.36     10076498.05
#Sta/Elev= 30
  4556.3 1492.93  4625.5 1488.38  4683.6 1482.81  4710.9 1480.66  4745.7 1475.97
  4750.9 1476.21  4801.6 1472.59  4907.1 1471.94  4956.9 1472.67    4978 1470.85
  4995.3 1467.19  4998.1 1466.69  5001.3 1467.19  5020.4  1469.2  5060.5 1471.09
  5175.1 1470.23  5296.8 1471.95  5324.6 1473.34  5329.8 1472.62  5350.4 1473.98
  5381.5 1473.18    5432 1473.73  5473.6 1476.81  5523.7 1477.19  5562.6 1478.82
  5582.7 1480.59    5633 1480.96  5653.1 1482.59  5713.4 1484.65  5749.2  1487.5
#Mann= 8 ,-1 , 0
  4556.3     .05       0  4683.6      .1       0  4907.1     .05       0
    4978      .1       0  4995.3     .07       0  5001.3      .1       0
  5296.8     .05       0  5523.7      .1       0
Bank Sta=4995.3,5001.3
XS Rating Curve= 0 ,0
Exp/Cntr=0.3,0.1

Type RM Length L Ch R = 1 ,22158   ,467,467,467
BEGIN DESCRIPTION:
POST OAK CREEK 44.0
END DESCRIPTION:
XS GIS Cut Line= 3
      2857428.43      10077605.6      2857493.53     10077041.37
      2857092.76     10076315.65
#Sta/Elev= 30
  4250.5 1478.54  4642.3 1468.26  4735.6 1465.65  4771.4  1465.7  4836.1 1464.76
  4895.7 1466.09  4901.4 1466.98    4930 1465.38  4961.3 1465.19  4975.7 1464.78
  4995.6 1462.37  4998.3 1461.87  5001.6 1462.37  5032.8 1465.68  5048.1 1464.64
  5080.8 1464.27  5204.2 1465.92  5329.1 1470.97  5357.4 1473.02  5379.2 1472.71
  5409.8 1475.63    5417 1475.19  5460.5 1477.08  5476.6 1478.92  5504.1 1479.62
  5520.1 1481.74  5533.6 1482.44  5547.6 1484.06  5563.7 1483.84  5647.5 1488.93
#Mann= 9 ,-1 , 0
  4250.5      .1       0  4642.3     .16       0  4771.4     .05       0
  4961.3      .1       0  4995.6     .07       0  5001.6      .1       0
  5080.8     .05       0  5329.1      .1       0  5533.6     .16       0
Bank Sta=4995.6,5001.6
XS Rating Curve= 0 ,0
Exp/Cntr=0.3,0.1

Type RM Length L Ch R = 1 ,21691   ,1166,1166,1166
BEGIN DESCRIPTION:
POST OAK CREEK 43.0
END DESCRIPTION:
XS GIS Cut Line= 3
      2858112.05     10077464.59      2857862.45     10077139.03
      2857569.49     10076173.32
#Sta/Elev= 30
  3936.4    1478  3950.9 1477.85  4096.7  1473.3  4160.8 1472.27  4246.3 1470.69
  4275.3 1469.72  4281.6 1468.83  4331.5 1468.85    4520 1459.45  4540.3 1461.46
  4618.7 1460.72  4717.4 1461.58  4722.6 1461.54  4728.4 1460.25  4780.6 1461.84
  4832.9 1462.26  4885.1 1460.92  4968.7 1461.06  4979.2 1460.44  4998.5 1457.15
  5001.2 1456.65  5004.5 1457.15    5021    1462  5029.1  1465.6    5115 1477.55
  5171.2 1481.15  5204.1 1484.86  5292.7 1488.84  5330.1 1489.73  5355.8 1490.78
#Mann= 6 ,-1 , 0
  3936.4     .16       0  3950.9      .1       0  4160.8     .16       0
  4998.5     .07       0  5004.5     .16       0  5330.1      .1       0
Bank Sta=4998.5,5004.5
XS Rating Curve= 0 ,0
Exp/Cntr=0.3,0.1

Type RM Length L Ch R = 1 ,20525   ,563,563,563
BEGIN DESCRIPTION:
Mapping XS 412fd644
END DESCRIPTION:
XS GIS Cut Line= 3
        2858839.     10077193.25      2858448.39     10076520.54
      2857949.25     10076195.01
#Sta/Elev= 30
  4585.8 1479.75  4631.2 1480.68  4666.2 1477.11  4708.7 1476.18  4758.5 1473.32
  4828.1 1470.37  4875.1 1467.13  4958.2 1462.75  4973.9 1457.69  4979.7 1454.47
  4989.7 1451.43  4992.4 1449.27  4995.2 1448.77  4998.4 1449.27  5011.2 1451.28
    5017 1453.83  5024.7 1454.05    5113 1453.63  5230.6 1455.93  5332.4 1455.24
  5542.7  1457.1  5570.5 1456.47  5627.8 1458.86  5679.1 1461.88  5694.2 1463.55
  5700.2 1462.92  5715.3 1463.55  5730.4 1465.06  5751.5 1465.25  5959.6 1475.69
#Mann= 6 ,-1 , 0
  4585.8      .1       0  4708.7     .16       0  4758.5      .1       0
  4875.1     .16       0  4992.4     .07       0  4998.4     .16       0
Bank Sta=4992.4,4998.4
XS Rating Curve= 0 ,0
Exp/Cntr=0.3,0.1

Type RM Length L Ch R = 1 ,19962   ,616,616,616
BEGIN DESCRIPTION:
POST OAK CREEK 41.0
END DESCRIPTION:
XS GIS Cut Line= 2
        2859174.      10076410.6      2858262.96     10076193.69
#Sta/Elev= 30
  4644.8 1460.38  4651.9 1460.75  4780.7 1464.51  4785.8 1463.83  4822.8 1464.41
  4876.6 1462.51  4897.2  1462.6  4907.1 1462.19  4912.3 1461.46  4948.6 1461.18
  4959.6  1459.9  4969.2 1456.73  4989.7 1446.79  4993.6 1445.56  4996.3 1445.06
  4999.6 1445.56  5010.3 1448.15  5020.5 1449.23  5063.4 1450.13    5123 1450.56
  5128.1 1450.29  5133.6 1450.77  5143.9  1450.9  5267.3 1451.97    5344 1453.55
  5386.2 1454.83  5411.2 1455.11  5462.6 1457.79  5499.2 1458.02  5581.3 1460.24
#Mann= 6 ,-1 , 0
  4644.8      .1       0  4651.9     .16       0  4993.6     .07       0
  4999.6     .16       0  5063.4      .1       0  5499.2     .05       0
Bank Sta=4993.6,4999.6
XS Rating Curve= 0 ,0
Exp/Cntr=0.3,0.1

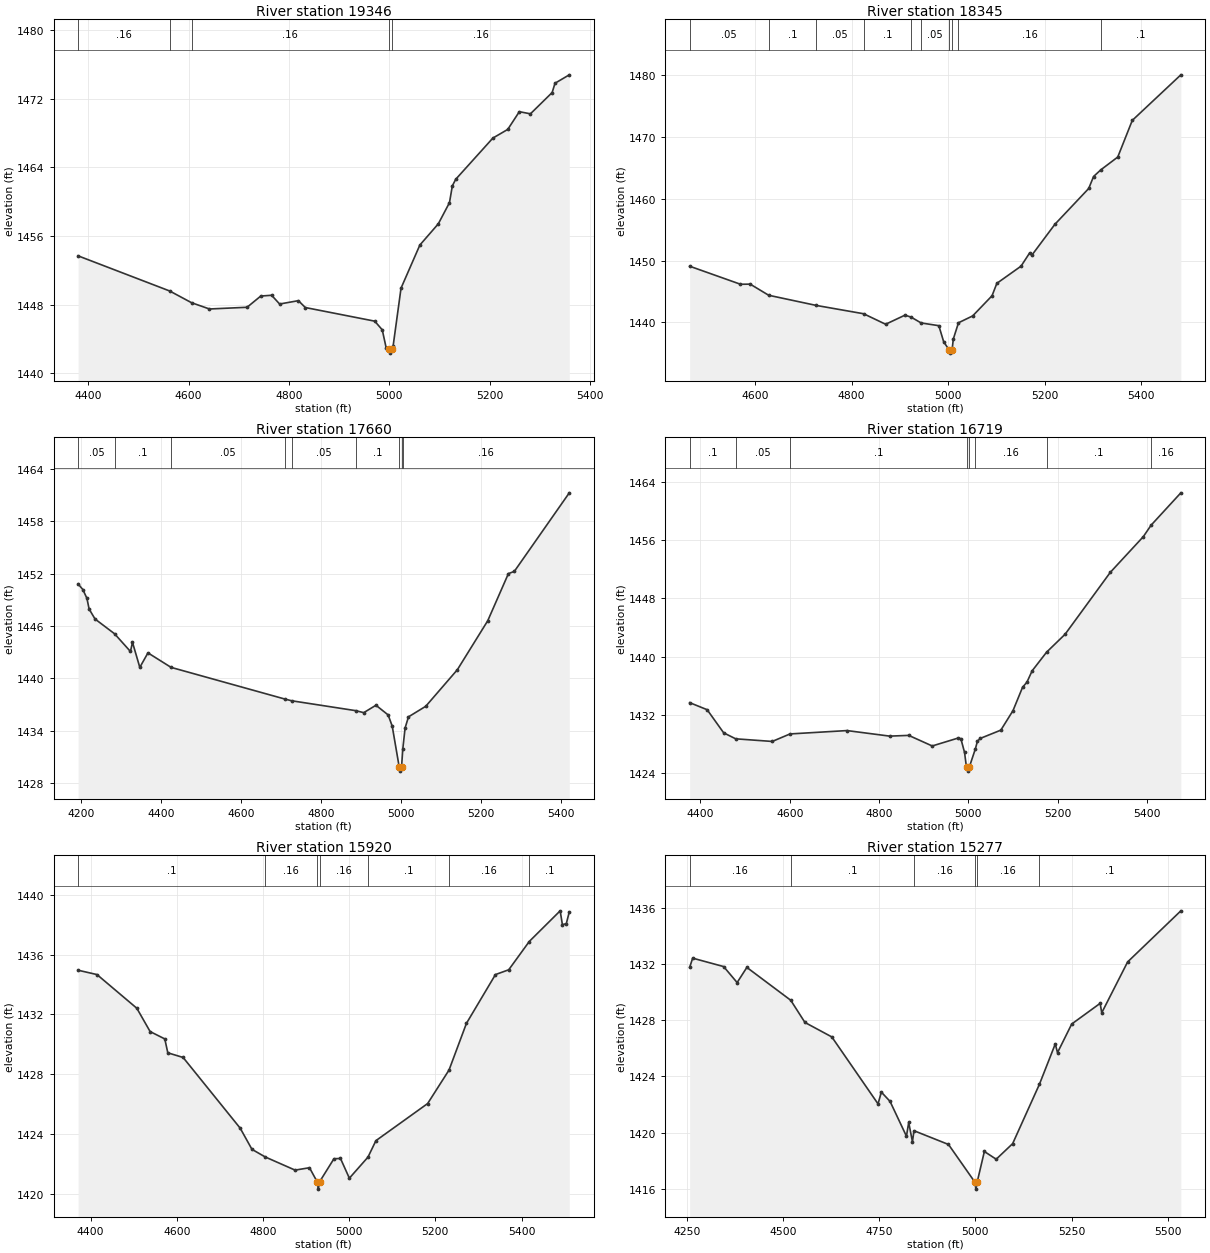
Type RM Length L Ch R = 1 ,19346   ,1001,1001,1001
BEGIN DESCRIPTION:
POST OAK CREEK 40.0
END DESCRIPTION:
XS GIS Cut Line= 2
      2859191.36      10076098.1      2858342.04     10075612.78
#Sta/Elev= 30
    4380 1453.68  4562.4 1449.58    4606 1448.21  4641.6 1447.48  4716.5 1447.68
  4743.8 1448.99  4765.4 1449.08  4781.3 1448.06  4818.7 1448.45  4832.5 1447.65
  4970.7 1446.06  4985.7 1445.05  4993.8 1442.87  4998.5 1442.83  5001.3 1442.33
  5004.5 1442.83  5007.3 1443.13  5023.1 1449.91  5060.6 1454.94  5097.4 1457.42
  5119.6 1459.89  5125.3 1461.85    5132 1462.61    5206 1467.42  5235.6 1468.43
  5258.7  1470.5  5280.8 1470.25    5324 1472.73  5329.8 1473.82  5358.2  1474.8
#Mann= 5 ,-1 , 0
    4380     .16       0  4562.4     .05       0    4606     .16       0
  4998.5     .07       0  5004.5     .16       0
Bank Sta=4998.5,5004.5
XS Rating Curve= 0 ,0
Exp/Cntr=0.3,0.1

Type RM Length L Ch R = 1 ,18345   ,685,685,685
BEGIN DESCRIPTION:
POST OAK CREEK 39.0
END DESCRIPTION:
XS GIS Cut Line= 2
      2859521.22     10076158.87      2859581.98     10075143.29
#Sta/Elev= 30
  4464.7 1449.08    4570 1446.16  4590.1 1446.18  4628.4 1444.38  4726.7 1442.74
    4825 1441.39  4870.6 1439.69  4910.6 1441.16  4923.2 1440.85  4944.2  1439.9
  4980.8 1439.46  4990.8 1436.87  5002.2 1435.52  5004.9 1435.02  5008.2 1435.52
  5010.8  1437.3  5021.5 1439.93  5050.9 1441.04    5091  1444.3    5101 1446.31
  5151.1 1449.09  5169.1 1451.25  5174.1 1450.93  5221.2 1455.86  5291.3 1461.66
  5301.3 1463.59  5316.3 1464.67  5351.4 1466.74  5381.5 1472.67  5482.1 1480.04
#Mann= 10 ,-1 , 0
  4464.7     .05       0  4628.4      .1       0  4726.7     .05       0
    4825      .1       0  4923.2     .16       0  4944.2     .05       0
  5002.2    .035       0  5008.2     .05       0  5021.5     .16       0
  5316.3      .1       0
Bank Sta=5002.2,5008.2
XS Rating Curve= 0 ,0
Exp/Cntr=0.3,0.1

Type RM Length L Ch R = 1 ,17660   ,941,941,941
BEGIN DESCRIPTION:
POST OAK CREEK 37.0
END DESCRIPTION:
XS GIS Cut Line= 2
       2860068.1     10076445.31      2860302.47     10075238.76
#Sta/Elev= 30
  4192.1 1450.81  4203.9 1450.17  4214.1 1449.17  4219.7 1447.93  4234.5 1446.79
  4283.3  1445.1  4323.1 1443.07  4328.2 1444.12  4346.5 1441.25  4366.9 1442.91
  4424.7 1441.25  4710.2 1437.61  4726.7 1437.42  4886.7 1436.29  4906.9 1436.06
  4937.4 1436.91  4967.9  1435.8  4978.1 1434.52  4995.5 1429.86  4998.2 1429.36
  5001.5 1429.86  5004.6  1431.9  5010.3  1434.3  5018.8 1435.58    5062 1436.79
  5141.1 1440.98  5217.1 1446.59  5268.8 1451.99  5283.7 1452.25  5421.2 1461.25
#Mann= 9 ,-1 , 0
  4192.1     .05       0  4283.3      .1       0  4424.7     .05       0
  4710.2      .1       0  4726.7     .05       0  4886.7      .1       0
  4995.5     .07       0  5001.5      .1       0  5004.6     .16       0
Bank Sta=4995.5,5001.5
XS Rating Curve= 0 ,0
Exp/Cntr=0.3,0.1

Type RM Length L Ch R = 1 ,16719   ,799,799,799
BEGIN DESCRIPTION:
POST OAK CREEK 35.0
END DESCRIPTION:
XS GIS Cut Line= 2
       2861283.4     10076002.66       2860719.8     10075057.55
#Sta/Elev= 30
  4375.8 1433.68    4415 1432.71    4452 1429.54  4478.9 1428.72  4560.8 1428.36
  4600.7 1429.39  4728.4 1429.85  4823.8 1429.09  4866.6 1429.19  4919.2 1427.74
  4977.5 1428.83  4983.4 1428.73  4991.6 1426.86    4996 1424.79  4998.7 1424.29
    5002 1424.79    5016 1427.37  5020.4 1428.38  5026.6 1428.77  5072.9 1429.91
  5100.2 1432.59  5121.6 1435.79  5131.3 1436.48    5143 1438.04  5175.4  1440.6
  5216.9 1443.06  5318.2 1451.55  5392.1 1456.44  5409.5 1458.01  5476.2 1462.45
#Mann= 8 ,-1 , 0
  4375.8      .1       0  4478.9     .05       0  4600.7      .1       0
    4996     .07       0    5002      .1       0    5016     .16       0
  5175.4      .1       0  5409.5     .16       0
Bank Sta=4996,5002
XS Rating Curve= 0 ,0
Exp/Cntr=0.3,0.1

Type RM Length L Ch R = 1 ,15920   ,643,643,643
BEGIN DESCRIPTION:
POST OAK CREEK 33.0
END DESCRIPTION:
XS GIS Cut Line= 2
      2861838.94     10075846.38      2861578.91     10074736.95
#Sta/Elev= 30
  4371.2 1434.95    4415 1434.66  4507.4 1432.41  4538.3 1430.85  4572.3 1430.36
  4579.3 1429.43  4614.8 1429.12  4747.3 1424.39  4774.5 1422.98  4805.3 1422.47
  4874.6 1421.59    4908 1421.75  4925.6 1420.82  4928.3 1420.32  4931.6 1420.82
  4964.7 1422.35  4979.9 1422.37  5000.5 1421.05  5043.7 1422.46  5062.1 1423.56
  5182.1 1426.04  5231.7 1428.28  5272.1  1431.4  5339.4 1434.66  5370.2 1434.98
  5417.8 1436.87  5489.5 1438.92  5494.7    1438  5503.7 1438.06  5510.7 1438.85
#Mann= 7 ,-1 , 0
  4371.2      .1       0  4805.3     .16       0  4925.6     .07       0
  4931.6     .16       0  5043.7      .1       0  5231.7     .16       0
  5417.8      .1       0
Bank Sta=4925.6,4931.6
XS Rating Curve= 0 ,0
Exp/Cntr=0.3,0.1

Type RM Length L Ch R = 1 ,15277   ,156,156,156
BEGIN DESCRIPTION:
Mapping XS 67534dad
END DESCRIPTION:
XS GIS Cut Line= 4
      2861998.63     10076041.47      2862043.13     10075674.39
      2862403.51     10075071.52       2862432.3     10074867.79
#Sta/Elev= 30
  4256.6 1431.76  4264.4 1432.42    4345 1431.82  4380.1 1430.68  4405.4 1431.76
  4519.6 1429.42  4556.5 1427.84  4626.4 1426.81  4746.7 1422.04  4755.3 1422.88
  4777.9 1422.22  4820.6 1419.74  4826.5 1420.72  4836.2 1419.34  4840.2 1420.13
    4930 1419.15  4998.6 1416.47  5001.3 1415.97  5004.6 1416.47  5023.3 1418.65
  5054.1  1418.1  5096.9 1419.21  5166.6 1423.44  5207.8 1426.31  5213.6 1425.69
  5250.6 1427.73  5324.5  1429.2  5328.7 1428.53    5396 1432.15  5534.5 1435.79
#Mann= 6 ,-1 , 0
  4256.6     .16       0  4519.6      .1       0  4840.2     .16       0
  4998.6     .07       0  5004.6     .16       0  5166.6      .1       0
Bank Sta=4998.6,5004.6
XS Rating Curve= 0 ,0
Exp/Cntr=0.3,0.1

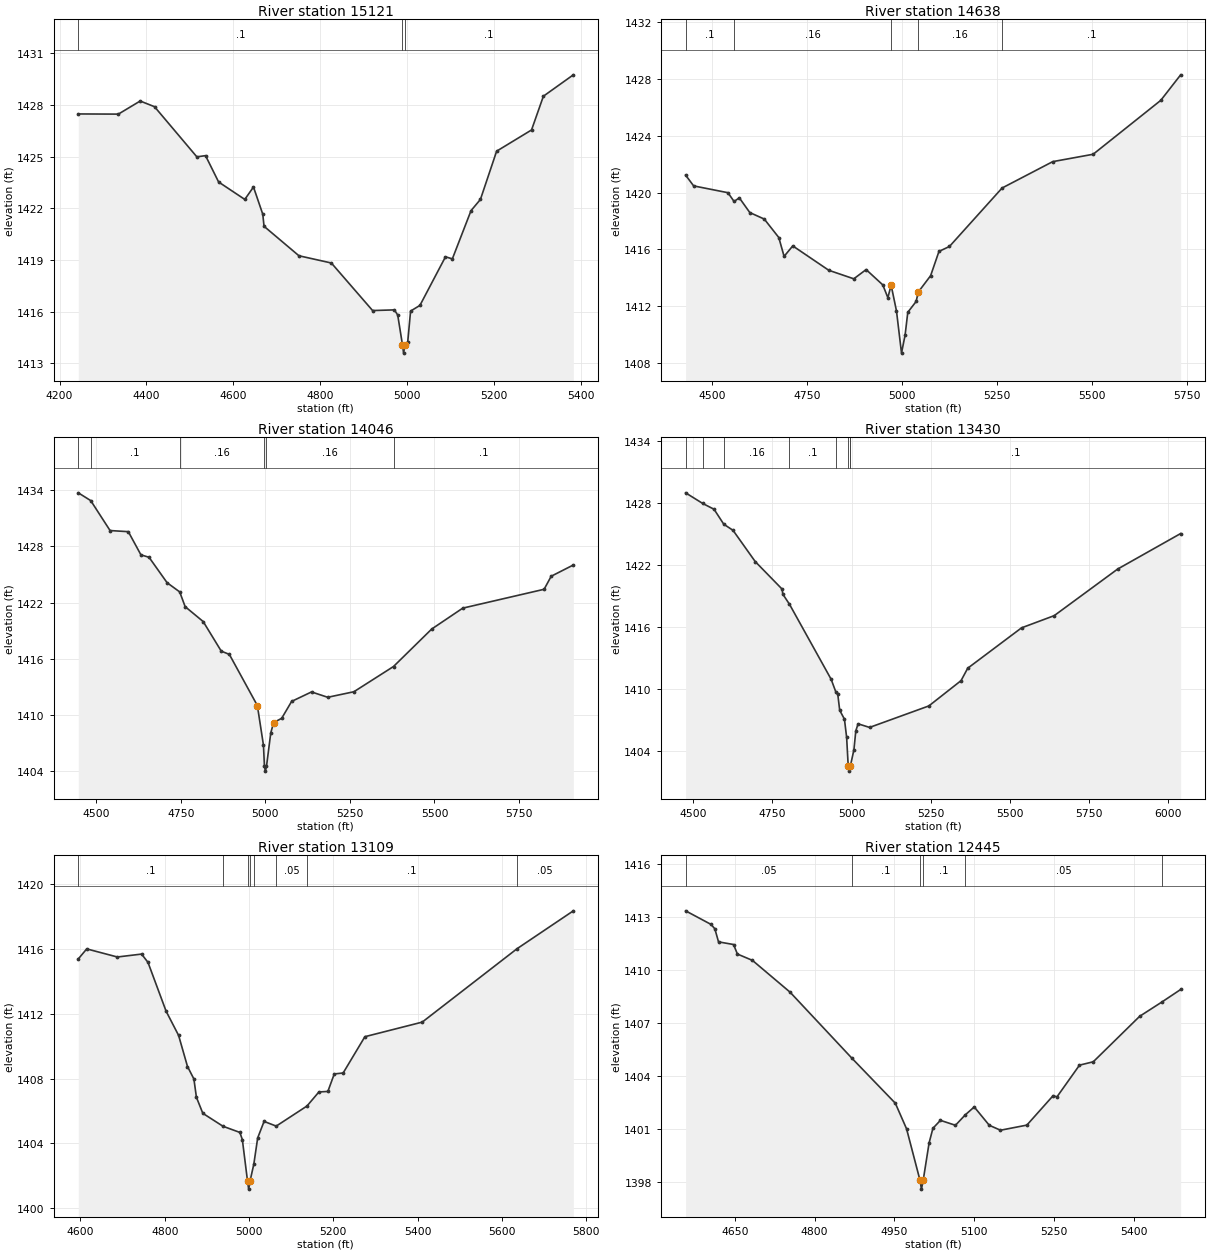
Type RM Length L Ch R = 1 ,15121   ,483,483,483
BEGIN DESCRIPTION:
POST OAK CREEK 31.0
END DESCRIPTION:
XS GIS Cut Line= 3
      2862170.18     10076075.69      2862202.73     10075652.48
      2862560.79     10075034.02
#Sta/Elev= 30
  4243.2 1427.47  4335.4 1427.46  4385.6 1428.22  4418.6 1427.89    4516 1424.98
    4536 1425.05  4566.1 1423.52  4626.3 1422.51  4646.3 1423.23  4667.7 1421.65
  4670.6 1420.95  4750.9 1419.24  4825.5 1418.82  4920.4 1416.06  4970.5  1416.1
  4978.2  1415.8    4989 1414.09  4991.7 1413.59    4995 1414.09  5001.3 1414.26
  5007.8 1416.03  5029.3 1416.36  5088.1 1419.18  5103.9 1419.06  5146.9 1421.86
  5168.5 1422.51  5205.8 1425.31  5286.1 1426.54  5313.4  1428.5  5382.3 1429.74
#Mann= 3 ,-1 , 0
  4243.2      .1       0    4989     .07       0    4995      .1       0
Bank Sta=4989,4995
XS Rating Curve= 0 ,0
Exp/Cntr=0.3,0.1

Type RM Length L Ch R = 1 ,14638   ,592,592,592
BEGIN DESCRIPTION:
Mapping XS b5aec69b
END DESCRIPTION:
XS GIS Cut Line= 3
      2862465.79     10076141.57      2862879.58     10075374.06
      2862599.25     10075049.25
#Sta/Elev= 30
  4431.2 1421.24  4452.3 1420.48  4542.4    1420  4558.6 1419.38  4572.3 1419.64
  4599.9  1418.6    4638 1418.14  4676.1 1416.84    4690 1415.51  4712.8 1416.25
  4807.5 1414.53  4873.2 1413.93  4905.6 1414.58  4949.4  1413.5  4962.7  1412.6
  4971.3 1413.48  4985.4 1411.66  4998.6 1408.69  5008.1 1409.98  5015.1 1411.57
    5037 1412.33  5042.7    1413  5075.1 1414.15    5097 1415.86  5124.6 1416.21
  5262.9 1420.33    5396 1422.19  5502.2 1422.71  5679.9 1426.51  5732.2 1428.31
#Mann= 5 ,-1 , 0
  4431.2      .1       0  4558.6     .16       0  4971.3     .07       0
  5042.7     .16       0  5262.9      .1       0
Bank Sta=4971.3,5042.7
XS Rating Curve= 0 ,0
Exp/Cntr=0.3,0.1

Type RM Length L Ch R = 1 ,14046   ,616,616,616
BEGIN DESCRIPTION:
POST OAK CREEK 30.0
END DESCRIPTION:
XS GIS Cut Line= 3
      2863373.45     10076350.69      2863006.38     10075454.15
        2862666.     10075093.75
#Sta/Elev= 30
  4446.4 1433.69  4483.2 1432.86  4540.4 1429.67  4594.4 1429.55  4631.7 1427.08
  4655.7 1426.82  4709.1 1424.11  4746.4 1423.13  4762.5 1421.56  4815.9 1419.97
  4869.3 1416.82  4893.3 1416.47  4976.1 1411.02  4994.2 1406.79  4997.1 1404.53
  4999.8 1404.03  5003.1 1404.53  5015.8  1408.1  5024.1  1409.2  5048.1 1409.66
  5077.5 1411.46  5136.3 1412.47  5184.3  1411.9  5261.7 1412.49  5378.9 1415.18
  5491.8 1419.17  5583.7  1421.4  5824.4 1423.41  5845.4  1424.8  5910.9    1426
#Mann= 6 ,-1 , 0
  4446.4     .16       0  4483.2      .1       0  4746.4     .16       0
  4997.1     .07       0  5003.1     .16       0  5378.9      .1       0
Bank Sta=4976.1,5024.1
XS Rating Curve= 0 ,0
Exp/Cntr=0.3,0.1

Type RM Length L Ch R = 1 ,13430   ,321,321,321
BEGIN DESCRIPTION:
POST OAK CREEK 29.0
END DESCRIPTION:
XS GIS Cut Line= 4
      2863842.83      10075923.5      2863847.28     10075618.77
      2863302.25     10075249.49      2862728.33     10075071.53
#Sta/Elev= 30
  4475.9 1429.01    4530 1427.98  4565.7 1427.42  4596.5 1425.97  4625.7 1425.38
  4695.7 1422.36  4780.7 1419.69    4783  1419.2  4804.1 1418.22  4935.7 1410.96
  4950.9  1409.7  4956.7 1409.49  4962.7 1407.96  4977.7  1407.1  4984.6 1405.34
  4989.6 1402.57  4992.4 1402.07  4995.6 1402.57  4996.4 1402.57  5007.6 1404.13
  5013.6 1405.97  5020.8 1406.65  5057.1  1406.3  5244.3 1408.38  5346.1 1410.83
  5367.1 1412.03  5537.2 1415.94  5640.4 1417.12  5840.8 1421.63  6039.9 1425.07
#Mann= 8 ,-1 , 0
  4475.9     .16       0    4530      .1       0  4596.5     .16       0
  4804.1      .1       0  4950.9     .16       0  4989.6     .07       0
  4995.6     .16       0  4996.4      .1       0
Bank Sta=4989.6,4995.6
XS Rating Curve= 0 ,0
Exp/Cntr=0.3,0.1

Type RM Length L Ch R = 1 ,13109   ,664,664,664
BEGIN DESCRIPTION:
POST OAK CREEK 28.0
END DESCRIPTION:
XS GIS Cut Line= 2
      2864174.03     10075447.08      2863184.44     10074813.39
#Sta/Elev= 30
  4594.8 1415.39  4614.8 1416.01  4687.5 1415.51    4745 1415.69  4760.2 1415.18
  4803.3 1412.16  4832.9 1410.67    4854 1408.75  4869.2 1407.98  4875.2 1406.85
  4890.4 1405.86  4938.3 1405.06  4978.3 1404.68  4984.2 1404.24  4996.5 1401.68
  4999.2 1401.18  5002.5 1401.68  5011.5 1402.73  5020.6 1404.34  5035.8 1405.36
  5064.6 1405.07  5137.6 1406.31    5166 1407.18  5187.2 1407.21  5202.4 1408.29
  5223.5 1408.35  5275.1 1410.59  5411.2 1411.49  5636.2 1416.02  5769.9 1418.36
#Mann= 8 ,-1 , 0
  4594.8      .1       0  4938.3     .05       0  4996.5    .035       0
  5002.5     .05       0  5011.5      .1       0  5064.6     .05       0
  5137.6      .1       0  5636.2     .05       0
Bank Sta=4996.5,5002.5
XS Rating Curve= 0 ,0
Exp/Cntr=0.3,0.1

Type RM Length L Ch R = 1 ,12445   ,805,805,805
BEGIN DESCRIPTION:
POST OAK CREEK 26.0
END DESCRIPTION:
XS GIS Cut Line= 2
      2864642.73     10075117.18      2863975.67     10074467.44
#Sta/Elev= 30
  4557.5 1413.35  4605.3 1412.58  4612.5 1412.33  4619.4 1411.59  4647.7 1411.44
  4654.9  1410.9  4683.2 1410.54  4753.9 1408.74  4870.4 1404.99    4952 1402.44
  4973.1 1400.99  4998.4 1398.07  5001.1 1397.57  5004.4 1398.07  5015.5 1400.19
  5022.7 1401.02  5036.8 1401.47  5065.1 1401.19  5083.5 1401.78  5100.4 1402.23
  5128.7 1401.19  5149.8 1400.91  5199.4  1401.2  5248.8 1402.87    5256  1402.8
  5298.4  1404.6  5324.3 1404.79  5411.6 1407.37  5453.4 1408.18  5488.7 1408.89
#Mann= 6 ,-1 , 0
  4557.5     .05       0  4870.4      .1       0  4998.4     .07       0
  5004.4      .1       0  5083.5     .05       0  5453.4      .1       0
Bank Sta=4998.4,5004.4
XS Rating Curve= 0 ,0
Exp/Cntr=0.3,0.1