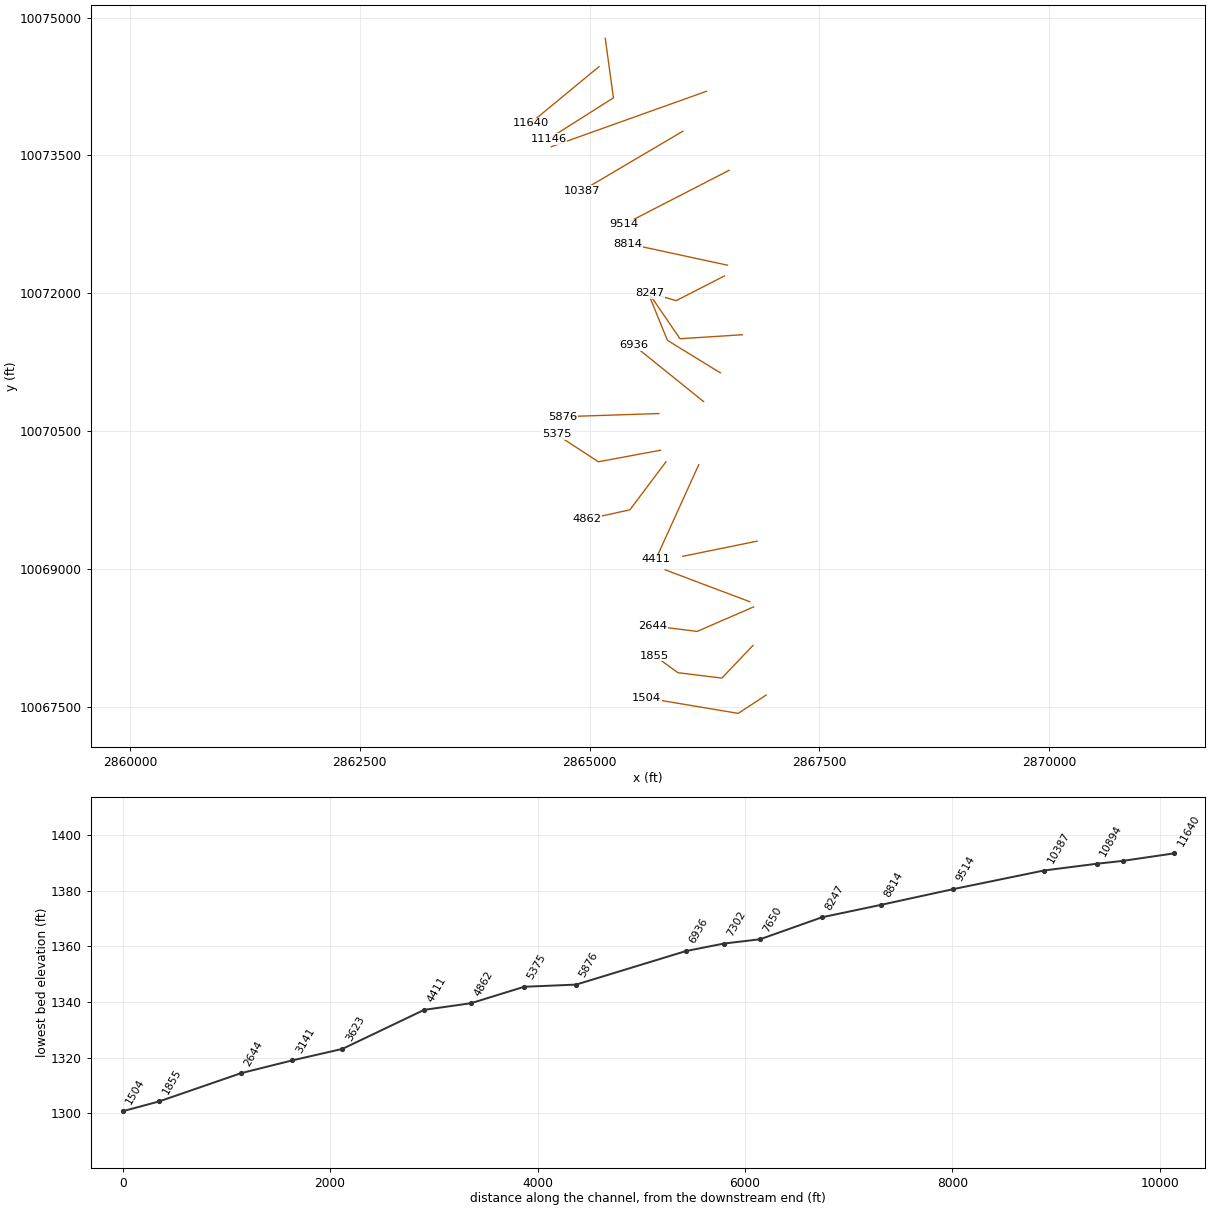
HEC-RAS study POST OAK CREEK.prj: POST OAK CREEK Base Level Engineering

--- POST OAK CREEK.g01 (geometry) --- (continued)

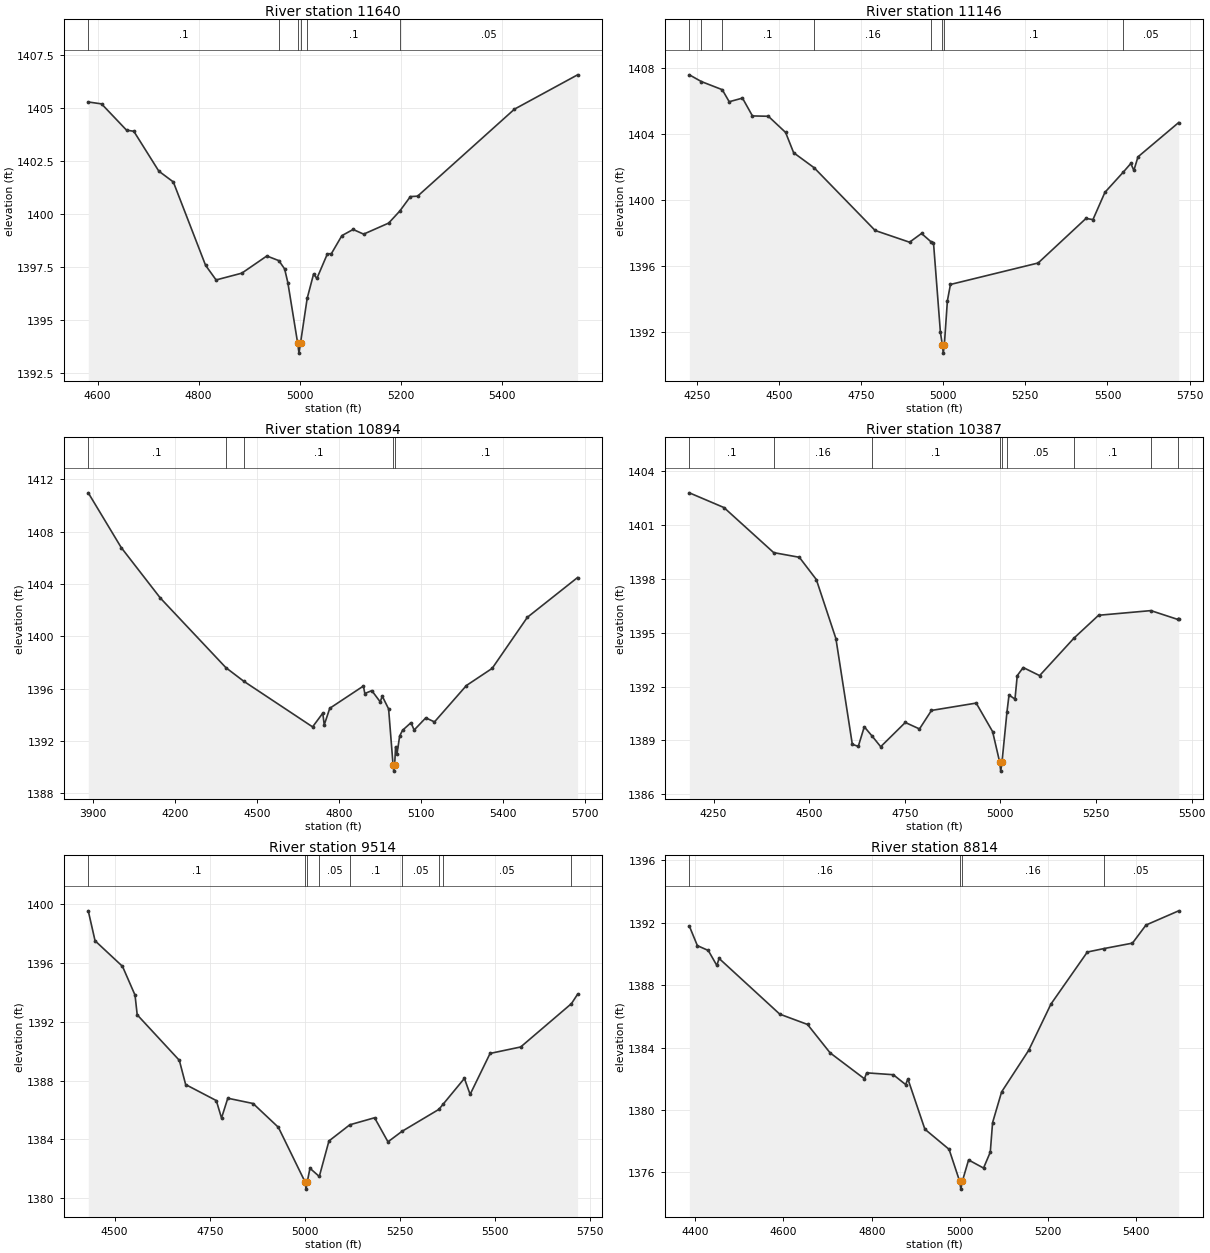
Type RM Length L Ch R = 1 ,11640   ,494,494,494
BEGIN DESCRIPTION:
POST OAK CREEK 24.0
END DESCRIPTION:
XS GIS Cut Line= 2
      2865102.85     10074466.19       2864356.3     10073849.85
#Sta/Elev= 30
  4581.7 1405.27    4608 1405.18  4657.5 1403.94  4671.8 1403.89  4721.3 1402.01
    4750  1401.5  4813.8 1397.57  4834.6 1396.88  4885.5  1397.2    4935 1398.01
  4958.8 1397.79  4970.2  1397.4  4976.6 1396.75  4995.8 1393.93  4998.6 1393.43
  5001.8 1393.93  5014.8 1396.01  5027.5 1397.16    5034 1396.95  5054.8 1398.11
  5062.7 1398.12  5083.5 1398.97  5105.7 1399.26  5126.5 1399.04    5176 1399.56
  5198.1 1400.13    5219 1400.81  5233.3 1400.83  5424.8 1404.93  5549.8 1406.55
#Mann= 6 ,-1 , 0
  4581.7      .1       0  4958.8     .05       0  4995.8    .035       0
  5001.8     .05       0  5014.8      .1       0  5198.1     .05       0
Bank Sta=4995.8,5001.8
XS Rating Curve= 0 ,0
Exp/Cntr=0.3,0.1

Type RM Length L Ch R = 1 ,11146   ,252,252,252
BEGIN DESCRIPTION:
POST OAK CREEK 23.0
END DESCRIPTION:
XS GIS Cut Line= 3
      2865170.33     10074773.91      2865259.32     10074126.51
       2864553.9     10073678.41
#Sta/Elev= 30
  4227.6  1407.6  4264.4 1407.19  4327.7  1406.7  4348.9 1405.97  4389.3 1406.19
  4419.6 1405.11    4468 1405.09  4520.5 1404.11    4545 1402.88  4607.4 1401.97
    4793 1398.17  4897.7 1397.46  4934.2 1397.99  4962.2  1397.5  4970.6 1397.43
  4991.7 1391.99  4997.6 1391.24  5000.3 1390.74  5003.6 1391.24  5012.9 1393.91
  5022.2  1394.9    5289  1396.2  5434.7  1398.9  5455.9 1398.83  5492.3 1400.48
  5547.9  1401.7  5571.1 1402.23  5580.4 1401.81  5592.9 1402.63  5716.8 1404.71
#Mann= 8 ,-1 , 0
  4227.6      .1       0  4264.4     .16       0  4327.7      .1       0
  4607.4     .16       0  4962.2      .1       0  4997.6     .07       0
  5003.6      .1       0  5547.9     .05       0
Bank Sta=4997.6,5003.6
XS Rating Curve= 0 ,0
Exp/Cntr=0.3,0.1

Type RM Length L Ch R = 1 ,10894   ,507,507,507
BEGIN DESCRIPTION:
Mapping XS 62f0dc36
END DESCRIPTION:
XS GIS Cut Line= 2
      2866271.56     10074197.71      2864585.29     10073594.84
#Sta/Elev= 30
  3881.6 1410.96  4002.2 1406.78  4145.5 1402.92  4385.5  1397.6  4450.5 1396.57
  4702.6 1393.08  4739.9 1394.13  4745.2 1393.23  4765.4  1394.5  4888.5  1396.2
  4893.8 1395.63  4919.3 1395.85  4950.1 1394.99  4957.5 1395.43  4980.8 1394.45
    4997  1390.2  4999.7  1389.7    5003  1390.2  5006.3 1391.57  5011.6 1391.03
  5021.2 1392.38  5031.8 1392.82  5062.6  1393.4  5074.3 1392.84  5116.8 1393.77
  5148.7 1393.46  5265.5 1396.24  5359.8 1397.55  5488.5 1401.45  5672.4 1404.49
#Mann= 5 ,-1 , 0
  3881.6      .1       0  4385.5     .05       0  4450.5      .1       0
    4997     .07       0    5003      .1       0
Bank Sta=4997,5003
XS Rating Curve= 0 ,0
Exp/Cntr=0.3,0.1

Type RM Length L Ch R = 1 ,10387   ,873,873,873
BEGIN DESCRIPTION:
POST OAK CREEK 22.0
END DESCRIPTION:
XS GIS Cut Line= 2
      2866014.31     10073763.05      2864912.67     10073112.48
#Sta/Elev= 30
  4186.8 1402.79  4277.3 1401.97  4407.3 1399.46  4474.4  1399.2  4518.8 1397.96
    4570 1394.67  4612.9 1388.78  4628.5 1388.67  4644.2 1389.76  4664.7 1389.24
  4687.1 1388.65  4751.4    1390  4788.5 1389.64  4819.8 1390.67  4936.8 1391.08
  4979.7 1389.49  4998.2 1387.79  5000.9 1387.29  5004.2 1387.79  5017.3  1390.6
  5022.6 1391.53  5038.2  1391.3  5044.1 1392.61  5059.7 1393.06  5102.6 1392.61
  5192.5  1394.7  5256.7 1395.97  5393.5 1396.23  5463.7 1395.74  5466.2 1395.79
#Mann= 9 ,-1 , 0
  4186.8      .1       0  4407.3     .16       0  4664.7      .1       0
  4998.2     .07       0  5004.2      .1       0  5017.3     .05       0
  5192.5      .1       0  5393.5     .05       0  5463.7      .1       0
Bank Sta=4998.2,5004.2
XS Rating Curve= 0 ,0
Exp/Cntr=0.3,0.1

Type RM Length L Ch R = 1 ,9514    ,700,700,700
BEGIN DESCRIPTION:
POST OAK CREEK 20.0
END DESCRIPTION:
XS GIS Cut Line= 2
      2866517.79     10073337.71      2865373.95     10072748.46
#Sta/Elev= 30
  4430.6 1399.56  4448.5 1397.52  4520.6 1395.78  4553.6 1393.82  4559.3 1392.48
  4670.1 1389.38  4686.7 1387.73  4767.3 1386.64    4781 1385.45  4797.5  1386.8
    4864 1386.44  4930.5 1384.82  5000.5 1381.11  5003.3 1380.61  5006.5 1381.11
  5013.6 1382.03  5038.1 1381.47  5063.5 1383.89  5118.3 1384.99  5183.5 1385.47
  5218.7 1383.83  5255.3 1384.54  5352.5 1386.04  5363.9  1386.4  5419.7 1388.15
  5434.7 1387.06  5487.2 1389.85  5567.7 1390.29  5701.1 1393.24  5717.3 1393.88
#Mann= 9 ,-1 , 0
  4430.6      .1       0  5000.5     .07       0  5006.5      .1       0
  5038.1     .05       0  5118.3      .1       0  5255.3     .05       0
  5352.5     .16       0  5363.9     .05       0  5701.1      .1       0
Bank Sta=5000.5,5006.5
XS Rating Curve= 0 ,0
Exp/Cntr=0.3,0.1

Type RM Length L Ch R = 1 ,8814    ,567,567,567
BEGIN DESCRIPTION:
POST OAK CREEK 19.0
END DESCRIPTION:
XS GIS Cut Line= 2
      2866500.37     10072304.71      2865416.07     10072538.91
#Sta/Elev= 30
  4386.6 1391.78  4404.8 1390.53  4429.5 1390.22  4448.9 1389.26    4454 1389.71
  4591.6 1386.14  4654.5 1385.48  4705.7 1383.66  4783.5    1382  4788.6 1382.38
  4848.9 1382.26  4876.9 1381.63    4882 1381.99  4920.5 1378.77  4975.4 1377.48
  4999.4 1375.43  5002.1 1374.93  5005.4 1375.43  5019.6  1376.8  5053.5 1376.28
  5068.8  1377.3    5074 1379.19  5094.5 1381.16  5155.8 1383.82  5206.4 1386.79
  5288.8 1390.12  5326.1 1390.34  5391.1 1390.69  5421.8 1391.85  5495.9 1392.76
#Mann= 4 ,-1 , 0
  4386.6     .16       0  4999.4     .07       0  5005.4     .16       0
  5326.1     .05       0
Bank Sta=4999.4,5005.4
XS Rating Curve= 0 ,0
Exp/Cntr=0.3,0.1

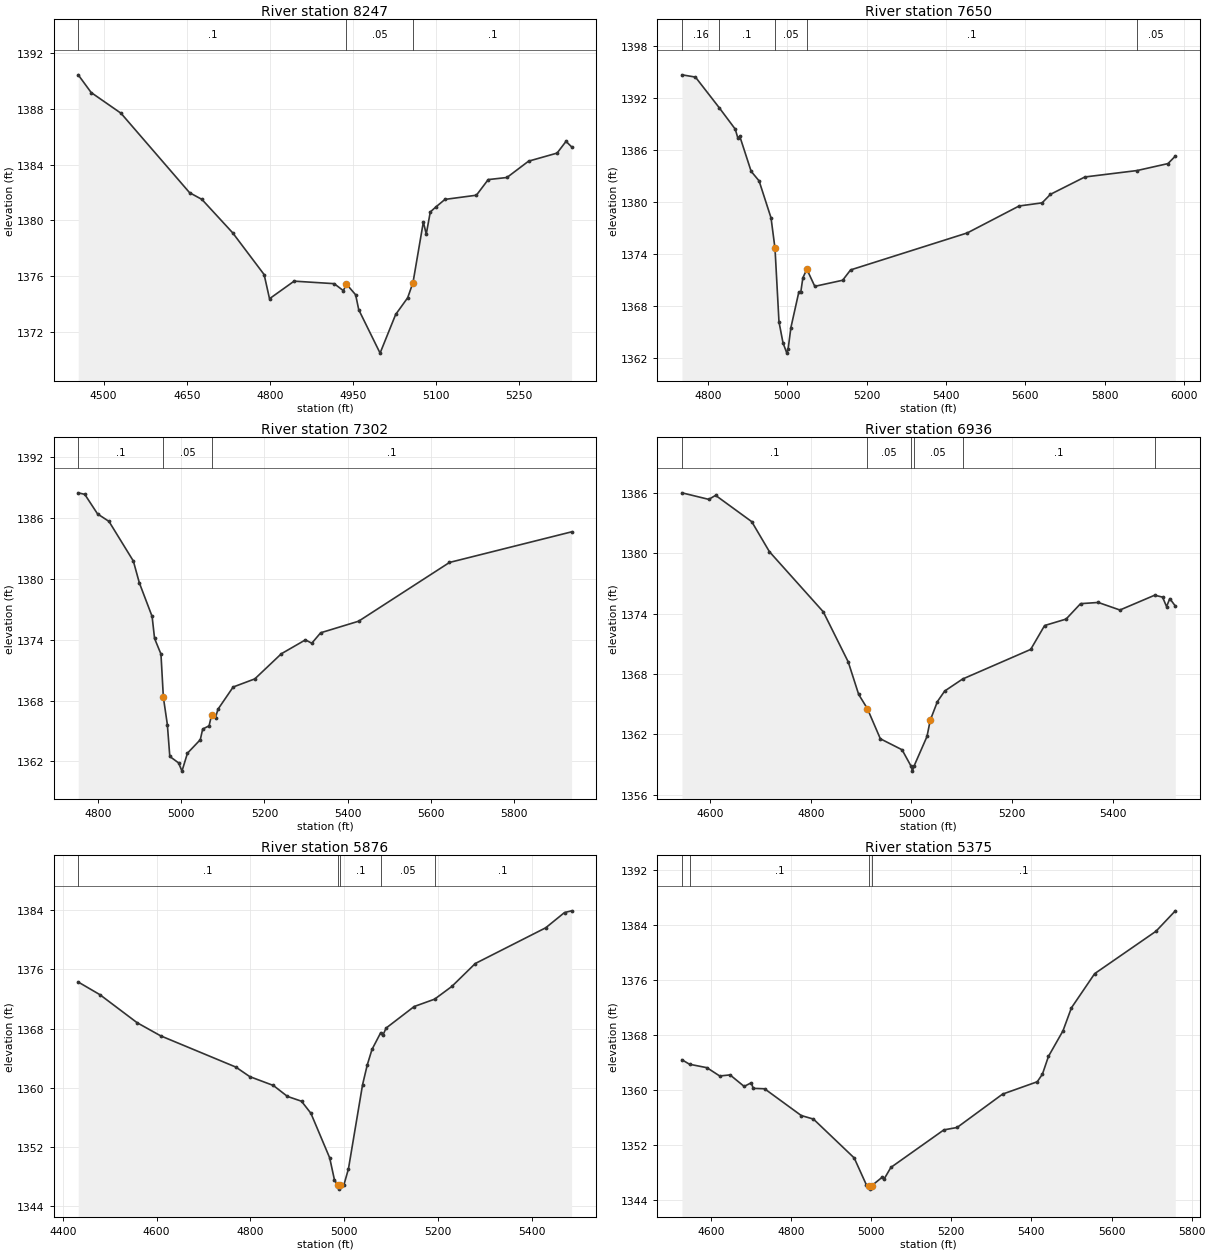
Type RM Length L Ch R = 1 ,8247    ,597,597,597
BEGIN DESCRIPTION:
POST OAK CREEK 18.0
END DESCRIPTION:
XS GIS Cut Line= 3
      2866467.08     10072187.97      2865941.95     10071918.89
      2865653.36     10072001.35
#Sta/Elev= 30
  4454.1 1390.44  4477.5 1389.17  4531.2 1387.69  4655.1 1381.99  4677.3 1381.51
  4732.7 1379.12  4789.6 1376.12  4799.3 1374.39  4843.7 1375.65  4915.9 1375.47
  4932.5 1374.97  4938.1 1375.44  4954.7 1374.67  4960.3  1373.6  4998.8 1370.49
  5026.9 1373.26  5048.6 1374.46  5058.2 1375.55  5076.9  1379.9  5082.1 1379.02
  5089.4 1380.61  5099.8 1380.98  5115.9 1381.51  5172.6 1381.81  5193.9 1382.93
  5227.7 1383.08  5266.7 1384.25  5318.2 1384.83  5334.3 1385.67  5344.3 1385.28
#Mann= 3 ,-1 , 0
  4454.1      .1       0  4938.1     .05       0  5058.2      .1       0
Bank Sta=4938.1,5058.2
XS Rating Curve= 0 ,0
Exp/Cntr=0.3,0.1

Type RM Length L Ch R = 1 ,7650    ,348,348,348
BEGIN DESCRIPTION:
POST OAK CREEK 17.0
END DESCRIPTION:
XS GIS Cut Line= 3
      2866662.41     10071547.79      2865983.18     10071504.39
      2865666.35      10071968.8
#Sta/Elev= 30
    4735 1394.63    4769 1394.37  4829.1 1390.83  4869.2 1388.38  4875.7 1387.37
  4880.7 1387.55  4909.3 1383.52  4929.3 1382.42  4959.4 1378.16  4969.4 1374.65
  4979.4  1366.2  4989.5 1363.78  4999.2 1362.59  5002.5 1363.09  5009.5 1365.54
  5029.2 1369.58  5034.2 1369.57  5039.6 1371.26  5049.6 1372.25  5069.6 1370.28
  5139.8 1370.98  5159.8 1372.17  5453.9 1376.43  5584.3 1379.53  5642.3 1379.89
  5663.2 1380.87    5750 1382.87  5881.4 1383.61  5959.3 1384.41  5977.8 1385.27
#Mann= 5 ,-1 , 0
    4735     .16       0  4829.1      .1       0  4969.4     .05       0
  5049.6      .1       0  5881.4     .05       0
Bank Sta=4969.4,5049.6
XS Rating Curve= 0 ,0
Exp/Cntr=0.3,0.1

Type RM Length L Ch R = 1 ,7302    ,366,366,366
BEGIN DESCRIPTION:
Mapping XS 605c4d83
END DESCRIPTION:
XS GIS Cut Line= 3
      2866421.55      10071133.3      2865846.47     10071487.03
      2865653.31     10071962.32
#Sta/Elev= 30
  4751.4 1388.51  4767.2 1388.36    4798 1386.43  4825.5 1385.69  4884.2 1381.78
  4898.6 1379.63  4929.4 1376.31  4935.3 1374.14  4950.7  1372.6  4956.5 1368.33
  4966.1 1365.65    4972  1362.5  4993.2 1361.86  5001.3 1361.05  5014.5 1362.82
  5045.4 1364.15  5051.2  1365.2  5066.6 1365.52  5072.5 1366.56  5082.1 1366.33
  5087.9 1367.15  5124.6 1369.35  5176.7 1370.15  5240.6 1372.63  5298.6    1374
    5314 1373.67  5335.3  1374.7  5426.6 1375.84  5645.6 1381.64  5939.6 1384.66
#Mann= 3 ,-1 , 0
  4751.4      .1       0  4956.5     .05       0  5072.5      .1       0
Bank Sta=4956.5,5072.5
XS Rating Curve= 0 ,0
Exp/Cntr=0.3,0.1

Type RM Length L Ch R = 1 ,6936    ,1060,1060,1060
BEGIN DESCRIPTION:
POST OAK CREEK 16.0
END DESCRIPTION:
XS GIS Cut Line= 2
      2866239.99     10070820.32      2865476.11     10071436.63
#Sta/Elev= 30
  4543.4 1385.98  4596.8 1385.33  4610.3 1385.73  4682.2 1383.12  4717.4 1380.14
  4824.6 1374.17  4874.2  1369.2    4895 1365.97  4912.2 1364.57  4938.1 1361.57
  4981.3 1360.48  4999.1 1358.86  5001.9 1358.36  5005.1 1358.86  5030.9  1361.8
  5037.3  1363.4  5051.7 1365.27  5066.1 1366.31  5101.7  1367.5  5237.2 1370.44
  5264.9 1372.81  5307.6 1373.45  5336.4 1374.98  5371.6  1375.1  5414.7 1374.35
  5483.9 1375.82  5499.5 1375.63  5507.5 1374.69  5513.9 1375.48  5524.9 1374.75
#Mann= 6 ,-1 , 0
  4543.4      .1       0  4912.2     .05       0  4999.1    .035       0
  5005.1     .05       0  5101.7      .1       0  5483.9     .16       0
Bank Sta=4912.2,5037.3
XS Rating Curve= 0 ,0
Exp/Cntr=0.3,0.1

Type RM Length L Ch R = 1 ,5876    ,501,501,501
BEGIN DESCRIPTION:
POST OAK CREEK 14.0
END DESCRIPTION:
XS GIS Cut Line= 2
      2865753.89     10070690.12      2864703.47      10070655.4
#Sta/Elev= 30
    4433 1374.29  4479.2 1372.58  4558.5 1368.79  4608.5 1367.02  4768.6  1362.8
  4798.6  1361.5  4848.7 1360.31  4878.7 1358.83  4908.7 1358.18  4928.7 1356.55
  4968.7 1350.53  4978.7  1347.6  4985.7  1346.8  4988.5  1346.3  4991.7  1346.8
  4998.7  1346.8  5008.7 1349.04  5038.8 1360.42  5048.8 1363.09  5058.8 1365.17
  5077.5 1367.45  5082.1  1367.1  5088.8 1368.06  5148.8 1370.98  5192.2 1371.97
  5228.9 1373.69  5278.9 1376.79    5429 1381.62    5469 1383.68    5484 1383.91
#Mann= 5 ,-1 , 0
    4433      .1       0  4985.7     .07       0  4991.7      .1       0
  5077.5     .05       0  5192.2      .1       0
Bank Sta=4985.7,4991.7
XS Rating Curve= 0 ,0
Exp/Cntr=0.3,0.1

Type RM Length L Ch R = 1 ,5375    ,513,513,513
BEGIN DESCRIPTION:
POST OAK CREEK 12.0
END DESCRIPTION:
XS GIS Cut Line= 3
      2865771.18     10070290.81      2865095.99     10070165.03
      2864639.97     10070462.92
#Sta/Elev= 30
  4527.7 1364.36  4546.7 1363.71    4590 1363.21    4622    1362  4647.8 1362.16
    4683 1360.48  4700.6 1361.01  4705.7  1360.2  4733.9 1360.14  4825.5 1356.24
    4856 1355.72  4957.7 1350.06  4988.2 1346.12  4995.4 1346.02  4998.1 1345.52
  5001.4 1346.02  5027.2 1347.24  5032.2 1346.98  5049.2 1348.68  5181.5 1354.15
  5214.5  1354.5    5328 1359.36  5414.6 1361.16  5427.5 1362.27  5442.6 1364.86
  5478.8 1368.58  5499.9 1371.93  5557.9 1376.91  5711.1 1383.09  5759.2 1386.06
#Mann= 4 ,-1 , 0
  4527.7     .05       0  4546.7      .1       0  4995.4     .07       0
  5001.4      .1       0
Bank Sta=4995.4,5001.4
XS Rating Curve= 0 ,0
Exp/Cntr=0.3,0.1

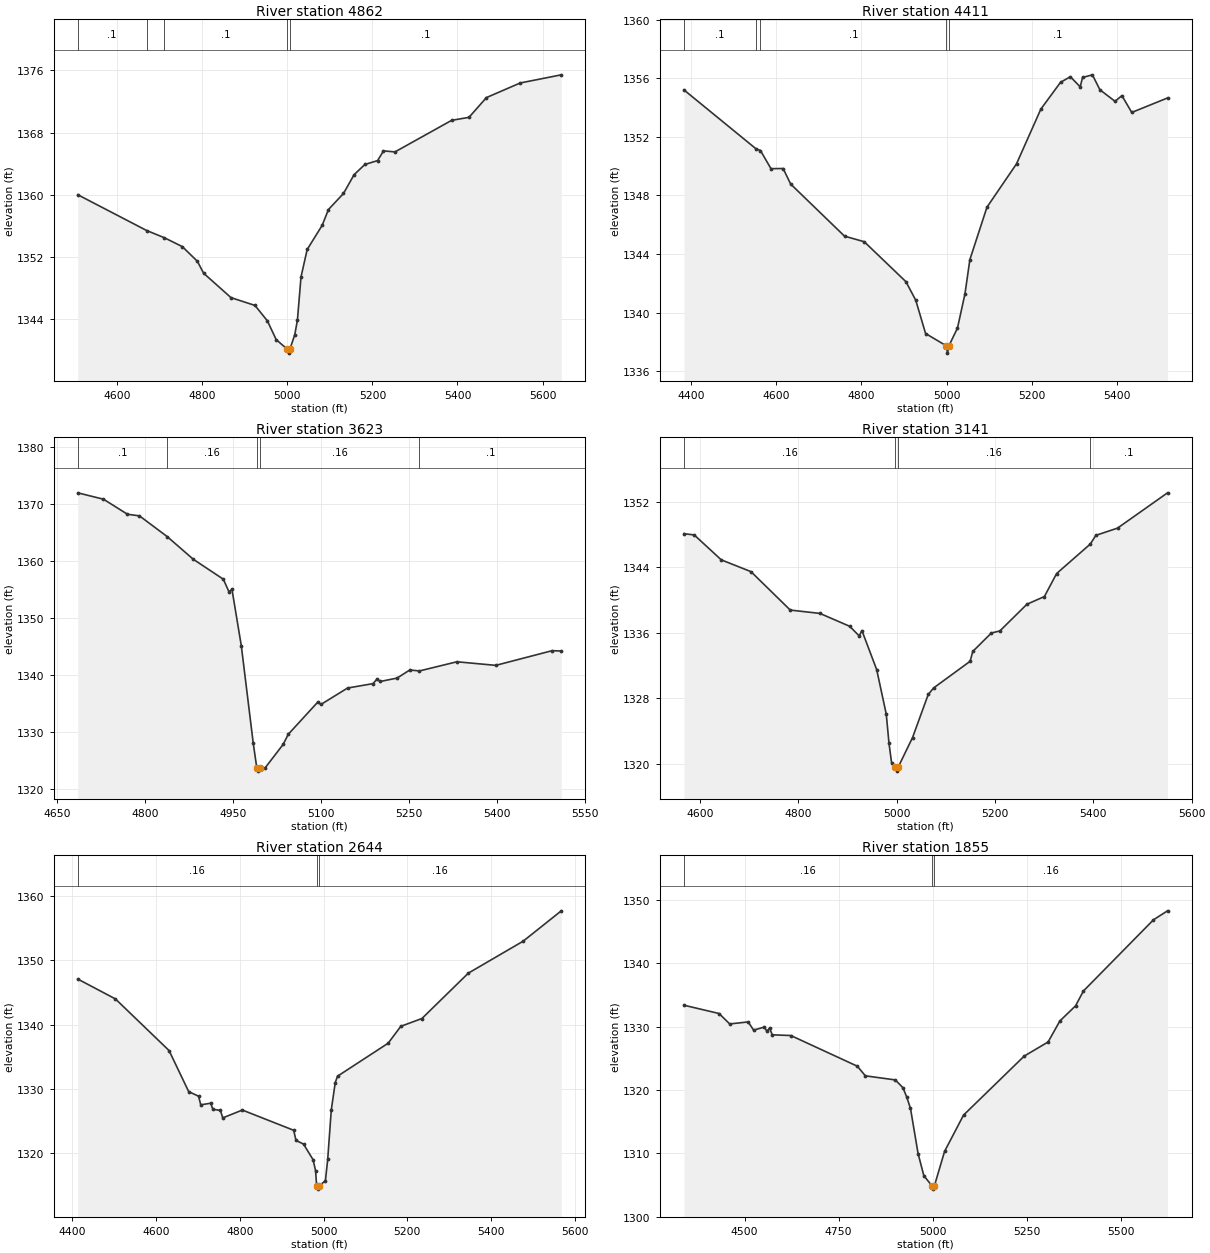
Type RM Length L Ch R = 1 ,4862    ,451,451,451
BEGIN DESCRIPTION:
POST OAK CREEK 11.0
END DESCRIPTION:
XS GIS Cut Line= 3
      2865831.27     10070165.41      2865438.48     10069642.41
      2864966.46     10069538.48
#Sta/Elev= 30
  4506.8    1360    4669 1355.39  4710.7 1354.46  4752.8 1353.32  4788.3 1351.43
  4802.8  1349.9  4867.4 1346.75  4923.7 1345.75  4952.8 1343.77  4973.6 1341.35
  4999.8 1340.11  5002.6 1339.61  5005.8 1340.11  5017.4 1341.99  5023.6 1343.89
    5032 1349.42  5046.5 1352.95  5081.9 1356.07  5096.5 1358.09  5131.9 1360.16
  5156.9 1362.58  5182.2 1363.89  5212.1 1364.39    5226 1365.64    5253 1365.51
  5386.2 1369.57  5427.1 1369.96  5468.1  1372.5  5547.5 1374.38  5644.2 1375.43
#Mann= 5 ,-1 , 0
  4506.8      .1       0    4669     .05       0  4710.7      .1       0
  4999.8     .07       0  5005.8      .1       0
Bank Sta=4999.8,5005.8
XS Rating Curve= 0 ,0
Exp/Cntr=0.3,0.1

Type RM Length L Ch R = 1 ,4411    ,788,788,788
BEGIN DESCRIPTION:
POST OAK CREEK 10.0
END DESCRIPTION:
XS GIS Cut Line= 2
      2866187.87     10070134.52      2865719.15     10069101.59
#Sta/Elev= 30
    4384 1355.21  4552.9 1351.19  4563.5 1351.07  4588.1 1349.83  4616.7 1349.84
  4634.3 1348.78  4760.7 1345.22  4806.9 1344.84  4904.7 1342.11  4927.8 1340.84
  4950.8 1338.57  4999.5 1337.73  5002.2 1337.23  5005.5 1337.73  5025.6 1338.94
  5043.2 1341.28  5054.7 1343.62  5094.8  1347.2  5164.1 1350.16  5221.2  1353.9
  5267.4 1355.73  5290.4 1356.11  5313.5 1355.42    5319 1356.06  5342.1 1356.24
  5359.7 1355.22  5395.2 1354.43  5411.3 1354.82  5434.4 1353.67  5518.3 1354.66
#Mann= 5 ,-1 , 0
    4384      .1       0  4552.9     .05       0  4563.5      .1       0
  4999.5     .07       0  5005.5      .1       0
Bank Sta=4999.5,5005.5
XS Rating Curve= 0 ,0
Exp/Cntr=0.3,0.1

Type RM Length L Ch R = 1 ,3623    ,482,482,482
BEGIN DESCRIPTION:
POST OAK CREEK 8.0
END DESCRIPTION:
XS GIS Cut Line= 2
      2866821.52     10069301.22       2866014.3      10069136.3
#Sta/Elev= 30
  4685.8 1372.02  4729.7  1370.9  4770.6 1368.26    4791 1367.98  4838.3 1364.34
  4882.8 1360.36  4933.9 1356.87  4943.5 1354.66  4948.6 1355.09  4964.5 1345.21
  4984.9 1328.06    4991 1323.71  4993.7 1323.21    4997 1323.71  5005.3 1323.81
  5035.9 1327.91  5044.5 1329.67    5095 1335.34  5100.1  1334.9  5145.5 1337.78
    5189 1338.56    5196 1339.39  5201.1 1338.93  5229.9 1339.53  5251.6 1340.95
    5268 1340.78  5331.9 1342.39    5398 1341.76  5493.9 1344.33  5509.7 1344.28
#Mann= 5 ,-1 , 0
  4685.8      .1       0  4838.3     .16       0    4991     .07       0
    4997     .16       0    5268      .1       0
Bank Sta=4991,4997
XS Rating Curve= 0 ,0
Exp/Cntr=0.3,0.1

Type RM Length L Ch R = 1 ,3141    ,497,497,497
BEGIN DESCRIPTION:
POST OAK CREEK 7.0
END DESCRIPTION:
XS GIS Cut Line= 2
      2866743.43     10068641.51      2865823.36     10068988.71
#Sta/Elev= 30
  4567.5 1348.07  4588.4 1347.92  4643.4 1344.88  4703.8 1343.44  4783.7 1338.75
  4844.1 1338.34  4904.5 1336.77    4924 1335.59  4929.4 1336.25  4959.5 1331.47
    4979 1326.03  4984.4 1322.54  4989.7 1320.13  4997.3 1319.59  5000.1 1319.09
  5003.3 1319.59  5032.4 1323.19  5064.3 1328.45  5075.2 1329.24  5149.5  1332.5
  5154.9  1333.7  5192.7 1335.95  5209.9  1336.2    5265 1339.46  5300.5  1340.4
  5325.4 1343.21  5393.9 1346.81  5405.2 1347.87  5449.2 1348.75  5550.9 1353.06
#Mann= 4 ,-1 , 0
  4567.5     .16       0  4997.3     .07       0  5003.3     .16       0
  5393.9      .1       0
Bank Sta=4997.3,5003.3
XS Rating Curve= 0 ,0
Exp/Cntr=0.3,0.1

Type RM Length L Ch R = 1 ,2644    ,789,789,789
BEGIN DESCRIPTION:
POST OAK CREEK 6.0
END DESCRIPTION:
XS GIS Cut Line= 3
      2866783.96     10068585.56      2866169.82     10068318.63
      2865688.08     10068379.39
#Sta/Elev= 30
  4412.8 1347.07  4502.9 1343.98    4631 1335.97  4677.9  1329.6  4701.4 1328.89
  4706.8 1327.55  4730.3  1327.8  4735.7 1326.85  4753.7 1326.69  4759.2 1325.52
  4806.1 1326.74  4928.7  1323.6  4934.2 1322.03  4952.2 1321.46  4974.9 1319.05
  4981.1 1317.31  4983.5 1314.97  4986.3 1314.47  4989.5 1314.97  5004.5 1315.78
    5010 1319.09  5018.5 1326.75    5028    1331  5033.4 1331.99  5154.4 1337.11
  5184.6 1339.73    5235 1340.94  5345.9 1347.98  5476.9 1352.94    5568 1357.65
#Mann= 3 ,-1 , 0
  4412.8     .16       0  4983.5     .07       0  4989.5     .16       0
Bank Sta=4983.5,4989.5
XS Rating Curve= 0 ,0
Exp/Cntr=0.3,0.1

Type RM Length L Ch R = 1 ,1855    ,351,351,351
BEGIN DESCRIPTION:
POST OAK CREEK 4.0
END DESCRIPTION:
XS GIS Cut Line= 4
      2866777.47     10068166.74      2866438.91     10067810.82
      2865961.48     10067869.41      2865707.56     10068053.89
#Sta/Elev= 30
  4338.8  1333.4  4432.2 1332.09  4460.5 1330.44  4509.8 1330.76    4524 1329.46
  4552.3 1329.94  4559.6 1329.28  4566.5 1329.78  4573.7 1328.72  4623.1 1328.61
  4799.9 1323.76  4821.3 1322.24    4901 1321.59  4921.2 1320.36  4931.2  1318.9
  4941.3 1317.09  4961.5 1309.95  4976.8 1306.46  4998.8 1304.83  5001.5 1304.33
  5004.8 1304.83    5032  1310.3  5082.4 1316.03  5243.6 1325.35  5307.3 1327.59
  5338.6 1330.91  5380.3  1333.3  5401.3 1335.65  5587.5  1346.9  5624.9 1348.32
#Mann= 3 ,-1 , 0
  4338.8     .16       0  4998.8     .07       0  5004.8     .16       0
Bank Sta=4998.8,5004.8
XS Rating Curve= 0 ,0
Exp/Cntr=0.3,0.1

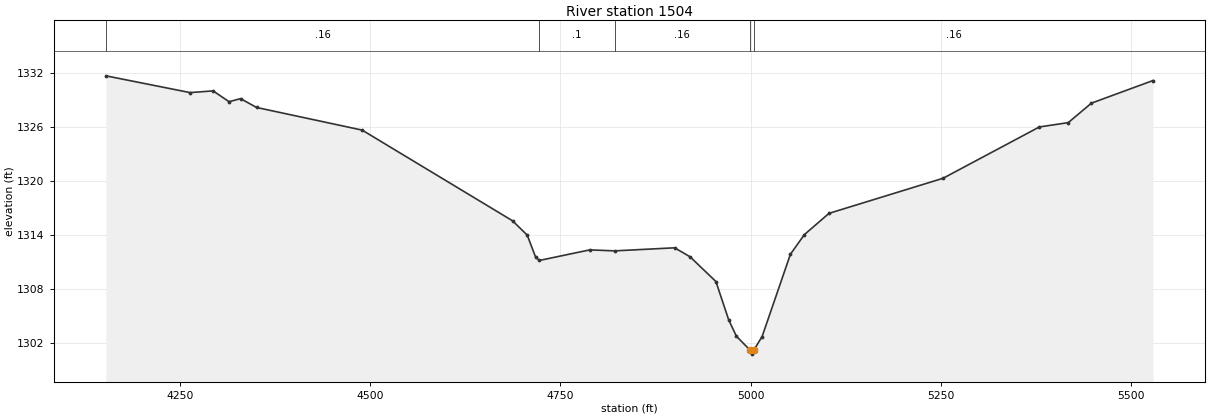
Type RM Length L Ch R = 1 ,1504    ,450,450,450
BEGIN DESCRIPTION:
POST OAK CREEK 3.0
END DESCRIPTION:
XS GIS Cut Line= 3
      2866920.66     10067626.34      2866616.87      10067426.7
      2865618.58     10067593.81
#Sta/Elev= 30
  4153.1 1331.67  4263.7 1329.81  4293.9    1330  4314.9  1328.8    4330 1329.14
  4351.1 1328.16  4489.8 1325.65  4687.4 1315.59  4706.6 1314.01  4717.8 1311.53
  4722.7  1311.2  4788.8 1312.37  4821.5 1312.26  4900.3  1312.6  4920.6  1311.6
  4954.5 1308.86  4971.3 1304.61  4981.4  1302.8  4998.7 1301.31  5001.4 1300.81
  5004.7 1301.31  5015.2 1302.76  5052.4 1311.89  5070.8 1314.07  5103.1 1316.42
  5252.9 1320.31  5379.4    1326  5417.4 1326.48  5447.8 1328.64  5528.8 1331.15
#Mann= 5 ,-1 , 0
  4153.1     .16       0  4722.7      .1       0  4821.5     .16       0
  4998.7     .07       0  5004.7     .16       0
Bank Sta=4998.7,5004.7
XS Rating Curve= 0 ,0
Exp/Cntr=0.3,0.1