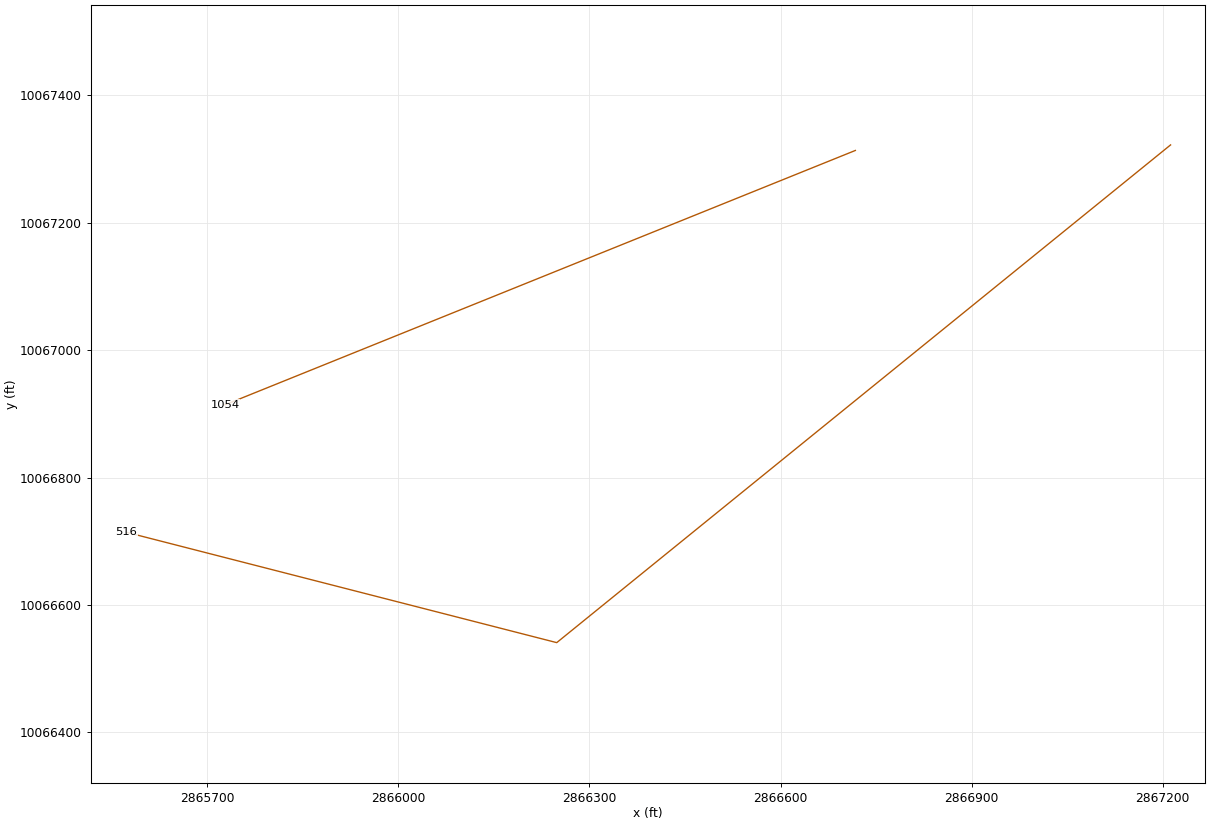
HEC-RAS study POST OAK CREEK.prj: POST OAK CREEK Base Level Engineering

--- POST OAK CREEK.g01 (geometry) --- (continued)

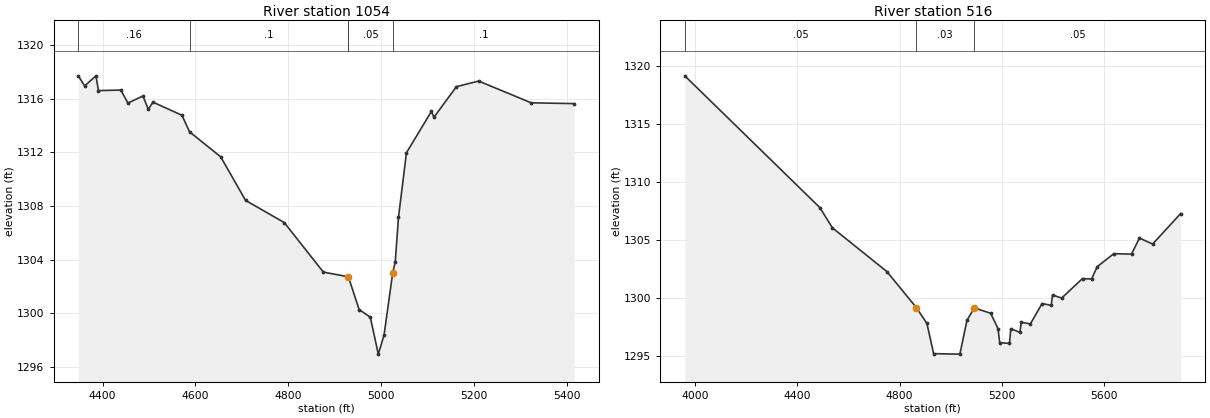
Type RM Length L Ch R = 1 ,1054    ,538,538,538
BEGIN DESCRIPTION:
POST OAK CREEK 2.0
END DESCRIPTION:
XS GIS Cut Line= 2
      2866717.42     10067313.39      2865727.84     10066914.09
#Sta/Elev= 30
  4347.9 1317.68  4361.6 1316.94  4385.8 1317.69  4391.2 1316.59  4439.5 1316.63
  4454.6 1315.66    4487 1316.19  4498.5 1315.19  4508.5 1315.73    4571 1314.75
  4587.2 1313.52  4654.2 1311.66  4707.9 1308.41  4791.1 1306.76  4875.2 1303.07
  4929.1 1302.72  4952.2 1300.28  4976.3 1299.71  4993.5 1296.96  5005.8 1298.37
  5024.6 1303.04    5030 1303.83  5036.9 1307.15  5054.1 1311.96  5107.8 1315.04
  5113.2  1314.6  5161.5 1316.88  5209.4  1317.3  5322.5 1315.68    5415 1315.62
#Mann= 5 ,-1 , 0
  4347.9     .16       0  4587.2      .1       0  4929.1     .16       0
  4929.1     .05       0  5024.6      .1       0
Bank Sta=4929.1,5024.6
XS Rating Curve= 0 ,0
Exp/Cntr=0.3,0.1

Type RM Length L Ch R = 1 ,516     ,0,0,0
BEGIN DESCRIPTION:
POST OAK CREEK 1.0
END DESCRIPTION:
XS GIS Cut Line= 3
      2867212.22     10067322.09      2866248.65     10066540.81
      2865572.53     10066714.18
#Sta/Elev= 30
  3960.5 1319.14  4488.3 1307.81  4537.8 1306.06  4750.7  1302.3  4865.5 1299.21
  4907.1 1297.84 4933.37 1295.24 5035.98  1295.2  5063.7 1298.11  5092.5 1299.18
  5156.4 1298.71  5185.2 1297.39  5191.6 1296.19  5229.9 1296.12  5235.1 1297.39
  5270.7 1297.07  5275.9 1297.94  5311.5  1297.8  5357.4 1299.55  5393.1  1299.4
  5398.2 1300.29  5433.8 1300.02  5515.4  1301.7    5551 1301.66  5572.8 1302.72
  5637.7 1303.84    5707  1303.8    5738 1305.18  5789.6 1304.67    5899 1307.29
#Mann= 3 , 0 , 0
  3960.5     .05       0  4865.5     .03       0  5092.5     .05       0
Bank Sta=4865.5,5092.5
XS Rating Curve= 0 ,0
Exp/Cntr=0.3,0.1

Chan Stop Cuts=-1
Use User Specified Reach Order=0
Composite Channel Slope=5