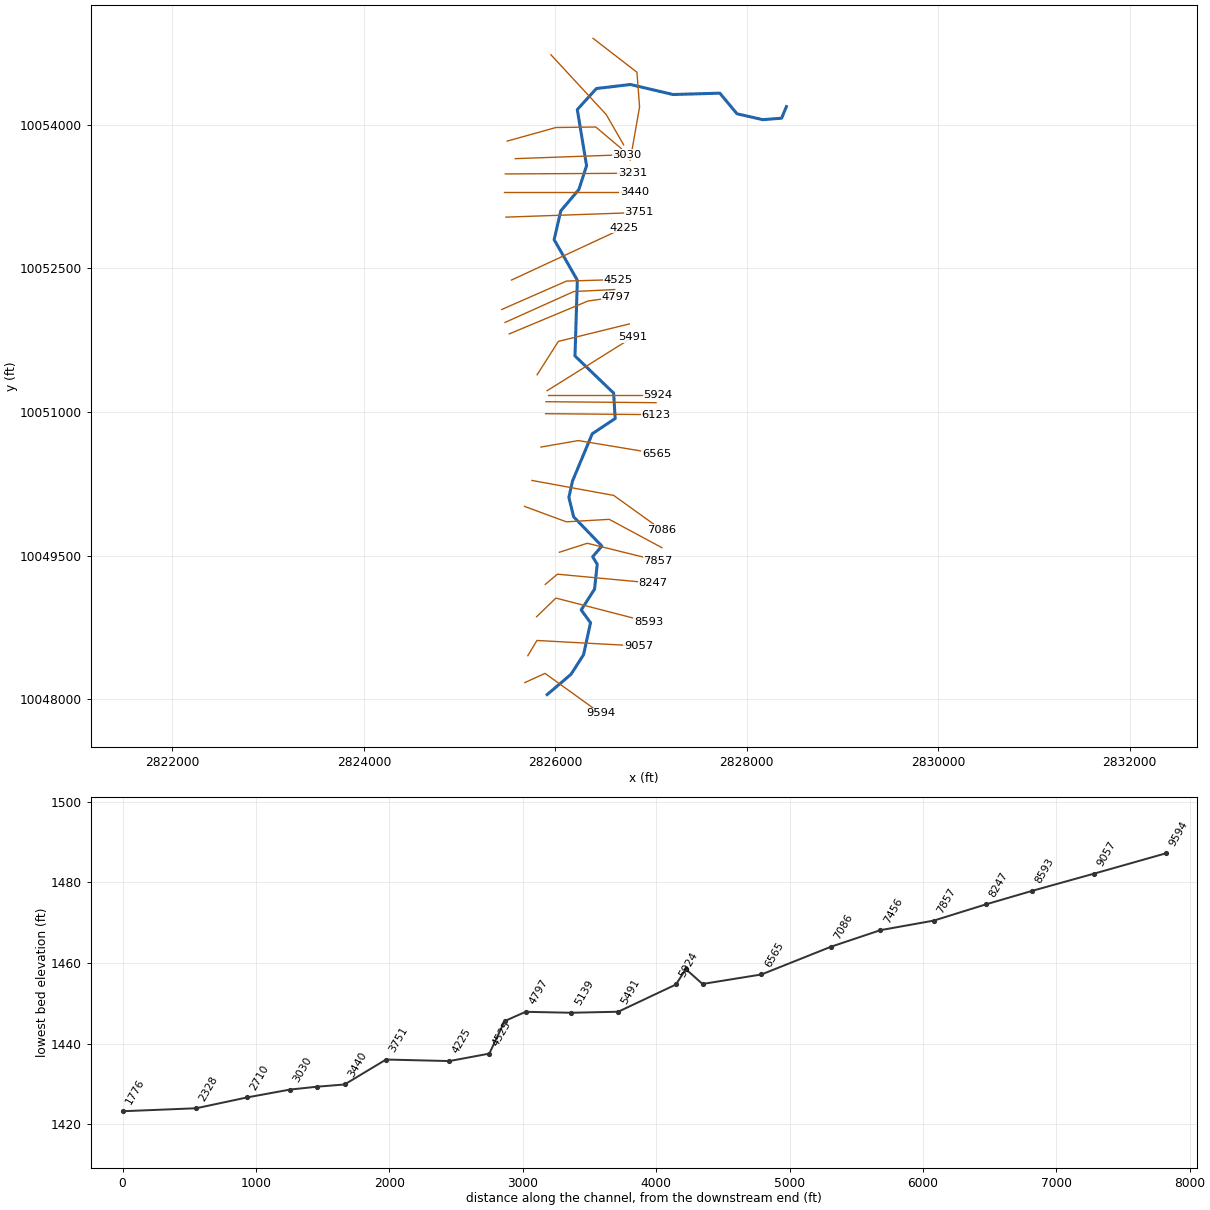
--- SALT BRANCH 2.prj (project) ---

Proj Title=SALT BRANCH Base Level Engineering
Current Plan=p01
Default Exp/Contr=0.3,0.1
English Units
Geom File=g01
Flow File=f01
Plan File=p01
BEGIN DESCRIPTION:
SALT BRANCH
END DESCRIPTION:

--- SALT BRANCH 2.p01 (plan) ---

Plan Title=Multiple Run
Short Identifier=Multiple
Geom File=g01
Flow File=f01
Subcritical Flow
K Sum by GR= 0
Std Step Tol= 0.01
Critical Tol= 0.01
Num of Std Step Trials= 20
Max Error Tol= 0.3
Flow Tol Ratio= 0.001
Split Flow NTrial= 30
Split Flow Tol= 0.02
Split Flow Ratio= 0.02
Log Output Level= 0
Friction Slope Method= 1
Unsteady Friction Slope Method= 2
Unsteady Bridges Friction Slope Method= 1
Parabolic Critical Depth
Global Vel Dist=  1 , 1 , 1
Global Log Level= 0
CheckData=True
Encroach Param= -1, 0, 0, 0
BEGIN DESCRIPTION:
Multiple Run
END DESCRIPTION:

--- SALT BRANCH 2.f01 (steady flow) ---

Flow Title=Multiple
Number of Profiles=7
Profile Names=10-year,25-year,50-year,1pct_min,100-year,1pct_plu,500-year
River Rch & RM= SALT BRANCH,Reach-1,9594
     696     988    1236    1133    1532    2072    2362
River Rch & RM= SALT BRANCH,Reach-1,7086
     834    1193    1500    1380    1866    2523    2898
River Rch & RM= SALT BRANCH,Reach-1,3231
    1410    2079    2667    2499    3379    4570    5452
River Rch & RM= SALT BRANCH,Reach-1,2328
    1475    2177    2796    2621    3545    4794    5726
Boundary for River Rch & Prof#=SALT BRANCH,Reach-1,1
Up Type=0
Dn Type=3
Dn Slope=0.005
Boundary for River Rch & Prof#=SALT BRANCH,Reach-1,2
Up Type=0
Dn Type=3
Dn Slope=0.005
Boundary for River Rch & Prof#=SALT BRANCH,Reach-1,3
Up Type=0
Dn Type=3
Dn Slope=0.005
Boundary for River Rch & Prof#=SALT BRANCH,Reach-1,4
Up Type=0
Dn Type=3
Dn Slope=0.005
Boundary for River Rch & Prof#=SALT BRANCH,Reach-1,5
Up Type=0
Dn Type=3
Dn Slope=0.005
Boundary for River Rch & Prof#=SALT BRANCH,Reach-1,6
Up Type=0
Dn Type=3
Dn Slope=0.005
Boundary for River Rch & Prof#=SALT BRANCH,Reach-1,7
Up Type=0
Dn Type=3
Dn Slope=0.005

--- SALT BRANCH 2.g01 (geometry) ---

Geom Title=Existing Conditions

River Reach=SALT BRANCH,Reach-1
Reach XY= 30
      2825915.84     10048048.03      2826165.02     10048260.35
      2826295.85     10048464.75      2826368.42     10048798.56
      2826271.30     10048932.44      2826410.68     10049149.71
      2826438.67     10049410.19      2826390.85     10049488.00
      2826487.15     10049599.49      2826192.29     10049905.32
      2826142.17     10050108.80      2826179.97     10050278.11
      2826386.40     10050772.96      2826626.15     10050932.13
      2826609.94     10051198.31      2826206.39     10051585.71
      2826230.81     10052377.03      2825988.47     10052800.68
      2826057.67     10053101.43      2826246.64     10053324.57
      2826327.19     10053573.49      2826230.41     10054160.31
      2826430.03     10054379.94      2826785.44     10054422.15
      2827230.89     10054317.53      2827719.69     10054331.61
      2827899.25     10054115.99      2828168.51     10054054.89
      2828364.99     10054069.96      2828415.22     10054190.96

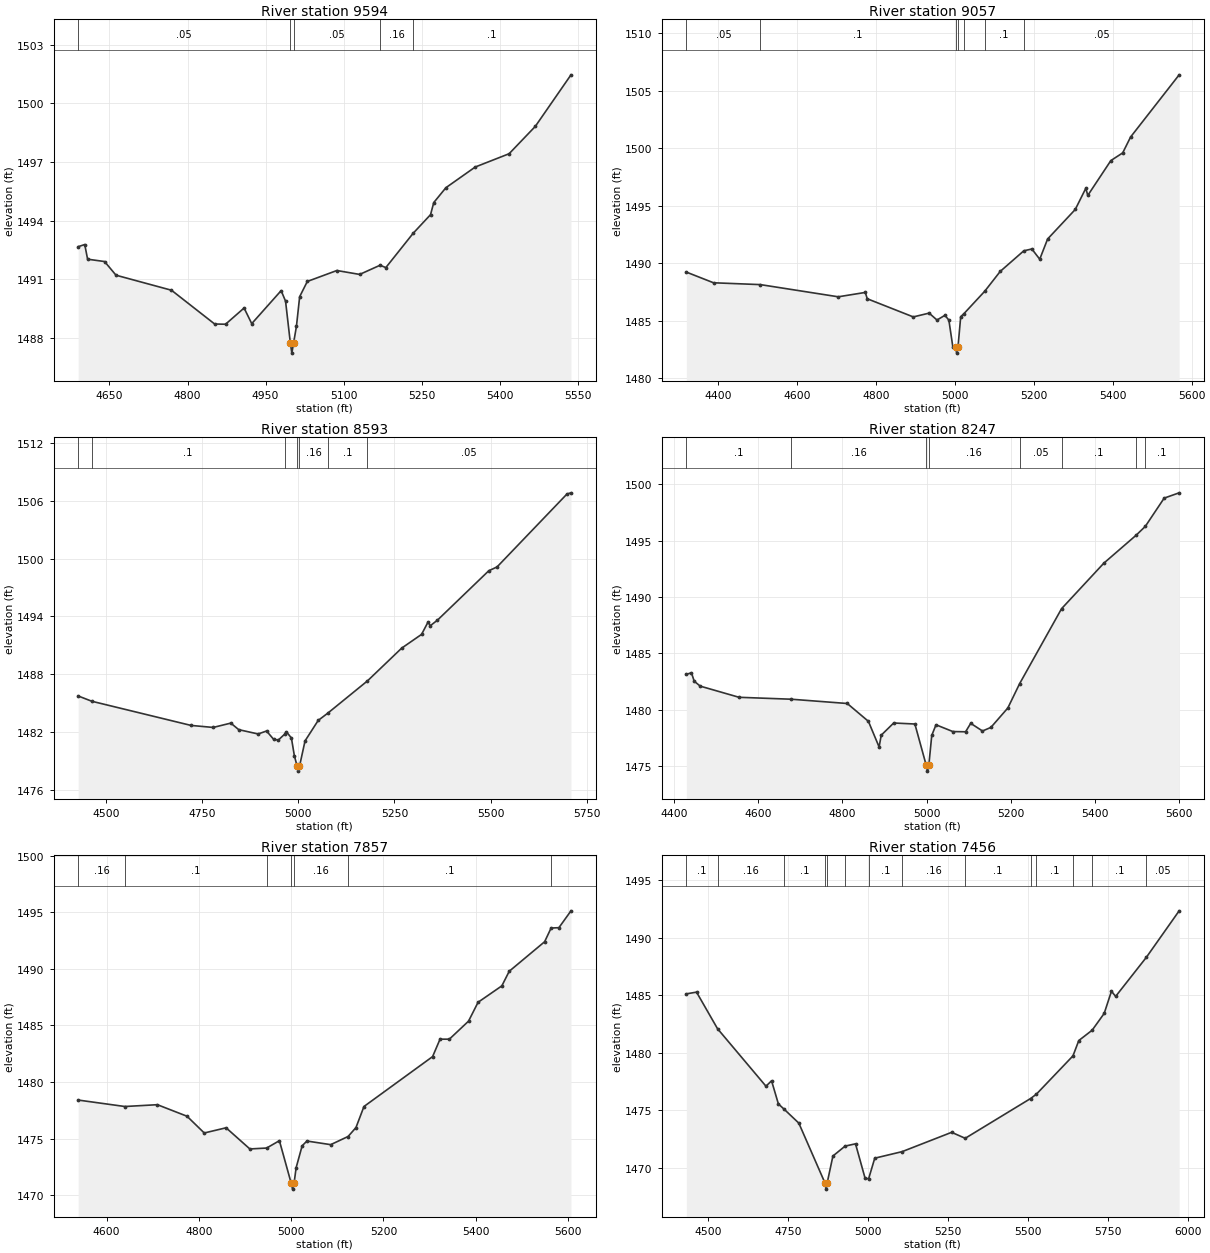
Type RM Length L Ch R = 1,9594,537,537,537
BEGIN DESCRIPTION:
SALT BRANCH 19.0
END DESCRIPTION:
XS GIS Cut Line= 3
      2825682.34     10048173.33      2825893.32     10048269.71
      2826473.51     10047851.75
#Sta/Elev= 30
  4589.9 1492.66  4602.5 1492.77  4608.0 1492.02  4640.6 1491.90  4662.6 1491.20
  4769.2 1490.43  4852.2 1488.70  4873.1 1488.69  4908.7 1489.52  4923.4 1488.72
  4979.9 1490.41  4988.4 1489.87  4997.7 1487.71  5000.5 1487.21  5003.7 1487.71
  5009.3 1488.58  5015.5 1490.10  5030.2 1490.88  5087.0 1491.44  5130.8 1491.24
  5170.0 1491.71  5181.1 1491.59  5233.7 1493.35  5267.0 1494.30  5273.2 1494.92
  5296.5 1495.68  5352.9 1496.74  5418.0 1497.42  5468.3 1498.82  5536.9 1501.46
#Mann=5,-1,0
  4589.9    0.05       0  4997.7   0.035       0  5003.7    0.05       0
  5170.0    0.16       0  5233.7     0.1       0
Bank Sta=4997.7,5003.7
Exp/Cntr=0.3,0.1

Type RM Length L Ch R = 1,9057,464,464,464
BEGIN DESCRIPTION:
Mapping XS 14f73ac6
END DESCRIPTION:
XS GIS Cut Line= 3
      2825713.63     10048454.60      2825808.81     10048613.37
      2826871.35     10048556.08
#Sta/Elev= 30
  4319.2 1489.23  4388.1 1488.30  4506.9 1488.14  4704.3 1487.08  4772.8 1487.46
  4777.8 1486.91  4894.5 1485.33  4934.6 1485.66  4954.6 1485.06  4974.7 1485.47
  4984.7 1485.05  4994.7 1482.73  5001.7 1482.68  5004.5 1482.18  5007.7 1482.68
  5014.7 1485.35  5022.5 1485.60  5075.5 1487.56  5114.9 1489.29  5174.6 1491.08
  5195.0 1491.24  5215.0 1490.35  5235.0 1492.11  5305.1 1494.68  5331.8 1496.52
  5336.8 1495.90  5395.3 1498.93  5425.3 1499.60  5445.3 1500.98  5568.4 1506.39
#Mann=7,-1,0
  4319.2    0.05       0  4506.9     0.1       0  5001.7    0.07       0
  5007.7     0.1       0  5022.5    0.16       0  5075.5     0.1       0
  5174.6    0.05       0
Bank Sta=5001.7,5007.7
Exp/Cntr=0.3,0.1

Type RM Length L Ch R = 1,8593,346,346,346
BEGIN DESCRIPTION:
SALT BRANCH 18.0
END DESCRIPTION:
XS GIS Cut Line= 3
      2825804.78     10048860.86      2826006.70     10049056.38
      2826974.45     10048806.34
#Sta/Elev= 30
  4428.2 1485.72  4463.7 1485.17  4721.4 1482.66  4779.0 1482.45  4824.8 1482.90
  4845.4 1482.22  4895.8 1481.77  4917.7 1482.08  4936.4 1481.20  4948.6 1481.15
  4964.7 1481.75  4969.3 1482.00  4982.3 1481.35  4990.0 1479.50  4997.3 1478.41
  5000.0 1477.91  5003.3 1478.41  5017.7 1481.05  5051.9 1483.18  5077.0 1483.94
  5180.0 1487.29  5268.8 1490.69  5320.5 1492.12  5337.7 1493.43  5342.9 1493.01
  5361.8 1493.60  5495.1 1498.73  5516.7 1499.13  5698.4 1506.71  5708.8 1506.83
#Mann=7,-1,0
  4428.2    0.05       0  4463.7     0.1       0  4964.7    0.16       0
  4997.3    0.07       0  5003.3    0.16       0  5077.0     0.1       0
  5180.0    0.05       0
Bank Sta=4997.3,5003.3
Exp/Cntr=0.3,0.1

Type RM Length L Ch R = 1,8247,390,390,390
BEGIN DESCRIPTION:
SALT BRANCH 17.0
END DESCRIPTION:
XS GIS Cut Line= 3
      2825895.95     10049199.42      2826022.35     10049306.08
      2827023.87     10049212.25
#Sta/Elev= 30
  4429.1 1483.14  4441.2 1483.29  4447.8 1482.54  4462.1 1482.10  4554.4 1481.11
  4678.3 1480.94  4811.6 1480.56  4861.8 1478.98  4887.3 1476.70  4892.3 1477.75
  4922.0 1478.83  4972.3 1478.74  4999.4 1475.06  5002.1 1474.56  5005.4 1475.06
  5012.4 1477.73  5022.5 1478.67  5062.6 1478.07  5092.8 1478.05  5105.0 1478.80
  5133.0 1478.12  5153.0 1478.44  5193.2 1480.16  5221.4 1482.33  5320.9 1488.97
  5421.4 1493.01  5497.9 1495.48  5519.9 1496.27  5564.8 1498.78  5600.4 1499.25
#Mann=8,-1,0
  4429.1     0.1       0  4678.3    0.16       0  4999.4    0.07       0
  5005.4    0.16       0  5221.4    0.05       0  5320.9     0.1       0
  5497.9    0.05       0  5519.9     0.1       0
Bank Sta=4999.4,5005.4
Exp/Cntr=0.3,0.1

Type RM Length L Ch R = 1,7857,401,401,401
BEGIN DESCRIPTION:
SALT BRANCH 16.0
END DESCRIPTION:
XS GIS Cut Line= 3
      2826043.15     10049535.23      2826334.85     10049629.00
      2827073.93     10049446.83
#Sta/Elev= 30
  4538.6 1478.41  4639.7 1477.84  4710.2 1478.00  4774.4 1476.98  4811.7 1475.50
  4859.0 1475.96  4910.5 1474.09  4946.9 1474.17  4974.5 1474.82  5000.2 1471.04
  5003.0 1470.54  5006.2 1471.04  5010.8 1472.44  5023.8 1474.37  5034.1 1474.79
  5085.6 1474.47  5123.3 1475.19  5140.4 1475.98  5157.7 1477.84  5306.4 1482.25
  5322.5 1483.79  5342.7 1483.79  5384.2 1485.38  5404.9 1487.05  5456.4 1488.50
  5472.4 1489.79  5549.1 1492.40  5563.1 1493.61  5580.0 1493.64  5606.2 1495.13
#Mann=7,-1,0
  4538.6    0.16       0  4639.7     0.1       0  4946.9    0.16       0
  5000.2    0.07       0  5006.2    0.16       0  5123.3     0.1       0
  5563.1    0.05       0
Bank Sta=5000.2,5006.2
Exp/Cntr=0.3,0.1

Type RM Length L Ch R = 1,7456,370,370,370
BEGIN DESCRIPTION:
SALT BRANCH 15.0
END DESCRIPTION:
XS GIS Cut Line= 4
      2825678.57     10050014.42      2826116.10     10049852.95
      2826564.02     10049879.00      2827114.79     10049582.83
#Sta/Elev= 30
  4432.9 1485.14  4464.8 1485.29  4530.4 1482.11  4681.8 1477.11  4699.3 1477.58
  4720.6 1475.57  4737.0 1475.15  4784.5 1473.90  4866.8 1468.66  4869.6 1468.16
  4872.8 1468.66  4891.1 1471.04  4929.1 1471.90  4961.7 1472.10  4991.8 1469.09
  5002.8 1469.07  5021.8 1470.85  5107.4 1471.42  5262.2 1473.10  5304.6 1472.58
  5509.0 1476.04  5526.8 1476.41  5641.5 1479.75  5659.6 1481.08  5701.4 1481.98
  5739.0 1483.44  5761.7 1485.37  5774.8 1484.92  5870.9 1488.32  5973.3 1492.36
#Mann=14,-1,0
  4432.9     0.1       0  4530.4    0.16       0  4737.0     0.1       0
  4866.8    0.07       0  4872.8     0.1       0  4929.1    0.16       0
  5002.8     0.1       0  5107.4    0.16       0  5304.6     0.1       0
  5509.0    0.05       0  5526.8     0.1       0  5641.5    0.05       0
  5701.4     0.1       0  5870.9    0.05       0
Bank Sta=4866.8,4872.8
Exp/Cntr=0.3,0.1

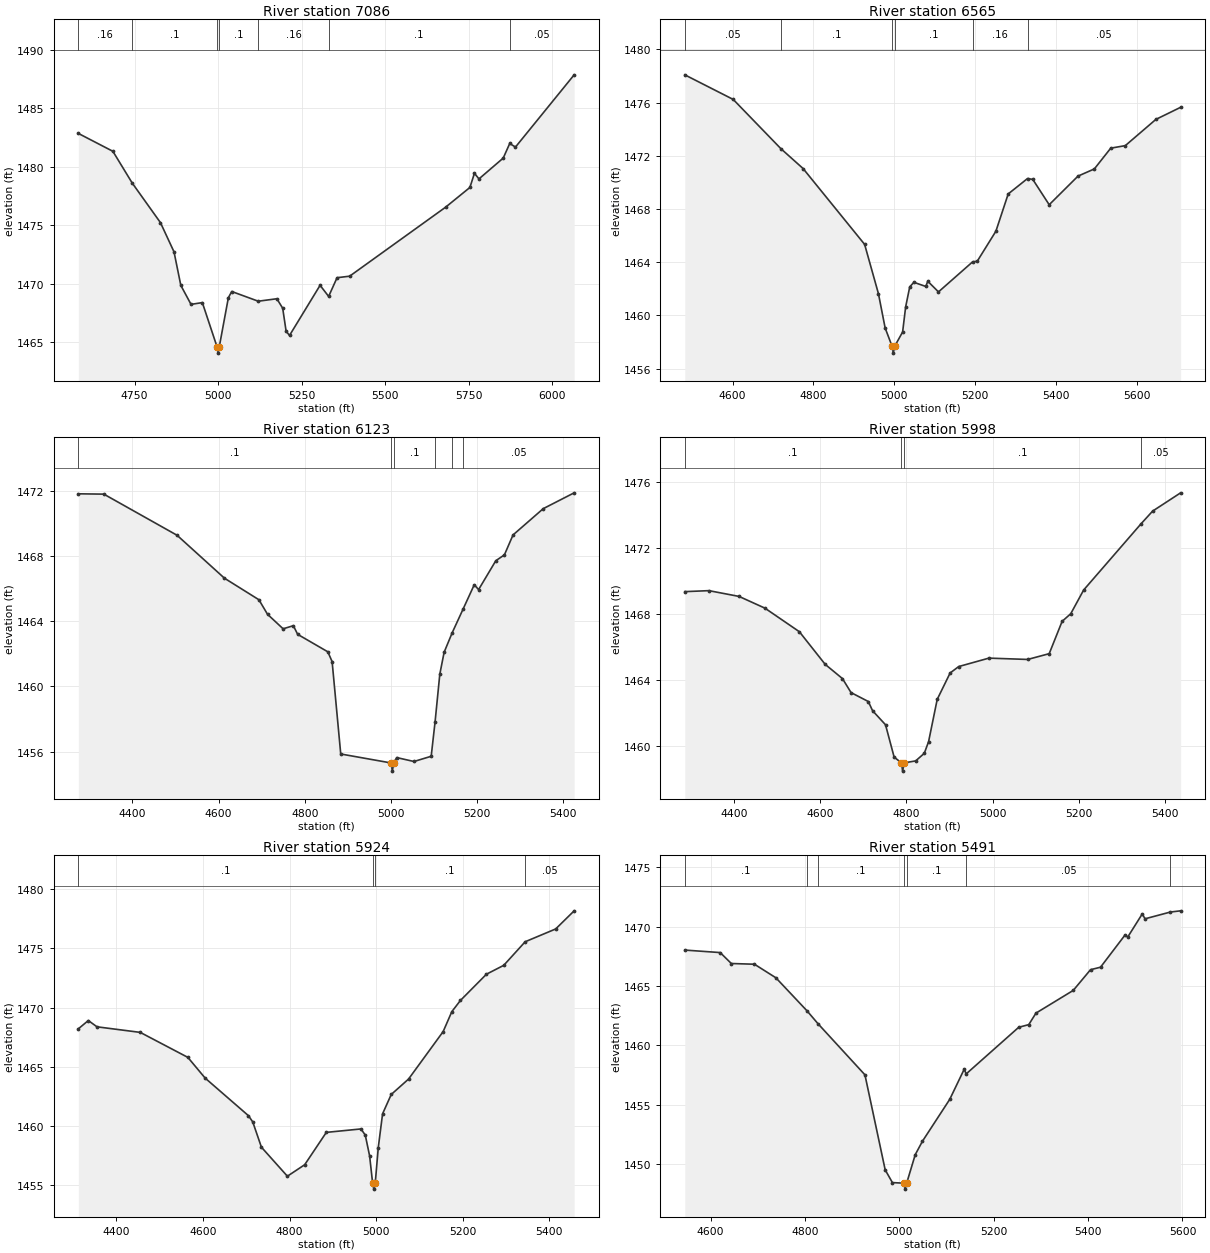
Type RM Length L Ch R = 1,7086,521,521,521
BEGIN DESCRIPTION:
SALT BRANCH 14.0
END DESCRIPTION:
XS GIS Cut Line= 3
      2825756.71     10050285.25      2826610.89     10050129.00
      2827110.89     10049769.62
#Sta/Elev= 30
  4581.6 1482.84  4685.0 1481.31  4743.0 1478.59  4827.4 1475.21  4868.0 1472.71
  4888.4 1469.84  4918.9 1468.22  4952.8 1468.37  4997.2 1464.55  4999.9 1464.05
  5003.2 1464.55  5030.7 1468.79  5040.8 1469.32  5120.1 1468.49  5175.8 1468.70
  5193.3 1467.89  5203.5 1465.93  5213.7 1465.56  5305.2 1469.85  5330.8 1468.90
  5356.0 1470.50  5393.7 1470.63  5680.9 1476.53  5753.7 1478.22  5767.2 1479.43
  5780.8 1478.95  5853.4 1480.73  5872.9 1481.98  5890.0 1481.67  6065.7 1487.85
#Mann=7,-1,0
  4581.6    0.16       0  4743.0     0.1       0  4997.2    0.07       0
  5003.2     0.1       0  5120.1    0.16       0  5330.8     0.1       0
  5872.9    0.05       0
Bank Sta=4997.2,5003.2
Exp/Cntr=0.3,0.1

Type RM Length L Ch R = 1,6565,442,442,442
BEGIN DESCRIPTION:
SALT BRANCH 13.0
END DESCRIPTION:
XS GIS Cut Line= 3
      2825850.49     10050634.21      2826241.10     10050701.91
      2827058.83     10050566.49
#Sta/Elev= 30
  4482.1 1478.08  4601.8 1476.23  4719.6 1472.53  4774.4 1471.04  4926.5 1465.34
  4960.6 1461.64  4977.2 1459.06  4994.5 1457.67  4997.3 1457.17  5000.5 1457.67
  5020.4 1458.76  5027.9 1460.65  5038.0 1462.15  5048.2 1462.49  5077.6 1462.18
  5082.6 1462.57  5109.0 1461.77  5193.4 1464.03  5204.7 1464.07  5250.9 1466.33
  5281.3 1469.13  5329.1 1470.29  5342.1 1470.22  5382.6 1468.32  5453.8 1470.47
  5494.2 1471.01  5534.7 1472.57  5570.7 1472.76  5646.2 1474.73  5707.4 1475.64
#Mann=6,-1,0
  4482.1    0.05       0  4719.6     0.1       0  4994.5    0.07       0
  5000.5     0.1       0  5193.4    0.16       0  5329.1    0.05       0
Bank Sta=4994.5,5000.5
Exp/Cntr=0.3,0.1

Type RM Length L Ch R = 1,6123,125,125,125
BEGIN DESCRIPTION:
Mapping XS cae5aa89
END DESCRIPTION:
XS GIS Cut Line= 2
      2825899.26     10050983.05      2827050.31     10050972.63
#Sta/Elev= 30
  4274.4 1471.80  4333.6 1471.78  4503.6 1469.26  4613.6 1466.63  4693.6 1465.31
  4713.6 1464.42  4749.8 1463.53  4773.6 1463.72  4783.6 1463.19  4853.6 1462.12
  4863.6 1461.52  4883.6 1455.86  5000.6 1455.31  5003.4 1454.81  5006.6 1455.31
  5013.6 1455.64  5053.6 1455.40  5093.6 1455.72  5102.7 1457.85  5113.6 1460.75
  5123.6 1462.09  5142.4 1463.29  5168.2 1464.77  5193.6 1466.23  5203.6 1465.93
  5243.6 1467.70  5263.6 1468.06  5283.6 1469.28  5353.7 1470.89  5425.5 1471.86
#Mann=6,-1,0
  4274.4     0.1       0  5000.6    0.07       0  5006.6     0.1       0
  5102.7    0.16       0  5142.4     0.1       0  5168.2    0.05       0
Bank Sta=5000.6,5006.6
Exp/Cntr=0.3,0.1

Type RM Length L Ch R = 1,5998,74,74,74
BEGIN DESCRIPTION:
Mapping XS 3d3339a4
END DESCRIPTION:
XS GIS Cut Line= 2
      2825902.52     10051108.16      2827053.57     10051097.75
#Sta/Elev= 30
  4285.6 1469.38  4341.6 1469.44  4411.6 1469.09  4471.6 1468.38  4551.6 1466.95
  4611.6 1464.97  4651.6 1464.11  4671.6 1463.26  4711.6 1462.72  4721.6 1462.16
  4751.6 1461.31  4771.6 1459.35  4788.6 1459.00  4791.3 1458.50  4794.6 1459.00
  4821.6 1459.12  4841.6 1459.58  4851.6 1460.29  4871.6 1462.85  4901.6 1464.45
  4921.6 1464.84  4991.6 1465.35  5081.6 1465.27  5131.6 1465.62  5161.6 1467.58
  5181.6 1468.04  5211.6 1469.48  5344.4 1473.48  5371.6 1474.26  5436.7 1475.37
#Mann=4,-1,0
  4285.6     0.1       0  4788.6    0.07       0  4794.6     0.1       0
  5344.4    0.05       0
Bank Sta=4788.6,4794.6
Exp/Cntr=0.3,0.1

Type RM Length L Ch R = 1,5924,433,433,433
BEGIN DESCRIPTION:
Mapping XS 527b52b6
END DESCRIPTION:
XS GIS Cut Line= 2
      2825925.34     10051175.75      2827071.14     10051175.75
#Sta/Elev= 30
  4311.9 1468.21  4335.0 1468.91  4355.0 1468.38  4455.0 1467.91  4565.0 1465.80
  4605.0 1464.05  4705.0 1460.88  4715.0 1460.35  4735.0 1458.22  4795.0 1455.77
  4835.0 1456.74  4885.0 1459.47  4965.0 1459.76  4975.0 1459.24  4985.0 1457.49
  4992.0 1455.18  4994.8 1454.68  4998.0 1455.18  5005.0 1458.18  5015.0 1461.04
  5035.0 1462.67  5075.0 1463.97  5155.0 1467.98  5175.0 1469.66  5195.0 1470.61
  5255.0 1472.82  5295.0 1473.57  5344.5 1475.56  5415.0 1476.64  5457.7 1478.17
#Mann=4,-1,0
  4311.9     0.1       0  4992.0    0.07       0  4998.0     0.1       0
  5344.5    0.05       0
Bank Sta=4992,4998
Exp/Cntr=0.3,0.1

Type RM Length L Ch R = 1,5491,352,352,352
BEGIN DESCRIPTION:
SALT BRANCH 12.0
END DESCRIPTION:
XS GIS Cut Line= 2
      2825914.89     10051222.63      2826805.50     10051779.91
#Sta/Elev= 30
  4545.5 1468.02  4620.5 1467.81  4644.1 1466.89  4693.1 1466.83  4738.5 1465.69
  4804.5 1462.91  4827.7 1461.83  4927.2 1457.53  4970.1 1449.54  4985.4 1448.47
  5009.6 1448.42  5012.3 1447.92  5015.6 1448.42  5033.8 1450.82  5049.1 1451.95
  5106.9 1455.47  5137.5 1458.00  5141.8 1457.61  5253.1 1461.53  5274.3 1461.75
  5289.6 1462.72  5368.6 1464.63  5405.2 1466.37  5426.4 1466.58  5478.2 1469.28
  5484.1 1469.12  5514.8 1471.06  5520.7 1470.65  5574.6 1471.22  5596.1 1471.32
#Mann=7,-1,0
  4545.5     0.1       0  4804.5    0.16       0  4827.7     0.1       0
  5009.6    0.07       0  5015.6     0.1       0  5141.8    0.05       0
  5574.6     0.1       0
Bank Sta=5009.6,5015.6
Exp/Cntr=0.3,0.1

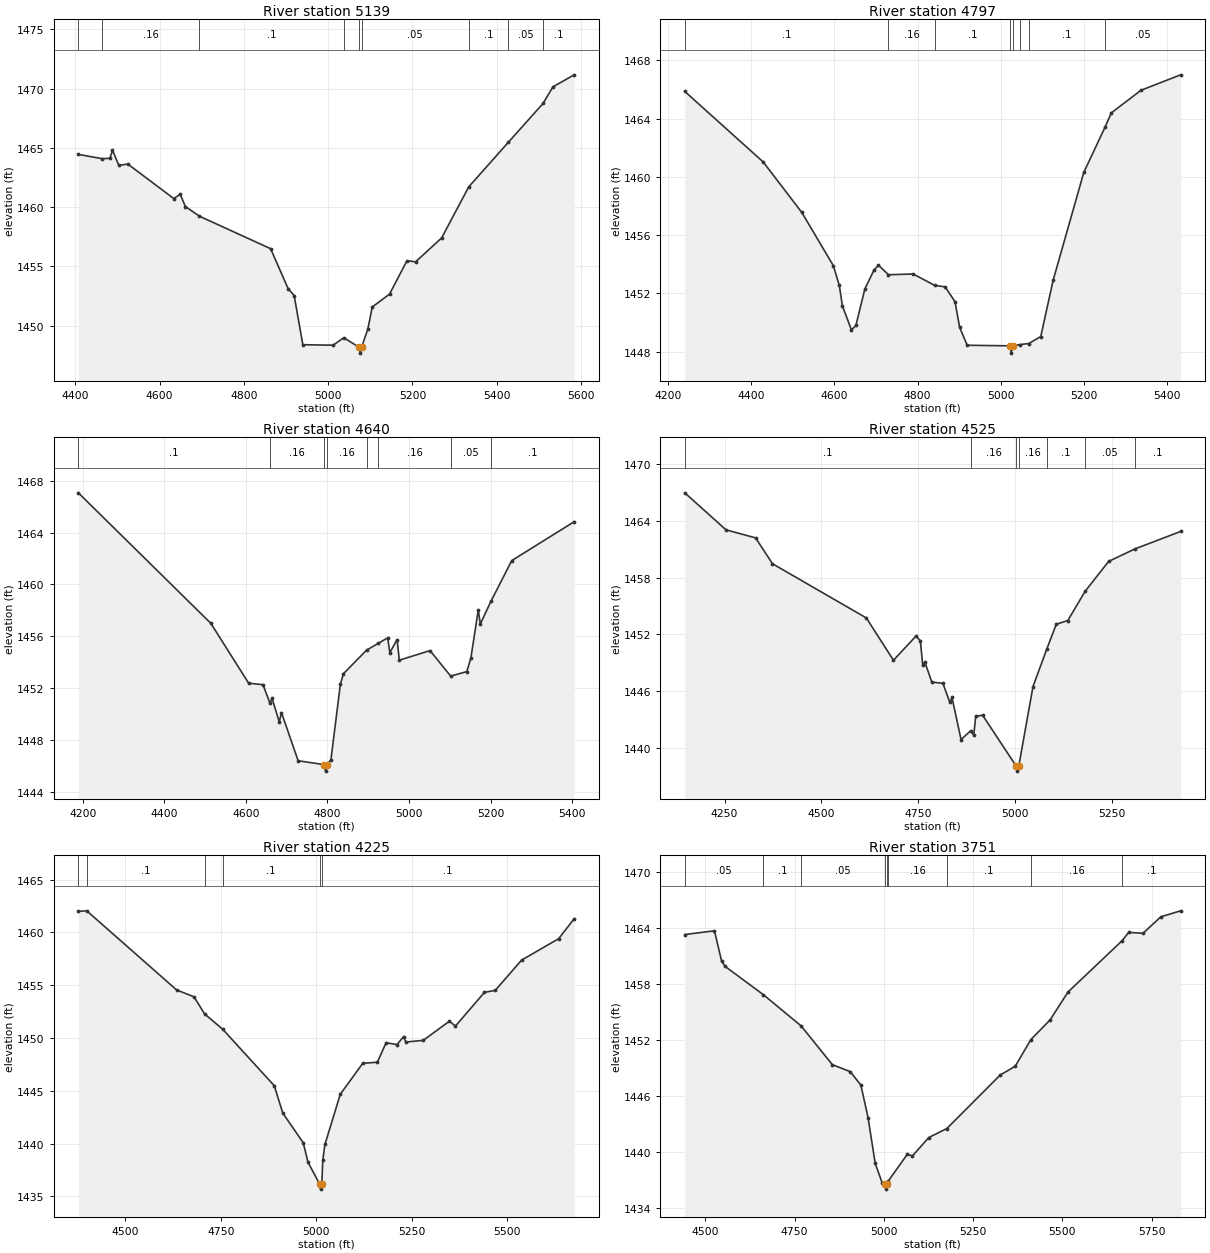
Type RM Length L Ch R = 1,5139,342,342,342
BEGIN DESCRIPTION:
SALT BRANCH 11.0
END DESCRIPTION:
XS GIS Cut Line= 3
      2825810.72     10051389.29      2826032.77     10051738.37
      2826773.91     10051920.46
#Sta/Elev= 30
  4406.9 1464.45  4463.1 1464.09  4481.9 1464.12  4487.9 1464.81  4503.1 1463.52
  4524.3 1463.64  4633.5 1460.72  4648.7 1461.09  4661.0 1460.05  4694.4 1459.23
  4863.3 1456.49  4904.8 1453.12  4919.2 1452.53  4939.8 1448.38  5011.8 1448.34
  5036.9 1448.97  5073.2 1448.17  5075.9 1447.67  5079.2 1448.17  5094.2 1449.71
  5104.5 1451.56  5145.7 1452.66  5186.9 1455.47  5207.5 1455.38  5269.3 1457.40
  5333.6 1461.71  5427.2 1465.46  5509.9 1468.75  5533.3 1470.15  5583.8 1471.17
#Mann=9,-1,0
  4406.9     0.1       0  4463.1    0.16       0  4694.4     0.1       0
  5036.9    0.05       0  5073.2    0.07       0  5079.2    0.05       0
  5333.6     0.1       0  5427.2    0.05       0  5509.9     0.1       0
Bank Sta=5073.2,5079.2
Exp/Cntr=0.3,0.1

Type RM Length L Ch R = 1,4797,157,157,157
BEGIN DESCRIPTION:
SALT BRANCH 10.0
END DESCRIPTION:
XS GIS Cut Line= 3
      2825519.07     10051816.38      2826341.97     10052160.13
      2826638.85     10052201.80
#Sta/Elev= 30
  4240.6 1465.86  4429.0 1461.02  4521.7 1457.56  4597.6 1453.90  4611.9 1452.55
  4619.3 1451.15  4641.1 1449.49  4651.8 1449.80  4673.4 1452.31  4695.1 1453.59
  4706.0 1453.94  4730.0 1453.28  4789.4 1453.33  4841.1 1452.55  4866.2 1452.45
  4890.0 1451.43  4901.0 1449.68  4919.3 1448.44  5022.3 1448.40  5025.1 1447.90
  5028.3 1448.40  5046.9 1448.49  5067.4 1448.56  5096.1 1449.04  5126.0 1452.92
  5199.6 1460.31  5250.4 1463.40  5265.7 1464.39  5337.0 1465.94  5432.2 1467.00
#Mann=8,-1,0
  4240.6     0.1       0  4730.0    0.16       0  4841.1     0.1       0
  5022.3    0.07       0  5028.3     0.1       0  5046.9    0.05       0
  5067.4     0.1       0  5250.4    0.05       0
Bank Sta=5022.3,5028.3
Exp/Cntr=0.3,0.1

Type RM Length L Ch R = 1,4640,115,115,115
BEGIN DESCRIPTION:
Mapping XS 3a092ad3
END DESCRIPTION:
XS GIS Cut Line= 3
      2825475.47     10051936.29      2826194.23     10052259.20
      2826621.36     10052280.04
#Sta/Elev= 30
  4189.2 1467.07  4514.1 1457.00  4606.8 1452.38  4642.0 1452.27  4659.0 1450.83
  4664.1 1451.22  4681.8 1449.40  4687.2 1450.12  4728.1 1446.40  4792.4 1446.10
  4795.2 1445.60  4798.4 1446.10  4808.5 1446.48  4831.7 1452.32  4839.3 1453.12
  4895.8 1454.93  4924.7 1455.46  4947.5 1455.88  4953.0 1454.74  4970.7 1455.75
  4976.2 1454.16  5051.5 1454.90  5102.1 1452.93  5141.6 1453.28  5151.6 1454.32
  5169.7 1458.03  5174.7 1456.95  5200.6 1458.69  5251.7 1461.84  5404.8 1464.84
#Mann=8,-1,0
  4189.2     0.1       0  4659.0    0.16       0  4792.4    0.07       0
  4798.4    0.16       0  4895.8     0.1       0  4924.7    0.16       0
  5102.1    0.05       0  5200.6     0.1       0
Bank Sta=4792.4,4798.4
Exp/Cntr=0.3,0.1

Type RM Length L Ch R = 1,4525,300,300,300
BEGIN DESCRIPTION:
Mapping XS 65021bf6
END DESCRIPTION:
XS GIS Cut Line= 3
      2825440.96     10052071.60      2826118.01     10052368.46
      2826659.71     10052384.09
#Sta/Elev= 30
  4147.3 1467.00  4253.8 1463.08  4330.2 1462.23  4373.9 1459.49  4616.4 1453.75
  4686.5 1449.27  4745.1 1451.85  4756.0 1451.31  4762.1 1448.77  4767.6 1449.08
  4785.5 1446.97  4814.3 1446.82  4832.2 1444.80  4837.7 1445.33  4861.1 1440.87
  4885.7 1441.80  4894.0 1441.33  4899.0 1443.34  4917.0 1443.44  5004.1 1438.03
  5006.8 1437.53  5010.1 1438.03  5047.1 1446.49  5082.9 1450.48  5107.1 1453.08
  5137.1 1453.48  5181.5 1456.56  5242.5 1459.74  5310.4 1461.06  5428.5 1462.91
#Mann=7,-1,0
  4147.3     0.1       0  4885.7    0.16       0  5004.1    0.07       0
  5010.1    0.16       0  5082.9     0.1       0  5181.5    0.05       0
  5310.4     0.1       0
Bank Sta=5004.1,5010.1
Exp/Cntr=0.3,0.1

Type RM Length L Ch R = 1,4225,474,474,474
BEGIN DESCRIPTION:
SALT BRANCH 9.0
END DESCRIPTION:
XS GIS Cut Line= 2
      2825543.22     10052379.01      2826720.29     10052925.88
#Sta/Elev= 30
  4377.0 1461.99  4399.1 1462.04  4634.1 1454.55  4679.9 1453.89  4707.4 1452.28
  4755.0 1450.82  4890.0 1445.47  4912.1 1442.89  4965.7 1440.07  4978.2 1438.23
  5008.3 1436.18  5011.0 1435.68  5014.3 1436.18  5017.0 1438.44  5022.5 1439.91
  5062.8 1444.67  5121.6 1447.60  5159.8 1447.70  5182.7 1449.55  5211.1 1449.37
  5228.5 1450.13  5234.0 1449.61  5279.8 1449.77  5348.5 1451.59  5364.1 1451.12
  5440.1 1454.32  5468.5 1454.51  5537.2 1457.37  5634.3 1459.40  5674.9 1461.29
#Mann=6,-1,0
  4377.0    0.05       0  4399.1     0.1       0  4707.4    0.16       0
  4755.0     0.1       0  5008.3    0.07       0  5014.3     0.1       0
Bank Sta=5008.3,5014.3
Exp/Cntr=0.3,0.1

Type RM Length L Ch R = 1,3751,311,311,311
BEGIN DESCRIPTION:
SALT BRANCH 8.0
END DESCRIPTION:
XS GIS Cut Line= 2
      2825485.32     10053036.44      2826873.87     10053085.04
#Sta/Elev= 30
  4442.1 1463.34  4525.3 1463.74  4545.3 1460.48  4555.3 1459.92  4662.4 1456.89
  4768.0 1453.55  4855.5 1449.40  4905.5 1448.65  4935.5 1447.21  4955.6 1443.73
  4975.6 1438.83  4995.6 1436.69  5002.6 1436.56  5005.3 1436.06  5008.6 1436.56
  5012.9 1436.96  5065.6 1439.79  5080.1 1439.62  5125.7 1441.59  5176.3 1442.55
  5325.8 1448.28  5368.1 1449.23  5411.8 1452.08  5465.9 1454.20  5515.9 1457.18
  5667.3 1462.67  5686.0 1463.57  5726.0 1463.47  5776.1 1465.24  5831.5 1465.88
#Mann=9,-1,0
  4442.1    0.05       0  4662.4     0.1       0  4768.0    0.05       0
  5002.6   0.035       0  5008.6    0.05       0  5012.9    0.16       0
  5176.3     0.1       0  5411.8    0.16       0  5667.3     0.1       0
Bank Sta=5002.6,5008.6
Exp/Cntr=0.3,0.1

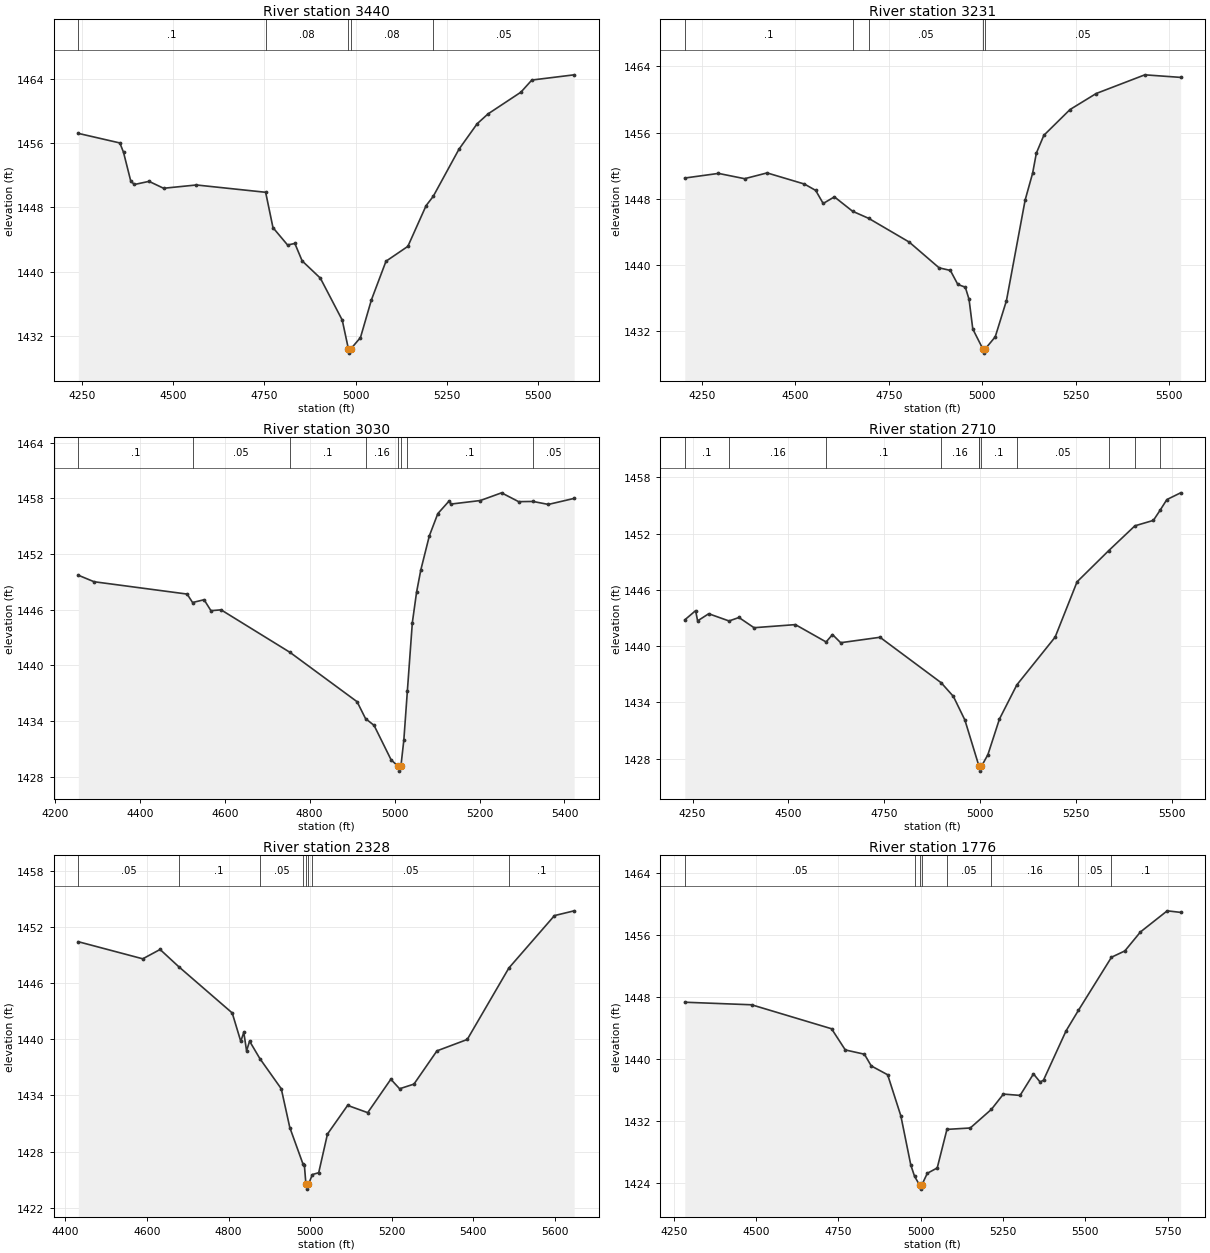
Type RM Length L Ch R = 1,3440,209,209,209
BEGIN DESCRIPTION:
Mapping XS ee335ce9
END DESCRIPTION:
XS GIS Cut Line= 2
      2825464.54     10053300.33      2826824.54     10053300.33
#Sta/Elev= 30
  4239.7 1457.22  4353.6 1456.03  4363.6 1454.87  4383.6 1451.27  4393.6 1450.86
  4433.6 1451.25  4473.6 1450.39  4563.6 1450.80  4753.5 1449.89  4773.6 1445.49
  4813.6 1443.33  4833.6 1443.52  4853.6 1441.35  4903.6 1439.20  4963.6 1433.98
  4980.6 1430.37  4983.4 1429.87  4986.6 1430.37  5013.6 1431.81  5043.6 1436.50
  5083.6 1441.31  5143.6 1443.16  5193.6 1448.23  5213.1 1449.38  5283.6 1455.24
  5333.6 1458.42  5363.6 1459.65  5453.6 1462.35  5483.6 1463.86  5599.7 1464.51
#Mann=5,-1,0
  4239.7     0.1       0  4753.5    0.08       0  4980.6    0.07       0
  4986.6    0.08       0  5213.1    0.05       0
Bank Sta=4980.6,4986.6
Exp/Cntr=0.3,0.1

Type RM Length L Ch R = 1,3231,201,201,201
BEGIN DESCRIPTION:
Mapping XS 94c2c169
END DESCRIPTION:
XS GIS Cut Line= 2
      2825478.45     10053487.83      2826804.13     10053494.77
#Sta/Elev= 30
  4204.4 1450.50  4294.4 1451.06  4364.4 1450.42  4424.4 1451.12  4524.4 1449.77
  4554.4 1449.00  4574.4 1447.42  4604.4 1448.22  4653.0 1446.48  4696.1 1445.62
  4804.4 1442.75  4884.4 1439.63  4914.4 1439.32  4934.4 1437.62  4954.4 1437.29
  4964.4 1435.82  4974.4 1432.23  5001.4 1429.81  5004.2 1429.31  5007.4 1429.81
  5034.4 1431.28  5064.4 1435.66  5114.4 1447.84  5134.4 1451.09  5144.4 1453.52
  5164.4 1455.67  5234.4 1458.79  5304.4 1460.73  5434.4 1462.99  5530.1 1462.68
#Mann=5,-1,0
  4204.4     0.1       0  4653.0    0.08       0  4696.1    0.05       0
  5001.4    0.04       0  5007.4    0.05       0
Bank Sta=5001.4,5007.4
Exp/Cntr=0.3,0.1

Type RM Length L Ch R = 1,3030,320,320,320
BEGIN DESCRIPTION:
SALT BRANCH 7.0
END DESCRIPTION:
XS GIS Cut Line= 2
      2825582.58     10053647.55      2826749.23     10053689.22
#Sta/Elev= 30
  4255.4 1449.71  4292.4 1449.01  4511.5 1447.68  4524.4 1446.77  4551.5 1447.07
  4567.6 1445.89  4591.5 1445.98  4753.7 1441.40  4911.7 1436.08  4931.6 1434.26
  4951.7 1433.53  4991.8 1429.82  5008.8 1429.10  5011.5 1428.60  5014.8 1429.10
  5021.8 1431.95  5030.1 1437.24  5041.8 1444.60  5051.8 1447.89  5061.8 1450.29
  5081.8 1453.95  5101.8 1456.35  5128.0 1457.69  5133.0 1457.38  5201.9 1457.76
  5251.9 1458.59  5292.0 1457.64  5325.9 1457.66  5362.0 1457.34  5422.8 1457.99
#Mann=8,-1,0
  4255.4     0.1       0  4524.4    0.05       0  4753.7     0.1       0
  4931.6    0.16       0  5008.8    0.07       0  5014.8    0.16       0
  5030.1     0.1       0  5325.9    0.05       0
Bank Sta=5008.8,5014.8
Exp/Cntr=0.3,0.1

Type RM Length L Ch R = 1,2710,382,382,382
BEGIN DESCRIPTION:
SALT BRANCH 6.0
END DESCRIPTION:
XS GIS Cut Line= 4
      2825497.67     10053830.75      2826006.73     10053972.75
      2826423.39     10053977.95      2826689.00     10053754.01
#Sta/Elev= 30
  4229.8 1442.80  4258.0 1443.78  4263.2 1442.69  4292.2 1443.45  4345.1 1442.68
  4371.0 1443.05  4410.3 1441.96  4518.1 1442.29  4598.2 1440.44  4614.8 1441.23
  4636.2 1440.36  4738.7 1440.94  4898.2 1436.09  4930.0 1434.63  4960.0 1432.11
  4996.8 1427.18  4997.0 1427.16  4999.8 1426.66  5003.0 1427.16  5020.0 1428.42
  5050.1 1432.22  5095.4 1435.86  5195.3 1440.96  5252.5 1446.86  5334.8 1450.18
  5403.2 1452.83  5451.4 1453.41  5468.7 1454.48  5486.5 1455.63  5522.4 1456.35
#Mann=11,-1,0
  4229.8     0.1       0  4345.1    0.16       0  4598.2     0.1       0
  4898.2    0.16       0  4996.8     0.1       0  4997.0    0.07       0
  5003.0     0.1       0  5095.4    0.05       0  5334.8     0.1       0
  5403.2    0.05       0  5468.7     0.1       0
Bank Sta=4997,5003
Exp/Cntr=0.3,0.1

Type RM Length L Ch R = 1,2328,552,552,552
BEGIN DESCRIPTION:
SALT BRANCH 5.0
END DESCRIPTION:
XS GIS Cut Line= 3
      2825954.68     10054733.13      2826532.77     10054108.16
      2826714.25     10053791.86
#Sta/Elev= 30
  4431.7 1450.47  4589.7 1448.64  4632.2 1449.64  4677.6 1447.81  4809.1 1442.84
  4830.1 1439.80  4837.5 1440.77  4844.3 1438.78  4851.7 1439.82  4876.8 1437.96
  4929.4 1434.72  4950.3 1430.57  4982.4 1426.69  4986.0 1426.58  4989.9 1424.47
  4992.6 1423.97  4995.9 1424.47  5005.7 1425.53  5021.2 1425.73  5042.7 1429.87
  5092.1 1432.94  5141.4 1432.16  5198.1 1435.74  5219.6 1434.72  5254.8 1435.22
  5311.2 1438.78  5385.5 1440.00  5487.5 1447.65  5599.4 1453.27  5647.7 1453.78
#Mann=8,-1,0
  4431.7    0.05       0  4677.6     0.1       0  4876.8    0.05       0
  4982.4     0.1       0  4989.9    0.07       0  4995.9     0.1       0
  5005.7    0.05       0  5487.5     0.1       0
Bank Sta=4989.9,4995.9
Exp/Cntr=0.3,0.1

Type RM Length L Ch R = 1,1776,0,0,0
BEGIN DESCRIPTION:
SALT BRANCH 4.0
END DESCRIPTION:
XS GIS Cut Line= 4
      2826395.07     10054904.49      2826853.40     10054550.33
      2826881.18     10054189.22      2826783.96     10053633.66
#Sta/Elev= 30
  4283.8 1447.32  4486.7 1446.99  4729.4 1443.90  4771.1 1441.17  4829.1 1440.62
  4849.9 1439.11  4899.7 1437.97  4939.8 1432.67  4969.9 1426.35  4981.3 1424.89
  4997.0 1423.73  4999.8 1423.23  5003.0 1423.73  5020.1 1425.27  5050.2 1425.96
  5079.7 1430.93  5150.5 1431.11  5214.9 1433.52  5251.1 1435.48  5301.8 1435.31
  5342.4 1438.08  5362.7 1437.03  5372.9 1437.28  5441.4 1443.63  5478.7 1446.26
  5579.3 1453.12  5619.8 1453.93  5667.3 1456.38  5748.5 1459.10  5789.2 1458.90
#Mann=8,-1,0
  4283.8    0.05       0  4981.3    0.16       0  4997.0    0.07       0
  5003.0    0.16       0  5079.7    0.05       0  5214.9    0.16       0
  5478.7    0.05       0  5579.3     0.1       0
Bank Sta=4997,5003
Exp/Cntr=0.3,0.1

Chan Stop Cuts=-1