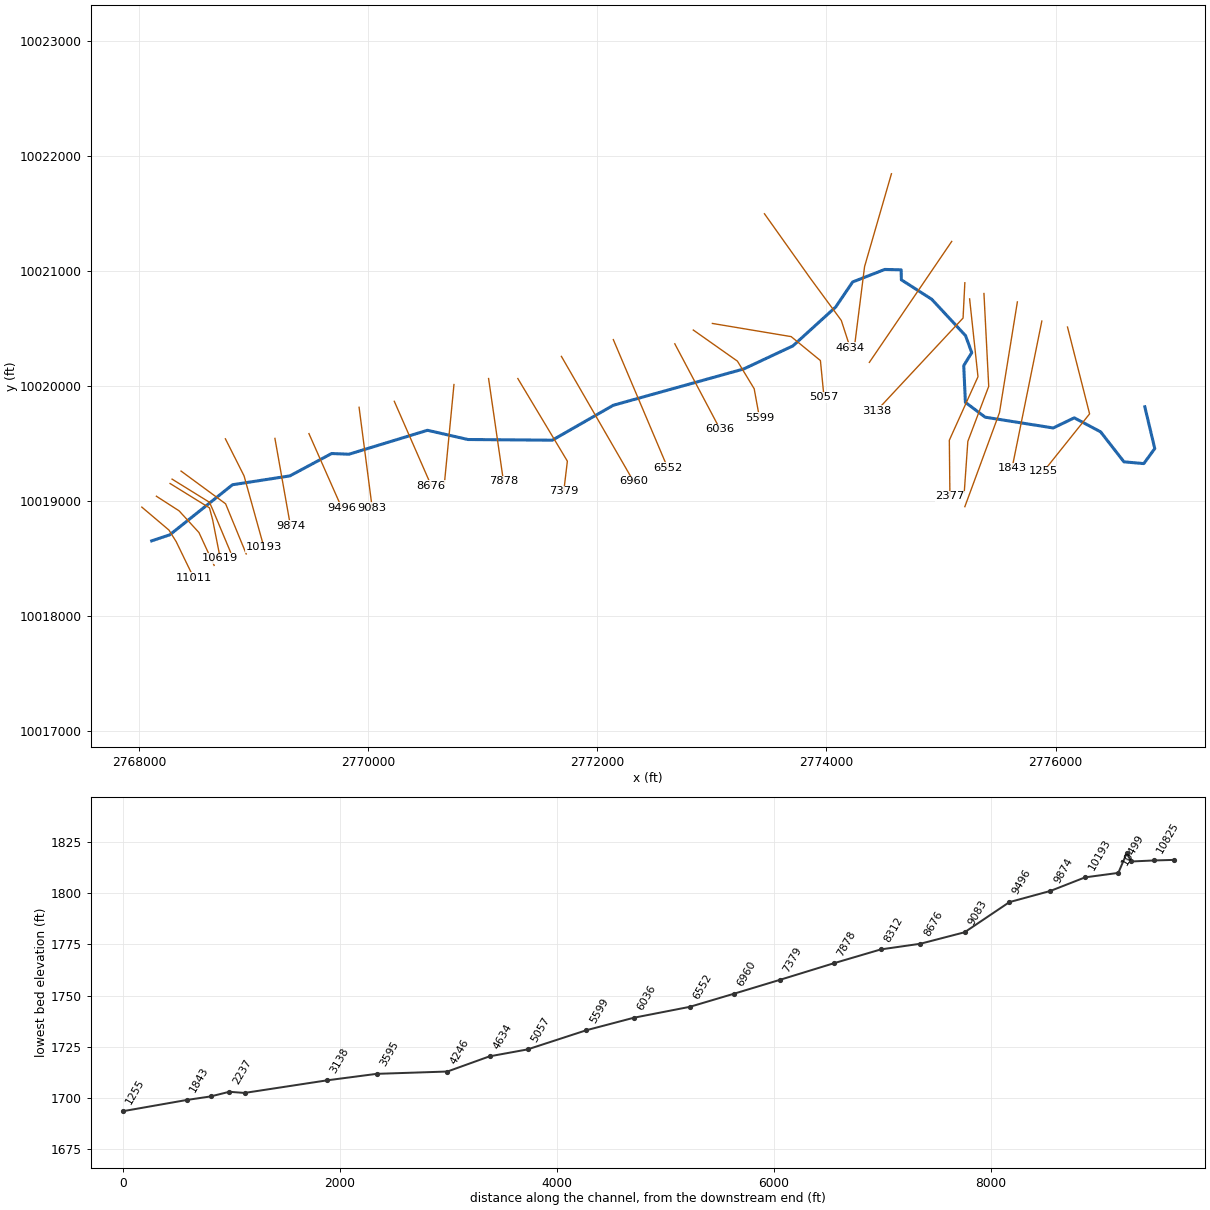
--- SCHOOL CREEK.prj (project) ---

Proj Title=SCHOOL CREEK Base Level Engineering
Current Plan=p01
Default Exp/Contr=0.3,0.1
English Units
Geom File=g01
Flow File=f01
Plan File=p01
Y Axis Title=Elevation
X Axis Title(PF)=Main Channel Distance
X Axis Title(XS)=Station
BEGIN DESCRIPTION:
SCHOOL CREEK
END DESCRIPTION:
DSS Export Rating Curves= 0
DSS Export Rating Curve Sorted= 0
DSS Export Volume Flow Curves= 0
DXF OffsetX= 0
DXF OffsetY= 0
DXF ScaleX= 1
DXF ScaleY= 10

--- SCHOOL CREEK.p01 (plan) ---

Plan Title=Multiple Run
Short Identifier=Multiple
Geom File=g01
Flow File=f01
Subcritical Flow
K Sum by GR= 0
Std Step Tol= 0.01
Critical Tol= 0.01
Num of Std Step Trials= 20
Max Error Tol= 0.3
Flow Tol Ratio= 0.001
Split Flow NTrial= 30
Split Flow Tol= 0.02
Split Flow Ratio= 0.02
Log Output Level= 0
Friction Slope Method= 1
Unsteady Friction Slope Method= 2
Unsteady Bridges Friction Slope Method= 1
Parabolic Critical Depth
Global Vel Dist=  1 , 1 , 1
Global Log Level= 0
CheckData=True
Encroach Param= -1, 0, 0, 0
BEGIN DESCRIPTION:
Multiple Run
END DESCRIPTION:

--- SCHOOL CREEK.f01 (steady flow) ---

Flow Title=Multiple
Program Version=4.10
Number of Profiles= 7
Profile Names=10-year,25-year,50-year,1pct_min,100-year,1pct_plu,500-year
River Rch & RM=SCHOOL CREEK,Reach-1         ,11011
     832    1207    1533    1427    1930    2609    3067
River Rch & RM=SCHOOL CREEK,Reach-1         ,9083
    1004    1470    1877    1754    2372    3208    3806
River Rch & RM=SCHOOL CREEK,Reach-1         ,4634
    2179    3312    4339    4148    5610    7586    9424
River Rch & RM=SCHOOL CREEK,Reach-1         ,4246
    2179    3312    4339    4148    5610    7586    9424
Boundary for River Rch & Prof#=SCHOOL CREEK,Reach-1         , 1
Up Type= 0
Dn Type= 3
Dn Slope=0.0096
Boundary for River Rch & Prof#=SCHOOL CREEK,Reach-1         , 2
Up Type= 0
Dn Type= 3
Dn Slope=0.0096
Boundary for River Rch & Prof#=SCHOOL CREEK,Reach-1         , 3
Up Type= 0
Dn Type= 3
Dn Slope=0.0096
Boundary for River Rch & Prof#=SCHOOL CREEK,Reach-1         , 4
Up Type= 0
Dn Type= 3
Dn Slope=0.0096
Boundary for River Rch & Prof#=SCHOOL CREEK,Reach-1         , 5
Up Type= 0
Dn Type= 3
Dn Slope=0.0096
Boundary for River Rch & Prof#=SCHOOL CREEK,Reach-1         , 6
Up Type= 0
Dn Type= 3
Dn Slope=0.0096
Boundary for River Rch & Prof#=SCHOOL CREEK,Reach-1         , 7
Up Type= 0
Dn Type= 3
Dn Slope=0.0096
DSS Import GetInterval= 0
DSS Import GetPeak= 0
DSS Import FillOption= 0

--- SCHOOL CREEK.g01 (geometry) ---

Geom Title=Existing Conditions
Program Version=4.10

River Reach=SCHOOL CREEK    ,Reach-1
Reach XY= 30
      2768110.91     10018651.58      2768268.46     10018703.67
      2768816.57     10019139.67      2769317.22     10019216.74
      2769681.26     10019411.15       2769832.6      10019405.2
      2770517.94     10019613.39      2770871.51      10019533.1
      2771607.03      10019527.2      2772139.63     10019831.04
      2773277.24     10020146.69      2773706.92     10020347.46
      2774080.67     10020686.05      2774228.47     10020903.73
      2774508.97     10021012.55       2774651.6     10021009.15
      2774653.33      10020922.2      2774918.39     10020753.15
       2775213.6     10020436.39      2775267.52     10020288.77
      2775197.63     10020175.67      2775212.13      10019856.5
      2775384.82      10019727.4      2775978.59     10019633.51
      2776162.28      10019721.6      2776392.15     10019599.83
      2776595.96     10019338.99      2776769.12      10019323.7
      2776864.81     10019454.53      2776777.86     10019817.43

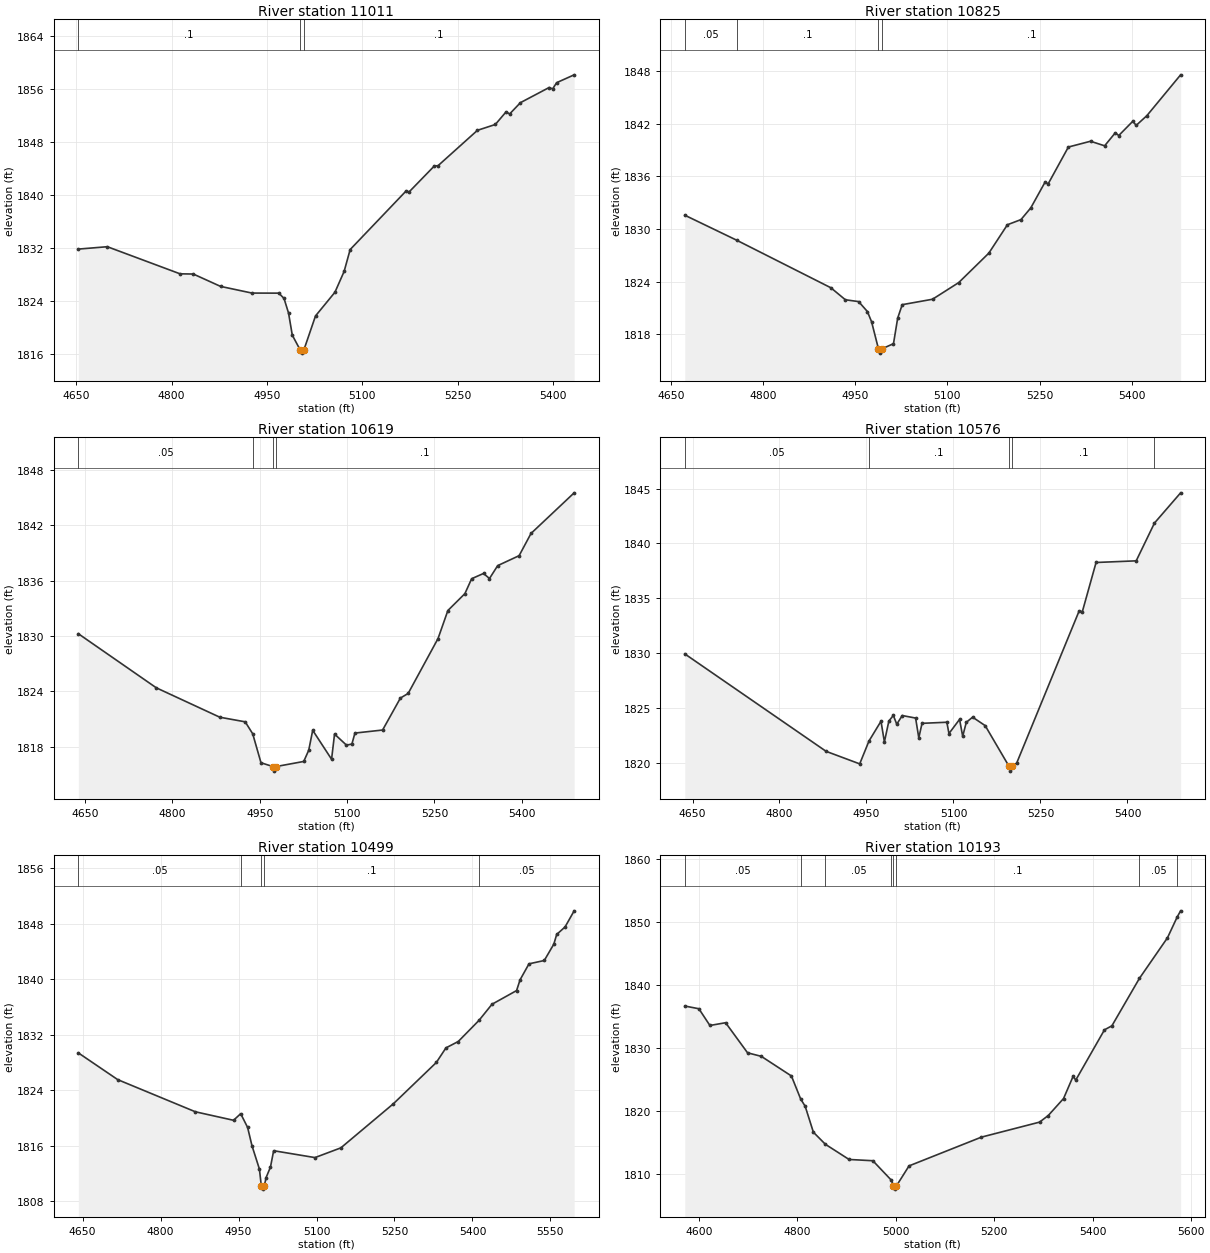
Type RM Length L Ch R = 1 ,11011   ,186,186,186
BEGIN DESCRIPTION:
SCHOOL CREEK 22.0
END DESCRIPTION:
XS GIS Cut Line= 4
        2768025.     10018945.12       2768261.7     10018745.37
      2768324.45     10018645.67      2768478.51     10018328.87
#Sta/Elev= 30
  4653.2 1831.85  4698.8 1832.21  4813.2 1828.11    4834 1828.08  4876.9 1826.21
  4926.3  1825.2  4968.5 1825.19  4976.7 1824.39  4983.8 1822.18  4989.7 1818.84
    5002 1816.62  5004.7 1816.12    5008 1816.62  5026.2 1821.74  5056.8 1825.33
  5071.2 1828.47  5080.7 1831.78  5168.1 1840.58  5173.7 1840.52  5213.2 1844.43
  5218.8 1844.45  5280.9 1849.81    5309 1850.69    5326 1852.61  5331.5 1852.28
  5348.5 1853.99  5393.6 1856.28  5399.2 1856.07  5405.4 1857.01    5433  1858.2
#Mann= 3 ,-1 , 0
  4653.2      .1       0    5002     .07       0    5008      .1       0
Bank Sta=5002,5008
XS Rating Curve= 0 ,0
Exp/Cntr=0.3,0.1

Type RM Length L Ch R = 1 ,10825   ,206,206,206
BEGIN DESCRIPTION:
SCHOOL CREEK 21.0
END DESCRIPTION:
XS GIS Cut Line= 4
      2768152.28     10019039.67      2768350.49      10018912.6
      2768523.85     10018723.67      2768656.14     10018438.08
#Sta/Elev= 30
  4672.8 1831.58  4757.1 1828.73  4910.4  1823.3    4934 1821.93  4955.6 1821.72
  4969.8 1820.59  4976.6 1819.43  4987.8 1816.34  4990.5 1815.84  4993.8 1816.34
  5012.3 1816.92  5019.1 1819.83  5026.5 1821.37  5075.8 1821.99  5118.4 1823.89
  5167.4 1827.25  5197.6 1830.49  5219.7 1831.08  5235.7 1832.42  5258.6 1835.32
  5264.1 1835.18  5296.8 1839.36  5332.8 1840.02  5355.8  1839.5  5373.2 1840.99
  5378.7 1840.67  5401.6  1842.3  5407.1 1841.83  5424.5 1842.94  5479.4  1847.6
#Mann= 4 ,-1 , 0
  4672.8     .05       0  4757.1      .1       0  4987.8     .07       0
  4993.8      .1       0
Bank Sta=4987.8,4993.8
XS Rating Curve= 0 ,0
Exp/Cntr=0.3,0.1

Type RM Length L Ch R = 1 ,10619   ,43,43,43
BEGIN DESCRIPTION:
SCHOOL CREEK 20.0
END DESCRIPTION:
XS GIS Cut Line= 4
       2768271.7     10019150.31      2768615.43     10018938.52
      2768643.21     10018834.35      2768709.17     10018501.06
#Sta/Elev= 30
  4638.6 1830.25  4772.5 1824.38  4881.5 1821.19  4925.1 1820.69    4938 1819.39
  4952.2 1816.25  4972.4 1815.84  4975.2 1815.34  4978.4 1815.84  5025.6 1816.39
  5034.2 1817.61    5041 1819.77  5073.4 1816.63  5078.5 1819.36    5099 1818.16
  5108.3 1818.28  5113.5 1819.47    5161  1819.8  5191.6 1823.27  5204.9 1823.77
  5256.2 1829.73  5273.1 1832.77  5302.3  1834.6  5313.9 1836.22  5334.3 1836.79
  5344.5 1836.24  5358.6 1837.64  5395.4 1838.72  5415.8 1841.13  5489.9 1845.54
#Mann= 4 ,-1 , 0
  4638.6     .05       0    4938      .1       0  4972.4     .07       0
  4978.4      .1       0
Bank Sta=4972.4,4978.4
XS Rating Curve= 0 ,0
Exp/Cntr=0.3,0.1

Type RM Length L Ch R = 1 ,10576   ,77,77,77
BEGIN DESCRIPTION:
Mapping XS 87402892
END DESCRIPTION:
XS GIS Cut Line= 4
      2768289.02     10019188.53      2768615.43     10018987.13
      2768643.21     10018924.63      2768799.46     10018553.08
#Sta/Elev= 30
  4636.7 1829.95  4880.4 1821.08  4938.3 1819.94  4954.3 1822.02    4975 1823.82
  4980.9 1821.94  4988.6 1823.84  4996.3 1824.35  5002.2 1823.55  5011.7 1824.34
  5034.7 1824.11  5040.2 1822.31  5045.8 1823.63  5088.6 1823.73  5092.2  1822.7
  5110.5 1823.99  5115.9 1822.45  5122.1 1823.72    5133 1824.19  5154.7 1823.42
  5195.1 1819.78  5197.8 1819.28  5201.1 1819.78  5208.9    1820  5316.7 1833.86
  5322.2 1833.79  5345.9 1838.27  5415.1 1838.42  5446.6 1841.86  5491.7 1844.61
#Mann= 5 ,-1 , 0
  4636.7     .05       0  4954.3      .1       0  5195.1     .07       0
  5201.1      .1       0  5446.6     .05       0
Bank Sta=5195.1,5201.1
XS Rating Curve= 0 ,0
Exp/Cntr=0.3,0.1

Type RM Length L Ch R = 1 ,10499   ,306,306,306
BEGIN DESCRIPTION:
Mapping XS aaabf68f
END DESCRIPTION:
XS GIS Cut Line= 3
      2768367.32     10019258.64      2768756.18     10018973.94
      2768936.26     10018537.58
#Sta/Elev= 30
  4641.7 1829.39  4717.5 1825.54    4867 1820.91  4940.3 1819.69  4954.1 1820.64
  4967.4 1818.66  4975.8 1816.03  4990.1 1812.67  4993.7 1810.28  4996.4 1809.78
  4999.7 1810.28  5002.9 1811.43  5011.4 1812.96  5017.5 1815.31    5097 1814.32
  5146.8 1815.72  5247.9 1822.07  5330.5 1828.01    5349 1830.11  5372.7 1831.03
  5412.6 1834.07  5437.6 1836.39  5484.9 1838.36  5491.7 1839.92  5508.8 1842.21
  5538.2 1842.69  5556.6 1845.05  5562.1 1846.44  5578.2 1847.52  5595.7 1849.84
#Mann= 5 ,-1 , 0
  4641.7     .05       0  4954.1      .1       0  4993.7     .07       0
  4999.7      .1       0  5412.6     .05       0
Bank Sta=4993.7,4999.7
XS Rating Curve= 0 ,0
Exp/Cntr=0.3,0.1

Type RM Length L Ch R = 1 ,10193   ,319,319,319
BEGIN DESCRIPTION:
Mapping XS 8c1540e9
END DESCRIPTION:
XS GIS Cut Line= 3
       2768754.3     10019539.24      2768917.51     10019216.29
      2769091.13     10018594.73
#Sta/Elev= 30
  4571.2 1836.68  4599.8 1836.25  4622.2 1833.59  4654.1 1834.03  4698.7 1829.25
  4726.6 1828.69  4787.8 1825.57  4806.7 1821.89  4815.7 1820.77  4832.4 1816.64
  4856.8 1814.72  4904.9 1812.31  4953.2 1812.11  4990.9 1809.01    4995  1808.1
  4997.7  1807.6    5001  1808.1  5026.7 1811.29  5173.8 1815.86  5291.8 1818.24
  5309.5 1819.29  5340.6 1821.99  5360.1 1825.53  5365.3 1824.91  5423.7  1832.9
  5438.8 1833.54  5494.6 1841.06  5551.7 1847.52  5571.6 1850.85  5578.4  1851.8
#Mann= 8 ,-1 , 0
  4571.2     .05       0  4806.7      .1       0  4856.8     .05       0
  4990.9      .1       0    4995     .07       0    5001      .1       0
  5494.6     .05       0  5571.6      .1       0
Bank Sta=4995,5001
XS Rating Curve= 0 ,0
Exp/Cntr=0.3,0.1

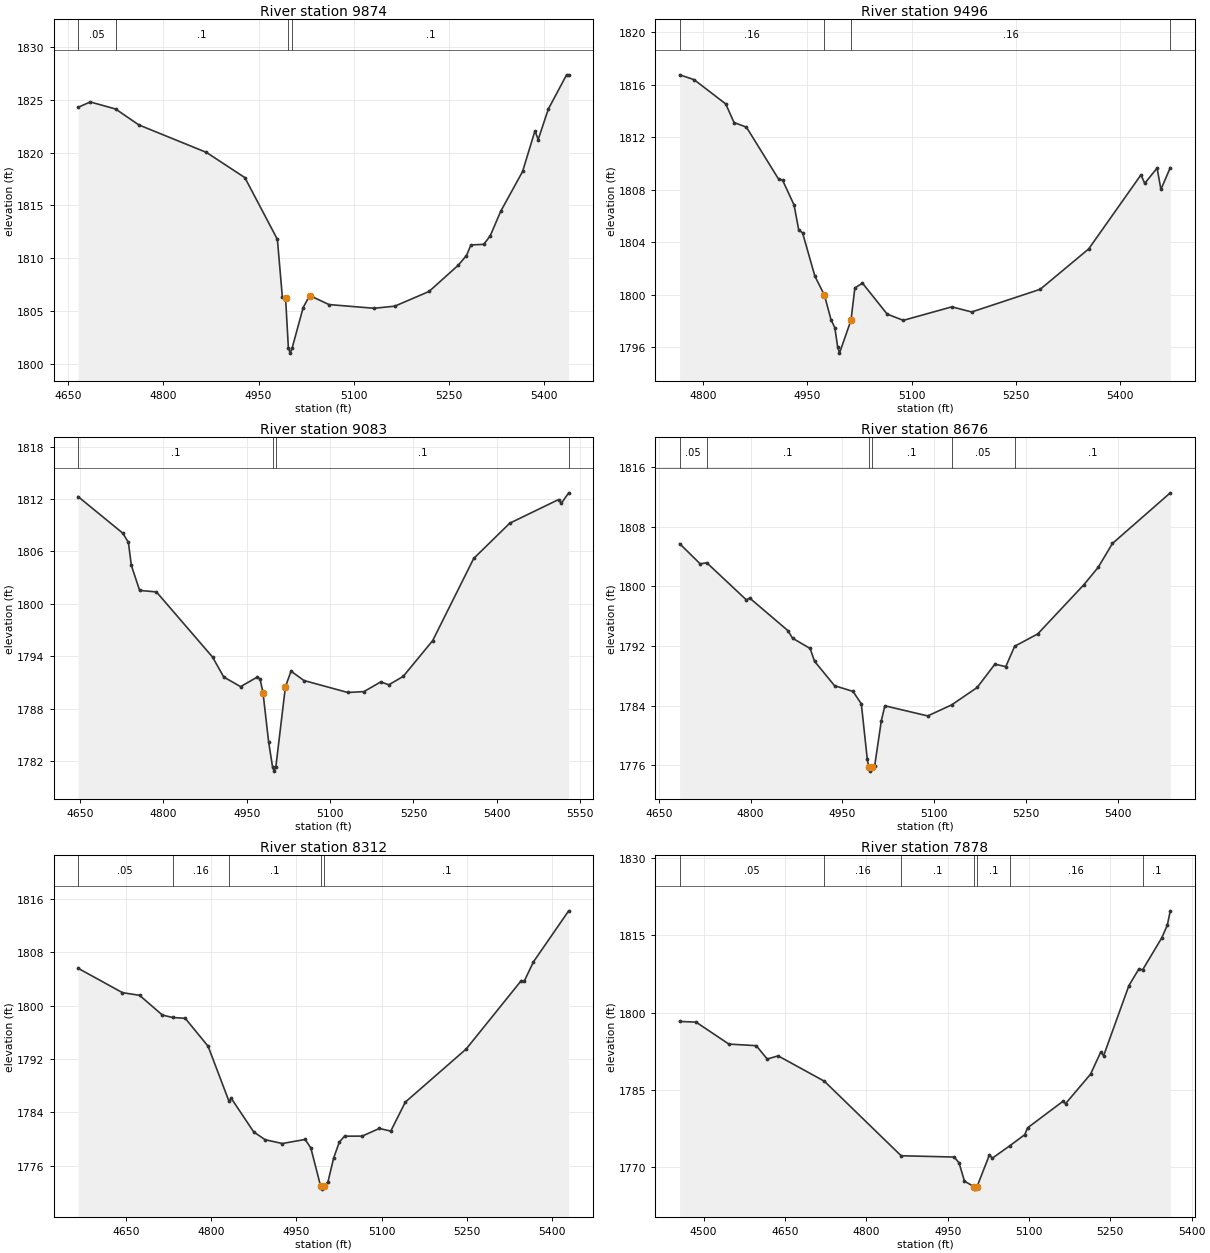
Type RM Length L Ch R = 1 ,9874    ,378,378,378
BEGIN DESCRIPTION:
SCHOOL CREEK 19.0
END DESCRIPTION:
XS GIS Cut Line= 2
      2769186.61     10019542.67      2769322.03     10018782.23
#Sta/Elev= 30
  4665.8 1824.28    4685 1824.79  4724.9 1824.12  4761.6 1822.61  4867.9 1820.01
  4928.4 1817.62  4979.6 1811.77  4987.4 1806.31  4992.5 1806.21  4996.9 1801.49
  4999.7 1800.99  5002.9 1801.49  5020.2 1805.31  5030.4 1806.45  5060.9 1805.59
    5132 1805.24  5164.4 1805.44  5218.3 1806.83    5264  1809.3  5277.3 1810.24
  5284.3 1811.24  5304.6  1811.3  5314.8 1812.12  5331.2 1814.43  5365.6  1818.2
  5385.1 1822.05  5390.2 1821.23  5406.2 1824.12  5434.9 1827.36  5438.2 1827.36
#Mann= 4 ,-1 , 0
  4665.8     .05       0  4724.9      .1       0  4996.9     .07       0
  5002.9      .1       0
Bank Sta=4992.5,5030.4
XS Rating Curve= 0 ,0
Exp/Cntr=0.3,0.1

Type RM Length L Ch R = 1 ,9496    ,413,413,413
BEGIN DESCRIPTION:
SCHOOL CREEK 18.0
END DESCRIPTION:
XS GIS Cut Line= 2
       2769483.5     10019584.31      2769769.91     10018938.58
#Sta/Elev= 30
    4766 1816.76  4786.8 1816.39  4832.3 1814.54  4844.3 1813.12  4862.1 1812.77
  4908.6 1808.79  4914.1 1808.73  4930.7 1806.83  4937.4 1804.93  4942.9 1804.71
  4960.7  1801.4  4974.5 1799.94  4983.9 1798.08  4989.4 1797.47  4993.4 1796.03
  4996.1 1795.53  5012.7 1798.05  5018.2  1800.5  5029.2 1800.87  5064.7 1798.51
    5088 1798.03  5157.8 1799.06  5186.5 1798.67  5285.1  1800.4  5354.9 1803.48
  5430.2 1809.13  5435.6 1808.48  5453.4 1809.65  5458.9 1808.02  5472.4 1809.68
#Mann= 4 ,-1 , 0
    4766     .16       0  4974.5     .07       0  5012.7     .16       0
  5472.4     .05       0
Bank Sta=4974.5,5012.7
XS Rating Curve= 0 ,0
Exp/Cntr=0.3,0.1

Type RM Length L Ch R = 1 ,9083    ,407,407,407
BEGIN DESCRIPTION:
SCHOOL CREEK 17.0
END DESCRIPTION:
XS GIS Cut Line= 2
      2769920.99     10019813.47      2770035.55     10018938.64
#Sta/Elev= 30
  4646.8 1812.28  4727.2 1808.09  4737.3 1807.04  4742.6  1804.4  4757.5 1801.53
  4787.7 1801.36  4888.6  1793.9  4908.8 1791.61    4939 1790.51  4969.1  1791.6
  4974.1 1791.37  4979.4 1789.81  4989.4 1784.22  4996.5 1781.33  4999.3 1780.83
  5002.5 1781.33  5019.7  1790.5  5029.8 1792.28    5053 1791.21  5131.8 1789.84
  5160.9 1789.94  5191.1 1791.05  5205.6 1790.72  5231.5 1791.68  5284.5 1795.78
  5358.3 1805.19  5423.1 1809.23  5510.9 1811.94    5516 1811.52  5529.1 1812.71
#Mann= 4 ,-1 , 0
  4646.8      .1       0  4996.5     .07       0  5002.5      .1       0
  5529.1     .16       0
Bank Sta=4979.4,5019.7
XS Rating Curve= 0 ,0
Exp/Cntr=0.3,0.1

Type RM Length L Ch R = 1 ,8676    ,364,364,364
BEGIN DESCRIPTION:
SCHOOL CREEK 16.0
END DESCRIPTION:
XS GIS Cut Line= 2
      2770228.28     10019865.58      2770551.19     10019131.24
#Sta/Elev= 30
  4684.1 1805.73  4717.6 1803.03  4728.5 1803.17  4793.1  1798.2  4798.6 1798.44
  4860.9 1794.09  4868.6 1793.07  4897.4 1791.68  4904.6 1789.97  4937.4 1786.69
  4967.5 1785.93  4981.1 1784.26  4990.8 1776.88  4993.3 1775.74    4996 1775.24
  4999.3 1775.74  5002.9 1775.93  5013.8 1781.99  5019.6    1784  5089.7 1782.64
    5129 1784.13  5170.6 1786.46  5199.5 1789.58  5217.3 1789.25  5231.8 1791.98
  5269.5 1793.63    5345 1800.23  5368.3 1802.55  5391.7 1805.76  5486.3 1812.55
#Mann= 6 ,-1 , 0
  4684.1     .05       0  4728.5      .1       0  4993.3     .07       0
  4999.3      .1       0    5129     .05       0  5231.8      .1       0
Bank Sta=4993.3,4999.3
XS Rating Curve= 0 ,0
Exp/Cntr=0.3,0.1

Type RM Length L Ch R = 1 ,8312    ,434,434,434
BEGIN DESCRIPTION:
SCHOOL CREEK 15.0
END DESCRIPTION:
XS GIS Cut Line= 2
      2770749.11     10020011.42      2770665.77     10019152.05
#Sta/Elev= 30
  4565.9  1805.6    4644 1801.94  4674.1 1801.54  4714.3 1798.58  4732.1 1798.22
  4754.5 1798.09  4794.7 1793.91  4831.3  1785.7  4835.7 1786.07    4875 1781.06
  4895.1 1779.89  4925.3 1779.32  4965.5 1779.93  4975.5 1778.66  4992.6 1772.98
  4995.3 1772.48  4998.6 1772.98  5005.6 1773.54  5015.7 1777.15  5025.7 1779.54
  5034.8 1780.42  5065.9 1780.43  5096.1 1781.58  5116.2 1781.18  5141.8 1785.53
  5248.9 1793.49  5345.9 1803.75  5350.9 1803.63  5367.3 1806.56  5429.3 1814.21
#Mann= 5 ,-1 , 0
  4565.9     .05       0  4732.1     .16       0  4831.3      .1       0
  4992.6     .07       0  4998.6      .1       0
Bank Sta=4992.6,4998.6
XS Rating Curve= 0 ,0
Exp/Cntr=0.3,0.1

Type RM Length L Ch R = 1 ,7878    ,499,499,499
BEGIN DESCRIPTION:
SCHOOL CREEK 14.0
END DESCRIPTION:
XS GIS Cut Line= 2
       2771051.2     10020063.47      2771181.33     10019168.18
#Sta/Elev= 30
  4455.9 1798.27    4486 1798.15  4546.6 1793.88  4597.1 1793.57  4617.3 1790.98
  4637.5 1791.59  4722.7 1786.67  4864.3  1772.2  4962.1 1771.95    4971 1770.84
  4981.1 1767.26  4998.3 1766.22  5001.1 1765.72  5004.3 1766.22  5027.2  1772.4
  5032.3 1771.72  5064.4 1774.12  5092.3  1776.3  5097.3 1777.61  5162.4 1782.75
  5167.5 1782.32  5213.5 1788.03  5232.5 1792.36  5237.6  1791.6  5284.3 1805.24
  5302.7 1808.47  5309.5 1808.28  5344.9 1814.51    5355 1816.93  5360.6 1819.75
#Mann= 7 ,-1 , 0
  4455.9     .05       0  4722.7     .16       0  4864.3      .1       0
  4998.3     .07       0  5004.3      .1       0  5064.4     .16       0
  5309.5      .1       0
Bank Sta=4998.3,5004.3
XS Rating Curve= 0 ,0
Exp/Cntr=0.3,0.1

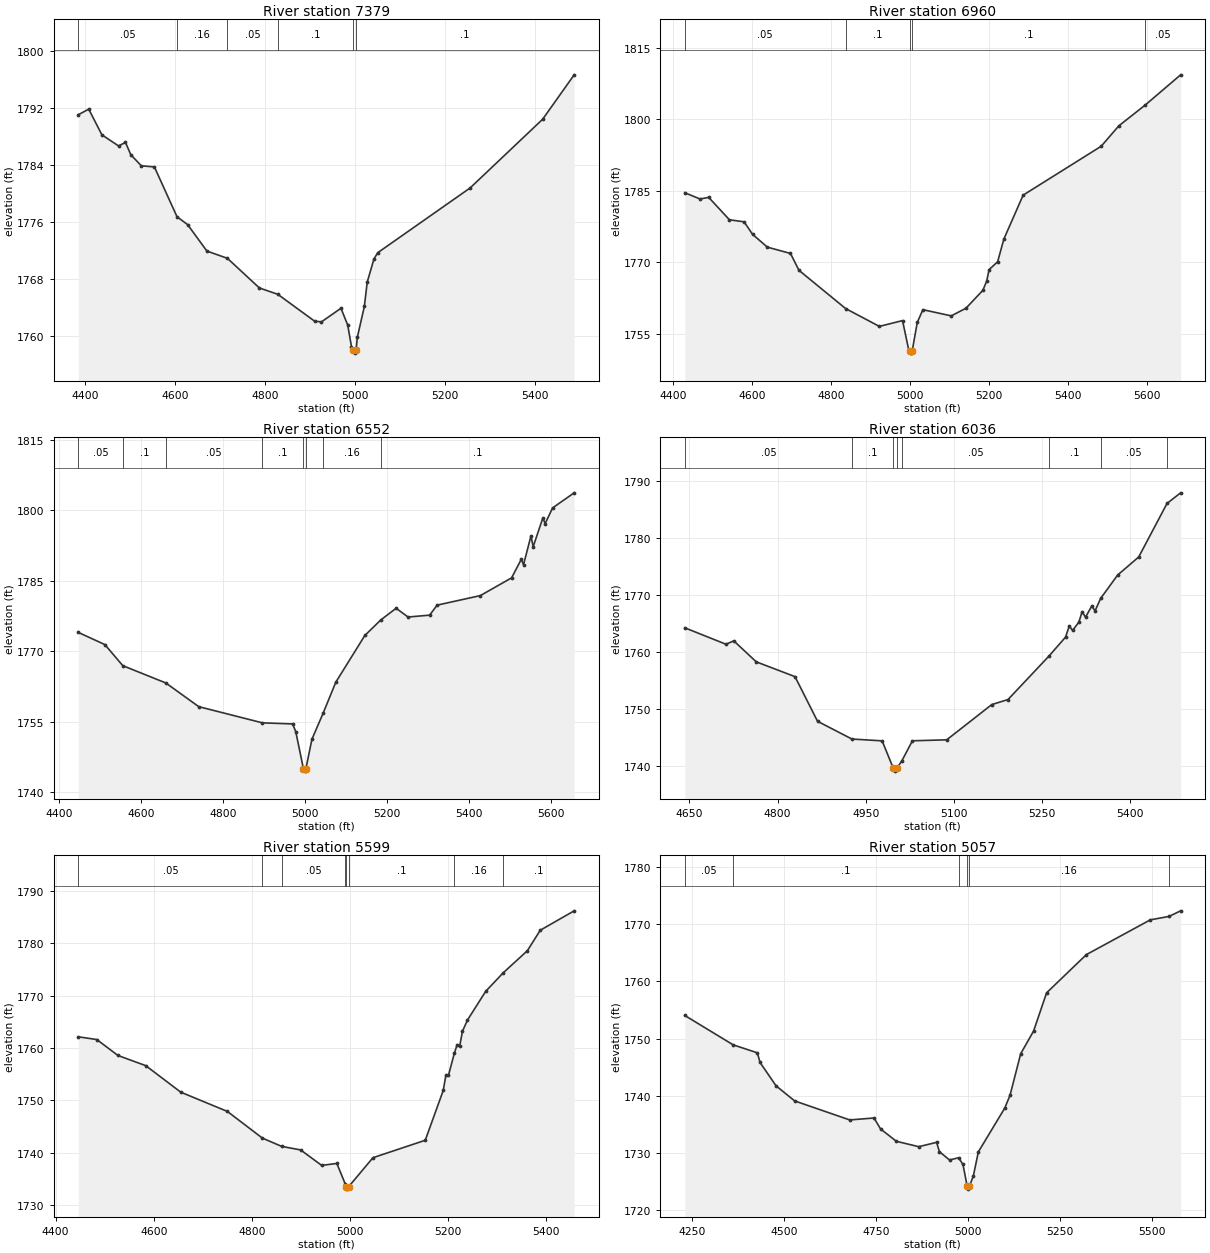
Type RM Length L Ch R = 1 ,7379    ,419,419,419
BEGIN DESCRIPTION:
SCHOOL CREEK 13.0
END DESCRIPTION:
XS GIS Cut Line= 3
      2771306.41     10020063.49      2771738.69     10019344.77
      2771707.44     10019084.34
#Sta/Elev= 30
  4385.3 1791.06  4408.4 1791.84  4437.7 1788.23  4474.6 1786.68    4490 1787.17
  4501.8 1785.45  4525.1 1783.89  4554.2 1783.73  4604.4 1776.74    4628 1775.63
  4670.8 1771.92  4716.3  1770.9  4787.3 1766.74  4828.2 1765.85  4910.1 1762.07
  4925.2 1761.98  4968.5 1763.89  4983.5 1761.52  4991.8 1758.52  4996.1 1758.09
  4998.8 1757.59  5002.1 1758.09  5004.9 1759.83  5020.4 1764.14  5026.8 1767.56
  5041.8 1770.82  5050.2 1771.69  5255.3 1780.78  5416.4 1790.43  5486.3 1796.66
#Mann= 6 ,-1 , 0
  4385.3     .05       0  4604.4     .16       0  4716.3     .05       0
  4828.2      .1       0  4996.1     .07       0  5002.1      .1       0
Bank Sta=4996.1,5002.1
XS Rating Curve= 0 ,0
Exp/Cntr=0.3,0.1

Type RM Length L Ch R = 1 ,6960    ,408,408,408
BEGIN DESCRIPTION:
SCHOOL CREEK 12.0
END DESCRIPTION:
XS GIS Cut Line= 2
      2771686.61     10020256.21      2772316.52      10019168.2
#Sta/Elev= 30
  4429.1 1784.56  4467.6 1783.24  4489.7 1783.58  4542.2 1778.88  4579.4 1778.45
    4601 1775.82  4638.3 1773.14  4697.1 1771.81  4718.6 1768.27  4836.8 1760.25
  4922.4  1756.5  4981.2 1757.72    4997 1751.53  4999.8 1751.39  5002.5 1750.89
  5005.8 1751.39  5018.5 1757.32  5032.8 1760.01  5104.7 1758.71    5142 1760.31
    5185 1764.09  5194.6 1766.03  5200.8 1768.43  5222.3 1770.06  5238.1 1774.83
    5287 1784.05  5484.9 1794.31  5529.7  1798.6  5596.7 1802.97  5686.3  1809.3
#Mann= 5 ,-1 , 0
  4429.1     .05       0  4836.8      .1       0  4999.8     .07       0
  5005.8      .1       0  5596.7     .05       0
Bank Sta=4999.8,5005.8
XS Rating Curve= 0 ,0
Exp/Cntr=0.3,0.1

Type RM Length L Ch R = 1 ,6552    ,516,516,516
BEGIN DESCRIPTION:
SCHOOL CREEK 11.0
END DESCRIPTION:
XS GIS Cut Line= 2
      2772139.72     10020402.09       2772613.3      10019288.4
#Sta/Elev= 30
  4447.1 1774.02  4511.9 1771.43  4555.6 1766.94  4660.6 1763.26    4741 1758.21
  4896.5 1754.76  4970.1 1754.53  4977.8 1752.89  4996.5 1744.98  4999.3 1744.48
  5002.5 1744.98  5017.3 1751.28  5044.7 1756.84  5075.6 1763.43  5146.4 1773.37
  5185.5 1776.69  5222.8 1779.17  5251.9  1777.3  5304.6  1777.7  5322.8 1779.83
  5428.2 1781.86  5504.6 1785.64  5528.3  1789.6  5533.7 1788.43  5551.9 1794.58
  5557.3 1792.28    5581 1798.43  5586.4 1797.18  5604.6 1800.53  5657.3 1803.75
#Mann= 8 ,-1 , 0
  4447.1     .05       0  4555.6      .1       0  4660.6     .05       0
  4896.5      .1       0  4996.5     .07       0  5002.5      .1       0
  5044.7     .16       0  5185.5      .1       0
Bank Sta=4996.5,5002.5
XS Rating Curve= 0 ,0
Exp/Cntr=0.3,0.1

Type RM Length L Ch R = 1 ,6036    ,437,437,437
BEGIN DESCRIPTION:
SCHOOL CREEK 10.0
END DESCRIPTION:
XS GIS Cut Line= 2
      2772676.17     10020365.64      2773072.03      10019620.8
#Sta/Elev= 30
  4642.2 1764.25  4712.3 1761.37  4725.5 1761.97  4763.8 1758.29  4829.7  1755.7
    4868 1747.89  4926.4 1744.78  4977.9 1744.46  4996.9 1739.66  4999.6 1739.16
  5002.9 1739.66  5011.5 1740.97  5029.4 1744.47  5087.8 1744.64  5164.4 1750.81
    5192 1751.69  5261.8 1759.31  5289.9 1762.62  5296.3 1764.56  5301.9  1763.8
  5312.5 1765.23  5318.2 1767.08  5323.9  1766.1  5334.5 1768.06  5340.2 1767.23
  5349.6 1769.39  5378.5 1773.48  5414.4 1776.65  5462.6 1786.03  5485.7 1787.88
#Mann= 8 ,-1 , 0
  4642.2     .05       0  4926.4      .1       0  4996.9     .07       0
  5002.9      .1       0  5011.5     .05       0  5261.8      .1       0
  5349.6     .05       0  5462.6      .1       0
Bank Sta=4996.9,5002.9
XS Rating Curve= 0 ,0
Exp/Cntr=0.3,0.1

Type RM Length L Ch R = 1 ,5599    ,542,542,542
BEGIN DESCRIPTION:
SCHOOL CREEK 9.0
END DESCRIPTION:
XS GIS Cut Line= 4
      2772837.62     10020485.41      2773223.07     10020214.56
       2773368.9     10019974.97      2773415.77     10019719.81
#Sta/Elev= 30
  4446.2 1762.12  4483.9  1761.6    4527 1758.56  4583.7 1756.62  4655.1 1751.56
  4750.1 1747.89  4821.5  1742.8  4861.1 1741.21  4899.4 1740.55  4942.4  1737.6
  4973.3 1737.97  4990.4 1734.06  4991.7 1733.57  4994.4 1733.07  4997.7 1733.57
  5046.9 1739.06  5153.6 1742.39  5190.3  1751.9  5195.6 1754.76  5200.9 1754.76
  5212.9 1758.99  5218.7 1760.64  5223.7 1760.31  5229.5 1763.19  5239.7 1765.32
  5276.8 1770.79  5312.1 1774.29  5361.7 1778.53  5388.1 1782.45  5457.2 1786.15
#Mann= 8 ,-1 , 0
  4446.2     .05       0  4821.5      .1       0  4861.1     .05       0
  4990.4      .1       0  4991.7     .07       0  4997.7      .1       0
  5212.9     .16       0  5312.1      .1       0
Bank Sta=4991.7,4997.7
XS Rating Curve= 0 ,0
Exp/Cntr=0.3,0.1

Type RM Length L Ch R = 1 ,5057    ,350,350,350
BEGIN DESCRIPTION:
SCHOOL CREEK 8.0
END DESCRIPTION:
XS GIS Cut Line= 4
      2773004.28     10020542.69      2773691.82      10020428.1
      2773947.02     10020219.77      2773978.27     10019902.07
#Sta/Elev= 30
  4230.9 1754.04  4362.2 1748.91  4427.8 1747.52  4435.1 1745.84  4478.5 1741.76
  4529.1 1739.12  4678.5  1735.8  4744.4 1736.14  4762.3 1734.22  4805.2 1732.07
    4866 1731.13  4914.4 1731.89  4921.8 1730.27  4949.4 1728.81  4974.1  1729.2
  4985.9 1728.02  4997.3 1724.22    5000 1723.72  5003.3 1724.22    5014 1726.01
  5027.6 1730.22  5099.4 1737.88  5113.7 1740.13  5142.5 1747.35  5177.6 1751.33
  5212.8 1757.99  5320.9 1764.67  5494.5 1770.74  5545.2 1771.33  5576.6 1772.31
#Mann= 6 ,-1 , 0
  4230.9     .05       0  4362.2      .1       0  4974.1     .16       0
  4997.3     .07       0  5003.3     .16       0  5545.2      .1       0
Bank Sta=4997.3,5003.3
XS Rating Curve= 0 ,0
Exp/Cntr=0.3,0.1

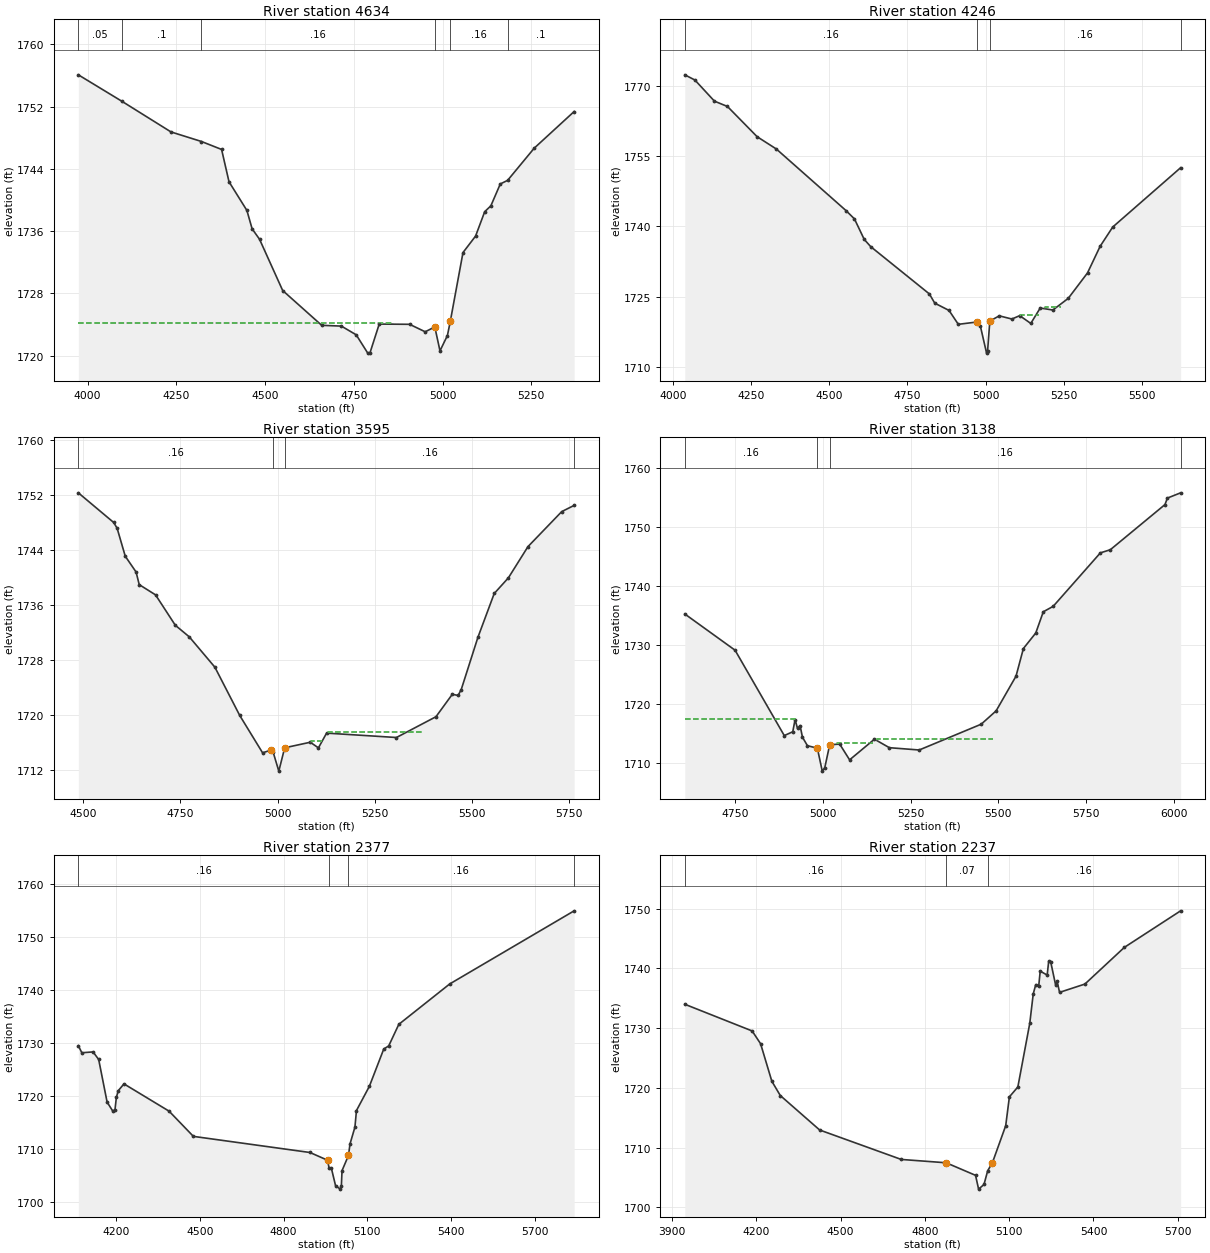
Type RM Length L Ch R = 1 ,4634    ,388,388,388
XS GIS Cut Line= 4
       2773458.7     10021496.68       2773856.9     10020938.14
      2774129.32     10020568.72      2774207.43     10020329.19
#Sta/Elev= 30
  3973.7 1756.07  4095.5  1752.7  4234.7 1748.74  4320.7 1747.51  4377.3 1746.49
  4398.2 1742.34  4448.6 1738.66  4463.3  1736.3  4484.2 1734.96  4549.4 1728.38
  4659.3 1723.91  4714.8 1723.81  4756.6 1722.69  4789.1 1720.34  4795.1 1720.34
  4821.4 1724.07    4907 1724.04  4950.9 1723.08    4978  1723.7  4992.6 1720.63
  5013.5  1722.6  5021.9 1724.48  5057.4 1733.25  5092.9 1735.37  5118.6  1738.5
  5135.9 1739.25  5162.5 1742.06  5183.1 1742.52  5258.2 1746.66  5370.6 1751.36
#Mann= 6 ,-1 , 0
  3973.7     .05       0  4095.5      .1       0  4320.7     .16       0
    4978     .07       0  5021.9     .16       0  5183.1      .1       0
#XS Ineff= 2 , 0
       0 4859.67 1724.15               0
Permanent Ineff=
       T       T
Bank Sta=4978,5021.9
XS Rating Curve= 0 ,0
Exp/Cntr=0.3,0.1

Type RM Length L Ch R = 1 ,4246    ,651,651,651
BEGIN DESCRIPTION:
SCHOOL CREEK 6.0
END DESCRIPTION:
XS GIS Cut Line= 3
      2774566.82     10021844.79      2774332.44     10021037.47
      2774238.75     10020298.34
#Sta/Elev= 30
  4038.2 1772.35  4070.5 1771.24    4133 1766.73  4174.7 1765.59  4269.5 1759.14
  4330.9 1756.52  4553.6 1743.38  4580.8 1741.59    4612 1737.22  4632.8 1735.67
  4820.3 1725.58  4837.6 1723.61  4883.3 1722.05  4912.9 1719.09  4973.3 1719.59
  4983.4 1718.74  5003.3 1712.94  5006.6 1713.44  5013.7 1719.78  5043.9  1720.9
  5084.2 1720.22  5109.3 1720.94  5144.7 1719.28  5174.9 1722.57  5215.3 1722.14
  5264.5 1724.63  5326.1 1730.06  5366.5 1735.75  5406.8 1739.86  5623.9 1752.52
#Mann= 4 ,-1 , 0
  4038.2     .16       0  4973.3     .07       0  5013.7     .16       0
  5623.9      .1       0
#XS Ineff= 2 ,-1
 5109.88 5169.63 1721.02 5190.54 5242.82 1722.76
Permanent Ineff=
       T       T
Bank Sta=4973.3,5013.7
XS Rating Curve= 0 ,0
Exp/Cntr=0.3,0.1

Type RM Length L Ch R = 1 ,3595    ,457,457,457
BEGIN DESCRIPTION:
SCHOOL CREEK 5.0
END DESCRIPTION:
XS GIS Cut Line= 2
      2775092.88     10021256.26      2774374.11     10020204.15
#Sta/Elev= 30
    4488 1752.37  4578.8 1748.05  4587.6 1747.22  4608.6 1743.13  4636.4 1740.83
  4644.5 1738.99  4686.4  1737.5  4737.2 1733.07  4773.1 1731.38  4838.9 1726.96
  4902.8 1719.92  4961.5 1714.48  4982.4 1714.86  4988.5  1714.6  5003.2 1711.81
  5018.3 1715.21  5084.1 1716.02    5105  1715.2    5126 1717.35  5305.5 1716.71
  5407.1 1719.74  5449.1 1723.01    5464 1722.84    5472  1723.7  5514.8  1731.3
  5556.8  1737.7  5593.2 1739.98  5643.5 1744.53  5730.2 1749.63  5762.2 1750.54
#Mann= 4 ,-1 , 0
    4488     .16       0  4988.5     .07       0  5018.3     .16       0
  5762.2     .16       0
#XS Ineff= 2 ,-1
 5086.64 5119.17 1716.14 5128.46 5371.29 1717.49
Permanent Ineff=
       T       T
Bank Sta=4982.4,5018.3
XS Rating Curve= 0 ,0
Exp/Cntr=0.3,0.1

Type RM Length L Ch R = 1 ,3138    ,761,761,761
BEGIN DESCRIPTION:
SCHOOL CREEK 4.0
END DESCRIPTION:
XS GIS Cut Line= 3
      2775207.44     10020896.82      2775191.82     10020589.56
      2774436.63     10019782.29
#Sta/Elev= 30
  4606.7 1735.27    4750 1729.13  4890.2 1714.67  4914.4 1715.32    4921 1717.38
  4927.9 1715.89  4935.2 1716.36  4942.1 1714.39  4956.2 1712.96  4984.5 1712.53
  4998.5 1708.65  5005.6 1709.23  5019.7 1713.12  5048.1 1713.23  5076.4 1710.56
  5147.2 1714.06  5189.7 1712.62  5274.7 1712.23  5451.5  1716.6    5494 1718.86
  5550.7 1724.74  5571.7 1729.42    5607 1732.05  5628.4 1735.64  5656.7 1736.57
  5791.1 1745.62  5819.4 1746.15  5975.2  1753.8  5982.1  1754.9  6019.8 1755.79
#Mann= 4 ,-1 , 0
  4606.7     .16       0  4984.5     .07       0  5019.7     .16       0
  6019.8     .16       0
#XS Ineff= 3 ,-1
  4606.7 4920.94 1717.47 5040.83 5143.07 1713.36 5155.02 5485.64 1714.17
Permanent Ineff=
       T       T       T
Bank Sta=4984.5,5019.7
XS Rating Curve= 0 ,0
Exp/Cntr=0.3,0.1

Type RM Length L Ch R = 1 ,2377    ,140,140,140
BEGIN DESCRIPTION:
Mapping XS efd87830
END DESCRIPTION:
XS GIS Cut Line= 4
       2775249.1     10020756.26      2775322.02     10020079.14
      2775072.02     10019527.06      2775077.23     10019038.07
#Sta/Elev= 30
  4064.7 1729.55  4077.3 1728.22  4117.5 1728.38  4137.6 1726.95  4167.8 1718.91
  4187.9 1717.23  4195.9 1717.41  4200.9  1719.8  4208.1 1721.09  4228.2 1722.35
  4389.9  1717.2  4476.8 1712.45  4894.4 1709.41  4957.6 1707.95  4963.1 1706.41
  4971.2 1706.43  4986.2 1703.13  5003.5  1702.5  5006.8    1703  5009.3 1705.99
  5032.4 1708.85  5037.9 1711.03  5055.5 1714.19    5061 1717.32  5107.2 1721.89
  5158.8 1728.93  5176.5 1729.51  5212.7 1733.58  5395.1  1741.2  5840.8 1754.99
#Mann= 4 ,-1 , 0
  4064.7     .16       0  4963.1     .07       0  5032.4     .16       0
  5840.8      .1       0
Bank Sta=4957.6,5032.4
XS Rating Curve= 0 ,0
Exp/Cntr=0.3,0.1

Type RM Length L Ch R = 1 ,2237    ,172,172,172
BEGIN DESCRIPTION:
Mapping XS 72cc43a9
END DESCRIPTION:
XS GIS Cut Line= 4
      2775374.11     10020803.13      2775415.77     10019995.81
      2775233.48     10019516.64      2775202.23     10019073.91
#Sta/Elev= 30
  3945.3 1734.01    4185 1729.54  4215.1  1727.4  4255.1 1721.12  4285.2 1718.73
  4425.3 1712.96  4715.7 1708.03  4875.8 1707.47  4980.2 1705.37  4991.1 1703.06
  5010.3 1703.84  5023.4 1706.13  5040.4  1707.5  5087.6 1713.68  5100.7 1718.51
  5130.8 1720.16  5173.2 1730.81  5185.6 1735.75  5194.6  1737.3  5205.1 1737.06
  5210.4 1739.56  5235.2 1738.89  5240.5 1741.18  5248.1 1741.03  5265.2 1737.24
  5270.5 1737.89  5279.3    1736  5369.5 1737.39  5509.9 1743.53  5710.2 1749.65
#Mann= 3 ,-1 , 0
  3945.3     .16       0  4875.8     .07       0  5023.4     .16       0
Bank Sta=4875.8,5040.4
XS Rating Curve= 0 ,0
Exp/Cntr=0.3,0.1

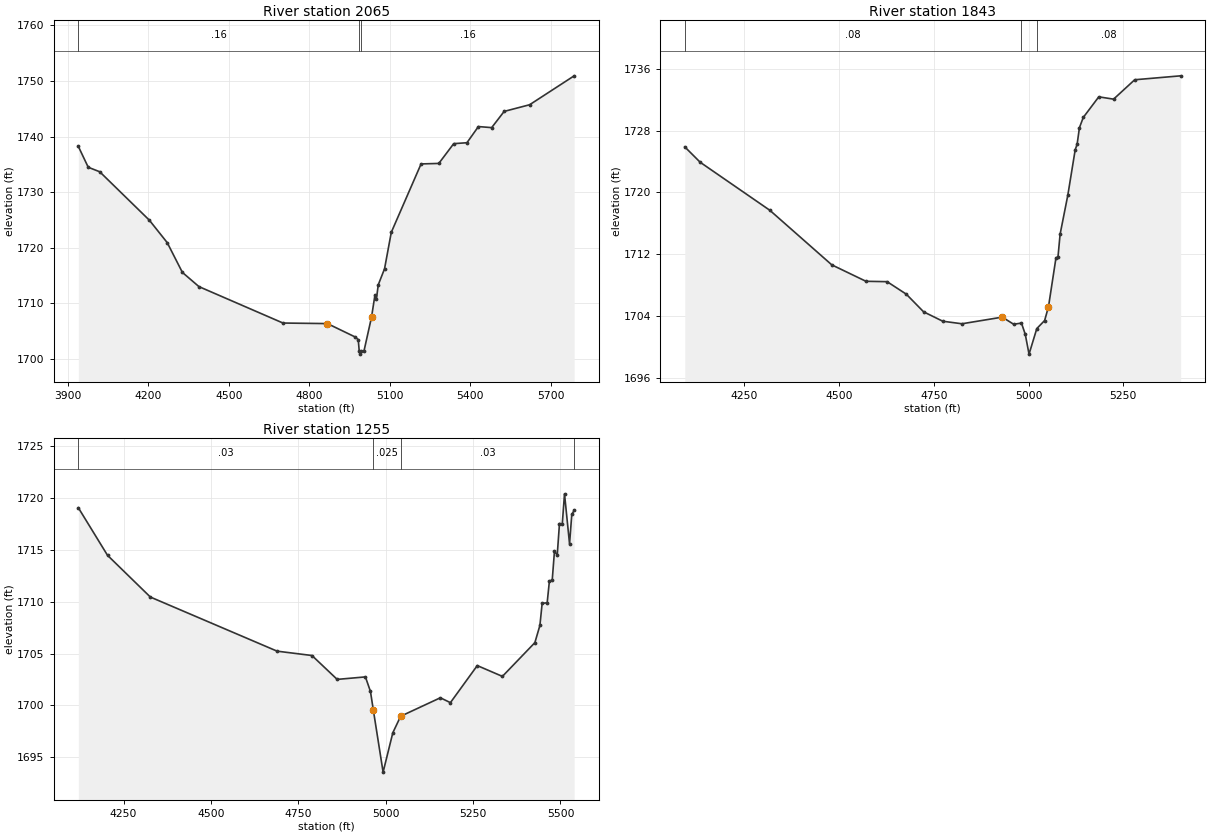
Type RM Length L Ch R = 1 ,2065    ,222,222,222
BEGIN DESCRIPTION:
SCHOOL CREEK 3.0
END DESCRIPTION:
XS GIS Cut Line= 3
      2775665.77     10020730.16      2775509.52     10019766.64
      2775207.45     10018948.96
#Sta/Elev= 30
  3938.8 1738.22  3975.7 1734.46  4018.5 1733.65  4203.4 1724.93  4270.1 1720.88
  4326.6 1715.52  4388.3 1712.96  4701.5  1706.4  4867.2  1706.3  4971.3 1703.87
    4982  1703.4  4985.7  1701.3  4988.5  1700.8  4991.7  1701.3  5003.3 1701.35
  5031.5 1707.47  5044.2 1711.44  5049.5 1710.69  5056.6 1713.29    5080 1716.18
  5105.1 1722.74  5216.1 1735.06  5282.2 1735.15  5337.7 1738.71  5387.1 1738.88
  5429.7 1741.79  5479.2  1741.6  5525.7 1744.52  5620.6 1745.72  5786.6 1750.93
#Mann= 3 ,-1 , 0
  3938.8     .16       0  4985.7     .07       0  4991.7     .16       0
Bank Sta=4867.2,5031.5
XS Rating Curve= 0 ,0
Exp/Cntr=0.3,0.1

Type RM Length L Ch R = 1 ,1843    ,588,588,588
BEGIN DESCRIPTION:
SCHOOL CREEK 2.0
END DESCRIPTION:
XS GIS Cut Line= 2
      2775879.31      10020563.5      2775618.91      10019282.3
#Sta/Elev= 30
  4093.7 1725.88  4134.3 1723.89    4318 1717.67  4481.2 1710.61  4571.4 1708.48
  4627.2 1708.43  4677.8 1706.81  4723.3 1704.53  4773.9 1703.31  4824.5 1702.98
  4930.8 1703.84  4960.8 1702.92  4981.5 1703.07  4991.5  1701.6  5001.4 1699.05
  5021.9 1702.36  5042.5  1703.4  5052.7 1705.19  5072.5 1711.54  5077.6 1711.56
  5083.3 1714.57  5103.7 1719.64  5123.1  1725.5  5128.2 1726.22  5134.3 1728.37
  5144.5  1729.7  5185.3 1732.36  5224.3 1732.06    5280 1734.57  5401.1 1735.08
#Mann= 3 ,-1 , 0
  4093.7     .08       0  4981.5     .05       0  5021.9     .08       0
Bank Sta=4930.8,5052.7
XS Rating Curve= 0 ,0
Exp/Cntr=0.3,0.1

Type RM Length L Ch R = 1 ,1255    ,0,0,0
BEGIN DESCRIPTION:
SCHOOL CREEK 1.0
END DESCRIPTION:
XS GIS Cut Line= 3
      2776103.26     10020511.47      2776295.98     10019756.22
      2775895.95     10019257.48
#Sta/Elev= 30
  4120.4 1719.04  4203.9 1714.46  4326.5 1710.44  4689.1 1705.23  4788.9 1704.81
  4861.1 1702.51  4941.9 1702.75  4956.3 1701.35  4964.3 1699.61  4992.5 1693.58
  5020.3 1697.37  5042.7 1698.96  5156.3 1700.74  5185.1 1700.27    5262 1703.84
  5333.9  1702.8  5426.8 1706.05  5441.2 1707.71  5447.6 1709.83    5462 1709.89
  5468.4    1712  5476.4 1712.05  5482.8 1714.83  5490.8  1714.5  5497.2 1717.52
  5505.2 1717.47  5511.6 1720.38    5526 1715.56  5532.4 1718.39  5539.2 1718.79
#Mann= 4 ,-1 , 0
  4120.4     .03       0  4964.3    .025       0  5042.7     .03       0
  5539.2      .1       0
Bank Sta=4964.3,5042.7
XS Rating Curve= 0 ,0
Exp/Cntr=0.3,0.1

Chan Stop Cuts=-1
Use User Specified Reach Order=0
Composite Channel Slope=5