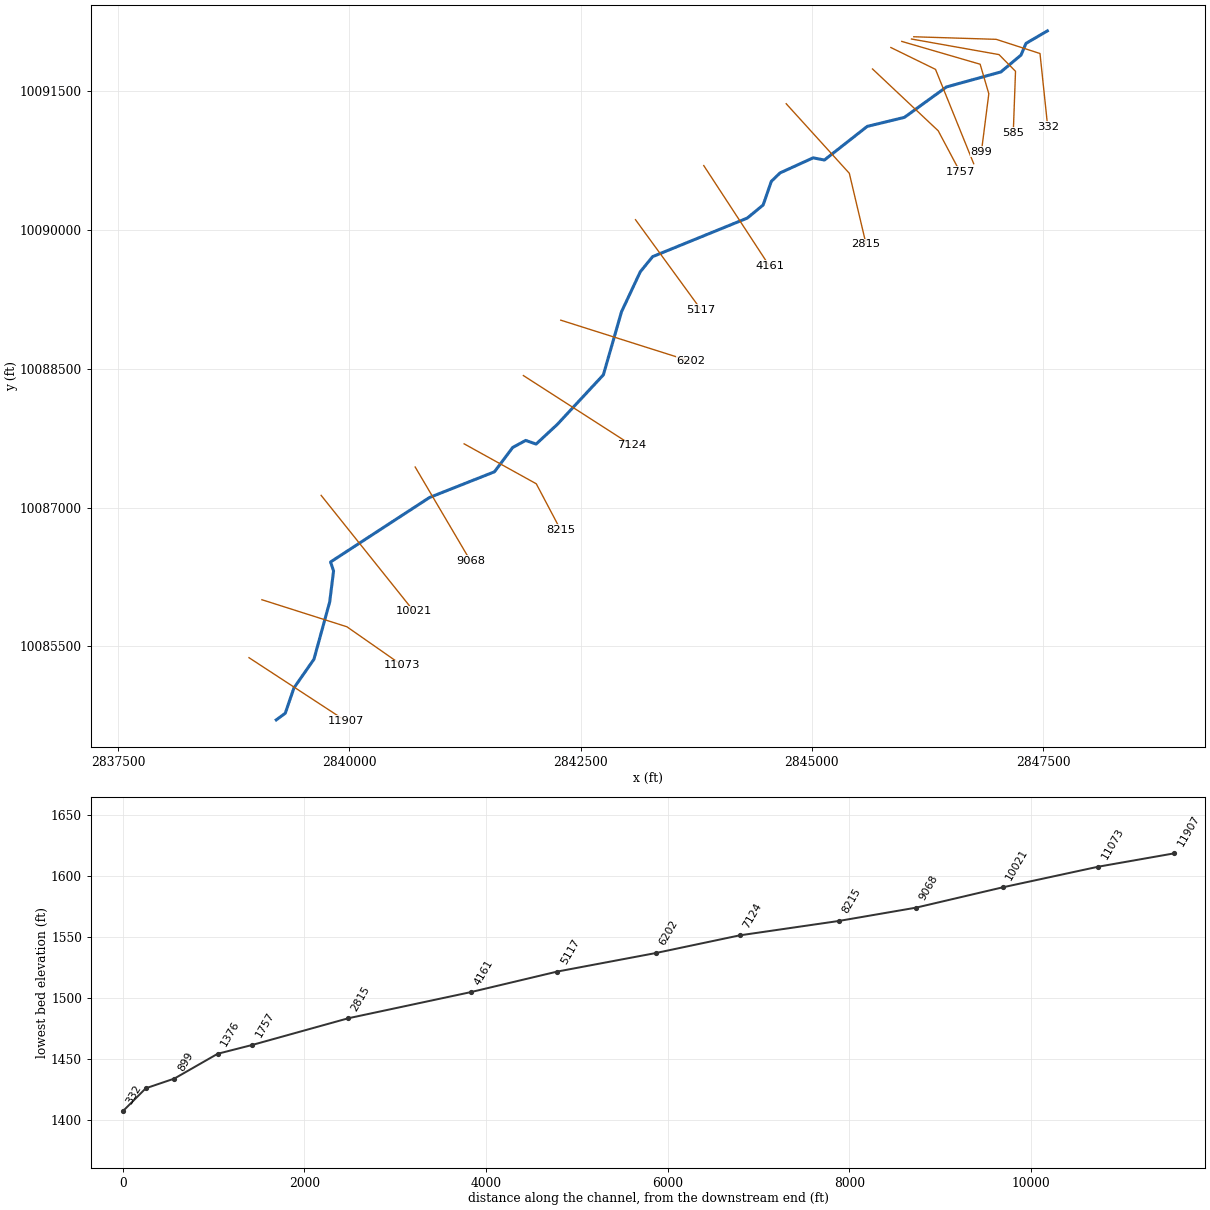
--- SMITH SPRING BRANCH.prj (project) ---

Proj Title=SMITH SPRING BRANCH Base Level Engineering
Current Plan=p01
Default Exp/Contr=0.3,0.1
English Units
Geom File=g01
Flow File=f01
Plan File=p01
Y Axis Title=Elevation
X Axis Title(PF)=Main Channel Distance
X Axis Title(XS)=Station
BEGIN DESCRIPTION:
SMITH SPRING BRANCH
END DESCRIPTION:
DSS Export Rating Curves= 0
DSS Export Rating Curve Sorted= 0
DSS Export Volume Flow Curves= 0
DXF OffsetX= 0
DXF OffsetY= 0
DXF ScaleX= 1
DXF ScaleY= 10

--- SMITH SPRING BRANCH.p01 (plan) ---

Plan Title=Multiple Run
Short Identifier=Multiple
Geom File=g01
Flow File=f01
Subcritical Flow
K Sum by GR= 0
Std Step Tol= 0.01
Critical Tol= 0.01
Num of Std Step Trials= 20
Max Error Tol= 0.3
Flow Tol Ratio= 0.001
Split Flow NTrial= 30
Split Flow Tol= 0.02
Split Flow Ratio= 0.02
Log Output Level= 0
Friction Slope Method= 1
Unsteady Friction Slope Method= 2
Unsteady Bridges Friction Slope Method= 1
Parabolic Critical Depth
Global Vel Dist=  1 , 1 , 1
Global Log Level= 0
CheckData=True
Encroach Param= -1, 0, 0, 0
BEGIN DESCRIPTION:
Multiple Run
END DESCRIPTION:

--- SMITH SPRING BRANCH.f01 (steady flow) ---

Flow Title=Multiple
Program Version=4.10
Number of Profiles= 7
Profile Names=10-year,25-year,50-year,1pct_min,100-year,1pct_plu,500-year
River Rch & RM=SMITH SPRING BRA,Reach-1         ,11907
    1465    2184    2824    2670    3611    4884    5928
River Rch & RM=SMITH SPRING BRA,Reach-1         ,5117
    1629    2440    3164    2999    4056    5486    6694
River Rch & RM=SMITH SPRING BRA,Reach-1         ,899
    2072    3145    4118    3937    5324    7200    8942
Boundary for River Rch & Prof#=SMITH SPRING BRA,Reach-1         , 1
Up Type= 0
Dn Type= 3
Dn Slope=0.046
Boundary for River Rch & Prof#=SMITH SPRING BRA,Reach-1         , 2
Up Type= 0
Dn Type= 3
Dn Slope=0.046
Boundary for River Rch & Prof#=SMITH SPRING BRA,Reach-1         , 3
Up Type= 0
Dn Type= 3
Dn Slope=0.046
Boundary for River Rch & Prof#=SMITH SPRING BRA,Reach-1         , 4
Up Type= 0
Dn Type= 3
Dn Slope=0.046
Boundary for River Rch & Prof#=SMITH SPRING BRA,Reach-1         , 5
Up Type= 0
Dn Type= 3
Dn Slope=0.046
Boundary for River Rch & Prof#=SMITH SPRING BRA,Reach-1         , 6
Up Type= 0
Dn Type= 3
Dn Slope=0.046
Boundary for River Rch & Prof#=SMITH SPRING BRA,Reach-1         , 7
Up Type= 0
Dn Type= 3
Dn Slope=0.046
DSS Import GetInterval= 0
DSS Import GetPeak= 0
DSS Import FillOption= 0

--- SMITH SPRING BRANCH.g01 (geometry) ---

Geom Title=Existing Conditions
Program Version=4.10

River Reach=SMITH SPRING BRA,Reach-1
Reach XY= 30
      2839208.47     10084703.73      2839305.95     10084774.79
      2839399.53      10085048.5      2839616.24     10085359.65
      2839786.54     10085979.49      2839828.34      10086313.8
      2839795.79     10086410.98      2840865.97     10087108.55
       2841567.6     10087386.06      2841765.02     10087648.97
      2841905.84     10087725.58      2842018.64     10087686.15
      2842246.84     10087897.75      2842745.94     10088434.78
      2842941.72       10089116.      2843145.35     10089549.83
       2843278.7     10089713.17      2844302.02     10090129.98
      2844473.53      10090271.2       2844562.1     10090526.98
      2844656.05     10090618.15      2845014.22      10090781.3
      2845136.13      10090757.8      2845599.41     10091121.46
      2846001.12     10091218.81      2846456.01      10091548.1
       2847044.6     10091710.39      2847262.47     10091892.89
      2847315.68     10092018.85      2847547.15     10092154.12

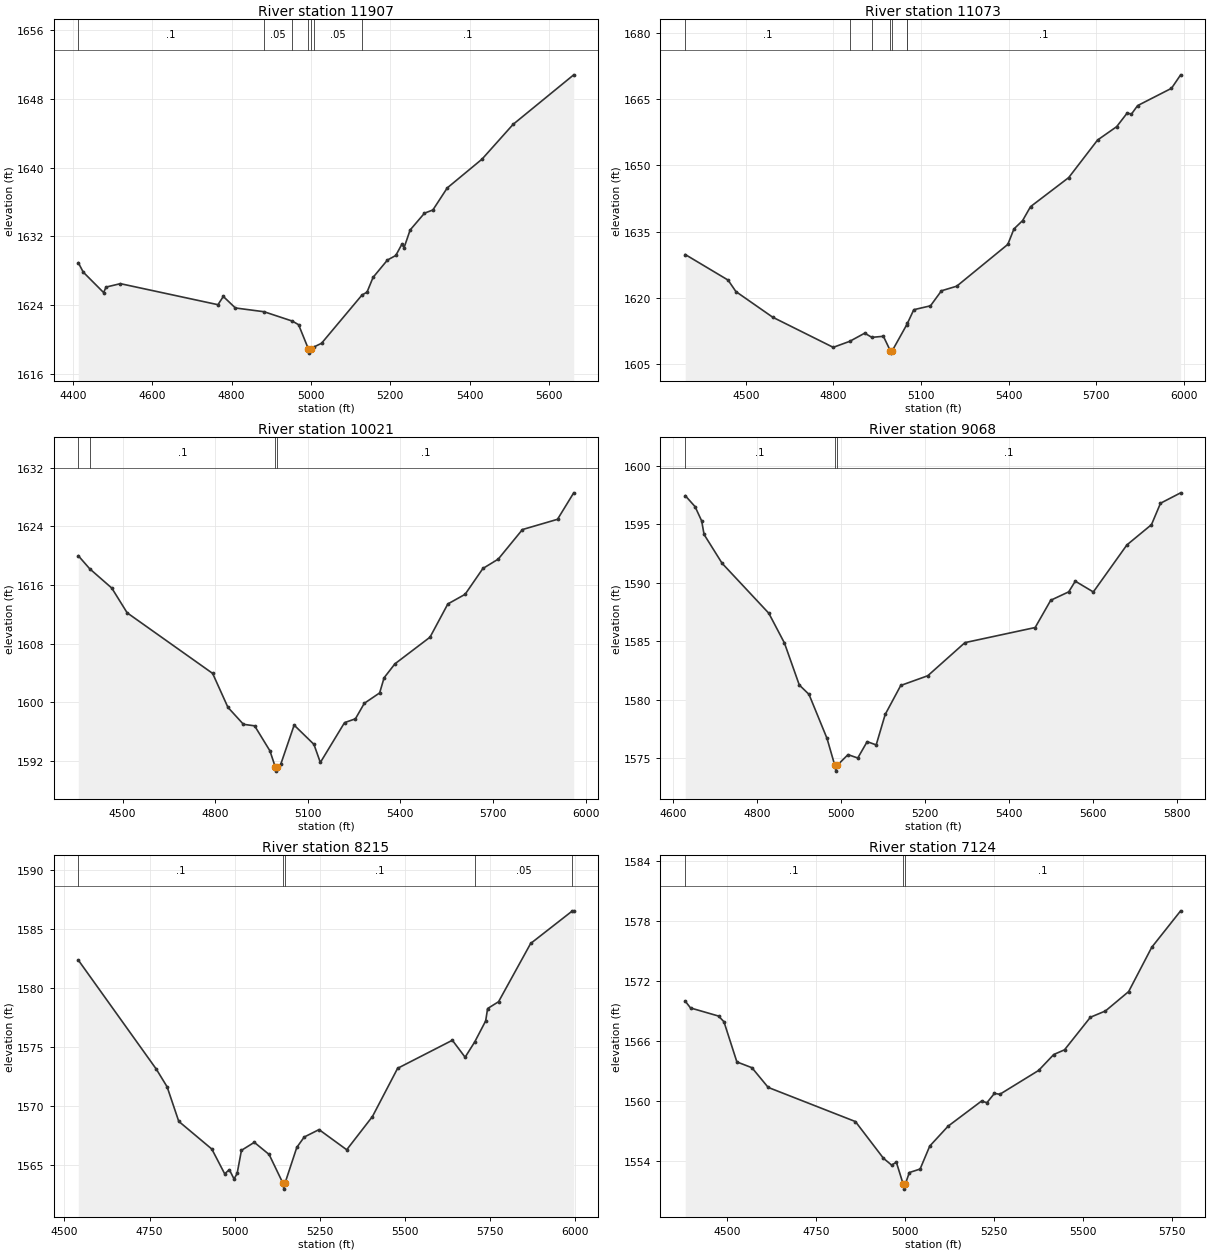
Type RM Length L Ch R = 1 ,11907   ,834,834,834
BEGIN DESCRIPTION:
SMITH SPRING BRANCH 27.0
END DESCRIPTION:
XS GIS Cut Line= 2
      2838913.91     10085376.13       2839958.7     10084693.54
#Sta/Elev= 30
    4414 1628.93  4426.5 1627.83  4477.8 1625.45  4483.8 1626.09    4520 1626.49
  4765.8 1624.04  4779.3    1625  4809.6 1623.66    4882 1623.22  4953.2 1622.13
  4968.9 1621.71  4993.5  1618.9  4996.3  1618.4  4999.5  1618.9  5007.4 1619.11
  5026.8 1619.55  5128.7 1625.17  5141.3  1625.5  5156.5 1627.22  5192.7 1629.24
  5213.7 1629.77  5228.9 1631.06  5234.8  1630.7  5249.9 1632.74  5286.1  1634.7
  5307.2 1635.07  5343.4 1637.64    5431 1640.99  5509.3 1645.04    5662 1650.81
#Mann= 7 ,-1 , 0
    4414      .1       0    4882     .05       0  4953.2      .1       0
  4993.5     .07       0  4999.5      .1       0  5007.4     .05       0
  5128.7      .1       0
Bank Sta=4993.5,4999.5
XS Rating Curve= 0 ,0
Exp/Cntr=0.3,0.1

Type RM Length L Ch R = 1 ,11073   ,1052,1052,1052
BEGIN DESCRIPTION:
SMITH SPRING BRANCH 25.0
END DESCRIPTION:
XS GIS Cut Line= 3
      2839053.21     10086003.02      2839972.63     10085710.48
      2840571.62     10085292.57
#Sta/Elev= 30
    4293  1629.8  4439.6 1624.01  4466.4 1621.41  4592.3 1615.61  4799.4 1608.79
  4855.8 1610.15  4907.2    1612  4931.4 1611.05  4971.1 1611.29    4995 1607.98
  4997.8 1607.48    5001 1607.98  5050.3 1613.83  5053.1  1614.2  5075.1 1617.31
  5132.2 1618.19  5169.7 1621.59    5222 1622.63  5396.8 1632.09  5417.8 1635.59
  5447.4 1637.48  5474.5 1640.63  5605.3 1647.22  5703.9 1655.71  5769.3 1658.74
  5805.1 1661.81  5819.9 1661.59  5840.9  1663.5  5956.9 1667.42  5988.2 1670.47
#Mann= 7 ,-1 , 0
    4293      .1       0  4855.8     .05       0  4931.4      .1       0
    4995     .07       0    5001      .1       0  5050.3     .05       0
  5053.1      .1       0
Bank Sta=4995,5001
XS Rating Curve= 0 ,0
Exp/Cntr=0.3,0.1

Type RM Length L Ch R = 1 ,10021   ,953,953,953
BEGIN DESCRIPTION:
SMITH SPRING BRANCH 23.0
END DESCRIPTION:
XS GIS Cut Line= 2
        2839694.     10087131.41      2840696.58      10085878.2
#Sta/Elev= 30
  4356.5    1620  4393.4 1618.22    4465 1615.58  4514.7  1612.2  4791.6 1603.92
  4841.2 1599.28  4891.4 1596.96  4927.7 1596.75  4977.3 1593.33  4995.1 1591.06
  4997.9 1590.56  5001.1 1591.06  5012.5 1591.52  5055.7 1596.85  5119.8 1594.22
  5140.6 1591.74    5219 1597.19  5254.2 1597.71    5283 1599.83  5332.7 1601.25
  5347.1 1603.32  5382.3 1605.23  5495.9 1608.87  5553.6 1613.41  5609.6 1614.73
  5667.2 1618.26  5716.9 1619.54  5795.3 1623.58  5908.9 1624.98  5961.4  1628.6
#Mann= 4 ,-1 , 0
  4356.5     .05       0  4393.4      .1       0  4995.1     .07       0
  5001.1      .1       0
Bank Sta=4995.1,5001.1
XS Rating Curve= 0 ,0
Exp/Cntr=0.3,0.1

Type RM Length L Ch R = 1 ,9068    ,853,853,853
BEGIN DESCRIPTION:
SMITH SPRING BRANCH 18.0
END DESCRIPTION:
XS GIS Cut Line= 2
      2840710.95     10087437.87      2841309.95     10086420.98
#Sta/Elev= 30
  4628.4 1597.45  4651.8 1596.51  4667.5 1595.29  4673.3 1594.13  4716.2 1591.67
  4827.5  1587.4  4864.7 1584.86  4900.1 1581.27  4923.2 1580.47  4966.1 1576.71
  4984.6 1574.41  4987.3 1573.91  4990.6 1574.41  5016.2 1575.32  5039.4 1575.03
  5061.8 1576.43  5083.3 1576.15  5104.7 1578.75  5141.8 1581.23  5206.2 1582.06
  5294.7 1584.89    5462 1586.18  5499.1 1588.51    5542 1589.23  5557.6 1590.14
  5600.6 1589.22  5680.6 1593.24  5739.1 1594.97  5760.6  1596.8  5808.6 1597.69
#Mann= 3 ,-1 , 0
  4628.4      .1       0  4984.6     .07       0  4990.6      .1       0
Bank Sta=4984.6,4990.6
XS Rating Curve= 0 ,0
Exp/Cntr=0.3,0.1

Type RM Length L Ch R = 1 ,8215    ,1091,1091,1091
BEGIN DESCRIPTION:
SMITH SPRING BRANCH 17.0
END DESCRIPTION:
XS GIS Cut Line= 3
      2841240.33     10087688.62      2842020.43     10087256.78
      2842283.38     10086758.56
#Sta/Elev= 30
  4540.6 1582.39  4770.1 1573.12  4801.4 1571.64  4835.6 1568.71  4932.7 1566.36
  4970.5 1564.26  4984.2 1564.61    4998 1563.82  5007.1 1564.29  5019.7 1566.25
  5057.5 1566.93    5101  1565.9  5141.6 1563.46  5144.3 1562.96  5147.6 1563.46
  5182.3  1566.5  5204.1 1567.38  5247.6 1568.01  5328.9  1566.3  5404.5 1569.12
  5478.4 1573.21  5639.2 1575.59  5676.6 1574.15  5705.1 1575.46    5737 1577.23
  5742.7 1578.28  5774.9 1578.86  5869.1  1583.8  5991.1 1586.55  5995.6 1586.57
#Mann= 5 ,-1 , 0
  4540.6      .1       0  5141.6     .07       0  5147.6      .1       0
  5705.1     .05       0  5991.1      .1       0
Bank Sta=5141.6,5147.6
XS Rating Curve= 0 ,0
Exp/Cntr=0.3,0.1

Type RM Length L Ch R = 1 ,7124    ,922,922,922
BEGIN DESCRIPTION:
SMITH SPRING BRANCH 16.0
END DESCRIPTION:
XS GIS Cut Line= 2
      2841881.13     10088426.95      2843051.29      10087674.7
#Sta/Elev= 30
  4383.1 1569.97    4398 1569.29  4476.6 1568.48  4491.8 1567.91  4528.1 1563.89
  4570.4 1563.31    4616 1561.34    4861 1557.92  4939.6 1554.25  4962.5 1553.57
  4975.9 1553.85  4995.1 1551.66  4997.9 1551.16  5001.1 1551.66  5012.3 1552.82
  5042.6 1553.17  5069.7 1555.47  5121.2 1557.46    5215 1559.97  5230.2 1559.81
  5251.3 1560.74  5266.5 1560.65  5375.5 1563.04  5417.8 1564.63  5448.1  1565.1
  5520.8 1568.36  5563.1 1568.99  5628.2 1570.93  5693.2 1575.37  5774.2 1579.01
#Mann= 3 ,-1 , 0
  4383.1      .1       0  4995.1     .07       0  5001.1      .1       0
Bank Sta=4995.1,5001.1
XS Rating Curve= 0 ,0
Exp/Cntr=0.3,0.1

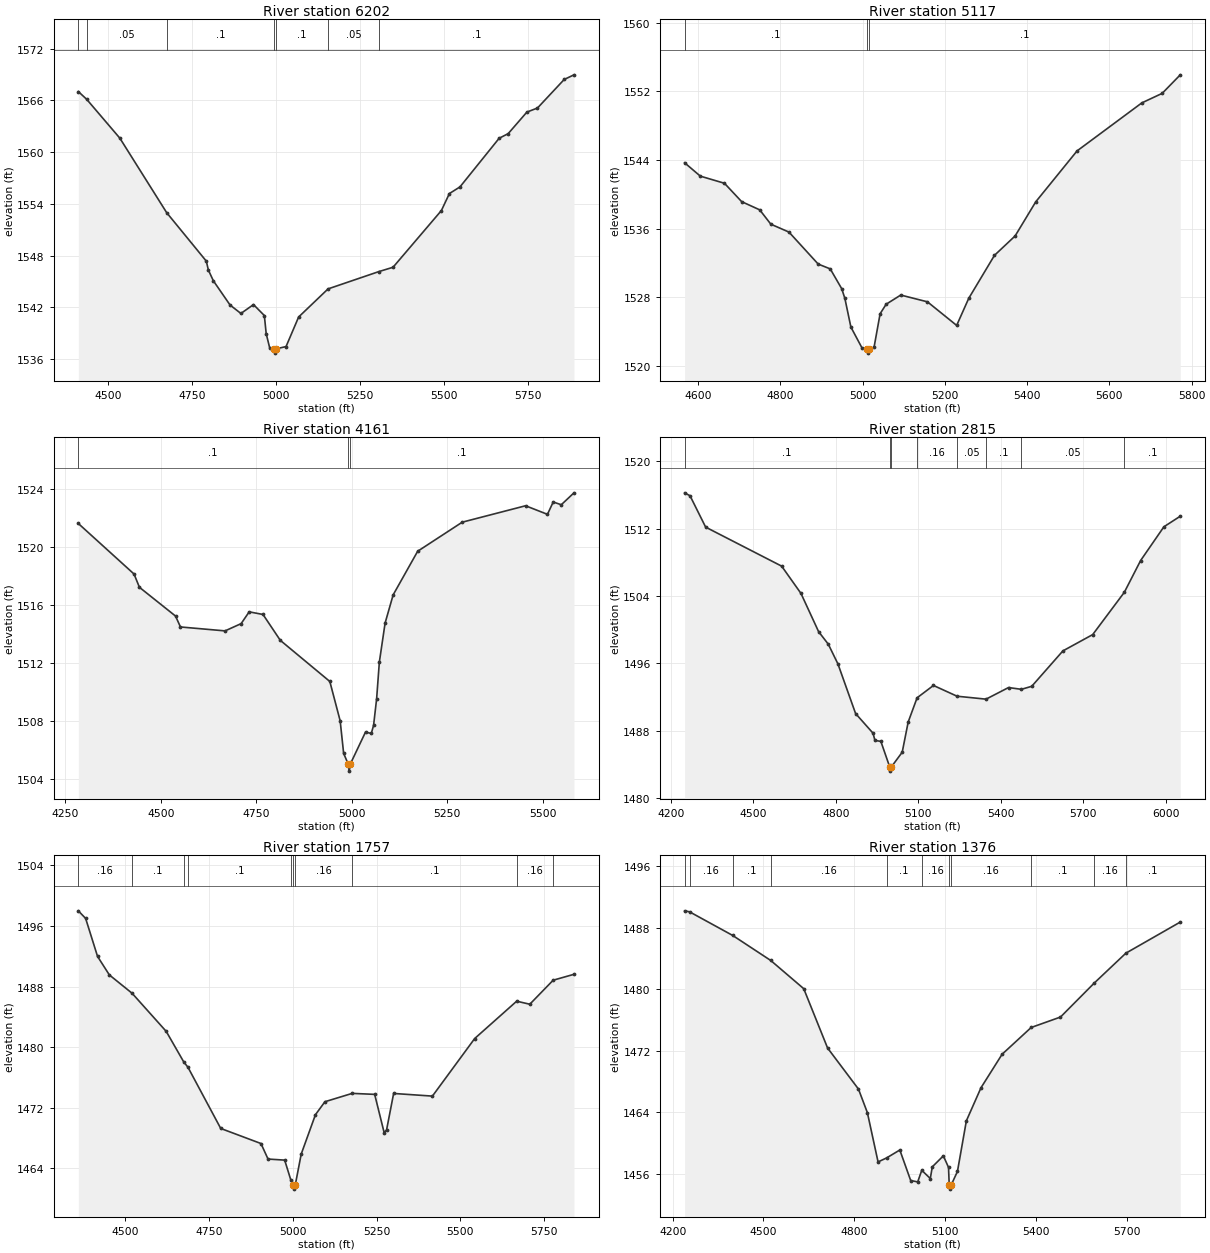
Type RM Length L Ch R = 1 ,6202    ,1085,1085,1085
BEGIN DESCRIPTION:
SMITH SPRING BRANCH 15.0
END DESCRIPTION:
XS GIS Cut Line= 2
      2842285.15     10089025.96      2843692.12     10088580.19
#Sta/Elev= 30
  4412.2 1567.02  4436.9 1566.13  4535.9 1561.61  4675.3 1552.97  4793.3 1547.35
  4799.4 1546.32  4814.3 1545.07    4864 1542.26  4896.3 1541.28  4933.8 1542.31
  4966.1 1541.04  4971.6 1538.94  4982.1 1537.27  4995.4 1537.18  4998.2 1536.68
  5001.4 1537.18  5030.7 1537.44  5068.2 1540.87  5155.8 1544.13  5306.5 1546.13
  5349.3 1546.64  5493.3 1553.22  5517.1 1555.19  5548.6 1555.96  5665.2  1561.6
  5692.2 1562.14  5747.9 1564.64  5779.4 1565.11  5858.9 1568.42  5888.1 1568.96
#Mann= 7 ,-1 , 0
  4412.2      .1       0  4436.9     .05       0  4675.3      .1       0
  4995.4     .07       0  5001.4      .1       0  5155.8     .05       0
  5306.5      .1       0
Bank Sta=4995.4,5001.4
XS Rating Curve= 0 ,0
Exp/Cntr=0.3,0.1

Type RM Length L Ch R = 1 ,5117    ,956,956,956
BEGIN DESCRIPTION:
SMITH SPRING BRANCH 10.0
END DESCRIPTION:
XS GIS Cut Line= 2
      2843093.09     10090112.56      2843803.02     10089138.15
#Sta/Elev= 30
  4566.8 1543.67    4605 1542.11  4663.7 1541.28  4705.5 1539.14  4749.5 1538.18
  4776.5 1536.51  4820.6 1535.59  4891.7 1531.86    4921  1531.3  4948.9 1528.99
  4956.6 1527.86  4971.2 1524.52  4998.4 1522.07    5010 1521.98  5012.7 1521.48
    5016 1521.98  5027.6 1522.17  5042.3 1526.07    5057 1527.18  5092.5 1528.25
  5157.4 1527.46  5228.5 1524.71  5257.9 1527.87  5320.5 1532.88  5370.7 1535.14
  5420.9 1539.12  5521.3 1545.05  5678.9 1550.65  5728.4 1551.76  5772.4 1553.92
#Mann= 3 ,-1 , 0
  4566.8      .1       0    5010     .07       0    5016      .1       0
Bank Sta=5010,5016
XS Rating Curve= 0 ,0
Exp/Cntr=0.3,0.1

Type RM Length L Ch R = 1 ,4161    ,1346,1346,1346
BEGIN DESCRIPTION:
SMITH SPRING BRANCH 9.0
END DESCRIPTION:
XS GIS Cut Line= 2
      2843831.42     10090697.65      2844541.86     10089611.09
#Sta/Elev= 30
  4283.6  1521.6  4429.6 1518.12  4443.6 1517.21  4538.2 1515.23  4551.1 1514.48
  4667.9 1514.21    4710 1514.71  4731.1 1515.52  4767.3 1515.34  4812.6 1513.56
  4942.3 1510.73  4969.4 1508.02  4978.5 1505.78  4990.2 1505.06  4992.9 1504.56
  4996.2 1505.06  5035.8 1507.25  5050.9 1507.15  5056.9 1507.71  5064.9 1509.54
    5072 1512.06  5087.1 1514.75  5108.2 1516.69  5172.4 1519.69  5289.1 1521.69
    5455 1522.82  5512.3 1522.23  5527.4 1523.08  5548.5 1522.89  5581.8 1523.71
#Mann= 3 ,-1 , 0
  4283.6      .1       0  4990.2     .07       0  4996.2      .1       0
Bank Sta=4990.2,4996.2
XS Rating Curve= 0 ,0
Exp/Cntr=0.3,0.1

Type RM Length L Ch R = 1 ,2815    ,1058,1058,1058
BEGIN DESCRIPTION:
SMITH SPRING BRANCH 5.0
END DESCRIPTION:
XS GIS Cut Line= 3
      2844722.97     10091366.33      2845405.58     10090614.06
      2845586.59     10089848.27
#Sta/Elev= 30
  4249.7 1516.27  4269.4 1515.92  4326.2 1512.19  4602.6 1507.55  4672.8 1504.31
    4737 1499.76  4772.2 1498.27  4807.3 1495.92  4871.5 1490.02    4935 1487.68
  4941.9 1486.82  4963.4 1486.71  4995.6 1483.67  4998.3 1483.17  5001.6 1483.67
  5041.1 1485.42  5062.8 1489.01  5095.2 1491.89  5154.7 1493.36  5240.5 1492.08
  5345.9 1491.73  5427.7 1493.11  5474.6  1492.9  5512.2 1493.26  5625.5 1497.47
  5733.9 1499.41  5848.9 1504.44  5908.2 1508.22  5992.8 1512.23  6052.4 1513.49
#Mann= 8 ,-1 , 0
  4249.7      .1       0  4995.6     .07       0  5001.6      .1       0
  5095.2     .16       0  5240.5     .05       0  5345.9      .1       0
  5474.6     .05       0  5848.9      .1       0
Bank Sta=4995.6,5001.6
XS Rating Curve= 0 ,0
Exp/Cntr=0.3,0.1

Type RM Length L Ch R = 1 ,1757    ,381,381,381
BEGIN DESCRIPTION:
SMITH SPRING BRANCH 4.0
END DESCRIPTION:
XS GIS Cut Line= 3
      2845656.33     10091742.45       2846366.8     10091073.78
      2846603.37     10090628.46
#Sta/Elev= 30
  4359.4 1498.01  4381.2 1497.01  4416.8 1491.99    4452 1489.55  4519.9 1487.13
  4621.9 1482.09  4674.3 1478.05  4686.6 1477.37  4784.6 1469.28  4904.7 1467.29
  4925.8 1465.24  4975.5  1465.1  4994.1 1462.44  5000.9 1461.77  5003.6 1461.27
  5006.9 1461.77  5024.9  1465.9  5067.4  1471.1  5095.7 1472.81  5177.2 1473.91
  5244.2 1473.78  5272.5 1468.73  5279.8  1469.1  5300.8  1473.9  5416.6 1473.55
  5542.8 1481.15  5668.2 1486.08  5707.4 1485.68  5777.1 1488.85  5839.3 1489.63
#Mann= 10 ,-1 , 0
  4359.4     .16       0  4519.9      .1       0  4674.3     .16       0
  4686.6      .1       0  4994.1     .16       0  5000.9     .07       0
  5006.9     .16       0  5177.2      .1       0  5668.2     .16       0
  5777.1      .1       0
Bank Sta=5000.9,5006.9
XS Rating Curve= 0 ,0
Exp/Cntr=0.3,0.1

Type RM Length L Ch R = 1 ,1376    ,477,477,477
BEGIN DESCRIPTION:
Mapping XS de7d1d3e
END DESCRIPTION:
XS GIS Cut Line= 3
      2845854.89     10091974.25      2846337.55     10091738.13
      2846750.44     10090718.05
#Sta/Elev= 30
  4239.5 1490.23  4255.9  1490.1  4398.2 1487.03  4524.1 1483.77  4633.1  1480.1
  4711.9 1472.38  4813.9 1467.04  4843.4 1463.97  4878.7 1457.56  4906.9 1458.08
  4950.6 1459.11  4986.5 1455.14  5009.7 1454.96  5023.1 1456.47  5051.3  1455.4
  5057.9 1456.92  5094.4 1458.35  5111.5 1456.85  5113.9 1454.52  5116.7 1454.02
  5119.9 1454.52    5141 1456.32  5170.5 1462.91  5218.8 1467.21  5288.6 1471.57
  5384.6 1475.05  5481.5 1476.41  5593.2 1480.84  5697.5 1484.72  5877.3 1488.77
#Mann= 11 ,-1 , 0
  4239.5      .1       0  4255.9     .16       0  4398.2      .1       0
  4524.1     .16       0  4906.9      .1       0  5023.1     .16       0
  5113.9     .07       0  5119.9     .16       0  5384.6      .1       0
  5593.2     .16       0  5697.5      .1       0
Bank Sta=5113.9,5119.9
XS Rating Curve= 0 ,0
Exp/Cntr=0.3,0.1

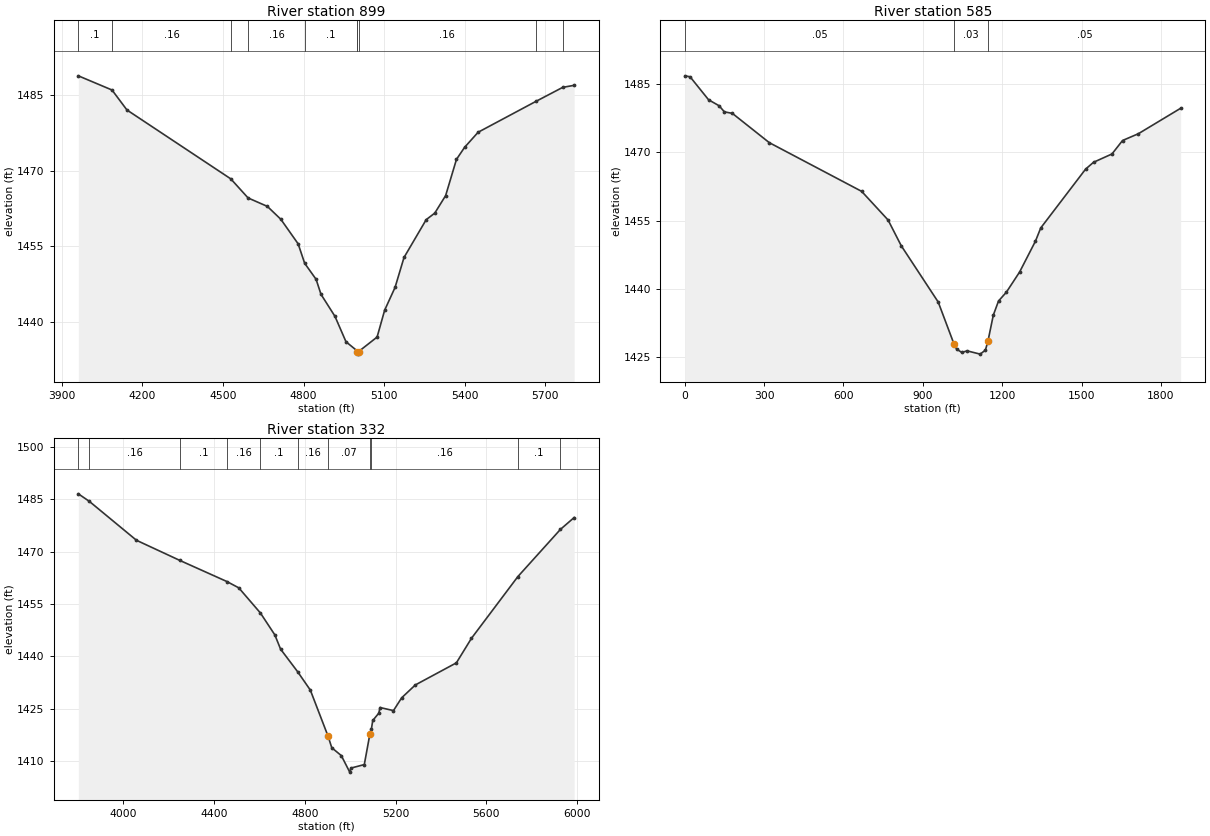
Type RM Length L Ch R = 1 ,899     ,314,314,314
BEGIN DESCRIPTION:
Mapping XS 6cda8b3c
END DESCRIPTION:
XS GIS Cut Line= 4
      2845973.01      10092040.2      2846820.19     10091793.68
      2846913.94     10091474.24      2846834.08     10090849.25
#Sta/Elev= 30
  3961.9 1488.77  4087.3 1485.96  4142.8 1482.01  4529.3 1468.37  4593.7 1464.59
  4665.4 1462.92  4715.5 1460.37  4779.9 1455.51  4804.3 1451.65  4846.8 1448.48
    4865 1445.51  4917.1 1441.14    4958 1436.12  4998.1 1434.38  4998.8 1434.17
  5001.5 1433.67  5004.8 1434.17  5073.8 1437.05    5102 1442.38  5140.6 1446.87
    5174 1452.81  5256.5 1460.29  5288.5 1461.59  5328.9 1465.06  5369.2 1472.23
  5399.4 1474.61  5449.8  1477.6  5664.2 1483.69  5764.7 1486.49  5807.2 1486.89
#Mann= 10 ,-1 , 0
  3961.9      .1       0  4087.3     .16       0  4529.3      .1       0
  4593.7     .16       0  4804.3      .1       0  4998.1     .16       0
  4998.8     .07       0  5004.8     .16       0  5664.2      .1       0
  5764.7     .16       0
Bank Sta=4998.8,5004.8
XS Rating Curve= 0 ,0
Exp/Cntr=0.3,0.1

Type RM Length L Ch R = 1 ,585     ,253,253,253
XS GIS Cut Line= 4
     2846077.678    10092066.321      2847023.89    10091897.918
     2847202.678    10091717.363     2847178.373    10091050.696
#Sta/Elev= 30
       0 1486.79   19.96 1486.58   89.83 1481.54  129.75 1480.22  149.71 1478.88
  179.65 1478.56  319.39 1472.13  668.71 1461.44  768.52 1455.16  818.43  1449.5
  958.09 1437.16 1017.59 1427.98  1027.5 1426.85 1047.34 1426.09 1067.17 1426.45
 1116.75 1425.73 1136.58 1426.61 1146.49 1428.66 1166.33 1434.26 1186.16 1437.39
 1215.97 1439.33 1265.87 1443.75 1325.74 1450.51  1345.7 1453.41 1515.35 1466.32
 1545.29 1467.82 1615.15 1469.65 1655.07  1472.6 1714.94 1474.09 1874.62 1479.67
#Mann= 3 , 0 , 0
       0     .05       0 1017.59     .03       0 1146.49     .05       0
Bank Sta=1017.59,1146.49
XS Rating Curve= 0 ,0
Exp/Cntr=0.3,0.1

Type RM Length L Ch R = 1 ,332     ,0,0,0
BEGIN DESCRIPTION:
SMITH SPRING BRANCH 1.0
END DESCRIPTION:
XS GIS Cut Line= 4
      2846102.15     10092090.71      2846993.67     10092062.85
      2847467.32     10091909.61      2847550.73     10091117.17
#Sta/Elev= 30
  3801.1 1486.51  3849.9 1484.34  4057.5 1473.22  4249.4 1467.44  4456.3 1461.42
  4508.8 1459.61    4604 1452.43  4667.8 1446.15    4693 1442.09  4767.8 1435.66
  4824.2 1430.37  4902.2 1417.21  4918.8 1413.88  4960.9 1411.62    4998  1406.9
  5003.5 1408.06  5062.2 1409.06    5087 1417.84  5093.6 1419.26  5099.5 1421.67
  5126.3 1423.78  5131.5 1425.38  5190.9  1424.5    5227 1428.16  5287.3 1431.84
  5468.3 1438.16  5534.9 1445.19  5739.4 1462.83  5927.2 1476.34  5987.7 1479.73
#Mann= 11 ,-1 , 0
  3801.1      .1       0  3849.9     .16       0  4249.4      .1       0
  4456.3     .16       0    4604      .1       0  4767.8     .16       0
  4902.2     .07       0    5087     .16       0  5093.6     .16       0
  5739.4      .1       0  5927.2     .16       0
Bank Sta=4902.2,5087
XS Rating Curve= 0 ,0
Exp/Cntr=0.3,0.1

Chan Stop Cuts=-1
Use User Specified Reach Order=0
Composite Channel Slope=5