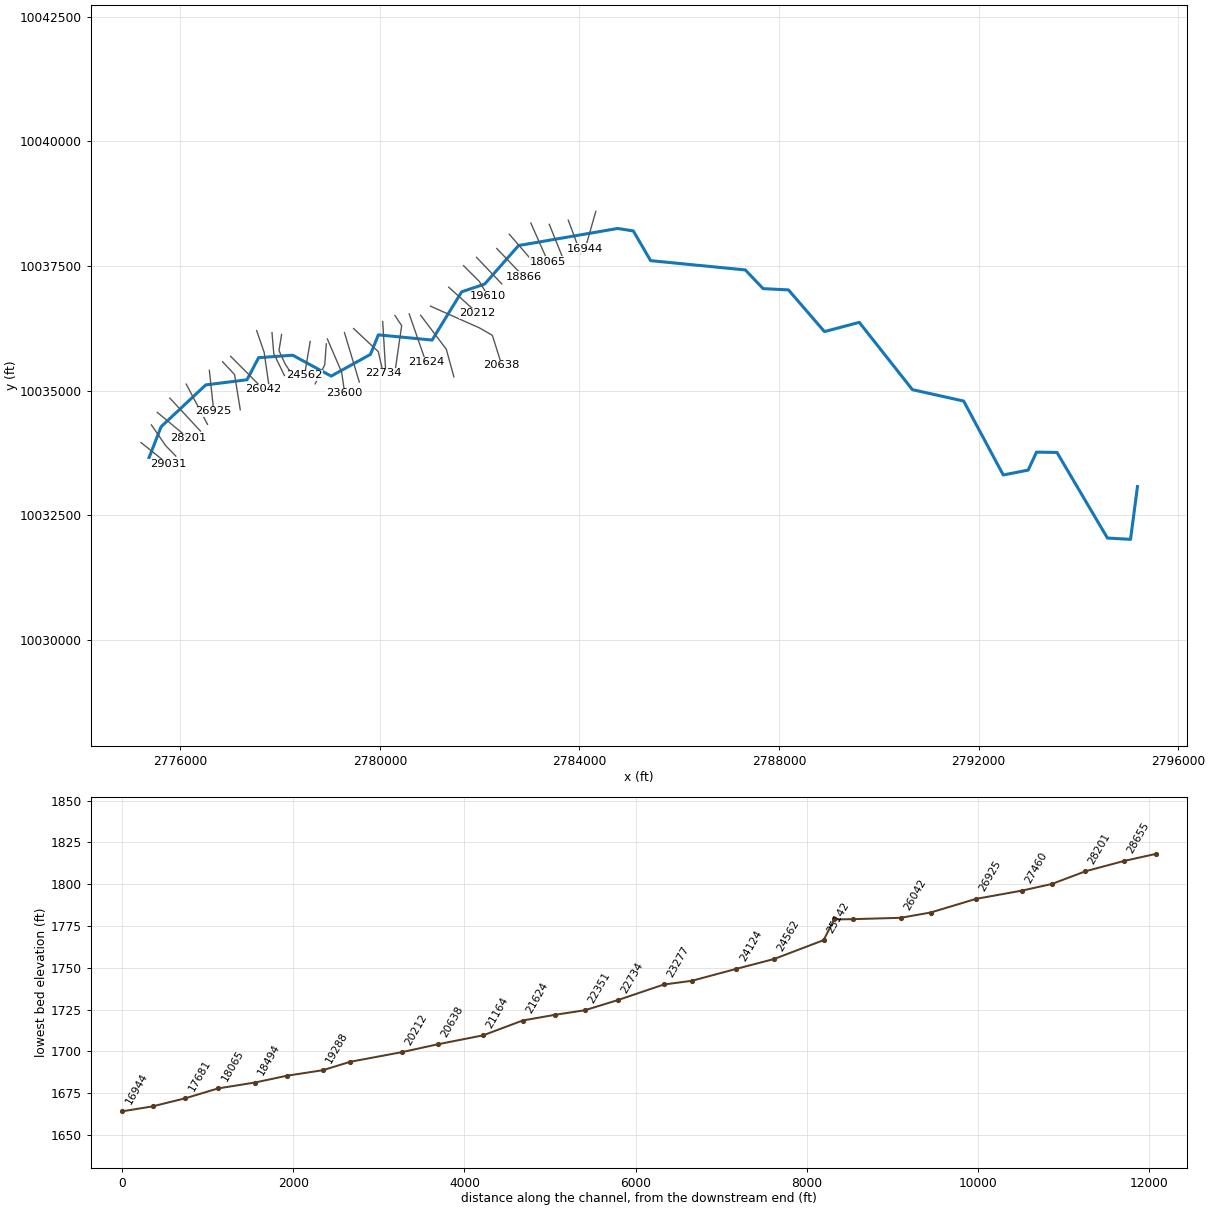
--- SNAKE CREEK.prj (project) ---

Proj Title=SNAKE CREEK Base Level Engineering
Current Plan=p01
Default Exp/Contr=0.3,0.1
English Units
Geom File=g01
Flow File=f01
Plan File=p01
Y Axis Title=Elevation
X Axis Title(PF)=Main Channel Distance
X Axis Title(XS)=Station
BEGIN DESCRIPTION:
SNAKE CREEK
END DESCRIPTION:
DSS Export Rating Curves= 0
DSS Export Rating Curve Sorted= 0
DSS Export Volume Flow Curves= 0
DXF OffsetX= 0
DXF OffsetY= 0
DXF ScaleX= 1
DXF ScaleY= 10

--- SNAKE CREEK.p01 (plan) ---

Plan Title=Multiple Run
Short Identifier=Multiple
Geom File=g01
Flow File=f01
Subcritical Flow
K Sum by GR= 0
Std Step Tol= 0.01
Critical Tol= 0.01
Num of Std Step Trials= 20
Max Error Tol= 0.3
Flow Tol Ratio= 0.001
Split Flow NTrial= 30
Split Flow Tol= 0.02
Split Flow Ratio= 0.02
Log Output Level= 0
Friction Slope Method= 1
Unsteady Friction Slope Method= 2
Unsteady Bridges Friction Slope Method= 1
Parabolic Critical Depth
Global Vel Dist=  1 , 1 , 1
Global Log Level= 0
CheckData=True
Encroach Param= -1, 0, 0, 0
BEGIN DESCRIPTION:
Multiple Run
END DESCRIPTION:

--- SNAKE CREEK.f01 (steady flow) ---

Flow Title=Multiple
Number of Profiles=7
Profile Names=10-year,25-year,50-year,1pct_min,100-year,1pct_plu,500-year
River Rch & RM= SNAKE CREEK,Reach-1,29031
     660     938    1173    1075    1454    1966    2241
River Rch & RM= SNAKE CREEK,Reach-1,27813
    1057    1541    1962    1827    2470    3341    3932
River Rch & RM= SNAKE CREEK,Reach-1,20638
    1452    2149    2765    2597    3512    4750    5696
River Rch & RM= SNAKE CREEK,Reach-1,13277
    1886    2823    3658    3458    4677    6325    7683
River Rch & RM= SNAKE CREEK,Reach-1,8021
    2124    3188    4138    3917    5297    7164    8725
Boundary for River Rch & Prof#=SNAKE CREEK,Reach-1,1
Up Type=0
Dn Type=3
Dn Slope=0.005
Boundary for River Rch & Prof#=SNAKE CREEK,Reach-1,2
Up Type=0
Dn Type=3
Dn Slope=0.005
Boundary for River Rch & Prof#=SNAKE CREEK,Reach-1,3
Up Type=0
Dn Type=3
Dn Slope=0.005
Boundary for River Rch & Prof#=SNAKE CREEK,Reach-1,4
Up Type=0
Dn Type=3
Dn Slope=0.005
Boundary for River Rch & Prof#=SNAKE CREEK,Reach-1,5
Up Type=0
Dn Type=3
Dn Slope=0.005
Boundary for River Rch & Prof#=SNAKE CREEK,Reach-1,6
Up Type=0
Dn Type=3
Dn Slope=0.005
Boundary for River Rch & Prof#=SNAKE CREEK,Reach-1,7
Up Type=0
Dn Type=3
Dn Slope=0.005

--- SNAKE CREEK.g01 (geometry) ---

Geom Title=Existing Conditions
Program Version=4.10

River Reach=SNAKE CREEK     ,Reach-1
Reach XY= 30
      2775374.88      10033659.8      2775616.31     10034279.48
      2776511.47     10035117.51      2777337.65     10035220.14
      2777570.25     10035663.15       2778252.7      10035712.3
      2779023.47      10035293.7      2779810.95      10035728.4
      2779969.73     10036120.36      2781047.02     10036016.21
      2781638.83     10036982.92      2782100.23     10037138.99
      2782779.38     10037911.27      2784765.22      10038253.6
      2785078.85     10038204.12      2785425.61     10037608.26
      2787322.82     10037422.24      2787679.98     10037047.31
      2788187.81     10037022.14      2788909.35      10036185.9
      2789607.39     10036371.13      2790671.91     10035021.66
      2791699.09     10034793.15      2792492.34     10033311.55
      2792991.15     10033408.82      2793159.92     10033770.07
      2793568.92     10033762.97      2794579.82     10032046.99
      2795043.02     10032020.82       2795182.3     10033079.13

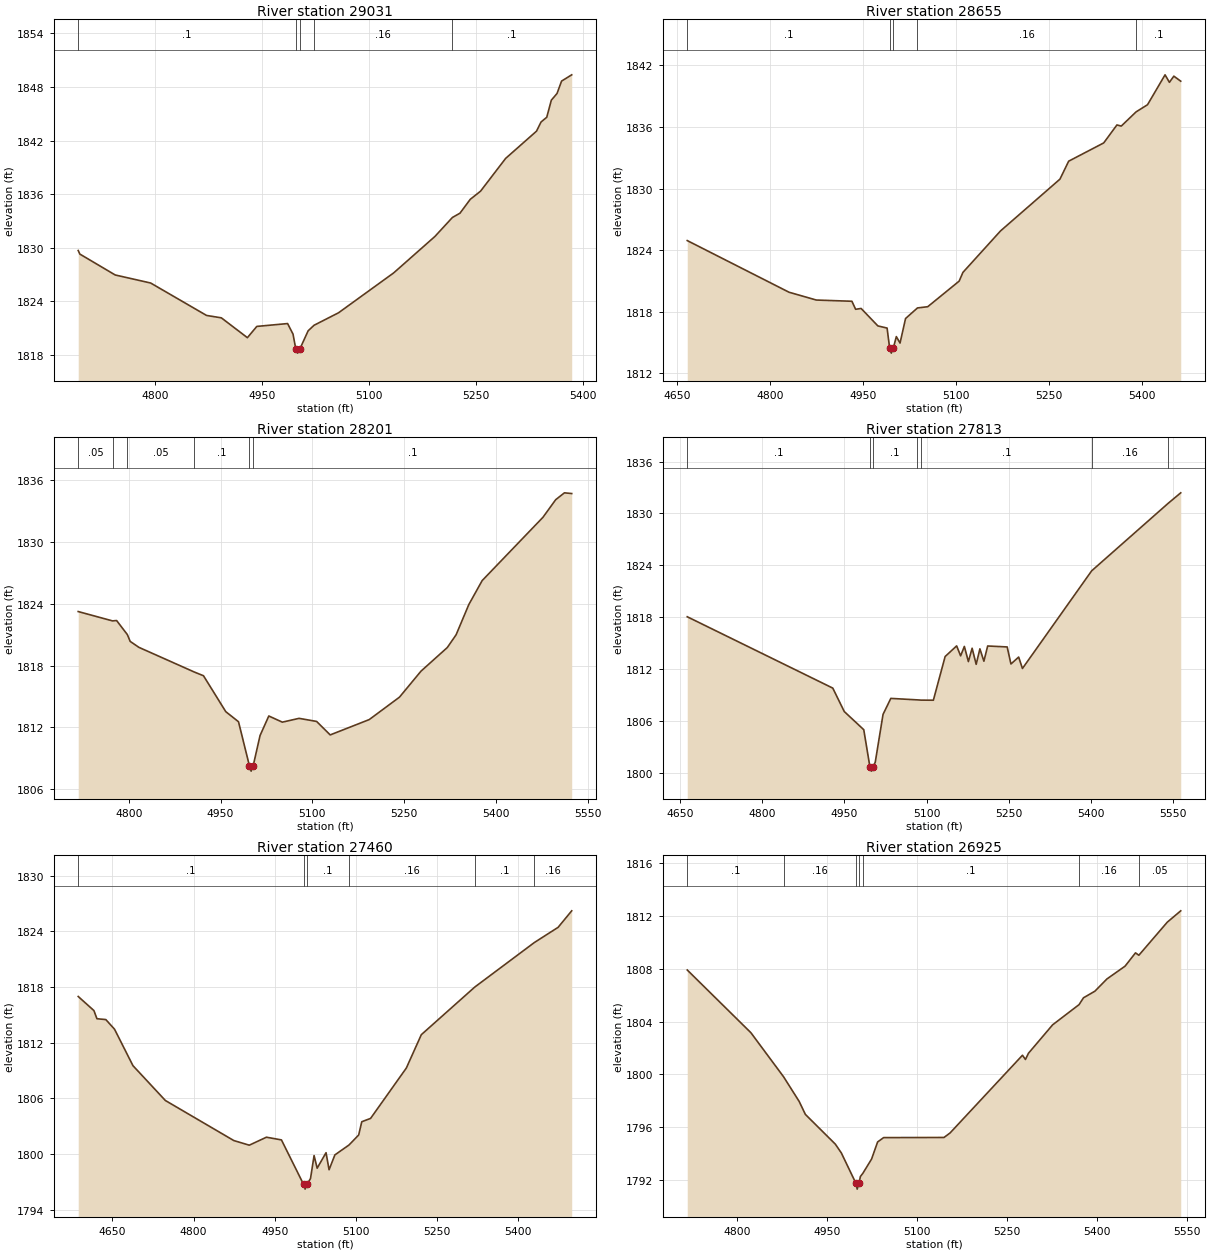
Type RM Length L Ch R = 1 ,29031   ,376,376,376
BEGIN DESCRIPTION:
SNAKE CREEK 59.0
END DESCRIPTION:
XS GIS Cut Line= 2
      2775213.01     10033961.21      2775754.03     10033529.43
#Sta/Elev= 30
  4691.6  1829.7  4693.9  1829.3  4743.5 1826.96  4793.2 1826.06  4871.6 1822.43
  4892.4 1822.16  4928.9 1819.94  4942.1  1821.2  4985.3 1821.52  4992.9 1820.34
  4996.7 1818.71  4999.5 1818.21  5002.7 1818.71  5014.1 1820.71  5022.4 1821.33
  5056.8 1822.73  5134.2  1827.2  5191.9 1831.27  5216.5  1833.4  5227.1 1833.88
  5241.5 1835.43  5255.9 1836.34  5291.1 1840.01  5334.4 1843.06  5340.8 1844.09
  5348.8 1844.62  5355.2 1846.53  5363.2 1847.28  5369.6 1848.67  5383.8 1849.37
#Mann= 5 ,-1 , 0
  4691.6      .1       0  4996.7     .07       0  5002.7      .1       0
  5022.4     .16       0  5216.5      .1       0
Bank Sta=4996.7,5002.7
XS Rating Curve= 0 ,0
Exp/Cntr=0.3,0.1

Type RM Length L Ch R = 1 ,28655   ,454,454,454
BEGIN DESCRIPTION:
SNAKE CREEK 58.0
END DESCRIPTION:
XS GIS Cut Line= 3
      2775421.31     10034315.41      2775707.79     10033898.72
      2775910.89     10033690.41
#Sta/Elev= 30
  4666.6 1824.93  4830.9  1819.9  4874.9 1819.14  4932.4 1819.02  4938.4 1818.24
  4947.3 1818.32  4974.3 1816.62  4989.2 1816.41  4993.3 1814.47    4996 1813.97
  4999.3 1814.47  5004.1 1815.58  5010.1 1814.95    5019 1817.34  5038.2 1818.37
  5054.8 1818.49  5105.5 1820.98  5111.6 1821.83  5172.3 1825.87  5268.2 1830.91
  5282.3 1832.66  5338.9 1834.44  5360.2 1836.19  5367.2 1836.08  5391.1 1837.46
  5409.6 1838.16  5437.9 1841.07  5444.9 1840.34  5452.1 1840.94  5463.2 1840.45
#Mann= 5 ,-1 , 0
  4666.6      .1       0  4993.3     .07       0  4999.3      .1       0
  5038.2     .16       0  5391.1      .1       0
Bank Sta=4993.3,4999.3
XS Rating Curve= 0 ,0
Exp/Cntr=0.3,0.1

Type RM Length L Ch R = 1 ,28201   ,388,388,388
BEGIN DESCRIPTION:
SNAKE CREEK 57.0
END DESCRIPTION:
XS GIS Cut Line= 2
      2775541.09     10034565.41      2776160.93     10034049.74
#Sta/Elev= 30
  4717.5 1823.25  4773.7 1822.34  4780.2 1822.38  4797.8 1821.01  4802.4 1820.35
  4816.7 1819.77  4906.9 1817.38  4922.2 1817.01  4958.6 1813.52  4979.4 1812.54
  4997.3 1808.24    5000 1807.74  5003.3 1808.24  5014.6  1811.2  5028.9  1813.1
    5051  1812.5  5078.4 1812.87    5107 1812.57  5129.2 1811.26    5193 1812.75
  5242.4 1814.93  5277.6 1817.46  5320.5 1819.75  5334.9 1820.99  5355.7 1823.93
  5377.5 1826.26  5476.8 1832.41  5497.6 1834.12  5511.9 1834.79  5523.8 1834.72
#Mann= 6 ,-1 , 0
  4717.5     .05       0  4773.7      .1       0  4797.8     .05       0
  4906.9      .1       0  4997.3     .07       0  5003.3      .1       0
Bank Sta=4997.3,5003.3
XS Rating Curve= 0 ,0
Exp/Cntr=0.3,0.1

Type RM Length L Ch R = 1 ,27813   ,353,353,353
BEGIN DESCRIPTION:
SNAKE CREEK 56.0
END DESCRIPTION:
XS GIS Cut Line= 2
      2775791.11     10034851.86       2776404.6     10034191.58
#Sta/Elev= 30
  4662.8 1818.06  4928.6 1809.81  4949.6  1807.1  4985.2    1805  4996.4 1800.71
  4999.2 1800.21  5002.4 1800.71  5006.2 1801.25  5020.4 1806.77  5034.6 1808.62
  5082.7 1808.45  5090.4 1808.42  5112.3 1808.41  5133.8 1813.46  5154.8 1814.69
  5162.1 1813.54  5168.9 1814.63  5176.3 1812.88  5183.1 1814.42  5190.5 1812.56
  5197.3 1814.35  5204.6 1812.92  5211.5 1814.68  5247.1 1814.57    5254  1812.6
  5268.1  1813.4    5275 1812.08  5401.4 1823.37  5541.2 1831.18  5564.1 1832.39
#Mann= 7 ,-1 , 0
  4662.8      .1       0  4996.4     .07       0  5002.4      .1       0
  5082.7     .16       0  5090.4      .1       0  5401.4     .16       0
  5541.2      .1       0
Bank Sta=4996.4,5002.4
XS Rating Curve= 0 ,0
Exp/Cntr=0.3,0.1

Type RM Length L Ch R = 1 ,27460   ,535,535,535
BEGIN DESCRIPTION:
SNAKE CREEK 55.0
END DESCRIPTION:
XS GIS Cut Line= 2
      2776119.26     10035133.07      2776545.55     10034327.28
#Sta/Elev= 30
    4587 1816.98    4616 1815.46  4621.6 1814.58    4638 1814.49  4654.1 1813.45
  4688.1 1809.52    4748 1805.76  4874.4 1801.44    4903 1800.94  4934.7  1801.8
  4962.4 1801.51  5003.4  1796.7  5006.1  1796.2  5009.4  1796.7  5016.1 1797.34
  5022.7 1799.82  5028.4 1798.46  5044.8 1800.13  5050.4 1798.29  5061.1 1799.89
  5087.2 1800.96  5105.1 1802.04  5110.8 1803.47  5127.1 1803.83  5193.1 1809.26
  5220.8 1812.86  5319.6    1818  5429.6  1822.8  5473.5 1824.44  5498.6 1826.22
#Mann= 6 ,-1 , 0
    4587      .1       0  5003.4     .07       0  5009.4      .1       0
  5087.2     .16       0  5319.6      .1       0  5429.6     .16       0
Bank Sta=5003.4,5009.4
XS Rating Curve= 0 ,0
Exp/Cntr=0.3,0.1

Type RM Length L Ch R = 1 ,26925   ,532,532,532
BEGIN DESCRIPTION:
SNAKE CREEK 54.0
END DESCRIPTION:
XS GIS Cut Line= 2
      2776582.78     10035409.17      2776671.33     10034591.45
#Sta/Elev= 30
  4717.5 1807.91  4823.6 1803.15    4878 1799.81    4904 1797.94  4914.4 1796.95
  4964.4 1794.69  4974.4 1794.02    4998 1791.78  5000.8 1791.28    5004 1791.78
  5006.1 1792.24  5010.2 1792.48  5024.7 1793.56  5034.8 1794.86  5044.8 1795.19
  5145.4  1795.2  5155.5 1795.54  5276.2 1801.44  5281.2 1801.12  5286.2 1801.59
  5326.5 1803.75  5370.5 1805.28  5377.9  1805.8  5396.9  1806.3    5417 1807.23
  5447.2  1808.2  5464.6 1809.21  5470.2 1809.03  5517.6 1811.54    5540  1812.4
#Mann= 7 ,-1 , 0
  4717.5      .1       0    4878     .16       0    4998     .07       0
    5004     .16       0  5010.2      .1       0  5370.5     .16       0
  5470.2     .05       0
Bank Sta=4998,5004
XS Rating Curve= 0 ,0
Exp/Cntr=0.3,0.1

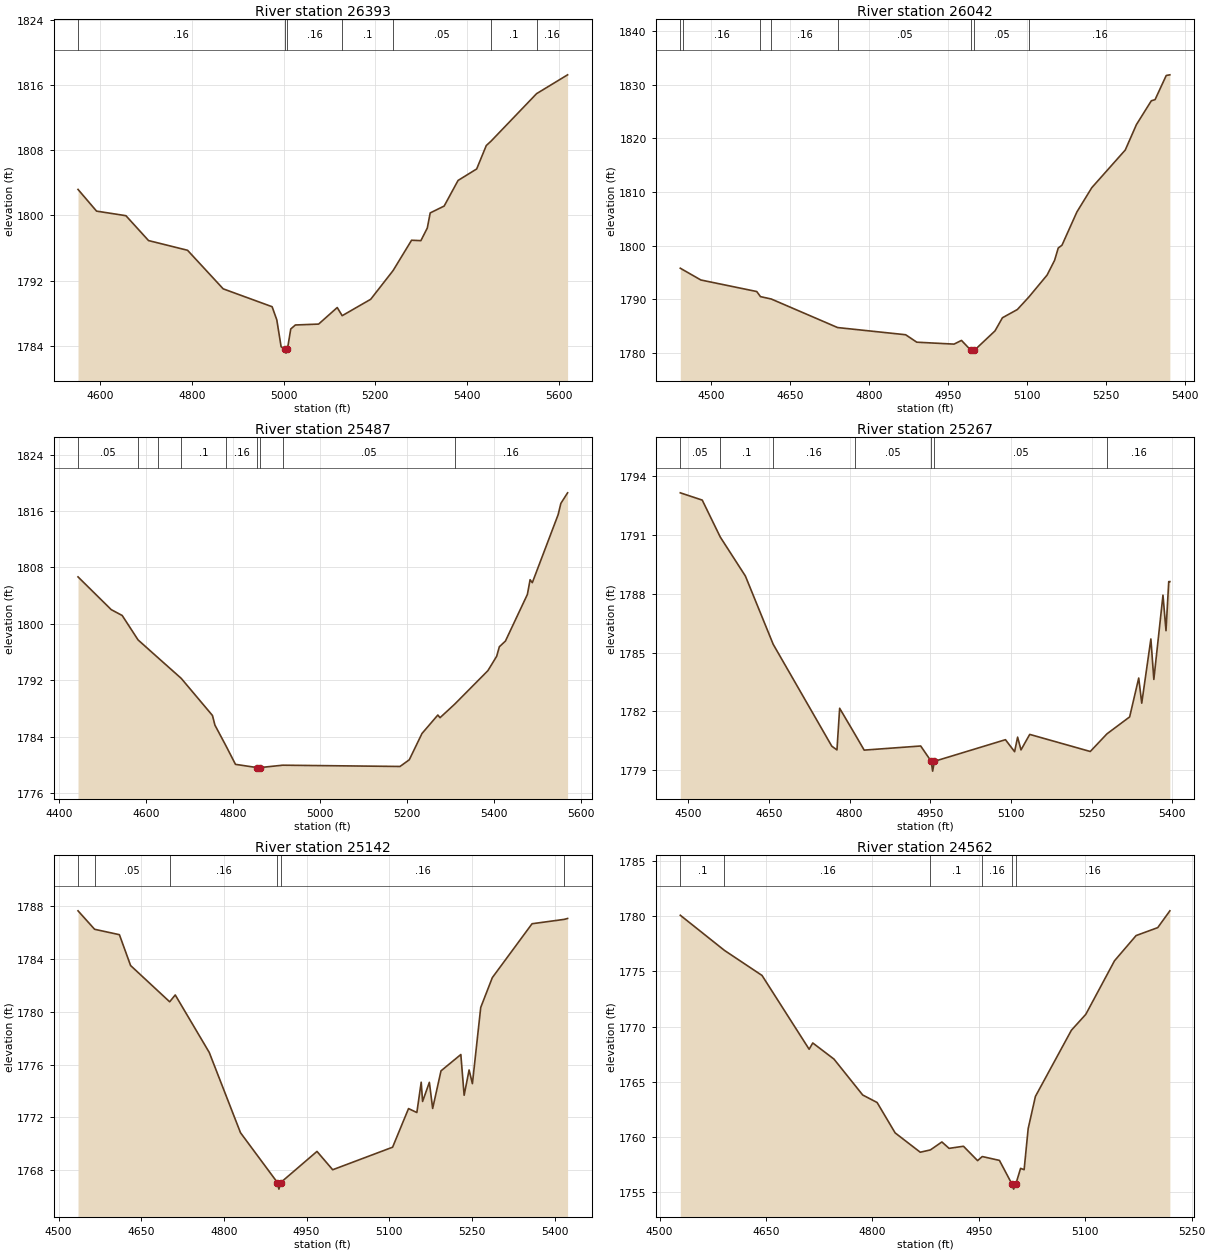
Type RM Length L Ch R = 1 ,26393   ,351,351,351
BEGIN DESCRIPTION:
SNAKE CREEK 53.0
END DESCRIPTION:
XS GIS Cut Line= 3
      2776848.42       10035581.        2777088.      10035325.8
      2777202.47     10034618.14
#Sta/Elev= 30
    4552 1803.17  4592.4 1800.51  4656.4 1799.95  4705.7  1796.9  4790.7 1795.71
  4868.4 1790.98    4975 1788.79  4985.2 1787.18  4994.6 1783.88  5002.4  1783.6
  5005.2  1783.1  5008.4  1783.6  5015.6 1786.06  5025.7 1786.55  5076.3 1786.66
  5116.9 1788.69  5127.7 1787.69  5189.8  1789.7  5238.6 1793.22  5278.9 1796.94
  5299.2 1796.89  5313.2 1798.44  5319.5 1800.29  5349.9 1801.13  5380.2 1804.27
  5420.8 1805.68  5441.7 1808.55  5452.3  1809.1  5551.3 1814.91  5618.9 1817.22
#Mann= 7 ,-1 , 0
    4552     .16       0  5002.4     .07       0  5008.4     .16       0
  5127.7      .1       0  5238.6     .05       0  5452.3      .1       0
  5551.3     .16       0
Bank Sta=5002.4,5008.4
XS Rating Curve= 0 ,0
Exp/Cntr=0.3,0.1

Type RM Length L Ch R = 1 ,26042   ,555,555,555
BEGIN DESCRIPTION:
SNAKE CREEK 52.0
END DESCRIPTION:
XS GIS Cut Line= 2
      2777009.85      10035690.4      2777664.79     10035030.27
#Sta/Elev= 30
    4441 1795.78  4446.8 1795.45  4480.1 1793.58  4586.2 1791.43  4593.3 1790.48
  4613.9 1790.03  4739.8 1784.71    4869 1783.37  4890.2 1781.98  4960.9 1781.62
  4975.1 1782.31  4993.3 1780.44    4996 1779.94  4999.3 1780.44  5038.7 1784.08
  5052.9 1786.54  5081.2 1788.07  5103.2 1790.42  5137.7  1794.5  5151.9 1797.24
  5158.9 1799.55    5166 1800.07  5194.3 1806.27  5222.6  1810.8  5286.2 1817.83
  5307.4 1822.57  5335.7 1827.01  5342.8 1827.22    5364 1831.73  5370.9 1831.85
#Mann= 8 ,-1 , 0
    4441      .1       0  4446.8     .16       0  4593.3     .05       0
  4613.9     .16       0  4739.8     .05       0  4993.3    .033       0
  4999.3     .05       0  5103.2     .16       0
Bank Sta=4993.3,4999.3
XS Rating Curve= 0 ,0
Exp/Cntr=0.3,0.1

Type RM Length L Ch R = 1 ,25487   ,220,220,220
BEGIN DESCRIPTION:
SNAKE CREEK 51.0
END DESCRIPTION:
XS GIS Cut Line= 3
      2777530.71     10036205.99      2777681.75     10035768.51
      2777775.49     10035112.29
#Sta/Elev= 30
  4443.5 1806.66  4519.9 1802.02  4545.1 1801.19  4581.6 1797.73  4628.1 1795.17
  4680.7 1792.29  4752.7 1787.02  4758.2 1785.67  4783.3 1782.77  4805.6  1780.1
  4855.5 1779.64  4858.2 1779.14  4861.5 1779.64  4914.1 1779.98  5183.9  1779.8
  5205.2 1780.75  5234.4 1784.47  5270.9 1787.09  5275.9 1786.71  5309.5 1788.62
  5385.9 1793.37  5406.1 1795.41  5412.3 1796.76  5426.3 1797.57  5476.8 1804.18
    5483 1806.26  5488.1 1805.84  5547.5 1815.48  5553.7 1817.07  5569.2 1818.57
#Mann= 9 ,-1 , 0
  4443.5     .05       0  4581.6      .1       0  4628.1     .05       0
  4680.7      .1       0  4783.3     .16       0  4855.5    .033       0
  4861.5     .16       0  4914.1     .05       0  5309.5     .16       0
Bank Sta=4855.5,4861.5
XS Rating Curve= 0 ,0
Exp/Cntr=0.3,0.1

Type RM Length L Ch R = 1 ,25267   ,125,125,125
BEGIN DESCRIPTION:
Mapping XS 78d06c24
END DESCRIPTION:
XS GIS Cut Line= 3
      2777837.99     10036164.38      2777874.46     10035742.47
      2778087.99     10035304.98
#Sta/Elev= 30
  4485.2 1793.13    4526 1792.76  4559.5 1790.88  4606.3 1788.89  4657.9 1785.42
  4766.9 1780.23  4776.5 1780.04  4781.5 1782.16  4809.7 1780.85  4827.1 1780.03
  4932.2 1780.24  4951.7 1779.46  4954.4 1778.96  4957.7 1779.46  5089.8 1780.56
  5106.8 1779.95  5112.4 1780.69  5118.7 1780.04  5134.9 1780.83  5247.5 1779.96
  5278.6 1780.86  5320.7 1781.72  5337.6  1783.7  5343.2 1782.42  5360.2 1785.69
  5365.7 1783.63  5382.7 1787.92  5388.3 1786.11  5393.4 1788.61  5395.5 1788.61
#Mann= 7 ,-1 , 0
  4485.2     .05       0  4559.5      .1       0  4657.9     .16       0
  4809.7     .05       0  4951.7    .033       0  4957.7     .05       0
  5278.6     .16       0
Bank Sta=4951.7,4957.7
XS Rating Curve= 0 ,0
Exp/Cntr=0.3,0.1

Type RM Length L Ch R = 1 ,25142   ,580,580,580
BEGIN DESCRIPTION:
SNAKE CREEK 50.0
END DESCRIPTION:
XS GIS Cut Line= 4
      2778030.71     10036127.91      2777978.62     10035804.97
      2778103.62     10035534.13      2778249.45     10035315.39
#Sta/Elev= 30
  4535.4 1787.67  4565.5 1786.27  4610.5 1785.86  4630.8 1783.52  4701.7 1780.77
  4711.8 1781.29  4773.5 1776.93  4830.2 1770.84  4897.2 1767.06  4899.9 1766.56
  4903.2 1767.06    4969 1769.42  4997.5 1768.03  5106.2 1769.74  5135.1 1772.67
  5150.2 1772.37  5158.1 1774.67  5160.6 1773.21  5172.9 1774.66  5178.9 1772.68
    5194 1775.53    5230 1776.77    5236 1773.68    5245  1775.6    5251 1774.56
  5266.1 1780.34  5287.1  1782.6  5359.2 1786.69  5417.3 1787.02  5423.7 1787.09
#Mann= 6 ,-1 , 0
  4535.4      .1       0  4565.5     .05       0  4701.7     .16       0
  4897.2     .07       0  4903.2     .16       0  5417.3      .1       0
Bank Sta=4897.2,4903.2
XS Rating Curve= 0 ,0
Exp/Cntr=0.3,0.1

Type RM Length L Ch R = 1 ,24562   ,438,438,438
BEGIN DESCRIPTION:
SNAKE CREEK 49.0
END DESCRIPTION:
XS GIS Cut Line= 2
      2778603.63     10035987.29      2778489.35     10035306.82
#Sta/Elev= 30
  4529.2 1780.07  4591.4 1776.89  4644.4 1774.62  4710.8 1767.94  4715.9 1768.51
  4745.8 1767.05  4786.3  1763.8  4806.6 1763.12    4832 1760.37  4867.4 1758.62
  4881.7 1758.83  4897.9 1759.55    4908 1758.97  4928.3 1759.16  4948.2 1757.86
  4954.8 1758.23    4979 1757.88  4996.3 1755.78    4999 1755.28  5002.3 1755.78
  5008.8 1757.16  5013.8 1757.04  5019.5 1760.76  5029.7 1763.67  5080.4 1769.66
  5100.7  1771.1  5141.2 1775.95  5171.6 1778.23  5202.1 1778.95  5219.2 1780.47
#Mann= 6 ,-1 , 0
  4529.2      .1       0  4591.4     .16       0  4881.7      .1       0
  4954.8     .16       0  4996.3     .07       0  5002.3     .16       0
Bank Sta=4996.3,5002.3
XS Rating Curve= 0 ,0
Exp/Cntr=0.3,0.1

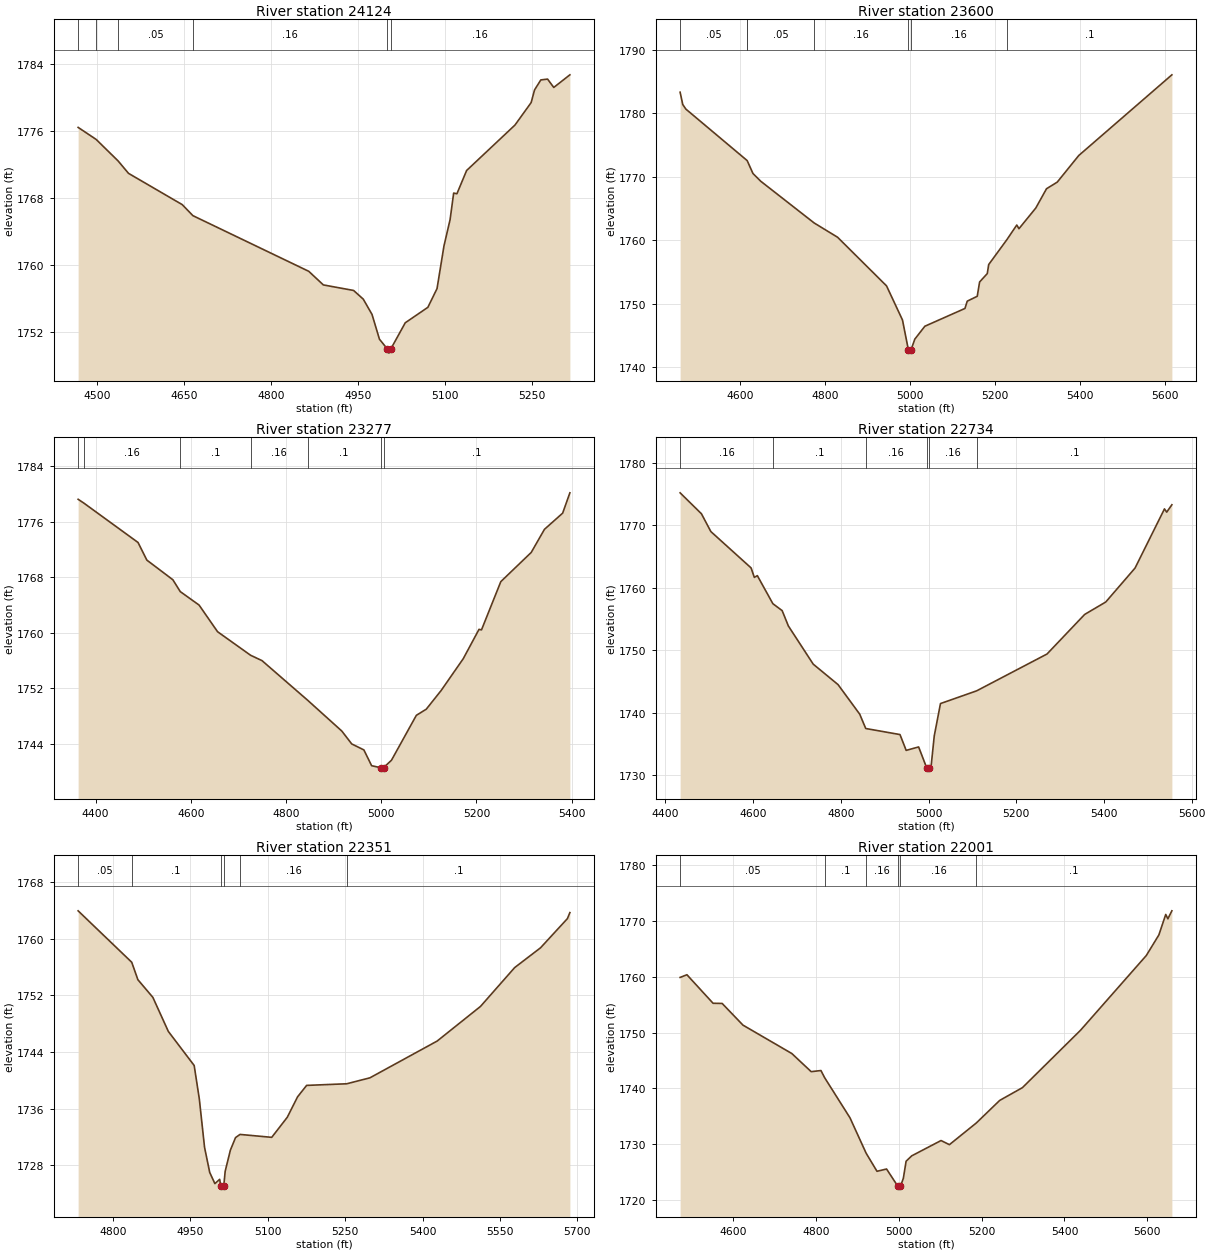
Type RM Length L Ch R = 1 ,24124   ,524,524,524
BEGIN DESCRIPTION:
SNAKE CREEK 48.0
END DESCRIPTION:
XS GIS Cut Line= 3
      2778926.54     10035940.35      2778895.29     10035518.51
      2778703.15     10035139.42
#Sta/Elev= 30
    4467 1776.44  4498.1    1775  4535.9 1772.43  4553.9 1770.94  4646.5  1767.2
  4664.9 1765.88  4864.7 1759.22  4889.9 1757.59    4942 1756.93  4958.7 1755.89
  4973.8 1754.06  4986.6  1751.1  5000.2 1749.93    5003 1749.43  5006.2 1749.93
  5031.1 1753.06  5070.1 1754.91  5085.9 1757.15  5097.9 1762.27  5108.4  1765.4
  5114.6 1768.58  5120.2  1768.5  5136.9 1771.28  5220.3 1776.72  5248.2 1779.41
  5254.1 1780.93  5264.9 1782.12  5276.5 1782.22  5287.2 1781.22    5315 1782.73
#Mann= 6 ,-1 , 0
    4467     .05       0  4498.1      .1       0  4535.9     .05       0
  4664.9     .16       0  5000.2     .07       0  5006.2     .16       0
Bank Sta=5000.2,5006.2
XS Rating Curve= 0 ,0
Exp/Cntr=0.3,0.1

Type RM Length L Ch R = 1 ,23600   ,323,323,323
BEGIN DESCRIPTION:
SNAKE CREEK 47.0
END DESCRIPTION:
XS GIS Cut Line= 3
      2778947.35     10036039.38      2779233.83     10035372.67
       2779296.1     10034947.16
#Sta/Elev= 30
  4459.6 1783.35  4465.8 1781.41  4473.1 1780.69  4616.9 1772.59  4617.2 1772.57
  4630.8 1770.54  4648.9 1769.33  4774.7 1762.74  4829.7 1760.49  4944.7 1752.83
  4982.2 1747.45  4996.1 1742.73  4998.8 1742.23  5002.1 1742.73  5011.2 1744.44
  5034.8 1746.47    5129 1749.27  5134.4 1750.42  5157.9 1751.19  5163.4 1753.44
  5181.5 1754.77  5184.8 1756.19  5227.2 1760.08  5250.8 1762.42  5255.9 1761.84
  5295.4 1765.09  5320.7 1768.14  5345.9 1769.18  5396.4 1773.37  5615.3 1786.09
#Mann= 7 ,-1 , 0
  4459.6     .05       0  4616.9      .1       0  4617.2     .05       0
  4774.7     .16       0  4996.1     .07       0  5002.1     .16       0
  5227.2      .1       0
Bank Sta=4996.1,5002.1
XS Rating Curve= 0 ,0
Exp/Cntr=0.3,0.1

Type RM Length L Ch R = 1 ,23277   ,543,543,543
BEGIN DESCRIPTION:
SNAKE CREEK 46.0
END DESCRIPTION:
XS GIS Cut Line= 2
      2779291.13     10036164.31      2779587.99     10035174.78
#Sta/Elev= 30
  4363.3 1779.27  4375.1 1778.73  4489.2 1773.04  4507.7  1770.5  4562.3 1767.67
  4577.9 1765.96  4617.4 1764.02  4656.2 1760.18  4725.7 1756.78  4749.6 1756.01
  4845.8 1750.28  4917.2 1745.86  4938.1    1744  4963.6 1743.14  4979.9 1740.86
  4998.9 1740.58  5001.7 1740.08  5004.9 1740.58  5021.6 1741.65  5073.8 1748.12
  5094.7 1749.01    5126 1751.71  5172.4 1756.29  5205.5 1760.52  5210.7 1760.44
  5251.3  1767.4  5315.1  1771.6    5343 1774.94  5381.2 1777.27  5396.4  1780.2
#Mann= 7 ,-1 , 0
  4363.3      .1       0  4375.1     .16       0  4577.9      .1       0
  4725.7     .16       0  4845.8      .1       0  4998.9     .07       0
  5004.9      .1       0
Bank Sta=4998.9,5004.9
XS Rating Curve= 0 ,0
Exp/Cntr=0.3,0.1

Type RM Length L Ch R = 1 ,22734   ,383,383,383
BEGIN DESCRIPTION:
SNAKE CREEK 45.0
END DESCRIPTION:
XS GIS Cut Line= 3
      2779473.44     10036247.65      2779968.21     10035784.13
      2780067.15     10035351.89
#Sta/Elev= 30
  4433.5  1775.2  4482.1 1771.85  4503.6    1769  4595.4 1763.18  4602.7 1761.67
  4609.6 1761.95    4645 1757.46  4666.2 1756.35  4680.4 1753.89    4737 1747.79
  4793.7 1744.51    4843 1739.79  4856.8 1737.49  4934.9 1736.52    4949 1733.99
  4977.4 1734.54  4995.9 1731.17  4998.6 1730.67  5001.9 1731.17  5005.7 1731.34
    5013 1736.29  5027.2 1741.48  5109.8 1743.52  5270.2 1749.41    5356 1755.74
  5404.1 1757.73  5470.9 1763.16    5538 1772.63  5543.1 1772.11  5554.9 1773.29
#Mann= 6 ,-1 , 0
  4433.5     .16       0    4645      .1       0  4856.8     .16       0
  4995.9     .07       0  5001.9     .16       0  5109.8      .1       0
Bank Sta=4995.9,5001.9
XS Rating Curve= 0 ,0
Exp/Cntr=0.3,0.1

Type RM Length L Ch R = 1 ,22351   ,350,350,350
BEGIN DESCRIPTION:
SNAKE CREEK 44.0
END DESCRIPTION:
XS GIS Cut Line= 2
      2780056.75     10036388.25      2780113.93     10035436.97
#Sta/Elev= 30
  4732.6 1763.93  4836.5 1756.67  4848.4 1754.21  4877.4 1751.72  4907.4 1746.91
  4957.5  1742.1  4967.5 1737.36  4977.6 1730.55  4987.6 1727.01  4997.6 1725.43
  5006.9 1726.03  5008.9 1725.15  5011.7 1724.65  5014.9 1725.15  5017.6 1727.18
  5027.7 1730.16  5037.7 1731.93  5046.4 1732.37  5107.8 1731.96  5137.9 1734.79
  5157.9 1737.68  5175.4 1739.29  5253.2 1739.52  5298.1 1740.36  5428.4 1745.55
  5512.4 1750.44  5578.6 1755.92  5628.7 1758.71  5680.8 1762.83  5685.6 1763.68
#Mann= 6 ,-1 , 0
  4732.6     .05       0  4836.5      .1       0  5008.9     .07       0
  5014.9      .1       0  5046.4     .16       0  5253.2      .1       0
Bank Sta=5008.9,5014.9
XS Rating Curve= 0 ,0
Exp/Cntr=0.3,0.1

Type RM Length L Ch R = 1 ,22001   ,377,377,377
BEGIN DESCRIPTION:
SNAKE CREEK 43.0
END DESCRIPTION:
XS GIS Cut Line= 3
      2780301.53     10036508.11      2780436.96     10036304.97
      2780301.54      10035372.7
#Sta/Elev= 30
  4472.9 1759.89  4489.3 1760.37  4552.4 1755.25  4574.3 1755.22  4624.5 1751.33
  4742.4 1746.23    4789 1742.98  4812.6 1743.18  4821.4 1741.91  4882.7 1734.69
  4921.5 1728.36  4947.8  1725.1  4970.9 1725.51  4998.2  1722.4    5001  1721.9
  5004.2  1722.4  5011.3 1723.82    5018 1726.91  5031.5 1727.87  5102.3 1730.62
  5122.5 1729.88  5187.5 1733.78  5243.8 1737.82  5298.6 1740.11  5438.9 1750.42
  5597.4 1763.82  5627.7 1767.51  5644.3 1771.19  5649.4 1770.41  5659.1 1771.84
#Mann= 6 ,-1 , 0
  4472.9     .05       0  4821.4      .1       0  4921.5     .16       0
  4998.2     .07       0  5004.2     .16       0  5187.5      .1       0
Bank Sta=4998.2,5004.2
XS Rating Curve= 0 ,0
Exp/Cntr=0.3,0.1

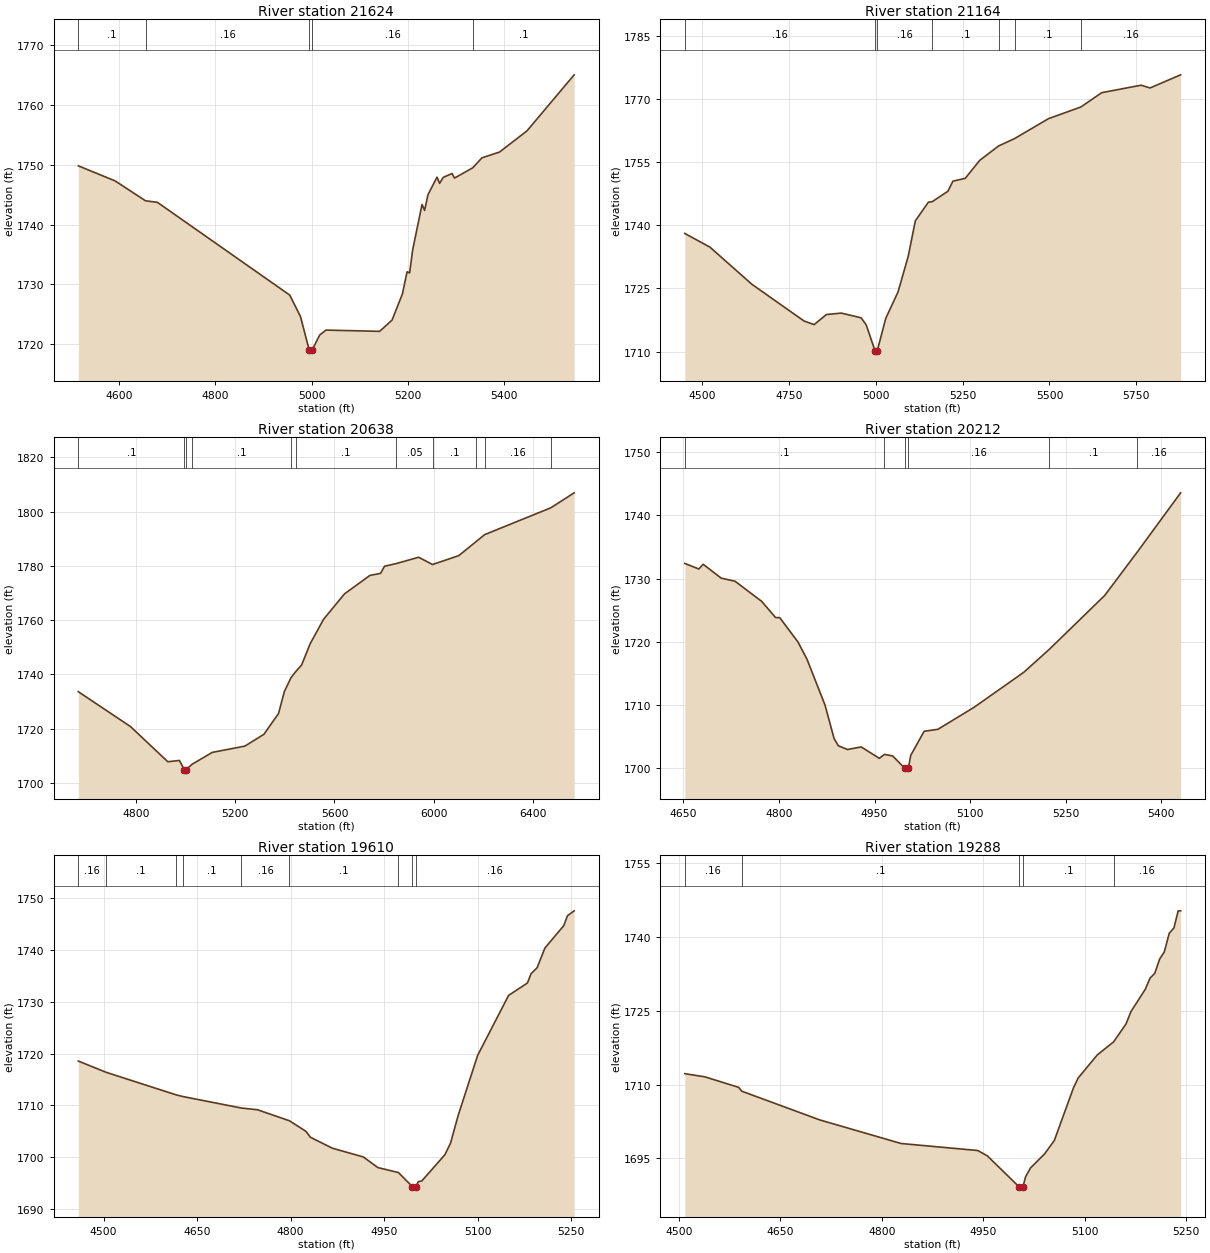
Type RM Length L Ch R = 1 ,21624   ,460,460,460
BEGIN DESCRIPTION:
SNAKE CREEK 42.0
END DESCRIPTION:
XS GIS Cut Line= 2
      2780587.99     10036539.35      2780925.97     10035567.02
#Sta/Elev= 30
  4515.7 1749.81  4591.9  1747.3  4655.2 1743.97  4679.9 1743.71  4954.6 1728.21
  4976.9 1724.63  4995.1 1719.01  4997.8 1718.51  5001.1 1719.01  5016.8 1721.54
  5029.8 1722.36  5141.3 1722.15  5167.1 1724.04  5188.6 1728.42  5198.2 1732.11
  5203.5 1731.91  5209.8 1735.76  5229.3 1743.36  5234.6 1742.36  5241.6 1744.99
  5260.4 1747.92  5265.7 1746.88  5273.3 1747.88  5291.5 1748.53  5296.8 1747.77
  5334.5 1749.48  5353.7 1751.15  5390.1 1752.11  5447.1 1755.65  5545.1 1765.02
#Mann= 5 ,-1 , 0
  4515.7      .1       0  4655.2     .16       0  4995.1     .07       0
  5001.1     .16       0  5334.5      .1       0
Bank Sta=4995.1,5001.1
XS Rating Curve= 0 ,0
Exp/Cntr=0.3,0.1

Type RM Length L Ch R = 1 ,21164   ,526,526,526
BEGIN DESCRIPTION:
SNAKE CREEK 41.0
END DESCRIPTION:
XS GIS Cut Line= 3
      2780817.17     10036513.29      2781331.09     10035832.91
      2781483.49     10035278.75
#Sta/Elev= 30
  4450.2 1738.06  4522.8 1734.79  4643.5 1725.98  4793.4 1717.28  4822.5 1716.42
  4857.9 1718.81  4900.8 1719.15  4957.8 1718.03  4972.4 1716.38  4998.1 1710.15
  5000.8 1709.65  5004.1 1710.15  5028.6 1717.88    5064 1724.16  5093.1 1732.53
  5113.9 1741.05  5151.3 1745.46  5162.4 1745.59  5207.6 1748.06  5222.1 1750.46
  5257.5 1751.13  5299.2  1755.4  5353.3  1758.8  5399.8 1760.58  5497.1 1765.29
  5590.5 1768.07  5650.3 1771.46    5764 1773.24  5789.5 1772.58  5877.6  1775.7
#Mann= 7 ,-1 , 0
  4450.2     .16       0  4998.1     .07       0  5004.1     .16       0
  5162.4      .1       0  5353.3     .05       0  5399.8      .1       0
  5590.5     .16       0
Bank Sta=4998.1,5004.1
XS Rating Curve= 0 ,0
Exp/Cntr=0.3,0.1

Type RM Length L Ch R = 1 ,20638   ,426,426,426
BEGIN DESCRIPTION:
SNAKE CREEK 40.0
END DESCRIPTION:
XS GIS Cut Line= 4
      2781015.09     10036695.59      2781989.04      10036263.3
      2782254.71     10036110.68       2782442.2     10035513.49
#Sta/Elev= 30
  4567.9 1733.62    4778 1720.78  4928.5 1707.81  4975.1 1708.29  4995.3 1704.85
    4998 1704.35  5001.3 1704.85  5025.8 1706.86  5107.8 1711.26    5239 1713.57
  5315.6 1717.91  5374.7  1725.6  5397.9 1733.63  5424.9  1738.8  5443.8 1741.02
  5467.7 1743.47  5501.9 1751.26  5556.3 1760.33  5640.6 1769.69  5742.7 1776.46
  5785.8 1777.24  5801.6 1779.85  5849.6 1780.85  5939.1 1783.17  5995.2 1780.49
  6100.9 1783.77  6172.1 1789.04  6205.1  1791.5  6471.6 1801.38  6565.8 1806.91
#Mann= 11 ,-1 , 0
  4567.9      .1       0  4995.3     .07       0  5001.3      .1       0
  5025.8      .1       0  5424.9     .16       0  5443.8      .1       0
  5849.6     .05       0  5995.2      .1       0  6172.1     .05       0
  6205.1     .16       0  6471.6      .1       0
Bank Sta=4995.3,5001.3
XS Rating Curve= 0 ,0
Exp/Cntr=0.3,0.1

Type RM Length L Ch R = 1 ,20212   ,602,602,602
BEGIN DESCRIPTION:
SNAKE CREEK 39.0
END DESCRIPTION:
XS GIS Cut Line= 2
      2781379.66      10037075.8      2781957.76     10036554.99
#Sta/Elev= 30
  4652.2 1732.41  4674.2 1731.53    4681 1732.28  4709.4 1730.08    4731  1729.6
  4772.9 1726.41  4794.6 1723.86  4801.3 1723.83  4829.7 1720.01  4843.9 1717.28
  4872.3 1710.01  4886.5 1704.72  4893.2 1703.59  4907.4    1703  4929.1  1703.4
  4957.5  1701.6  4965.5 1702.23  4978.4 1701.98  4997.1 1700.08  4999.8 1699.58
  5003.1 1700.08  5006.8 1702.08  5027.8 1705.88  5049.4 1706.19  5106.2 1709.67
    5184 1715.19  5224.2 1718.83    5311 1727.33  5362.4 1734.23  5430.3 1743.57
#Mann= 6 ,-1 , 0
  4652.2      .1       0  4965.5     .16       0  4997.1     .07       0
  5003.1     .16       0  5224.2      .1       0  5362.4     .16       0
Bank Sta=4997.1,5003.1
XS Rating Curve= 0 ,0
Exp/Cntr=0.3,0.1

Type RM Length L Ch R = 1 ,19610   ,322,322,322
BEGIN DESCRIPTION:
SNAKE CREEK 38.0
END DESCRIPTION:
XS GIS Cut Line= 3
      2781676.55     10037508.08      2781994.25     10037190.38
      2782171.35     10036893.48
#Sta/Elev= 30
  4459.6 1718.55  4504.2 1716.38  4615.8 1712.05  4627.3  1711.7  4721.2 1709.48
  4746.9 1709.15    4798 1707.03  4824.6 1704.98  4831.7 1703.84  4867.1 1701.72
  4916.6 1700.04  4939.9 1697.99  4972.9 1697.03  4995.1 1694.33  4997.9 1693.83
  5001.1 1694.33  5004.5 1695.25  5010.3 1695.41  5047.3 1700.46  5056.4 1702.71
  5068.7 1708.08  5099.8 1719.64  5149.5 1731.23  5179.6 1733.61  5185.5 1735.41
  5195.2 1736.56  5207.7 1740.37    5238  1744.7  5243.8 1746.59  5254.6 1747.55
#Mann= 9 ,-1 , 0
  4459.6     .16       0  4504.2      .1       0  4615.8     .16       0
  4627.3      .1       0  4721.2     .16       0    4798      .1       0
  4972.9     .16       0  4995.1     .07       0  5001.1     .16       0
Bank Sta=4995.1,5001.1
XS Rating Curve= 0 ,0
Exp/Cntr=0.3,0.1

Type RM Length L Ch R = 1 ,19288   ,422,422,422
BEGIN DESCRIPTION:
SNAKE CREEK 37.0
END DESCRIPTION:
XS GIS Cut Line= 2
      2781936.99     10037674.72      2782442.19     10037143.48
#Sta/Elev= 30
  4508.8 1712.22  4538.7 1711.57  4588.4 1709.44  4593.1 1708.66  4708.6 1702.82
  4828.7 1698.04  4941.9 1696.62  4956.1 1695.54  5002.8 1689.28  5005.6 1688.78
  5008.8 1689.28  5012.7  1691.3    5020 1693.09    5041 1695.97  5055.2 1698.67
  5083.5 1709.35  5090.4 1711.34  5118.7 1716.03  5142.9 1718.69  5161.2 1722.32
  5168.4 1724.81  5189.5 1729.32  5196.7 1731.62  5203.6 1732.57  5210.9 1735.49
  5217.8 1736.95  5225.1 1740.73    5232  1741.8  5238.3 1745.28  5241.9 1745.28
#Mann= 5 ,-1 , 0
  4508.8     .16       0  4593.1      .1       0  5002.8     .07       0
  5008.8      .1       0  5142.9     .16       0
Bank Sta=5002.8,5008.8
XS Rating Curve= 0 ,0
Exp/Cntr=0.3,0.1

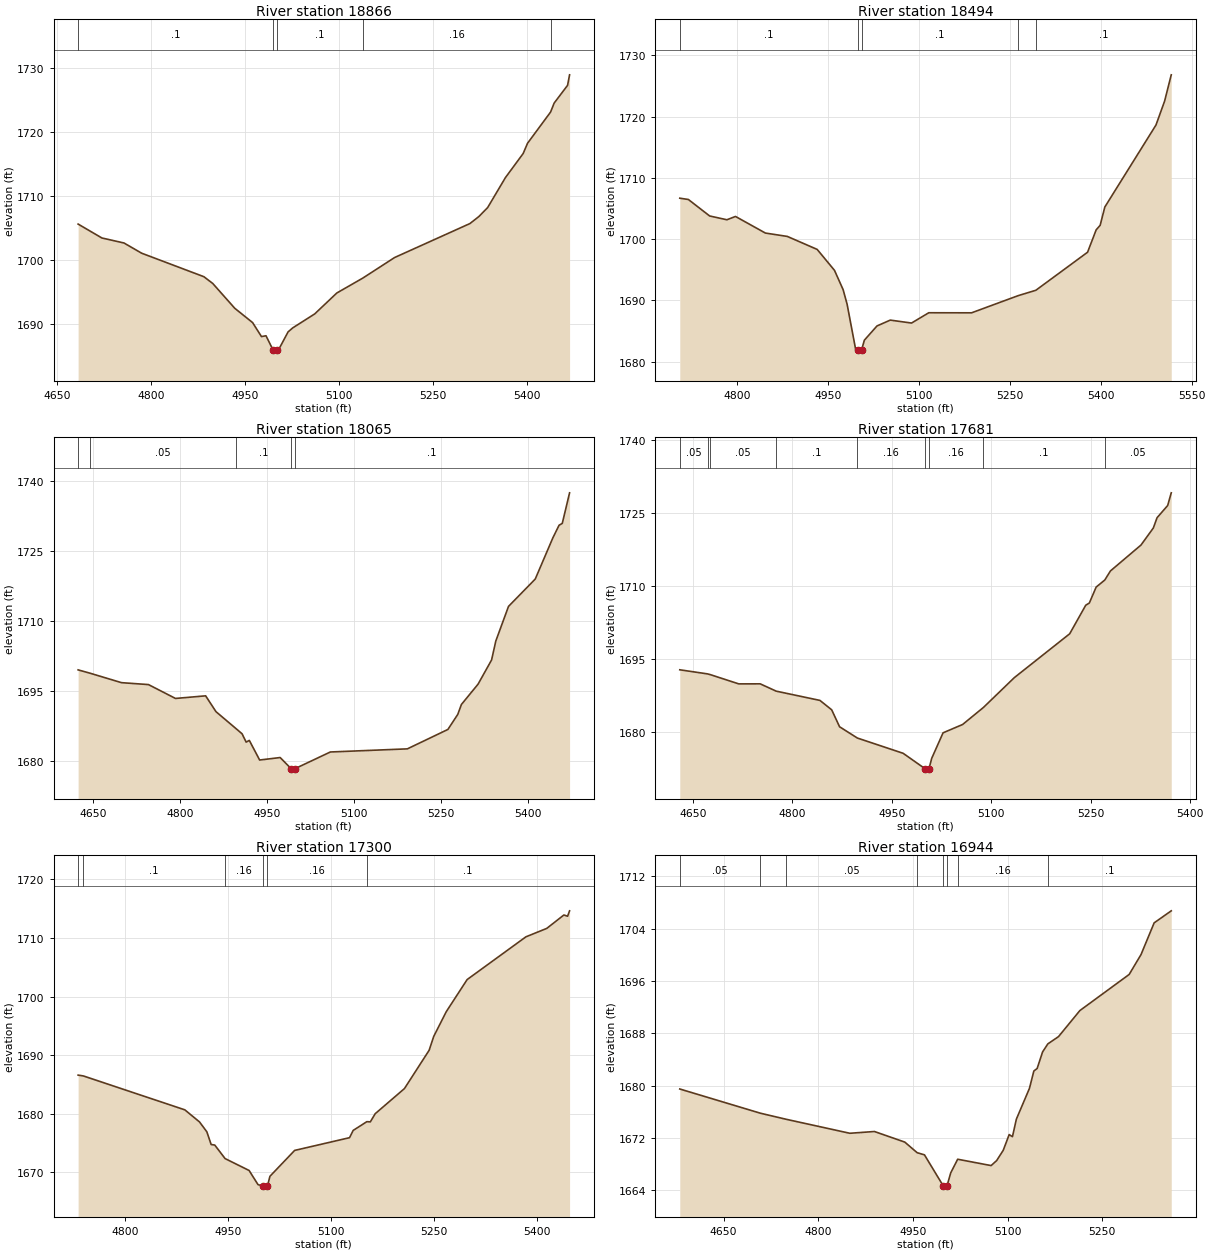
Type RM Length L Ch R = 1 ,18866   ,372,372,372
BEGIN DESCRIPTION:
SNAKE CREEK 36.0
END DESCRIPTION:
XS GIS Cut Line= 2
      2782343.18     10037851.86      2782884.19     10037284.85
#Sta/Elev= 30
    4684 1705.59  4721.9 1703.42  4757.1 1702.64  4785.4 1701.04  4884.5 1697.38
  4898.7 1696.32  4933.9 1692.44  4962.2 1690.22  4976.4 1688.03  4983.6 1688.16
  4994.8 1685.95  4997.5 1685.45  5000.8 1685.95  5004.7 1686.17  5018.8 1688.76
  5026.1 1689.38  5061.3 1691.57  5096.5 1694.83    5138 1697.16  5188.7 1700.37
  5308.8 1705.67    5323 1706.76  5337.1 1708.17  5365.4 1712.84  5393.7  1716.6
  5400.6 1718.19  5437.4 1723.07  5443.1 1724.47  5464.5 1727.24  5467.7 1728.88
#Mann= 5 ,-1 , 0
    4684      .1       0  4994.8     .07       0  5000.8      .1       0
    5138     .16       0  5437.4      .1       0
Bank Sta=4994.8,5000.8
XS Rating Curve= 0 ,0
Exp/Cntr=0.3,0.1

Type RM Length L Ch R = 1 ,18494   ,429,429,429
BEGIN DESCRIPTION:
SNAKE CREEK 35.0
END DESCRIPTION:
XS GIS Cut Line= 2
      2782593.21     10038138.29      2783123.96     10037524.29
#Sta/Elev= 30
  4704.7 1706.69  4718.9 1706.48    4754 1703.79  4782.5 1703.17  4796.7 1703.71
  4846.1    1701  4882.3 1700.45  4931.6 1698.33  4960.2 1694.91  4974.4 1691.77
    4981 1689.39  4995.3 1681.92  4998.9  1681.9  5001.6  1681.4  5004.9  1681.9
  5009.5 1683.51  5030.4 1685.84  5052.3 1686.79  5087.4 1686.31  5115.9 1687.99
  5186.6 1687.98  5263.4 1690.78  5292.7 1691.66  5378.1 1697.87  5392.3 1701.52
  5398.9 1702.27  5406.6 1705.25  5491.1 1718.64  5505.3 1722.53  5516.3 1726.83
#Mann= 5 ,-1 , 0
  4704.7      .1       0  4998.9     .07       0  5004.9      .1       0
  5263.4     .16       0  5292.7      .1       0
Bank Sta=4998.9,5004.9
XS Rating Curve= 0 ,0
Exp/Cntr=0.3,0.1

Type RM Length L Ch R = 1 ,18065   ,384,384,384
BEGIN DESCRIPTION:
SNAKE CREEK 34.0
END DESCRIPTION:
XS GIS Cut Line= 2
       2783025.5     10038362.24       2783368.7     10037587.45
#Sta/Elev= 30
  4624.5 1699.59  4644.2 1698.91  4699.4 1696.85  4745.8 1696.44  4792.4 1693.47
  4844.4 1694.03  4862.2 1690.64  4897.5 1686.93  4907.2  1685.9  4914.2 1684.12
  4919.7 1684.48  4937.5 1680.28  4972.9 1680.81    4992  1678.4  4994.8  1677.9
    4998  1678.4  5059.4    1682  5192.2 1682.67  5262.1 1686.83  5279.1 1690.05
  5285.4 1692.18  5314.1 1696.53  5337.4 1701.71  5344.7 1705.77  5366.6 1713.19
  5412.7 1719.05  5443.2 1727.91  5453.8 1730.58  5459.3 1730.97  5471.9 1737.52
#Mann= 5 ,-1 , 0
  4624.5      .1       0  4644.2     .05       0  4897.5      .1       0
    4992     .07       0    4998      .1       0
Bank Sta=4992,4998
XS Rating Curve= 0 ,0
Exp/Cntr=0.3,0.1

Type RM Length L Ch R = 1 ,17681   ,381,381,381
BEGIN DESCRIPTION:
SNAKE CREEK 33.0
END DESCRIPTION:
XS GIS Cut Line= 2
      2783395.28     10038336.23      2783671.35     10037648.68
#Sta/Elev= 30
  4630.5 1692.77  4672.3 1691.93  4676.7 1691.77  4719.4 1689.88  4751.7 1689.89
  4775.8 1688.39  4841.8 1686.49  4859.5 1684.56  4871.4 1681.08  4898.2 1678.77
  4967.2 1675.64  5000.2 1672.48  5002.9 1671.98  5006.2 1672.48  5010.3 1674.61
  5027.4 1679.84  5056.9 1681.55  5088.3 1685.05  5134.9 1691.17  5218.3 1700.16
  5242.5 1706.02  5247.9 1706.47  5258.2 1709.74  5271.2 1711.19  5279.7 1713.05
  5325.8 1718.37  5344.4 1721.87    5350 1723.97    5366 1726.48  5371.4 1729.08
#Mann= 9 ,-1 , 0
  4630.5     .05       0  4672.3      .1       0  4676.7     .05       0
  4775.8      .1       0  4898.2     .16       0  5000.2     .07       0
  5006.2     .16       0  5088.3      .1       0  5271.2     .05       0
Bank Sta=5000.2,5006.2
XS Rating Curve= 0 ,0
Exp/Cntr=0.3,0.1

Type RM Length L Ch R = 1 ,17300   ,356,356,356
BEGIN DESCRIPTION:
SNAKE CREEK 32.0
END DESCRIPTION:
XS GIS Cut Line= 2
      2783775.51     10038419.51      2784025.31     10037748.18
#Sta/Elev= 30
  4731.9  1686.6  4739.5 1686.46  4887.4 1680.68  4908.8 1678.62  4919.5 1676.94
  4925.8 1674.77  4931.1 1674.67  4946.1 1672.37  4981.1 1670.34  4994.1 1667.93
  5001.8 1667.66  5004.6 1667.16  5007.8 1667.66  5011.5 1669.35  5047.5 1673.76
  5127.5 1675.93  5132.8 1677.17  5152.7 1678.66  5157.8 1678.63  5164.9 1680.02
  5207.5  1684.3  5243.5 1690.83  5250.2  1693.2  5268.5 1697.42  5298.9 1702.89
  5384.6 1710.18  5414.9 1711.61  5439.9  1713.9  5445.3 1713.69  5448.2 1714.61
#Mann= 6 ,-1 , 0
  4731.9     .05       0  4739.5      .1       0  4946.1     .16       0
  5001.8     .07       0  5007.8     .16       0  5152.7      .1       0
Bank Sta=5001.8,5007.8
XS Rating Curve= 0 ,0
Exp/Cntr=0.3,0.1

Type RM Length L Ch R = 1 ,16944   ,563,563,563
BEGIN DESCRIPTION:
SNAKE CREEK 31.0
END DESCRIPTION:
XS GIS Cut Line= 2
      2784327.57      10038596.6      2784114.33     10037847.67
#Sta/Elev= 30
  4580.5 1679.51  4708.1 1675.81  4749.5 1674.87  4849.9 1672.74  4888.9 1673.01
    4937 1671.39  4956.6 1669.77  4968.2 1669.44  4997.9  1664.7  5000.6  1664.2
  5003.9  1664.7  5009.8 1666.69  5020.8 1668.77  5073.8  1667.8  5082.6 1668.57
    5093 1670.14  5102.4 1672.54  5107.6 1672.22  5113.8  1674.9  5134.5  1679.6
  5141.5 1682.26  5146.7 1682.64  5155.3 1685.17  5163.7 1686.41  5180.6 1687.52
  5214.4  1691.5  5292.5 1697.02  5311.3 1700.06  5332.1 1704.91  5359.2 1706.75
#Mann= 8 ,-1 , 0
  4580.5     .05       0  4708.1      .1       0  4749.5     .05       0
  4956.6      .1       0  4997.9     .07       0  5003.9      .1       0
  5020.8     .16       0  5163.7      .1       0
Bank Sta=4997.9,5003.9
XS Rating Curve= 0 ,0
Exp/Cntr=0.3,0.1