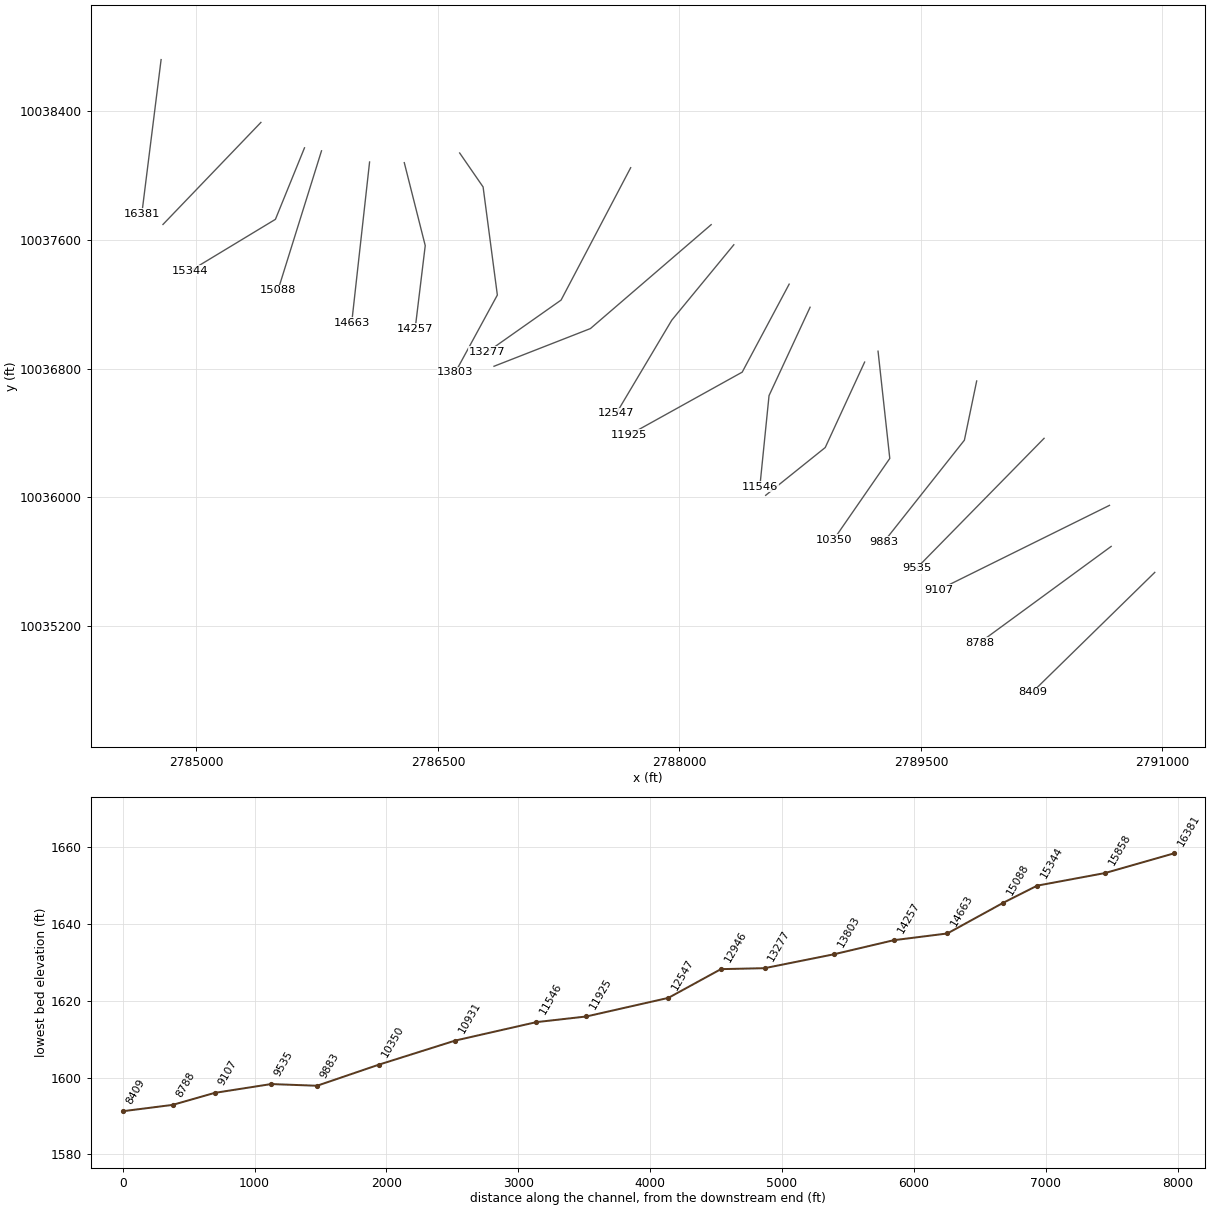
HEC-RAS study SNAKE CREEK.prj: SNAKE CREEK Base Level Engineering

--- SNAKE CREEK.g01 (geometry) --- (continued)

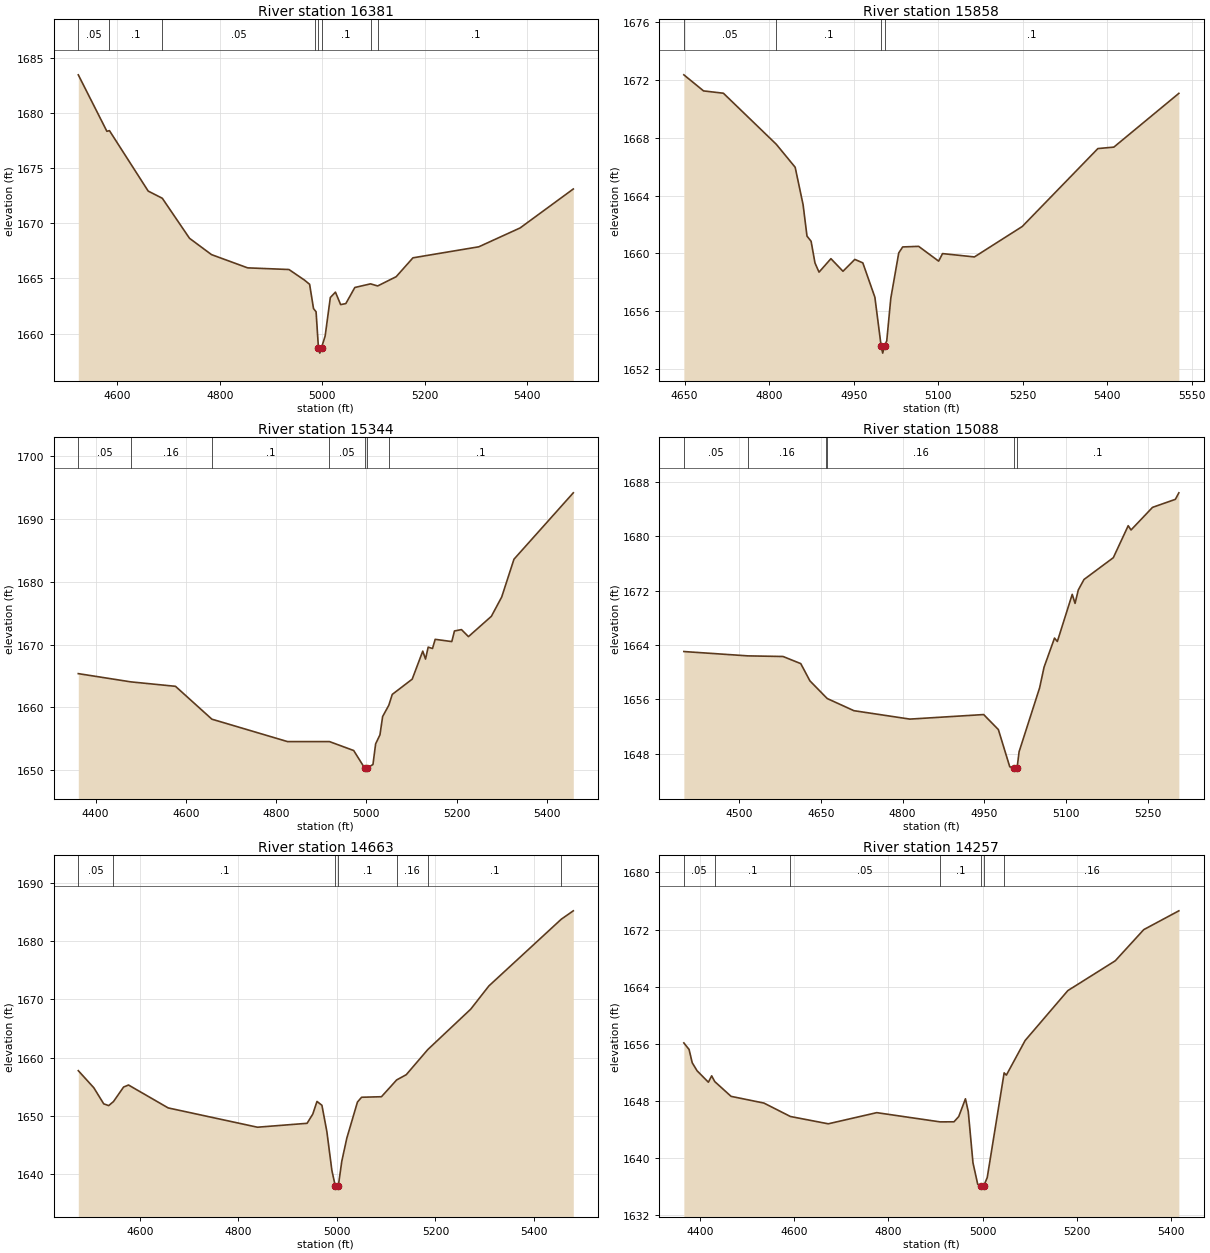
Type RM Length L Ch R = 1 ,16381   ,523,523,523
BEGIN DESCRIPTION:
SNAKE CREEK 30.0
END DESCRIPTION:
XS GIS Cut Line= 2
       2784780.7     10038721.59      2784660.92     10037763.34
#Sta/Elev= 30
  4524.1 1683.46  4579.9 1678.34  4584.9  1678.4  4660.5 1672.92    4688 1672.27
  4741.1 1668.64    4784 1667.16  4854.5 1665.96  4935.1 1665.81  4965.4 1664.85
  4975.4 1664.47    4983 1662.27  4986.1 1662.09    4988 1661.98  4992.6 1658.73
  4995.3 1658.23  4998.6 1658.73  5005.7 1659.78  5015.8 1663.27  5025.8 1663.76
  5035.9 1662.63    5046 1662.72  5063.6 1664.18  5094.2 1664.51  5108.2 1664.32
  5144.3 1665.16    5177 1666.87  5305.5 1667.87  5386.1 1669.58  5489.8 1673.11
#Mann= 8 ,-1 , 0
  4524.1     .05       0  4584.9      .1       0    4688     .05       0
  4986.1      .1       0  4992.6     .07       0  4998.6      .1       0
  5094.2     .16       0  5108.2      .1       0
Bank Sta=4992.6,4998.6
XS Rating Curve= 0 ,0
Exp/Cntr=0.3,0.1

Type RM Length L Ch R = 1 ,15858   ,514,514,514
BEGIN DESCRIPTION:
SNAKE CREEK 29.0
END DESCRIPTION:
XS GIS Cut Line= 2
       2785400.5     10038331.01       2784792.3     10037696.82
#Sta/Elev= 30
  4648.6 1672.33  4683.6 1671.22  4718.8 1671.06  4812.6 1667.54  4846.2 1665.95
  4860.3 1663.36  4867.2  1661.2  4874.5 1660.84  4881.4 1659.34  4888.6 1658.71
  4909.7 1659.64  4931.1 1658.77  4952.1 1659.59  4966.3 1659.35  4987.7 1656.98
  4998.8 1653.62  5001.6 1653.12  5004.8 1653.62  5008.8 1653.97    5016 1656.91
  5030.1 1660.04  5037.1 1660.45  5065.4 1660.49  5100.9 1659.47  5107.8 1659.99
  5164.4 1659.76  5249.3 1661.86  5383.6 1667.24  5411.9 1667.34  5527.3 1671.05
#Mann= 4 ,-1 , 0
  4648.6     .05       0  4812.6      .1       0  4998.8     .07       0
  5004.8      .1       0
Bank Sta=4998.8,5004.8
XS Rating Curve= 0 ,0
Exp/Cntr=0.3,0.1

Type RM Length L Ch R = 1 ,15344   ,256,256,256
BEGIN DESCRIPTION:
SNAKE CREEK 28.0
END DESCRIPTION:
XS GIS Cut Line= 3
      2785671.37     10038173.17      2785490.82     10037728.74
      2784963.24     10037409.41
#Sta/Elev= 30
  4361.8 1665.37    4478 1664.06  4577.1 1663.35  4657.7 1658.12  4825.3 1654.55
  4918.2 1654.55  4971.8 1653.13    4996 1650.35  4998.8 1649.85    5002 1650.35
  5014.5 1650.91  5020.4 1654.19    5030 1655.63  5035.9 1658.54  5049.6 1660.34
  5057.2 1662.06  5101.4 1664.49  5124.8 1668.95  5130.9 1667.69  5136.8 1669.59
  5146.4 1669.37  5152.3 1670.83  5189.1 1670.47    5195 1672.16  5210.5 1672.38
    5226 1671.26  5276.7 1674.49  5299.6 1677.56  5326.8 1683.58  5458.2 1694.15
#Mann= 7 ,-1 , 0
  4361.8     .05       0    4478     .16       0  4657.7      .1       0
  4918.2     .05       0    4996     .04       0    5002     .05       0
  5049.6      .1       0
Bank Sta=4996,5002
XS Rating Curve= 0 ,0
Exp/Cntr=0.3,0.1

Type RM Length L Ch R = 1 ,15088   ,425,425,425
BEGIN DESCRIPTION:
SNAKE CREEK 27.0
END DESCRIPTION:
XS GIS Cut Line= 2
      2785777.02     10038154.52      2785506.55     10037287.63
#Sta/Elev= 30
  4398.6 1663.03  4516.3 1662.39  4580.6  1662.3  4613.1 1661.25  4629.9 1658.71
  4659.9 1656.25  4661.9  1656.1  4710.6 1654.32  4813.3 1653.08  4948.6 1653.75
  4975.6 1651.54  4996.5 1646.06    5004 1645.92  5006.7 1645.42    5010 1645.92
  5013.6 1648.27  5051.3 1657.69  5059.4 1660.72  5078.6 1665.01  5083.8 1664.51
  5111.1 1671.45  5116.3 1670.12  5122.2 1672.09  5132.7 1673.64  5186.5 1676.85
  5213.8 1681.56    5219 1680.93  5258.4 1684.26  5300.3 1685.44  5306.7  1686.4
#Mann= 6 ,-1 , 0
  4398.6     .05       0  4516.3     .16       0  4659.9      .1       0
  4661.9     .16       0    5004     .07       0    5010      .1       0
Bank Sta=5004,5010
XS Rating Curve= 0 ,0
Exp/Cntr=0.3,0.1

Type RM Length L Ch R = 1 ,14663   ,406,406,406
BEGIN DESCRIPTION:
SNAKE CREEK 26.0
END DESCRIPTION:
XS GIS Cut Line= 2
      2786075.63     10038085.05      2785964.72      10037086.9
#Sta/Elev= 30
  4475.3 1657.75  4506.8 1654.82  4526.9 1652.06    4537 1651.76  4546.7 1652.45
  4567.2 1654.94  4577.2 1655.29  4657.7 1651.36  4838.8 1648.05  4939.5 1648.72
  4951.1 1650.31  4959.6 1652.47  4969.6 1651.81  4979.7 1647.27  4989.8 1640.64
  4996.8 1637.93  4999.6 1637.43  5002.8 1637.93  5009.9  1642.2    5020 1646.14
  5041.7 1652.37  5050.1 1653.19  5090.4 1653.28  5121.2 1656.16  5140.7 1657.06
  5184.4 1661.37  5271.5  1668.3  5308.3 1672.28  5455.2 1683.73  5479.6 1685.17
#Mann= 7 ,-1 , 0
  4475.3     .05       0  4546.7      .1       0  4996.8     .07       0
  5002.8      .1       0  5121.2     .16       0  5184.4      .1       0
  5455.2     .05       0
Bank Sta=4996.8,5002.8
XS Rating Curve= 0 ,0
Exp/Cntr=0.3,0.1

Type RM Length L Ch R = 1 ,14257   ,454,454,454
BEGIN DESCRIPTION:
SNAKE CREEK 25.0
END DESCRIPTION:
XS GIS Cut Line= 3
      2786291.13     10038080.99      2786421.33     10037565.38
      2786358.83     10037049.75
#Sta/Elev= 30
  4365.7 1656.14  4376.8 1655.22  4383.5 1653.36  4393.8 1652.24  4417.8 1650.64
  4424.8 1651.53  4431.3 1650.73    4466 1648.66  4535.8 1647.72  4592.1 1645.84
  4672.3 1644.82  4775.4 1646.38  4909.8 1645.09  4939.4  1645.1  4949.5 1645.84
  4963.7 1648.32  4969.7 1646.53  4979.7 1639.37  4989.8 1636.35  4996.9 1636.18
  4999.6 1635.68  5002.9 1636.18    5010  1637.3  5045.9 1651.95  5050.6 1651.63
  5090.5 1656.48  5181.2 1663.46  5281.9 1667.63  5342.4 1671.99  5416.9 1674.62
#Mann= 7 ,-1 , 0
  4365.7     .05       0  4431.3      .1       0  4592.1     .05       0
  4909.8      .1       0  4996.9     .07       0  5002.9      .1       0
  5045.9     .16       0
Bank Sta=4996.9,5002.9
XS Rating Curve= 0 ,0
Exp/Cntr=0.3,0.1

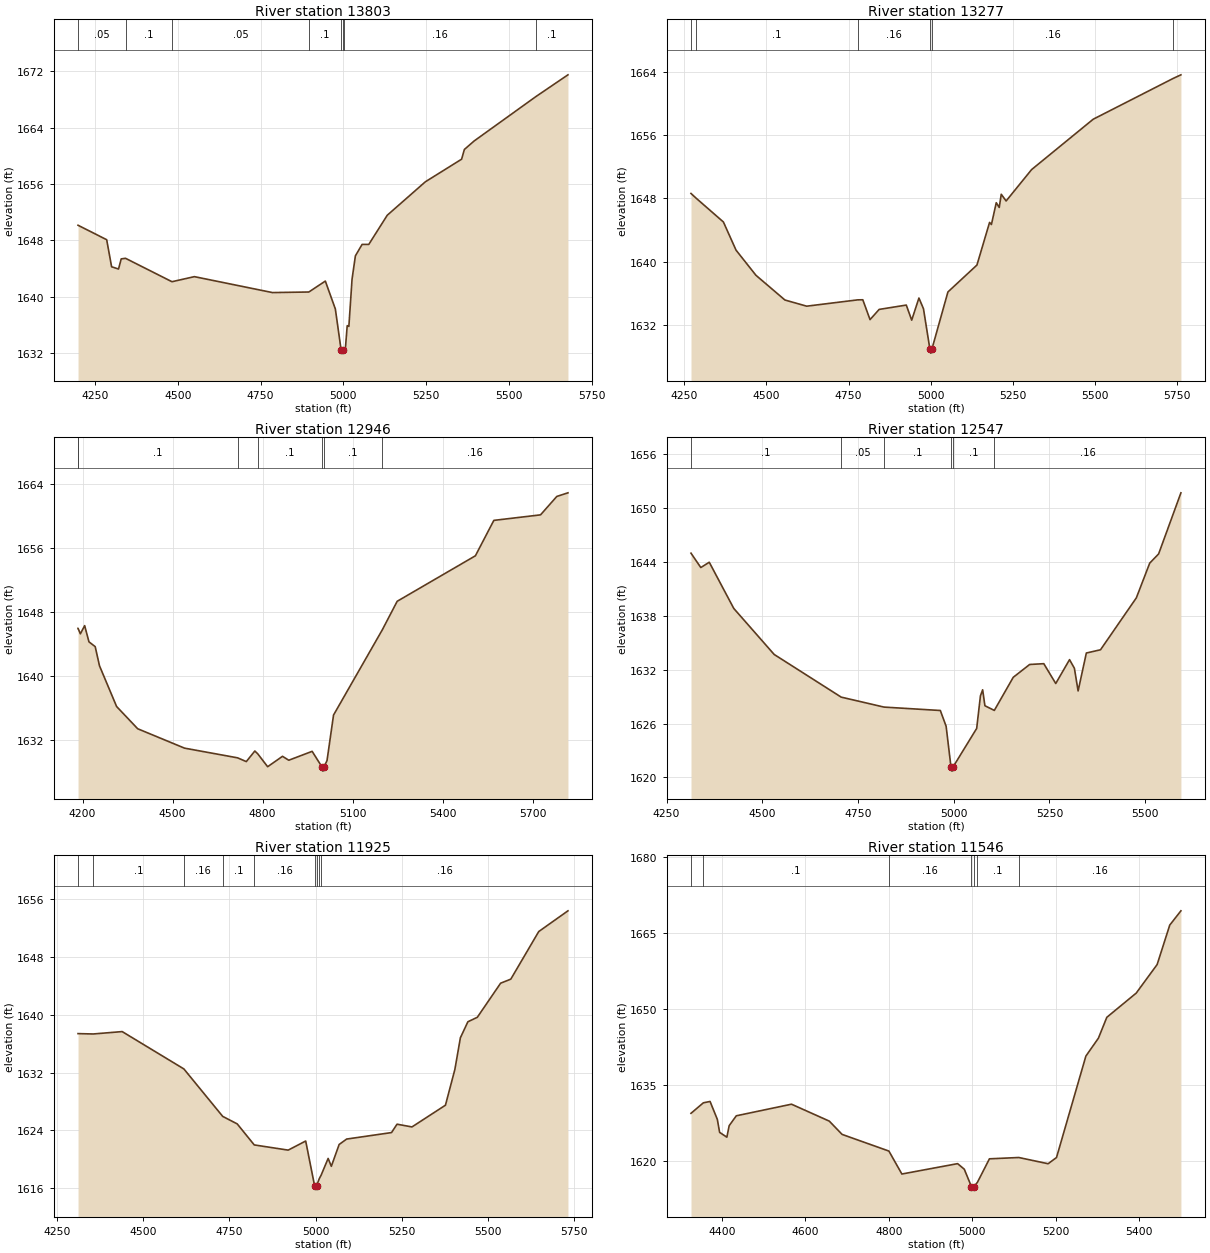
Type RM Length L Ch R = 1 ,13803   ,526,526,526
BEGIN DESCRIPTION:
SNAKE CREEK 24.0
END DESCRIPTION:
XS GIS Cut Line= 4
      2786635.17     10038141.07      2786780.71     10037929.97
      2786869.25     10037258.09      2786608.81     10036778.89
#Sta/Elev= 30
  4198.8 1650.16  4285.3 1648.11  4300.2 1644.27  4321.1 1643.95  4329.2 1645.39
  4342.3 1645.47  4482.5 1642.15  4550.1 1642.87  4785.9 1640.61  4895.8 1640.69
  4945.6 1642.24  4975.9 1638.28  4993.1 1632.52  4995.8 1632.02  4999.1 1632.52
  5002.9  1632.6  5006.2 1632.67  5011.7 1635.92  5016.7 1635.81  5026.3 1642.52
  5036.4 1645.82  5056.6 1647.44  5076.8 1647.44  5132.6 1651.58  5247.8 1656.33
  5357.1 1659.53  5365.5 1660.91  5395.1 1662.12  5581.1  1668.4  5678.3  1671.5
#Mann= 8 ,-1 , 0
  4198.8     .05       0  4342.3      .1       0  4482.5     .05       0
  4895.8      .1       0  4993.1     .07       0  4999.1      .1       0
  5002.9     .16       0  5581.1      .1       0
Bank Sta=4993.1,4999.1
XS Rating Curve= 0 ,0
Exp/Cntr=0.3,0.1

Type RM Length L Ch R = 1 ,13277   ,331,331,331
BEGIN DESCRIPTION:
SNAKE CREEK 23.0
END DESCRIPTION:
XS GIS Cut Line= 3
      2787697.36     10038049.74      2787265.08     10037226.84
      2786806.75     10036903.93
#Sta/Elev= 30
  4270.9 1648.61  4286.3 1648.02  4369.5    1645  4407.9 1641.44  4468.4 1638.26
  4556.6 1635.13  4622.8 1634.35  4778.2 1635.15  4793.5 1635.16  4815.5 1632.65
  4843.2 1633.94  4925.8 1634.49  4942.2 1632.58  4964.2 1635.38    4978 1634.03
  4997.6 1628.91  5000.4 1628.41  5003.6 1628.91  5052.4 1636.15  5140.6 1639.55
  5179.1 1644.95  5184.7 1644.68  5199.4 1647.44  5208.5 1646.84  5214.6 1648.51
  5229.4 1647.66  5306.9 1651.63  5494.2    1658  5736.9 1663.15  5761.1 1663.62
#Mann= 6 ,-1 , 0
  4270.9     .05       0  4286.3      .1       0  4778.2     .16       0
  4997.6     .07       0  5003.6     .16       0  5736.9      .1       0
Bank Sta=4997.6,5003.6
XS Rating Curve= 0 ,0
Exp/Cntr=0.3,0.1

Type RM Length L Ch R = 1 ,12946   ,399,399,399
BEGIN DESCRIPTION:
SNAKE CREEK 22.0
END DESCRIPTION:
XS GIS Cut Line= 3
      2788197.37     10037695.59      2787447.37     10037049.76
      2786848.44     10036815.39
#Sta/Elev= 30
  4185.1 1645.98  4185.2 1645.98  4192.9  1645.3  4207.2 1646.32  4221.5  1644.3
  4242.3  1643.7  4256.6 1641.31  4313.6 1636.23  4383.9 1633.45    4540 1631.03
  4716.8 1629.82  4745.9 1629.35  4774.4 1630.67  4784.1 1630.32  4817.1 1628.71
  4866.6 1630.01  4887.5 1629.52  4965.4 1630.63  4998.5 1628.66  5001.3 1628.16
  5004.5 1628.66    5015 1629.48  5036.7 1635.16  5199.7 1645.83  5248.8 1649.36
  5509.5 1655.04    5571 1659.46  5726.6 1660.15  5780.9 1662.45    5818  1662.9
#Mann= 7 ,-1 , 0
  4185.1     .05       0  4185.2      .1       0  4716.8     .05       0
  4784.1      .1       0  4998.5     .07       0  5004.5      .1       0
  5199.7     .16       0
Bank Sta=4998.5,5004.5
XS Rating Curve= 0 ,0
Exp/Cntr=0.3,0.1

Type RM Length L Ch R = 1 ,12547   ,622,622,622
BEGIN DESCRIPTION:
SNAKE CREEK 21.0
END DESCRIPTION:
XS GIS Cut Line= 3
      2788338.01     10037570.61      2787952.58     10037101.84
      2787608.82      10036523.7
#Sta/Elev= 30
  4313.8 1644.99  4339.4 1643.39  4361.5 1643.98  4425.5 1638.83    4531  1633.7
  4706.1 1628.94  4817.9 1627.83    4965 1627.45  4980.1 1625.69  4992.7 1621.19
  4995.4 1620.69  4998.7 1621.19  5059.9 1625.45  5069.7 1629.08  5075.5 1629.76
  5081.4 1627.98    5106 1627.46  5155.4 1631.15  5198.2 1632.58  5235.2 1632.67
  5266.4 1630.46  5302.4 1633.12  5315.1 1632.16  5324.8 1629.63  5346.3 1633.86
  5383.3 1634.22  5476.9 1640.01  5511.8 1643.88  5535.1 1644.91  5593.3 1651.72
#Mann= 6 ,-1 , 0
  4313.8      .1       0  4706.1     .05       0  4817.9      .1       0
  4992.7     .07       0  4998.7      .1       0    5106     .16       0
Bank Sta=4992.7,4998.7
XS Rating Curve= 0 ,0
Exp/Cntr=0.3,0.1

Type RM Length L Ch R = 1 ,11925   ,379,379,379
BEGIN DESCRIPTION:
SNAKE CREEK 20.0
END DESCRIPTION:
XS GIS Cut Line= 3
      2788681.77     10037325.84      2788390.08     10036778.92
      2787687.38     10036388.54
#Sta/Elev= 30
  4309.9 1637.39  4353.9 1637.34  4438.2 1637.67  4617.5  1632.5  4730.3 1625.93
  4772.5 1624.89    4822 1621.98  4920.6 1621.26  4971.5 1622.52  4997.2 1616.36
    5000 1615.86  5003.2 1616.36  5011.3 1617.34  5016.4  1617.8  5036.7 1620.11
    5046 1619.02  5068.7 1622.04  5090.4 1622.79  5220.9 1623.69  5236.9 1624.85
  5280.3 1624.47  5377.6 1627.48    5405 1632.43    5421 1636.81  5442.8 1639.03
  5470.2 1639.65  5537.9 1644.37  5567.5 1644.93  5648.7 1651.52  5733.6 1654.39
#Mann= 9 ,-1 , 0
  4309.9     .05       0  4353.9      .1       0  4617.5     .16       0
  4730.3      .1       0    4822     .16       0  4997.2     .07       0
  5003.2     .16       0  5011.3      .1       0  5016.4     .16       0
Bank Sta=4997.2,5003.2
XS Rating Curve= 0 ,0
Exp/Cntr=0.3,0.1

Type RM Length L Ch R = 1 ,11546   ,615,615,615
BEGIN DESCRIPTION:
SNAKE CREEK 19.0
END DESCRIPTION:
XS GIS Cut Line= 3
      2788811.73     10037182.26      2788556.75     10036633.09
      2788499.62     10036067.04
#Sta/Elev= 30
  4325.7 1629.35  4355.3 1631.42  4371.4 1631.69  4388.8 1628.16  4394.3 1625.59
  4411.7 1624.64  4417.2 1626.91  4434.3 1628.86  4566.6 1631.15  4657.2 1627.81
  4687.9 1625.19  4800.1  1621.9  4831.2 1617.37  4964.8 1619.42  4980.8 1618.32
  4997.9 1614.89  5000.6 1614.39  5003.9 1614.89  5012.2 1615.72  5041.1 1620.37
  5111.5 1620.63  5181.8  1619.4  5201.9 1620.63  5272.3 1640.65  5302.4 1644.19
  5322.5  1648.3  5392.9 1653.07  5443.1 1658.71  5473.3 1666.49  5500.1 1669.31
#Mann= 7 ,-1 , 0
  4325.7     .05       0  4355.3      .1       0  4800.1     .16       0
  4997.9     .07       0  5003.9     .16       0  5012.2      .1       0
  5111.5     .16       0
Bank Sta=4997.9,5003.9
XS Rating Curve= 0 ,0
Exp/Cntr=0.3,0.1

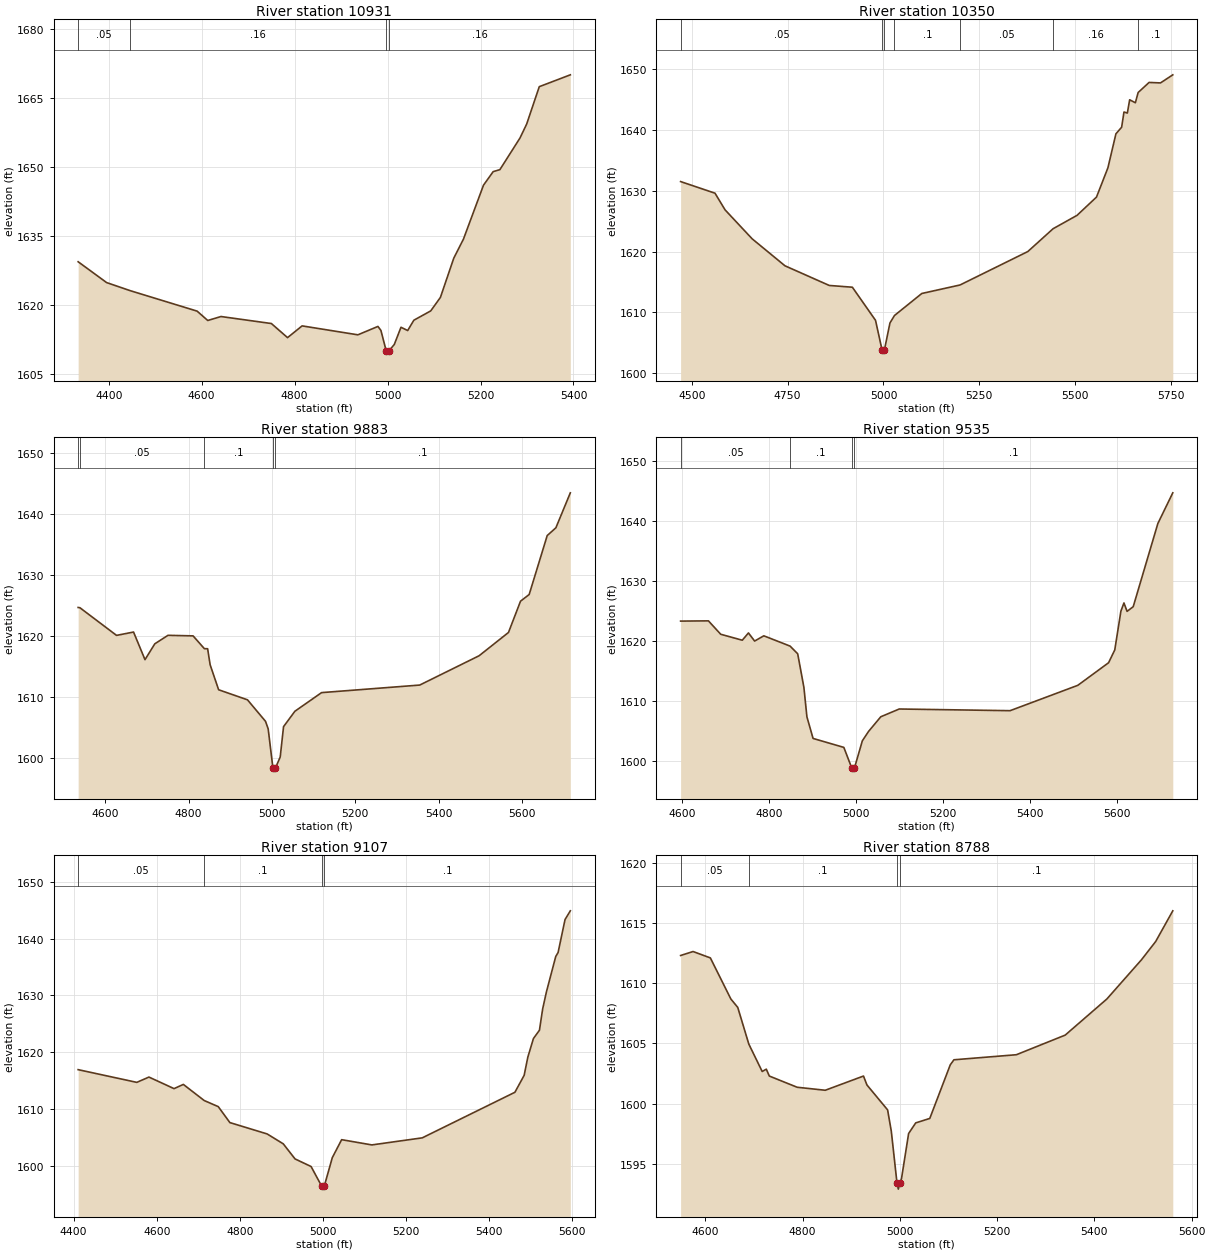
Type RM Length L Ch R = 1 ,10931   ,581,581,581
BEGIN DESCRIPTION:
SNAKE CREEK 18.0
END DESCRIPTION:
XS GIS Cut Line= 3
      2789150.48      10036841.4      2788905.71     10036310.17
      2788535.93     10036013.31
#Sta/Elev= 30
  4334.2 1629.42  4395.5  1624.9  4446.5 1623.14  4590.2 1618.71  4613.1 1616.68
  4641.6 1617.54    4750 1616.02  4784.8 1612.96  4816.1 1615.51  4936.1 1613.57
  4979.3 1615.39  4985.7 1614.53  4997.1  1610.1  4999.8  1609.6  5003.1  1610.1
  5014.5 1611.48  5028.9 1615.21  5043.3  1614.5  5056.6 1616.74  5092.9 1618.76
  5113.7 1621.68  5142.5  1630.2  5163.3 1634.33  5206.5 1646.04  5227.3 1648.97
  5241.7  1649.4  5284.9 1656.25  5299.3 1659.28  5326.5  1667.4  5393.3 1669.97
#Mann= 4 ,-1 , 0
  4334.2     .05       0  4446.5     .16       0  4997.1     .07       0
  5003.1     .16       0
Bank Sta=4997.1,5003.1
XS Rating Curve= 0 ,0
Exp/Cntr=0.3,0.1

Type RM Length L Ch R = 1 ,10350   ,467,467,467
BEGIN DESCRIPTION:
SNAKE CREEK 17.0
END DESCRIPTION:
XS GIS Cut Line= 3
      2789233.84     10036909.09      2789306.75     10036242.47
       2788958.3       10035738.
#Sta/Elev= 30
  4470.9 1631.51  4560.6  1629.6  4586.9 1626.86  4657.4 1622.11  4743.1 1617.67
  4858.6 1614.44  4918.9 1614.15  4979.3 1608.71  4996.4 1603.82  4999.1 1603.32
  5002.4 1603.82  5016.9 1608.27  5028.7  1609.5    5100 1613.12  5199.8 1614.52
  5376.5 1620.01  5442.4 1623.76  5504.9 1625.96  5555.6 1628.96  5585.4 1633.77
  5606.3 1639.36  5621.2 1640.44  5627.3 1642.94  5636.1 1642.77  5642.1 1644.95
    5657 1644.46  5664.2 1646.14  5692.8  1647.8  5722.6 1647.72  5754.6 1649.05
#Mann= 7 ,-1 , 0
  4470.9     .05       0  4996.4     .04       0  5002.4     .05       0
  5028.7      .1       0  5199.8     .05       0  5442.4     .16       0
  5664.2      .1       0
Bank Sta=4996.4,5002.4
XS Rating Curve= 0 ,0
Exp/Cntr=0.3,0.1

Type RM Length L Ch R = 1 ,9883    ,348,348,348
BEGIN DESCRIPTION:
SNAKE CREEK 16.0
END DESCRIPTION:
XS GIS Cut Line= 3
      2789846.47     10036723.98      2789770.07     10036355.88
      2789270.05     10035723.91
#Sta/Elev= 30
  4534.7 1624.71  4538.9 1624.67  4626.9 1620.13  4667.7 1620.68  4695.2 1616.15
  4718.8 1618.75  4750.4 1620.14  4810.7 1620.05  4837.8 1617.95  4845.6 1617.94
  4851.6 1615.32    4872 1611.21  4941.3 1609.56  4984.6 1606.03    4991 1604.79
  5002.4 1598.36  5005.2 1597.86  5008.4 1598.36  5019.9 1600.18  5027.9 1605.16
  5055.1 1607.68  5119.2 1610.74  5354.9 1611.98  5497.5 1616.79    5568 1620.61
  5596.9 1625.74  5617.7 1626.84    5661 1636.51  5681.8 1637.78  5716.5 1643.52
#Mann= 5 ,-1 , 0
  4534.7      .1       0  4538.9     .05       0  4837.8      .1       0
  5002.4     .07       0  5008.4      .1       0
Bank Sta=5002.4,5008.4
XS Rating Curve= 0 ,0
Exp/Cntr=0.3,0.1

Type RM Length L Ch R = 1 ,9535    ,428,428,428
BEGIN DESCRIPTION:
SNAKE CREEK 15.0
END DESCRIPTION:
XS GIS Cut Line= 2
      2790265.09     10036367.48      2789473.42     10035560.18
#Sta/Elev= 30
  4597.2 1623.27  4661.1 1623.31  4689.4 1621.08  4738.9 1620.09  4753.1  1621.3
  4767.2 1619.95  4788.4 1620.82  4848.7 1619.11  4866.2 1617.83  4880.4 1612.26
  4887.4 1607.33  4901.5 1603.74  4972.2 1602.25  4990.5  1598.8  4993.3  1598.3
  4996.5  1598.8  5014.7 1603.34  5028.8 1604.89  5057.1 1607.35  5099.5 1608.64
  5354.1 1608.36  5509.7 1612.58  5580.4 1616.34  5594.6 1618.47  5608.7 1624.92
  5615.7 1626.29  5622.9 1624.89    5637 1625.67  5693.6 1639.51  5727.9 1644.62
#Mann= 4 ,-1 , 0
  4597.2     .05       0  4848.7      .1       0  4990.5     .07       0
  4996.5      .1       0
Bank Sta=4990.5,4996.5
XS Rating Curve= 0 ,0
Exp/Cntr=0.3,0.1

Type RM Length L Ch R = 1 ,9107    ,319,319,319
BEGIN DESCRIPTION:
SNAKE CREEK 14.0
END DESCRIPTION:
XS GIS Cut Line= 2
      2790671.31     10035950.79       2789608.8     10035424.74
#Sta/Elev= 30
  4410.8 1616.98  4552.1 1614.75  4581.3 1615.68  4641.8 1613.65  4664.2 1614.39
  4714.5 1611.56  4748.3 1610.49  4776.3 1607.69    4866  1605.7  4904.9 1603.96
  4933.3 1601.31  4971.9 1599.98  4997.6 1596.51  5000.4 1596.01  5003.6 1596.51
    5023 1601.53  5045.5 1604.69  5118.3 1603.77  5239.7 1605.01  5462.9 1613.01
  5485.2 1615.99    5494 1619.17  5507.5 1622.44    5522  1623.9  5529.8 1627.66
  5538.9 1630.66  5561.3 1636.85  5566.9 1637.54  5583.7 1643.34  5596.4 1644.86
#Mann= 4 ,-1 , 0
  4410.8     .05       0  4714.5      .1       0  4997.6     .07       0
  5003.6      .1       0
Bank Sta=4997.6,5003.6
XS Rating Curve= 0 ,0
Exp/Cntr=0.3,0.1

Type RM Length L Ch R = 1 ,8788    ,379,379,379
BEGIN DESCRIPTION:
SNAKE CREEK 13.0
END DESCRIPTION:
XS GIS Cut Line= 2
      2790681.78     10035695.62      2789865.45     10035097.67
#Sta/Elev= 30
  4549.3 1612.29  4574.9 1612.62  4610.5 1612.09  4652.6 1608.68  4666.8 1607.98
  4689.5 1604.94    4717 1602.66  4725.5 1602.85  4731.7 1602.28  4788.9 1601.35
  4846.7  1601.1  4925.3 1602.28  4932.4 1601.54  4974.9 1599.47  4982.5  1597.7
  4994.2 1593.39  4996.9 1592.89  5000.2 1593.39  5003.4 1593.75  5018.1 1597.51
  5032.7 1598.39  5061.6 1598.76  5103.7 1603.21  5111.2 1603.63  5239.6 1604.05
    5340 1605.68  5425.7 1608.68  5496.7 1611.93    5526 1613.45  5561.2    1616
#Mann= 4 ,-1 , 0
  4549.3     .05       0  4689.5      .1       0  4994.2     .07       0
  5000.2      .1       0
Bank Sta=4994.2,5000.2
XS Rating Curve= 0 ,0
Exp/Cntr=0.3,0.1

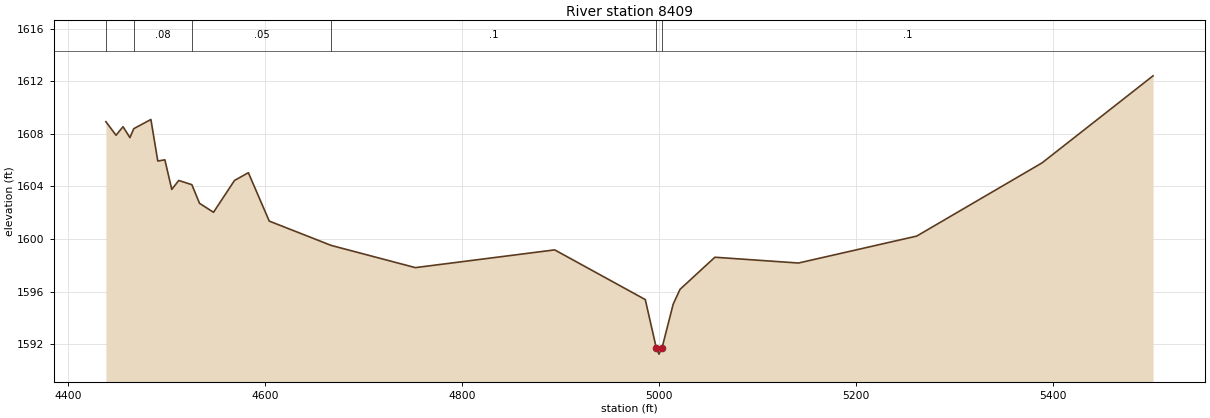
Type RM Length L Ch R = 1 ,8409    ,388,388,388
BEGIN DESCRIPTION:
SNAKE CREEK 12.0
END DESCRIPTION:
XS GIS Cut Line= 2
      2790952.61     10035534.16      2790192.83       10034790.
#Sta/Elev= 30
  4438.2 1608.92  4448.5 1607.89  4455.6 1608.54  4462.6 1607.71  4466.5 1608.39
  4483.9 1609.09  4490.9 1605.93  4498.1 1606.02  4505.1 1603.77  4512.2 1604.45
  4525.5 1604.13  4533.3 1602.71  4547.5 1602.03  4568.8 1604.45  4582.9 1605.04
  4604.1 1601.36    4667 1599.51  4752.5 1597.82    4894 1599.17    4986 1595.39
  4997.1 1591.74  4999.9 1591.24  5003.1 1591.74  5014.3 1595.03  5021.3 1596.17
  5056.7 1598.61  5141.6 1598.17  5261.7 1600.22    5389 1605.79  5501.7 1612.41
#Mann= 6 ,-1 , 0
  4438.2      .1       0  4466.5     .08       0  4525.5     .05       0
    4667      .1       0  4997.1     .07       0  5003.1      .1       0
Bank Sta=4997.1,5003.1
XS Rating Curve= 0 ,0
Exp/Cntr=0.3,0.1