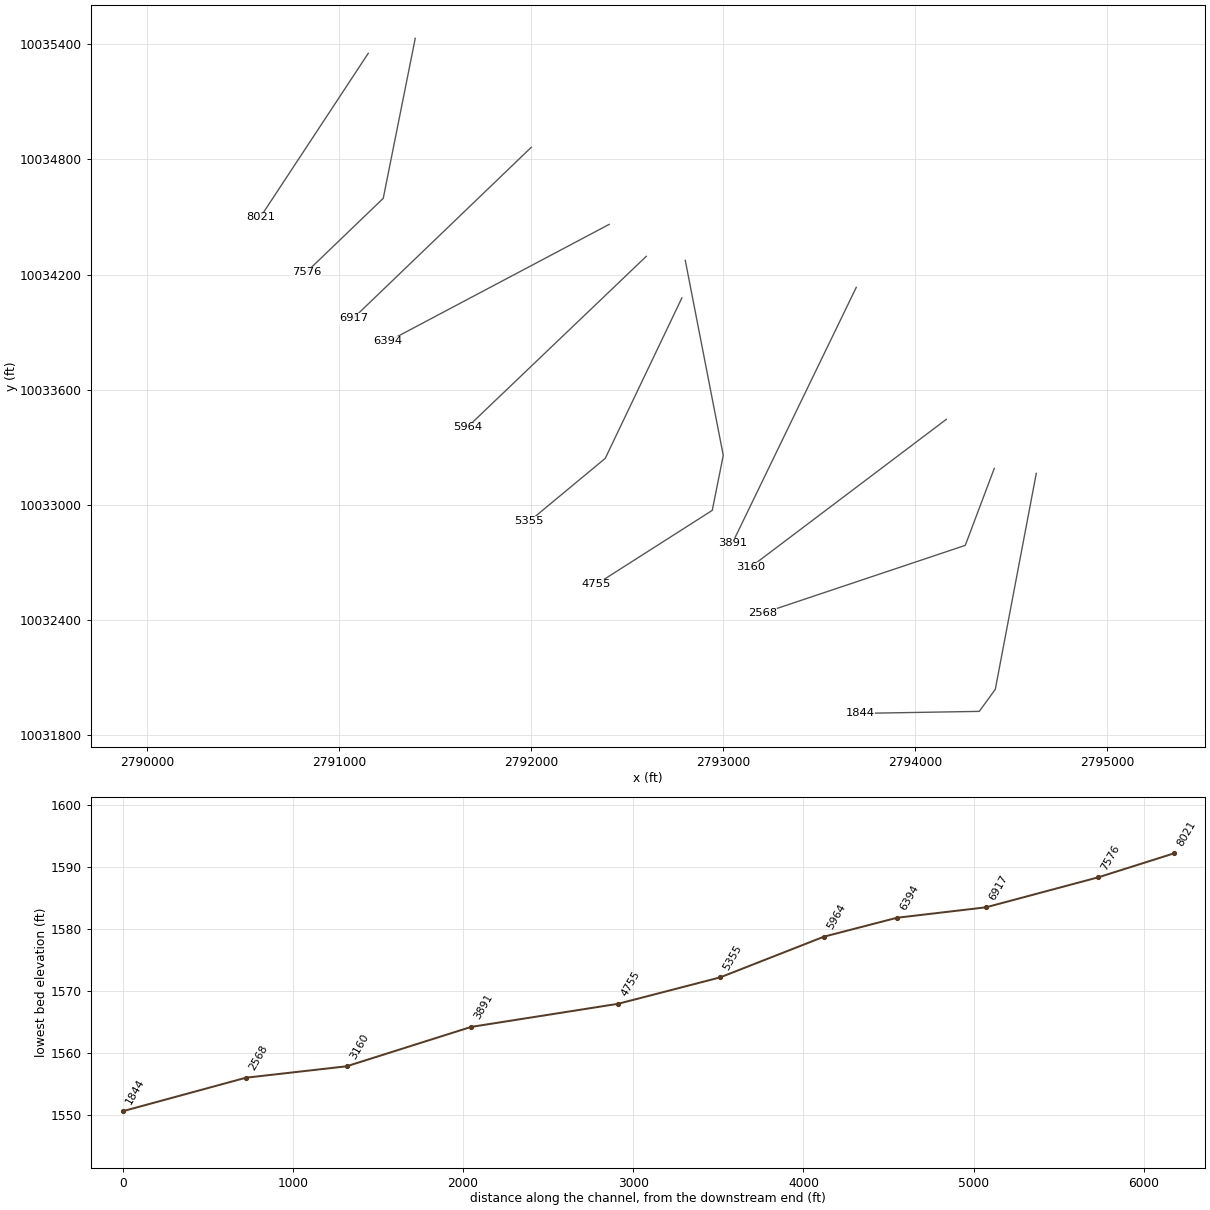
HEC-RAS study SNAKE CREEK.prj: SNAKE CREEK Base Level Engineering

--- SNAKE CREEK.g01 (geometry) --- (continued)

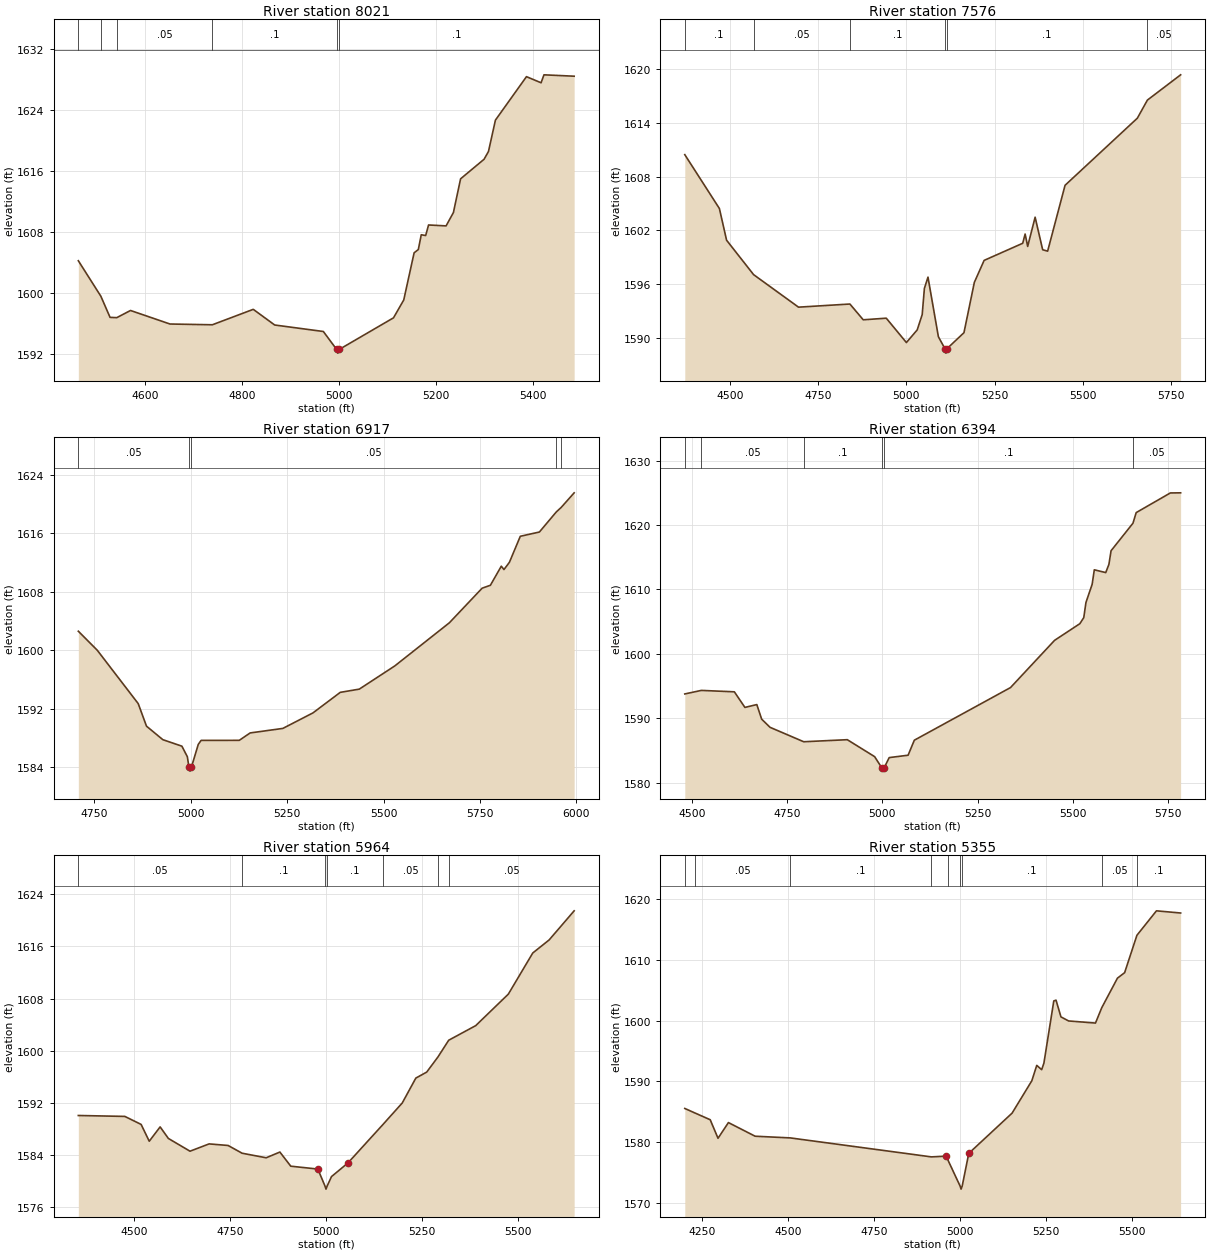
Type RM Length L Ch R = 1 ,8021    ,445,445,445
BEGIN DESCRIPTION:
SNAKE CREEK 11.0
END DESCRIPTION:
XS GIS Cut Line= 2
      2791150.48     10035351.81      2790588.33     10034498.19
#Sta/Elev= 30
  4462.4 1604.24  4508.8  1599.6  4527.8 1596.83  4541.6 1596.79    4570 1597.73
  4651.3 1595.96  4738.7 1595.86    4823 1597.88  4867.2 1595.83  4967.5 1594.98
  4994.7 1592.65  4997.4 1592.15  5000.7 1592.65  5112.1 1596.77  5133.2  1599.1
  5154.6 1605.28  5163.3 1605.71  5169.3 1607.64  5178.4 1607.54  5184.4 1608.92
  5220.5  1608.8  5235.6 1610.55  5250.4 1614.96  5298.8 1617.52  5307.9 1618.54
  5322.2 1622.64  5386.2 1628.33  5416.3 1627.53  5422.3 1628.57  5484.5 1628.39
#Mann= 6 ,-1 , 0
  4462.4      .1       0  4508.8     .08       0  4541.6     .05       0
  4738.7      .1       0  4994.7     .07       0  5000.7      .1       0
Bank Sta=4994.7,5000.7
XS Rating Curve= 0 ,0
Exp/Cntr=0.3,0.1

Type RM Length L Ch R = 1 ,7576    ,659,659,659
BEGIN DESCRIPTION:
SNAKE CREEK 10.0
END DESCRIPTION:
XS GIS Cut Line= 3
      2791395.29     10035429.95      2791228.62     10034596.63
      2790827.61     10034211.24
#Sta/Elev= 30
  4371.6 1610.45  4469.7 1604.44  4490.1  1600.9  4566.7 1597.06  4694.1 1593.43
  4839.8 1593.78  4877.6 1592.02  4942.9  1592.2    5000 1589.48  5030.6 1590.89
  5044.8  1592.6    5051 1595.52  5061.2 1596.78  5090.7 1590.13  5109.2  1588.8
    5112  1588.3  5115.2  1588.8  5163.2 1590.58  5192.7  1596.2  5220.4 1598.65
  5329.8 1600.56  5336.7 1601.59  5343.9 1600.21    5365 1603.47  5386.4 1599.84
  5400.5 1599.68  5449.9 1607.03  5654.9 1614.52  5683.4 1616.54  5777.6 1619.36
#Mann= 6 ,-1 , 0
  4371.6      .1       0  4566.7     .05       0  4839.8      .1       0
  5109.2     .07       0  5115.2      .1       0  5683.4     .05       0
Bank Sta=5109.2,5115.2
XS Rating Curve= 0 ,0
Exp/Cntr=0.3,0.1

Type RM Length L Ch R = 1 ,6917    ,523,523,523
BEGIN DESCRIPTION:
SNAKE CREEK 9.0
END DESCRIPTION:
XS GIS Cut Line= 2
      2791999.49     10034862.29      2791072.89     10033972.13
#Sta/Elev= 30
  4709.1 1602.61  4758.3    1600  4864.3 1592.71  4885.7 1589.63  4928.1 1587.78
  4977.5 1586.89  4991.6 1585.45  4995.9 1583.98  4998.6 1583.48  5001.9 1583.98
  5019.9 1587.13  5027.2 1587.68  5126.2 1587.69  5154.3  1588.7  5239.1 1589.32
  5317.1 1591.44  5387.9 1594.25  5437.2 1594.69  5529.1 1597.86  5670.6 1603.76
  5755.5 1608.49  5776.9 1608.89  5805.2  1611.5  5812.1 1611.04  5826.2 1612.03
  5854.5 1615.59  5903.9 1616.17  5947.6 1618.91  5960.7 1619.55    5994 1621.53
#Mann= 5 ,-1 , 0
  4709.1     .05       0  4995.9     .07       0  5001.9     .05       0
  5947.6     .05       0  5960.7      .1       0
Bank Sta=4995.9,5001.9
XS Rating Curve= 0 ,0
Exp/Cntr=0.3,0.1

Type RM Length L Ch R = 1 ,6394    ,430,430,430
BEGIN DESCRIPTION:
SNAKE CREEK 8.0
END DESCRIPTION:
XS GIS Cut Line= 2
      2792405.67      10034461.2      2791254.63     10033851.82
#Sta/Elev= 30
  4481.1 1593.78  4524.4 1594.33  4611.3 1594.11    4639 1591.69  4670.3 1592.13
    4683 1589.87    4705  1588.6  4793.5 1586.36  4907.9 1586.68  4979.7 1584.05
  4998.7  1582.3  5001.4  1581.8  5004.7  1582.3    5018  1583.9  5067.7 1584.27
    5084  1586.6  5336.7 1594.77  5452.4  1602.1  5518.9 1604.69  5529.1 1605.63
  5534.8 1607.97  5551.1  1610.8  5556.8 1613.05  5586.8 1612.62  5595.1 1613.89
  5600.8 1616.01  5658.3 1620.28  5666.8 1621.93  5756.5 1624.98  5783.5    1625
#Mann= 6 ,-1 , 0
  4481.1      .1       0  4524.4     .05       0  4793.5      .1       0
  4998.7     .07       0  5004.7      .1       0  5658.3     .05       0
Bank Sta=4998.7,5004.7
XS Rating Curve= 0 ,0
Exp/Cntr=0.3,0.1

Type RM Length L Ch R = 1 ,5964    ,609,609,609
BEGIN DESCRIPTION:
SNAKE CREEK 7.0
END DESCRIPTION:
XS GIS Cut Line= 2
      2792598.41     10034294.55      2791666.15     10033403.95
#Sta/Elev= 30
  4355.6 1590.05  4476.5 1589.91  4518.9 1588.68    4540  1586.1  4568.3  1588.3
  4589.7 1586.53    4646 1584.57  4695.7 1585.69    4745 1585.45  4781.5 1584.26
  4844.1 1583.56  4879.7 1584.44    4908 1582.27  4978.4 1581.83  4996.8 1579.25
  4999.6 1578.75  5002.8 1579.25    5014 1580.68  5056.4 1582.75  5148.5 1588.72
  5197.9 1591.97  5233.2 1595.79  5261.5 1596.71  5290.8 1599.04  5318.7  1601.6
  5388.9 1603.84  5473.8 1608.68  5537.3 1614.99  5579.8 1616.99  5644.9 1621.46
#Mann= 7 ,-1 , 0
  4355.6     .05       0  4781.5      .1       0  4996.8     .07       0
  5002.8      .1       0  5148.5     .05       0  5290.8      .1       0
  5318.7     .05       0
Bank Sta=4978.4,5056.4
XS Rating Curve= 0 ,0
Exp/Cntr=0.3,0.1

Type RM Length L Ch R = 1 ,5355    ,600,600,600
BEGIN DESCRIPTION:
SNAKE CREEK 6.0
END DESCRIPTION:
XS GIS Cut Line= 3
      2792783.94     10034078.07      2792384.87     10033242.47
      2791989.01     10032914.32
#Sta/Elev= 30
  4199.8 1585.52  4230.2 1584.75  4273.6 1583.66  4296.3  1580.6  4326.5 1583.19
  4404.1 1580.94  4506.3 1580.66    4916 1577.53  4958.2 1577.65  4963.4  1577.1
  4999.5 1572.71  5002.3 1572.21  5005.5 1572.71  5024.7 1578.11  5150.5 1584.75
  5207.8 1590.09  5222.1 1592.63  5236.4 1591.92  5242.9    1593  5271.6 1603.26
  5278.1 1603.39  5292.4 1600.63  5314.6 1599.96  5392.7 1599.61  5410.9 1602.14
  5456.5 1607.02  5477.4 1607.93    5513 1614.09  5569.8 1618.13    5640 1617.77
#Mann= 9 ,-1 , 0
  4199.8      .1       0  4230.2     .05       0  4506.3      .1       0
    4916     .16       0  4963.4      .1       0  4999.5     .07       0
  5005.5      .1       0  5410.9     .05       0    5513      .1       0
Bank Sta=4958.2,5024.7
XS Rating Curve= 0 ,0
Exp/Cntr=0.3,0.1

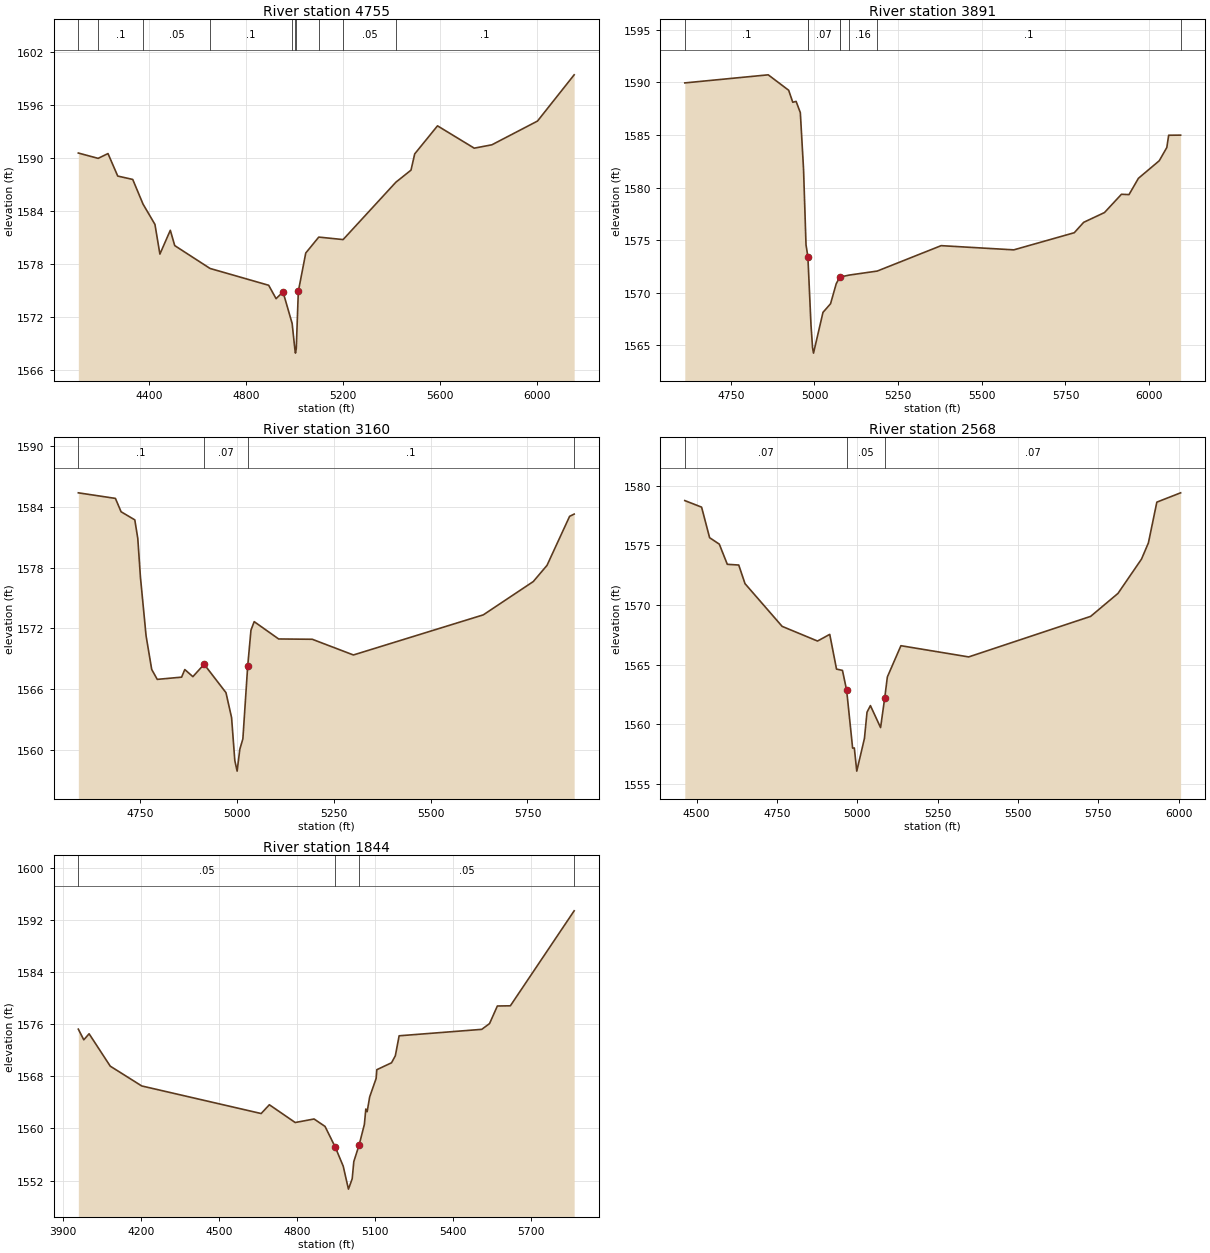
Type RM Length L Ch R = 1 ,4755    ,864,864,864
BEGIN DESCRIPTION:
SNAKE CREEK 5.0
END DESCRIPTION:
XS GIS Cut Line= 4
      2792801.54     10034273.73      2792999.46     10033258.09
      2792942.16     10032971.63        2792338.     10032586.22
#Sta/Elev= 30
  4107.7 1590.55  4189.3 1589.95    4230 1590.49  4270.1 1587.95  4331.9 1587.57
  4374.3 1584.79  4423.5 1582.49  4443.9 1579.14  4486.8 1581.83    4505  1580.1
  4650.5 1577.52  4892.2 1575.62  4922.7 1574.11  4951.3 1574.87  4988.9 1571.31
  4999.9 1568.46  5002.6 1567.96  5005.9 1568.46  5014.4 1574.93    5045 1579.26
  5098.6 1581.06    5199 1580.78  5416.6 1587.26  5478.8 1588.62    5494 1590.45
    5588 1593.62  5739.4  1591.1  5812.2 1591.48  6000.1 1594.16  6151.2 1599.38
#Mann= 10 ,-1 , 0
  4107.7     .05       0  4189.3      .1       0  4374.3     .05       0
  4650.5      .1       0  4988.9     .16       0  4999.9     .07       0
  5005.9     .16       0  5098.6      .1       0    5199     .05       0
  5416.6      .1       0
Bank Sta=4951.3,5014.4
XS Rating Curve= 0 ,0
Exp/Cntr=0.3,0.1

Type RM Length L Ch R = 1 ,3891    ,731,731,731
BEGIN DESCRIPTION:
SNAKE CREEK 4.0
END DESCRIPTION:
XS GIS Cut Line= 2
      2793692.16     10034133.09      2793046.33     10032799.76
#Sta/Elev= 30
  4612.5 1589.96  4861.8 1590.73  4922.9 1589.26  4935.1 1588.12  4945.1  1588.2
  4957.7 1587.13  4967.3 1581.76  4974.7 1574.54  4980.3 1573.41  4989.6 1566.91
  4994.3 1564.74  4997.1 1564.24  5025.4 1568.12    5048 1568.94    5065 1570.85
  5075.7 1571.48  5104.1 1571.67  5187.4 1572.05  5378.5 1574.47  5595.5 1574.07
  5776.2  1575.7  5804.3 1576.69  5866.5 1577.62  5917.2 1579.36  5939.8 1579.33
  5967.9 1580.88  6030.1 1582.55  6052.7 1583.81  6058.3 1584.98    6094 1584.99
#Mann= 8 ,-1 , 0
  4612.5      .1       0  4980.3     .05       0  4980.3     .07       0
  5075.7     .05       0  5075.7      .1       0  5104.1     .16       0
  5187.4      .1       0    6094      .1       0
Bank Sta=4980.3,5075.7
XS Rating Curve= 0 ,0
Exp/Cntr=0.3,0.1

Type RM Length L Ch R = 1 ,3160    ,592,592,592
BEGIN DESCRIPTION:
SNAKE CREEK 3.0
END DESCRIPTION:
XS GIS Cut Line= 2
      2794160.91     10033445.59      2793140.06     10032674.74
#Sta/Elev= 30
  4591.2 1585.39  4686.9 1584.84  4701.5 1583.52  4736.9 1582.72  4744.6 1580.89
  4751.4 1577.08    4766 1571.27  4780.5 1567.95  4794.8 1566.97  4857.6 1567.19
  4865.9 1567.94  4886.7 1567.24  4915.8 1568.46  4972.1 1565.66  4986.6 1563.19
  4994.9 1558.96  5000.9 1557.91  5007.8 1560.07  5015.7 1561.09  5028.1 1568.25
  5036.6 1571.83  5044.9 1572.67    5108 1570.96  5194.7 1570.93  5300.9 1569.38
    5636 1573.34    5765 1576.63  5800.4 1578.23  5858.7 1583.07  5870.4 1583.29
#Mann= 4 ,-1 , 0
  4591.2      .1       0  4915.8     .07       0  5028.1      .1       0
  5870.4      .1       0
Bank Sta=4915.8,5028.1
XS Rating Curve= 0 ,0
Exp/Cntr=0.3,0.1

Type RM Length L Ch R = 1 ,2568    ,724,724,724
BEGIN DESCRIPTION:
SNAKE CREEK 2.0
END DESCRIPTION:
XS GIS Cut Line= 3
      2794410.91     10033190.38      2794259.87     10032789.34
      2793203.03     10032435.32
#Sta/Elev= 30
  4463.2 1578.74  4515.5 1578.19  4540.4 1575.63  4570.6 1575.09  4595.5  1573.4
  4631.1 1573.34  4650.6 1571.78  4766.1  1568.2  4876.3 1566.97  4914.3 1567.53
  4935.4 1564.62  4953.9 1564.51    4967 1562.83  4985.5    1558  4990.8 1558.01
  4998.4 1556.07  5022.3 1558.81  5030.3 1561.01  5040.9 1561.56  5072.5 1559.72
  5085.4  1562.2  5093.6 1563.96  5135.8 1566.58  5346.7 1565.64  5726.4 1569.04
  5811.3 1570.96  5884.6 1573.84    5906 1575.19  5932.3 1578.61  6006.3 1579.39
#Mann= 3 , 0 , 0
  4463.2     .07       0    4967     .05       0  5085.4     .07       0
Bank Sta=4967,5085.4
XS Rating Curve= 0 ,0
Exp/Cntr=0.3,0.1

Type RM Length L Ch R = 1 ,1844    ,0,0,0
BEGIN DESCRIPTION:
SNAKE CREEK 1.0
END DESCRIPTION:
XS GIS Cut Line= 4
      2794629.67     10033164.38      2794416.12     10032039.34
      2794332.79     10031924.76      2793713.18     10031914.34
#Sta/Elev= 30
    3960 1575.27    3981 1573.63  4001.4 1574.56  4082.8 1569.58  4203.8 1566.54
    4663  1562.3  4694.5 1563.65  4793.9 1560.92  4866.5 1561.46  4908.6 1560.32
    4948 1557.13  4978.5 1554.21  4998.6 1550.68  5013.1 1552.28  5019.2 1554.91
  5039.6 1557.46  5059.9 1560.63  5065.4 1562.99  5070.5 1562.58  5080.3 1564.86
  5105.1  1567.7  5107.8 1569.04  5164.2  1570.1  5178.9 1571.17  5193.5 1574.25
  5511.2 1575.24  5541.2 1576.13  5571.2 1578.83  5621.2 1578.86  5866.5 1593.46
#Mann= 4 ,-1 , 0
    3960     .05       0    4948     .03       0  5039.6     .05       0
  5866.5     .05       0
Bank Sta=4948,5039.6
XS Rating Curve= 0 ,0
Exp/Cntr=0.3,0.1

Chan Stop Cuts=-1
Use User Specified Reach Order=0
Composite Channel Slope=5