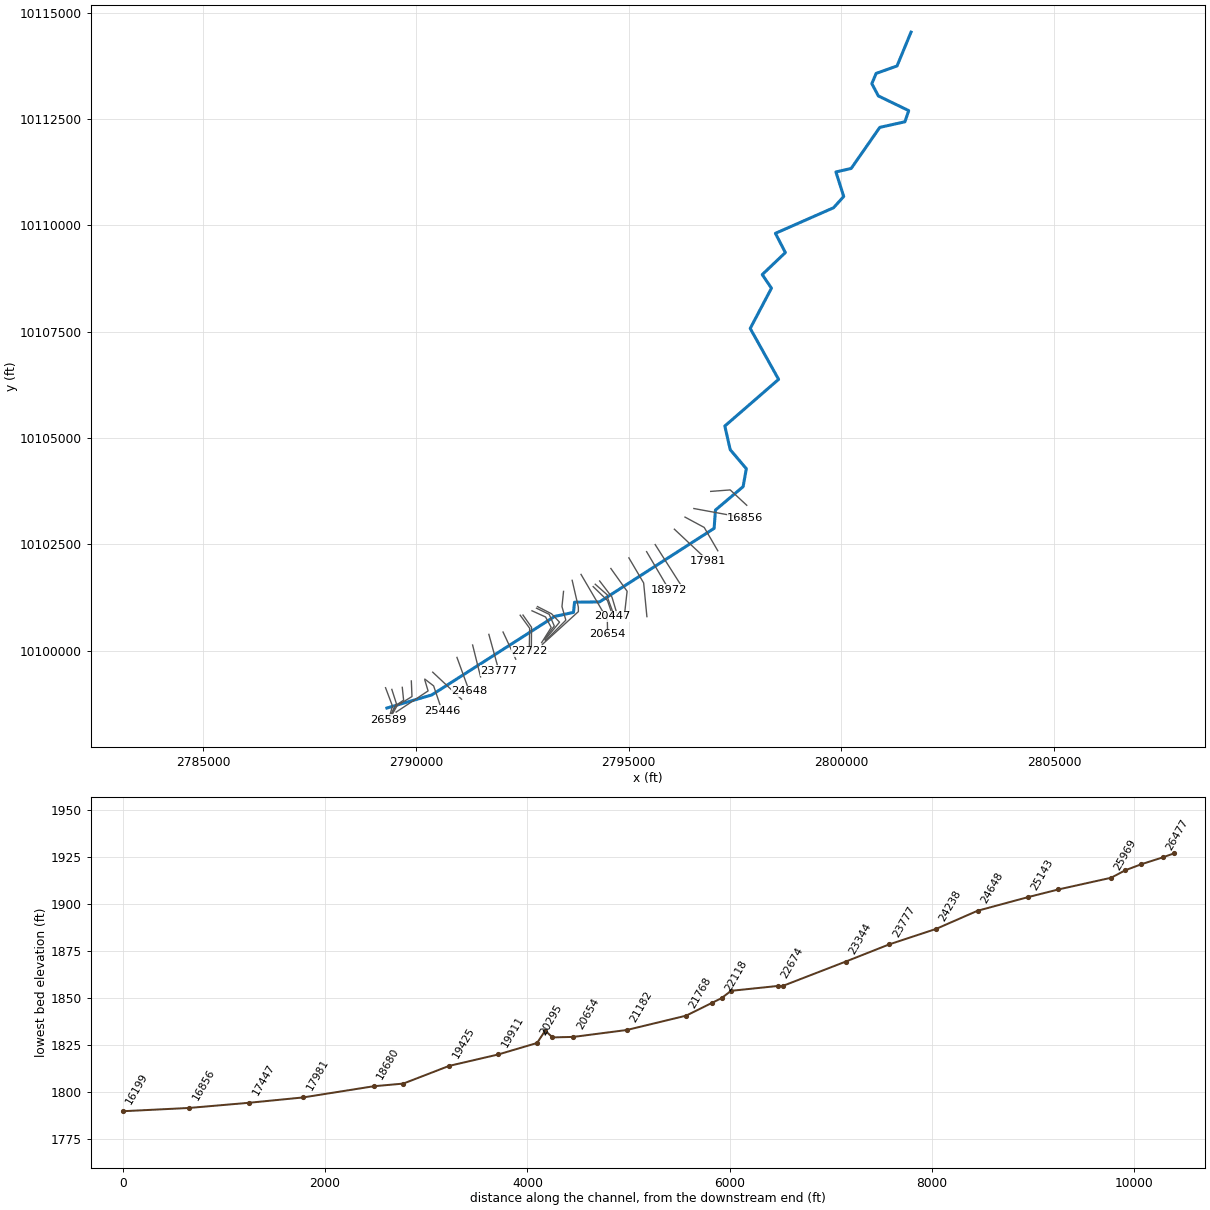
--- SOUTH BRANCH WILLOW CREEK.prj (project) ---

Proj Title=SOUTH BRANCH WILLOW CREEK Base Level Engineering
Current Plan=p01
Default Exp/Contr=0.3,0.1
English Units
Geom File=g01
Flow File=f01
Plan File=p01
Y Axis Title=Elevation
X Axis Title(PF)=Main Channel Distance
X Axis Title(XS)=Station
BEGIN DESCRIPTION:
SOUTH BRANCH WILLOW CREEK
END DESCRIPTION:
DSS Export Rating Curves= 0
DSS Export Rating Curve Sorted= 0
DSS Export Volume Flow Curves= 0
DXF OffsetX= 0
DXF OffsetY= 0
DXF ScaleX= 1
DXF ScaleY= 10

--- SOUTH BRANCH WILLOW CREEK.p01 (plan) ---

Plan Title=Multiple Run
Short Identifier=Multiple
Geom File=g01
Flow File=f01
Subcritical Flow
K Sum by GR= 0
Std Step Tol= 0.01
Critical Tol= 0.01
Num of Std Step Trials= 20
Max Error Tol= 0.3
Flow Tol Ratio= 0.001
Split Flow NTrial= 30
Split Flow Tol= 0.02
Split Flow Ratio= 0.02
Log Output Level= 0
Friction Slope Method= 1
Unsteady Friction Slope Method= 2
Unsteady Bridges Friction Slope Method= 1
Parabolic Critical Depth
Global Vel Dist=  1 , 1 , 1
Global Log Level= 0
CheckData=True
Encroach Param= -1, 0, 0, 0
BEGIN DESCRIPTION:
Multiple Run
END DESCRIPTION:

--- SOUTH BRANCH WILLOW CREEK.f01 (steady flow) ---

Flow Title=Multiple
Number of Profiles=7
Profile Names=10-year,25-year,50-year,1pct_min,100-year,1pct_plu,500-year
River Rch & RM= SOUTH BRANCH WIL,Reach-1,26589
     677     965    1211    1115    1507    2039    2340
River Rch & RM= SOUTH BRANCH WIL,Reach-1,20654
    1423    2112    2724    2567    3472    4695    5666
River Rch & RM= SOUTH BRANCH WIL,Reach-1,17447
    1530    2271    2928    2758    3730    5044    6077
River Rch & RM= SOUTH BRANCH WIL,Reach-1,14452
    1763    2628    3398    3208    4338    5867    7101
River Rch & RM= SOUTH BRANCH WIL,Reach-1,10070
    1973    2957    3837    3632    4912    6643    8090
River Rch & RM= SOUTH BRANCH WIL,Reach-1,9468
    2071    3092    4001    3774    5104    6903    8348
Boundary for River Rch & Prof#=SOUTH BRANCH WIL,Reach-1,1
Up Type=0
Dn Type=3
Dn Slope=0.005
Boundary for River Rch & Prof#=SOUTH BRANCH WIL,Reach-1,2
Up Type=0
Dn Type=3
Dn Slope=0.005
Boundary for River Rch & Prof#=SOUTH BRANCH WIL,Reach-1,3
Up Type=0
Dn Type=3
Dn Slope=0.005
Boundary for River Rch & Prof#=SOUTH BRANCH WIL,Reach-1,4
Up Type=0
Dn Type=3
Dn Slope=0.005
Boundary for River Rch & Prof#=SOUTH BRANCH WIL,Reach-1,5
Up Type=0
Dn Type=3
Dn Slope=0.005
Boundary for River Rch & Prof#=SOUTH BRANCH WIL,Reach-1,6
Up Type=0
Dn Type=3
Dn Slope=0.005
Boundary for River Rch & Prof#=SOUTH BRANCH WIL,Reach-1,7
Up Type=0
Dn Type=3
Dn Slope=0.005

--- SOUTH BRANCH WILLOW CREEK.g01 (geometry) ---

Geom Title=Existing Conditions
Program Version=4.10

River Reach=SOUTH BRANCH WIL,Reach-1
Reach XY= 30
      2789319.08     10098652.96      2790373.77     10098961.12
      2793262.28     10100806.43       2793705.2     10100901.29
      2793729.26      10101141.4      2794317.83     10101147.51
      2797010.78     10102876.96      2797042.16     10103306.91
      2797692.45      10103857.3      2797767.76     10104279.18
      2797389.01     10104726.46      2797262.09     10105282.11
      2798526.53     10106379.37      2797859.46     10107576.77
      2798358.46     10108522.79      2798142.04     10108842.24
      2798685.54     10109359.91      2798451.88     10109812.25
      2799818.47     10110413.73      2800057.39      10110678.6
      2799874.22     10111255.34      2800233.56     10111337.93
        2800905.     10112302.92      2801496.16     10112434.69
      2801585.37     10112697.16      2800871.94     10113041.99
      2800718.35     10113330.62      2800819.15      10113571.8
      2801310.86      10113747.3       2801639.8     10114541.99

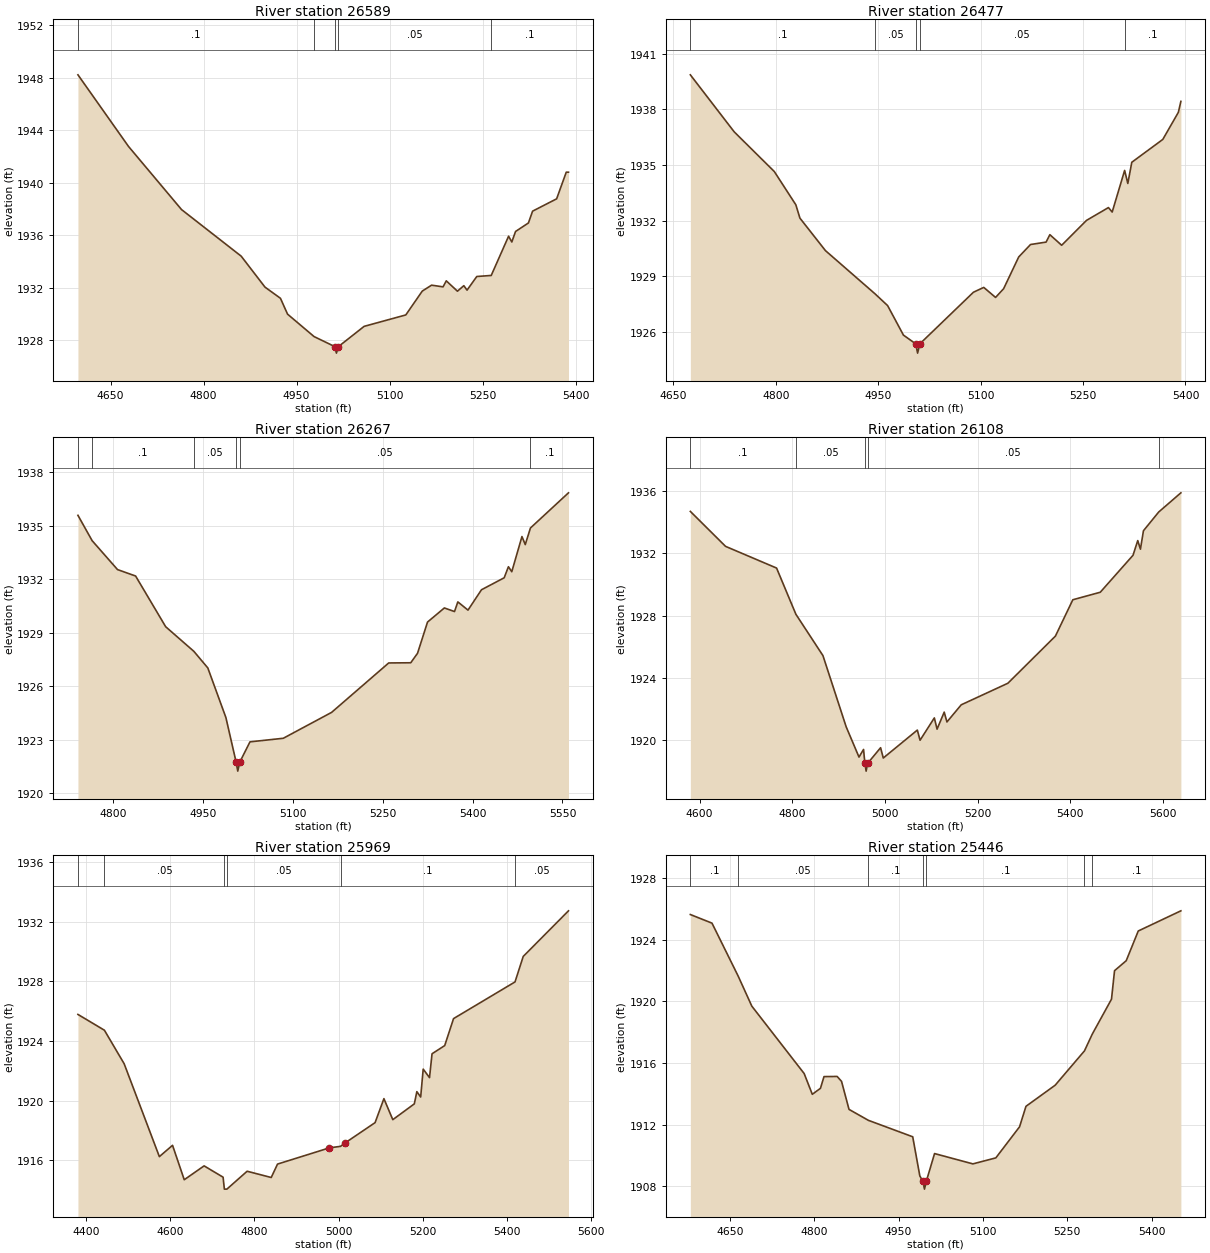
Type RM Length L Ch R = 1 ,26589   ,112,112,112
BEGIN DESCRIPTION:
SOUTH BRANCH WILLOW CREEK 52.0
END DESCRIPTION:
XS GIS Cut Line= 3
      2789286.53     10099130.05      2789449.73     10098697.74
      2789357.71     10098381.75
#Sta/Elev= 30
  4597.3 1948.23  4678.9 1942.77  4764.4 1937.96  4860.6 1934.41    4899 1932.05
  4923.9  1931.2  4935.4 1929.99  4978.2 1928.28  5011.5 1927.52  5014.2 1927.02
  5017.5 1927.52  5058.9 1929.06  5126.1 1929.93  5152.7 1931.75  5167.7  1932.2
  5186.2 1932.07  5191.4 1932.53  5209.4 1931.74  5219.7 1932.16  5224.9 1931.82
  5240.6 1932.86  5263.9 1932.94  5291.9 1935.93  5297.1 1935.49  5303.1 1936.29
  5323.9 1936.94  5330.6 1937.84  5369.4 1938.78  5384.9 1940.81  5388.5 1940.81
#Mann= 5 ,-1 , 0
  4597.3      .1       0  4978.2     .05       0  5011.5     .04       0
  5017.5     .05       0  5263.9      .1       0
Bank Sta=5011.5,5017.5
XS Rating Curve= 0 ,0
Exp/Cntr=0.3,0.1

Type RM Length L Ch R = 1 ,26477   ,210,210,210
BEGIN DESCRIPTION:
Mapping XS a5c4eef3
END DESCRIPTION:
XS GIS Cut Line= 4
      2789434.14     10099090.86      2789542.66     10098753.15
      2789514.88     10098715.82      2789380.39      10098428.6
#Sta/Elev= 30
  4674.9 1939.86  4739.1 1936.79  4797.9 1934.65  4829.4 1932.86  4835.4 1932.14
  4872.8 1930.39  4945.5 1928.06  4963.8 1927.43    4987 1925.84    5005 1925.37
  5007.7 1924.87    5011 1925.37  5089.5 1928.15  5104.6 1928.41  5121.9 1927.87
  5133.7 1928.34  5155.8 1930.05  5173.1 1930.72  5195.9 1930.85  5201.4 1931.25
  5218.7 1930.68  5255.1 1932.02  5287.2 1932.71  5292.7 1932.47  5310.9 1934.71
  5315.6 1934.01  5321.4 1935.15  5366.8 1936.38  5389.6 1937.84  5393.3 1938.43
#Mann= 5 ,-1 , 0
  4674.9      .1       0  4945.5     .05       0    5005     .04       0
    5011     .05       0  5310.9      .1       0
Bank Sta=5005,5011
XS Rating Curve= 0 ,0
Exp/Cntr=0.3,0.1

Type RM Length L Ch R = 1 ,26267   ,159,159,159
BEGIN DESCRIPTION:
Mapping XS 04f3a819
END DESCRIPTION:
XS GIS Cut Line= 4
      2789679.81     10099139.47      2789711.07     10098838.22
      2789531.38     10098715.82      2789400.12     10098447.27
#Sta/Elev= 30
  4740.8 1935.58  4764.5 1934.16  4806.9 1932.54  4837.1 1932.18  4887.3 1929.34
  4934.4 1927.96  4957.7 1927.03  4987.9 1924.25    5005 1921.75  5007.7 1921.25
    5011 1921.75  5028.1 1922.89  5083.7 1923.09  5164.4 1924.54  5259.8 1927.31
  5296.6 1927.32  5307.9 1927.85  5324.6  1929.6  5352.7 1930.39  5369.7 1930.19
  5375.2 1930.73  5392.2 1930.27  5414.7 1931.41  5452.6 1932.08  5459.7  1932.7
  5465.3 1932.42  5482.3 1934.39  5487.8 1933.94  5496.5 1934.87    5560 1936.84
#Mann= 6 ,-1 , 0
  4740.8     .16       0  4764.5      .1       0  4934.4     .05       0
    5005     .04       0    5011     .05       0  5496.5      .1       0
Bank Sta=5005,5011
XS Rating Curve= 0 ,0
Exp/Cntr=0.3,0.1

Type RM Length L Ch R = 1 ,26108   ,139,139,139
BEGIN DESCRIPTION:
SOUTH BRANCH WILLOW CREEK 51.0
END DESCRIPTION:
XS GIS Cut Line= 4
      2789892.44     10099289.71      2789908.06     10098923.43
       2789559.1     10098709.89       2789420.2     10098463.35
#Sta/Elev= 30
    4580 1934.67    4656 1932.43  4766.1 1931.04  4807.8 1928.08  4866.2 1925.43
  4916.3 1920.87    4944 1918.93  4953.8 1919.42  4956.7 1918.53  4959.4 1918.03
  4962.7 1918.53  4990.6 1919.53  4996.4 1918.87  5069.9 1920.66  5075.8 1920.01
  5106.6 1921.44  5112.5 1920.72  5127.9 1921.81  5133.8 1921.18  5164.7 1922.28
  5265.3 1923.66  5367.9 1926.68  5405.5 1929.01  5464.7 1929.49  5535.4 1931.86
  5545.6  1932.8  5551.4 1932.25  5557.9 1933.43  5590.8 1934.63  5638.7 1935.86
#Mann= 5 ,-1 , 0
    4580      .1       0  4807.8     .05       0  4956.7     .04       0
  4962.7     .05       0  5590.8      .1       0
Bank Sta=4956.7,4962.7
XS Rating Curve= 0 ,0
Exp/Cntr=0.3,0.1

Type RM Length L Ch R = 1 ,25969   ,523,523,523
BEGIN DESCRIPTION:
SOUTH BRANCH WILLOW CREEK 50.0
END DESCRIPTION:
XS GIS Cut Line= 3
      2790210.14     10099308.87      2790286.53     10099055.38
      2789535.99      10098557.9
#Sta/Elev= 30
    4381 1925.78  4443.9 1924.72  4490.8 1922.47  4574.4 1916.24  4605.7    1917
  4633.5 1914.69  4680.7 1915.62  4725.8 1914.86  4728.8 1914.06  4734.8 1914.06
  4782.9 1915.26  4840.1 1914.84  4855.1 1915.74  4978.5 1916.83  5004.8 1916.93
  5014.6 1917.14  5086.8 1918.52  5107.8 1920.13  5128.9 1918.72    5180 1919.78
    5186  1920.6  5195.1 1920.24  5201.1 1922.11  5216.1 1921.54  5222.1 1923.14
  5252.2 1923.69  5273.2  1925.5  5419.2 1927.96  5438.7 1929.67  5546.2 1932.73
#Mann= 6 ,-1 , 0
    4381      .1       0  4443.9     .05       0  4728.8     .04       0
  4734.8     .05       0  5004.8      .1       0  5419.2     .05       0
#XS Ineff= 2 , 0
       0 4977.39 1916.78               0
Permanent Ineff=
       T       F
Bank Sta=4978.5,5014.6
XS Rating Curve= 0 ,0
Exp/Cntr=0.3,0.1

Type RM Length L Ch R = 1 ,25446   ,303,303,303
BEGIN DESCRIPTION:
SOUTH BRANCH WILLOW CREEK 49.0
END DESCRIPTION:
XS GIS Cut Line= 3
      2790211.92     10099331.39      2790416.74     10099173.43
      2790612.91     10098591.88
#Sta/Elev= 30
  4579.6 1925.65  4618.1 1925.09  4664.8 1921.64  4688.9  1919.7    4782 1915.32
  4796.5 1913.97    4811 1914.36  4817.3 1915.12  4840.7 1915.13  4848.5 1914.81
  4861.8 1912.99  4896.2 1912.28  4975.1 1911.21  4987.7 1908.67  4993.2 1908.31
    4996 1907.81  4999.2 1908.31  5013.9 1910.12  5082.1 1909.45  5122.9 1909.84
  5165.1 1911.86  5176.5 1913.19  5228.4 1914.56  5280.5 1916.79  5294.4 1917.88
  5328.6 1920.15    5334    1922  5354.8 1922.65  5376.2 1924.58    5452 1925.89
#Mann= 7 ,-1 , 0
  4579.6      .1       0  4664.8     .05       0  4896.2      .1       0
  4993.2     .07       0  4999.2      .1       0  5280.5     .05       0
  5294.4      .1       0
Bank Sta=4993.2,4999.2
XS Rating Curve= 0 ,0
Exp/Cntr=0.3,0.1

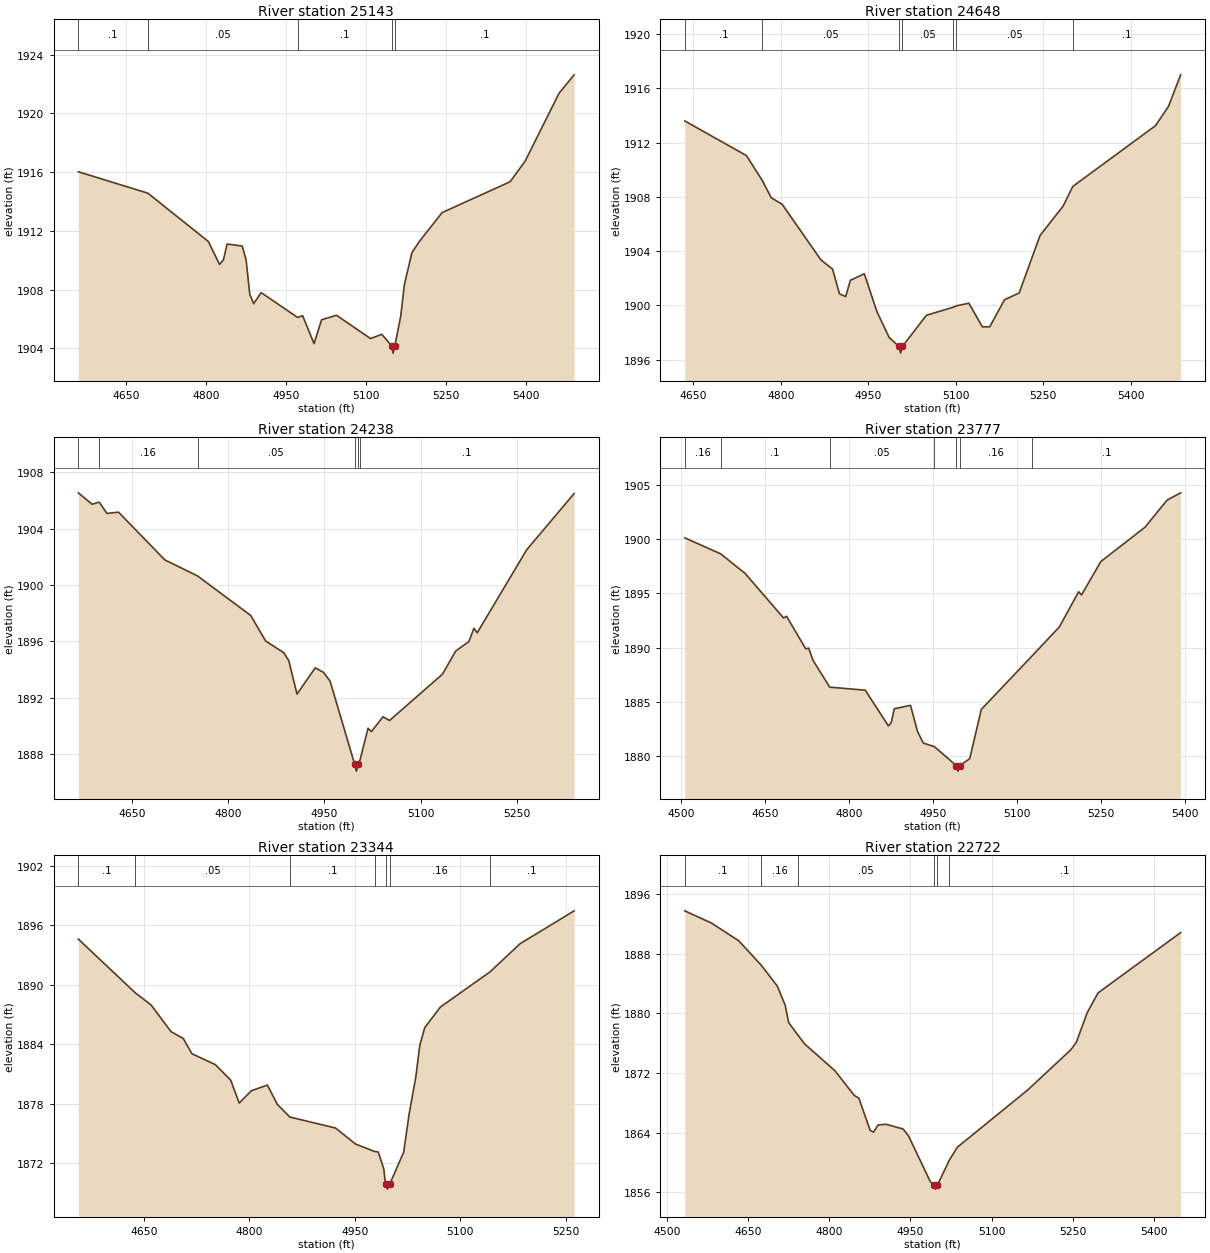
Type RM Length L Ch R = 1 ,25143   ,495,495,495
BEGIN DESCRIPTION:
SOUTH BRANCH WILLOW CREEK 48.0
END DESCRIPTION:
XS GIS Cut Line= 2
      2790395.71      10099495.7      2791073.82      10098859.1
#Sta/Elev= 30
  4560.6 1916.03  4691.1 1914.57  4804.5 1911.28  4825.5 1909.72  4832.8 1910.03
  4839.7 1911.11    4868 1910.97  4875.3 1910.03  4882.2 1907.69  4889.5 1907.05
  4903.6  1907.8    4972 1906.11  4981.3 1906.23  5002.8 1904.33  5016.9 1905.95
  5044.8 1906.26  5108.8 1904.67  5129.8 1904.96  5148.3 1904.18    5151 1903.68
  5154.3 1904.18  5165.4  1906.2  5172.3 1908.36  5186.4 1910.52  5200.6  1911.3
  5243.1 1913.25  5370.6 1915.35  5398.9 1916.76  5462.4 1921.38  5490.7 1922.63
#Mann= 5 ,-1 , 0
  4560.6      .1       0  4691.1     .05       0    4972      .1       0
  5148.3     .07       0  5154.3      .1       0
Bank Sta=5148.3,5154.3
XS Rating Curve= 0 ,0
Exp/Cntr=0.3,0.1

Type RM Length L Ch R = 1 ,24648   ,410,410,410
BEGIN DESCRIPTION:
SOUTH BRANCH WILLOW CREEK 47.0
END DESCRIPTION:
XS GIS Cut Line= 2
      2790965.17     10099842.93      2791256.84     10099044.32
#Sta/Elev= 30
  4635.4  1913.6    4741 1911.05  4767.9 1909.24  4783.6 1907.94  4802.4 1907.45
  4868.9 1903.35  4888.7 1902.68  4900.7 1900.85  4911.3 1900.65  4919.3 1901.85
  4943.3 1902.33  4964.6 1899.56  4985.9 1897.63  5002.6 1896.98  5005.4 1896.48
  5008.6 1896.98  5049.7 1899.27  5095.2 1899.86  5101.2 1899.97  5122.5 1900.16
  5145.6 1898.42  5158.3 1898.42  5183.5 1900.41  5208.8 1900.92  5244.6 1905.16
    5284 1907.31  5300.7 1908.77  5442.5 1913.25  5464.9 1914.68  5485.6    1917
#Mann= 7 ,-1 , 0
  4635.4      .1       0  4767.9     .05       0  5002.6     .04       0
  5008.6     .05       0  5095.2      .1       0  5101.2     .05       0
  5300.7      .1       0
Bank Sta=5002.6,5008.6
XS Rating Curve= 0 ,0
Exp/Cntr=0.3,0.1

Type RM Length L Ch R = 1 ,24238   ,461,461,461
BEGIN DESCRIPTION:
SOUTH BRANCH WILLOW CREEK 46.0
END DESCRIPTION:
XS GIS Cut Line= 2
      2791333.25     10100134.54      2791520.75     10099384.53
#Sta/Elev= 30
  4566.3 1906.53  4587.8 1905.72  4598.8 1905.87    4611 1905.07    4629 1905.16
  4701.1 1901.78  4752.2 1900.64  4835.1 1897.84  4858.4 1896.03  4886.7  1895.2
  4894.4 1894.64  4907.3 1892.27  4935.7 1894.13  4948.5 1893.81  4958.8 1893.19
  4997.1 1887.31  4999.8 1886.81  5003.1 1887.31  5005.5  1887.6  5018.1 1889.85
  5023.3 1889.61  5041.3 1890.66  5051.6  1890.4  5134.1 1893.68  5154.7 1895.32
  5175.3 1895.99  5183.1 1896.93  5188.2 1896.61  5265.5  1902.5  5339.4 1906.48
#Mann= 6 ,-1 , 0
  4566.3      .1       0  4598.8     .16       0  4752.2     .05       0
  4997.1     .04       0  5003.1     .05       0  5005.5      .1       0
Bank Sta=4997.1,5003.1
XS Rating Curve= 0 ,0
Exp/Cntr=0.3,0.1

Type RM Length L Ch R = 1 ,23777   ,433,433,433
BEGIN DESCRIPTION:
SOUTH BRANCH WILLOW CREEK 45.0
END DESCRIPTION:
XS GIS Cut Line= 2
      2791715.18     10100384.58      2791951.29     10099530.41
#Sta/Elev= 30
  4506.1 1900.12  4570.1 1898.65  4614.1 1896.83  4682.7 1892.73  4687.9  1892.9
  4722.3 1889.89  4727.5 1889.96  4735.2 1888.84  4765.1 1886.36  4828.6 1886.08
    4870 1882.79  4875.1 1883.09  4880.5 1884.37  4909.5 1884.68    4922 1882.28
  4932.4 1881.21  4952.1 1880.88  4991.6 1879.12  4994.4 1878.62  4997.6 1879.12
  5015.4 1879.78  5036.1 1884.31  5126.8 1889.24  5175.7 1891.92    5210 1895.15
  5215.2 1894.86  5249.6 1897.93  5328.6  1901.1  5368.1  1903.6  5392.3 1904.27
#Mann= 7 ,-1 , 0
  4506.1     .16       0  4570.1      .1       0  4765.1     .05       0
  4952.1     .16       0  4991.6     .07       0  4997.6     .16       0
  5126.8      .1       0
Bank Sta=4991.6,4997.6
XS Rating Curve= 0 ,0
Exp/Cntr=0.3,0.1

Type RM Length L Ch R = 1 ,23344   ,622,622,622
BEGIN DESCRIPTION:
SOUTH BRANCH WILLOW CREEK 44.0
END DESCRIPTION:
XS GIS Cut Line= 2
      2792048.53     10100440.09      2792347.13     10099801.23
#Sta/Elev= 30
  4556.9 1894.61  4638.1 1889.18  4660.4 1887.97  4688.7 1885.28  4706.1 1884.59
  4718.5 1883.05  4751.6 1881.96  4773.6 1880.39  4785.7 1878.08    4803 1879.32
  4825.8 1879.89  4839.9 1877.95  4857.7 1876.67  4922.7 1875.56  4951.1 1873.95
  4978.4 1873.19  4983.4 1873.15  4991.3 1871.46  4993.8  1869.9  4996.5  1869.4
  4999.8  1869.9  5019.6 1873.12  5027.5 1877.02    5037 1880.75  5042.5 1883.89
  5049.6 1885.68  5071.7 1887.75  5142.7 1891.32  5185.1 1894.14  5262.1 1897.46
#Mann= 7 ,-1 , 0
  4556.9      .1       0  4638.1     .05       0  4857.7      .1       0
  4978.4     .16       0  4993.8     .07       0  4999.8     .16       0
  5142.7      .1       0
Bank Sta=4993.8,4999.8
XS Rating Curve= 0 ,0
Exp/Cntr=0.3,0.1

Type RM Length L Ch R = 1 ,22722   ,48,48,48
BEGIN DESCRIPTION:
SOUTH BRANCH WILLOW CREEK 42.0
END DESCRIPTION:
XS GIS Cut Line= 3
      2792451.44     10100834.93      2792673.69     10100529.34
      2792665.01     10099991.17
#Sta/Elev= 30
  4533.3 1893.73  4582.9 1892.08  4633.1 1889.71  4674.5 1886.45  4704.2 1883.65
  4718.9 1881.06  4725.1 1878.77  4742.2 1877.09  4754.5 1875.91  4810.9 1872.29
  4846.4    1869  4854.9 1868.63  4875.8 1864.31    4882 1864.08  4890.5 1865.04
  4905.2 1865.13  4936.8 1864.49  4946.8 1863.55  4986.8 1857.46  4993.8 1856.94
  4996.5 1856.44  4999.8 1856.94  5022.2 1860.34  5036.8 1862.05  5166.8 1869.72
  5246.8 1875.13  5256.8 1876.13  5276.8 1880.08  5296.8 1882.73  5449.4 1890.81
#Mann= 6 ,-1 , 0
  4533.3      .1       0  4674.5     .16       0  4742.2     .05       0
  4993.8     .04       0  4999.8     .05       0  5022.2      .1       0
Bank Sta=4993.8,4999.8
XS Rating Curve= 0 ,0
Exp/Cntr=0.3,0.1

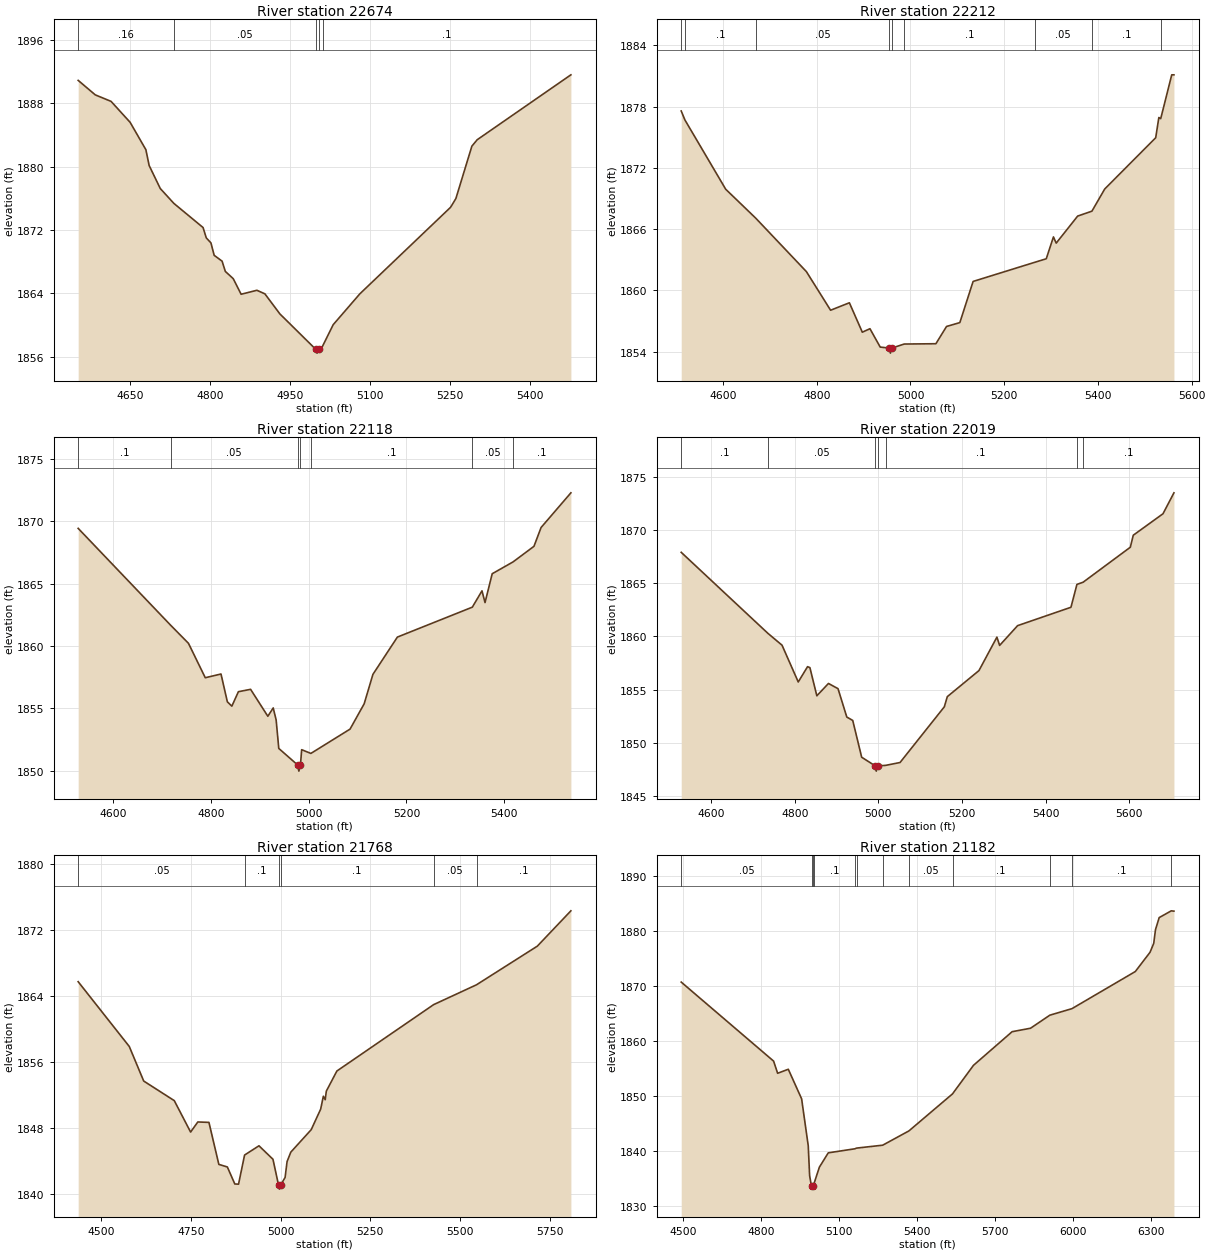
Type RM Length L Ch R = 1 ,22674   ,462,462,462
BEGIN DESCRIPTION:
Mapping XS 20a51e08
END DESCRIPTION:
XS GIS Cut Line= 3
      2792517.43     10100838.37      2792718.82     10100551.91
      2792713.62       10099978.
#Sta/Elev= 30
  4552.6 1890.87  4584.7 1889.04  4614.3 1888.22    4650 1885.58  4679.6 1882.12
  4685.7 1880.13  4706.6 1877.22    4732 1875.35  4786.8  1872.3  4792.9 1870.99
  4801.6 1870.36  4807.7 1868.79  4822.5 1868.06  4828.6 1866.76  4843.4 1865.85
  4858.2 1863.88  4887.8 1864.38  4902.8 1863.93  4930.9  1861.4  4997.9 1856.95
  5000.7 1856.45  5003.9 1856.95  5010.9 1857.32  5030.9 1860.04    5081 1863.94
    5251 1874.85    5261 1875.96    5291 1882.57    5301 1883.38  5476.7 1891.57
#Mann= 5 ,-1 , 0
  4552.6     .16       0    4732     .05       0  4997.9     .04       0
  5003.9     .05       0  5010.9      .1       0
Bank Sta=4997.9,5003.9
XS Rating Curve= 0 ,0
Exp/Cntr=0.3,0.1

Type RM Length L Ch R = 1 ,22212   ,94,94,94
BEGIN DESCRIPTION:
Mapping XS 76c2f6a9
END DESCRIPTION:
XS GIS Cut Line= 4
       2792729.2     10100939.08      2793048.69     10100793.23
      2793180.63      10100546.7      2792956.68     10100190.81
#Sta/Elev= 30
  4510.9 1877.57  4518.8 1876.69  4605.8 1869.91    4670 1867.07    4778 1861.84
  4829.6 1858.06  4869.7 1858.79  4897.3 1855.91  4913.6 1856.25  4935.5 1854.45
  4954.5 1854.36  4957.2 1853.86  4960.5 1854.36  4986.7 1854.75  5054.3 1854.78
    5077 1856.47  5105.4 1856.85  5133.7 1860.88    5265 1862.75  5289.8  1863.1
  5305.1 1865.24    5311 1864.63  5356.8 1867.28  5387.2 1867.76  5414.5 1869.93
  5523.3 1874.95    5530 1876.93    5534 1876.82  5557.5 1881.11  5562.2 1881.11
#Mann= 9 ,-1 , 0
  4510.9     .16       0  4518.8      .1       0    4670     .05       0
  4954.5     .07       0  4960.5     .05       0  4986.7      .1       0
    5265     .05       0  5387.2      .1       0    5534     .16       0
Bank Sta=4954.5,4960.5
XS Rating Curve= 0 ,0
Exp/Cntr=0.3,0.1

Type RM Length L Ch R = 1 ,22118   ,99,99,99
BEGIN DESCRIPTION:
Mapping XS 05f7dba5
END DESCRIPTION:
XS GIS Cut Line= 4
       2792835.1     10100999.85      2793133.76     10100855.73
      2793253.55     10100581.42      2793028.28     10100278.17
#Sta/Elev= 30
  4527.9 1869.43    4717 1861.67  4753.7 1860.21  4788.1 1857.45  4820.3 1857.75
  4833.3 1855.52  4842.5 1855.17  4855.9 1856.33  4880.9 1856.52  4916.2 1854.36
  4927.2 1855.03  4933.2 1854.06  4938.6 1851.78    4977 1850.46  4979.7 1849.96
    4983 1850.46  4985.4 1851.68  5004.3 1851.38  5084.5 1853.33  5113.4 1855.36
  5131.3 1857.72  5181.4 1860.71  5334.8 1863.11  5354.6 1864.42  5360.8 1863.48
  5375.5 1865.79  5418.2 1866.74    5461 1867.99  5475.6  1869.5  5536.6 1872.28
#Mann= 7 ,-1 , 0
  4527.9      .1       0    4717     .05       0    4977     .04       0
    4983     .05       0  5004.3      .1       0  5334.8     .05       0
  5418.2      .1       0
Bank Sta=4977,4983
XS Rating Curve= 0 ,0
Exp/Cntr=0.3,0.1

Type RM Length L Ch R = 1 ,22019   ,251,251,251
BEGIN DESCRIPTION:
SOUTH BRANCH WILLOW CREEK 41.0
END DESCRIPTION:
XS GIS Cut Line= 4
       2792857.7     10101038.02      2793187.57     10100869.62
      2793376.81      10100671.7      2793036.65     10100258.64
#Sta/Elev= 30
    4528 1867.92  4735.1 1860.31  4769.3 1859.18  4808.1 1855.72  4830.4 1857.16
    4836 1857.07  4852.6 1854.42  4880.4 1855.58  4903.3 1855.09  4924.3 1852.42
  4938.5  1852.1  4959.9 1848.64  4992.1 1847.83  4994.8 1847.33  4998.1 1847.83
    5017 1847.87  5051.7 1848.14  5157.7 1853.38  5164.9 1854.34  5240.6 1856.79
  5283.6 1859.94  5290.1 1859.16  5333.1 1861.02  5460.8 1862.75  5475.1  1864.9
    5490 1865.11  5602.9  1868.4    5610 1869.53  5681.1 1871.55  5707.3 1873.52
#Mann= 7 ,-1 , 0
    4528      .1       0  4735.1     .05       0  4992.1     .04       0
  4998.1     .05       0    5017      .1       0  5475.1     .05       0
    5490      .1       0
Bank Sta=4992.1,4998.1
XS Rating Curve= 0 ,0
Exp/Cntr=0.3,0.1

Type RM Length L Ch R = 1 ,21768   ,586,586,586
BEGIN DESCRIPTION:
SOUTH BRANCH WILLOW CREEK 40.0
END DESCRIPTION:
XS GIS Cut Line= 4
      2793470.88     10101395.35      2793433.99     10101037.31
      2793525.14      10100718.3      2793045.57     10100234.39
#Sta/Elev= 30
  4436.1 1865.72  4578.5 1857.89  4618.7 1853.71  4703.9 1851.34  4749.4 1847.54
  4769.5 1848.76  4800.5 1848.71  4828.1 1843.63  4851.8 1843.32  4872.6 1841.26
    4883 1841.24  4899.8 1844.76  4939.9 1845.88  4978.9 1844.25  4994.4 1841.14
  4997.1 1840.64  5000.4 1841.14  5012.7 1842.05  5018.2 1843.97  5028.6 1845.11
  5085.5 1847.83  5111.8 1850.31  5119.3 1851.87  5124.5 1851.45  5127.6 1852.49
    5157 1854.92  5426.7 1862.95  5546.2 1865.35  5715.6 1870.02  5809.1 1874.29
#Mann= 6 ,-1 , 0
  4436.1     .05       0  4899.8      .1       0  4994.4     .07       0
  5000.4      .1       0  5426.7     .05       0  5546.2      .1       0
Bank Sta=4994.4,5000.4
XS Rating Curve= 0 ,0
Exp/Cntr=0.3,0.1

Type RM Length L Ch R = 1 ,21182   ,528,528,528
BEGIN DESCRIPTION:
SOUTH BRANCH WILLOW CREEK 39.0
END DESCRIPTION:
XS GIS Cut Line= 4
      2793673.51     10101655.43      2793819.35     10101023.44
      2793819.35     10100919.28      2792972.93     10100149.17
#Sta/Elev= 30
  4492.1 1870.66  4847.8 1856.29  4863.3 1854.08  4904.4 1854.81  4955.7 1849.43
  4981.2 1840.88  4986.5 1835.45  4993.7 1833.51  4996.5 1833.01  4999.7 1833.51
  5004.8 1834.22    5024    1837  5058.3 1839.61  5161.3 1840.35  5167.1 1840.47
  5267.9    1841  5368.9  1843.6  5536.6 1850.33  5617.5 1855.53  5766.2 1861.64
  5837.1 1862.27  5911.3 1864.64  5996.5 1865.83  6240.5 1872.58  6297.3 1876.09
  6311.5 1877.73  6318.2  1880.2  6332.4 1882.39    6379 1883.62  6389.2 1883.56
#Mann= 12 ,-1 , 0
  4492.1     .05       0  4993.7     .04       0  4999.7     .05       0
  5004.8      .1       0  5161.3     .16       0  5167.1     .05       0
  5267.9      .1       0  5368.9     .05       0  5536.6      .1       0
  5911.3     .05       0  5996.5      .1       0    6379     .16       0
Bank Sta=4993.7,4999.7
XS Rating Curve= 0 ,0
Exp/Cntr=0.3,0.1

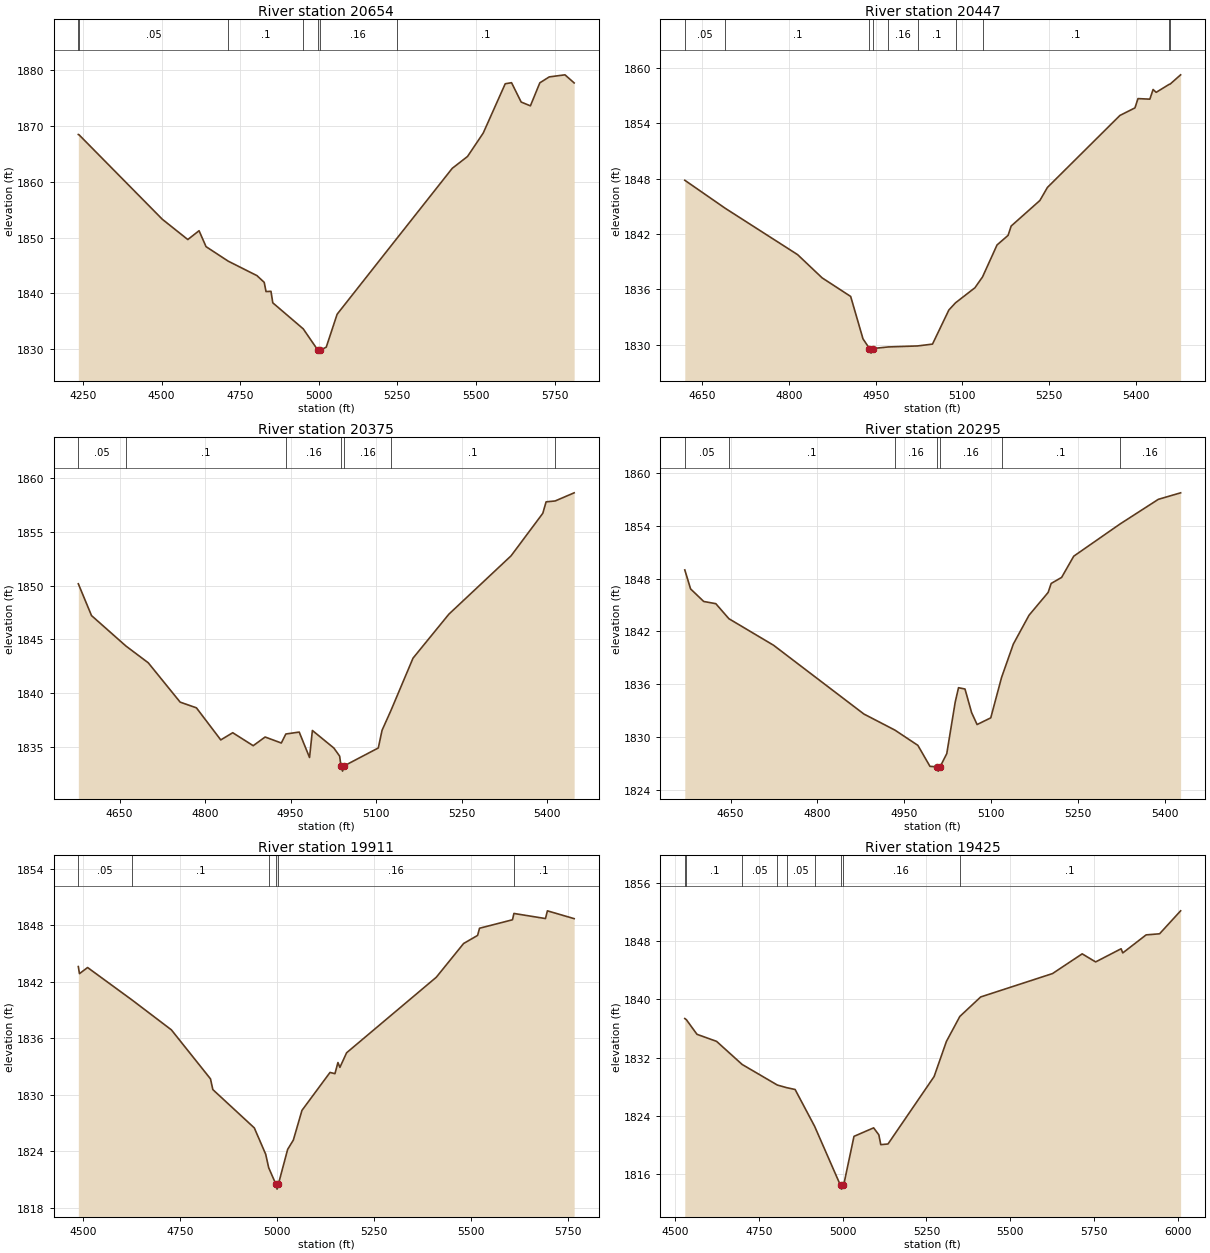
Type RM Length L Ch R = 1 ,20654   ,207,207,207
BEGIN DESCRIPTION:
SOUTH BRANCH WILLOW CREEK 38.0
END DESCRIPTION:
XS GIS Cut Line= 3
      2793881.83     10101794.32      2794499.91     10100738.72
      2794506.86     10100384.52
#Sta/Elev= 30
    4235 1868.44  4237.4 1868.38  4502.2 1853.28  4583.3 1849.65  4619.1 1851.23
  4641.3 1848.38    4712 1845.78  4803.5 1843.19  4826.4 1841.99  4832.2 1840.34
  4847.9 1840.39  4853.7 1838.33  4950.6 1833.67  4997.5 1829.83  5000.2 1829.33
  5003.5 1829.83  5023.7 1830.39  5058.4 1836.29  5248.3 1849.84  5424.6 1862.39
  5473.2 1864.51  5523.2  1868.7  5593.2 1877.52  5613.3 1877.71  5643.9 1874.25
  5673.3 1873.57  5703.3 1877.69  5733.3 1878.75  5783.3 1879.12  5812.5 1877.67
#Mann= 7 ,-1 , 0
    4235     .16       0  4237.4     .05       0    4712      .1       0
  4950.6     .16       0  4997.5     .07       0  5003.5     .16       0
  5248.3      .1       0
Bank Sta=4997.5,5003.5
XS Rating Curve= 0 ,0
Exp/Cntr=0.3,0.1

Type RM Length L Ch R = 1 ,20447   ,72,72,72
BEGIN DESCRIPTION:
Mapping XS 69db68fd
END DESCRIPTION:
XS GIS Cut Line= 3
      2794166.93     10101507.82      2794503.73      10101179.7
      2794628.74     10100813.35
#Sta/Elev= 30
    4620 1847.83  4690.1 1844.78    4815 1839.76  4857.4 1837.24  4906.8 1835.22
  4928.1 1830.62  4939.3 1829.57    4942 1829.07  4945.3 1829.57  4971.7 1829.74
  5022.5 1829.85  5048.3 1830.05  5076.6 1833.75  5088.1 1834.53  5121.6 1836.16
  5134.8 1837.34  5159.9 1840.81    5179 1841.85  5184.3 1842.86  5233.9 1845.63
    5247 1847.05  5372.3 1854.86  5398.3 1855.68  5403.6 1856.69  5424.1 1856.63
  5429.7 1857.68    5435 1857.37  5457.6 1858.24  5458.9 1858.25  5477.3 1859.27
#Mann= 10 ,-1 , 0
    4620     .05       0  4690.1      .1       0  4939.3     .07       0
  4945.3      .1       0  4971.7     .16       0  5022.5      .1       0
  5088.1     .16       0  5134.8      .1       0  5457.6     .16       0
  5458.9      .1       0
Bank Sta=4939.3,4945.3
XS Rating Curve= 0 ,0
Exp/Cntr=0.3,0.1

Type RM Length L Ch R = 1 ,20375   ,80,80,80
BEGIN DESCRIPTION:
Mapping XS 674d3e6d
END DESCRIPTION:
XS GIS Cut Line= 4
       2794215.5     10101563.41      2794498.52     10101313.38
      2794512.41     10101228.31       2794652.6     10100847.54
#Sta/Elev= 30
  4577.7 1850.17  4600.8 1847.21  4661.2 1844.37  4700.3 1842.81  4756.3 1839.14
  4784.8 1838.61  4827.5 1835.62  4848.5 1836.29  4884.4 1835.08  4905.3 1835.89
  4933.7 1835.33  4941.6 1836.17  4965.1 1836.35  4983.2 1833.98  4988.2  1836.5
  5025.9 1834.86    5036 1834.11  5038.3 1833.21  5041.1 1832.71  5044.3 1833.21
  5103.8 1834.87  5110.4 1836.52  5125.8 1838.34  5164.7 1843.24  5227.6 1847.34
  5336.7 1852.78  5392.3 1856.74  5398.1 1857.81  5413.9 1857.89  5447.3 1858.65
#Mann= 7 ,-1 , 0
  4577.7     .05       0  4661.2      .1       0  4941.6     .16       0
  5038.3     .07       0  5044.3     .16       0  5125.8      .1       0
  5413.9     .16       0
Bank Sta=5038.3,5044.3
XS Rating Curve= 0 ,0
Exp/Cntr=0.3,0.1

Type RM Length L Ch R = 1 ,20295   ,384,384,384
BEGIN DESCRIPTION:
SOUTH BRANCH WILLOW CREEK 37.0
END DESCRIPTION:
XS GIS Cut Line= 3
      2794319.72     10101639.74      2794609.63     10101259.56
      2794718.45     10100896.84
#Sta/Elev= 30
  4570.8 1848.99  4580.8 1846.83  4603.5  1845.4  4624.4 1845.15    4647 1843.44
  4724.2 1840.42  4880.2  1832.6  4933.8 1830.77  4973.6 1829.03  4994.5 1826.64
    5006  1826.6  5008.7  1826.1    5012  1826.6  5023.5 1828.09  5038.1 1833.96
  5043.8 1835.59    5055 1835.44  5066.4 1832.76  5075.9  1831.4  5099.5 1832.16
  5118.2 1836.76  5138.5 1840.55  5165.6 1843.83  5198.7 1846.43  5203.9 1847.45
    5222 1848.14  5242.9 1850.55  5322.6  1854.2  5389.1 1857.02  5427.6 1857.76
#Mann= 7 ,-1 , 0
  4570.8     .05       0    4647      .1       0  4933.8     .16       0
    5006     .07       0    5012     .16       0  5118.2      .1       0
  5322.6     .16       0
Bank Sta=5006,5012
XS Rating Curve= 0 ,0
Exp/Cntr=0.3,0.1

Type RM Length L Ch R = 1 ,19911   ,486,486,486
BEGIN DESCRIPTION:
SOUTH BRANCH WILLOW CREEK 36.0
END DESCRIPTION:
XS GIS Cut Line= 3
      2794583.24     10101933.17      2794965.19     10101398.44
      2794895.74     10100780.36
#Sta/Elev= 30
  4487.7 1843.61  4490.6 1842.86  4511.6 1843.51  4626.7 1840.05  4727.8 1836.89
  4828.6 1831.69  4834.7 1830.55  4941.7 1826.48  4971.1 1823.68  4978.8 1822.25
  4997.6 1820.48  5000.4 1819.98  5003.6 1820.48  5027.7  1824.2  5042.4 1825.19
  5064.6 1828.34    5137 1832.37  5149.7 1832.24  5157.4 1833.42  5162.5 1832.91
  5179.8 1834.46  5411.2 1842.48  5481.6 1846.06  5517.7 1846.92  5522.7 1847.68
  5607.7 1848.58  5611.4 1849.25  5692.8 1848.71  5697.8 1849.53  5766.8  1848.7
#Mann= 6 ,-1 , 0
  4487.7     .05       0  4626.7      .1       0  4978.8     .16       0
  4997.6     .07       0  5003.6     .16       0  5611.4      .1       0
Bank Sta=4997.6,5003.6
XS Rating Curve= 0 ,0
Exp/Cntr=0.3,0.1

Type RM Length L Ch R = 1 ,19425   ,453,453,453
BEGIN DESCRIPTION:
SOUTH BRANCH WILLOW CREEK 35.0
END DESCRIPTION:
XS GIS Cut Line= 3
      2795006.85     10102183.17      2795354.08     10101592.89
      2795430.47      10100801.2
#Sta/Elev= 30
  4528.7 1837.36  4533.6 1837.19  4565.1 1835.19  4623.6 1834.22    4700 1831.04
    4805 1828.21  4832.8 1827.85    4858  1827.6  4916.2 1822.54  4993.6 1814.39
  4996.4 1813.89  4999.6 1814.39  5003.7  1814.6  5033.8 1821.15  5092.4 1822.32
    5108 1821.36  5113.8 1820.01  5135.3  1820.1    5273 1829.38  5309.7 1834.21
  5349.8 1837.65    5412 1840.33  5626.6 1843.55    5715 1846.26  5755.2 1845.15
  5831.2 1846.96  5836.2 1846.39  5905.9 1848.87  5946.1 1849.02  6008.9 1852.18
#Mann= 9 ,-1 , 0
  4528.7     .16       0  4533.6      .1       0    4700     .05       0
    4805     .16       0  4832.8     .05       0  4916.2     .16       0
  4993.6     .07       0  4999.6     .16       0  5349.8      .1       0
Bank Sta=4993.6,4999.6
XS Rating Curve= 0 ,0
Exp/Cntr=0.3,0.1

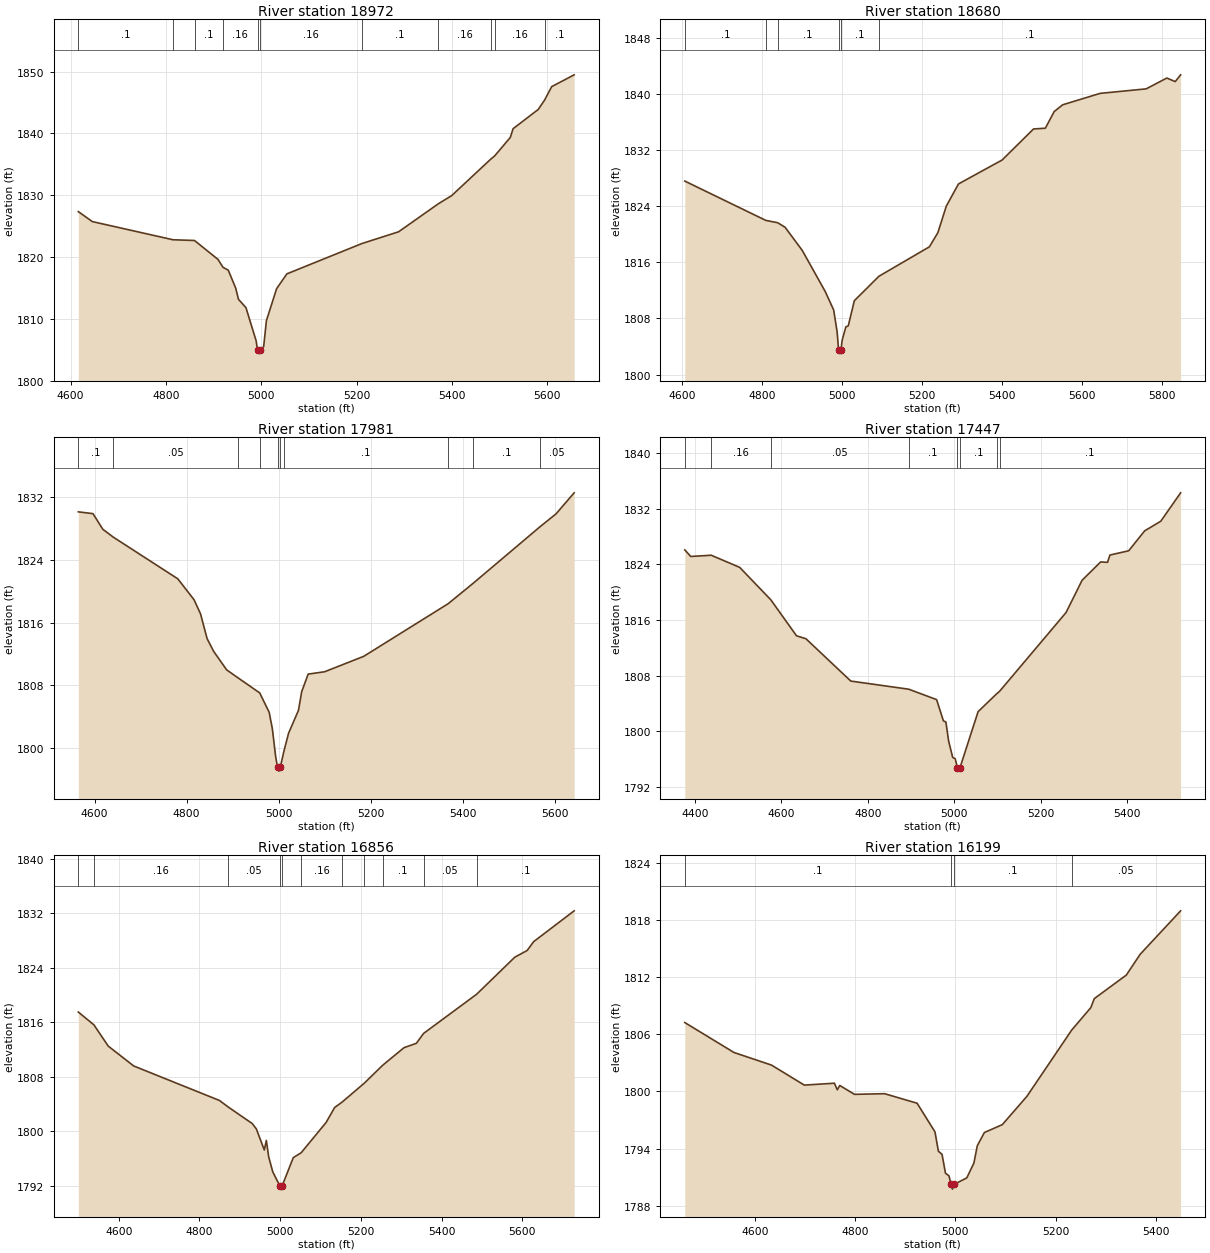
Type RM Length L Ch R = 1 ,18972   ,292,292,292
BEGIN DESCRIPTION:
SOUTH BRANCH WILLOW CREEK 34.0
END DESCRIPTION:
XS GIS Cut Line= 2
      2795423.53     10102328.98      2795951.29     10101433.18
#Sta/Elev= 30
  4616.4 1827.36  4645.7 1825.75  4814.9 1822.81    4860 1822.69  4909.3 1819.63
  4919.8 1818.35  4930.8 1817.89  4946.4 1814.99  4952.2 1813.18  4967.9 1811.83
  4989.3 1806.45  4992.1 1804.97  4994.9 1804.47  4998.1 1804.97    5005 1805.52
  5010.8 1809.73  5032.2  1814.9  5053.7 1817.29  5210.8 1822.19    5288  1824.1
  5371.5 1828.64  5399.3 1829.95  5481.5 1835.87  5489.6 1836.39  5522.2 1839.36
    5528 1840.77  5580.8 1843.89    5594 1845.39    5609 1847.58  5656.1 1849.49
#Mann= 11 ,-1 , 0
  4616.4      .1       0  4814.9     .05       0    4860      .1       0
  4919.8     .16       0  4992.1     .07       0  4998.1     .16       0
  5210.8      .1       0  5371.5     .16       0  5481.5      .1       0
  5489.6     .16       0    5594      .1       0
Bank Sta=4992.1,4998.1
XS Rating Curve= 0 ,0
Exp/Cntr=0.3,0.1

Type RM Length L Ch R = 1 ,18680   ,699,699,699
BEGIN DESCRIPTION:
SOUTH BRANCH WILLOW CREEK 33.0
END DESCRIPTION:
XS GIS Cut Line= 2
       2795624.9     10102495.68      2796291.04     10101447.91
#Sta/Elev= 30
    4606 1827.56  4808.9 1821.96  4838.6 1821.63  4857.2 1820.98  4900.1 1817.69
  4957.7 1811.83  4978.8  1809.2  4987.5 1806.07  4991.1 1803.56  4993.8 1803.06
  4997.1 1803.56    5000 1804.89  5009.3  1806.8  5015.3 1806.93  5030.5 1810.52
    5092    1814  5218.5  1818.2  5239.7 1820.21  5260.8 1823.99  5291.3 1827.15
  5400.6 1830.56  5479.3 1834.98  5508.9 1835.09    5531 1837.46  5552.1 1838.42
  5646.1 1840.05  5761.3 1840.69    5813 1842.23  5834.1 1841.73  5847.6 1842.69
#Mann= 6 ,-1 , 0
    4606      .1       0  4808.9     .05       0  4838.6      .1       0
  4991.1     .07       0  4997.1      .1       0    5092      .1       0
Bank Sta=4991.1,4997.1
XS Rating Curve= 0 ,0
Exp/Cntr=0.3,0.1

Type RM Length L Ch R = 1 ,17981   ,534,534,534
BEGIN DESCRIPTION:
SOUTH BRANCH WILLOW CREEK 32.0
END DESCRIPTION:
XS GIS Cut Line= 2
      2796076.33     10102856.75      2796861.02     10102120.66
#Sta/Elev= 30
  4564.9 1830.08  4596.7 1829.85  4618.1 1827.86  4640.6 1826.87  4780.8 1821.56
    4816  1818.9  4830.1  1817.1  4844.3 1813.96  4858.5 1812.34  4886.8 1809.98
  4910.6    1809  4958.5 1807.05  4979.1 1804.57  4985.9  1802.5  4992.9 1799.02
  4997.1  1797.6  4999.9  1797.1  5003.1  1797.6  5011.3  1799.7  5021.1 1801.92
  5042.6 1804.83  5049.5 1807.19  5063.6 1809.44  5099.3 1809.74  5184.2  1811.7
  5367.5  1818.4  5422.2 1821.02  5566.8 1828.19  5601.4 1829.82  5640.8  1832.5
#Mann= 10 ,-1 , 0
  4564.9      .1       0  4640.6     .05       0  4910.6      .1       0
  4958.5     .05       0  4997.1    .035       0  5003.1     .05       0
  5011.3      .1       0  5367.5     .05       0  5422.2      .1       0
  5566.8     .05       0
Bank Sta=4997.1,5003.1
XS Rating Curve= 0 ,0
Exp/Cntr=0.3,0.1

Type RM Length L Ch R = 1 ,17447   ,591,591,591
BEGIN DESCRIPTION:
SOUTH BRANCH WILLOW CREEK 31.0
END DESCRIPTION:
XS GIS Cut Line= 3
      2796326.28     10103141.51      2796777.69     10102898.44
      2797097.12     10102349.85
#Sta/Elev= 30
  4376.6  1826.1  4390.4 1825.15  4437.7 1825.33  4503.7 1823.58  4575.9  1818.9
  4635.1 1813.74    4657 1813.31  4760.8 1807.22  4894.8 1806.05  4959.4 1804.55
  4975.1  1801.5  4980.9 1801.32  4987.3 1798.56  4996.6 1796.23  5002.4 1796.05
  5007.5 1794.76  5010.2 1794.26  5013.5 1794.76  5055.4 1802.82  5098.2 1805.38
    5105 1805.74  5258.9 1817.08  5296.1 1821.73  5339.1 1824.37  5354.8  1824.3
  5360.6 1825.36  5403.9 1825.97  5440.9 1828.84  5478.1 1830.22  5524.1 1834.31
#Mann= 8 ,-1 , 0
  4376.6      .1       0  4437.7     .16       0  4575.9     .05       0
  4894.8      .1       0  5007.5     .07       0  5013.5      .1       0
  5098.2     .05       0    5105      .1       0
Bank Sta=5007.5,5013.5
XS Rating Curve= 0 ,0
Exp/Cntr=0.3,0.1

Type RM Length L Ch R = 1 ,16856   ,657,657,657
BEGIN DESCRIPTION:
SOUTH BRANCH WILLOW CREEK 30.0
END DESCRIPTION:
XS GIS Cut Line= 2
      2796534.65     10103342.89      2797742.98     10103120.66
#Sta/Elev= 30
  4499.8 1817.51  4538.4 1815.63  4573.9 1812.51  4637.1 1809.59  4849.4 1804.53
  4871.4 1803.56  4930.7 1801.14  4940.9 1800.35  4960.6 1797.26  4965.7 1798.66
  4971.4 1796.27  4981.6 1794.05  4998.9 1792.01  5001.6 1791.51  5004.9 1792.01
  5032.4 1796.13  5051.9 1796.85  5113.7 1801.29    5135  1803.5    5153 1804.27
  5207.9 1807.04  5254.2 1809.71  5306.9 1812.28  5337.4 1812.92  5355.3 1814.37
  5486.7 1820.12  5581.5 1825.57    5612 1826.55  5627.9 1827.84  5728.4 1832.37
#Mann= 11 ,-1 , 0
  4499.8      .1       0  4538.4     .16       0  4871.4     .05       0
  4998.9    .035       0  5004.9     .05       0  5051.9     .16       0
    5153      .1       0  5207.9     .05       0  5254.2      .1       0
  5355.3     .05       0  5486.7      .1       0
Bank Sta=4998.9,5004.9
XS Rating Curve= 0 ,0
Exp/Cntr=0.3,0.1

Type RM Length L Ch R = 1 ,16199   ,633,633,633
BEGIN DESCRIPTION:
SOUTH BRANCH WILLOW CREEK 29.0
END DESCRIPTION:
XS GIS Cut Line= 3
      2796930.48     10103745.67       2797388.8     10103780.39
      2797777.67     10103419.29
#Sta/Elev= 30
  4459.5 1807.23  4557.8 1804.09  4632.7 1802.77  4698.2 1800.67  4758.3 1800.87
  4764.1 1800.18  4769.1 1800.63  4798.5  1799.7  4858.6 1799.77  4923.5 1798.77
  4959.2 1795.76    4966 1793.74  4973.3  1793.4  4980.2 1791.42    4987 1791.17
  4991.4 1790.26  4994.1 1789.76  4997.4 1790.26  5022.7 1790.94  5036.9 1792.49
  5043.7 1794.31  5057.9  1795.7  5093.6 1796.52  5142.9  1799.5  5232.2 1806.44
  5270.5  1808.8  5277.3 1809.74  5341.3 1812.21  5369.1  1814.4  5449.8 1818.95
#Mann= 4 ,-1 , 0
  4459.5      .1       0  4991.4     .07       0  4997.4      .1       0
  5232.2     .05       0
Bank Sta=4991.4,4997.4
XS Rating Curve= 0 ,0
Exp/Cntr=0.3,0.1