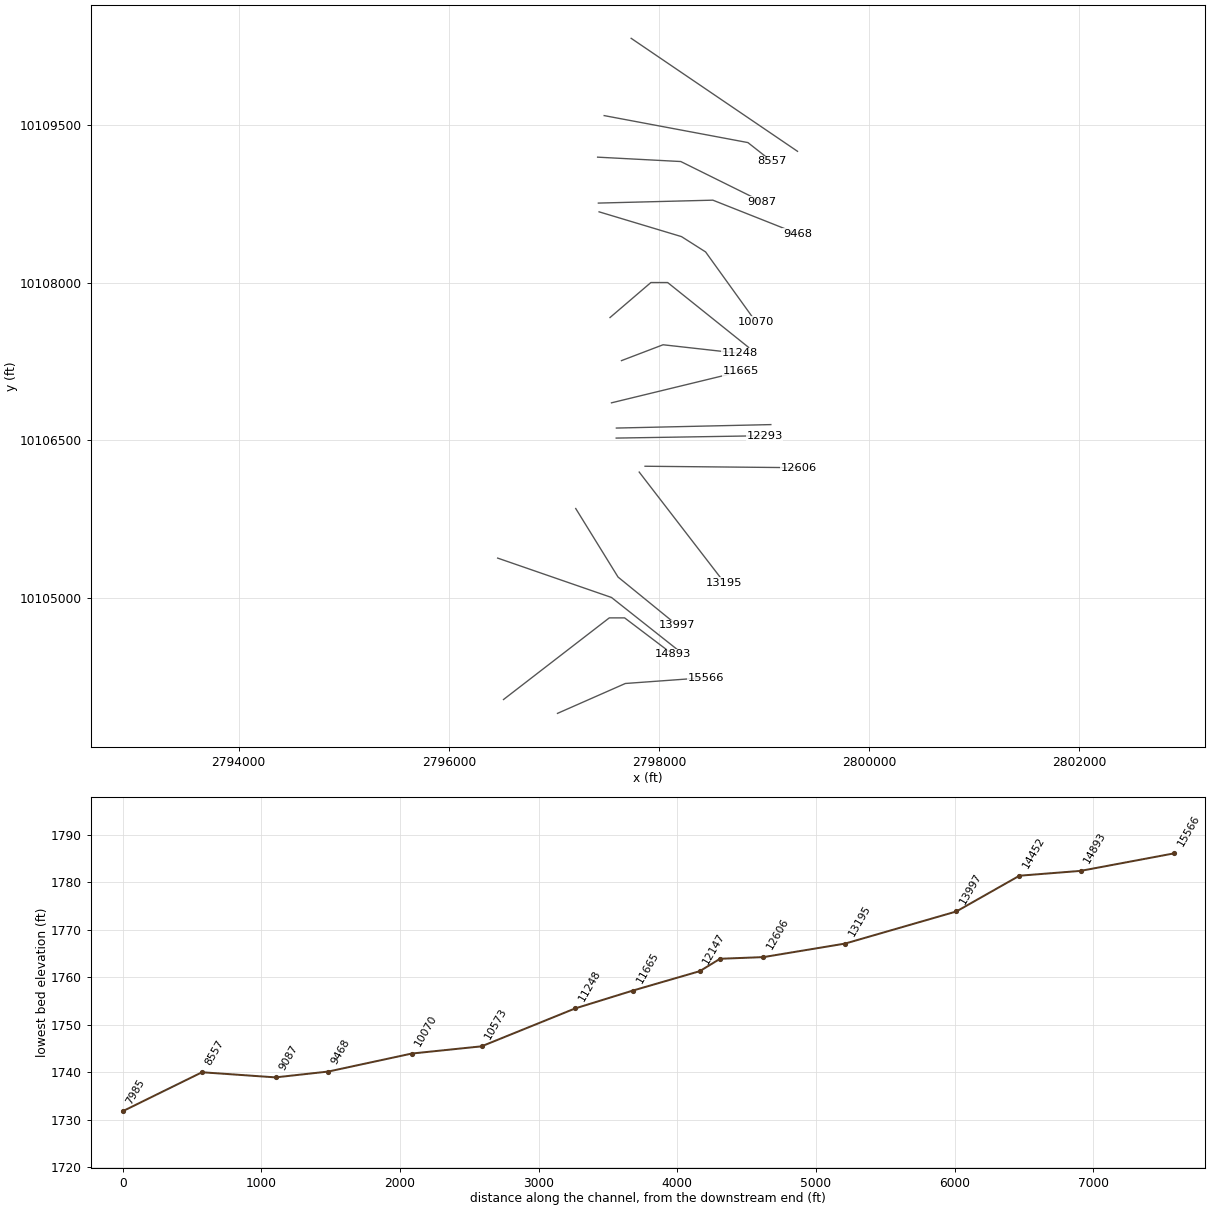
HEC-RAS study SOUTH BRANCH WILLOW CREEK.prj: SOUTH BRANCH WILLOW CREEK Base Level Engineering

--- SOUTH BRANCH WILLOW CREEK.g01 (geometry) --- (continued)

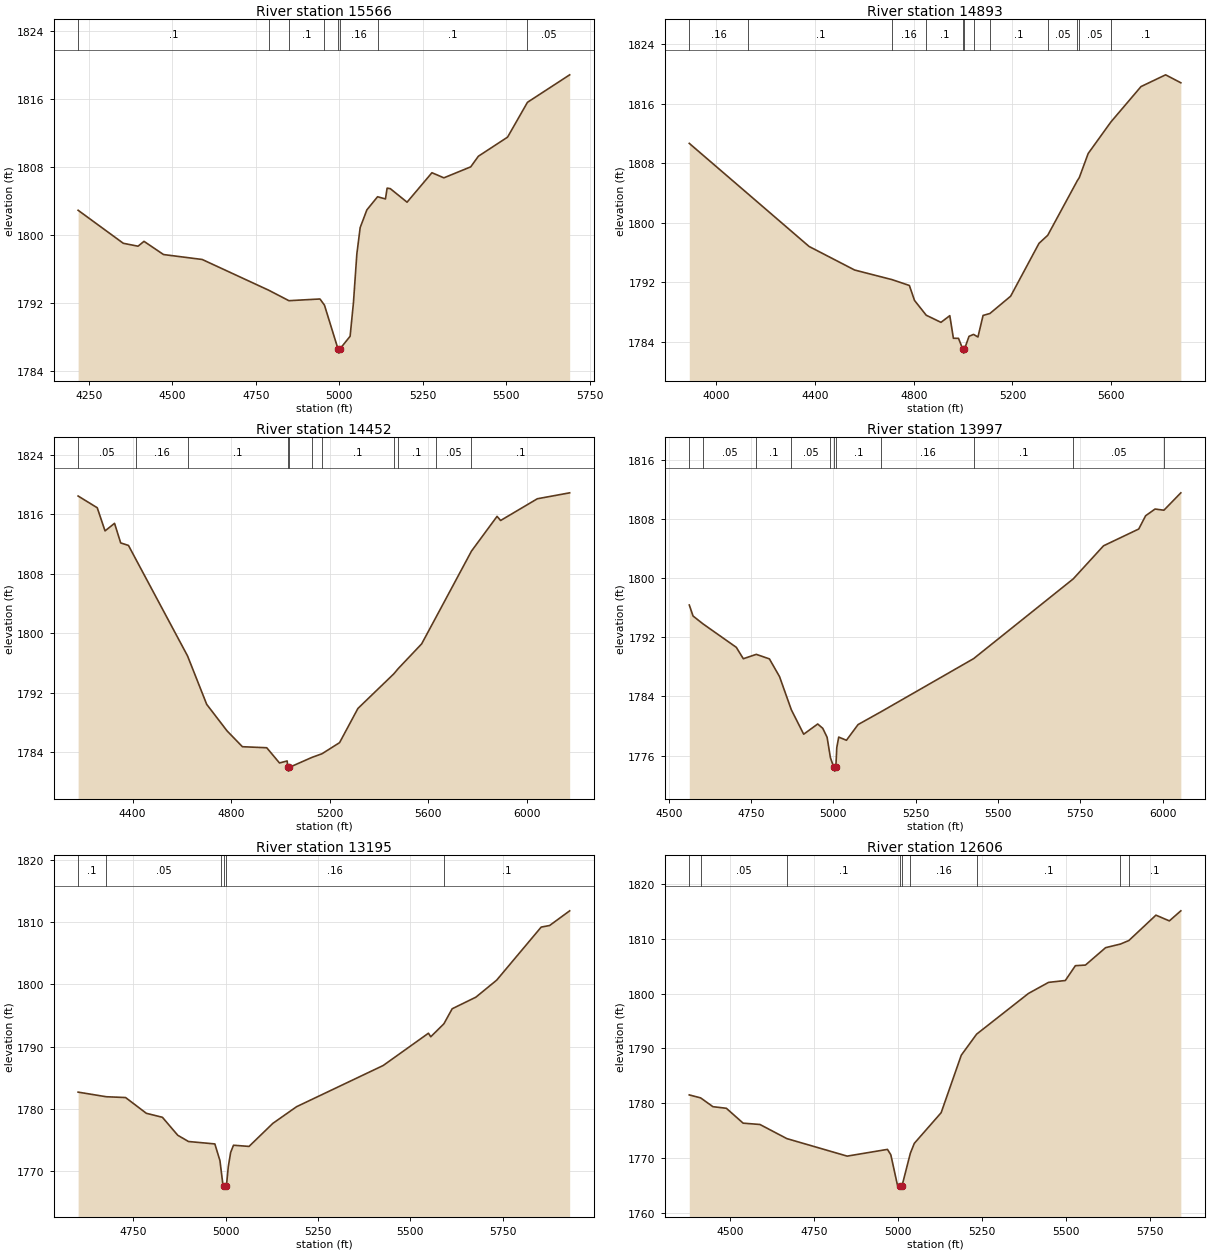
Type RM Length L Ch R = 1 ,15566   ,673,673,673
BEGIN DESCRIPTION:
SOUTH BRANCH WILLOW CREEK 28.0
END DESCRIPTION:
XS GIS Cut Line= 3
      2797034.62     10103898.44      2797680.47     10104183.17
      2798443.93     10104238.69
#Sta/Elev= 30
  4218.2  1802.9  4353.5 1799.02  4397.6 1798.68  4415.4 1799.25  4473.8  1797.7
  4589.6 1797.12  4789.2  1793.5  4849.1 1792.28  4942.1 1792.48  4955.6 1791.75
    4996 1786.62  4998.7 1786.12    5002 1786.62  5032.3  1788.1  5042.3 1792.04
  5052.4 1797.74  5062.4 1800.86  5082.4 1802.94  5114.5 1804.49  5138.1 1804.23
  5143.1  1805.5  5152.6 1805.44  5202.8 1803.85  5277.2 1807.31    5313 1806.71
  5393.3    1808  5416.3 1809.25  5503.6 1811.49  5563.1 1815.58  5689.5 1818.81
#Mann= 8 ,-1 , 0
  4218.2      .1       0  4789.2     .05       0  4849.1      .1       0
  4955.6     .16       0    4996     .07       0    5002     .16       0
  5114.5      .1       0  5563.1     .05       0
Bank Sta=4996,5002
XS Rating Curve= 0 ,0
Exp/Cntr=0.3,0.1

Type RM Length L Ch R = 1 ,14893   ,441,441,441
BEGIN DESCRIPTION:
SOUTH BRANCH WILLOW CREEK 27.0
END DESCRIPTION:
XS GIS Cut Line= 4
      2796520.76      10104030.4      2797527.69     10104808.17
      2797673.52     10104808.17      2798131.88     10104460.92
#Sta/Elev= 30
  3889.7 1810.66  4129.1 1803.83  4375.5 1796.79  4560.2 1793.62  4712.6 1792.32
  4782.2 1791.54    4803 1789.53  4850.5 1787.54  4910.3 1786.58  4946.1 1787.48
  4960.6 1784.44  4981.4 1784.43  4999.2 1782.94    5002 1782.44  5005.2 1782.94
    5024  1784.7  5042.4 1784.96  5060.2 1784.61    5081 1787.51  5108.7 1787.77
  5192.8  1790.1  5307.8 1797.21  5343.1 1798.29  5463.5 1805.66  5471.1 1806.05
  5507.1 1809.29  5599.1 1813.53  5721.4  1818.3  5821.2 1819.88  5882.9 1818.81
#Mann= 12 ,-1 , 0
  3889.7     .16       0  4129.1      .1       0  4712.6     .16       0
  4850.5      .1       0  4999.2     .07       0  5005.2      .1       0
  5042.4     .16       0  5108.7      .1       0  5343.1     .05       0
  5463.5     .16       0  5471.1     .05       0  5599.1      .1       0
Bank Sta=4999.2,5005.2
XS Rating Curve= 0 ,0
Exp/Cntr=0.3,0.1

Type RM Length L Ch R = 1 ,14452   ,455,455,455
BEGIN DESCRIPTION:
SOUTH BRANCH WILLOW CREEK 26.0
END DESCRIPTION:
XS GIS Cut Line= 3
      2796465.17     10105377.62      2797548.52     10105002.61
      2798214.32     10104475.52
#Sta/Elev= 30
    4179 1818.49  4256.6 1816.91  4288.3 1813.79  4326.9 1814.81  4351.8 1812.17
  4383.5 1811.83  4412.2 1810.04  4623.3 1796.94    4701 1790.42  4783.7 1786.84
    4846 1784.71  4944.8 1784.57  4996.5 1782.52  5027.7 1782.79    5030 1781.92
  5032.7 1781.42    5036 1781.92  5128.9 1783.28  5169.1 1783.76  5240.5 1785.26
  5314.8 1789.86  5460.7 1794.53  5477.6  1795.2  5573.7 1798.57  5632.3 1802.18
    5776 1811.07  5879.8 1815.75  5894.2 1815.19  6043.3 1818.12  6174.6 1818.92
#Mann= 11 ,-1 , 0
    4179     .05       0  4412.2     .16       0  4623.3      .1       0
    5030     .07       0    5036      .1       0  5128.9     .16       0
  5169.1      .1       0  5460.7     .05       0  5477.6      .1       0
  5632.3     .05       0    5776      .1       0
Bank Sta=5030,5036
XS Rating Curve= 0 ,0
Exp/Cntr=0.3,0.1

Type RM Length L Ch R = 1 ,13997   ,802,802,802
BEGIN DESCRIPTION:
SOUTH BRANCH WILLOW CREEK 25.0
END DESCRIPTION:
XS GIS Cut Line= 3
      2797208.23     10105849.86      2797611.02     10105197.05
      2798173.48     10104738.76
#Sta/Elev= 30
  4562.3 1796.34  4573.8 1794.85  4604.6 1793.77  4705.1 1790.62  4726.4 1789.08
  4765.8 1789.67  4805.6 1789.06  4836.4 1786.66  4872.2 1782.18  4909.7 1778.88
  4952.3 1780.26  4967.7 1779.67  4980.8 1778.46  4990.9  1775.7  5001.3 1774.39
    5004 1773.89  5007.3 1774.39  5010.2 1777.07  5016.1 1778.49  5039.5 1778.06
  5074.8 1780.18  5145.6 1781.94  5425.6 1789.09  5728.2 1799.87  5820.1 1804.34
  5927.1 1806.61  5947.9  1808.4  5976.6 1809.31  6003.5 1809.15  6054.9  1811.5
#Mann= 11 ,-1 , 0
  4562.3     .16       0  4604.6     .05       0  4765.8      .1       0
  4872.2     .05       0  4990.9      .1       0  5001.3     .07       0
  5007.3      .1       0  5145.6     .16       0  5425.6      .1       0
  5728.2     .05       0  6003.5      .1       0
Bank Sta=5001.3,5007.3
XS Rating Curve= 0 ,0
Exp/Cntr=0.3,0.1

Type RM Length L Ch R = 1 ,13195   ,589,589,589
BEGIN DESCRIPTION:
SOUTH BRANCH WILLOW CREEK 23.0
END DESCRIPTION:
XS GIS Cut Line= 2
      2797812.39     10106197.08      2798624.19     10105142.44
#Sta/Elev= 30
  4600.7 1782.71  4676.8 1781.97  4729.2 1781.84  4785.4 1779.31  4828.9 1778.67
  4870.5 1775.78  4899.5 1774.78  4970.9 1774.39  4984.7 1771.71    4988 1770.12
  4992.9 1767.76  4996.2 1767.63  4998.9 1767.13  5002.2 1767.63  5007.4 1770.77
  5013.7 1773.03  5021.4 1774.18  5063.5 1773.99  5127.9 1777.69  5192.2 1780.37
  5426.8 1786.99  5549.2 1792.17  5555.5  1791.6  5591.1 1793.69  5613.5  1796.1
  5677.6 1797.96    5734  1800.7  5854.5 1809.22  5877.2 1809.47  5931.6 1811.83
#Mann= 6 ,-1 , 0
  4600.7      .1       0  4676.8     .05       0    4988     .16       0
  4996.2     .07       0  5002.2     .16       0  5591.1      .1       0
Bank Sta=4996.2,5002.2
XS Rating Curve= 0 ,0
Exp/Cntr=0.3,0.1

Type RM Length L Ch R = 1 ,12606   ,313,313,313
BEGIN DESCRIPTION:
SOUTH BRANCH WILLOW CREEK 22.0
END DESCRIPTION:
XS GIS Cut Line= 2
      2797868.01     10106252.61      2799332.64     10106238.73
#Sta/Elev= 30
  4377.4 1781.49  4411.2 1780.95  4447.9 1779.34  4487.9 1779.05  4537.9 1776.33
  4587.9 1776.09  4668.1 1773.51  4847.9 1770.31  4967.9 1771.54  4977.9 1770.56
  4997.9 1764.96  5004.9 1764.78  5007.6 1764.28  5010.9 1764.78  5036.1 1770.83
  5047.9 1772.64  5127.9 1778.24  5187.9 1788.75  5233.6 1792.59  5387.9 1800.02
  5447.9 1802.05  5497.9 1802.39  5527.9  1805.1  5557.9 1805.21  5617.9 1808.39
  5662.1 1809.05  5687.2 1809.69  5767.9 1814.33  5807.9 1813.28  5842.1 1815.12
#Mann= 9 ,-1 , 0
  4377.4      .1       0  4411.2     .05       0  4668.1      .1       0
  5004.9     .07       0  5010.9      .1       0  5036.1     .16       0
  5233.6      .1       0  5662.1     .05       0  5687.2      .1       0
Bank Sta=5004.9,5010.9
XS Rating Curve= 0 ,0
Exp/Cntr=0.3,0.1

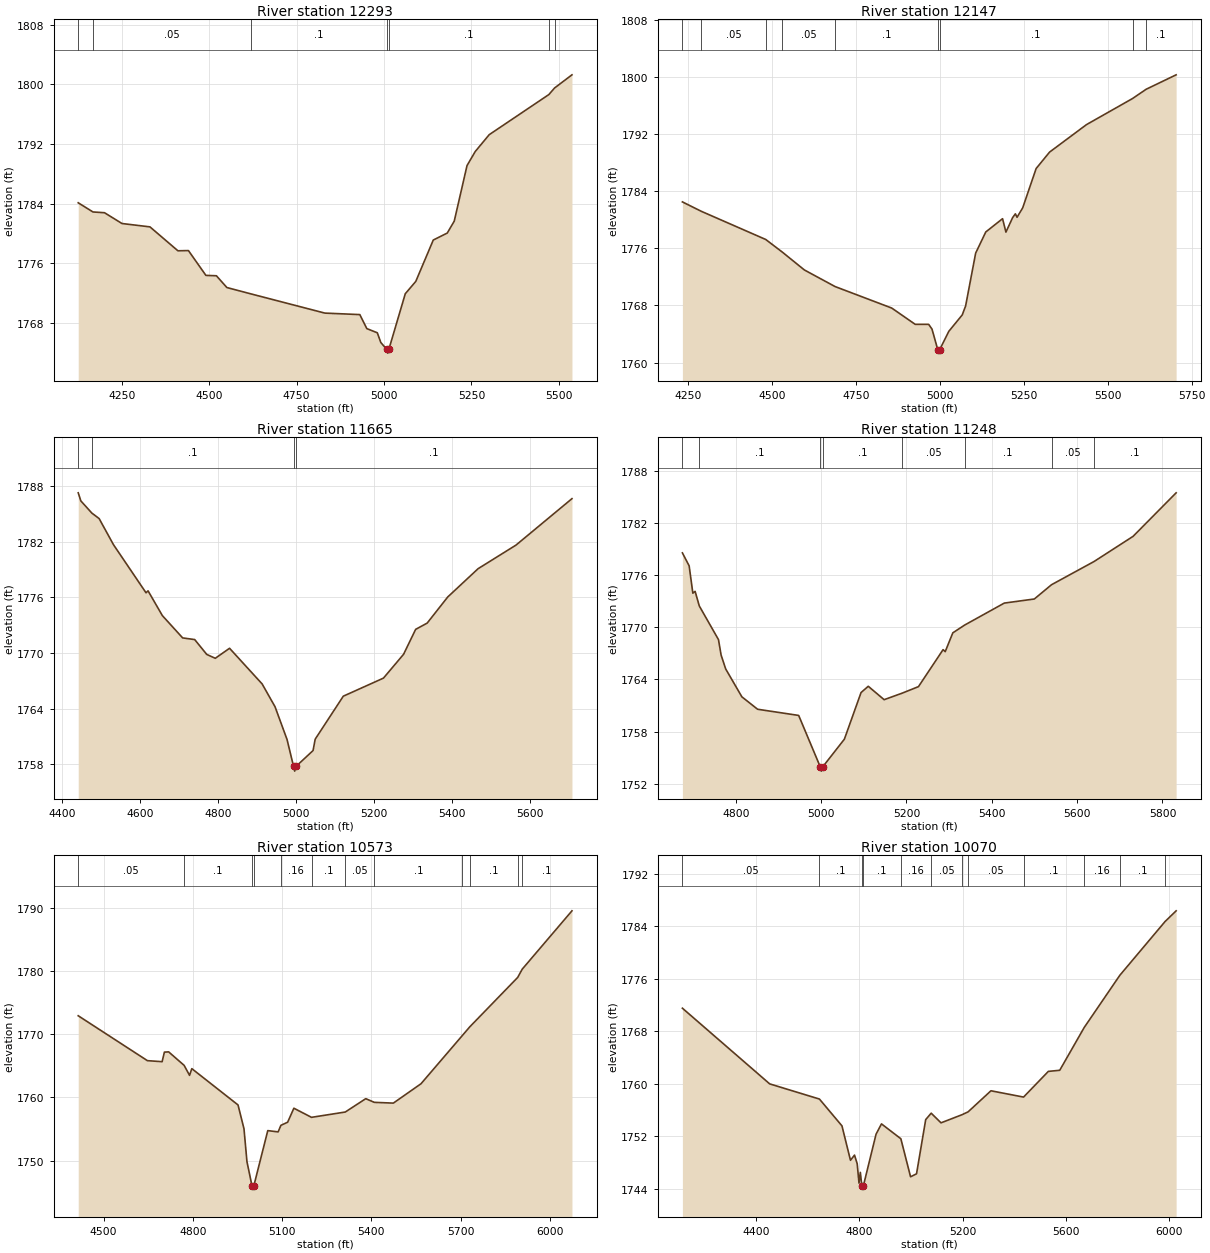
Type RM Length L Ch R = 1 ,12293   ,146,146,146
BEGIN DESCRIPTION:
Mapping XS aa8c22ca
END DESCRIPTION:
XS GIS Cut Line= 2
      2797593.37     10106520.96      2799004.99      10106543.5
#Sta/Elev= 30
  4125.7  1784.1  4167.9 1782.87  4200.8 1782.77  4250.8 1781.32  4330.8 1780.87
  4410.8 1777.66  4440.8 1777.69  4490.8 1774.36  4520.8 1774.31  4550.8 1772.73
  4618.6 1771.89  4830.9  1769.3  4930.9  1769.1  4950.9 1767.22  4980.9 1766.66
  4990.9 1765.36  5007.9 1764.43  5010.7 1763.93  5013.9 1764.43  5060.9  1771.9
  5090.9 1773.55  5140.9  1779.1  5180.9 1780.04  5200.9 1781.64  5237.4 1789.09
  5260.9 1790.98  5300.9 1793.24  5471.4 1798.62  5487.7  1799.5  5537.5 1801.27
#Mann= 7 ,-1 , 0
  4125.7      .1       0  4167.9     .05       0  4618.6      .1       0
  5007.9     .07       0  5013.9      .1       0  5471.4     .16       0
  5487.7      .1       0
Bank Sta=5007.9,5013.9
XS Rating Curve= 0 ,0
Exp/Cntr=0.3,0.1

Type RM Length L Ch R = 1 ,12147   ,482,482,482
BEGIN DESCRIPTION:
SOUTH BRANCH WILLOW CREEK 20.0
END DESCRIPTION:
XS GIS Cut Line= 2
      2797595.14     10106616.44      2799065.37     10106649.39
#Sta/Elev= 30
  4233.2 1782.49  4288.8 1781.19  4481.4 1777.23  4530.6 1775.47  4596.6 1772.96
  4687.9 1770.64  4856.7 1767.63  4926.7 1765.35  4966.7 1765.35  4976.7 1764.68
  4993.7 1761.82  4996.5 1761.32  4999.7 1761.82  5026.7 1764.37  5066.7 1766.67
  5076.7 1767.91  5106.7 1775.32  5136.8 1778.28  5186.8 1780.14  5196.8 1778.26
  5216.8 1780.29    5225 1780.82    5230 1780.34  5246.8 1781.66  5286.8 1787.16
  5326.8 1789.46  5436.8 1793.31  5573.9 1796.96  5614.5 1798.26  5703.8 1800.28
#Mann= 9 ,-1 , 0
  4233.2      .1       0  4288.8     .05       0  4481.4      .1       0
  4530.6     .05       0  4687.9      .1       0  4993.7     .07       0
  4999.7      .1       0  5573.9     .05       0  5614.5      .1       0
Bank Sta=4993.7,4999.7
XS Rating Curve= 0 ,0
Exp/Cntr=0.3,0.1

Type RM Length L Ch R = 1 ,11665   ,417,417,417
BEGIN DESCRIPTION:
SOUTH BRANCH WILLOW CREEK 19.0
END DESCRIPTION:
XS GIS Cut Line= 2
      2797548.54     10106856.78      2798777.69     10107155.39
#Sta/Elev= 30
  4442.2 1787.28  4448.9 1786.41  4477.2 1785.09  4495.8  1784.5  4532.4 1781.69
  4615.9 1776.49  4621.1  1776.7  4657.7 1774.03  4709.7 1771.62  4740.6 1771.44
  4771.4 1769.84  4793.3 1769.42  4829.9  1770.5  4913.4 1766.65  4946.4 1764.19
  4977.2 1760.65  4993.9 1757.74  4996.7 1757.24  4999.9 1757.74  5043.8 1759.46
  5049.3 1760.69  5121.3 1765.33  5224.2 1767.28  5275.7 1769.85  5306.6 1772.54
  5336.2 1773.22  5388.9 1776.04  5466.6 1779.09  5563.8 1781.64  5707.1 1786.65
#Mann= 4 ,-1 , 0
  4442.2     .05       0  4477.2      .1       0  4993.9     .07       0
  4999.9      .1       0
Bank Sta=4993.9,4999.9
XS Rating Curve= 0 ,0
Exp/Cntr=0.3,0.1

Type RM Length L Ch R = 1 ,11248   ,675,675,675
BEGIN DESCRIPTION:
SOUTH BRANCH WILLOW CREEK 18.0
END DESCRIPTION:
XS GIS Cut Line= 3
      2797643.75     10107258.81      2798039.57     10107409.85
      2798768.76     10107328.25
#Sta/Elev= 30
  4674.7 1778.55  4690.5 1777.06  4699.2 1773.92  4704.5 1774.13  4714.3 1772.45
  4759.3 1768.58  4765.4 1766.82  4776.1 1765.22  4814.1 1762.01    4851 1760.58
  4947.3 1759.87  4997.8 1753.97  5000.6 1753.47  5003.8 1753.97  5054.4 1757.14
  5093.5  1762.5  5110.4 1763.22  5147.6 1761.68  5189.9 1762.43  5228.1 1763.18
  5285.8 1767.43  5290.8  1767.2  5308.6 1769.36  5336.2 1770.25  5429.3 1772.78
  5499.7 1773.25    5540 1774.89  5639.8 1777.56  5731.2 1780.45  5832.1 1785.45
#Mann= 8 ,-1 , 0
  4674.7     .05       0  4714.3      .1       0  4997.8     .07       0
  5003.8      .1       0  5189.9     .05       0  5336.2      .1       0
    5540     .05       0  5639.8      .1       0
Bank Sta=4997.8,5003.8
XS Rating Curve= 0 ,0
Exp/Cntr=0.3,0.1

Type RM Length L Ch R = 1 ,10573   ,503,503,503
BEGIN DESCRIPTION:
SOUTH BRANCH WILLOW CREEK 17.0
END DESCRIPTION:
XS GIS Cut Line= 4
      2797534.65     10107669.29      2797923.52     10108002.61
      2798083.24     10108002.61      2798853.75     10107384.81
#Sta/Elev= 30
  4414.5  1772.9  4647.1  1765.8  4696.5 1765.64  4704.1 1767.15  4718.4 1767.19
  4770.4 1765.06  4788.7 1763.48  4796.3 1764.54  4951.6  1758.8  4971.6 1755.04
  4981.6 1749.84  4998.6 1745.99  5001.4 1745.49  5004.6 1745.99  5051.6 1754.74
  5086.4 1754.54  5095.8 1755.58  5118.4 1756.07  5139.3 1758.28  5198.6 1756.84
  5312.1 1757.68  5380.9 1759.79  5409.8 1759.21  5473.7 1759.09  5566.6 1762.15
  5705.3 1769.76  5730.6 1771.15  5891.6 1778.96  5906.9 1780.27    6074 1789.49
#Mann= 12 ,-1 , 0
  4414.5     .05       0  4770.4      .1       0  4998.6     .07       0
  5004.6      .1       0  5095.8     .16       0  5198.6      .1       0
  5312.1     .05       0  5409.8      .1       0  5705.3     .05       0
  5730.6      .1       0  5891.6     .05       0  5906.9      .1       0
Bank Sta=4998.6,5004.6
XS Rating Curve= 0 ,0
Exp/Cntr=0.3,0.1

Type RM Length L Ch R = 1 ,10070   ,602,602,602
BEGIN DESCRIPTION:
SOUTH BRANCH WILLOW CREEK 16.0
END DESCRIPTION:
XS GIS Cut Line= 4
      2797430.43     10108676.23      2798215.19     10108440.11
      2798444.35     10108294.28      2798923.09     10107628.22
#Sta/Elev= 30
  4115.5 1771.51  4453.4 1759.99    4646 1757.68  4733.2  1753.6  4766.2 1748.36
  4781.8 1749.15  4792.2 1747.83  4799.2 1744.88  4804.4 1746.52  4810.1 1744.47
  4812.9 1743.97  4816.1 1744.47  4865.2 1752.33  4886.2  1753.9  4961.2 1751.64
  4998.8 1745.85  5021.9  1746.3  5057.4 1754.55  5078.6 1755.53  5116.7 1754.06
  5198.9 1755.31  5221.5 1755.73    5310 1758.94  5436.2 1757.98  5532.2 1761.89
  5576.3 1762.06  5670.8 1768.56  5808.8 1776.51  5983.6 1784.68  6026.9 1786.33
#Mann= 12 ,-1 , 0
  4115.5     .05       0    4646      .1       0  4810.1     .07       0
  4816.1      .1       0  4961.2     .16       0  5078.6     .05       0
  5198.9      .1       0  5221.5     .05       0  5436.2      .1       0
  5670.8     .16       0  5808.8      .1       0  5983.6     .05       0
Bank Sta=4810.1,4816.1
XS Rating Curve= 0 ,0
Exp/Cntr=0.3,0.1

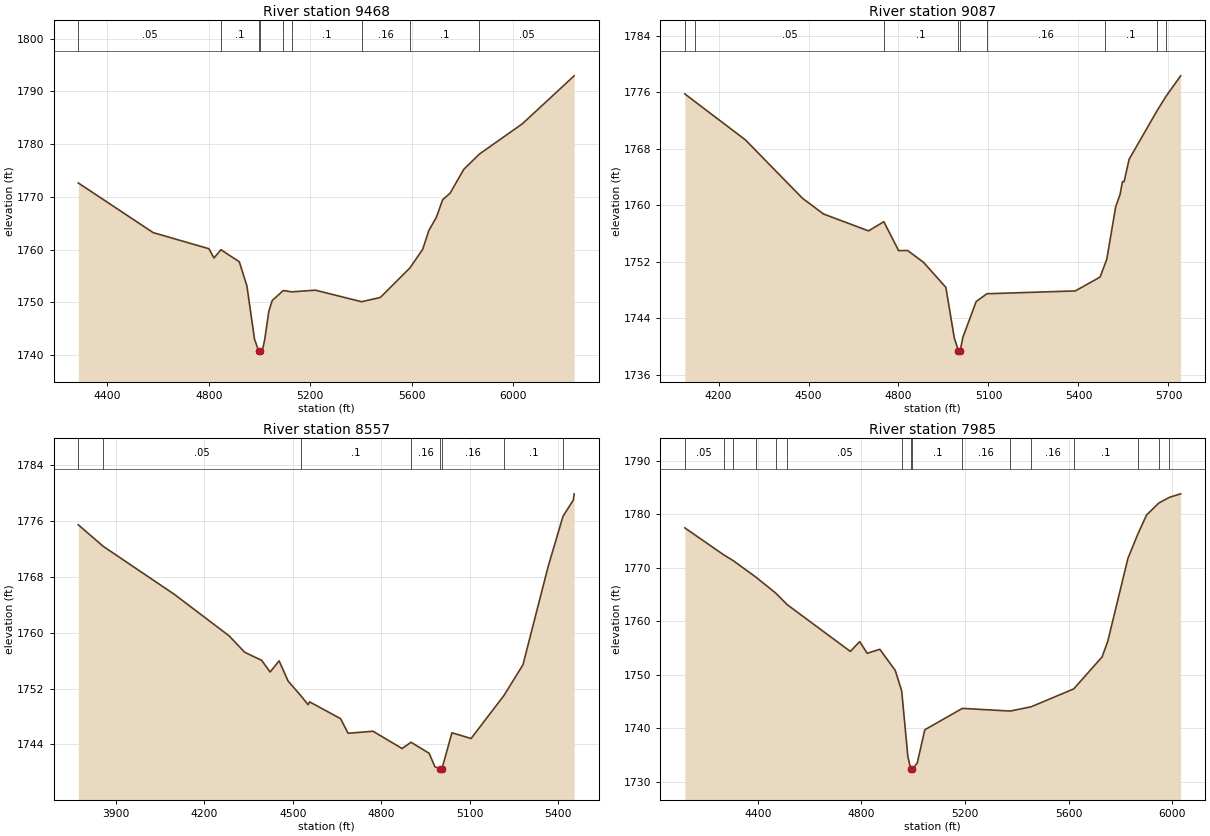
Type RM Length L Ch R = 1 ,9468    ,381,381,381
BEGIN DESCRIPTION:
SOUTH BRANCH WILLOW CREEK 15.0
END DESCRIPTION:
XS GIS Cut Line= 3
      2797423.57     10108759.56       2798513.8     10108787.33
      2799318.27     10108468.32
#Sta/Elev= 30
  4285.4 1772.64  4580.4 1763.23  4800.5 1760.17  4820.5 1758.42    4848 1759.98
  4920.5 1757.69  4950.5 1753.11  4980.5 1743.01  4997.5 1740.68  5000.3 1740.18
  5003.5 1740.68  5010.5 1740.69  5020.5 1742.88  5036.9 1748.31  5050.5 1750.36
  5093.9 1752.24  5127.2 1751.99  5220.6 1752.31  5402.6 1750.12  5476.6 1750.92
  5593.8 1756.55    5644 1760.07  5668.3 1763.64    5698 1766.14  5722.4 1769.44
  5752.1 1770.71  5806.1 1775.23  5867.2 1778.11  6037.2 1783.87  6241.4 1792.96
#Mann= 9 ,-1 , 0
  4285.4     .05       0    4848      .1       0  4997.5     .07       0
  5003.5      .1       0  5093.9     .16       0  5127.2      .1       0
  5402.6     .16       0  5593.8      .1       0  5867.2     .05       0
Bank Sta=4997.5,5003.5
XS Rating Curve= 0 ,0
Exp/Cntr=0.3,0.1

Type RM Length L Ch R = 1 ,9087    ,530,530,530
BEGIN DESCRIPTION:
SOUTH BRANCH WILLOW CREEK 14.0
END DESCRIPTION:
XS GIS Cut Line= 3
       2797416.6     10109197.05      2798208.24     10109155.39
      2798979.07     10108773.45
#Sta/Elev= 30
  4087.6 1775.76  4122.4 1774.63  4289.7 1769.25    4480 1760.99  4550.1 1758.77
  4700.3 1756.38  4751.2 1757.68  4800.4 1753.59  4830.5 1753.61  4883.3 1751.94
    4958 1748.39    4986 1741.25  4999.9 1739.45  5002.6 1738.95  5005.9 1739.45
  5014.5 1741.31  5059.1  1746.4    5095 1747.49  5389.6 1747.89  5472.1 1749.85
  5489.1 1751.77  5494.4 1752.37  5524.1 1759.78    5539 1761.58  5546.6 1763.35
  5552.1 1763.33    5569 1766.52  5662.7 1773.42  5692.8 1775.47  5740.6 1778.31
#Mann= 9 ,-1 , 0
  4087.6      .1       0  4122.4     .05       0  4751.2      .1       0
  4999.9     .07       0  5005.9      .1       0    5095     .16       0
  5489.1      .1       0  5662.7     .16       0  5692.8     .05       0
Bank Sta=4999.9,5005.9
XS Rating Curve= 0 ,0
Exp/Cntr=0.3,0.1

Type RM Length L Ch R = 1 ,8557    ,572,572,572
BEGIN DESCRIPTION:
SOUTH BRANCH WILLOW CREEK 13.0
END DESCRIPTION:
XS GIS Cut Line= 3
      2797479.07     10109592.89      2798847.13     10109335.94
      2799074.86     10109156.53
#Sta/Elev= 30
  3772.7 1775.47  3857.3 1772.38  4097.7 1765.53  4284.4 1759.55  4336.9 1757.21
  4394.5 1756.05  4423.3 1754.38  4453.8 1755.98  4484.3 1753.08    4527 1751.01
  4552.1  1749.7  4557.2  1750.1  4662.2 1747.69  4687.8  1745.6  4772.3 1745.89
    4871 1743.41  4901.2 1744.31  4962.5 1742.74  4982.4 1740.79  5000.2 1740.53
    5003 1740.03  5006.2 1740.53    5040 1745.67    5105 1744.85  5216.4 1751.01
    5281 1755.42    5367 1769.59  5416.8 1776.69  5451.9 1779.03  5454.6 1779.91
#Mann= 8 ,-1 , 0
  3772.7      .1       0  3857.3     .05       0    4527      .1       0
  4901.2     .16       0  5000.2     .07       0  5006.2     .16       0
  5216.4      .1       0  5416.8     .16       0
Bank Sta=5000.2,5006.2
XS Rating Curve= 0 ,0
Exp/Cntr=0.3,0.1

Type RM Length L Ch R = 1 ,7985    ,804,804,804
BEGIN DESCRIPTION:
SOUTH BRANCH WILLOW CREEK 12.0
END DESCRIPTION:
XS GIS Cut Line= 2
      2797736.05     10110328.98      2799319.33     10109252.63
#Sta/Elev= 30
  4118.2  1777.5  4268.2 1772.46  4304.1  1771.4  4391.2 1768.34  4468.6 1765.33
  4514.1 1763.12  4757.5 1754.39  4793.4 1756.23  4822.5 1754.04  4871.3 1754.79
    4931 1750.82  4955.7    1747  4979.6 1734.72    4991 1732.32  4993.7 1731.82
    4997 1732.32  5015.9 1733.56  5044.9 1739.74  5189.9 1743.74  5374.9 1743.24
  5455.4 1744.04  5619.9 1747.38  5729.4 1753.36  5751.3 1756.27  5829.2 1771.78
  5866.7 1776.24    5901 1779.89  5948.8 1782.15  5989.7 1783.21  6032.7 1783.86
#Mann= 16 ,-1 , 0
  4118.2     .05       0  4268.2      .1       0  4304.1     .16       0
  4391.2     .05       0  4468.6      .1       0  4514.1     .05       0
  4955.7      .1       0    4991     .07       0    4997      .1       0
  5189.9     .16       0  5374.9      .1       0  5455.4     .16       0
  5619.9      .1       0  5866.7     .16       0  5948.8      .1       0
  5989.7     .16       0
Bank Sta=4991,4997
XS Rating Curve= 0 ,0
Exp/Cntr=0.3,0.1