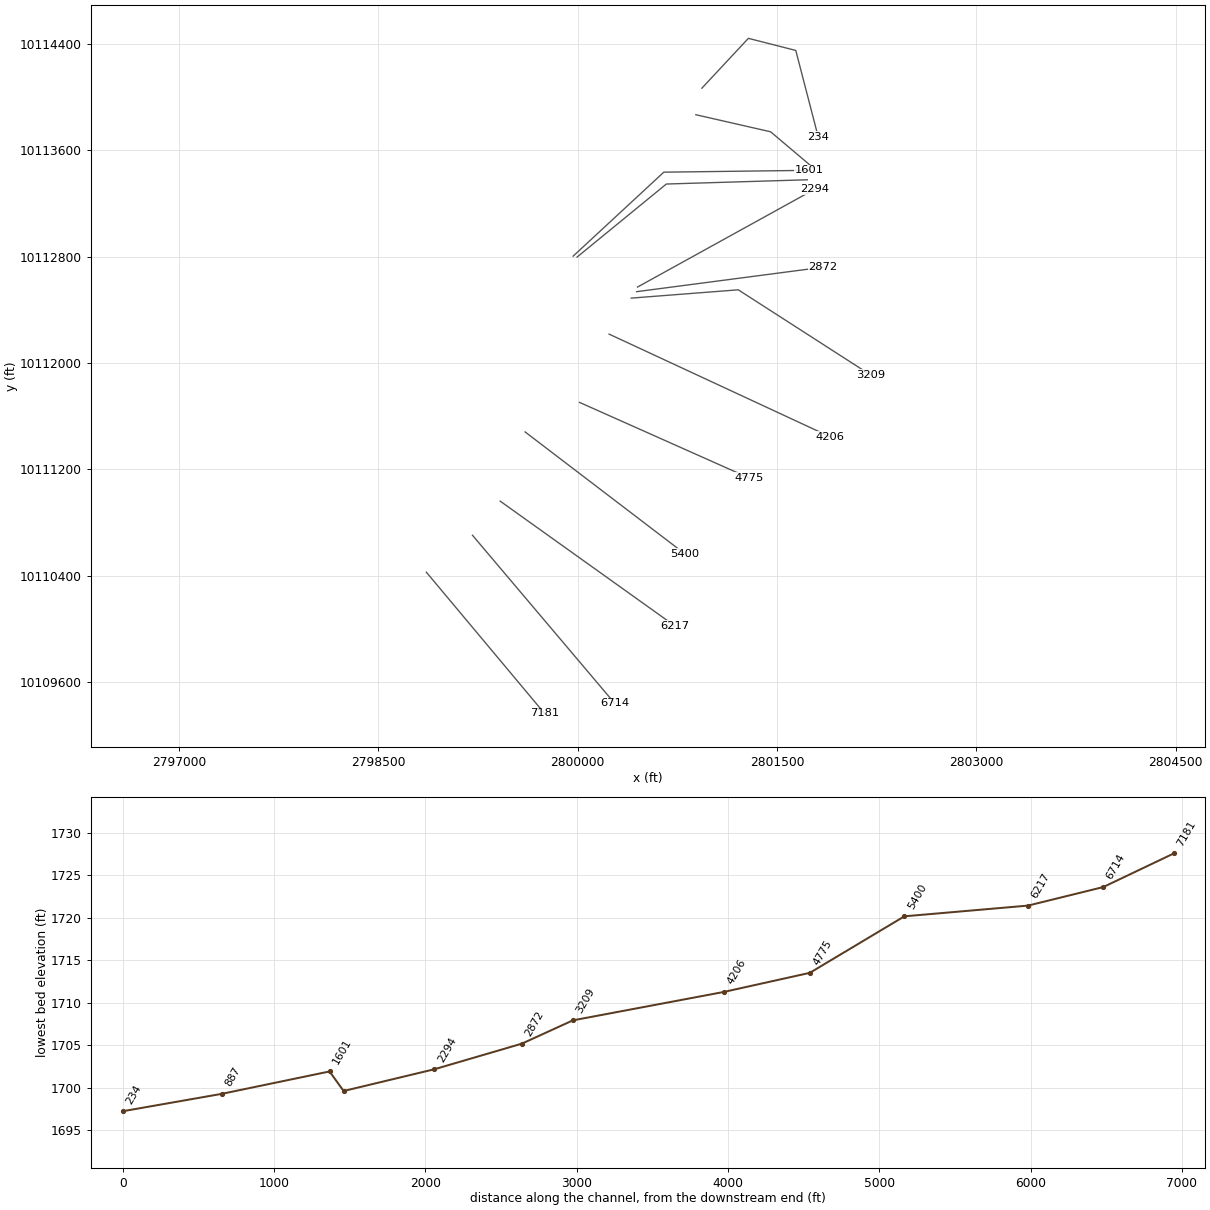
HEC-RAS study SOUTH BRANCH WILLOW CREEK.prj: SOUTH BRANCH WILLOW CREEK Base Level Engineering

--- SOUTH BRANCH WILLOW CREEK.g01 (geometry) --- (continued)

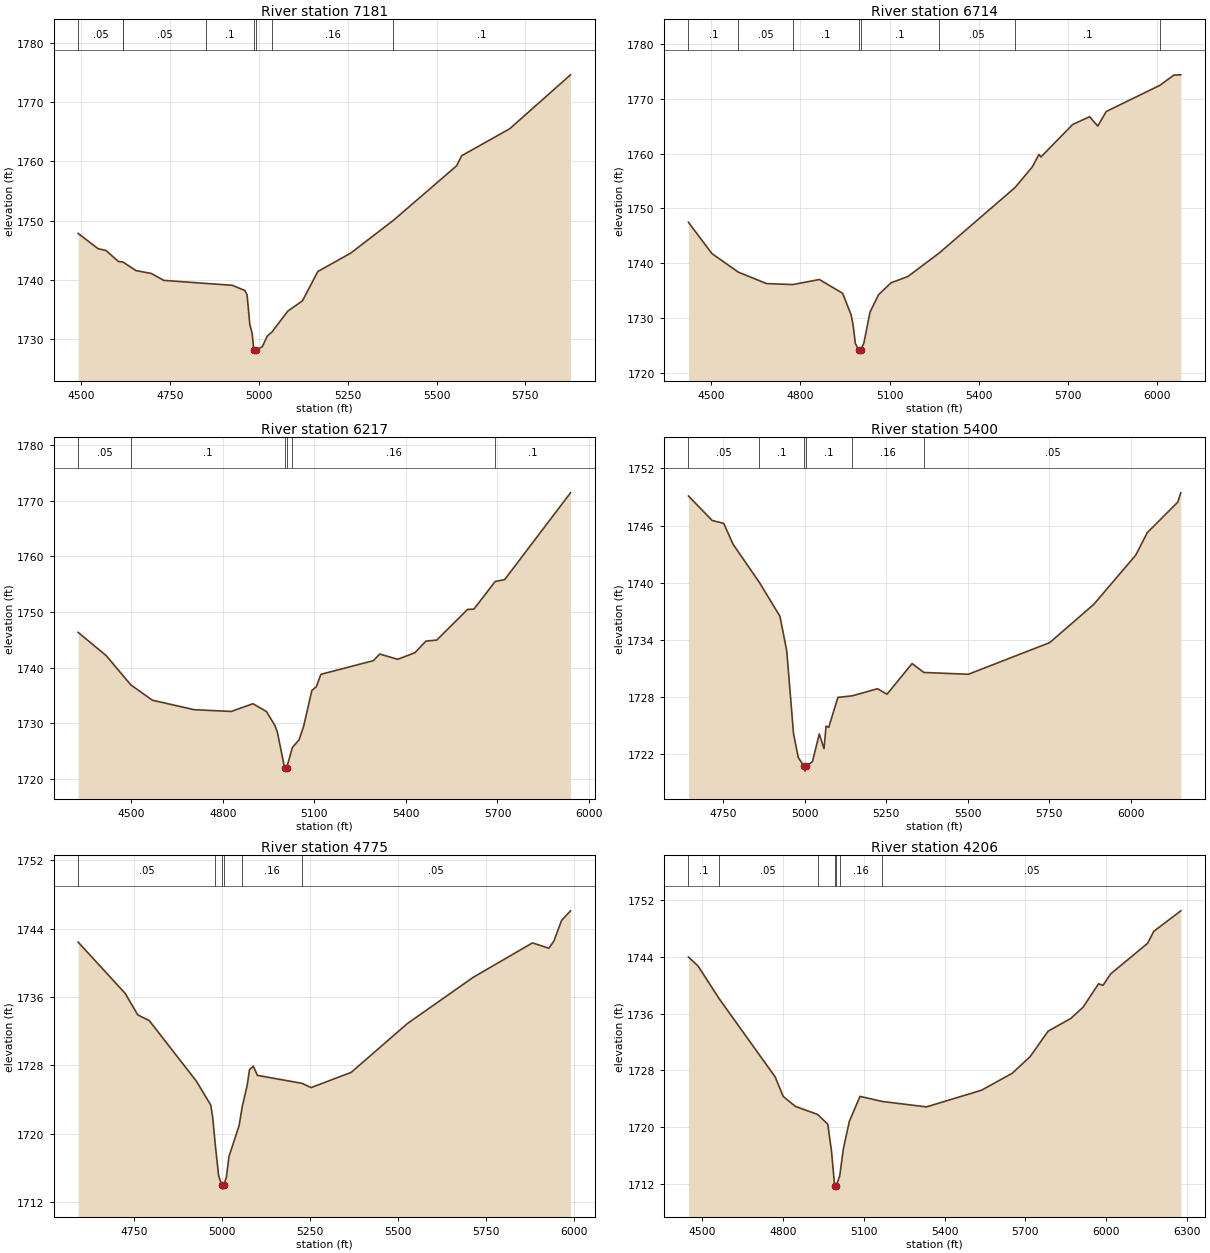
Type RM Length L Ch R = 1 ,7181    ,467,467,467
BEGIN DESCRIPTION:
SOUTH BRANCH WILLOW CREEK 10.0
END DESCRIPTION:
XS GIS Cut Line= 2
      2798861.05     10110426.18      2799749.88     10109363.75
#Sta/Elev= 30
  4491.8 1747.81    4548 1745.23  4570.1 1744.93  4605.2 1743.06  4616.9 1742.98
  4618.1 1742.97  4654.7 1741.52  4697.6 1741.04  4732.8 1739.87  4851.8 1739.35
  4925.3 1739.04  4960.5 1738.17    4967 1737.45  4974.8  1732.4  4981.3 1730.93
  4986.1 1728.06  4988.8 1727.56  4992.1 1728.06  5009.9 1728.65  5024.2 1730.47
  5037.1 1731.14  5081.5 1734.66  5123.1 1736.43  5166.1 1741.37  5258.5 1744.48
  5378.7 1750.03  5556.5 1759.25  5570.8 1760.96  5706.1 1765.53    5877 1774.65
#Mann= 8 ,-1 , 0
  4491.8     .05       0  4616.9      .1       0  4618.1     .05       0
  4851.8      .1       0  4986.1     .07       0  4992.1      .1       0
  5037.1     .16       0  5378.7      .1       0
Bank Sta=4986.1,4992.1
XS Rating Curve= 0 ,0
Exp/Cntr=0.3,0.1

Type RM Length L Ch R = 1 ,6714    ,497,497,497
BEGIN DESCRIPTION:
SOUTH BRANCH WILLOW CREEK 9.0
END DESCRIPTION:
XS GIS Cut Line= 2
      2799208.23     10110704.01      2800277.72     10109440.07
#Sta/Elev= 30
  4423.5 1747.47  4502.5 1741.76  4591.1 1738.38  4685.9 1736.29  4774.1 1736.11
  4863.9 1737.03  4941.9 1734.52  4970.5  1730.6    4977  1728.8  4984.8 1725.36
  4996.1  1724.1  4998.8  1723.6  5002.1  1724.1  5013.3 1725.42  5034.2  1731.1
  5062.8 1734.27    5105 1736.43  5161.6 1737.59  5266.6 1741.86  5521.7 1753.81
  5580.2 1757.61  5602.2 1759.86  5608.8 1759.39  5715.4 1765.31  5772.5 1766.74
  5799.9 1765.03  5828.5 1767.69  6008.7 1772.46  6055.9 1774.33  6079.2 1774.38
#Mann= 8 ,-1 , 0
  4423.5      .1       0  4591.1     .05       0  4774.1      .1       0
  4996.1     .07       0  5002.1      .1       0  5266.6     .05       0
  5521.7      .1       0  6008.7     .16       0
Bank Sta=4996.1,5002.1
XS Rating Curve= 0 ,0
Exp/Cntr=0.3,0.1

Type RM Length L Ch R = 1 ,6217    ,817,817,817
BEGIN DESCRIPTION:
SOUTH BRANCH WILLOW CREEK 8.0
END DESCRIPTION:
XS GIS Cut Line= 2
      2799416.59     10110960.93      2800729.07     10110023.45
#Sta/Elev= 30
  4326.4 1746.35  4418.5 1742.16    4499 1736.91  4569.7 1734.16  4706.1 1732.46
  4827.8 1732.14    4899 1733.53  4943.2 1732.13  4970.3 1729.69  4978.9 1728.47
    5003 1721.92  5005.7 1721.42    5009 1721.92  5028.3 1725.68  5050.2 1727.06
  5064.9 1729.44    5092 1735.91  5106.7 1736.59  5121.5 1738.81  5293.5 1741.27
  5314.4 1742.46  5373.3 1741.51  5429.9  1742.7  5465.6 1744.78  5501.2 1744.97
    5602 1750.47  5622.9 1750.53  5692.5 1755.49  5723.6 1755.83  5939.3 1771.42
#Mann= 6 ,-1 , 0
  4326.4     .05       0    4499      .1       0    5003     .07       0
    5009      .1       0  5028.3     .16       0  5692.5      .1       0
Bank Sta=5003,5009
XS Rating Curve= 0 ,0
Exp/Cntr=0.3,0.1

Type RM Length L Ch R = 1 ,5400    ,625,625,625
BEGIN DESCRIPTION:
SOUTH BRANCH WILLOW CREEK 6.0
END DESCRIPTION:
XS GIS Cut Line= 2
      2799604.11     10111481.75       2800804.5     10110565.85
#Sta/Elev= 30
  4643.3 1749.11  4716.1 1746.53  4751.4 1746.23  4780.5 1744.01  4860.7 1740.02
  4923.9 1736.45  4944.7 1732.82  4965.5 1724.11    4980  1721.6    4998 1720.66
  5000.7 1720.16    5004 1720.66  5023.6 1721.17  5044.5 1724.07    5059 1722.52
  5065.3  1724.9  5073.5 1724.77  5101.6 1727.92  5145.4 1728.08  5223.2 1728.83
  5252.2 1728.25  5329.2 1731.48  5365.2 1730.54  5501.7 1730.35  5751.1 1733.68
  5886.2  1737.7  6015.1 1742.89  6050.4 1745.25  6143.9 1748.46  6153.2 1749.44
#Mann= 6 ,-1 , 0
  4643.3     .05       0  4860.7      .1       0    4998     .07       0
    5004      .1       0  5145.4     .16       0  5365.2     .05       0
Bank Sta=4998,5004
XS Rating Curve= 0 ,0
Exp/Cntr=0.3,0.1

Type RM Length L Ch R = 1 ,4775    ,569,569,569
BEGIN DESCRIPTION:
SOUTH BRANCH WILLOW CREEK 5.0
END DESCRIPTION:
XS GIS Cut Line= 2
      2800013.82     10111703.99      2801291.57     10111134.56
#Sta/Elev= 30
    4591 1742.41  4724.4 1736.42  4760.3  1733.9  4793.2 1733.22  4926.6 1726.16
  4967.6 1723.36  4973.1 1721.98  4980.8 1718.62  4990.2 1715.07  4998.8 1714.01
  5001.6 1713.51  5004.8 1714.01  5012.1 1714.89  5019.6 1717.34  5048.3 1720.94
  5057.3 1723.18  5071.5 1725.69  5077.8 1727.49  5088.8  1727.9  5100.2 1726.82
  5226.7 1725.89    5253 1725.39  5366.7 1727.17  5526.7 1732.89  5713.8  1738.3
  5881.9 1742.32  5928.4 1741.69  5942.7 1742.53  5964.6 1744.95  5989.9 1746.07
#Mann= 6 ,-1 , 0
    4591     .05       0  4980.8      .1       0  4998.8     .07       0
  5004.8      .1       0  5057.3     .16       0  5226.7     .05       0
Bank Sta=4998.8,5004.8
XS Rating Curve= 0 ,0
Exp/Cntr=0.3,0.1

Type RM Length L Ch R = 1 ,4206    ,997,997,997
BEGIN DESCRIPTION:
SOUTH BRANCH WILLOW CREEK 4.0
END DESCRIPTION:
XS GIS Cut Line= 2
      2800236.05     10112217.88      2801895.78     10111447.04
#Sta/Elev= 30
  4448.2 1743.97  4483.9 1742.71  4561.6 1738.14  4770.6 1727.07  4800.2 1724.33
    4846 1722.91    4928 1721.79    4966 1720.42  4980.1 1716.54  4991.4 1711.76
  4994.2 1711.26  4997.4 1711.76  5010.3  1713.1  5024.2 1716.99  5046.3 1720.83
    5086 1724.33    5169 1723.61  5332.9 1722.85  5537.6  1725.2  5652.1  1727.6
  5718.8 1729.96    5785 1733.52  5869.1 1735.31  5914.9 1736.89  5972.4  1740.2
  5989.1 1739.98  6017.5 1741.59  6154.9 1745.91  6177.8 1747.59  6278.2 1750.48
#Mann= 7 ,-1 , 0
  4448.2      .1       0  4561.6     .05       0    4928      .1       0
  4991.4     .07       0  4997.4      .1       0  5010.3     .16       0
    5169     .05       0
Bank Sta=4991.4,4997.4
XS Rating Curve= 0 ,0
Exp/Cntr=0.3,0.1

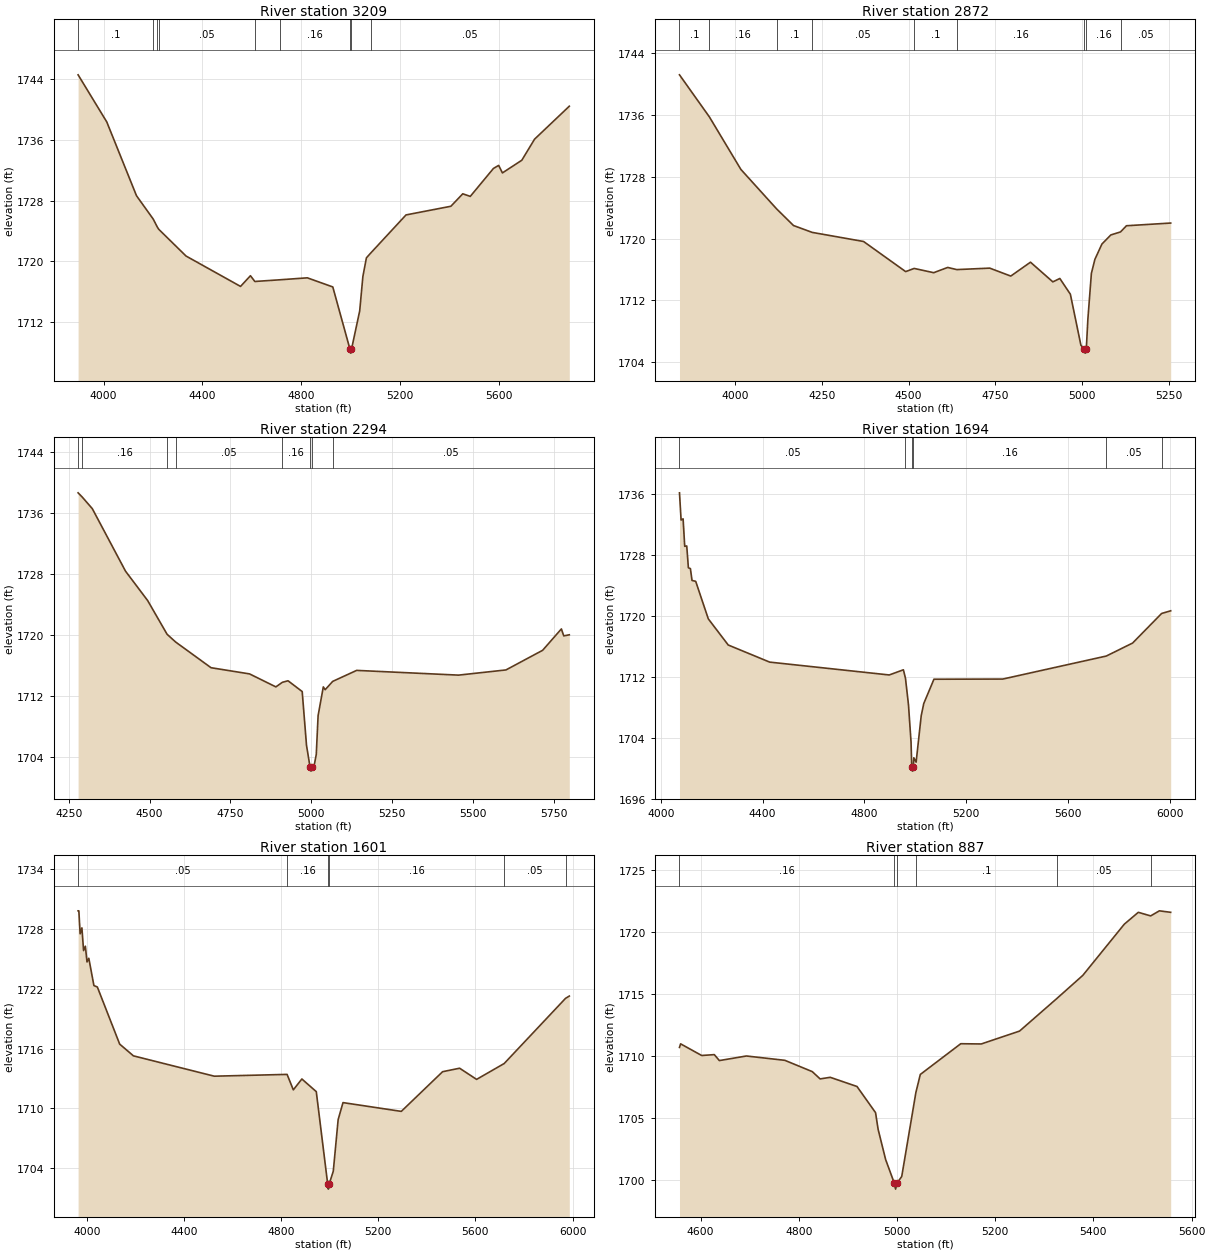
Type RM Length L Ch R = 1 ,3209    ,337,337,337
BEGIN DESCRIPTION:
SOUTH BRANCH WILLOW CREEK 3.0
END DESCRIPTION:
XS GIS Cut Line= 3
      2800402.74     10112488.72      2801208.24     10112551.22
      2802201.34     10111912.31
#Sta/Elev= 30
  3896.9 1744.55    4013 1738.35  4133.3 1728.64  4201.3 1725.55  4217.9  1724.5
  4223.7 1724.21  4333.9  1720.7  4554.6  1716.7  4594.7 1718.11  4612.5 1717.35
  4712.7 1717.57  4825.1 1717.83  4928.1 1716.63  4997.8 1708.42  5000.5 1707.92
  5003.8 1708.42  5037.1 1713.49  5049.9    1718  5064.2 1720.46  5081.3 1721.08
  5224.6 1726.11  5406.2 1727.25  5454.4 1728.89  5484.8 1728.55  5578.6 1732.23
  5599.7 1732.63  5614.9 1731.64  5693.5 1733.31    5745 1736.08  5885.7 1740.42
#Mann= 9 ,-1 , 0
  3896.9      .1       0  4201.3     .16       0  4217.9      .1       0
  4223.7     .05       0  4612.5      .1       0  4712.7     .16       0
  4997.8     .07       0  5003.8     .16       0  5081.3     .05       0
Bank Sta=4997.8,5003.8
XS Rating Curve= 0 ,0
Exp/Cntr=0.3,0.1

Type RM Length L Ch R = 1 ,2872    ,578,578,578
BEGIN DESCRIPTION:
Mapping XS 454d821a
END DESCRIPTION:
XS GIS Cut Line= 2
      2800443.12     10112537.18      2801844.71     10112721.05
#Sta/Elev= 30
  3840.9 1741.23  3927.1 1735.77  4017.7 1728.97  4120.3 1723.87    4169 1721.71
  4222.8 1720.82  4370.7 1719.64  4491.8 1715.74  4516.3 1716.15  4572.5  1715.6
  4612.8 1716.28  4638.9    1716  4733.8 1716.19  4794.3 1715.16    4851 1716.96
  4915.4 1714.41  4935.5 1714.85  4965.8 1712.81  4996.1 1706.21  5005.6 1705.68
  5008.4 1705.18  5011.6 1705.68  5016.2 1709.59  5026.3 1715.51  5036.4 1717.33
  5056.6 1719.31  5082.3 1720.49  5110.1 1720.88  5127.2 1721.68  5254.5 1722.03
#Mann= 9 ,-1 , 0
  3840.9      .1       0  3927.1     .16       0  4120.3      .1       0
  4222.8     .05       0  4516.3      .1       0  4638.9     .16       0
  5005.6     .07       0  5011.6     .16       0  5110.1     .05       0
Bank Sta=5005.6,5011.6
XS Rating Curve= 0 ,0
Exp/Cntr=0.3,0.1

Type RM Length L Ch R = 1 ,2294    ,600,600,600
BEGIN DESCRIPTION:
Mapping XS 5a0404f2
END DESCRIPTION:
XS GIS Cut Line= 2
      2800450.05     10112571.89      2801779.95     10113306.28
#Sta/Elev= 30
  4279.1 1738.61    4292 1738.05    4323 1736.54  4425.8 1728.35  4494.3  1724.5
  4554.3 1720.09  4580.6 1719.08  4690.3 1715.71  4809.4  1714.9  4890.8  1713.2
  4910.9  1713.8  4928.4    1714  4972.2 1712.59  4985.5 1705.56  4996.6 1702.67
  4999.4 1702.17  5002.6 1702.67  5008.4 1702.72  5015.7 1704.36  5021.4 1709.44
  5037.5  1713.2  5043.2 1712.83  5066.5 1713.92  5140.6 1715.36  5455.7 1714.74
  5602.4 1715.42  5715.8 1717.99  5773.8 1720.79  5781.1 1719.88  5798.3 1720.02
#Mann= 8 ,-1 , 0
  4279.1      .1       0    4292     .16       0  4554.3      .1       0
  4580.6     .05       0  4910.9     .16       0  4996.6     .07       0
  5002.6     .16       0  5066.5     .05       0
Bank Sta=4996.6,5002.6
XS Rating Curve= 0 ,0
Exp/Cntr=0.3,0.1

Type RM Length L Ch R = 1 ,1694    ,93,93,93
BEGIN DESCRIPTION:
SOUTH BRANCH WILLOW CREEK 2.0
END DESCRIPTION:
XS GIS Cut Line= 3
      2799995.19     10112797.57      2800667.17     10113347.29
       2801727.9      10113379.2
#Sta/Elev= 30
  4073.4 1736.22  4079.7 1732.64  4087.6  1732.8    4094 1729.18  4101.9 1729.23
  4108.4 1726.36  4116.3 1726.25  4122.7 1724.69  4137.1 1724.58  4186.6 1719.64
  4264.9  1716.2  4427.8 1713.95  4897.3 1712.26  4952.9 1712.94  4961.1 1711.82
  4972.9 1708.33  4982.9 1703.45  4985.8 1700.11  4988.5 1699.61  4991.8 1700.11
  4993.8 1701.37  5002.9 1700.79  5022.9  1706.9  5032.9  1708.5  5072.9  1711.7
  5343.1 1711.72    5750 1714.75  5853.3 1716.46  5967.2 1720.35  6002.8  1720.7
#Mann= 6 ,-1 , 0
  4073.4     .05       0  4961.1     .16       0  4985.8     .07       0
  4991.8     .16       0    5750     .05       0  5967.2      .1       0
Bank Sta=4985.8,4991.8
XS Rating Curve= 0 ,0
Exp/Cntr=0.3,0.1

Type RM Length L Ch R = 1 ,1601    ,714,714,714
BEGIN DESCRIPTION:
Mapping XS 4046df68
END DESCRIPTION:
XS GIS Cut Line= 3
       2799965.7     10112804.54        2800648.     10113436.49
      2801740.02     10113450.38
#Sta/Elev= 30
  3964.6 1729.83  3967.7 1729.83    3973 1727.52  3980.3 1728.12  3987.1 1725.84
  3994.5 1726.28  4001.3  1724.7  4008.7 1725.07  4029.7 1722.33  4043.8 1722.19
  4135.7 1716.46  4192.4 1715.28  4525.2 1713.24  4824.9 1713.42  4850.6 1711.87
  4885.8 1712.96  4945.1 1711.69  4992.1 1702.41  4994.8 1701.91  4998.1 1702.41
  5015.1 1703.71  5035.1 1708.88  5055.1 1710.59  5295.1 1709.71  5465.1 1713.69
  5535.1 1714.04  5605.1 1712.92  5718.6 1714.51  5971.2 1721.05  5986.7 1721.28
#Mann= 6 ,-1 , 0
  3964.6     .05       0  4824.9     .16       0  4992.1     .07       0
  4998.1     .16       0  5718.6     .05       0  5971.2      .1       0
Bank Sta=4992.1,4998.1
XS Rating Curve= 0 ,0
Exp/Cntr=0.3,0.1

Type RM Length L Ch R = 1 ,887     ,653,653,653
BEGIN DESCRIPTION:
Mapping XS e703f5cb
END DESCRIPTION:
XS GIS Cut Line= 3
       2800889.3     10113868.79      2801451.82     10113740.31
        2801775.     10113467.25
#Sta/Elev= 30
  4557.2  1710.7  4559.5 1710.99  4602.4 1710.05  4628.1 1710.12  4638.4 1709.64
  4693.5 1710.01  4771.7 1709.66  4827.5 1708.75  4843.6 1708.16  4864.1 1708.29
  4918.6 1707.55  4956.4 1705.44  4961.6  1704.1  4976.9 1701.66  4994.4 1699.77
  4997.2 1699.27  5000.4 1699.77  5009.7 1700.29  5038.5 1707.06  5047.5 1708.52
  5129.9    1711  5171.6 1710.98  5249.6 1712.02  5325.9 1714.66  5378.3 1716.51
  5462.8 1720.64  5491.4  1721.6  5516.5 1721.31  5534.3 1721.72  5557.3  1721.6
#Mann= 6 ,-1 , 0
  4557.2     .16       0  4994.4     .07       0  5000.4     .16       0
  5038.5      .1       0  5325.9     .05       0  5516.5      .1       0
Bank Sta=4994.4,5000.4
XS Rating Curve= 0 ,0
Exp/Cntr=0.3,0.1

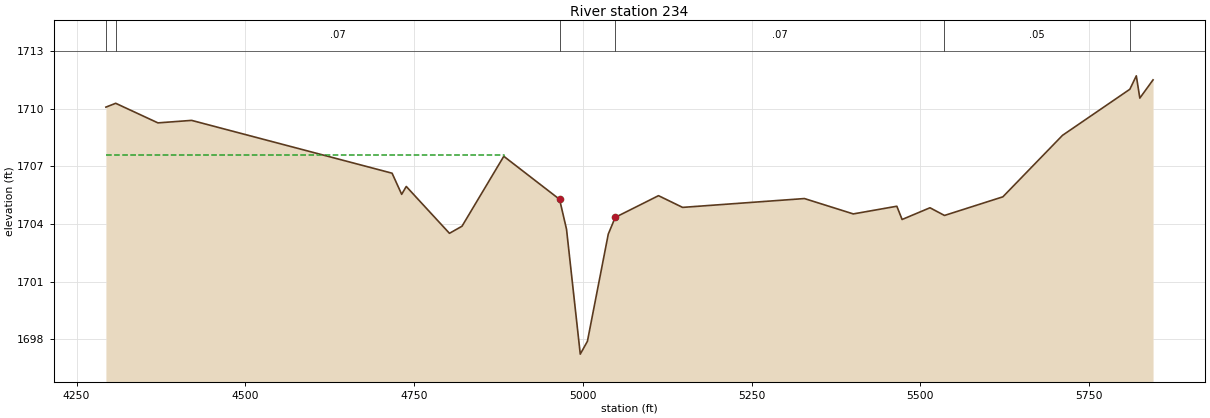
Type RM Length L Ch R = 1 ,234     ,0,0,0
BEGIN DESCRIPTION:
SOUTH BRANCH WILLOW CREEK 1.0
END DESCRIPTION:
XS GIS Cut Line= 4
      2800934.48     10114068.45      2801284.36     10114443.64
      2801641.13      10114352.5      2801809.46     10113703.83
#Sta/Elev= 30
  4293.5 1710.09    4308 1710.29  4370.6 1709.27  4420.5  1709.4  4717.5 1706.65
  4731.7 1705.55  4738.5 1705.96  4802.5 1703.52  4821.1 1703.89    4883 1707.53
  4965.6 1705.29  4975.9 1703.74  4996.3 1697.23  5006.9  1697.9  5037.8 1703.48
  5048.1 1704.35  5112.2 1705.48  5147.9 1704.87  5328.4 1705.33  5400.8 1704.53
  5465.3 1704.93  5473.1 1704.24  5514.4 1704.85  5535.9 1704.45  5622.4 1705.42
  5710.7 1708.62  5810.5 1711.02  5820.1 1711.72  5825.3 1710.56  5844.9 1711.51
#Mann= 6 ,-1 , 0
  4293.5     .05       0    4308     .07       0  4965.6     .03       0
  5048.1     .07       0  5535.9     .05       0  5810.5      .1       0
#XS Ineff= 2 , 0
         4883.43 1707.61
Permanent Ineff=
       F       F
Bank Sta=4965.6,5048.1
XS Rating Curve= 0 ,0
Exp/Cntr=0.3,0.1

Chan Stop Cuts=-1
Use User Specified Reach Order=0
Composite Channel Slope=5