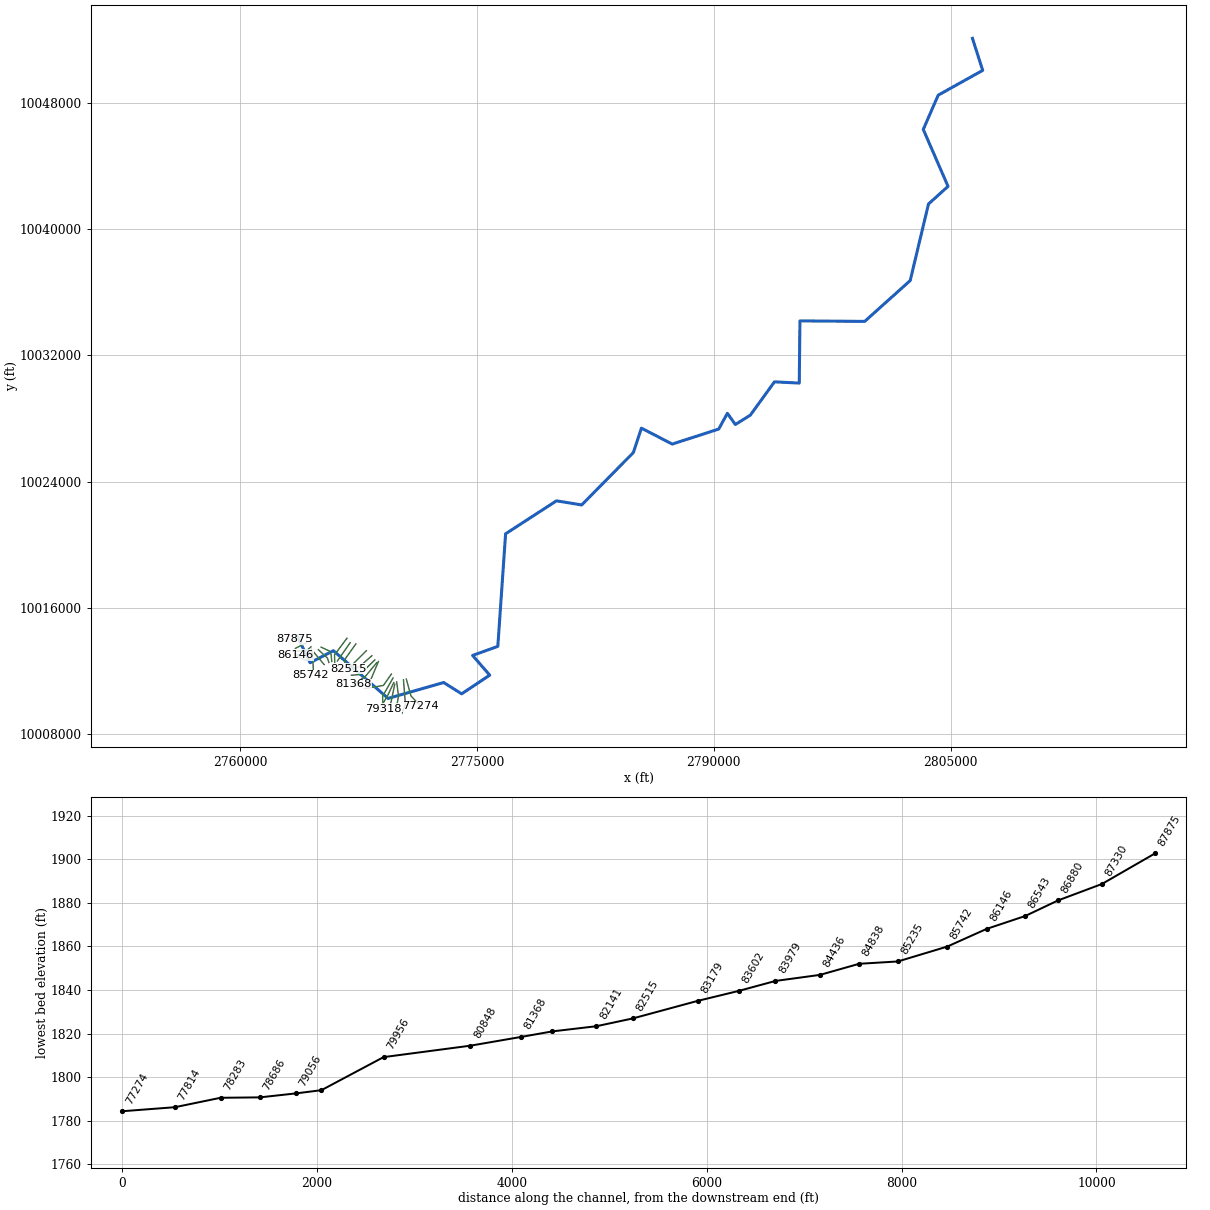
--- SOUTH GRAPE CREEK.prj (project) ---

Proj Title=SOUTH GRAPE CREEK Base Level Engineering
Current Plan=p01
Default Exp/Contr=0.3,0.1
English Units
Geom File=g01
Flow File=f01
Plan File=p01
Y Axis Title=Elevation
X Axis Title(PF)=Main Channel Distance
X Axis Title(XS)=Station
BEGIN DESCRIPTION:
SOUTH GRAPE CREEK
END DESCRIPTION:
DSS File=dss
DSS Export Rating Curves= 0
DSS Export Rating Curve Sorted= 0
DSS Export Volume Flow Curves= 0
DXF OffsetX= 0
DXF OffsetY= 0
DXF ScaleX= 1
DXF ScaleY= 10

--- SOUTH GRAPE CREEK.p01 (plan) ---

Plan Title=Multiple Run
Program Version=4.10
Short Identifier=Multiple Run
Geom File=g01
Flow File=f01
Subcritical Flow
K Sum by GR= 0
Std Step Tol= 0.01
Critical Tol= 0.01
Num of Std Step Trials= 20
Max Error Tol= 0.3
Flow Tol Ratio= 0.001
Split Flow NTrial= 30
Split Flow Tol= 0.02
Split Flow Ratio= 0.02
Log Output Level= 0
Friction Slope Method= 1
Unsteady Friction Slope Method= 2
Unsteady Bridges Friction Slope Method= 1
Parabolic Critical Depth
Global Vel Dist= 1 , 1 , 1
Global Log Level= 0
CheckData=True
Encroach Param=-1 ,0,0, 0
BEGIN DESCRIPTION:
Multiple Run
END DESCRIPTION:
Computation Interval=1HOUR
Output Interval=1HOUR
Run HTab= 0
Run UNet= 0
Run PostProcess= 0
Run WQNet= 0
UNET Theta= 1
UNET Theta Warmup= 1
UNET ZTol= 0.02
UNET ZSATol= 0.05
UNET MxIter= 20
UNET MaxInSteps= 0
UNET DtIC= 0
UNET DtMin= 0
UNET MaxCRTS= 20
UNET WFStab= 2
UNET SFStab= 1
UNET WFX= 1
UNET SFX= 1
UNET DSS MLevel= 4
UNET DZMax Abort= 100
UNET Convert EG Bridges= 0
UNET Use Existing IB Tables=-1
UNET Froude Reduction=False
UNET Froude Limit= 1
UNET Froude Power= 10
UNET Time Slicing=0,0, 5
UNET Junction Losses=0
Instantaneous Interval=1HOUR
DSS File=dss
Write IC File= 0
Write IC File at Sim End=0
Echo Input=False
Echo Parameters=False
Echo Output=False
Write Detailed= 0
WQ AD Non Conservative
WQ ULTIMATE=-1
WQ Max Comp Step=1HOUR
WQ Output Interval=15MIN
WQ Output Selected Increments= 0
WQ Output face flow=0
WQ Output face velocity=0
WQ Output face area=0
WQ Output face dispersion=0
WQ Output cell volume=0
WQ Output cell surface area=0
WQ Output cell continuity=0
WQ Output cumulative cell continuity=0
WQ Output face conc=0
WQ Output face dconc_dx=0
WQ Output face courant=0
WQ Output face peclet=0
WQ Output face adv mass=0
WQ Output face disp mass=0
WQ Output cell mass=0
WQ Output cell source sink temp=0
WQ Output cell source sink nsm=0
WQ Output MaxMinRange=-1
WQ Daily Max Min Mean=-1
WQ Daily Range=0
WQ Daily Time=0
WQ Create Restart=0
WQ Fixed Restart=0
WQ System Summary=0
WQ Use Fixed Temperature=0
Sorting and Armoring Iterations= 10
XS Update Threshold= 0.02
Hydraulics Update Threshold= 0.02
Energy Slope Method= 1
Volume Change Method= 0
XS Weighting Method= 0
Number of US Weighted Cross Sections= 1
Number of DS Weighted Cross Sections= 1
Upstream XS Weight=0.25
Main XS Weight=0.5
Downstream XS Weight=0.25
Number of DS XS's Weighted with US Boundary= 1
Upstream Boundary Weight= 1
Weight of XSs Associated with US Boundary= 0
Number of US XS's Weighted with DS Boundary= 1
Downstream Boundary Weight= 0.5
Weight of XSs Associated with DS Boundary= 0.5
Sediment Output Level= 4
Mass or Volume Output= 0
Output Increment Type= 1
Profile and TS Output Increment= 10
XS Output Flag= 0
XS Output Increment= 10
Disregard all LS=0
Disregard all Conn=0
Disregard all Breaches=0
Disregard all Pumps=0

--- SOUTH GRAPE CREEK.f01 (steady flow) ---

Flow Title=Multiple
Program Version=4.10
Number of Profiles= 7
Profile Names=10-year,25-year,50-year,1pct_min,100-year,1pct_plu,500-year
River Rch & RM=SOUTH GRAPE CREE,Reach-1         ,87875
     352     484     592     533     720     974    1068
River Rch & RM=SOUTH GRAPE CREE,Reach-1         ,85742
     912    1321    1676    1555    2103    2844    3326
River Rch & RM=SOUTH GRAPE CREE,Reach-1         ,83979
    1160    1701    2174    2031    2747    3714    4404
River Rch & RM=SOUTH GRAPE CREE,Reach-1         ,79318
    1837    2754    3573    3382    4574    6186    7536
River Rch & RM=SOUTH GRAPE CREE,Reach-1         ,77274
    1984    2975    3859    3652    4938    6679    8128
River Rch & RM=SOUTH GRAPE CREE,Reach-1         ,72145
    2621    3972    5189    4941    6682    9037   11137
River Rch & RM=SOUTH GRAPE CREE,Reach-1         ,71863
    2621    3972    5189    4941    6682    9037   11137
River Rch & RM=SOUTH GRAPE CREE,Reach-1         ,66714
    2831    4301    5629    5368    7259    9817   12136
River Rch & RM=SOUTH GRAPE CREE,Reach-1         ,65943
    3200    4879    6403    6118    8274   11190   13890
River Rch & RM=SOUTH GRAPE CREE,Reach-1         ,65798
    3200    4879    6403    6118    8274   11190   13890
River Rch & RM=SOUTH GRAPE CREE,Reach-1         ,65296
    3200    4879    6403    6118    8274   11190   13890
River Rch & RM=SOUTH GRAPE CREE,Reach-1         ,60703
    4190    6450    8519    8187   11072   14974   18802
River Rch & RM=SOUTH GRAPE CREE,Reach-1         ,59971
    4190    6450    8519    8187   11072   14974   18802
River Rch & RM=SOUTH GRAPE CREE,Reach-1         ,57095
    4290    6594    8699    8350   11293   15272   19128
River Rch & RM=SOUTH GRAPE CREE,Reach-1         ,49571
    5585    8654   11481   11075   14978   20256   25618
River Rch & RM=SOUTH GRAPE CREE,Reach-1         ,48336
    5585    8654   11481   11075   14978   20256   25618
River Rch & RM=SOUTH GRAPE CREE,Reach-1         ,45307
    5793    8977   11910   11488   15537   21012   26568
River Rch & RM=SOUTH GRAPE CREE,Reach-1         ,44278
    5793    8977   11910   11488   15537   21012   26568
River Rch & RM=SOUTH GRAPE CREE,Reach-1         ,40482
    6038    9361   12422   11983   16206   21917   27718
River Rch & RM=SOUTH GRAPE CREE,Reach-1         ,35606
    6000    9283   12301   11849   16025   21672   27325
River Rch & RM=SOUTH GRAPE CREE,Reach-1         ,30112
    6853   10638   14131   13640   18447   24947   31583
River Rch & RM=SOUTH GRAPE CREE,Reach-1         ,29076
    6853   10638   14131   13640   18447   24947   31583
River Rch & RM=SOUTH GRAPE CREE,Reach-1         ,23235
    7234   11242   14945   14436   19524   26403   33472
River Rch & RM=SOUTH GRAPE CREE,Reach-1         ,21772
    9890   15457   20634   20003   27052   36585   46690
River Rch & RM=SOUTH GRAPE CREE,Reach-1         ,20918
    9890   15457   20634   20003   27052   36585   46690
River Rch & RM=SOUTH GRAPE CREE,Reach-1         ,16985
   10154   15878   21204   20563   27809   37608   48026
River Rch & RM=SOUTH GRAPE CREE,Reach-1         ,13255
   10154   15878   21204   20563   27809   37608   48026
River Rch & RM=SOUTH GRAPE CREE,Reach-1         ,12062
   10286   16059   21423   20751   28064   37953   48351
River Rch & RM=SOUTH GRAPE CREE,Reach-1         ,4112
   10258   15994   21317   20629   27898   37728   47970
Boundary for River Rch & Prof#=SOUTH GRAPE CREE,Reach-1         , 1
Up Type= 0
Dn Type= 3
Dn Slope=0.00013
Boundary for River Rch & Prof#=SOUTH GRAPE CREE,Reach-1         , 2
Up Type= 0
Dn Type= 3
Dn Slope=0.00013
Boundary for River Rch & Prof#=SOUTH GRAPE CREE,Reach-1         , 3
Up Type= 0
Dn Type= 3
Dn Slope=0.00013
Boundary for River Rch & Prof#=SOUTH GRAPE CREE,Reach-1         , 4
Up Type= 0
Dn Type= 3
Dn Slope=0.00013
Boundary for River Rch & Prof#=SOUTH GRAPE CREE,Reach-1         , 5
Up Type= 0
Dn Type= 3
Dn Slope=0.00013
Boundary for River Rch & Prof#=SOUTH GRAPE CREE,Reach-1         , 6
Up Type= 0
Dn Type= 3
Dn Slope=0.00013
Boundary for River Rch & Prof#=SOUTH GRAPE CREE,Reach-1         , 7
Up Type= 0
Dn Type= 3
Dn Slope=0.00013
DSS Import GetInterval= 0
DSS Import GetPeak= 0
DSS Import FillOption= 0

--- SOUTH GRAPE CREEK.g01 (geometry) ---

Geom Title=Existing Conditions
Program Version=4.10

River Reach=SOUTH GRAPE CREE,Reach-1
Reach XY= 30
      2763613.76     10014218.95      2764435.13     10012524.42
      2765911.15     10013287.39      2769374.25     10010265.24
      2772893.66     10011273.09      2774032.56     10010555.79
      2775812.18     10011738.19      2774728.92     10012988.35
      2776324.36     10013562.59      2776816.89     10020692.89
      2780040.04     10022779.94      2781635.42     10022518.65
      2784908.08     10025835.88      2785419.17     10027381.93
      2787373.21     10026374.44      2790314.87     10027325.91
      2790864.04      10028322.6      2791368.47     10027613.73
      2792317.73     10028206.14      2793845.28     10030315.26
      2795416.83     10030238.51      2795459.48     10034176.34
      2799562.98     10034145.12      2802443.48     10036730.81
      2803602.29     10041582.15      2804840.49     10042698.08
      2803271.08     10046302.49      2804215.79     10048472.49
      2807035.34     10050044.96      2806386.73      10052073.2

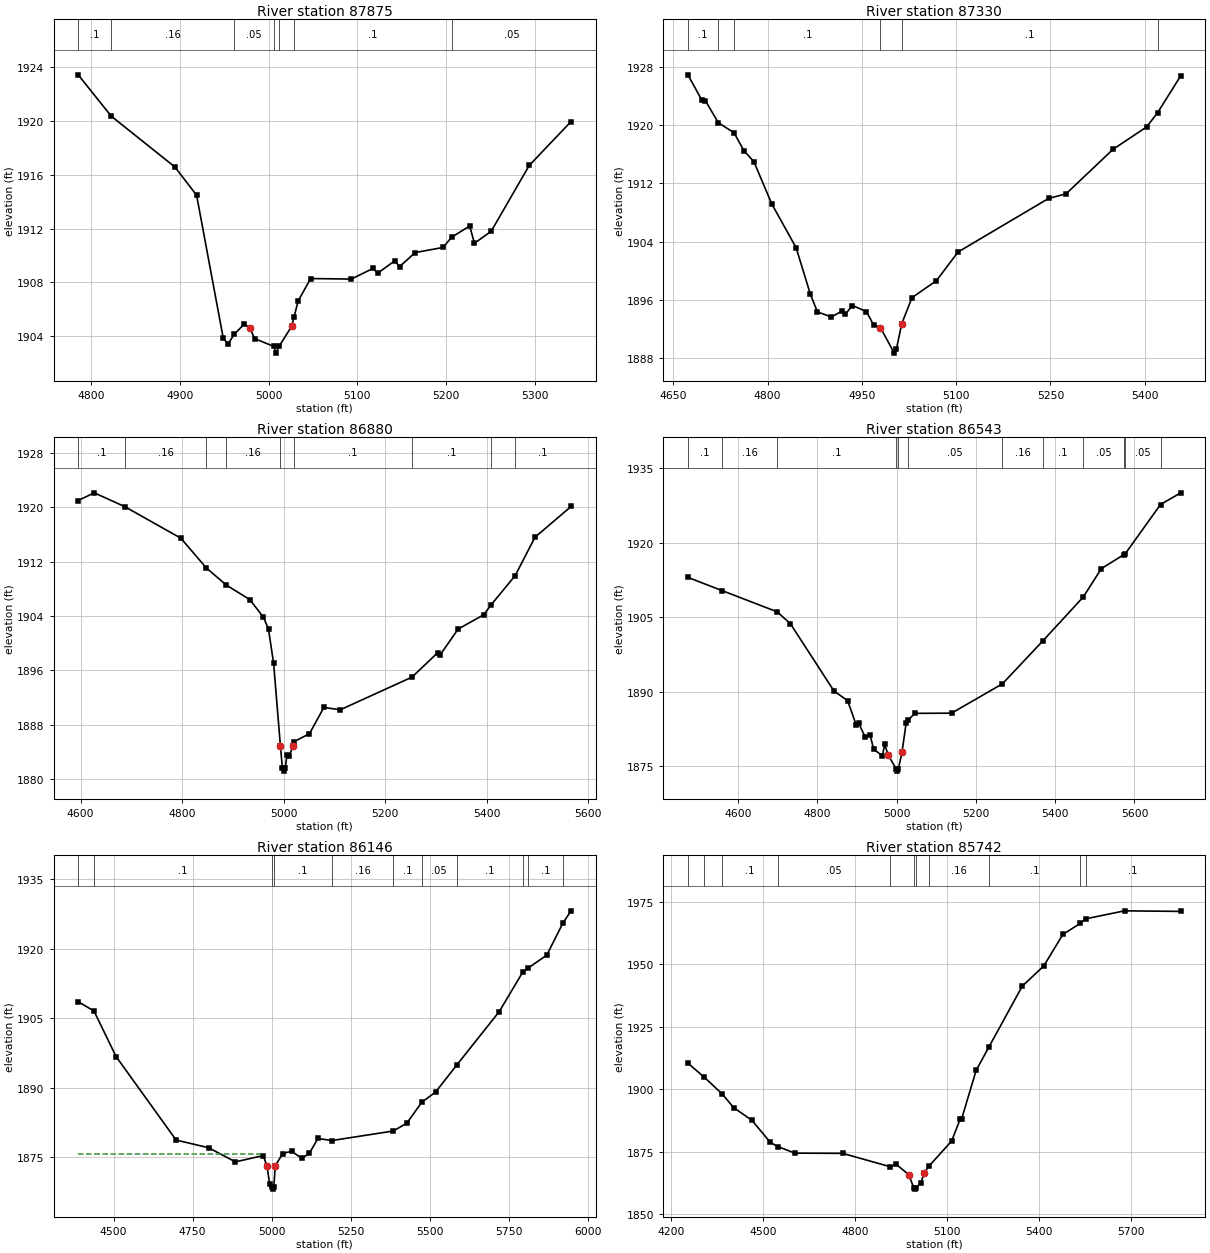
Type RM Length L Ch R = 1 ,87875   ,545,545,545
BEGIN DESCRIPTION:
SOUTH GRAPE CREEK 151.0
END DESCRIPTION:
XS GIS Cut Line= 2
       2763973.1     10014198.94      2763454.42     10013998.39
#Sta/Elev= 30
  4785.1 1923.42  4822.4 1920.35  4894.3 1916.57  4918.7 1914.48  4948.8 1903.85
  4954.2 1903.44  4961.2 1904.15  4972.3  1904.9  4978.7 1904.64  4984.1 1903.83
  5005.7 1903.25  5008.4 1902.75  5011.7 1903.25  5025.9 1904.73  5028.6 1905.42
  5033.3 1906.63  5047.4 1908.29  5093.2 1908.25  5117.7 1909.04  5123.1 1908.69
  5142.3 1909.61  5147.7 1909.17  5165.3 1910.22  5196.9  1910.6  5206.4 1911.36
  5226.8 1912.19  5232.2 1910.91  5251.1  1911.8    5294 1916.69  5341.2 1919.95
#Mann= 7 ,-1 , 0
  4785.1      .1       0  4822.4     .16       0  4961.2     .05       0
  5005.7    .035       0  5011.7     .05       0  5028.6      .1       0
  5206.4     .05       0
Bank Sta=4978.7,5025.9
XS Rating Curve= 0 ,0
Exp/Cntr=0.3,0.1

Type RM Length L Ch R = 1 ,87330   ,450,450,450
BEGIN DESCRIPTION:
SOUTH GRAPE CREEK 150.0
END DESCRIPTION:
XS GIS Cut Line= 2
      2764202.22     10013789.21      2763502.12     10013435.69
#Sta/Elev= 30
  4673.1 1926.92  4695.2 1923.46  4700.8 1923.38  4721.6 1920.34  4746.6 1918.96
  4762.1 1916.52  4778.1 1914.99  4806.7 1909.17  4845.3 1903.18  4867.8 1896.84
  4879.2 1894.36  4901.5 1893.67  4918.2 1894.47  4923.8 1894.06  4934.9 1895.24
  4957.2 1894.41  4968.6 1892.57  4979.5  1892.2  5001.5  1888.7  5004.8  1889.2
  5013.4 1892.75  5029.7 1896.32  5068.6 1898.65    5103 1902.59    5247 1909.94
  5274.9 1910.58  5349.5 1916.68  5403.1 1919.77  5420.6 1921.73  5457.4 1926.79
#Mann= 6 ,-1 , 0
  4673.1      .1       0  4721.6     .16       0  4746.6      .1       0
  4979.5     .07       0  5013.4      .1       0  5420.6     .05       0
#XS Ineff= 2 , 0
         4935.03 1895.18
Permanent Ineff=
       T       T
Bank Sta=4979.5,5013.4
XS Rating Curve= 0 ,0
Exp/Cntr=0.3,0.1

Type RM Length L Ch R = 1 ,86880   ,337,337,337
BEGIN DESCRIPTION:
SOUTH GRAPE CREEK 149.0
END DESCRIPTION:
XS GIS Cut Line= 3
       2764493.9     10013532.27      2764271.68     10013344.77
      2763598.06     10013254.49
#Sta/Elev= 30
  4595.4 1920.98    4627 1922.11  4686.8 1920.09  4797.4 1915.44  4847.6 1911.07
    4887 1908.54  4933.2  1906.4    4960 1903.83  4970.1 1902.06  4980.2    1897
  4993.6 1884.82  4997.4 1881.66  5000.1 1881.16  5003.4 1881.66  5006.2  1883.5
  5011.2 1883.35 5017.67 1884.82  5020.6  1885.5  5050.8 1886.67  5079.1 1890.53
  5111.4 1890.19  5252.6 1894.99    5303 1898.57  5308.1 1898.27  5343.4 1902.06
  5393.9 1904.17  5407.5 1905.55  5455.6 1909.91  5494.8 1915.58  5565.8  1920.1
#Mann= 9 ,-1 , 0
  4595.4      .1       0  4686.8     .16       0  4847.6      .1       0
    4887     .16       0  4993.6     .07       0  5020.6      .1       0
  5252.6      .1       0  5407.5     .16       0  5455.6      .1       0
Bank Sta=4993.6,5017.67
XS Rating Curve= 0 ,0
Exp/Cntr=0.3,0.1

Type RM Length L Ch R = 1 ,86543   ,397,397,397
BEGIN DESCRIPTION:
SOUTH GRAPE CREEK 147.0
END DESCRIPTION:
XS GIS Cut Line= 4
      2764528.62     10013358.66      2764278.62     10013087.82
      2764021.68     10012948.93      2763452.88     10013073.79
#Sta/Elev= 30
  4473.8    1913  4559.9 1910.34  4698.8 1906.07  4732.2 1903.69  4841.8 1890.18
  4876.7 1888.16  4898.6 1883.23  4904.3 1883.67  4920.5 1880.94  4933.5 1881.22
  4942.4 1878.39  4964.3 1877.09    4970 1879.39    4979 1877.22  4998.7  1874.5
  5001.5    1874  5004.7  1874.5  5013.7 1877.76  5024.2 1883.68  5028.7 1884.22
  5046.1 1885.63  5138.7 1885.67    5267 1891.57    5369 1900.22    5471 1909.06
  5516.6 1914.77    5573 1917.56  5576.5 1917.72  5665.7 1927.67  5716.8 1930.02
#Mann= 12 ,-1 , 0
  4473.8      .1       0  4559.9     .16       0  4698.8      .1       0
  4998.7     .07       0  5004.7      .1       0  5028.7     .05       0
    5267     .16       0    5369      .1       0    5471     .05       0
    5573      .1       0  5576.5     .05       0  5665.7      .1       0
Bank Sta=4979,5013.7
XS Rating Curve= 0 ,0
Exp/Cntr=0.3,0.1

Type RM Length L Ch R = 1 ,86146   ,404,404,404
BEGIN DESCRIPTION:
SOUTH GRAPE CREEK 148.0
END DESCRIPTION:
XS GIS Cut Line= 4
      2764459.18     10013233.65      2764452.23     10012733.66
      2764174.46      10012678.1      2763473.23     10013011.35
#Sta/Elev= 30
  4388.1 1908.53    4438 1906.53    4508 1896.69    4698 1878.66  4801.2 1876.99
  4885.6 1873.94  4973.6 1875.31 4985.86 1872.99    4994 1869.11  5001.2 1868.56
  5003.9 1868.06  5007.2 1868.56  5011.8 1873.03  5034.8 1875.74  5063.2 1876.25
  5095.9 1874.71  5119.3 1875.77  5146.9    1879  5190.9 1878.55  5385.8 1880.62
  5428.2 1882.33  5475.8 1886.84    5519 1889.02  5585.9 1894.84  5720.6 1906.41
    5796 1915.05  5810.4 1915.73  5870.9 1918.59  5921.9  1925.5  5947.8 1928.16
#Mann= 11 ,-1 , 0
  4388.1     .16       0    4438      .1       0  5001.2     .07       0
  5007.2      .1       0  5190.9     .16       0  5385.8      .1       0
  5475.8     .05       0  5585.9      .1       0    5796     .05       0
  5810.4      .1       0  5921.9     .05       0
#XS Ineff= 2 , 0
         4962.65 1875.61 5063.37         1876.21
Permanent Ineff=
       T       T
Bank Sta=4985.86,5011.8
XS Rating Curve= 0 ,0
Exp/Cntr=0.3,0.1

Type RM Length L Ch R = 1 ,85742   ,507,507,507
BEGIN DESCRIPTION:
SOUTH GRAPE CREEK 146.0
END DESCRIPTION:
XS GIS Cut Line= 3
      2764577.23     10013282.25      2764639.73     10012080.88
      2764459.19     10011719.79
#Sta/Elev= 30
  4255.6 1910.36  4309.4 1904.69  4368.2 1897.94  4404.3 1892.61  4464.4 1887.49
  4524.5 1878.63  4549.5 1876.94  4604.6 1874.34  4760.2 1874.26  4913.8 1868.95
    4935 1869.83  4975.1 1865.78  4992.1 1860.44  4994.9 1859.94  4998.1 1860.44
  5015.1 1862.36  5025.2 1866.29    5041 1869.08  5115.3 1879.19  5142.9 1887.89
  5147.9 1888.04  5195.4 1907.51  5237.6 1917.01  5345.6 1941.18  5415.7 1949.28
    5478 1961.89  5534.6 1966.31  5552.2 1968.13  5679.2 1971.34  5862.3 1971.11
#Mann= 11 ,-1 , 0
  4255.6      .1       0  4309.4     .16       0  4368.2      .1       0
  4549.5     .05       0  4913.8      .1       0  4992.1     .07       0
  4998.1      .1       0    5041     .16       0  5237.6      .1       0
  5534.6     .05       0  5552.2      .1       0
Bank Sta=4975.1,5025.2
XS Rating Curve= 0 ,0
Exp/Cntr=0.3,0.1

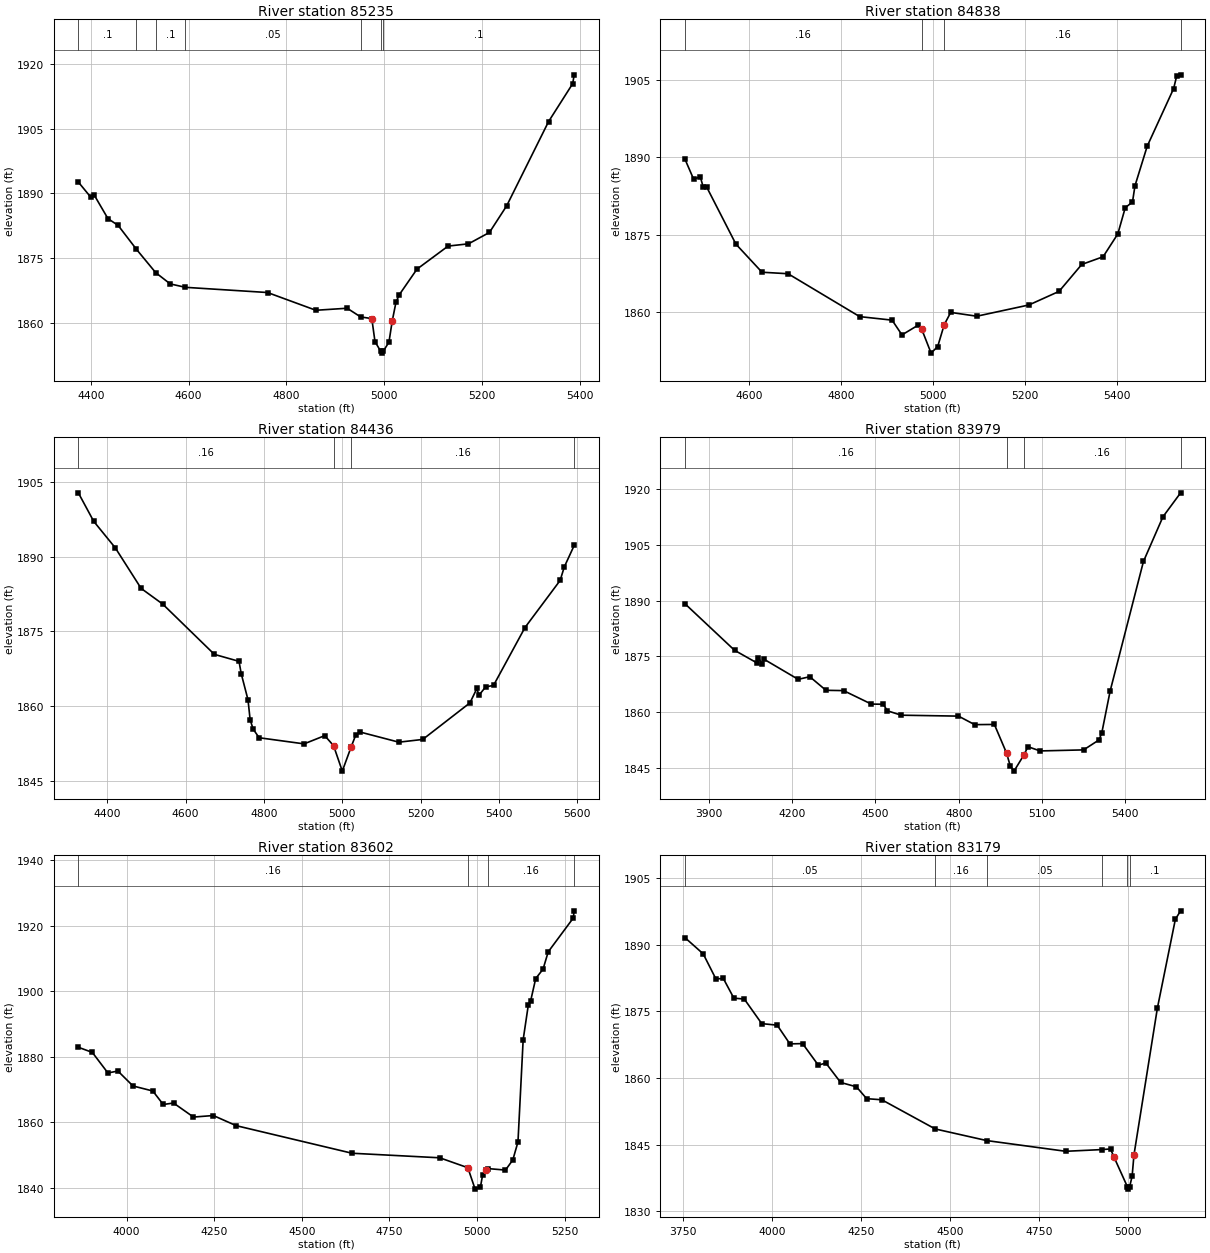
Type RM Length L Ch R = 1 ,85235   ,397,397,397
BEGIN DESCRIPTION:
SOUTH GRAPE CREEK 145.0
END DESCRIPTION:
XS GIS Cut Line= 2
      2764674.47     10013185.03       2765326.6     10012408.02
#Sta/Elev= 30
  4374.4 1892.63  4399.8 1889.14  4406.3 1889.74    4435 1884.18  4455.8 1882.62
  4493.3 1877.09  4532.7  1871.7  4562.4  1869.1  4593.6 1868.31  4761.5 1867.11
  4860.4 1863.01  4924.4 1863.48    4952 1861.47  4974.8 1861.09  4981.3 1855.78
  4992.6 1853.61  4995.4 1853.11  4998.6 1853.61  5009.9 1855.65  5016.5 1860.48
  5024.2 1864.83  5030.8 1866.56  5067.2 1872.51  5130.9 1877.84  5172.6 1878.36
  5215.5 1880.99  5250.8 1887.15  5336.5 1906.61  5385.9 1915.38  5388.8  1917.4
#Mann= 7 ,-1 , 0
  4374.4      .1       0  4493.3     .16       0  4532.7      .1       0
  4593.6     .05       0    4952      .1       0  4992.6     .07       0
  4998.6      .1       0
Bank Sta=4974.8,5016.5
XS Rating Curve= 0 ,0
Exp/Cntr=0.3,0.1

Type RM Length L Ch R = 1 ,84838   ,402,402,402
BEGIN DESCRIPTION:
SOUTH GRAPE CREEK 144.0
END DESCRIPTION:
XS GIS Cut Line= 3
      2764959.15     10013351.74      2765535.57     10012816.99
      2765625.83     10012539.25
#Sta/Elev= 30
  4460.3 1889.69  4479.6 1885.71  4493.8 1886.23  4500.6 1884.16    4508 1884.19
  4571.5 1873.15  4628.2 1867.71  4684.9 1867.42  4840.7 1859.11  4911.1 1858.43
  4932.6 1855.57  4967.8 1857.46  4975.1 1856.78  4995.9 1852.04  5010.3 1853.32
  5024.5 1857.55  5038.6 1859.93  5095.3 1859.19  5208.7 1861.37  5274.2    1864
  5323.6 1869.22    5370 1870.71    5402 1875.13  5418.2 1880.22  5433.9 1881.31
  5439.3 1884.45  5465.9 1892.12  5523.4 1903.29  5529.8 1905.64  5538.6 1905.95
#Mann= 4 ,-1 , 0
  4460.3     .16       0  4975.1     .07       0  5024.5     .16       0
  5538.6      .1       0
Bank Sta=4975.1,5024.5
XS Rating Curve= 0 ,0
Exp/Cntr=0.3,0.1

Type RM Length L Ch R = 1 ,84436   ,457,457,457
BEGIN DESCRIPTION:
SOUTH GRAPE CREEK 143.0
END DESCRIPTION:
XS GIS Cut Line= 4
      2765132.79     10013511.43      2765660.57     10013268.38
      2765764.73      10013053.1       2765806.4     10012608.66
#Sta/Elev= 30
  4325.9 1902.79  4365.2 1897.07  4420.2 1891.76  4486.3 1883.61  4541.3 1880.47
  4673.4 1870.37  4736.4 1868.97  4741.9 1866.53  4759.3 1861.26  4764.8 1857.24
  4772.5 1855.37  4787.8 1853.64  4902.6 1852.41  4955.3 1854.06  4977.9 1852.05
  5000.2 1846.94    5023 1851.84  5034.3 1854.13  5045.4 1854.79  5144.7 1852.75
  5205.7  1853.3  5326.3 1860.64  5344.1 1863.54  5349.1 1862.15  5366.4 1863.84
  5386.5 1864.14  5466.9 1875.76  5556.7 1885.21  5567.3 1887.92  5592.5 1892.22
#Mann= 4 ,-1 , 0
  4325.9     .16       0  4977.9     .07       0    5023     .16       0
  5592.5     .05       0
Bank Sta=4977.9,5023
XS Rating Curve= 0 ,0
Exp/Cntr=0.3,0.1

Type RM Length L Ch R = 1 ,83979   ,377,377,377
BEGIN DESCRIPTION:
SOUTH GRAPE CREEK 142.0
END DESCRIPTION:
XS GIS Cut Line= 3
       2766771.7     10014080.91      2765980.01     10013025.32
       2765993.9     10012560.02
#Sta/Elev= 30
  3813.8 1889.21  3992.9 1876.65    4072 1873.32  4078.3 1874.61  4092.9 1872.95
  4099.1 1874.24    4222 1868.84  4263.7 1869.55    4322 1865.89  4385.3 1865.81
  4485.3 1862.19  4528.3 1862.14  4542.9 1860.39  4592.9  1859.2  4799.1 1858.95
  4857.4 1856.66  4928.3 1856.71    4972 1849.04  4985.3  1845.6  4998.9 1844.16
  5035.3 1848.59  5049.1 1850.73  5092.9 1849.59  5249.5 1849.87    5305 1852.55
    5315 1854.44    5345 1865.68    5465 1900.54  5535.1 1912.54  5598.8 1918.99
#Mann= 4 ,-1 , 0
  3813.8     .16       0    4972     .07       0  5035.3     .16       0
  5598.8     .16       0
Bank Sta=4972,5035.3
XS Rating Curve= 0 ,0
Exp/Cntr=0.3,0.1

Type RM Length L Ch R = 1 ,83602   ,423,423,423
BEGIN DESCRIPTION:
SOUTH GRAPE CREEK 141.0
END DESCRIPTION:
XS GIS Cut Line= 2
      2766973.07     10013796.16      2766161.39      10012637.6
#Sta/Elev= 30
  3862.5 1882.91  3902.4 1881.34  3946.9 1875.06  3975.4 1875.65  4018.4 1871.09
    4075 1869.55  4104.7 1865.43  4134.1 1865.88    4191 1861.59  4247.7 1862.06
    4313 1858.96  4643.4 1850.54  4893.6 1849.15  4973.8 1846.12  4994.5 1839.58
  5009.6 1840.17  5015.7 1843.77  5024.4 1845.43  5030.5 1845.86  5081.1  1845.4
    5102 1848.47  5116.8 1853.99  5131.6  1885.2  5146.4 1895.89  5152.6  1896.9
  5167.4  1903.9  5188.3 1906.75  5203.1 1912.06  5274.6 1922.38  5277.1 1924.58
#Mann= 4 ,-1 , 0
  3862.5     .16       0  4973.8     .07       0  5030.5     .16       0
  5277.1     .16       0
Bank Sta=4973.8,5024.4
XS Rating Curve= 0 ,0
Exp/Cntr=0.3,0.1

Type RM Length L Ch R = 1 ,83179   ,664,664,664
BEGIN DESCRIPTION:
SOUTH GRAPE CREEK 140.0
END DESCRIPTION:
XS GIS Cut Line= 3
       2767334.2     10013719.79       2766681.4      10012803.1
      2766639.74     10012539.24
#Sta/Elev= 30
  3755.8 1891.64  3807.5 1887.96  3843.1 1882.32    3864 1882.42  3893.6 1877.98
  3922.8 1877.79  3971.9 1872.25  4015.3  1871.9  4050.9 1867.69  4086.6 1867.75
  4130.9 1862.88  4151.8 1863.39  4193.5    1859  4237.8 1858.02  4266.6 1855.35
  4309.1  1855.1  4459.1 1848.53    4604 1845.91  4825.5  1843.5  4927.9 1843.89
  4951.4 1844.03  4961.5 1842.14    4999 1835.48  5001.8 1834.98    5005 1835.48
  5012.1 1837.88 5017.27  1842.7    5083 1875.73  5133.6 1895.77  5148.3 1897.65
#Mann= 6 ,-1 , 0
  3755.8     .05       0  4459.1     .16       0    4604     .05       0
  4927.9      .1       0    4999     .07       0    5005      .1       0
Bank Sta=4961.5,5017.27
XS Rating Curve= 0 ,0
Exp/Cntr=0.3,0.1

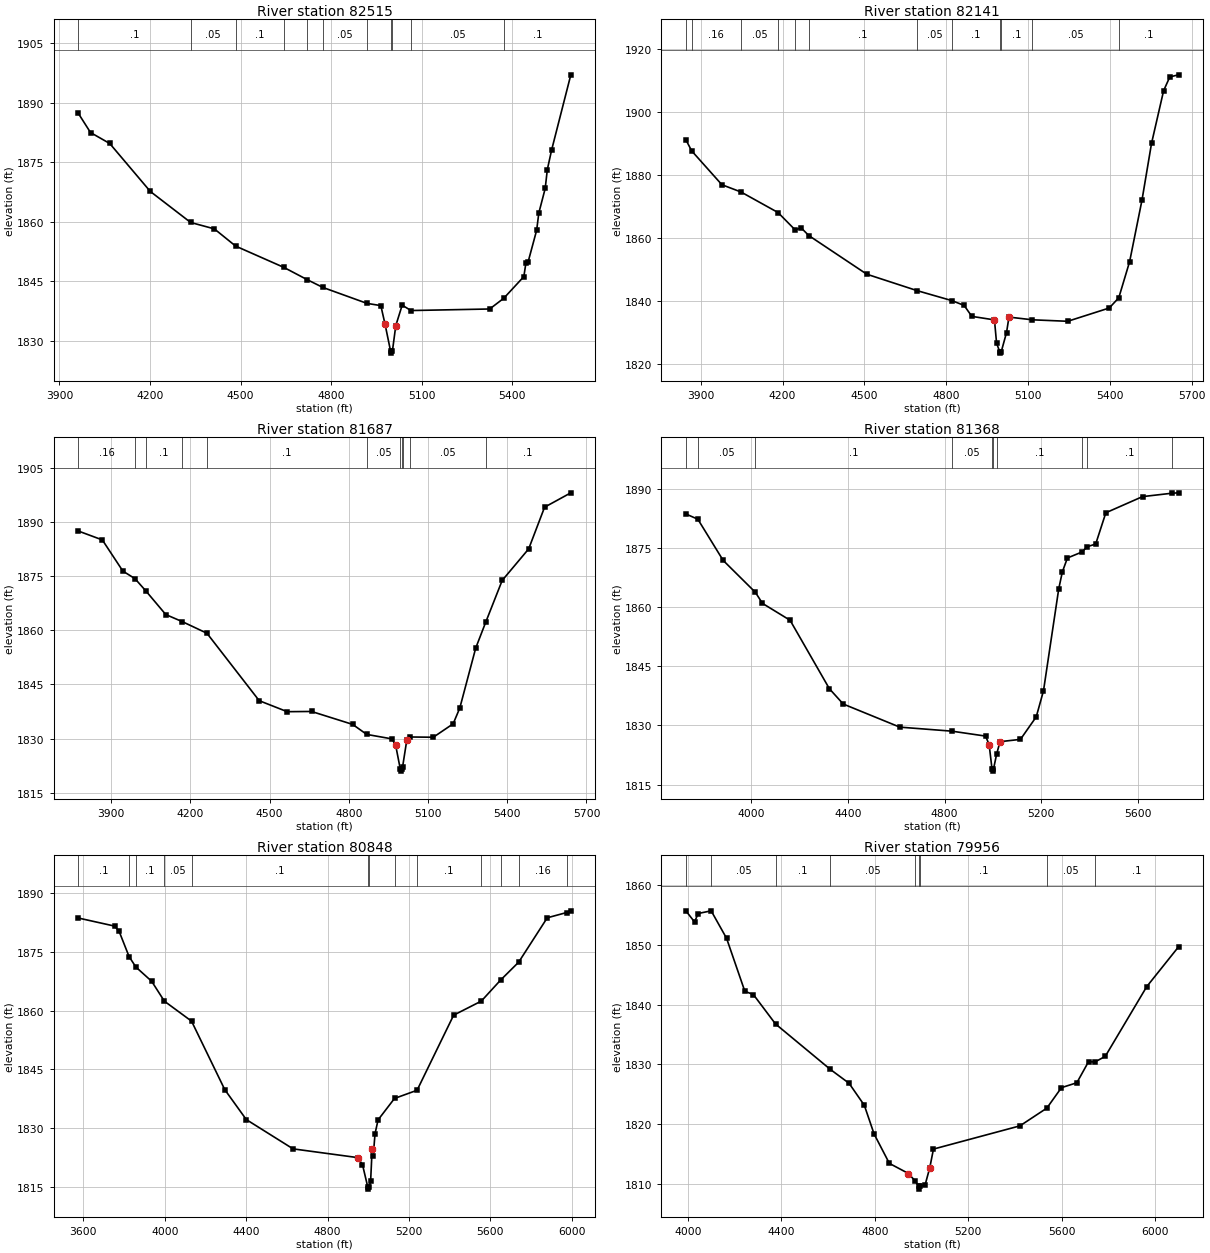
Type RM Length L Ch R = 1 ,82515   ,374,374,374
BEGIN DESCRIPTION:
SOUTH GRAPE CREEK 139.0
END DESCRIPTION:
XS GIS Cut Line= 2
      2768000.84     10013289.21      2766843.46     10012138.75
#Sta/Elev= 30
  3962.1 1887.41    4003 1882.52  4066.6 1879.76    4201 1867.68  4334.7 1859.86
  4413.1 1858.25  4483.7 1853.91  4643.5 1848.54  4720.2 1845.47  4772.7 1843.49
  4918.6 1839.48  4964.7 1838.91  4978.8 1834.17    4997 1827.44  4999.8 1826.94
    5003 1827.44  5014.2 1833.86  5035.4 1839.03  5064.5 1837.67  5325.3 1838.06
    5372 1840.77  5438.4 1846.22  5445.5 1849.76  5452.6 1849.93  5480.9 1857.92
    5488 1862.24  5509.2 1868.44  5516.2 1873.19  5530.4 1878.11    5594 1897.06
#Mann= 11 ,-1 , 0
  3962.1      .1       0  4334.7     .05       0  4483.7      .1       0
  4643.5     .05       0  4720.2      .1       0  4772.7     .05       0
  4918.6      .1       0    4997     .07       0    5003      .1       0
  5064.5     .05       0    5372      .1       0
Bank Sta=4978.8,5014.2
XS Rating Curve= 0 ,0
Exp/Cntr=0.3,0.1

Type RM Length L Ch R = 1 ,82141   ,454,454,454
BEGIN DESCRIPTION:
SOUTH GRAPE CREEK 138.0
END DESCRIPTION:
XS GIS Cut Line= 3
      2768348.09     10012969.79      2767598.07     10012310.04
      2766868.91     10011962.83
#Sta/Elev= 30
  3845.6 1891.15  3866.6 1887.65  3977.5 1876.88  4047.7 1874.57  4183.4 1868.04
  4246.3 1862.51  4267.9  1863.2    4296 1860.74  4508.9 1848.44  4693.8 1843.21
  4821.1 1840.04  4865.7 1838.53    4894 1835.04    4977 1833.92  4984.8 1826.51
  4996.1 1823.86  4998.9 1823.36  5002.1 1823.86  5021.3 1829.91  5030.2 1834.81
  5116.2 1833.95  5245.6 1833.48  5397.9  1837.7  5432.9 1840.95  5472.7 1852.46
  5518.1 1872.04  5552.9 1889.99  5597.3 1906.77    5620 1911.15  5652.1 1911.81
#Mann= 12 ,-1 , 0
  3845.6      .1       0  3866.6     .16       0  4047.7     .05       0
  4183.4      .1       0  4246.3     .05       0    4296      .1       0
  4693.8     .05       0  4821.1      .1       0  4996.1     .07       0
  5002.1      .1       0  5116.2     .05       0  5432.9      .1       0
Bank Sta=4977,5030.2
XS Rating Curve= 0 ,0
Exp/Cntr=0.3,0.1

Type RM Length L Ch R = 1 ,81687   ,319,319,319
BEGIN DESCRIPTION:
SOUTH GRAPE CREEK 137.0
END DESCRIPTION:
XS GIS Cut Line= 3
      2768535.56     10012705.87      2767577.23     10011775.32
      2767049.45     10011733.66
#Sta/Elev= 30
  3775.6 1887.51  3867.1 1885.03  3944.8  1876.4  3990.8 1874.29  4032.9 1870.81
  4107.3 1864.35  4169.2 1862.41  4263.2 1859.17    4461 1840.49    4567 1837.44
  4659.1  1837.5  4814.7 1833.92  4868.1 1831.14  4963.1 1829.91  4977.3 1828.27
  4995.4 1821.47  4998.1 1820.97  5001.4 1821.47  5003.8 1822.09  5019.7  1829.5
  5031.5 1830.43  5120.2 1830.36  5195.3 1834.08  5220.5 1838.46  5280.7 1855.05
  5318.3 1862.17    5381 1873.81  5481.3 1882.55  5541.5  1894.1  5640.8 1898.08
#Mann= 11 ,-1 , 0
  3775.6     .16       0  3990.8     .05       0  4032.9      .1       0
  4169.2     .05       0  4263.2      .1       0  4868.1     .05       0
  4995.4    .035       0  5001.4     .05       0  5003.8      .1       0
  5031.5     .05       0  5318.3      .1       0
Bank Sta=4977.3,5019.7
XS Rating Curve= 0 ,0
Exp/Cntr=0.3,0.1

Type RM Length L Ch R = 1 ,81368   ,520,520,520
BEGIN DESCRIPTION:
SOUTH GRAPE CREEK 136.0
END DESCRIPTION:
XS GIS Cut Line= 3
      2768653.65     10012525.35       2767931.4     10011657.27
      2767174.43     10011150.31
#Sta/Elev= 30
    3729 1883.55  3778.3 1882.23  3883.2  1871.8  4016.8 1863.71  4045.9 1860.92
  4160.4 1856.64  4323.2  1839.3  4380.5 1835.43  4614.8 1829.58  4830.4 1828.56
  4970.1 1827.31  4984.8 1825.14  4996.8 1818.94  4999.5 1818.44  5002.8 1818.94
  5015.7  1822.7  5029.8  1825.9  5114.5 1826.48  5179.9 1832.19  5209.9 1838.78
    5273 1864.58    5288 1868.89    5309 1872.41  5369.4 1873.93  5390.5 1875.26
  5426.1 1875.94  5468.1 1883.86    5620 1887.95  5741.8 1888.81  5769.3 1888.91
#Mann= 10 ,-1 , 0
    3729     .16       0  3778.3     .05       0  4016.8      .1       0
  4830.4     .05       0  4996.8    .035       0  5002.8     .05       0
  5015.7      .1       0  5369.4     .16       0  5390.5      .1       0
  5741.8     .16       0
Bank Sta=4984.8,5029.8
XS Rating Curve= 0 ,0
Exp/Cntr=0.3,0.1

Type RM Length L Ch R = 1 ,80848   ,892,892,892
BEGIN DESCRIPTION:
SOUTH GRAPE CREEK 135.0
END DESCRIPTION:
XS GIS Cut Line= 3
      2768764.74     10012608.68       2768118.9     10011073.93
      2767362.69     10011094.75
#Sta/Elev= 30
  3574.4 1883.72  3753.1 1881.65  3775.1 1880.38  3824.7 1873.85  3858.1 1871.18
  3935.5 1867.55  3998.3 1862.45  4131.7 1857.35    4295 1839.85  4400.8  1832.2
  4630.7 1824.71  4948.2 1822.48  4971.9  1820.7  4998.1 1814.92  5000.8 1814.42
  5004.1 1814.92  5011.9 1816.41  5019.4 1824.63  5024.8 1822.89  5033.6 1828.58
  5048.6 1832.12  5129.4  1837.6  5240.3 1839.69    5420 1858.88  5556.1 1862.48
  5651.2 1867.87  5739.7 1872.43  5880.2 1883.77  5975.3 1885.11    5996 1885.55
#Mann= 13 ,-1 , 0
  3574.4      .1       0  3824.7     .05       0  3858.1      .1       0
  3998.3     .05       0  4131.7      .1       0  4998.1     .07       0
  5004.1      .1       0  5129.4     .16       0  5240.3      .1       0
  5556.1     .16       0  5651.2      .1       0  5739.7     .16       0
  5975.3      .1       0
Bank Sta=4948.2,5019.4
XS Rating Curve= 0 ,0
Exp/Cntr=0.3,0.1

Type RM Length L Ch R = 1 ,79956   ,638,638,638
BEGIN DESCRIPTION:
SOUTH GRAPE CREEK 134.0
END DESCRIPTION:
XS GIS Cut Line= 3
      2769584.16     10011810.02      2769077.23     10011087.82
      2767868.85     10010886.43
#Sta/Elev= 30
  3991.8 1855.64  4028.9 1853.78  4043.7  1855.2  4099.8 1855.65  4165.7 1851.06
  4243.8 1842.21  4280.5 1841.66  4375.1 1836.75  4609.9 1829.15  4689.5 1826.85
  4754.9 1823.17  4796.7 1818.38  4862.1 1813.46  4943.9 1811.77  4972.6 1810.51
  4986.9 1809.66  4989.6 1809.16  4992.9 1809.66  5014.8 1809.84  5035.1 1812.76
  5050.7 1815.85  5420.7 1819.73  5535.7 1822.69  5598.2 1826.11  5664.1 1826.93
  5714.4 1830.47  5740.9 1830.39  5785.7 1831.34  5963.1 1842.99  6099.2 1849.64
#Mann= 9 ,-1 , 0
  3991.8      .1       0  4099.8     .05       0  4375.1      .1       0
  4609.9     .05       0  4972.6      .1       0  4986.9     .07       0
  4992.9      .1       0  5535.7     .05       0  5740.9      .1       0
Bank Sta=4943.9,5035.1
XS Rating Curve= 0 ,0
Exp/Cntr=0.3,0.1

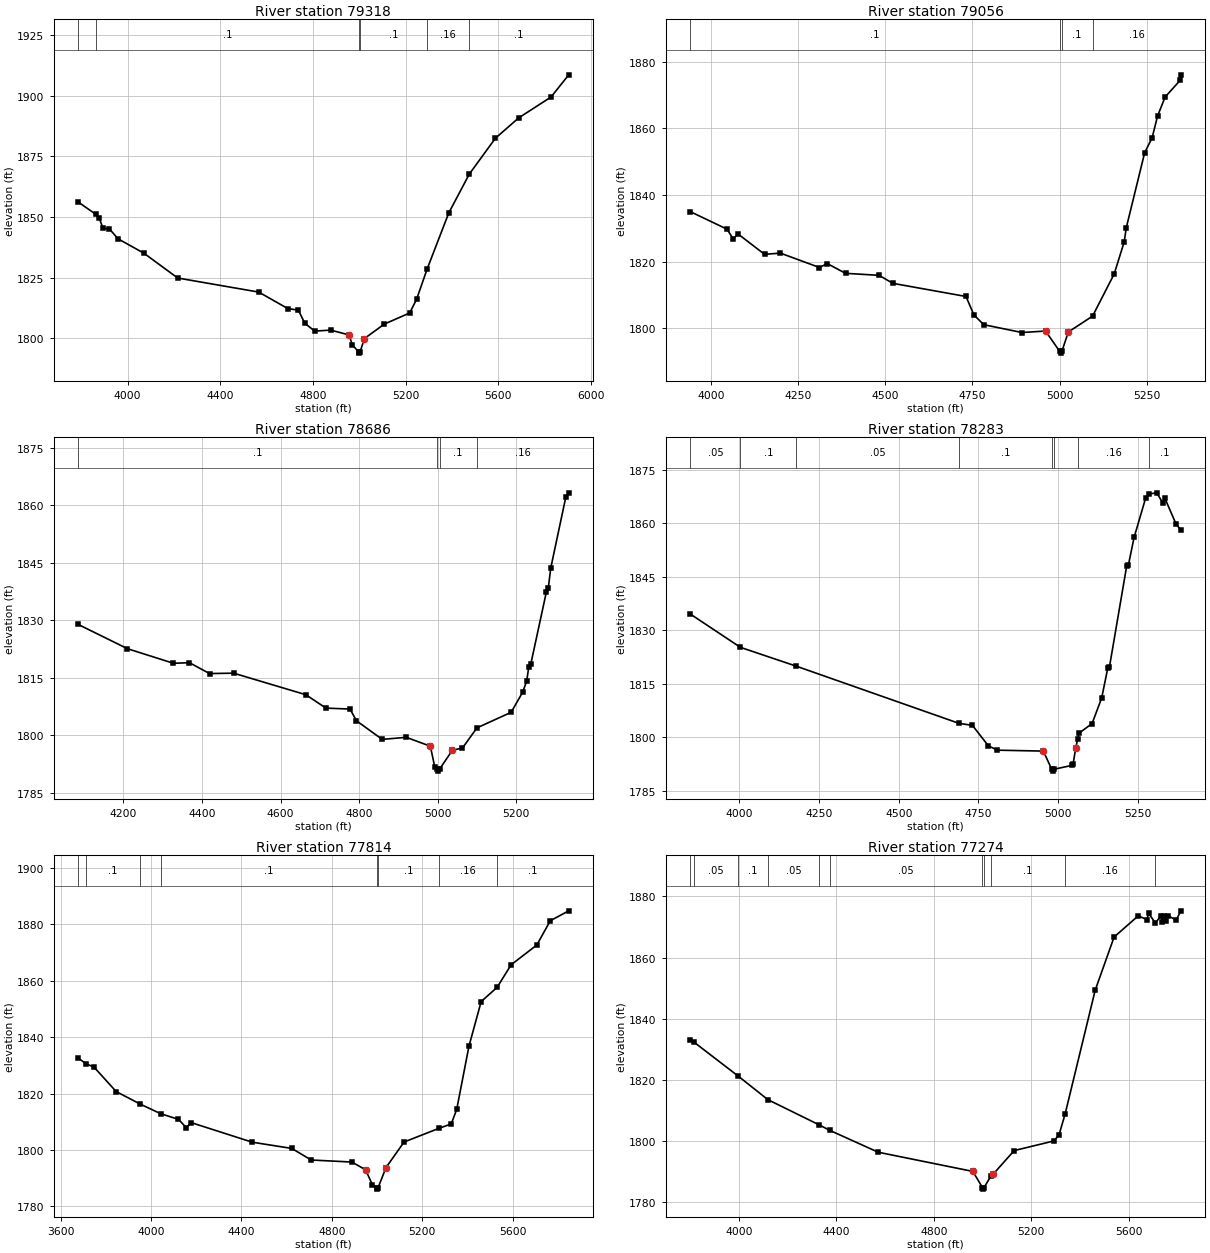
Type RM Length L Ch R = 1 ,79318   ,262,262,262
BEGIN DESCRIPTION:
SOUTH GRAPE CREEK 133.0
END DESCRIPTION:
XS GIS Cut Line= 3
      2769688.33     10011560.01      2769028.62     10010407.27
      2769042.48     10009617.16
#Sta/Elev= 30
  3786.2 1856.21  3863.4 1851.07  3878.2 1849.41    3894  1845.3  3921.4 1845.11
  3958.8 1841.03    4070 1835.13  4216.4 1824.89  4566.1  1819.1  4692.1 1812.29
  4737.3 1811.68  4764.7 1806.29  4807.9 1803.03  4876.5 1803.45  4957.1 1801.44
  4969.1 1797.48  4997.7 1794.47  5000.5 1793.97  5003.7 1794.47  5022.3 1799.97
  5108.6 1805.94  5217.9  1810.5  5247.9 1816.19  5292.5 1828.43  5386.7 1851.71
  5475.3 1867.69    5588 1882.44    5688 1890.78    5828  1899.4  5904.6 1908.54
#Mann= 6 ,-1 , 0
  3786.2     .05       0  3863.4      .1       0  4997.7     .07       0
  5003.7      .1       0  5292.5     .16       0  5475.3      .1       0
Bank Sta=4957.1,5022.3
XS Rating Curve= 0 ,0
Exp/Cntr=0.3,0.1

Type RM Length L Ch R = 1 ,79056   ,370,370,370
BEGIN DESCRIPTION:
SOUTH GRAPE CREEK 132.0
END DESCRIPTION:
XS GIS Cut Line= 3
      2769736.95     10011268.37      2769355.01     10010469.77
      2769091.22     10010018.55
#Sta/Elev= 30
  3940.1 1835.02  4045.7 1829.74  4062.8 1826.93  4078.3 1828.22  4153.5 1822.18
  4198.9 1822.54    4311 1818.22  4333.2 1819.41  4385.8 1816.47  4482.1 1815.87
  4521.6 1813.46  4731.5 1809.51  4754.1 1803.97  4782.4 1801.04  4891.9 1798.68
  4959.7 1799.13  5000.5 1792.99  5003.3 1792.49  5006.5 1792.99    5025 1798.84
  5094.6 1803.61  5156.7  1816.3  5185.3  1825.9  5191.4 1830.21    5244 1852.69
  5265.5 1857.22  5281.2 1863.76  5302.7 1869.44  5345.7 1874.45    5348 1876.12
#Mann= 4 ,-1 , 0
  3940.1      .1       0  5000.5     .07       0  5006.5      .1       0
  5094.6     .16       0
Bank Sta=4959.7,5025
XS Rating Curve= 0 ,0
Exp/Cntr=0.3,0.1

Type RM Length L Ch R = 1 ,78686   ,403,403,403
BEGIN DESCRIPTION:
SOUTH GRAPE CREEK 131.0
END DESCRIPTION:
XS GIS Cut Line= 2
      2769799.46     10011171.16      2769542.52     10009948.97
#Sta/Elev= 30
  4084.5 1828.93  4210.2 1822.59  4327.1 1818.79    4368 1818.94  4419.1 1816.11
  4480.4 1816.21  4664.3 1810.59  4715.4  1807.1  4776.7 1806.85  4793.1  1803.8
  4858.5 1798.95  4919.8 1799.48  4981.1 1797.17  4992.5 1791.68  4998.5 1791.17
  5001.3 1790.67  5004.5 1791.17  5037.2 1796.12  5062.9  1796.7  5099.6 1801.94
  5186.8 1806.01  5216.1 1811.26  5226.4 1814.17  5231.5 1817.75  5236.6  1818.5
  5276.3 1837.33  5281.4  1838.5  5287.7 1843.68  5326.1 1862.22  5333.4 1863.23
#Mann= 4 ,-1 , 0
  4084.5      .1       0  4998.5     .07       0  5004.5      .1       0
  5099.6     .16       0
Bank Sta=4981.1,5037.2
XS Rating Curve= 0 ,0
Exp/Cntr=0.3,0.1

Type RM Length L Ch R = 1 ,78283   ,469,469,469
BEGIN DESCRIPTION:
SOUTH GRAPE CREEK 130.0
END DESCRIPTION:
XS GIS Cut Line= 3
      2769917.51     10011310.05      2770035.57     10010421.16
      2769924.46     10009789.25
#Sta/Elev= 30
  3846.2 1834.58  4003.7 1825.21  4179.4 1819.91  4688.4  1803.9  4731.1 1803.31
  4780.9 1797.58  4809.5 1796.36  4953.5  1796.1  4979.5 1790.98  4982.2 1790.48
  4985.5 1790.98  5041.8 1792.07  5046.9 1792.62    5055  1797.1    5061 1799.47
  5065.2 1801.13  5106.2 1803.84  5136.3 1811.05  5155.4 1819.43  5160.5 1819.68
  5214.7 1848.09  5219.8 1848.24  5237.8 1856.06    5274 1867.09  5285.4 1868.26
  5308.9 1868.57  5328.3 1865.65  5333.4 1867.24  5369.8 1859.72  5384.5 1858.18
#Mann= 8 ,-1 , 0
  3846.2     .05       0  4003.7      .1       0  4179.4     .05       0
  4688.4      .1       0  4979.5     .07       0  4985.5      .1       0
    5061     .16       0  5285.4      .1       0
Bank Sta=4953.5,5055
XS Rating Curve= 0 ,0
Exp/Cntr=0.3,0.1

Type RM Length L Ch R = 1 ,77814   ,540,540,540
BEGIN DESCRIPTION:
SOUTH GRAPE CREEK 129.0
END DESCRIPTION:
XS GIS Cut Line= 3
      2770348.06     10011442.03      2770473.07     10009879.49
      2770251.19     10009317.87
#Sta/Elev= 30
  3677.3  1832.6  3712.2 1830.57  3747.9 1829.35  3846.1 1820.69  3952.7 1816.25
  4042.3 1812.88  4121.6 1810.85  4157.1 1807.87  4177.2 1809.72  4448.1 1802.77
  4623.2 1800.56  4708.9 1796.46  4889.5 1795.74  4949.7 1792.98  4979.8 1787.69
  4998.9 1786.65  5001.7 1786.15  5004.9 1786.65  5039.9 1793.77  5119.8 1802.83
  5272.9 1807.64  5328.5 1809.23  5352.9 1814.38    5407 1836.76  5461.1 1852.58
  5531.7 1857.61  5593.6  1865.6  5707.2 1872.59  5767.1 1881.21  5848.7 1884.71
#Mann= 8 ,-1 , 0
  3677.3     .05       0  3712.2      .1       0  3952.7     .05       0
  4042.3      .1       0  4998.9     .07       0  5004.9      .1       0
  5272.9     .16       0  5531.7      .1       0
Bank Sta=4949.7,5039.9
XS Rating Curve= 0 ,0
Exp/Cntr=0.3,0.1

Type RM Length L Ch R = 1 ,77274   ,482,482,482
BEGIN DESCRIPTION:
SOUTH GRAPE CREEK 128.0
END DESCRIPTION:
XS GIS Cut Line= 3
      2770528.62      10011490.6      2770820.29      10010428.1
      2771444.38      10009762.4
#Sta/Elev= 30
  3799.7 1833.05  3816.1  1832.3  3996.1 1821.29  4118.6 1813.55  4329.6 1805.29
  4372.2 1803.53  4571.3 1796.37  4960.1 1790.09  4999.5  1784.8  5002.3  1784.3
  5005.5  1784.8  5034.5 1788.55  5044.6 1789.29  5129.6  1796.9  5292.2 1800.04
  5313.7 1802.02  5338.8 1808.87  5462.2 1849.31  5539.9 1866.72    5639 1873.64
  5674.7 1872.39  5681.5 1874.44  5709.7 1871.26  5730.9 1873.57  5738.2 1871.72
    5745 1873.71  5752.3 1871.92  5759.2 1873.75  5794.8 1872.26    5814 1875.28
#Mann= 11 ,-1 , 0
  3799.7      .1       0  3816.1     .05       0  3996.1      .1       0
  4118.6     .05       0  4329.6      .1       0  4372.2     .05       0
  4999.5    .035       0  5005.5     .05       0  5034.5      .1       0
  5338.8     .16       0  5709.7      .1       0
Bank Sta=4960.1,5044.6
XS Rating Curve= 0 ,0
Exp/Cntr=0.3,0.1