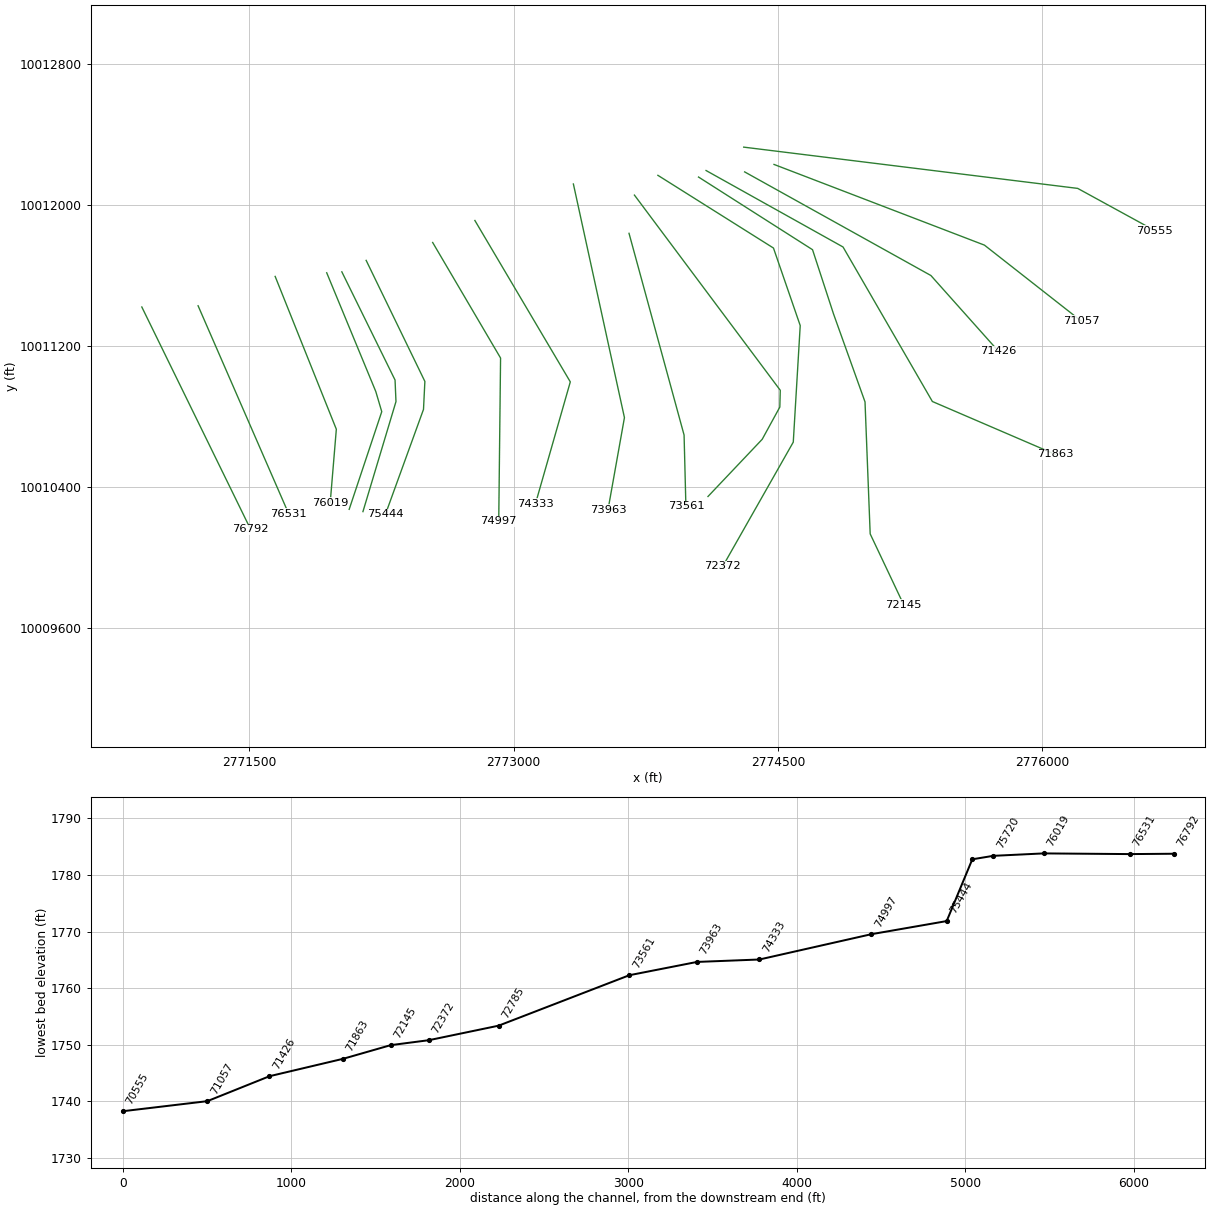
HEC-RAS study SOUTH GRAPE CREEK.prj: SOUTH GRAPE CREEK Base Level Engineering

--- SOUTH GRAPE CREEK.g01 (geometry) --- (continued)

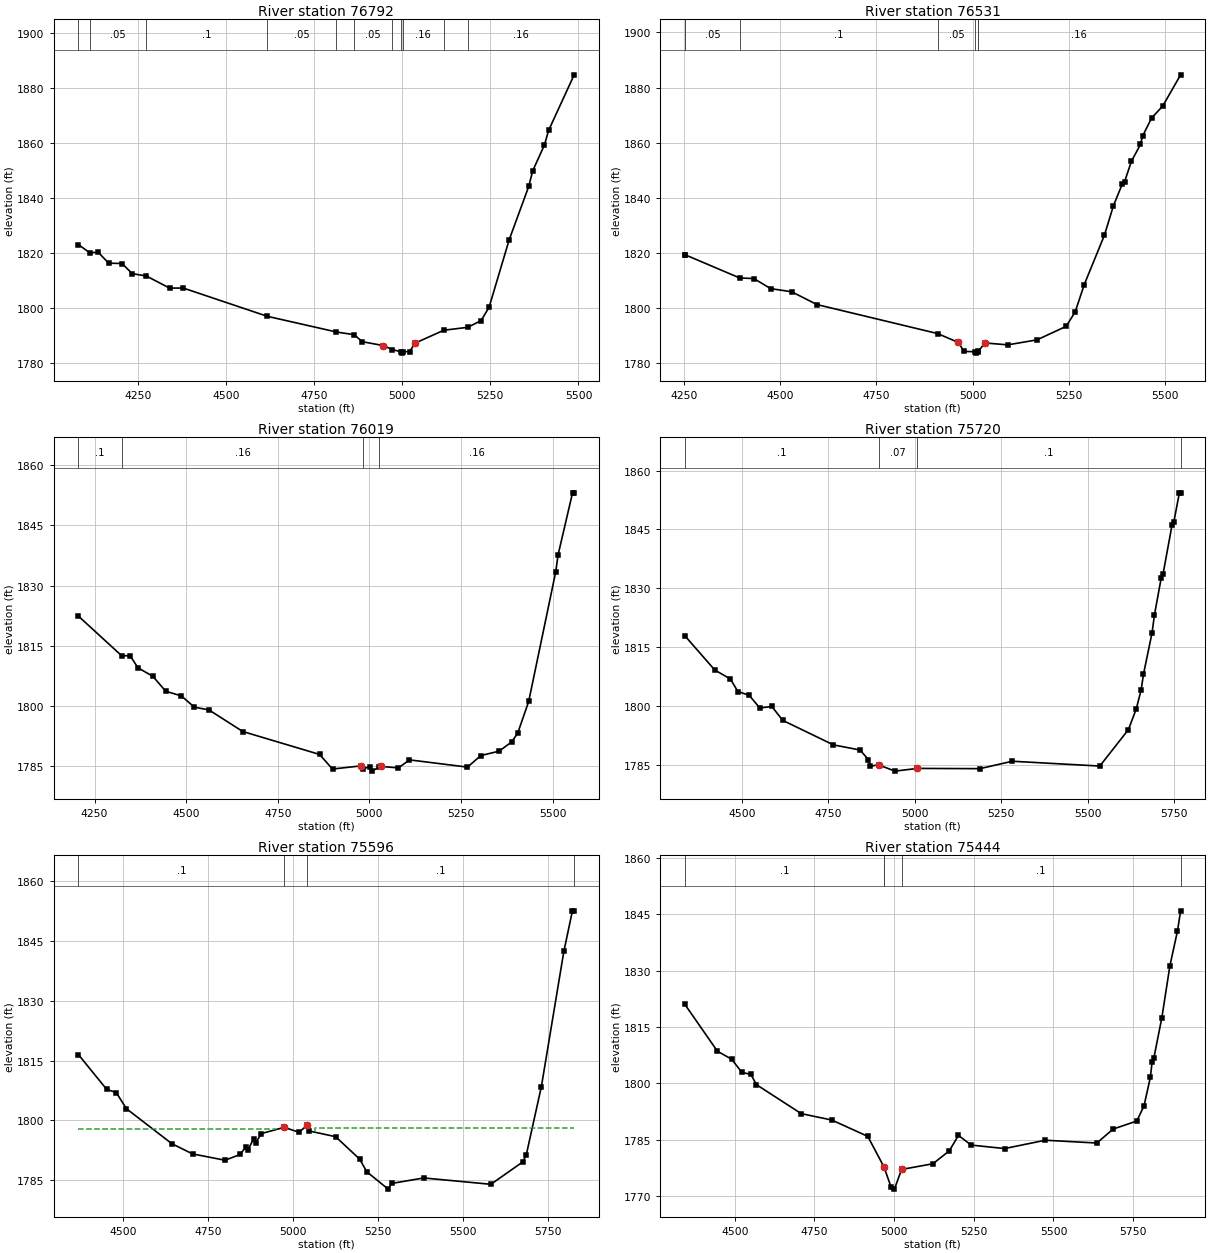
Type RM Length L Ch R = 1 ,76792   ,261,261,261
BEGIN DESCRIPTION:
SOUTH GRAPE CREEK 127.0
END DESCRIPTION:
XS GIS Cut Line= 2
      2770889.72     10011421.17      2771507.42     10010158.02
#Sta/Elev= 30
  4081.7 1823.27  4113.7 1820.29  4137.9 1820.46  4167.9 1816.48  4205.5 1816.36
  4234.7 1812.66  4274.2 1811.84  4340.5 1807.42  4379.4 1807.43  4617.6 1797.16
  4813.4 1791.46  4864.5 1790.46  4886.4 1787.94  4947.1  1786.5  4971.7 1785.07
    4996 1784.27  4998.7 1783.77    5002 1784.27  5021.5 1784.34  5036.2 1787.38
  5118.2 1792.09  5186.2 1793.16  5224.1 1795.63  5246.6 1800.47  5303.3  1824.9
    5359  1844.4  5370.3 1850.06  5403.5 1859.46  5415.4 1864.77  5487.8 1884.97
#Mann= 11 ,-1 , 0
  4081.7      .1       0  4113.7     .05       0  4274.2      .1       0
  4617.6     .05       0  4813.4      .1       0  4864.5     .05       0
  4971.7     .16       0    4996     .07       0    5002     .16       0
  5118.2      .1       0  5186.2     .16       0
Bank Sta=4947.1,5036.2
XS Rating Curve= 0 ,0
Exp/Cntr=0.3,0.1

Type RM Length L Ch R = 1 ,76531   ,512,512,512
BEGIN DESCRIPTION:
SOUTH GRAPE CREEK 126.0
END DESCRIPTION:
XS GIS Cut Line= 2
      2771209.18     10011428.09      2771722.81     10010248.13
#Sta/Elev= 30
  4252.9 1819.32  4254.7 1819.32  4395.3 1810.97  4432.2 1810.75  4475.8  1807.1
  4530.3 1805.96  4595.7 1801.33  4908.9 1790.81  4963.1 1787.57  4977.5 1784.33
    5007 1784.21  5009.8 1783.71    5013 1784.21  5014.2 1784.32    5032  1787.4
  5091.2 1786.71    5167 1788.52  5242.7 1793.43  5266.2 1798.68  5289.6 1808.54
  5341.9 1826.43  5365.4 1837.15  5388.8  1845.2  5394.2 1845.83  5412.2 1853.31
  5435.5 1859.37  5441.1 1862.44  5464.5 1868.96  5493.4 1873.33  5539.8 1884.63
#Mann= 7 ,-1 , 0
  4252.9      .1       0  4254.7     .05       0  4395.3      .1       0
  4908.9     .05       0    5007    .035       0    5013     .05       0
  5014.2     .16       0
Bank Sta=4963.1,5032
XS Rating Curve= 0 ,0
Exp/Cntr=0.3,0.1

Type RM Length L Ch R = 1 ,76019   ,299,299,299
BEGIN DESCRIPTION:
SOUTH GRAPE CREEK 125.0
END DESCRIPTION:
XS GIS Cut Line= 3
      2771646.69     10011594.74       2771993.9     10010726.71
      2771959.18     10010310.05
#Sta/Elev= 30
  4205.8 1822.42  4324.7 1812.49  4346.9 1812.58  4368.4 1809.55  4409.3 1807.41
  4444.3 1803.71  4486.9 1802.55  4522.4 1799.75  4562.3 1799.06  4654.4 1793.69
  4863.9 1787.99  4899.4 1784.35  4977.5 1785.14  4982.9 1784.44  5001.7 1784.94
  5006.8 1783.83  5025.4 1784.77  5031.3    1785  5079.3 1784.63  5109.4 1786.63
  5267.7 1784.83  5304.2  1787.7  5354.4 1788.81  5388.1 1791.09  5404.6 1793.24
  5434.7 1801.16  5508.6 1833.48    5515 1837.67  5554.4 1853.08  5558.8 1853.08
#Mann= 4 ,-1 , 0
  4205.8      .1       0  4324.7     .16       0  4982.9     .07       0
  5025.4     .16       0
Bank Sta=4977.5,5031.3
XS Rating Curve= 0 ,0
Exp/Cntr=0.3,0.1

Type RM Length L Ch R = 1 ,75720   ,124,124,124
BEGIN DESCRIPTION:
SOUTH GRAPE CREEK 124.0
END DESCRIPTION:
XS GIS Cut Line= 4
      2771939.22     10011615.59      2772217.86     10010941.12
      2772251.71     10010826.54      2772066.83     10010271.88
#Sta/Elev= 30
  4335.2 1817.91  4421.6 1809.19  4467.1 1806.88  4488.7 1803.68  4521.2 1802.74
    4552  1799.5  4586.8 1799.88  4618.5 1796.33    4765 1790.09  4842.1 1788.78
  4866.1 1786.33  4871.5 1784.64  4895.4 1785.01  4942.9  1783.4    5008 1784.09
  5188.6 1784.03  5282.3 1785.92  5535.3 1784.69    5618 1793.96  5640.7 1799.23
  5654.9 1804.09  5661.7 1808.11  5686.5 1818.65  5693.4  1823.2  5712.8 1832.57
  5718.1 1833.55  5744.5 1846.23  5749.7    1847  5765.5 1854.32  5769.1 1854.32
#Mann= 4 ,-1 , 0
  4335.2      .1       0  4895.4     .07       0    5008      .1       0
  5769.1     .16       0
Bank Sta=4895.4,5008
XS Rating Curve= 0 ,0
Exp/Cntr=0.3,0.1

Type RM Length L Ch R = 1 ,75596   ,152,152,152
BEGIN DESCRIPTION:
Mapping XS c15b15bf
END DESCRIPTION:
XS GIS Cut Line= 4
      2772025.16     10011620.79      2772327.23     10011006.22
      2772332.44     10010883.83      2772144.95     10010258.85
#Sta/Elev= 30
  4367.5 1816.52  4451.1 1807.77  4479.1    1807  4509.1 1802.94  4642.8 1794.18
  4703.9 1791.61  4799.4 1790.03  4844.3 1791.48  4861.2 1793.47  4866.8 1792.59
  4883.7 1795.41  4889.3 1794.31  4906.2 1796.71  4973.6 1798.27  5017.1 1797.04
  5041.1 1798.77  5046.6 1797.37  5124.9 1795.93  5195.8 1790.31  5216.7 1787.14
  5279.8 1782.79  5289.7 1784.21  5384.5 1785.59  5582.1    1784    5676 1789.61
  5686.5 1791.44  5730.8 1808.49  5796.9 1842.33  5822.2 1852.52  5827.3 1852.52
#Mann= 4 ,-1 , 0
  4367.5      .1       0  4973.6     .05       0  5041.1      .1       0
  5827.3     .16       0
#XS Ineff= 2 , 0
       0 4951.37 1797.97  5064.9       0 1798.12
Permanent Ineff=
       T       T
Bank Sta=4973.6,5041.1
XS Rating Curve= 0 ,0
Exp/Cntr=0.3,0.1

Type RM Length L Ch R = 1 ,75444   ,447,447,447
BEGIN DESCRIPTION:
SOUTH GRAPE CREEK 123.0
END DESCRIPTION:
XS GIS Cut Line= 4
      2772163.17     10011685.91       2772496.5     10010998.41
      2772488.69     10010839.56      2772272.99     10010244.44
#Sta/Elev= 30
    4343 1821.02  4445.4 1808.54  4489.9 1806.42  4522.4 1802.89  4550.5  1802.4
  4567.5 1799.67  4708.5 1791.94  4804.4 1790.24  4917.2  1785.9  4967.9 1777.81
  4990.5 1772.39  5000.9 1771.87  5023.3  1777.1  5121.7 1778.62  5172.9 1782.03
  5201.8 1786.15  5241.9 1783.58  5346.7 1782.66  5474.4 1784.87  5636.4 1784.13
    5687 1787.83  5761.6 1789.98  5784.2 1794.02  5804.1 1801.59  5809.6 1805.71
  5814.9 1806.66  5840.2 1817.47  5865.5 1831.28  5889.2 1840.51  5899.1 1845.87
#Mann= 5 ,-1 , 0
    4343      .1       0  4967.9     .05       0  4967.9     .07       0
  5023.3      .1       0  5899.1     .16       0
Bank Sta=4967.9,5023.3
XS Rating Curve= 0 ,0
Exp/Cntr=0.3,0.1

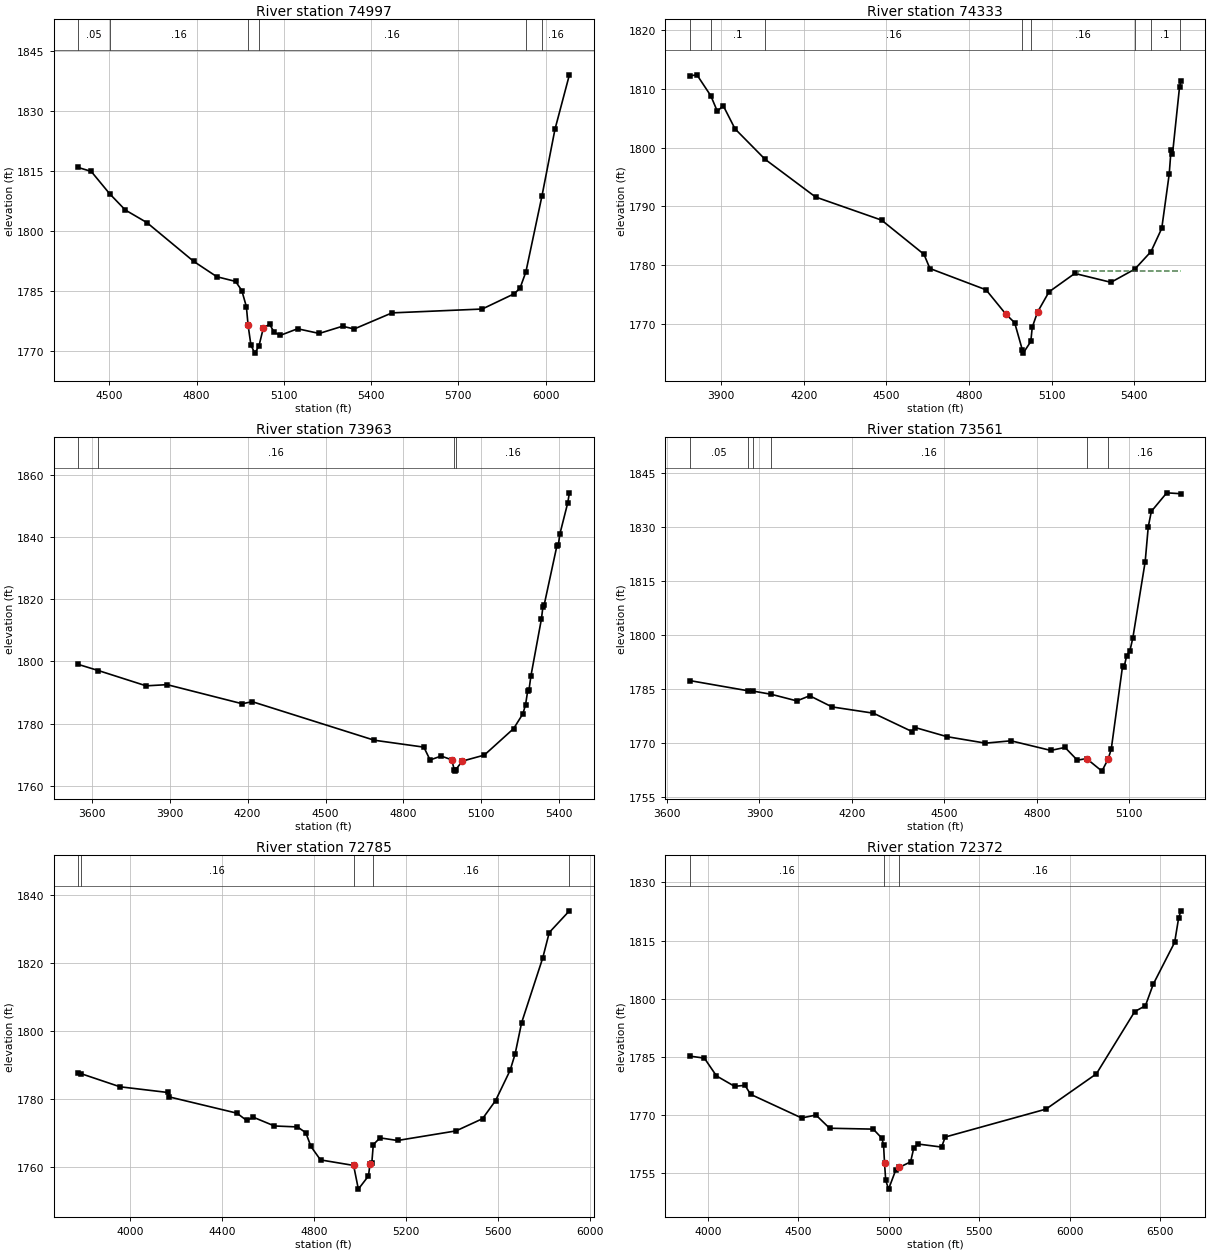
Type RM Length L Ch R = 1 ,74997   ,664,664,664
BEGIN DESCRIPTION:
SOUTH GRAPE CREEK 122.0
END DESCRIPTION:
XS GIS Cut Line= 3
      2772540.75     10011787.51      2772926.19     10011131.22
      2772915.78     10010204.19
#Sta/Elev= 30
  4393.1 1815.87    4438 1814.89  4501.6  1809.3  4555.2 1805.26  4629.4 1802.12
  4789.7 1792.47  4869.8 1788.61  4934.2 1787.44  4955.6 1785.17  4971.3 1781.15
  4977.3 1776.46    4987 1771.53  5000.3 1769.55  5014.3 1771.27  5029.9 1775.89
  5051.4 1776.74  5067.1 1774.71  5088.5    1774  5147.2 1775.63  5221.7 1774.46
  5301.7 1776.26  5341.7 1775.57  5471.7 1779.59  5781.7 1780.55  5891.7 1784.36
  5911.7 1785.77  5931.7 1789.79  5986.7 1808.64  6031.8 1825.41  6081.3 1838.98
#Mann= 6 ,-1 , 0
  4393.1     .05       0  4501.6     .16       0  4977.3     .07       0
  5014.3     .16       0  5931.7      .1       0  5986.7     .16       0
Bank Sta=4977.3,5029.9
XS Rating Curve= 0 ,0
Exp/Cntr=0.3,0.1

Type RM Length L Ch R = 1 ,74333   ,370,370,370
BEGIN DESCRIPTION:
SOUTH GRAPE CREEK 121.0
END DESCRIPTION:
XS GIS Cut Line= 3
      2772780.34      10011912.5      2773322.02     10010995.81
      2773124.11      10010303.1
#Sta/Elev= 30
  3784.5 1812.19  3811.2 1812.37  3861.8  1808.8  3885.4 1806.17  3906.8 1807.13
  3949.7 1803.19  4058.8 1798.02  4242.3 1791.61  4482.2 1787.68  4636.3 1781.87
  4657.8 1779.46  4861.8 1775.84  4934.6 1771.66  4965.8 1770.25    4994 1765.58
  4996.8 1765.08  5024.5 1767.06  5029.7 1769.48    5049 1772.06  5090.6 1775.49
  5184.2 1778.62  5315.7 1777.11  5402.6 1779.36  5461.2 1782.33  5500.3 1786.28
  5527.4 1795.49  5534.1 1799.65  5539.3 1798.87  5564.8 1810.25  5569.7 1811.28
#Mann= 8 ,-1 , 0
  3784.5     .05       0  3861.8      .1       0  4058.8     .16       0
    4994     .07       0  5024.5     .16       0  5402.6     .05       0
  5461.2      .1       0  5564.8     .16       0
#XS Ineff= 2 , 0
                         5195.02            1779
Permanent Ineff=
       T       T
Bank Sta=4934.6,5049
XS Rating Curve= 0 ,0
Exp/Cntr=0.3,0.1

Type RM Length L Ch R = 1 ,73963   ,402,402,402
BEGIN DESCRIPTION:
SOUTH GRAPE CREEK 120.0
END DESCRIPTION:
XS GIS Cut Line= 3
      2773339.51      10012119.8      2773629.32     10010792.68
      2773535.75     10010267.65
#Sta/Elev= 30
  3547.4 1799.06  3625.3 1797.07  3809.5 1792.14  3890.2 1792.52  4179.2 1786.37
    4218 1787.03  4687.8 1774.61  4878.7 1772.38  4902.7 1768.25  4945.4 1769.51
    4986  1768.3  4995.7 1765.15  4998.4 1764.65  5001.7 1765.15  5026.6 1767.87
  5111.5 1769.82  5224.4 1778.36  5260.2 1783.15  5270.4 1786.11  5278.3 1790.37
  5283.4  1790.7  5290.7 1795.21  5331.3 1813.64  5337.3 1817.67  5342.3 1818.34
  5391.2 1837.33  5396.2 1837.38  5402.4 1841.06  5432.9 1851.17  5439.1 1854.35
#Mann= 4 ,-1 , 0
  3547.4     .05       0  3625.3     .16       0  4995.7     .07       0
  5001.7     .16       0
Bank Sta=4986,5026.6
XS Rating Curve= 0 ,0
Exp/Cntr=0.3,0.1

Type RM Length L Ch R = 1 ,73561   ,776,776,776
BEGIN DESCRIPTION:
SOUTH GRAPE CREEK 119.0
END DESCRIPTION:
XS GIS Cut Line= 3
      2773655.35      10011839.6      2773967.86     10010693.72
      2773978.26     10010288.08
#Sta/Elev= 30
  3673.4 1787.45    3863 1784.61  3878.5 1784.54  3938.6 1783.63  4021.5  1781.8
    4063 1783.23  4135.5 1780.13  4269.7 1778.39  4394.7  1773.3    4405 1774.41
  4508.7 1771.86  4633.1 1770.07    4716 1770.72    4845 1768.05  4891.1 1768.88
  4931.1 1765.34  4961.1 1765.78  5010.9  1762.3  5031.2 1765.69  5041.2 1768.44
    5078 1791.54    5083 1791.29  5091.2 1794.37  5101.2 1795.54  5111.2 1799.31
  5151.2 1820.47  5161.2 1830.15  5171.2 1834.43  5221.2 1839.58  5266.9 1839.33
#Mann= 6 ,-1 , 0
  3673.4     .05       0    3863      .1       0  3878.5     .05       0
  3938.6     .16       0  4961.1     .07       0  5031.2     .16       0
Bank Sta=4961.1,5031.2
XS Rating Curve= 0 ,0
Exp/Cntr=0.3,0.1

Type RM Length L Ch R = 1 ,72785   ,413,413,413
XS GIS Cut Line= 5
      2773686.07     10012056.68      2774513.89     10010948.03
      2774511.45     10010852.79      2774411.33     10010669.64
      2774103.64     10010344.86
#Sta/Elev= 30
  3774.6 1787.57  3785.7 1787.39  3956.7 1783.49  4165.2 1781.81  4171.4  1780.5
  4464.7 1775.73    4507 1773.59  4536.2 1774.53  4627.9 1771.96    4728 1771.68
  4764.2 1769.97  4786.4 1765.93    4828 1761.98  4971.9 1760.35  4992.5 1753.38
  5036.5 1757.26  5042.8 1760.68  5051.1 1761.19  5057.4 1766.47  5086.6 1768.46
  5162.9 1767.69  5416.9 1770.51  5532.1  1774.1  5588.7 1779.42  5652.2 1788.36
  5673.7 1793.14    5702 1802.35  5793.8  1821.4  5822.1 1828.88  5909.6 1835.26
#Mann= 5 ,-1 , 0
  3774.6     .05       0  3785.7     .16       0  4971.9     .07       0
  5057.4     .16       0  5909.6      .1       0
Bank Sta=4971.9,5042.8
XS Rating Curve= 0 ,0
Exp/Cntr=0.3,0.1

Type RM Length L Ch R = 1 ,72372   ,227,227,227
BEGIN DESCRIPTION:
SOUTH GRAPE CREEK 117.0
END DESCRIPTION:
XS GIS Cut Line= 5
      2773819.27       10012169.      2774475.31     10011755.94
      2774627.16     10011315.56      2774587.68     10010653.48
      2774187.19     10009947.73
#Sta/Elev= 30
  3899.7 1785.17  3981.5 1784.64  4048.4 1780.05  4148.5 1777.36  4206.2 1777.62
  4236.8  1775.3  4519.4 1769.19  4598.3 1769.95  4673.9 1766.54    4915 1766.31
  4962.9 1763.96  4972.1 1762.23  4977.4 1757.59    4984 1753.08  4999.8 1750.82
  5039.8 1755.79  5058.1 1756.42  5121.6 1757.86  5139.1 1761.45  5162.6 1762.46
  5292.9 1761.68  5312.9 1764.27  5870.2 1771.48  6148.7 1780.59  6360.5 1796.66
  6419.7 1798.17  6462.9 1803.73  6581.2 1814.53  6602.8  1820.7  6615.5 1822.67
#Mann= 3 ,-1 , 0
  3899.7     .16       0  4972.1     .07       0  5058.1     .16       0
Bank Sta=4977.4,5058.1
XS Rating Curve= 0 ,0
Exp/Cntr=0.3,0.1

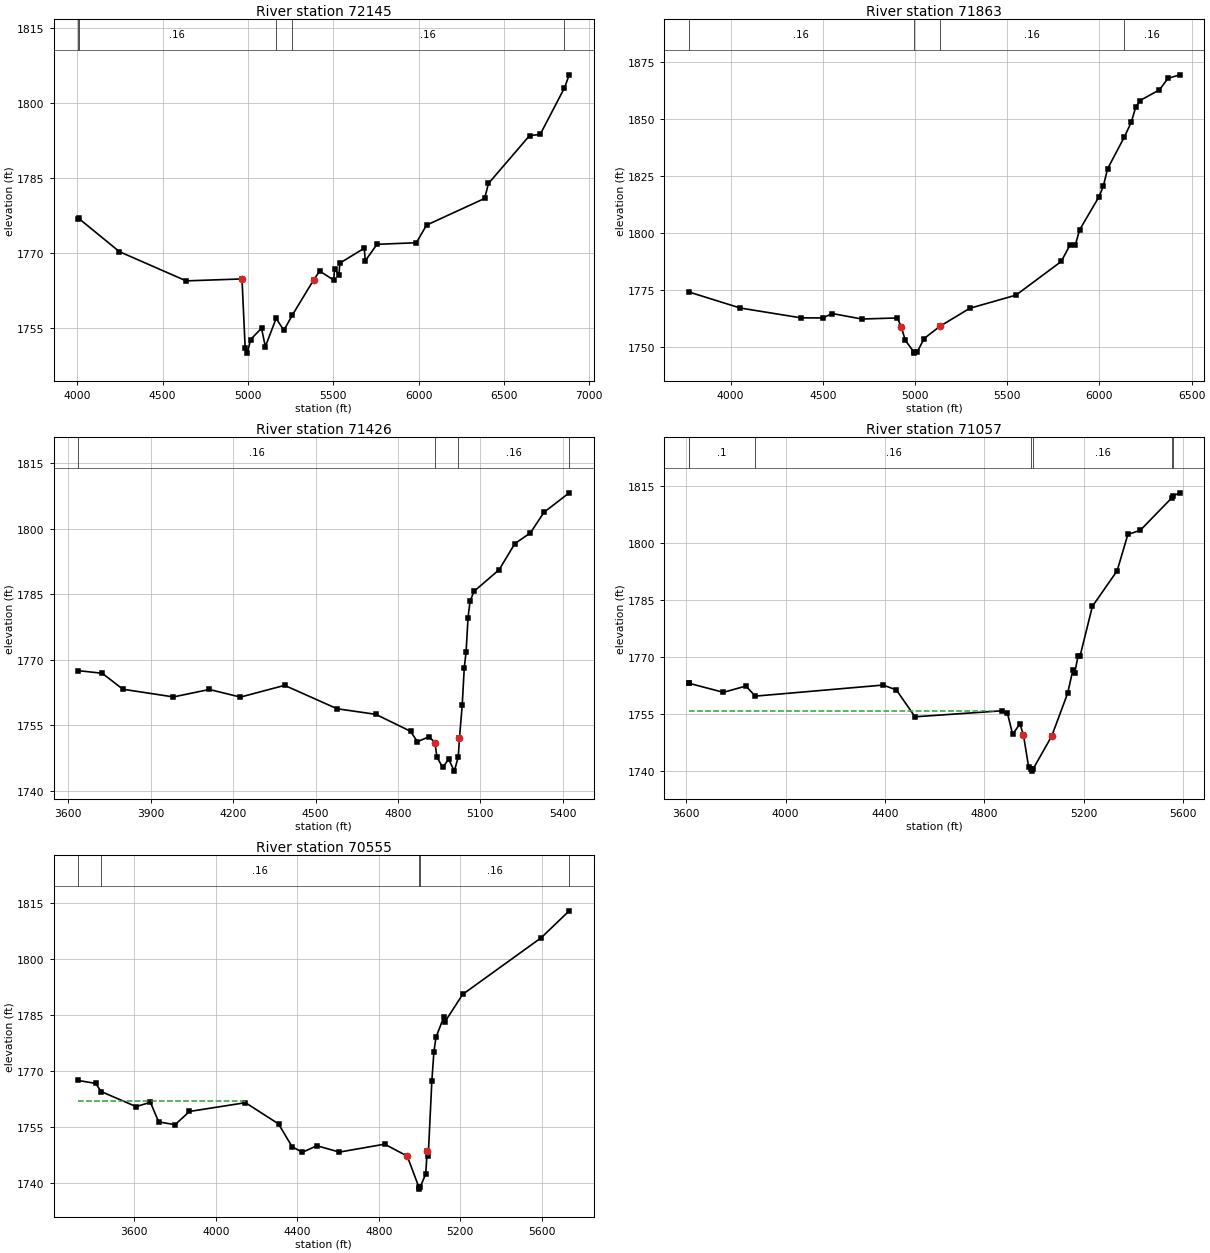
Type RM Length L Ch R = 1 ,72145   ,282,282,282
XS GIS Cut Line= 6
      2774049.91     10012159.27      2774697.04     10011746.57
       2774816.7     10011380.27      2774994.97     10010882.09
      2775024.28     10010132.39       2775214.1     10009730.83
#Sta/Elev= 30
  4005.4 1776.84    4008 1776.91  4247.5 1770.23  4638.5 1764.39  4965.3 1764.78
  4983.9    1751  4996.6 1749.94  5015.8 1752.66  5079.6 1754.93    5102 1751.23
  5165.2 1756.88  5210.5  1754.5  5259.7 1757.52  5384.5 1764.56  5420.6 1766.34
  5502.3 1764.56  5507.6 1766.75  5533.1 1765.63  5538.4 1767.94  5681.6 1770.93
  5687.4  1768.4  5755.8  1771.7  5986.2 1772.02  6046.3 1775.54  6386.4 1780.88
  6408.8 1783.87  6649.2 1793.43  6711.9 1793.69    6854 1802.99  6881.9  1805.6
#Mann= 5 ,-1 , 0
  4005.4     .05       0    4008     .16       0  5165.2     .07       0
  5259.7     .16       0    6854     .05       0
Bank Sta=4965.3,5384.5
XS Rating Curve= 0 ,0
Exp/Cntr=0.3,0.1

Type RM Length L Ch R = 1 ,71863   ,437,437,437
XS GIS Cut Line= 4
      2774092.61     10012196.34      2774870.13     10011762.02
      2775377.33      10010884.3      2776074.64     10010584.15
#Sta/Elev= 30
    3773 1774.33    4052 1767.29  4382.2 1762.98    4501 1762.94  4550.1 1764.88
  4711.9 1762.47  4904.2 1762.94  4925.8 1758.91  4947.3 1753.13  4993.6 1748.03
  4996.3 1747.53    5012 1748.06  5049.3 1753.93  5135.4  1759.3  5296.8 1767.17
  5547.4 1772.93  5792.7 1787.67  5839.8 1794.78  5868.8 1794.72  5892.3  1801.5
  5997.3 1815.99  6020.9 1820.57  6044.4 1828.31  6135.8 1842.31    6173 1848.75
  6196.5 1855.18    6220 1858.18    6325 1862.83  6372.1 1867.92  6436.5 1869.44
#Mann= 4 ,-1 , 0
    3773     .16       0  4993.6     .07       0  5135.4     .16       0
  6135.8     .16       0
Bank Sta=4925.8,5135.4
XS Rating Curve= 0 ,0
Exp/Cntr=0.3,0.1

Type RM Length L Ch R = 1 ,71426   ,369,369,369
BEGIN DESCRIPTION:
SOUTH GRAPE CREEK 115.0
END DESCRIPTION:
XS GIS Cut Line= 3
      2774311.64      10012188.5       2775368.9     10011599.97
       2775753.4     10011168.72
#Sta/Elev= 30
  3635.7 1767.49  3723.6 1766.88  3798.9 1763.22  3982.9 1761.46  4113.3 1763.17
  4226.5 1761.42  4387.4 1764.11  4578.6 1758.75  4719.3 1757.47  4845.7 1753.59
  4870.9  1751.2  4913.5 1752.34  4934.5 1750.99    4942 1747.65  4962.9  1745.3
  4984.6 1747.17  5005.3 1744.45  5019.7 1747.77 5023.86    1752  5033.9 1759.52
  5041.4 1768.14  5048.1 1771.85  5055.1 1779.63  5062.4 1783.37  5076.6 1785.65
  5168.5 1790.63  5225.4  1796.6  5282.2 1799.06  5331.6 1803.79  5423.5 1808.25
#Mann= 4 ,-1 , 0
  3635.7     .16       0  4934.5     .07       0  5019.7     .16       0
  5423.5      .1       0
Bank Sta=4934.5,5023.86
XS Rating Curve= 0 ,0
Exp/Cntr=0.3,0.1

Type RM Length L Ch R = 1 ,71057   ,502,502,502
BEGIN DESCRIPTION:
SOUTH GRAPE CREEK 114.0
END DESCRIPTION:
XS GIS Cut Line= 3
       2774478.4     10012230.88      2775672.85     10011772.55
       2776221.5     10011341.96
#Sta/Elev= 30
  3610.1 1763.17  3610.5 1763.17  3749.4 1760.78  3839.9 1762.43  3877.9 1759.78
  4392.1 1762.69  4445.6 1761.42  4520.6 1754.34  4870.5 1755.92  4892.9 1755.24
  4913.8 1749.69  4942.7 1752.51  4957.1 1749.56  4977.9  1741.2  4989.4 1740.54
  4992.1 1740.04  4995.4 1740.54    5071 1749.27  5135.2 1760.56    5156 1766.68
  5163.6 1765.96  5176.8 1770.29  5184.9 1770.31  5234.6  1783.4  5334.1 1792.76
  5377.4 1802.33  5427.2 1803.42  5555.5 1812.05  5557.7 1812.43  5586.9 1813.29
#Mann= 7 ,-1 , 0
  3610.1     .05       0  3610.5      .1       0  3877.9     .16       0
  4989.4     .07       0  4995.4     .16       0  5555.5      .1       0
  5557.7     .16       0
#XS Ineff= 2 , 0
         4850.62 1755.97
Permanent Ineff=
       T       T
Bank Sta=4957.1,5071
XS Rating Curve= 0 ,0
Exp/Cntr=0.3,0.1

Type RM Length L Ch R = 1 ,70555   ,1080,1080,1080
BEGIN DESCRIPTION:
SOUTH GRAPE CREEK 113.0
END DESCRIPTION:
XS GIS Cut Line= 3
      2774306.36     10012329.15      2776202.23     10012094.77
      2776639.72     10011855.19
#Sta/Elev= 30
  3324.9  1767.4  3411.2 1766.59  3437.9 1764.41  3609.2 1760.39  3679.7 1761.53
    3720 1756.28  3800.6 1755.53  3871.1 1759.08  4145.8 1761.43  4307.9 1755.75
  4374.9 1749.61  4425.3 1748.13  4495.9 1749.89  4606.7 1748.19  4828.4 1750.31
  4939.2 1747.12  4996.7 1738.76  4999.4 1738.26  5002.7 1738.76  5029.9 1742.33
  5037.4 1748.46  5042.4 1747.13  5060.1 1767.23  5070.2 1775.04  5080.3 1778.92
  5118.5 1784.39  5123.5 1783.04  5211.3 1790.47  5595.8 1805.61    5734 1812.86
#Mann= 5 ,-1 , 0
  3324.9     .05       0  3437.9     .16       0  4996.7     .07       0
  5002.7     .16       0    5734     .16       0
#XS Ineff= 2 , 0
         4142.74 1761.79
Permanent Ineff=
       T       T
Bank Sta=4939.2,5037.4
XS Rating Curve= 0 ,0
Exp/Cntr=0.3,0.1