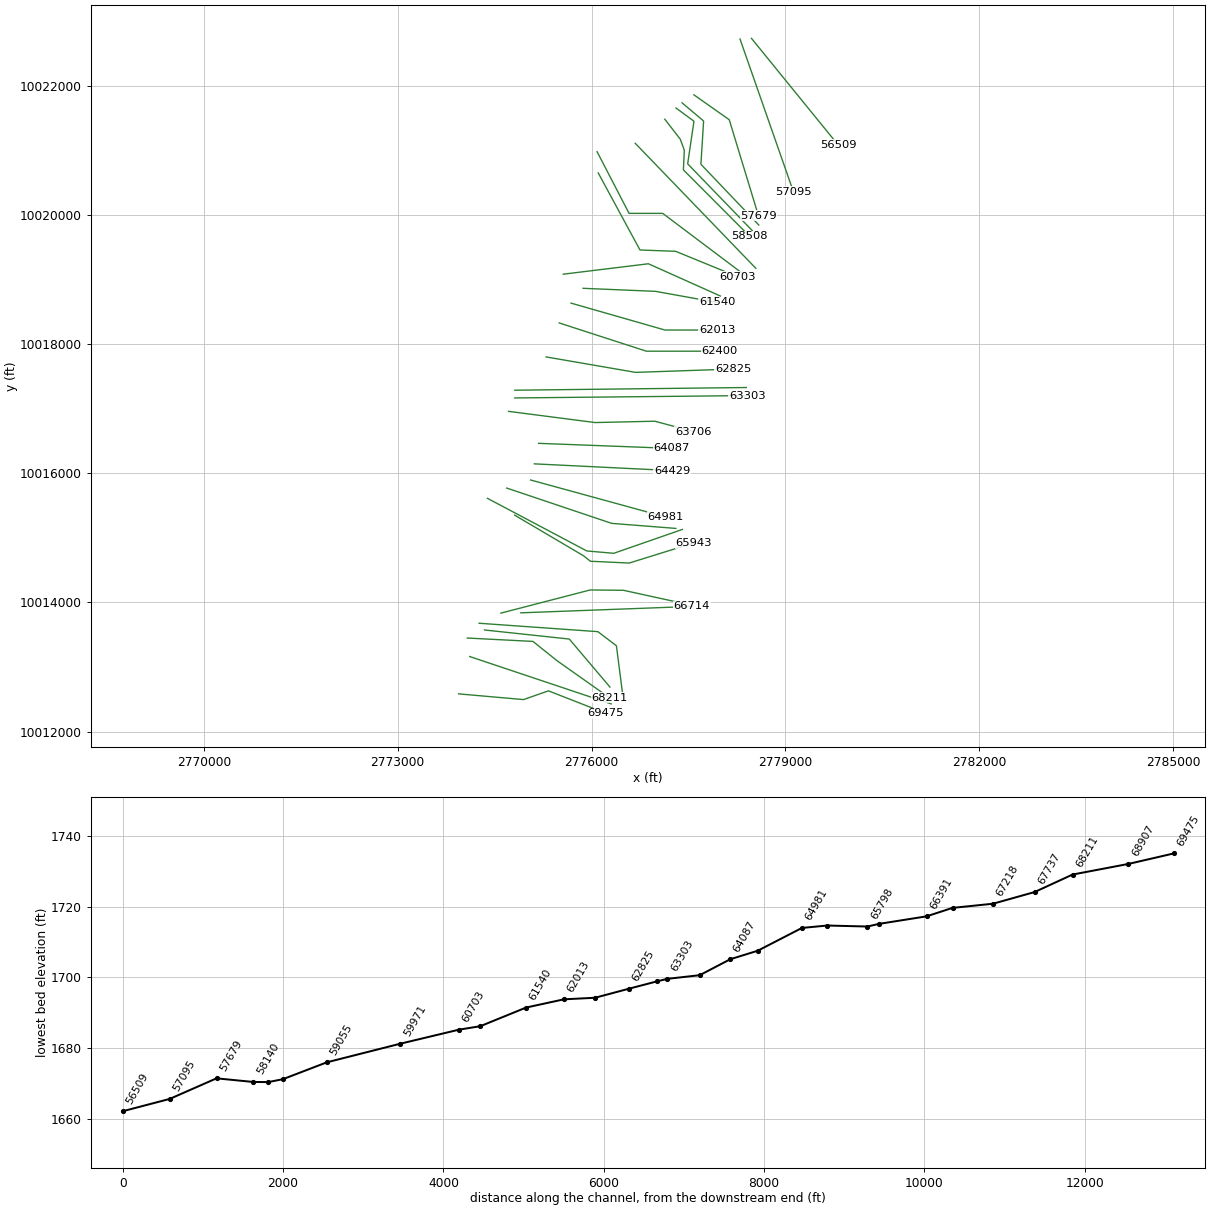
HEC-RAS study SOUTH GRAPE CREEK.prj: SOUTH GRAPE CREEK Base Level Engineering

--- SOUTH GRAPE CREEK.g01 (geometry) --- (continued)

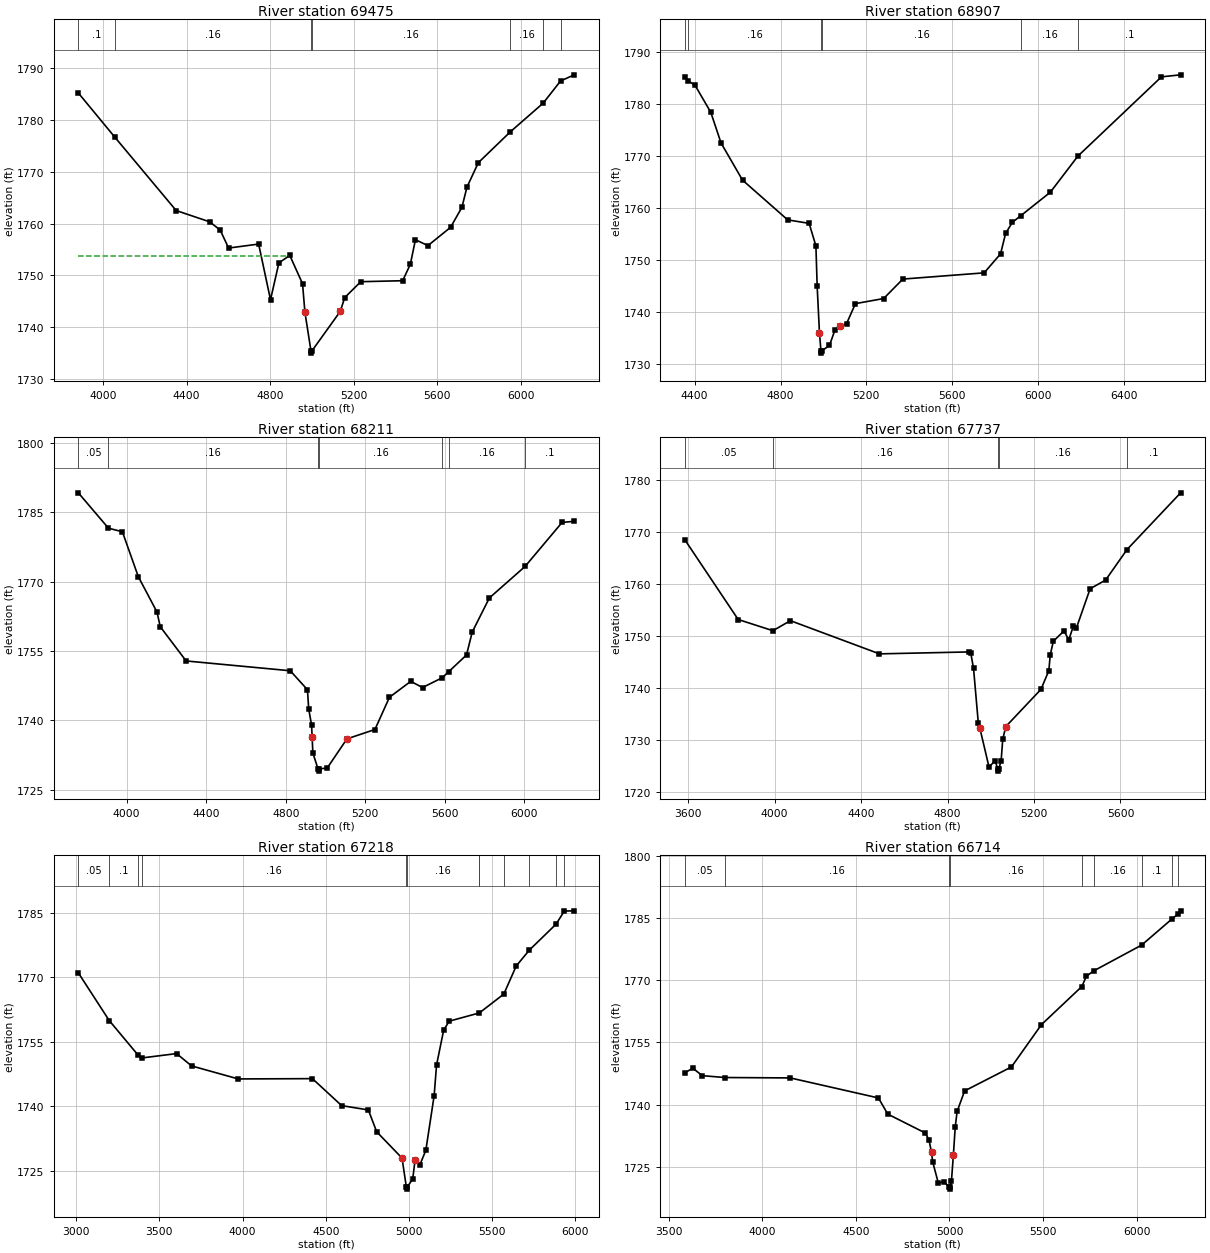
Type RM Length L Ch R = 1 ,69475   ,568,568,568
BEGIN DESCRIPTION:
Mapping XS 1c7c6d63
END DESCRIPTION:
XS GIS Cut Line= 4
      2773941.78     10012584.35      2774947.02     10012495.81
      2775332.44     10012631.22      2776223.06     10012282.27
#Sta/Elev= 30
  3881.7  1785.2  4056.9 1776.65  4350.2 1762.52  4510.7 1760.34    4561 1758.75
  4601.2 1755.28  4745.1 1756.05  4801.9 1745.31  4842.1 1752.42  4894.3 1753.86
  4955.3  1748.4  4966.6 1742.92  4995.4 1735.51  4998.1 1735.01  5001.4 1735.51
  5135.9 1743.06  5157.3 1745.73  5234.2 1748.79  5434.7 1748.98  5471.5 1752.16
  5495.9 1756.89  5555.6 1755.75  5664.1 1759.28  5718.3 1763.13  5742.8 1767.05
    5797 1771.75  5950.2  1777.7  6107.8 1783.25  6190.6  1787.5  6255.9  1788.7
#Mann= 7 ,-1 , 0
  3881.7      .1       0  4056.9     .16       0  4995.4     .07       0
  5001.4     .16       0  5950.2     .16       0  6107.8      .1       0
  6190.6     .16       0
#XS Ineff= 2 , 0
         4889.21 1753.84
Permanent Ineff=
       T       T
Bank Sta=4966.6,5135.9
XS Rating Curve= 0 ,0
Exp/Cntr=0.3,0.1

Type RM Length L Ch R = 1 ,68907   ,696,696,696
BEGIN DESCRIPTION:
SOUTH GRAPE CREEK 112.0
END DESCRIPTION:
XS GIS Cut Line= 2
      2774113.66     10013162.49      2776303.98     10012428.91
#Sta/Elev= 30
  4354.1 1785.16  4370.5 1784.49    4402 1783.64  4475.2 1778.43    4523 1772.52
    4623 1765.37  4833.4 1757.71  4933.3 1757.04  4964.9 1752.69  4970.8 1744.88
  4981.4 1735.99  4988.2 1732.53  4990.9 1732.03  4994.2 1732.53    5028  1733.5
  5054.3 1736.57  5076.3 1737.25  5107.9 1737.73    5149 1741.57  5280.5 1742.55
  5369.9  1746.3  5748.7  1747.5  5825.1 1751.16  5848.6 1755.09  5880.2 1757.24
    5920 1758.53  6057.1 1763.04  6185.5    1770  6574.6 1785.27    6664 1785.66
#Mann= 6 ,-1 , 0
  4354.1      .1       0  4370.5     .16       0  4988.2     .07       0
  4994.2     .16       0    5920     .16       0  6185.5      .1       0
Bank Sta=4981.4,5076.3
XS Rating Curve= 0 ,0
Exp/Cntr=0.3,0.1

Type RM Length L Ch R = 1 ,68211   ,474,474,474
BEGIN DESCRIPTION:
SOUTH GRAPE CREEK 111.0
END DESCRIPTION:
XS GIS Cut Line= 4
      2774077.27     10013448.93      2775092.86     10013396.85
      2775462.65     10013099.97      2776280.38     10012521.84
#Sta/Elev= 30
  3757.3  1789.2  3908.7 1781.56  3978.8 1780.78  4058.9 1771.06  4152.9 1763.42
    4169 1760.26  4299.2 1752.85  4822.7 1750.73  4909.1 1746.63  4915.5 1742.44
  4929.9 1738.97  4932.6 1736.44  4936.3 1732.97  4962.1 1729.53  4964.9 1729.03
  4968.1 1729.53  5008.3 1729.69  5107.5    1736  5248.4 1738.03  5321.4    1745
  5428.5 1748.44  5487.6  1747.1  5586.2 1749.21  5619.7 1750.55  5708.7 1754.14
  5737.5  1759.1  5823.6 1766.47  6003.1 1773.28  6189.2  1782.8  6249.9 1783.04
#Mann= 7 ,-1 , 0
  3757.3     .05       0  3908.7     .16       0  4962.1     .07       0
  4968.1     .16       0  5586.2      .1       0  5619.7     .16       0
  6003.1      .1       0
Bank Sta=4932.6,5107.5
XS Rating Curve= 0 ,0
Exp/Cntr=0.3,0.1

Type RM Length L Ch R = 1 ,67737   ,519,519,519
BEGIN DESCRIPTION:
SOUTH GRAPE CREEK 110.0
END DESCRIPTION:
XS GIS Cut Line= 3
      2774342.86     10013573.93      2775655.36     10013433.31
      2776284.44     10012689.85
#Sta/Elev= 30
  3584.3 1768.54  3831.3 1753.21  3992.2 1751.06  4072.7 1752.99    4485 1746.61
  4897.4 1746.98  4907.3 1746.75  4920.1 1743.84  4942.2 1733.31  4948.7 1732.46
  4991.6 1724.88  5020.2 1726.07  5031.5 1724.58  5034.2 1724.08  5037.5 1724.58
  5047.8 1726.09  5055.3 1730.23  5069.6 1732.65  5232.1 1739.79  5268.5 1743.39
    5275  1746.4  5289.3 1749.03  5338.7 1751.03  5360.8  1749.3  5381.6 1751.91
  5395.9 1751.57  5459.6 1759.13    5531 1760.78  5630.2 1766.65  5878.2 1777.55
#Mann= 5 ,-1 , 0
  3584.3     .05       0  3992.2     .16       0  5031.5     .07       0
  5037.5     .16       0  5630.2      .1       0
Bank Sta=4948.7,5069.6
XS Rating Curve= 0 ,0
Exp/Cntr=0.3,0.1

Type RM Length L Ch R = 1 ,67218   ,504,504,504
BEGIN DESCRIPTION:
SOUTH GRAPE CREEK 109.0
END DESCRIPTION:
XS GIS Cut Line= 4
      2774259.48      10013678.1      2776098.07     10013547.89
      2776384.52     10013329.14      2776483.45     10012558.59
#Sta/Elev= 30
  3012.8 1771.03  3198.7 1759.94  3369.8 1752.02  3392.7 1751.25  3603.3 1752.27
  3693.5 1749.41  3974.2 1746.38  4419.9 1746.45  4595.7 1740.18  4756.1 1739.18
  4806.3  1734.1  4958.5    1728  4984.5 1721.28  4987.3 1720.78  4990.5 1721.28
  5022.9 1723.17  5037.4 1727.66  5066.5 1726.48  5101.8 1729.81  5151.7 1742.52
  5166.2 1749.63  5208.8  1757.7    5242  1759.8  5423.5 1761.72  5570.5  1766.1
  5645.3 1772.64  5724.6 1776.34  5884.7 1782.35  5934.2 1785.39  5993.3 1785.44
#Mann= 12 ,-1 , 0
  3012.8     .05       0  3198.7      .1       0  3369.8     .05       0
  3392.7     .16       0  4984.5     .07       0  4990.5     .16       0
  5423.5     .16       0  5423.5      .1       0  5570.5     .16       0
  5724.6      .1       0  5884.7     .16       0  5934.2      .1       0
Bank Sta=4958.5,5037.4
XS Rating Curve= 0 ,0
Exp/Cntr=0.3,0.1

Type RM Length L Ch R = 1 ,66714   ,323,323,323
BEGIN DESCRIPTION:
SOUTH GRAPE CREEK 108.0
END DESCRIPTION:
XS GIS Cut Line= 2
      2774905.33     10013839.56      2777551.18     10013938.52
#Sta/Elev= 30
  3586.8 1747.68    3630 1748.78    3680 1746.99  3800.1 1746.54  4150.3 1746.44
  4620.7 1741.61  4670.7 1737.71  4870.8 1733.16  4890.9 1731.48  4904.2 1728.45
  4910.9 1726.12  4940.9 1721.03  4970.9 1721.44  4997.9 1720.11  5000.7 1719.61
  5003.9 1720.11  5010.9 1721.69  5020.9 1727.76  5030.9 1734.61    5041 1738.36
    5081 1743.31  5331.2  1749.1  5491.3  1759.3    5707  1768.5  5731.4 1770.98
  5769.9 1772.26  6026.5  1778.5  6186.8 1784.74  6219.5 1785.95  6234.5 1786.76
#Mann= 9 ,-1 , 0
  3586.8     .05       0  3800.1     .16       0  4997.9     .07       0
  5003.9     .16       0    5707      .1       0  5769.9     .16       0
  6026.5      .1       0  6186.8     .05       0  6219.5      .1       0
Bank Sta=4904.2,5020.9
XS Rating Curve= 0 ,0
Exp/Cntr=0.3,0.1

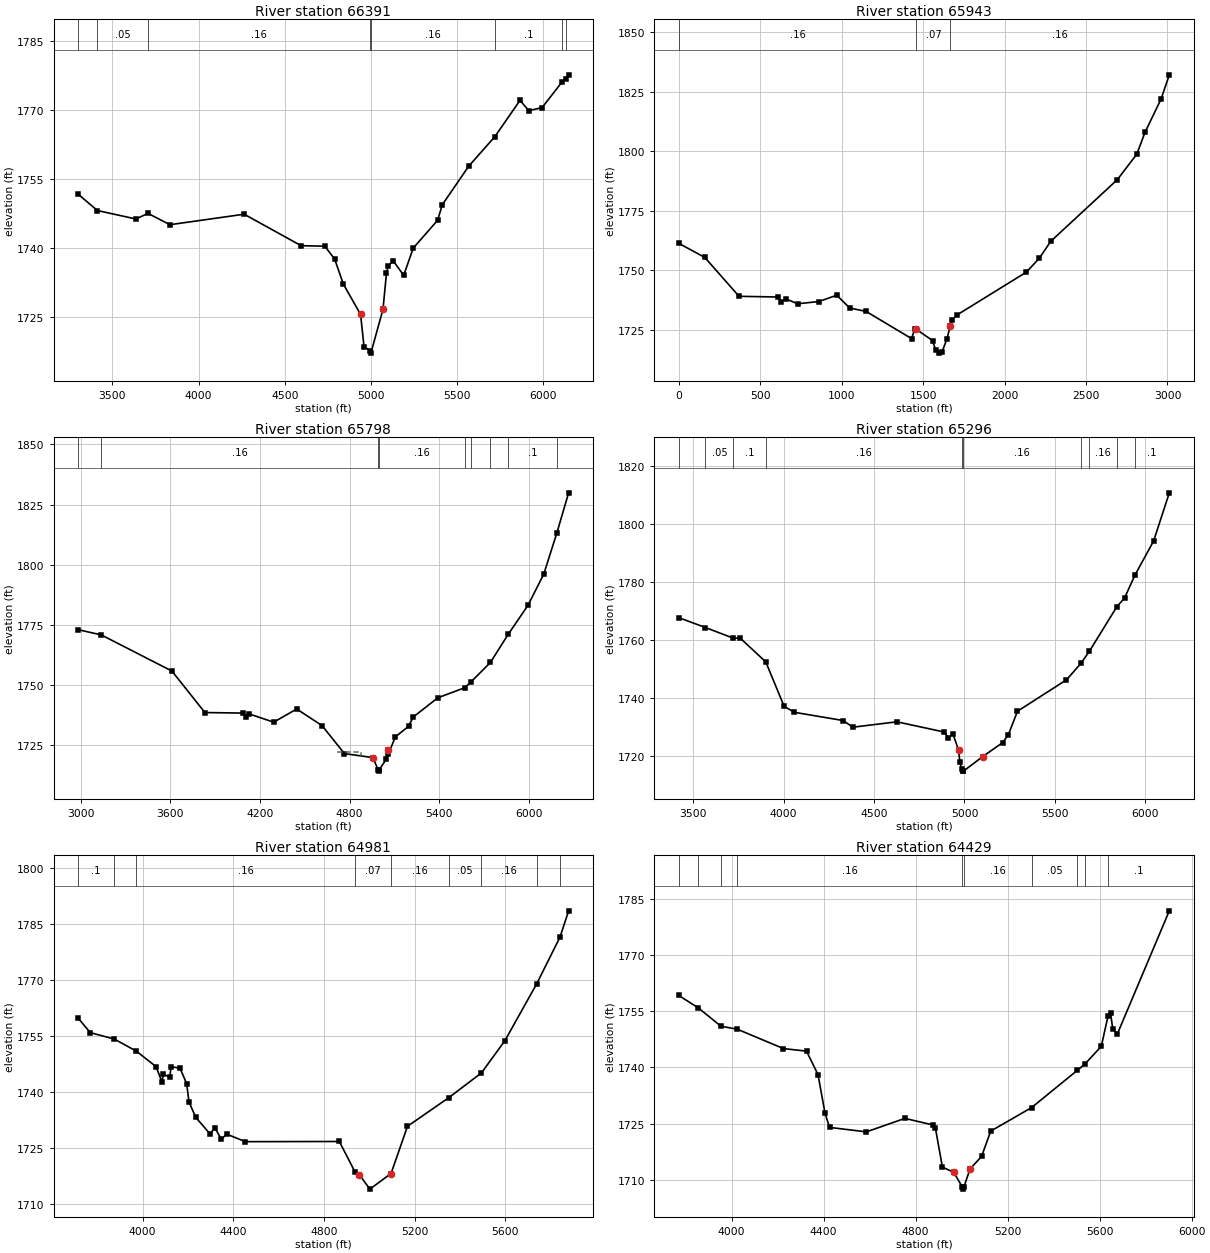
Type RM Length L Ch R = 1 ,66391   ,593,593,593
BEGIN DESCRIPTION:
SOUTH GRAPE CREEK 107.0
END DESCRIPTION:
XS GIS Cut Line= 4
      2774596.48     10013835.05      2775978.27     10014193.72
       2776493.9     10014188.52      2777373.82     10013995.87
#Sta/Elev= 30
  3301.7 1751.77  3413.9 1748.21  3637.1 1746.37  3706.7 1747.59  3834.8 1745.13
  4264.6 1747.41  4595.2 1740.56  4731.9 1740.47  4789.5 1737.64  4839.5 1732.23
  4939.5 1725.63  4959.5 1718.62  4996.5 1717.72  4999.2 1717.22  5069.5 1726.74
  5089.5 1734.56  5099.5 1736.23  5129.5 1737.25  5189.5 1734.11  5244.7 1740.04
    5386 1746.08  5413.4 1749.47  5566.5 1757.85  5718.3 1764.28  5863.8 1772.15
    5915 1769.91  5991.9 1770.59  6109.6 1776.24  6130.9 1776.83  6145.7  1777.7
#Mann= 8 ,-1 , 0
  3301.7      .1       0  3413.9     .05       0  3706.7     .16       0
  4996.5     .07       0  4999.2     .16       0  5718.3      .1       0
  6109.6     .16       0  6130.9      .1       0
Bank Sta=4939.5,5069.5
XS Rating Curve= 0 ,0
Exp/Cntr=0.3,0.1

Type RM Length L Ch R = 1 ,65943   ,145,145,145
BEGIN DESCRIPTION:
SOUTH GRAPE CREEK 10777.0
END DESCRIPTION:
XS GIS Cut Line= 5
     2774809.635     10015352.08     2775877.343    10014721.872
      2775981.51    10014638.539     2776582.442    10014610.392
      2777575.26    10014919.789
#Sta/Elev= 30
       01761.248159.98761755.318369.97141738.976609.95291738.685629.95141736.751
 659.9491737.796729.94371735.841859.93361736.781969.92511739.4311049.9191734.042
1149.9111732.6331428.7631721.2161448.5981725.0631458.516 1725.081557.6921720.384
1577.527 1716.261597.3621715.0931617.1981715.772 1646.951721.1911666.7861726.524
1676.7031728.9691706.4561731.0752133.8151749.141 2213.58    17552283.3741762.082
2692.1711788.0112811.8181798.7412861.6711807.8422961.378 1822.023011.2311832.077
#Mann= 3 ,-1 , 0
       0     .16       01458.516     .07       01666.786     .16       0
Bank Sta=1458.516,1666.786
XS Rating Curve= 0 ,0
Exp/Cntr=0.3,0.1

Type RM Length L Ch R = 1 ,65798   ,502,502,502
BEGIN DESCRIPTION:
SOUTH GRAPE CREEK 106.0
END DESCRIPTION:
XS GIS Cut Line= 4
      2774388.14     10015612.82      2775926.19     10014797.89
      2776342.86     10014761.43      2777405.38     10015131.23
#Sta/Elev= 30
    2982  1773.1  3137.7  1770.9  3610.3  1755.9  3831.1 1738.67  4082.9 1738.45
  4104.9 1736.64  4126.9 1738.11  4291.6 1734.67  4445.5 1740.14  4615.8 1733.22
    4765 1721.62  4955.8 1719.96    4991 1714.84  4993.8 1714.34    4997 1714.84
  5046.1 1719.38  5054.1 1722.95  5059.2 1721.47  5106.3 1728.59    5194 1732.92
  5225.1 1736.78  5390.3  1744.8  5570.3 1748.97    5611  1751.3  5742.4 1759.48
  5861.5 1771.17  5993.9  1783.2  6099.8 1796.22  6187.4 1813.33  6265.9 1829.92
#Mann= 9 ,-1 , 0
    2982      .1       0  3137.7     .16       0    4991     .07       0
    4997     .16       0  5570.3     .05       0    5611      .1       0
  5742.4     .16       0  5861.5      .1       0  6187.4     .05       0
#XS Ineff= 1 ,-1
 4712.89 4875.56 1722.09
Permanent Ineff=
       T
Bank Sta=4955.8,5054.1
XS Rating Curve= 0 ,0
Exp/Cntr=0.3,0.1

Type RM Length L Ch R = 1 ,65296   ,315,315,315
BEGIN DESCRIPTION:
SOUTH GRAPE CREEK 105.0
END DESCRIPTION:
XS GIS Cut Line= 3
      2774686.63     10015771.84      2776311.61     10015224.97
      2777304.91     10015146.97
#Sta/Elev= 30
  3420.9 1767.69  3568.7 1764.25  3722.1 1760.59  3760.5  1760.6  3901.9 1752.38
  4003.2 1737.03  4059.4 1734.96  4330.2  1732.1    4383  1729.8  4626.5 1731.67
  4889.4 1728.12  4910.5 1726.05  4936.2 1727.47  4967.7 1721.81  4973.9 1717.94
  4984.4 1715.27  4993.7 1714.62  4994.2 1714.62  5100.5 1719.64  5211.3  1724.5
  5242.6 1727.23  5292.8 1735.33  5563.6 1746.18  5643.9  1751.9  5690.7 1756.12
    5842 1771.46  5884.6 1774.48  5941.3 1782.31  6045.1 1794.18  6131.8 1810.83
#Mann= 10 ,-1 , 0
  3420.9      .1       0  3568.7     .05       0  3722.1      .1       0
  3901.9     .16       0  4984.4     .07       0  4994.2     .16       0
  5643.9      .1       0  5690.7     .16       0    5842     .05       0
  5941.3      .1       0
Bank Sta=4967.7,5100.5
XS Rating Curve= 0 ,0
Exp/Cntr=0.3,0.1

Type RM Length L Ch R = 1 ,64981   ,552,552,552
BEGIN DESCRIPTION:
SOUTH GRAPE CREEK 104.0
END DESCRIPTION:
XS GIS Cut Line= 2
      2775056.42     10015896.84       2777144.2     10015324.14
#Sta/Elev= 30
  3714.9 1759.72  3768.9 1755.82  3874.8  1754.1  3971.7 1750.88  4059.2 1746.71
  4085.5 1742.58  4090.6 1744.65  4119.9 1743.93  4125.1 1746.68  4164.7 1746.34
    4194 1742.17  4204.4  1737.3  4233.6  1733.2  4297.7 1728.69  4318.4 1730.39
  4347.4 1727.26  4370.3 1728.67  4453.2 1726.64    4868 1726.69  4937.7 1718.45
  4955.7 1717.85  5002.6 1713.94  5096.1 1718.12  5168.7 1730.76  5351.8 1738.45
  5495.2 1745.06  5598.4 1753.65  5738.3 1768.82  5841.8  1781.4  5879.8 1788.42
#Mann= 9 ,-1 , 0
  3714.9      .1       0  3874.8     .05       0  3971.7     .16       0
  4937.7     .07       0  5096.1     .16       0  5351.8     .05       0
  5495.2     .16       0  5738.3     .05       0  5841.8      .1       0
Bank Sta=4955.7,5096.1
XS Rating Curve= 0 ,0
Exp/Cntr=0.3,0.1

Type RM Length L Ch R = 1 ,64429   ,342,342,342
BEGIN DESCRIPTION:
SOUTH GRAPE CREEK 103.0
END DESCRIPTION:
XS GIS Cut Line= 2
      2775113.74     10016146.85      2777243.69     10016042.69
#Sta/Elev= 30
  3770.3 1759.24  3854.8 1755.94  3953.8 1751.02  4025.3 1750.21  4225.6 1745.04
  4325.7 1744.36  4375.8 1738.08  4405.8 1727.87  4425.8 1723.98    4586 1722.79
  4753.3 1726.39  4876.3 1724.62  4886.4  1723.7  4916.4 1713.38  4966.5 1711.95
  5003.5 1707.99  5006.3 1707.49  5009.5 1707.99  5036.5 1712.87  5086.6 1716.22
  5126.6    1723    5304 1729.27  5503.6 1739.26  5534.4 1740.82  5607.2 1745.64
  5636.4 1753.74  5647.3 1754.51  5657.3 1750.23  5677.3    1749  5902.8 1781.85
#Mann= 10 ,-1 , 0
  3770.3     .16       0  3854.8     .05       0  3953.8     .16       0
  4025.3     .16       0  5003.5     .07       0  5009.5     .16       0
    5304     .05       0  5503.6      .1       0  5534.4     .05       0
  5636.4      .1       0
Bank Sta=4966.5,5036.5
XS Rating Curve= 0 ,0
Exp/Cntr=0.3,0.1

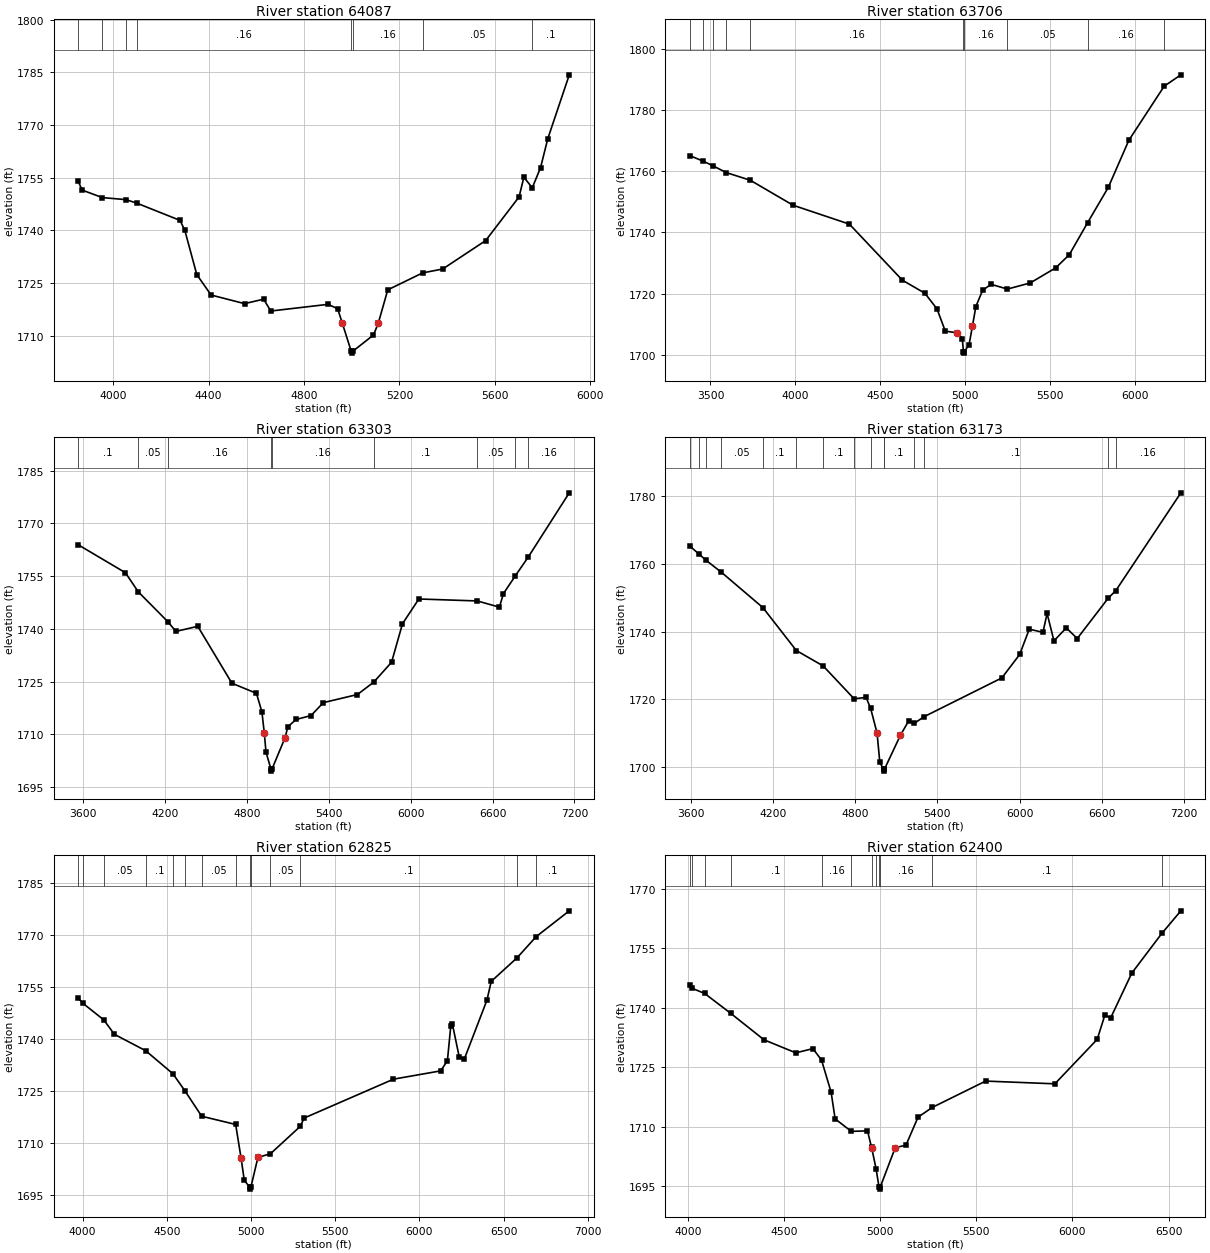
Type RM Length L Ch R = 1 ,64087   ,381,381,381
BEGIN DESCRIPTION:
SOUTH GRAPE CREEK 102.0
END DESCRIPTION:
XS GIS Cut Line= 2
      2775181.35     10016464.56      2777238.67     10016386.43
#Sta/Elev= 30
    3853 1754.02  3870.1 1751.47  3954.7 1749.34  4053.6 1748.76  4100.3 1747.73
  4280.4 1742.85  4300.4    1740  4350.5 1727.43  4410.5 1721.62  4550.6 1719.17
  4630.7 1720.44  4660.7 1717.07  4900.9 1718.97  4940.9 1717.72  4960.9 1713.52
  4997.9 1705.59  5000.7 1705.09  5003.9 1705.59    5091 1710.24    5111 1713.55
    5151 1723.09  5297.2 1727.92  5381.2 1729.02  5561.3 1737.11  5701.4 1749.54
  5721.5 1755.15  5756.7 1752.12  5791.5 1757.88  5821.5 1766.04  5911.8 1784.27
#Mann= 8 ,-1 , 0
    3853     .16       0  3954.7     .05       0  4053.6      .1       0
  4100.3     .16       0  4997.9     .07       0  5003.9     .16       0
  5297.2     .05       0  5756.7      .1       0
Bank Sta=4960.9,5111
XS Rating Curve= 0 ,0
Exp/Cntr=0.3,0.1

Type RM Length L Ch R = 1 ,63706   ,403,403,403
BEGIN DESCRIPTION:
SOUTH GRAPE CREEK 101.0
END DESCRIPTION:
XS GIS Cut Line= 4
      2774714.47     10016960.05      2776054.79     10016786.44
       2776978.4     10016807.27      2777574.59     10016647.83
#Sta/Elev= 30
  3377.6 1765.09  3454.1 1763.31  3512.9  1761.8  3592.5 1759.53  3734.6 1757.02
  3986.6 1748.86  4318.2 1742.69  4630.2 1724.39  4762.8 1720.13  4834.3 1714.99
  4882.8 1707.76  4952.9 1707.21  4982.9 1705.33  4989.9 1701.08  4992.6 1700.58
  4995.9 1701.08  5022.9 1703.37  5042.9 1709.45  5062.9  1715.8  5102.9 1721.12
  5152.9 1723.04  5248.4 1721.49    5383 1723.49    5533 1728.42    5613 1732.71
  5721.3  1743.2  5842.7 1754.69  5963.6 1770.05  6171.8 1787.72  6270.1 1791.44
#Mann= 10 ,-1 , 0
  3377.6      .1       0  3454.1     .05       0  3512.9      .1       0
  3592.5     .05       0  3734.6     .16       0  4989.9     .07       0
  4995.9     .16       0  5248.4     .05       0  5721.3     .16       0
  6171.8      .1       0
Bank Sta=4952.9,5042.9
XS Rating Curve= 0 ,0
Exp/Cntr=0.3,0.1

Type RM Length L Ch R = 1 ,63303   ,130,130,130
BEGIN DESCRIPTION:
SOUTH GRAPE CREEK 100.0
END DESCRIPTION:
XS GIS Cut Line= 2
      2774811.65     10017167.68      2778410.57     10017204.14
#Sta/Elev= 30
  3563.3 1763.92  3910.1 1755.96  4003.8 1750.54  4220.1 1742.06  4280.2 1739.27
  4440.2 1740.72  4690.2 1724.55  4870.2 1721.66  4910.2 1716.39 4927.26 1710.52
  4940.2 1704.94  4977.2 1700.05  4979.9 1699.55  4983.2 1700.05  5080.2 1709.09
  5100.2 1712.16  5160.2 1714.23  5270.2 1715.35  5360.2 1719.02  5610.2 1721.33
  5730.2 1724.87  5860.2  1730.5  5940.2 1741.45  6060.2 1748.49  6488.3 1747.93
  6650.3 1746.17  6680.3 1750.04  6764.9 1754.94  6863.5 1760.52  7162.4 1778.67
#Mann= 9 ,-1 , 0
  3563.3      .1       0  4003.8     .05       0  4220.1     .16       0
  4977.2     .07       0  4983.2     .16       0  5730.2      .1       0
  6488.3     .05       0  6764.9      .1       0  6863.5     .16       0
Bank Sta=4927.26,5080.2
XS Rating Curve= 0 ,0
Exp/Cntr=0.3,0.1

Type RM Length L Ch R = 1 ,63173   ,348,348,348
BEGIN DESCRIPTION:
Mapping XS 4b8fcc1f
END DESCRIPTION:
XS GIS Cut Line= 2
      2774811.63     10017287.48      2778394.19     10017329.13
#Sta/Elev= 30
  3593.2 1765.26  3659.5 1762.94  3709.5 1761.15  3824.9  1757.5  4127.1 1747.09
    4371 1734.43  4567.3 1729.86  4792.5 1720.18  4880.1  1720.6  4913.3 1717.33
  4960.1 1710.05  4980.1 1701.45  5007.1 1699.34  5009.9 1698.84  5013.1 1699.34
  5130.1  1709.4  5190.1 1713.63  5230.5  1712.9  5301.4 1714.87  5870.2 1726.34
  6000.2 1733.25  6070.2 1740.72  6170.2 1739.79  6200.2 1745.38  6250.2 1737.28
  6340.2  1741.1  6420.2 1737.97  6647.9 1749.96  6700.9 1752.06    7176 1780.95
#Mann= 15 ,-1 , 0
  3593.2      .1       0  3659.5     .05       0  3709.5      .1       0
  3824.9     .05       0  4127.1      .1       0    4371     .05       0
  4567.3      .1       0  4792.5     .05       0  4913.3      .1       0
  5007.1     .07       0  5013.1      .1       0  5230.5     .05       0
  5301.4      .1       0  6647.9     .05       0  6700.9     .16       0
Bank Sta=4960.1,5130.1
XS Rating Curve= 0 ,0
Exp/Cntr=0.3,0.1

Type RM Length L Ch R = 1 ,62825   ,425,425,425
BEGIN DESCRIPTION:
SOUTH GRAPE CREEK 99.0
END DESCRIPTION:
XS GIS Cut Line= 3
      2775295.99      10017803.1       2776681.4     10017563.52
      2778191.83      10017615.6
#Sta/Elev= 30
  3973.2 1751.87  4001.2 1750.36  4125.4 1745.57  4188.8  1741.4    4375 1736.66
  4536.3 1730.03  4606.5 1725.19  4707.3 1717.78  4909.1 1715.41  4941.3 1705.67
  4960.1 1699.35    4993 1697.27  4995.8 1696.77    4999 1697.27  5041.3 1705.92
  5115.8 1706.97  5293.3 1714.89  5315.3 1717.25  5846.5 1728.47  6126.7 1730.86
  6166.7 1733.78  6186.7 1743.81  6196.7 1744.27  6236.7 1734.91  6266.8 1734.23
  6401.4 1751.24  6426.9 1756.66  6579.8 1763.43    6694 1769.56  6890.5    1777
#Mann= 14 ,-1 , 0
  3973.2     .05       0  4001.2      .1       0  4125.4     .05       0
    4375      .1       0  4536.3     .05       0  4606.5      .1       0
  4707.3     .05       0  4909.1      .1       0    4993     .07       0
    4999      .1       0  5115.8     .05       0  5293.3      .1       0
  6579.8     .05       0    6694      .1       0
Bank Sta=4941.3,5041.3
XS Rating Curve= 0 ,0
Exp/Cntr=0.3,0.1

Type RM Length L Ch R = 1 ,62400   ,387,387,387
BEGIN DESCRIPTION:
SOUTH GRAPE CREEK 98.0
END DESCRIPTION:
XS GIS Cut Line= 3
      2775499.14     10018329.13      2776848.07     10017891.64
      2777983.47     10017891.64
#Sta/Elev= 30
  4009.9 1745.75  4021.7 1744.92  4087.6 1743.61  4222.5 1738.61  4396.5  1731.9
  4561.7 1728.61  4650.5 1729.68  4695.3 1726.79  4745.1 1718.69  4766.1 1711.94
  4850.1 1708.78  4934.3 1708.91  4955.3 1704.76  4955.9 1704.68  4978.6 1699.39
  4994.4  1694.7  4997.1  1694.2  5000.4  1694.7  5078.6 1704.68  5134.1 1705.28
  5197.1 1712.37  5271.1 1714.83  5548.4 1721.48  5908.4 1720.79  6128.4 1732.01
  6168.4 1738.15  6198.4 1737.42  6308.4 1748.75  6464.4 1758.76  6563.4 1764.47
#Mann= 12 ,-1 , 0
  4009.9     .05       0  4021.7      .1       0  4087.6     .05       0
  4222.5      .1       0  4695.3     .16       0  4850.1     .05       0
  4955.3      .1       0  4978.6     .16       0  4994.4     .07       0
  5000.4     .16       0  5271.1      .1       0  6464.4     .05       0
Bank Sta=4955.9,5078.6
XS Rating Curve= 0 ,0
Exp/Cntr=0.3,0.1

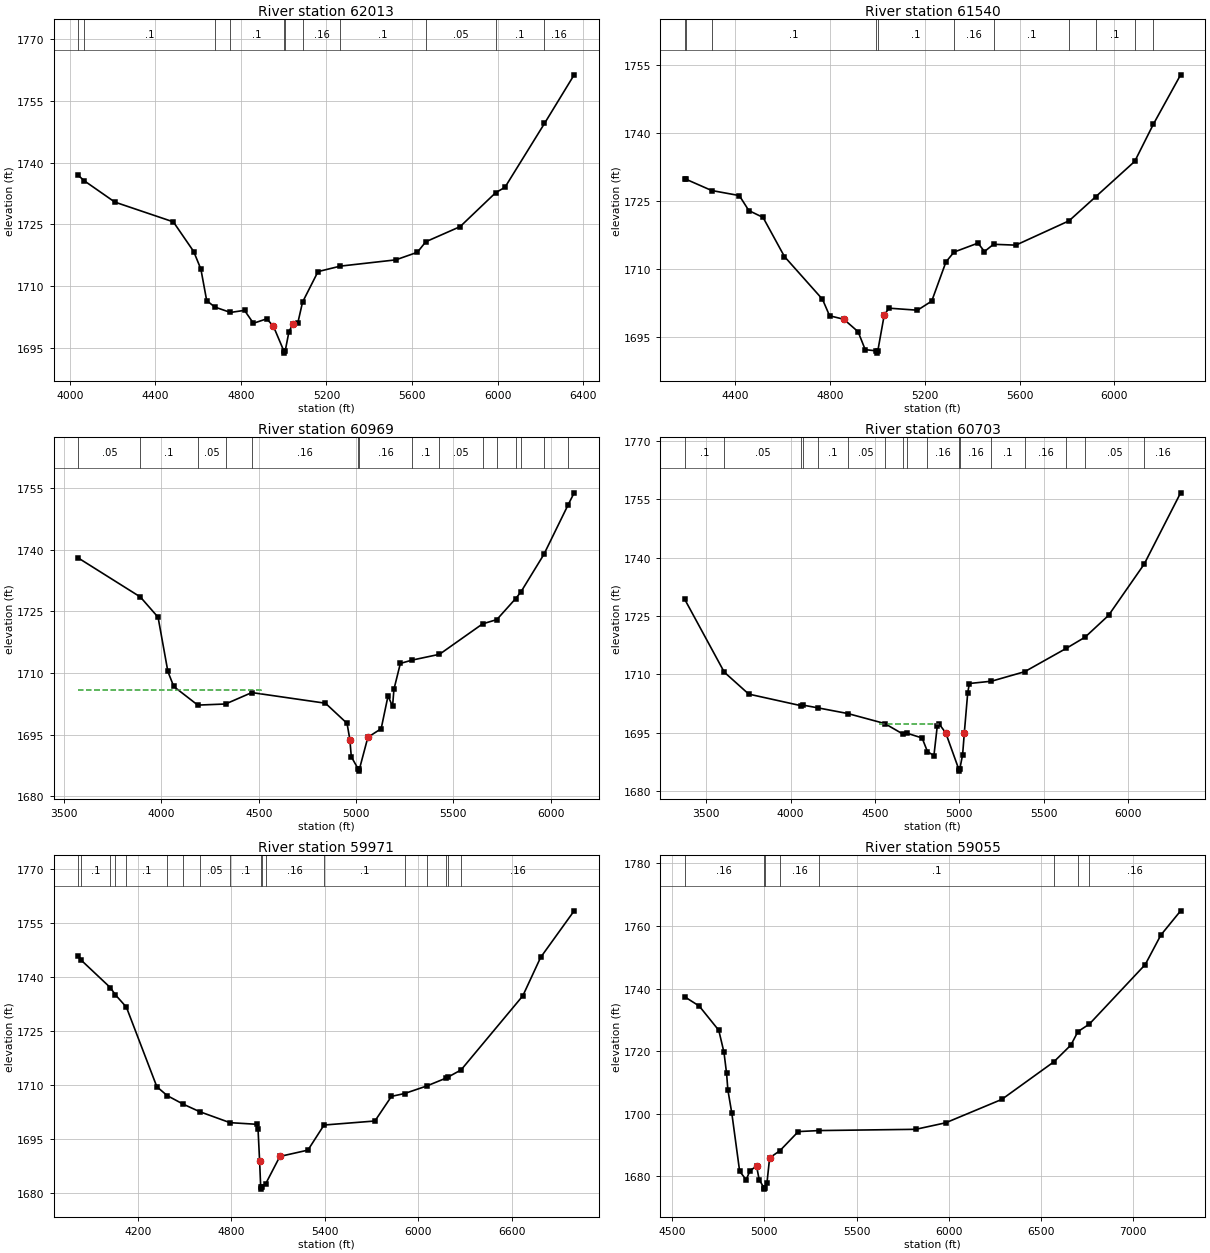
Type RM Length L Ch R = 1 ,62013   ,473,473,473
BEGIN DESCRIPTION:
SOUTH GRAPE CREEK 97.0
END DESCRIPTION:
XS GIS Cut Line= 3
      2775681.41     10018636.43      2777134.52     10018219.77
      2777941.85     10018219.77
#Sta/Elev= 30
  4039.4 1736.92    4067 1735.62  4210.2 1730.44  4483.7 1725.64  4578.9 1718.44
  4612.6 1714.16  4639.7 1706.53  4677.2 1704.96  4750.9 1703.64  4816.6 1704.15
  4858.2 1701.01  4920.6 1702.09  4951.8 1700.29  5000.8 1694.26  5003.6 1693.76
  5006.8 1694.26  5024.6 1698.99  5043.6 1700.89  5066.2 1701.15  5088.1 1706.15
  5160.4 1713.56  5264.7 1714.89    5524 1716.41    5625 1718.25  5664.5 1720.81
    5825 1724.48  5990.8  1732.7    6035 1734.05  6219.5 1749.53  6358.4 1761.35
#Mann= 11 ,-1 , 0
  4039.4     .05       0    4067      .1       0  4677.2     .05       0
  4750.9      .1       0  5000.8     .07       0  5006.8      .1       0
  5088.1     .16       0  5264.7      .1       0  5664.5     .05       0
  5990.8      .1       0  6219.5     .16       0
Bank Sta=4951.8,5043.6
XS Rating Curve= 0 ,0
Exp/Cntr=0.3,0.1

Type RM Length L Ch R = 1 ,61540   ,571,571,571
BEGIN DESCRIPTION:
SOUTH GRAPE CREEK 96.0
END DESCRIPTION:
XS GIS Cut Line= 3
      2775868.92      10018865.6      2776988.69     10018818.72
      2777941.87     10018646.84
#Sta/Elev= 30
  4189.4 1729.98    4196  1729.8  4302.5 1727.35  4419.1 1726.23  4459.2 1722.92
  4519.2  1721.4  4609.3 1712.76  4769.5 1703.33  4799.5 1699.68  4859.5 1698.91
  4919.6 1696.16  4949.6  1692.2  4996.7 1691.93  4999.4 1691.43  5002.7 1691.93
  5029.7 1699.83  5049.7 1701.36  5169.8 1700.91  5229.9 1702.92  5289.9 1711.58
  5323.8 1713.75  5424.8 1715.73  5452.2 1713.87  5490.3 1715.47  5584.3 1715.28
  5808.4 1720.65    5921 1725.98  6085.4 1733.79  6163.9    1742  6278.7  1752.9
#Mann= 11 ,-1 , 0
  4189.4      .1       0    4196     .05       0  4302.5      .1       0
  4996.7     .07       0  5002.7      .1       0  5323.8     .16       0
  5490.3      .1       0  5808.4     .05       0    5921      .1       0
  6085.4     .05       0  6163.9      .1       0
Bank Sta=4859.5,5029.7
XS Rating Curve= 0 ,0
Exp/Cntr=0.3,0.1

Type RM Length L Ch R = 1 ,60969   ,266,266,266
BEGIN DESCRIPTION:
SOUTH GRAPE CREEK 95.0
END DESCRIPTION:
XS GIS Cut Line= 3
      2775561.62     10019084.35      2776879.32     10019245.81
      2777993.68     10018745.91
#Sta/Elev= 30
  3572.7    1738  3891.4 1728.53  3982.6  1723.6    4033  1710.4  4063.2 1706.75
  4186.8 1702.22  4329.3 1702.49  4464.6 1705.27    4843 1702.68  4954.1 1697.78
  4968.5 1693.83    4976 1689.64  5011.8 1686.66  5014.6 1686.16  5017.8 1686.66
  5061.2  1694.4  5129.5 1696.48  5164.8 1704.46    5188 1701.93  5195.2 1706.07
  5228.1 1712.36  5288.7 1713.17  5429.3 1714.58  5650.8 1721.98  5723.9 1723.02
  5820.7 1728.12  5847.9 1729.75  5965.7 1738.86  6091.1 1750.99  6121.6 1753.86
#Mann= 15 ,-1 , 0
  3572.7     .05       0  3891.4      .1       0  4186.8     .05       0
  4329.3      .1       0  4464.6     .16       0  5011.8     .07       0
  5017.8     .16       0  5288.7      .1       0  5429.3     .05       0
  5650.8      .1       0  5723.9     .05       0  5820.7      .1       0
  5847.9     .05       0  5965.7      .1       0  6091.1     .16       0
#XS Ineff= 2 , 0
         4513.28 1705.95
Permanent Ineff=
       T       T
Bank Sta=4968.5,5061.2
XS Rating Curve= 0 ,0
Exp/Cntr=0.3,0.1

Type RM Length L Ch R = 1 ,60703   ,732,732,732
BEGIN DESCRIPTION:
SOUTH GRAPE CREEK 94.0
END DESCRIPTION:
XS GIS Cut Line= 4
      2776103.26     10020652.08      2776749.11     10019459.35
      2777301.19     10019438.52      2778252.83      10019048.5
#Sta/Elev= 30
  3373.1 1729.24    3607 1710.58  3751.9 1704.95  4063.5 1701.96  4071.4 1702.14
  4160.3 1701.43  4338.8 1699.96  4557.4  1697.4  4666.7 1694.66  4688.8 1694.92
  4778.9 1693.69  4810.5 1690.21  4848.9 1689.15  4868.9 1696.81  4878.9 1697.34
    4919 1694.99    4996 1685.68  4998.8 1685.18    5002 1685.68    5019 1689.43
    5029 1695.01  5049.1 1705.28  5059.1 1707.67  5189.8 1708.26  5386.6  1710.7
  5632.8 1716.69  5744.7 1719.57  5883.3 1725.15  6094.5 1738.31  6310.4 1756.61
#Mann= 17 ,-1 , 0
  3373.1      .1       0    3607     .05       0  4063.5      .1       0
  4071.4     .05       0  4160.3      .1       0  4338.8     .05       0
  4557.4      .1       0  4666.7     .16       0  4688.8      .1       0
  4810.5     .16       0    4996     .07       0    5002     .16       0
  5189.8      .1       0  5386.6     .16       0  5632.8      .1       0
  5744.7     .05       0  6094.5     .16       0
#XS Ineff= 1 ,-1
  4523.3 4879.26 1697.32
Permanent Ineff=
       T
Bank Sta=4919,5029
XS Rating Curve= 0 ,0
Exp/Cntr=0.3,0.1

Type RM Length L Ch R = 1 ,59971   ,916,916,916
BEGIN DESCRIPTION:
SOUTH GRAPE CREEK 93.0
END DESCRIPTION:
XS GIS Cut Line= 4
      2776085.38     10020981.21      2776580.18     10020026.32
      2777101.02     10020026.32      2778368.36     10019071.47
#Sta/Elev= 30
  3816.8 1745.92    3837 1744.72  4022.4 1737.17  4053.8 1735.22  4125.3 1731.75
  4320.8 1709.65  4387.1 1707.19  4490.4  1704.8  4595.7 1702.72  4790.3 1699.67
  4960.6 1699.22  4970.6 1697.77  4980.6 1688.97  4987.6 1681.71  4990.3 1681.21
  4993.6 1681.71  5018.8 1682.63  5110.6 1690.29  5290.6 1692.04  5394.1 1699.01
  5720.8 1700.13    5827 1706.97  5911.2 1707.76    6052 1709.83  6179.7 1712.08
  6191.6 1712.36  6273.7 1714.31  6670.2 1734.89  6784.7 1745.57  6999.9  1758.5
#Mann= 18 ,-1 , 0
  3816.8     .16       0    3837      .1       0  4022.4     .16       0
  4053.8     .05       0  4125.3      .1       0  4387.1     .05       0
  4490.4      .1       0  4595.7     .05       0  4790.3      .1       0
  4987.6     .07       0  4993.6      .1       0  5018.8     .16       0
  5394.1      .1       0  5911.2     .05       0    6052      .1       0
  6179.7     .05       0  6191.6      .1       0  6273.7     .16       0
Bank Sta=4980.6,5110.6
XS Rating Curve= 0 ,0
Exp/Cntr=0.3,0.1

Type RM Length L Ch R = 1 ,59055   ,547,547,547
BEGIN DESCRIPTION:
SOUTH GRAPE CREEK 92.0
END DESCRIPTION:
XS GIS Cut Line= 2
      2776675.67     10021111.39      2778541.97     10019175.65
#Sta/Elev= 30
  4568.2 1737.38  4646.4 1734.45  4752.4  1726.7  4780.7 1719.65  4794.8 1712.91
  4801.8 1707.62  4823.1 1700.24  4865.6 1681.67  4900.8 1678.95  4922.2 1681.87
  4957.4 1683.29  4971.6 1678.97  4996.9 1676.45  4999.6 1675.95  5002.9 1676.45
    5014 1678.04  5028.2 1685.93  5084.3 1688.25  5183.8 1694.34  5296.9 1694.66
  5820.3 1695.06  5982.9 1697.14  6287.2 1704.62    6569 1716.59    6662 1721.98
  6700.2 1726.28  6762.3 1728.69  7065.2  1747.7  7149.8 1757.12  7257.1 1764.87
#Mann= 8 ,-1 , 0
  4568.2     .16       0  4996.9     .07       0  5002.9     .16       0
  5084.3     .16       0  5296.9      .1       0    6569     .05       0
  6700.2      .1       0  6762.3     .16       0
Bank Sta=4957.4,5028.2
XS Rating Curve= 0 ,0
Exp/Cntr=0.3,0.1

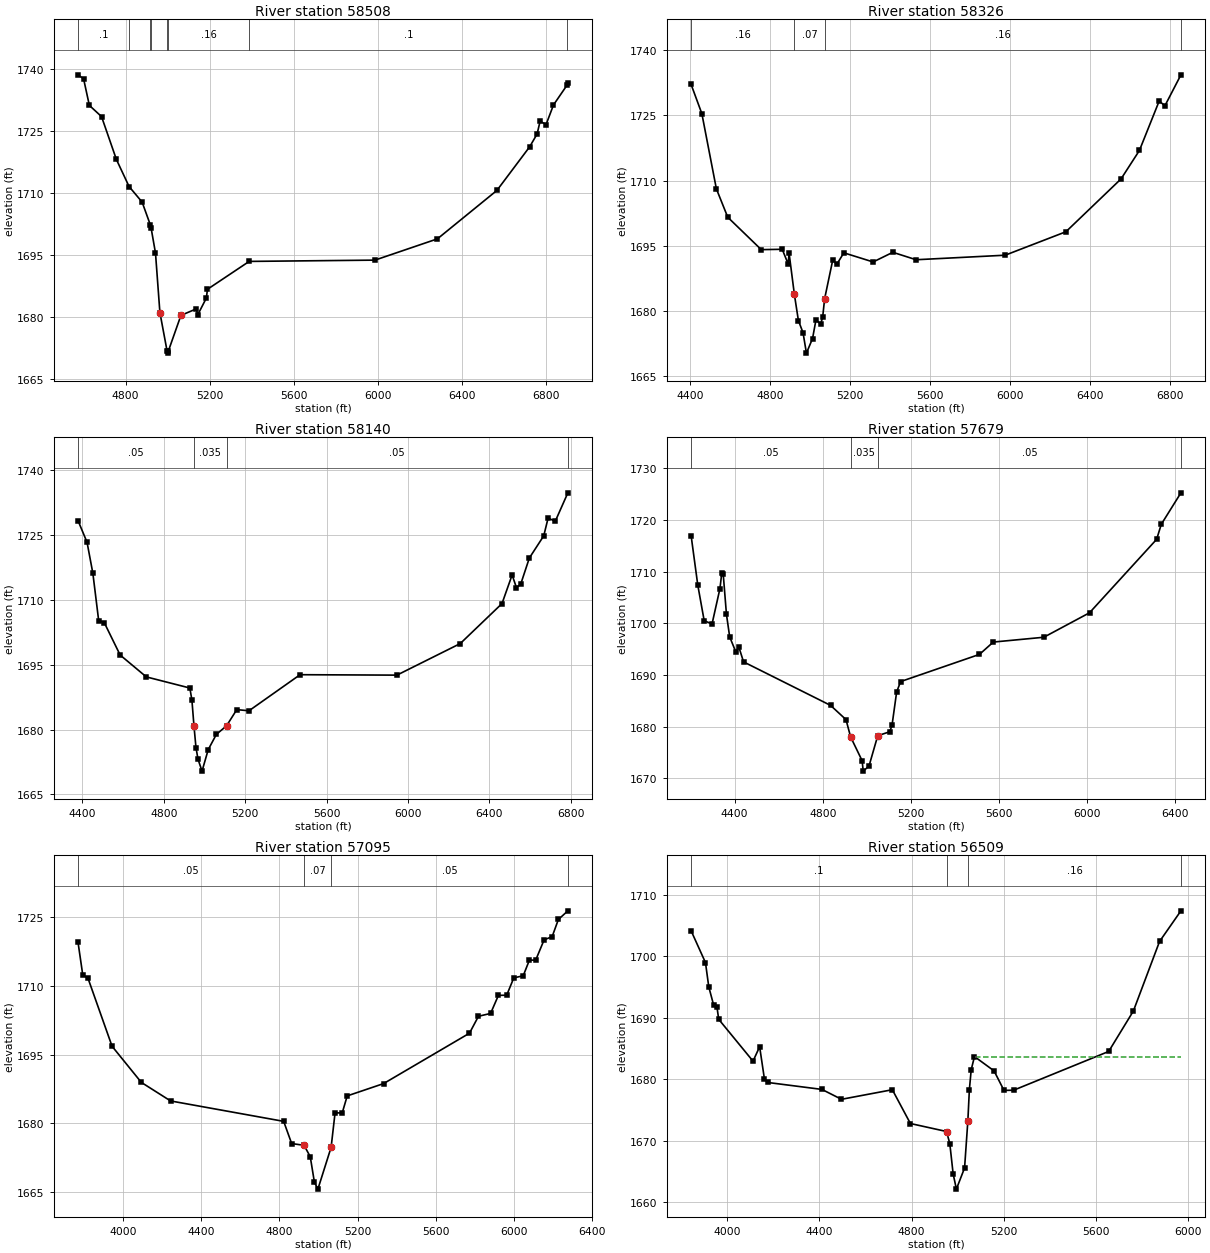
Type RM Length L Ch R = 1 ,58508   ,182,182,182
BEGIN DESCRIPTION:
SOUTH GRAPE CREEK 91.0
END DESCRIPTION:
XS GIS Cut Line= 5
      2777133.16     10021484.62      2777372.72     10021175.63
      2777435.22     10021005.49      2777421.33     10020699.93
      2778444.54     10019673.25
#Sta/Elev= 30
  4574.1 1738.55  4600.5 1737.59  4627.9 1731.15  4685.8 1728.44  4756.4 1718.06
  4816.7 1711.51  4878.6 1707.75  4917.6 1702.24  4921.4 1701.45  4942.2  1695.4
  4963.1 1681.02  4997.3 1671.69  5000.1 1671.19  5003.3 1671.69    5063 1680.32
  5136.7 1681.92  5142.1 1680.38    5184 1684.54    5189 1686.64  5387.4 1693.39
  5984.9  1693.7  6281.9 1698.85  6564.7 1710.58  6720.3 1721.14  6755.6 1724.24
  6769.8 1727.33  6798.1 1726.51  6833.4 1731.26  6899.5 1736.18  6901.7 1736.51
#Mann= 8 ,-1 , 0
  4574.1      .1       0  4816.7     .16       0  4917.6      .1       0
  4921.4     .16       0  4997.3     .07       0  5003.3     .16       0
  5387.4      .1       0  6899.5     .16       0
Bank Sta=4963.1,5063
XS Rating Curve= 0 ,0
Exp/Cntr=0.3,0.1

Type RM Length L Ch R = 1 ,58326   ,186,186,186
BEGIN DESCRIPTION:
Mapping XS af891fb8
END DESCRIPTION:
XS GIS Cut Line= 4
      2777306.73     10021658.28      2777584.52      10021453.4
       2777487.3     10020793.68       2778487.3     10019758.96
#Sta/Elev= 30
  4405.6 1732.11  4459.5 1725.38    4532 1708.13    4589 1701.59  4756.8 1694.14
  4861.6 1694.22  4891.1 1690.87  4896.1 1693.28  4922.3 1683.89  4942.5 1677.85
  4965.8 1675.04  4982.7 1670.36  5013.3 1673.71  5030.4    1678  5053.7 1677.05
  5063.8 1678.58  5073.9 1682.88  5114.3 1691.74  5134.5 1690.75  5169.8 1693.41
  5316.5 1691.31  5415.1 1693.53  5531.5 1691.82    5977 1692.86  6281.1 1698.25
  6557.1  1710.4    6649 1716.94    6748 1728.31  6776.3 1727.18  6856.6 1734.31
#Mann= 4 ,-1 , 0
  4405.6     .16       0  4922.3     .07       0  5073.9     .16       0
  6856.6     .16       0
Bank Sta=4922.3,5073.9
XS Rating Curve= 0 ,0
Exp/Cntr=0.3,0.1

Type RM Length L Ch R = 1 ,58140   ,461,461,461
BEGIN DESCRIPTION:
SOUTH GRAPE CREEK 90.0
END DESCRIPTION:
XS GIS Cut Line= 4
      2777400.53      10021738.1      2777733.83     10021456.88
      2777692.16     10020786.74      2778587.98     10019845.79
#Sta/Elev= 30
  4378.5 1728.32  4422.8 1723.31  4451.4 1716.13    4480 1705.17  4507.4 1704.73
  4585.4 1697.24  4714.1 1692.18  4927.9 1689.61    4938 1686.83    4948 1680.92
    4958 1675.83    4968 1673.14  4987.8 1670.39  5018.1 1675.36  5058.2 1678.89
  5108.3 1680.87  5158.4 1684.61  5218.5 1684.35  5469.5 1692.69  5945.4 1692.59
  6256.5 1699.89  6461.6 1709.14  6511.3 1715.76  6532.4 1712.85  6553.4 1713.61
  6595.9 1719.67  6666.7 1724.81  6688.1 1728.91  6723.3 1728.17  6785.2 1734.75
#Mann= 4 ,-1 , 0
  4378.5     .05       0    4948    .035       0  5108.3     .05       0
  6785.2     .16       0
Bank Sta=4948,5108.3
XS Rating Curve= 0 ,0
Exp/Cntr=0.3,0.1

Type RM Length L Ch R = 1 ,57679   ,584,584,584
BEGIN DESCRIPTION:
SOUTH GRAPE CREEK 89.0
END DESCRIPTION:
XS GIS Cut Line= 3
      2777583.68     10021862.24      2778130.53     10021476.84
      2778583.34      10019988.3
#Sta/Elev= 30
  4202.2 1716.97  4232.5  1707.4  4261.7 1700.49  4297.4 1699.88  4333.2 1706.71
  4341.8 1709.79    4348 1709.58  4362.8 1701.73  4377.5 1697.38  4404.6 1694.53
  4419.4 1695.37  4440.5 1692.54  4835.7 1684.13  4905.8 1681.38  4926.7 1678.04
    4979 1673.44    4984 1671.42  5010.3  1672.4    5050 1678.27  5104.4 1679.03
  5114.9 1680.29  5135.8 1686.71  5153.8 1688.73  5512.1 1693.99  5574.8 1696.37
  5804.3  1697.3  6011.9 1702.03  6316.9 1716.24  6337.8 1719.13  6427.1 1725.22
#Mann= 4 ,-1 , 0
  4202.2     .05       0  4926.7    .035       0    5050     .05       0
  6427.1     .16       0
Bank Sta=4926.7,5050
XS Rating Curve= 0 ,0
Exp/Cntr=0.3,0.1

Type RM Length L Ch R = 1 ,57095   ,586,586,586
BEGIN DESCRIPTION:
SOUTH GRAPE CREEK 88.0
END DESCRIPTION:
XS GIS Cut Line= 2
      2778297.19     10022726.86      2779125.05     10020357.84
#Sta/Elev= 30
  3767.9 1719.52  3792.4 1712.32  3818.1 1711.78  3942.2 1696.82  4092.2 1688.92
  4242.1 1684.87  4821.4 1680.41  4862.3 1675.56  4925.9 1675.17  4957.6 1672.69
  4978.8 1667.13  4996.8  1665.6  5064.5 1674.74  5084.7 1682.27  5121.3 1682.24
    5147 1685.97  5333.3 1688.66  5773.3 1699.67  5819.4 1703.37  5881.5 1703.99
  5921.6 1707.94    5964 1707.97  6000.4 1711.76  6048.7 1712.22  6080.5 1715.66
  6112.3 1715.61  6155.6 1720.06    6197 1720.78  6228.8 1724.52  6277.4 1726.41
#Mann= 4 ,-1 , 0
  3767.9     .05       0  4925.9     .07       0  5064.5     .05       0
  6277.4      .1       0
Bank Sta=4925.9,5064.5
XS Rating Curve= 0 ,0
Exp/Cntr=0.3,0.1

Type RM Length L Ch R = 1 ,56509   ,60,60,60
BEGIN DESCRIPTION:
SOUTH GRAPE CREEK 87.0
END DESCRIPTION:
XS GIS Cut Line= 2
      2778474.28     10022737.26      2779813.72     10021088.98
#Sta/Elev= 30
  3843.9 1704.18  3906.2    1699  3920.6 1695.04  3941.4 1692.11  3955.8 1691.82
  3963.7 1689.76  4112.4 1682.95  4141.1  1685.3  4161.9 1680.04  4176.3 1679.48
  4411.2 1678.35    4496 1676.74  4716.5  1678.3  4794.8  1672.8  4951.4  1671.5
  4965.7 1669.52  4980.1 1664.62  4994.2 1662.12  5029.7 1665.57    5044 1673.27
  5050.5  1678.3  5058.4 1681.54 5072.61  1683.7  5157.5 1681.37  5200.6 1678.19
  5242.3 1678.22  5654.6 1684.53  5761.6 1691.11  5875.1 1702.43  5967.8 1707.42
#Mann= 4 ,-1 , 0
  3843.9      .1       0  4951.4     .07       0    5044     .16       0
  5967.8     .16       0
#XS Ineff= 2 , 0
                         5074.69          1683.7
Permanent Ineff=
       T       T
Bank Sta=4951.4,5044
XS Rating Curve= 0 ,0
Exp/Cntr=0.3,0.1