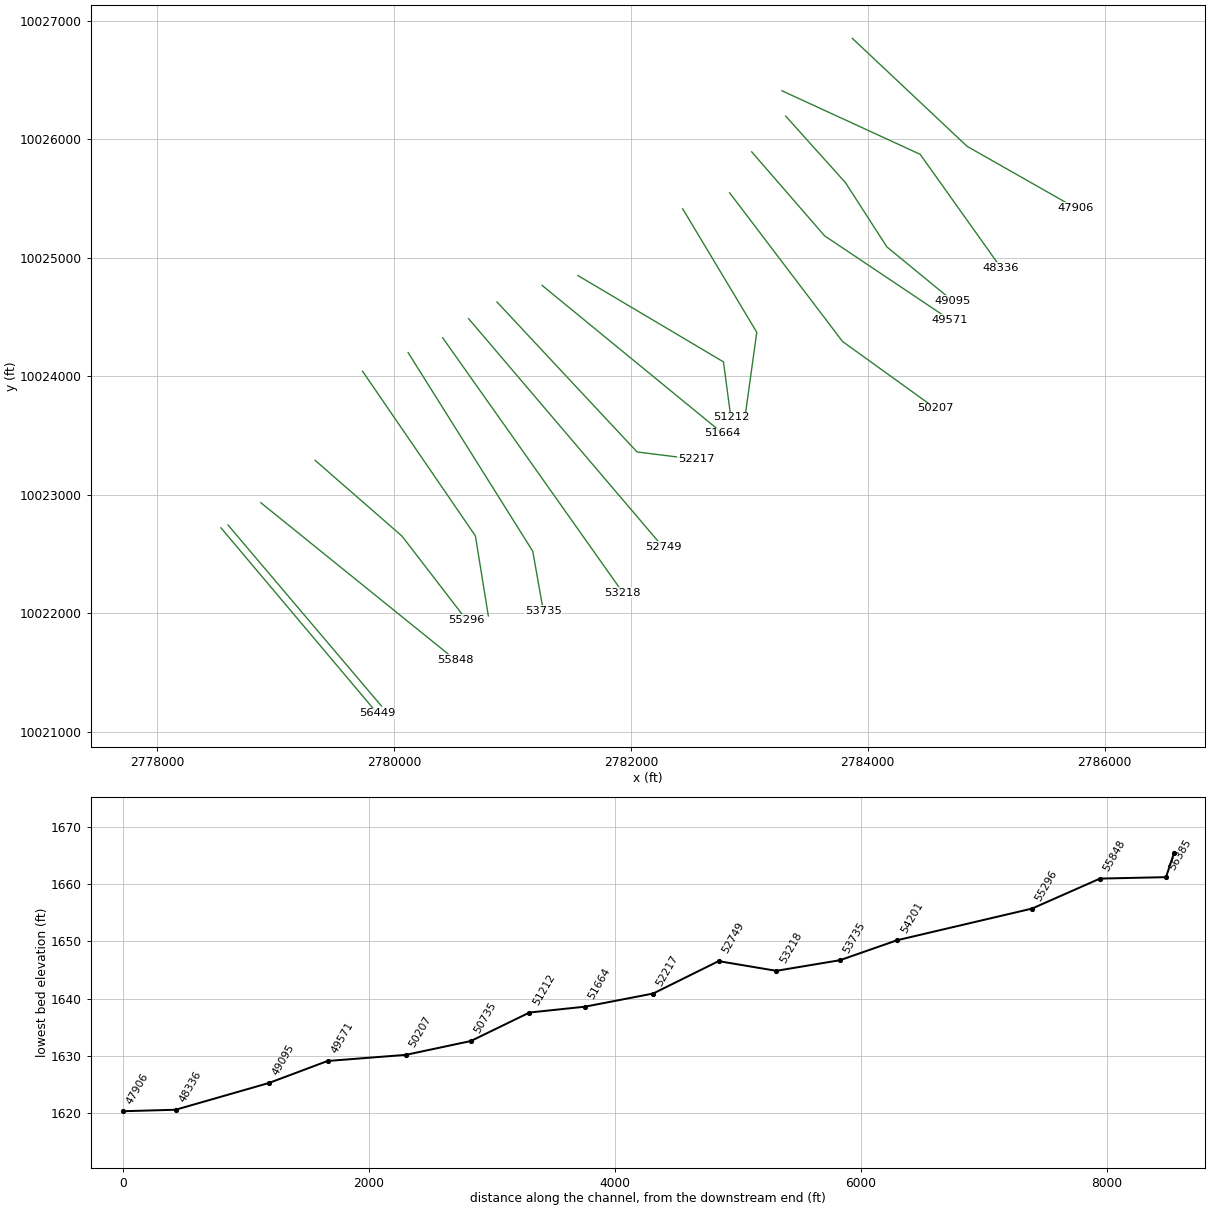
HEC-RAS study SOUTH GRAPE CREEK.prj: SOUTH GRAPE CREEK Base Level Engineering

--- SOUTH GRAPE CREEK.g01 (geometry) --- (continued)

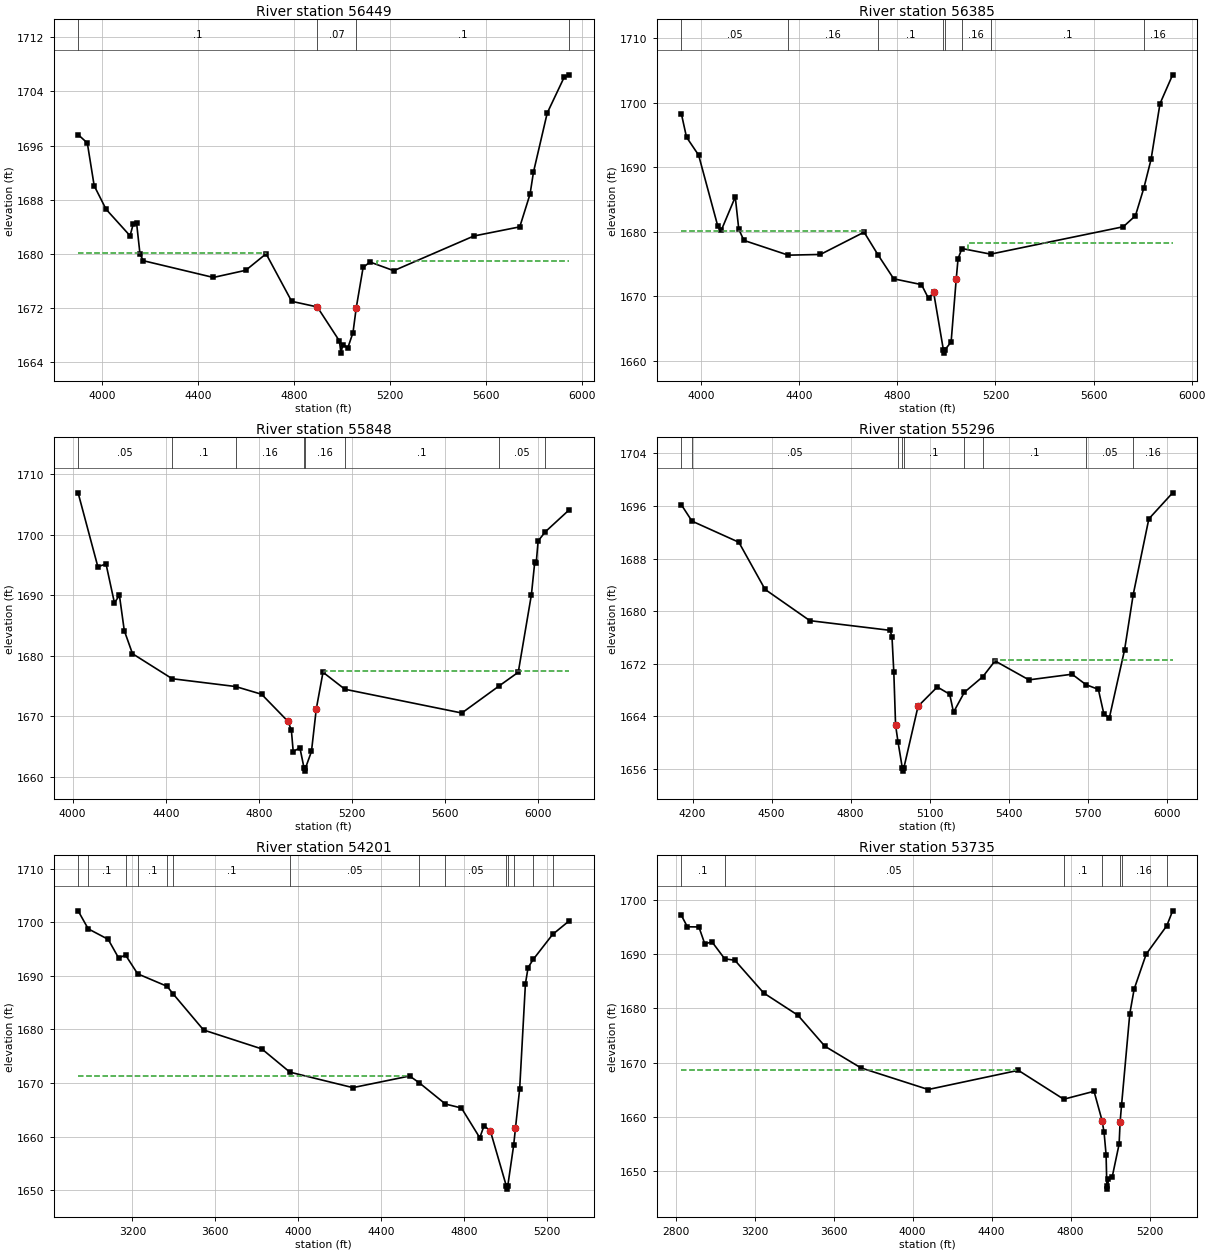
Type RM Length L Ch R = 1 ,56449   ,64,64,64
BEGIN DESCRIPTION:
Mapping XS 5b25c32c
END DESCRIPTION:
XS GIS Cut Line= 2
      2778540.28     10022719.87       2779859.7     10021153.92
#Sta/Elev= 30
  3900.2 1697.62  3938.6 1696.38  3967.2 1690.06  4016.6 1686.59  4116.7 1682.66
  4130.5 1684.47    4144 1684.52  4158.3 1679.91  4172.6 1678.97  4463.9  1676.5
  4599.1 1677.56  4683.7    1680  4790.3 1672.97    4897 1672.14  4989.3 1667.11
  4995.6 1665.31  5003.6 1666.58  5024.4  1666.1  5045.9 1668.35  5059.5 1672.03
  5088.1 1677.98  5116.7 1678.78  5215.9  1677.5  5549.8 1682.63    5741 1683.98
  5783.9 1688.83  5798.2 1692.09  5855.4 1700.81  5925.6 1706.07  5947.9 1706.46
#Mann= 4 ,-1 , 0
  3900.2      .1       0    4897     .07       0  5059.5      .1       0
  5947.9     .16       0
#XS Ineff= 2 , 0
         4684.65 1680.06 5145.23         1678.91
Permanent Ineff=
       T       T
Bank Sta=4897,5059.5
XS Rating Curve= 0 ,0
Exp/Cntr=0.3,0.1

Type RM Length L Ch R = 1 ,56385   ,537,537,537
BEGIN DESCRIPTION:
Mapping XS a172d160
END DESCRIPTION:
XS GIS Cut Line= 2
       2778599.3     10022744.18      2779894.39     10021216.46
#Sta/Elev= 30
  3919.7 1698.34  3940.8 1694.68  3990.2 1691.89  4068.2 1680.89  4082.5 1680.22
  4139.6  1685.4  4153.9 1680.39  4174.8 1678.66  4355.7 1676.37  4486.7 1676.48
  4664.7 1679.94  4720.6 1676.47  4785.5  1672.7  4898.7  1671.8  4927.3 1669.66
  4948.1 1670.62    4988 1661.67  4990.7 1661.17    4994 1661.67  5019.5  1662.9
  5040.4  1672.7  5047.7 1675.79  5063.4  1677.4  5180.4 1676.53  5721.5 1680.78
  5770.9 1682.49  5805.6 1686.85  5834.6 1691.24  5870.9 1699.87  5922.5 1704.35
#Mann= 8 ,-1 , 0
  3919.7     .05       0  4355.7     .16       0  4720.6      .1       0
    4988     .07       0    4994      .1       0  5063.4     .16       0
  5180.4      .1       0  5805.6     .16       0
#XS Ineff= 2 , 0
         4668.05 1680.15 5089.21         1678.23
Permanent Ineff=
       T       T
Bank Sta=4948.1,5040.4
XS Rating Curve= 0 ,0
Exp/Cntr=0.3,0.1

Type RM Length L Ch R = 1 ,55848   ,552,552,552
BEGIN DESCRIPTION:
Mapping XS 2fc69356
END DESCRIPTION:
XS GIS Cut Line= 2
      2778877.07      10022931.7      2780519.44     10021605.29
#Sta/Elev= 30
  4023.6 1706.94  4108.4 1694.72  4143.6 1695.17  4179.6 1688.76  4201.2 1689.97
    4222 1684.16  4257.2 1680.34  4427.8  1676.2  4700.2 1674.91  4812.1 1673.63
  4925.6 1669.14    4940 1667.68  4947.9 1664.15  4976.6 1664.78  4994.5 1661.42
  4997.3 1660.92  5000.5 1661.42  5026.3 1664.17  5047.1 1671.22  5075.9 1677.27
  5169.9 1674.46  5672.4 1670.53  5831.7 1674.98  5914.9 1677.27  5971.4  1690.1
  5985.8  1695.5  5992.2 1695.39  6000.2 1698.98  6031.6 1700.51  6134.7 1704.16
#Mann= 8 ,-1 , 0
  4023.6     .05       0  4427.8      .1       0  4700.2     .16       0
  4994.5     .07       0  5000.5     .16       0  5169.9      .1       0
  5831.7     .05       0  6031.6     .16       0
#XS Ineff= 2 , 0
                         5078.84         1677.47
Permanent Ineff=
       T       T
Bank Sta=4925.6,5047.1
XS Rating Curve= 0 ,0
Exp/Cntr=0.3,0.1

Type RM Length L Ch R = 1 ,55296   ,1095,1095,1095
BEGIN DESCRIPTION:
SOUTH GRAPE CREEK 85.0
END DESCRIPTION:
XS GIS Cut Line= 3
      2779335.42     10023289.32      2780068.03     10022650.45
      2780613.19     10021942.09
#Sta/Elev= 30
  4157.4 1696.18  4197.8 1693.69  4375.8 1690.48  4475.5 1683.31  4645.5 1678.56
  4950.2 1677.09  4957.5 1676.08  4964.4 1670.72  4971.1 1662.67  4980.1 1660.19
  4996.6 1656.19  4999.3 1655.69  5002.6 1656.19  5056.5 1665.55  5129.4 1668.48
  5176.6 1667.38  5191.1 1664.64  5232.2 1667.67  5302.3 1670.04  5348.8 1672.44
  5477.5 1669.56  5641.5 1670.42  5694.2 1668.83  5741.2 1668.12    5762  1664.4
  5782.8 1663.76  5840.8 1674.13  5873.6 1682.53  5932.9 1694.03  6023.3 1697.99
#Mann= 9 ,-1 , 0
  4157.4      .1       0  4197.8     .05       0  4980.1      .1       0
  4996.6     .07       0  5002.6      .1       0  5232.2     .16       0
  5302.3      .1       0  5694.2     .05       0  5873.6     .16       0
#XS Ineff= 2 , 0
                         5346.47         1672.55
Permanent Ineff=
       T       T
Bank Sta=4971.1,5056.5
XS Rating Curve= 0 ,0
Exp/Cntr=0.3,0.1

Type RM Length L Ch R = 1 ,54201   ,466,466,466
BEGIN DESCRIPTION:
SOUTH GRAPE CREEK 84.0
END DESCRIPTION:
XS GIS Cut Line= 3
      2779734.68     10024042.83      2780687.82     10022652.19
      2780796.91     10021976.88
#Sta/Elev= 30
  2937.7 1702.14  2986.4 1698.78  3082.6 1696.82  3133.4 1693.32  3166.4 1693.89
  3224.8 1690.38  3366.8 1688.05  3396.7  1686.6  3542.9 1679.89  3823.8 1676.36
  3959.3 1672.02  4263.1 1669.13  4536.9  1671.3  4583.8 1670.02  4709.9 1666.06
  4786.8 1665.33  4875.3 1659.77  4895.6 1661.98    4926  1661.1    5004 1650.68
  5006.7 1650.18    5010 1650.68  5038.8 1658.38  5047.5 1661.56  5067.8 1668.93
  5095.5 1688.53  5108.3 1691.54  5133.3 1693.08  5226.9 1697.74  5307.7  1700.3
#Mann= 14 ,-1 , 0
  2937.7     .05       0  2986.4      .1       0  3166.4     .05       0
  3224.8      .1       0  3366.8     .05       0  3396.7      .1       0
  3959.3     .05       0  4583.8      .1       0  4709.9     .05       0
    5004     .04       0    5010     .05       0  5038.8      .1       0
  5133.3     .16       0  5226.9     .05       0
#XS Ineff= 2 , 0
            4539 1671.31
Permanent Ineff=
       T       T
Bank Sta=4926,5047.5
XS Rating Curve= 0 ,0
Exp/Cntr=0.3,0.1

Type RM Length L Ch R = 1 ,53735   ,517,517,517
BEGIN DESCRIPTION:
Mapping XS a5b6bd5a
END DESCRIPTION:
XS GIS Cut Line= 3
      2780120.11     10024199.07       2781172.2     10022521.98
      2781260.75     10022021.94
#Sta/Elev= 30
    2829 1697.13  2859.5 1695.01  2917.9 1694.98  2947.8 1691.86  2984.4 1692.23
  3048.8  1689.1  3099.8 1688.85  3245.9 1682.82  3419.2 1678.72  3555.8 1673.01
  3738.5 1669.02    4079 1665.04  4535.2 1668.57  4765.2 1663.25  4918.7 1664.71
  4959.3 1659.32  4969.5 1657.13  4979.6 1653.06  4983.4 1647.19  4986.2 1646.69
  4991.5 1648.48  5010.1 1648.84  5045.6 1654.98  5050.7 1659.09  5058.2 1662.26
  5099.6 1678.99  5121.8 1683.54  5182.8 1689.98    5287  1695.2  5316.6 1697.95
#Mann= 7 ,-1 , 0
    2829      .1       0  3048.8     .05       0  4765.2      .1       0
  4959.3     .07       0  5050.7      .1       0  5058.2     .16       0
    5287      .1       0
#XS Ineff= 2 , 0
         4524.07 1668.68
Permanent Ineff=
       T       T
Bank Sta=4959.3,5050.7
XS Rating Curve= 0 ,0
Exp/Cntr=0.3,0.1

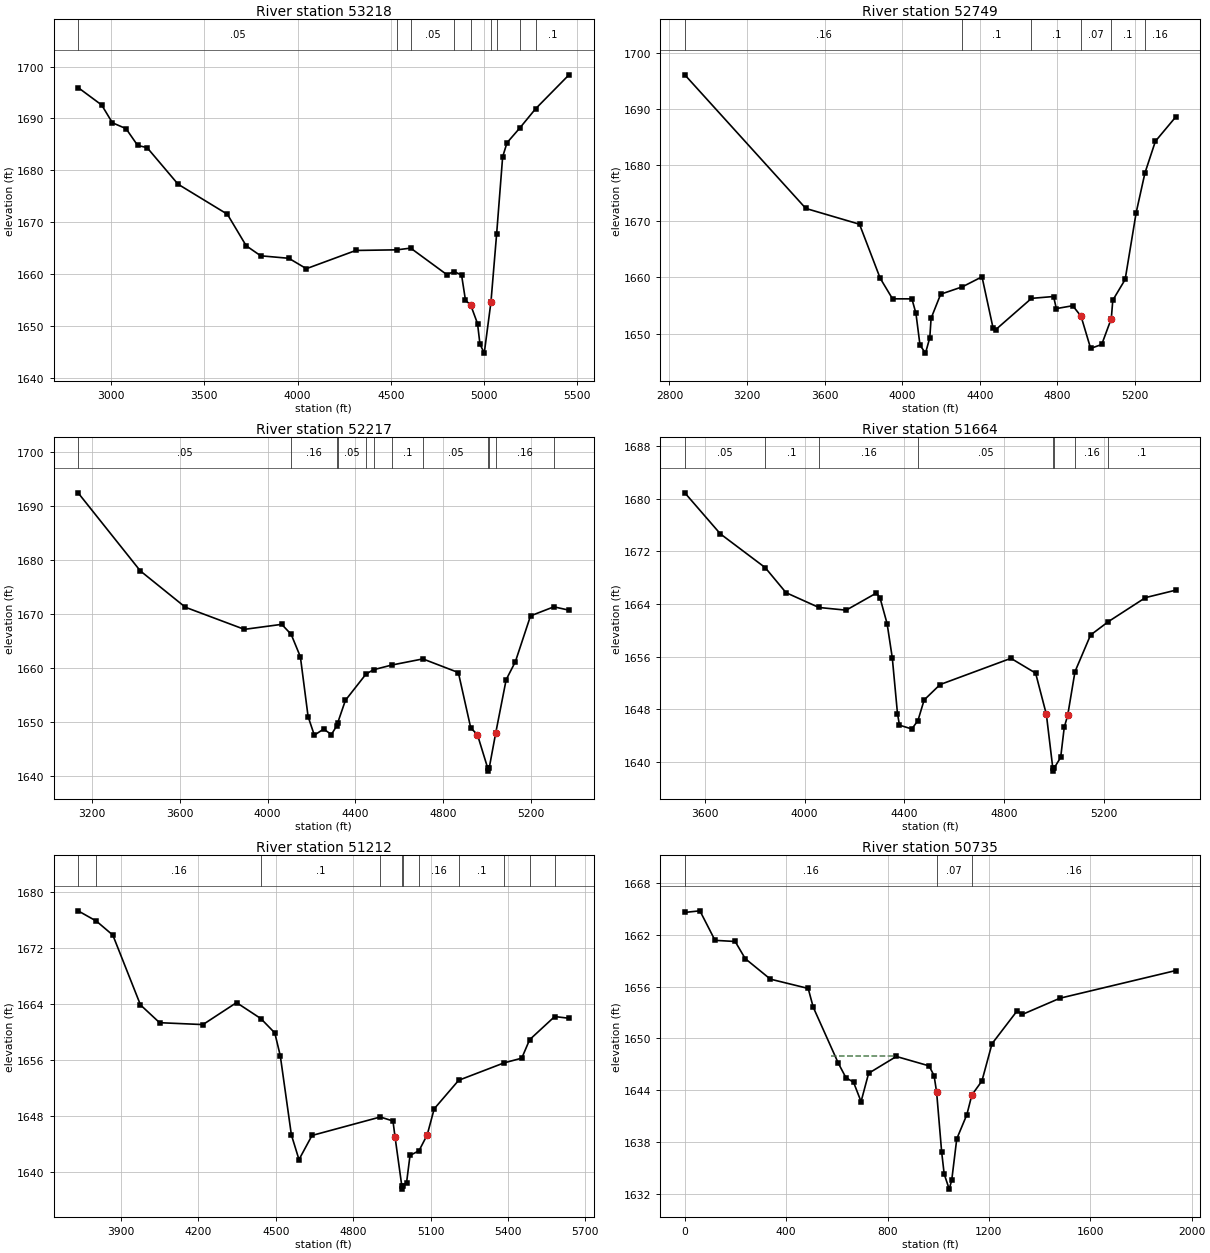
Type RM Length L Ch R = 1 ,53218   ,469,469,469
BEGIN DESCRIPTION:
SOUTH GRAPE CREEK 83.0
END DESCRIPTION:
XS GIS Cut Line= 2
      2780411.79     10024324.05      2781932.64     10022172.98
#Sta/Elev= 30
  2822.3 1695.95  2948.9 1692.59  3006.4 1689.17  3079.4 1688.05  3142.1 1684.81
  3192.6 1684.39  3358.8 1677.35  3623.4 1671.57  3724.4  1665.5  3802.4 1663.57
  3953.3 1663.09  4047.4 1661.09  4312.8  1664.6  4533.5 1664.72  4607.1 1665.05
  4800.2 1659.97  4840.9 1660.53  4880.2 1659.86  4901.2    1655  4929.2  1654.1
  4965.9 1650.51  4978.7 1646.59  5001.9 1644.84  5037.8 1654.66  5068.5 1667.85
  5100.6 1682.61    5124 1685.33  5191.6 1688.12  5277.5 1691.87  5456.7  1698.4
#Mann= 9 ,-1 , 0
  2822.3     .05       0  4533.5      .1       0  4607.1     .05       0
  4840.9      .1       0  4929.2     .07       0  5037.8      .1       0
  5068.5     .16       0  5191.6     .05       0  5277.5      .1       0
Bank Sta=4929.2,5037.8
XS Rating Curve= 0 ,0
Exp/Cntr=0.3,0.1

Type RM Length L Ch R = 1 ,52749   ,532,532,532
BEGIN DESCRIPTION:
SOUTH GRAPE CREEK 82.0
END DESCRIPTION:
XS GIS Cut Line= 2
      2780630.53     10024485.53      2782271.04     10022558.58
#Sta/Elev= 30
    2879 1696.08  3502.9 1672.29  3779.6 1669.48  3886.1 1659.87  3949.8  1656.2
  4049.8 1656.19  4070.6 1653.59  4091.5 1647.94  4119.8 1646.53    4142 1649.29
  4148.6 1652.73    4198 1657.02  4310.2 1658.34  4411.1 1660.12  4468.2 1650.98
  4482.5 1650.73  4666.1 1656.28    4780 1656.61  4794.3 1654.46  4878.8 1654.97
  4921.7 1653.09  4971.1 1647.37  5028.2 1648.07  5077.6 1652.68  5085.3 1655.95
    5149 1659.64  5205.9 1671.56    5251  1678.6  5304.9 1684.25  5409.7 1688.58
#Mann= 6 ,-1 , 0
    2879     .16       0  4310.2      .1       0  4666.1      .1       0
  4921.7     .07       0  5077.6      .1       0    5251     .16       0
Bank Sta=4921.7,5077.6
XS Rating Curve= 0 ,0
Exp/Cntr=0.3,0.1

Type RM Length L Ch R = 1 ,52217   ,553,553,553
BEGIN DESCRIPTION:
SOUTH GRAPE CREEK 81.0
END DESCRIPTION:
XS GIS Cut Line= 3
      2780870.14     10024626.12      2782052.41     10023360.52
      2782552.41     10023298.02
#Sta/Elev= 30
  3136.8 1692.49  3420.3 1678.01  3625.5 1671.27  3894.2 1667.17  4064.2  1668.1
  4107.2 1666.25  4149.2 1662.08  4184.3    1651  4212.7 1647.55  4255.2 1648.68
  4290.3 1647.67  4315.2 1649.29  4318.9  1649.8  4354.3 1654.01  4448.3 1658.89
  4482.2 1659.68  4564.9 1660.55  4707.1 1661.69  4868.7 1659.16  4925.2 1648.87
  4955.4 1647.66  5002.8 1641.38  5005.6 1640.88  5008.8 1641.38  5038.6  1647.9
  5086.4 1657.84  5128.4 1661.18  5197.3 1669.67  5303.6 1671.35  5372.6 1670.73
#Mann= 12 ,-1 , 0
  3136.8     .05       0  4107.2     .16       0  4315.2      .1       0
  4318.9     .05       0  4448.3      .1       0  4482.2     .05       0
  4564.9      .1       0  4707.1     .05       0  5002.8     .04       0
  5008.8     .05       0  5038.6     .16       0  5303.6      .1       0
Bank Sta=4955.4,5038.6
XS Rating Curve= 0 ,0
Exp/Cntr=0.3,0.1

Type RM Length L Ch R = 1 ,51664   ,452,452,452
BEGIN DESCRIPTION:
SOUTH GRAPE CREEK 80.0
END DESCRIPTION:
XS GIS Cut Line= 2
      2781250.33     10024766.77      2782773.71     10023518.95
#Sta/Elev= 30
  3519.7  1680.9  3662.3 1674.66  3842.2 1669.53  3925.7 1665.72  4057.6 1663.47
  4166.9 1663.06  4288.1 1665.66  4302.5 1664.97  4331.2 1661.01    4352 1655.81
  4372.8 1647.35  4380.7 1645.58  4430.3    1645  4454.9 1646.28  4479.8 1649.41
  4543.7 1651.75  4827.9 1655.74  4926.9 1653.49    4970 1647.22  4995.7 1639.09
  4998.5 1638.59  5001.7 1639.09  5027.4 1640.67  5041.8 1645.26  5055.5 1647.05
  5084.8 1653.71  5147.3 1659.28  5219.2 1661.33  5367.6 1664.97  5488.9  1666.1
#Mann= 8 ,-1 , 0
  3519.7     .05       0  3842.2      .1       0  4057.6     .16       0
  4454.9     .05       0  4995.7     .04       0  5001.7     .05       0
  5084.8     .16       0  5219.2      .1       0
Bank Sta=4970,5055.5
XS Rating Curve= 0 ,0
Exp/Cntr=0.3,0.1

Type RM Length L Ch R = 1 ,51212   ,477,477,477
BEGIN DESCRIPTION:
SOUTH GRAPE CREEK 79.0
END DESCRIPTION:
XS GIS Cut Line= 3
      2781552.37     10024850.13      2782781.57     10024120.94
      2782844.07      10023652.2
#Sta/Elev= 30
  3734.3 1677.35  3805.2 1675.88  3868.9 1673.88    3976  1663.9  4050.1 1661.36
  4218.1 1661.09  4348.2 1664.23  4442.3 1661.95  4496.4  1659.9  4517.8 1656.62
  4560.7 1645.33  4590.2 1641.79  4640.6 1645.24  4905.1 1647.88  4954.3 1647.31
  4962.2 1645.07  4988.4 1638.07  4991.1 1637.57  4994.4 1638.07    5007  1638.5
  5020.4 1642.39  5055.1 1643.05  5086.9 1645.32  5114.1 1649.05    5209 1653.13
  5384.3 1655.61  5453.3 1656.29  5483.8 1658.93  5580.9 1662.24  5636.4 1661.99
#Mann= 11 ,-1 , 0
  3734.3      .1       0  3805.2     .16       0  4442.3      .1       0
  4905.1     .05       0  4988.4     .04       0  4994.4     .05       0
  5055.1     .16       0    5209      .1       0  5384.3     .16       0
  5483.8      .1       0  5580.9     .16       0
Bank Sta=4962.2,5086.9
XS Rating Curve= 0 ,0
Exp/Cntr=0.3,0.1

Type RM Length L Ch R = 1 ,50735   ,528,528,528
BEGIN DESCRIPTION:
SOUTH GRAPE CREEK 78.0
END DESCRIPTION:
XS GIS Cut Line= 3
      2782437.82     10025412.61      2783062.82     10024370.94
     2782961.529    10023640.367
#Sta/Elev= 30
       0 1664.5659.611981664.745 119.2241661.336198.70661661.203238.44791659.222
337.80121656.851486.8311 1655.78506.70181653.614606.0551 1647.12635.86111645.465
665.66711644.953695.47311642.707725.27911645.979834.56771647.922 963.7271646.836
983.59771645.698 993.5331643.8051013.4041636.9051023.3391634.354 1043.211632.598
1053.1451633.6191073.0161638.4021112.7571641.1931132.6281643.4741172.3691645.093
 1212.111649.3951311.4031653.1971331.2621652.7721480.2011654.6511936.9491657.846
#Mann= 3 ,-1 , 0
       0     .16       0 993.533     .07       01132.628     .16       0
#XS Ineff= 1 ,-1
  578.12  834.38 1647.98
Permanent Ineff=
       T
Bank Sta=993.533,1132.628
XS Rating Curve= 0 ,0
Exp/Cntr=0.3,0.1

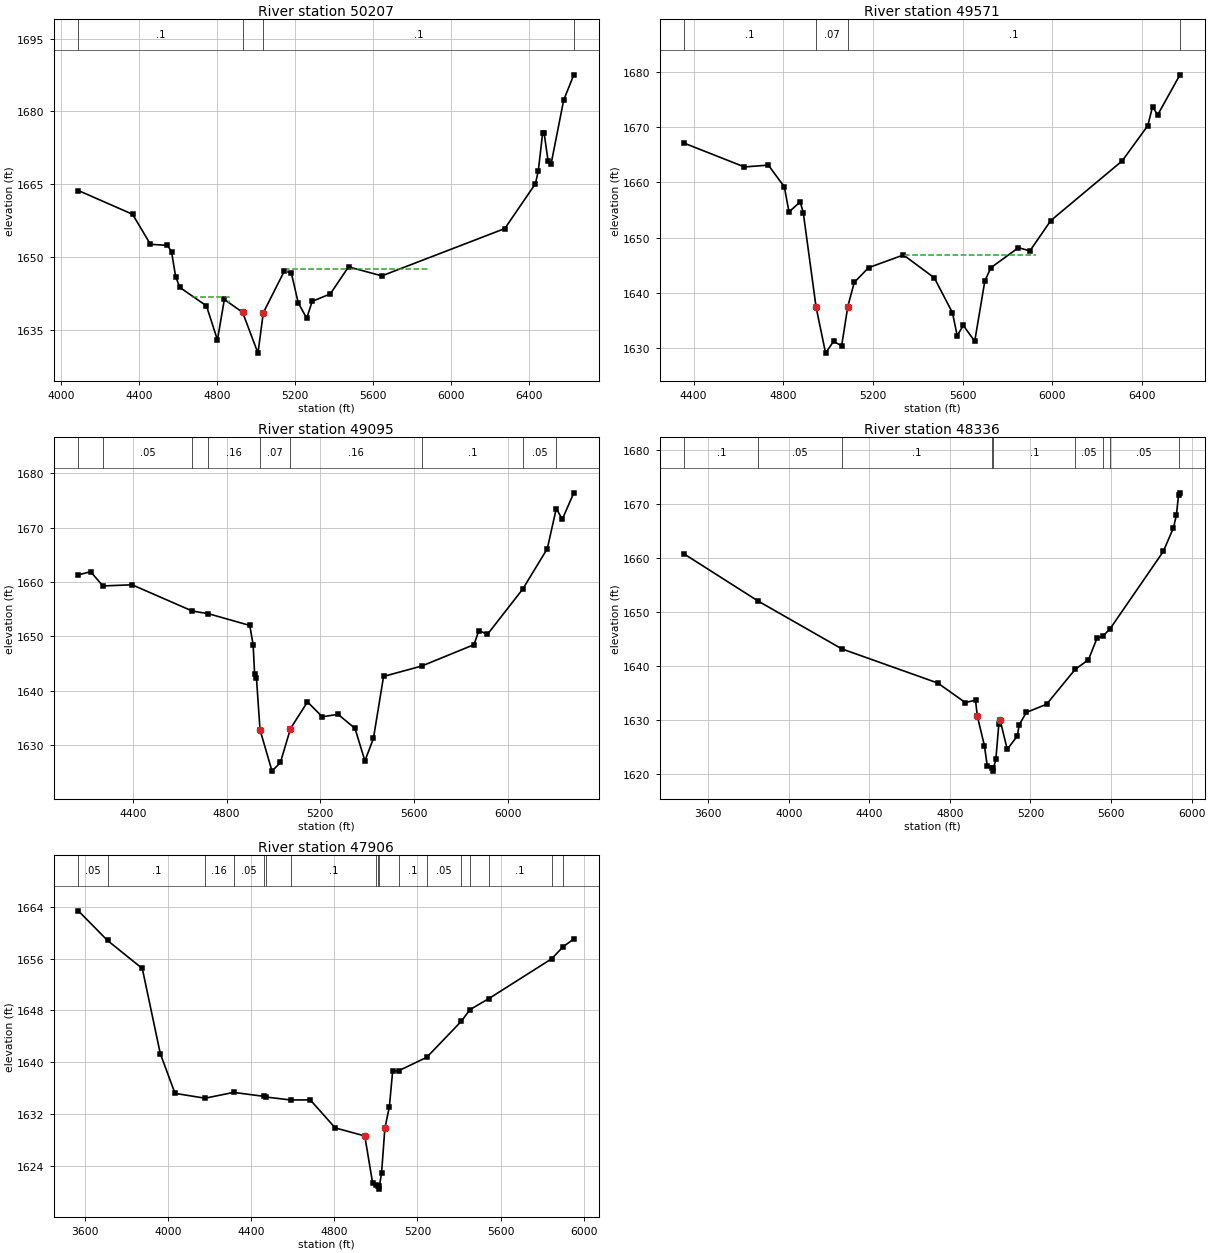
Type RM Length L Ch R = 1 ,50207   ,636,636,636
BEGIN DESCRIPTION:
SOUTH GRAPE CREEK 77.0
END DESCRIPTION:
XS GIS Cut Line= 3
      2782833.65     10025548.03      2783786.78     10024292.81
      2784568.06     10023730.29
#Sta/Elev= 30
  4088.8  1663.7  4366.9  1658.8  4458.4 1652.61  4545.7  1652.4  4566.5 1651.06
  4587.4 1645.98    4609 1643.73  4745.4 1639.93  4801.6  1632.9    4837 1641.25
  4930.5  1638.6  5009.3 1630.19  5036.6 1638.51  5144.7 1647.12  5180.1 1646.74
  5215.5 1640.55  5259.1 1637.37    5287 1640.86  5379.8 1642.39  5473.3 1647.97
  5643.9 1646.11  6273.9 1655.86    6431  1665.1  6445.7 1667.75  6467.9 1675.56
  6475.2 1675.61    6496 1669.73  6510.8 1669.11  6575.8 1682.35  6627.6 1687.54
#Mann= 4 ,-1 , 0
  4088.8      .1       0  4930.5     .07       0  5036.6      .1       0
  6627.6      .1       0
#XS Ineff= 2 ,-1
 4673.47 4860.31 1641.72 5160.09 5886.881647.448
Permanent Ineff=
       T       T
Bank Sta=4930.5,5036.6
XS Rating Curve= 0 ,0
Exp/Cntr=0.3,0.1

Type RM Length L Ch R = 1 ,49571   ,476,476,476
BEGIN DESCRIPTION:
SOUTH GRAPE CREEK 76.0
END DESCRIPTION:
XS GIS Cut Line= 3
      2783020.28     10025893.52      2783634.87     10025185.17
      2784690.72     10024477.81
#Sta/Elev= 30
  4359.4 1667.05  4627.1 1662.77  4733.5  1663.1  4804.7 1659.18  4825.6 1654.64
  4875.5 1656.46  4889.2 1654.49  4946.2 1637.45  4988.7 1629.12  5024.1 1631.25
  5060.2 1630.43  5087.7 1637.54  5116.2 1641.89    5180 1644.56  5335.8 1646.86
  5473.3 1642.73  5554.3 1636.41  5575.3 1632.28  5602.5 1634.13  5653.4 1631.26
  5698.4 1642.13  5725.4 1644.56  5848.5 1648.18  5899.5  1647.6  5992.6 1653.08
  6310.8 1663.87  6424.8 1670.23  6445.9 1673.64  6469.1 1672.18  6568.1 1679.42
#Mann= 4 ,-1 , 0
  4359.4      .1       0  4946.2     .07       0  5087.7      .1       0
  6568.1      .1       0
#XS Ineff= 1 ,-1
 5341.26 5927.641646.893
Permanent Ineff=
       T
Bank Sta=4946.2,5087.7
XS Rating Curve= 0 ,0
Exp/Cntr=0.3,0.1

Type RM Length L Ch R = 1 ,49095   ,759,759,759
BEGIN DESCRIPTION:
SOUTH GRAPE CREEK 75.0
END DESCRIPTION:
XS GIS Cut Line= 4
      2783306.73     10026195.61      2783811.96     10025633.09
      2784160.91     10025091.42      2784712.72     10024638.53
#Sta/Elev= 30
  4167.3  1661.3  4219.6  1661.9  4272.2 1659.28  4396.7 1659.49  4653.9 1654.67
  4721.9 1654.19    4899 1652.03  4913.3 1648.45  4919.6 1643.04  4927.4 1642.41
  4942.6 1632.89  4993.8 1625.29  5029.7 1626.88  5072.6  1633.1  5145.2 1637.99
  5208.6 1635.26  5275.3 1635.72  5347.9 1633.14  5390.2 1627.17  5426.5 1631.29
  5469.8 1642.67  5633.3 1644.59  5855.7  1648.5  5876.5  1651.1  5913.1 1650.39
  6063.6  1658.7  6168.5 1666.12  6206.8 1673.49  6232.4 1671.51  6281.6 1676.37
#Mann= 9 ,-1 , 0
  4167.3      .1       0  4272.2     .05       0  4653.9      .1       0
  4721.9     .16       0  4942.6     .07       0  5072.6     .16       0
  5633.3      .1       0  6063.6     .05       0  6206.8      .1       0
#XS Ineff= 1 ,-1
 5144.89 5511.361637.119
Permanent Ineff=
       T
Bank Sta=4942.6,5072.6
XS Rating Curve= 0 ,0
Exp/Cntr=0.3,0.1

Type RM Length L Ch R = 1 ,48336   ,430,430,430
BEGIN DESCRIPTION:
SOUTH GRAPE CREEK 74.0
END DESCRIPTION:
XS GIS Cut Line= 3
      2783275.54     10026409.11      2784442.16     10025872.67
      2785123.96     10024915.03
#Sta/Elev= 30
  3482.4 1660.71  3848.8 1652.03  4264.2  1643.2  4740.4 1636.89    4877 1633.28
  4927.4 1633.75    4936 1630.84  4971.6 1625.31  4986.1 1621.48  5010.4 1621.12
  5013.2 1620.62  5016.4 1621.12  5028.2 1622.77    5043 1629.26  5049.1 1630.13
  5084.7 1624.64  5135.2 1627.12  5143.8 1629.15  5179.4 1631.46  5280.3 1632.98
  5421.6 1639.41  5488.1 1641.21  5529.9 1645.13  5559.4 1645.57    5594 1646.85
  5859.4  1661.2  5909.8 1665.57  5924.5 1667.91  5935.3 1671.68    5942 1672.04
#Mann= 9 ,-1 , 0
  3482.4      .1       0  3848.8     .05       0  4264.2      .1       0
  5010.4     .07       0  5016.4      .1       0  5421.6     .05       0
  5559.4      .1       0    5594     .05       0  5935.3      .1       0
Bank Sta=4936,5049.1
XS Rating Curve= 0 ,0
Exp/Cntr=0.3,0.1

Type RM Length L Ch R = 1 ,47906   ,505,505,505
BEGIN DESCRIPTION:
SOUTH GRAPE CREEK 73.0
END DESCRIPTION:
XS GIS Cut Line= 3
      2783869.28     10026851.81        2784838.     10025940.38
      2785754.08     10025419.88
#Sta/Elev= 30
  3568.7 1663.37  3709.1 1658.79  3876.5 1654.46  3963.1  1641.3  4033.9 1635.16
  4178.5 1634.41  4315.8 1635.31  4461.2  1634.7    4472 1634.59  4590.3 1634.14
  4684.4 1634.15  4804.6 1629.82  4946.8 1628.58  4984.3 1621.34  5001.4 1621.06
  5011.3 1620.86  5014.1 1620.36  5017.3 1620.86  5027.6 1622.86  5043.4 1629.75
  5065.1 1633.09  5080.9 1638.62  5110.2 1638.66  5245.2 1640.74  5410.9 1646.29
  5453.2 1648.11  5542.9 1649.79  5845.9 1655.96  5901.1 1657.82  5952.4 1659.02
#Mann= 17 ,-1 , 0
  3568.7     .05       0  3709.1      .1       0  4178.5     .16       0
  4315.8     .05       0  4461.2      .1       0    4472     .05       0
  4590.3      .1       0  5001.4     .16       0  5011.3     .07       0
  5017.3     .16       0  5110.2      .1       0  5245.2     .05       0
  5410.9      .1       0  5453.2     .05       0  5542.9      .1       0
  5845.9     .05       0  5901.1      .1       0
Bank Sta=4946.8,5043.4
XS Rating Curve= 0 ,0
Exp/Cntr=0.3,0.1