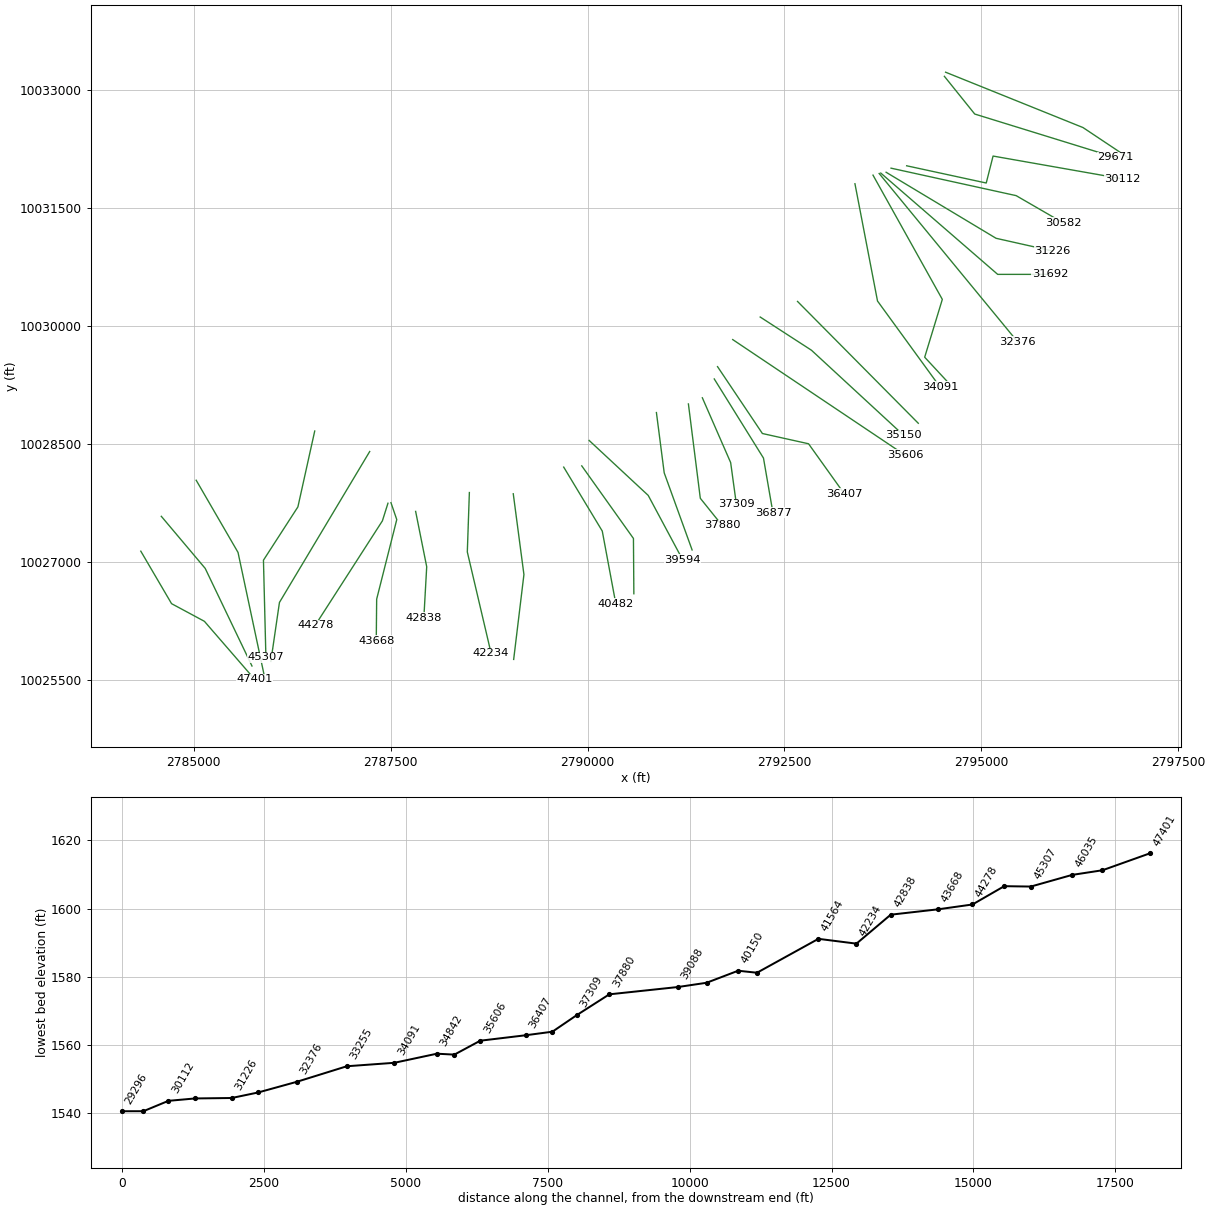
HEC-RAS study SOUTH GRAPE CREEK.prj: SOUTH GRAPE CREEK Base Level Engineering

--- SOUTH GRAPE CREEK.g01 (geometry) --- (continued)

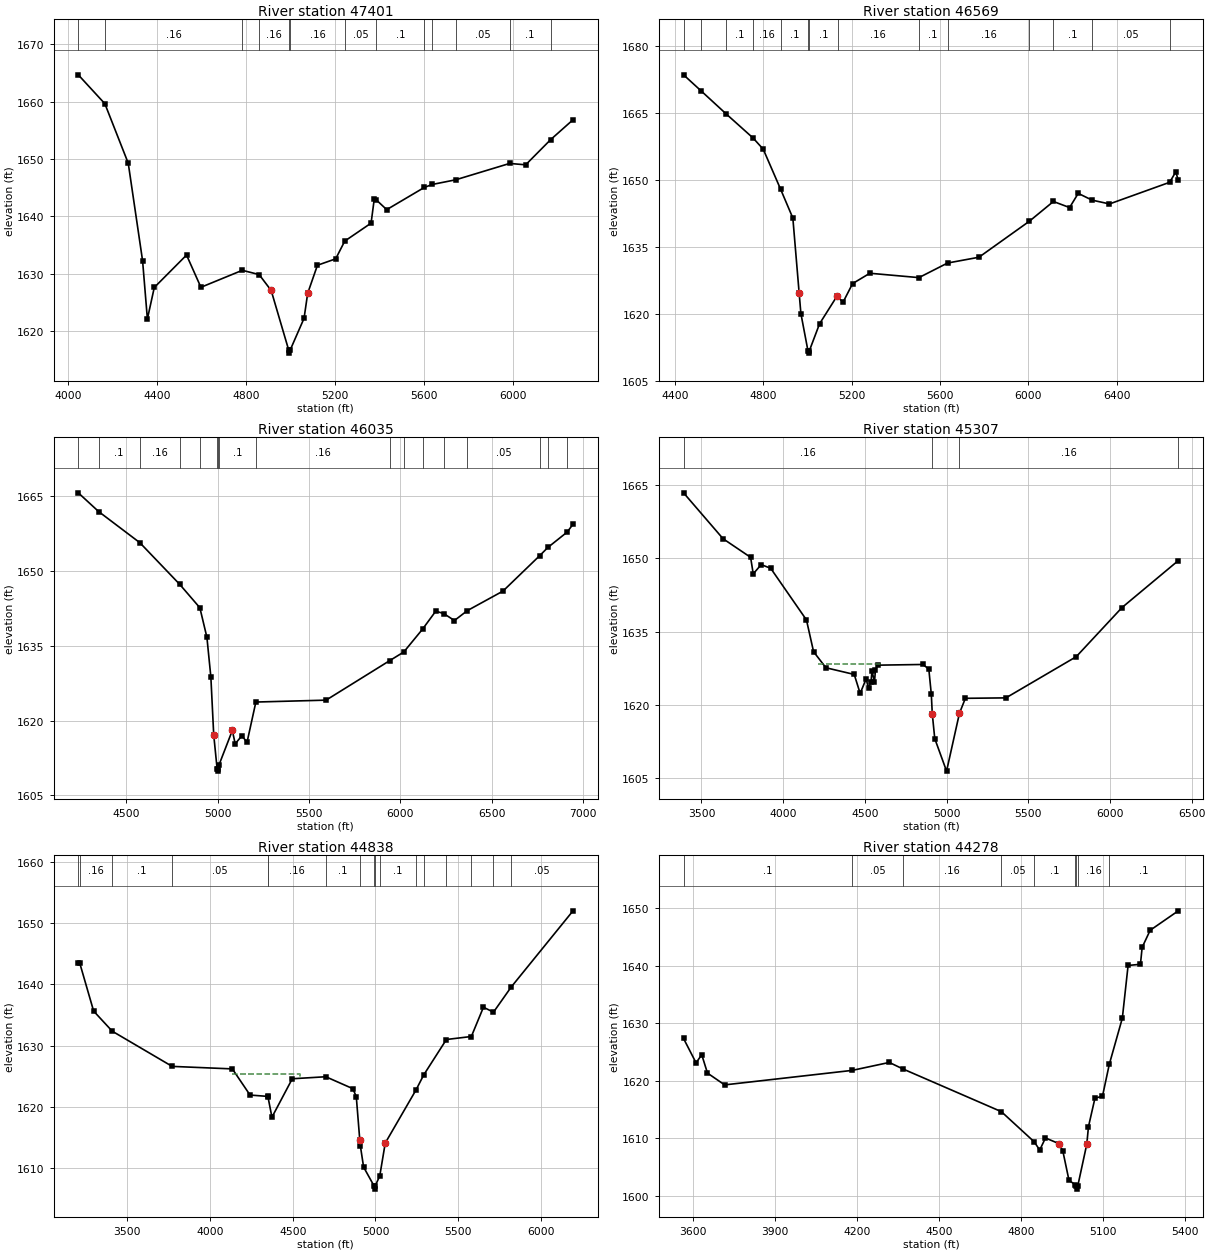
Type RM Length L Ch R = 1 ,47401   ,832,832,832
BEGIN DESCRIPTION:
SOUTH GRAPE CREEK 72.0
END DESCRIPTION:
XS GIS Cut Line= 4
      2784327.58     10027138.31      2784718.21     10026471.63
      2785134.87     10026247.67       2785774.2     10025509.59
#Sta/Elev= 30
  4045.4 1664.66  4164.9 1659.62  4269.9 1649.25  4334.3 1632.25  4355.8 1622.12
  4386.8 1627.61  4531.7 1633.26  4596.2 1627.64  4782.1  1630.6  4857.6 1629.86
  4911.8 1627.09  4990.8 1616.67  4993.5 1616.17  4996.8 1616.67  5059.5 1622.24
  5075.8 1626.59  5119.6 1631.48  5201.6  1632.6  5242.3 1635.69  5360.6 1638.82
  5374.9 1643.04  5384.7 1642.84  5430.8 1641.17  5599.7 1645.04  5635.6 1645.56
  5740.6 1646.37    5983 1649.22  6054.9 1648.98  6167.7 1653.39  6267.6 1656.83
#Mann= 13 ,-1 , 0
  4045.4      .1       0  4164.9     .16       0  4782.1      .1       0
  4857.6     .16       0  4990.8     .07       0  4996.8     .16       0
  5242.3     .05       0  5384.7      .1       0  5599.7     .05       0
  5635.6      .1       0  5740.6     .05       0    5983      .1       0
  6167.7     .05       0
Bank Sta=4911.8,5075.8
XS Rating Curve= 0 ,0
Exp/Cntr=0.3,0.1

Type RM Length L Ch R = 1 ,46569   ,534,534,534
BEGIN DESCRIPTION:
SOUTH GRAPE CREEK 71.0
END DESCRIPTION:
XS GIS Cut Line= 3
      2784588.02     10027580.98      2785145.29     10026919.55
      2785739.02       10025680.
#Sta/Elev= 30
  4438.8 1673.63  4519.8 1669.96  4629.8 1664.95    4754 1659.44  4799.5 1656.95
  4878.1 1647.98  4933.5 1641.52  4962.1 1624.66  4969.9 1620.11    5002 1611.73
  5004.7 1611.23    5008 1611.73  5054.4 1617.81  5132.5 1623.94  5136.5 1623.75
  5161.1 1622.68  5203.9 1626.82    5282 1629.14  5504.1 1628.16  5633.7 1631.43
  5775.8 1632.73    6004  1640.8  6112.8 1645.23  6186.1 1643.87  6225.2 1647.05
  6287.6 1645.54  6366.7 1644.68  6638.9 1649.53  6666.8 1651.87  6678.1 1649.97
#Mann= 14 ,-1 , 0
  4438.8      .1       0  4519.8     .16       0  4629.8      .1       0
    4754     .16       0  4878.1      .1       0    5002     .07       0
    5008      .1       0  5136.5     .16       0  5504.1      .1       0
  5633.7     .16       0    6004     .05       0  6112.8      .1       0
  6287.6     .05       0  6638.9      .1       0
Bank Sta=4962.1,5132.5
XS Rating Curve= 0 ,0
Exp/Cntr=0.3,0.1

Type RM Length L Ch R = 1 ,46035   ,728,728,728
BEGIN DESCRIPTION:
SOUTH GRAPE CREEK 70.0
END DESCRIPTION:
XS GIS Cut Line= 3
       2785030.7     10028039.35      2785561.96     10027122.67
      2785905.63     10025508.44
#Sta/Elev= 30
  4236.6 1665.66    4348 1661.91  4573.6 1655.67  4791.5 1647.34  4902.6 1642.62
  4941.2 1636.68  4962.8 1628.76  4978.5 1617.12    4997 1610.37  4999.8 1609.87
    5003 1610.37    5008 1611.17  5080.4 1618.02  5096.1 1615.34  5133.1 1616.99
  5160.7 1615.61  5209.3 1623.72    5594  1624.1  5941.9 1632.01  6019.5 1633.75
  6122.1 1638.32  6194.7 1641.94  6238.2 1641.46    6297 1640.06  6367.3 1642.04
  6562.8 1645.96  6763.6 1653.05  6808.8 1654.71  6914.1 1657.78  6946.5 1659.36
#Mann= 17 ,-1 , 0
  4236.6     .16       0    4348      .1       0  4573.6     .16       0
  4791.5      .1       0  4902.6     .16       0    4997     .07       0
    5003     .16       0    5008      .1       0  5209.3     .16       0
  5941.9      .1       0  6019.5     .16       0  6122.1     .05       0
  6238.2      .1       0  6367.3     .05       0  6763.6      .1       0
  6808.8     .05       0  6914.1      .1       0
Bank Sta=4978.5,5080.4
XS Rating Curve= 0 ,0
Exp/Cntr=0.3,0.1

Type RM Length L Ch R = 1 ,45307   ,469,469,469
BEGIN DESCRIPTION:
SOUTH GRAPE CREEK 69.0
END DESCRIPTION:
XS GIS Cut Line= 4
      2786535.92     10028664.38      2786322.37      10027700.8
      2785884.87     10027023.72      2785916.12      10025789.3
#Sta/Elev= 30
  3390.5 1663.36  3632.4 1653.97  3800.9 1650.17    3817 1646.79  3865.7 1648.68
  3923.8 1647.93  4142.7 1637.37  4186.3 1630.87  4261.8 1627.59  4435.1 1626.22
  4471.4 1622.34  4507.7  1625.3  4522.8 1623.42    4538 1624.76  4543.9 1626.98
  4559.1 1624.61  4565.1 1627.23  4580.2 1628.12  4855.3 1628.26  4891.6 1627.32
  4906.8 1622.18  4912.7 1618.21  4927.9 1613.11  5000.2 1606.45    5079 1618.28
  5115.3 1621.34  5363.6 1621.43  5793.8 1629.85  6073.9  1639.9  6418.4  1649.5
#Mann= 4 ,-1 , 0
  3390.5     .16       0  4912.7     .07       0    5079     .16       0
  6418.4     .05       0
#XS Ineff= 1 ,-1
 4214.32 4608.071628.299
Permanent Ineff=
       T
Bank Sta=4912.7,5079
XS Rating Curve= 0 ,0
Exp/Cntr=0.3,0.1

Type RM Length L Ch R = 1 ,44838   ,560,560,560
BEGIN DESCRIPTION:
SOUTH GRAPE CREEK 68.0
END DESCRIPTION:
XS GIS Cut Line= 3
      2787233.81     10028403.89        2786088.     10026487.26
      2785978.73       10025738.
#Sta/Elev= 30
  3203.9  1643.4  3212.1 1643.53  3296.7 1635.63    3409 1632.35  3771.4  1626.6
  4135.2 1626.19  4242.1 1621.92  4349.2  1621.7  4350.2 1621.66  4374.4  1618.3
  4497.3 1624.58  4699.9 1624.91  4862.7 1622.97  4884.1 1621.68  4905.5 1614.51
  4908.6 1613.67  4928.4 1610.16    4992 1607.06  4994.7 1606.56    4998 1607.06
  5026.1 1608.72  5059.2 1614.08  5245.5 1622.77  5291.4 1625.19  5428.8 1630.99
  5579.7 1631.48  5652.7 1636.26  5713.4 1635.45  5820.5 1639.56  6194.1    1652
#Mann= 17 ,-1 , 0
  3203.9     .05       0  3212.1     .16       0    3409      .1       0
  3771.4     .05       0  4349.2      .1       0  4350.2     .16       0
  4699.9      .1       0  4908.6     .16       0    4992     .07       0
    4998     .16       0  5026.1      .1       0  5245.5     .16       0
  5291.4      .1       0  5428.8     .16       0  5579.7     .05       0
  5713.4      .1       0  5820.5     .05       0
#XS Ineff= 1 ,-1
  4135.4 4541.081625.394
Permanent Ineff=
       T
Bank Sta=4905.5,5059.2
XS Rating Curve= 0 ,0
Exp/Cntr=0.3,0.1

Type RM Length L Ch R = 1 ,44278   ,610,610,610
BEGIN DESCRIPTION:
SOUTH GRAPE CREEK 67.0
END DESCRIPTION:
XS GIS Cut Line= 3
      2787465.73     10027747.24      2787395.29     10027523.72
      2786542.12     10026197.14
#Sta/Elev= 30
    3565 1627.36  3610.8 1623.13  3631.6 1624.54  3652.6 1621.35  3715.5  1619.3
  4182.6 1621.82  4318.4  1623.2  4367.8 1622.08  4728.7 1614.65    4849 1609.41
  4869.2 1607.98  4890.3 1610.08  4940.7 1609.07  4953.7 1607.84  4976.4 1602.72
  4999.9 1601.93  5002.3 1601.69    5005 1601.19  5008.3 1601.69  5041.6 1609.01
  5047.7 1612.04  5071.5    1617    5099 1617.32  5123.9 1622.86  5171.7 1630.89
  5192.8 1640.05    5238 1640.25  5244.3 1643.19  5273.6 1646.16  5376.6 1649.54
#Mann= 9 ,-1 , 0
    3565      .1       0  4182.6     .05       0  4367.8     .16       0
  4728.7     .05       0    4849      .1       0  4999.9     .16       0
  5002.3     .07       0  5008.3     .16       0  5123.9      .1       0
Bank Sta=4940.7,5041.6
XS Rating Curve= 0 ,0
Exp/Cntr=0.3,0.1

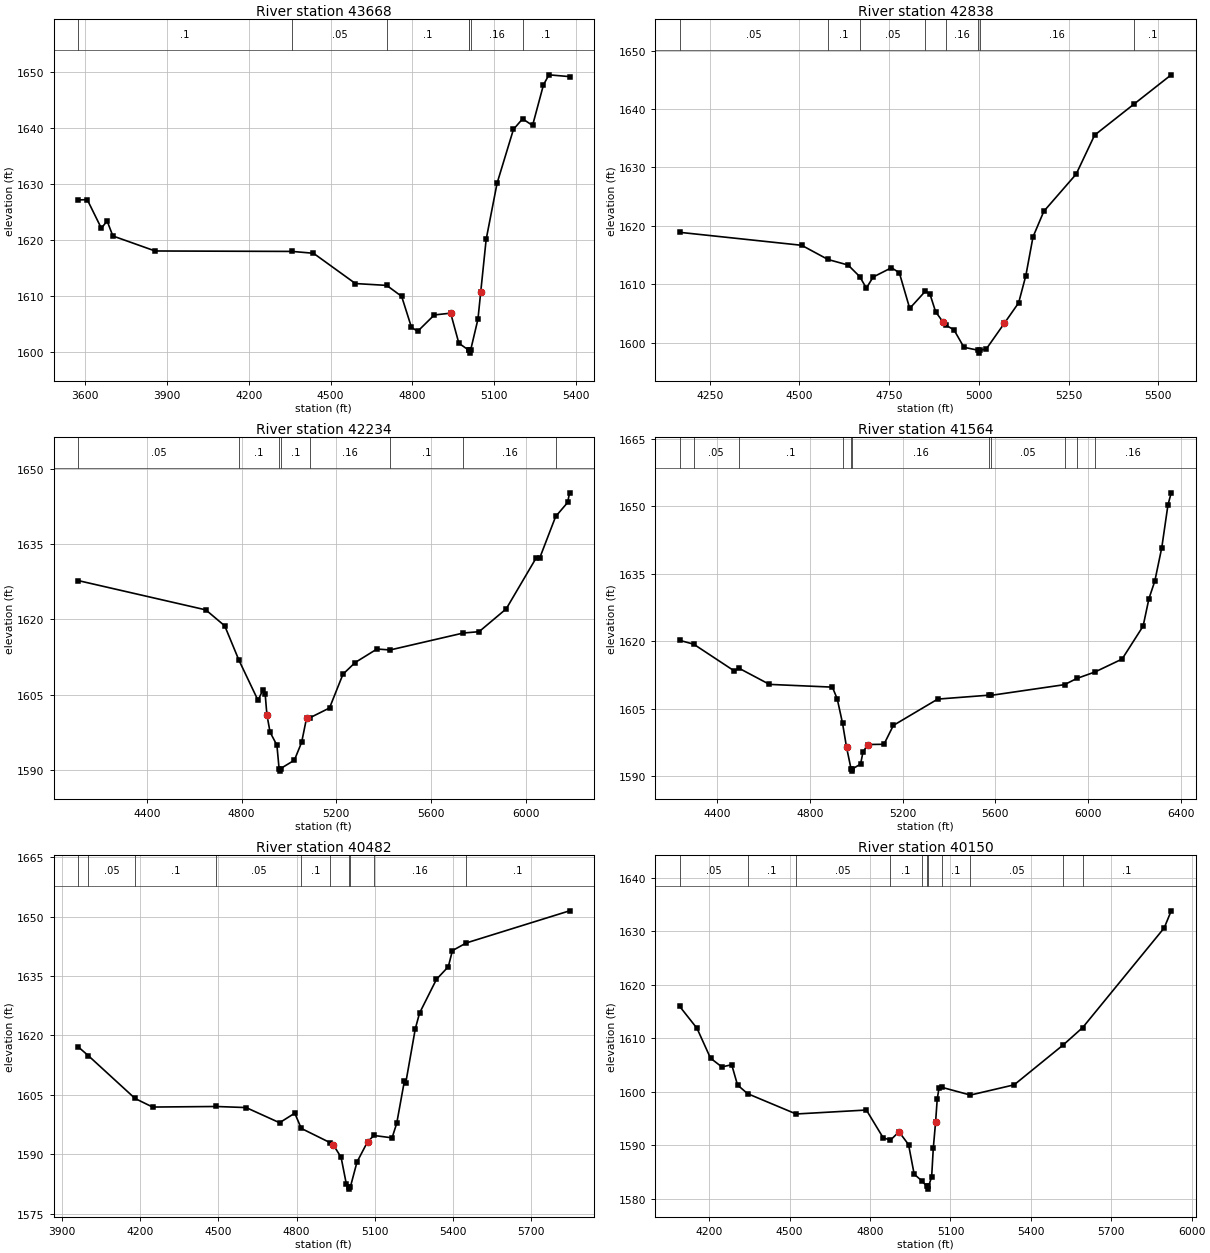
Type RM Length L Ch R = 1 ,43668   ,830,830,830
BEGIN DESCRIPTION:
SOUTH GRAPE CREEK 66.0
END DESCRIPTION:
XS GIS Cut Line= 4
      2787503.95     10027754.19      2787577.58     10027539.34
      2787322.37     10026528.92      2787317.17     10025998.22
#Sta/Elev= 30
  3575.3 1627.13  3608.7  1627.2  3660.4 1622.08  3681.5 1623.38  3702.6  1620.7
  3857.3 1618.02  4359.5 1617.94  4437.4 1617.61    4591  1612.2  4705.6 1611.87
  4760.3 1609.91  4796.2 1604.38    4819 1603.67  4879.8 1606.59  4939.8 1606.91
  4969.8 1601.54  5006.5 1600.28  5006.8 1600.27  5009.5 1599.77  5012.8 1600.27
  5039.8 1605.85  5049.8 1610.63  5069.8 1620.08  5109.8 1630.12  5169.8 1639.75
  5203.3 1641.63  5239.8 1640.44  5279.8 1647.71  5299.8 1649.49  5375.3 1649.17
#Mann= 7 ,-1 , 0
  3575.3      .1       0  4359.5     .05       0  4705.6      .1       0
  5006.5     .16       0  5006.8     .07       0  5012.8     .16       0
  5203.3      .1       0
Bank Sta=4939.8,5049.8
XS Rating Curve= 0 ,0
Exp/Cntr=0.3,0.1

Type RM Length L Ch R = 1 ,42838   ,604,604,604
BEGIN DESCRIPTION:
SOUTH GRAPE CREEK 65.0
END DESCRIPTION:
XS GIS Cut Line= 3
      2787817.17      10027643.5      2787957.79     10026940.38
      2787921.33     10026289.34
#Sta/Elev= 30
  4166.6 1618.89  4506.3 1616.67  4579.5 1614.24  4635.5 1613.29  4667.8 1611.32
  4686.5 1609.33  4705.2 1611.23  4756.2 1612.82  4778.2 1611.98  4807.2 1605.86
  4850.9 1608.81  4863.3 1608.37  4879.4 1605.28  4900.3  1603.5  4907.2    1603
  4930.4  1602.2  4958.2  1599.2  4997.5  1598.7  5000.2  1598.2  5003.5  1598.7
  5020.5 1598.91  5070.6 1603.29  5110.6 1606.81  5130.7 1611.47  5150.7 1618.11
  5180.8 1622.49  5270.9 1628.86  5322.3 1635.54  5431.7 1640.84  5535.7 1645.87
#Mann= 8 ,-1 , 0
  4166.6     .05       0  4579.5      .1       0  4667.8     .05       0
  4850.9      .1       0  4907.2     .16       0  4997.5     .07       0
  5003.5     .16       0  5431.7      .1       0
Bank Sta=4900.3,5070.6
XS Rating Curve= 0 ,0
Exp/Cntr=0.3,0.1

Type RM Length L Ch R = 1 ,42234   ,670,670,670
BEGIN DESCRIPTION:
SOUTH GRAPE CREEK 64.0
END DESCRIPTION:
XS GIS Cut Line= 3
      2788499.46     10027883.09      2788473.41     10027127.88
       2788775.5     10025841.43
#Sta/Elev= 30
  4109.1 1627.74  4648.8 1621.89  4728.8  1618.7  4788.7 1611.86  4869.6 1603.83
  4889.6 1605.89  4899.8 1605.06  4906.9    1601  4920.4 1597.48  4949.3 1594.89
  4958.5 1590.21  4961.2 1589.71  4964.5 1590.21  5023.1 1591.89  5053.9 1595.47
  5074.5 1600.27  5089.2 1600.37  5171.6 1602.31  5228.5 1609.05  5279.9 1611.38
  5372.3 1614.08  5427.8 1613.89    5737 1617.27  5803.8 1617.54  5918.4 1622.09
  6045.6  1632.3  6060.6 1632.31  6127.5 1640.53    6178 1643.32  6186.2 1645.25
#Mann= 8 ,-1 , 0
  4109.1     .05       0  4788.7      .1       0  4958.5     .07       0
  4964.5      .1       0  5089.2     .16       0  5427.8      .1       0
    5737     .16       0  6127.5      .1       0
Bank Sta=4906.9,5074.5
XS Rating Curve= 0 ,0
Exp/Cntr=0.3,0.1

Type RM Length L Ch R = 1 ,41564   ,1082,1082,1082
BEGIN DESCRIPTION:
SOUTH GRAPE CREEK 63.0
END DESCRIPTION:
XS GIS Cut Line= 3
      2789056.75     10027867.47      2789192.16     10026841.42
      2789061.96      10025763.3
#Sta/Elev= 30
  4238.3 1620.18  4298.3 1619.34  4474.1 1613.37  4492.8 1614.02  4625.4  1610.4
  4896.9 1609.79  4917.9 1607.18  4940.8 1601.75  4958.2 1596.38  4977.5 1591.62
  4980.2 1591.12  4983.5 1591.62  5018.7 1592.69  5028.8 1595.31  5048.9 1597.03
  5119.6 1597.09    5160 1601.28  5351.5 1607.13  5572.2    1608  5582.8 1607.97
  5898.7 1610.34  5951.4 1611.71  6030.3 1613.16  6147.2 1616.03  6237.9 1623.35
  6263.1 1629.46  6288.3 1633.34  6318.5 1640.81  6345.1 1650.27  6359.2 1652.98
#Mann= 11 ,-1 , 0
  4238.3      .1       0  4298.3     .05       0  4492.8      .1       0
  4940.8     .16       0  4977.5     .07       0  4983.5     .16       0
  5572.2      .1       0  5582.8     .05       0  5898.7      .1       0
  5951.4     .05       0  6030.3     .16       0
Bank Sta=4958.2,5048.9
XS Rating Curve= 0 ,0
Exp/Cntr=0.3,0.1

Type RM Length L Ch R = 1 ,40482   ,332,332,332
BEGIN DESCRIPTION:
SOUTH GRAPE CREEK 62.0
END DESCRIPTION:
XS GIS Cut Line= 3
      2789697.37     10028206.01      2790186.96     10027393.51
      2790358.84      10026471.6
#Sta/Elev= 30
  3961.6 1617.13  4000.8 1614.89  4180.3 1604.07  4247.5 1601.91  4491.6 1602.05
  4606.4 1601.78  4734.9 1597.95  4793.2 1600.36  4818.1 1596.52  4927.8 1592.95
  4940.5 1592.42    4971 1589.23  4991.4 1582.39  5000.5 1581.68  5003.2 1581.18
  5006.5 1581.68    5032 1588.02  5072.7 1593.14  5097.3 1594.73  5166.7 1594.13
  5184.6 1597.81  5214.3 1608.61  5219.4 1608.07  5255.8 1621.65  5272.1 1625.63
  5337.2 1634.18  5382.6 1637.36  5398.3 1641.42  5451.6 1643.36    5848 1651.47
#Mann= 10 ,-1 , 0
  3961.6      .1       0  4000.8     .05       0  4180.3      .1       0
  4491.6     .05       0  4818.1      .1       0  4927.8     .05       0
  5000.5    .035       0  5006.5     .05       0  5097.3     .16       0
  5451.6      .1       0
Bank Sta=4940.5,5072.7
XS Rating Curve= 0 ,0
Exp/Cntr=0.3,0.1

Type RM Length L Ch R = 1 ,40150   ,556,556,556
BEGIN DESCRIPTION:
SOUTH GRAPE CREEK 61.0
END DESCRIPTION:
XS GIS Cut Line= 3
      2789926.55     10028221.62      2790582.79     10027299.76
      2790587.99     10026597.66
#Sta/Elev= 30
    4090 1615.92  4154.3 1611.84  4204.7 1606.26    4247 1604.62  4283.8 1605.03
  4305.5 1601.24  4343.1 1599.62  4524.2 1595.82  4786.3 1596.56    4849 1591.37
    4876 1590.93    4908 1592.49  4943.7 1590.09  4964.6 1584.57  4993.2 1583.32
    5012 1582.27  5014.7 1581.77    5018 1582.27  5029.8 1584.04  5035.9 1589.38
  5044.5 1594.29  5050.7 1598.65  5057.1  1600.6  5067.6 1600.81  5174.3 1599.36
  5337.6 1601.27  5521.6 1608.77  5593.5 1611.99  5897.6 1630.62  5923.7 1633.81
#Mann= 11 ,-1 , 0
    4090     .05       0  4343.1      .1       0  4524.2     .05       0
    4876      .1       0  4993.2     .16       0    5012     .07       0
    5018     .16       0  5067.6      .1       0  5174.3     .05       0
  5521.6     .16       0  5593.5      .1       0
Bank Sta=4908,5044.5
XS Rating Curve= 0 ,0
Exp/Cntr=0.3,0.1

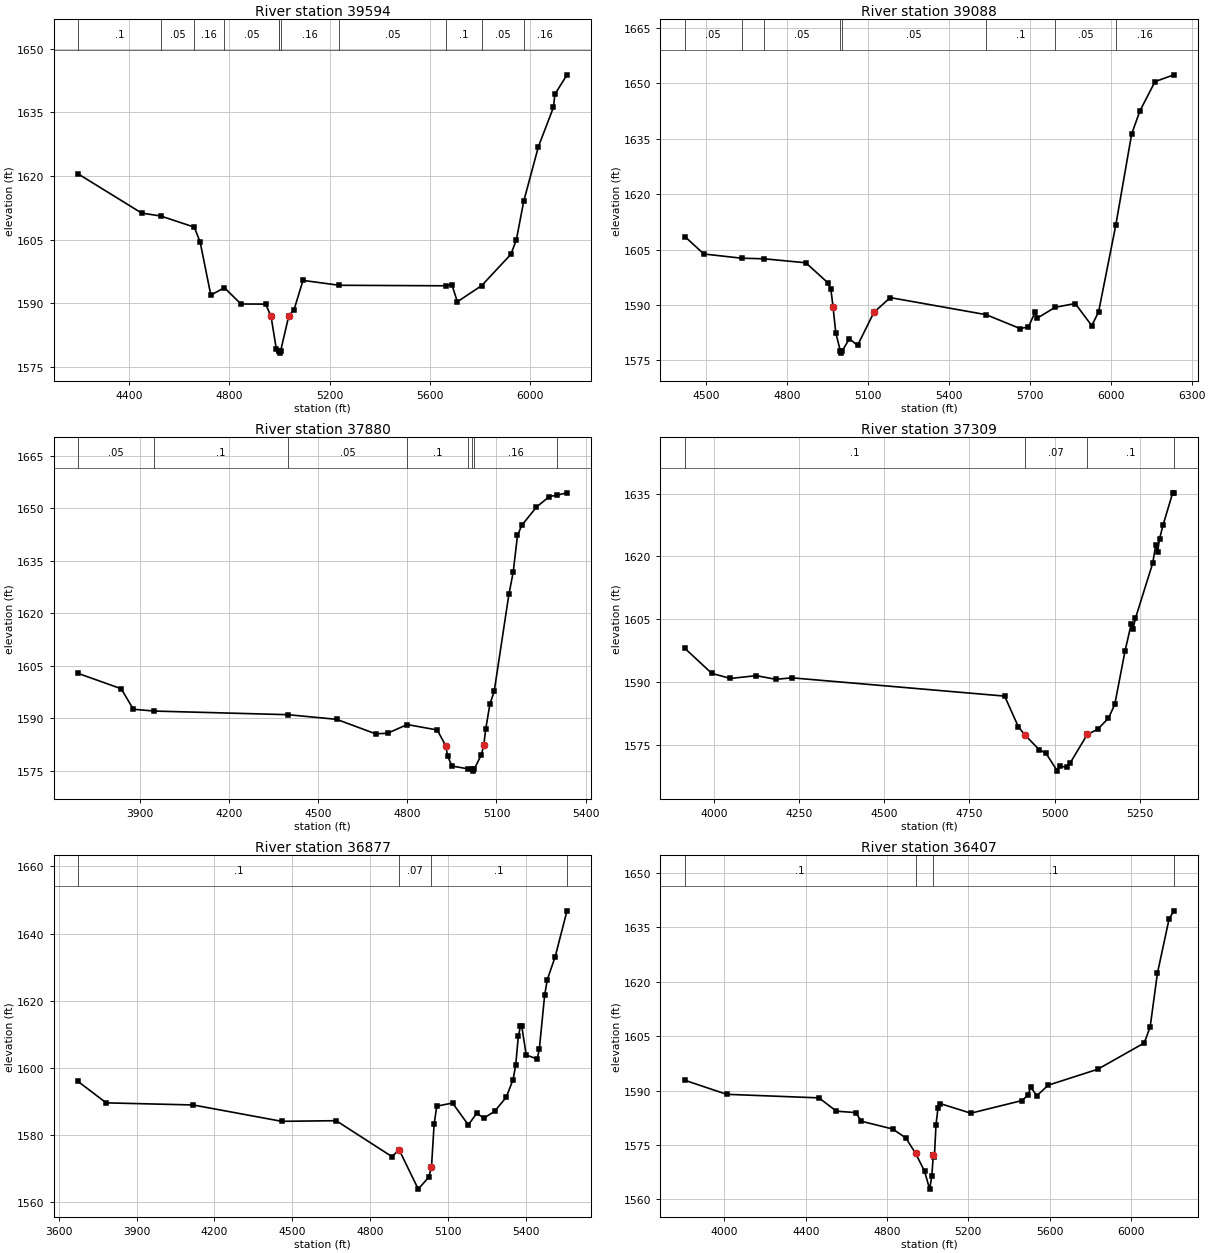
Type RM Length L Ch R = 1 ,39594   ,506,506,506
BEGIN DESCRIPTION:
SOUTH GRAPE CREEK 60.0
END DESCRIPTION:
XS GIS Cut Line= 3
      2790020.27     10028544.56      2790770.29     10027846.63
      2791207.79     10027028.93
#Sta/Elev= 30
  4195.3  1620.5  4449.5 1611.25  4525.3 1610.56  4659.5 1607.93    4683 1604.38
  4725.5 1591.91  4779.7 1593.66  4845.7 1589.82  4944.4 1589.79  4965.9  1586.9
  4986.9  1579.2    4998 1578.75  4998.1 1578.74  5000.8 1578.24  5004.1 1578.74
  5036.7 1587.02  5057.7 1588.48  5093.4 1595.38  5238.4 1594.23    5663 1594.11
  5687.7 1594.37  5709.6 1590.35  5806.5 1594.15  5923.3 1601.53  5945.3    1605
  5974.5 1614.03    6033 1626.88  6093.2 1636.18  6098.9 1639.24  6147.2 1643.83
#Mann= 11 ,-1 , 0
  4195.3      .1       0  4525.3     .05       0  4659.5     .16       0
  4779.7     .05       0    4998     .16       0  4998.1     .07       0
  5004.1     .16       0  5238.4     .05       0    5663      .1       0
  5806.5     .05       0  5974.5     .16       0
Bank Sta=4965.9,5036.7
XS Rating Curve= 0 ,0
Exp/Cntr=0.3,0.1

Type RM Length L Ch R = 1 ,39088   ,1208,1208,1208
BEGIN DESCRIPTION:
SOUTH GRAPE CREEK 59.0
END DESCRIPTION:
XS GIS Cut Line= 3
      2790874.46     10028898.71      2790973.41     10028133.09
      2791327.57     10027153.96
#Sta/Elev= 30
  4420.8 1608.54  4491.2 1603.82  4631.1 1602.68  4714.8 1602.52  4869.5 1601.44
  4950.1 1596.09  4962.2 1594.36  4970.3 1589.46  4980.4 1582.51  4997.6 1577.49
  5000.3 1576.99  5003.6 1577.49  5030.8 1580.89  5061.1 1579.07  5121.6 1587.99
  5182.1 1592.02  5537.9  1587.4  5664.3 1583.63    5695  1584.1  5720.3 1588.21
  5725.6 1586.38  5794.1  1589.4  5868.3 1590.41  5929.6 1584.42  5954.9 1588.14
  6018.6 1611.59  6077.5 1636.29  6108.2 1642.54  6164.1 1650.47    6234 1652.31
#Mann= 8 ,-1 , 0
  4420.8     .05       0  4631.1      .1       0  4714.8     .05       0
  4997.6     .04       0  5003.6     .05       0  5537.9      .1       0
  5794.1     .05       0  6018.6     .16       0
Bank Sta=4970.3,5121.6
XS Rating Curve= 0 ,0
Exp/Cntr=0.3,0.1

Type RM Length L Ch R = 1 ,37880   ,571,571,571
BEGIN DESCRIPTION:
SOUTH GRAPE CREEK 58.0
END DESCRIPTION:
XS GIS Cut Line= 3
      2791280.71     10029008.07      2791431.75     10027810.17
      2791706.88     10027467.55
#Sta/Elev= 30
  3690.6 1602.81  3836.1 1598.41    3877 1592.54  3946.7 1592.03  4397.4 1590.99
  4561.8 1589.66  4692.8 1585.52  4733.1 1585.68  4799.5 1588.17  4900.3 1586.62
  4929.1 1582.11  4935.5 1579.12  4949.9 1576.31  5003.6 1575.51  5018.7 1575.35
  5021.4 1574.85  5024.7 1575.35  5049.1 1579.56  5057.1 1582.23  5063.5  1586.8
  5077.9 1594.04  5092.3 1597.68  5141.9 1625.48  5156.3 1631.77  5170.7 1642.25
  5185.1 1645.14  5234.7 1650.38  5277.9 1653.37  5302.5 1653.76  5337.4 1654.44
#Mann= 8 ,-1 , 0
  3690.6     .05       0  3946.7      .1       0  4397.4     .05       0
  4799.5      .1       0  5003.6     .16       0  5018.7     .07       0
  5024.7     .16       0  5302.5      .1       0
Bank Sta=4929.1,5057.1
XS Rating Curve= 0 ,0
Exp/Cntr=0.3,0.1

Type RM Length L Ch R = 1 ,37309   ,432,432,432
BEGIN DESCRIPTION:
SOUTH GRAPE CREEK 57.0
END DESCRIPTION:
XS GIS Cut Line= 3
      2791457.77     10029086.26      2791817.16      10028263.3
      2791890.07     10027732.09
#Sta/Elev= 30
  3915.2 1598.07  3994.3  1592.1  4048.9 1590.89  4124.6 1591.56  4182.3 1590.68
  4229.1 1591.04  4853.1 1586.68  4893.5 1579.33  4913.7 1577.32  4954.1 1573.93
  4974.3 1573.04  5007.9 1568.78  5014.6 1569.99  5034.8 1569.71  5044.9 1570.66
  5095.4 1577.52  5125.7 1578.75  5157.4 1581.38  5176.1 1584.69  5206.4 1597.51
  5224.4  1603.9  5229.5 1602.65  5236.7 1605.23  5287.2 1618.35  5296.5 1622.77
  5301.6 1620.98  5307.4 1624.19  5317.5 1627.42  5346.1 1635.18  5349.4 1635.18
#Mann= 4 ,-1 , 0
  3915.2      .1       0  4913.7     .07       0  5095.4      .1       0
  5349.4     .16       0
Bank Sta=4913.7,5095.4
XS Rating Curve= 0 ,0
Exp/Cntr=0.3,0.1

Type RM Length L Ch R = 1 ,36877   ,470,470,470
BEGIN DESCRIPTION:
SOUTH GRAPE CREEK 56.0
END DESCRIPTION:
XS GIS Cut Line= 3
      2791608.81     10029325.83      2792233.83     10028320.59
      2792353.47     10027628.76
#Sta/Elev= 30
  3673.6 1595.96  3782.5 1589.58  4117.8 1588.95    4459 1584.08  4669.2 1584.27
  4884.6 1573.56  4911.9 1575.63  4985.8 1563.89  5026.4 1567.47  5036.8 1570.42
  5046.9 1583.14  5057.1  1588.6    5118 1589.53  5178.9 1583.01  5210.8 1586.42
  5239.8 1585.09  5280.4 1587.06  5325.3 1591.28  5351.4 1596.51  5361.5 1600.71
  5371.7 1609.38    5380 1612.44  5385.1 1612.32  5402.1 1603.84  5444.9 1602.63
  5452.9 1605.75  5473.2 1621.58  5483.3 1626.24  5513.8 1633.08  5559.4 1646.76
#Mann= 4 ,-1 , 0
  3673.6      .1       0  4911.9     .07       0  5036.8      .1       0
  5559.4     .16       0
Bank Sta=4911.9,5036.8
XS Rating Curve= 0 ,0
Exp/Cntr=0.3,0.1

Type RM Length L Ch R = 1 ,36407   ,801,801,801
BEGIN DESCRIPTION:
Mapping XS bf49d6e4
END DESCRIPTION:
XS GIS Cut Line= 4
       2791650.5     10029482.05      2792220.13     10028632.73
      2792806.07     10028502.52      2793261.77     10027864.54
#Sta/Elev= 30
  3804.9 1592.82  4010.6 1588.96  4465.1 1587.98  4550.9 1584.31  4645.7 1583.93
  4673.9 1581.54  4827.6 1579.41  4892.3 1576.96  4940.9 1572.68  4984.5  1567.8
    5010 1562.85  5020.5 1566.51    5028 1572.28  5028.4 1572.23  5033.1 1571.65
    5041 1580.54  5051.2 1585.31  5061.5 1586.41  5212.4 1583.76  5463.5 1587.23
    5493 1588.67  5507.8 1590.94  5536.9 1588.56  5593.8 1591.48  5837.1 1595.86
  6065.7 1603.09  6095.2 1607.51  6130.8 1622.27  6188.2 1637.21  6211.8 1639.49
#Mann= 4 ,-1 , 0
  3804.9      .1       0  4940.9     .07       0  5028.4      .1       0
  6211.8      .1       0
Bank Sta=4940.9,5028
XS Rating Curve= 0 ,0
Exp/Cntr=0.3,0.1

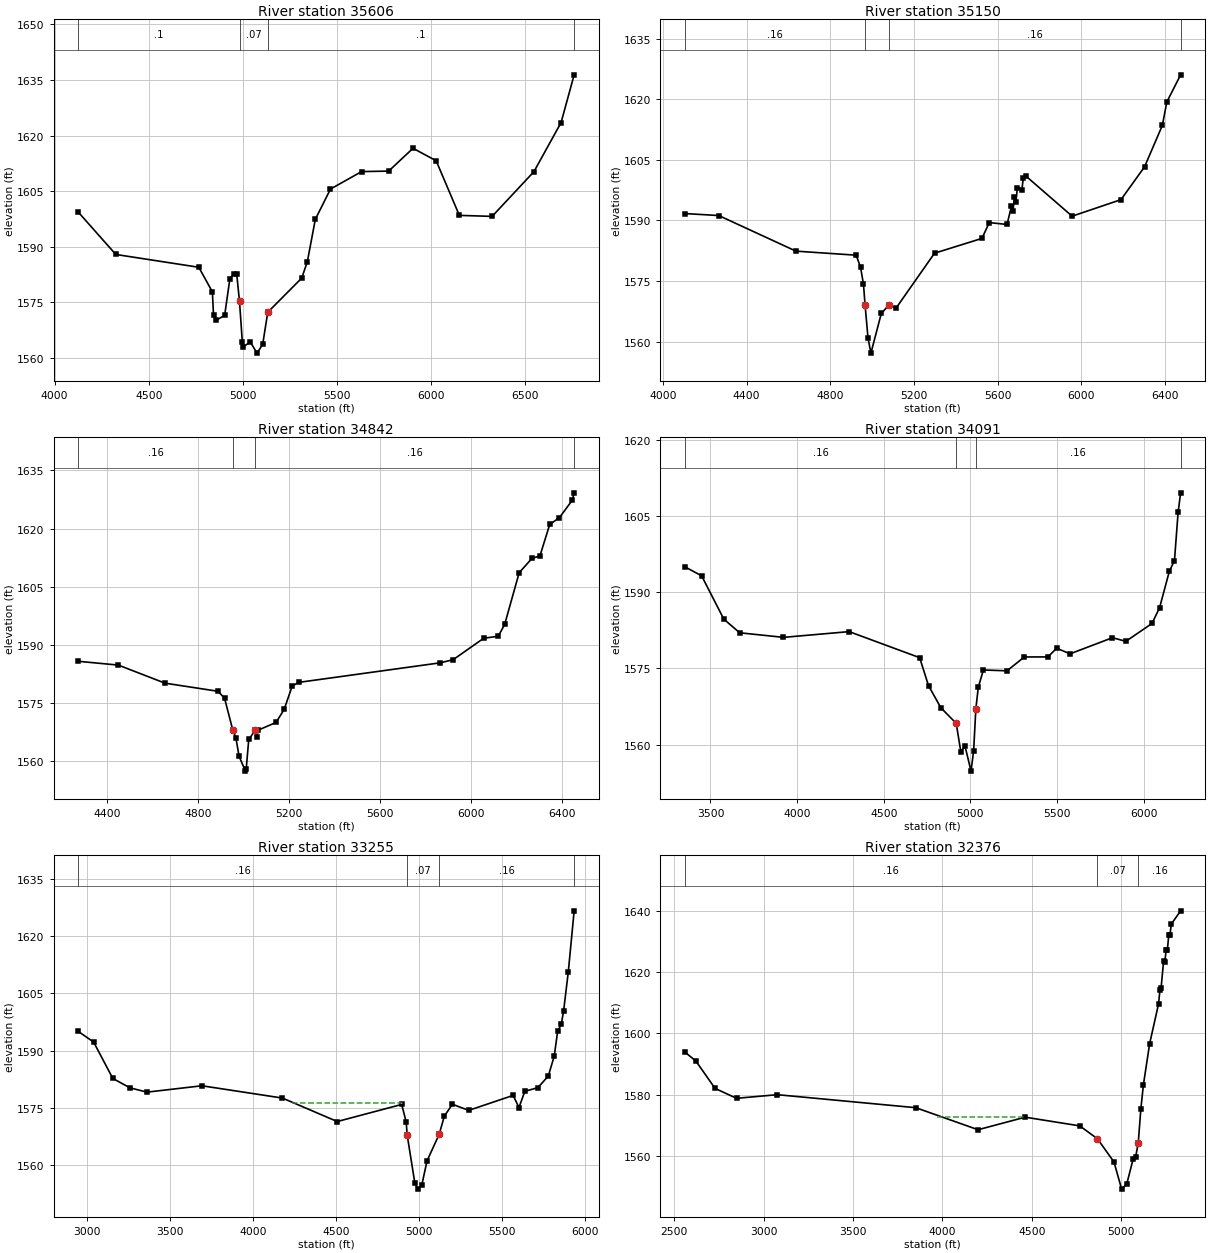
Type RM Length L Ch R = 1 ,35606   ,456,456,456
BEGIN DESCRIPTION:
SOUTH GRAPE CREEK 55.0
END DESCRIPTION:
XS GIS Cut Line= 2
      2791843.17     10029825.82      2794030.06     10028359.27
#Sta/Elev= 30
  4125.9 1599.31  4324.9 1587.89  4765.7 1584.43  4837.7  1577.8  4843.8 1571.59
  4858.8 1570.16  4902.9 1571.44  4930.8 1581.36  4951.8 1582.57  4966.8  1582.7
  4981.8 1575.22  4996.8 1564.23  5002.8 1562.95  5038.8 1564.31  5074.6 1561.25
  5104.8 1563.58  5131.9 1572.29  5312.2 1581.51    5342 1585.92  5384.5 1597.38
    5465 1605.55  5630.1 1610.26  5774.1  1610.4  5903.2 1616.56  6026.2 1613.19
  6149.3 1598.44  6323.3 1598.17  6545.4 1610.25  6689.5  1623.5    6759 1636.39
#Mann= 4 ,-1 , 0
  4125.9      .1       0  4981.8     .07       0  5131.9      .1       0
    6759     .16       0
Bank Sta=4981.8,5131.9
XS Rating Curve= 0 ,0
Exp/Cntr=0.3,0.1

Type RM Length L Ch R = 1 ,35150   ,308,308,308
BEGIN DESCRIPTION:
SOUTH GRAPE CREEK 54.0
END DESCRIPTION:
XS GIS Cut Line= 3
      2792192.17     10030112.25      2792843.21     10029690.38
      2794015.88     10028607.73
#Sta/Elev= 30
    4104  1591.7  4266.4 1591.21  4635.8  1582.4  4923.7  1581.4  4944.7 1578.43
  4958.8 1574.17  4966.2 1569.16  4980.4 1560.91  4994.3 1557.17  5043.9 1566.98
  5079.1 1568.99  5114.8 1568.32  5298.5 1581.89  5525.3 1585.55  5560.5 1589.46
  5645.5    1589  5666.5 1593.51  5673.9  1592.3  5680.7  1595.7  5688.1 1594.66
  5694.9 1598.12  5716.4 1597.59  5723.2 1600.45  5737.4  1600.9  5956.8 1591.05
  6190.5 1595.14  6303.3 1603.26  6388.4 1613.52  6409.9 1619.32  6475.8 1626.02
#Mann= 4 ,-1 , 0
    4104     .16       0  4966.2     .07       0  5079.1     .16       0
  6475.8      .1       0
Bank Sta=4966.2,5079.1
XS Rating Curve= 0 ,0
Exp/Cntr=0.3,0.1

Type RM Length L Ch R = 1 ,34842   ,751,751,751
BEGIN DESCRIPTION:
SOUTH GRAPE CREEK 53.0
END DESCRIPTION:
XS GIS Cut Line= 2
      2792666.15     10030310.14      2794199.33     10028762.91
#Sta/Elev= 30
  4275.4 1585.77  4451.3 1584.79  4656.3 1580.13  4889.7 1578.03  4917.9 1576.22
  4953.3 1568.17  4967.5 1566.03  4981.6 1561.26  5009.6 1557.44  5012.9 1557.94
    5024 1565.61  5052.3 1567.94  5059.4 1566.37  5066.5 1568.04  5144.2    1570
  5179.6 1573.37  5214.9 1579.39  5243.2 1580.33  5865.5 1585.38  5922.1 1586.19
  6056.4 1591.72  6120.1 1592.23  6148.3 1595.27    6212 1608.62  6268.6 1612.34
  6303.2 1612.94  6346.3 1621.08  6388.8 1622.82  6445.3 1627.32  6453.6 1629.23
#Mann= 4 ,-1 , 0
  4275.4     .16       0  4953.3     .07       0  5052.3     .16       0
  6453.6      .1       0
Bank Sta=4953.3,5052.3
XS Rating Curve= 0 ,0
Exp/Cntr=0.3,0.1

Type RM Length L Ch R = 1 ,34091   ,836,836,836
BEGIN DESCRIPTION:
SOUTH GRAPE CREEK 52.0
END DESCRIPTION:
XS GIS Cut Line= 3
      2793395.29     10031804.97      2793681.75     10030315.38
      2794472.73     10029227.78
#Sta/Elev= 30
  3352.1 1595.01  3449.2 1593.23  3577.4 1584.69    3669 1582.01  3921.7 1581.11
  4300.6 1582.24  4707.7 1577.11  4758.7  1571.6  4830.1 1567.24  4918.6 1564.18
  4945.7 1558.49  4968.8 1559.78  5004.1 1554.77  5019.1 1558.75  5031.8 1567.01
  5046.1  1571.3  5075.5 1574.69  5211.5 1574.52    5312 1577.25    5448 1577.26
  5498.2 1578.97  5575.8 1577.87  5820.5 1581.04  5897.8 1580.33  6048.5 1583.84
  6092.5 1586.96  6148.9 1594.15  6178.3 1596.23  6199.2  1605.7  6213.8 1609.57
#Mann= 4 ,-1 , 0
  3352.1     .16       0  4918.6     .07       0  5031.8     .16       0
  6213.8     .16       0
Bank Sta=4918.6,5031.8
XS Rating Curve= 0 ,0
Exp/Cntr=0.3,0.1

Type RM Length L Ch R = 1 ,33255   ,879,879,879
BEGIN DESCRIPTION:
SOUTH GRAPE CREEK 51.0
END DESCRIPTION:
XS GIS Cut Line= 4
      2793624.43     10031914.38      2794504.66     10030336.22
      2794280.71     10029601.84      2794562.77     10029297.99
#Sta/Elev= 30
  2947.9 1595.06  3040.2 1592.27  3155.8 1582.75  3258.7  1580.3  3361.5 1579.16
  3692.9 1580.83  4178.6 1577.61  4508.9 1571.46  4897.4 1575.94  4924.8  1571.3
  4930.3 1567.99  4977.1 1555.25  4995.6 1553.76  5018.9 1554.87  5050.3 1561.17
  5123.5 1568.12  5154.8 1572.89  5203.3 1575.99  5301.2 1574.38  5569.4 1578.31
  5604.5 1575.13  5640.2 1579.39  5717.9 1580.32  5781.4 1583.36  5817.1  1588.6
  5838.1 1595.18  5859.6 1596.92  5873.8 1600.46  5902.1 1610.72  5937.3 1626.65
#Mann= 4 ,-1 , 0
  2947.9     .16       0  4930.3     .07       0  5123.5     .16       0
  5937.3     .16       0
#XS Ineff= 1 ,-1
 4237.21 4896.97 1576.23
Permanent Ineff=
       T
Bank Sta=4930.3,5123.5
XS Rating Curve= 0 ,0
Exp/Cntr=0.3,0.1

Type RM Length L Ch R = 1 ,32376   ,684,684,684
BEGIN DESCRIPTION:
SOUTH GRAPE CREEK 50.0
END DESCRIPTION:
XS GIS Cut Line= 2
      2793702.59     10031935.16      2795462.99     10029794.56
#Sta/Elev= 30
  2559.7 1593.91  2621.9 1590.94  2728.8 1582.04  2848.7 1578.81  3076.8 1579.99
  3850.9 1575.75  4198.9 1568.57  4462.2 1572.66  4767.1 1569.83  4866.2 1565.62
  4958.7 1558.06  5001.5 1549.21  5030.4 1550.95  5065.6 1558.98  5079.9 1559.77
  5094.3 1564.23  5108.6 1575.18    5123 1583.15  5158.1 1596.65  5207.6 1609.53
  5215.5 1613.99    5222 1614.75  5236.3  1623.7  5242.8  1623.3  5250.7 1627.29
  5257.1 1627.13    5265 1632.12  5271.5 1632.15  5279.4 1635.62  5331.2 1639.92
#Mann= 3 ,-1 , 0
  2559.7     .16       0  4866.2     .07       0  5094.3     .16       0
#XS Ineff= 1 ,-1
 3967.19 4459.38 1572.79
Permanent Ineff=
       T
Bank Sta=4866.2,5094.3
XS Rating Curve= 0 ,0
Exp/Cntr=0.3,0.1

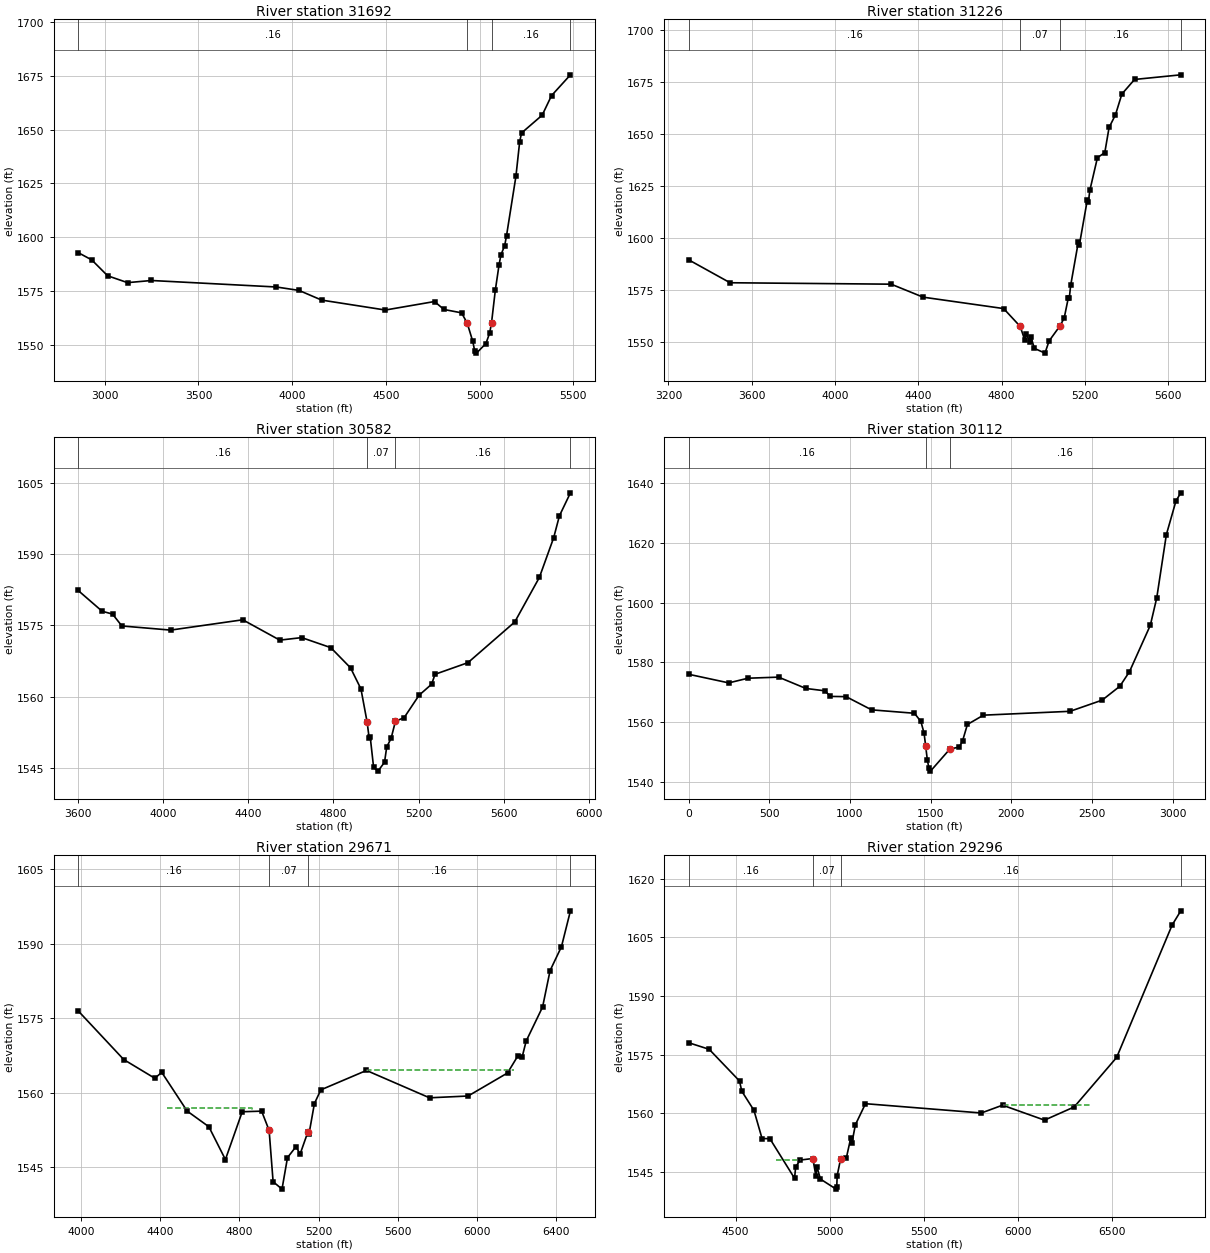
Type RM Length L Ch R = 1 ,31692   ,466,466,466
BEGIN DESCRIPTION:
SOUTH GRAPE CREEK 49.0
END DESCRIPTION:
XS GIS Cut Line= 3
      2793723.39      10031940.4      2795207.79     10030653.92
       2795869.3     10030653.92
#Sta/Elev= 30
  2858.2 1592.81  2930.8 1589.41  3015.3 1582.04  3121.6 1578.84  3248.9 1579.84
  3915.6 1576.82  4036.2 1575.23  4156.9 1570.73  4496.8 1566.11    4759 1570.06
  4809.3 1566.37  4903.2  1564.8  4933.2 1560.06  4963.2 1551.49  4973.2 1547.16
  4982.9 1546.07  5033.2 1550.54  5053.2 1555.42  5063.2 1560.21  5083.2 1575.24
  5103.2 1587.09  5113.2 1591.74  5133.2 1596.03  5143.2 1600.73  5193.2 1628.25
  5213.2 1644.33  5223.2 1648.43  5333.2  1656.7  5383.2 1665.81    5484 1675.47
#Mann= 4 ,-1 , 0
  2858.2     .16       0  4933.2     .07       0  5063.2     .16       0
    5484      .1       0
Bank Sta=4933.2,5063.2
XS Rating Curve= 0 ,0
Exp/Cntr=0.3,0.1

Type RM Length L Ch R = 1 ,31226   ,644,644,644
BEGIN DESCRIPTION:
SOUTH GRAPE CREEK 48.0
END DESCRIPTION:
XS GIS Cut Line= 3
      2793791.13     10031950.79      2795186.96     10031112.26
      2795904.54     10030951.06
#Sta/Elev= 30
  3296.5 1589.41  3496.1 1578.33  4269.5 1577.64    4423 1571.39  4809.6  1565.9
  4889.3 1557.28  4910.7 1550.84  4916.5 1553.66  4936.2 1549.94  4941.3 1552.09
  4957.1 1546.74  5008.1 1544.45    5028 1550.33  5081.5 1557.74  5100.6 1561.47
  5119.7 1570.82  5124.8 1570.87  5131.4 1577.02  5168.1 1597.86  5173.3 1596.54
  5211.5 1618.27  5216.6 1617.31  5223.6 1622.82  5259.9 1638.51  5295.4 1641.02
  5315.9 1653.07  5346.5 1659.15  5377.3 1669.17  5438.3 1676.19  5660.3 1678.42
#Mann= 4 ,-1 , 0
  3296.5     .16       0  4889.3     .07       0  5081.5     .16       0
  5660.3     .16       0
Bank Sta=4889.3,5081.5
XS Rating Curve= 0 ,0
Exp/Cntr=0.3,0.1

Type RM Length L Ch R = 1 ,30582   ,470,470,470
BEGIN DESCRIPTION:
SOUTH GRAPE CREEK 47.0
END DESCRIPTION:
XS GIS Cut Line= 3
      2793853.65     10032002.88      2795442.16     10031653.92
      2796034.73     10031310.86
#Sta/Elev= 30
  3601.3 1582.34  3713.8 1577.97  3762.7 1577.37  3806.5 1574.87  4035.6    1574
  4374.1 1576.17  4547.9 1571.89  4650.8 1572.42  4787.3 1570.31    4880 1566.06
  4928.9 1561.62  4957.7 1554.69  4967.5 1551.28  4972.7  1551.4  4988.4  1545.1
  5008.7 1544.32  5039.6 1546.18  5049.9  1549.4  5070.5 1551.22  5090.8 1554.81
  5131.8 1555.58  5201.8 1560.29  5260.9 1562.62  5276.7  1564.7  5431.4 1567.15
    5651 1575.71  5766.5 1585.08  5833.4  1593.4  5860.8 1598.06  5912.4 1602.89
#Mann= 4 ,-1 , 0
  3601.3     .16       0  4957.7     .07       0  5090.8     .16       0
  5912.4     .16       0
Bank Sta=4957.7,5090.8
XS Rating Curve= 0 ,0
Exp/Cntr=0.3,0.1

Type RM Length L Ch R = 1 ,30112   ,441,441,441
BEGIN DESCRIPTION:
SOUTH GRAPE CREEK 46.0
END DESCRIPTION:
XS GIS Cut Line= 4
     2794051.822    10032033.133     2795062.238    10031814.383
     2795149.053    10032156.694     2796791.122    10031867.466
#Sta/Elev= 30
       01576.053249.1567 1573.16368.75191574.726 558.1111575.088727.53751571.291
847.13271570.495877.03151568.634976.6942 1568.551134.7441564.1321400.1421562.989
1439.9181560.2441459.8051556.3511469.7491551.9581479.6931547.4871489.6371544.634
 1499.581543.6181618.9061550.9581678.5691551.7181698.4571553.7671728.2881559.237
1827.7261562.3552364.6911563.6452563.5681567.3892672.9491572.0292732.6121576.901
2861.8821592.4472901.6571601.593 2961.321622.8063020.9831634.0933050.8141636.793
#Mann= 3 ,-1 , 0
       0     .16       01469.749     .07       01618.906     .16       0
Bank Sta=1469.749,1618.906
XS Rating Curve= 0 ,0
Exp/Cntr=0.3,0.1

Type RM Length L Ch R = 1 ,29671   ,375,375,375
BEGIN DESCRIPTION:
SOUTH GRAPE CREEK 45.0
END DESCRIPTION:
XS GIS Cut Line= 3
       2794530.7     10033169.56      2794916.12     10032690.38
      2796701.85     10032138.53
#Sta/Elev= 30
  3987.2  1576.5  4217.1 1566.69  4373.9 1562.92  4409.1  1564.1  4537.1 1556.31
  4646.7 1553.15  4730.2 1546.54  4815.1 1556.17    4913 1556.29  4950.8 1552.41
  4970.9 1542.08  5015.8 1540.58  5043.5 1546.93  5086.6 1549.15    5107 1547.62
  5146.6 1552.12  5151.9 1551.66  5179.3 1557.82  5211.7 1560.58  5441.9 1564.49
  5760.2 1558.98  5954.8 1559.34  6153.7 1563.98    6206 1567.43  6226.9  1567.1
  6247.9 1570.42  6330.7 1577.28  6368.6 1584.62  6425.8 1589.41  6471.2 1596.65
#Mann= 4 ,-1 , 0
  3987.2     .16       0  4950.8     .07       0  5146.6     .16       0
  6471.2      .1       0
#XS Ineff= 2 ,-1
  4435.8 4863.64  1556.9 5445.31 6185.94 1564.62
Permanent Ineff=
       T       T
Bank Sta=4950.8,5146.6
XS Rating Curve= 0 ,0
Exp/Cntr=0.3,0.1

Type RM Length L Ch R = 1 ,29296   ,220,220,220
BEGIN DESCRIPTION:
SOUTH GRAPE CREEK 43.0
END DESCRIPTION:
XS GIS Cut Line= 3
      2794546.37     10033221.62      2796291.12     10032518.51
      2796900.52     10032112.24
#Sta/Elev= 30
  4250.4 1578.06  4360.1 1576.36  4521.2 1568.25    4533 1565.65  4597.7 1560.74
  4640.8 1553.52  4682.4 1553.48  4813.3 1543.34  4819.3 1546.28  4843.5 1548.01
  4910.3 1548.41  4926.7 1543.94  4932.1 1546.27  4950.9 1543.14  5033.9 1540.57
  5037.2 1541.07  5039.7 1544.05  5058.3 1548.41  5087.9 1548.47    5112 1553.73
  5117.4 1552.26  5136.2 1557.04  5189.9 1562.44  5804.8 1560.06  5917.6 1562.06
  6140.3 1558.23    6298 1561.61  6523.3 1574.28  6817.8 1608.17  6863.9 1611.81
#Mann= 4 ,-1 , 0
  4250.4     .16       0  4910.3     .07       0  5058.3     .16       0
  6863.9      .1       0
#XS Ineff= 2 ,-1
  4714.2 4845.45 1548.11 5919.53 6390.62 1562.23
Permanent Ineff=
       T       T
Bank Sta=4910.3,5058.3
XS Rating Curve= 0 ,0
Exp/Cntr=0.3,0.1