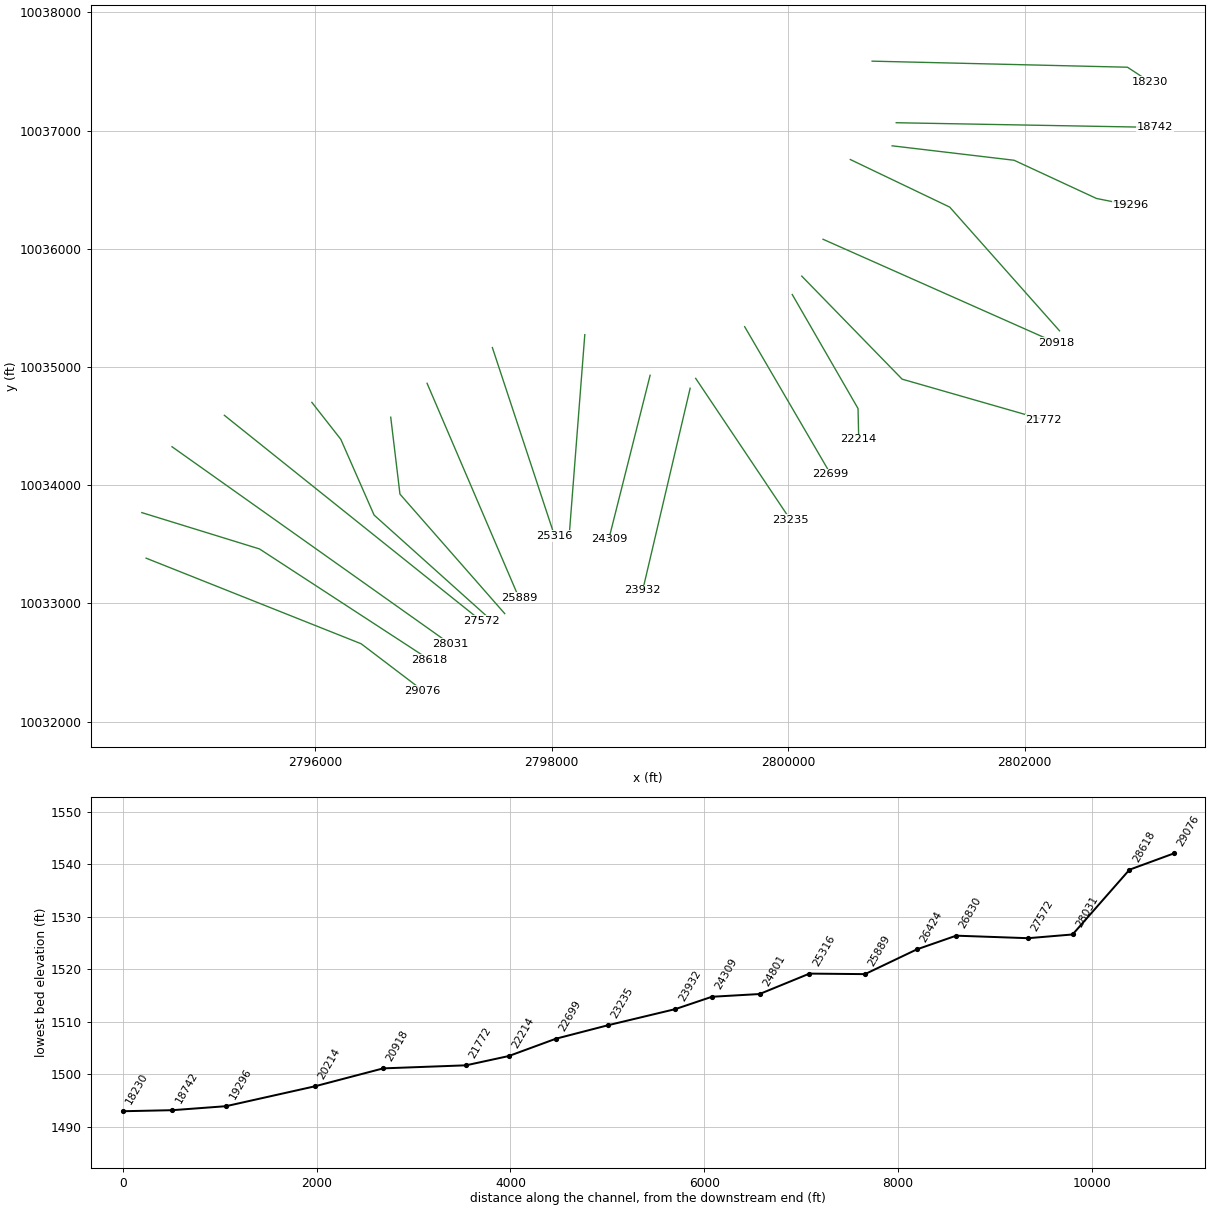
HEC-RAS study SOUTH GRAPE CREEK.prj: SOUTH GRAPE CREEK Base Level Engineering

--- SOUTH GRAPE CREEK.g01 (geometry) --- (continued)

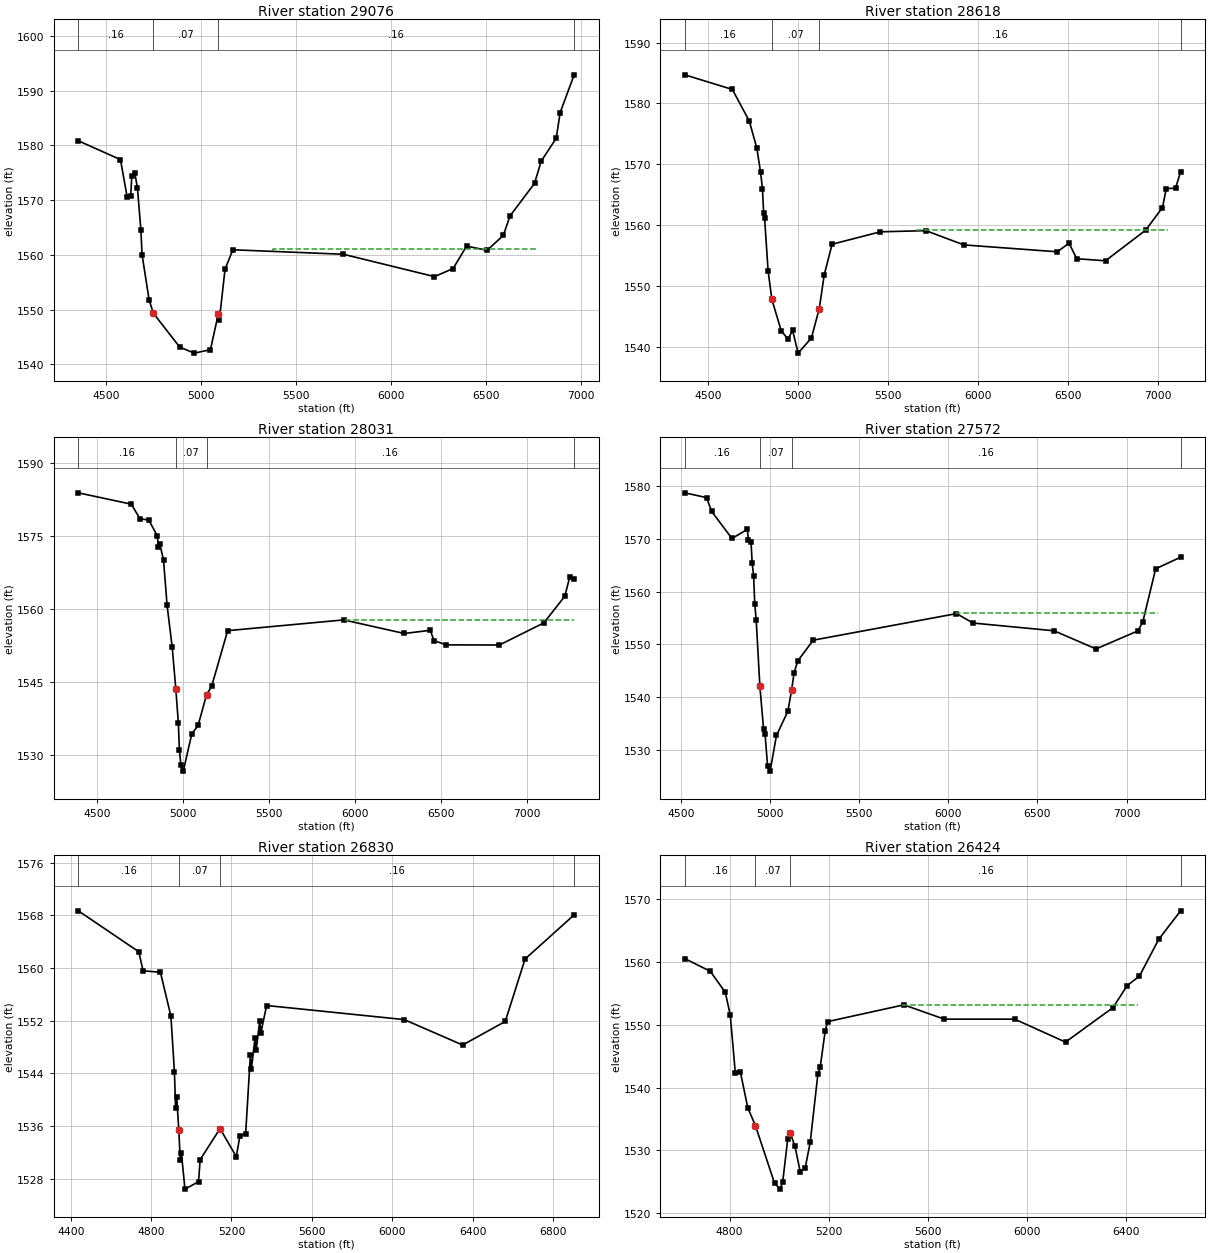
Type RM Length L Ch R = 1 ,29076   ,458,458,458
BEGIN DESCRIPTION:
Mapping XS 78a7bacf
END DESCRIPTION:
XS GIS Cut Line= 3
      2794572.35      10033383.1      2796390.08     10032659.13
      2796910.93     10032263.29
#Sta/Elev= 30
  4355.3 1580.84  4577.2  1577.4  4612.6 1570.54    4631 1570.71  4636.9 1574.39
  4652.5 1574.96  4666.5 1572.25  4684.8 1564.48  4690.8 1560.05  4727.9  1551.8
  4750.1 1549.37  4889.3 1543.16  4965.6 1542.07  5050.8 1542.69  5092.6 1549.24
    5098 1548.15  5127.7 1557.38  5169.2 1560.94  5750.6 1560.12  6230.7 1556.04
  6328.9 1557.52  6399.6 1561.61  6507.7 1560.84    6593 1563.56  6628.4 1567.12
  6757.3 1573.06  6792.6 1577.12  6871.6  1581.3  6892.5    1586  6966.1 1592.88
#Mann= 4 ,-1 , 0
  4355.3     .16       0  4750.1     .07       0  5092.6     .16       0
  6966.1      .1       0
#XS Ineff= 1 ,-1
 5382.81 6763.28 1561.13
Permanent Ineff=
       T
Bank Sta=4750.1,5092.6
XS Rating Curve= 0 ,0
Exp/Cntr=0.3,0.1

Type RM Length L Ch R = 1 ,28618   ,587,587,587
BEGIN DESCRIPTION:
SOUTH GRAPE CREEK 44.0
END DESCRIPTION:
XS GIS Cut Line= 3
      2794535.88     10033768.52      2795530.71     10033461.22
      2796968.21     10032523.71
#Sta/Elev= 30
  4370.8 1584.69  4635.2 1582.29  4729.4  1577.1  4771.2 1572.67  4792.2  1568.7
  4802.6 1566.01  4809.2 1562.05  4814.4 1561.23    4834  1552.5    4855 1547.79
  4907.1 1542.63    4945 1541.27  4970.1 1542.71  5001.2 1538.97  5074.7 1541.45
  5118.7 1546.29  5146.1 1551.82  5189.9 1556.86  5458.1  1558.9  5711.6 1559.09
  5922.7 1556.75  6441.9 1555.62  6507.7 1557.02  6550.5 1554.48  6710.5 1554.14
  6933.7 1559.17  7027.3 1562.89  7048.3 1566.01  7099.7 1566.06  7128.2 1568.75
#Mann= 4 ,-1 , 0
  4370.8     .16       0    4855     .07       0  5118.7     .16       0
  7128.2     .05       0
#XS Ineff= 1 ,-1
 5659.77 7059.77 1559.27
Permanent Ineff=
       T
Bank Sta=4855,5118.7
XS Rating Curve= 0 ,0
Exp/Cntr=0.3,0.1

Type RM Length L Ch R = 1 ,28031   ,459,459,459
BEGIN DESCRIPTION:
Mapping XS eaff9f1a
END DESCRIPTION:
XS GIS Cut Line= 2
      2794791.09     10034325.82      2797140.07     10032659.14
#Sta/Elev= 30
  4391.9 1583.82  4699.6 1581.49  4750.1 1578.48  4800.5 1578.25    4851 1574.97
  4857.1 1572.59  4865.7 1573.25  4886.7 1570.03  4907.6 1560.68  4937.1 1552.11
    4958 1543.61  4972.8 1536.59  4978.9 1530.98  4987.5 1527.99  5001.5 1526.64
  5050.8 1534.28  5087.6 1536.02  5136.6 1542.33  5165.9 1544.03  5259.3  1555.5
  5933.6 1557.71  6285.4 1554.92  6436.4 1555.57  6457.7 1553.46    6529 1552.58
  6837.8 1552.55  7096.2  1557.1    7218 1562.58  7245.6 1566.43  7272.1 1566.12
#Mann= 4 ,-1 , 0
  4391.9     .16       0    4958     .07       0  5136.6     .16       0
  7272.1     .05       0
#XS Ineff= 1 ,-1
 5941.41 7281.25 1557.66
Permanent Ineff=
       T
Bank Sta=4958,5136.6
XS Rating Curve= 0 ,0
Exp/Cntr=0.3,0.1

Type RM Length L Ch R = 1 ,27572   ,742,742,742
BEGIN DESCRIPTION:
SOUTH GRAPE CREEK 42.0
END DESCRIPTION:
XS GIS Cut Line= 2
      2795233.86      10034591.4      2797404.59     10032852.73
#Sta/Elev= 30
    4522 1578.72  4643.9 1577.81  4672.7 1575.19  4786.4 1570.06  4872.8 1571.79
  4879.2 1569.76  4893.6 1569.31    4900 1565.34    4908    1563  4914.4 1557.62
  4922.4 1554.64  4943.2 1541.99    4964 1533.85    4972 1533.04  4986.4 1526.87
  5000.6 1525.93  5036.1 1532.69  5100.1 1537.28  5120.9 1541.27  5135.3 1544.63
  5156.1 1546.86  5242.5 1550.77    6046 1555.81  6138.9 1554.02  6593.4 1552.55
  6828.7 1549.11    7064 1552.54  7091.2 1554.27  7163.2 1564.31  7303.2 1566.51
#Mann= 4 ,-1 , 0
    4522     .16       0  4943.2     .07       0  5120.9     .16       0
  7303.2      .1       0
#XS Ineff= 1 ,-1
 6042.19 7178.91 1555.96
Permanent Ineff=
       T
Bank Sta=4943.2,5120.9
XS Rating Curve= 0 ,0
Exp/Cntr=0.3,0.1

Type RM Length L Ch R = 1 ,26830   ,406,406,406
BEGIN DESCRIPTION:
SOUTH GRAPE CREEK 41.0
END DESCRIPTION:
XS GIS Cut Line= 4
      2795973.43     10034700.78      2796218.21      10034388.3
      2796499.46     10033747.67      2797520.31     10032830.99
#Sta/Elev= 30
  4437.5 1568.68  4738.6 1562.46  4759.8 1559.57  4846.2 1559.35  4898.4 1552.69
  4915.9 1544.25  4921.7 1538.77  4927.2 1540.41  4937.7 1535.41  4945.1 1530.77
  4950.6 1531.96  4968.2 1526.41    5036 1527.54    5044 1530.88  5142.9 1535.61
  5223.9 1531.34  5241.8 1534.47  5270.6 1534.85    5294 1546.72  5299.4 1544.69
  5317.3  1549.4  5322.8  1547.5  5340.7 1551.97  5346.2 1550.14    5375  1554.3
    6060 1552.16  6350.8  1548.3  6563.1 1551.88  6661.7 1561.36  6906.1 1568.07
#Mann= 4 ,-1 , 0
  4437.5     .16       0  4937.7     .07       0  5142.9     .16       0
  6906.1     .05       0
#XS Ineff= 1 ,-1
 5396.88 6690.62 1554.17
Permanent Ineff=
       T
Bank Sta=4937.7,5142.9
XS Rating Curve= 0 ,0
Exp/Cntr=0.3,0.1

Type RM Length L Ch R = 1 ,26424   ,535,535,535
BEGIN DESCRIPTION:
SOUTH GRAPE CREEK 40.0
END DESCRIPTION:
XS GIS Cut Line= 3
      2796640.08     10034575.78      2796718.21     10033924.76
      2797603.51     10032914.46
#Sta/Elev= 30
  4619.6 1560.55  4722.4 1558.53  4782.8 1555.19    4803 1551.52  4823.1 1542.37
  4843.2 1542.55  4873.5 1536.77  4904.3 1533.93  4981.5 1524.74  5004.1  1523.8
  5014.5    1525  5034.6  1531.8  5044.7 1532.75  5063.7 1530.63    5085 1526.58
  5105.1  1527.2  5125.3 1531.27    5156 1542.09  5165.5 1543.24  5185.7 1549.05
  5195.8 1550.51  5502.7 1553.18  5665.8  1550.9  5949.5  1550.9  6154.5 1547.24
  6346.2 1552.75  6403.1 1556.25  6452.5 1557.76  6530.3 1563.63  6618.6 1568.17
#Mann= 4 ,-1 , 0
  4619.6     .16       0  4904.3     .07       0  5044.7     .16       0
  6618.6     .05       0
#XS Ineff= 1 ,-1
 5496.09 6445.31  1553.2
Permanent Ineff=
       T
Bank Sta=4904.3,5044.7
XS Rating Curve= 0 ,0
Exp/Cntr=0.3,0.1

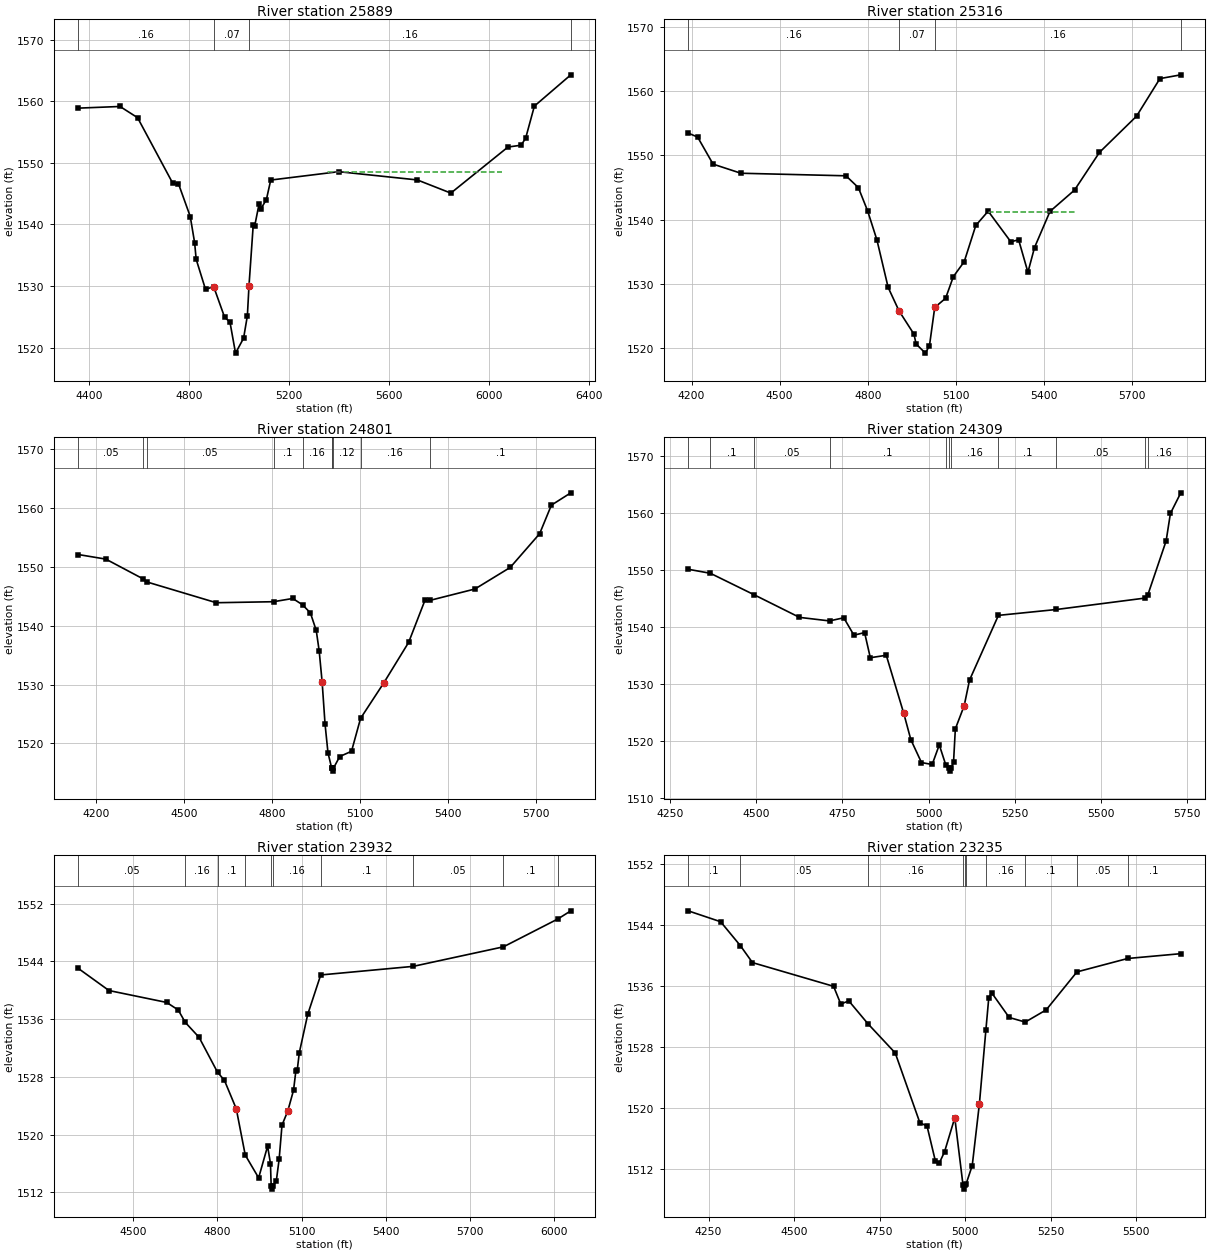
Type RM Length L Ch R = 1 ,25889   ,573,573,573
BEGIN DESCRIPTION:
SOUTH GRAPE CREEK 39.0
END DESCRIPTION:
XS GIS Cut Line= 2
      2796947.37     10034862.26      2797723.43     10033049.71
#Sta/Elev= 30
  4356.7 1558.88  4524.2 1559.15  4594.4 1557.33  4735.8 1546.64  4758.2 1546.59
  4805.3 1541.28  4822.9 1536.99  4828.9 1534.34  4866.4 1529.44    4899 1529.89
  4942.5 1524.95  4964.3 1524.11  4986.5 1519.09  5018.7 1521.51  5033.9 1525.16
  5040.4 1530.05  5057.4 1539.93  5062.9 1539.68    5081 1543.38  5086.5 1542.42
    5110 1544.03  5127.4  1547.2  5399.4 1548.56  5714.1 1547.22  5848.3 1545.08
  6076.8 1552.56  6129.4 1552.86  6147.6 1553.99  6182.6 1559.21  6328.4 1564.29
#Mann= 4 ,-1 , 0
  4356.7     .16       0    4899     .07       0  5040.4     .16       0
  6328.4      .1       0
#XS Ineff= 1 ,-1
 5355.77 6054.07 1548.56
Permanent Ineff=
       T
Bank Sta=4899,5040.4
XS Rating Curve= 0 ,0
Exp/Cntr=0.3,0.1

Type RM Length L Ch R = 1 ,25316   ,515,515,515
BEGIN DESCRIPTION:
SOUTH GRAPE CREEK 38.0
END DESCRIPTION:
XS GIS Cut Line= 2
      2797499.44     10035164.38      2798025.51     10033570.56
#Sta/Elev= 30
  4188.3 1553.49  4220.6 1552.87  4273.2 1548.65    4368 1547.23    4726 1546.83
  4768.2 1544.99  4799.8 1541.36  4831.4 1536.84  4869.7 1529.43  4906.7 1525.78
  4957.7 1522.14  4964.9 1520.62  4996.4 1519.19  5010.4 1520.33  5028.4 1526.31
  5065.4 1527.74  5091.9 1531.12  5128.9 1533.45  5168.3 1539.09  5210.5 1541.32
  5287.7 1536.54  5314.2 1536.86  5345.9  1531.8  5368.4 1535.65  5421.1 1541.28
  5504.6  1544.6  5589.6 1550.48  5715.9 1556.12  5795.6 1561.98  5866.7 1562.57
#Mann= 4 ,-1 , 0
  4188.3     .16       0  4906.7     .07       0  5028.4     .16       0
  5866.7      .1       0
#XS Ineff= 1 ,-1
 5214.06  5512.5 1541.21
Permanent Ineff=
       T
Bank Sta=4906.7,5028.4
XS Rating Curve= 0 ,0
Exp/Cntr=0.3,0.1

Type RM Length L Ch R = 1 ,24801   ,492,492,492
BEGIN DESCRIPTION:
SOUTH GRAPE CREEK 37.0
END DESCRIPTION:
XS GIS Cut Line= 2
       2798280.7     10035273.71      2798150.58     10033597.65
#Sta/Elev= 30
  4137.5 1552.06  4231.9 1551.28  4359.7 1547.91  4371.6 1547.41  4608.9 1543.88
  4804.1 1544.05  4869.7  1544.6  4903.1 1543.53  4929.9 1542.15  4949.9 1539.18
  4959.9 1535.71    4970 1530.43    4980 1523.25    4990  1518.4  5002.1 1515.91
  5002.6  1515.8  5005.4  1515.3  5008.6  1515.8  5030.2 1517.78  5070.3 1518.67
  5101.1 1524.25  5180.6 1530.29  5265.2 1537.15    5321 1544.31  5337.4 1544.27
  5491.5 1546.21  5611.9 1549.87  5712.2 1555.59  5752.3 1560.44  5818.6 1562.53
#Mann= 10 ,-1 , 0
  4137.5     .05       0  4359.7      .1       0  4371.6     .05       0
  4804.1      .1       0  4903.1     .16       0  5002.1     .12       0
  5002.6     .07       0  5008.6     .12       0  5101.1     .16       0
  5337.4      .1       0
Bank Sta=4970,5180.6
XS Rating Curve= 0 ,0
Exp/Cntr=0.3,0.1

Type RM Length L Ch R = 1 ,24309   ,377,377,377
BEGIN DESCRIPTION:
SOUTH GRAPE CREEK 36.0
END DESCRIPTION:
XS GIS Cut Line= 2
      2798832.79     10034929.98      2798483.83     10033544.55
#Sta/Elev= 30
  4302.5  1550.1  4367.1 1549.39    4493 1545.66  4625.4 1541.68  4712.5 1541.06
  4753.8 1541.61  4783.3 1538.56  4814.2 1539.02  4830.8 1534.62  4877.1 1535.05
  4927.7  1524.9  4948.3 1520.29  4979.2 1516.28  5010.2 1515.94  5030.8 1519.37
  5049.9 1515.82  5058.7 1515.28  5061.5 1514.78  5064.7 1515.28  5072.1 1516.29
  5077.4 1522.17    5103 1526.22  5118.5  1530.7  5202.3 1542.03  5370.7 1543.06
  5626.8 1545.05  5635.5 1545.59  5688.7 1555.06  5701.1 1559.86  5731.2 1563.47
#Mann= 11 ,-1 , 0
  4302.5     .05       0  4367.1      .1       0    4493     .05       0
  4712.5      .1       0  5049.9     .16       0  5058.7     .07       0
  5064.7     .16       0  5202.3      .1       0  5370.7     .05       0
  5626.8      .1       0  5635.5     .16       0
Bank Sta=4927.7,5103
XS Rating Curve= 0 ,0
Exp/Cntr=0.3,0.1

Type RM Length L Ch R = 1 ,23932   ,697,697,697
BEGIN DESCRIPTION:
SOUTH GRAPE CREEK 35.0
END DESCRIPTION:
XS GIS Cut Line= 2
      2799171.32     10034820.54       2798770.3     10033112.28
#Sta/Elev= 30
  4304.1 1543.04  4413.8 1539.96  4619.3 1538.31  4660.3 1537.27  4685.5 1535.55
  4734.8 1533.47  4800.5 1528.63  4824.8 1527.53  4867.2 1523.57  4899.2 1517.15
  4946.9 1513.99  4978.8 1518.39    4989 1515.98  4991.5 1512.93  4994.2 1512.43
  4997.5 1512.93  5009.6  1513.5  5019.9 1516.57  5030.1  1521.3  5050.7 1523.26
  5071.2 1526.14  5079.3 1528.75  5084.5 1528.97  5091.8 1531.35  5121.7 1536.65
    5168 1542.12  5497.3 1543.31  5818.9 1546.02  6012.6 1549.88  6058.8 1551.01
#Mann= 10 ,-1 , 0
  4304.1     .05       0  4685.5     .16       0  4800.5      .1       0
  4899.2     .16       0  4991.5     .07       0  4997.5     .16       0
    5168      .1       0  5497.3     .05       0  5818.9      .1       0
  6012.6     .05       0
Bank Sta=4867.2,5050.7
XS Rating Curve= 0 ,0
Exp/Cntr=0.3,0.1

Type RM Length L Ch R = 1 ,23235   ,536,536,536
BEGIN DESCRIPTION:
SOUTH GRAPE CREEK 34.0
END DESCRIPTION:
XS GIS Cut Line= 2
      2799218.22     10034903.91      2800019.38     10033707.36
#Sta/Elev= 30
  4190.3 1545.85  4285.2 1544.42  4342.8 1541.29  4378.3 1539.06  4615.4 1535.95
  4636.5 1533.62  4659.9 1534.04  4715.4 1531.06  4795.6 1527.21  4867.6 1518.06
  4888.6 1517.62  4912.6  1513.1  4924.7  1512.8  4939.7 1514.24  4969.7 1518.71
  4993.8 1509.85  4996.6 1509.35  4999.8 1509.85  5002.4 1509.98  5020.7 1512.44
  5041.7 1520.57  5060.6 1530.22    5069 1534.42  5077.8 1535.08  5128.8 1531.86
  5175.7 1531.26  5236.9 1532.86  5326.8 1537.84  5475.1  1539.6  5630.3 1540.23
#Mann= 10 ,-1 , 0
  4190.3      .1       0  4342.8     .05       0  4715.4     .16       0
  4993.8     .07       0  4999.8     .16       0  5002.4      .1       0
  5060.6     .16       0  5175.7      .1       0  5326.8     .05       0
  5475.1      .1       0
Bank Sta=4969.7,5041.7
XS Rating Curve= 0 ,0
Exp/Cntr=0.3,0.1

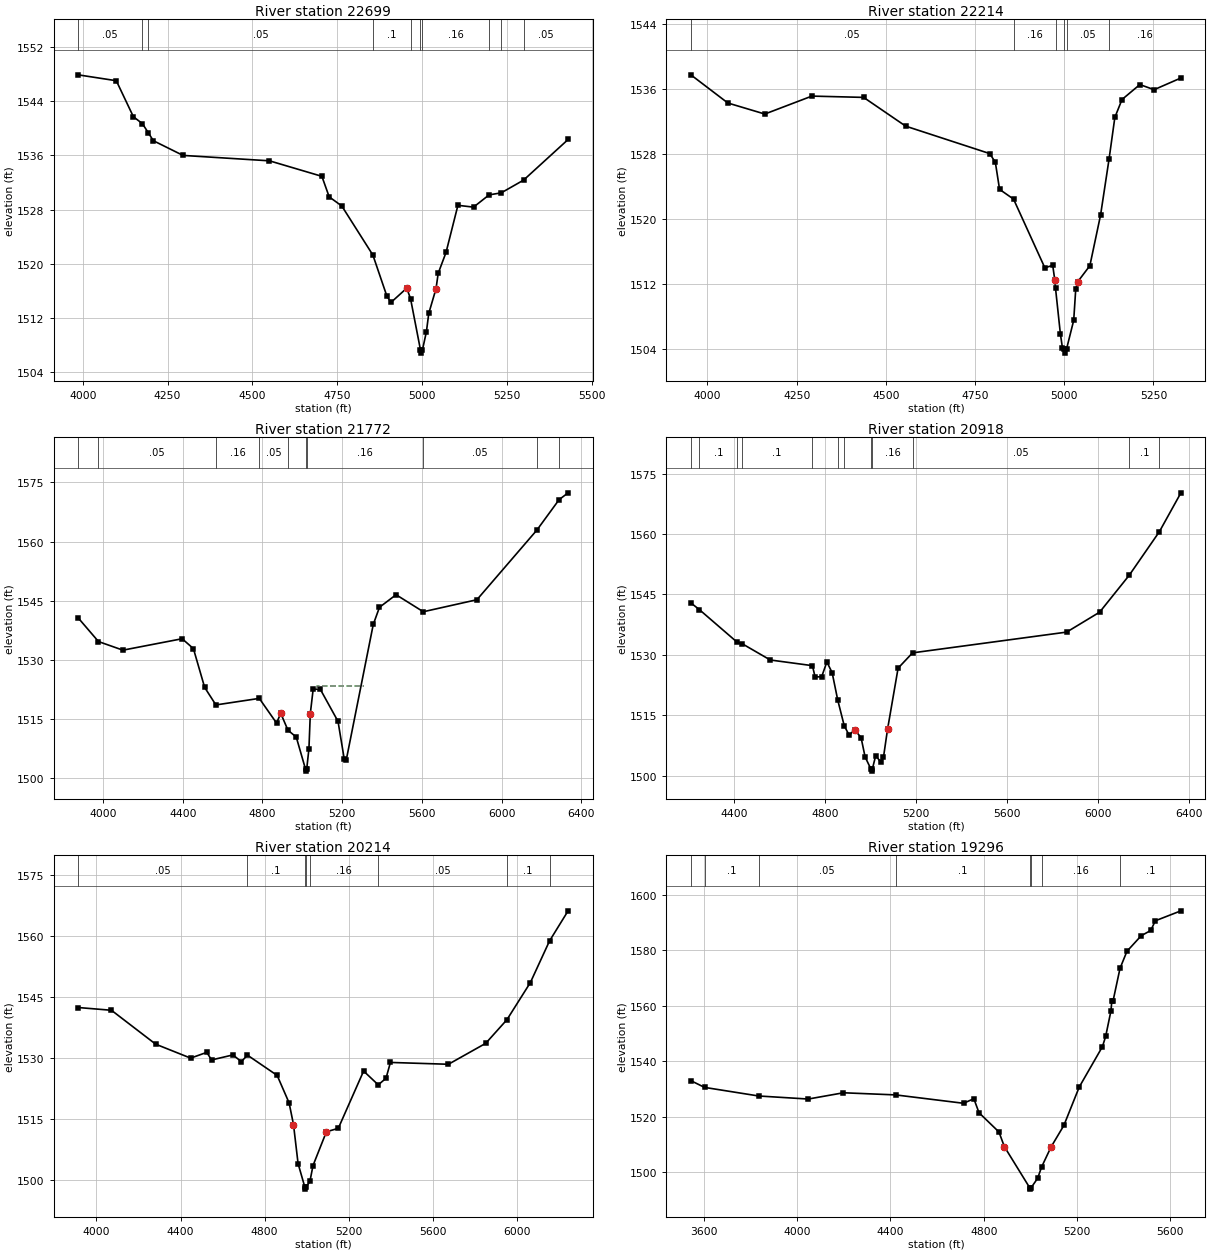
Type RM Length L Ch R = 1 ,22699   ,485,485,485
BEGIN DESCRIPTION:
SOUTH GRAPE CREEK 33.0
END DESCRIPTION:
XS GIS Cut Line= 2
      2799632.08     10035341.16      2800359.81     10034092.78
#Sta/Elev= 30
  3985.9 1547.89  4098.7 1547.02  4149.1  1541.7  4175.7 1540.68  4193.5  1539.3
  4207.9 1538.16  4295.4 1535.99  4550.3 1535.19  4704.9  1532.9  4726.4 1529.87
  4763.6 1528.52  4855.3 1521.27  4896.8 1515.17  4908.9 1514.29  4955.2 1516.39
  4966.4 1514.81  4995.5 1507.29  4998.3 1506.79  5001.5 1507.29  5013.1 1509.95
    5020 1512.65  5041.5 1516.32  5047.8 1518.57    5071 1521.67    5106 1528.62
    5152 1528.35  5197.9 1530.16  5233.7 1530.46  5299.6 1532.34  5430.9 1538.34
#Mann= 10 ,-1 , 0
  3985.9     .05       0  4175.7      .1       0  4193.5     .05       0
  4855.3      .1       0  4966.4     .16       0  4995.5     .07       0
  5001.5     .16       0  5197.9      .1       0  5233.7     .16       0
  5299.6     .05       0
Bank Sta=4955.2,5041.5
XS Rating Curve= 0 ,0
Exp/Cntr=0.3,0.1

Type RM Length L Ch R = 1 ,22214   ,442,442,442
BEGIN DESCRIPTION:
SOUTH GRAPE CREEK 32.0
END DESCRIPTION:
XS GIS Cut Line= 3
       2800034.4     10035613.29      2800590.53     10034648.94
      2800596.45     10034388.63
#Sta/Elev= 30
  3953.4 1537.78  4057.1 1534.31  4160.7 1532.95  4292.6 1535.16  4437.7    1535
  4555.5 1531.46    4791 1528.08  4806.8 1527.02  4818.7 1523.67  4857.9 1522.47
  4945.6 1514.01  4967.7 1514.31  4973.5  1512.5  4975.6 1511.47  4989.2 1505.86
    4995 1504.13  5000.4    1504  5003.1  1503.5  5006.4    1504  5026.5 1507.54
  5032.3 1511.45  5038.1 1512.31  5071.8 1514.27  5101.8 1520.51  5125.8 1527.46
  5141.8 1532.53  5161.9 1534.74  5211.9 1536.58  5251.9 1535.95    5327 1537.39
#Mann= 6 ,-1 , 0
  3953.4     .05       0  4857.9     .16       0  4975.6     .05       0
  5000.4     .04       0  5006.4     .05       0  5125.8     .16       0
Bank Sta=4973.5,5038.1
XS Rating Curve= 0 ,0
Exp/Cntr=0.3,0.1

Type RM Length L Ch R = 1 ,21772   ,854,854,854
BEGIN DESCRIPTION:
SOUTH GRAPE CREEK 31.0
END DESCRIPTION:
XS GIS Cut Line= 3
      2800114.97     10035768.81      2800963.26     10034897.42
      2802158.37     10034554.27
#Sta/Elev= 30
  3874.7 1540.66  3977.3 1534.61    4100 1532.43  4397.1 1535.33  4453.7 1532.82
  4510.1 1522.98  4566.5 1518.53  4784.3 1520.19  4870.9 1513.93    4892 1516.39
  4928.3 1512.11  4969.9 1510.37  5016.3 1502.23  5019.1 1501.73  5022.3 1502.23
  5033.5 1507.44  5040.4 1516.34  5054.6 1522.48  5089.9 1522.56  5179.5 1514.35
  5210.7 1504.79  5221.1 1504.63  5356.3 1538.95  5387.5 1543.31  5470.8  1546.5
  5607.5 1542.18  5876.5 1545.23  6177.9 1562.93  6289.1 1570.63  6334.2 1572.36
#Mann= 10 ,-1 , 0
  3874.7      .1       0  3977.3     .05       0  4566.5     .16       0
  4784.3     .05       0  4928.3     .16       0  5016.3     .07       0
  5022.3     .16       0  5607.5     .05       0  6177.9      .1       0
  6289.1     .16       0
#XS Ineff= 1 ,-1
    5075 5311.93 1523.33
Permanent Ineff=
       T
Bank Sta=4892,5040.4
XS Rating Curve= 0 ,0
Exp/Cntr=0.3,0.1

Type RM Length L Ch R = 1 ,20918   ,704,704,704
BEGIN DESCRIPTION:
SOUTH GRAPE CREEK 30.0
END DESCRIPTION:
XS GIS Cut Line= 2
      2800294.68      10036080.7      2802264.13     10035205.39
#Sta/Elev= 30
  4208.2  1542.9  4245.8 1541.22  4412.6  1533.1  4432.8  1532.8  4557.4 1528.73
  4742.8 1527.32  4754.4 1524.57  4783.1 1524.52  4806.4 1528.24  4829.6 1525.58
  4854.2 1518.78  4882.7 1512.42  4904.8 1510.02  4928.1 1511.47  4956.8 1509.46
  4974.6 1504.66  5000.3 1501.65  5003.1 1501.15  5006.3 1501.65  5021.1 1504.97
    5044 1503.37  5055.3 1504.58  5073.1 1511.49  5119.6  1526.7  5183.2  1530.5
    5861 1535.65    6006  1540.6  6135.9 1549.74  6268.9 1560.59  6363.4 1570.21
#Mann= 12 ,-1 , 0
  4208.2     .05       0  4245.8      .1       0  4412.6     .05       0
  4432.8      .1       0  4742.8     .05       0  4854.2      .1       0
  4882.7     .16       0  5000.3     .07       0  5006.3     .16       0
  5183.2     .05       0  6135.9      .1       0  6268.9     .16       0
Bank Sta=4928.1,5073.1
XS Rating Curve= 0 ,0
Exp/Cntr=0.3,0.1

Type RM Length L Ch R = 1 ,20214   ,918,918,918
BEGIN DESCRIPTION:
SOUTH GRAPE CREEK 29.0
END DESCRIPTION:
XS GIS Cut Line= 3
      2800525.44     10036755.14      2801365.57     10036352.83
      2802293.92     10035306.22
#Sta/Elev= 30
  3912.7 1542.41  4071.6 1541.73  4281.9 1533.39  4448.2 1529.96  4524.9 1531.38
  4547.6 1529.51  4649.3 1530.75  4689.1  1529.1  4718.4 1530.69  4859.6 1525.71
  4916.4 1518.95  4937.3 1513.62  4959.1 1504.02  4991.2 1498.24    4994 1497.74
  4997.2 1498.24  5015.4 1499.65  5030.1 1503.54  5093.7 1511.84  5150.4  1512.7
  5270.7 1526.78  5340.3 1523.39  5377.3 1525.01  5398.2  1528.9  5674.1 1528.45
  5851.4  1533.6  5952.4 1539.42  6063.9 1548.56  6154.9 1558.79  6243.2 1566.19
#Mann= 8 ,-1 , 0
  3912.7     .05       0  4718.4      .1       0  4991.2     .07       0
  4997.2      .1       0  5015.4     .16       0  5340.3     .05       0
  5952.4      .1       0  6154.9     .16       0
Bank Sta=4937.3,5093.7
XS Rating Curve= 0 ,0
Exp/Cntr=0.3,0.1

Type RM Length L Ch R = 1 ,19296   ,554,554,554
BEGIN DESCRIPTION:
SOUTH GRAPE CREEK 28.0
END DESCRIPTION:
XS GIS Cut Line= 4
      2800878.92     10036871.21      2801909.84     10036749.02
      2802606.18     10036425.88      2802895.26     10036368.11
#Sta/Elev= 30
  3544.7 1533.06  3603.4 1530.63  3835.5 1527.53  4047.7 1526.43  4198.8 1528.69
  4422.7 1527.92  4713.6  1524.9  4757.7 1526.55  4779.8  1521.5  4865.5 1514.54
  4888.4 1509.29  4997.2 1494.45    5000 1493.95  5003.2 1494.45  5031.3 1497.88
  5048.2 1501.94  5088.4 1509.11  5143.6 1516.92  5209.7  1530.8  5308.9 1545.32
  5322.7    1549  5345.6 1558.31    5349 1561.72  5354.2 1561.72  5384.2 1573.53
    5414  1579.7  5475.2 1585.32    5516 1587.21  5535.7  1590.7  5645.3 1594.29
#Mann= 8 ,-1 , 0
  3544.7     .05       0  3603.4      .1       0  3835.5     .05       0
  4422.7      .1       0  4997.2     .07       0  5003.2      .1       0
  5048.2     .16       0  5384.2      .1       0
Bank Sta=4888.4,5088.4
XS Rating Curve= 0 ,0
Exp/Cntr=0.3,0.1

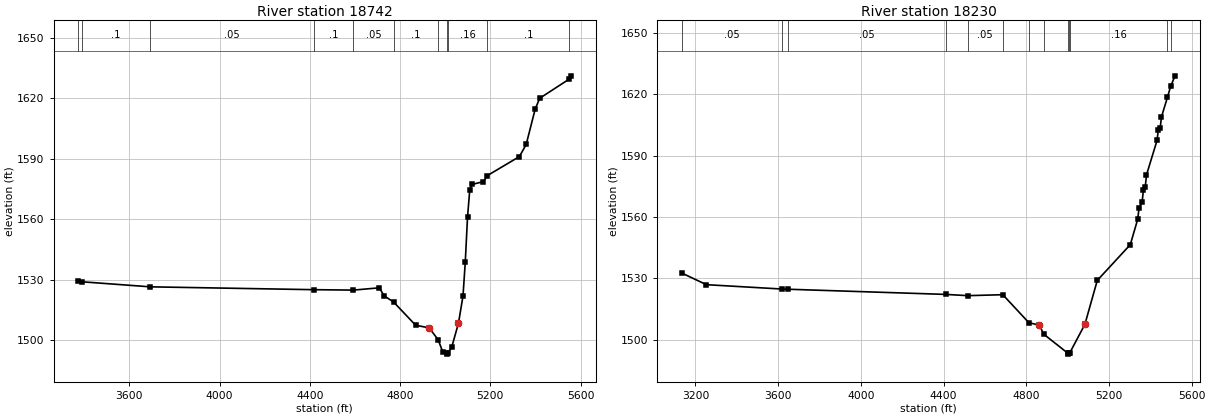
Type RM Length L Ch R = 1 ,18742   ,512,512,512
BEGIN DESCRIPTION:
SOUTH GRAPE CREEK 27.0
END DESCRIPTION:
XS GIS Cut Line= 2
      2800913.56     10037066.52        2803099.     10037027.29
#Sta/Elev= 30
  3373.7 1529.41  3388.7 1529.07  3693.3 1526.55  4417.5 1525.14  4593.4 1524.93
  4708.8 1526.07  4728.8 1522.11  4771.2 1519.05  4868.8 1507.53  4928.9  1506.2
  4968.7 1500.34  4988.9  1494.4  5005.9 1493.69  5008.6 1493.19  5011.9 1493.69
  5028.9 1496.61  5058.9 1508.58  5078.9 1522.02  5088.9 1538.67  5098.9    1561
  5108.9 1574.72  5118.9 1577.31  5168.9  1578.7    5187 1581.71  5328.9 1591.13
  5358.9 1597.14  5398.9 1614.73  5418.9 1620.04  5549.7 1629.55  5559.5 1631.16
#Mann= 11 ,-1 , 0
  3373.7     .05       0  3388.7      .1       0  3693.3     .05       0
  4417.5      .1       0  4593.4     .05       0  4771.2      .1       0
  4968.7     .16       0  5005.9     .07       0  5011.9     .16       0
    5187      .1       0  5549.7     .16       0
Bank Sta=4928.9,5058.9
XS Rating Curve= 0 ,0
Exp/Cntr=0.3,0.1

Type RM Length L Ch R = 1 ,18230   ,644,644,644
BEGIN DESCRIPTION:
SOUTH GRAPE CREEK 26.0
END DESCRIPTION:
XS GIS Cut Line= 3
      2800709.64     10037587.36      2802868.31     10037536.09
      2803057.61     10037411.86
#Sta/Elev= 30
  3134.2 1532.58  3253.1 1526.91  3620.1 1524.77  3649.3 1524.68    4413 1522.15
  4516.3 1521.55  4686.8 1522.01  4812.6 1508.35  4863.5 1507.15  4884.6 1502.73
  5000.6 1493.49  5003.3 1492.99  5006.6 1493.49  5010.2 1493.55  5083.6 1507.51
  5143.6    1529  5303.3 1546.46  5339.4 1558.98  5345.4 1564.27  5360.5 1567.16
  5366.5 1573.06  5375.6 1574.64  5381.6 1580.52  5432.8 1597.42  5438.8 1602.66
  5447.9 1603.36  5453.9  1608.8  5482.8 1618.38    5499 1623.96  5519.9 1628.92
#Mann= 13 ,-1 , 0
  3134.2     .05       0  3620.1      .1       0  3649.3     .05       0
    4413      .1       0  4516.3     .05       0  4686.8      .1       0
  4812.6     .16       0  4884.6      .1       0  5000.6     .07       0
  5006.6      .1       0  5010.2     .16       0  5482.8      .1       0
    5499     .16       0
Bank Sta=4863.5,5083.6
XS Rating Curve= 0 ,0
Exp/Cntr=0.3,0.1