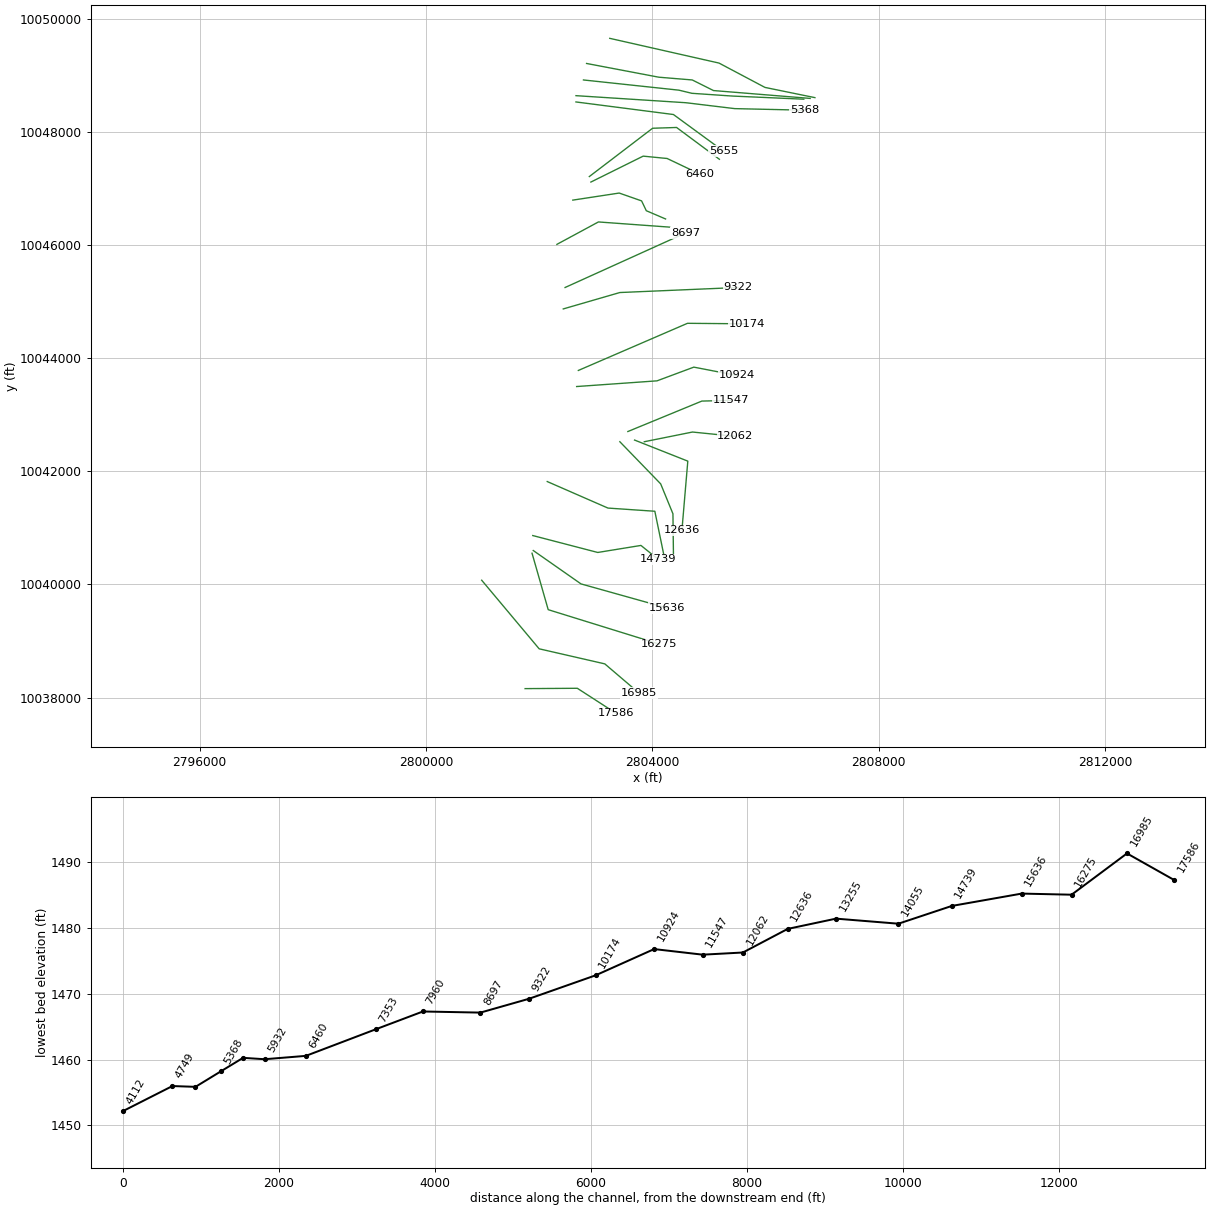
HEC-RAS study SOUTH GRAPE CREEK.prj: SOUTH GRAPE CREEK Base Level Engineering

--- SOUTH GRAPE CREEK.g01 (geometry) --- (continued)

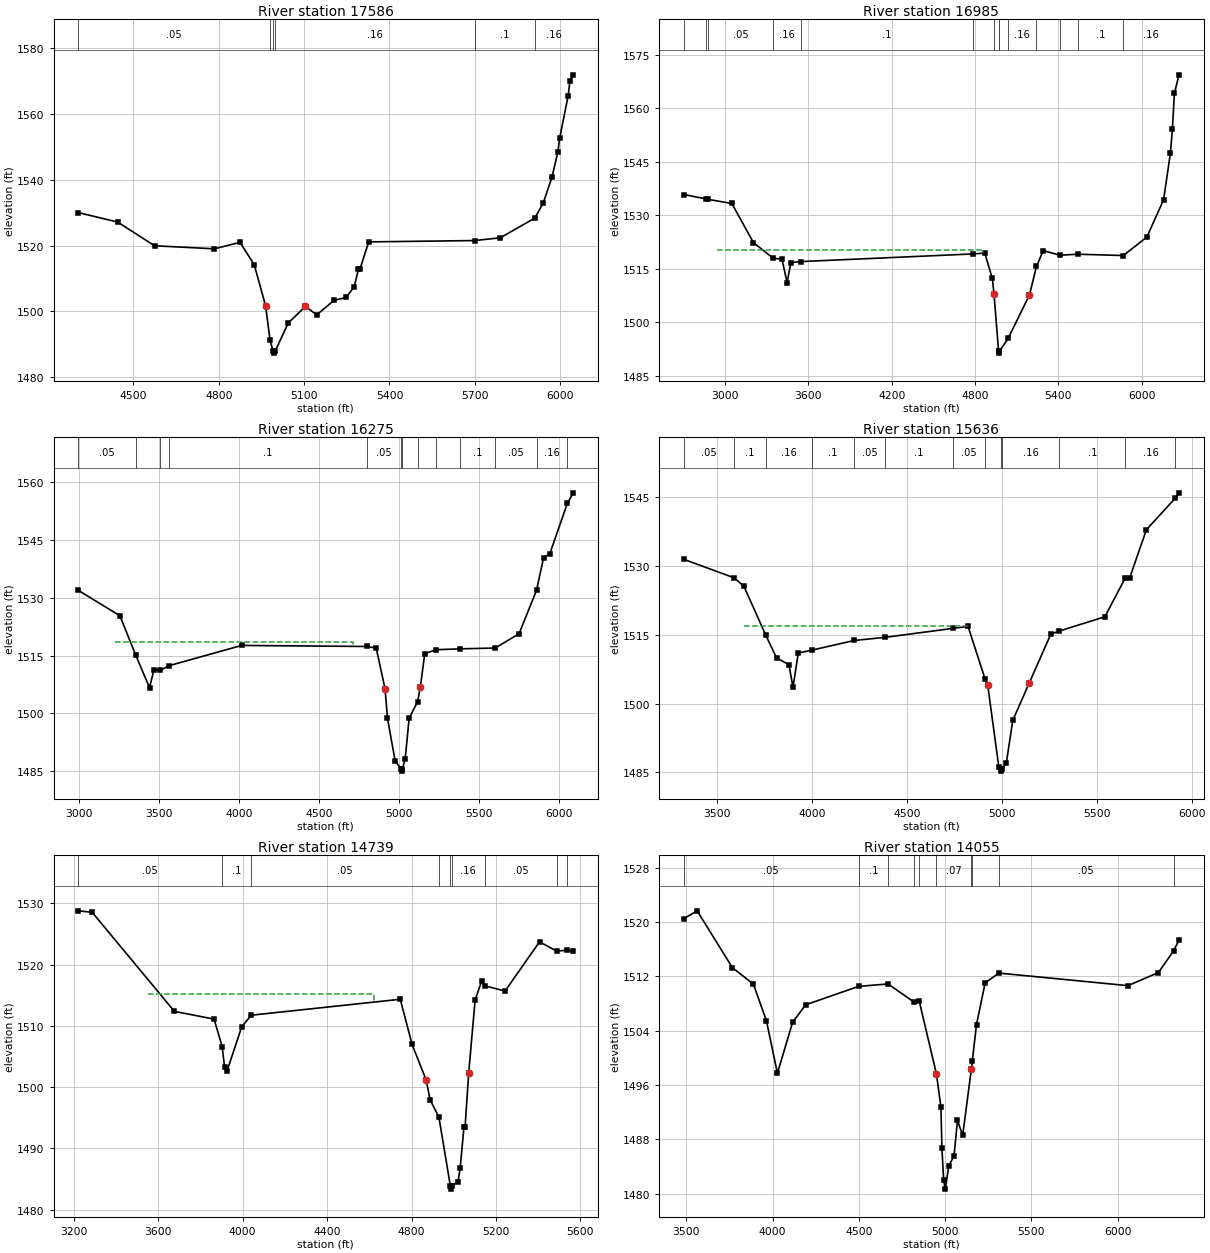
Type RM Length L Ch R = 1 ,17586   ,601,601,601
BEGIN DESCRIPTION:
SOUTH GRAPE CREEK 25.0
END DESCRIPTION:
XS GIS Cut Line= 3
      2801750.13      10038157.3      2802673.07     10038163.22
      2803359.36      10037719.5
#Sta/Elev= 30
  4306.2 1530.02  4444.5 1527.14  4574.5 1519.94  4784.5 1519.02  4874.6 1520.98
  4924.6  1514.2  4964.6 1501.72  4980.1 1491.31  4991.6 1487.83  4994.3 1487.33
  4997.6 1487.83  5044.6 1496.53  5104.6 1501.51  5144.6 1498.96  5204.6 1503.34
  5247.5 1504.23  5275.8 1507.43  5290.9  1512.8  5296.9    1513  5327.2 1521.12
  5700.7 1521.53  5789.6 1522.37  5911.1 1528.36  5940.7 1532.94    5971 1540.74
  5992.2 1548.44  5998.1 1552.54  6028.4 1565.59  6034.4  1570.1  6046.4 1571.87
#Mann= 6 ,-1 , 0
  4306.2     .05       0  4980.1     .16       0  4991.6     .07       0
  4997.6     .16       0  5700.7      .1       0  5911.1     .16       0
Bank Sta=4964.6,5104.6
XS Rating Curve= 0 ,0
Exp/Cntr=0.3,0.1

Type RM Length L Ch R = 1 ,16985   ,710,710,710
BEGIN DESCRIPTION:
SOUTH GRAPE CREEK 24.0
END DESCRIPTION:
XS GIS Cut Line= 4
      2800983.02     10040074.37      2801998.61     10038861.34
      2803158.21     10038595.11      2803761.69     10038080.37
#Sta/Elev= 30
  2703.5 1535.83  2861.4  1534.6  2880.2 1534.45  3048.4 1533.33  3204.6 1522.34
    3346 1517.98  3410.2 1517.69  3446.6 1511.11  3473.9 1516.75    3549 1517.03
  4785.7 1519.17  4870.2 1519.42  4924.8 1512.28  4936.5 1507.98  4969.8 1491.85
  4972.6 1491.35  4975.8 1491.85  5038.7 1495.48  5192.2  1507.7  5242.7 1515.66
  5290.9  1520.1  5411.9 1518.81  5538.3 1519.09  5867.8 1518.72  6037.1 1523.88
  6157.8 1534.34  6207.2 1547.49  6221.5 1554.21  6235.8 1564.17  6268.5  1569.4
#Mann= 14 ,-1 , 0
  2703.5     .05       0  2861.4      .1       0  2880.2     .05       0
    3346     .16       0    3549      .1       0  4785.7     .05       0
  4936.5      .1       0  4969.8     .07       0  4975.8      .1       0
  5038.7     .16       0  5242.7      .1       0  5411.9     .05       0
  5538.3      .1       0  5867.8     .16       0
#XS Ineff= 1 ,-1
 2940.91 4856.82 1520.18
Permanent Ineff=
       T
Bank Sta=4936.5,5192.2
XS Rating Curve= 0 ,0
Exp/Cntr=0.3,0.1

Type RM Length L Ch R = 1 ,16275   ,639,639,639
BEGIN DESCRIPTION:
SOUTH GRAPE CREEK 23.0
END DESCRIPTION:
XS GIS Cut Line= 3
       2801872.8     10040551.77      2802158.35     10039553.55
      2804122.53     10038944.18
#Sta/Elev= 30
  2995.2 1531.89  3255.3 1525.31  3354.4  1515.1  3440.4  1506.7  3468.4  1511.3
  3507.4 1511.14  3559.3 1512.34  4016.7 1517.62  4800.1 1517.35  4857.6 1516.92
  4913.1 1506.35    4928 1498.76  4975.9 1487.74  5014.8 1485.57  5017.5 1485.07
  5020.8 1485.57  5038.7 1488.15  5063.5  1498.8  5116.6 1503.05  5133.9 1506.98
  5161.3  1515.5  5231.7 1516.51  5383.4 1516.74    5602 1516.95  5750.7 1520.66
  5859.9  1531.9  5904.2 1540.39    5942 1541.28  6052.5 1554.39    6090 1557.14
#Mann= 13 ,-1 , 0
  2995.2     .05       0  3354.4      .1       0  3507.4     .16       0
  3559.3      .1       0  4800.1     .05       0  5014.8     .04       0
  5020.8     .05       0  5116.6      .1       0  5231.7     .05       0
  5383.4      .1       0    5602     .05       0  5859.9     .16       0
  6052.5      .1       0
#XS Ineff= 1 ,-1
 3224.64 4713.37 1518.58
Permanent Ineff=
       T
Bank Sta=4913.1,5133.9
XS Rating Curve= 0 ,0
Exp/Cntr=0.3,0.1

Type RM Length L Ch R = 1 ,15636   ,897,897,897
BEGIN DESCRIPTION:
SOUTH GRAPE CREEK 22.0
END DESCRIPTION:
XS GIS Cut Line= 3
      2801894.48     10040599.52      2802738.15      10040009.1
      2804258.67     10039583.12
#Sta/Elev= 30
  3324.3 1531.47    3588 1527.46    3640 1525.64  3755.5 1514.94  3812.7 1509.95
    3878 1508.48    3899 1503.53  3927.2 1511.02  3999.2 1511.66  4222.6 1513.77
  4383.1 1514.44    4743 1516.41  4821.7 1516.84  4910.8 1505.44  4925.5 1503.97
  4984.1  1486.1  4995.2 1485.74    4998 1485.24  5001.2 1485.74  5023.4 1487.01
  5057.5 1496.32  5143.6 1504.44  5257.9 1515.15  5301.4 1515.81  5542.5 1518.94
  5651.1 1527.46  5673.3  1527.4  5761.5 1537.94  5914.5 1544.87  5933.1    1546
#Mann= 13 ,-1 , 0
  3324.3     .05       0    3588      .1       0  3755.5     .16       0
  3999.2      .1       0  4222.6     .05       0  4383.1      .1       0
    4743     .05       0  4910.8     .16       0  4995.2     .07       0
  5001.2     .16       0  5301.4      .1       0  5651.1     .16       0
  5914.5      .1       0
#XS Ineff= 1 ,-1
 3642.61 4822.16 1516.97
Permanent Ineff=
       T
Bank Sta=4925.5,5143.6
XS Rating Curve= 0 ,0
Exp/Cntr=0.3,0.1

Type RM Length L Ch R = 1 ,14739   ,684,684,684
BEGIN DESCRIPTION:
SOUTH GRAPE CREEK 21.0
END DESCRIPTION:
XS GIS Cut Line= 4
      2801885.87     10040864.25      2803033.96     10040565.24
      2803797.17     10040689.48      2804097.74     10040447.84
#Sta/Elev= 30
  3221.4 1528.79  3287.1 1528.55  3676.7 1512.38  3864.8 1511.11  3902.9 1506.63
  3914.5 1503.28  3926.8 1502.72  3995.5 1509.84  4040.4 1511.75  4746.7 1514.35
  4802.7 1506.98  4869.3 1501.18  4888.5 1497.92    4930 1495.08  4984.2 1483.86
    4987 1483.36  4990.2 1483.86  5020.3 1484.56  5030.4 1486.76  5048.7 1493.54
  5053.8 1493.48  5070.9 1502.29  5101.3 1514.22  5131.7 1517.27    5148 1516.54
  5243.3  1515.7  5406.5 1523.73  5487.3 1522.22  5534.5 1522.35  5566.7 1522.21
#Mann= 9 ,-1 , 0
  3221.4     .05       0  3902.9      .1       0  4040.4     .05       0
    4930     .16       0  4984.2     .07       0  4990.2     .16       0
    5148     .05       0  5487.3      .1       0  5534.5     .05       0
#XS Ineff= 1 ,-1
 3549.86 4624.33 1515.17
Permanent Ineff=
       T
Bank Sta=4869.3,5070.9
XS Rating Curve= 0 ,0
Exp/Cntr=0.3,0.1

Type RM Length L Ch R = 1 ,14055   ,800,800,800
BEGIN DESCRIPTION:
Mapping XS 4b2cdbc7
END DESCRIPTION:
XS GIS Cut Line= 4
      2802141.89     10041819.13      2803213.95     10041350.38
      2804042.94     10041293.95      2804217.91     10040443.75
#Sta/Elev= 30
  3486.1 1520.51  3563.1 1521.65  3766.6  1513.3  3889.1 1510.84  3964.7 1505.43
  4028.1 1497.73    4116 1505.22  4191.8 1507.81  4498.5 1510.52  4668.7 1510.88
  4817.4 1508.26  4850.3 1508.32  4949.5 1497.64  4975.7 1492.74  4981.4 1486.67
  4991.5 1481.95  5001.2 1480.66  5021.5 1484.11  5051.6 1485.54  5071.6 1490.79
  5101.7 1488.57  5151.8 1498.28  5157.3 1499.48  5181.9 1504.89    5232 1511.05
  5312.2 1512.48    6059 1510.63  6235.8 1512.55  6324.2 1515.77  6355.1 1517.34
#Mann= 10 ,-1 , 0
  3486.1     .05       0  4498.5      .1       0  4668.7     .05       0
  4817.4      .1       0  4850.3     .05       0  4949.5     .07       0
  5151.8     .16       0  5157.3      .1       0  5312.2     .05       0
  6324.2      .1       0
#XS Ineff= 1 ,-1
 3831.91 4279.531508.215
Permanent Ineff=
       T
Bank Sta=4949.5,5151.8
XS Rating Curve= 0 ,0
Exp/Cntr=0.3,0.1

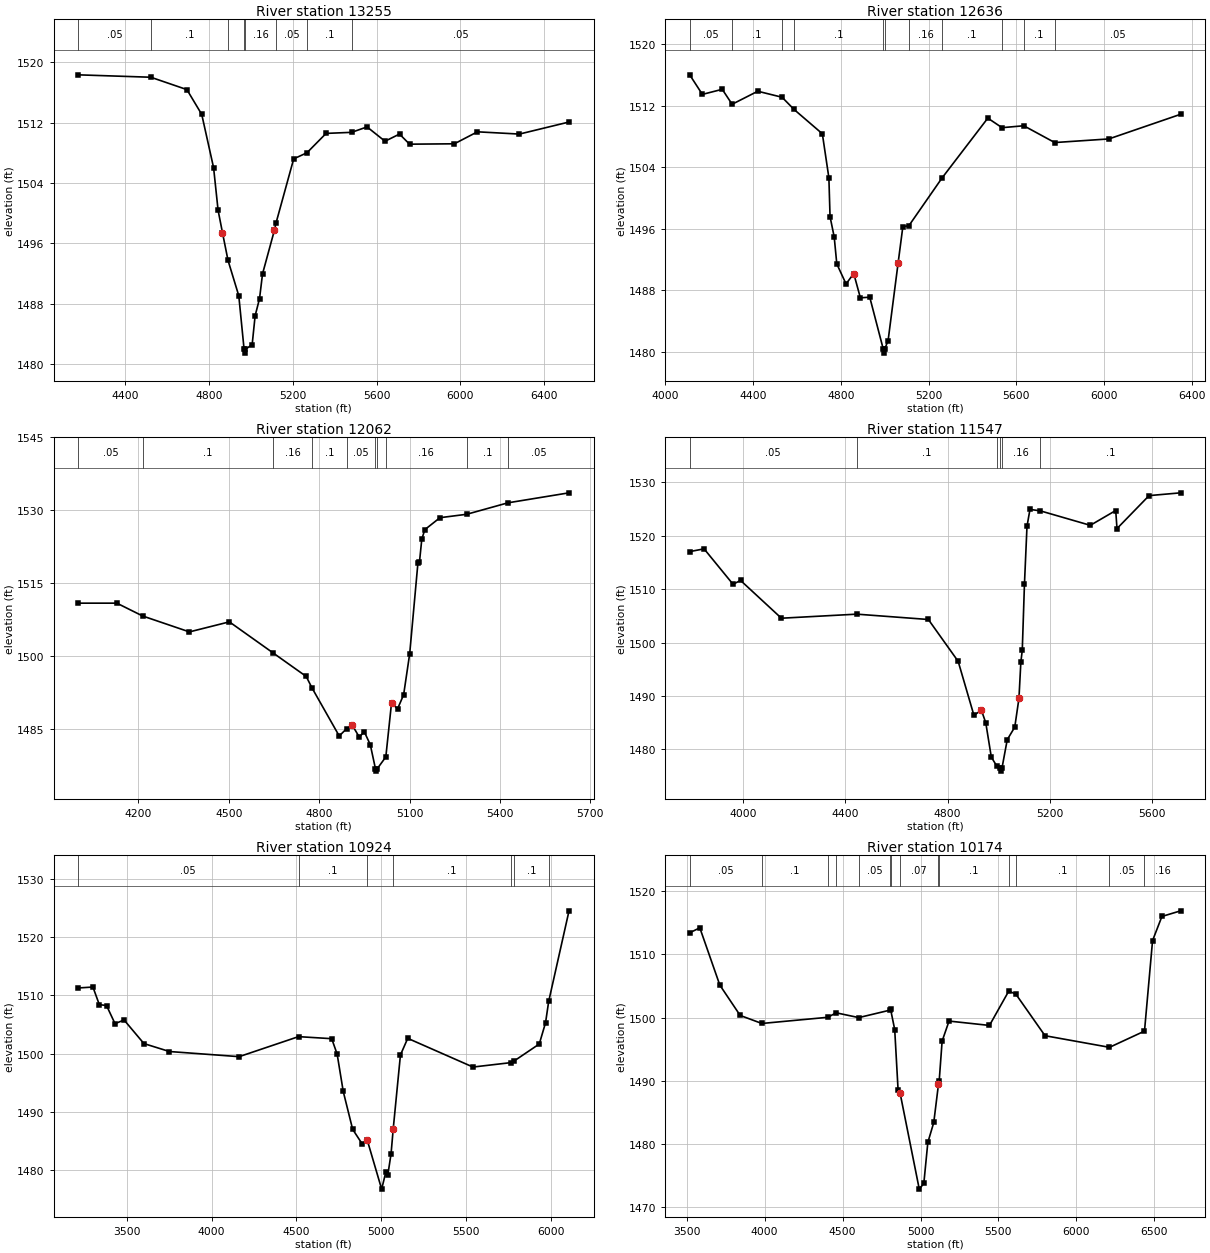
Type RM Length L Ch R = 1 ,13255   ,619,619,619
BEGIN DESCRIPTION:
SOUTH GRAPE CREEK 20.0
END DESCRIPTION:
XS GIS Cut Line= 4
      2803424.43     10042523.54      2804146.23     10041778.08
      2804362.82     10041249.11      2804371.92     10040517.01
#Sta/Elev= 30
  4176.7 1518.35  4523.6 1518.03  4695.6 1516.39  4766.4  1513.1    4823 1506.02
  4844.3  1500.4  4865.4  1497.4  4891.7 1493.74  4943.1 1489.04  4968.4 1481.93
  4971.1 1481.43  4974.4 1481.93  5006.9 1482.56    5021 1486.38  5042.1 1488.67
  5056.3 1491.94  5112.9 1497.72  5120.5 1498.67  5204.9  1507.2  5268.2 1508.01
  5359.5 1510.58  5481.2 1510.72  5554.8 1511.44  5640.5 1509.54  5709.6 1510.49
  5757.6 1509.15  5971.3  1509.2  6081.3 1510.79  6281.4 1510.49  6518.1 1512.09
#Mann= 8 ,-1 , 0
  4176.7     .05       0  4523.6      .1       0  4891.7     .16       0
  4968.4     .07       0  4974.4     .16       0  5120.5     .05       0
  5268.2      .1       0  5481.2     .05       0
Bank Sta=4865.4,5112.9
XS Rating Curve= 0 ,0
Exp/Cntr=0.3,0.1

Type RM Length L Ch R = 1 ,12636   ,574,574,574
BEGIN DESCRIPTION:
SOUTH GRAPE CREEK 19.0
END DESCRIPTION:
XS GIS Cut Line= 3
      2803684.76     10042553.11      2804625.45     10042180.39
      2804521.35     10040957.55
#Sta/Elev= 30
  4110.8 1515.99  4168.6 1513.45  4259.2 1514.11  4304.3 1512.17  4421.3 1513.86
  4532.1 1513.08  4586.6  1511.5  4715.8 1508.34  4745.6 1502.63  4750.9 1497.59
  4769.9 1494.94  4781.7 1491.45  4823.9 1488.85    4859  1490.2  4889.2 1487.05
    4932 1487.13  4993.8 1480.37  4996.6 1479.87  4999.8 1480.37  5015.7  1481.5
  5061.3 1491.56  5082.9 1496.27  5110.8 1496.42  5261.6  1502.6  5470.5 1510.37
  5535.4 1509.13  5634.5 1509.38  5775.6  1507.2  6022.5 1507.67  6349.9 1510.87
#Mann= 11 ,-1 , 0
  4110.8     .05       0  4304.3      .1       0  4532.1     .05       0
  4586.6      .1       0  4993.8     .07       0  4999.8      .1       0
  5110.8     .16       0  5261.6      .1       0  5535.4     .05       0
  5634.5      .1       0  5775.6     .05       0
Bank Sta=4859,5061.3
XS Rating Curve= 0 ,0
Exp/Cntr=0.3,0.1

Type RM Length L Ch R = 1 ,12062   ,515,515,515
BEGIN DESCRIPTION:
SOUTH GRAPE CREEK 18.0
END DESCRIPTION:
XS GIS Cut Line= 3
      2803856.35     10042523.54      2804708.28     10042695.11
      2805464.56      10042618.3
#Sta/Elev= 30
  4000.1 1510.87  4128.7 1510.87  4214.6 1508.22  4369.5 1504.95  4502.1 1507.02
  4646.8 1500.64  4757.1 1495.78  4776.1 1493.44  4866.7 1483.52  4891.2 1485.02
  4909.5 1485.79  4933.4 1483.28  4949.7 1484.41  4969.8 1481.72  4986.9 1476.78
  4989.7 1476.28  4992.9 1476.78  5021.3  1479.2  5040.2 1490.29  5060.3 1489.11
  5080.4    1492  5100.5 1500.44  5127.9 1519.18  5132.9 1519.29  5140.7 1524.04
  5150.8 1526.01    5201 1528.47  5289.6 1529.17  5426.4 1531.53  5629.3 1533.59
#Mann= 10 ,-1 , 0
  4000.1     .05       0  4214.6      .1       0  4646.8     .16       0
  4776.1      .1       0  4891.2     .05       0  4986.9    .035       0
  4992.9     .05       0  5021.3     .16       0  5289.6      .1       0
  5426.4     .05       0
Bank Sta=4909.5,5040.2
XS Rating Curve= 0 ,0
Exp/Cntr=0.3,0.1

Type RM Length L Ch R = 1 ,11547   ,623,623,623
BEGIN DESCRIPTION:
SOUTH GRAPE CREEK 17.0
END DESCRIPTION:
XS GIS Cut Line= 3
      2803566.41     10042704.17      2804873.93     10043242.56
      2805382.06     10043254.69
#Sta/Elev= 30
    3790 1517.02  3846.3 1517.54  3959.7 1510.91  3989.1 1511.63  4149.1 1504.56
  4444.3 1505.32  4724.5 1504.32  4841.2 1496.49  4902.9 1486.39  4932.2 1487.35
  4949.4 1484.97    4971 1478.57  4993.3 1476.83  5006.5 1476.45  5009.2 1475.95
  5012.5 1476.45  5033.4 1481.84  5062.8 1484.18  5079.2 1489.56  5086.7 1496.39
  5092.2 1498.55  5100.8 1510.99  5110.7 1521.76  5122.4 1524.92  5163.4 1524.64
  5358.6 1521.94  5458.1 1524.71  5463.1 1521.33  5588.7  1527.5  5712.3 1528.02
#Mann= 6 ,-1 , 0
    3790     .05       0  4444.3      .1       0  4993.3     .16       0
  5006.5     .07       0  5012.5     .16       0  5163.4      .1       0
Bank Sta=4932.2,5079.2
XS Rating Curve= 0 ,0
Exp/Cntr=0.3,0.1

Type RM Length L Ch R = 1 ,10924   ,750,750,750
BEGIN DESCRIPTION:
SOUTH GRAPE CREEK 16.0
END DESCRIPTION:
XS GIS Cut Line= 4
      2802661.21     10043499.72      2804081.15      10043600.3
      2804731.94     10043842.87      2805494.33     10043695.12
#Sta/Elev= 30
    3213 1511.27  3300.5 1511.43  3338.1 1508.42  3380.7 1508.26  3430.8 1505.15
    3484 1505.79  3601.2 1501.74  3751.6 1500.38  4162.6  1499.5  4512.6 1502.93
  4708.3 1502.58  4740.4 1499.94  4776.4 1493.53  4831.8 1487.05  4887.1 1484.59
  4917.4 1485.25  5002.8  1476.8    5028 1479.78  5039.2 1479.24  5058.3 1482.85
  5071.2 1487.18  5113.6 1499.79  5156.6 1502.64  5541.4 1497.72  5762.7 1498.47
  5784.9 1498.78  5932.2 1501.67  5969.2 1505.32  5987.6 1508.96  6107.6 1524.49
#Mann= 7 ,-1 , 0
    3213     .05       0  4512.6      .1       0  4917.4     .07       0
  5071.2      .1       0  5762.7     .05       0  5784.9      .1       0
  5987.6     .16       0
Bank Sta=4917.4,5071.2
XS Rating Curve= 0 ,0
Exp/Cntr=0.3,0.1

Type RM Length L Ch R = 1 ,10174   ,852,852,852
BEGIN DESCRIPTION:
SOUTH GRAPE CREEK 15.0
END DESCRIPTION:
XS GIS Cut Line= 3
      2802691.04      10043784.2      2804619.53      10044617.9
      2805668.51     10044608.86
#Sta/Elev= 30
  3519.1 1513.43    3584 1514.22  3712.4 1505.14  3843.1 1500.33  3982.2 1499.06
  4405.4 1500.04  4458.7 1500.75  4603.9 1499.99  4805.3 1501.18  4808.2 1501.29
  4834.5  1498.1  4856.3 1488.46  4869.4 1487.98  4992.1 1472.81  5021.3 1473.72
    5047  1480.2  5085.1 1483.37  5115.2  1489.4  5119.9 1489.95  5138.7 1496.26
  5183.1 1499.44  5442.5 1498.75  5566.3 1504.19  5611.8 1503.71    5799 1497.12
  6212.6 1495.28  6437.2 1497.85    6489  1512.2    6549 1516.02  6669.1 1516.91
#Mann= 14 ,-1 , 0
  3519.1     .05       0  3982.2      .1       0  4405.4     .05       0
  4458.7      .1       0  4603.9     .05       0  4805.3      .1       0
  4808.2     .05       0  4869.4     .07       0  5115.2     .16       0
  5119.9      .1       0  5566.3     .05       0  5611.8      .1       0
  6212.6     .05       0  6437.2     .16       0
Bank Sta=4869.4,5115.2
XS Rating Curve= 0 ,0
Exp/Cntr=0.3,0.1

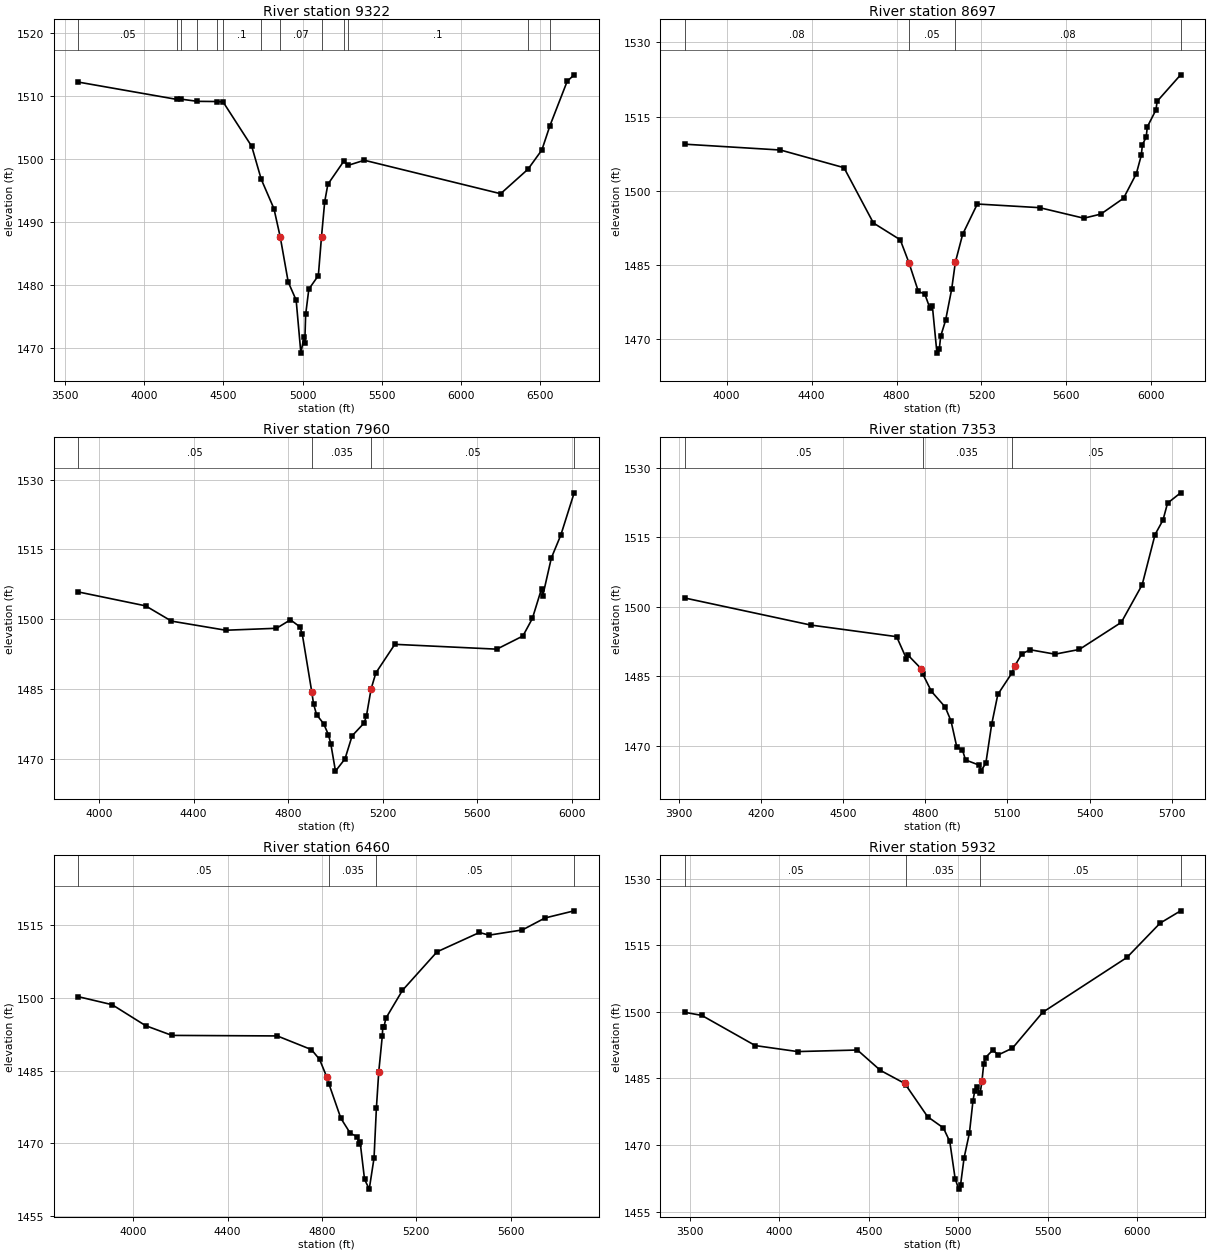
Type RM Length L Ch R = 1 ,9322    ,625,625,625
BEGIN DESCRIPTION:
SOUTH GRAPE CREEK 14.0
END DESCRIPTION:
XS GIS Cut Line= 3
      2802424.55     10044872.29      2803424.44      10045162.2
      2805512.28     10045251.22
#Sta/Elev= 30
  3583.8 1512.18  4207.7 1509.43  4234.5 1509.47    4336 1509.13  4460.3  1509.1
  4497.7 1509.04  4678.9 1501.99  4738.5  1496.8  4819.1 1492.12  4859.1 1487.59
  4909.1 1480.51  4959.2 1477.64    4989 1469.25  5008.6 1471.81  5013.6 1470.84
  5019.2 1475.37  5039.3 1479.39  5099.3 1481.53  5119.3  1487.7  5139.4 1493.22
  5159.4 1495.99  5258.9 1499.61    5287 1498.99  5389.6  1499.8  6250.4  1494.5
    6423 1498.38  6510.6 1501.42  6561.6 1505.27  6670.7 1512.31  6714.6 1513.33
#Mann= 13 ,-1 , 0
  3583.8     .05       0  4207.7      .1       0  4234.5     .05       0
    4336      .1       0  4460.3     .05       0  4497.7      .1       0
  4738.5     .05       0  4859.1     .07       0  5119.3      .1       0
  5258.9     .16       0    5287      .1       0    6423     .05       0
  6561.6      .1       0
Bank Sta=4859.1,5119.3
XS Rating Curve= 0 ,0
Exp/Cntr=0.3,0.1

Type RM Length L Ch R = 1 ,8697    ,737,737,737
BEGIN DESCRIPTION:
SOUTH GRAPE CREEK 13.0
END DESCRIPTION:
XS GIS Cut Line= 2
      2802456.63      10045251.2      2804583.43     10046214.77
#Sta/Elev= 30
    3803  1509.4  4253.5 1508.22  4552.6 1504.65  4691.2 1493.46  4817.6 1490.06
  4858.3 1485.45  4902.9 1479.61  4933.1  1479.1  4956.2 1476.36  4968.7 1476.73
  4990.4 1467.14  5001.7 1468.01  5007.9 1470.54    5031 1473.76  5059.6 1480.05
  5077.2 1485.54  5111.5 1491.18  5180.5  1497.3  5474.1 1496.56    5682 1494.43
  5762.2 1495.26    5869 1498.46  5929.4 1503.45  5952.5 1507.13    5958 1509.31
  5975.6 1510.81  5981.1 1512.91  6021.8 1516.34  6027.2 1518.07  6137.9 1523.43
#Mann= 4 ,-1 , 0
    3803     .08       0  4858.3     .05       0  5077.2     .08       0
  6137.9      .1       0
Bank Sta=4858.3,5077.2
XS Rating Curve= 0 ,0
Exp/Cntr=0.3,0.1

Type RM Length L Ch R = 1 ,7960    ,607,607,607
BEGIN DESCRIPTION:
SOUTH GRAPE CREEK 12.0
END DESCRIPTION:
XS GIS Cut Line= 3
      2802312.16     10046014.14       2803045.8     10046410.54
      2804304.59       10046319.
#Sta/Elev= 30
    3913 1505.83  4197.4 1502.84  4306.8 1499.56  4536.2  1497.6  4750.7 1498.02
  4809.7 1499.84  4849.8 1498.32  4859.8 1496.72    4900 1484.29  4907.3 1481.77
    4920 1479.46  4950.1  1477.5  4970.1 1475.15  4980.2 1473.21    5000 1467.31
  5040.3 1469.95  5070.4  1474.9  5120.5 1477.62  5130.6 1479.08  5150.6 1484.98
  5170.7 1488.42  5250.9 1494.57    5682 1493.53  5792.3 1496.36  5832.4 1500.13
  5871.2 1506.54  5876.2 1504.98  5912.6 1513.14  5952.7 1518.07    6009 1527.14
#Mann= 4 ,-1 , 0
    3913     .05       0    4900    .035       0  5150.6     .05       0
    6009     .16       0
Bank Sta=4900,5150.6
XS Rating Curve= 0 ,0
Exp/Cntr=0.3,0.1

Type RM Length L Ch R = 1 ,7353    ,893,893,893
BEGIN DESCRIPTION:
Mapping XS 55053424
END DESCRIPTION:
XS GIS Cut Line= 5
      2802593.51     10046796.63      2803412.92     10046921.63
      2803808.76     10046782.74      2803892.09     10046609.13
       2804232.4     10046463.28
#Sta/Elev= 30
  3921.5 1501.89  4381.7 1496.06  4695.3 1493.56  4730.9 1488.84    4736 1489.63
    4786 1486.59  4791.3 1485.45  4822.3 1481.78  4872.8 1478.39    4894 1475.39
  4915.3 1469.73  4935.7 1469.16    4947    1467  4997.7 1465.86  5002.8 1464.59
  5021.2  1466.3  5042.4 1474.65    5065 1481.12  5116.4 1485.73  5127.2  1487.3
  5152.7 1489.85  5183.1 1490.74  5273.7 1489.79  5362.5  1490.8    5516 1496.64
  5592.2 1504.74  5639.3 1515.56  5668.3 1518.68  5684.9 1522.32  5732.7 1524.55
#Mann= 3 ,-1 , 0
  3921.5     .05       0  4791.3    .035       0  5116.4     .05       0
Bank Sta=4786,5127.2
XS Rating Curve= 0 ,0
Exp/Cntr=0.3,0.1

Type RM Length L Ch R = 1 ,6460    ,528,528,528
BEGIN DESCRIPTION:
Mapping XS 89858ec7
END DESCRIPTION:
XS GIS Cut Line= 4
      2802912.89     10047116.06      2803836.54     10047574.41
      2804260.15     10047532.74      2804843.51     10047254.95
#Sta/Elev= 30
  3766.9 1500.23  3910.3 1498.58  4052.2 1494.26  4163.9 1492.25  4610.6 1492.14
  4755.5 1489.32  4789.9 1487.32  4820.1 1483.74  4830.1  1482.2  4880.3 1475.17
  4920.5 1472.06  4950.7 1471.36  4956.9 1469.79    4962 1470.28  4980.8 1462.58
  5000.7 1460.56    5021 1466.95  5031.1 1477.32  5041.1 1484.78  5056.2 1492.18
  5058.2 1494.07  5063.3 1494.05  5071.3 1495.79  5141.6 1501.54  5288.3 1509.48
  5468.3 1513.47  5508.2 1512.91    5650 1513.99  5746.3 1516.46  5869.8 1517.93
#Mann= 4 ,-1 , 0
  3766.9     .05       0  4830.1    .035       0  5031.1     .05       0
  5869.8     .05       0
Bank Sta=4820.1,5041.1
XS Rating Curve= 0 ,0
Exp/Cntr=0.3,0.1

Type RM Length L Ch R = 1 ,5932    ,277,277,277
BEGIN DESCRIPTION:
Mapping XS b68a766f
END DESCRIPTION:
XS GIS Cut Line= 4
      2802885.17     10047213.31       2804003.2     10048067.46
      2804426.81     10048081.35      2805183.62     10047518.95
#Sta/Elev= 30
  3470.6 1499.87  3565.5 1499.18  3864.9 1492.38  4101.6 1491.03  4436.2 1491.38
    4565 1486.79  4700.1 1483.87    4708 1483.44  4828.9 1476.36  4917.1 1473.84
  4952.9 1470.78  4982.9 1462.42  5002.6 1460.05  5012.9 1460.89  5032.9 1467.08
  5062.9 1472.72  5082.9 1480.01  5092.9 1482.22    5103 1482.99    5123 1481.66
    5133 1484.43    5143 1488.34    5153 1489.69    5193 1491.34  5224.8  1490.3
  5303.6  1491.8  5472.6 1499.87    5944 1512.23  6129.6 1519.96  6244.3 1522.73
#Mann= 4 ,-1 , 0
  3470.6     .05       0    4708    .035       0    5123     .05       0
  6244.3      .1       0
Bank Sta=4700.1,5133
XS Rating Curve= 0 ,0
Exp/Cntr=0.3,0.1

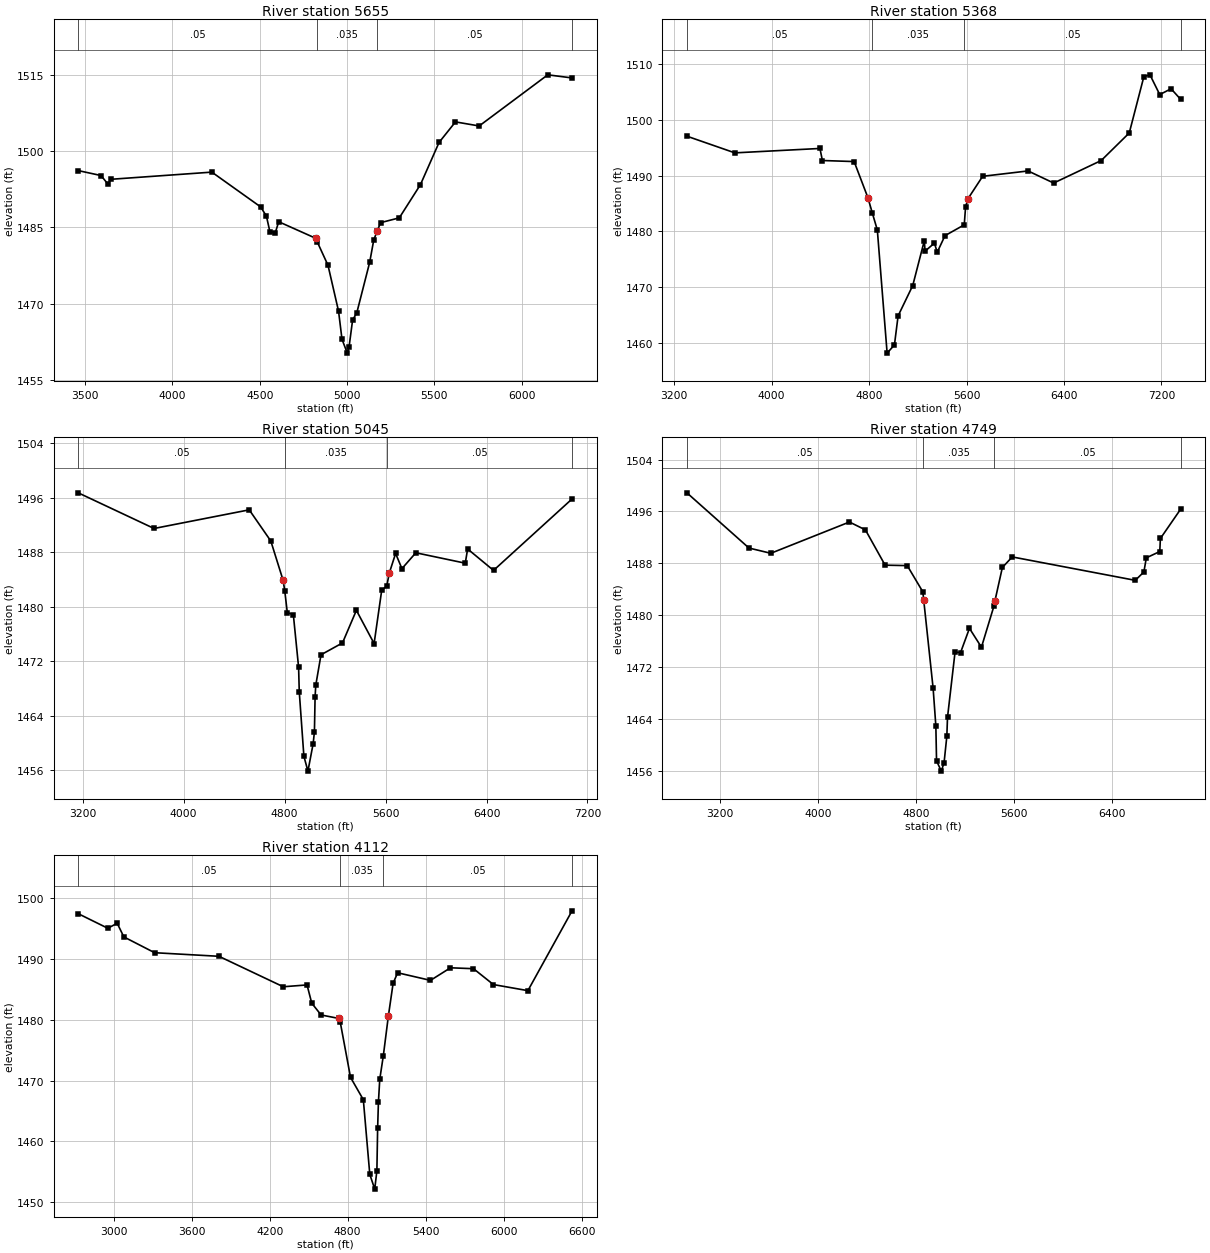
Type RM Length L Ch R = 1 ,5655    ,287,287,287
BEGIN DESCRIPTION:
Mapping XS be224509
END DESCRIPTION:
XS GIS Cut Line= 3
      2802649.07     10048532.74      2804371.26     10048310.52
      2805253.21     10047664.68
#Sta/Elev= 30
  3459.9 1496.13  3590.4 1495.16  3630.7 1493.45  3646.6 1494.42  4225.6 1495.83
    4505    1489  4538.2 1487.18  4558.3  1484.1  4589.4 1483.95  4608.7 1486.08
  4822.6  1482.8  4830.6 1482.04  4891.1 1477.52  4951.6  1468.5  4971.3 1462.98
  5001.7 1460.26  5012.1 1461.56  5032.2 1466.79  5055.7 1468.13  5130.1 1478.13
  5153.2 1482.49  5173.4 1484.29  5192.4  1485.9  5299.6 1486.84  5420.8 1493.37
  5527.6 1501.67  5621.5  1505.7  5757.4  1504.9  6150.4 1514.95  6289.5 1514.34
#Mann= 4 ,-1 , 0
  3459.9     .05       0  4830.6    .035       0  5173.4     .05       0
  6289.5      .1       0
Bank Sta=4822.6,5173.4
XS Rating Curve= 0 ,0
Exp/Cntr=0.3,0.1

Type RM Length L Ch R = 1 ,5368    ,323,323,323
BEGIN DESCRIPTION:
Mapping XS 65c8eb7d
END DESCRIPTION:
XS GIS Cut Line= 4
      2802649.08     10048643.85      2804593.48     10048518.85
      2805454.59     10048414.68      2806690.67     10048386.91
#Sta/Elev= 30
  3305.7 1497.08  3699.1 1494.09  4397.3 1494.88  4417.4 1492.72  4677.9 1492.53
  4790.7 1486.07  4828.2 1483.23  4868.3 1480.26  4948.6 1458.19  5008.6 1459.66
  5038.7 1464.87  5158.9 1470.31  5254.1 1478.37  5259.6 1476.46  5336.5 1477.91
  5359.9 1476.28  5423.5 1479.25  5581.5 1481.19  5592.4 1484.39  5611.7 1485.86
  5732.6 1489.89  6105.3 1490.85  6315.4 1488.68  6705.5 1492.72  6935.6 1497.66
  7055.6 1507.77  7105.6 1508.08  7185.6 1504.54  7278.7 1505.58  7357.9 1503.67
#Mann= 4 ,-1 , 0
  3305.7     .05       0  4828.2    .035       0  5581.5     .05       0
  7357.9      .1       0
Bank Sta=4790.7,5611.7
XS Rating Curve= 0 ,0
Exp/Cntr=0.3,0.1

Type RM Length L Ch R = 1 ,5045    ,296,296,296
BEGIN DESCRIPTION:
Mapping XS ce9c6c26
END DESCRIPTION:
XS GIS Cut Line= 5
      2802781.02     10048921.62      2804468.48     10048741.07
      2804697.65     10048685.52      2805412.92     10048636.91
      2806675.19     10048581.42
#Sta/Elev= 30
  3164.5 1496.75  3765.4 1491.51  4519.6 1494.25  4690.6 1489.67  4787.9  1483.9
  4801.2 1482.35  4821.3 1479.14  4869.1 1478.86  4910.9 1471.11  4916.1 1467.52
  4952.7 1458.04  4984.8 1455.85  5026.2 1459.89  5036.3 1461.64  5041.5 1466.74
  5046.8 1468.46  5088.4 1472.95  5258.6 1474.69  5368.8 1479.48  5509.2  1474.6
  5569.3 1482.41  5609.4 1483.05  5629.4 1484.95  5679.6 1487.84  5729.7 1485.61
  5839.9 1487.94  6231.7 1486.41  6250.3  1488.5  6455.7 1485.35  7077.8 1495.85
#Mann= 4 ,-1 , 0
  3164.5     .05       0  4801.2    .035       0  5609.4     .05       0
  7077.8     .05       0
Bank Sta=4787.9,5629.4
XS Rating Curve= 0 ,0
Exp/Cntr=0.3,0.1

Type RM Length L Ch R = 1 ,4749    ,637,637,637
BEGIN DESCRIPTION:
Mapping XS 4178ded1
END DESCRIPTION:
XS GIS Cut Line= 5
      2802836.56     10049213.29      2804114.31     10048970.24
      2804704.59     10048921.63      2805079.59     10048734.13
      2806787.95     10048595.24
#Sta/Elev= 30
  2930.6 1498.87  3436.5 1490.36  3614.6 1489.55  4255.5 1494.37  4385.9 1493.16
  4546.5 1487.72  4727.1 1487.65  4854.1 1483.61  4861.4 1482.32    4938 1468.75
  4960.3 1462.94  4965.9 1457.55  5004.8 1455.97  5027.4 1457.29  5049.8 1461.34
  5055.3 1464.26  5116.8 1474.32  5161.6 1474.24  5234.2 1477.98    5332 1475.07
  5435.1 1481.49  5442.3 1482.24  5502.5 1487.36  5582.8 1488.99  6586.1 1485.38
  6656.3 1486.67  6676.4 1488.85    6786 1489.82    6791 1491.83  6956.8 1496.37
#Mann= 4 ,-1 , 0
  2930.6     .05       0  4854.1    .035       0  5435.1     .05       0
  6956.8     .05       0
Bank Sta=4861.4,5442.3
XS Rating Curve= 0 ,0
Exp/Cntr=0.3,0.1

Type RM Length L Ch R = 1 ,4112    ,0,0,0
BEGIN DESCRIPTION:
SOUTH GRAPE CREEK 11.0
END DESCRIPTION:
XS GIS Cut Line= 4
      2803246.26     10049657.74      2805176.81     10049220.24
      2805989.31     10048789.68      2806871.29     10048609.12
#Sta/Elev= 30
    2727 1497.45  2954.8 1495.05  3026.6 1495.88  3077.9 1493.63  3314.8 1491.03
  3809.7 1490.44  4304.6 1485.43  4487.4 1485.73  4523.6 1482.73  4595.4 1480.79
  4733.9 1480.21  4742.3 1479.68  4821.9 1470.53  4920.5 1466.85  4970.2 1454.57
  5008.2 1452.14  5024.8 1455.16  5030.5 1462.13  5036.6 1466.44  5046.8 1470.19
  5074.5 1474.11  5112.8 1480.56  5149.7 1486.01  5184.5 1487.73  5437.1 1486.48
  5591.1 1488.55  5768.1  1488.4  5921.2 1485.79  6186.6 1484.79  6526.3 1497.92
#Mann= 4 ,-1 , 0
    2727     .05       0  4742.3    .035       0  5074.5     .05       0
  6526.3     .05       0
Bank Sta=4733.9,5112.8
XS Rating Curve= 0 ,0
Exp/Cntr=0.3,0.1

Chan Stop Cuts=-1
Use User Specified Reach Order=0
Composite Channel Slope=5