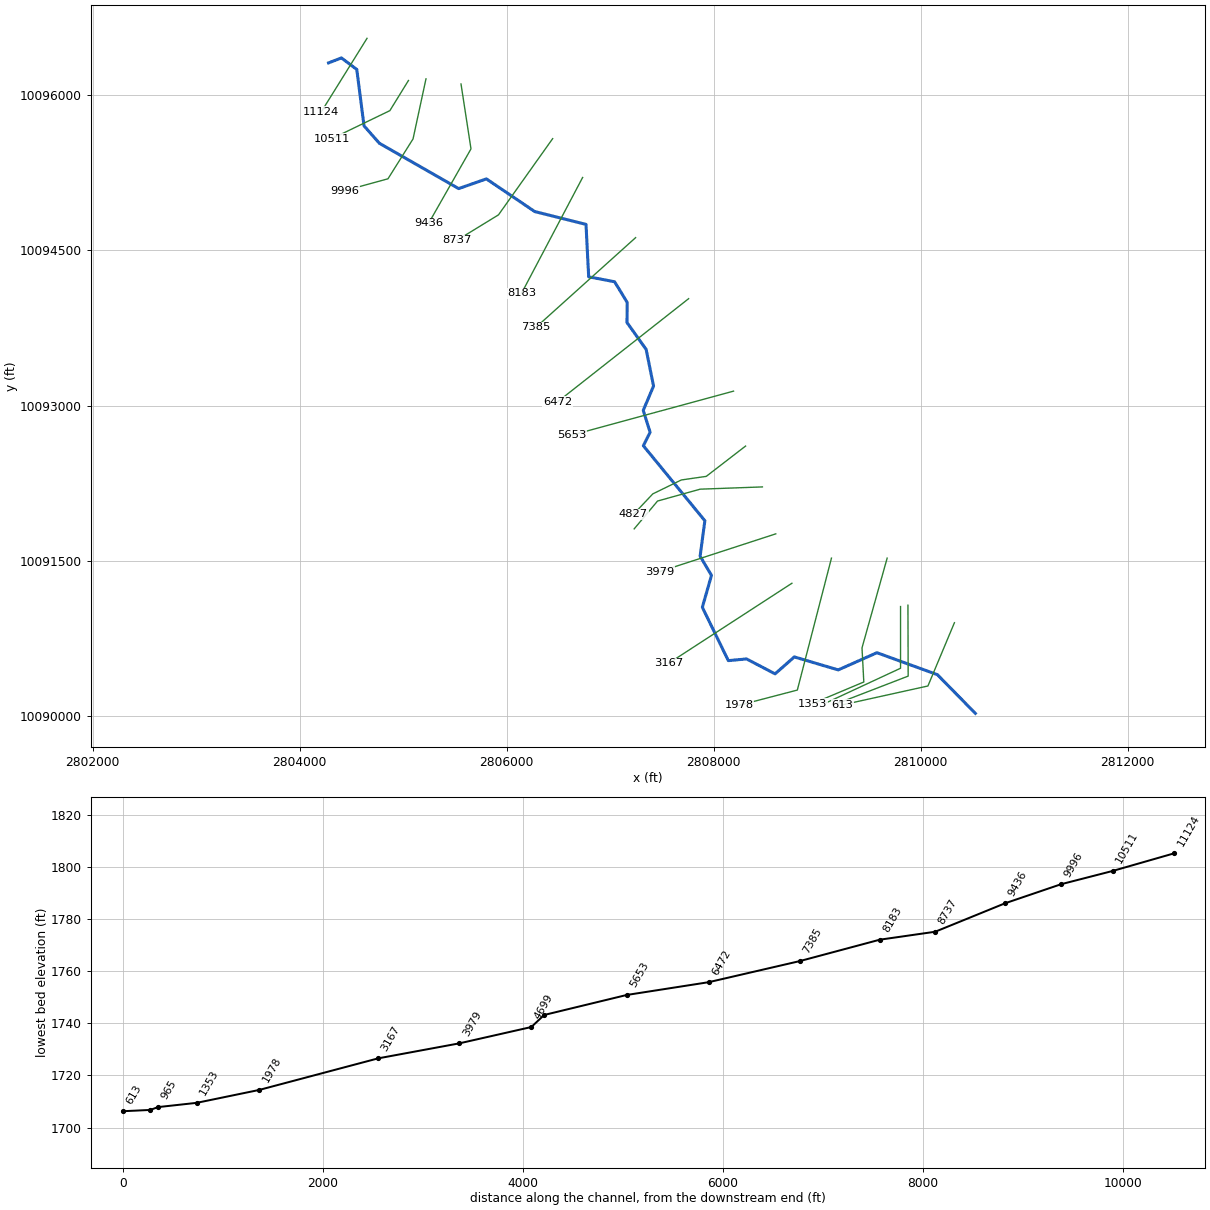
--- SPRING CREEK 2.prj (project) ---

Proj Title=SPRING CREEK 2 Base Level Engineering
Current Plan=p01
Default Exp/Contr=0.3,0.1
English Units
Geom File=g01
Flow File=f01
Plan File=p01
Y Axis Title=Elevation
X Axis Title(PF)=Main Channel Distance
X Axis Title(XS)=Station
BEGIN DESCRIPTION:
SPRING CREEK 2
END DESCRIPTION:
DSS Export Rating Curves= 0
DSS Export Rating Curve Sorted= 0
DSS Export Volume Flow Curves= 0
DXF OffsetX= 0
DXF OffsetY= 0
DXF ScaleX= 1
DXF ScaleY= 10

--- SPRING CREEK 2.p01 (plan) ---

Plan Title=Multiple Run
Short Identifier=Multiple
Geom File=g01
Flow File=f01
Subcritical Flow
K Sum by GR= 0
Std Step Tol= 0.01
Critical Tol= 0.01
Num of Std Step Trials= 20
Max Error Tol= 0.3
Flow Tol Ratio= 0.001
Split Flow NTrial= 30
Split Flow Tol= 0.02
Split Flow Ratio= 0.02
Log Output Level= 0
Friction Slope Method= 1
Unsteady Friction Slope Method= 2
Unsteady Bridges Friction Slope Method= 1
Parabolic Critical Depth
Global Vel Dist=  1 , 1 , 1
Global Log Level= 0
CheckData=True
Encroach Param= -1, 0, 0, 0
BEGIN DESCRIPTION:
Multiple Run
END DESCRIPTION:

--- SPRING CREEK 2.f01 (steady flow) ---

Flow Title=Multiple
Program Version=4.10
Number of Profiles= 7
Profile Names=10-year,25-year,50-year,1pct_min,100-year,1pct_plu,500-year
River Rch & RM=SPRING CREEK 2,Reach-1         ,11124
    1148    1668    2120    1968    2662    3600    4215
Boundary for River Rch & Prof#=SPRING CREEK 2,Reach-1         , 1
Up Type= 0
Dn Type= 3
Dn Slope=0.0052
Boundary for River Rch & Prof#=SPRING CREEK 2,Reach-1         , 2
Up Type= 0
Dn Type= 3
Dn Slope=0.0052
Boundary for River Rch & Prof#=SPRING CREEK 2,Reach-1         , 3
Up Type= 0
Dn Type= 3
Dn Slope=0.0052
Boundary for River Rch & Prof#=SPRING CREEK 2,Reach-1         , 4
Up Type= 0
Dn Type= 3
Dn Slope=0.0052
Boundary for River Rch & Prof#=SPRING CREEK 2,Reach-1         , 5
Up Type= 0
Dn Type= 3
Dn Slope=0.0052
Boundary for River Rch & Prof#=SPRING CREEK 2,Reach-1         , 6
Up Type= 0
Dn Type= 3
Dn Slope=0.0052
Boundary for River Rch & Prof#=SPRING CREEK 2,Reach-1         , 7
Up Type= 0
Dn Type= 3
Dn Slope=0.0052
DSS Import GetInterval= 0
DSS Import GetPeak= 0
DSS Import FillOption= 0

--- SPRING CREEK 2.g01 (geometry) ---

Geom Title=Existing Conditions
Program Version=4.10

River Reach=SPRING CREEK 2  ,Reach-1
Reach XY= 30
      2804278.47     10096313.73      2804402.46      10096361.8
      2804551.13     10096250.18      2804621.01     10095704.84
      2804769.52     10095536.27      2805535.53     10095098.09
      2805803.42     10095192.03      2806270.61     10094876.11
        2806766.     10094752.12      2806791.85     10094245.17
      2807042.22     10094197.47      2807164.54     10093996.89
       2807162.1     10093803.06      2807347.17     10093543.04
      2807418.73     10093188.95      2807319.14     10092953.31
       2807385.5     10092742.17      2807320.08     10092611.79
      2807914.51      10091886.7      2807868.67     10091543.91
      2807978.42     10091357.88      2807890.16     10091049.58
      2808141.18     10090533.67      2808317.27     10090550.27
      2808593.08     10090405.79      2808779.08     10090569.67
      2809203.25     10090444.06       2809577.3     10090610.35
       2810161.1     10090398.18      2810528.47     10090023.73

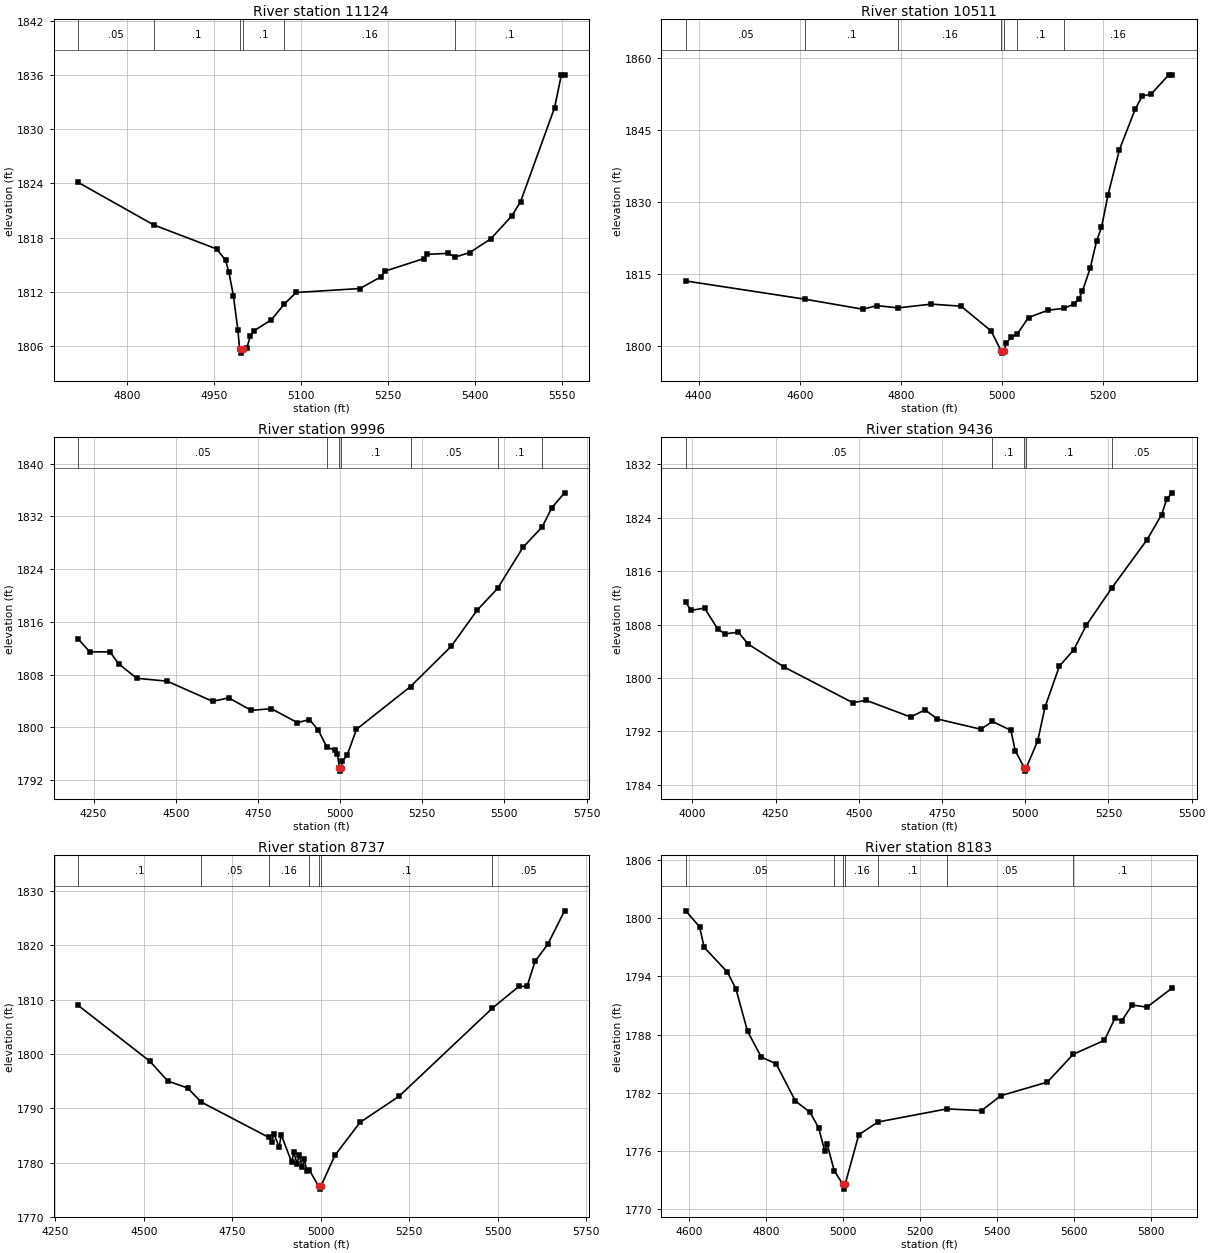
Type RM Length L Ch R = 1 ,11124   ,613,613,613
BEGIN DESCRIPTION:
SPRING CREEK 2 18.0
END DESCRIPTION:
XS GIS Cut Line= 2
      2804650.02     10096551.12      2804207.34     10095839.36
#Sta/Elev= 30
  4715.8 1824.14  4846.5  1819.4  4954.8 1816.73  4970.1 1815.49    4976 1814.13
  4983.6 1811.56  4991.4 1807.72  4994.3 1805.67    4997 1805.17  5000.3 1805.67
  5006.7 1805.71  5012.6 1807.04  5018.9 1807.64  5049.2 1808.87  5070.8 1810.59
  5091.7  1811.9  5201.5 1812.34  5238.1 1813.65    5244 1814.25  5311.3 1815.66
  5317.2 1816.13  5353.8 1816.25  5365.1 1815.83  5390.4 1816.32    5427 1817.86
  5463.6 1820.43  5478.2 1821.98  5536.8 1832.41  5548.5 1836.06    5554 1836.06
#Mann= 6 ,-1 , 0
  4715.8     .05       0  4846.5      .1       0  4994.3     .07       0
  5000.3      .1       0  5070.8     .16       0  5365.1      .1       0
Bank Sta=4994.3,5000.3
XS Rating Curve= 0 ,0
Exp/Cntr=0.3,0.1

Type RM Length L Ch R = 1 ,10511   ,515,515,515
BEGIN DESCRIPTION:
SPRING CREEK 2 17.0
END DESCRIPTION:
XS GIS Cut Line= 3
      2805050.47     10096143.61      2804870.77     10095851.94
      2804312.18     10095581.73
#Sta/Elev= 30
  4374.4 1813.51    4611 1809.69  4724.7 1807.61  4752.9 1808.36  4794.8 1807.88
  4860.3 1808.67  4919.5 1808.23  4978.8 1803.06  4998.4 1798.93  5001.1 1798.43
  5004.4 1798.93  5008.4 1800.45  5018.4 1801.71  5030.2 1802.37  5052.8 1805.87
  5091.7 1807.41  5122.2 1807.77  5142.5 1808.67  5152.8  1809.8  5159.5  1811.4
    5175 1816.21  5187.6  1821.9  5197.2 1824.68  5210.2 1831.54  5232.8 1840.97
  5263.9  1849.4    5278 1852.17    5295 1852.51  5330.5 1856.58  5337.5 1856.51
#Mann= 7 ,-1 , 0
  4374.4     .05       0    4611      .1       0  4794.8     .16       0
  4998.4     .07       0  5004.4     .16       0  5030.2      .1       0
  5122.2     .16       0
Bank Sta=4998.4,5004.4
XS Rating Curve= 0 ,0
Exp/Cntr=0.3,0.1

Type RM Length L Ch R = 1 ,9996    ,560,560,560
BEGIN DESCRIPTION:
SPRING CREEK 2 16.0
END DESCRIPTION:
XS GIS Cut Line= 4
      2805219.74     10096159.25      2805094.73      10095578.5
      2804852.55     10095193.08      2804436.34     10095078.63
#Sta/Elev= 30
  4202.2 1813.44  4238.5 1811.44  4299.9 1811.44  4326.3 1809.61  4381.7 1807.43
  4474.3 1806.99    4612 1803.94  4661.4 1804.46  4729.5 1802.57  4790.9 1802.82
  4870.3  1800.7  4906.8 1801.18  4933.9 1799.55    4960 1796.96  4985.8 1796.52
  4991.7    1796  4998.1 1793.85  5000.8 1793.35  5004.1 1793.85    5007 1794.82
  5022.3 1795.86  5049.9 1799.69  5214.4 1806.18  5338.4 1812.29  5417.6 1817.79
  5479.1 1821.05  5556.4 1827.28  5615.3 1830.41  5644.8 1833.33  5683.1 1835.56
#Mann= 7 ,-1 , 0
  4202.2     .05       0    4960      .1       0  4998.1     .07       0
  5004.1      .1       0  5214.4     .05       0  5479.1      .1       0
  5615.3     .16       0
Bank Sta=4998.1,5004.1
XS Rating Curve= 0 ,0
Exp/Cntr=0.3,0.1

Type RM Length L Ch R = 1 ,9436    ,699,699,699
BEGIN DESCRIPTION:
SPRING CREEK 2 15.0
END DESCRIPTION:
XS GIS Cut Line= 3
      2805558.27     10096109.78      2805654.63     10095482.15
      2805245.77     10094763.38
#Sta/Elev= 30
  3980.2 1811.33  3996.4 1810.14  4036.9 1810.47  4076.3 1807.35  4097.6 1806.61
  4138.1 1806.87  4168.4 1805.06  4276.3 1801.63  4482.1  1796.3  4522.5 1796.65
  4655.8 1794.15    4699 1795.22  4736.5 1793.85  4866.5 1792.32  4901.6 1793.48
  4957.1 1792.15    4970 1789.11  4997.3 1786.54    5000 1786.04  5003.3 1786.54
  5037.8 1790.61  5059.4 1795.62  5102.6 1801.77  5145.9 1804.22  5183.3 1807.89
  5259.7 1813.46  5366.4 1820.75  5409.6 1824.46  5425.5 1826.84  5442.1 1827.75
#Mann= 5 ,-1 , 0
  3980.2     .05       0  4901.6      .1       0  4997.3     .07       0
  5003.3      .1       0  5259.7     .05       0
Bank Sta=4997.3,5003.3
XS Rating Curve= 0 ,0
Exp/Cntr=0.3,0.1

Type RM Length L Ch R = 1 ,8737    ,554,554,554
BEGIN DESCRIPTION:
SPRING CREEK 2 14.0
END DESCRIPTION:
XS GIS Cut Line= 3
      2806443.71     10095581.13      2805920.25     10094844.13
      2805518.24     10094597.73
#Sta/Elev= 30
  4313.8 1808.97  4517.2 1798.65  4567.7 1795.02  4624.2 1793.72  4661.9 1791.16
    4853 1784.65  4861.6 1783.84  4867.8 1785.31  4882.5 1782.86  4888.7  1785.1
  4918.2 1780.06  4924.3 1782.01    4933 1779.74  4939.1 1781.44  4947.7 1779.12
  4953.9 1780.68  4960.7 1778.48  4968.4 1778.57  4994.5 1775.62  4997.2 1775.12
  5000.5 1775.62    5040 1781.31  5111.3 1787.41  5221.8 1792.22  5485.3 1808.42
    5560 1812.41  5583.5 1812.46  5605.9 1817.03  5642.1 1820.21  5689.3 1826.33
#Mann= 7 ,-1 , 0
  4313.8      .1       0  4661.9     .05       0    4853     .16       0
  4968.4      .1       0  4994.5     .07       0  5000.5      .1       0
  5485.3     .05       0
Bank Sta=4994.5,5000.5
XS Rating Curve= 0 ,0
Exp/Cntr=0.3,0.1

Type RM Length L Ch R = 1 ,8183    ,798,798,798
BEGIN DESCRIPTION:
SPRING CREEK 2 10.0
END DESCRIPTION:
XS GIS Cut Line= 2
      2806733.38     10095205.68      2806144.06      10094087.7
#Sta/Elev= 30
    4592 1800.76  4628.1 1799.11  4639.9    1797  4700.3 1794.44  4722.3 1792.73
  4752.5 1788.35  4788.4 1785.68  4826.8 1784.99  4876.8 1781.16  4914.9 1779.99
    4937 1778.41  4953.3 1775.98    4959 1776.77  4977.5 1773.98    5000 1772.57
  5002.8 1772.07    5006 1772.57  5041.4 1777.67  5091.2 1778.99  5270.1 1780.34
  5360.5 1780.17  5410.2  1781.7  5531.1  1783.1  5598.2 1785.97  5679.4 1787.41
  5707.3 1789.74  5723.7 1789.38  5751.4 1791.05  5789.8 1790.83  5855.8 1792.82
#Mann= 7 ,-1 , 0
    4592     .05       0  4977.5     .16       0    5000     .07       0
    5006     .16       0  5091.2      .1       0  5270.1     .05       0
  5598.2      .1       0
Bank Sta=5000,5006
XS Rating Curve= 0 ,0
Exp/Cntr=0.3,0.1

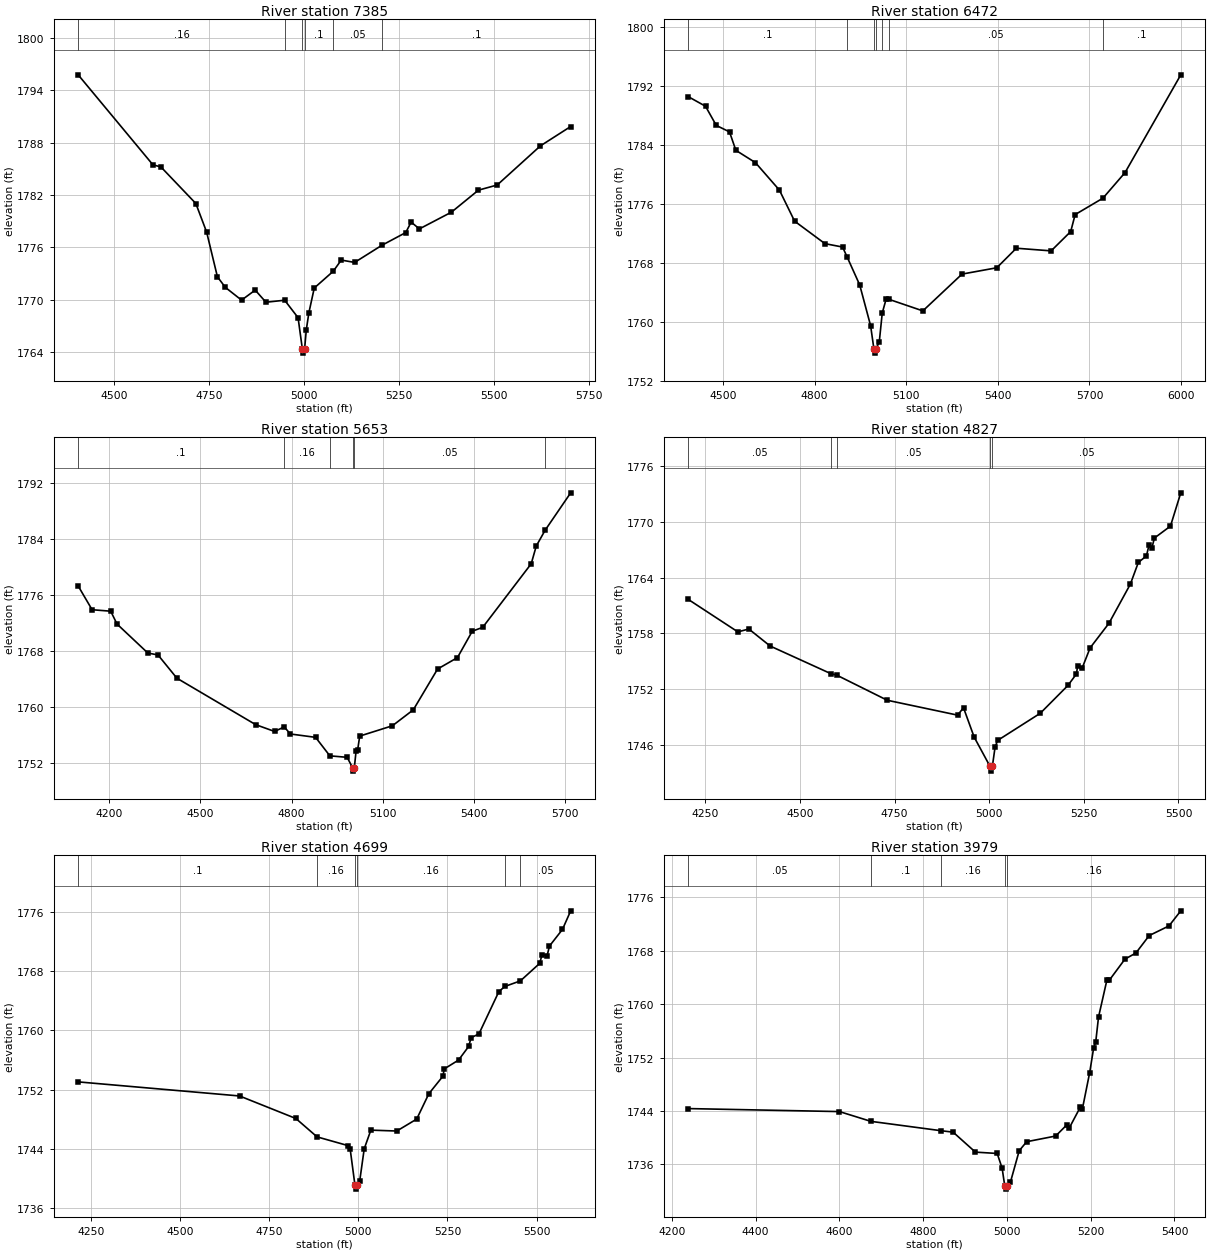
Type RM Length L Ch R = 1 ,7385    ,913,913,913
BEGIN DESCRIPTION:
SPRING CREEK 2 9.0
END DESCRIPTION:
XS GIS Cut Line= 2
      2807245.54     10094624.09      2806282.74      10093756.7
#Sta/Elev= 30
  4406.4 1795.76  4603.1 1785.45  4624.1 1785.21    4716 1781.02  4744.4 1777.75
  4772.8 1772.62  4793.7 1771.41  4836.3 1769.95  4872.2  1771.1  4900.5 1769.71
  4949.7 1769.94    4985 1767.94  4996.2 1764.38    4999 1763.88  5002.2 1764.38
  5006.7 1766.57  5013.4  1768.5  5027.6 1771.34  5077.6 1773.26  5098.6 1774.54
  5133.8 1774.27  5205.4 1776.23  5268.3 1777.69  5282.5 1778.89  5304.2 1778.11
  5388.6 1780.03  5459.6 1782.55    5509 1783.14  5622.6 1787.62  5702.3 1789.84
#Mann= 6 ,-1 , 0
  4406.4     .16       0  4949.7      .1       0  4996.2     .07       0
  5002.2      .1       0  5077.6     .05       0  5205.4      .1       0
Bank Sta=4996.2,5002.2
XS Rating Curve= 0 ,0
Exp/Cntr=0.3,0.1

Type RM Length L Ch R = 1 ,6472    ,819,819,819
BEGIN DESCRIPTION:
SPRING CREEK 2 8.0
END DESCRIPTION:
XS GIS Cut Line= 2
      2807757.68      10094033.8      2806490.32     10093035.53
#Sta/Elev= 30
  4385.9 1790.56  4442.4 1789.26  4477.6 1786.66    4521 1785.78  4541.8 1783.28
  4605.9 1781.61  4684.5 1777.88  4734.2 1773.67  4833.6 1770.62  4891.4 1770.16
  4906.6 1768.78  4947.5 1765.02  4983.2 1759.49  4994.2 1756.27  4996.9 1755.77
  5000.2 1756.27  5011.6 1757.31  5021.3 1761.21  5034.1 1763.11  5043.1 1763.07
  5154.3  1761.5  5282.6 1766.49  5396.5 1767.35  5460.6    1770  5574.5 1769.64
  5638.6 1772.26  5653.1 1774.56  5744.2 1776.79  5816.6 1780.26  5999.2 1793.52
#Mann= 7 ,-1 , 0
  4385.9      .1       0  4906.6     .16       0  4994.2     .07       0
  5000.2     .16       0  5021.3      .1       0  5043.1     .05       0
  5744.2      .1       0
Bank Sta=4994.2,5000.2
XS Rating Curve= 0 ,0
Exp/Cntr=0.3,0.1

Type RM Length L Ch R = 1 ,5653    ,826,826,826
BEGIN DESCRIPTION:
SPRING CREEK 2 7.0
END DESCRIPTION:
XS GIS Cut Line= 2
      2808191.66     10093139.69      2806629.22     10092714.36
#Sta/Elev= 30
  4098.4 1777.29  4144.2  1773.9  4205.4 1773.69  4226.1 1771.86  4327.5 1767.72
  4360.8 1767.45    4423 1764.13  4682.1  1757.5  4744.2 1756.53  4775.8 1757.18
  4796.1 1756.17    4879 1755.69  4925.9 1753.05  4982.8 1752.84  5000.4 1751.37
  5003.1 1750.87  5006.4 1751.37  5012.2 1753.78  5017.3 1753.92  5024.1 1755.87
  5131.4 1757.34  5200.3 1759.62  5280.1 1765.44  5345.4 1767.07  5394.2 1770.84
  5428.3 1771.38  5587.9 1780.46  5604.5 1782.99  5633.6 1785.24  5717.7 1790.58
#Mann= 6 ,-1 , 0
  4098.4      .1       0  4775.8     .16       0  4925.9     .05       0
  5000.4    .035       0  5006.4     .05       0  5633.6      .1       0
Bank Sta=5000.4,5006.4
XS Rating Curve= 0 ,0
Exp/Cntr=0.3,0.1

Type RM Length L Ch R = 1 ,4827    ,128,128,128
BEGIN DESCRIPTION:
SPRING CREEK 2 6.0
END DESCRIPTION:
XS GIS Cut Line= 5
       2808307.8     10092608.42      2807928.07     10092315.48
      2807687.18     10092280.76      2807411.57     10092146.21
      2807224.93     10091948.72
#Sta/Elev= 30
  4204.7 1761.65  4335.8 1758.16  4364.8 1758.47    4421 1756.64  4581.9 1753.66
  4596.5 1753.52  4730.5 1750.81  4916.3 1749.21    4932    1750  4960.1 1746.85
  5002.2 1743.69  5004.9 1743.19  5008.2 1743.69  5015.3 1745.75  5022.1 1746.49
  5134.8 1749.41  5207.9  1752.4  5230.4 1753.64  5233.3 1754.45  5245.4 1754.26
  5266.5 1756.44  5316.2 1759.08  5372.8 1763.29  5393.9 1765.62  5415.3 1766.33
  5422.2 1767.49  5429.5 1767.15  5436.4 1768.25  5478.8 1769.53  5506.1 1773.11
#Mann= 5 ,-1 , 0
  4204.7     .05       0  4581.9      .1       0  4596.5     .05       0
  5002.2     .04       0  5008.2     .05       0
Bank Sta=5002.2,5008.2
XS Rating Curve= 0 ,0
Exp/Cntr=0.3,0.1

Type RM Length L Ch R = 1 ,4699    ,720,720,720
BEGIN DESCRIPTION:
Mapping XS 642842cf
END DESCRIPTION:
XS GIS Cut Line= 4
      2808470.65     10092213.49      2807869.47     10092191.78
      2807457.15     10092076.76      2807231.42     10091807.63
#Sta/Elev= 30
  4214.6 1753.04  4667.1 1751.14    4825  1748.1  4884.4 1745.62  4972.1 1744.43
  4977.3 1743.95  4990.7 1739.07  4993.5 1738.57  4996.7 1739.07  5004.1 1739.71
  5016.6 1744.01  5035.2 1746.53  5107.9 1746.41  5163.7 1748.02  5197.9 1751.45
  5237.3 1753.81    5241 1754.79    5281 1755.98  5309.6 1757.83  5316.1    1759
  5338.2 1759.51  5394.2 1765.23  5411.1 1765.92  5454.5 1766.67  5508.6 1769.03
  5515.1  1770.2  5529.4 1770.07    5536 1771.37  5572.4 1773.61  5595.5 1776.12
#Mann= 6 ,-1 , 0
  4214.6      .1       0  4884.4     .16       0  4990.7     .07       0
  4996.7     .16       0  5411.1      .1       0  5454.5     .05       0
Bank Sta=4990.7,4996.7
XS Rating Curve= 0 ,0
Exp/Cntr=0.3,0.1

Type RM Length L Ch R = 1 ,3979    ,812,812,812
BEGIN DESCRIPTION:
SPRING CREEK 2 5.0
END DESCRIPTION:
XS GIS Cut Line= 2
      2808599.71      10091759.5      2807481.68     10091395.49
#Sta/Elev= 30
  4239.3 1744.37  4600.3 1743.92  4675.1 1742.46  4842.4 1741.06  4871.6 1740.84
  4924.8 1737.85  4976.8 1737.65  4988.6 1735.44  4994.8 1732.81  4997.6 1732.31
  5000.8 1732.81  5008.3 1733.33  5029.4 1738.07  5047.2 1739.41  5116.3 1740.26
    5143 1741.93  5148.3  1741.4  5174.9 1744.55  5180.2 1744.32  5197.6 1749.76
  5206.9 1753.39  5212.1 1754.39  5218.7 1758.07  5238.8 1763.64    5244 1763.55
  5281.8 1766.75  5307.9 1767.66  5339.8 1770.28  5386.9 1771.72  5415.1 1773.98
#Mann= 5 ,-1 , 0
  4239.3     .05       0  4675.1      .1       0  4842.4     .16       0
  4994.8     .07       0  5000.8     .16       0
Bank Sta=4994.8,5000.8
XS Rating Curve= 0 ,0
Exp/Cntr=0.3,0.1

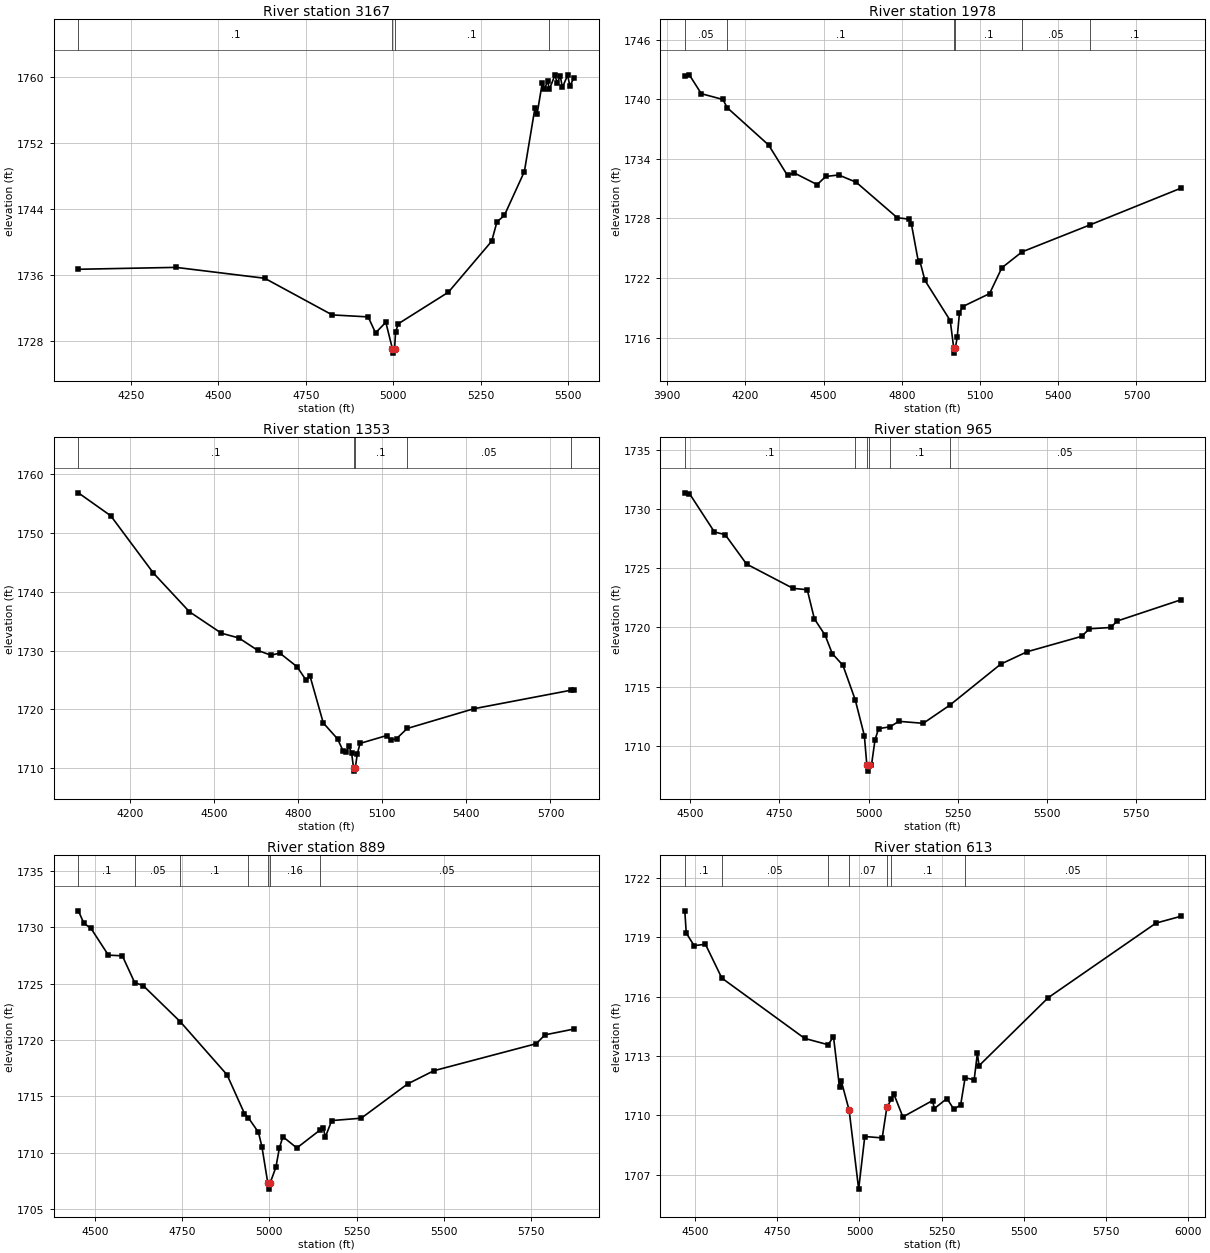
Type RM Length L Ch R = 1 ,3167    ,1189,1189,1189
BEGIN DESCRIPTION:
SPRING CREEK 2 4.0
END DESCRIPTION:
XS GIS Cut Line= 2
      2808755.98     10091282.08       2807566.7     10090509.49
#Sta/Elev= 30
  4099.1 1736.71  4378.5 1736.94  4632.2 1735.62  4825.3 1731.18  4928.1 1730.94
  4949.2    1729  4978.6 1730.29  4997.6 1727.05  5000.3 1726.55  5003.6 1727.05
  5006.5  1729.1  5014.3 1730.11  5157.5 1733.93  5281.4 1740.11  5296.5 1742.46
  5317.6 1743.23  5374.9 1748.55  5405.2 1756.26  5411.2  1755.5  5426.3 1759.34
  5432.3 1758.51  5441.5 1759.54  5446.3  1758.5  5462.6 1760.27  5468.5 1759.28
  5477.7  1760.1  5483.7 1758.74  5498.8 1760.24  5504.8 1758.91  5517.3 1759.94
#Mann= 4 ,-1 , 0
  4099.1      .1       0  4997.6     .07       0  5003.6      .1       0
  5446.3     .16       0
Bank Sta=4997.6,5003.6
XS Rating Curve= 0 ,0
Exp/Cntr=0.3,0.1

Type RM Length L Ch R = 1 ,1978    ,625,625,625
BEGIN DESCRIPTION:
SPRING CREEK 2 3.0
END DESCRIPTION:
XS GIS Cut Line= 3
      2809137.88     10091525.09      2808808.03     10090249.08
      2808243.77      10090101.5
#Sta/Elev= 30
    3968 1742.37  3985.3 1742.45  4031.4 1740.55    4114 1739.97  4130.7 1739.14
  4289.6 1735.38  4361.9 1732.32  4386.5 1732.59  4475.5  1731.4  4508.4 1732.22
  4558.1 1732.37  4625.1 1731.64  4782.5 1728.07  4828.3 1727.92    4837 1727.42
  4863.8 1723.61  4868.9 1723.76  4888.7 1721.76  4985.7 1717.72  4999.3 1714.94
    5002 1714.44  5005.3 1714.94  5012.6 1716.05  5021.1 1718.47  5033.3 1719.12
  5136.6 1720.43  5183.7 1723.03    5261 1724.63  5520.1 1727.33  5869.2 1731.03
#Mann= 6 ,-1 , 0
    3968     .05       0  4130.7      .1       0  4999.3     .07       0
  5005.3      .1       0    5261     .05       0  5520.1      .1       0
Bank Sta=4999.3,5005.3
XS Rating Curve= 0 ,0
Exp/Cntr=0.3,0.1

Type RM Length L Ch R = 1 ,1353    ,388,388,388
BEGIN DESCRIPTION:
SPRING CREEK 2 2.0
END DESCRIPTION:
XS GIS Cut Line= 4
       2809676.1     10091525.16      2809433.03     10090657.06
      2809450.39      10090327.2      2808955.56     10090118.85
#Sta/Elev= 30
  4015.9 1756.87  4131.6 1752.96  4283.7 1743.21    4412 1736.63  4526.2 1732.97
  4588.5 1732.16  4656.1 1730.04  4702.8 1729.23  4734.7 1729.58  4796.2 1727.26
  4827.4 1725.04  4842.3 1725.69  4889.7 1717.69  4940.7 1714.97  4960.8 1712.89
  4970.8 1712.69  4980.8 1713.77  4990.8 1712.53  4997.8 1709.99  5000.6 1709.49
  5003.8 1709.99  5010.8 1712.39  5020.9 1714.21    5116 1715.55    5131 1714.74
    5151 1715.02    5189 1716.75  5426.5 1720.11  5771.6 1723.25  5784.6 1723.23
#Mann= 5 ,-1 , 0
  4015.9      .1       0  4997.8     .07       0  5003.8      .1       0
    5189     .05       0  5771.6      .1       0
Bank Sta=4997.8,5003.8
XS Rating Curve= 0 ,0
Exp/Cntr=0.3,0.1

Type RM Length L Ch R = 1 ,965     ,76,76,76
BEGIN DESCRIPTION:
Mapping XS 77e4e464
END DESCRIPTION:
XS GIS Cut Line= 3
      2809805.24     10091056.77      2809805.24     10090460.01
      2809086.93     10090125.82
#Sta/Elev= 30
  4485.2 1731.37  4498.2 1731.31  4568.2 1728.06  4598.2 1727.84  4658.2 1725.35
  4788.2  1723.3  4828.2 1723.18  4848.2 1720.72  4878.2 1719.34  4898.2 1717.79
  4928.2 1716.79  4962.5 1713.89  4988.2 1710.85  4995.2 1708.35    4998 1707.85
  5001.2 1708.35  5008.2 1708.37  5018.2 1710.52  5028.2 1711.44  5060.8  1711.6
  5084.4 1712.06  5153.1 1711.89  5227.4 1713.42  5370.1 1716.89  5444.2 1717.94
  5596.8 1719.24  5618.8 1719.88  5678.6 1719.99  5695.9 1720.53  5874.2 1722.32
#Mann= 6 ,-1 , 0
  4485.2      .1       0  4962.5     .16       0  4995.2     .07       0
  5001.2     .16       0  5060.8      .1       0  5227.4     .05       0
Bank Sta=4995.2,5001.2
XS Rating Curve= 0 ,0
Exp/Cntr=0.3,0.1

Type RM Length L Ch R = 1 ,889     ,276,276,276
BEGIN DESCRIPTION:
Mapping XS 5e896dab
END DESCRIPTION:
XS GIS Cut Line= 3
      2809876.85     10091069.82      2809879.02     10090384.06
      2809193.32     10090119.32
#Sta/Elev= 30
  4452.9 1731.45    4469 1730.34    4489  1729.9    4539 1727.52    4579 1727.46
  4614.3 1725.09    4639 1724.81  4744.9 1721.62    4879 1716.91    4929 1713.47
  4940.1  1713.1    4969 1711.81    4979 1710.53    4996 1707.27  4998.7 1706.77
    5002 1707.27    5019 1708.71    5029 1710.41    5039 1711.42    5079 1710.42
  5146.7 1712.04  5154.4 1712.23  5160.7 1711.39    5179 1712.85  5263.5 1713.06
  5396.5  1716.1  5471.6 1717.27  5765.3 1719.67  5789.9 1720.45  5873.7 1720.97
#Mann= 7 ,-1 , 0
  4452.9      .1       0  4614.3     .05       0  4744.9      .1       0
  4940.1     .16       0    4996     .07       0    5002     .16       0
  5146.7     .05       0
Bank Sta=4996,5002
XS Rating Curve= 0 ,0
Exp/Cntr=0.3,0.1

Type RM Length L Ch R = 1 ,613     ,0,0,0
BEGIN DESCRIPTION:
SPRING CREEK 2 1.0
END DESCRIPTION:
XS GIS Cut Line= 3
      2810326.08     10090900.58      2810069.99     10090288.57
      2809245.33     10090106.28
#Sta/Elev= 30
  4468.8 1720.34  4473.2 1719.22    4497 1718.58  4531.6 1718.65  4581.4 1716.94
  4833.4 1713.89  4904.8 1713.57    4921 1713.98  4939.4 1711.41  4944.8 1711.73
  4968.6 1710.26  4997.6 1706.27  5016.2 1708.93  5069.2 1708.86  5083.3  1710.4
  5096.8 1710.81    5105 1711.06  5132.1 1709.92  5222.5 1710.75  5227.6 1710.34
  5266.1 1710.85  5287.4  1710.3  5307.9 1710.54  5321.3  1711.9  5348.9  1711.8
  5358.6 1713.13  5363.7 1712.51  5574.2 1715.95  5901.9 1719.72  5976.8 1720.06
#Mann= 7 ,-1 , 0
  4468.8      .1       0  4581.4     .05       0  4904.8      .1       0
  4968.6     .07       0  5083.3     .16       0  5096.8      .1       0
  5321.3     .05       0
Bank Sta=4968.6,5083.3
XS Rating Curve= 0 ,0
Exp/Cntr=0.3,0.1

Chan Stop Cuts=-1
Use User Specified Reach Order=0
Composite Channel Slope=5