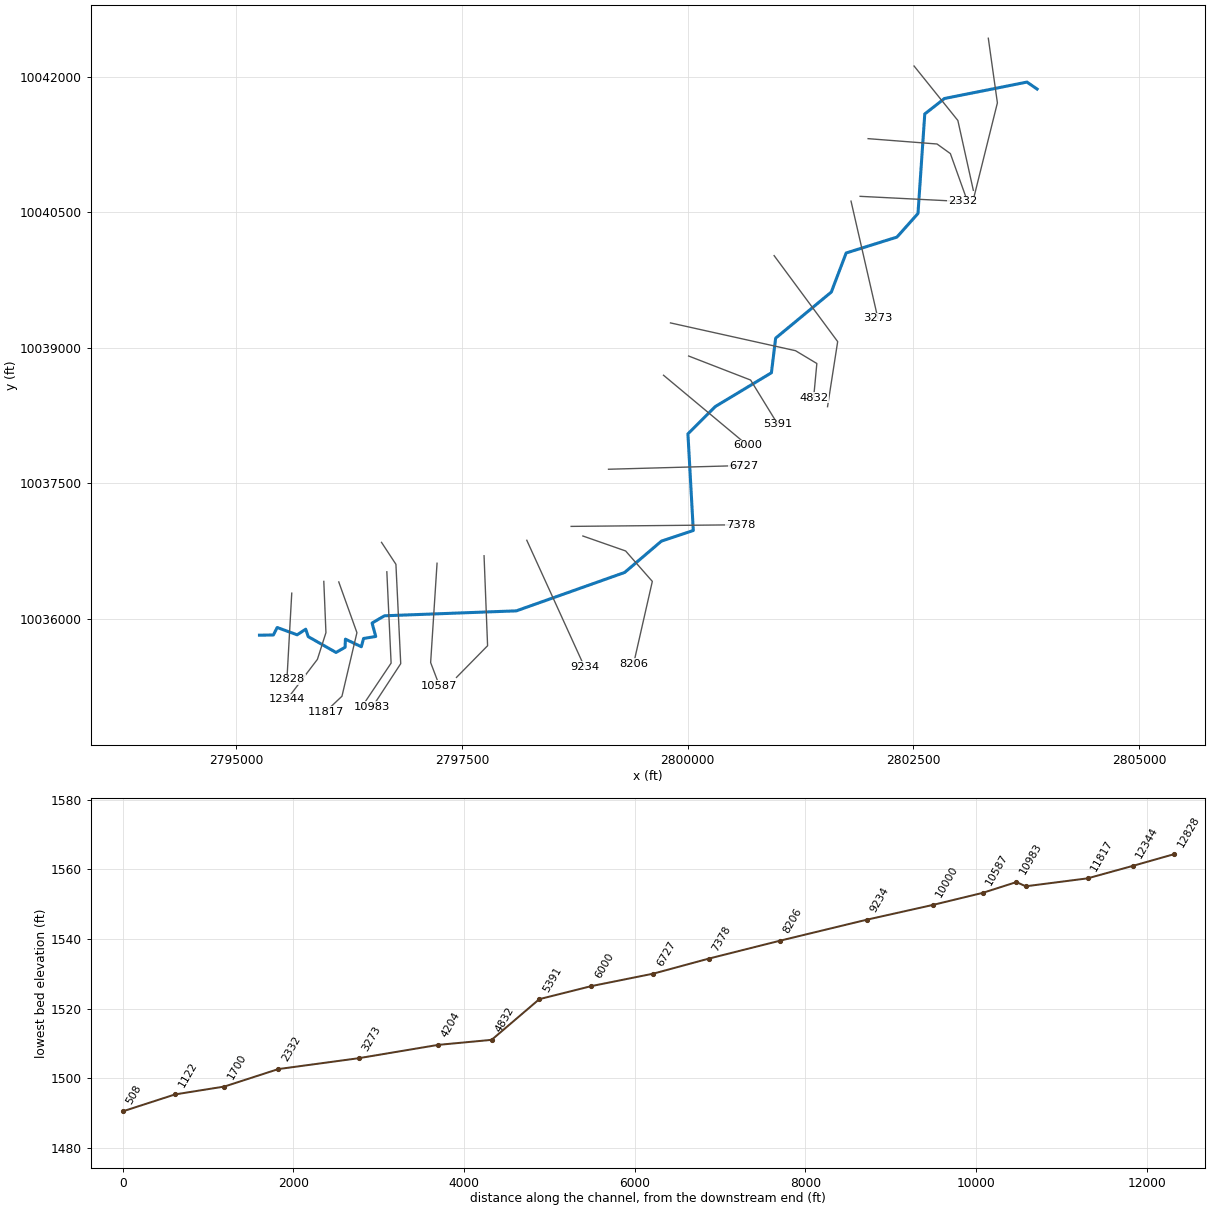
--- STOLLES CREEK.prj (project) ---

Proj Title=STOLLES CREEK Base Level Engineering
Current Plan=p01
Default Exp/Contr=0.3,0.1
English Units
Geom File=g01
Flow File=f01
Plan File=p01
Y Axis Title=Elevation
X Axis Title(PF)=Main Channel Distance
X Axis Title(XS)=Station
BEGIN DESCRIPTION:
STOLLES CREEK
END DESCRIPTION:
DSS Export Rating Curves= 0
DSS Export Rating Curve Sorted= 0
DSS Export Volume Flow Curves= 0
DXF OffsetX= 0
DXF OffsetY= 0
DXF ScaleX= 1
DXF ScaleY= 10

--- STOLLES CREEK.p01 (plan) ---

Plan Title=Multiple Run
Short Identifier=Multiple
Geom File=g01
Flow File=f01
Subcritical Flow
K Sum by GR= 0
Std Step Tol= 0.01
Critical Tol= 0.01
Num of Std Step Trials= 20
Max Error Tol= 0.3
Flow Tol Ratio= 0.001
Split Flow NTrial= 30
Split Flow Tol= 0.02
Split Flow Ratio= 0.02
Log Output Level= 0
Friction Slope Method= 1
Unsteady Friction Slope Method= 2
Unsteady Bridges Friction Slope Method= 1
Parabolic Critical Depth
Global Vel Dist=  1 , 1 , 1
Global Log Level= 0
CheckData=True
Encroach Param= -1, 0, 0, 0
BEGIN DESCRIPTION:
Multiple Run
END DESCRIPTION:

--- STOLLES CREEK.f01 (steady flow) ---

Flow Title=Multiple
Number of Profiles=7
Profile Names=10-year,25-year,50-year,1pct_min,100-year,1pct_plu,500-year
River Rch & RM= STOLLES CREEK,Reach-1,12828
    1128    1639    2082    1932    2613    3534    4134
Boundary for River Rch & Prof#=STOLLES CREEK,Reach-1,1
Up Type=0
Dn Type=3
Dn Slope=0.005
Boundary for River Rch & Prof#=STOLLES CREEK,Reach-1,2
Up Type=0
Dn Type=3
Dn Slope=0.005
Boundary for River Rch & Prof#=STOLLES CREEK,Reach-1,3
Up Type=0
Dn Type=3
Dn Slope=0.005
Boundary for River Rch & Prof#=STOLLES CREEK,Reach-1,4
Up Type=0
Dn Type=3
Dn Slope=0.005
Boundary for River Rch & Prof#=STOLLES CREEK,Reach-1,5
Up Type=0
Dn Type=3
Dn Slope=0.005
Boundary for River Rch & Prof#=STOLLES CREEK,Reach-1,6
Up Type=0
Dn Type=3
Dn Slope=0.005
Boundary for River Rch & Prof#=STOLLES CREEK,Reach-1,7
Up Type=0
Dn Type=3
Dn Slope=0.005

--- STOLLES CREEK.g01 (geometry) ---

Geom Title=Existing Conditions
Program Version=4.10

River Reach=STOLLES CREEK   ,Reach-1
Reach XY= 30
      2795257.42     10035816.33      2795411.08     10035818.19
       2795453.7      10035901.3      2795674.56     10035820.23
      2795769.34      10035882.5      2795797.46     10035800.04
      2796105.39     10035624.87      2796205.35     10035682.13
       2796209.5      10035772.3      2796385.46     10035687.93
      2796410.47     10035779.81      2796544.99     10035801.77
      2796504.64     10035950.63       2796641.7     10036030.94
      2798103.18     10036085.77       2799301.9     10036510.95
      2799708.74     10036857.76      2800062.22     10036976.07
       2800002.8     10038046.73       2800305.6     10038348.65
      2800927.52     10038723.36      2800974.21     10039106.32
      2801590.87     10039617.29      2801755.29     10040050.07
      2802317.58     10040226.09      2802550.72     10040487.39
      2802625.99     10041590.13       2802844.5     10041761.44
      2803757.81     10041943.26      2803870.18     10041866.15

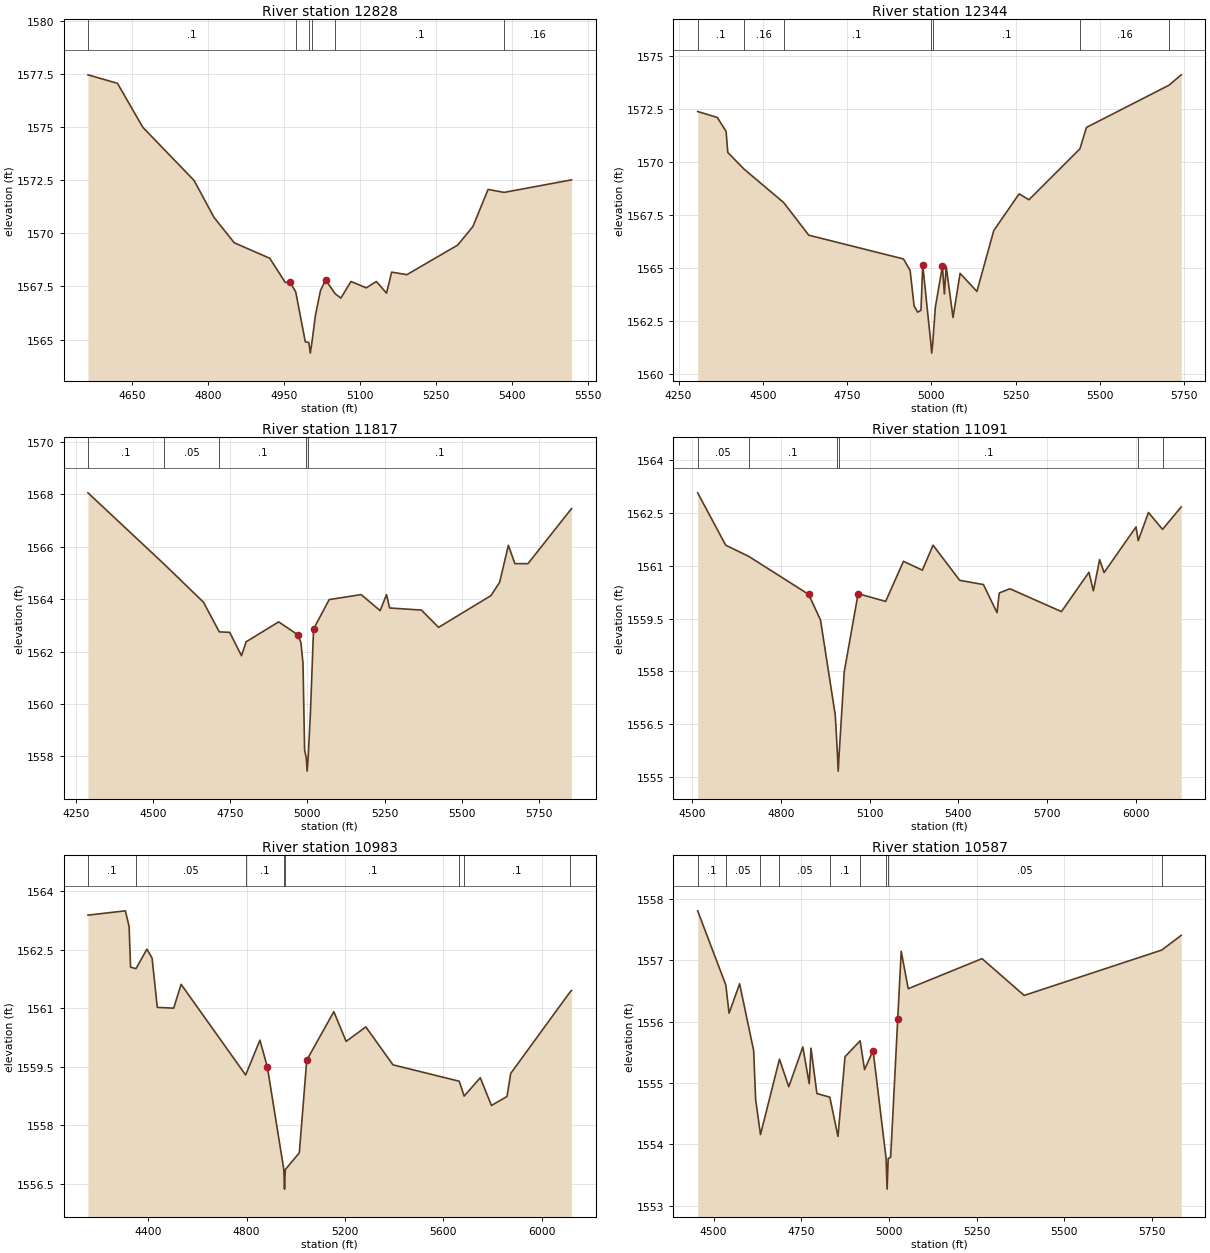
Type RM Length L Ch R = 1 ,12828   ,484,484,484
BEGIN DESCRIPTION:
STOLLES CREEK 16.0
END DESCRIPTION:
XS GIS Cut Line= 2
      2795614.92     10036281.86      2795561.68     10035329.34
#Sta/Elev= 30
  4562.7 1577.45  4620.9 1577.05    4671 1574.98  4772.1 1572.48  4811.2 1570.75
  4851.3 1569.55  4921.4 1568.82  4951.8 1567.69  4961.4  1567.7  4972.6 1567.24
  4991.5 1564.89  4998.5 1564.86  5001.3 1564.36  5004.5 1564.86  5011.5 1566.15
  5021.5 1567.31  5031.6  1567.8  5050.5 1567.15  5061.6 1566.95  5081.6 1567.73
  5111.7 1567.43  5131.7 1567.73  5151.7 1567.18  5161.8 1568.17  5191.8 1568.05
    5292 1569.44    5322 1570.31  5352.1 1572.06  5383.6 1571.92  5516.7 1572.51
#Mann= 6 ,-1 , 0
  4562.7      .1       0  4972.6     .16       0  4998.5     .07       0
  5004.5     .16       0  5050.5      .1       0  5383.6     .16       0
Bank Sta=4961.4,5031.6
XS Rating Curve= 0 ,0
Exp/Cntr=0.3,0.1

Type RM Length L Ch R = 1 ,12344   ,527,527,527
BEGIN DESCRIPTION:
STOLLES CREEK 15.0
END DESCRIPTION:
XS GIS Cut Line= 4
       2795969.9     10036411.95      2795993.57     10035844.03
      2795898.91     10035548.21      2795562.55     10035105.64
#Sta/Elev= 30
  4306.8 1572.39  4365.1 1572.11  4391.2 1571.45  4396.2 1570.46  4444.8 1569.67
  4561.9  1568.1  4636.5 1566.56  4917.5 1565.44  4937.2  1564.9    4949 1563.23
  4959.5 1562.93  4969.4 1563.02  4974.6 1565.16  4998.5  1561.5  5001.3    1561
  5004.5  1561.5    5012 1563.16    5033 1565.09  5038.9 1563.79  5044.2 1565.09
  5064.5 1562.68  5085.5 1564.76  5135.4 1563.91  5185.5 1566.78  5260.7 1568.51
  5289.8 1568.23  5441.1 1570.63  5460.4 1571.64  5705.3 1573.63  5741.7 1574.12
#Mann= 7 ,-1 , 0
  4306.8      .1       0  4444.8     .16       0  4561.9      .1       0
  4998.5     .07       0  5004.5      .1       0  5441.1     .16       0
  5705.3     .05       0
Bank Sta=4974.6,5033
XS Rating Curve= 0 ,0
Exp/Cntr=0.3,0.1

Type RM Length L Ch R = 1 ,11817   ,726,726,726
BEGIN DESCRIPTION:
Mapping XS 11d36082
END DESCRIPTION:
XS GIS Cut Line= 4
      2796135.57     10036406.04      2796336.71     10035844.03
      2796171.06     10035139.99      2795992.23      10034970.6
#Sta/Elev= 30
  4289.2 1568.05  4534.3 1565.35  4663.4 1563.88  4714.6 1562.75  4748.4 1562.73
  4786.5 1561.84  4801.5 1562.37    4907 1563.13  4968.6 1562.64  4978.9 1562.35
  4985.8 1561.55    4991 1558.25  4996.4 1557.94  4999.2 1557.44  5002.4 1557.94
  5009.7 1559.62    5020 1562.86  5070.6 1563.98  5174.1 1564.17  5235.7 1563.56
  5256.3 1564.17  5266.5 1563.66  5369.3 1563.58    5425 1562.92  5594.5 1564.13
  5622.8 1564.64  5651.1 1566.05  5672.2 1565.35  5714.6 1565.35  5855.7 1567.45
#Mann= 5 ,-1 , 0
  4289.2      .1       0  4534.3     .05       0  4714.6      .1       0
  4996.4     .07       0  5002.4      .1       0
Bank Sta=4968.6,5020
XS Rating Curve= 0 ,0
Exp/Cntr=0.3,0.1

Type RM Length L Ch R = 1 ,11091   ,108,108,108
BEGIN DESCRIPTION:
Mapping XS 01a3bb60
END DESCRIPTION:
XS GIS Cut Line= 3
      2796668.03     10036518.46      2796715.36      10035506.8
      2796369.48     10034990.28
#Sta/Elev= 30
    4519 1563.08  4613.8 1561.59  4691.9 1561.27  4894.1 1560.19  4934.2 1559.46
  4984.2 1556.75  4991.3 1555.66    4994 1555.16  4997.3 1555.66  5014.3 1557.98
  5061.3 1560.21  5154.4 1559.99  5214.5 1561.13  5278.5 1560.88  5314.6 1561.59
  5404.7 1560.59  5484.8 1560.47  5530.8 1559.67  5538.3 1560.23  5574.3 1560.35
  5748.5  1559.7  5841.5 1560.82  5856.5 1560.29  5877.6 1561.18  5892.6 1560.81
  6000.6 1562.11    6008 1561.72  6042.7 1562.52  6090.2 1562.04  6153.4 1562.68
#Mann= 6 ,-1 , 0
    4519     .05       0  4691.9      .1       0  4991.3     .07       0
  4997.3      .1       0    6008     .05       0  6090.2      .1       0
Bank Sta=4894.1,5061.3
XS Rating Curve= 0 ,0
Exp/Cntr=0.3,0.1

Type RM Length L Ch R = 1 ,10983   ,396,396,396
BEGIN DESCRIPTION:
Mapping XS d34f9834
END DESCRIPTION:
XS GIS Cut Line= 4
      2796609.08     10036844.42       2796768.6     10036601.32
      2796821.85     10035500.88      2796508.39     10035021.57
#Sta/Elev= 30
  4155.7 1563.38  4307.8 1563.49  4322.9 1563.09  4328.8 1562.05  4350.7 1562.01
  4395.2 1562.51  4416.3 1562.28  4437.4 1561.02  4504.1    1561  4534.2 1561.61
  4796.5 1559.29  4854.5 1560.18  4884.6  1559.5  4951.6 1556.87  4954.4 1556.37
  4957.6 1556.87  5014.7  1557.3  5044.8 1559.67  5154.9 1560.91  5204.9 1560.15
    5285 1560.52  5395.2 1559.55  5664.7 1559.13  5684.4 1558.75    5750 1559.22
  5795.4 1558.51  5858.6 1558.74  5873.7 1559.33  6114.5 1561.41  6120.9 1561.45
#Mann= 8 ,-1 , 0
  4155.7      .1       0  4350.7     .05       0  4796.5      .1       0
  4951.6     .07       0  4957.6      .1       0  5664.7     .05       0
  5684.4      .1       0  6114.5     .05       0
Bank Sta=4884.6,5044.8
XS Rating Curve= 0 ,0
Exp/Cntr=0.3,0.1

Type RM Length L Ch R = 1 ,10587   ,587,587,587
BEGIN DESCRIPTION:
Mapping XS 4e74324a
END DESCRIPTION:
XS GIS Cut Line= 3
      2797224.16     10036613.11      2797153.16     10035512.72
      2797251.43     10035254.14
#Sta/Elev= 30
  4454.4 1557.81  4534.7  1556.6    4544 1556.14    4574 1556.62  4614.1 1555.53
  4619.8 1554.73  4633.6 1554.16  4687.7 1555.39  4714.3 1554.94  4754.4 1555.59
  4772.6 1554.99  4777.6 1555.57  4794.5 1554.83  4831.3 1554.77  4854.6 1554.13
  4874.7 1555.43  4917.8 1555.69  4930.4 1555.22  4954.8 1555.53  4991.9 1553.77
  4994.7 1553.27  4997.9 1553.77  5004.9 1553.79    5025 1556.04    5035 1557.15
    5055 1556.54  5265.5 1557.03  5385.7 1556.43  5778.1 1557.17  5833.7 1557.41
#Mann= 9 ,-1 , 0
  4454.4      .1       0  4534.7     .05       0  4633.6     .16       0
  4687.7     .05       0  4831.3      .1       0  4917.8     .05       0
  4991.9    .035       0  4997.9     .05       0  5778.1      .1       0
Bank Sta=4954.8,5025
XS Rating Curve= 0 ,0
Exp/Cntr=0.3,0.1

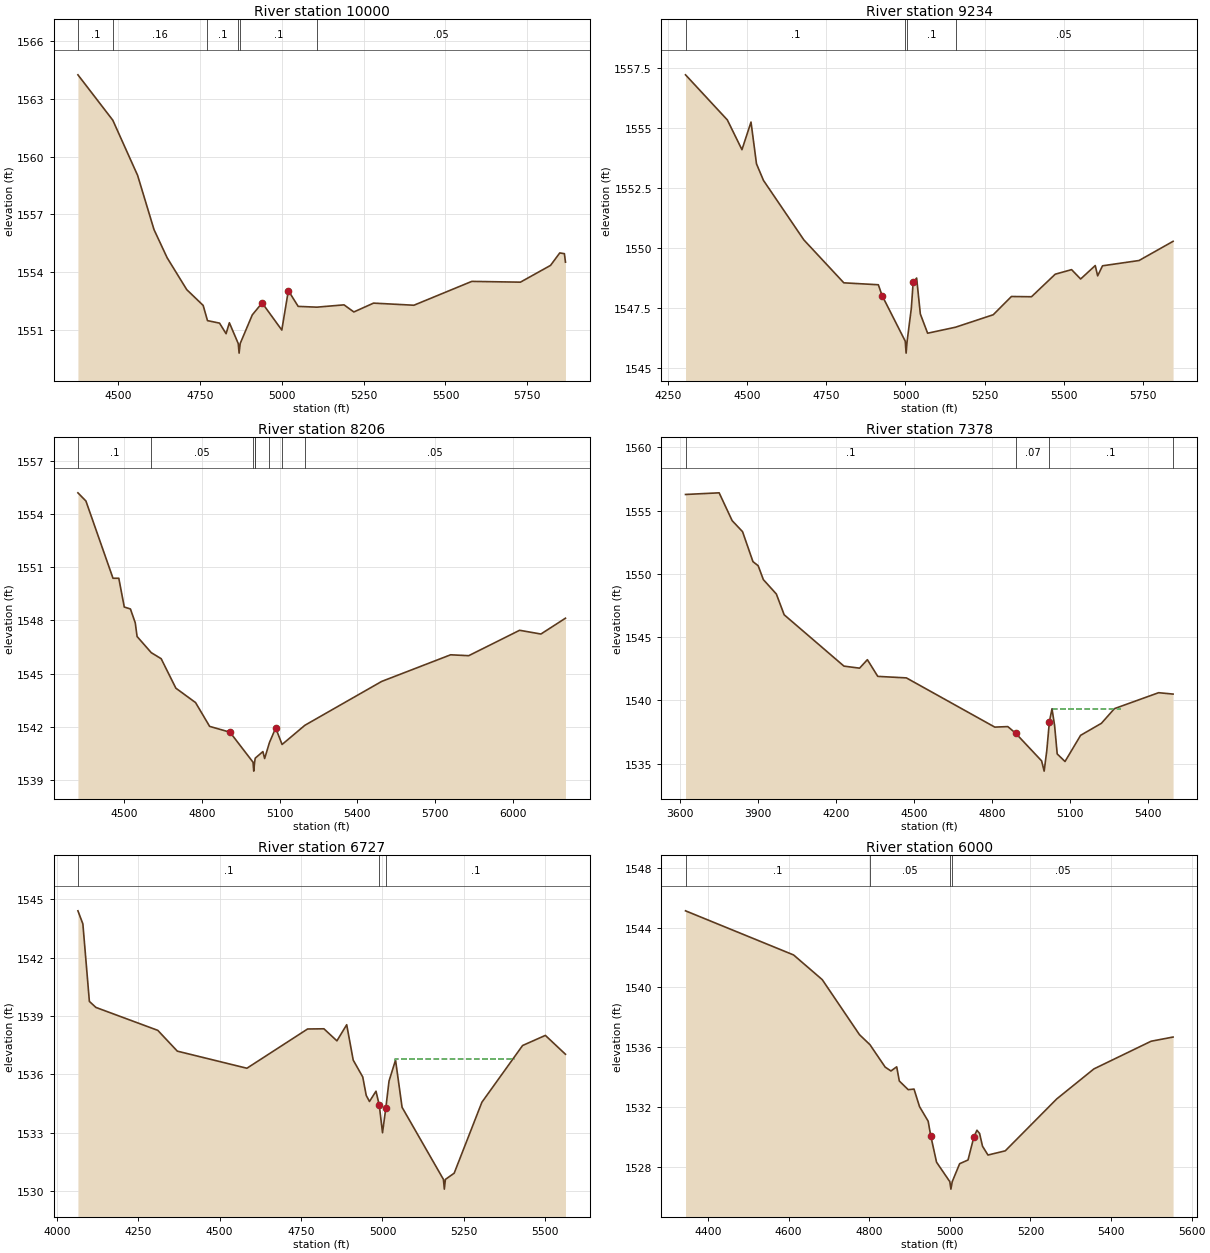
Type RM Length L Ch R = 1 ,10000   ,766,766,766
BEGIN DESCRIPTION:
STOLLES CREEK 14.0
END DESCRIPTION:
XS GIS Cut Line= 3
      2797744.79     10036696.01      2797783.88     10035699.34
      2797439.32     10035348.32
#Sta/Elev= 30
  4377.2 1564.26  4483.8  1561.9  4559.6 1559.03  4609.7 1556.21  4649.7 1554.75
  4709.7 1553.09  4759.8 1552.27    4773 1551.48  4809.8 1551.35  4829.8  1550.8
  4839.8 1551.37  4866.9 1550.29  4869.6 1549.79  4872.9 1550.29  4909.9 1551.78
  4939.9  1552.4    5000 1550.99    5020 1553.04    5050 1552.22  5107.1 1552.18
  5190.1  1552.3  5220.1 1551.93  5280.2 1552.39  5403.5 1552.28  5580.4 1553.52
  5728.9 1553.48  5820.8 1554.35  5849.1    1555  5863.3 1554.96  5866.5 1554.52
#Mann= 6 ,-1 , 0
  4377.2      .1       0  4483.8     .16       0    4773      .1       0
  4866.9     .07       0  4872.9      .1       0  5107.1     .05       0
Bank Sta=4939.9,5020
XS Rating Curve= 0 ,0
Exp/Cntr=0.3,0.1

Type RM Length L Ch R = 1 ,9234    ,1028,1028,1028
BEGIN DESCRIPTION:
STOLLES CREEK 13.0
END DESCRIPTION:
XS GIS Cut Line= 2
       2798218.1     10036867.55      2798856.28      10035467.1
#Sta/Elev= 30
  4305.8  1557.2  4437.8 1555.32  4483.9 1554.08  4512.5 1555.23  4529.8 1553.49
  4551.8  1552.8  4679.3 1550.32  4805.5 1548.53  4914.4 1548.45  4926.3    1548
  4999.3  1546.1  5002.1  1545.6  5005.3  1546.1  5018.5 1547.46  5024.3 1548.55
  5035.3 1548.73    5047 1547.23    5070 1546.43  5158.1 1546.68  5277.1  1547.2
  5334.5 1547.96  5397.9 1547.95  5472.8 1548.89  5524.4 1549.08    5553 1548.69
  5599.1 1549.25  5606.7 1548.82  5622.1 1549.24  5737.3 1549.46  5844.8 1550.26
#Mann= 4 ,-1 , 0
  4305.8      .1       0  4999.3     .07       0  5005.3      .1       0
  5158.1     .05       0
Bank Sta=4926.3,5024.3
XS Rating Curve= 0 ,0
Exp/Cntr=0.3,0.1

Type RM Length L Ch R = 1 ,8206    ,828,828,828
BEGIN DESCRIPTION:
STOLLES CREEK 12.0
END DESCRIPTION:
XS GIS Cut Line= 4
       2798839.3     10036914.88      2799312.61     10036749.22
      2799608.43     10036411.99      2799401.36     10035500.88
#Sta/Elev= 30
  4320.3 1555.18  4351.2 1554.72  4455.9 1550.37  4478.3 1550.37  4499.5 1548.75
  4523.3 1548.64  4541.9 1547.86    4549 1547.09  4603.8 1546.18  4642.1 1545.84
  4698.9 1544.18    4775 1543.37  4829.4 1542.03  4908.1  1541.7  4997.2 1540.01
  4999.9 1539.51  5003.2 1540.01  5005.6 1540.24  5035.3 1540.61    5042 1540.22
  5060.6 1541.12  5084.7 1541.94  5109.4 1541.01  5197.4 1542.09  5494.2 1544.56
  5760.8 1546.06  5830.8 1546.01  6027.4 1547.44  6109.8 1547.23  6204.7 1548.12
#Mann= 8 ,-1 , 0
  4320.3      .1       0  4603.8     .05       0  4997.2    .035       0
  5003.2     .05       0  5005.6      .1       0  5060.6     .05       0
  5109.4      .1       0  5197.4     .05       0
Bank Sta=4908.1,5084.7
XS Rating Curve= 0 ,0
Exp/Cntr=0.3,0.1

Type RM Length L Ch R = 1 ,7378    ,651,651,651
BEGIN DESCRIPTION:
STOLLES CREEK 11.0
END DESCRIPTION:
XS GIS Cut Line= 2
       2798709.2     10037021.37      2800584.01     10037039.12
#Sta/Elev= 30
  3621.6 1556.28  3750.9 1556.41  3800.9 1554.21  3840.9 1553.34  3880.9 1550.97
  3900.9 1550.65  3920.9 1549.55  3970.9 1548.41  4000.9 1546.77  4230.9 1542.71
  4290.9 1542.55  4320.9 1543.22  4360.9  1541.9  4470.9 1541.78  4810.9 1537.89
  4860.9 1537.93  4890.9 1537.41  4990.9 1535.22  5000.7 1534.41  5010.9 1536.04
  5020.9 1538.32  5030.9 1539.34  5040.9 1538.01  5050.9 1535.77  5080.9 1535.17
  5140.9 1537.24  5220.9 1538.19  5270.9 1539.35  5440.9 1540.61  5496.5  1540.5
#Mann= 4 ,-1 , 0
  3621.6      .1       0  4890.9     .07       0  5020.9      .1       0
  5496.5     .05       0
#XS Ineff= 1 ,-1
 5030.68 5296.59 1539.35
Permanent Ineff=
       F
Bank Sta=4890.9,5020.9
XS Rating Curve= 0 ,0
Exp/Cntr=0.3,0.1

Type RM Length L Ch R = 1 ,6727    ,727,727,727
BEGIN DESCRIPTION:
STOLLES CREEK 10.0
END DESCRIPTION:
XS GIS Cut Line= 2
       2799123.3     10037654.42      2800620.12     10037695.83
#Sta/Elev= 30
  4064.6 1544.41  4079.8 1543.74  4099.8 1539.75  4119.8 1539.44  4309.9 1538.26
  4369.9 1537.19  4583.6 1536.31    4770 1538.33  4820.1 1538.34  4860.1 1537.72
  4890.1 1538.55  4910.1 1536.73  4939.4 1535.86  4950.1 1534.91  4960.1  1534.6
  4980.1 1535.13  4990.1 1534.41  5000.1 1532.99  5010.1 1534.24  5020.1 1535.65
  5040.1 1536.73  5060.2  1534.3  5187.2 1530.59    5190 1530.09  5193.2 1530.59
  5220.2 1530.91  5305.3 1534.56  5430.3 1537.48  5500.3    1538    5562 1537.03
#Mann= 3 , 0 , 0
  4064.6      .1       0  4990.1     .07       0  5010.1      .1       0
#XS Ineff= 1 ,-1
 5039.09 5408.18 1536.77
Permanent Ineff=
       F
Bank Sta=4990.1,5010.1
XS Rating Curve= 0 ,0
Exp/Cntr=0.3,0.1

Type RM Length L Ch R = 1 ,6000    ,609,609,609
BEGIN DESCRIPTION:
STOLLES CREEK 9.0
END DESCRIPTION:
XS GIS Cut Line= 2
      2799732.64     10038695.71      2800661.55     10037920.64
#Sta/Elev= 30
  4344.1 1545.12  4612.2 1542.17  4683.3 1540.52  4775.7 1536.84  4801.7 1536.17
  4839.5 1534.67  4853.8 1534.41  4868.1 1534.69  4874.6 1533.74  4896.7 1533.16
  4911.1  1533.2  4924.7 1532.03  4946.2 1531.05  4952.7 1530.06    4967 1528.31
  4999.9 1527.01  5002.6 1526.51  5005.9 1527.01  5024.3 1528.21  5045.1 1528.46
  5059.4 1529.98  5067.2 1530.45  5073.8 1530.23    5081 1529.38  5094.6 1528.79
  5137.5 1529.07  5265.1 1532.54  5357.5 1534.55  5499.4  1536.4  5553.9 1536.68
#Mann= 4 ,-1 , 0
  4344.1      .1       0  4801.7     .05       0  4999.9    .035       0
  5005.9     .05       0
Bank Sta=4952.7,5059.4
XS Rating Curve= 0 ,0
Exp/Cntr=0.3,0.1

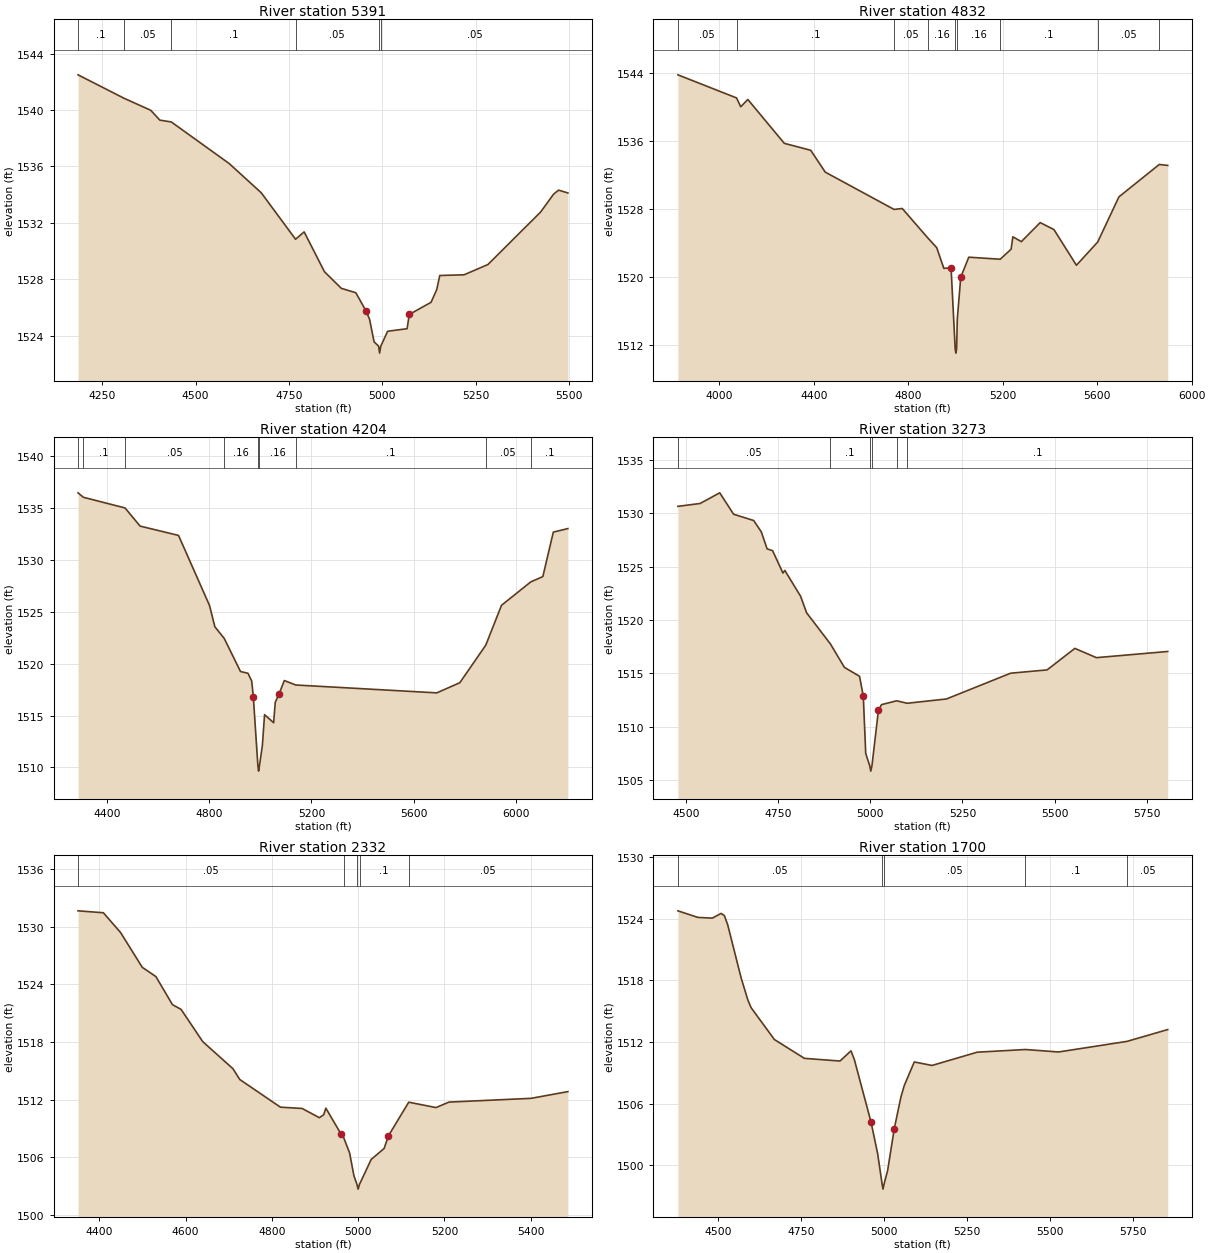
Type RM Length L Ch R = 1 ,5391    ,559,559,559
BEGIN DESCRIPTION:
STOLLES CREEK 8.0
END DESCRIPTION:
XS GIS Cut Line= 3
      2800010.74     10038908.67      2800697.03     10038642.44
      2800998.78     10038151.36
#Sta/Elev= 30
  4184.8 1542.49    4308 1540.83  4379.5 1539.98    4404 1539.28  4434.8 1539.15
    4590  1536.2  4675.8 1534.13  4767.6 1530.84  4790.7 1531.36  4845.1 1528.54
  4890.3 1527.36  4929.2 1527.05  4956.4 1525.76    4966 1525.17  4978.1 1523.57
  4990.1 1523.27  4992.9 1522.77  4996.1 1523.27  5014.4 1524.32  5066.5  1524.5
  5072.4 1525.51  5130.7 1526.37  5145.8 1527.26  5154.1 1528.27  5219.2 1528.32
  5283.2 1529.05    5424 1532.76  5459.3 1534.04  5472.5 1534.32  5497.3 1534.12
#Mann= 6 ,-1 , 0
  4184.8      .1       0    4308     .05       0  4434.8      .1       0
  4767.6     .05       0  4990.1     .04       0  4996.1     .05       0
Bank Sta=4956.4,5072.4
XS Rating Curve= 0 ,0
Exp/Cntr=0.3,0.1

Type RM Length L Ch R = 1 ,4832    ,628,628,628
BEGIN DESCRIPTION:
STOLLES CREEK 7.0
END DESCRIPTION:
XS GIS Cut Line= 4
      2799809.55     10039275.49        2801194.     10038967.84
      2801430.65     10038825.84      2801395.22       10038448.
#Sta/Elev= 30
    3825 1543.84  4073.3 1541.12    4091 1540.08    4121 1540.94  4275.4 1535.78
  4387.3 1534.96  4448.8 1532.39  4740.1    1528  4774.8 1528.11  4883.5 1524.63
  4920.8  1523.5  4950.7 1521.07  4981.5 1521.11  4998.9 1511.59  5001.7 1511.09
  5004.9 1511.59  5007.8 1515.08  5022.4 1520.02  5056.5 1522.38  5189.7 1522.14
  5235.8 1523.33  5242.9 1524.78    5279 1524.21  5358.7 1526.45    5417 1525.63
  5512.2 1521.43  5602.3 1524.17  5692.1 1529.48  5862.8 1533.29  5898.7 1533.18
#Mann= 9 ,-1 , 0
    3825     .05       0  4073.3      .1       0  4740.1     .05       0
  4883.5     .16       0  4998.9     .07       0  5004.9     .16       0
  5189.7      .1       0  5602.3     .05       0  5862.8      .1       0
Bank Sta=4981.5,5022.4
XS Rating Curve= 0 ,0
Exp/Cntr=0.3,0.1

Type RM Length L Ch R = 1 ,4204    ,931,931,931
BEGIN DESCRIPTION:
STOLLES CREEK 6.0
END DESCRIPTION:
XS GIS Cut Line= 3
      2800957.36     10040020.92      2801661.38     10039068.41
      2801549.13     10038347.65
#Sta/Elev= 30
  4287.9 1536.49  4308.9 1536.06  4471.7 1535.03  4530.3 1533.28  4680.6 1532.38
  4801.7 1525.62  4822.5 1523.57  4859.2 1522.44  4922.7 1519.25    4952 1519.08
  4966.6 1518.32  4972.8 1516.83  4990.7 1510.14  4993.4 1509.64  4996.7 1510.14
  5008.3 1512.14  5016.7 1515.09  5052.2 1514.31  5058.4 1516.27  5073.1 1517.07
  5093.9 1518.38  5138.3 1517.95  5689.6 1517.19  5779.7 1518.17    5881 1521.79
  5942.6 1525.64  6056.5 1527.89  6104.1 1528.41    6145  1532.7  6201.8 1533.04
#Mann= 9 ,-1 , 0
  4287.9     .05       0  4308.9      .1       0  4471.7     .05       0
  4859.2     .16       0  4990.7     .07       0  4996.7     .16       0
  5138.3      .1       0    5881     .05       0  6056.5      .1       0
Bank Sta=4972.8,5073.1
XS Rating Curve= 0 ,0
Exp/Cntr=0.3,0.1

Type RM Length L Ch R = 1 ,3273    ,941,941,941
BEGIN DESCRIPTION:
STOLLES CREEK 5.0
END DESCRIPTION:
XS GIS Cut Line= 2
      2801809.28     10040624.44      2802106.27     10039327.92
#Sta/Elev= 30
  4477.3 1530.67  4537.6 1530.94  4590.9 1531.94  4628.6 1529.93  4683.2 1529.34
  4703.7 1528.28  4719.5 1526.68  4734.5 1526.51  4762.5 1524.41  4767.6 1524.66
  4810.5 1522.23  4826.8 1520.68  4891.4 1517.76  4929.4 1515.56  4970.5 1514.72
  4980.7 1512.87  4987.3 1507.48  4998.2 1506.32    5001 1505.82  5004.2 1506.32
  5021.8 1511.53  5030.2 1512.06  5071.3 1512.42  5099.6 1512.19  5206.4 1512.59
  5380.8 1515.01  5479.8 1515.32  5555.2 1517.34  5613.7 1516.47  5807.4 1517.05
#Mann= 6 ,-1 , 0
  4477.3     .05       0  4891.4      .1       0  4998.2     .07       0
  5004.2      .1       0  5071.3     .16       0  5099.6      .1       0
Bank Sta=4980.7,5021.8
XS Rating Curve= 0 ,0
Exp/Cntr=0.3,0.1

Type RM Length L Ch R = 1 ,2332    ,632,632,632
BEGIN DESCRIPTION:
STOLLES CREEK 4.0
END DESCRIPTION:
XS GIS Cut Line= 2
      2801909.86     10040677.65      2803043.72      10040620.5
#Sta/Elev= 30
  4350.7 1531.64  4409.4 1531.44  4449.4 1529.38  4499.5 1525.77  4531.2  1524.8
  4569.6 1521.88  4589.6 1521.39  4639.7 1518.04  4709.8 1515.22  4725.6  1514.1
  4819.9 1511.22    4870 1511.09    4910 1510.13    4920 1510.43  4925.1 1511.12
  4960.1 1508.44  4966.4 1508.06  4980.1 1506.47  4990.1  1504.1  4997.1  1503.2
  4999.9  1502.7  5003.1  1503.2  5030.2 1505.79  5060.2 1506.93  5070.2 1508.25
  5117.2 1511.74  5180.4 1511.18  5210.4 1511.75  5400.6 1512.14    5486 1512.84
#Mann= 5 ,-1 , 0
  4350.7     .05       0  4966.4      .1       0  4997.1     .07       0
  5003.1      .1       0  5117.2     .05       0
Bank Sta=4960.1,5070.2
XS Rating Curve= 0 ,0
Exp/Cntr=0.3,0.1

Type RM Length L Ch R = 1 ,1700    ,578,578,578
BEGIN DESCRIPTION:
STOLLES CREEK 3.0
END DESCRIPTION:
XS GIS Cut Line= 4
       2801998.6     10041316.61      2802761.81     10041257.44
      2802909.72     10041150.95      2803087.22     10040653.96
#Sta/Elev= 30
  4378.1 1524.76  4438.2 1524.12  4481.6 1524.05  4508.4 1524.51  4518.4 1524.28
  4528.4 1523.37  4568.5 1518.24  4588.6 1516.11  4598.6 1515.34  4668.8 1512.24
  4759.1 1510.41  4866.3 1510.15  4899.5 1511.14  4909.6 1510.29  4959.7 1504.23
  4979.8 1501.14  4993.2 1498.19  4995.9 1497.69  4999.2 1498.19  5009.9 1499.51
  5029.9 1503.58    5050 1506.66    5060 1507.77  5090.1 1510.06  5143.6 1509.72
  5279.8 1511.01  5425.1 1511.27  5524.7 1511.03  5730.8 1512.06  5853.6 1513.21
#Mann= 5 ,-1 , 0
  4378.1     .05       0  4993.2    .035       0  4999.2     .05       0
  5425.1      .1       0  5730.8     .05       0
Bank Sta=4959.7,5029.9
XS Rating Curve= 0 ,0
Exp/Cntr=0.3,0.1

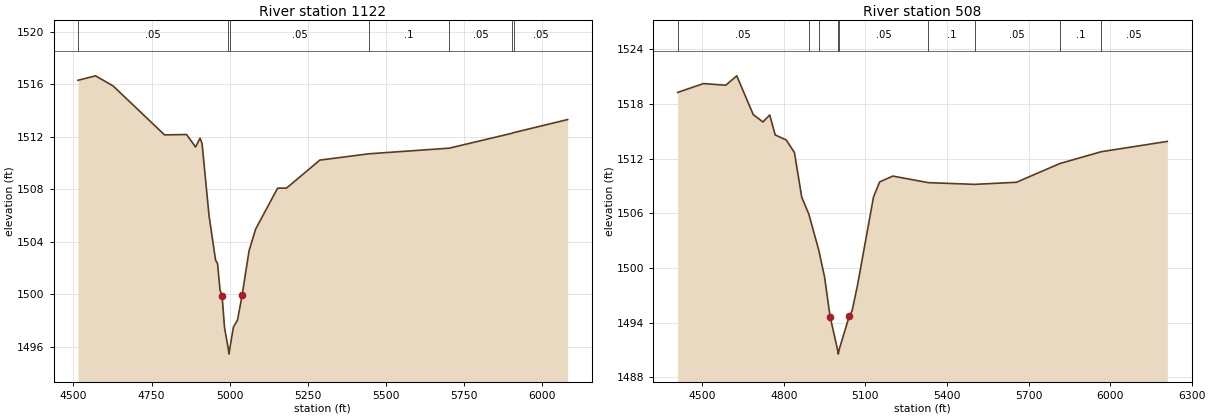
Type RM Length L Ch R = 1 ,1122    ,614,614,614
BEGIN DESCRIPTION:
STOLLES CREEK 2.0
END DESCRIPTION:
XS GIS Cut Line= 3
      2802507.39     10042121.25      2802992.55     10041517.76
      2803163.79     10040744.22
#Sta/Elev= 30
  4514.6 1516.29  4570.7 1516.63  4626.9 1515.86  4791.5 1512.13  4861.9 1512.16
  4890.7 1511.21  4905.1 1511.88  4911.5 1511.47  4933.8 1505.98  4954.7 1502.59
  4961.1 1502.32    4969  1500.3  4975.5 1499.88  4983.4 1497.44  4994.8 1495.93
  4997.6 1495.43  5000.8 1495.93  5011.8 1497.49  5025.1 1498.04  5039.5  1499.9
  5061.8 1503.29  5082.6 1504.94  5153.1 1508.07  5181.9 1508.08  5288.3 1510.21
  5445.1 1510.69  5702.6 1511.12  5902.2 1512.25  5908.1  1512.3  6081.2  1513.3
#Mann= 7 ,-1 , 0
  4514.6     .05       0  4994.8    .035       0  5000.8     .05       0
  5445.1      .1       0  5702.6     .05       0  5902.2      .1       0
  5908.1     .05       0
Bank Sta=4975.5,5039.5
XS Rating Curve= 0 ,0
Exp/Cntr=0.3,0.1

Type RM Length L Ch R = 1 ,508     ,0,0,0
BEGIN DESCRIPTION:
STOLLES CREEK 1.0
END DESCRIPTION:
XS GIS Cut Line= 3
      2803329.77     10042428.92      2803430.36       10041713.
       2803170.4     10040667.28
#Sta/Elev= 30
  4409.9 1519.25  4504.6 1520.22  4586.8 1520.04  4627.2 1521.07  4687.8 1516.82
  4723.5 1516.01  4748.4 1516.78  4768.6 1514.59    4809 1514.04  4839.3 1512.66
  4866.1 1507.77  4892.2 1505.91  4929.3  1501.9  4950.3 1498.97  4970.5 1494.66
  4997.8 1491.06  5000.6 1490.56  5003.8 1491.06  5041.2 1494.76  5051.3  1495.3
  5071.5 1498.16    5130 1507.78  5152.7 1509.44    5201 1510.08  5331.4 1509.36
  5502.4 1509.17  5655.7  1509.4  5814.9 1511.45  5967.3 1512.75  6210.4 1513.88
#Mann= 9 ,-1 , 0
  4409.9     .05       0  4892.2      .1       0  4929.3     .05       0
  4997.8    .035       0  5003.8     .05       0  5331.4      .1       0
  5502.4     .05       0  5814.9      .1       0  5967.3     .05       0
Bank Sta=4970.5,5041.2
XS Rating Curve= 0 ,0
Exp/Cntr=0.3,0.1

Chan Stop Cuts=-1
Use User Specified Reach Order=0
Composite Channel Slope=5