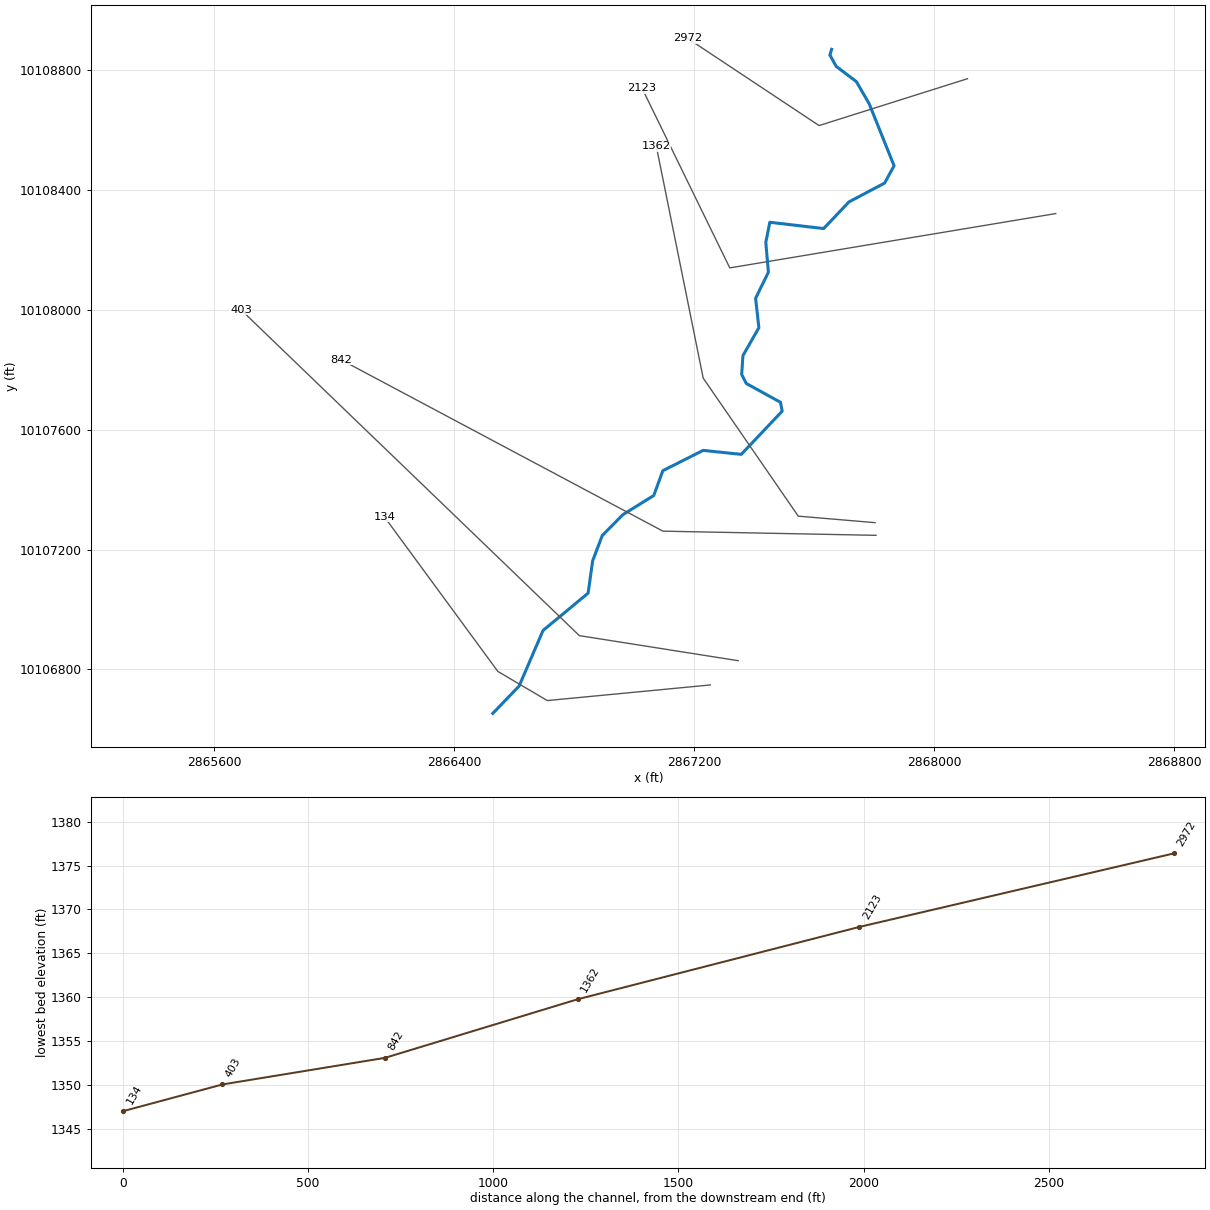
--- TANK WATER CREEK.prj (project) ---

Proj Title=TANK WATER CREEK Base Level Engineering
Current Plan=p01
Default Exp/Contr=0.3,0.1
English Units
Geom File=g01
Flow File=f01
Plan File=p01
Y Axis Title=Elevation
X Axis Title(PF)=Main Channel Distance
X Axis Title(XS)=Station
BEGIN DESCRIPTION:
TANK WATER CREEK
END DESCRIPTION:
DSS Export Rating Curves= 0
DSS Export Rating Curve Sorted= 0
DSS Export Volume Flow Curves= 0
DXF OffsetX= 0
DXF OffsetY= 0
DXF ScaleX= 1
DXF ScaleY= 10

--- TANK WATER CREEK.p01 (plan) ---

Plan Title=Multiple Run
Short Identifier=Multiple
Geom File=g01
Flow File=f01
Subcritical Flow
K Sum by GR= 0
Std Step Tol= 0.01
Critical Tol= 0.01
Num of Std Step Trials= 20
Max Error Tol= 0.3
Flow Tol Ratio= 0.001
Split Flow NTrial= 30
Split Flow Tol= 0.02
Split Flow Ratio= 0.02
Log Output Level= 0
Friction Slope Method= 1
Unsteady Friction Slope Method= 2
Unsteady Bridges Friction Slope Method= 1
Parabolic Critical Depth
Global Vel Dist=  1 , 1 , 1
Global Log Level= 0
CheckData=True
Encroach Param= -1, 0, 0, 0
BEGIN DESCRIPTION:
Multiple Run
END DESCRIPTION:

--- TANK WATER CREEK.f01 (steady flow) ---

Flow Title=Multiple
Program Version=4.10
Number of Profiles= 7
Profile Names=10-year,25-year,50-year,1pct_min,100-year,1pct_plu,500-year
River Rch & RM=TANK WATER CREEK,Reach-1         ,2972
     947    1394    1787    1679    2270    3070    3678
River Rch & RM=TANK WATER CREEK,Reach-1         ,842
    1799    2734    3581    3429    4637    6271    7811
Boundary for River Rch & Prof#=TANK WATER CREEK,Reach-1         , 1
Up Type= 0
Dn Type= 3
Dn Slope=0.0106
Boundary for River Rch & Prof#=TANK WATER CREEK,Reach-1         , 2
Up Type= 0
Dn Type= 3
Dn Slope=0.0106
Boundary for River Rch & Prof#=TANK WATER CREEK,Reach-1         , 3
Up Type= 0
Dn Type= 3
Dn Slope=0.0106
Boundary for River Rch & Prof#=TANK WATER CREEK,Reach-1         , 4
Up Type= 0
Dn Type= 3
Dn Slope=0.0106
Boundary for River Rch & Prof#=TANK WATER CREEK,Reach-1         , 5
Up Type= 0
Dn Type= 3
Dn Slope=0.0106
Boundary for River Rch & Prof#=TANK WATER CREEK,Reach-1         , 6
Up Type= 0
Dn Type= 3
Dn Slope=0.0106
Boundary for River Rch & Prof#=TANK WATER CREEK,Reach-1         , 7
Up Type= 0
Dn Type= 3
Dn Slope=0.0106
DSS Import GetInterval= 0
DSS Import GetPeak= 0
DSS Import FillOption= 0

--- TANK WATER CREEK.g01 (geometry) ---

Geom Title=Existing Conditions
Program Version=4.10

River Reach=TANK WATER CREEK,Reach-1
Reach XY= 30
      2867658.02     10108867.59      2867652.29     10108848.43
      2867673.22     10108810.77      2867740.65     10108759.64
      2867783.11     10108686.25      2867866.23     10108479.29
      2867834.57     10108421.54      2867715.78     10108358.74
      2867631.47     10108269.98      2867451.95     10108290.93
      2867438.57     10108223.75      2867447.22     10108124.31
      2867404.59     10108037.58       2867415.5      10107939.3
       2867362.4     10107846.59      2867358.16     10107783.71
      2867373.37      10107753.6      2867487.44     10107690.81
      2867493.28     10107661.33      2867356.88     10107517.18
      2867229.59     10107530.41      2867095.33     10107462.79
      2867065.09     10107380.11      2866961.83     10107315.93
      2866893.41     10107246.63      2866861.38     10107162.53
      2866846.26     10107054.56        2866696.     10106930.09
      2866616.11     10106744.69      2866528.47     10106653.73

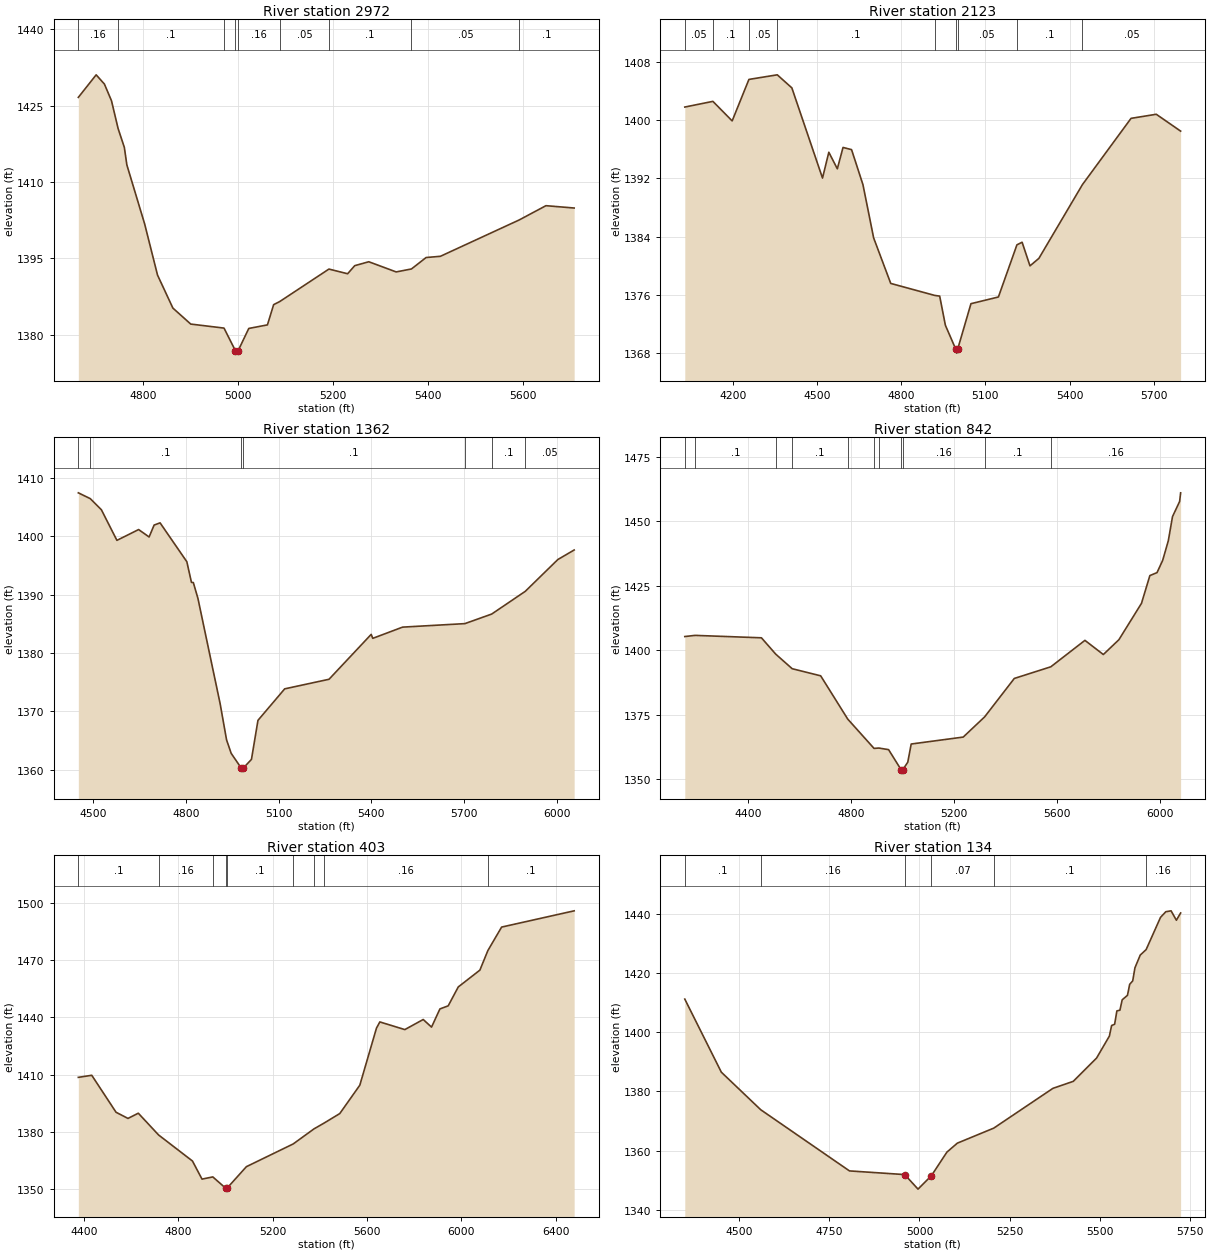
Type RM Length L Ch R = 1 ,2972    ,849,849,849
BEGIN DESCRIPTION:
TANK WATER CREEK 6.0
END DESCRIPTION:
XS GIS Cut Line= 3
      2868110.95     10108769.54      2867616.19      10108613.3
      2867177.82      10108904.1
#Sta/Elev= 30
  4663.5 1426.65  4701.1 1431.08  4718.5 1429.26  4733.4 1425.98  4747.3 1420.53
  4760.5 1416.81  4765.8 1413.37  4803.3 1401.76  4830.4 1391.72  4862.8 1385.23
  4900.4 1382.09  4970.5  1381.3  4994.4 1376.88  4997.1 1376.38  5000.4 1376.88
  5022.7 1381.23    5062 1381.93  5075.1 1385.91    5088 1386.52  5191.6  1392.9
    5231 1391.98    5246 1393.57  5275.6 1394.34  5333.3 1392.34  5365.5 1392.92
  5396.4 1395.17  5426.5 1395.41  5592.7 1402.56    5649 1405.36  5708.4  1404.9
#Mann= 9 ,-1 , 0
  4663.5     .16       0  4747.3      .1       0  4970.5     .16       0
  4994.4     .07       0  5000.4     .16       0    5088     .05       0
  5191.6      .1       0  5365.5     .05       0  5592.7      .1       0
Bank Sta=4994.4,5000.4
XS Rating Curve= 0 ,0
Exp/Cntr=0.3,0.1

Type RM Length L Ch R = 1 ,2123    ,761,761,761
BEGIN DESCRIPTION:
TANK WATER CREEK 5.0
END DESCRIPTION:
XS GIS Cut Line= 3
      2868405.08     10108319.92      2867318.49     10108138.82
      2867025.96     10108737.83
#Sta/Elev= 30
  4027.9 1401.76  4128.1 1402.54  4196.8 1399.86  4256.6 1405.55  4357.7 1406.18
  4409.7 1404.39    4519 1392.02  4541.5 1395.56  4571.9 1393.29  4592.2 1396.22
  4622.6 1395.92  4663.2 1391.12  4701.4 1383.81  4762.3 1377.57  4919.7 1375.92
  4936.9 1375.83  4957.2 1371.83  4994.7 1368.51  4997.5 1368.01  5000.7 1368.51
  5048.4 1374.79  5146.3 1375.71  5212.3 1382.86  5230.8 1383.22  5258.9 1379.98
  5290.7 1381.01  5445.9 1391.12  5619.3 1400.21  5709.3 1400.77  5796.1 1398.46
#Mann= 9 ,-1 , 0
  4027.9     .05       0  4128.1      .1       0  4256.6     .05       0
  4357.7      .1       0  4919.7     .05       0  4994.7    .035       0
  5000.7     .05       0  5212.3      .1       0  5445.9     .05       0
Bank Sta=4994.7,5000.7
XS Rating Curve= 0 ,0
Exp/Cntr=0.3,0.1

Type RM Length L Ch R = 1 ,1362    ,520,520,520
BEGIN DESCRIPTION:
TANK WATER CREEK 3.0
END DESCRIPTION:
XS GIS Cut Line= 4
      2867802.81     10107289.51      2867546.74     10107311.22
       2867229.9     10107771.28      2867073.65     10108543.84
#Sta/Elev= 30
  4452.1 1407.43  4490.9 1406.43  4526.7 1404.53  4576.9 1399.29  4647.1 1401.14
    4681 1399.87  4697.3 1401.91  4716.5 1402.29  4803.1 1395.63    4818  1392.1
  4824.1 1392.06    4839 1389.34  4910.6 1371.37  4931.6 1365.12  4946.5 1362.82
  4979.3 1360.27  4982.1 1359.77  4985.3 1360.27  5012.1 1361.78  5033.1 1368.46
  5119.6 1373.86    5263  1375.5  5399.4 1383.19  5404.5 1382.51  5500.9 1384.43
  5702.4 1385.03  5789.2 1386.67  5897.8 1390.56    6003    1396  6055.9 1397.64
#Mann= 7 ,-1 , 0
  4452.1     .16       0  4490.9      .1       0  4979.3     .07       0
  4985.3      .1       0  5702.4     .05       0  5789.2      .1       0
  5897.8     .05       0
Bank Sta=4979.3,4985.3
XS Rating Curve= 0 ,0
Exp/Cntr=0.3,0.1

Type RM Length L Ch R = 1 ,842     ,439,439,439
BEGIN DESCRIPTION:
TANK WATER CREEK 2.0
END DESCRIPTION:
XS GIS Cut Line= 3
      2867806.02     10107247.26       2867095.6     10107261.19
       2866023.2     10107832.21
#Sta/Elev= 30
  4153.4 1405.28  4193.4 1405.73    4451 1404.79  4506.4 1398.47  4570.4 1392.81
  4681.1 1390.05  4786.2 1373.27  4888.3 1361.91  4906.9 1362.05  4944.8 1361.43
  4993.7  1353.6  4996.4  1353.1  4999.7  1353.6  5019.3 1356.56  5032.6 1363.61
  5234.6  1366.3  5317.6 1374.11    5433 1389.03  5574.8 1393.55  5707.3  1403.8
  5778.8 1398.31  5839.1 1404.04  5926.9 1418.15  5959.5 1428.92  5987.2 1430.06
  6009.1 1434.79  6031.1 1442.42  6047.4 1451.78  6075.1 1457.66  6078.9    1461
#Mann= 11 ,-1 , 0
  4153.4     .16       0  4193.4      .1       0  4506.4     .05       0
  4570.4      .1       0  4786.2     .16       0  4888.3      .1       0
  4906.9     .16       0  4993.7     .07       0  4999.7     .16       0
  5317.6      .1       0  5574.8     .16       0
Bank Sta=4993.7,4999.7
XS Rating Curve= 0 ,0
Exp/Cntr=0.3,0.1

Type RM Length L Ch R = 1 ,403     ,269,269,269
BEGIN DESCRIPTION:
TANK WATER CREEK 1.0
END DESCRIPTION:
XS GIS Cut Line= 3
      2867346.38     10106829.34      2866816.99     10106912.93
        2865689.     10107999.14
#Sta/Elev= 30
    4376 1408.59  4432.9 1409.68  4535.9 1390.32  4586.5 1387.09  4630.3 1389.82
  4716.3 1378.42  4859.8 1364.79  4900.3 1355.31    4946 1356.47  5000.5 1350.57
  5003.2 1350.07  5006.5 1350.57  5088.4 1361.82    5287 1373.74  5374.7 1381.59
  5418.6 1384.71  5484.3 1389.63  5569.2 1404.47  5639.9 1434.37  5654.1 1437.62
  5760.1  1433.6    5838 1438.89  5873.3  1434.9  5908.8 1444.41    5944 1446.05
  5986.5 1455.92  6078.3 1464.74  6112.1 1474.97  6170.4 1487.28  6477.9 1495.79
#Mann= 9 ,-1 , 0
    4376      .1       0  4716.3     .16       0    4946      .1       0
  5000.5     .07       0  5006.5      .1       0    5287     .16       0
  5374.7      .1       0  5418.6     .16       0  6112.1      .1       0
Bank Sta=5000.5,5006.5
XS Rating Curve= 0 ,0
Exp/Cntr=0.3,0.1

Type RM Length L Ch R = 1 ,134     ,0,0,0
BEGIN DESCRIPTION:
TANK WATER CREEK 1.1
END DESCRIPTION:
XS GIS Cut Line= 4
      2867253.58      10106748.5      2866710.17     10106696.42
      2866545.24     10106793.64      2866166.99     10107308.97
#Sta/Elev= 30
  4348.4 1411.17  4449.9 1386.49  4559.2 1373.82  4805.6 1353.17    4959 1351.93
  4995.9 1347.02  5033.2 1351.57  5076.1 1359.51  5105.1 1362.54  5206.2 1367.61
  5370.5 1381.04  5426.9  1383.4  5491.7 1391.27  5527.2 1398.68  5533.4 1402.24
  5541.8 1402.68    5548 1407.17  5556.5 1407.43  5562.7 1410.91  5577.4 1412.44
  5583.6 1416.15    5592 1417.31  5598.2 1421.74  5612.9 1426.03  5629.2 1427.86
  5669.2 1438.75  5683.9 1440.66  5698.5 1440.96  5713.2 1437.79    5725 1440.23
#Mann= 6 ,-1 , 0
  4348.4      .1       0  4559.2     .16       0    4959     .05       0
  5033.2     .07       0  5206.2      .1       0  5629.2     .16       0
Bank Sta=4959,5033.2
XS Rating Curve= 0 ,0
Exp/Cntr=0.3,0.1

Chan Stop Cuts=-1
Use User Specified Reach Order=0
Composite Channel Slope=5