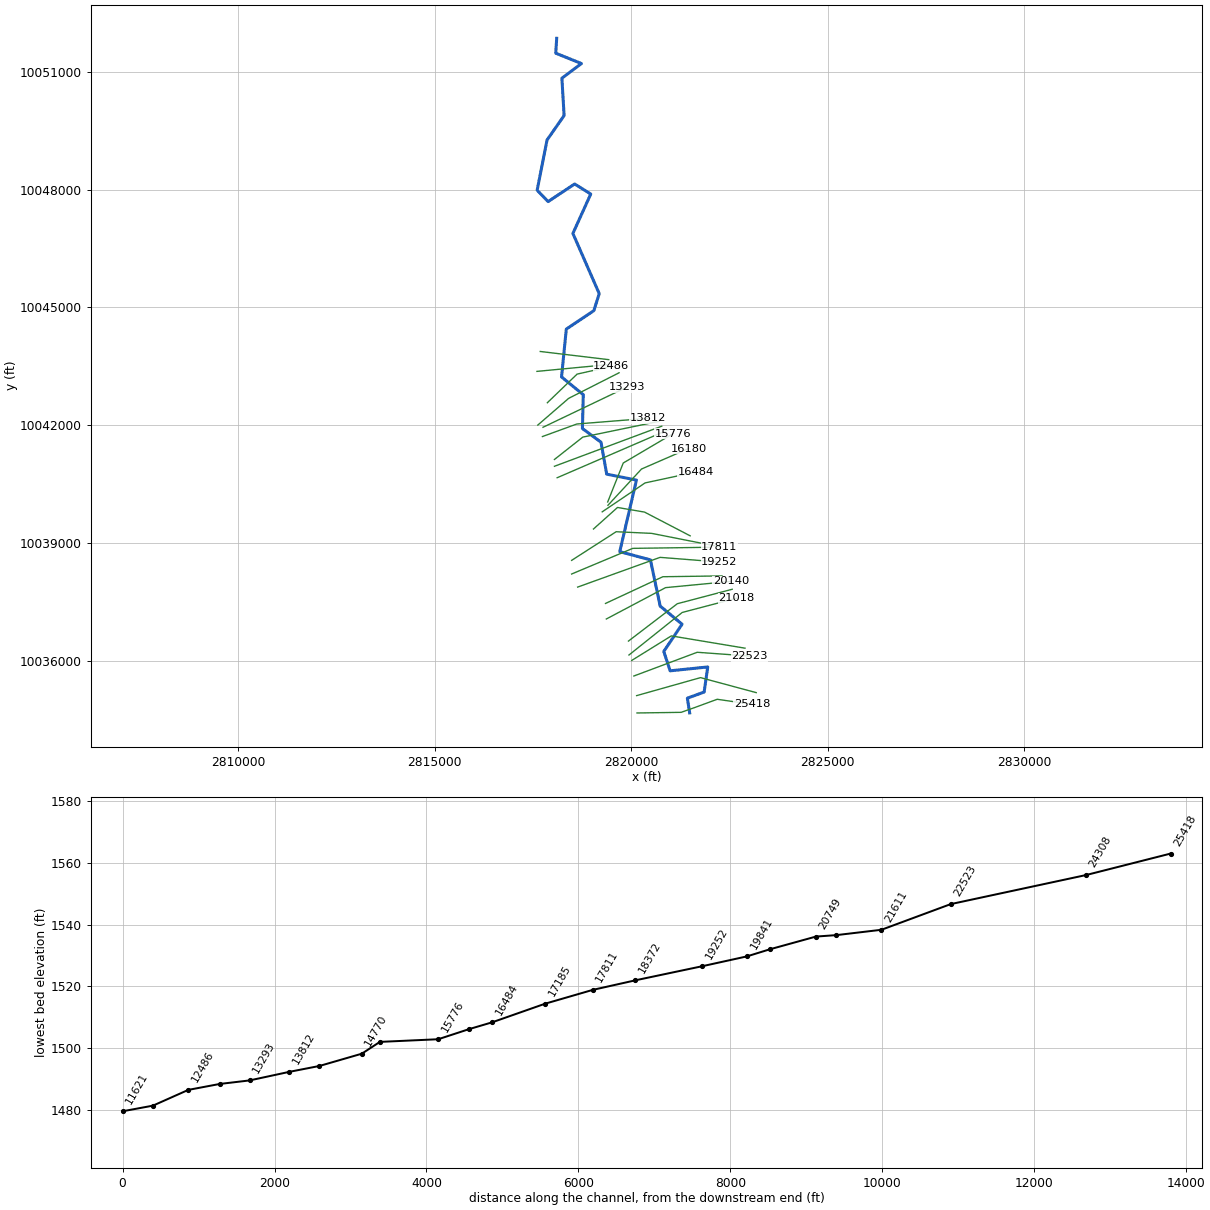
--- THREEMILE CREEK.prj (project) ---

Proj Title=THREEMILE CREEK Base Level Engineering
Current Plan=p01
Default Exp/Contr=0.3,0.1
English Units
Geom File=g01
Flow File=f01
Plan File=p01
Y Axis Title=Elevation
X Axis Title(PF)=Main Channel Distance
X Axis Title(XS)=Station
BEGIN DESCRIPTION:
THREEMILE CREEK
END DESCRIPTION:
DSS Export Rating Curves= 0
DSS Export Rating Curve Sorted= 0
DSS Export Volume Flow Curves= 0
DXF OffsetX= 0
DXF OffsetY= 0
DXF ScaleX= 1
DXF ScaleY= 10

--- THREEMILE CREEK.p01 (plan) ---

Plan Title=Multiple Run
Short Identifier=Multiple
Geom File=g01
Flow File=f01
Subcritical Flow
K Sum by GR= 0
Std Step Tol= 0.01
Critical Tol= 0.01
Num of Std Step Trials= 20
Max Error Tol= 0.3
Flow Tol Ratio= 0.001
Split Flow NTrial= 30
Split Flow Tol= 0.02
Split Flow Ratio= 0.02
Log Output Level= 0
Friction Slope Method= 1
Unsteady Friction Slope Method= 2
Unsteady Bridges Friction Slope Method= 1
Parabolic Critical Depth
Global Vel Dist=  1 , 1 , 1
Global Log Level= 0
CheckData=True
Encroach Param= -1, 0, 0, 0
BEGIN DESCRIPTION:
Multiple Run
END DESCRIPTION:

--- THREEMILE CREEK.f01 (steady flow) ---

Flow Title=Multiple
Program Version=4.10
Number of Profiles= 7
Profile Names=10-year,25-year,50-year,1pct_min,100-year,1pct_plu,500-year
River Rch & RM=THREEMILE CREEK,Reach-1         ,25418
    3069    4705    6200    5956    8055   10894   13661
River Rch & RM=THREEMILE CREEK,Reach-1         ,24308
    3069    4705    6200    5956    8055   10894   13661
River Rch & RM=THREEMILE CREEK,Reach-1         ,20140
    3268    5012    6606    6344    8580   11604   14545
River Rch & RM=THREEMILE CREEK,Reach-1         ,15008
    3371    5175    6824    6556    8867   11991   15043
River Rch & RM=THREEMILE CREEK,Reach-1         ,13812
    3505    5379    7092    6811    9211   12457   15614
River Rch & RM=THREEMILE CREEK,Reach-1         ,9911
    3527    5394    7095    6796    9191   12430   15498
Boundary for River Rch & Prof#=THREEMILE CREEK,Reach-1         , 1
Up Type= 0
Dn Type= 3
Dn Slope=0.01073
Boundary for River Rch & Prof#=THREEMILE CREEK,Reach-1         , 2
Up Type= 0
Dn Type= 3
Dn Slope=0.01073
Boundary for River Rch & Prof#=THREEMILE CREEK,Reach-1         , 3
Up Type= 0
Dn Type= 3
Dn Slope=0.01073
Boundary for River Rch & Prof#=THREEMILE CREEK,Reach-1         , 4
Up Type= 0
Dn Type= 3
Dn Slope=0.01073
Boundary for River Rch & Prof#=THREEMILE CREEK,Reach-1         , 5
Up Type= 0
Dn Type= 3
Dn Slope=0.01073
Boundary for River Rch & Prof#=THREEMILE CREEK,Reach-1         , 6
Up Type= 0
Dn Type= 3
Dn Slope=0.01073
Boundary for River Rch & Prof#=THREEMILE CREEK,Reach-1         , 7
Up Type= 0
Dn Type= 3
Dn Slope=0.01073
DSS Import GetInterval= 0
DSS Import GetPeak= 0
DSS Import FillOption= 0

--- THREEMILE CREEK.g01 (geometry) ---

Geom Title=Existing Conditions
Program Version=4.10

River Reach=THREEMILE CREEK ,Reach-1
Reach XY= 30
      2821488.47     10034673.73      2821429.58     10035048.53
      2821856.22     10035204.42      2821948.47     10035843.73
      2820991.63     10035744.98      2820830.34     10036238.36
      2821295.33     10036932.43      2820738.47     10037393.73
      2820490.93     10038570.25      2819710.23     10038779.22
      2820134.97     10040602.42      2819378.84     10040753.19
      2819233.28     10041566.45       2818761.2      10041914.8
      2818782.79     10042776.13      2818229.99     10043228.98
      2818351.05     10044446.62       2819051.7     10044916.94
      2819188.71     10045350.01      2818518.98     10046883.09
      2818973.11     10047886.36      2818563.96     10048142.21
      2817887.76     10047693.96      2817609.56     10047983.84
      2817861.32     10049262.55      2818295.39     10049884.94
      2818238.77     10050835.63      2818736.29      10051209.4
      2818082.76     10051472.85      2818106.72     10051851.62

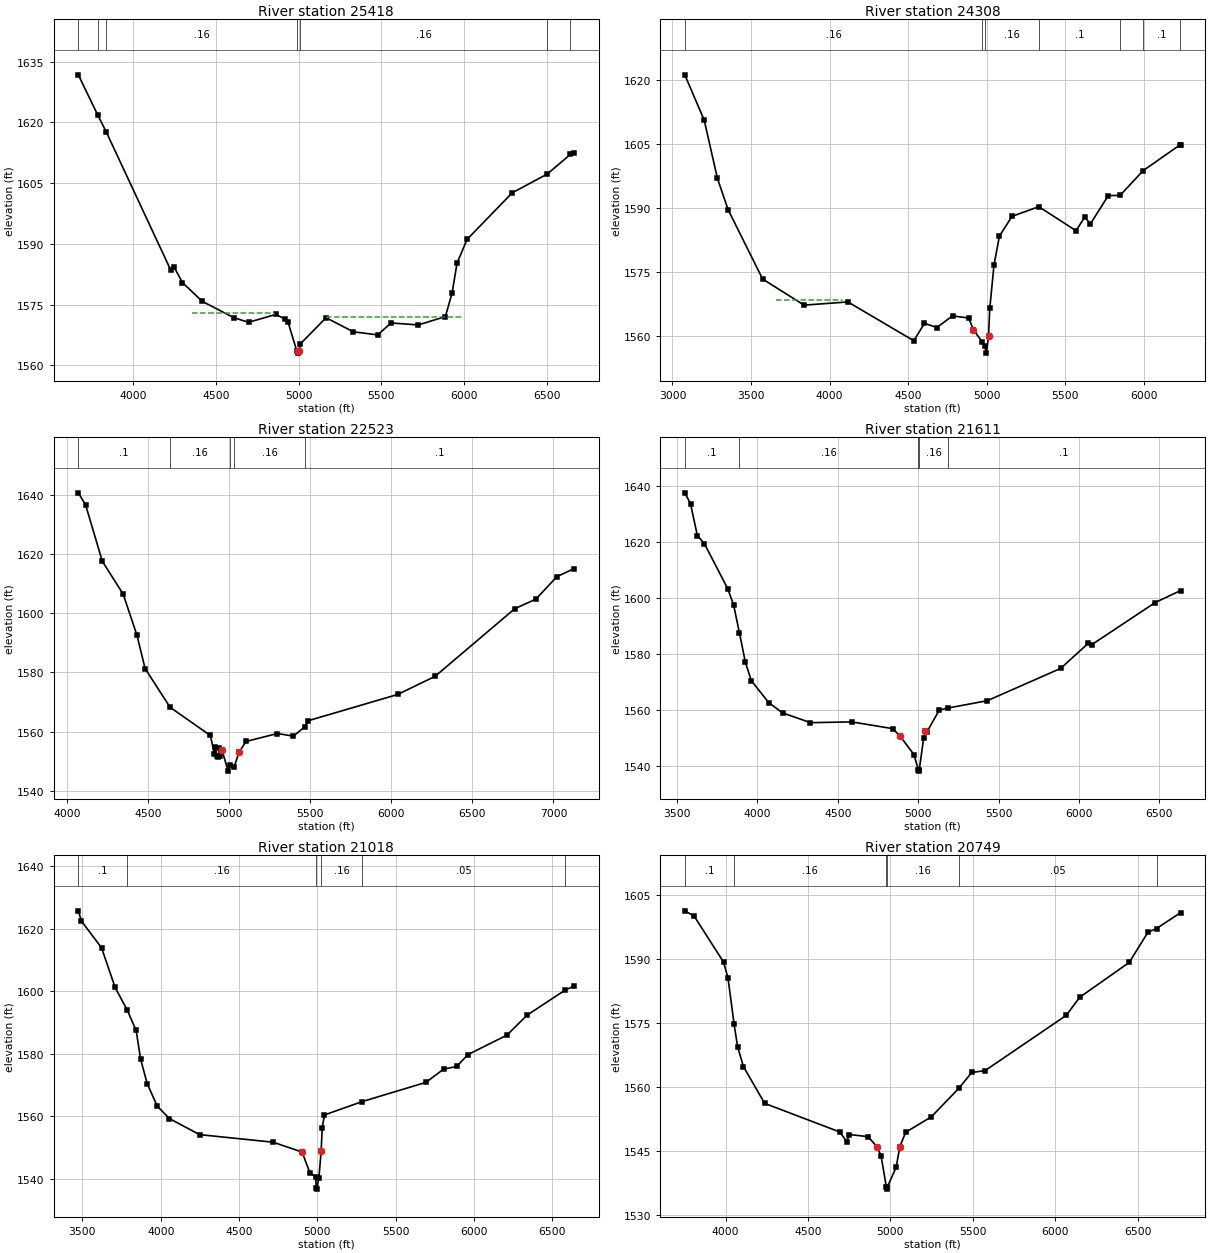
Type RM Length L Ch R = 1 ,25418   ,1110,1110,1110
BEGIN DESCRIPTION:
THREEMILE CREEK 43.0
END DESCRIPTION:
XS GIS Cut Line= 5
      2820149.18      10034671.8       2821272.1     10034687.93
      2821627.05     10034813.78      2822188.53      10035020.3
      2823079.14     10034891.23
#Sta/Elev= 30
  3668.5 1631.75  3785.6 1621.85  3837.8 1617.61  4227.8 1583.49  4247.8 1584.27
  4297.8 1580.46  4417.9 1575.82  4607.9  1571.8  4697.9 1570.65  4861.9 1572.59
    4917 1571.47  4936.2 1570.72  4989.3 1563.59    4996 1563.54  4998.7 1563.04
    5002 1563.54  5010.5  1565.3  5166.2 1571.78  5331.1 1568.31  5478.6 1567.54
  5558.8 1570.49  5723.7    1570  5887.6 1572.06    5928 1577.83  5958.3 1585.28
  6018.9 1591.12  6291.8 1602.62    6504 1607.26    6643 1612.09  6666.3 1612.41
#Mann= 7 ,-1 , 0
  3668.5     .05       0  3785.6      .1       0  3837.8     .16       0
  4989.3     .07       0  5010.5     .16       0    6504     .05       0
    6643      .1       0
#XS Ineff= 2 ,-1
 4358.02  4853.7  1572.9 5173.26 5993.53 1571.94
Permanent Ineff=
       T       T
Bank Sta=4996,5002
XS Rating Curve= 0 ,0
Exp/Cntr=0.3,0.1

Type RM Length L Ch R = 1 ,24308   ,1785,1785,1785
BEGIN DESCRIPTION:
THREEMILE CREEK 43.0
END DESCRIPTION:
XS GIS Cut Line= 3
      2820139.57     10035113.41      2821764.58     10035571.75
      2823181.28      10035189.8
#Sta/Elev= 30
  3078.4 1621.23  3201.9 1610.63  3286.2 1596.97  3354.2 1589.66  3573.8 1573.43
  3837.8 1567.33  4116.3 1568.08  4535.9    1559  4603.9 1563.08  4682.3 1562.09
  4782.4 1564.81  4884.8 1564.32  4915.8 1561.54  4971.6 1558.72  4988.3 1557.73
  4998.4  1556.1  5011.6 1560.18  5019.4 1566.56  5046.3 1576.74  5081.1 1583.51
  5160.9 1588.11  5331.5 1590.37  5568.3 1584.75  5624.4 1587.98  5659.2  1586.3
  5773.8 1592.98  5848.4    1593  5995.3  1598.8  6233.1 1604.91  6234.1 1604.91
#Mann= 7 ,-1 , 0
  3078.4     .16       0  4971.6     .07       0  4988.3     .16       0
  5331.5      .1       0  5848.4     .05       0  5995.3      .1       0
  6233.1     .05       0
#XS Ineff= 2 ,-1
 3658.79 4075.94 1568.52 4192.95 4841.57 1564.41
Permanent Ineff=
       T       T
Bank Sta=4915.8,5011.6
XS Rating Curve= 0 ,0
Exp/Cntr=0.3,0.1

Type RM Length L Ch R = 1 ,22523   ,912,912,912
BEGIN DESCRIPTION:
THREEMILE CREEK 42.0
END DESCRIPTION:
XS GIS Cut Line= 3
      2820070.18     10035613.43      2821681.25     10036217.58
      2823013.99      10036120.4
#Sta/Elev= 30
  4070.6 1640.71  4115.5 1636.62  4218.3  1617.6  4346.9 1606.48  4432.3 1592.54
  4482.2 1581.33    4636 1568.25  4884.5 1558.71  4909.4 1552.49  4914.7 1554.95
  4923.2 1551.82  4933.8 1551.56  4939.6 1554.63    4945 1551.91  4955.2 1553.93
  4994.6 1546.66  5008.6 1548.76  5030.4 1547.97    5062 1553.14  5104.7 1556.69
    5297 1559.36  5397.1  1558.5  5467.8  1561.7  5489.2 1563.72  6039.1 1572.56
  6269.7 1578.68    6761 1601.54  6891.3 1604.78  7021.7 1612.41  7127.5 1615.11
#Mann= 5 ,-1 , 0
  4070.6      .1       0    4636     .16       0  5008.6     .07       0
  5030.4     .16       0  5467.8      .1       0
Bank Sta=4955.2,5062
XS Rating Curve= 0 ,0
Exp/Cntr=0.3,0.1

Type RM Length L Ch R = 1 ,21611   ,593,593,593
BEGIN DESCRIPTION:
THREEMILE CREEK 41.0
END DESCRIPTION:
XS GIS Cut Line= 3
      2820014.56     10036009.23      2821021.53     10036634.25
      2822895.01       10036322.
#Sta/Elev= 30
    3548 1637.72  3583.5 1633.86    3626 1622.48  3670.3 1619.51    3815 1603.49
  3851.6 1597.71  3888.2 1587.61  3924.8 1577.23  3961.4 1570.68  4070.5 1562.78
  4156.3 1559.15  4329.9 1555.64  4586.2 1555.92  4841.6 1553.51  4887.8  1550.8
  4973.4 1544.26  5000.8 1538.84  5003.5 1538.34  5006.8 1538.84  5034.2 1550.27
  5044.3 1552.63  5054.5 1552.36  5131.1 1560.14  5182.7 1560.84  5429.6 1563.49
  5885.8 1575.01  6058.1 1583.99  6078.4 1583.45  6474.4 1598.54  6632.5 1602.83
#Mann= 5 ,-1 , 0
    3548      .1       0  3888.2     .16       0  5000.8     .07       0
  5006.8     .16       0  5182.7      .1       0
Bank Sta=4887.8,5044.3
XS Rating Curve= 0 ,0
Exp/Cntr=0.3,0.1

Type RM Length L Ch R = 1 ,21018   ,269,269,269
BEGIN DESCRIPTION:
THREEMILE CREEK 40.0
END DESCRIPTION:
XS GIS Cut Line= 3
      2819945.12     10036148.12       2821299.3     10037231.47
       2822684.1     10037595.31
#Sta/Elev= 30
  3473.9 1625.75  3494.1 1622.43  3622.2 1613.92  3708.6 1601.22  3785.5 1594.01
  3843.1 1587.42  3871.9 1578.18  3913.6 1570.41  3977.6  1563.2    4056  1559.2
  4248.1 1554.07  4718.7 1551.63  4902.8 1548.47  4952.4 1541.82  4989.3 1540.48
  4992.7 1537.11  4995.4 1536.61  5010.1 1540.24  5024.5 1548.89  5030.9 1556.13
  5045.3 1560.37  5286.6 1564.65  5693.2  1570.8  5806.9 1575.06  5889.6 1575.89
    5962 1579.71  6210.2 1585.92    6339 1592.32  6582.7 1600.37  6639.9 1601.67
#Mann= 6 ,-1 , 0
  3473.9      .1       0  3785.5     .16       0  4992.7     .07       0
  5024.5     .16       0  5286.6     .05       0  6582.7      .1       0
Bank Sta=4902.8,5024.5
XS Rating Curve= 0 ,0
Exp/Cntr=0.3,0.1

Type RM Length L Ch R = 1 ,20749   ,609,609,609
BEGIN DESCRIPTION:
THREEMILE CREEK 39.0
END DESCRIPTION:
XS GIS Cut Line= 3
      2819931.23     10036502.29       2821174.3     10037453.69
      2822570.11     10037821.74
#Sta/Elev= 30
  3752.4 1601.33    3809  1600.1  3987.6 1589.32  4014.7 1585.57  4051.2 1574.86
  4072.8 1569.49  4108.2 1564.85  4236.9 1556.23  4693.4 1549.52  4735.6 1547.24
  4750.1 1548.93  4864.4 1548.44  4920.5 1545.98  4943.3 1543.92  4975.6 1536.64
  4978.4 1536.14  4981.6 1536.64  5034.8 1541.25  5057.5  1546.1  5092.9 1549.46
  5248.8 1553.08  5418.2 1559.88  5493.6 1563.47  5574.2 1563.89  6066.7 1576.83
  6149.4 1581.09  6449.3 1589.24  6563.1 1596.31    6615 1597.19  6761.3  1600.9
#Mann= 6 ,-1 , 0
  3752.4      .1       0  4051.2     .16       0  4975.6     .07       0
  4981.6     .16       0  5418.2     .05       0    6615      .1       0
Bank Sta=4920.5,5057.5
XS Rating Curve= 0 ,0
Exp/Cntr=0.3,0.1

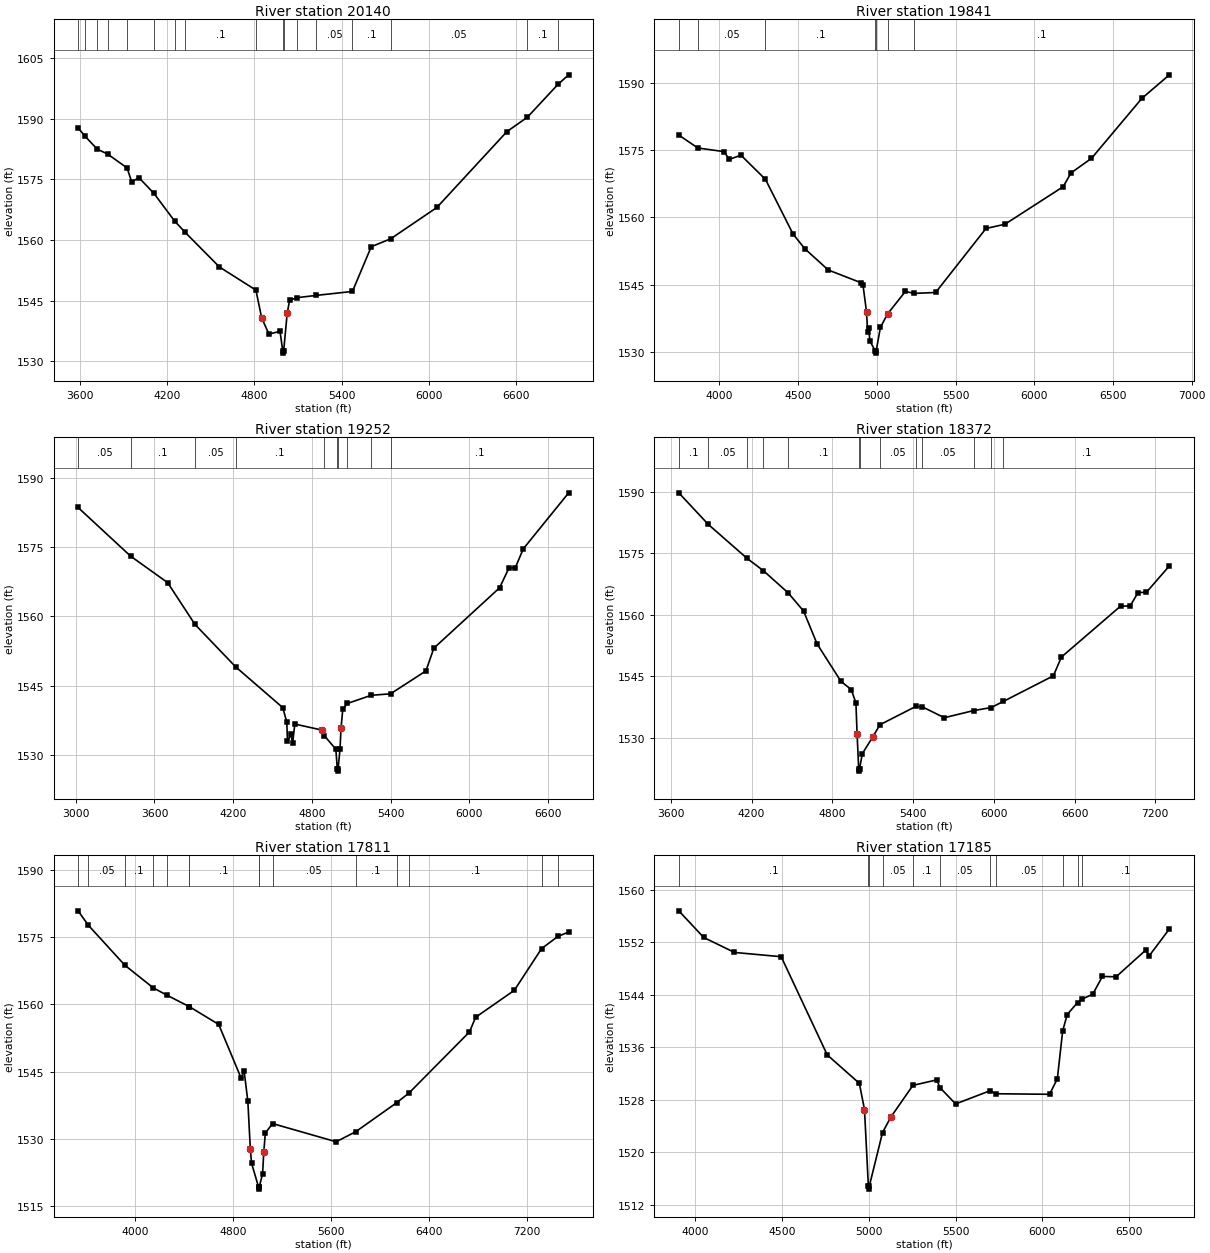
Type RM Length L Ch R = 1 ,20140   ,299,299,299
BEGIN DESCRIPTION:
THREEMILE CREEK 38.0
END DESCRIPTION:
XS GIS Cut Line= 3
      2819368.75     10037064.81      2820875.69     10037863.42
      2822542.38     10038023.14
#Sta/Elev= 30
    3585 1587.76  3631.1 1585.77  3716.5  1582.5  3787.9 1581.29  3922.6 1577.85
  3954.5 1574.37  4004.1 1575.44  4108.3 1571.52  4250.1 1564.69  4322.1 1561.92
    4559 1553.32  4810.2  1547.6    4850 1540.69  4899.6 1536.72  4976.3 1537.39
  4995.3  1532.5    4998    1532  5001.3  1532.5  5025.9 1541.96  5042.3 1545.05
    5092 1545.72  5225.9 1546.29  5475.3 1547.27  5604.7 1558.34  5738.7  1560.3
  6056.7 1568.05  6538.9 1586.82  6680.5  1590.4  6890.9 1598.52  6964.8 1600.89
#Mann= 17 ,-1 , 0
    3585     .05       0  3631.1      .1       0  3716.5     .05       0
  3787.9      .1       0  3922.6     .05       0  4108.3      .1       0
  4250.1     .05       0  4322.1      .1       0  4810.2     .16       0
  4995.3     .07       0  5001.3     .16       0    5092      .1       0
  5225.9     .05       0  5475.3      .1       0  5738.7     .05       0
  6680.5      .1       0  6890.9     .05       0
Bank Sta=4850,5025.9
XS Rating Curve= 0 ,0
Exp/Cntr=0.3,0.1

Type RM Length L Ch R = 1 ,19841   ,589,589,589
BEGIN DESCRIPTION:
THREEMILE CREEK 37.0
END DESCRIPTION:
XS GIS Cut Line= 3
      2819347.95     10037460.65      2820806.25     10038141.19
      2822313.23     10038162.03
#Sta/Elev= 30
  3742.1 1578.31  3862.8 1575.43  4029.6 1574.62  4062.7 1572.89    4137 1573.82
  4292.5 1568.44    4468 1556.25  4542.1    1553  4691.7 1548.24  4901.6 1545.38
  4912.4 1544.85  4934.5 1538.93  4941.8 1534.42  4947.3 1535.26  4956.6 1532.38
    4990 1530.22  4992.8 1529.72    4996 1530.22  5022.8 1535.45  5068.1 1538.44
  5181.4 1543.46  5237.1 1543.03  5373.6 1543.23  5693.6  1557.5  5813.6 1558.43
  6183.7  1566.8  6233.7 1569.88  6363.7 1573.12  6683.7 1586.48  6858.5 1591.73
#Mann= 7 ,-1 , 0
  3742.1      .1       0  3862.8     .05       0  4292.5      .1       0
    4990     .07       0    4996      .1       0  5068.1     .16       0
  5237.1      .1       0
Bank Sta=4934.5,5068.1
XS Rating Curve= 0 ,0
Exp/Cntr=0.3,0.1

Type RM Length L Ch R = 1 ,19252   ,880,880,880
BEGIN DESCRIPTION:
THREEMILE CREEK 36.0
END DESCRIPTION:
XS GIS Cut Line= 3
      2818639.62     10037877.32       2820736.8     10038634.25
      2822243.59     10038516.21
#Sta/Elev= 30
  3017.6 1583.56  3417.9 1573.04  3700.7  1567.3  3908.6 1558.28  4219.8 1549.07
  4578.4 1540.27  4609.1 1537.14  4614.4 1532.98  4639.7 1534.49  4653.6 1532.58
  4670.4 1536.71  4874.5 1535.43    4896 1534.18  4983.2 1531.27  4994.2 1527.03
    4997 1526.53  5000.2 1527.03  5015.1 1531.32  5022.6  1535.8  5036.3 1539.97
  5071.7 1541.17  5253.8 1542.94  5400.1 1543.25  5670.2 1548.21  5730.3 1553.12
  6231.9 1566.19  6302.1  1570.4  6352.2 1570.57  6412.4 1574.61  6758.6 1586.73
#Mann= 10 ,-1 , 0
  3017.6     .05       0  3417.9      .1       0  3908.6     .05       0
  4219.8      .1       0    4896     .05       0  4994.2    .035       0
  5000.2     .05       0  5071.7      .1       0  5253.8     .05       0
  5400.1      .1       0
Bank Sta=4874.5,5022.6
XS Rating Curve= 0 ,0
Exp/Cntr=0.3,0.1

Type RM Length L Ch R = 1 ,18372   ,561,561,561
BEGIN DESCRIPTION:
THREEMILE CREEK 35.0
END DESCRIPTION:
XS GIS Cut Line= 3
      2818486.84     10038210.65      2820042.36     10038863.42
      2822000.73     10038891.19
#Sta/Elev= 30
    3659 1589.69  3877.9 1582.01  4166.2 1573.74  4286.9 1570.76  4471.2 1565.36
  4586.2 1560.92  4686.7 1552.92  4863.9 1543.81  4940.5 1541.81  4975.2 1538.55
  4983.8 1531.05    4996 1522.46  4998.7 1521.96    5002 1522.46  5022.8 1526.21
  5099.5 1530.24  5153.8 1533.25  5419.3 1537.69  5466.1 1537.64  5632.1 1534.96
  5850.6  1536.7  5980.2 1537.43  6069.8 1538.91  6442.2 1545.15  6502.2 1549.72
  6942.2 1562.13  7012.2 1562.14  7072.2 1565.42    7134 1565.49  7304.5 1571.91
#Mann= 13 ,-1 , 0
    3659      .1       0  3877.9     .05       0  4166.2      .1       0
  4286.9     .05       0  4471.2      .1       0    4996     .07       0
    5002      .1       0  5153.8     .05       0  5419.3      .1       0
  5466.1     .05       0  5850.6      .1       0  5980.2     .05       0
  6069.8      .1       0
Bank Sta=4983.8,5099.5
XS Rating Curve= 0 ,0
Exp/Cntr=0.3,0.1

Type RM Length L Ch R = 1 ,17811   ,626,626,626
BEGIN DESCRIPTION:
THREEMILE CREEK 34.0
END DESCRIPTION:
XS GIS Cut Line= 4
      2818486.79     10038557.85      2819618.75     10039287.03
      2820521.53     10039245.36      2822243.61     10038905.11
#Sta/Elev= 30
  3535.6 1580.84  3619.8 1577.62    3918 1568.71  4149.8 1563.68  4260.7 1562.06
  4444.6 1559.49  4444.7 1559.49  4683.8 1555.54  4865.3 1543.69  4891.8 1545.06
  4921.8 1538.42  4941.9 1527.82  4951.9 1524.65  5008.9 1519.36  5011.7 1518.86
  5014.9 1519.36    5042 1522.26    5052 1527.15  5064.5 1531.35  5123.2 1533.46
  5642.6 1529.41  5802.2 1531.64  6136.2 1538.09  6237.7 1540.27  6730.7 1553.85
  6781.6 1557.13  7097.6 1563.14  7320.3 1572.44  7454.8 1575.16  7541.2 1576.12
#Mann= 15 ,-1 , 0
  3535.6      .1       0  3619.8     .05       0    3918      .1       0
  4149.8     .05       0  4260.7      .1       0  4444.6     .05       0
  4444.7      .1       0  5008.9     .07       0  5014.9      .1       0
  5123.2     .05       0  5802.2      .1       0  6136.2     .05       0
  6237.7      .1       0  7320.3     .05       0  7454.8     .16       0
Bank Sta=4941.9,5052
XS Rating Curve= 0 ,0
Exp/Cntr=0.3,0.1

Type RM Length L Ch R = 1 ,17185   ,701,701,701
BEGIN DESCRIPTION:
THREEMILE CREEK 33.0
END DESCRIPTION:
XS GIS Cut Line= 4
       2819042.4     10039356.51      2819653.47     10039905.08
      2820340.97     10039787.03      2821500.68     10039182.87
#Sta/Elev= 30
    3905 1556.79  4048.7 1552.73  4225.8 1550.45  4494.9  1549.8  4760.2 1534.84
  4945.2 1530.51  4974.8 1526.52  4997.1 1514.89  4999.9 1514.39  5003.1 1514.89
  5078.7 1523.01    5127 1525.38  5253.8  1530.2  5390.8 1531.03    5410 1529.84
  5499.9 1527.37  5698.1 1529.38  5731.8 1528.92  6041.1 1528.84  6085.8 1531.19
  6116.6 1538.48  6142.6 1540.99  6202.5 1542.82  6225.8  1543.3  6290.3  1544.1
  6345.3 1546.79  6424.5 1546.74    6594 1550.78  6616.1 1549.97  6731.4 1554.03
#Mann= 11 ,-1 , 0
    3905      .1       0  4997.1     .07       0  5003.1      .1       0
  5078.7     .05       0  5253.8      .1       0    5410     .05       0
  5698.1      .1       0  5731.8     .05       0  6116.6      .1       0
  6202.5     .05       0  6225.8      .1       0
Bank Sta=4974.8,5127
XS Rating Curve= 0 ,0
Exp/Cntr=0.3,0.1

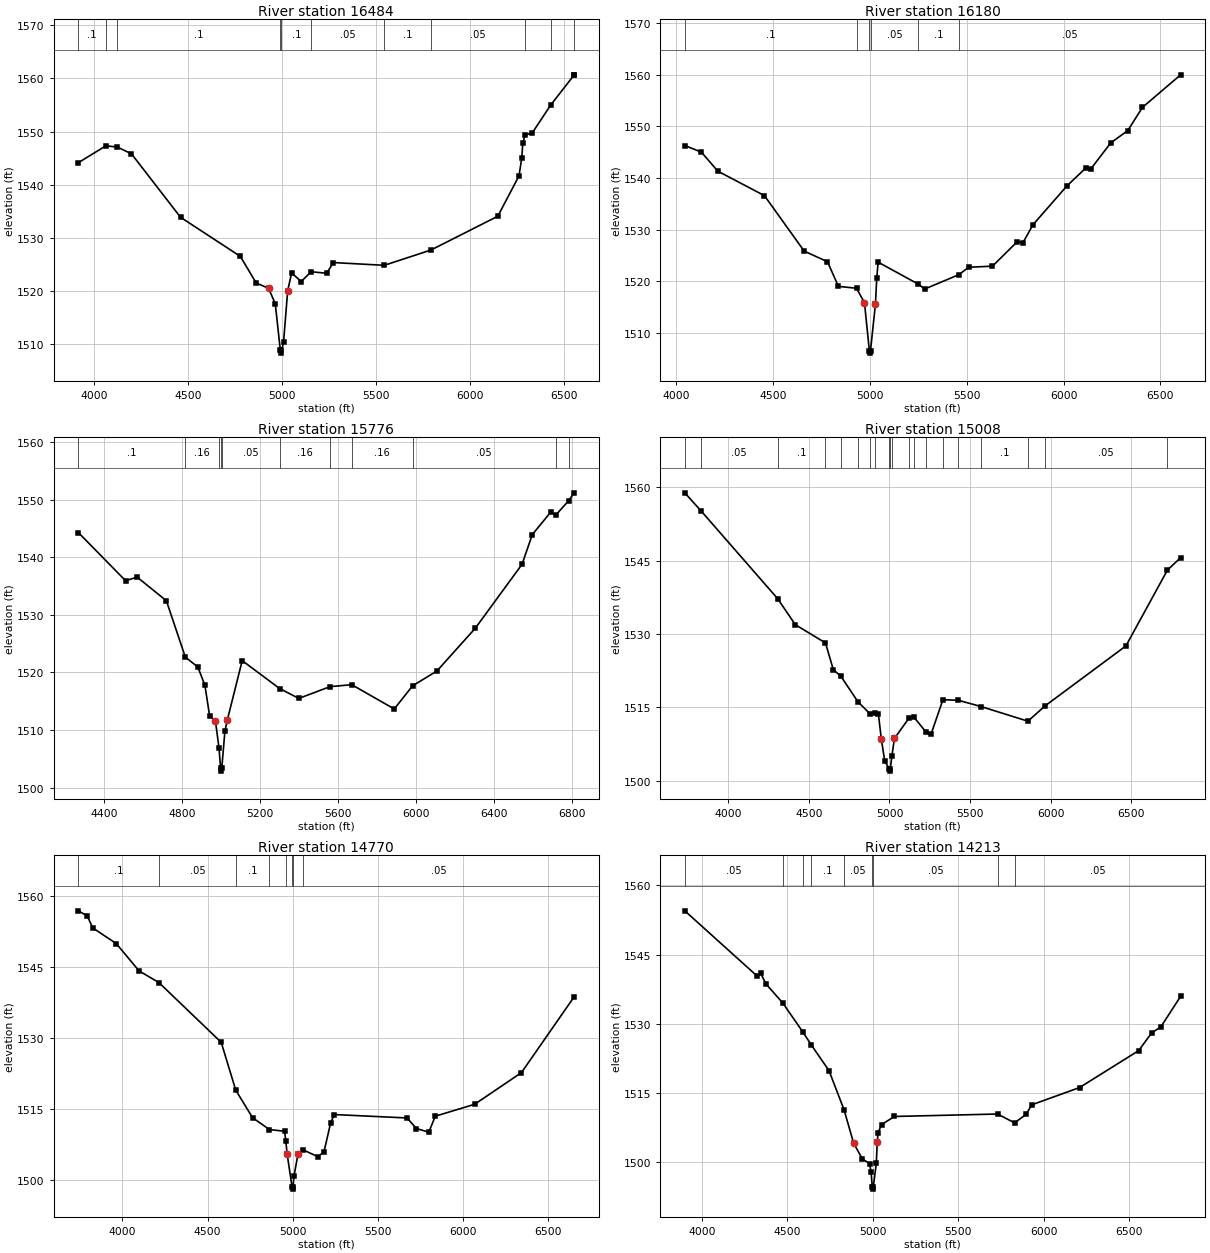
Type RM Length L Ch R = 1 ,16484   ,304,304,304
BEGIN DESCRIPTION:
THREEMILE CREEK 32.0
END DESCRIPTION:
XS GIS Cut Line= 3
      2819264.56     10039793.96      2820354.86     10040530.08
      2821645.03     10040807.54
#Sta/Elev= 30
  3916.8 1544.16  4063.6 1547.34  4124.1  1547.1  4199.2 1545.83    4460 1533.89
  4777.6 1526.54  4862.6  1521.5  4927.6 1520.55  4963.5 1517.62  4990.5 1508.83
  4993.2 1508.33  4996.5 1508.83  5007.4 1510.33  5029.4 1520.06  5050.4 1523.42
  5101.4  1521.8  5153.8 1523.64  5236.7 1523.36  5272.6 1525.37  5542.6 1524.85
  5790.4 1527.72  6146.4 1534.09  6258.9 1541.69  6273.3    1545  6279.3 1547.88
  6290.4 1549.33  6330.5 1549.82    6427 1554.99    6551 1560.62    6552 1560.69
#Mann= 11 ,-1 , 0
  3916.8      .1       0  4063.6     .16       0  4124.1      .1       0
  4990.5     .07       0  4996.5      .1       0  5153.8     .05       0
  5542.6      .1       0  5790.4     .05       0  6290.4      .1       0
    6427     .05       0    6551      .1       0
Bank Sta=4927.6,5029.4
XS Rating Curve= 0 ,0
Exp/Cntr=0.3,0.1

Type RM Length L Ch R = 1 ,16180   ,404,404,404
BEGIN DESCRIPTION:
THREEMILE CREEK 31.0
END DESCRIPTION:
XS GIS Cut Line= 3
      2819410.43     10039960.65      2820264.58     10040884.25
      2821459.05     10041405.09
#Sta/Elev= 30
  4043.4 1546.28  4129.3 1544.99  4213.9 1541.32  4454.8 1536.58  4660.1 1525.85
  4780.3  1523.8    4837 1519.03  4930.3 1518.67  4971.4 1515.88  4996.7 1506.62
  4999.5 1506.12  5002.7 1506.62  5028.1 1515.57  5034.9  1520.6  5041.9 1523.72
    5249 1519.47  5282.7 1518.52  5458.6 1521.29  5510.1 1522.73  5632.7 1522.94
  5760.7 1527.68  5789.6 1527.45  5841.8 1530.95  6016.7 1538.44  6115.8 1541.97
  6139.2 1541.68  6243.9  1546.8  6331.1 1549.15  6407.5 1553.66  6604.5 1559.95
#Mann= 6 ,-1 , 0
  4043.4      .1       0  4930.3     .05       0  4996.7    .035       0
  5002.7     .05       0    5249      .1       0  5458.6     .05       0
Bank Sta=4971.4,5028.1
XS Rating Curve= 0 ,0
Exp/Cntr=0.3,0.1

Type RM Length L Ch R = 1 ,15776   ,768,768,768
BEGIN DESCRIPTION:
THREEMILE CREEK 30.0
END DESCRIPTION:
XS GIS Cut Line= 3
      2819403.46     10040043.94       2819799.3     10041037.03
      2821070.12     10041787.02
#Sta/Elev= 30
  4268.1 1544.27  4510.6 1535.91  4569.9 1536.53    4720 1532.43  4817.2 1522.65
  4881.5 1520.93  4917.7 1517.75    4942 1512.44  4971.7 1511.55  4990.2 1506.86
  4998.3 1503.36  5001.1 1502.86  5004.3 1503.36  5020.2 1509.74  5032.2 1511.66
  5109.1 1522.04  5300.9  1517.2  5399.8 1515.48  5559.6 1517.52  5671.3 1517.86
  5889.6 1513.65  5983.5 1517.66  6108.1 1520.23  6305.2 1527.65  6545.2 1538.75
  6597.9 1543.91  6693.5 1547.85  6718.8 1547.32  6783.8 1549.75  6812.8 1551.16
#Mann= 11 ,-1 , 0
  4268.1      .1       0  4817.2     .16       0  4990.2     .05       0
  4998.3    .035       0  5004.3     .05       0  5300.9     .16       0
  5559.6      .1       0  5671.3     .16       0  5983.5     .05       0
  6718.8      .1       0  6783.8     .05       0
Bank Sta=4971.7,5032.2
XS Rating Curve= 0 ,0
Exp/Cntr=0.3,0.1

Type RM Length L Ch R = 1 ,15008   ,238,238,238
BEGIN DESCRIPTION:
THREEMILE CREEK 29.0
END DESCRIPTION:
XS GIS Cut Line= 2
      2818118.76     10040662.03      2820944.29     10041883.88
#Sta/Elev= 30
  3729.1 1558.85  3830.2 1555.15  4304.9 1537.26  4415.2 1531.92  4602.5 1528.19
  4651.2 1522.73  4698.7 1521.36  4804.2 1516.16  4877.7 1513.75  4909.7  1513.8
  4931.4 1513.58    4949 1508.61  4970.8 1503.99  4998.9  1502.5  5001.6    1502
  5004.9  1502.5  5015.2 1505.17  5030.8 1508.68  5120.8 1512.82  5152.9 1512.98
  5226.3 1509.99  5258.6 1509.61  5331.8 1516.59  5428.1 1516.47  5570.5 1515.17
  5859.4  1512.2  5964.9  1515.3  6467.9 1527.58  6725.3 1543.05  6807.5 1545.62
#Mann= 20 ,-1 , 0
  3729.1      .1       0  3830.2     .05       0  4304.9      .1       0
  4602.5     .05       0  4698.7     .16       0  4804.2      .1       0
  4877.7     .16       0  4909.7     .05       0  4998.9    .035       0
  5004.9     .05       0  5015.2      .1       0  5120.8     .05       0
  5152.9      .1       0  5226.3     .05       0  5331.8      .1       0
  5428.1     .05       0  5570.5      .1       0  5859.4     .16       0
  5964.9     .05       0  6725.3      .1       0
Bank Sta=4949,5030.8
XS Rating Curve= 0 ,0
Exp/Cntr=0.3,0.1

Type RM Length L Ch R = 1 ,14770   ,557,557,557
BEGIN DESCRIPTION:
THREEMILE CREEK 28.0
END DESCRIPTION:
XS GIS Cut Line= 2
      2818049.32      10040953.7      2820778.45     10041974.52
#Sta/Elev= 30
  3740.6 1556.87  3793.1  1555.8  3825.1 1553.27  3963.9 1549.95  4097.4  1544.2
  4214.1 1541.74  4580.3 1529.13  4665.6 1519.05  4764.6 1513.23  4863.9 1510.73
  4952.6 1510.38  4960.2 1508.25  4967.5 1505.61  4996.5 1498.67  4999.3 1498.17
  5002.5 1498.67  5007.9 1500.92  5031.6 1505.59  5063.8 1506.41  5148.6 1505.01
  5184.3 1506.04  5223.7  1512.2  5245.1  1513.9  5672.4 1513.18  5727.7 1510.94
  5800.3 1510.18  5838.2 1513.55  6069.8 1516.07  6344.8 1522.75  6654.4 1538.74
#Mann= 8 ,-1 , 0
  3740.6      .1       0  4214.1     .05       0  4665.6      .1       0
  4863.9     .16       0  4960.2      .1       0  4996.5     .07       0
  5002.5      .1       0  5063.8     .05       0
Bank Sta=4967.5,5031.6
XS Rating Curve= 0 ,0
Exp/Cntr=0.3,0.1

Type RM Length L Ch R = 1 ,14213   ,401,401,401
BEGIN DESCRIPTION:
THREEMILE CREEK 27.0
END DESCRIPTION:
XS GIS Cut Line= 3
      2818049.27     10041127.28      2818771.53     10041696.75
      2820712.77     10042098.86
#Sta/Elev= 30
  3899.4 1554.49  4323.3 1540.34  4344.1 1540.95    4373 1538.72    4473 1534.52
  4590.6 1528.23    4641 1525.38  4743.4 1519.87  4831.1 1511.44  4887.5 1504.18
  4938.6 1500.75  4980.7 1499.75  4989.6 1497.93  4996.8  1494.7  4999.6  1494.2
  5002.8  1494.7  5020.3 1499.77  5025.8 1504.47  5030.9 1506.44  5050.9 1508.17
  5126.1 1509.94  5729.8 1510.47  5829.7 1508.56  5898.5 1510.43  5929.2 1512.45
  6209.7  1516.2  6555.8  1524.2  6633.8 1528.13  6684.9 1529.29  6801.6 1535.96
#Mann= 9 ,-1 , 0
  3899.4     .05       0    4473      .1       0  4590.6     .05       0
    4641      .1       0  4831.1     .05       0  4996.8    .035       0
  5002.8     .05       0  5729.8      .1       0  5829.7     .05       0
Bank Sta=4887.5,5025.8
XS Rating Curve= 0 ,0
Exp/Cntr=0.3,0.1

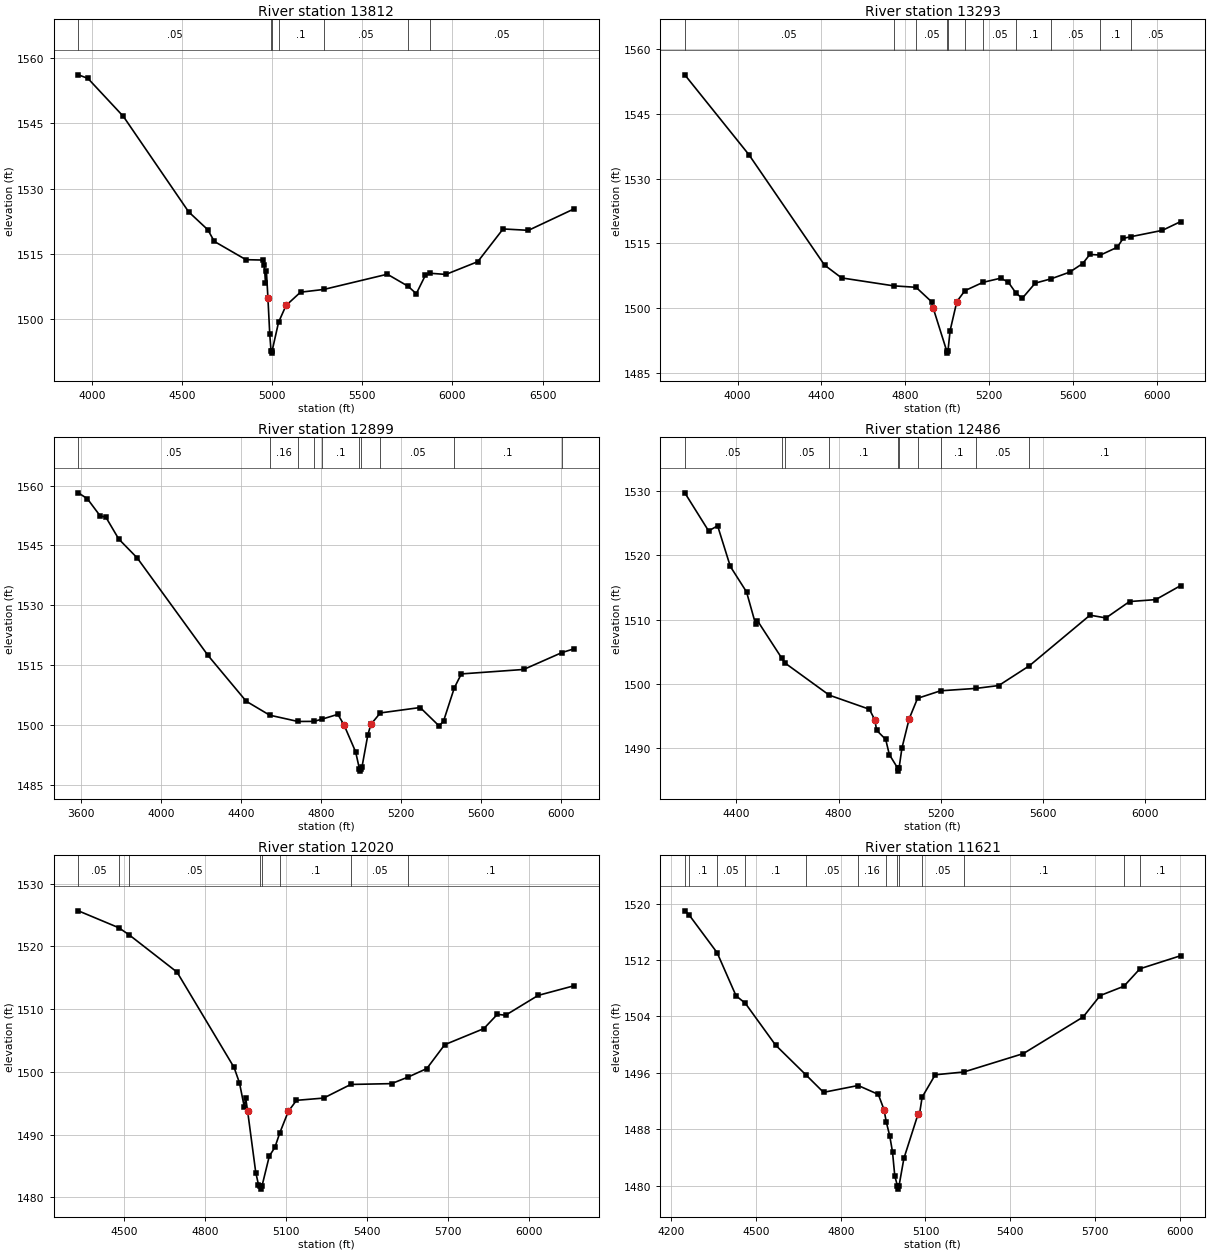
Type RM Length L Ch R = 1 ,13812   ,519,519,519
BEGIN DESCRIPTION:
THREEMILE CREEK 26.0
END DESCRIPTION:
XS GIS Cut Line= 3
      2817743.72     10041710.63      2818618.75     10042030.08
      2820431.27     10042175.92
#Sta/Elev= 30
    3925 1556.07  3977.9 1555.26  4174.9 1546.53    4537 1524.65  4643.2 1520.55
  4679.1 1517.88  4854.6 1513.69  4946.5 1513.61  4956.6  1512.4    4963 1508.33
    4968 1511.12  4976.6 1504.83  4986.7 1496.56  4993.7 1492.77  4996.4 1492.27
  4999.7 1492.77  5035.4 1499.34  5076.9 1503.19  5157.2 1506.24  5286.5 1506.87
  5638.8 1510.36  5753.8  1507.6  5799.3 1505.89  5849.4 1510.09  5876.4 1510.58
  5963.3 1510.31  6140.4 1513.24  6280.8 1520.74  6421.3 1520.42  6674.9 1525.35
#Mann= 7 ,-1 , 0
    3925     .05       0  4993.7    .035       0  4999.7     .05       0
  5035.4      .1       0  5286.5     .05       0  5753.8      .1       0
  5876.4     .05       0
Bank Sta=4976.6,5076.9
XS Rating Curve= 0 ,0
Exp/Cntr=0.3,0.1

Type RM Length L Ch R = 1 ,13293   ,394,394,394
BEGIN DESCRIPTION:
THREEMILE CREEK 25.0
END DESCRIPTION:
XS GIS Cut Line= 2
      2817757.67     10041946.77      2819889.58     10042967.58
#Sta/Elev= 30
  3748.5 1554.07  4054.2 1535.54  4414.6 1509.94  4495.9 1506.96  4743.7 1505.12
  4850.9 1504.78  4924.6 1501.44  4932.1 1500.05  4997.1 1490.01  4999.8 1489.51
  5003.1 1490.01  5013.3 1494.74  5045.4 1501.47  5083.9    1504    5170 1505.93
  5254.9  1506.9  5290.5 1505.98  5327.2 1503.45    5357 1502.22  5419.1 1505.75
  5494.8 1506.75  5583.3  1508.3  5645.3 1510.29  5679.5  1512.4  5729.9 1512.26
    5810 1514.07  5838.2 1516.12  5875.1 1516.52    6025 1517.99  6112.2 1520.02
#Mann= 11 ,-1 , 0
  3748.5     .05       0  4743.7     .16       0  4850.9     .05       0
  4997.1    .035       0  5003.1     .05       0  5083.9     .16       0
    5170     .05       0  5327.2      .1       0  5494.8     .05       0
  5729.9      .1       0  5875.1     .05       0
Bank Sta=4932.1,5045.4
XS Rating Curve= 0 ,0
Exp/Cntr=0.3,0.1

Type RM Length L Ch R = 1 ,12899   ,413,413,413
BEGIN DESCRIPTION:
THREEMILE CREEK 24.0
END DESCRIPTION:
XS GIS Cut Line= 3
      2817625.66     10042002.27      2818410.42     10042682.86
      2819694.31     10043335.22
#Sta/Elev= 30
  3586.7 1558.19  3631.9  1556.7  3696.3 1552.37    3724 1552.11  3788.7  1546.6
  3880.8 1541.87    4235 1517.39  4425.9  1505.9  4543.4  1502.4  4684.6 1500.82
  4764.1 1500.84  4805.1  1501.4  4884.1 1502.61  4914.9 1499.96  4973.1  1493.2
  4992.3 1488.86  4995.1 1488.36  4998.3 1488.86  5004.7 1489.36  5034.2 1497.48
  5049.5  1500.1  5096.3 1502.96  5295.7 1504.32  5390.3  1499.7  5412.6 1500.92
  5466.6 1509.27  5501.6 1512.75  5813.2 1513.87  6004.1  1518.1  6065.6 1519.06
#Mann= 10 ,-1 , 0
  3586.7     .05       0  4543.4     .16       0  4684.6     .05       0
  4764.1     .16       0  4805.1      .1       0  4992.3     .07       0
  4998.3      .1       0  5096.3     .05       0  5466.6      .1       0
  6004.1     .05       0
Bank Sta=4914.9,5049.5
XS Rating Curve= 0 ,0
Exp/Cntr=0.3,0.1

Type RM Length L Ch R = 1 ,12486   ,466,466,466
BEGIN DESCRIPTION:
THREEMILE CREEK 23.0
END DESCRIPTION:
XS GIS Cut Line= 3
      2817868.77     10042571.77      2818625.69     10043300.92
       2819493.6     10043495.33
#Sta/Elev= 30
  4197.9 1529.75  4291.1 1523.82  4326.3 1524.62    4376  1518.3  4439.5 1514.33
    4475  1509.3    4482 1509.86  4577.5 1504.01  4591.2 1503.23  4763.4 1498.26
  4920.3 1496.07  4941.7  1494.4  4948.6 1492.79  4984.1 1491.38  4998.3 1489.02
  5030.5 1486.94  5033.3 1486.44  5036.5 1486.94  5047.7 1490.04    5076 1494.59
  5108.8 1497.77  5198.6 1498.94  5338.6 1499.32  5426.5 1499.76  5546.5 1502.84
  5783.7 1510.71  5846.1 1510.28  5938.3 1512.83  6040.8 1513.13  6138.3 1515.31
#Mann= 10 ,-1 , 0
  4197.9     .05       0  4577.5      .1       0  4591.2     .05       0
  4763.4      .1       0  5030.5     .07       0  5036.5      .1       0
  5108.8     .05       0  5198.6      .1       0  5338.6     .05       0
  5546.5      .1       0
Bank Sta=4941.7,5076
XS Rating Curve= 0 ,0
Exp/Cntr=0.3,0.1

Type RM Length L Ch R = 1 ,12020   ,399,399,399
BEGIN DESCRIPTION:
THREEMILE CREEK 22.0
END DESCRIPTION:
XS GIS Cut Line= 2
      2817604.89     10043370.36      2819431.26     10043543.97
#Sta/Elev= 30
  4331.2 1525.65  4480.7 1522.96  4519.4 1521.82  4696.4 1515.89  4907.4 1500.71
  4927.4 1498.26  4945.3 1494.41  4950.3 1495.87  4957.6 1493.75  4987.7 1483.97
  4997.8 1482.03  5004.8 1481.83  5007.6 1481.33  5010.8 1481.83  5037.9  1486.6
  5058.4 1487.97  5076.9 1490.32  5108.3 1493.72  5138.4 1495.47  5238.8 1495.83
  5339.1    1498    5490 1498.13    5551 1499.17  5620.6 1500.53  5686.8 1504.33
  5831.5 1506.89  5881.7 1509.17  5911.9 1509.02  6032.4 1512.18  6165.8 1513.72
#Mann= 8 ,-1 , 0
  4331.2     .05       0  4480.7      .1       0  4519.4     .05       0
  5004.8    .035       0  5010.8     .05       0  5076.9      .1       0
  5339.1     .05       0    5551      .1       0
Bank Sta=4957.6,5108.3
XS Rating Curve= 0 ,0
Exp/Cntr=0.3,0.1

Type RM Length L Ch R = 1 ,11621   ,361,361,361
BEGIN DESCRIPTION:
THREEMILE CREEK 21.0
END DESCRIPTION:
XS GIS Cut Line= 2
      2817688.22      10043877.3      2819431.22     10043668.98
#Sta/Elev= 30
  4247.9 1518.99  4262.4 1518.45  4362.3 1513.05  4429.4 1506.93  4462.1 1505.88
  4569.1 1499.95  4675.4 1495.77    4739 1493.24  4861.7 1494.21    4933 1492.95
  4953.1 1490.79  4961.5 1488.99  4973.3 1487.09  4983.3 1484.78  4991.3 1481.38
  5000.5 1480.01  5003.2 1479.51  5006.5 1480.01  5023.6 1483.87  5073.7 1490.15
  5078.7 1490.14  5088.2 1492.56  5134.4 1495.73  5236.1 1496.13  5446.6 1498.74
  5658.1 1503.93  5718.5 1506.97  5802.4 1508.29  5859.3 1510.77  6003.3 1512.62
#Mann= 13 ,-1 , 0
  4247.9     .05       0  4262.4      .1       0  4362.3     .05       0
  4462.1      .1       0  4675.4     .05       0  4861.7     .16       0
  4961.5      .1       0  5000.5     .07       0  5006.5      .1       0
  5088.2     .05       0  5236.1      .1       0  5802.4     .05       0
  5859.3      .1       0
Bank Sta=4953.1,5073.7
XS Rating Curve= 0 ,0
Exp/Cntr=0.3,0.1