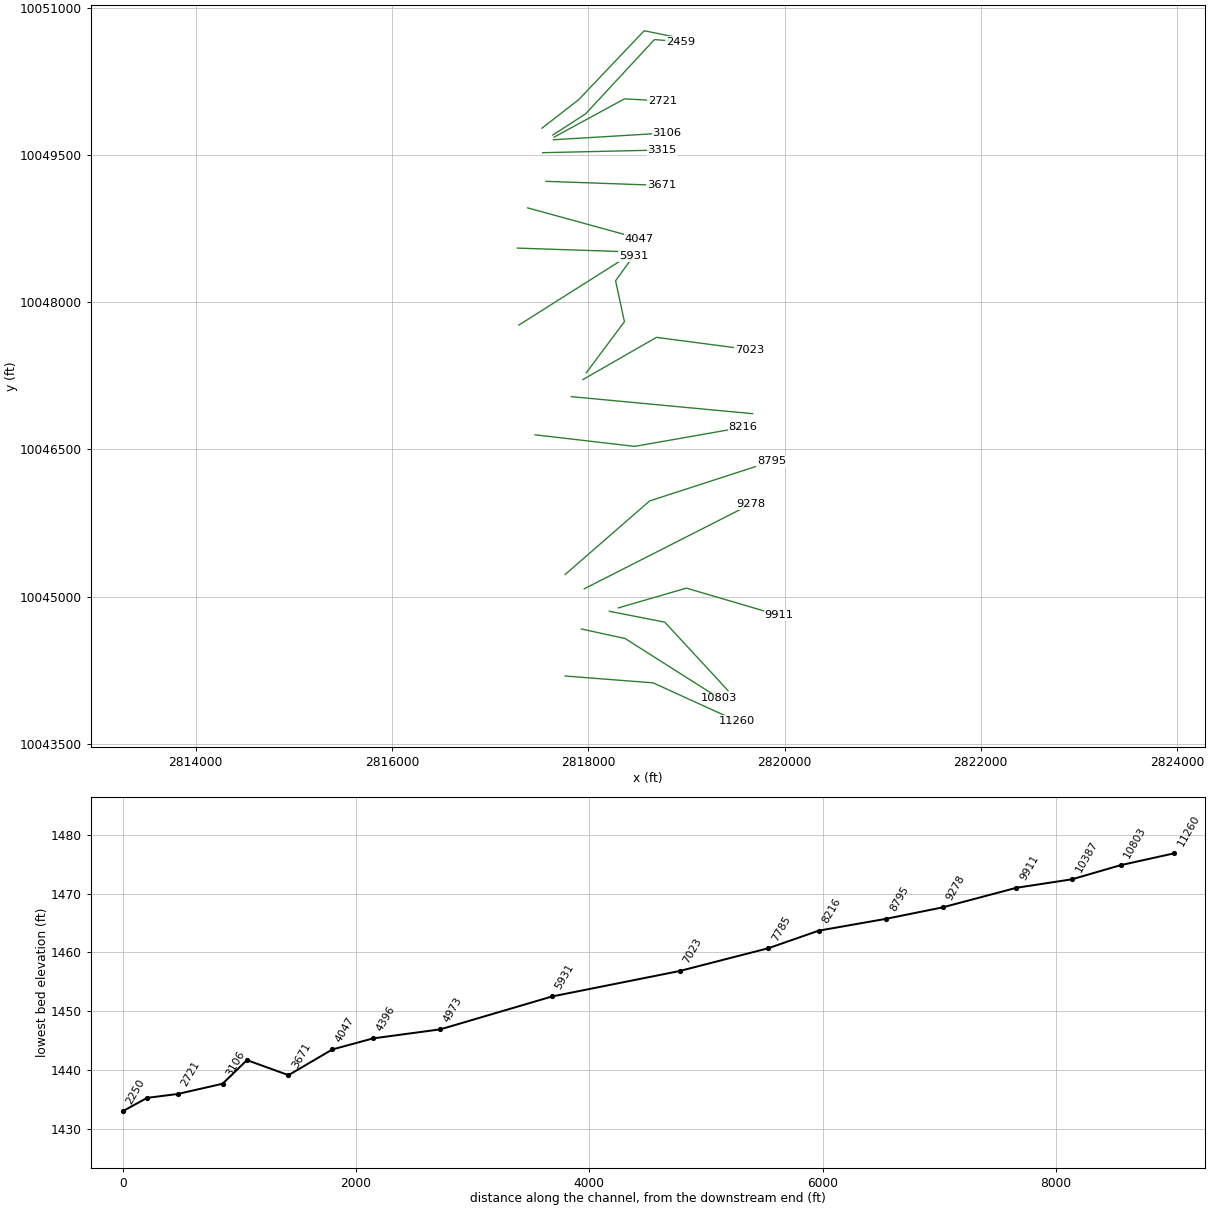
HEC-RAS study THREEMILE CREEK.prj: THREEMILE CREEK Base Level Engineering

--- THREEMILE CREEK.g01 (geometry) --- (continued)

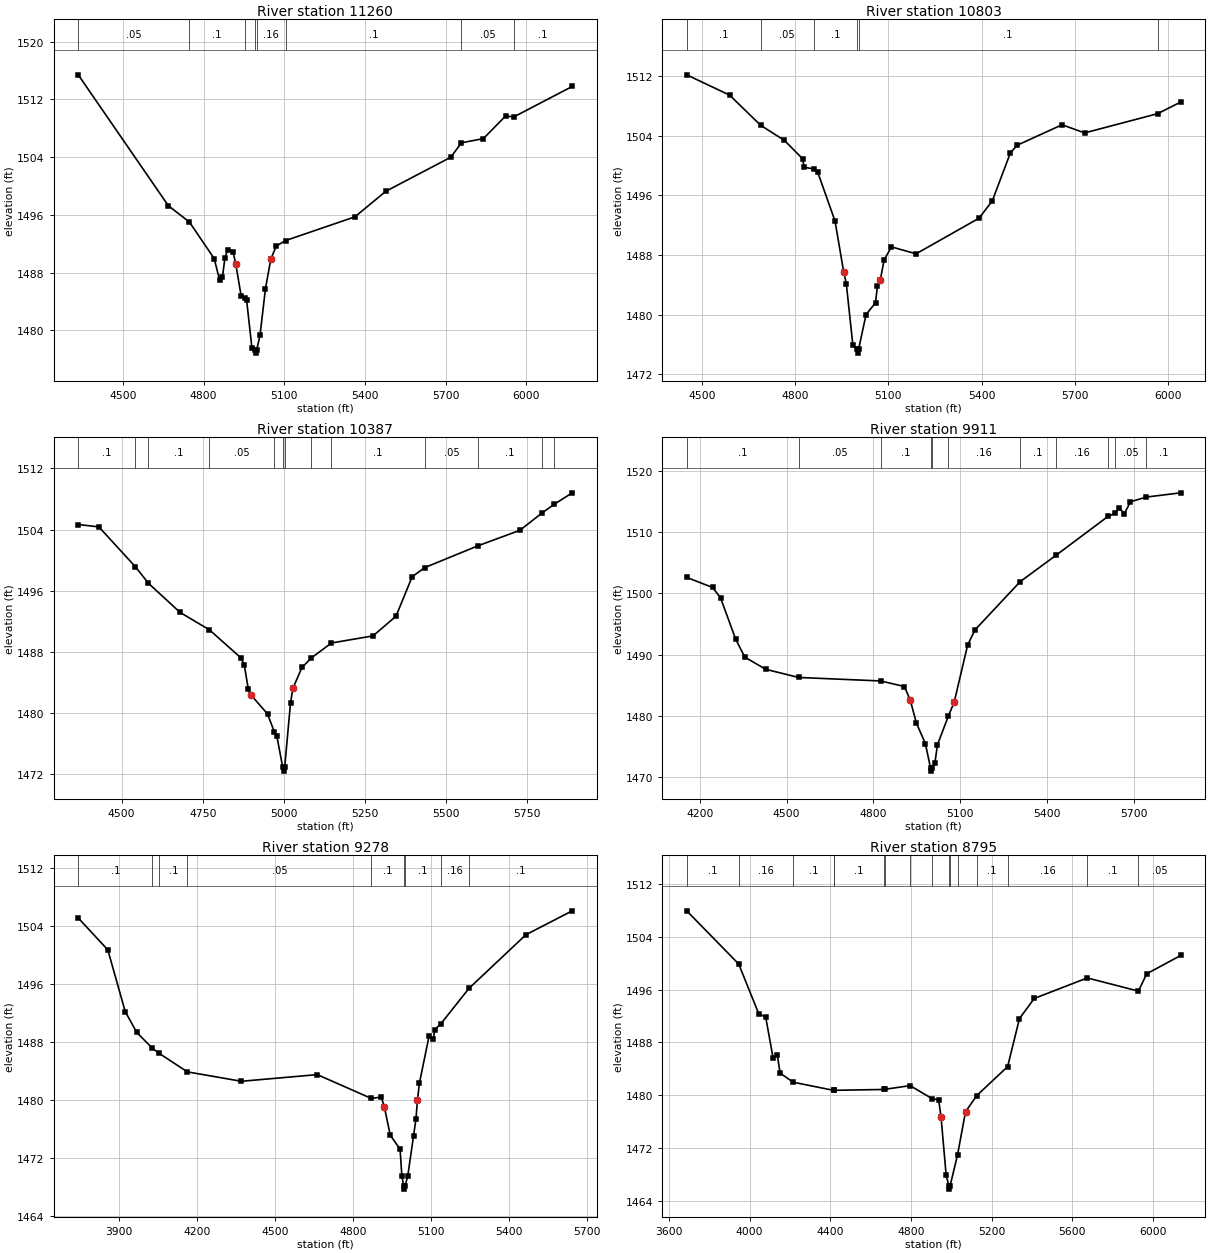
Type RM Length L Ch R = 1 ,11260   ,457,457,457
BEGIN DESCRIPTION:
THREEMILE CREEK 20.0
END DESCRIPTION:
XS GIS Cut Line= 3
      2817764.56     10044189.81      2818660.42     10044120.36
      2819514.06     10043731.71
#Sta/Elev= 30
    4334  1515.4  4668.9 1497.27  4747.4    1495  4839.4 1489.94  4859.5 1486.97
    4870 1487.35  4879.5 1490.06  4889.6 1491.19  4909.6 1490.87  4919.7 1489.17
  4939.7 1484.75    4953 1484.54  4959.8 1484.24  4979.8 1477.52  4991.9 1477.34
  4994.6 1476.84  4997.9 1477.34  5009.9 1479.35    5030 1485.78    5050 1489.87
  5070.1 1491.67    5105 1492.44  5362.4 1495.72  5477.7 1499.27  5719.3 1503.99
  5758.4 1505.98    5840 1506.56  5922.6 1509.69  5953.9 1509.58  6170.5 1513.79
#Mann= 8 ,-1 , 0
    4334     .05       0  4747.4      .1       0    4953     .16       0
  4991.9     .07       0  4997.9     .16       0    5105      .1       0
  5758.4     .05       0  5953.9      .1       0
Bank Sta=4919.7,5050
XS Rating Curve= 0 ,0
Exp/Cntr=0.3,0.1

Type RM Length L Ch R = 1 ,10803   ,416,416,416
BEGIN DESCRIPTION:
THREEMILE CREEK 19.0
END DESCRIPTION:
XS GIS Cut Line= 3
      2817931.28     10044668.96      2818375.69     10044571.75
      2819335.09     10043963.28
#Sta/Elev= 30
  4450.5 1512.17  4588.9 1509.44  4688.6  1505.4  4764.9 1503.38  4823.6 1500.92
  4828.7 1499.77    4860 1499.55  4872.6 1499.09  4928.1 1492.56  4956.1 1485.73
  4964.5 1484.15  4985.7 1475.88    4998 1475.34  5000.7 1474.84    5004 1475.34
  5028.1 1480.02  5058.6  1481.6  5064.5 1483.78  5073.8 1484.62  5086.3 1487.35
    5110 1489.09  5189.1 1488.16  5392.4 1492.95  5434.7 1495.27  5492.4 1501.64
  5513.5  1502.7  5659.3 1505.47  5732.1 1504.38  5967.3 1506.96  6041.5 1508.52
#Mann= 6 ,-1 , 0
  4450.5      .1       0  4688.6     .05       0    4860      .1       0
    4998     .07       0    5004      .1       0  5967.3     .05       0
Bank Sta=4956.1,5073.8
XS Rating Curve= 0 ,0
Exp/Cntr=0.3,0.1

Type RM Length L Ch R = 1 ,10387   ,476,476,476
BEGIN DESCRIPTION:
THREEMILE CREEK 18.0
END DESCRIPTION:
XS GIS Cut Line= 3
      2818215.92     10044849.54      2818780.21     10044738.42
       2819424.4     10044041.31
#Sta/Elev= 30
    4366 1504.66  4429.7 1504.35  4542.6 1499.13  4582.7 1496.98  4680.1 1493.18
  4770.8  1490.9    4868 1487.24  4878.2 1486.32  4890.6 1483.21  4898.6 1482.41
  4950.1 1479.91  4971.1 1477.57  4978.5 1477.08    4997 1472.94  4999.8 1472.44
    5003 1472.94    5021 1481.35  5028.4 1483.26  5056.4 1485.99  5085.4 1487.23
  5147.2 1489.18  5275.6 1490.11  5346.5 1492.68  5396.4 1497.84  5435.6 1499.04
    5600 1501.89  5728.6  1503.9  5797.5 1506.18  5834.7  1507.3  5890.3  1508.8
#Mann= 13 ,-1 , 0
    4366      .1       0  4542.6     .05       0  4582.7      .1       0
  4770.8     .05       0  4971.1      .1       0    4997     .07       0
    5003      .1       0  5085.4     .16       0  5147.2      .1       0
  5435.6     .05       0    5600      .1       0  5797.5     .05       0
  5834.7      .1       0
Bank Sta=4898.6,5028.4
XS Rating Curve= 0 ,0
Exp/Cntr=0.3,0.1

Type RM Length L Ch R = 1 ,9911    ,633,633,633
BEGIN DESCRIPTION:
THREEMILE CREEK 17.0
END DESCRIPTION:
XS GIS Cut Line= 3
      2818306.25     10044884.25      2819000.69     10045085.64
      2819945.13     10044807.86
#Sta/Elev= 30
  4154.8 1502.62  4244.2 1500.98  4271.6  1499.3  4323.7 1492.58  4355.3 1489.62
  4427.8 1487.62  4541.9 1486.29  4825.5 1485.72  4907.2 1484.81  4927.7 1482.56
  4948.5 1478.87  4979.8 1475.48  4997.6  1471.5  5000.4    1471  5003.6  1471.5
  5012.5 1472.29  5021.5 1475.31  5059.1 1479.98  5079.2 1482.24  5125.7 1491.57
  5151.1 1494.05  5307.2 1501.92  5431.4 1506.24  5611.3 1512.59  5635.5 1513.08
  5649.3 1513.94  5667.7 1513.04  5688.6 1514.97  5743.9 1515.74  5862.3 1516.43
#Mann= 11 ,-1 , 0
  4154.8      .1       0  4541.9     .05       0  4825.5      .1       0
  4997.6     .07       0  5003.6      .1       0  5059.1     .16       0
  5307.2      .1       0  5431.4     .16       0  5611.3      .1       0
  5635.5     .05       0  5743.9      .1       0
Bank Sta=4927.7,5079.2
XS Rating Curve= 0 ,0
Exp/Cntr=0.3,0.1

Type RM Length L Ch R = 1 ,9278    ,483,483,483
BEGIN DESCRIPTION:
THREEMILE CREEK 16.0
END DESCRIPTION:
XS GIS Cut Line= 2
      2817958.99     10045078.68      2819652.46     10045939.29
#Sta/Elev= 30
  3742.9 1505.13  3856.7 1500.72  3923.5 1492.21    3968 1489.31  4028.4 1487.12
  4054.2 1486.43  4162.5 1483.87  4370.5 1482.57  4662.1 1483.49  4869.9  1480.2
  4908.1 1480.39  4920.1 1479.01  4942.6 1475.14  4980.5 1473.17  4987.4 1469.46
  4994.1 1468.17  4996.8 1467.67  5000.1 1468.17  5009.9 1469.45  5032.3 1475.04
  5041.6 1477.37  5047.2 1479.95  5054.7 1482.28  5091.7 1488.77  5108.4 1488.44
    5114 1489.71  5137.2 1490.51  5245.5 1495.41  5464.4 1502.82  5642.5 1506.12
#Mann= 9 ,-1 , 0
  3742.9      .1       0  4028.4     .16       0  4054.2      .1       0
  4162.5     .05       0  4869.9      .1       0  4994.1     .07       0
  5000.1      .1       0  5137.2     .16       0  5245.5      .1       0
Bank Sta=4920.1,5047.2
XS Rating Curve= 0 ,0
Exp/Cntr=0.3,0.1

Type RM Length L Ch R = 1 ,8795    ,579,579,579
BEGIN DESCRIPTION:
THREEMILE CREEK 15.0
END DESCRIPTION:
XS GIS Cut Line= 3
      2817764.59     10045224.54      2818625.69     10045974.53
      2819868.75      10046377.3
#Sta/Elev= 30
  3688.2 1507.95  3945.9 1499.88  4044.8 1492.37  4079.9 1491.79    4116 1485.69
  4136.9 1486.13  4151.1 1483.33  4215.7 1481.95  4417.2 1480.71  4418.6 1480.72
  4668.1 1480.85  4669.1 1480.87  4795.5 1481.43  4904.3 1479.46    4937 1479.27
  4948.7  1476.7  4974.2 1467.82  4987.7 1466.23  4990.5 1465.73  4993.7 1466.23
  5030.5 1470.91  5070.2 1477.48  5126.2 1479.93  5278.9 1484.32  5337.6 1491.61
  5411.2 1494.66  5673.6 1497.77  5927.2 1495.77  5968.3  1498.4  6136.8 1501.18
#Mann= 16 ,-1 , 0
  3688.2      .1       0  3945.9     .16       0  4215.7      .1       0
  4417.2     .05       0  4418.6      .1       0  4668.1     .05       0
  4669.1      .1       0  4795.5     .05       0  4904.3      .1       0
  4987.7     .07       0  4993.7      .1       0  5030.5     .16       0
  5126.2      .1       0  5278.9     .16       0  5673.6      .1       0
  5927.2     .05       0
Bank Sta=4948.7,5070.2
XS Rating Curve= 0 ,0
Exp/Cntr=0.3,0.1

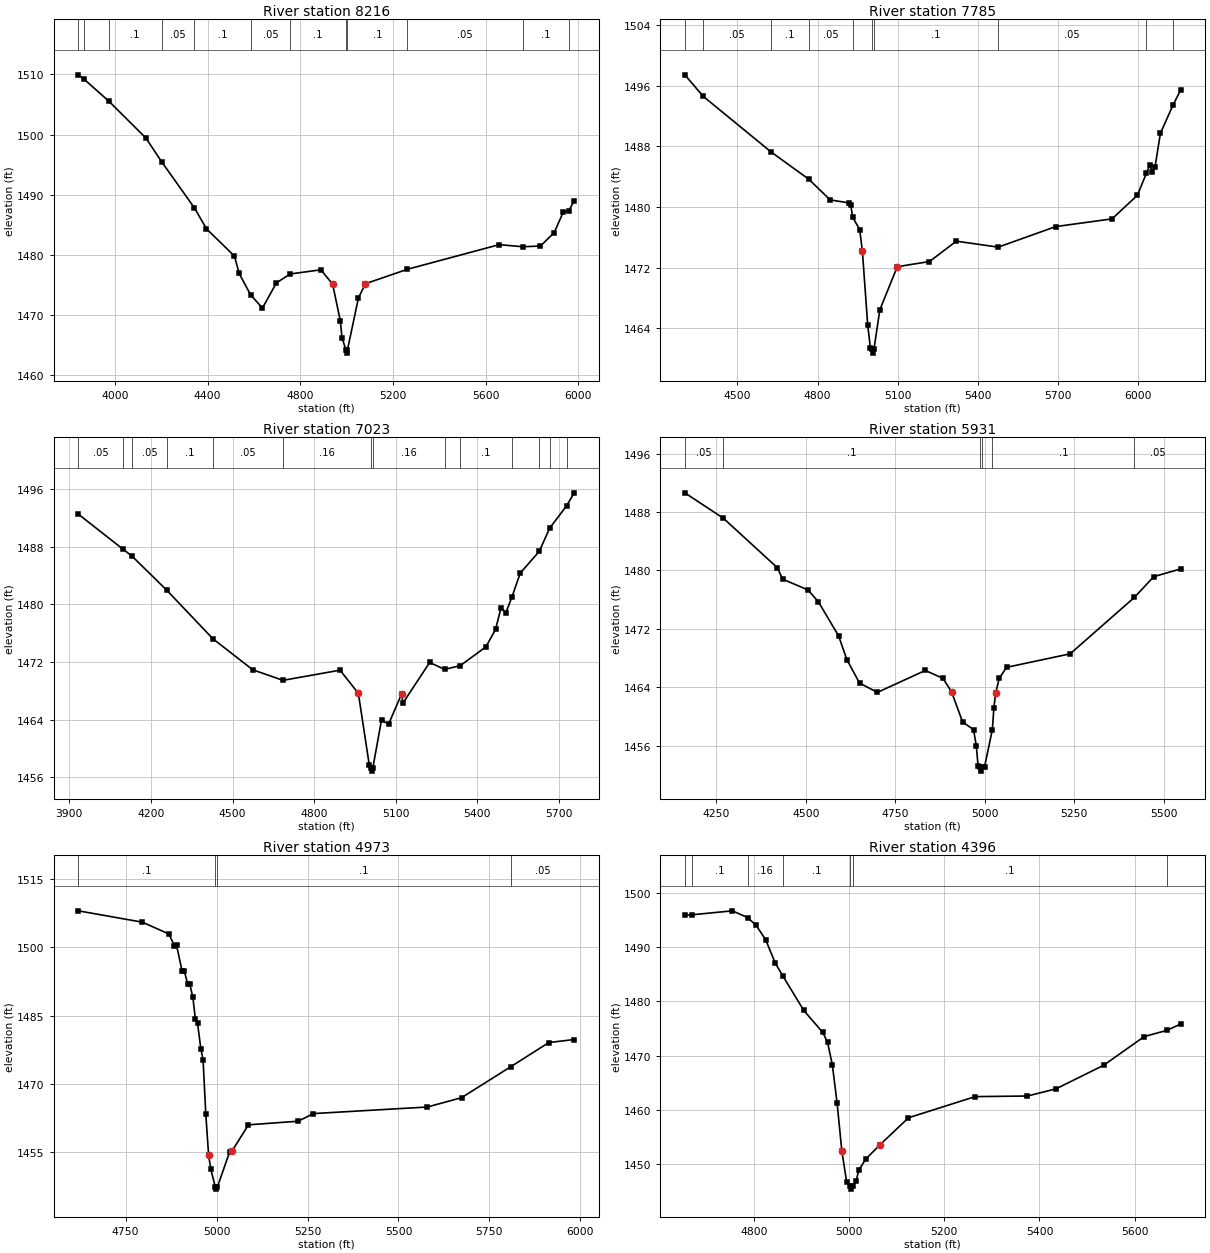
Type RM Length L Ch R = 1 ,8216    ,431,431,431
BEGIN DESCRIPTION:
THREEMILE CREEK 14.0
END DESCRIPTION:
XS GIS Cut Line= 3
      2817459.06     10046648.14      2818472.92     10046530.08
      2819575.24      10046724.2
#Sta/Elev= 30
  3842.4 1509.91  3867.9 1509.16    3974 1505.54  4133.8 1499.43  4201.5  1495.5
  4343.2 1487.83  4395.5 1484.35  4516.3 1479.81  4536.5 1476.94  4586.4 1473.36
  4637.1 1471.19  4697.2 1475.36  4756.3 1476.85  4889.1 1477.54  4939.8 1475.18
    4973 1469.11  4980.4 1466.27  4997.7 1464.21  5000.5 1463.71  5003.7 1464.21
  5051.5  1472.9  5081.4 1475.23  5262.6 1477.63  5659.1 1481.72    5761 1481.37
    5837 1481.49  5896.3 1483.72  5934.9 1487.08  5959.9 1487.36  5982.4 1489.02
#Mann= 12 ,-1 , 0
  3842.4      .1       0  3867.9     .05       0    3974      .1       0
  4201.5     .05       0  4343.2      .1       0  4586.4     .05       0
  4756.3      .1       0  4997.7     .07       0  5003.7      .1       0
  5262.6     .05       0    5761      .1       0  5959.9     .16       0
Bank Sta=4939.8,5081.4
XS Rating Curve= 0 ,0
Exp/Cntr=0.3,0.1

Type RM Length L Ch R = 1 ,7785    ,762,762,762
BEGIN DESCRIPTION:
THREEMILE CREEK 13.0
END DESCRIPTION:
XS GIS Cut Line= 2
      2817827.08     10047037.03      2819673.84     10046863.46
#Sta/Elev= 30
  4303.3 1497.44  4372.6 1494.59  4625.6 1487.28  4767.5 1483.66  4847.1 1480.94
  4917.4 1480.55  4924.4 1480.26    4931 1478.67  4957.6 1477.03  4967.6  1474.2
  4987.7 1464.38  4997.7 1461.39  5004.8 1461.23  5007.5 1460.73  5010.8 1461.23
    5033 1466.45  5098.2 1472.13  5218.7 1472.81  5319.1  1475.5  5475.8 1474.71
  5690.8 1477.42  5901.7 1478.44  5996.1 1481.54  6030.1 1484.43  6042.3 1485.56
  6052.4 1484.63  6062.4 1485.29  6082.5 1489.71  6129.6 1493.44  6158.2 1495.43
#Mann= 10 ,-1 , 0
  4303.3      .1       0  4372.6     .05       0  4625.6      .1       0
  4767.5     .05       0    4931      .1       0  5004.8     .07       0
  5010.8      .1       0  5475.8     .05       0  6030.1     .16       0
  6129.6     .05       0
Bank Sta=4967.6,5098.2
XS Rating Curve= 0 ,0
Exp/Cntr=0.3,0.1

Type RM Length L Ch R = 1 ,7023    ,1092,1092,1092
BEGIN DESCRIPTION:
THREEMILE CREEK 12.0
END DESCRIPTION:
XS GIS Cut Line= 3
      2817945.16     10047210.65      2818695.14     10047641.19
        2819645.     10047516.39
#Sta/Elev= 30
  3933.2 1492.51    4096 1487.69  4130.7 1486.68  4259.2 1481.92  4427.8 1475.22
  4574.5 1470.91  4685.7 1469.45  4895.4 1470.86  4962.7 1467.64    5003 1457.64
  5010.1 1457.35  5012.9 1456.85  5016.1 1457.35  5047.8 1463.95  5073.6 1463.36
  5121.5 1467.54  5126.5 1466.29  5224.9 1471.93  5279.5 1470.97    5337 1471.48
  5431.3 1474.09    5467 1476.51  5487.2 1479.52    5505 1478.81  5527.8 1481.07
  5557.8 1484.33  5627.9 1487.36    5666 1490.57  5727.9 1493.65    5756 1495.47
#Mann= 14 ,-1 , 0
  3933.2     .05       0    4096      .1       0  4130.7     .05       0
  4259.2      .1       0  4427.8     .05       0  4685.7     .16       0
  5010.1     .07       0  5016.1     .16       0  5279.5     .05       0
    5337      .1       0  5527.8     .16       0  5627.9     .05       0
    5666      .1       0  5727.9     .05       0
Bank Sta=4962.7,5121.5
XS Rating Curve= 0 ,0
Exp/Cntr=0.3,0.1

Type RM Length L Ch R = 1 ,5931    ,958,958,958
BEGIN DESCRIPTION:
THREEMILE CREEK 11.0
END DESCRIPTION:
XS GIS Cut Line= 4
      2817979.86     10047280.08      2818368.75     10047800.92
      2818278.47     10048217.58      2818459.01     10048467.56
#Sta/Elev= 30
  4162.2 1490.63    4270 1487.15  4420.8 1480.37  4435.4 1478.81  4506.2 1477.34
  4535.4  1475.7  4591.7 1471.05  4614.7 1467.81  4650.1 1464.59  4700.1 1463.31
  4833.8 1466.31    4883 1465.24  4907.2 1463.39  4937.9 1459.27  4968.6 1458.21
  4976.3 1455.99  4981.4 1453.18    4986 1453.03  4988.8 1452.53    4992 1453.03
  4999.3 1453.13  5021.1  1458.2  5025.4 1461.21  5030.6 1463.27  5040.2 1465.22
  5060.7 1466.74  5238.5 1468.59  5417.9 1476.32  5471.7 1479.15  5546.9 1480.21
#Mann= 6 ,-1 , 0
  4162.2     .05       0    4270      .1       0    4986    .035       0
    4992      .1       0  5021.1      .1       0  5417.9     .05       0
Bank Sta=4907.2,5030.6
XS Rating Curve= 0 ,0
Exp/Cntr=0.3,0.1

Type RM Length L Ch R = 1 ,4973    ,577,577,577
BEGIN DESCRIPTION:
THREEMILE CREEK 10.0
END DESCRIPTION:
XS GIS Cut Line= 2
      2817292.37      10047766.2      2818444.28     10048494.82
#Sta/Elev= 30
  4619.9 1508.05  4795.8 1505.56  4868.8 1502.97    4884 1500.39  4889.9 1500.49
  4905.2 1494.78  4911.1 1494.84  4920.5 1492.03  4926.4 1491.92  4934.8 1489.02
  4941.7 1484.26  4947.6 1483.36  4956.9 1477.62  4962.8  1475.4  4970.3 1463.35
  4978.1 1454.34    4984 1451.35  4996.3 1447.44  4999.1 1446.94  5002.3 1447.44
  5035.8 1455.11  5041.7 1455.21  5087.5 1461.06    5224 1461.85  5266.3 1463.53
  5579.2 1464.97  5673.3 1467.02    5808 1473.79  5913.2 1479.12  5982.9 1479.79
#Mann= 4 ,-1 , 0
  4619.9      .1       0  4996.3     .07       0  5002.3      .1       0
    5808     .05       0
Bank Sta=4978.1,5041.7
XS Rating Curve= 0 ,0
Exp/Cntr=0.3,0.1

Type RM Length L Ch R = 1 ,4396    ,349,349,349
BEGIN DESCRIPTION:
THREEMILE CREEK 9.0
END DESCRIPTION:
XS GIS Cut Line= 2
      2817278.52     10048550.92      2818320.14     10048516.19
#Sta/Elev= 30
  4654.5 1495.93  4668.8 1495.98  4754.5 1496.72  4786.4 1495.48  4804.5 1494.05
  4824.5 1491.38  4844.6 1487.09  4860.7 1484.69  4904.6 1478.35  4944.6 1474.29
  4954.6 1472.44  4964.6 1468.33  4974.6 1461.29  4984.6 1452.42  4994.6 1446.79
  5001.6  1445.9  5004.4  1445.4  5007.6  1445.9  5014.6 1446.82  5019.9 1448.85
  5034.7 1450.93  5064.7 1453.57  5124.7 1458.56  5264.8 1462.46  5374.8 1462.57
  5434.9  1463.9  5534.9 1468.24  5620.3 1473.54    5668 1474.68  5696.7 1475.84
#Mann= 7 ,-1 , 0
  4654.5     .16       0  4668.8      .1       0  4786.4     .16       0
  4860.7      .1       0  5001.6     .07       0  5007.6      .1       0
    5668     .05       0
Bank Sta=4984.6,5064.7
XS Rating Curve= 0 ,0
Exp/Cntr=0.3,0.1

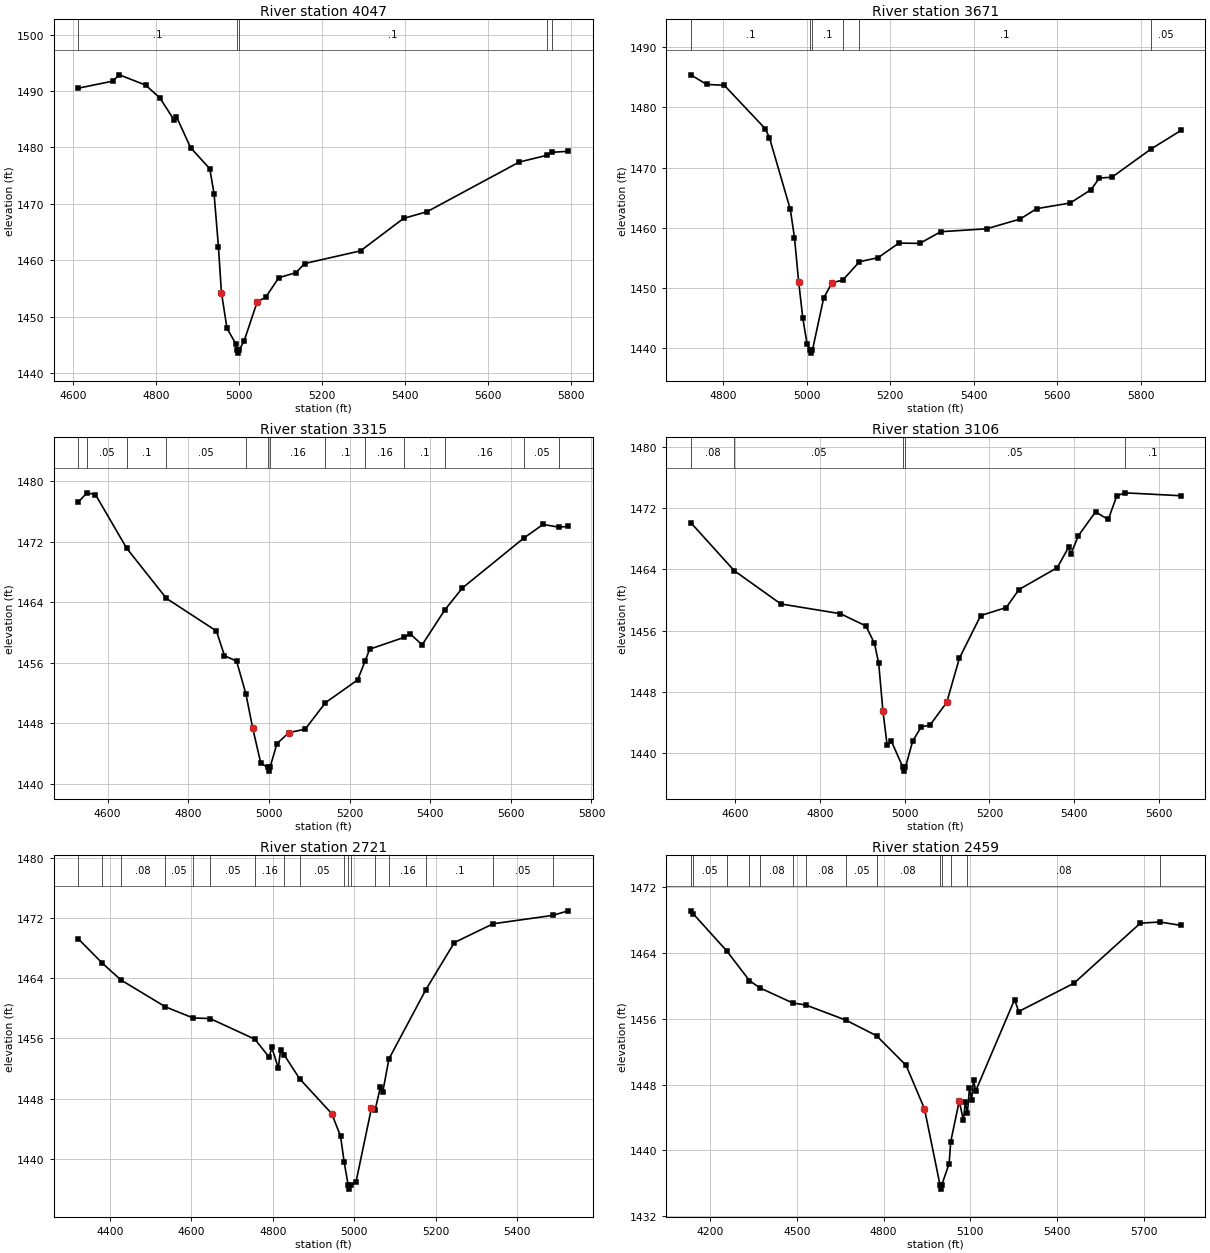
Type RM Length L Ch R = 1 ,4047    ,376,376,376
BEGIN DESCRIPTION:
THREEMILE CREEK 8.0
END DESCRIPTION:
XS GIS Cut Line= 2
      2817382.63     10048960.64      2818520.47     10048648.43
#Sta/Elev= 30
  4612.9 1490.49  4696.2 1491.75  4712.3 1492.87  4775.5 1491.05  4809.9 1488.78
  4844.4 1484.82  4849.6 1485.47    4884 1479.93    4930 1476.22  4940.4 1471.74
  4950.8 1462.42  4958.1 1454.23  4971.5  1447.9  4992.3 1445.22  4994.7 1444.02
  4997.5 1443.52  5000.7 1444.02    5013 1445.74  5044.1 1452.61  5064.8 1453.44
    5096 1456.89  5137.4 1457.79  5158.2  1459.4    5293 1461.66  5396.7 1467.42
  5452.6 1468.58  5674.9  1477.4  5742.1 1478.61  5753.6 1479.13  5792.8 1479.31
#Mann= 5 ,-1 , 0
  4612.9      .1       0  4994.7     .07       0  5000.7      .1       0
  5742.1     .05       0  5753.6      .1       0
Bank Sta=4958.1,5044.1
XS Rating Curve= 0 ,0
Exp/Cntr=0.3,0.1

Type RM Length L Ch R = 1 ,3671    ,356,356,356
BEGIN DESCRIPTION:
THREEMILE CREEK 7.0
END DESCRIPTION:
XS GIS Cut Line= 2
      2817570.16     10049231.47      2818743.62     10049189.81
#Sta/Elev= 30
  4722.2 1485.41  4760.5 1483.81  4802.5 1483.67  4900.6 1476.45  4910.6 1474.97
  4960.7 1463.03  4970.7 1458.34  4980.7 1450.98  4990.7 1444.92  5000.7 1440.72
  5007.7 1439.65  5010.4 1439.15  5013.7 1439.65  5040.7 1448.34  5060.7 1450.85
  5086.5 1451.29  5126.4 1454.35  5170.8 1455.01  5220.8 1457.44  5270.9 1457.39
  5320.9 1459.33    5431 1459.82    5511 1461.43    5551 1463.17  5631.1  1464.1
  5681.1 1466.32  5701.1 1468.25  5731.1 1468.39  5824.7 1473.07  5896.4 1476.16
#Mann= 6 ,-1 , 0
  4722.2      .1       0  5007.7     .07       0  5013.7      .1       0
  5086.5     .16       0  5126.4      .1       0  5824.7     .05       0
Bank Sta=4980.7,5060.7
XS Rating Curve= 0 ,0
Exp/Cntr=0.3,0.1

Type RM Length L Ch R = 1 ,3315    ,209,209,209
BEGIN DESCRIPTION:
THREEMILE CREEK 6.0
END DESCRIPTION:
XS GIS Cut Line= 2
      2817535.38     10049523.14      2818750.67     10049550.92
#Sta/Elev= 30
  4526.7 1477.18  4548.7 1478.43  4569.8  1478.2  4647.3 1471.12  4745.9  1464.5
  4869.9  1460.2  4889.9 1456.93  4919.9 1456.23  4943.1 1451.88  4959.9 1447.37
  4979.9 1442.76  4996.9 1442.21  4999.7 1441.71  5002.9 1442.21  5019.9 1445.33
  5049.9  1446.8  5089.9 1447.24  5140.3 1450.74    5220 1453.74  5238.9 1456.27
    5250  1457.8  5335.3 1459.36    5350 1459.85    5380 1458.37  5436.5 1462.99
    5480 1465.88  5633.2  1472.5  5680.1 1474.26  5718.9  1473.9  5742.3    1474
#Mann= 13 ,-1 , 0
  4526.7     .08       0  4548.7     .05       0  4647.3      .1       0
  4745.9     .05       0  4943.1     .16       0  4996.9     .07       0
  5002.9     .16       0  5140.3      .1       0  5238.9     .16       0
  5335.3      .1       0  5436.5     .16       0  5633.2     .05       0
  5718.9      .1       0
Bank Sta=4959.9,5049.9
XS Rating Curve= 0 ,0
Exp/Cntr=0.3,0.1

Type RM Length L Ch R = 1 ,3106    ,385,385,385
BEGIN DESCRIPTION:
Mapping XS b368eee8
END DESCRIPTION:
XS GIS Cut Line= 2
      2817646.57     10049655.09      2818799.28     10049724.53
#Sta/Elev= 30
  4496.2 1470.11  4598.6 1463.84  4708.5  1459.5  4848.7 1458.23  4908.8 1456.63
  4928.9 1454.38  4938.9 1451.79  4948.9 1445.55  4958.9 1441.06  4968.9 1441.59
    4996 1438.19  4998.8 1437.69    5002 1438.19    5019  1441.6  5039.1 1443.46
  5059.9  1443.7  5099.2 1446.65  5129.2 1452.44  5179.3 1457.99  5239.4 1459.03
  5269.5 1461.38  5359.7 1464.24  5386.5  1466.9  5391.5 1466.01  5409.7 1468.42
  5449.8 1471.51  5479.9 1470.52  5499.9  1473.6  5519.1    1474    5651 1473.62
#Mann= 5 ,-1 , 0
  4496.2     .08       0  4598.6     .05       0    4996     .04       0
    5002     .05       0  5519.1      .1       0
Bank Sta=4948.9,5099.2
XS Rating Curve= 0 ,0
Exp/Cntr=0.3,0.1

Type RM Length L Ch R = 1 ,2721    ,262,262,262
BEGIN DESCRIPTION:
THREEMILE CREEK 5.0
END DESCRIPTION:
XS GIS Cut Line= 3
      2817653.44     10049682.84      2818368.75     10050071.75
      2818757.59     10050050.92
#Sta/Elev= 30
    4322 1469.28  4380.7 1466.06    4427 1463.79  4536.7  1460.2  4604.3 1458.73
  4646.4 1458.64  4756.2  1455.9  4791.8 1453.47  4797.5 1454.86  4813.7 1452.04
  4819.4 1454.49  4827.9 1453.84  4865.9 1450.65  4944.8    1446  4966.6 1443.01
  4975.6  1439.5  4985.5 1436.45  4988.2 1435.95  4991.5 1436.45  5004.6 1436.92
  5042.6 1446.75  5051.5 1446.49  5064.5 1449.52  5070.2 1448.86  5085.4 1453.27
  5176.1 1462.49  5246.1 1468.76  5341.4 1471.26  5487.3 1472.37  5525.6 1472.98
#Mann= 17 ,-1 , 0
    4322     .08       0  4380.7     .05       0    4427     .08       0
  4536.7     .05       0  4604.3     .08       0  4646.4     .05       0
  4756.2     .16       0  4827.9     .08       0  4865.9     .05       0
  4975.6     .16       0  4985.5     .07       0  4991.5     .16       0
  5051.5     .05       0  5085.4     .16       0  5176.1      .1       0
  5341.4     .05       0  5487.3      .1       0
Bank Sta=4944.8,5042.6
XS Rating Curve= 0 ,0
Exp/Cntr=0.3,0.1

Type RM Length L Ch R = 1 ,2459    ,209,209,209
BEGIN DESCRIPTION:
Mapping XS 459550fc
END DESCRIPTION:
XS GIS Cut Line= 4
      2817639.59      10049703.7      2817972.92     10049918.97
       2818674.3     10050675.92      2818938.24     10050655.08
#Sta/Elev= 30
    4134 1469.15  4142.6 1468.78  4258.3 1464.27  4336.8 1460.66  4372.6 1459.78
  4486.9 1457.93    4531  1457.7  4670.7 1455.84    4776 1453.95    4878 1450.35
  4941.5 1445.06  4995.2 1435.79    4998 1435.29  5001.2 1435.79  5026.6  1438.4
  5032.3 1441.08  5061.7 1446.02  5075.9 1443.66  5082.7 1445.88  5089.7 1444.51
  5096.9 1447.54  5104.2 1446.17  5111.1 1448.57  5118.4 1447.23  5252.8 1458.35
    5267  1456.9    5458 1460.34  5687.3 1467.65  5755.3 1467.79  5827.5 1467.38
#Mann= 14 ,-1 , 0
    4134     .08       0  4142.6     .05       0  4258.3     .08       0
  4336.8     .05       0  4372.6     .08       0  4486.9     .05       0
    4531     .08       0  4670.7     .05       0    4776     .08       0
  4995.2     .07       0  5001.2     .08       0  5032.3     .05       0
  5089.7     .08       0  5755.3      .1       0
Bank Sta=4941.5,5061.7
XS Rating Curve= 0 ,0
Exp/Cntr=0.3,0.1

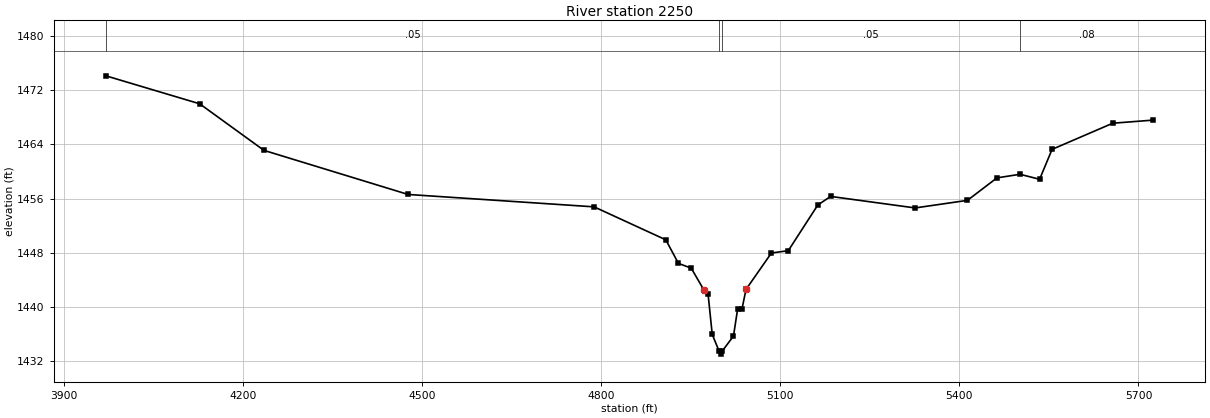
Type RM Length L Ch R = 1 ,2250    ,0,0,0
BEGIN DESCRIPTION:
THREEMILE CREEK 4.0
END DESCRIPTION:
XS GIS Cut Line= 4
      2817528.48     10049773.15      2817903.47     10050064.81
      2818570.14     10050766.19       2818874.6     10050703.92
#Sta/Elev= 30
  3970.9 1474.12  4127.9 1469.99  4235.6 1463.11    4477  1456.6  4788.4 1454.77
  4908.5  1449.9  4929.6 1446.42    4951 1445.72  4972.1 1442.52  4979.3 1441.87
  4986.2 1435.94  4997.4 1433.52  5000.1 1433.02  5003.4 1433.52  5021.8 1435.69
  5028.7 1439.65    5036 1439.67  5042.8 1442.58  5085.3 1447.95  5113.6  1448.3
    5163 1455.04  5184.4 1456.31    5326 1454.61  5413.6 1455.73    5463 1459.05
  5501.7 1459.58  5534.4 1458.84  5555.3 1463.26  5656.9 1467.12  5724.4 1467.58
#Mann= 4 ,-1 , 0
  3970.9     .05       0  4997.4     .04       0  5003.4     .05       0
  5501.7     .08       0
Bank Sta=4972.1,5042.8
XS Rating Curve= 0 ,0
Exp/Cntr=0.3,0.1

Chan Stop Cuts=-1
Use User Specified Reach Order=0
Composite Channel Slope=5