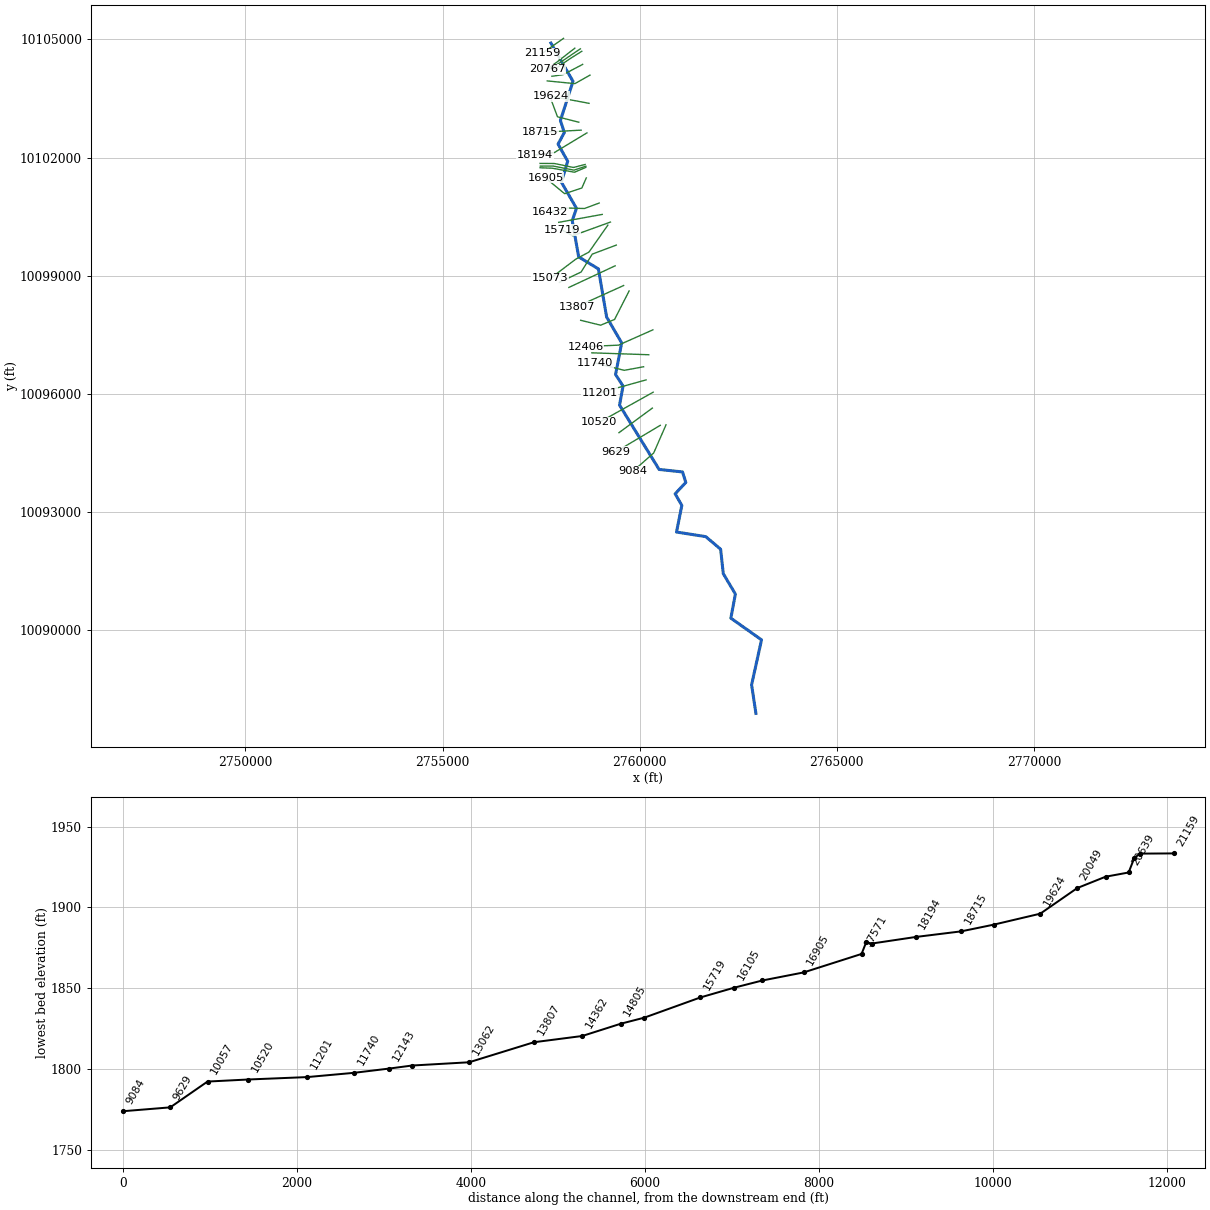
--- TREIBS CREEK.prj (project) ---

Proj Title=TREIBS CREEK Base Level Engineering
Current Plan=p01
Default Exp/Contr=0.3,0.1
English Units
Geom File=g01
Flow File=f01
Plan File=p01
Y Axis Title=Elevation
X Axis Title(PF)=Main Channel Distance
X Axis Title(XS)=Station
BEGIN DESCRIPTION:
TREIBS CREEK
END DESCRIPTION:
DSS Export Rating Curves= 0
DSS Export Rating Curve Sorted= 0
DSS Export Volume Flow Curves= 0
DXF OffsetX= 0
DXF OffsetY= 0
DXF ScaleX= 1
DXF ScaleY= 10

--- TREIBS CREEK.p01 (plan) ---

Plan Title=Multiple Run
Short Identifier=Multiple
Geom File=g01
Flow File=f01
Subcritical Flow
K Sum by GR= 0
Std Step Tol= 0.01
Critical Tol= 0.01
Num of Std Step Trials= 20
Max Error Tol= 0.3
Flow Tol Ratio= 0.001
Split Flow NTrial= 30
Split Flow Tol= 0.02
Split Flow Ratio= 0.02
Log Output Level= 0
Friction Slope Method= 1
Unsteady Friction Slope Method= 2
Unsteady Bridges Friction Slope Method= 1
Parabolic Critical Depth
Global Vel Dist=  1 , 1 , 1
Global Log Level= 0
CheckData=True
Encroach Param= -1, 0, 0, 0
BEGIN DESCRIPTION:
Multiple Run
END DESCRIPTION:

--- TREIBS CREEK.f01 (steady flow) ---

Flow Title=Multiple
Program Version=4.10
Number of Profiles= 7
Profile Names=10-year,25-year,50-year,1pct_min,100-year,1pct_plu,500-year
River Rch & RM=TREIBS CREEK,Reach-1         ,21159
     911    1330    1697    1586    2145    2901    3440
River Rch & RM=TREIBS CREEK,Reach-1         ,19089
    1206    1785    2298    2164    2927    3958    4768
River Rch & RM=TREIBS CREEK,Reach-1         ,14805
    1783    2688    3503    3335    4510    6099    7510
River Rch & RM=TREIBS CREEK,Reach-1         ,11201
    2021    3047    3970    3774    5104    6902    8477
Boundary for River Rch & Prof#=TREIBS CREEK,Reach-1         , 1
Up Type= 0
Dn Type= 3
Dn Slope=0.008
Boundary for River Rch & Prof#=TREIBS CREEK,Reach-1         , 2
Up Type= 0
Dn Type= 3
Dn Slope=0.008
Boundary for River Rch & Prof#=TREIBS CREEK,Reach-1         , 3
Up Type= 0
Dn Type= 3
Dn Slope=0.008
Boundary for River Rch & Prof#=TREIBS CREEK,Reach-1         , 4
Up Type= 0
Dn Type= 3
Dn Slope=0.008
Boundary for River Rch & Prof#=TREIBS CREEK,Reach-1         , 5
Up Type= 0
Dn Type= 3
Dn Slope=0.008
Boundary for River Rch & Prof#=TREIBS CREEK,Reach-1         , 6
Up Type= 0
Dn Type= 3
Dn Slope=0.008
Boundary for River Rch & Prof#=TREIBS CREEK,Reach-1         , 7
Up Type= 0
Dn Type= 3
Dn Slope=0.008
DSS Import GetInterval= 0
DSS Import GetPeak= 0
DSS Import FillOption= 0

--- TREIBS CREEK.g01 (geometry) ---

Geom Title=Existing Conditions
Program Version=4.10

River Reach=TREIBS CREEK    ,Reach-1
Reach XY= 30
      2757748.03     10104909.68      2758307.99     10103938.46
      2757989.29     10102943.31      2758087.85     10102638.49
      2757929.49     10102343.64      2758174.06     10101908.78
      2758012.25     10101380.65      2758396.87     10100712.95
      2758288.58     10100403.83      2758452.49     10099480.96
      2758952.77     10099176.17      2759161.41     10097955.08
       2759542.8     10097298.57      2759388.44     10096494.63
      2759577.47     10096203.31      2759489.33     10095718.42
      2760493.11     10094085.63      2761085.92     10094022.69
      2761169.65     10093755.86      2760899.53     10093466.82
      2761069.06     10093173.46      2760934.49     10092496.85
      2761677.01     10092380.05      2762053.22     10092060.51
      2762120.63     10091439.63      2762427.56      10090923.2
        2762313.      10090310.9      2763090.74     10089760.28
      2762838.96     10088618.39      2762948.47     10087893.73

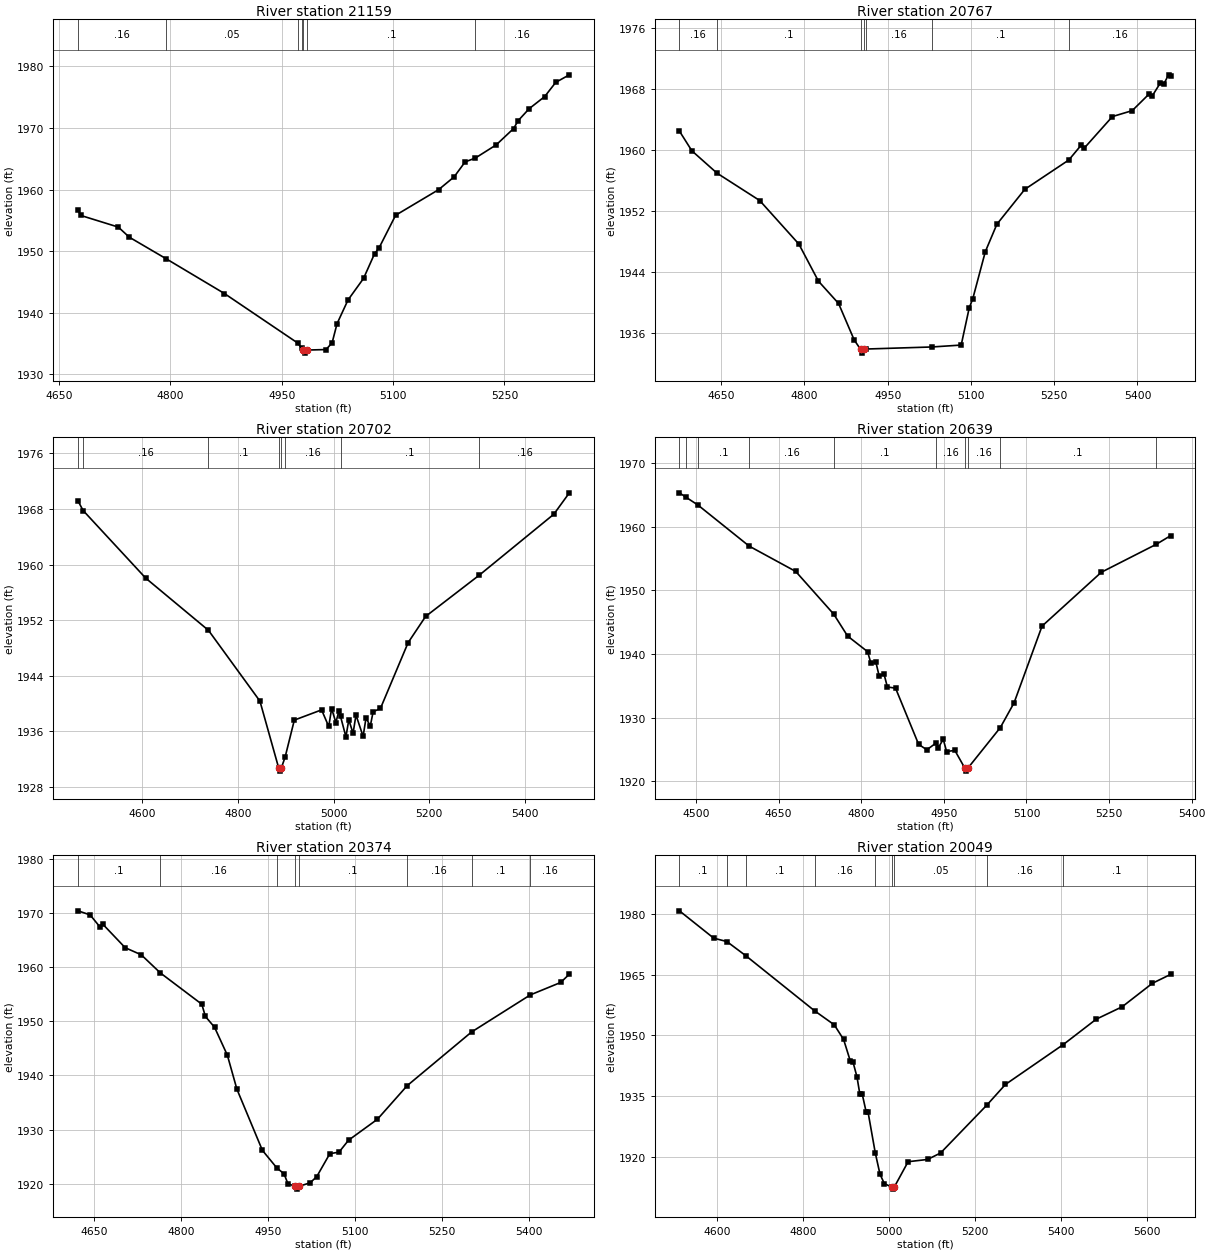
Type RM Length L Ch R = 1 ,21159   ,392,392,392
BEGIN DESCRIPTION:
TREIBS CREEK 46.0
END DESCRIPTION:
XS GIS Cut Line= 2
      2758068.64     10105029.45      2757526.96     10104649.24
#Sta/Elev= 30
  4675.7 1956.66  4679.5 1955.79    4730  1953.9  4744.8 1952.26  4794.5 1948.75
    4873  1943.1  4971.9 1935.04  4976.9 1934.19  4978.4 1933.92  4981.1 1933.42
  4984.4 1933.92  5009.8    1934    5018 1935.11  5024.6  1938.2  5039.4 1942.06
  5060.3 1945.56  5075.1 1949.56  5081.2 1950.52  5103.5 1955.82  5161.4 1959.98
  5182.3 1962.06  5197.1 1964.49  5210.9 1965.12    5239 1967.26  5262.4 1969.91
  5268.6  1971.2  5283.4 1973.14  5304.3 1975.11  5319.2 1977.42  5337.5 1978.64
#Mann= 7 ,-1 , 0
  4675.7     .16       0  4794.5     .05       0  4971.9     .16       0
  4976.9      .1       0  4978.4     .07       0  4984.4      .1       0
  5210.9     .16       0
Bank Sta=4978.4,4984.4
XS Rating Curve= 0 ,0
Exp/Cntr=0.3,0.1

Type RM Length L Ch R = 1 ,20767   ,65,65,65
BEGIN DESCRIPTION:
Mapping XS fa890f18
END DESCRIPTION:
XS GIS Cut Line= 3
      2758355.08     10104779.44      2757891.53     10104420.06
       2757647.1     10104248.44
#Sta/Elev= 30
  4574.8 1962.49  4597.2  1959.9  4642.5 1956.96  4719.4 1953.36    4790 1947.63
  4825.3 1942.75  4861.5 1939.82  4889.6 1935.03  4901.1 1933.79  4903.8 1933.29
  4907.1 1933.79  4911.8 1933.83  5029.8  1934.1  5082.4 1934.35  5096.9 1939.25
  5103.3 1940.45  5125.9 1946.64  5146.7 1950.24    5197 1954.83  5276.3 1958.69
  5298.1  1960.6  5304.2 1960.26  5354.8  1964.4  5390.5 1965.18  5420.1 1967.31
  5426.2 1967.07    5441  1968.8  5447.2 1968.64  5455.9 1969.89    5460 1969.74
#Mann= 7 ,-1 , 0
  4574.8     .16       0  4642.5      .1       0  4901.1     .07       0
  4907.1      .1       0  4911.8     .16       0  5029.8      .1       0
  5276.3     .16       0
Bank Sta=4901.1,4907.1
XS Rating Curve= 0 ,0
Exp/Cntr=0.3,0.1

Type RM Length L Ch R = 1 ,20702   ,63,63,63
BEGIN DESCRIPTION:
Mapping XS c6280c0d
END DESCRIPTION:
XS GIS Cut Line= 3
      2758495.72     10104763.82      2757980.07     10104414.85
      2757636.33     10104201.32
#Sta/Elev= 30
  4465.5 1969.16  4476.3 1967.78  4607.1 1958.06  4738.3 1950.55  4845.9 1940.37
  4884.9  1930.8  4887.6  1930.3  4890.9  1930.8  4898.6 1932.33  4917.8 1937.64
  4974.8 1939.11  4989.7 1936.72  4995.8  1939.3  5004.7 1937.28  5010.7 1938.89
  5014.4 1938.17  5025.7 1935.23  5031.7 1937.69  5040.6 1935.73  5046.7 1938.38
  5061.6 1935.29  5067.7 1937.96  5076.6 1936.78  5082.6 1938.85  5097.8 1939.31
  5155.7 1948.78  5192.3 1952.55  5304.9 1958.51  5460.3 1967.25  5492.8 1970.33
#Mann= 8 ,-1 , 0
  4465.5      .1       0  4476.3     .16       0  4738.3      .1       0
  4884.9     .07       0  4890.9      .1       0  4898.6     .16       0
  5014.4      .1       0  5304.9     .16       0
Bank Sta=4884.9,4890.9
XS Rating Curve= 0 ,0
Exp/Cntr=0.3,0.1

Type RM Length L Ch R = 1 ,20639   ,265,265,265
BEGIN DESCRIPTION:
Mapping XS 21a14aed
END DESCRIPTION:
XS GIS Cut Line= 3
      2758532.13     10104701.29      2758250.91     10104524.23
        2757789.     10104207.64
#Sta/Elev= 30
  4469.8 1965.29  4481.9 1964.59  4503.5 1963.37  4596.4 1956.93    4681 1952.95
    4750 1946.25  4775.2 1942.81  4811.5 1940.36  4817.6 1938.53  4826.4 1938.77
  4832.5 1936.54  4841.3 1936.86  4847.4 1934.82  4862.3 1934.63  4904.2 1925.81
  4919.1 1924.96  4936.4 1926.06  4940.1  1925.3  4948.9 1926.61    4955 1924.68
  4969.9 1924.87  4987.9 1922.11  4990.6 1921.61  4993.9 1922.11  5052.5 1928.44
  5077.5 1932.33  5128.3 1944.37  5235.9 1952.82  5335.5  1957.2  5362.1 1958.58
#Mann= 10 ,-1 , 0
  4469.8      .1       0  4481.9     .16       0  4503.5      .1       0
  4596.4     .16       0    4750      .1       0  4936.4     .16       0
  4987.9     .07       0  4993.9     .16       0  5052.5      .1       0
  5335.5     .16       0
Bank Sta=4987.9,4993.9
XS Rating Curve= 0 ,0
Exp/Cntr=0.3,0.1

Type RM Length L Ch R = 1 ,20374   ,325,325,325
BEGIN DESCRIPTION:
Mapping XS cd6ba3cb
END DESCRIPTION:
XS GIS Cut Line= 3
      2758552.96     10104367.96       2758058.2     10104107.56
      2757772.61     10104066.02
#Sta/Elev= 30
  4622.4  1970.4  4643.3 1969.65  4659.7  1967.5  4665.4 1967.91  4703.8 1963.59
  4731.5 1962.28  4764.6 1958.92    4836 1953.15  4842.2 1950.89    4858 1948.89
  4880.1 1943.73  4896.5 1937.47  4940.5 1926.16  4965.5  1922.9  4977.8 1921.83
  4984.6 1919.99  4997.4 1919.49  5000.1 1918.99  5003.4 1919.49    5023 1920.17
  5034.3  1921.3  5056.9 1925.54  5072.7 1925.82  5089.1 1928.02  5138.9 1931.89
  5190.3  1938.1  5301.3 1948.01  5402.6 1954.86  5455.2 1957.17  5470.1  1958.7
#Mann= 8 ,-1 , 0
  4622.4      .1       0  4764.6     .16       0  4965.5      .1       0
  4997.4     .07       0  5003.4      .1       0  5190.3     .16       0
  5301.3      .1       0  5402.6     .16       0
Bank Sta=4997.4,5003.4
XS Rating Curve= 0 ,0
Exp/Cntr=0.3,0.1

Type RM Length L Ch R = 1 ,20049   ,425,425,425
BEGIN DESCRIPTION:
TREIBS CREEK 45.0
END DESCRIPTION:
XS GIS Cut Line= 3
      2758737.91     10104094.85      2758355.96     10103879.57
      2757656.03     10103948.87
#Sta/Elev= 30
  4513.3  1980.8    4593 1974.04  4623.6  1973.2  4667.8 1969.68  4827.2 1956.09
  4873.1 1952.61  4894.8 1948.99  4910.7 1943.56  4916.4 1943.51  4925.9 1939.73
  4932.4 1935.57  4938.1 1935.47  4947.4 1930.98  4951.7 1930.98  4968.4 1920.94
  4979.4 1915.66  4989.4 1913.36  5006.5 1912.48  5009.3 1911.98  5012.5 1912.48
  5044.7 1918.76  5089.9 1919.32  5120.1 1920.91    5228  1932.8  5270.8 1937.86
  5405.4 1947.74  5481.8    1954  5542.1 1957.07  5612.5 1962.89  5655.1  1965.1
#Mann= 9 ,-1 , 0
  4513.3      .1       0  4623.6     .16       0  4667.8      .1       0
  4827.2     .16       0  4968.4     .05       0  5006.5    .035       0
  5012.5     .05       0    5228     .16       0  5405.4      .1       0
Bank Sta=5006.5,5012.5
XS Rating Curve= 0 ,0
Exp/Cntr=0.3,0.1

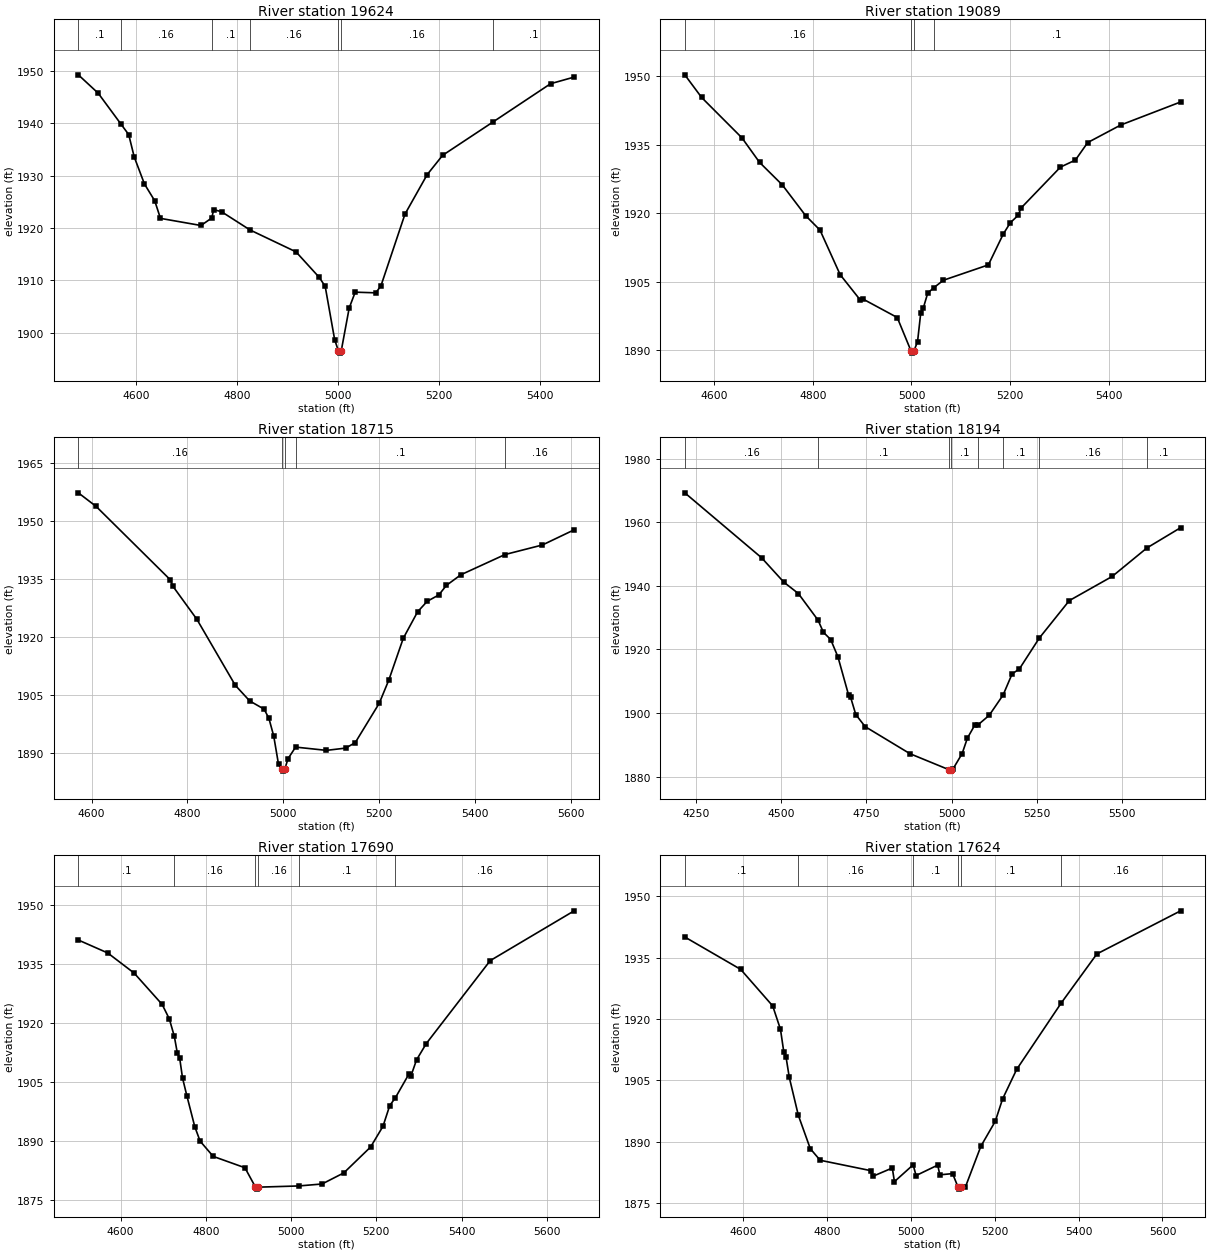
Type RM Length L Ch R = 1 ,19624   ,535,535,535
BEGIN DESCRIPTION:
TREIBS CREEK 44.0
END DESCRIPTION:
XS GIS Cut Line= 2
      2758717.07     10103379.57      2757752.59     10103559.97
#Sta/Elev= 30
  4485.7  1949.3    4525 1945.79  4569.8 1939.92  4585.4 1937.88  4596.2 1933.64
  4616.5 1928.45  4636.9 1925.23  4648.2 1921.87  4728.4 1920.51  4749.8 1921.95
  4753.5 1923.55  4769.1 1923.14  4825.4 1919.66  4916.5 1915.47  4962.4  1910.6
  4974.2 1908.88  4992.9 1898.72  5000.1 1896.62  5002.9 1896.12  5006.1 1896.62
  5021.7 1904.74  5033.6 1907.77  5074.3 1907.64  5084.5 1908.97  5132.1 1922.68
  5176.1 1930.24  5206.6 1933.92  5306.6 1940.31  5420.2  1947.6  5466.9 1948.87
#Mann= 7 ,-1 , 0
  4485.7      .1       0  4569.8     .16       0  4749.8      .1       0
  4825.4     .16       0  5000.1     .07       0  5006.1     .16       0
  5306.6      .1       0
Bank Sta=5000.1,5006.1
XS Rating Curve= 0 ,0
Exp/Cntr=0.3,0.1

Type RM Length L Ch R = 1 ,19089   ,374,374,374
BEGIN DESCRIPTION:
TREIBS CREEK 43.0
END DESCRIPTION:
XS GIS Cut Line= 3
      2758456.27     10102900.18      2757914.57     10103038.21
      2757758.34     10103457.44
#Sta/Elev= 30
  4539.9 1950.35  4574.1 1945.38  4655.9 1936.53  4691.6 1931.16  4737.7 1926.23
  4785.3 1919.46  4814.3 1916.31  4855.2 1906.54  4896.1 1900.97  4901.2 1901.21
  4971.1 1897.14    4999 1889.83  5001.8 1889.33    5005 1889.83  5012.3 1891.83
  5018.8 1898.13  5023.9 1899.18    5033  1902.5  5044.9 1903.64  5064.8 1905.31
  5156.1 1908.68  5186.4 1915.46  5200.8 1917.94  5216.7 1919.56  5222.2 1921.12
  5302.4 1930.12  5332.7 1931.66  5357.7  1935.5    5425 1939.36  5546.3  1944.4
#Mann= 4 ,-1 , 0
  4539.9     .16       0    4999     .07       0    5005     .16       0
  5044.9      .1       0
Bank Sta=4999,5005
XS Rating Curve= 0 ,0
Exp/Cntr=0.3,0.1

Type RM Length L Ch R = 1 ,18715   ,521,521,521
BEGIN DESCRIPTION:
TREIBS CREEK 42.0
END DESCRIPTION:
XS GIS Cut Line= 2
      2758515.64     10102699.01      2757482.23     10102643.52
#Sta/Elev= 30
  4572.5 1957.32  4609.7 1953.79  4764.6 1934.76    4770 1933.08    4820 1924.52
  4900.1 1907.43  4930.2 1903.37  4960.2 1901.25  4970.2 1898.89  4980.3 1894.29
  4990.3 1886.97  4997.3 1885.68    5000 1885.18  5003.3 1885.68  5010.3 1888.43
    5026 1891.41  5090.4 1890.56  5130.5 1891.15  5150.5 1892.57  5200.6 1902.78
  5220.6 1908.81  5250.7 1919.61  5280.7 1926.49  5300.7  1929.2  5324.8 1930.84
  5340.8 1933.33  5370.8 1936.07  5463.2 1941.33  5541.1  1943.8  5607.4 1947.73
#Mann= 5 ,-1 , 0
  4572.5     .16       0  4997.3     .07       0  5003.3     .16       0
    5026      .1       0  5463.2     .16       0
Bank Sta=4997.3,5003.3
XS Rating Curve= 0 ,0
Exp/Cntr=0.3,0.1

Type RM Length L Ch R = 1 ,18194   ,504,504,504
BEGIN DESCRIPTION:
TREIBS CREEK 41.0
END DESCRIPTION:
XS GIS Cut Line= 3
      2758661.53     10102629.58      2757835.12     10102129.57
      2757349.02     10102067.07
#Sta/Elev= 30
  4216.6 1969.22  4442.2 1948.79  4507.3 1941.14    4550 1937.56  4607.8 1929.19
  4623.7 1925.36    4645 1923.09  4666.3 1917.64  4697.4  1905.7  4703.2 1905.05
  4718.7  1899.5  4746.1 1895.71  4877.8 1887.19  4991.2 1882.21  4993.9 1881.71
  4997.2 1882.21  5003.3 1882.23    5031 1887.23  5046.5  1892.1  5067.9 1896.14
  5078.4 1896.33  5110.6 1899.27  5151.3 1905.65  5177.6 1912.25  5199.3 1913.88
  5257.8 1923.58  5345.7 1935.33  5471.5 1942.92  5573.9 1951.91  5672.6 1958.26
#Mann= 8 ,-1 , 0
  4216.6     .16       0  4607.8      .1       0  4991.2     .07       0
  4997.2      .1       0  5078.4     .16       0  5151.3      .1       0
  5257.8     .16       0  5573.9      .1       0
Bank Sta=4991.2,4997.2
XS Rating Curve= 0 ,0
Exp/Cntr=0.3,0.1

Type RM Length L Ch R = 1 ,17690   ,66,66,66
BEGIN DESCRIPTION:
Mapping XS e5a606c0
END DESCRIPTION:
XS GIS Cut Line= 4
      2758615.36     10101827.15      2758319.78     10101751.62
      2757839.31     10101851.88      2757471.51     10101854.47
#Sta/Elev= 30
  4500.6 1941.15  4569.6 1937.85  4631.6 1932.72  4697.4 1924.72  4714.1 1921.05
  4725.8 1916.65  4733.1 1912.26  4738.3 1911.17  4745.1 1906.01  4755.4 1901.41
  4773.9 1893.57  4786.4 1889.89  4817.2    1886  4891.6 1883.11  4916.4 1878.16
  4919.1 1877.66  4922.4 1878.16    5018 1878.47  5072.6 1878.97  5123.7  1881.8
  5186.6  1888.4  5215.6 1893.67  5231.5 1898.97  5244.5 1900.91  5276.4 1906.97
  5281.5 1906.59  5294.4 1910.61  5317.3 1914.77  5467.3  1935.9  5664.3 1948.59
#Mann= 6 ,-1 , 0
  4500.6      .1       0  4725.8     .16       0  4916.4     .07       0
  4922.4     .16       0    5018      .1       0  5244.5     .16       0
Bank Sta=4916.4,4922.4
XS Rating Curve= 0 ,0
Exp/Cntr=0.3,0.1

Type RM Length L Ch R = 1 ,17624   ,53,53,53
BEGIN DESCRIPTION:
TREIBS CREEK 40.0
END DESCRIPTION:
XS GIS Cut Line= 4
      2758634.91     10101784.19       2758334.1     10101683.92
      2757800.25     10101788.08      2757478.66     10101785.48
#Sta/Elev= 30
  4460.7 1940.01    4594  1932.1  4670.4 1923.17  4688.9 1917.46  4696.7 1912.02
    4702 1910.81  4709.9 1905.73  4731.5 1896.46    4760 1888.32  4783.5 1885.49
    4904 1882.96  4909.1 1881.57  4955.6  1883.6  4960.7 1880.27  5005.3 1884.37
  5012.3 1881.76  5063.9  1884.3    5069 1881.93  5099.4 1882.23  5112.4 1878.94
  5115.2 1878.44  5118.4 1878.94  5129.9 1878.94    5167 1888.94  5201.3 1895.02
  5218.6 1900.45  5252.2 1907.67  5358.1 1923.83  5443.5 1935.87  5643.3  1946.4
#Mann= 6 ,-1 , 0
  4460.7      .1       0  4731.5     .16       0  5005.3      .1       0
  5112.4     .07       0  5118.4      .1       0  5358.1     .16       0
Bank Sta=5112.4,5118.4
XS Rating Curve= 0 ,0
Exp/Cntr=0.3,0.1

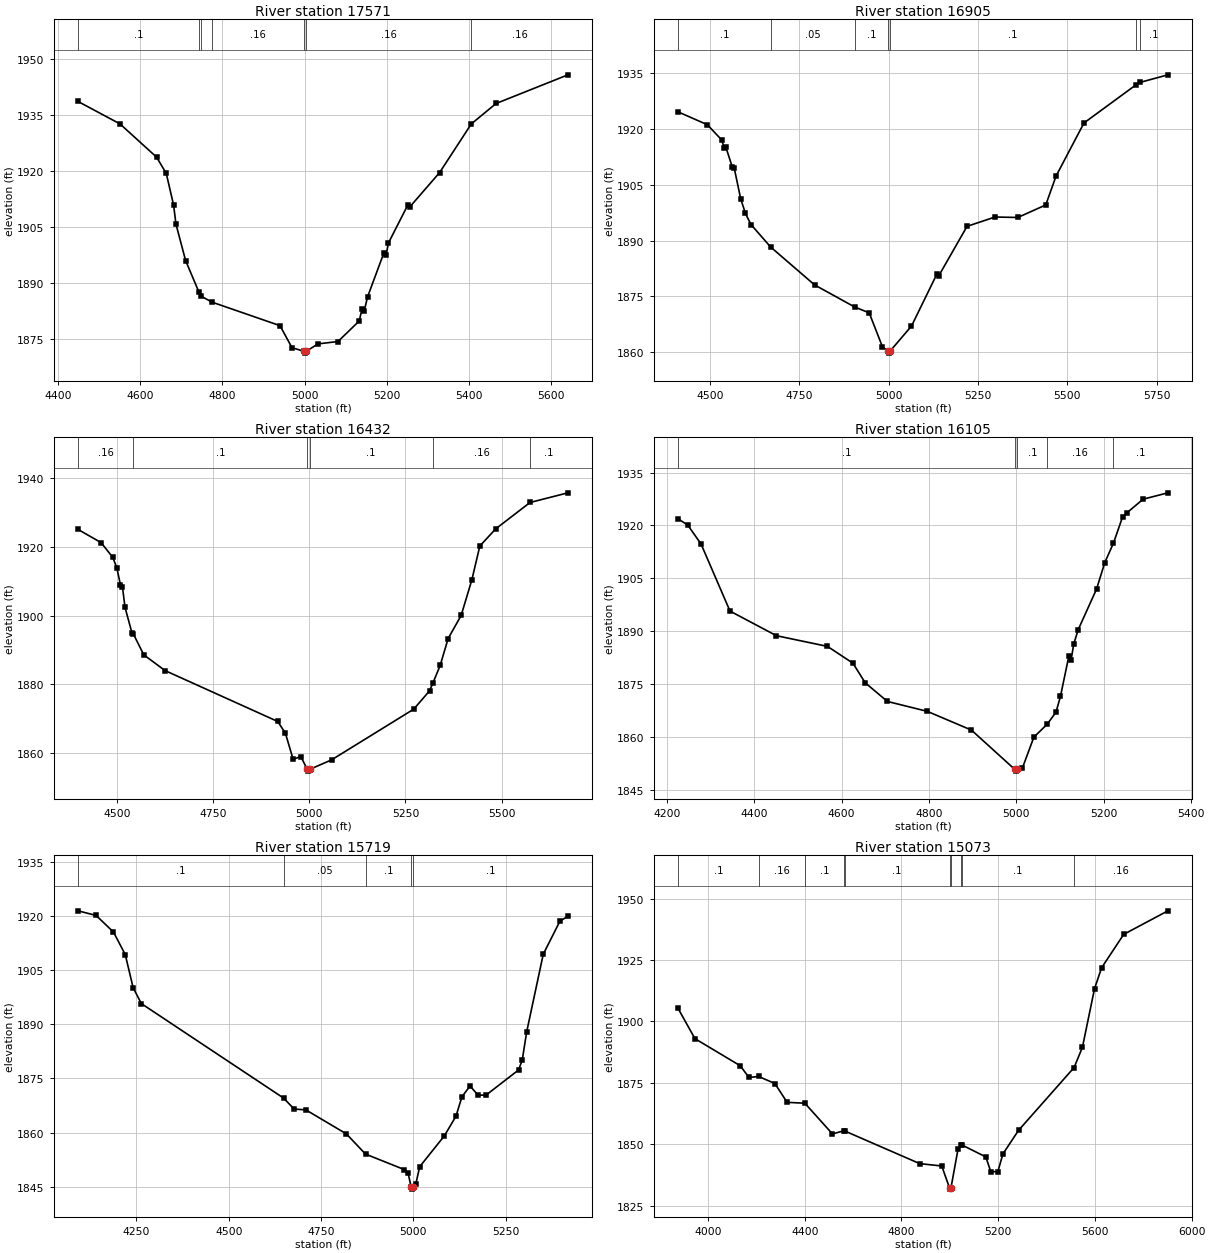
Type RM Length L Ch R = 1 ,17571   ,666,666,666
BEGIN DESCRIPTION:
Mapping XS 6b3a38d2
END DESCRIPTION:
XS GIS Cut Line= 4
      2758632.29     10101752.93      2758347.12     10101630.53
      2757785.92     10101732.09      2757473.49     10101743.81
#Sta/Elev= 30
  4448.2 1938.53  4550.3 1932.54  4639.6 1923.63  4663.1 1919.27  4680.9 1910.86
  4686.7 1905.73  4710.2 1895.98  4742.6 1887.55  4748.1 1886.42  4775.3 1884.82
  4940.1 1878.56  4969.3 1872.67  4998.1 1871.71  5000.8 1871.21  5004.1 1871.71
  5032.9 1873.69  5081.3 1874.31  5133.2 1879.82  5139.9 1883.11    5145 1882.39
  5153.5 1886.28  5193.4 1898.11  5198.4 1897.41  5204.3 1900.68  5251.9 1910.94
    5257 1910.41  5328.8  1919.5  5406.2 1932.54  5466.4 1937.99  5641.5 1945.66
#Mann= 7 ,-1 , 0
  4448.2      .1       0  4742.6     .16       0  4748.1      .1       0
  4775.3     .16       0  4998.1     .07       0  5004.1     .16       0
  5406.2     .16       0
Bank Sta=4998.1,5004.1
XS Rating Curve= 0 ,0
Exp/Cntr=0.3,0.1

Type RM Length L Ch R = 1 ,16905   ,473,473,473
BEGIN DESCRIPTION:
TREIBS CREEK 38.0
END DESCRIPTION:
XS GIS Cut Line= 4
      2758645.39     10101486.28      2758532.56     10101230.25
      2758096.36     10101084.85      2757610.21     10101486.35
#Sta/Elev= 30
  4411.3 1924.68  4493.3 1921.22  4534.3 1917.04  4539.9  1914.9  4545.4 1915.12
  4563.2 1909.79  4568.7 1909.48  4586.6  1901.3  4599.9 1897.34  4615.4 1894.36
  4670.3 1888.32  4793.2 1878.12  4905.8 1872.15    4946  1870.6  4982.9  1861.5
  4998.1 1860.26  5000.8 1859.76  5004.1 1860.26  5064.3 1867.05  5135.7 1881.11
    5141 1880.64  5219.6 1893.87  5297.8 1896.38  5361.6 1896.26  5439.8 1899.63
  5468.5 1907.39  5546.7 1921.69  5691.9 1931.93  5703.3  1932.6  5781.4 1934.64
#Mann= 7 ,-1 , 0
  4411.3      .1       0  4670.3     .05       0  4905.8      .1       0
  4998.1     .07       0  5004.1      .1       0  5691.9     .16       0
  5703.3      .1       0
Bank Sta=4998.1,5004.1
XS Rating Curve= 0 ,0
Exp/Cntr=0.3,0.1

Type RM Length L Ch R = 1 ,16432   ,327,327,327
BEGIN DESCRIPTION:
TREIBS CREEK 37.0
END DESCRIPTION:
XS GIS Cut Line= 4
      2758973.14     10100848.32      2758597.66     10100709.42
      2758141.93     10100722.44      2757736.12     10100620.44
#Sta/Elev= 30
  4398.2 1925.09  4458.2 1921.26  4488.6 1916.95  4499.1 1913.94  4508.4 1909.05
  4513.7 1908.42  4520.5  1902.4  4538.8 1894.86  4542.4 1894.64  4569.2 1888.62
  4624.7 1884.03  4917.8 1869.23  4937.8 1865.81  4957.8 1858.23  4977.8 1859.03
  4994.8 1855.29  4997.6 1854.79  5000.8 1855.29  5057.8 1858.06  5271.6 1872.81
  5312.7 1878.13  5321.1  1880.3  5340.5 1885.55  5361.1 1893.35    5395 1900.06
    5423 1910.49  5443.6 1920.26  5484.9 1925.26  5574.3 1932.93  5672.9 1935.74
#Mann= 6 ,-1 , 0
  4398.2     .16       0  4542.4      .1       0  4994.8     .07       0
  5000.8      .1       0  5321.1     .16       0  5574.3      .1       0
Bank Sta=4994.8,5000.8
XS Rating Curve= 0 ,0
Exp/Cntr=0.3,0.1

Type RM Length L Ch R = 1 ,16105   ,386,386,386
BEGIN DESCRIPTION:
TREIBS CREEK 36.0
END DESCRIPTION:
XS GIS Cut Line= 2
      2759050.44     10100560.13      2757946.25     10100358.74
#Sta/Elev= 30
  4225.1 1921.91  4247.4 1920.12  4277.9 1914.75  4344.2 1895.71  4450.7 1888.72
  4567.5 1885.69  4625.8 1880.93    4654 1875.36  4704.9 1870.06  4796.3 1867.25
  4897.3 1861.94  4996.6 1850.79  4999.4 1850.29  5002.6 1850.79    5014 1851.12
  5040.3 1859.91  5070.9 1863.61  5091.1 1867.02  5101.3  1871.5  5120.6 1882.95
  5125.7 1881.87  5131.8 1886.37  5141.9 1890.42    5184 1901.96  5202.9 1909.49
  5222.7 1914.99  5243.6 1922.42  5253.8 1923.62  5290.6 1927.46  5347.5 1929.27
#Mann= 5 ,-1 , 0
  4225.1      .1       0  4996.6     .07       0  5002.6      .1       0
  5070.9     .16       0  5222.7      .1       0
Bank Sta=4996.6,5002.6
XS Rating Curve= 0 ,0
Exp/Cntr=0.3,0.1

Type RM Length L Ch R = 1 ,15719   ,646,646,646
BEGIN DESCRIPTION:
TREIBS CREEK 35.0
END DESCRIPTION:
XS GIS Cut Line= 3
      2759258.73     10100365.68       2758300.4     10100018.46
      2758029.56     10100164.29
#Sta/Elev= 30
  4091.7 1921.56  4140.6 1920.28  4187.7 1915.66  4219.6 1909.41  4240.9 1900.21
  4263.2  1895.8  4648.3 1869.57    4677 1866.52  4708.9 1866.28  4818.6 1859.61
  4870.3 1854.01  4974.8 1849.73  4985.4 1848.85  4994.1 1844.78  4996.8 1844.28
  5000.1 1844.78  5006.7 1845.79  5017.1 1850.51  5083.6 1859.04  5115.2  1864.5
  5131.4 1869.89  5153.4 1872.93  5175.3 1870.34  5197.2 1870.42  5284.8 1877.37
  5294.9 1880.16  5306.7  1887.9  5351.7 1909.51  5397.1 1918.74  5418.6 1920.02
#Mann= 5 ,-1 , 0
  4091.7      .1       0  4648.3     .05       0  4870.3      .1       0
  4994.1     .07       0  5000.1      .1       0
Bank Sta=4994.1,5000.1
XS Rating Curve= 0 ,0
Exp/Cntr=0.3,0.1

Type RM Length L Ch R = 1 ,15073   ,268,268,268
BEGIN DESCRIPTION:
TREIBS CREEK 34.0
END DESCRIPTION:
XS GIS Cut Line= 4
      2759192.19     10100288.27      2758713.02     10099603.37
      2758382.29     10099426.29      2757732.35     10098934.94
#Sta/Elev= 30
    3876 1905.33  3946.1 1892.98  4133.6 1881.95  4169.3 1877.18  4209.1 1877.59
  4276.6 1874.73  4327.2 1867.06  4400.5 1866.71  4514.6 1854.21  4563.3 1855.51
  4565.5  1855.4  4875.8 1842.11  4966.6 1841.16  4998.7 1832.24  5001.5 1831.74
  5004.7 1832.24  5034.2 1848.21  5048.2  1849.8  5048.3  1849.8  5148.8 1844.85
  5169.6 1838.79  5198.7 1838.88  5219.5 1846.05    5284 1855.65  5513.9 1881.24
  5548.3 1889.48  5598.3  1913.3  5627.4  1921.8    5719 1935.43  5901.8 1945.01
#Mann= 10 ,-1 , 0
    3876      .1       0  4209.1     .16       0  4400.5      .1       0
  4563.3     .05       0  4565.5      .1       0  4998.7     .07       0
  5004.7      .1       0  5048.2     .05       0  5048.3      .1       0
  5513.9     .16       0
Bank Sta=4998.7,5004.7
XS Rating Curve= 0 ,0
Exp/Cntr=0.3,0.1

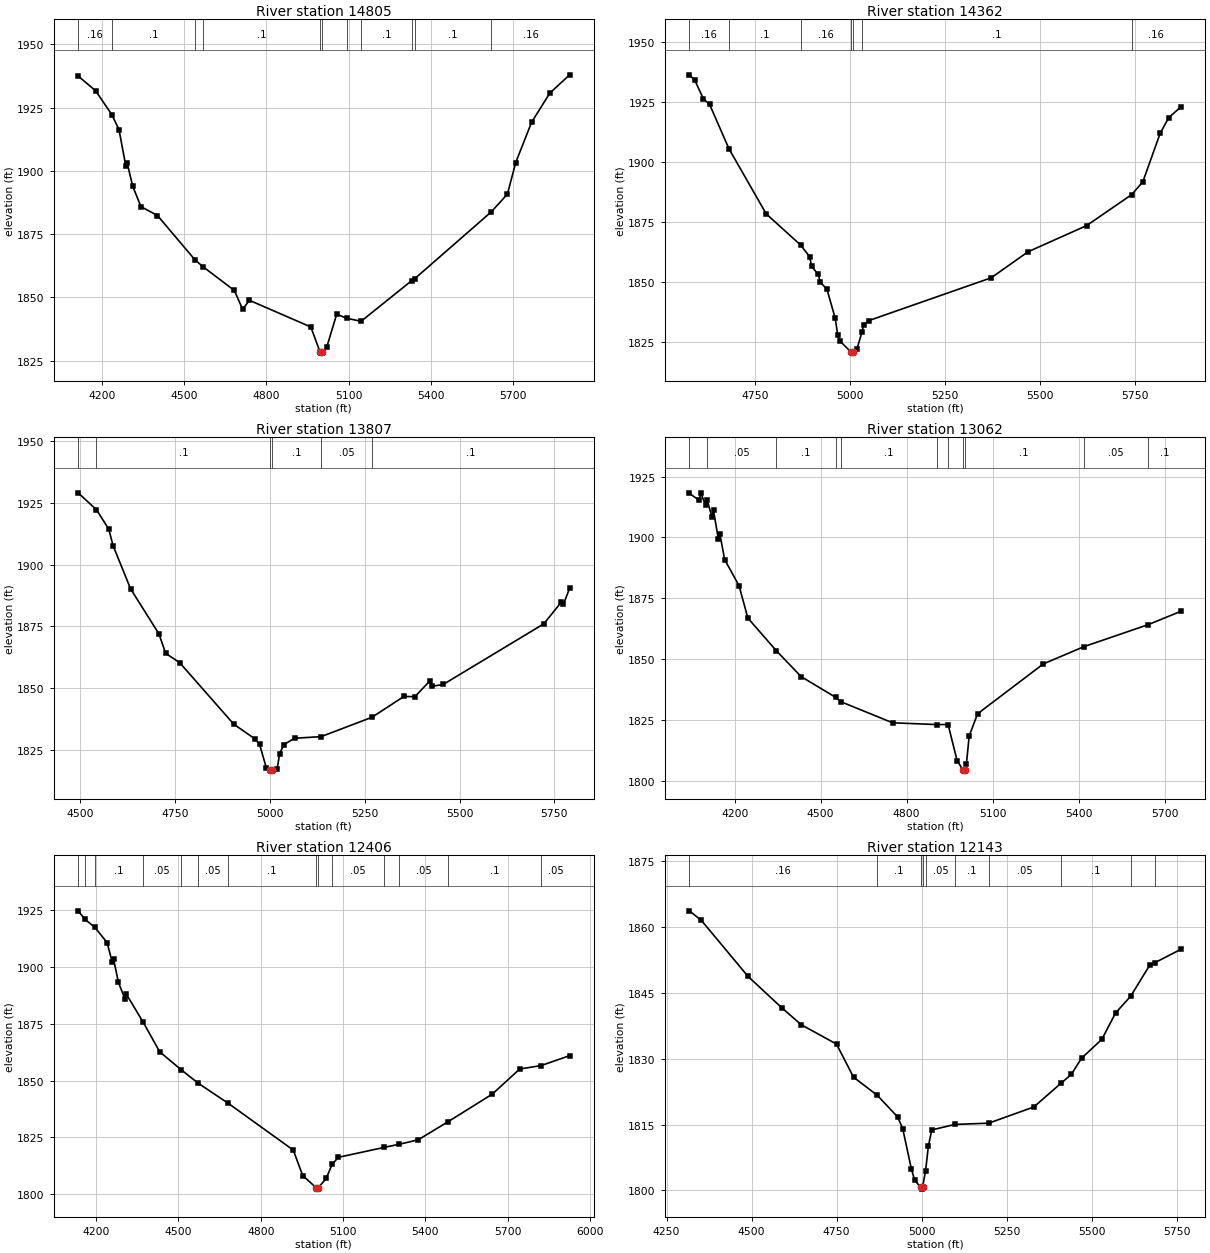
Type RM Length L Ch R = 1 ,14805   ,443,443,443
BEGIN DESCRIPTION:
TREIBS CREEK 33.0
END DESCRIPTION:
XS GIS Cut Line= 4
      2759405.68     10099780.44      2758796.35     10099551.29
       2758515.1     10099098.16      2757963.24     10098835.25
#Sta/Elev= 30
  4111.9 1937.47    4176 1931.61  4234.9 1922.24  4261.3 1916.26  4286.2 1901.93
  4291.5 1902.97  4311.1 1894.03  4341.3 1885.89  4401.8 1882.37  4538.8 1864.86
  4568.4 1862.14  4682.7 1852.77  4712.9 1845.35  4737.8 1848.88    4962 1838.37
  4995.6 1828.53  4998.4 1828.03  5001.6 1828.53  5019.9 1830.27  5056.5 1843.42
    5093  1841.8  5145.8 1840.61  5330.2 1856.62  5341.6 1857.41    5622 1883.88
  5680.2 1890.82  5710.6 1903.29  5768.8 1919.26  5835.2 1930.71  5907.5 1937.93
#Mann= 11 ,-1 , 0
  4111.9     .16       0  4234.9      .1       0  4538.8     .16       0
  4568.4      .1       0  4995.6     .07       0  5001.6      .1       0
    5093     .05       0  5145.8      .1       0  5330.2     .05       0
  5341.6      .1       0    5622     .16       0
Bank Sta=4995.6,5001.6
XS Rating Curve= 0 ,0
Exp/Cntr=0.3,0.1

Type RM Length L Ch R = 1 ,14362   ,555,555,555
BEGIN DESCRIPTION:
TREIBS CREEK 32.0
END DESCRIPTION:
XS GIS Cut Line= 2
      2759376.83     10099254.58      2758203.31     10098706.02
#Sta/Elev= 30
  4576.5 1936.31  4590.8 1934.07  4613.6 1926.32  4629.9 1923.98  4681.1 1905.48
  4779.1 1878.42  4869.7 1865.45  4893.3 1860.65  4898.8 1856.59  4916.1 1853.18
  4921.7 1849.92    4939 1847.11    4961 1834.94  4967.4 1828.11  4972.9 1825.54
  5002.2 1820.93  5004.9 1820.43  5008.2 1820.93  5018.6 1822.33  5031.6 1829.22
  5035.9 1832.17  5049.4 1833.97  5372.3 1851.81  5469.2 1862.63  5623.4 1873.52
  5742.3 1886.43  5771.7 1891.75  5817.4 1911.96  5840.2 1918.53  5871.9 1922.92
#Mann= 7 ,-1 , 0
  4576.5     .16       0  4681.1      .1       0  4869.7     .16       0
  5002.2     .07       0  5008.2     .16       0  5031.6      .1       0
  5742.3     .16       0
Bank Sta=5002.2,5008.2
XS Rating Curve= 0 ,0
Exp/Cntr=0.3,0.1

Type RM Length L Ch R = 1 ,13807   ,745,745,745
BEGIN DESCRIPTION:
TREIBS CREEK 31.0
END DESCRIPTION:
XS GIS Cut Line= 2
      2759592.04     10098754.55      2758412.49     10098220.29
#Sta/Elev= 30
  4495.2 1928.98  4543.5 1922.15    4576 1914.33  4587.2 1907.68  4633.4 1890.22
  4708.2 1871.98  4725.8 1864.15  4762.6 1860.41  4905.3 1835.52  4960.2 1829.69
  4973.2 1827.39  4990.8 1818.02  5001.1 1817.07  5003.9 1816.57  5007.1 1817.07
  5019.4 1817.31  5026.1 1823.54    5037 1827.28  5065.6 1829.85  5135.3  1830.5
  5269.6 1838.34  5353.8 1846.76  5382.3 1846.61  5421.3 1852.91  5428.5 1850.84
  5457.1 1851.58  5722.2 1876.08  5768.4 1884.88  5773.8 1883.94  5790.1 1890.45
#Mann= 6 ,-1 , 0
  4495.2     .16       0  4543.5      .1       0  5001.1     .07       0
  5007.1      .1       0  5135.3     .05       0  5269.6      .1       0
Bank Sta=5001.1,5007.1
XS Rating Curve= 0 ,0
Exp/Cntr=0.3,0.1

Type RM Length L Ch R = 1 ,13062   ,656,656,656
BEGIN DESCRIPTION:
TREIBS CREEK 29.0
END DESCRIPTION:
XS GIS Cut Line= 4
      2759730.93     10098615.64       2759362.9     10097893.46
      2759008.73     10097747.62      2758502.66     10097872.41
#Sta/Elev= 30
  4041.8 1918.07  4076.1 1915.26  4081.7 1918.31  4098.4 1913.17  4103.5 1915.56
  4120.6 1908.44  4126.2 1911.09  4142.8 1899.48  4148.5 1901.26  4165.1 1890.91
  4215.2 1880.23    4246 1866.94  4345.7  1853.5  4431.9 1842.93  4552.1 1834.45
  4571.4 1832.59    4751 1823.99  4904.9 1823.27  4944.5 1823.29  4976.1 1808.44
  4996.6 1804.67  4999.4 1804.17  5002.6 1804.67  5008.6 1807.18  5018.1 1818.57
  5047.5  1827.7  5276.7 1848.13  5417.8 1855.19  5643.2 1864.27  5756.6 1869.71
#Mann= 11 ,-1 , 0
  4041.8     .16       0  4103.5     .05       0  4345.7      .1       0
  4552.1     .16       0  4571.4      .1       0  4904.9     .16       0
  4944.5      .1       0  4996.6     .07       0  5002.6      .1       0
  5417.8     .05       0  5643.2      .1       0
Bank Sta=4996.6,5002.6
XS Rating Curve= 0 ,0
Exp/Cntr=0.3,0.1

Type RM Length L Ch R = 1 ,12406   ,263,263,263
BEGIN DESCRIPTION:
TREIBS CREEK 28.0
END DESCRIPTION:
XS GIS Cut Line= 3
      2760335.08     10097629.55      2759460.12     10097240.68
      2758626.83     10097205.96
#Sta/Elev= 30
  4134.4 1924.81  4159.3 1921.08  4195.6 1917.51  4240.3 1910.74    4258 1902.45
  4263.5 1903.63  4281.3  1893.3  4304.5 1886.11    4310  1888.1  4371.2  1875.8
  4431.8 1862.66  4509.7 1854.81    4571 1848.92  4680.6 1840.06  4918.6 1819.36
  4952.9 1808.15  5003.2 1802.65  5005.9 1802.15  5009.2 1802.65    5039 1806.93
  5060.1 1813.05  5082.8 1816.16  5249.7 1820.54    5304  1821.9  5373.8 1823.87
  5482.2 1831.81    5644 1844.02  5744.1  1855.1  5821.8  1856.6  5925.9 1860.98
#Mann= 14 ,-1 , 0
  4134.4      .1       0  4159.3     .05       0  4195.6      .1       0
  4371.2     .05       0  4509.7      .1       0    4571     .05       0
  4680.6      .1       0  5003.2     .07       0  5009.2      .1       0
  5060.1     .05       0  5249.7      .1       0    5304     .05       0
  5482.2      .1       0  5821.8     .05       0
Bank Sta=5003.2,5009.2
XS Rating Curve= 0 ,0
Exp/Cntr=0.3,0.1

Type RM Length L Ch R = 1 ,12143   ,403,403,403
BEGIN DESCRIPTION:
TREIBS CREEK 27.0
END DESCRIPTION:
XS GIS Cut Line= 2
      2760230.98     10096997.62       2758786.5     10097046.23
#Sta/Elev= 30
  4316.9 1863.74  4352.2 1861.57  4489.5 1848.78  4589.6 1841.57  4645.9 1837.77
  4749.7 1833.35  4799.7  1825.8  4869.8 1821.65  4929.8  1816.7  4944.7 1813.94
  4969.8 1804.88  4979.8 1802.24  4996.8 1800.77  4999.6 1800.27  5002.8 1800.77
  5011.7  1804.5  5019.8  1810.1  5029.8 1813.77  5098.3 1815.03  5197.2 1815.31
    5330 1819.01  5409.7 1824.41  5440.1 1826.42  5470.1 1830.12  5530.1 1834.44
  5570.1 1840.43  5614.7 1844.27  5670.2 1851.28  5684.9 1851.87  5762.2 1854.96
#Mann= 10 ,-1 , 0
  4316.9     .16       0  4869.8      .1       0  4996.8     .07       0
  5002.8      .1       0  5011.7     .05       0  5098.3      .1       0
  5197.2     .05       0  5409.7      .1       0  5614.7     .05       0
  5684.9      .1       0
Bank Sta=4996.8,5002.8
XS Rating Curve= 0 ,0
Exp/Cntr=0.3,0.1

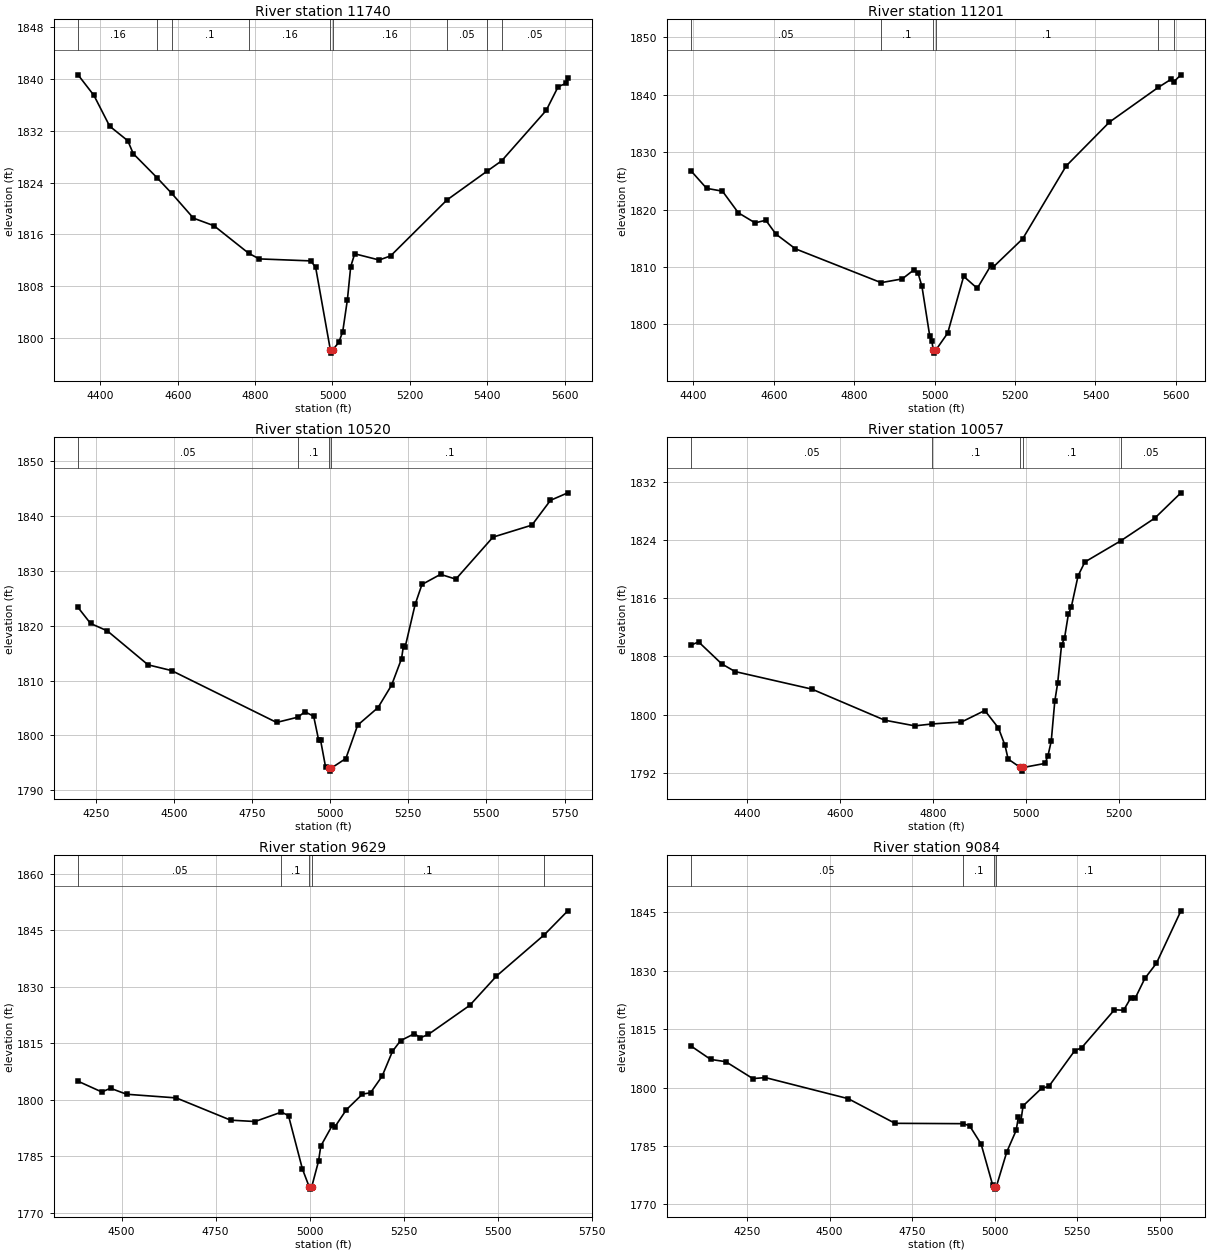
Type RM Length L Ch R = 1 ,11740   ,539,539,539
BEGIN DESCRIPTION:
TREIBS CREEK 26.0
END DESCRIPTION:
XS GIS Cut Line= 3
      2760098.97     10096692.06      2759605.96     10096601.79
      2758864.32     10096788.93
#Sta/Elev= 30
  4342.2 1840.67  4383.4 1837.48    4424 1832.73  4470.8 1830.48    4485 1828.48
  4546.3 1824.77  4584.1 1822.36  4640.5 1818.51  4693.6 1817.34  4783.1 1813.09
  4810.4 1812.21    4944  1811.9  4956.5 1810.89  4994.5 1798.14  4997.3 1797.64
  5000.5 1798.14  5016.2 1799.29  5026.5 1800.97  5038.6 1805.92  5047.1 1811.01
  5057.4    1813  5120.7 1812.04  5150.2 1812.67  5295.7 1821.31  5398.6 1825.73
  5437.5 1827.38  5552.5 1835.17  5583.4 1838.84  5603.2 1839.33  5608.3 1840.14
#Mann= 9 ,-1 , 0
  4342.2     .16       0  4546.3     .05       0  4584.1      .1       0
  4783.1     .16       0  4994.5     .07       0  5000.5     .16       0
  5295.7     .05       0  5398.6     .16       0  5437.5     .05       0
Bank Sta=4994.5,5000.5
XS Rating Curve= 0 ,0
Exp/Cntr=0.3,0.1

Type RM Length L Ch R = 1 ,11201   ,681,681,681
BEGIN DESCRIPTION:
TREIBS CREEK 25.0
END DESCRIPTION:
XS GIS Cut Line= 2
      2760161.52     10096358.73      2758987.86     10096032.33
#Sta/Elev= 30
  4394.4 1826.73  4432.8 1823.71  4472.2 1823.22  4511.7 1819.45  4553.3  1817.7
  4580.1 1818.15  4605.2 1815.74  4653.8 1813.17  4866.7 1807.28  4919.3 1807.93
  4947.7 1809.47  4958.7 1808.96  4968.4 1806.64  4987.8 1797.99    4993 1797.12
  4996.6  1795.5  4999.3    1795  5002.6  1795.5  5032.4 1798.48  5072.2 1808.38
    5106 1806.29  5140.3 1810.32  5145.5 1809.98  5219.1 1814.93    5327  1827.6
  5434.9 1835.26  5556.6 1841.32  5587.4 1842.68  5594.6 1842.26  5612.6 1843.49
#Mann= 6 ,-1 , 0
  4394.4     .05       0  4866.7      .1       0  4996.6     .07       0
  5002.6      .1       0  5556.6     .16       0  5594.6      .1       0
Bank Sta=4996.6,5002.6
XS Rating Curve= 0 ,0
Exp/Cntr=0.3,0.1

Type RM Length L Ch R = 1 ,10520   ,463,463,463
BEGIN DESCRIPTION:
TREIBS CREEK 23.0
END DESCRIPTION:
XS GIS Cut Line= 2
      2760342.03     10096046.21      2758974.04     10095282.36
#Sta/Elev= 30
  4193.7 1823.35  4233.7 1820.44  4287.4 1819.08  4417.6 1812.89    4493 1811.84
  4828.9 1802.38  4897.6 1803.35  4919.3 1804.33  4947.5 1803.51  4963.7  1799.1
  4969.4 1799.22  4985.4 1794.32  4996.5    1794  4999.3  1793.5  5002.5    1794
  5050.5  1795.8  5088.2 1801.88  5153.4 1805.09  5196.8 1809.18  5228.6    1814
  5234.5 1816.26  5240.2 1816.13  5272.2 1823.92  5293.9 1827.54  5353.3 1829.39
  5402.4 1828.52  5521.2 1836.18  5645.7 1838.37  5705.1 1842.89  5760.5 1844.26
#Mann= 4 ,-1 , 0
  4193.7     .05       0  4897.6      .1       0  4996.5     .07       0
  5002.5      .1       0
Bank Sta=4996.5,5002.5
XS Rating Curve= 0 ,0
Exp/Cntr=0.3,0.1

Type RM Length L Ch R = 1 ,10057   ,428,428,428
BEGIN DESCRIPTION:
TREIBS CREEK 22.0
END DESCRIPTION:
XS GIS Cut Line= 2
      2760321.24     10095643.46      2759474.19     10095018.58
#Sta/Elev= 30
  4280.6 1809.55  4296.5 1809.99  4346.2 1806.97    4375 1805.91    4540  1803.5
  4696.6 1799.23  4761.3 1798.45  4797.9 1798.71  4861.6 1798.98  4911.7 1800.56
    4941 1798.16  4955.1 1795.77  4961.8 1793.89  4988.1 1792.73  4990.8 1792.23
  4994.1 1792.73  5041.2 1793.29  5047.4 1794.33  5054.5 1796.36  5062.1 1801.85
  5068.3 1804.33  5076.7 1809.59  5082.9 1810.46  5091.3 1813.79  5097.6 1814.78
  5112.2 1819.08  5126.8 1820.97    5204 1823.88  5277.2    1827  5333.2 1830.47
#Mann= 5 ,-1 , 0
  4280.6     .05       0  4797.9      .1       0  4988.1     .07       0
  4994.1      .1       0    5204     .05       0
Bank Sta=4988.1,4994.1
XS Rating Curve= 0 ,0
Exp/Cntr=0.3,0.1

Type RM Length L Ch R = 1 ,9629    ,545,545,545
BEGIN DESCRIPTION:
TREIBS CREEK 21.0
END DESCRIPTION:
XS GIS Cut Line= 2
      2760522.63     10095205.96       2759404.6     10094539.31
#Sta/Elev= 30
  4384.3 1804.92  4447.4 1802.07  4470.6 1803.05  4513.5 1801.46  4645.3 1800.49
  4789.9 1794.58  4854.9 1794.22  4924.9 1796.73  4943.7 1795.77  4980.7 1781.61
  4999.1 1776.77  5001.8 1776.27  5005.1 1776.77  5023.5 1783.69  5029.5  1787.7
  5060.5 1793.28  5066.3  1792.7  5097.4 1797.34  5140.3  1801.5  5161.7 1801.85
  5192.5 1806.25  5220.1 1812.87  5241.5 1815.69  5278.5 1817.55    5294 1816.45
  5315.4 1817.35  5425.4 1825.06  5496.5 1832.84  5623.9 1843.83    5686 1850.16
#Mann= 5 ,-1 , 0
  4384.3     .05       0  4924.9      .1       0  4999.1     .07       0
  5005.1      .1       0  5623.9     .05       0
Bank Sta=4999.1,5005.1
XS Rating Curve= 0 ,0
Exp/Cntr=0.3,0.1

Type RM Length L Ch R = 1 ,9084    ,508,508,508
BEGIN DESCRIPTION:
TREIBS CREEK 20.0
END DESCRIPTION:
XS GIS Cut Line= 3
      2760668.46     10095219.85      2760355.96     10094504.57
      2759828.14     10094039.26
#Sta/Elev= 30
  4080.6 1810.64  4139.7 1807.22  4185.5 1806.64  4267.6 1802.29  4305.5 1802.55
  4556.5 1797.13  4698.4 1790.79  4904.2  1790.7  4924.1  1790.2  4959.3 1785.45
  4994.4 1774.87  4998.9 1774.37  5001.7 1773.87  5004.9 1774.37  5037.1 1783.45
  5065.5 1788.98  5072.2  1792.4  5079.7 1791.34  5086.4 1795.27  5143.3 1799.86
  5164.4 1800.27  5242.9 1809.46  5263.8 1810.21  5363.4 1819.99  5391.1 1819.86
  5412.7 1823.01  5426.9 1823.08  5455.4 1828.04  5490.5 1831.94  5564.8 1845.43
#Mann= 4 ,-1 , 0
  4080.6     .05       0  4904.2      .1       0  4998.9     .07       0
  5004.9      .1       0
Bank Sta=4998.9,5004.9
XS Rating Curve= 0 ,0
Exp/Cntr=0.3,0.1