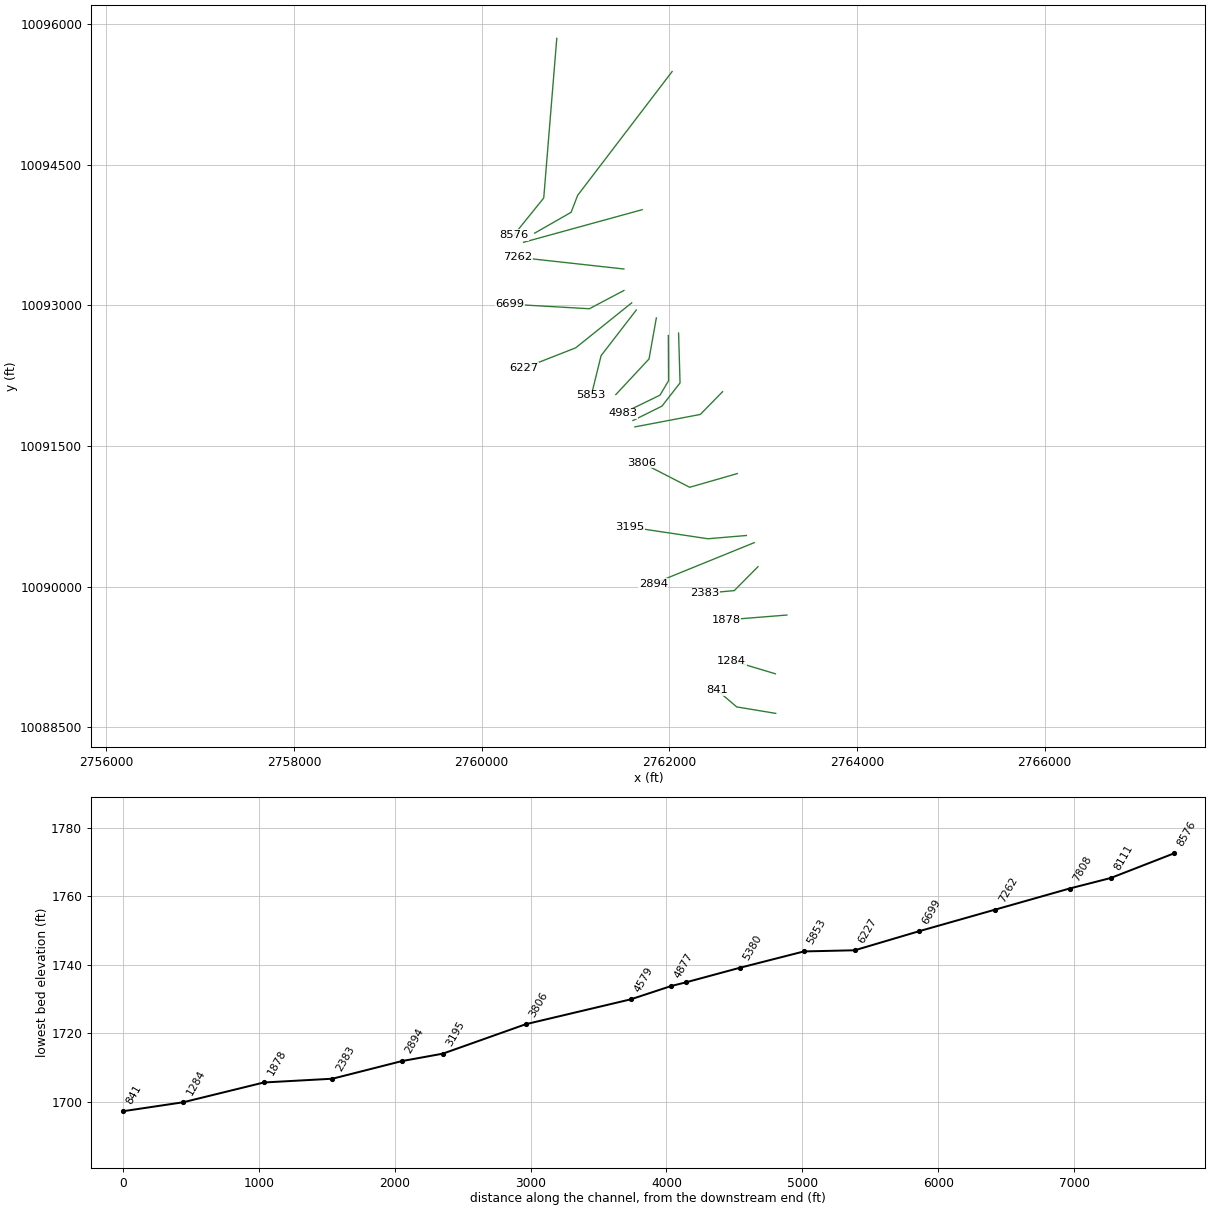
HEC-RAS study TREIBS CREEK.prj: TREIBS CREEK Base Level Engineering

--- TREIBS CREEK.g01 (geometry) --- (continued)

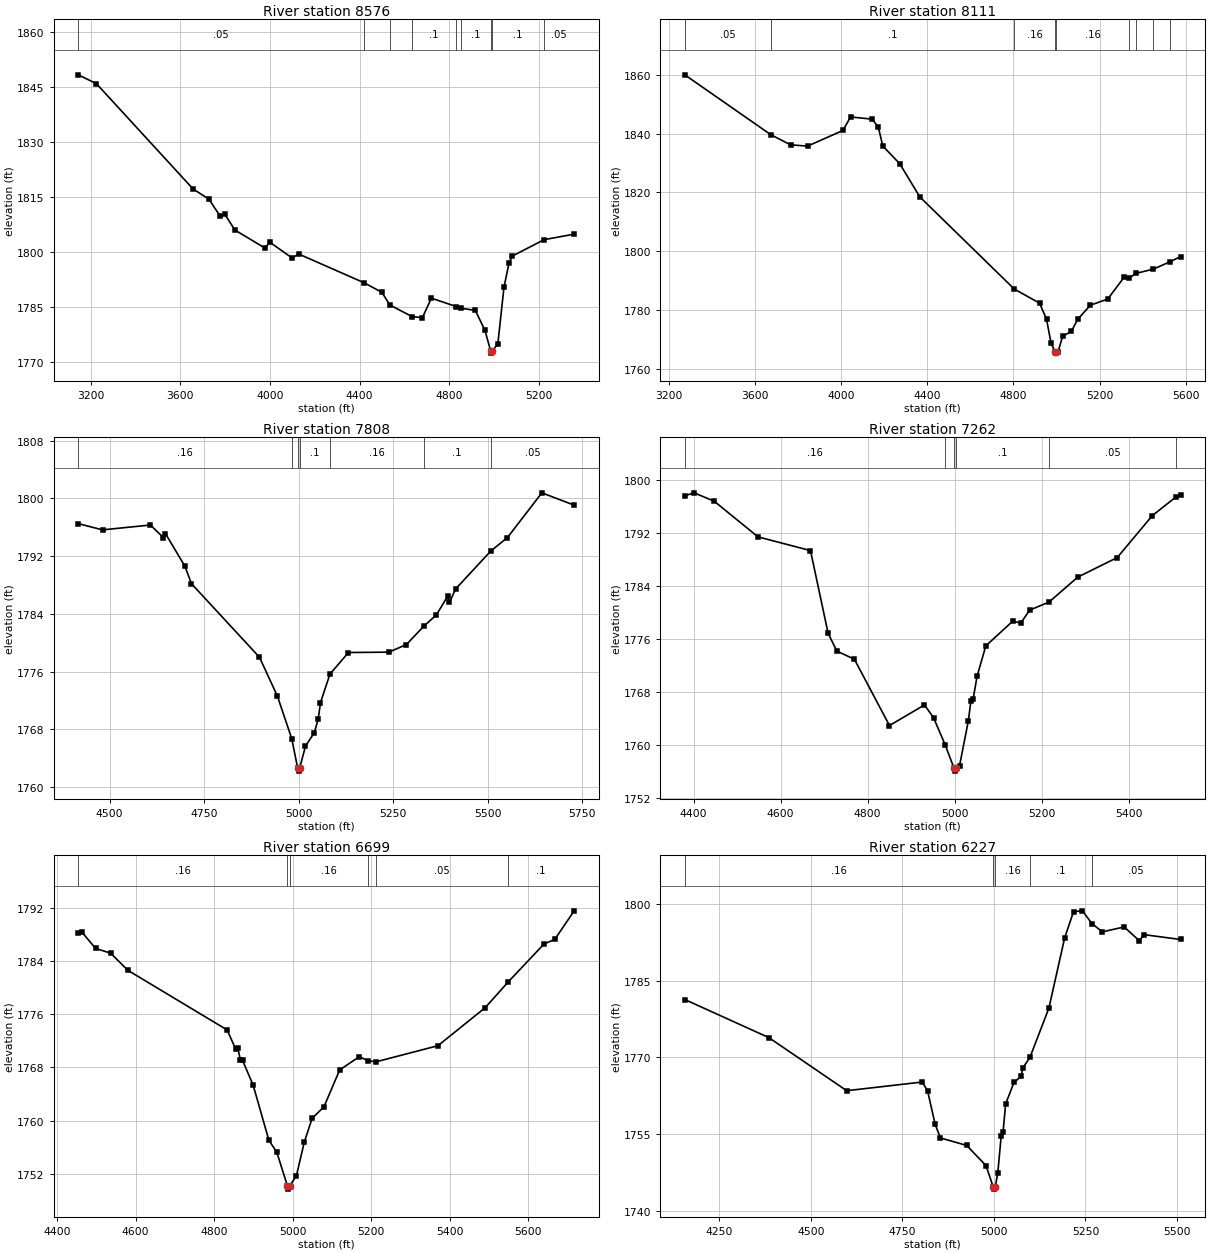
Type RM Length L Ch R = 1 ,8576    ,465,465,465
BEGIN DESCRIPTION:
TREIBS CREEK 19.0
END DESCRIPTION:
XS GIS Cut Line= 3
       2760800.4     10095844.87      2760661.51     10094143.46
      2760343.22     10093749.04
#Sta/Elev= 30
  3144.5 1848.23  3225.3 1845.82  3657.3 1817.14  3727.6 1814.38  3777.7 1809.78
  3797.8 1810.35  3843.6 1805.99  3978.4 1801.06  3998.5 1802.71  4098.8  1798.4
  4128.9 1799.45  4421.2 1791.62  4500.1 1789.03  4535.2  1785.6  4634.2 1782.45
  4680.7 1782.13  4720.9 1787.45  4832.2 1785.16  4852.6 1784.71    4917 1784.12
  4960.2 1778.68    4986 1772.99  4988.7 1772.49    4992 1772.99  5017.7 1775.07
    5045 1790.39  5067.3 1796.93  5081.7 1798.89  5224.3 1803.37  5358.4 1804.87
#Mann= 9 ,-1 , 0
  3144.5     .05       0  4421.2      .1       0  4535.2     .05       0
  4634.2      .1       0  4832.2     .05       0  4852.6      .1       0
    4986     .07       0    4992      .1       0  5224.3     .05       0
Bank Sta=4986,4992
XS Rating Curve= 0 ,0
Exp/Cntr=0.3,0.1

Type RM Length L Ch R = 1 ,8111    ,303,303,303
BEGIN DESCRIPTION:
TREIBS CREEK 18.0
END DESCRIPTION:
XS GIS Cut Line= 4
      2762029.59      10095490.7      2761022.62     10094171.23
      2760953.18     10093990.68      2760564.52     10093768.59
#Sta/Elev= 30
  3275.5 1859.98  3674.8  1839.6  3766.1 1836.17    3845 1835.72  4009.2 1841.05
  4044.6 1845.65  4144.3 1844.91  4173.4 1842.23  4194.2 1835.78  4273.2 1829.71
  4366.1 1818.45  4804.6 1787.09  4921.7 1782.31  4954.1 1776.83  4975.5 1768.58
  4993.9  1765.8  4996.7  1765.3  4999.9  1765.8  5007.6 1765.82  5029.1 1771.03
  5069.4 1772.71  5099.4 1776.87  5157.9 1781.61  5238.5 1783.72  5313.4 1791.05
    5339 1790.93  5369.5 1792.44  5449.9 1793.88  5526.8 1796.37  5576.4 1798.15
#Mann= 9 ,-1 , 0
  3275.5     .05       0  3674.8      .1       0  4804.6     .16       0
  4993.9     .07       0  4999.9     .16       0    5339      .1       0
  5369.5     .05       0  5449.9      .1       0  5526.8     .05       0
Bank Sta=4993.9,4999.9
XS Rating Curve= 0 ,0
Exp/Cntr=0.3,0.1

Type RM Length L Ch R = 1 ,7808    ,546,546,546
BEGIN DESCRIPTION:
TREIBS CREEK 17.0
END DESCRIPTION:
XS GIS Cut Line= 2
      2761710.12     10094018.46      2760446.25     10093671.24
#Sta/Elev= 30
  4417.6 1796.51  4481.5 1795.65  4608.2 1796.32  4642.7 1794.57  4647.9 1795.14
  4699.3 1790.61  4716.7 1788.19  4896.4 1778.01    4944  1772.6  4981.7 1766.73
  4997.1 1762.73  4999.8 1762.23  5003.1 1762.73  5018.1 1765.69  5041.5 1767.57
  5051.9  1769.5  5057.7 1771.71  5082.8 1775.68  5131.7 1778.66  5238.6 1778.71
    5285 1779.77  5330.5 1782.29  5364.2 1783.87  5393.5 1786.43  5398.7  1785.6
  5414.9 1787.46  5507.6  1792.7    5552 1794.59    5643 1800.78  5728.3 1799.07
#Mann= 7 ,-1 , 0
  4417.6     .16       0  4981.7      .1       0  4997.1     .07       0
  5003.1      .1       0  5082.8     .16       0  5330.5      .1       0
  5507.6     .05       0
Bank Sta=4997.1,5003.1
XS Rating Curve= 0 ,0
Exp/Cntr=0.3,0.1

Type RM Length L Ch R = 1 ,7262    ,563,563,563
BEGIN DESCRIPTION:
TREIBS CREEK 16.0
END DESCRIPTION:
XS GIS Cut Line= 2
      2761515.68     10093386.51      2760383.76     10093511.51
#Sta/Elev= 30
    4380 1797.65  4401.3 1798.09  4447.6 1796.82  4548.2 1791.44  4668.7 1789.37
  4709.2 1776.87  4729.3  1774.2  4769.6 1772.96  4850.1 1762.96  4930.5 1766.07
  4951.3 1764.15  4978.1 1760.03    4998 1756.58  5000.7 1756.08    5004 1756.58
    5011 1756.89  5031.1 1763.62  5037.1 1766.65  5042.1 1766.91  5051.3  1770.4
  5071.4 1774.99  5132.9  1778.7  5151.9 1778.44    5172 1780.38  5216.4  1781.6
  5282.7 1785.37  5373.2 1788.32  5453.7 1794.64  5508.2 1797.48  5518.8 1797.83
#Mann= 6 ,-1 , 0
    4380     .16       0  4978.1      .1       0    4998     .07       0
    5004      .1       0  5216.4     .05       0  5508.2      .1       0
Bank Sta=4998,5004
XS Rating Curve= 0 ,0
Exp/Cntr=0.3,0.1

Type RM Length L Ch R = 1 ,6699    ,472,472,472
BEGIN DESCRIPTION:
TREIBS CREEK 15.0
END DESCRIPTION:
XS GIS Cut Line= 3
      2761515.71     10093157.36      2761147.62      10092962.9
      2760301.91     10093011.42
#Sta/Elev= 30
  4454.2 1788.22  4462.4 1788.39    4498 1785.88  4536.4 1785.17  4580.4 1782.59
  4833.3 1773.64  4855.3 1770.74    4861 1770.86  4867.2 1769.07  4872.6 1769.07
  4899.7 1765.34  4939.8 1757.06  4959.8  1755.3  4986.9 1750.24  4989.6 1749.74
  4992.9 1750.24  5009.9 1751.75  5029.9 1756.78  5049.9 1760.37    5080 1762.09
  5120.1 1767.63  5170.1 1769.62  5191.7 1769.04  5211.9 1768.84  5370.5 1771.27
  5490.7 1776.97  5549.6 1780.85  5640.9 1786.55  5668.3 1787.24  5717.6 1791.52
#Mann= 6 ,-1 , 0
  4454.2     .16       0  4986.9     .07       0  4992.9     .16       0
  5191.7      .1       0  5211.9     .05       0  5549.6      .1       0
Bank Sta=4986.9,4992.9
XS Rating Curve= 0 ,0
Exp/Cntr=0.3,0.1

Type RM Length L Ch R = 1 ,6227    ,374,374,374
BEGIN DESCRIPTION:
TREIBS CREEK 14.0
END DESCRIPTION:
XS GIS Cut Line= 3
        2761599.     10093025.39      2761001.79     10092546.23
      2760453.28     10092330.99
#Sta/Elev= 30
  4155.2 1781.29  4384.9 1773.84  4597.7 1763.45  4804.2 1765.15  4818.6 1763.41
  4839.4 1756.85  4853.8  1754.2  4925.3 1752.75  4978.2  1748.8  4997.6 1744.69
  5000.3 1744.19  5003.6 1744.69  5010.4 1747.28  5019.6 1754.49    5025 1755.45
  5031.9 1760.85  5054.8 1765.08  5073.9 1766.24  5079.2 1767.93  5098.3 1769.97
    5150 1779.58  5193.1 1793.32  5217.5  1798.5  5241.9 1798.65  5267.5 1796.16
  5296.2 1794.54  5355.8 1795.49  5397.1 1792.82    5410 1793.99  5510.1 1793.04
#Mann= 5 ,-1 , 0
  4155.2     .16       0  4997.6     .07       0  5003.6     .16       0
  5098.3      .1       0  5267.5     .05       0
Bank Sta=4997.6,5003.6
XS Rating Curve= 0 ,0
Exp/Cntr=0.3,0.1

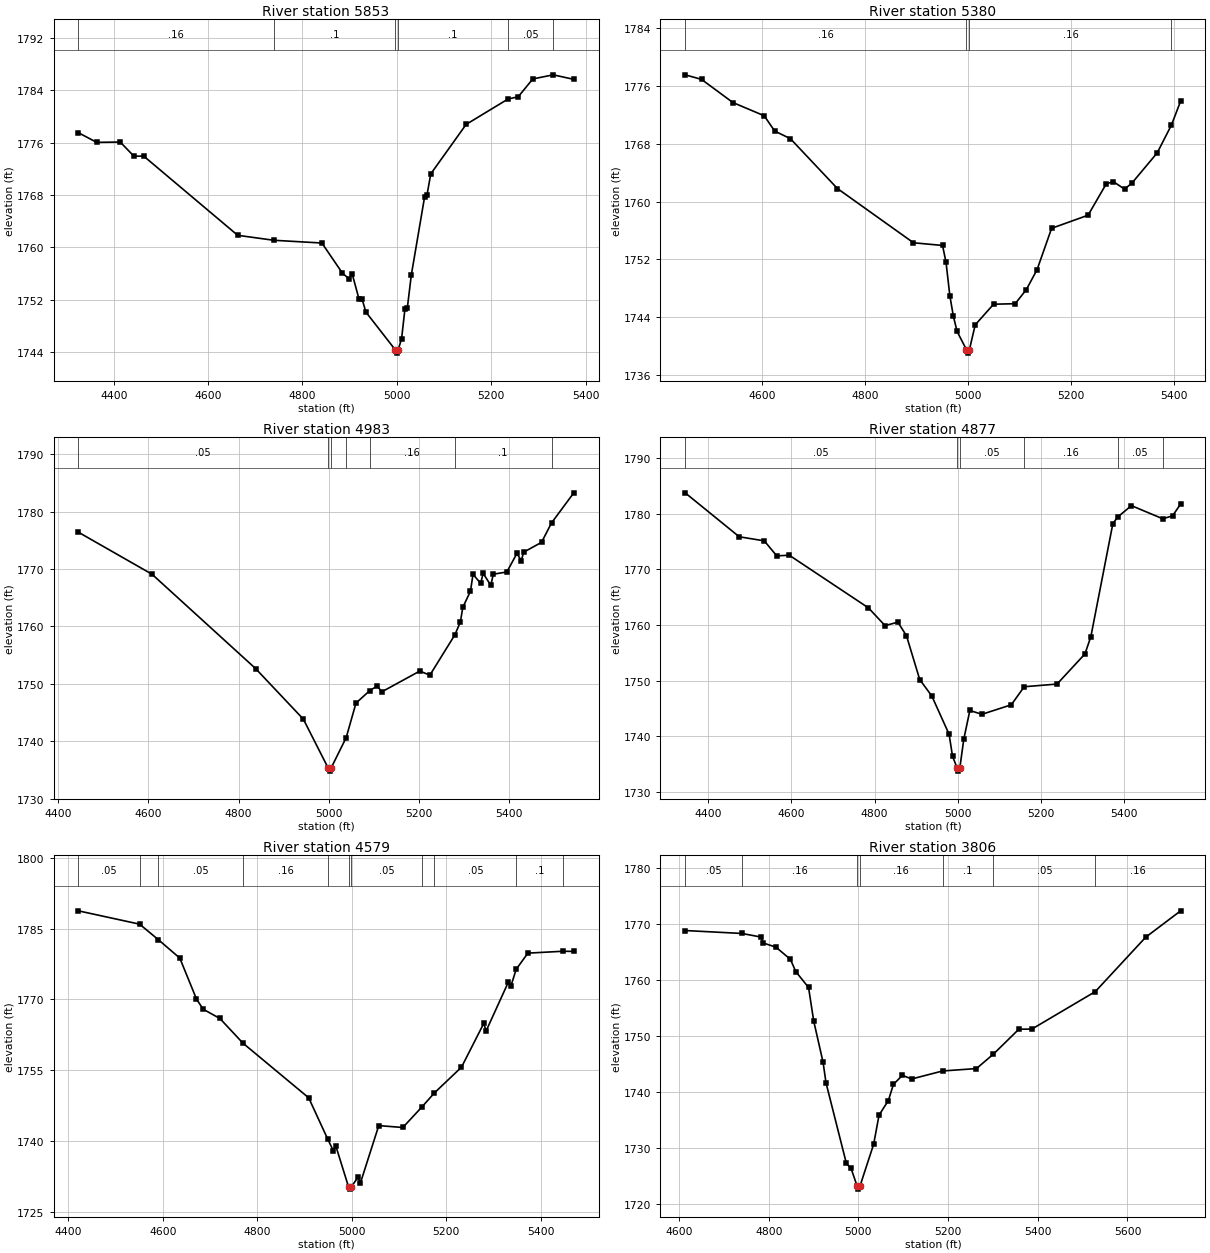
Type RM Length L Ch R = 1 ,5853    ,473,473,473
BEGIN DESCRIPTION:
TREIBS CREEK 13.0
END DESCRIPTION:
XS GIS Cut Line= 3
      2761647.65     10092949.04      2761272.62      10092462.9
      2761168.46      10092039.3
#Sta/Elev= 30
  4324.9 1777.51  4363.8 1776.03  4413.7 1776.08  4442.7 1773.92  4463.5 1773.93
  4662.7 1761.84  4739.2 1761.08  4841.2 1760.66  4884.7 1756.06  4899.2 1755.16
  4905.5 1755.92    4920 1752.06  4926.3 1752.12  4934.5 1750.11  4996.8 1744.35
  4999.6 1743.85  5002.8 1744.35  5010.1 1746.05  5017.2  1750.6  5022.3 1750.77
  5030.7 1755.77  5058.7 1767.63  5063.9 1767.97  5071.9 1771.21  5146.9 1778.77
  5235.8 1782.65  5257.3 1782.99  5288.2 1785.71  5331.4 1786.34  5375.1 1785.65
#Mann= 6 ,-1 , 0
  4324.9     .16       0  4739.2      .1       0  4996.8     .07       0
  5002.8      .1       0  5235.8     .05       0  5331.4      .1       0
Bank Sta=4996.8,5002.8
XS Rating Curve= 0 ,0
Exp/Cntr=0.3,0.1

Type RM Length L Ch R = 1 ,5380    ,397,397,397
BEGIN DESCRIPTION:
TREIBS CREEK 12.0
END DESCRIPTION:
XS GIS Cut Line= 3
       2761861.6     10092865.07      2761783.47     10092427.56
      2761429.95     10092048.04
#Sta/Elev= 30
  4450.4 1777.52  4482.2 1776.89  4543.2 1773.69  4604.1 1771.86  4624.4 1769.75
  4654.9  1768.7  4746.3 1761.81  4894.2 1754.31  4950.7 1753.94  4957.5 1751.59
  4964.9 1746.99  4971.7 1744.17    4979 1742.05    4997 1739.56  4999.8 1739.06
    5003 1739.56  5014.2 1742.97  5049.9 1745.82  5091.9 1745.89  5113.4 1747.82
  5134.4 1750.59  5162.7 1756.31  5233.6 1758.12  5269.1 1762.48  5282.9 1762.75
  5304.4 1761.73  5318.6 1762.54  5367.9 1766.73  5395.6 1770.58  5413.5 1773.89
#Mann= 4 ,-1 , 0
  4450.4     .16       0    4997     .07       0    5003     .16       0
  5395.6      .1       0
Bank Sta=4997,5003
XS Rating Curve= 0 ,0
Exp/Cntr=0.3,0.1

Type RM Length L Ch R = 1 ,4983    ,106,106,106
BEGIN DESCRIPTION:
Mapping XS cf7ab1cb
END DESCRIPTION:
XS GIS Cut Line= 4
       2761989.2     10092677.55      2761991.81     10092195.79
      2761900.66     10092042.14       2761504.8     10091849.42
#Sta/Elev= 30
  4444.1 1776.41  4607.9 1769.08  4837.9 1752.66    4944 1743.85  4999.4  1735.3
  5002.2  1734.8  5005.4  1735.3  5039.2 1740.64  5060.9 1746.64  5091.7 1748.83
  5108.4 1749.63  5118.1  1748.6  5202.6 1752.22  5225.1 1751.51  5280.5 1758.52
  5292.8 1760.76  5298.3 1763.33  5315.3 1766.14  5320.9 1769.08  5337.9 1767.49
  5343.4 1769.24  5360.4 1767.16    5366 1769.09  5396.1 1769.48  5418.4  1772.7
    5428 1771.46  5433.6 1772.93  5473.1 1774.64  5495.5 1778.04  5544.8 1783.26
#Mann= 7 ,-1 , 0
  4444.1     .05       0  4999.4     .04       0  5005.4     .05       0
  5039.2      .1       0  5091.7     .16       0  5280.5      .1       0
  5495.5     .05       0
Bank Sta=4999.4,5005.4
XS Rating Curve= 0 ,0
Exp/Cntr=0.3,0.1

Type RM Length L Ch R = 1 ,4877    ,298,298,298
BEGIN DESCRIPTION:
TREIBS CREEK 11.0
END DESCRIPTION:
XS GIS Cut Line= 4
      2762098.58     10092703.63       2762114.2     10092172.35
      2761921.49     10091924.96      2761612.58     10091771.79
#Sta/Elev= 30
  4345.3 1783.72  4475.2 1775.83  4535.3  1775.1  4565.3  1772.4  4595.3 1772.52
  4785.4 1763.07  4825.4 1759.88  4856.1  1760.5  4876.8 1758.06  4908.6  1750.2
  4937.6 1747.25  4979.2 1740.36  4987.4 1736.42  4998.8 1734.26  5001.6 1733.76
  5004.8 1734.26  5014.5 1739.53    5029 1744.65  5057.9 1743.96  5128.6 1745.67
  5159.5 1748.91  5238.4 1749.39  5305.4  1754.8  5319.6 1757.91  5372.4 1778.19
  5384.2 1779.39    5417 1781.42    5492 1779.07  5515.7 1779.58  5535.2 1781.72
#Mann= 6 ,-1 , 0
  4345.3     .05       0  4998.8     .04       0  5004.8     .05       0
  5159.5     .16       0  5384.2     .05       0    5492      .1       0
Bank Sta=4998.8,5004.8
XS Rating Curve= 0 ,0
Exp/Cntr=0.3,0.1

Type RM Length L Ch R = 1 ,4579    ,773,773,773
BEGIN DESCRIPTION:
TREIBS CREEK 10.0
END DESCRIPTION:
XS GIS Cut Line= 3
      2762567.32     10092078.59      2762330.35     10091836.41
      2761632.99     10091703.71
#Sta/Elev= 30
    4421 1788.74  4550.7 1785.92  4590.2 1782.65  4635.8 1778.74  4671.1 1770.08
  4685.3 1767.92  4720.7 1765.96  4769.7 1760.72  4908.6 1749.18  4949.2 1740.37
  4960.8 1737.98  4965.9 1739.03  4992.9 1730.36  4995.6 1729.86  4998.9 1730.36
    5013 1732.37  5018.1 1731.17  5056.9  1743.3  5107.8  1742.9  5148.5 1747.27
  5174.8 1750.23    5232 1755.66  5279.1 1764.91  5284.2 1763.34  5331.3 1773.68
  5336.4 1772.77  5347.8 1776.37  5372.5 1779.79  5447.4 1780.19  5469.7 1780.15
#Mann= 11 ,-1 , 0
    4421     .05       0  4550.7      .1       0  4590.2     .05       0
  4769.7     .16       0  4949.2     .05       0  4992.9     .04       0
  4998.9     .05       0  5148.5     .16       0  5174.8     .05       0
  5347.8      .1       0  5447.4     .05       0
Bank Sta=4992.9,4998.9
XS Rating Curve= 0 ,0
Exp/Cntr=0.3,0.1

Type RM Length L Ch R = 1 ,3806    ,611,611,611
BEGIN DESCRIPTION:
TREIBS CREEK 8.0
END DESCRIPTION:
XS GIS Cut Line= 3
        2762724.     10091205.95      2762217.07     10091060.12
      2761703.33     10091323.93
#Sta/Elev= 30
  4613.6 1768.77  4740.1 1768.25  4782.5 1767.61  4787.7 1766.55  4816.2 1765.79
  4848.3 1763.63  4860.3 1761.44  4888.8  1758.6  4900.3  1752.6  4921.1 1745.27
  4927.7 1741.58  4973.1 1727.19  4983.6 1726.29  4997.3 1723.09    5000 1722.59
  5003.3 1723.09    5034 1730.62    5046 1735.81  5066.8 1738.41  5078.1  1741.3
    5098 1742.91  5118.8 1742.26  5187.7 1743.69  5263.2 1744.12  5301.2 1746.71
  5357.8 1751.15  5386.8 1751.17  5528.2 1757.86  5640.7 1767.58  5718.6 1772.29
#Mann= 7 ,-1 , 0
  4613.6     .05       0  4740.1     .16       0  4997.3     .07       0
  5003.3     .16       0  5187.7      .1       0  5301.2     .05       0
  5528.2     .16       0
Bank Sta=4997.3,5003.3
XS Rating Curve= 0 ,0
Exp/Cntr=0.3,0.1

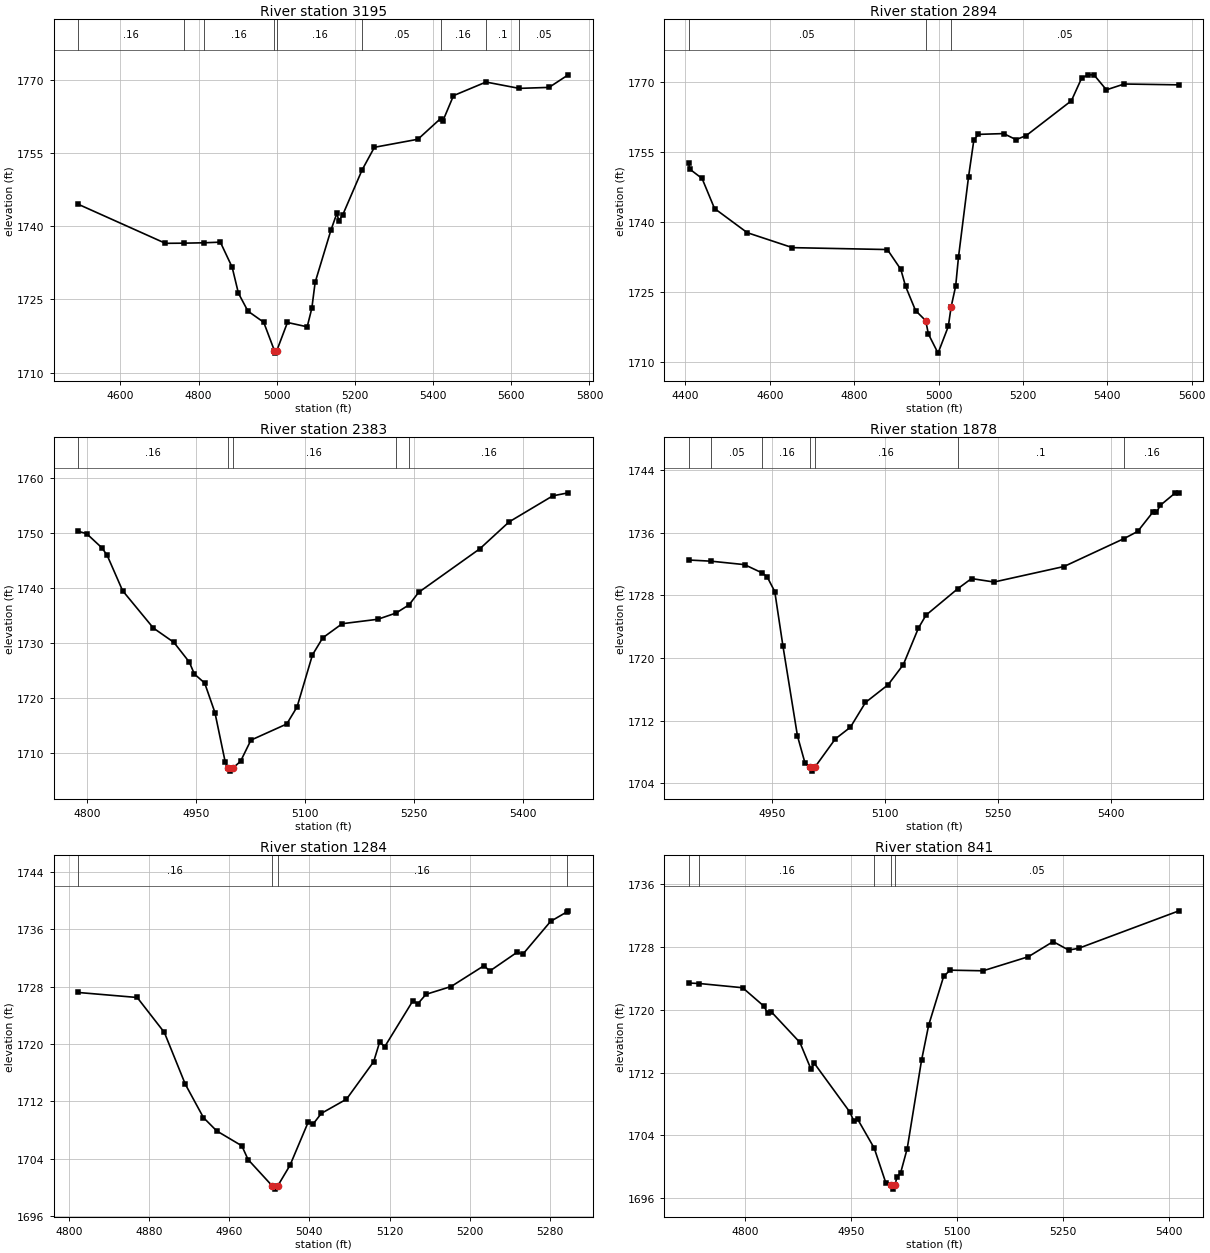
Type RM Length L Ch R = 1 ,3195    ,301,301,301
BEGIN DESCRIPTION:
TREIBS CREEK 7.0
END DESCRIPTION:
XS GIS Cut Line= 3
      2762821.21     10090546.23      2762411.51     10090511.51
       2761578.2     10090636.51
#Sta/Elev= 30
  4491.9 1744.54  4715.4 1736.51  4761.9 1736.54  4814.4 1736.62  4855.9 1736.75
  4886.1  1731.6  4902.1 1726.27  4926.4  1722.6  4966.8 1720.31  4994.2 1714.48
  4996.9 1713.98  5000.2 1714.48  5027.5 1720.27    5078 1719.38  5089.9 1723.21
  5098.3 1728.49  5138.7 1739.21  5153.9 1742.66    5159 1741.13  5169.1 1742.38
  5218.4 1751.56  5249.9 1756.21  5361.2 1757.86  5419.3 1762.11  5425.3 1761.67
  5452.2 1766.81  5535.4  1769.6  5620.2  1768.3  5696.6  1768.5  5745.7 1771.08
#Mann= 9 ,-1 , 0
  4491.9     .16       0  4761.9     .05       0  4814.4     .16       0
  4994.2     .07       0  5000.2     .16       0  5218.4     .05       0
  5419.3     .16       0  5535.4      .1       0  5620.2     .05       0
Bank Sta=4994.2,5000.2
XS Rating Curve= 0 ,0
Exp/Cntr=0.3,0.1

Type RM Length L Ch R = 1 ,2894    ,511,511,511
BEGIN DESCRIPTION:
TREIBS CREEK 6.0
END DESCRIPTION:
XS GIS Cut Line= 2
      2762904.54     10090469.83      2761828.15     10090032.33
#Sta/Elev= 30
  4408.1 1752.51  4410.1 1751.32  4439.6 1749.29  4469.1 1742.85  4546.7 1737.66
  4653.8 1734.45  4878.8 1734.04  4910.7 1729.78    4922 1726.13  4945.6 1720.95
  4969.7 1718.78    4976 1715.92  4998.9 1711.81  5023.2 1717.53  5029.9 1721.73
  5040.7  1726.2  5047.3 1732.36  5071.3 1749.71  5083.9  1757.6  5094.7 1758.76
  5154.4 1758.93  5183.8 1757.63  5207.9  1758.5    5315 1765.98  5339.1 1770.79
  5353.8 1771.54  5368.5 1771.53    5398 1768.32  5440.1 1769.57    5570 1769.39
#Mann= 3 , 0 , 0
  4408.1     .05       0  4969.7     .03       0  5029.9     .05       0
Bank Sta=4969.7,5029.9
XS Rating Curve= 0 ,0
Exp/Cntr=0.3,0.1

Type RM Length L Ch R = 1 ,2383    ,505,505,505
BEGIN DESCRIPTION:
TREIBS CREEK 5.0
END DESCRIPTION:
XS GIS Cut Line= 3
      2762944.95     10090214.03      2762692.33     10089958.81
      2762377.23     10089930.16
#Sta/Elev= 30
  4787.4 1750.32  4799.3 1749.87  4820.5 1747.27  4827.6 1745.91  4848.8  1739.5
  4891.2  1732.7  4919.5 1730.09  4940.7 1726.51  4947.7 1724.33  4961.9 1722.69
    4976 1717.33  4990.2 1708.32  4994.3 1707.16    4997 1706.66  5000.3 1707.16
  5011.4 1708.46  5025.6  1712.3    5075 1715.24  5089.2 1718.34  5110.4 1727.81
  5124.6 1730.92  5151.4 1733.49  5200.6  1734.3  5225.7 1735.44  5243.6 1736.93
  5256.8  1739.2  5341.2 1747.14  5381.3 1752.01  5441.6 1756.76  5462.9 1757.31
#Mann= 5 ,-1 , 0
  4787.4     .16       0  4994.3     .07       0  5000.3     .16       0
  5225.7      .1       0  5243.6     .16       0
Bank Sta=4994.3,5000.3
XS Rating Curve= 0 ,0
Exp/Cntr=0.3,0.1

Type RM Length L Ch R = 1 ,1878    ,594,594,594
BEGIN DESCRIPTION:
TREIBS CREEK 4.0
END DESCRIPTION:
XS GIS Cut Line= 2
      2763252.24     10089698.39      2762603.82     10089646.31
#Sta/Elev= 30
  4839.2 1732.52  4868.9 1732.37  4913.2 1731.93    4937 1730.85  4943.3 1730.35
  4953.3 1728.49  4964.1 1721.56  4983.4 1710.06  4993.5 1706.56  5000.5 1706.06
  5003.2 1705.56  5006.5 1706.06  5033.6 1709.67  5053.7 1711.17  5073.7 1714.33
  5103.8  1716.6  5123.9 1719.16  5143.9 1723.82    5154 1725.48  5196.1 1728.85
  5214.4 1730.15  5244.3 1729.71  5337.1 1731.69  5416.9 1735.26  5434.9 1736.17
  5454.7 1738.59  5459.7  1738.6    5465 1739.51  5484.9  1741.1  5489.7  1741.1
#Mann= 7 ,-1 , 0
  4839.2      .1       0  4868.9     .05       0    4937     .16       0
  5000.5     .07       0  5006.5     .16       0  5196.1      .1       0
  5416.9     .16       0
Bank Sta=5000.5,5006.5
XS Rating Curve= 0 ,0
Exp/Cntr=0.3,0.1

Type RM Length L Ch R = 1 ,1284    ,443,443,443
BEGIN DESCRIPTION:
TREIBS CREEK 3.0
END DESCRIPTION:
XS GIS Cut Line= 2
      2763130.91     10089072.08      2762662.53     10089212.59
#Sta/Elev= 30
  4809.2 1727.17  4868.2 1726.47  4895.3  1721.6  4916.2 1714.39  4934.3 1709.74
  4947.5 1707.89  4972.6 1705.81  4978.8  1703.9  5002.6 1700.28  5005.4 1699.78
  5008.6 1700.28  5020.6 1703.09  5038.7 1709.08  5043.9 1708.88  5051.9 1710.33
    5077 1712.31  5104.1 1717.53    5110 1720.23  5115.2 1719.63  5143.1 1725.98
  5148.3 1725.62  5156.3 1726.91  5181.4    1728  5214.4 1730.92  5219.7 1730.13
  5247.5  1732.8  5252.7 1732.46  5280.6 1737.07  5296.6 1738.37  5298.2 1738.54
#Mann= 4 ,-1 , 0
  4809.2     .16       0  5002.6     .07       0  5008.6     .16       0
  5296.6     .05       0
Bank Sta=5002.6,5008.6
XS Rating Curve= 0 ,0
Exp/Cntr=0.3,0.1

Type RM Length L Ch R = 1 ,841     ,506,506,506
BEGIN DESCRIPTION:
TREIBS CREEK 2.0
END DESCRIPTION:
XS GIS Cut Line= 3
      2763133.71     10088650.41      2762718.37     10088719.23
      2762510.05     10088896.29
#Sta/Elev= 30
  4719.8 1723.42  4734.6 1723.36  4796.1 1722.82  4826.5 1720.45  4831.7 1719.55
  4836.8 1719.74  4877.2 1715.85  4892.7 1712.49  4897.8 1713.17  4948.1 1706.96
  4953.7  1705.8  4958.8  1706.1  4982.5 1702.38  4998.8 1697.99  5005.9 1697.66
  5008.7 1697.16  5011.9 1697.66  5014.7 1698.74  5019.8  1699.2  5029.2 1702.32
  5049.5 1713.57  5059.6 1718.05  5080.8 1724.26    5090 1725.06  5136.7 1724.98
  5200.8 1726.77  5235.9  1728.7  5257.9 1727.62  5271.9 1727.84  5414.2 1732.62
#Mann= 5 ,-1 , 0
  4719.8      .1       0  4734.6     .16       0  4982.5     .05       0
  5005.9    .035       0  5011.9     .05       0
Bank Sta=5005.9,5011.9
XS Rating Curve= 0 ,0
Exp/Cntr=0.3,0.1