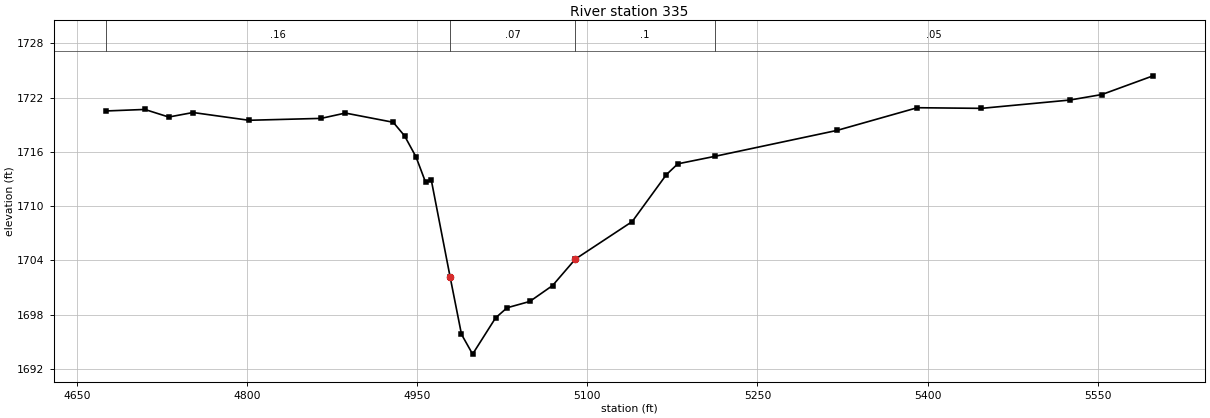
HEC-RAS study TREIBS CREEK.prj: TREIBS CREEK Base Level Engineering

--- TREIBS CREEK.g01 (geometry) --- (continued)

Type RM Length L Ch R = 1 ,335     ,0,0,0
BEGIN DESCRIPTION:
TREIBS CREEK 1.0
END DESCRIPTION:
XS GIS Cut Line= 4
      2763230.96     10088379.58      2763072.54     10088214.02
      2762762.64     10088240.06      2762489.18     10088508.31
#Sta/Elev= 30
  4675.6 1720.53  4709.9  1720.7    4731 1719.86  4752.4 1720.36  4801.7  1719.5
  4865.3 1719.71  4886.7  1720.3  4928.9 1719.28  4938.9 1717.78    4949 1715.45
  4957.5 1712.62  4962.5 1712.87  4979.1 1702.14  4989.1 1695.81  4998.9 1693.62
  5019.2 1697.64  5029.3 1698.75  5049.3 1699.45  5069.4 1701.21  5089.5 1704.14
  5139.6 1708.29  5169.7 1713.48  5179.8 1714.68  5212.5 1715.51  5320.2 1718.38
  5390.9 1720.89  5447.5 1720.82  5525.4 1721.74  5553.7 1722.35  5598.8 1724.42
#Mann= 4 ,-1 , 0
  4675.6     .16       0  4979.1     .07       0  5089.5      .1       0
  5212.5     .05       0
Bank Sta=4979.1,5089.5
XS Rating Curve= 0 ,0
Exp/Cntr=0.3,0.1

Chan Stop Cuts=-1
Use User Specified Reach Order=0
Composite Channel Slope=5