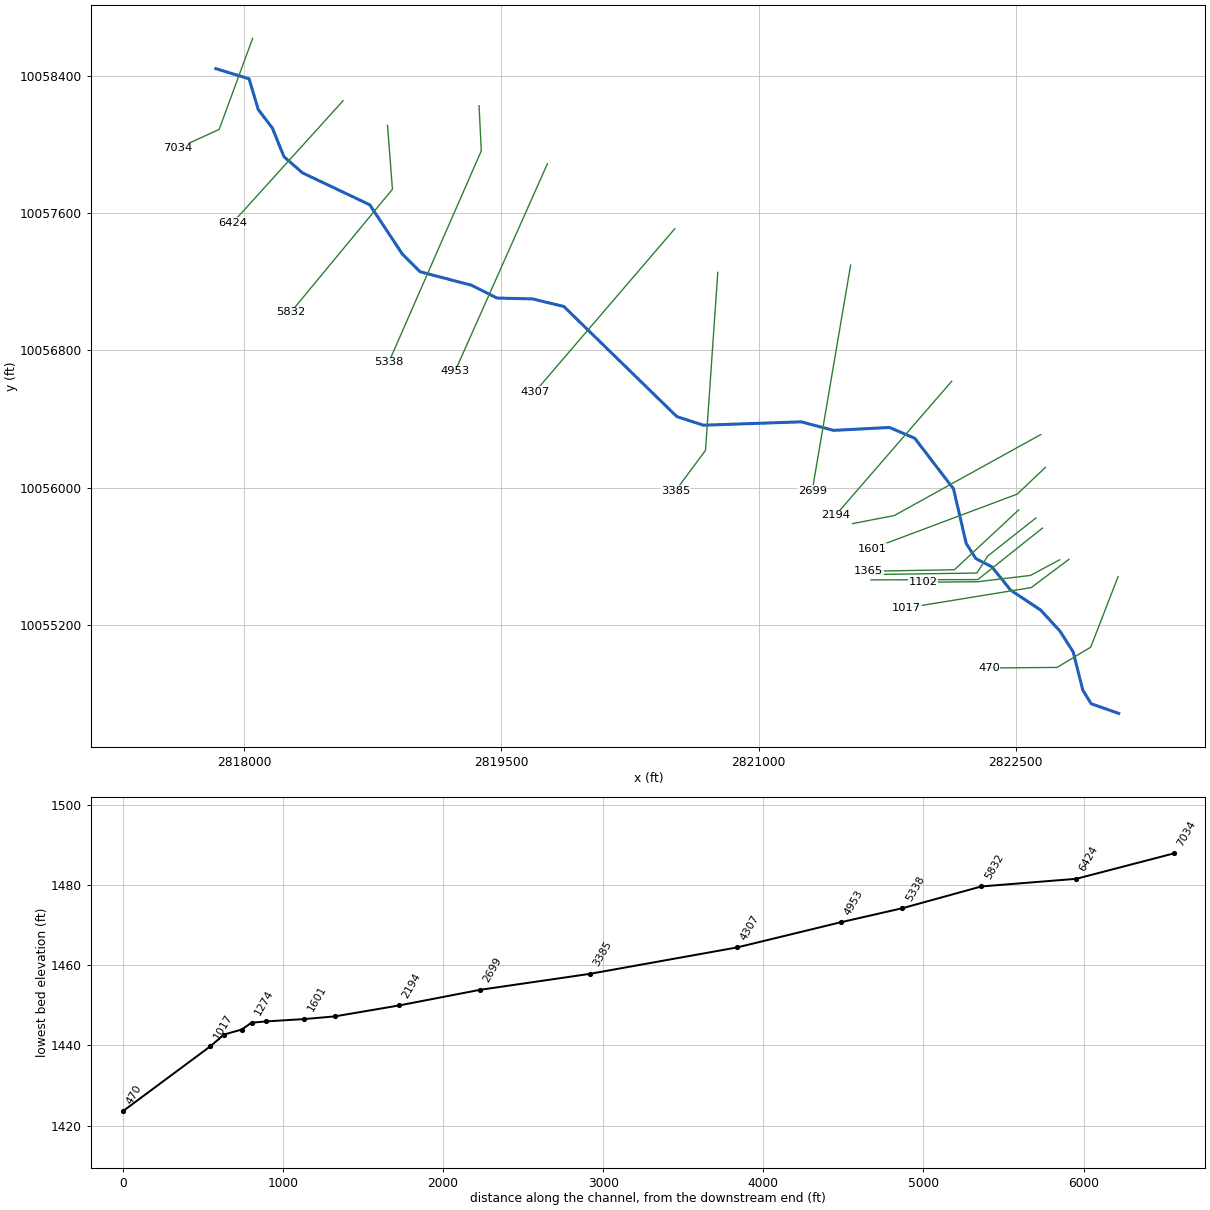
--- UNT001 IN NNOGR.prj (project) ---

Proj Title=UNT001 IN NNOGR Base Level Engineering
Current Plan=p01
Default Exp/Contr=0.3,0.1
English Units
Geom File=g01
Flow File=f01
Plan File=p01
BEGIN DESCRIPTION:
UNT001 IN NNOGR
END DESCRIPTION:

--- UNT001 IN NNOGR.p01 (plan) ---

Plan Title=Multiple Run
Short Identifier=Multiple
Geom File=g01
Flow File=f01
Subcritical Flow
K Sum by GR= 0
Std Step Tol= 0.01
Critical Tol= 0.01
Num of Std Step Trials= 20
Max Error Tol= 0.3
Flow Tol Ratio= 0.001
Split Flow NTrial= 30
Split Flow Tol= 0.02
Split Flow Ratio= 0.02
Log Output Level= 0
Friction Slope Method= 1
Unsteady Friction Slope Method= 2
Unsteady Bridges Friction Slope Method= 1
Parabolic Critical Depth
Global Vel Dist=  1 , 1 , 1
Global Log Level= 0
CheckData=True
Encroach Param= -1, 0, 0, 0
BEGIN DESCRIPTION:
Multiple Run
END DESCRIPTION:

--- UNT001 IN NNOGR.f01 (steady flow) ---

Flow Title=Multiple
Number of Profiles=7
Profile Names=10-year,25-year,50-year,1pct_min,100-year,1pct_plu,500-year
River Rch & RM= UNT001 IN NNOGR,Reach-1,7034
     666     936    1162    1057    1429    1933    2168
Boundary for River Rch & Prof#=UNT001 IN NNOGR,Reach-1,1
Up Type=0
Dn Type=3
Dn Slope=0.005
Boundary for River Rch & Prof#=UNT001 IN NNOGR,Reach-1,2
Up Type=0
Dn Type=3
Dn Slope=0.005
Boundary for River Rch & Prof#=UNT001 IN NNOGR,Reach-1,3
Up Type=0
Dn Type=3
Dn Slope=0.005
Boundary for River Rch & Prof#=UNT001 IN NNOGR,Reach-1,4
Up Type=0
Dn Type=3
Dn Slope=0.005
Boundary for River Rch & Prof#=UNT001 IN NNOGR,Reach-1,5
Up Type=0
Dn Type=3
Dn Slope=0.005
Boundary for River Rch & Prof#=UNT001 IN NNOGR,Reach-1,6
Up Type=0
Dn Type=3
Dn Slope=0.005
Boundary for River Rch & Prof#=UNT001 IN NNOGR,Reach-1,7
Up Type=0
Dn Type=3
Dn Slope=0.005

--- UNT001 IN NNOGR.g01 (geometry) ---

Geom Title=Existing Conditions

River Reach=UNT001 IN NNOGR,Reach-1
Reach XY= 30
      2817834.84     10058443.43      2818028.88     10058384.13
      2818082.20     10058205.28      2818164.67     10058096.87
      2818232.09     10057930.47      2818339.40     10057836.11
      2818732.61     10057649.35      2818923.34     10057360.97
      2819026.08     10057258.77      2819326.89     10057179.92
      2819474.25     10057105.63      2819682.79     10057100.52
      2819864.75     10057056.15      2820523.61     10056414.06
      2820678.22     10056364.06      2821248.47     10056383.73
      2821437.82     10056334.00      2821763.13     10056350.92
      2821910.64     10056288.11      2822136.62     10055992.97
      2822210.98     10055673.98      2822266.97     10055586.31
      2822360.37     10055538.31      2822469.75     10055402.37
      2822645.12     10055285.82      2822757.00     10055163.96
      2822834.51     10055042.09      2822890.60     10054819.48
      2822939.37     10054739.69      2823099.60     10054683.64

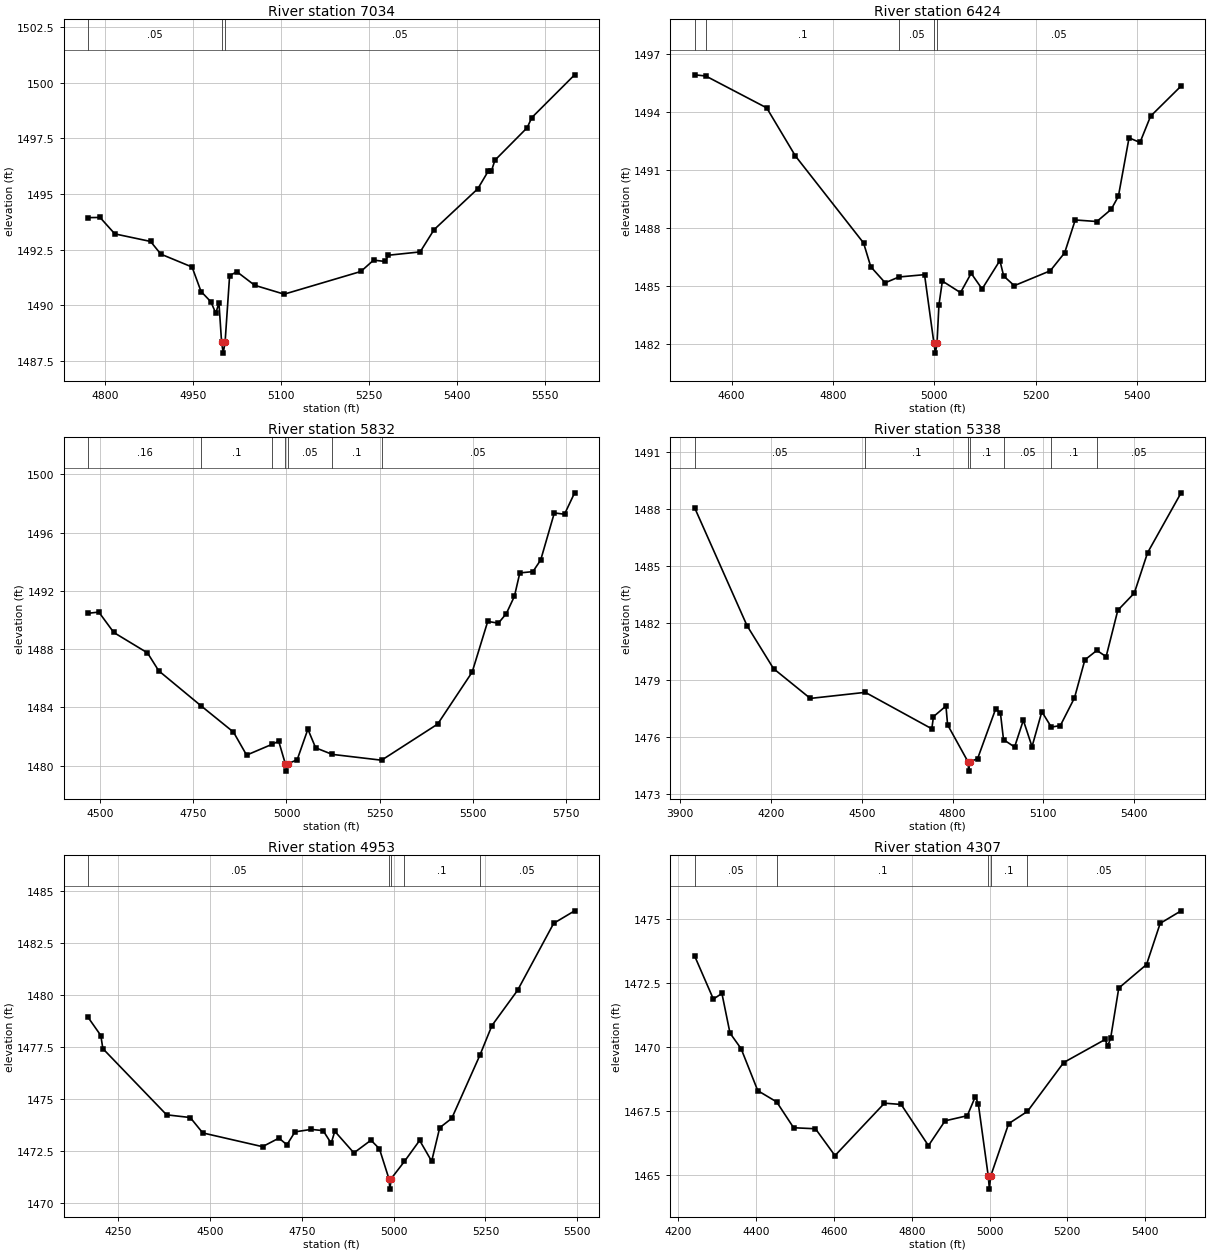
Type RM Length L Ch R = 1,7034,610,610,610
BEGIN DESCRIPTION:
UNT001 IN NNOGR 15.0
END DESCRIPTION:
XS GIS Cut Line= 3
      2818049.66     10058620.08      2817854.36     10058088.86
      2817614.82     10057979.51
#Sta/Elev= 30
  4771.1 1493.94  4791.4 1493.95  4816.6 1493.21  4877.5 1492.87  4895.1 1492.30
  4948.3 1491.72  4963.6 1490.62  4980.3 1490.16  4988.8 1489.64  4994.1 1490.12
  4998.6 1488.35  5001.4 1487.85  5004.6 1488.35  5012.3 1491.33  5024.6 1491.51
  5055.0 1490.90  5105.3 1490.50  5236.0 1491.52  5257.7 1492.03  5277.5 1491.97
  5282.8 1492.25  5337.1 1492.40  5360.8 1493.40  5435.4 1495.24  5452.9 1496.02
  5458.4 1496.02  5464.5 1496.52  5519.4 1497.98  5527.5 1498.44  5600.4 1500.36
#Mann=3,-1,0
  4771.1    0.05       0  4998.6    0.03       0  5004.6    0.05       0
Bank Sta=4998.6,5004.6
Exp/Cntr=0.3,0.1

Type RM Length L Ch R = 1,6424,592,592,592
BEGIN DESCRIPTION:
UNT001 IN NNOGR 14.0
END DESCRIPTION:
XS GIS Cut Line= 2
      2818577.07     10058256.26      2817932.93     10057544.31
#Sta/Elev= 30
  4526.9 1495.92  4548.9 1495.86  4669.2 1494.21  4725.9 1491.72  4860.4 1487.22
  4874.6 1485.99  4903.0 1485.16  4930.2 1485.46  4980.7 1485.58  4999.3 1482.02
  5002.1 1481.52  5005.3 1482.02  5009.1 1484.01  5015.9 1485.25  5051.7 1484.65
  5072.7 1485.65  5094.3 1484.84  5129.4 1486.31  5136.9 1485.51  5157.8 1485.01
  5228.8 1485.78  5257.2 1486.71  5278.1 1488.41  5320.7 1488.33  5349.1 1488.96
  5363.3 1489.64  5384.3 1492.66  5405.9 1492.42  5426.8 1493.78  5487.0 1495.34
#Mann=5,-1,0
  4526.9    0.05       0  4548.9     0.1       0  4930.2    0.05       0
  4999.3   0.035       0  5005.3    0.05       0
Bank Sta=4999.3,5005.3
Exp/Cntr=0.3,0.1

Type RM Length L Ch R = 1,5832,494,494,494
BEGIN DESCRIPTION:
UNT001 IN NNOGR 12.0
END DESCRIPTION:
XS GIS Cut Line= 3
      2818836.13     10058112.33      2818864.77     10057739.91
      2818272.23     10057022.62
#Sta/Elev= 30
  4468.4 1490.46  4497.1 1490.54  4537.2 1489.14  4627.5 1487.74  4657.6 1486.51
  4770.3 1484.12  4858.0 1482.30  4893.2 1480.72  4961.2 1481.46  4979.2 1481.67
  4997.0 1480.12  4999.8 1479.62  5003.0 1480.12  5028.7 1480.40  5057.4 1482.50
  5078.2 1481.22  5122.7 1480.77  5254.9 1480.37  5405.2 1482.85  5497.7 1486.42
  5539.4 1489.90  5568.0 1489.78  5589.3 1490.44  5611.0 1491.63  5625.4 1493.23
  5660.5 1493.32  5681.4 1494.12  5717.9 1497.35  5745.2 1497.26  5772.3 1498.73
#Mann=7,-1,0
  4468.4    0.16       0  4770.3     0.1       0  4961.2    0.05       0
  4997.0   0.035       0  5003.0    0.05       0  5122.7     0.1       0
  5254.9    0.05       0
Bank Sta=4997,5003
Exp/Cntr=0.3,0.1

Type RM Length L Ch R = 1,5338,385,385,385
BEGIN DESCRIPTION:
Mapping XS 7cea9a53
END DESCRIPTION:
XS GIS Cut Line= 3
      2819369.98     10058226.90      2819383.00     10057963.86
      2818843.95     10056732.12
#Sta/Elev= 30
  3947.5 1488.07  4120.9 1481.85  4208.4 1479.59  4330.0 1478.02  4511.7 1478.34
  4731.5 1476.42  4737.0 1477.06  4778.3 1477.62  4783.7 1476.63  4850.9 1474.69
  4853.6 1474.19  4856.9 1474.69  4882.7 1474.84  4942.4 1477.46  4958.4 1477.24
  4968.5 1475.85  5005.1 1475.46  5034.0 1476.87  5062.8 1475.48  5095.2 1477.32
  5126.5 1476.51  5156.4 1476.59  5203.1 1478.05  5237.4 1480.05  5277.0 1480.55
  5307.6 1480.22  5346.2 1482.66  5400.8 1483.57  5444.5 1485.69  5555.4 1488.85
#Mann=7,-1,0
  3947.5    0.05       0  4511.7     0.1       0  4850.9   0.035       0
  4856.9     0.1       0  4968.5    0.05       0  5126.5     0.1       0
  5277.0    0.05       0
Bank Sta=4850.9,4856.9
Exp/Cntr=0.3,0.1

Type RM Length L Ch R = 1,4953,646,646,646
BEGIN DESCRIPTION:
UNT001 IN NNOGR 11.0
END DESCRIPTION:
XS GIS Cut Line= 2
      2819768.44     10057888.38      2819229.66     10056678.08
#Sta/Elev= 30
  4168.1 1478.94  4202.7 1478.07  4208.2 1477.44  4381.8 1474.26  4446.1 1474.13
  4480.3 1473.39  4643.0 1472.73  4687.7 1473.14  4709.5 1472.82  4731.4 1473.44
  4775.6 1473.56  4808.1 1473.50  4830.0 1472.89  4839.8 1473.47  4891.8 1472.43
  4938.3 1473.04  4961.3 1472.63  4987.2 1471.19  4990.0 1470.69  4993.2 1471.19
  5029.4 1472.02  5070.9 1473.03  5103.6 1472.03  5125.5 1473.64  5158.3 1474.09
  5234.6 1477.11  5267.8 1478.55  5337.5 1480.24  5435.9 1483.46  5492.9 1484.06
#Mann=5,-1,0
  4168.1    0.05       0  4987.2   0.035       0  4993.2    0.05       0
  5029.4     0.1       0  5234.6    0.05       0
Bank Sta=4987.2,4993.2
Exp/Cntr=0.3,0.1

Type RM Length L Ch R = 1,4307,922,922,922
BEGIN DESCRIPTION:
UNT001 IN NNOGR 10.0
END DESCRIPTION:
XS GIS Cut Line= 2
      2820511.19     10057509.77      2819696.85     10056559.71
#Sta/Elev= 30
  4241.4 1473.55  4289.7 1471.86  4311.7 1472.08  4332.5 1470.53  4361.1 1469.92
  4403.9 1468.28  4452.5 1467.84  4496.1 1466.83  4552.3 1466.79  4602.5 1465.74
  4729.8 1467.79  4772.7 1467.74  4842.9 1466.13  4885.7 1467.10  4942.8 1467.30
  4963.6 1468.05  4971.3 1467.75  4996.8 1464.93  4999.6 1464.43  5002.8 1464.93
  5049.2 1466.99  5097.6 1467.47  5190.8 1469.38  5297.3 1470.28  5303.9 1470.02
  5311.6 1470.34  5332.4 1472.29  5403.8 1473.21  5438.9 1474.82  5492.7 1475.31
#Mann=5,-1,0
  4241.4    0.05       0  4452.5     0.1       0  4996.8    0.07       0
  5002.8     0.1       0  5097.6    0.05       0
Bank Sta=4996.8,5002.8
Exp/Cntr=0.3,0.1

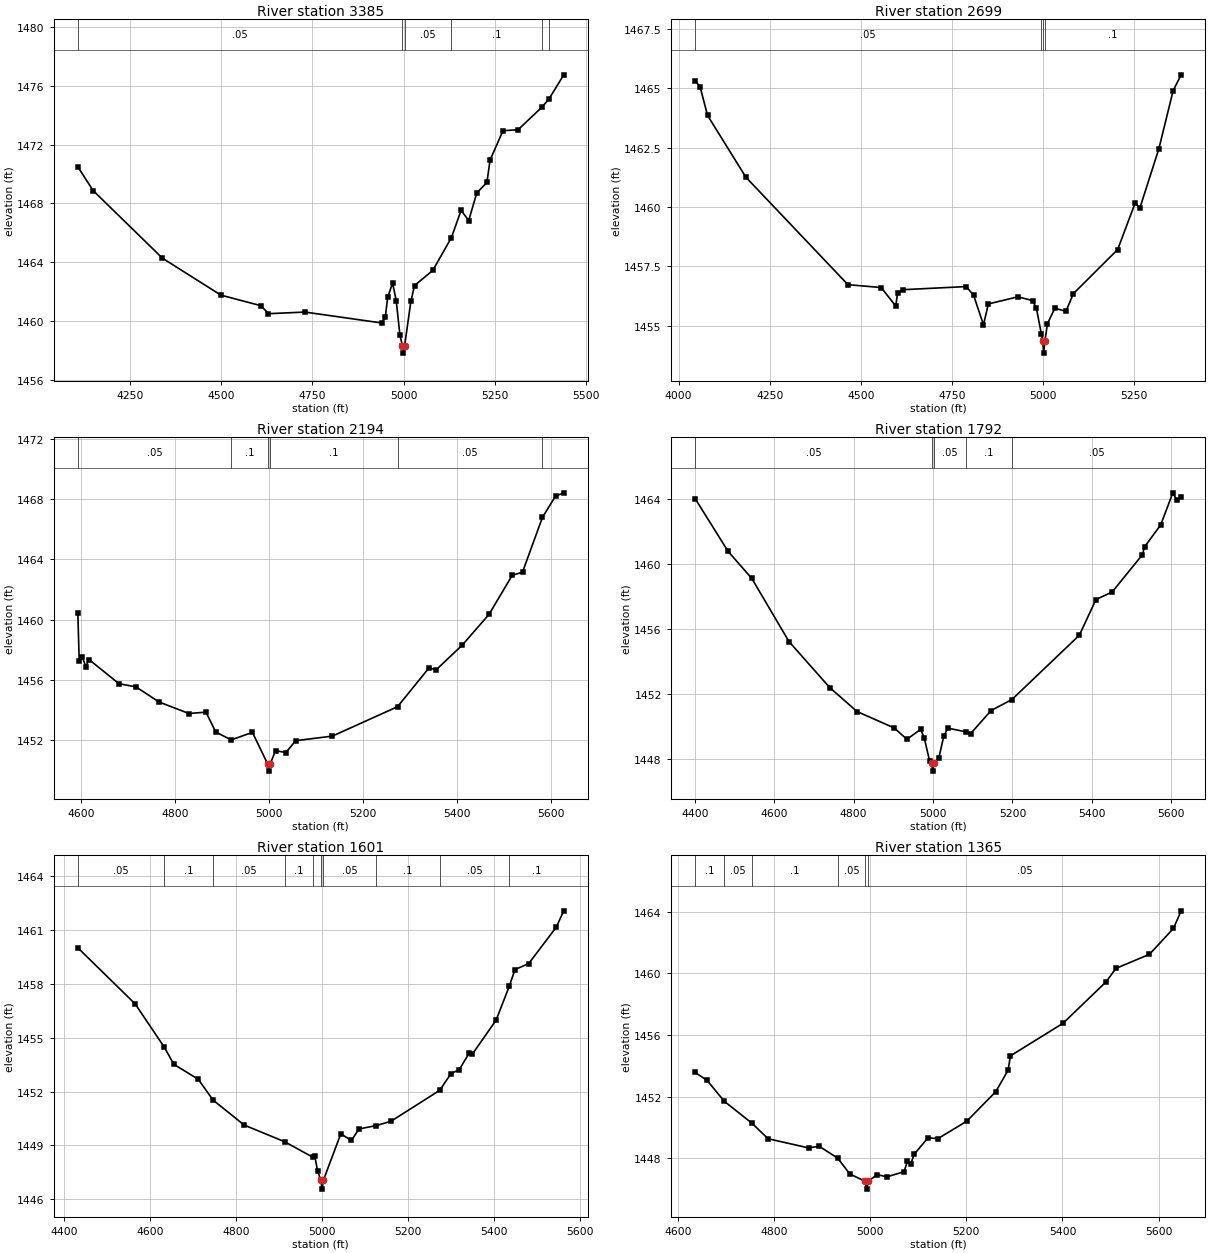
Type RM Length L Ch R = 1,3385,686,686,686
BEGIN DESCRIPTION:
UNT001 IN NNOGR 7.0
END DESCRIPTION:
XS GIS Cut Line= 3
      2820762.10     10057255.35      2820690.49     10056217.61
      2820516.04     10055981.97
#Sta/Elev= 30
  4106.1 1470.49  4147.8 1468.88  4338.3 1464.28  4498.7 1461.77  4608.9 1461.05
  4629.0 1460.51  4729.2 1460.62  4939.7 1459.88  4949.7 1460.26  4956.3 1461.62
  4969.8 1462.59  4979.8 1461.39  4989.8 1459.06  4996.8 1458.33  4999.6 1457.83
  5002.8 1458.33  5019.9 1461.34  5029.9 1462.42  5080.0 1463.45  5131.2 1465.68
  5157.7 1467.53  5178.6 1466.84  5200.9 1468.72  5228.7 1469.43  5237.1 1470.94
  5272.6 1472.94  5314.2 1473.01  5379.8 1474.55  5398.6 1475.09  5439.5 1476.74
#Mann=6,-1,0
  4106.1    0.05       0  4996.8   0.035       0  5002.8    0.05       0
  5131.2     0.1       0  5379.8    0.05       0  5398.6     0.1       0
Bank Sta=4996.8,5002.8
Exp/Cntr=0.3,0.1

Type RM Length L Ch R = 1,2699,505,505,505
BEGIN DESCRIPTION:
UNT001 IN NNOGR 4.0
END DESCRIPTION:
XS GIS Cut Line= 2
      2821536.65     10057297.22      2821312.68     10055982.05
#Sta/Elev= 30
  4045.5 1465.32  4059.2 1465.04  4079.5 1463.85  4184.8 1461.25  4464.9 1456.73
  4556.2 1456.61  4596.2 1455.83  4601.2 1456.39  4617.1 1456.52  4789.5 1456.65
  4809.8 1456.29  4837.0 1455.04  4850.4 1455.92  4931.6 1456.22  4972.1 1456.06
  4982.3 1455.74  4995.7 1454.67  4999.6 1454.35  5002.3 1453.85  5005.6 1454.35
  5012.6 1455.09  5033.0 1455.74  5063.4 1455.61  5083.7 1456.35  5205.4 1458.21
  5253.5 1460.17  5266.3 1459.95  5318.7 1462.46  5357.6 1464.89  5379.6 1465.56
#Mann=4,-1,0
  4045.5    0.05       0  4995.7     0.1       0  4999.6    0.07       0
  5005.6     0.1       0
Bank Sta=4999.6,5005.6
Exp/Cntr=0.3,0.1

Type RM Length L Ch R = 1,2194,402,402,402
BEGIN DESCRIPTION:
Mapping XS efdab966
END DESCRIPTION:
XS GIS Cut Line= 2
      2822126.05     10056620.10      2821448.98     10055838.87
#Sta/Elev= 30
  4593.8 1460.42  4596.7 1457.29  4603.3 1457.53  4610.9 1456.88  4617.5 1457.36
  4681.6 1455.75  4717.3 1455.55  4766.7 1454.54  4830.3 1453.78  4866.4 1453.87
  4887.3 1452.55  4920.2 1452.03  4965.2 1452.53  4997.3 1450.46  5000.0 1449.96
  5003.3 1450.46  5014.5 1451.32  5036.4 1451.19  5057.3 1451.98  5135.2 1452.28
  5273.9 1454.23  5341.3 1456.82  5355.5 1456.66  5411.5 1458.31  5468.5 1460.35
  5517.9 1462.94  5539.8 1463.15  5582.3 1466.79  5610.0 1468.19  5627.6 1468.41
#Mann=6,-1,0
  4593.8    0.05       0  4920.2     0.1       0  4997.3    0.07       0
  5003.3     0.1       0  5273.9    0.05       0  5582.3     0.1       0
Bank Sta=4997.3,5003.3
Exp/Cntr=0.3,0.1

Type RM Length L Ch R = 1,1792,191,191,191
BEGIN DESCRIPTION:
UNT001 IN NNOGR 3.0
END DESCRIPTION:
XS GIS Cut Line= 3
      2822645.20     10056309.37      2821790.99     10055837.13
      2821547.92     10055790.25
#Sta/Elev= 30
  4401.0 1464.01  4484.0 1460.76  4543.5 1459.10  4637.2 1455.21  4740.1 1452.37
  4808.6 1450.90  4902.1 1449.89  4934.1 1449.19  4968.6 1449.80  4977.7 1449.29
  4991.4 1447.84  4996.4 1447.73  4999.2 1447.23  5002.4 1447.73  5014.3 1448.03
  5026.9 1449.37  5037.1 1449.88  5082.3 1449.65  5094.3 1449.53  5146.0 1450.96
  5198.6 1451.64  5368.3 1455.60  5410.2 1457.80  5450.9 1458.26  5527.2 1460.56
  5532.4 1461.04  5573.1 1462.39  5603.7 1464.37  5613.9 1463.92  5624.6 1464.14
#Mann=5,-1,0
  4401.0    0.05       0  4996.4   0.035       0  5002.4    0.05       0
  5082.3     0.1       0  5198.6    0.05       0
Bank Sta=4996.4,5002.4
Exp/Cntr=0.3,0.1

Type RM Length L Ch R = 1,1601,236,236,236
BEGIN DESCRIPTION:
Mapping XS d32121ca
END DESCRIPTION:
XS GIS Cut Line= 3
      2822672.91     10056118.35      2822508.00     10055962.13
      2821662.08     10055644.91
#Sta/Elev= 30
  4431.2 1460.01  4564.8 1456.88  4632.2 1454.48  4654.6 1453.52  4711.3 1452.69
  4745.8 1451.53  4818.1 1450.14  4912.3 1449.21  4978.5 1448.34  4982.5 1448.41
  4988.9 1447.58  4996.6 1447.07  4999.4 1446.57  5002.6 1447.07  5043.0 1449.65
  5067.9 1449.28  5085.1 1449.92  5125.6 1450.11  5159.8 1450.35  5273.0 1452.07
  5299.3 1453.00  5318.9 1453.23  5341.4 1454.14  5349.1 1454.09  5404.3 1455.98
  5435.2 1457.88  5448.2 1458.80  5480.2 1459.13  5544.3 1461.16  5561.8 1462.07
#Mann=10,-1,0
  4431.2    0.05       0  4632.2     0.1       0  4745.8    0.05       0
  4912.3     0.1       0  4978.5    0.05       0  4996.6   0.035       0
  5002.6    0.05       0  5125.6     0.1       0  5273.0    0.05       0
  5435.2     0.1       0
Bank Sta=4996.6,5002.6
Exp/Cntr=0.3,0.1

Type RM Length L Ch R = 1,1365,91,91,91
BEGIN DESCRIPTION:
Mapping XS 6d70dfce
END DESCRIPTION:
XS GIS Cut Line= 3
      2822516.66     10055870.09      2822141.68     10055521.16
      2821642.57     10055512.49
#Sta/Elev= 30
  4635.6 1453.56  4660.3 1453.05  4696.2 1451.69  4753.3 1450.28  4787.3 1449.26
  4872.3 1448.66  4893.3 1448.78  4932.2 1448.00  4957.3 1446.98  4989.5 1446.49
  4992.3 1445.99  4995.5 1446.49  5014.0 1446.93  5035.0 1446.79  5070.3 1447.12
  5077.5 1447.81  5084.4 1447.65  5091.7 1448.26  5120.0 1449.32  5141.0 1449.27
  5201.0 1450.40  5261.1 1452.31  5286.8 1453.70  5291.8 1454.64  5401.1 1456.75
  5491.1 1459.45  5511.1 1460.31  5581.1 1461.23  5631.1 1462.91  5647.0 1464.05
#Mann=6,-1,0
  4635.6     0.1       0  4696.2    0.05       0  4753.3     0.1       0
  4932.2    0.05       0  4989.5   0.035       0  4995.5    0.05       0
Bank Sta=4989.5,4995.5
Exp/Cntr=0.3,0.1

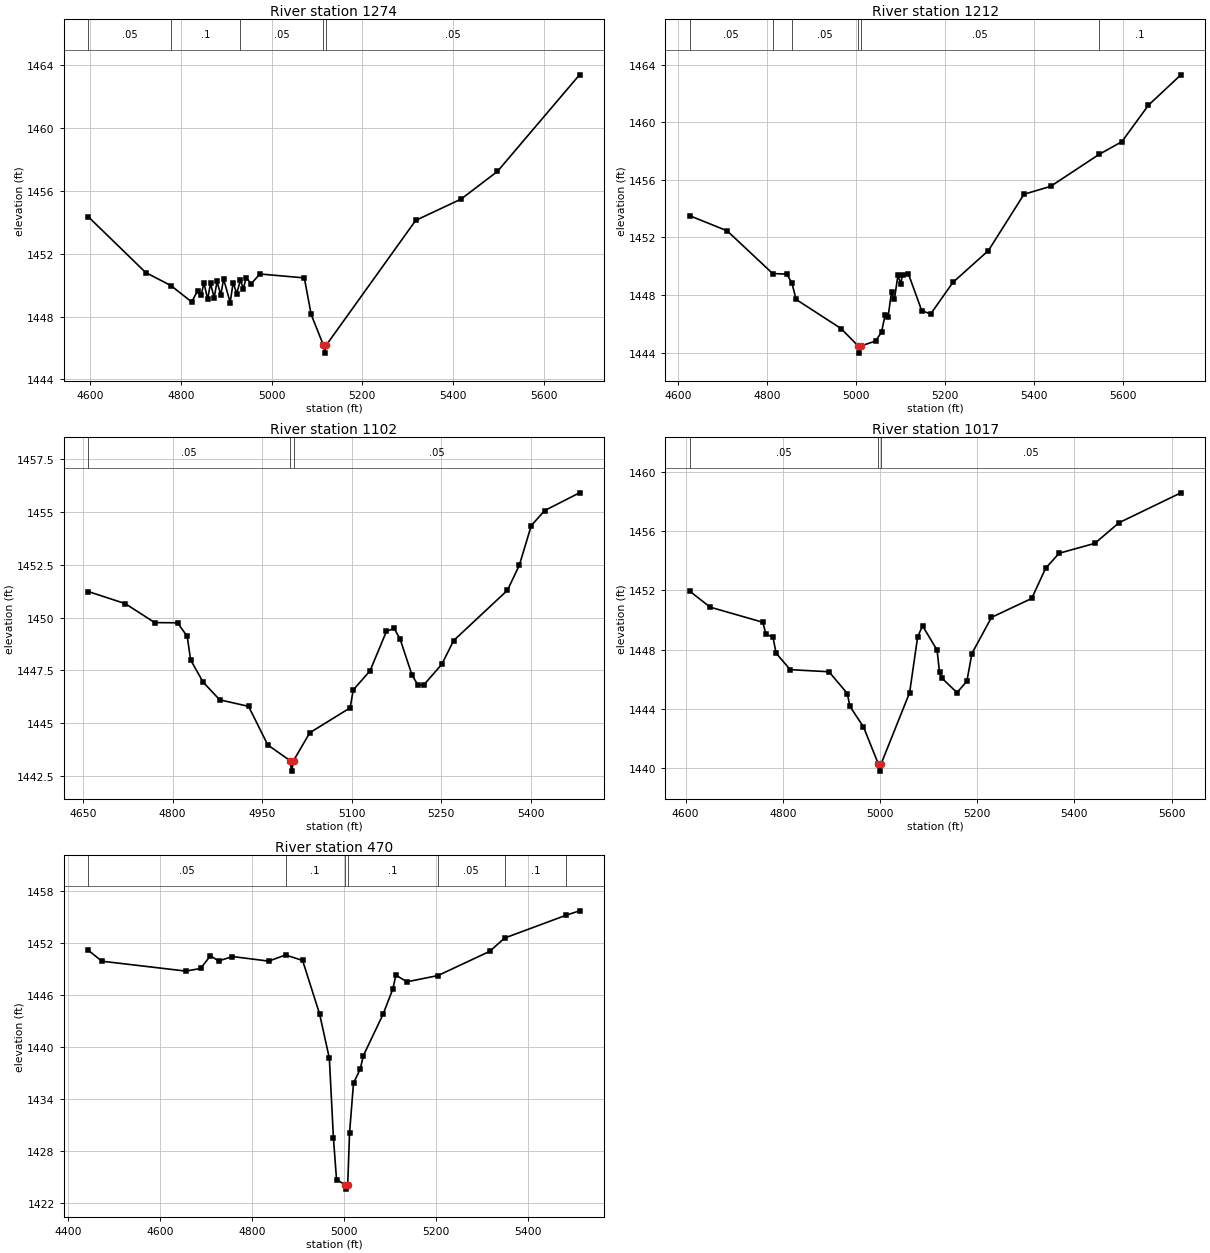
Type RM Length L Ch R = 1,1274,62,62,62
BEGIN DESCRIPTION:
Mapping XS 58ec29d0
END DESCRIPTION:
XS GIS Cut Line= 4
      2822617.37     10055823.23      2822336.13     10055601.02
      2822273.63     10055502.06      2821667.76     10055493.38
#Sta/Elev= 30
  4596.7 1454.35  4723.0 1450.80  4778.6 1449.97  4824.1 1448.93  4837.4 1449.64
  4844.9 1449.34  4851.2 1450.15  4859.3 1449.10  4865.7 1450.11  4873.7 1449.19
  4880.1 1450.24  4888.2 1449.37  4894.5 1450.39  4909.0 1448.89  4915.4 1450.16
  4923.4 1449.46  4931.5 1450.32  4937.9 1449.77  4944.2 1450.48  4955.1 1450.08
  4974.3 1450.71  5072.2 1450.46  5087.3 1448.13  5114.3 1446.17  5117.1 1445.67
  5120.3 1446.17  5317.4 1454.12  5417.4 1455.48  5497.4 1457.24  5678.1 1463.39
#Mann=5,-1,0
  4596.7    0.05       0  4778.6     0.1       0  4931.5    0.05       0
  5114.3    0.04       0  5120.3    0.05       0
Bank Sta=5114.3,5120.3
Exp/Cntr=0.3,0.1

Type RM Length L Ch R = 1,1212,110,110,110
BEGIN DESCRIPTION:
Mapping XS 5dc3be44
END DESCRIPTION:
XS GIS Cut Line= 3
      2822655.54     10055764.18      2822278.84     10055463.86
      2821655.60     10055462.13
#Sta/Elev= 30
  4626.0 1453.51  4710.2 1452.46  4812.7 1449.49  4844.7 1449.45  4855.9 1448.83
  4865.5 1447.69  4966.4 1445.67  5005.0 1444.46  5007.8 1443.96  5011.0 1444.46
  5044.3 1444.80  5057.6 1445.42  5065.7 1446.62  5072.1 1446.44  5080.1 1448.21
  5086.5 1447.69  5094.5 1449.37  5100.9 1448.78  5104.8 1449.42  5118.1 1449.46
  5148.1 1446.91  5168.1 1446.68  5218.1 1448.87  5298.1 1451.09  5378.1 1455.00
  5438.1 1455.55  5547.0 1457.77  5598.1 1458.65  5658.1 1461.19  5731.0 1463.30
#Mann=6,-1,0
  4626.0    0.05       0  4812.7     0.1       0  4855.9    0.05       0
  5005.0    0.04       0  5011.0    0.05       0  5547.0     0.1       0
Bank Sta=5005,5011
Exp/Cntr=0.3,0.1

Type RM Length L Ch R = 1,1102,85,85,85
BEGIN DESCRIPTION:
Mapping XS e034e201
END DESCRIPTION:
XS GIS Cut Line= 4
      2822755.40     10055579.14      2822585.28     10055488.01
      2822278.86     10055451.55      2821957.65     10055448.08
#Sta/Elev= 30
  4658.9 1451.23  4720.6 1450.66  4770.1 1449.76  4808.3 1449.75  4824.5 1449.11
  4830.2 1447.99  4851.1 1446.94  4878.9 1446.10  4927.3 1445.79  4959.5 1443.96
  4996.7 1443.22  4999.5 1442.72  5002.7 1443.22  5029.9 1444.54  5097.5 1445.72
  5102.6 1446.57  5130.7 1447.47  5158.2 1449.34  5170.9 1449.49  5180.9 1449.00
  5200.9 1447.29  5210.9 1446.80  5220.9 1446.81  5250.9 1447.78  5270.9 1448.91
  5360.9 1451.29  5380.9 1452.48  5400.9 1454.36  5423.4 1455.07  5481.7 1455.91
#Mann=3,-1,0
  4658.9    0.05       0  4996.7   0.035       0  5002.7    0.05       0
Bank Sta=4996.7,5002.7
Exp/Cntr=0.3,0.1

Type RM Length L Ch R = 1,1017,547,547,547
BEGIN DESCRIPTION:
Mapping XS 04d50031
END DESCRIPTION:
XS GIS Cut Line= 3
      2822810.07     10055581.91      2822589.60     10055416.99
      2821863.87     10055298.93
#Sta/Elev= 30
  4608.5 1451.95  4650.7 1450.87  4759.1 1449.85  4765.3 1449.04  4779.9 1448.85
  4786.2 1447.77  4815.3 1446.65  4895.1 1446.51  4932.9 1445.04  4938.0 1444.18
  4966.0 1442.79  4996.5 1440.30  4999.3 1439.80  5002.5 1440.30  5061.0 1445.10
  5077.5 1448.86  5087.6 1449.61  5117.5 1447.97  5122.6 1446.46  5128.1 1446.06
  5158.5 1445.10  5178.8 1445.87  5189.2 1447.74  5229.4 1450.18  5312.2 1451.46
  5340.9 1453.50  5368.7 1454.51  5442.2 1455.18  5491.8 1456.57  5619.1 1458.59
#Mann=3,-1,0
  4608.5    0.05       0  4996.5   0.035       0  5002.5    0.05       0
Bank Sta=4996.5,5002.5
Exp/Cntr=0.3,0.1

Type RM Length L Ch R = 1,470,0,0,0
BEGIN DESCRIPTION:
UNT001 IN NNOGR 1.0
END DESCRIPTION:
XS GIS Cut Line= 4
      2823096.53     10055481.18      2822936.82     10055069.77
      2822740.64     10054951.71      2822343.24     10054948.24
#Sta/Elev= 30
  4444.3 1451.20  4473.7 1449.94  4656.1 1448.80  4688.3 1449.10  4709.7 1450.57
  4727.5 1449.97  4757.4 1450.48  4836.4 1449.95  4872.9 1450.66  4910.0 1450.03
  4946.9 1443.86  4968.2 1438.72  4977.1 1429.47  4983.8 1424.72  5002.1 1424.11
  5004.9 1423.61  5008.1 1424.11  5012.1 1430.12  5020.7 1435.85  5035.4 1437.50
  5042.0 1439.02  5084.8 1443.79  5106.1 1446.72  5112.9 1448.33  5136.8 1447.56
  5204.2 1448.28  5316.8 1451.08  5349.0 1452.61  5482.7 1455.25  5512.0 1455.76
#Mann=7,-1,0
  4444.3    0.05       0  4872.9     0.1       0  5002.1    0.07       0
  5008.1     0.1       0  5204.2    0.05       0  5349.0     0.1       0
  5482.7    0.05       0
Bank Sta=5002.1,5008.1
Exp/Cntr=0.3,0.1

Chan Stop Cuts=-1