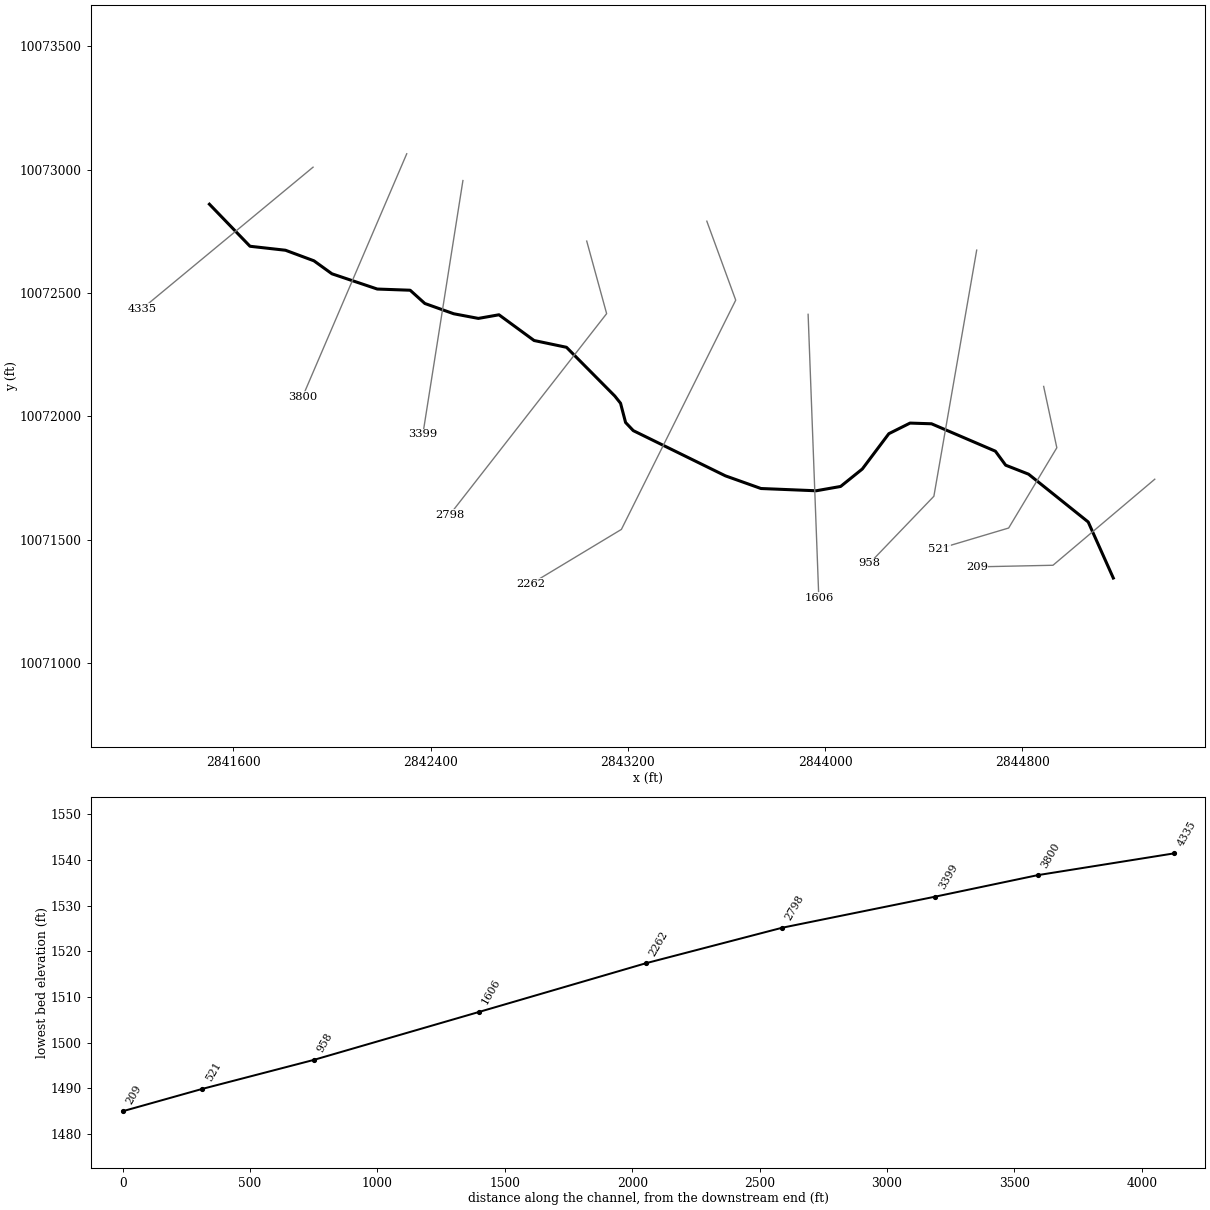
--- UNT002 IN NNOGR.prj (project) ---

Proj Title=UNT002 IN NNOGR Base Level Engineering
Current Plan=p01
Default Exp/Contr=0.3,0.1
English Units
Geom File=g01
Flow File=f01
Plan File=p01
Y Axis Title=Elevation
X Axis Title(PF)=Main Channel Distance
X Axis Title(XS)=Station
BEGIN DESCRIPTION:
UNT002 IN NNOGR
END DESCRIPTION:
DSS Export Rating Curves= 0
DSS Export Rating Curve Sorted= 0
DSS Export Volume Flow Curves= 0
DXF OffsetX= 0
DXF OffsetY= 0
DXF ScaleX= 1
DXF ScaleY= 10

--- UNT002 IN NNOGR.p01 (plan) ---

Plan Title=Multiple Run
Short Identifier=Multiple
Geom File=g01
Flow File=f01
Subcritical Flow
K Sum by GR= 0
Std Step Tol= 0.01
Critical Tol= 0.01
Num of Std Step Trials= 20
Max Error Tol= 0.3
Flow Tol Ratio= 0.001
Split Flow NTrial= 30
Split Flow Tol= 0.02
Split Flow Ratio= 0.02
Log Output Level= 0
Friction Slope Method= 1
Unsteady Friction Slope Method= 2
Unsteady Bridges Friction Slope Method= 1
Parabolic Critical Depth
Global Vel Dist=  1 , 1 , 1
Global Log Level= 0
CheckData=True
Encroach Param= -1, 0, 0, 0
BEGIN DESCRIPTION:
Multiple Run
END DESCRIPTION:

--- UNT002 IN NNOGR.f01 (steady flow) ---

Flow Title=Multiple
Program Version=4.10
Number of Profiles= 7
Profile Names=10-year,25-year,50-year,1pct_min,100-year,1pct_plu,500-year
River Rch & RM=UNT002 IN NNOGR,Reach-1         ,4335
     998    1472    1892    1783    2411    3260    3927
River Rch & RM=UNT002 IN NNOGR,Reach-1         ,3399
    1223    1820    2352    2225    3009    4070    4946
Boundary for River Rch & Prof#=UNT002 IN NNOGR,Reach-1         , 1
Up Type= 0
Dn Type= 3
Dn Slope=0.015
Boundary for River Rch & Prof#=UNT002 IN NNOGR,Reach-1         , 2
Up Type= 0
Dn Type= 3
Dn Slope=0.015
Boundary for River Rch & Prof#=UNT002 IN NNOGR,Reach-1         , 3
Up Type= 0
Dn Type= 3
Dn Slope=0.015
Boundary for River Rch & Prof#=UNT002 IN NNOGR,Reach-1         , 4
Up Type= 0
Dn Type= 3
Dn Slope=0.015
Boundary for River Rch & Prof#=UNT002 IN NNOGR,Reach-1         , 5
Up Type= 0
Dn Type= 3
Dn Slope=0.015
Boundary for River Rch & Prof#=UNT002 IN NNOGR,Reach-1         , 6
Up Type= 0
Dn Type= 3
Dn Slope=0.015
Boundary for River Rch & Prof#=UNT002 IN NNOGR,Reach-1         , 7
Up Type= 0
Dn Type= 3
Dn Slope=0.015
DSS Import GetInterval= 0
DSS Import GetPeak= 0
DSS Import FillOption= 0

--- UNT002 IN NNOGR.g01 (geometry) ---

Geom Title=Existing Conditions
Program Version=4.10

River Reach=UNT002 IN NNOGR ,Reach-1
Reach XY= 30
      2841503.27     10072859.78      2841667.84      10072689.2
      2841811.78     10072673.04      2841927.03     10072630.27
      2842000.05     10072577.56      2842183.92     10072515.72
      2842317.27     10072510.91      2842376.82     10072457.14
      2842494.06     10072415.46      2842593.84     10072396.63
      2842677.35     10072411.35      2842819.77     10072307.03
      2842951.15     10072279.47      2843147.07     10072081.84
      2843170.35     10072052.61      2843190.82     10071974.49
      2843222.03     10071941.53      2843595.59     10071758.18
      2843739.78     10071706.81      2843963.57     10071697.63
      2844062.78     10071715.12      2844150.78     10071785.99
      2844258.29     10071929.13      2844344.23     10071972.12
       2844431.3     10071969.31      2844690.35     10071858.17
      2844731.99     10071801.37      2844824.69     10071765.02
      2845066.72     10071571.07      2845168.47     10071343.73

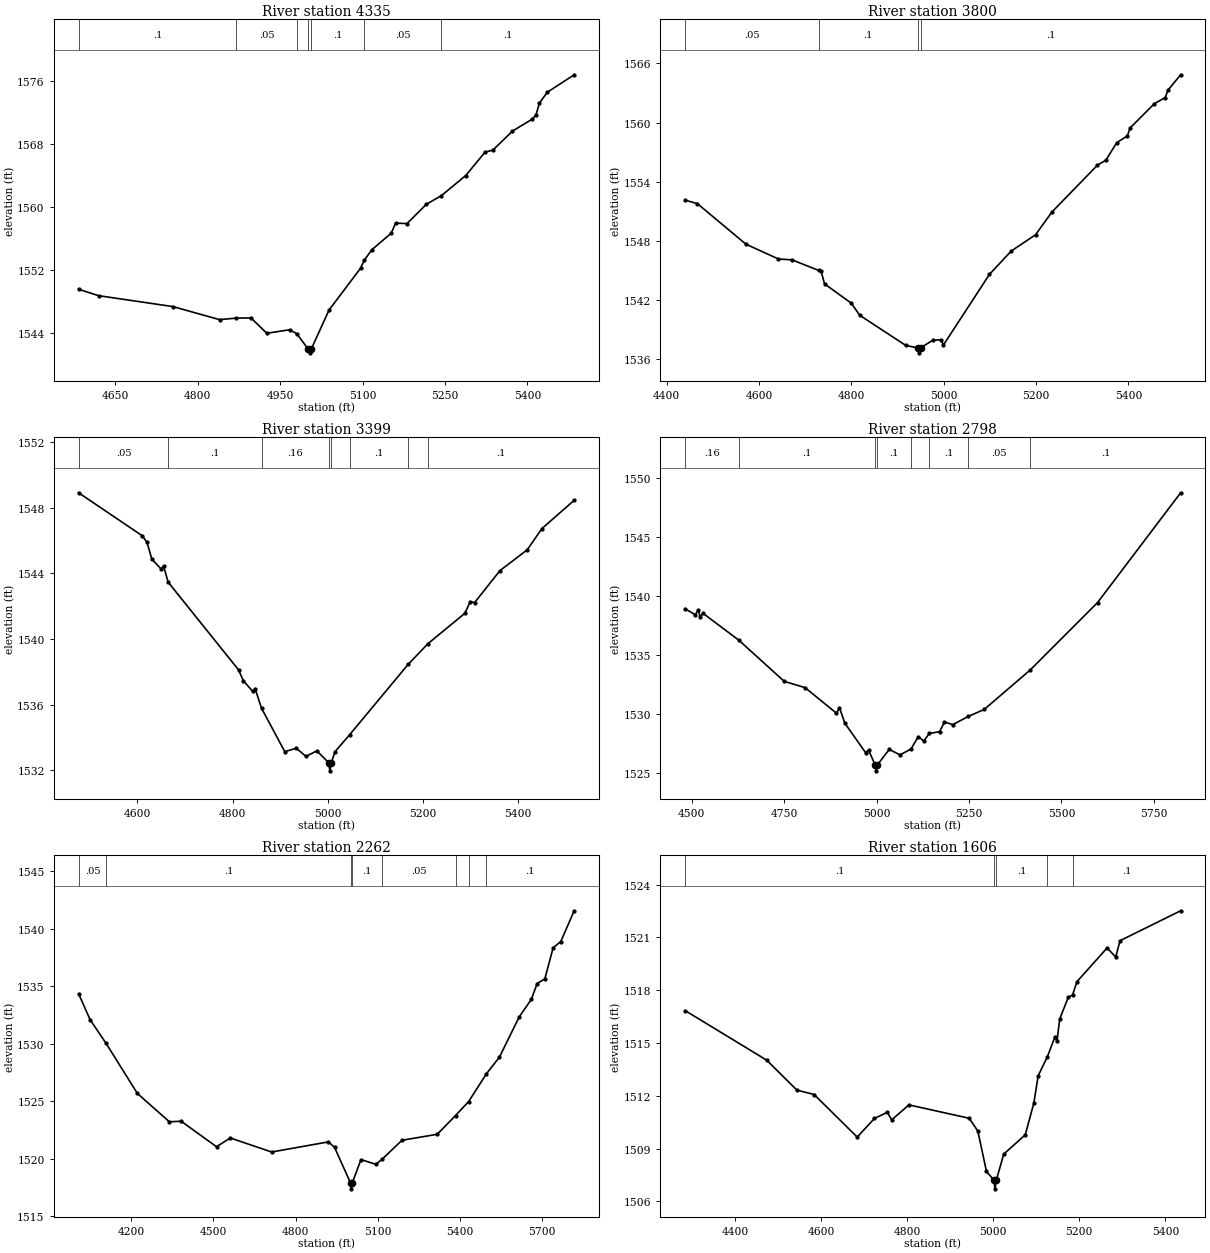
Type RM Length L Ch R = 1 ,4335    ,535,535,535
BEGIN DESCRIPTION:
UNT002 IN NNOGR 8.0
END DESCRIPTION:
XS GIS Cut Line= 2
      2841923.53     10073009.97      2841229.13     10072434.91
#Sta/Elev= 30
  4583.4 1549.51  4619.6 1548.69    4755  1547.3  4839.7 1545.64  4869.8 1545.83
    4897 1545.86  4925.7  1543.9  4967.3 1544.35  4980.3 1543.85  5000.8 1541.91
  5003.6 1541.41  5006.8 1541.91    5039 1546.86  5096.3 1552.18  5103.4 1553.24
  5117.1 1554.55  5152.3 1556.66  5160.1 1557.93  5180.9 1557.87  5216.1 1560.33
  5243.5 1561.43  5287.7 1563.99  5322.9 1566.97  5337.2 1567.23  5372.4 1569.63
    5408 1571.14  5415.4 1571.67  5421.9 1573.24  5436.2  1574.6    5485 1576.82
#Mann= 7 ,-1 , 0
  4583.4      .1       0  4869.8     .05       0  4980.3      .1       0
  5000.8     .07       0  5006.8      .1       0  5103.4     .05       0
  5243.5      .1       0
Bank Sta=5000.8,5006.8
XS Rating Curve= 0 ,0
Exp/Cntr=0.3,0.1

Type RM Length L Ch R = 1 ,3800    ,401,401,401
BEGIN DESCRIPTION:
UNT002 IN NNOGR 7.0
END DESCRIPTION:
XS GIS Cut Line= 2
      2842303.36     10073064.28      2841880.56     10072077.77
#Sta/Elev= 30
  4439.7 1552.13  4466.2 1551.78  4571.3 1547.67    4642 1546.16  4671.1 1546.08
  4729.3    1545  4734.1 1544.95  4741.8 1543.64  4799.8 1541.68  4817.9 1540.46
  4917.7  1537.4  4943.7 1537.15  4946.4 1536.65  4949.7 1537.15  4975.7 1537.92
  4993.8 1537.98  4999.3 1537.45    5099 1544.61  5146.1 1546.97  5198.7 1548.62
  5234.5 1550.94  5332.9 1555.68    5351 1556.18  5374.6 1557.96  5397.7 1558.64
  5403.6 1559.45  5456.2 1561.92  5479.8 1562.53  5485.2 1563.26    5513 1564.84
#Mann= 4 ,-1 , 0
  4439.7     .05       0  4729.3      .1       0  4943.7     .07       0
  4949.7      .1       0
Bank Sta=4943.7,4949.7
XS Rating Curve= 0 ,0
Exp/Cntr=0.3,0.1

Type RM Length L Ch R = 1 ,3399    ,601,601,601
BEGIN DESCRIPTION:
UNT002 IN NNOGR 6.0
END DESCRIPTION:
XS GIS Cut Line= 2
       2842531.2     10072955.71      2842368.75     10071926.86
#Sta/Elev= 30
  4476.4 1548.92    4610  1546.3  4620.1  1545.9  4630.3 1544.87  4649.8 1544.27
  4654.9 1544.46  4664.5 1543.47  4812.5 1538.12  4822.6 1537.46  4842.2 1536.81
  4847.3 1536.98  4860.8 1535.78  4909.7 1533.13    4934 1533.34  4954.2 1532.84
  4977.2 1533.18  5001.8 1532.46  5004.6 1531.96  5007.8 1532.46    5015 1533.12
    5046 1534.16  5169.2 1538.46  5210.8 1539.72  5288.3 1541.57  5299.5 1542.28
  5308.6 1542.22  5361.9 1544.17  5419.3 1545.44  5450.3 1546.74    5518 1548.46
#Mann= 8 ,-1 , 0
  4476.4     .05       0  4664.5      .1       0  4860.8     .16       0
  5001.8     .07       0  5007.8     .16       0    5046      .1       0
  5169.2     .05       0  5210.8      .1       0
Bank Sta=5001.8,5007.8
XS Rating Curve= 0 ,0
Exp/Cntr=0.3,0.1

Type RM Length L Ch R = 1 ,2798    ,536,536,536
BEGIN DESCRIPTION:
UNT002 IN NNOGR 5.0
END DESCRIPTION:
XS GIS Cut Line= 3
      2843033.24     10072710.22      2843113.95     10072415.99
      2842476.92     10071599.37
#Sta/Elev= 30
  4481.8 1538.91  4509.3  1538.4  4517.5 1538.81  4522.6  1538.2    4530 1538.53
  4626.5 1536.26  4750.1 1532.75  4806.4 1532.22  4891.4 1530.05  4899.5 1530.52
    4914  1529.2  4970.1 1526.71  4978.2 1526.92    4996 1525.66  4998.8 1525.16
    5002 1525.66  5034.3 1526.98  5063.3 1526.51    5093 1527.01    5113 1528.07
  5127.5 1527.68  5142.4 1528.33  5170.2 1528.48  5183.6  1529.3  5206.2 1529.08
  5248.4 1529.78  5291.2 1530.37  5415.4 1533.71  5597.9 1539.44  5822.6 1548.75
#Mann= 8 ,-1 , 0
  4481.8     .16       0  4626.5      .1       0    4996     .07       0
    5002      .1       0    5093     .05       0  5142.4      .1       0
  5248.4     .05       0  5415.4      .1       0
Bank Sta=4996,5002
XS Rating Curve= 0 ,0
Exp/Cntr=0.3,0.1

Type RM Length L Ch R = 1 ,2262    ,656,656,656
BEGIN DESCRIPTION:
UNT002 IN NNOGR 4.0
END DESCRIPTION:
XS GIS Cut Line= 4
      2843520.22     10072790.95      2843637.39     10072470.67
      2843173.85     10071540.99      2842806.68     10071319.64
#Sta/Elev= 30
  4007.9 1534.33  4049.7 1532.08  4108.4 1530.01  4222.2 1525.67  4338.9 1523.21
  4382.4 1523.25  4511.1 1521.04  4561.4  1521.8  4712.5 1520.58  4919.5 1521.46
  4941.9 1520.99  5000.4 1517.88  5003.2 1517.38  5006.4 1517.88  5038.3 1519.92
  5092.9 1519.51    5116 1519.96    5188  1521.6  5316.7 1522.12  5383.5 1523.75
  5431.2 1524.96  5496.3 1527.38  5543.6 1528.82  5615.9 1532.32    5660 1533.84
  5681.4 1535.22  5709.3 1535.62  5739.7 1538.32  5767.7 1538.87  5816.5 1541.54
#Mann= 8 ,-1 , 0
  4007.9     .05       0  4108.4      .1       0  5000.4     .07       0
  5006.4      .1       0    5116     .05       0  5383.5      .1       0
  5431.2     .05       0  5496.3      .1       0
Bank Sta=5000.4,5006.4
XS Rating Curve= 0 ,0
Exp/Cntr=0.3,0.1

Type RM Length L Ch R = 1 ,1606    ,648,648,648
BEGIN DESCRIPTION:
UNT002 IN NNOGR 3.0
END DESCRIPTION:
XS GIS Cut Line= 2
      2843930.95     10072413.23      2843974.35     10071263.05
#Sta/Elev= 30
  4284.5 1516.84  4474.1 1514.02  4544.2 1512.32  4584.2 1512.07  4684.3 1509.65
  4724.3 1510.71  4754.3 1511.06  4764.3 1510.63  4804.4 1511.48  4944.5 1510.72
  4964.5 1509.99  4984.5  1507.7  5001.5 1507.21  5004.3 1506.71  5007.5 1507.21
  5024.5 1508.68  5074.6 1509.78  5094.6 1511.59  5104.6 1513.14  5125.9 1514.21
  5143.3 1515.33  5148.3  1515.1  5154.6 1516.36  5174.6  1517.6  5184.4 1517.72
  5194.6 1518.48  5264.7  1520.4  5284.7 1519.88  5294.7 1520.81  5435.5 1522.51
#Mann= 5 ,-1 , 0
  4284.5      .1       0  5001.5     .07       0  5007.5      .1       0
  5125.9     .16       0  5184.4      .1       0
Bank Sta=5001.5,5007.5
XS Rating Curve= 0 ,0
Exp/Cntr=0.3,0.1

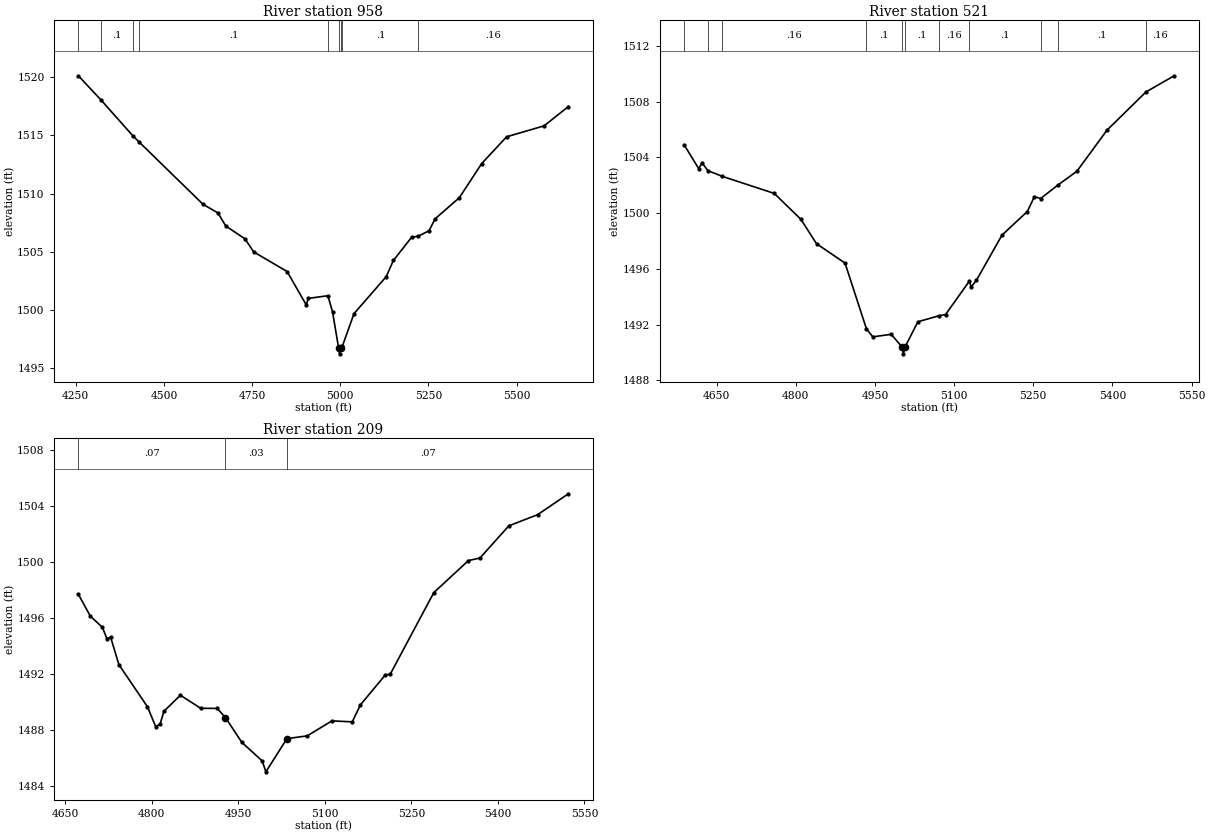
Type RM Length L Ch R = 1 ,958     ,437,437,437
BEGIN DESCRIPTION:
UNT002 IN NNOGR 2.0
END DESCRIPTION:
XS GIS Cut Line= 3
      2844614.54     10072673.61      2844440.93     10071675.36
      2844180.49     10071404.07
#Sta/Elev= 30
  4257.4 1520.11  4322.3 1518.01  4411.1 1514.98  4430.4  1514.4  4610.6 1509.08
  4653.1 1508.33  4675.3 1507.21  4729.9  1506.1  4754.6 1504.98  4849.2  1503.3
  4903.7 1500.42  4908.8 1500.99  4964.8 1501.22  4977.9 1499.85  4995.2 1496.73
    4998 1496.23  5001.2 1496.73  5005.8 1496.88  5038.8 1499.68  5130.2 1502.86
  5150.5 1504.25  5201.9 1506.23  5221.3 1506.34  5251.4  1506.8  5268.9 1507.83
  5337.2 1509.63  5400.8 1512.57  5471.5 1514.87  5577.8 1515.81  5646.7 1517.47
#Mann= 9 ,-1 , 0
  4257.4     .05       0  4322.3      .1       0  4411.1     .05       0
  4430.4      .1       0  4964.8     .05       0  4995.2    .035       0
  5001.2     .05       0  5005.8      .1       0  5221.3     .16       0
Bank Sta=4995.2,5001.2
XS Rating Curve= 0 ,0
Exp/Cntr=0.3,0.1

Type RM Length L Ch R = 1 ,521     ,312,312,312
BEGIN DESCRIPTION:
UNT002 IN NNOGR 1.0
END DESCRIPTION:
XS GIS Cut Line= 4
       2844886.1     10072120.76      2844939.47     10071872.11
      2844744.16     10071546.59      2844461.88     10071462.42
#Sta/Elev= 30
  4588.4  1504.9    4616 1503.19  4622.3  1503.6  4633.6 1503.04    4661 1502.63
  4759.2 1501.41  4809.7 1499.55  4839.3  1497.8  4893.3 1496.41  4933.7 1491.71
  4945.8 1491.12  4980.8  1491.3  5001.1  1490.4  5003.8  1489.9  5007.1  1490.4
  5031.3  1492.2  5071.1 1492.63  5083.8 1492.72  5128.7 1495.11  5132.4  1494.7
  5142.1 1495.17  5190.7 1498.42  5238.7 1500.11  5252.1 1501.18  5263.7 1501.04
    5297 1502.02  5332.6    1503  5389.9 1505.96  5463.5 1508.69  5516.9 1509.85
#Mann= 11 ,-1 , 0
  4588.4     .16       0  4633.6      .1       0    4661     .16       0
  4933.7      .1       0  5001.1     .07       0  5007.1      .1       0
  5071.1     .16       0  5128.7      .1       0  5263.7     .16       0
    5297      .1       0  5463.5     .16       0
Bank Sta=5001.1,5007.1
XS Rating Curve= 0 ,0
Exp/Cntr=0.3,0.1

Type RM Length L Ch R = 1 ,209     ,0,0,0
BEGIN DESCRIPTION:
UNT002 IN NNOGR 1.1
END DESCRIPTION:
XS GIS Cut Line= 3
      2845336.62     10071744.51      2844923.85     10071395.54
      2844615.23     10071389.03
#Sta/Elev= 30
    4673  1497.7  4693.8 1496.14  4714.7 1495.34  4722.4 1494.53    4729 1494.63
  4743.2 1492.68  4792.7 1489.67    4807 1488.25  4814.6 1488.43  4821.3 1489.35
  4849.8 1490.49    4885 1489.56  4913.6 1489.55  4927.8  1488.9  4956.4 1487.12
  4991.6  1485.8  4997.9 1485.02  5034.4 1487.39  5069.6 1487.59  5112.4 1488.66
  5147.6 1488.59  5161.9 1489.81  5204.7 1491.93  5213.5    1492  5288.9 1497.82
  5348.9 1500.11  5368.9 1500.29  5418.9 1502.59  5468.9 1503.39  5522.2 1504.88
#Mann= 3 , 0 , 0
    4673     .07       0  4927.8     .03       0  5034.4     .07       0
Bank Sta=4927.8,5034.4
XS Rating Curve= 0 ,0
Exp/Cntr=0.3,0.1

Chan Stop Cuts=-1
Use User Specified Reach Order=0
Composite Channel Slope=5