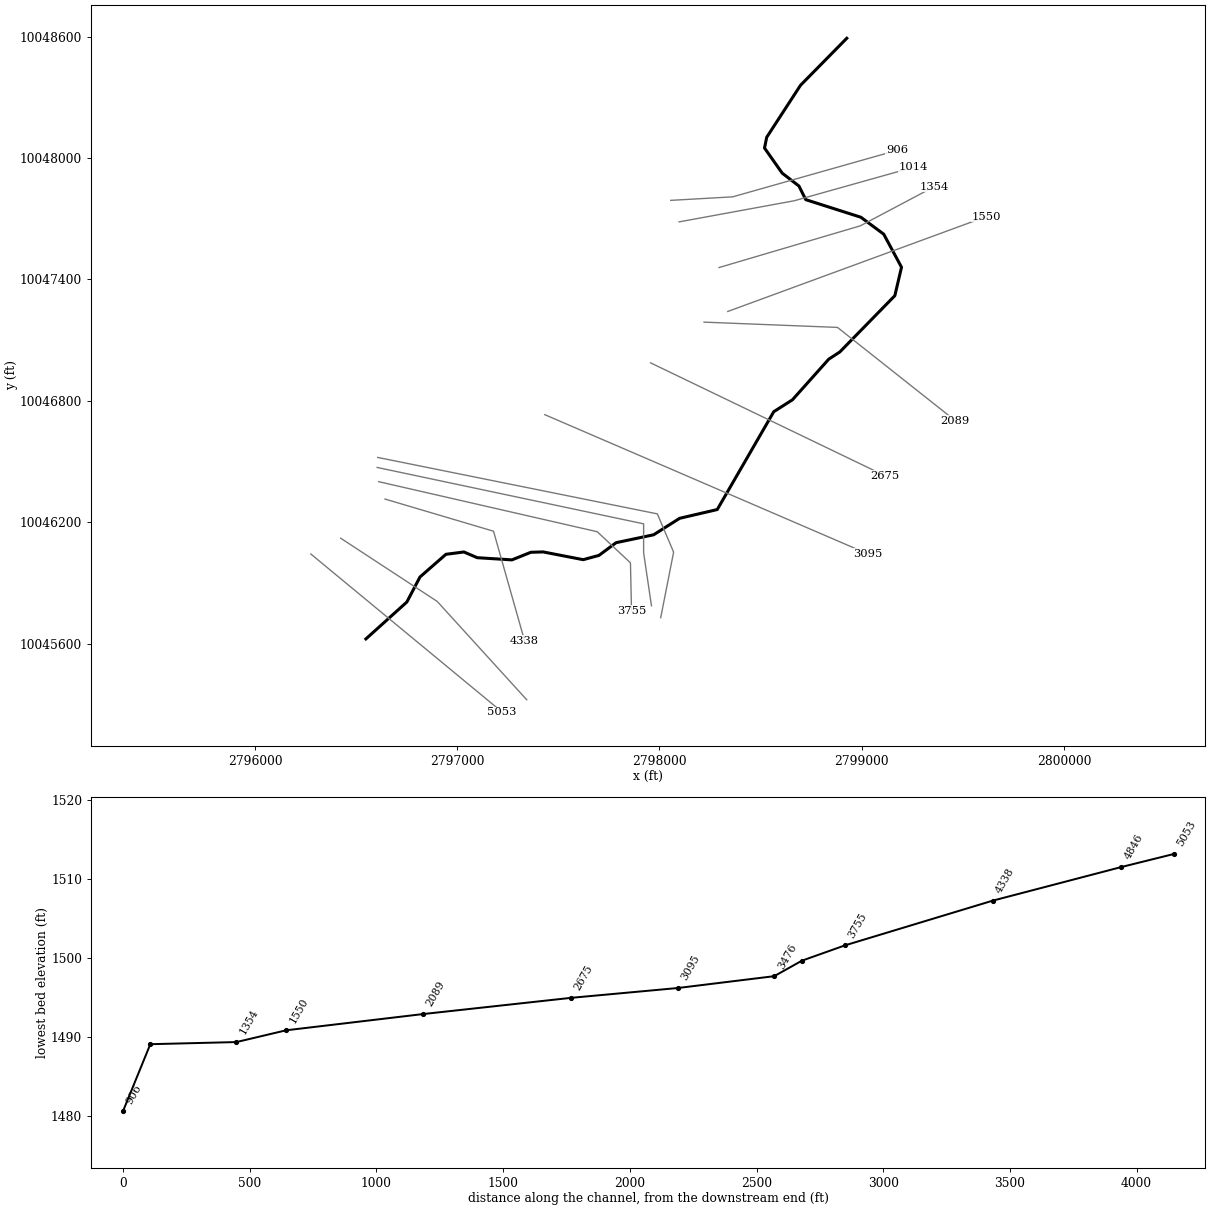
--- UNT002 IN SNOGR.prj (project) ---

Proj Title=UNT002 IN SNOGR Base Level Engineering
Current Plan=p01
Default Exp/Contr=0.3,0.1
English Units
Geom File=g01
Flow File=f01
Plan File=p01
Y Axis Title=Elevation
X Axis Title(PF)=Main Channel Distance
X Axis Title(XS)=Station
BEGIN DESCRIPTION:
UNT002 IN SNOGR
END DESCRIPTION:
DSS Export Rating Curves= 0
DSS Export Rating Curve Sorted= 0
DSS Export Volume Flow Curves= 0
DXF OffsetX= 0
DXF OffsetY= 0
DXF ScaleX= 1
DXF ScaleY= 10

--- UNT002 IN SNOGR.p01 (plan) ---

Plan Title=Multiple Run
Short Identifier=Multiple
Geom File=g01
Flow File=f01
Subcritical Flow
K Sum by GR= 0
Std Step Tol= 0.01
Critical Tol= 0.01
Num of Std Step Trials= 20
Max Error Tol= 0.3
Flow Tol Ratio= 0.001
Split Flow NTrial= 30
Split Flow Tol= 0.02
Split Flow Ratio= 0.02
Log Output Level= 0
Friction Slope Method= 1
Unsteady Friction Slope Method= 2
Unsteady Bridges Friction Slope Method= 1
Parabolic Critical Depth
Global Vel Dist=  1 , 1 , 1
Global Log Level= 0
CheckData=True
Encroach Param= -1, 0, 0, 0
BEGIN DESCRIPTION:
Multiple Run
END DESCRIPTION:

--- UNT002 IN SNOGR.f01 (steady flow) ---

Flow Title=Multiple
Number of Profiles=7
Profile Names=10-year,25-year,50-year,1pct_min,100-year,1pct_plu,500-year
River Rch & RM= UNT002 IN SNOGR,Reach-1,5053
     679     964    1205    1103    1492    2018    2296
River Rch & RM= UNT002 IN SNOGR,Reach-1,3585
     908    1305    1644    1514    2048    2770    3192
River Rch & RM= UNT002 IN SNOGR,Reach-1,906
    1181    1724    2198    2046    2767    3742    4408
Boundary for River Rch & Prof#=UNT002 IN SNOGR,Reach-1,1
Up Type=0
Dn Type=3
Dn Slope=0.005
Boundary for River Rch & Prof#=UNT002 IN SNOGR,Reach-1,2
Up Type=0
Dn Type=3
Dn Slope=0.005
Boundary for River Rch & Prof#=UNT002 IN SNOGR,Reach-1,3
Up Type=0
Dn Type=3
Dn Slope=0.005
Boundary for River Rch & Prof#=UNT002 IN SNOGR,Reach-1,4
Up Type=0
Dn Type=3
Dn Slope=0.005
Boundary for River Rch & Prof#=UNT002 IN SNOGR,Reach-1,5
Up Type=0
Dn Type=3
Dn Slope=0.005
Boundary for River Rch & Prof#=UNT002 IN SNOGR,Reach-1,6
Up Type=0
Dn Type=3
Dn Slope=0.005
Boundary for River Rch & Prof#=UNT002 IN SNOGR,Reach-1,7
Up Type=0
Dn Type=3
Dn Slope=0.005

--- UNT002 IN SNOGR.g01 (geometry) ---

Geom Title=Existing Conditions
Program Version=4.10

River Reach=UNT002 IN SNOGR ,Reach-1
Reach XY= 30
      2796548.47     10045623.73      2796750.88     10045805.98
      2796816.08       10045930.      2796944.25     10046041.91
      2797033.14     10046053.38      2797099.05     10046025.16
       2797270.7     10046014.36      2797364.03     10046051.84
      2797424.62     10046053.72      2797623.01     10046015.34
      2797700.92     10046036.51      2797785.58     10046099.27
      2797971.26     10046138.38      2798100.09      10046219.8
      2798285.89      10046263.1      2798565.37     10046746.67
      2798657.72     10046805.43      2798837.25     10047006.23
      2798891.68     10047041.61      2799164.03     10047319.92
      2799197.05     10047460.61      2799108.95     10047624.14
      2798996.13      10047707.5      2798723.54     10047794.49
      2798689.72     10047862.04      2798607.02     10047925.47
      2798519.65     10048049.58      2798530.38     10048102.75
      2798697.58     10048359.69      2798926.38       10048592.

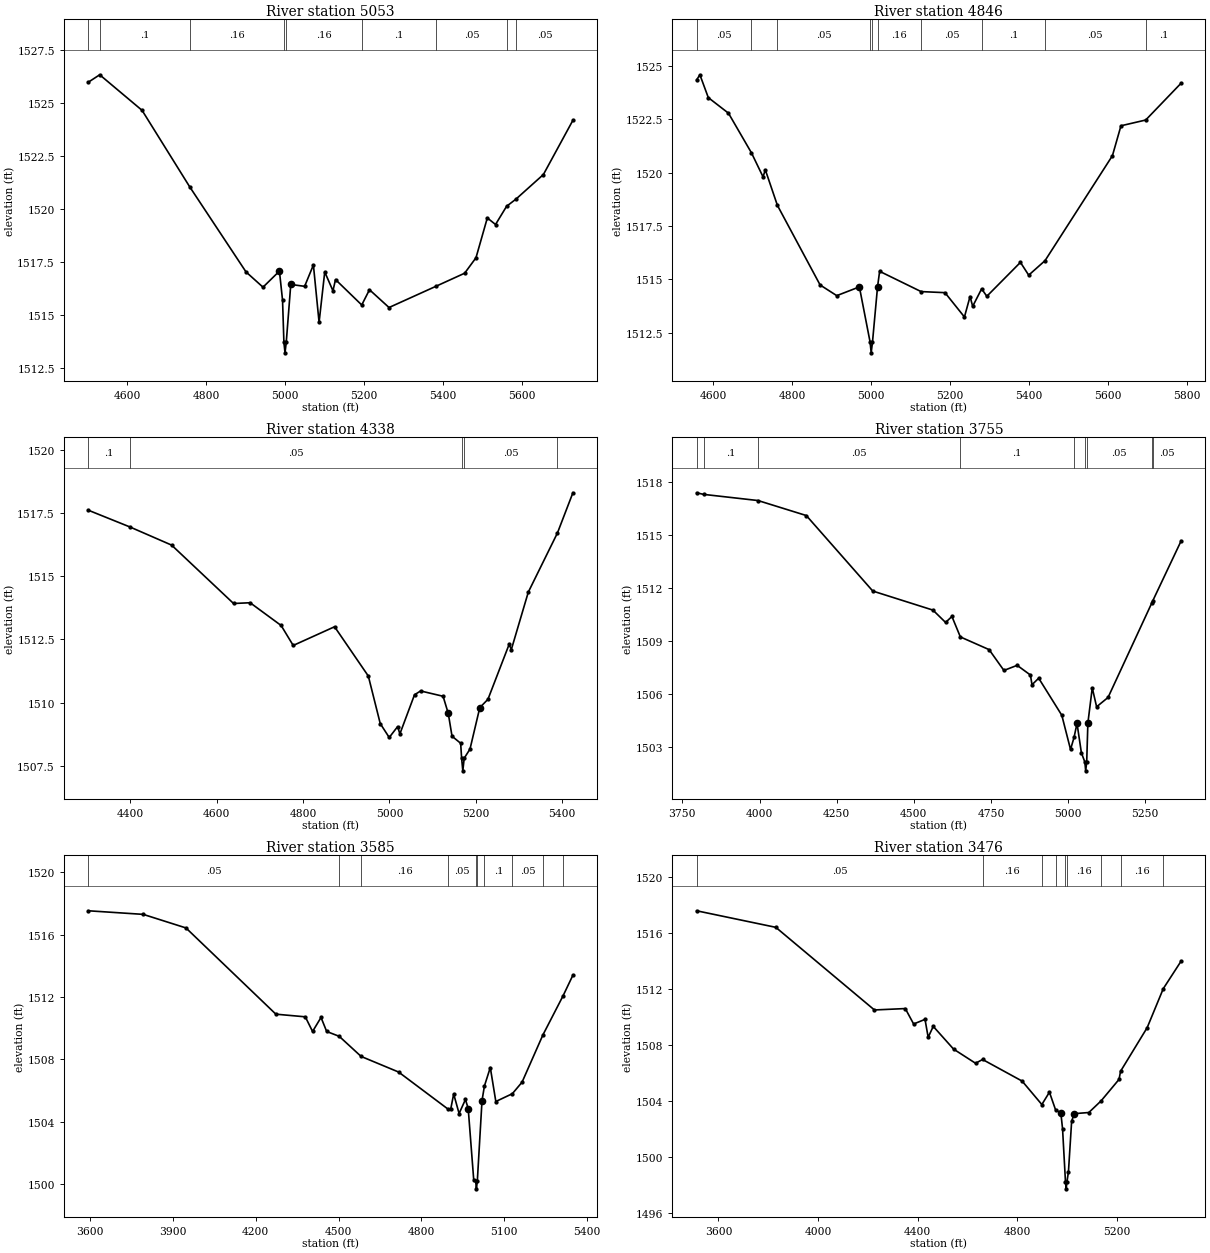
Type RM Length L Ch R = 1 ,5053    ,207,207,207
BEGIN DESCRIPTION:
UNT002 IN SNOGR 9.0
END DESCRIPTION:
XS GIS Cut Line= 2
      2796276.14     10046043.38       2797222.3     10045262.16
#Sta/Elev= 30
  4501.5 1525.99  4530.3 1526.34  4637.6 1524.66  4757.8 1521.06  4900.8 1517.03
  4943.8 1516.31  4985.4 1517.07  4993.3 1515.69  4996.7 1513.71  4999.5 1513.21
  5002.7 1513.71  5014.1 1516.44  5049.2 1516.35  5071.4 1517.36  5085.8 1514.65
  5100.1 1517.03  5120.9 1516.14  5127.4 1516.67  5193.8 1515.47  5213.4 1516.19
  5262.9 1515.35  5382.6 1516.36  5454.4 1516.97  5483.1  1517.7  5511.8 1519.58
  5532.6 1519.27  5560.6 1520.13  5584.4 1520.47  5653.8 1521.63  5728.5 1524.19
#Mann= 9 ,-1 , 0
  4501.5     .05       0  4530.3      .1       0  4757.8     .16       0
  4996.7     .07       0  5002.7     .16       0  5193.8      .1       0
  5382.6     .05       0  5560.6      .1       0  5584.4     .05       0
Bank Sta=4985.4,5014.1
XS Rating Curve= 0 ,0
Exp/Cntr=0.3,0.1

Type RM Length L Ch R = 1 ,4846    ,508,508,508
BEGIN DESCRIPTION:
Mapping XS ad7cfdd6
END DESCRIPTION:
XS GIS Cut Line= 3
      2796423.73      10046121.5      2796901.15     10045809.01
      2797343.66     10045323.11
#Sta/Elev= 30
  4558.4 1524.35  4566.7 1524.59    4588 1523.52  4639.1 1522.79  4697.4 1520.93
  4726.6 1519.81  4732.6 1520.13  4763.1 1518.47  4871.3 1514.74  4913.5 1514.24
  4970.8 1514.65    4998 1512.06  5000.7 1511.56    5004 1512.06  5016.8 1514.65
  5022.1 1515.38  5127.2 1514.43  5187.7 1514.38    5237 1513.24  5251.2  1514.2
  5257.9 1513.74  5280.6 1514.56  5293.7 1514.21  5378.9  1515.8  5399.8  1515.2
  5441.2 1515.88    5612  1520.8  5633.6  1522.2  5696.3 1522.47  5786.2  1524.2
#Mann= 10 ,-1 , 0
  4558.4     .05       0  4697.4      .1       0  4763.1     .05       0
    4998    .035       0    5004     .05       0  5016.8     .16       0
  5127.2     .05       0  5280.6      .1       0  5441.2     .05       0
  5696.3      .1       0
Bank Sta=4970.8,5016.8
XS Rating Curve= 0 ,0
Exp/Cntr=0.3,0.1

Type RM Length L Ch R = 1 ,4338    ,583,583,583
BEGIN DESCRIPTION:
UNT002 IN SNOGR 8.0
END DESCRIPTION:
XS GIS Cut Line= 3
      2796643.09     10046314.88      2797179.58     10046156.02
      2797333.21      10045614.4
#Sta/Elev= 30
  4302.4 1517.61  4398.4 1516.95  4495.3 1516.23  4638.8 1513.92  4677.2 1513.95
    4749 1513.05    4777 1512.26  4872.8    1513    4951 1511.05  4978.6 1509.17
  4999.4 1508.62  5018.9 1509.05  5024.1 1508.76    5058 1510.31  5072.2 1510.46
  5124.2 1510.25  5136.2 1509.57  5144.9 1508.67  5164.9 1508.39  5167.1  1507.8
  5169.9  1507.3  5173.1  1507.8  5186.5 1508.16  5209.2  1509.8  5228.1 1510.13
  5277.1  1512.3  5282.3  1512.1  5321.6 1514.37  5389.1 1516.71  5424.9  1518.3
#Mann= 5 ,-1 , 0
  4302.4      .1       0  4398.4     .05       0  5167.1    .035       0
  5173.1     .05       0  5389.1      .1       0
Bank Sta=5136.2,5209.2
XS Rating Curve= 0 ,0
Exp/Cntr=0.3,0.1

Type RM Length L Ch R = 1 ,3755    ,170,170,170
BEGIN DESCRIPTION:
Mapping XS 40ced6d7
END DESCRIPTION:
XS GIS Cut Line= 4
      2796611.91      10046400.8       2797692.6     10046153.41
      2797856.66     10045999.77      2797861.87     10045762.84
#Sta/Elev= 30
  3796.2  1517.4  3818.5 1517.31  3995.2 1516.96  4151.7 1516.11  4367.1 1511.83
  4562.1 1510.75  4603.1 1510.05  4623.6 1510.39  4650.9 1509.23  4744.1 1508.51
  4792.1 1507.33    4835 1507.62    4878 1507.07  4883.1 1506.52  4904.8 1506.89
  4979.7 1504.79    5008 1502.85  5019.3 1503.53    5029 1504.33  5043.2 1502.66
  5054.4 1502.14  5057.1 1501.64  5060.4 1502.14  5064.2 1504.35  5078.4 1506.34
  5092.5 1505.27  5129.6  1505.8  5271.8 1511.17  5274.3 1511.27  5366.6 1514.68
#Mann= 9 ,-1 , 0
  3796.2     .05       0  3818.5      .1       0  3995.2     .05       0
  4650.9      .1       0  5019.3     .05       0  5054.4     .07       0
  5060.4     .05       0  5271.8      .1       0  5274.3     .05       0
Bank Sta=5029,5064.2
XS Rating Curve= 0 ,0
Exp/Cntr=0.3,0.1

Type RM Length L Ch R = 1 ,3585    ,109,109,109
BEGIN DESCRIPTION:
Mapping XS 876670e2
END DESCRIPTION:
XS GIS Cut Line= 4
      2796604.07     10046471.12      2797921.77     10046192.47
      2797921.77     10046049.25      2797960.64     10045787.48
#Sta/Elev= 30
    3594 1517.53  3792.7  1517.3  3947.5 1516.43  4273.1  1510.9  4379.7 1510.73
    4406 1509.79  4436.6 1510.69  4457.1 1509.79  4502.5 1509.48  4581.8 1508.19
  4717.5 1507.19  4897.5  1504.8  4906.1  1504.8    4917 1505.78  4936.6 1504.53
  4959.6 1505.43  4969.6 1504.85  4989.6 1500.27  4996.6  1500.2  4999.3  1499.7
  5002.6  1500.2  5019.6 1505.36  5028.4  1506.3  5049.6 1507.48  5069.6  1505.3
  5129.4  1505.8  5164.6 1506.54  5240.1 1509.57  5313.2 1512.08  5348.7  1513.4
#Mann= 10 ,-1 , 0
    3594     .05       0  4502.5      .1       0  4581.8     .16       0
  4897.5     .05       0  4996.6    .035       0  5002.6     .05       0
  5028.4      .1       0  5129.4     .05       0  5240.1      .1       0
  5313.2     .05       0
Bank Sta=4969.6,5019.6
XS Rating Curve= 0 ,0
Exp/Cntr=0.3,0.1

Type RM Length L Ch R = 1 ,3476    ,381,381,381
BEGIN DESCRIPTION:
Mapping XS 42e29a39
END DESCRIPTION:
XS GIS Cut Line= 4
      2796606.77     10046520.64      2797989.73     10046241.68
       2798070.1     10046052.56      2798006.28      10045728.7
#Sta/Elev= 30
  3512.3 1517.56  3830.4 1516.38  4226.5 1510.49  4350.5 1510.59    4384 1509.49
  4429.7 1509.82  4442.4 1508.54  4462.8 1509.32  4544.4  1507.7  4632.8 1506.69
    4661 1506.96  4819.8 1505.42    4899 1503.75  4929.5 1504.63  4954.7 1503.34
  4975.2 1503.17  4982.2 1502.02  4993.9 1498.24  4996.7 1497.74  4999.9 1498.24
  5005.9 1498.97  5018.7 1502.57  5029.5  1503.1  5087.7 1503.18    5137 1504.01
    5209 1505.54  5215.2 1506.12  5322.1 1509.23  5386.8 1512.01  5458.7 1513.98
#Mann= 9 ,-1 , 0
  3512.3     .05       0    4661     .16       0    4899     .05       0
  4954.7     .16       0  4993.9     .07       0  4999.9     .16       0
    5137      .1       0  5215.2     .16       0  5386.8      .1       0
Bank Sta=4975.2,5029.5
XS Rating Curve= 0 ,0
Exp/Cntr=0.3,0.1

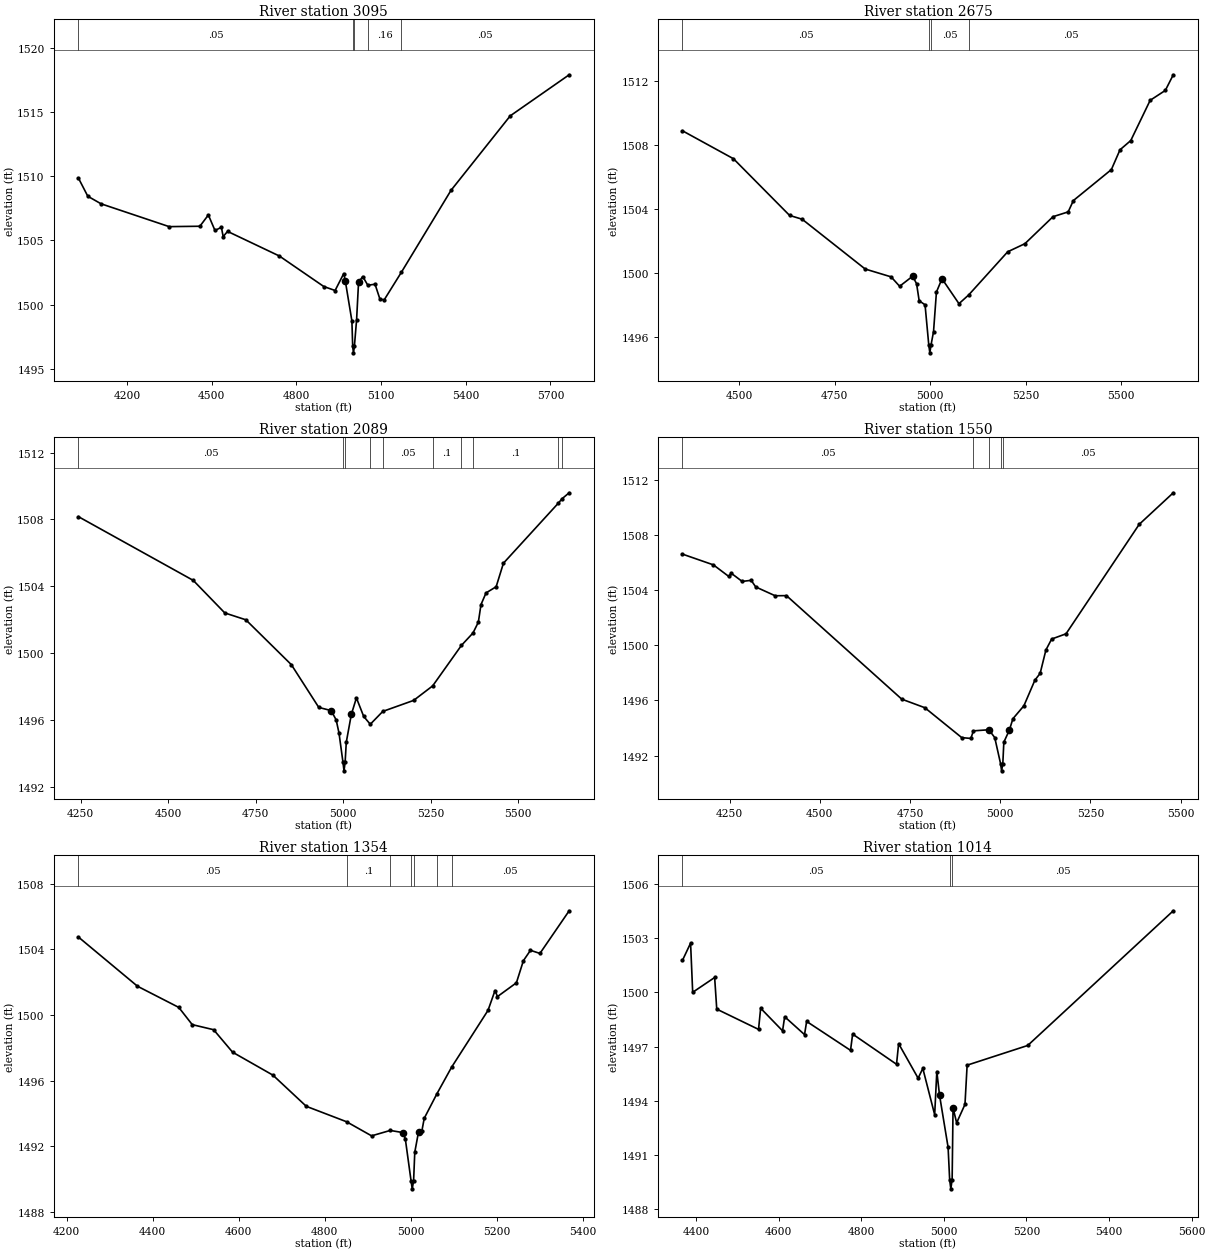
Type RM Length L Ch R = 1 ,3095    ,420,420,420
BEGIN DESCRIPTION:
UNT002 IN SNOGR 7.0
END DESCRIPTION:
XS GIS Cut Line= 2
      2797433.08     10046731.96      2799030.23     10046044.05
#Sta/Elev= 30
  4027.4 1509.87  4060.7 1508.45  4107.7 1507.86    4349 1506.08  4457.9 1506.11
  4487.9 1506.99  4511.4 1505.78  4534.1 1506.03  4540.4  1505.3  4555.9 1505.71
  4739.5 1503.79    4897 1501.41    4937  1501.1  4967.6 1502.42    4973 1501.87
  4996.5 1498.73  4999.3 1496.74  5002.1 1496.24  5005.3 1496.74  5013.2 1498.83
  5020.1 1501.75    5035 1502.19  5052.9 1501.51  5078.5 1501.59  5096.1 1500.41
  5111.2 1500.38  5171.5 1502.51  5347.7 1508.91  5557.7 1514.72  5766.4 1517.92
#Mann= 5 ,-1 , 0
  4027.4     .05       0  4999.3    .035       0  5005.3     .05       0
  5052.9     .16       0  5171.5     .05       0
Bank Sta=4973,5020.1
XS Rating Curve= 0 ,0
Exp/Cntr=0.3,0.1

Type RM Length L Ch R = 1 ,2675    ,586,586,586
BEGIN DESCRIPTION:
UNT002 IN SNOGR 6.0
END DESCRIPTION:
XS GIS Cut Line= 2
       2797956.1     10046988.03      2799114.16     10046430.68
#Sta/Elev= 30
  4351.6 1508.91  4485.1 1507.16    4632 1503.61    4665 1503.37  4830.1 1500.25
  4897.9 1499.76  4920.2 1499.17  4954.3  1499.8  4964.6 1499.33  4971.4 1498.26
  4986.8 1498.01  4996.5  1495.5  4999.3    1495  5002.5  1495.5    5009 1496.33
  5016.6 1498.81  5031.2 1499.64  5075.6 1498.08  5101.2 1498.63  5203.2 1501.33
  5248.4 1501.84  5321.9 1503.53  5361.6 1503.83  5375.2 1504.54  5474.7 1506.48
  5497.3 1507.72  5525.5  1508.3  5576.3 1510.82    5616 1511.44  5636.8 1512.42
#Mann= 4 ,-1 , 0
  4351.6     .05       0  4996.5     .07       0  5002.5     .05       0
  5101.2     .05       0
Bank Sta=4954.3,5031.2
XS Rating Curve= 0 ,0
Exp/Cntr=0.3,0.1

Type RM Length L Ch R = 1 ,2089    ,539,539,539
BEGIN DESCRIPTION:
UNT002 IN SNOGR 5.0
END DESCRIPTION:
XS GIS Cut Line= 3
      2798220.59     10047189.22      2798880.31     10047163.17
      2799461.91     10046703.11
#Sta/Elev= 30
  4243.5 1508.17  4571.6 1504.35  4661.7  1502.4  4721.7 1501.99  4851.8  1499.3
  4930.1 1496.74  4965.4 1496.55  4979.8 1495.99  4987.9  1495.2  4999.3 1493.44
  5002.1 1492.94  5005.3 1493.44  5008.7 1494.66  5023.1 1496.32  5037.6 1497.31
  5058.4  1496.2  5077.2 1495.73  5112.9  1496.5    5201 1497.16  5255.4 1498.03
  5337.7 1500.46  5370.6  1501.2  5385.9 1501.85  5393.4  1502.9  5407.8  1503.6
  5436.7 1503.97  5457.5 1505.38  5614.4 1508.98  5625.3 1509.25  5645.3  1509.6
#Mann= 10 ,-1 , 0
  4243.5     .05       0  4999.3    .035       0  5005.3     .05       0
  5077.2      .1       0  5112.9     .05       0  5255.4      .1       0
  5337.7     .05       0  5370.6      .1       0  5614.4     .05       0
  5625.3      .1       0
Bank Sta=4965.4,5023.1
XS Rating Curve= 0 ,0
Exp/Cntr=0.3,0.1

Type RM Length L Ch R = 1 ,1550    ,196,196,196
BEGIN DESCRIPTION:
UNT002 IN SNOGR 4.0
END DESCRIPTION:
XS GIS Cut Line= 2
      2798337.99     10047241.95      2799614.84      10047710.2
#Sta/Elev= 30
  4119.4 1506.61  4205.1 1505.83  4247.7 1504.99  4254.2 1505.23  4284.7 1504.63
  4309.8 1504.71  4322.3 1504.23  4376.2 1503.59  4407.5  1503.6    4727 1496.09
  4790.9 1495.47  4893.2  1493.3  4918.4 1493.24  4925.7 1493.79  4968.5 1493.87
  4984.7  1493.3    5001 1491.39  5003.7 1490.89    5007 1491.39  5009.9 1492.97
  5025.3 1493.85    5035 1494.67  5065.5 1495.61    5096 1497.47  5110.5 1497.96
  5126.5 1499.66  5142.4 1500.45  5182.2 1500.83    5385 1508.77  5479.4 1511.06
#Mann= 5 ,-1 , 0
  4119.4     .05       0  4925.7      .1       0  4968.5     .05       0
    5001    .035       0    5007     .05       0
Bank Sta=4968.5,5025.3
XS Rating Curve= 0 ,0
Exp/Cntr=0.3,0.1

Type RM Length L Ch R = 1 ,1354    ,340,340,340
BEGIN DESCRIPTION:
UNT002 IN SNOGR 3.0
END DESCRIPTION:
XS GIS Cut Line= 3
      2798294.63     10047458.98      2798993.38     10047665.13
      2799357.95     10047858.27
#Sta/Elev= 30
  4227.1 1504.75  4364.5 1501.75  4460.5 1500.46  4491.8 1499.41  4541.5  1499.1
  4585.6 1497.73  4679.4 1496.33    4757 1494.43  4850.6 1493.49  4908.8 1492.63
  4952.1 1492.96  4981.5 1492.83  4987.2 1492.45  5000.5  1489.9  5003.3  1489.4
  5006.5  1489.9  5009.2 1491.63    5018 1492.88  5025.5  1492.9  5031.2  1493.7
    5061 1495.21  5094.7 1496.81  5179.5 1500.28  5195.8 1501.49  5201.5 1501.12
  5245.5 1501.96  5261.8 1503.31  5278.2 1503.94  5300.2 1503.75  5368.2 1506.35
#Mann= 7 ,-1 , 0
  4227.1     .05       0  4850.6      .1       0  4952.1     .05       0
  5000.5    .035       0  5006.5     .05       0    5061      .1       0
  5094.7     .05       0
Bank Sta=4981.5,5018
XS Rating Curve= 0 ,0
Exp/Cntr=0.3,0.1

Type RM Length L Ch R = 1 ,1014    ,108,108,108
BEGIN DESCRIPTION:
Mapping XS 151a6ba7
END DESCRIPTION:
XS GIS Cut Line= 3
      2798097.09     10047684.66      2798665.69     10047788.83
      2799253.64     10047953.72
#Sta/Elev= 30
  4366.8 1501.77  4386.4 1502.72  4391.5    1500  4444.7 1500.82  4449.8 1499.07
    4551 1497.95  4556.1 1499.12  4609.2 1497.87  4614.3 1498.65  4662.4 1497.66
  4667.5 1498.39  4773.8 1496.79  4778.9 1497.69  4885.2 1496.02  4890.3 1497.16
  4937.5 1495.25  4948.9 1495.79  4977.6 1493.23  4982.8 1495.62  4989.3 1494.32
  5010.1 1491.43  5013.9 1489.63  5016.7 1489.13  5019.9 1489.63  5022.1 1493.61
  5030.8 1492.78    5051  1493.8  5056.2 1495.97    5203 1497.06  5555.5 1504.51
#Mann= 3 ,-1 , 0
  4366.8     .05       0  5013.9     .04       0  5019.9     .05       0
Bank Sta=4989.3,5022.1
XS Rating Curve= 0 ,0
Exp/Cntr=0.3,0.1

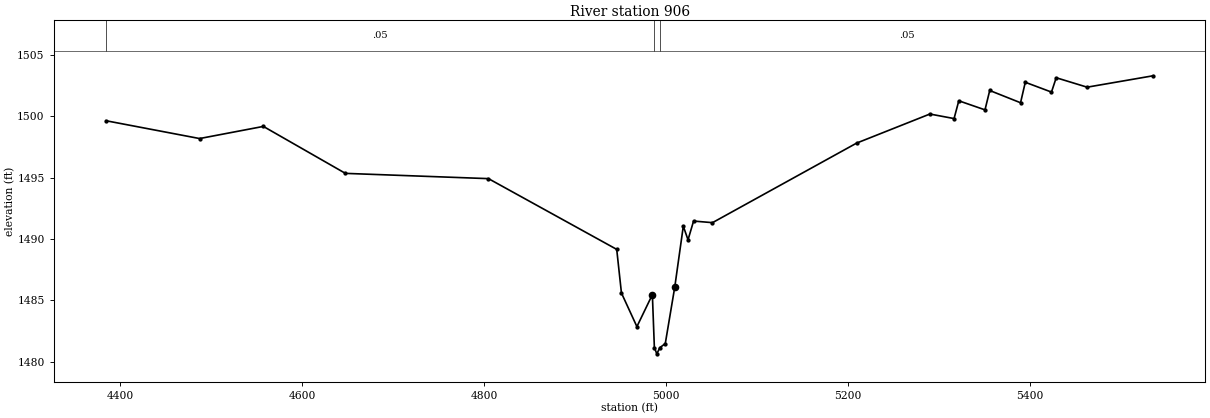
Type RM Length L Ch R = 1 ,906     ,0,0,0
BEGIN DESCRIPTION:
Mapping XS 52b4258c
END DESCRIPTION:
XS GIS Cut Line= 3
      2798055.92       10047791.      2798361.87     10047808.36
      2799174.58     10048038.09
#Sta/Elev= 30
  4384.4 1499.64  4487.1 1498.19  4557.2 1499.18  4647.4 1495.35  4804.7 1494.92
  4945.7 1489.15  4950.9 1485.59  4967.9 1482.85  4984.9 1485.46  4987.1 1481.13
  4989.8 1480.63  4993.1 1481.13  4999.1 1481.47  5009.5 1486.07  5018.9 1491.04
  5024.1 1489.93  5030.2 1491.46    5051 1491.33  5209.5 1497.82    5290 1500.19
  5316.6 1499.82  5321.8 1501.27  5350.6 1500.53  5355.8 1502.11  5389.7 1501.11
  5394.9 1502.78  5423.7 1501.98  5428.9 1503.15  5462.9 1502.38  5535.4 1503.31
#Mann= 3 ,-1 , 0
  4384.4     .05       0  4987.1     .04       0  4993.1     .05       0
Bank Sta=4984.9,5009.5
XS Rating Curve= 0 ,0
Exp/Cntr=0.3,0.1

Chan Stop Cuts=-1
Use User Specified Reach Order=0
Composite Channel Slope=5