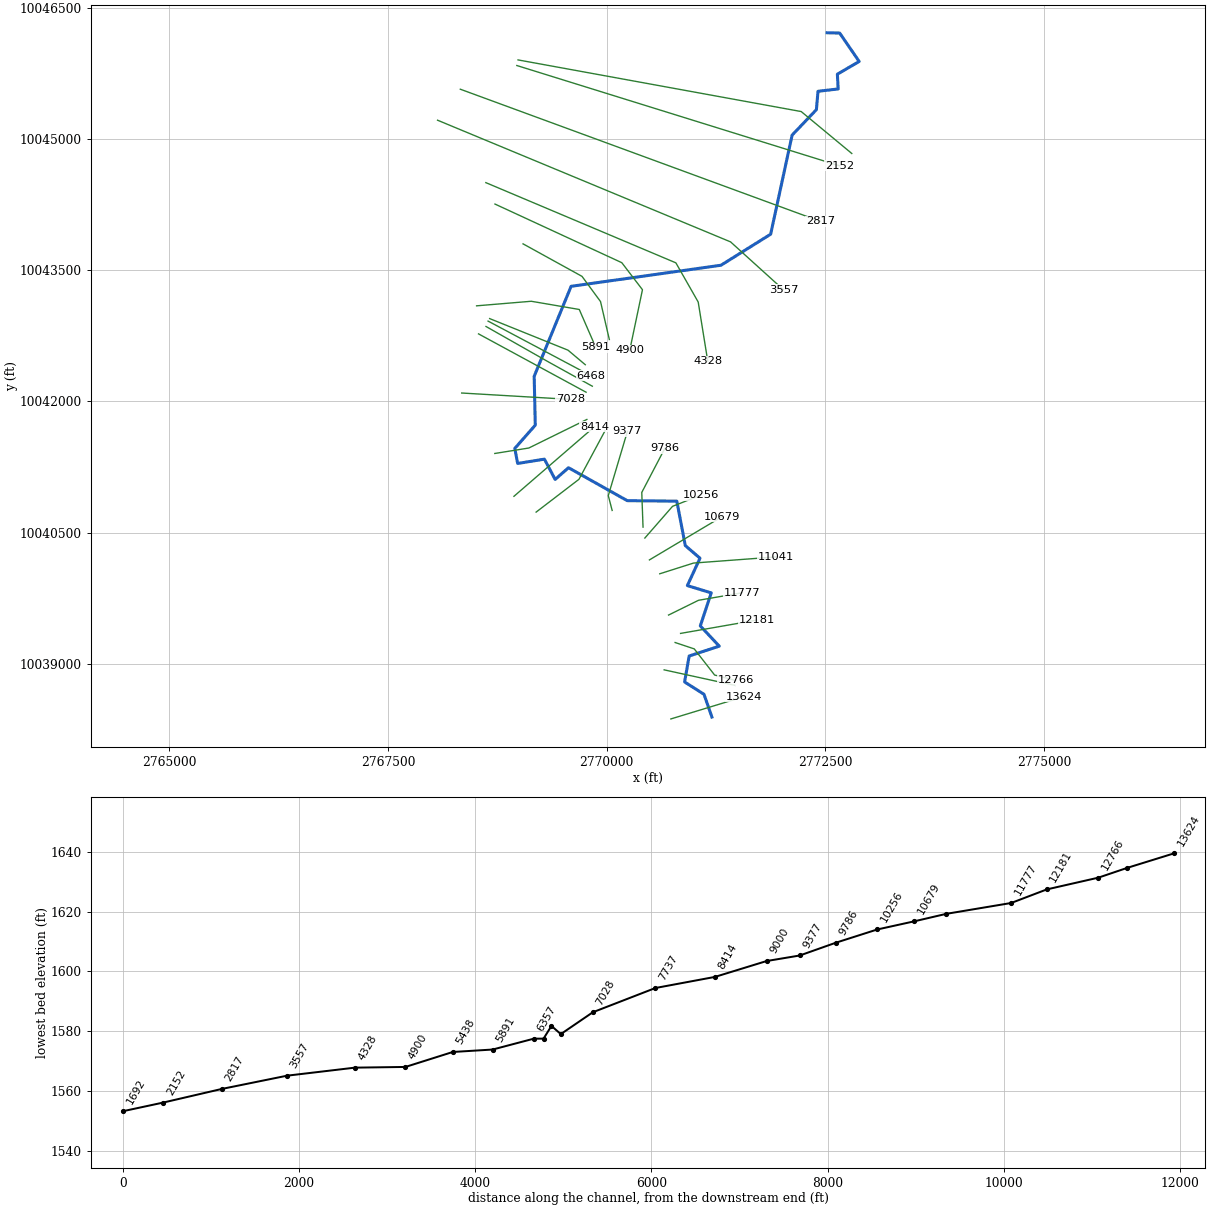
--- UNT003 IN SNOGR.prj (project) ---

Proj Title=UNT003 IN SNOGR Base Level Engineering
Current Plan=p01
Default Exp/Contr=0.3,0.1
English Units
Geom File=g01
Flow File=f01
Plan File=p01
Y Axis Title=Elevation
X Axis Title(PF)=Main Channel Distance
X Axis Title(XS)=Station
BEGIN DESCRIPTION:
UNT003 IN SNOGR
END DESCRIPTION:
DSS Export Rating Curves= 0
DSS Export Rating Curve Sorted= 0
DSS Export Volume Flow Curves= 0
DXF OffsetX= 0
DXF OffsetY= 0
DXF ScaleX= 1
DXF ScaleY= 10

--- UNT003 IN SNOGR.p01 (plan) ---

Plan Title=Multiple Run
Short Identifier=Multiple
Geom File=g01
Flow File=f01
Subcritical Flow
K Sum by GR= 0
Std Step Tol= 0.01
Critical Tol= 0.01
Num of Std Step Trials= 20
Max Error Tol= 0.3
Flow Tol Ratio= 0.001
Split Flow NTrial= 30
Split Flow Tol= 0.02
Split Flow Ratio= 0.02
Log Output Level= 0
Friction Slope Method= 1
Unsteady Friction Slope Method= 2
Unsteady Bridges Friction Slope Method= 1
Parabolic Critical Depth
Global Vel Dist=  1 , 1 , 1
Global Log Level= 0
CheckData=True
Encroach Param= -1, 0, 0, 0
BEGIN DESCRIPTION:
Multiple Run
END DESCRIPTION:

--- UNT003 IN SNOGR.f01 (steady flow) ---

Flow Title=Multiple
Program Version=4.10
Number of Profiles= 7
Profile Names=10-year,25-year,50-year,1pct_min,100-year,1pct_plu,500-year
River Rch & RM=UNT003 IN SNOGR,Reach-1         ,13624
     851    1242    1584    1481    2003    2708    3211
River Rch & RM=UNT003 IN SNOGR,Reach-1         ,10256
    1277    1895    2443    2302    3114    4211    5081
River Rch & RM=UNT003 IN SNOGR,Reach-1         ,2817
    1634    2451    3182    3017    4080    5518    6744
Boundary for River Rch & Prof#=UNT003 IN SNOGR,Reach-1         , 1
Up Type= 0
Dn Type= 3
Dn Slope=0.00644
Boundary for River Rch & Prof#=UNT003 IN SNOGR,Reach-1         , 2
Up Type= 0
Dn Type= 3
Dn Slope=0.00644
Boundary for River Rch & Prof#=UNT003 IN SNOGR,Reach-1         , 3
Up Type= 0
Dn Type= 3
Dn Slope=0.00644
Boundary for River Rch & Prof#=UNT003 IN SNOGR,Reach-1         , 4
Up Type= 0
Dn Type= 3
Dn Slope=0.00644
Boundary for River Rch & Prof#=UNT003 IN SNOGR,Reach-1         , 5
Up Type= 0
Dn Type= 3
Dn Slope=0.00644
Boundary for River Rch & Prof#=UNT003 IN SNOGR,Reach-1         , 6
Up Type= 0
Dn Type= 3
Dn Slope=0.00644
Boundary for River Rch & Prof#=UNT003 IN SNOGR,Reach-1         , 7
Up Type= 0
Dn Type= 3
Dn Slope=0.00644
DSS Import GetInterval= 0
DSS Import GetPeak= 0
DSS Import FillOption= 0

--- UNT003 IN SNOGR.g01 (geometry) ---

Geom Title=Existing Conditions
Program Version=4.10

River Reach=UNT003 IN SNOGR ,Reach-1
Reach XY= 30
      2771201.71     10038392.66      2771111.28     10038652.98
       2770889.6     10038793.74      2770941.88     10039090.44
      2771285.98     10039203.06      2771069.07     10039434.32
      2771194.13     10039812.03       2770921.2     10039895.06
       2771065.5     10040208.22      2770897.55     10040352.47
      2770800.77     10040860.36      2770234.36      10040865.9
      2769562.77     10041242.64      2769410.18     10041108.45
      2769287.44     10041340.49      2768981.55     10041291.02
      2768949.26     10041463.42      2769183.15     10041729.09
      2769170.34     10042287.13      2769592.56     10043315.76
      2771305.54     10043556.63      2771873.24     10043911.36
      2772118.47     10045043.73      2772395.91     10045334.79
      2772414.48     10045544.83      2772644.86     10045571.52
      2772635.82     10045740.29      2772884.79     10045885.53
      2772662.23     10046210.11      2772518.47     10046213.73

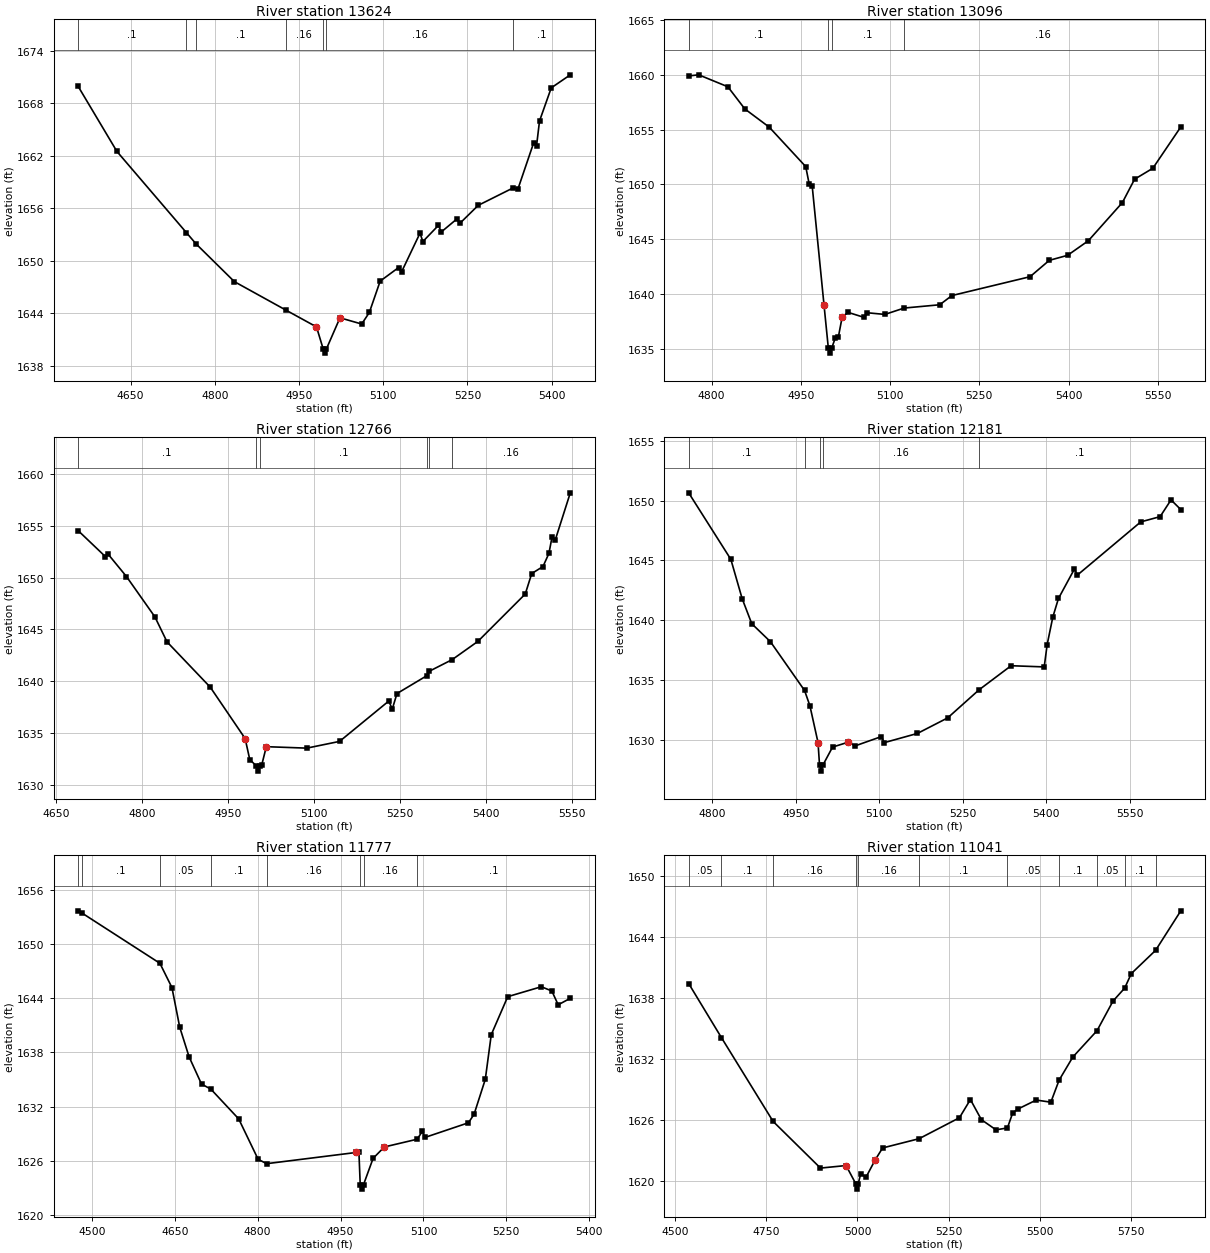
Type RM Length L Ch R = 1 ,13624   ,528,528,528
BEGIN DESCRIPTION:
UNT003 IN SNOGR 25.0
END DESCRIPTION:
XS GIS Cut Line= 2
      2770732.34     10038371.08      2771570.86     10038626.28
#Sta/Elev= 30
  4556.6 1669.96  4625.7 1662.51  4749.2 1653.24  4766.4 1651.95  4834.8 1647.62
  4926.1 1644.38  4981.1 1642.44  4992.9 1639.94  4995.7 1639.44  4998.9 1639.94
  5022.9 1643.48  5061.6 1642.77  5075.2 1644.09  5094.5 1647.68  5127.3 1649.23
  5132.5 1648.72  5165.4 1653.16  5170.6 1652.21  5198.2 1654.05  5203.5 1653.31
  5231.1 1654.79  5236.3 1654.28  5269.2 1656.35  5330.3 1658.31  5340.1 1658.26
  5367.7 1663.47    5373 1663.16  5378.3    1666  5399.2 1669.79  5433.1 1671.28
#Mann= 7 ,-1 , 0
  4556.6      .1       0  4749.2     .05       0  4766.4      .1       0
  4926.1     .16       0  4992.9     .07       0  4998.9     .16       0
  5330.3      .1       0
Bank Sta=4981.1,5022.9
XS Rating Curve= 0 ,0
Exp/Cntr=0.3,0.1

Type RM Length L Ch R = 1 ,13096   ,330,330,330
BEGIN DESCRIPTION:
UNT003 IN SNOGR 24.0
END DESCRIPTION:
XS GIS Cut Line= 2
      2770656.24      10038932.2      2771464.41     10038755.31
#Sta/Elev= 30
  4761.4  1659.9  4778.3    1660  4827.3 1658.91  4855.8 1656.89  4896.8 1655.23
  4958.2 1651.63    4964 1650.04  4969.1 1649.83  4988.9 1639.02  4996.1 1635.12
  4998.9 1634.62  5002.1 1635.12  5007.8 1635.99    5013 1636.08  5019.6 1637.96
  5029.8 1638.33  5056.8 1637.87  5061.9  1638.3  5091.2 1638.15  5123.6 1638.73
  5183.4 1639.03  5203.9 1639.87  5335.3 1641.59  5367.6 1643.08  5398.4 1643.54
  5433.3 1644.87  5490.5 1648.35    5511 1650.48  5541.7 1651.48  5588.7 1655.25
#Mann= 4 ,-1 , 0
  4761.4      .1       0  4996.1     .07       0  5002.1      .1       0
  5123.6     .16       0
Bank Sta=4988.9,5019.6
XS Rating Curve= 0 ,0
Exp/Cntr=0.3,0.1

Type RM Length L Ch R = 1 ,12766   ,585,585,585
BEGIN DESCRIPTION:
UNT003 IN SNOGR 23.0
END DESCRIPTION:
XS GIS Cut Line= 4
      2770781.32     10039244.68      2771000.03     10039171.78
      2771232.66     10038873.17      2771474.62     10038810.95
#Sta/Elev= 30
  4688.4 1654.54  4735.8 1652.04  4741.1 1652.24  4772.7 1650.11  4822.4 1646.21
  4843.5  1643.8  4918.9 1639.43  4979.8 1634.47  4987.9 1632.44  4999.4 1631.82
  5002.1 1631.32  5005.4 1631.82  5008.7 1631.89  5016.8 1633.68  5087.4 1633.54
  5144.6 1634.19  5230.4 1638.08  5236.7 1637.32  5244.8 1638.81  5297.1 1640.54
  5301.1 1640.96  5341.3 1642.09  5386.1 1643.85  5468.7 1648.42    5480  1650.4
  5499.6 1651.07    5510 1652.34  5515.6 1653.97  5520.8 1653.59  5547.3 1658.19
#Mann= 6 ,-1 , 0
  4688.4      .1       0  4999.4     .07       0  5005.4      .1       0
  5297.1     .16       0  5301.1      .1       0  5341.3     .16       0
Bank Sta=4979.8,5016.8
XS Rating Curve= 0 ,0
Exp/Cntr=0.3,0.1

Type RM Length L Ch R = 1 ,12181   ,404,404,404
BEGIN DESCRIPTION:
UNT003 IN SNOGR 22.0
END DESCRIPTION:
XS GIS Cut Line= 2
      2770843.77     10039348.86      2771715.08       10039501.
#Sta/Elev= 30
  4757.6 1650.65  4833.4 1645.09  4853.7 1641.81    4871 1639.71  4904.5 1638.21
  4965.9 1634.13  4975.5 1632.85  4990.1 1629.78  4992.8 1627.89  4995.6 1627.39
  4998.8 1627.89  5016.2  1629.4  5044.5 1629.81  5056.8  1629.5  5104.1 1630.28
  5109.1 1629.77  5168.7 1630.54  5223.1 1631.84  5279.6 1634.19  5337.1  1636.2
  5396.6  1636.1  5401.9 1637.97  5412.1 1640.27  5422.2 1641.82    5451 1644.29
  5456.1 1643.77  5570.1 1648.22  5604.9 1648.66  5624.5 1650.06  5642.1 1649.25
#Mann= 5 ,-1 , 0
  4757.6      .1       0  4965.9     .16       0  4992.8     .07       0
  4998.8     .16       0  5279.6      .1       0
Bank Sta=4990.1,5044.5
XS Rating Curve= 0 ,0
Exp/Cntr=0.3,0.1

Type RM Length L Ch R = 1 ,11777   ,736,736,736
BEGIN DESCRIPTION:
UNT003 IN SNOGR 21.0
END DESCRIPTION:
XS GIS Cut Line= 3
      2770706.29     10039558.58      2771048.64     10039727.33
      2771550.06     10039813.79
#Sta/Elev= 30
  4475.2 1653.68  4482.5 1653.42  4623.1 1647.87  4644.9 1645.18    4659 1640.79
  4675.9 1637.51  4698.4 1634.49  4715.3 1633.93  4765.7 1630.63  4800.9 1626.15
  4816.3 1625.67  4978.1 1626.91  4983.2 1626.99  4985.6 1623.35  4988.4 1622.85
  4991.6 1623.35  5008.9 1626.26  5029.2 1627.52  5088.7 1628.38  5097.8 1629.24
  5102.9 1628.58  5181.4  1630.2  5191.6 1631.14  5211.9 1635.01  5222.7 1639.96
  5252.5 1644.17  5313.3 1645.27  5332.3  1644.8  5343.8 1643.27  5365.7 1643.99
#Mann= 8 ,-1 , 0
  4475.2     .05       0  4482.5      .1       0  4623.1     .05       0
  4715.3      .1       0  4816.3     .16       0  4985.6     .07       0
  4991.6     .16       0  5088.7      .1       0
Bank Sta=4978.1,5029.2
XS Rating Curve= 0 ,0
Exp/Cntr=0.3,0.1

Type RM Length L Ch R = 1 ,11041   ,362,362,362
BEGIN DESCRIPTION:
UNT003 IN SNOGR 20.0
END DESCRIPTION:
XS GIS Cut Line= 3
      2770605.95     10040030.29      2770991.35     10040152.68
      2771933.77     10040222.97
#Sta/Elev= 30
  4537.2 1639.44  4627.2 1634.11  4768.7 1625.88  4898.6 1621.29  4968.8 1621.54
  4995.8 1619.72  4998.6 1619.22  5001.8 1619.72  5008.9 1620.72  5023.4 1620.39
    5049 1622.12    5069 1623.27    5169 1624.18  5279.6 1626.24  5309.7 1628.03
  5339.8 1626.05  5379.9 1625.05  5411.2 1625.24  5425.6 1626.71  5440.1  1627.1
  5490.2 1627.98  5530.3 1627.77  5552.8 1629.93  5590.5 1632.21  5656.8  1634.8
  5700.8 1637.72  5732.7 1638.99  5750.9 1640.42  5817.4  1642.7  5886.6 1646.59
#Mann= 11 ,-1 , 0
  4537.2     .05       0  4627.2      .1       0  4768.7     .16       0
  4995.8     .07       0  5001.8     .16       0    5169      .1       0
  5411.2     .05       0  5552.8      .1       0  5656.8     .05       0
  5732.7      .1       0  5817.4     .05       0
Bank Sta=4968.8,5049
XS Rating Curve= 0 ,0
Exp/Cntr=0.3,0.1

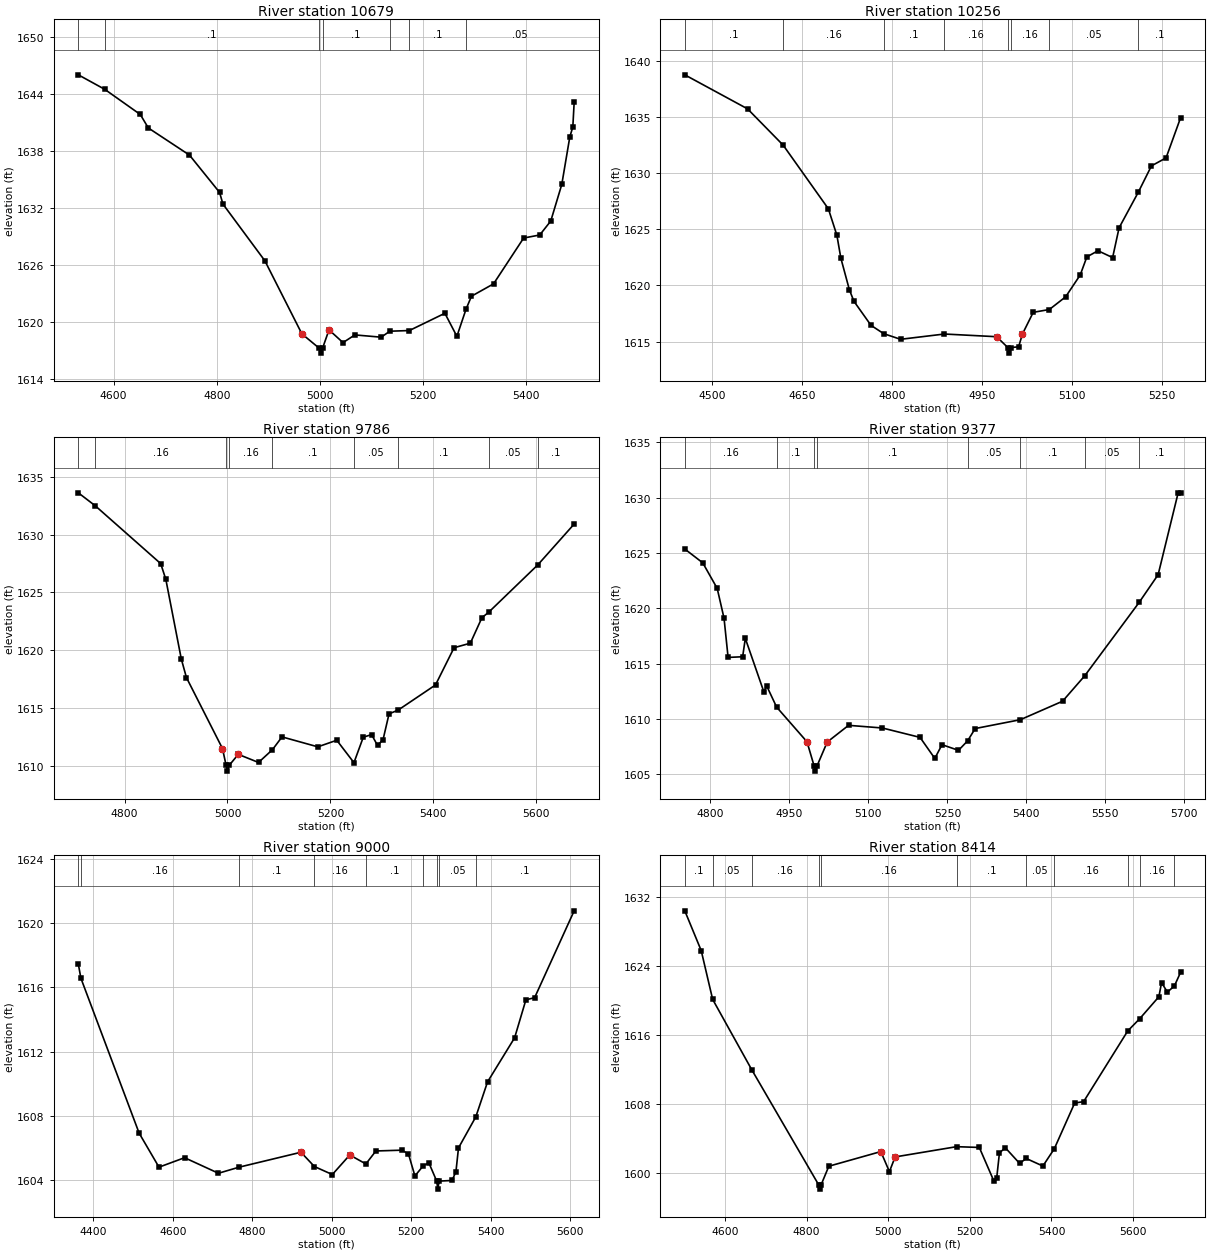
Type RM Length L Ch R = 1 ,10679   ,423,423,423
BEGIN DESCRIPTION:
UNT003 IN SNOGR 19.0
END DESCRIPTION:
XS GIS Cut Line= 2
      2770487.53     10040188.79      2771313.89      10040681.1
#Sta/Elev= 30
  4531.5 1646.06  4582.8 1644.53  4651.7 1641.88  4667.3 1640.46  4747.1  1637.6
  4805.5 1633.67    4812 1632.44  4893.4 1626.46  4965.2 1618.76  4999.2 1617.23
  5001.9 1616.73  5005.2 1617.23  5017.8 1619.18    5045 1617.84    5068 1618.65
    5119 1618.41  5135.8 1619.04  5173.7 1619.11  5242.6 1620.93  5265.9  1618.5
  5283.7 1621.37  5294.2 1622.73    5337 1624.03  5395.4 1628.86  5426.6 1629.18
    5448 1630.65  5469.4 1634.51    5485 1639.53  5490.8 1640.56  5493.4 1643.15
#Mann= 7 ,-1 , 0
  4531.5     .05       0  4582.8      .1       0  4999.2     .07       0
  5005.2      .1       0  5135.8     .16       0  5173.7      .1       0
  5283.7     .05       0
Bank Sta=4965.2,5017.8
XS Rating Curve= 0 ,0
Exp/Cntr=0.3,0.1

Type RM Length L Ch R = 1 ,10256   ,470,470,470
BEGIN DESCRIPTION:
UNT003 IN SNOGR 18.0
END DESCRIPTION:
XS GIS Cut Line= 3
      2770435.44     10040438.78      2770751.76     10040801.12
      2771074.03     10040928.46
#Sta/Elev= 30
  4454.1 1638.74  4558.9 1635.71  4618.3 1632.48  4693.7 1626.82  4707.9 1624.47
  4714.6 1622.42  4728.8 1619.61  4736.4 1618.59  4764.9 1616.45  4786.1 1615.71
  4814.2 1615.21  4887.4 1615.68  4974.6 1615.44  4993.1 1614.48  4995.8 1613.98
  4999.1 1614.48  5011.2 1614.54  5017.6 1615.68  5035.6 1617.61  5062.5 1617.86
  5089.7 1618.99    5114 1620.93  5125.1 1622.54  5143.7 1623.09  5168.1 1622.48
  5178.9 1625.13    5211  1628.3  5232.9 1630.64  5257.3 1631.35  5281.6 1634.93
#Mann= 8 ,-1 , 0
  4454.1      .1       0  4618.3     .16       0  4786.1      .1       0
  4887.4     .16       0  4993.1     .07       0  4999.1     .16       0
  5062.5     .05       0    5211      .1       0
Bank Sta=4974.6,5017.6
XS Rating Curve= 0 ,0
Exp/Cntr=0.3,0.1

Type RM Length L Ch R = 1 ,9786    ,409,409,409
BEGIN DESCRIPTION:
UNT003 IN SNOGR 17.0
END DESCRIPTION:
XS GIS Cut Line= 3
       2770414.6     10040563.76       2770400.2     10040959.97
       2770663.2     10041462.54
#Sta/Elev= 30
  4710.1 1633.61    4743 1632.49  4870.2 1627.49  4880.2 1626.12  4910.2 1619.25
  4920.2 1617.64  4990.3  1611.5  4997.3 1610.05    5000 1609.55  5003.3 1610.05
    5021    1611  5060.3  1610.3  5087.3  1611.4    5106 1612.51  5175.6 1611.65
  5212.4 1612.22  5245.8 1610.28  5263.9 1612.48  5280.1 1612.71  5291.6 1611.77
  5302.4 1612.28    5314  1614.5  5331.8 1614.83  5404.3    1617  5440.4 1620.22
    5472 1620.61  5494.6 1622.82  5507.5 1623.28  5603.1 1627.38  5673.8 1630.91
#Mann= 9 ,-1 , 0
  4710.1      .1       0    4743     .16       0  4997.3     .07       0
  5003.3     .16       0  5087.3      .1       0  5245.8     .05       0
  5331.8      .1       0  5507.5     .05       0  5603.1      .1       0
Bank Sta=4990.3,5021
XS Rating Curve= 0 ,0
Exp/Cntr=0.3,0.1

Type RM Length L Ch R = 1 ,9377    ,377,377,377
BEGIN DESCRIPTION:
UNT003 IN SNOGR 16.0
END DESCRIPTION:
XS GIS Cut Line= 3
      2770061.67      10040754.2      2770017.39     10040923.51
      2770236.15     10041657.92
#Sta/Elev= 30
  4751.5 1625.36  4785.6 1624.11    4813  1621.8    4826  1619.1  4833.7 1615.56
  4861.3 1615.62  4866.4 1617.28  4901.7 1612.43  4906.9 1612.99  4925.8 1611.07
  4983.5 1607.93  4996.8 1605.78  4999.5 1605.28  5002.8 1605.78  5021.9 1607.91
  5062.4 1609.42  5126.6 1609.18  5198.1 1608.33  5226.1 1606.43  5239.8 1607.67
  5271.1 1607.16  5288.3 1608.01  5302.8 1609.13  5388.6 1609.93  5468.7  1611.6
  5510.6 1613.89    5614 1620.53  5650.1 1623.04  5688.1 1630.44  5692.8 1630.44
#Mann= 8 ,-1 , 0
  4751.5     .16       0  4925.8      .1       0  4996.8     .07       0
  5002.8      .1       0  5288.3     .05       0  5388.6      .1       0
  5510.6     .05       0    5614      .1       0
Bank Sta=4983.5,5021.9
XS Rating Curve= 0 ,0
Exp/Cntr=0.3,0.1

Type RM Length L Ch R = 1 ,9000    ,586,586,586
BEGIN DESCRIPTION:
UNT003 IN SNOGR 15.0
END DESCRIPTION:
XS GIS Cut Line= 3
      2769192.72     10040735.14      2769682.32     10041110.14
      2769980.91     10041665.67
#Sta/Elev= 30
  4362.3 1617.46  4368.7 1616.58  4515.3 1606.91  4565.2 1604.79  4629.6 1605.38
  4714.8 1604.41  4766.8 1604.79  4922.4 1605.72  4956.2 1604.83  5001.3 1604.33
  5045.2 1605.55  5085.7 1604.99  5110.9  1605.8  5176.7 1605.85  5192.9 1605.61
  5209.1 1604.24  5230.1 1604.88  5244.2 1605.06  5263.9 1603.92  5266.7 1603.42
  5269.9 1603.92  5302.5 1603.96  5312.3 1604.51  5318.7 1605.99  5362.3 1607.93
  5391.8 1610.11  5459.9 1612.86  5488.3 1615.23  5510.2 1615.36  5609.7 1620.78
#Mann= 9 ,-1 , 0
  4362.3     .05       0  4368.7     .16       0  4766.8      .1       0
  4956.2     .16       0  5085.7      .1       0  5230.1     .05       0
  5263.9     .07       0  5269.9     .05       0  5362.3      .1       0
Bank Sta=4922.4,5045.2
XS Rating Curve= 0 ,0
Exp/Cntr=0.3,0.1

Type RM Length L Ch R = 1 ,8414    ,677,677,677
BEGIN DESCRIPTION:
UNT003 IN SNOGR 14.0
END DESCRIPTION:
XS GIS Cut Line= 2
      2768939.26      10040915.7      2769858.19     10041709.79
#Sta/Elev= 30
  4501.9 1630.43  4542.1 1625.81  4570.1 1620.15  4665.6    1612  4829.8 1598.61
  4832.5 1598.11  4835.8 1598.61  4854.7 1600.77    4982 1602.47  5003.1 1600.14
  5017.1 1601.85  5167.6 1603.04  5223.3 1602.95  5258.4 1599.11    5266 1599.46
  5272.6 1602.31  5286.9 1602.92    5322  1601.1  5338.2 1601.67    5379 1600.79
    5407  1602.8  5456.9 1608.11  5478.8 1608.27    5587 1616.49  5615.8 1617.88
  5663.1 1620.45  5669.7 1622.09    5684 1620.99  5701.2 1621.71  5716.4  1623.3
#Mann= 11 ,-1 , 0
  4501.9      .1       0  4570.1     .05       0  4665.6     .16       0
  4829.8     .07       0  4835.8     .16       0  5167.6      .1       0
  5338.2     .05       0    5407     .16       0    5587      .1       0
  5615.8     .16       0  5701.2      .1       0
Bank Sta=4982,5017.1
XS Rating Curve= 0 ,0
Exp/Cntr=0.3,0.1

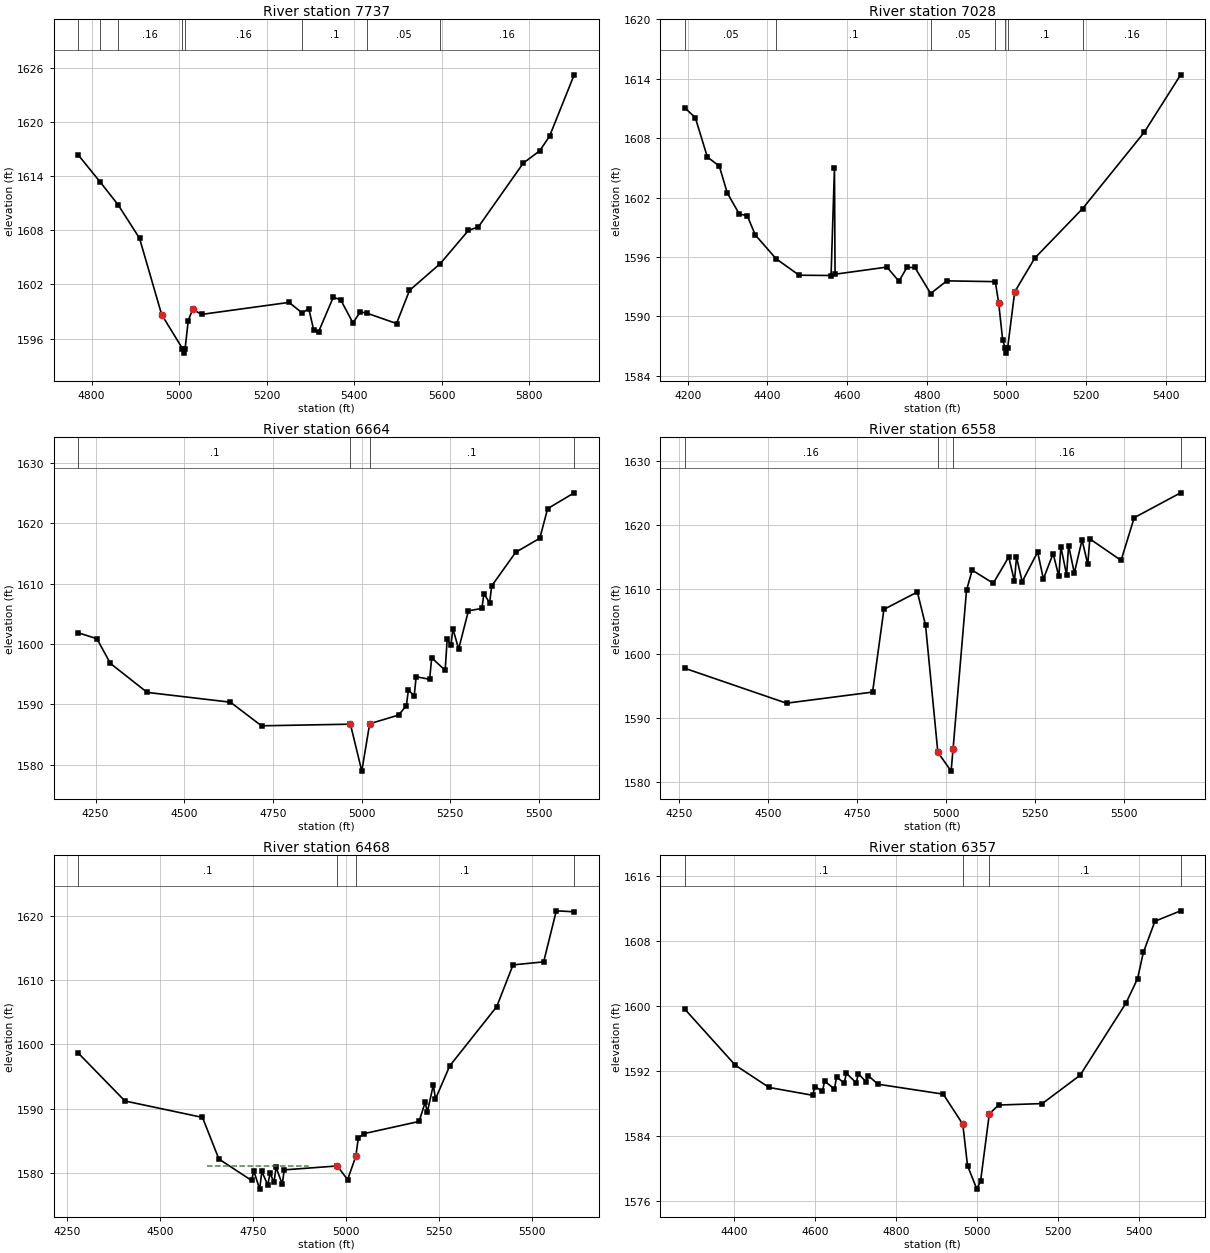
Type RM Length L Ch R = 1 ,7737    ,709,709,709
BEGIN DESCRIPTION:
UNT003 IN SNOGR 13.0
END DESCRIPTION:
XS GIS Cut Line= 3
      2768720.47     10041405.28       2769109.4     10041467.78
      2769772.62     10041794.18
#Sta/Elev= 30
  4769.5 1616.33  4818.7 1613.39  4860.4 1610.82  4909.3 1607.12  4959.9 1598.66
  5007.5 1594.89  5010.3 1594.39  5013.5 1594.89  5020.7    1598  5030.8 1599.24
  5051.1 1598.68  5251.1 1600.01    5281 1598.84    5296 1599.33  5307.3 1596.97
  5318.4 1596.74  5352.1 1600.58    5369  1600.3    5397 1597.75  5413.9 1598.95
  5428.7 1598.82  5496.7 1597.67  5526.3 1601.34  5596.7 1604.31  5661.1 1607.99
  5683.5 1608.36  5786.5 1615.45  5823.9  1616.8  5846.4 1618.42  5902.6 1625.22
#Mann= 8 ,-1 , 0
  4769.5     .16       0  4818.7      .1       0  4860.4     .16       0
  5007.5     .07       0  5013.5     .16       0    5281      .1       0
  5428.7     .05       0  5596.7     .16       0
Bank Sta=4959.9,5030.8
XS Rating Curve= 0 ,0
Exp/Cntr=0.3,0.1

Type RM Length L Ch R = 1 ,7028    ,364,364,364
BEGIN DESCRIPTION:
UNT003 IN SNOGR 12.0
END DESCRIPTION:
XS GIS Cut Line= 2
      2768342.01     10042096.26      2769584.27     10042023.39
#Sta/Elev= 30
  4192.8 1611.07  4219.3 1610.06  4249.4  1606.1  4279.4 1605.18  4299.4 1602.47
  4329.5 1600.34  4349.5 1600.18  4369.6 1598.23    4422 1595.82  4479.7 1594.16
  4559.9 1594.13 4568.42 1605.01  4569.9 1594.26  4700.1 1594.98  4730.2 1593.55
  4750.2 1594.94  4770.2 1594.95  4809.8 1592.31  4850.4 1593.59  4972.1 1593.51
  4980.6 1591.34  4990.6 1587.61    4997 1586.79  4999.8 1586.29    5003 1586.79
  5020.7 1592.47  5070.8 1595.87  5191.2 1600.89  5346.1 1608.61  5437.2  1614.4
#Mann= 7 ,-1 , 0
  4192.8     .05       0    4422      .1       0  4809.8     .05       0
  4972.1      .1       0    4997     .07       0    5003      .1       0
  5191.2     .16       0
Bank Sta=4980.6,5020.7
XS Rating Curve= 0 ,0
Exp/Cntr=0.3,0.1

Type RM Length L Ch R = 1 ,6664    ,106,106,106
BEGIN DESCRIPTION:
UNT003 IN SNOGR 11.0
END DESCRIPTION:
XS GIS Cut Line= 2
       2768534.4     10042772.11      2769763.55     10042105.45
#Sta/Elev= 30
  4201.3 1601.86  4253.7 1600.88  4291.8 1596.79  4395.4    1592  4630.2 1590.38
  4717.9 1586.47  4968.6 1586.74  5000.7 1578.97  5022.9 1586.81  5104.6 1588.25
  5126.5 1589.82  5132.2 1592.45  5148.4 1591.37    5154 1594.59  5192.1 1594.17
  5197.8 1597.72  5235.8 1595.66  5241.5 1600.79    5252 1599.79  5257.7 1602.53
  5273.8 1599.17  5301.4  1605.5  5339.4  1605.9  5345.1 1608.34  5361.3  1606.8
    5367 1609.62  5434.6 1615.18  5502.8 1617.52  5524.8 1622.41  5599.6 1625.03
#Mann= 4 ,-1 , 0
  4201.3      .1       0  4968.6     .07       0  5022.9      .1       0
  5599.6      .1       0
Bank Sta=4968.6,5022.9
XS Rating Curve= 0 ,0
Exp/Cntr=0.3,0.1

Type RM Length L Ch R = 1 ,6558    ,90,90,90
BEGIN DESCRIPTION:
Mapping XS 8fde55c6
END DESCRIPTION:
XS GIS Cut Line= 3
       2768619.8     10042856.68      2769342.04     10042446.95
      2769834.95       10042174.
#Sta/Elev= 30
  4265.8 1597.71  4551.7 1592.28  4793.7 1594.01  4825.5 1606.88  4919.6 1609.58
  4942.6 1604.39  4977.1 1584.65  5014.4 1581.71    5020 1585.21  5057.7 1609.82
  5073.6 1612.98  5132.9 1610.94  5176.4 1615.03  5192.5 1611.25  5198.2 1615.02
  5214.2 1611.19  5257.7  1615.8  5273.8 1611.61  5301.2 1615.56  5317.3    1612
    5323  1616.6    5339 1612.25  5344.7 1616.81  5360.8 1612.53  5382.5 1617.68
  5398.6 1613.89  5404.3 1617.85  5492.2  1614.5  5529.1 1621.14  5659.6 1625.01
#Mann= 4 ,-1 , 0
  4265.8     .16       0  4977.1     .07       0    5020     .16       0
  5659.6      .1       0
Bank Sta=4977.1,5020
XS Rating Curve= 0 ,0
Exp/Cntr=0.3,0.1

Type RM Length L Ch R = 1 ,6468    ,111,111,111
BEGIN DESCRIPTION:
Mapping XS a701b74d
END DESCRIPTION:
XS GIS Cut Line= 2
      2768643.74     10042917.97      2769820.89     10042292.93
#Sta/Elev= 30
  4280.9 1598.63  4406.2 1591.18  4614.6 1588.62  4658.7 1582.14  4746.6  1578.8
  4752.3 1580.33  4768.3 1577.45  4774.2  1580.2  4790.1 1578.09  4796.2  1579.9
  4806.9 1578.55  4812.5 1580.84  4828.9 1578.25  4834.5 1580.45  4976.9 1581.06
  5004.7 1578.93  5026.7 1582.54  5033.5  1585.4  5048.7 1586.09  5196.9 1587.99
  5213.3    1591  5218.9 1589.42  5235.2 1593.69  5240.9 1591.49  5279.2 1596.64
  5405.5 1605.87  5449.4 1612.38  5531.7 1612.85  5565.7  1620.8  5613.7 1620.65
#Mann= 4 ,-1 , 0
  4280.9      .1       0  4976.9     .07       0  5026.7      .1       0
  5613.7      .1       0
#XS Ineff= 1 ,-1
 4627.37 4898.95 1581.08
Permanent Ineff=
       F
Bank Sta=4976.9,5026.7
XS Rating Curve= 0 ,0
Exp/Cntr=0.3,0.1

Type RM Length L Ch R = 1 ,6357    ,466,466,466
BEGIN DESCRIPTION:
UNT003 IN SNOGR 10.0
END DESCRIPTION:
XS GIS Cut Line= 3
      2768661.49     10042946.95      2769557.32     10042585.84
      2769754.38     10042419.89
#Sta/Elev= 30
  4278.6 1599.57  4403.4 1592.67  4486.7 1589.94  4594.1 1588.98  4599.5 1590.05
  4618.3 1589.48  4623.6 1590.71  4647.8 1589.77  4653.2 1591.23    4672 1590.48
  4677.3 1591.68  4701.5 1590.52  4706.9 1591.62  4725.7 1590.65  4731.1  1591.4
  4755.2 1590.34  4916.3 1589.12  4964.6 1585.42  4976.2 1580.33  4999.3 1577.44
  5008.5 1578.44  5030.1 1586.71  5053.3 1587.78  5160.7 1587.96    5254 1591.44
  5367.2 1600.31  5395.8 1603.31  5410.1 1606.54  5438.7 1610.38  5502.1 1611.66
#Mann= 4 ,-1 , 0
  4278.6      .1       0  4964.6     .07       0  5030.1      .1       0
  5502.1      .1       0
Bank Sta=4964.6,5030.1
XS Rating Curve= 0 ,0
Exp/Cntr=0.3,0.1

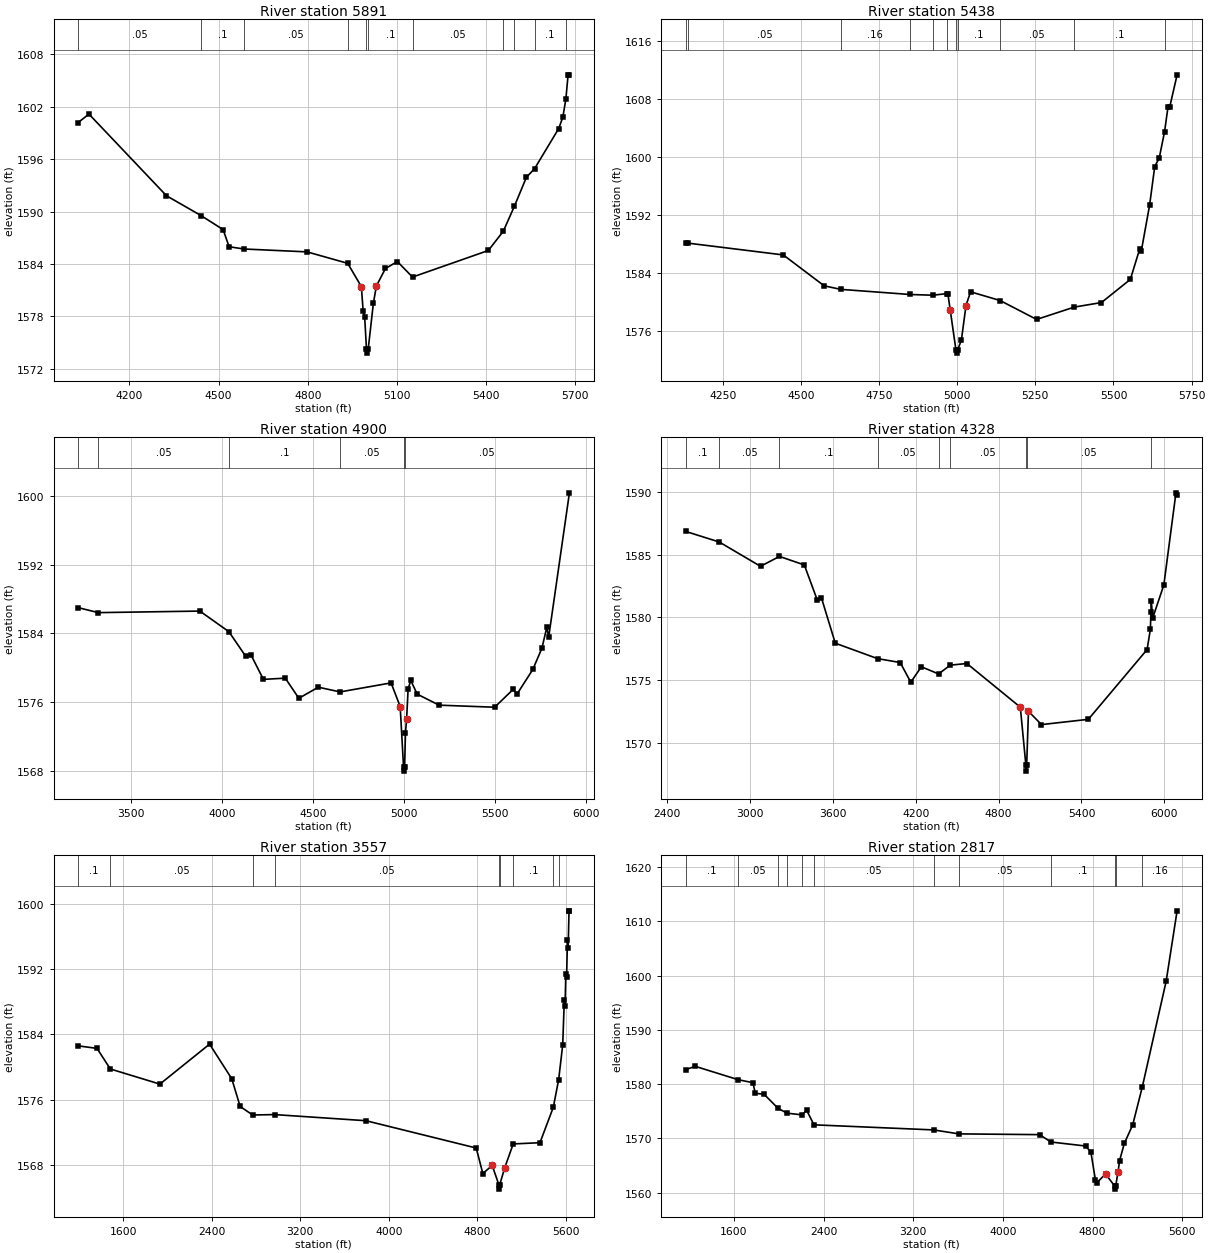
Type RM Length L Ch R = 1 ,5891    ,453,453,453
BEGIN DESCRIPTION:
UNT003 IN SNOGR 9.0
END DESCRIPTION:
XS GIS Cut Line= 4
      2768512.14     10043092.78      2769137.18     10043144.87
      2769685.79     10043051.12       2769873.3     10042620.55
#Sta/Elev= 30
  4027.4 1600.18  4063.9 1601.15  4324.8 1591.81  4440.7 1589.55  4515.4 1587.94
  4535.5 1585.98  4585.4 1585.72  4797.9 1585.39  4934.6 1584.08  4980.6 1581.42
  4986.7 1578.59  4991.8  1577.9  4997.8 1574.31  5000.6 1573.81  5003.8 1574.31
  5021.1 1579.54  5031.3  1581.5  5061.7 1583.49  5101.9 1584.28  5152.8 1582.51
  5407.9 1585.55  5458.3 1587.75  5495.6 1590.61    5536 1593.92  5563.6 1594.91
  5644.6 1599.49  5658.6 1600.79  5668.9 1602.89  5676.3 1605.64  5680.8 1605.64
#Mann= 11 ,-1 , 0
  4027.4     .05       0  4440.7      .1       0  4585.4     .05       0
  4934.6      .1       0  4997.8     .07       0  5003.8      .1       0
  5152.8     .05       0  5458.3      .1       0  5495.6     .16       0
  5563.6      .1       0  5668.9     .16       0
Bank Sta=4980.6,5031.3
XS Rating Curve= 0 ,0
Exp/Cntr=0.3,0.1

Type RM Length L Ch R = 1 ,5438    ,538,538,538
BEGIN DESCRIPTION:
UNT003 IN SNOGR 8.0
END DESCRIPTION:
XS GIS Cut Line= 4
      2769043.46      10043801.1      2769717.04     10043429.59
      2769928.85     10043141.39      2770029.39     10042708.01
#Sta/Elev= 30
  4131.7 1588.13  4139.9 1588.16  4443.6 1586.54  4574.3 1582.28    4627 1581.79
  4849.3 1581.08  4922.3 1580.98  4966.1  1581.2  4970.3 1581.13  4977.9 1578.89
  4995.8 1573.49  4998.5 1572.99  5001.8 1573.49  5013.4 1574.78  5028.1 1579.54
  5042.7 1581.45  5137.2 1580.25  5254.1 1577.64  5374.4 1579.34  5461.5 1579.97
  5553.9 1583.16  5584.2 1587.41  5589.3 1587.15  5615.5  1593.4    5632 1598.74
  5646.3  1599.9  5663.3 1603.52  5674.6 1607.01  5679.8 1606.93  5703.5 1611.39
#Mann= 11 ,-1 , 0
  4131.7      .1       0  4139.9     .05       0    4627     .16       0
  4849.3      .1       0  4922.3     .16       0  4966.1      .1       0
  4995.8     .07       0  5001.8      .1       0  5137.2     .05       0
  5374.4      .1       0  5663.3     .16       0
Bank Sta=4977.9,5028.1
XS Rating Curve= 0 ,0
Exp/Cntr=0.3,0.1

Type RM Length L Ch R = 1 ,4900    ,572,572,572
BEGIN DESCRIPTION:
UNT003 IN SNOGR 7.0
END DESCRIPTION:
XS GIS Cut Line= 4
      2768722.24     10044255.98       2770171.9     10043585.84
      2770408.01     10043276.81      2770262.17     10042582.32
#Sta/Elev= 30
  3211.4 1586.99  3322.5 1586.41  3879.3 1586.59  4038.9 1584.19  4130.7 1581.34
  4159.2 1581.52    4228 1578.65  4348.1 1578.79  4422.4 1576.45  4529.3 1577.74
  4648.8 1577.19  4928.5 1578.24  4978.4 1575.49  4996.9 1568.48  4999.6 1567.98
  5002.9 1568.48  5007.4 1572.44  5013.7 1574.02    5022 1577.53  5036.5 1578.53
  5071.8 1576.93  5192.4 1575.65  5496.8 1575.41    5599  1577.5  5619.5 1576.94
  5706.2  1579.8  5756.1 1582.28  5782.9  1584.7  5793.2 1583.56    5907 1600.34
#Mann= 6 ,-1 , 0
  3211.4      .1       0  3322.5     .05       0  4038.9      .1       0
  4648.8     .05       0  4996.9    .035       0  5002.9     .05       0
Bank Sta=4978.4,5013.7
XS Rating Curve= 0 ,0
Exp/Cntr=0.3,0.1

Type RM Length L Ch R = 1 ,4328    ,771,771,771
BEGIN DESCRIPTION:
UNT003 IN SNOGR 6.0
END DESCRIPTION:
XS GIS Cut Line= 4
      2768618.08     10044500.77      2770789.96      10043584.1
      2771045.16     10043136.19      2771154.54     10042459.08
#Sta/Elev= 30
  2533.7 1586.86    2776 1586.02  3075.2 1584.08  3212.2 1584.87  3392.3 1584.19
  3487.2 1581.36  3516.3 1581.57  3616.6 1577.95  3922.9 1576.72  4086.8 1576.41
  4163.4 1574.84    4240 1576.07    4365  1575.5  4449.4  1576.2  4569.9 1576.33
  4956.8 1572.85    4997 1568.25  4999.8 1567.75    5003 1568.25  5015.9 1572.52
  5110.2 1571.46  5449.6 1571.88  5875.1 1577.44    5899 1579.06  5902.9 1580.43
  5905.5 1581.34  5915.6 1579.95  5996.6  1582.6  6084.2 1589.94  6092.5 1589.77
#Mann= 9 ,-1 , 0
  2533.7      .1       0    2776     .05       0  3212.2      .1       0
  3922.9     .05       0    4365      .1       0  4449.4     .05       0
    4997    .035       0    5003     .05       0  5902.9     .16       0
Bank Sta=4956.8,5015.9
XS Rating Curve= 0 ,0
Exp/Cntr=0.3,0.1

Type RM Length L Ch R = 1 ,3557    ,740,740,740
BEGIN DESCRIPTION:
UNT003 IN SNOGR 5.0
END DESCRIPTION:
XS GIS Cut Line= 3
        2768066.     10045214.31      2771414.96     10043823.69
      2772018.07     10043277.76
#Sta/Elev= 30
  1192.7 1582.59  1363.4 1582.28  1483.9 1579.76  1931.7 1577.91  2380.8  1582.8
  2581.3 1578.56  2657.1 1575.17  2770.3 1574.13  2968.3 1574.18  3794.1 1573.43
  4790.2 1570.09    4850 1566.96  4934.4 1567.96  4995.7 1565.56  4998.4 1565.06
  5001.7 1565.56    5048 1567.69  5124.5 1570.59  5366.3 1570.74  5486.9 1575.08
  5535.1 1578.46  5571.8 1582.72    5586 1588.15  5592.7 1587.51  5600.2 1591.41
  5606.9 1591.04  5614.4  1595.5  5621.1 1594.62  5628.6 1599.11  5632.4  1599.1
#Mann= 9 ,-1 , 0
  1192.7      .1       0  1483.9     .05       0  2770.3      .1       0
  2968.3     .05       0  4995.7    .035       0  5001.7     .05       0
  5124.5      .1       0  5486.9     .05       0  5535.1     .16       0
Bank Sta=4934.4,5048
XS Rating Curve= 0 ,0
Exp/Cntr=0.3,0.1

Type RM Length L Ch R = 1 ,2817    ,665,665,665
BEGIN DESCRIPTION:
UNT003 IN SNOGR 4.0
END DESCRIPTION:
XS GIS Cut Line= 2
      2768326.38     10045568.49      2772440.07      10044058.4
#Sta/Elev= 30
  1171.5 1582.67  1255.7 1583.28  1639.5 1580.81  1770.3 1580.26  1791.6  1578.3
  1869.4 1578.14  1994.6 1575.53  2074.6 1574.64  2208.2 1574.33  2249.7 1575.17
    2315 1572.49    3383 1571.55  3606.8 1570.82  4326.9 1570.68  4428.9 1569.32
  4738.5 1568.58  4784.9 1567.43  4824.7 1562.38  4838.2 1561.84  4916.1 1563.41
  4999.3 1561.13    5002 1560.63  5005.3 1561.13  5027.4 1563.85  5040.6 1565.89
  5083.1 1569.07  5157.7 1572.49  5242.9 1579.44    5456 1598.97  5553.6 1611.96
#Mann= 12 ,-1 , 0
  1171.5      .1       0  1639.5     .05       0  1994.6      .1       0
  2074.6     .05       0  2208.2      .1       0    2315     .05       0
    3383      .1       0  3606.8     .05       0  4428.9      .1       0
  4999.3     .07       0  5005.3      .1       0  5242.9     .16       0
Bank Sta=4916.1,5027.4
XS Rating Curve= 0 ,0
Exp/Cntr=0.3,0.1

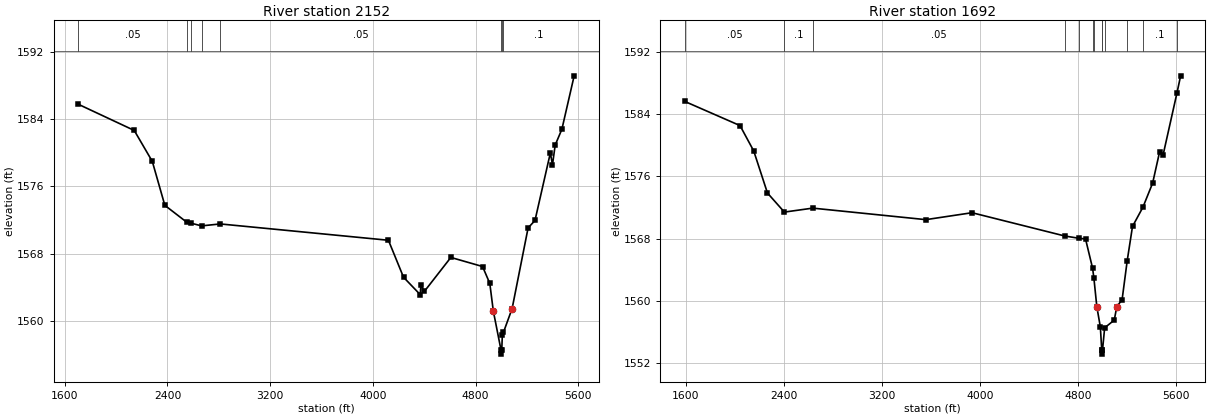
Type RM Length L Ch R = 1 ,2152    ,460,460,460
BEGIN DESCRIPTION:
Mapping XS 37cc71da
END DESCRIPTION:
XS GIS Cut Line= 2
       2768972.2     10045839.32      2772659.78     10044693.47
#Sta/Elev= 30
  1705.8 1585.76  2141.2 1582.65  2281.9 1578.97  2379.5 1573.75  2548.9 1571.76
  2580.5 1571.64  2665.9 1571.31  2811.2 1571.54  4120.8  1569.6  4238.3 1565.21
  4368.5 1563.14  4373.7 1564.23  4401.1 1563.53  4606.9 1567.56  4853.9 1566.48
  4910.4 1564.47  4937.6  1561.2  4997.5 1556.57  5000.2 1556.07  5003.5 1556.57
    5008 1558.35  5016.9 1558.67  5084.2 1561.49  5208.6 1571.07  5262.2 1571.95
  5381.9 1579.98  5398.4 1578.57  5419.7 1580.92  5471.7 1582.79  5567.3 1589.14
#Mann= 8 ,-1 , 0
  1705.8     .05       0  2548.9      .1       0  2580.5     .05       0
  2665.9      .1       0  2811.2     .05       0  4997.5    .035       0
  5003.5     .05       0  5016.9      .1       0
Bank Sta=4937.6,5084.2
XS Rating Curve= 0 ,0
Exp/Cntr=0.3,0.1

Type RM Length L Ch R = 1 ,1692    ,0,0,0
BEGIN DESCRIPTION:
Mapping XS 14360f73
END DESCRIPTION:
XS GIS Cut Line= 3
      2768985.75     10045903.51      2772222.25     10045313.27
       2772800.4     10044834.08
#Sta/Elev= 30
  1593.8 1585.61  2043.8 1582.51  2155.6 1579.25  2267.4 1573.85  2405.3  1571.4
  2636.2 1571.91  3558.4 1570.43  3934.5 1571.32  4690.6 1568.33  4809.1 1568.03
  4859.5 1567.96  4917.3 1564.18  4927.9  1562.9  4951.8 1559.24  4980.5 1556.64
  4991.8 1553.66  4994.6 1553.16  4997.8 1553.66  5015.5 1556.54  5093.8 1557.53
  5114.6 1559.27  5157.6 1560.15  5199.4 1565.17  5242.4 1569.56  5327.4 1572.03
  5406.4 1575.12  5463.2 1579.13    5491 1578.69  5604.2 1586.66  5634.6  1588.9
#Mann= 13 ,-1 , 0
  1593.8     .05       0  2405.3      .1       0  2636.2     .05       0
  4690.6      .1       0  4809.1     .05       0  4917.3      .1       0
  4927.9     .05       0  4991.8    .035       0  4997.8     .05       0
  5015.5      .1       0  5199.4     .16       0  5327.4      .1       0
  5604.2     .05       0
Bank Sta=4951.8,5114.6
XS Rating Curve= 0 ,0
Exp/Cntr=0.3,0.1

Chan Stop Cuts=-1
Use User Specified Reach Order=0
Composite Channel Slope=5