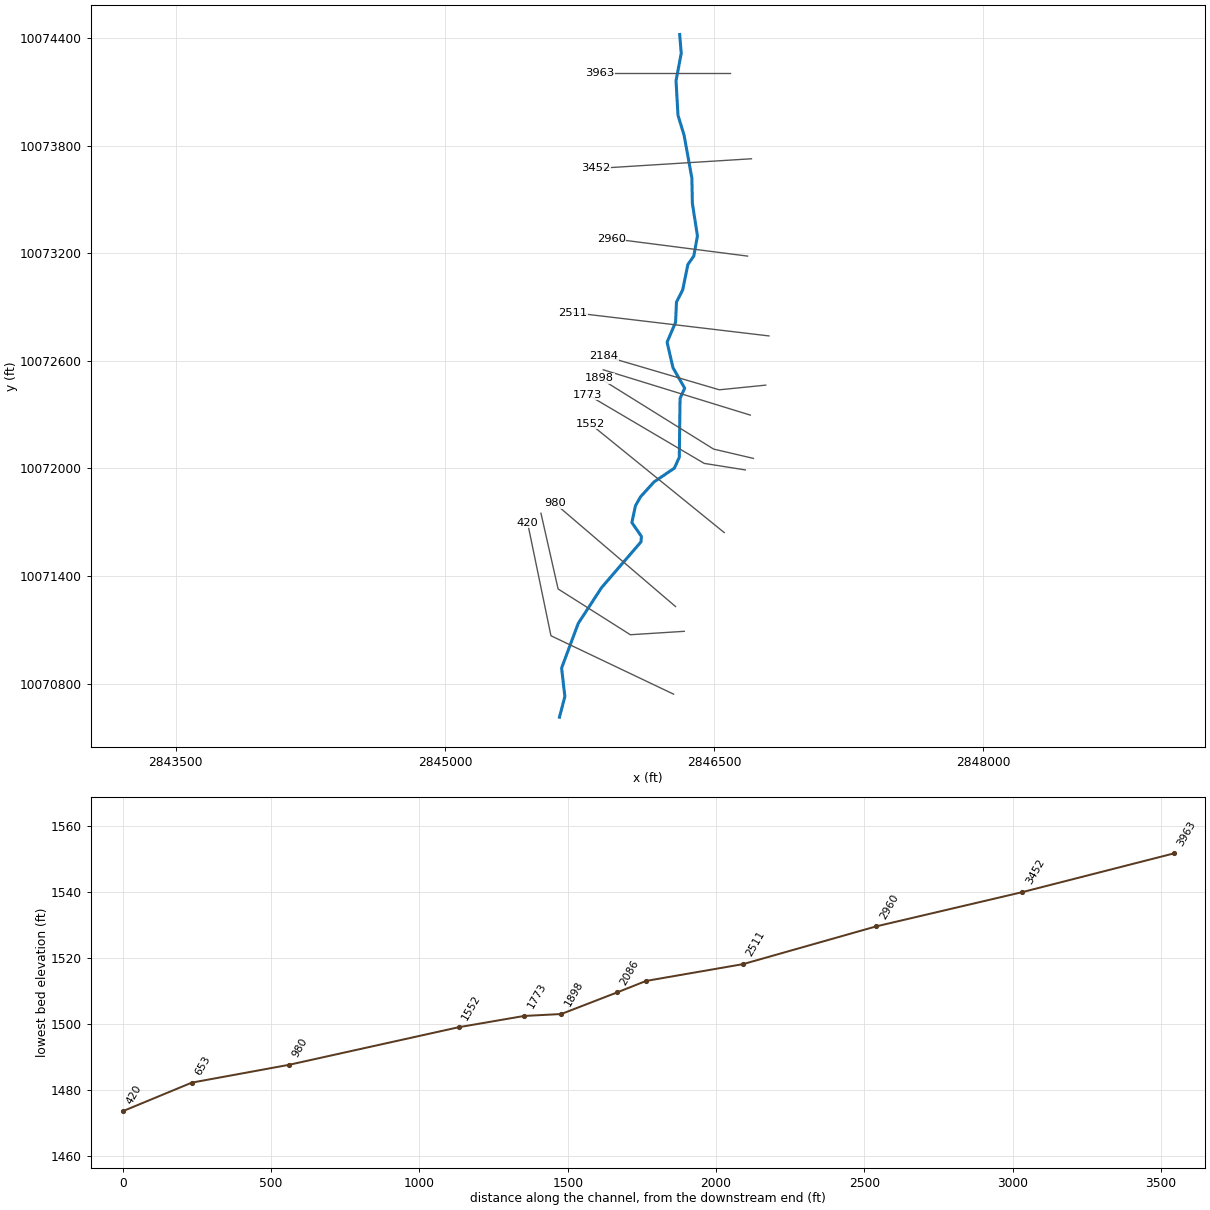
--- UNT004 IN NNOGR.prj (project) ---

Proj Title=UNT004 IN NNOGR Base Level Engineering
Current Plan=p01
Default Exp/Contr=0.3,0.1
English Units
Geom File=g01
Flow File=f01
Plan File=p01
Y Axis Title=Elevation
X Axis Title(PF)=Main Channel Distance
X Axis Title(XS)=Station
BEGIN DESCRIPTION:
UNT004 IN NNOGR
END DESCRIPTION:
DSS Export Rating Curves= 0
DSS Export Rating Curve Sorted= 0
DSS Export Volume Flow Curves= 0
DXF OffsetX= 0
DXF OffsetY= 0
DXF ScaleX= 1
DXF ScaleY= 10

--- UNT004 IN NNOGR.p01 (plan) ---

Plan Title=Multiple Run
Short Identifier=Multiple
Geom File=g01
Flow File=f01
Subcritical Flow
K Sum by GR= 0
Std Step Tol= 0.01
Critical Tol= 0.01
Num of Std Step Trials= 20
Max Error Tol= 0.3
Flow Tol Ratio= 0.001
Split Flow NTrial= 30
Split Flow Tol= 0.02
Split Flow Ratio= 0.02
Log Output Level= 0
Friction Slope Method= 1
Unsteady Friction Slope Method= 2
Unsteady Bridges Friction Slope Method= 1
Parabolic Critical Depth
Global Vel Dist=  1 , 1 , 1
Global Log Level= 0
CheckData=True
Encroach Param= -1, 0, 0, 0
BEGIN DESCRIPTION:
Multiple Run
END DESCRIPTION:

--- UNT004 IN NNOGR.f01 (steady flow) ---

Flow Title=Multiple
Program Version=4.10
Number of Profiles= 7
Profile Names=10-year,25-year,50-year,1pct_min,100-year,1pct_plu,500-year
River Rch & RM=UNT004 IN NNOGR,Reach-1         ,3963
     299     404     489     435     589     796     855
Boundary for River Rch & Prof#=UNT004 IN NNOGR,Reach-1         , 1
Up Type= 0
Dn Type= 3
Dn Slope=0.0206
Boundary for River Rch & Prof#=UNT004 IN NNOGR,Reach-1         , 2
Up Type= 0
Dn Type= 3
Dn Slope=0.0206
Boundary for River Rch & Prof#=UNT004 IN NNOGR,Reach-1         , 3
Up Type= 0
Dn Type= 3
Dn Slope=0.0206
Boundary for River Rch & Prof#=UNT004 IN NNOGR,Reach-1         , 4
Up Type= 0
Dn Type= 3
Dn Slope=0.0206
Boundary for River Rch & Prof#=UNT004 IN NNOGR,Reach-1         , 5
Up Type= 0
Dn Type= 3
Dn Slope=0.0206
Boundary for River Rch & Prof#=UNT004 IN NNOGR,Reach-1         , 6
Up Type= 0
Dn Type= 3
Dn Slope=0.0206
Boundary for River Rch & Prof#=UNT004 IN NNOGR,Reach-1         , 7
Up Type= 0
Dn Type= 3
Dn Slope=0.0206
DSS Import GetInterval= 0
DSS Import GetPeak= 0
DSS Import FillOption= 0

--- UNT004 IN NNOGR.g01 (geometry) ---

Geom Title=Existing Conditions
Program Version=4.10

River Reach=UNT004 IN NNOGR ,Reach-1
Reach XY= 30
      2846308.47     10074418.73      2846317.27     10074314.23
      2846288.21     10074160.57      2846299.15     10073968.49
      2846333.23     10073856.96      2846376.56      10073618.1
      2846379.21     10073478.58      2846407.55     10073295.83
      2846387.42     10073184.39      2846354.25     10073136.73
      2846325.28     10072995.06      2846290.79     10072927.77
      2846285.62     10072814.91      2846238.49     10072703.58
      2846271.24     10072561.26      2846336.37     10072447.92
      2846310.71      10072390.2      2846306.41     10072062.56
      2846279.15      10072001.9      2846165.69     10071925.05
      2846090.93     10071842.77      2846062.15     10071792.19
      2846042.08     10071698.65      2846095.11     10071622.04
      2846093.35     10071591.47       2845873.4      10071336.4
      2845743.18      10071136.5      2845650.49     10070887.99
      2845668.66     10070728.85      2845638.47     10070613.73

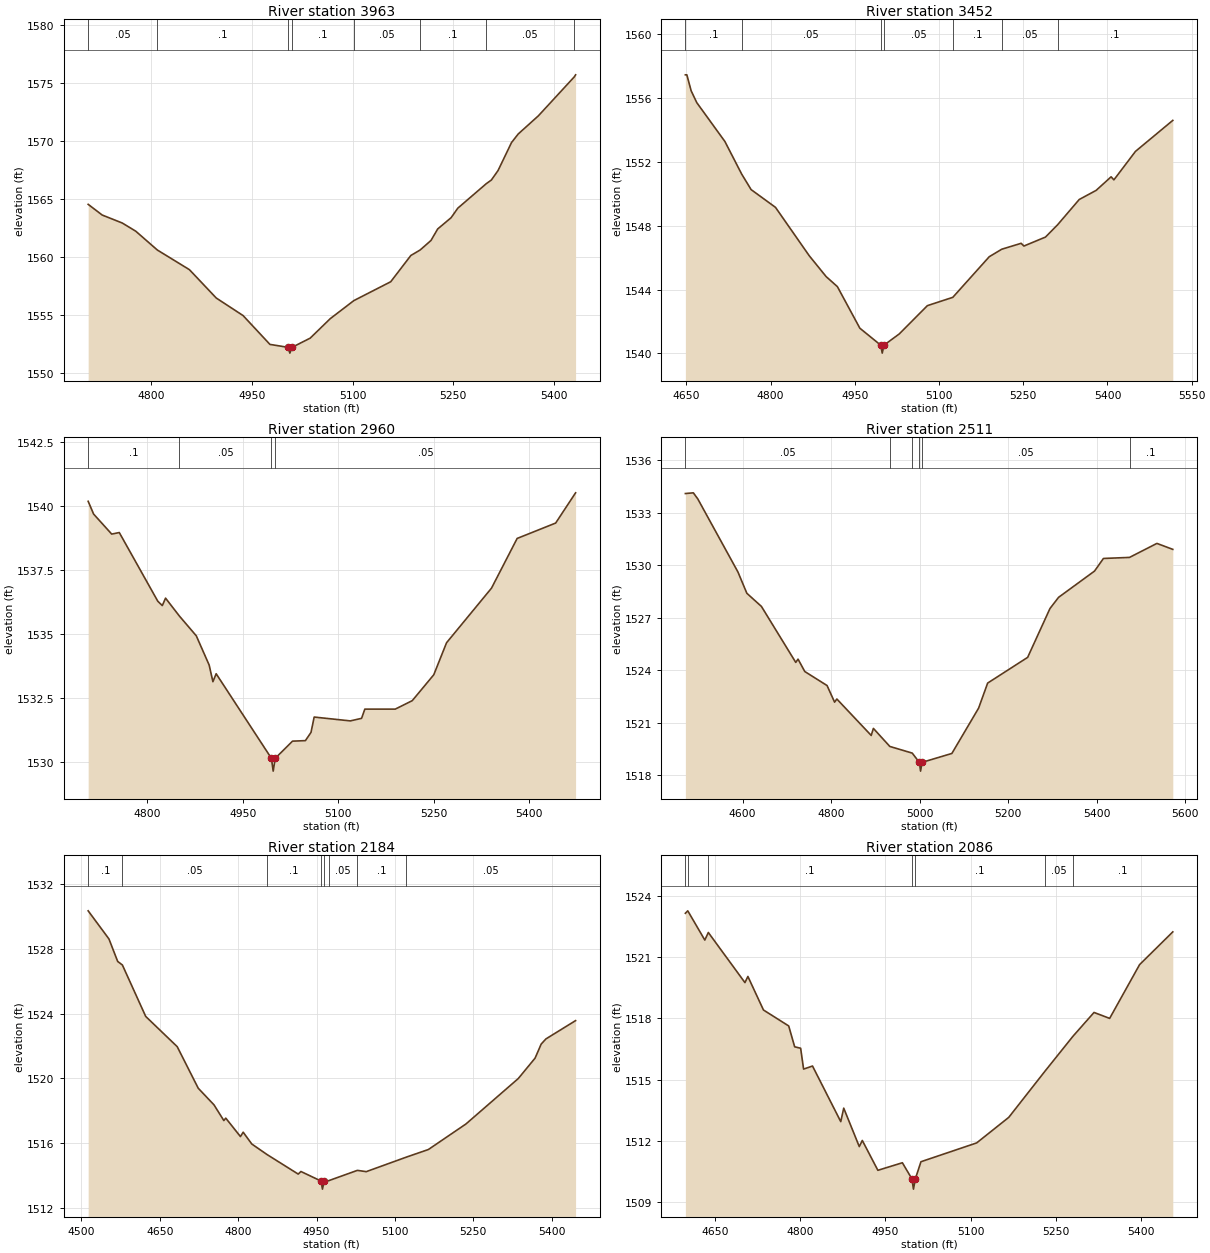
Type RM Length L Ch R = 1 ,3963    ,511,511,511
BEGIN DESCRIPTION:
UNT004 IN NNOGR 8.0
END DESCRIPTION:
XS GIS Cut Line= 2
      2846589.32     10074203.57      2845862.92     10074203.57
#Sta/Elev= 30
    4706 1564.54  4726.9 1563.62  4756.9 1562.93  4776.9 1562.23  4809.1 1560.61
  4856.9 1558.92  4896.9 1556.48  4936.9 1554.97  4976.9 1552.49  5003.9 1552.24
  5006.6 1551.74  5009.9 1552.24  5036.9 1553.03  5066.9 1554.71    5102 1556.26
  5156.9 1557.88  5186.9 1560.14  5200.7 1560.61  5216.9 1561.43  5226.9 1562.42
  5246.9 1563.39  5256.9 1564.21  5299.4 1566.32  5306.9 1566.63  5316.9 1567.45
  5336.9 1569.85  5346.9 1570.59  5376.9 1572.15  5430.4  1575.5  5432.4 1575.68
#Mann= 8 ,-1 , 0
    4706     .05       0  4809.1      .1       0  5003.9     .07       0
  5009.9      .1       0    5102     .05       0  5200.7      .1       0
  5299.4     .05       0  5430.4      .1       0
Bank Sta=5003.9,5009.9
XS Rating Curve= 0 ,0
Exp/Cntr=0.3,0.1

Type RM Length L Ch R = 1 ,3452    ,492,492,492
BEGIN DESCRIPTION:
UNT004 IN NNOGR 7.0
END DESCRIPTION:
XS GIS Cut Line= 2
       2846708.7     10073726.14      2845842.09     10073671.98
#Sta/Elev= 30
  4648.1 1557.43  4650.7 1557.43  4658.4 1556.43  4668.4 1555.69  4718.5 1553.26
  4748.4 1551.22  4765.2 1550.25  4808.6 1549.14  4868.8 1546.11  4898.8 1544.81
  4918.9 1544.18  4958.9 1541.58    4996 1540.52  4998.8 1540.02    5002 1540.52
  5029.1 1541.22  5079.2 1542.99  5124.5 1543.51  5189.4 1546.05  5211.7 1546.52
  5246.2 1546.89  5251.2 1546.72  5289.6 1547.28  5311.2 1548.05  5349.7 1549.63
  5379.8  1550.2  5406.5 1551.05  5411.5 1550.86  5449.9 1552.64  5516.4 1554.58
#Mann= 7 ,-1 , 0
  4648.1      .1       0  4748.4     .05       0    4996    .035       0
    5002     .05       0  5124.5      .1       0  5211.7     .05       0
  5311.2      .1       0
Bank Sta=4996,5002
XS Rating Curve= 0 ,0
Exp/Cntr=0.3,0.1

Type RM Length L Ch R = 1 ,2960    ,449,449,449
BEGIN DESCRIPTION:
UNT004 IN NNOGR 6.0
END DESCRIPTION:
XS GIS Cut Line= 2
      2846686.99     10073183.61      2845927.44     10073281.27
#Sta/Elev= 30
  4707.2 1540.19  4715.8 1539.69  4744.2 1538.91  4756.1 1538.97  4816.6 1536.29
  4823.7 1536.12  4828.8 1536.41  4850.6 1535.71  4877.1 1534.94  4897.3  1533.8
  4903.2 1533.15  4908.3 1533.46  4995.1 1530.16  4997.9 1529.66  5001.1 1530.16
  5028.3 1530.83  5048.5 1530.85  5057.3 1531.17  5062.3 1531.77  5119.1 1531.62
  5136.8 1531.72  5141.9 1532.08  5189.7 1532.08  5216.4 1532.41  5250.2 1533.42
  5270.3 1534.67  5340.9  1536.8  5381.2 1538.74  5441.7 1539.34    5473 1540.52
#Mann= 4 ,-1 , 0
  4707.2      .1       0  4850.6     .05       0  4995.1    .035       0
  5001.1     .05       0
Bank Sta=4995.1,5001.1
XS Rating Curve= 0 ,0
Exp/Cntr=0.3,0.1

Type RM Length L Ch R = 1 ,2511    ,327,327,327
BEGIN DESCRIPTION:
UNT004 IN NNOGR 5.0
END DESCRIPTION:
XS GIS Cut Line= 2
      2846806.37     10072738.73      2845712.86     10072868.65
#Sta/Elev= 30
  4470.9 1534.09  4488.9 1534.13    4499 1533.78  4589.6 1529.61  4609.8 1528.39
  4642.7 1527.64  4720.3 1524.44  4725.4 1524.63  4740.7 1523.92    4791 1523.12
    4808 1522.17  4813.1 1522.35  4890.7 1520.27  4895.7 1520.67  4932.8 1519.64
  4983.4 1519.26  4999.5 1518.73  5002.3 1518.23  5005.5 1518.73    5073 1519.24
  5133.4 1521.83  5153.8 1523.26  5244.2 1524.73  5294.6 1527.52  5314.1 1528.16
  5395.3 1529.66  5415.4 1530.38  5474.3 1530.44  5536.2 1531.24  5572.1  1530.9
#Mann= 6 ,-1 , 0
  4470.9     .05       0  4932.8      .1       0  4983.4     .05       0
  4999.5    .035       0  5005.5     .05       0  5474.3      .1       0
Bank Sta=4999.5,5005.5
XS Rating Curve= 0 ,0
Exp/Cntr=0.3,0.1

Type RM Length L Ch R = 1 ,2184    ,98,98,98
BEGIN DESCRIPTION:
Mapping XS e897c914
END DESCRIPTION:
XS GIS Cut Line= 3
      2846788.04     10072464.56      2846529.75     10072438.51
       2845884.1     10072628.41
#Sta/Elev= 30
    4513 1530.35  4552.8 1528.61  4569.5 1527.22  4578.5    1527  4623.1 1523.82
  4683.4 1521.95  4723.6 1519.38  4753.8 1518.35  4772.6 1517.38  4776.3 1517.53
  4804.4 1516.39  4809.6 1516.66  4826.1 1515.93  4855.2 1515.28  4914.9 1514.07
  4920.1 1514.23  4958.6 1513.64  4961.3 1513.14  4964.6 1513.64    4973 1513.66
  5028.1  1514.3    5045 1514.22  5121.9 1515.12    5164 1515.59  5235.9 1517.17
    5336 1519.98  5368.1 1521.24  5379.8 1522.11  5388.9 1522.43  5445.6 1523.56
#Mann= 8 ,-1 , 0
    4513      .1       0  4578.5     .05       0  4855.2      .1       0
  4958.6    .035       0  4964.6      .1       0    4973     .05       0
  5028.1      .1       0  5121.9     .05       0
Bank Sta=4958.6,4964.6
XS Rating Curve= 0 ,0
Exp/Cntr=0.3,0.1

Type RM Length L Ch R = 1 ,2086    ,188,188,188
BEGIN DESCRIPTION:
Mapping XS 465e76f6
END DESCRIPTION:
XS GIS Cut Line= 2
      2846702.25     10072297.46      2845882.69     10072550.05
#Sta/Elev= 30
  4598.2 1523.14  4602.4 1523.26  4632.4 1521.83  4638.6  1522.2    4703 1519.75
  4708.2 1520.05  4735.6 1518.41    4780 1517.63  4790.5 1516.61    4801 1516.54
  4806.2 1515.52  4821.9 1515.67  4871.6 1512.95  4876.8 1513.61  4904.2 1511.73
  4909.5 1512.03  4936.9 1510.57    4980 1510.94  4996.8 1510.15  4999.5 1509.65
  5002.8 1510.15  5012.7 1510.99  5110.7 1511.91  5167.2 1513.16  5230.4  1515.4
  5280.3 1517.13  5317.2 1518.29  5344.7    1518  5397.4 1520.63  5455.8 1522.23
#Mann= 7 ,-1 , 0
  4598.2      .1       0  4602.4     .05       0  4638.6      .1       0
  4996.8     .07       0  5002.8      .1       0  5230.4     .05       0
  5280.3      .1       0
Bank Sta=4996.8,5002.8
XS Rating Curve= 0 ,0
Exp/Cntr=0.3,0.1

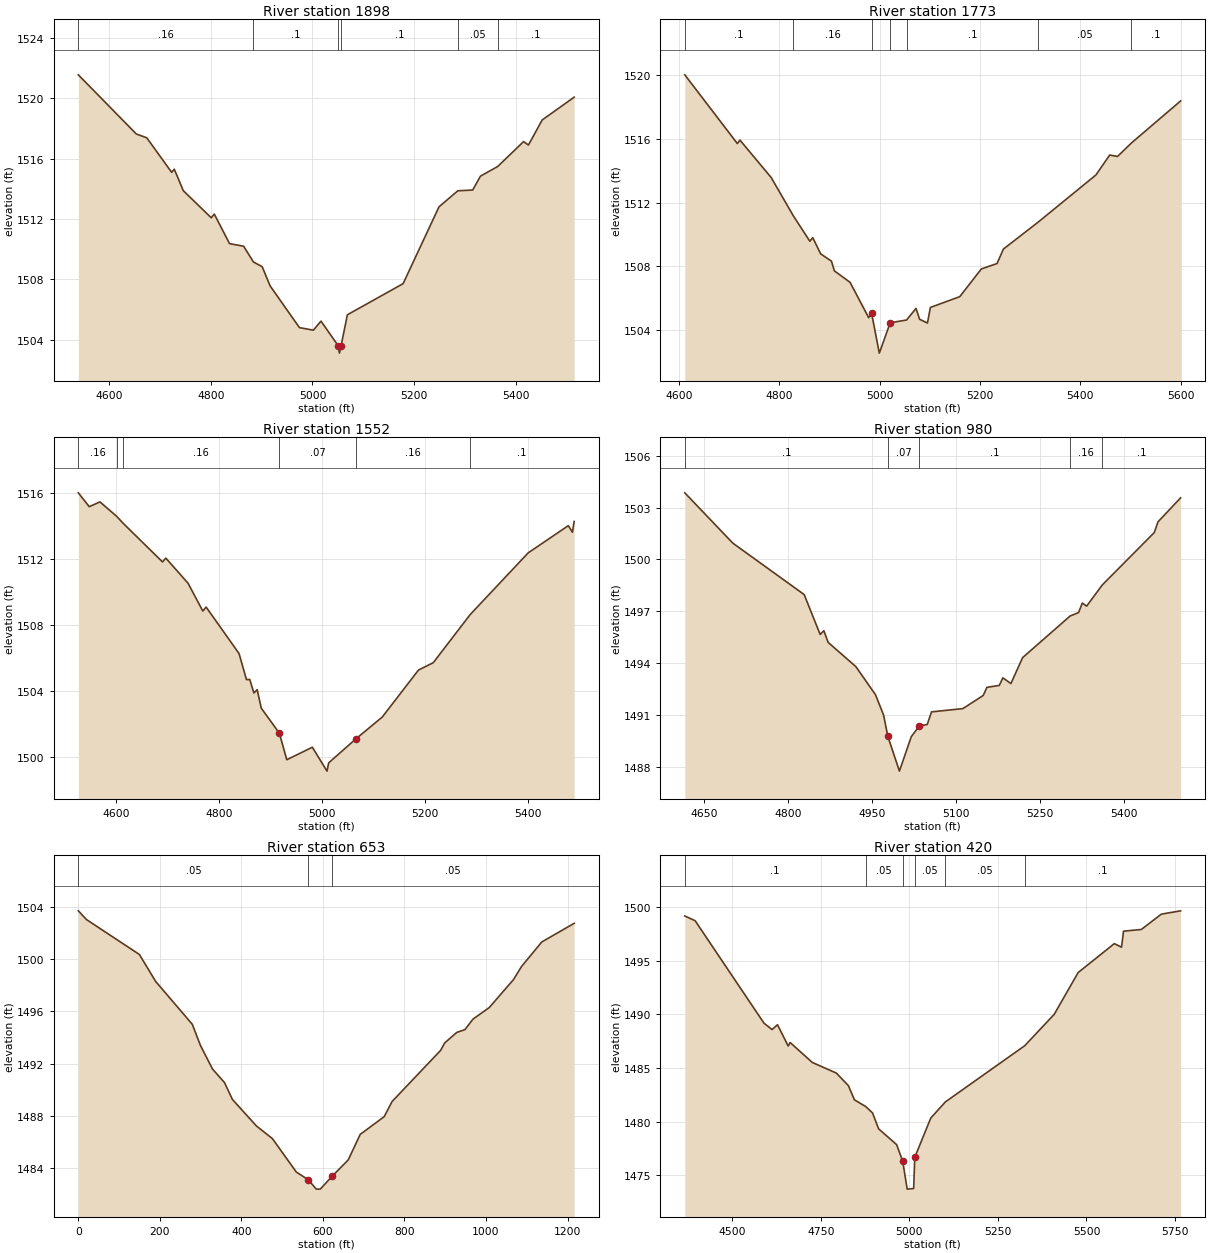
Type RM Length L Ch R = 1 ,1898    ,125,125,125
BEGIN DESCRIPTION:
UNT004 IN NNOGR 4.0
END DESCRIPTION:
XS GIS Cut Line= 3
      2846719.61     10072056.14      2846497.42     10072108.22
      2845862.71     10072503.61
#Sta/Elev= 30
  4539.1 1521.55  4653.3 1517.63  4673.8 1517.38  4722.9 1515.09    4728  1515.3
  4745.7 1513.88  4800.8 1512.08  4806.7 1512.33  4836.8 1510.37  4864.5  1510.2
  4883.7 1509.16  4901.1 1508.84  4916.5 1507.58  4974.3 1504.81  5001.7 1504.64
  5016.8 1505.24  5050.4 1503.62  5053.1 1503.12  5056.4 1503.62  5068.7 1505.66
  5178.4 1507.72  5249.1 1512.81  5286.1 1513.87  5315.3 1513.92  5330.7 1514.84
  5364.6 1515.48  5415.6 1517.13  5425.1  1516.9  5452.2 1518.56  5515.1 1520.07
#Mann= 6 ,-1 , 0
  4539.1     .16       0  4883.7      .1       0  5050.4     .07       0
  5056.4      .1       0  5286.1     .05       0  5364.6      .1       0
Bank Sta=5050.4,5056.4
XS Rating Curve= 0 ,0
Exp/Cntr=0.3,0.1

Type RM Length L Ch R = 1 ,1773    ,221,221,221
BEGIN DESCRIPTION:
Mapping XS 0bdd0e0f
END DESCRIPTION:
XS GIS Cut Line= 3
      2846674.49      10071991.9      2846445.33     10072028.36
      2845794.32     10072412.02
#Sta/Elev= 30
  4611.9 1520.03  4716.6 1515.71  4721.7 1515.93  4783.9 1513.58  4828.1 1511.17
    4861 1509.57  4866.8  1509.8  4882.5 1508.78    4904 1508.32  4909.9 1507.71
  4941.1 1506.99  4978.2 1504.77    4984 1505.05  4999.4 1502.54  5021.1 1504.45
  5053.6 1504.62  5072.5 1505.35  5079.6 1504.67  5095.3 1504.43  5101.1 1505.41
  5159.7 1506.09  5202.6 1507.83  5233.9 1508.17  5246.6 1509.08  5315.7 1510.77
    5431 1513.74  5458.3 1514.99  5473.9  1514.9  5501.4 1515.74  5599.6 1518.39
#Mann= 7 ,-1 , 0
  4611.9      .1       0  4828.1     .16       0    4984     .07       0
  5021.1     .16       0  5053.6      .1       0  5315.7     .05       0
  5501.4      .1       0
Bank Sta=4984,5021.1
XS Rating Curve= 0 ,0
Exp/Cntr=0.3,0.1

Type RM Length L Ch R = 1 ,1552    ,572,572,572
BEGIN DESCRIPTION:
UNT004 IN NNOGR 3.0
END DESCRIPTION:
XS GIS Cut Line= 2
      2846556.78     10071642.84      2845809.21     10072249.56
#Sta/Elev= 30
  4526.6    1516  4547.8 1515.16  4568.6 1515.45  4601.2 1514.57  4613.4 1514.16
    4690 1511.81  4696.5 1512.04  4739.6 1510.52  4768.3 1508.83  4774.8 1509.07
  4838.7 1506.25  4853.1 1504.67  4859.5 1504.68  4867.5 1503.86  4873.9 1504.06
  4881.8 1502.94    4917 1501.42  4931.4 1499.81    4981 1500.57  5009.5 1499.12
  5012.7 1499.62  5065.7 1501.08  5116.8  1502.4  5187.1 1505.25  5215.9  1505.7
  5287.6 1508.62  5400.2 1512.36  5478.1 1514.01    5486 1513.61  5489.4 1514.26
#Mann= 6 ,-1 , 0
  4526.6     .16       0  4601.2      .1       0  4613.4     .16       0
    4917     .07       0  5065.7     .16       0  5287.6      .1       0
Bank Sta=4917,5065.7
XS Rating Curve= 0 ,0
Exp/Cntr=0.3,0.1

Type RM Length L Ch R = 1 ,980     ,327,327,327
BEGIN DESCRIPTION:
UNT004 IN NNOGR 2.0
END DESCRIPTION:
XS GIS Cut Line= 2
      2846285.52      10071230.5      2845613.12      10071805.3
#Sta/Elev= 30
  4616.3 1503.85  4701.9 1500.94  4829.3 1497.96  4857.8 1495.65  4864.4 1495.87
  4872.1 1495.19  4921.5 1493.79  4956.6 1492.16  4970.9 1490.99  4978.6 1489.75
  4999.2 1487.74  5020.3 1489.73  5034.5 1490.35  5048.8 1490.44  5056.5 1491.17
  5112.5 1491.36  5148.7 1492.12  5155.3 1492.59  5177.3  1492.7  5183.8 1493.14
  5198.1 1492.81    5219 1494.31  5303.8 1496.72  5318.9 1496.92  5325.5 1497.47
  5333.2 1497.29  5361.2 1498.52  5453.9 1501.55  5460.5 1502.17  5500.9 1503.56
#Mann= 5 ,-1 , 0
  4616.3      .1       0  4978.6     .07       0  5034.5      .1       0
  5303.8     .16       0  5361.2      .1       0
Bank Sta=4978.6,5034.5
XS Rating Curve= 0 ,0
Exp/Cntr=0.3,0.1

Type RM Length L Ch R = 1 ,653     ,233,233,233
XS GIS Cut Line= 4
     2846334.036    10071092.459     2846033.689    10071073.362
     2845630.911     10071328.57     2845535.425    10071750.445
#Sta/Elev= 30
       0 1503.72   19.97 1503.05  149.77 1500.37   189.7  1498.3  279.56 1495.01
  299.53 1493.39   329.1 1491.58  358.48 1490.54  378.06 1489.24  436.82 1487.21
  475.99 1486.24  534.74 1483.67  564.12 1483.08   583.7 1482.36  593.49 1482.36
  622.87 1483.36  662.04  1484.6  691.42 1486.56  750.17 1487.92  769.76 1489.09
  888.73 1493.01  898.65 1493.58  928.43 1494.39  948.28  1494.6  968.13 1495.41
 1007.83 1496.29 1067.38 1498.44 1087.23 1499.45 1136.86 1501.33 1216.26 1502.76
#Mann= 3 , 0 , 0
       0     .05       0  564.12     .03       0  622.87     .05       0
Bank Sta=564.12,622.87
XS Rating Curve= 0 ,0
Exp/Cntr=0.3,0.1

Type RM Length L Ch R = 1 ,420     ,0,0,0
BEGIN DESCRIPTION:
UNT004 IN NNOGR 1.0
END DESCRIPTION:
XS GIS Cut Line= 3
      2846274.71      10070742.2       2845591.1     10071067.72
       2845460.9     10071697.04
#Sta/Elev= 30
  4366.1 1499.19  4395.2 1498.75  4589.8 1489.18  4612.5 1488.59  4627.8 1489.04
  4657.9 1487.06  4663.5 1487.38  4726.1 1485.52  4793.9 1484.53  4827.9 1483.36
  4845.1 1482.03  4876.8 1481.41  4896.1 1480.81  4913.2 1479.33  4964.2 1477.85
  4981.4 1476.29 4993.99  1473.7 5012.21 1473.76  5015.4 1476.67  5060.5 1480.33
  5101.8 1481.84  5325.7 1487.08    5409 1490.01  5476.6 1493.91  5578.7 1496.61
  5599.1 1496.28  5604.7 1497.77  5654.9 1497.93  5711.5 1499.36  5765.9 1499.67
#Mann= 6 ,-1 , 0
  4366.1      .1       0  4876.8     .05       0  4981.4     .03       0
  5015.4     .05       0  5101.8     .05       0  5325.7      .1       0
Bank Sta=4981.4,5015.4
XS Rating Curve= 0 ,0
Exp/Cntr=0.3,0.1

Chan Stop Cuts=-1
Use User Specified Reach Order=0
Composite Channel Slope=5