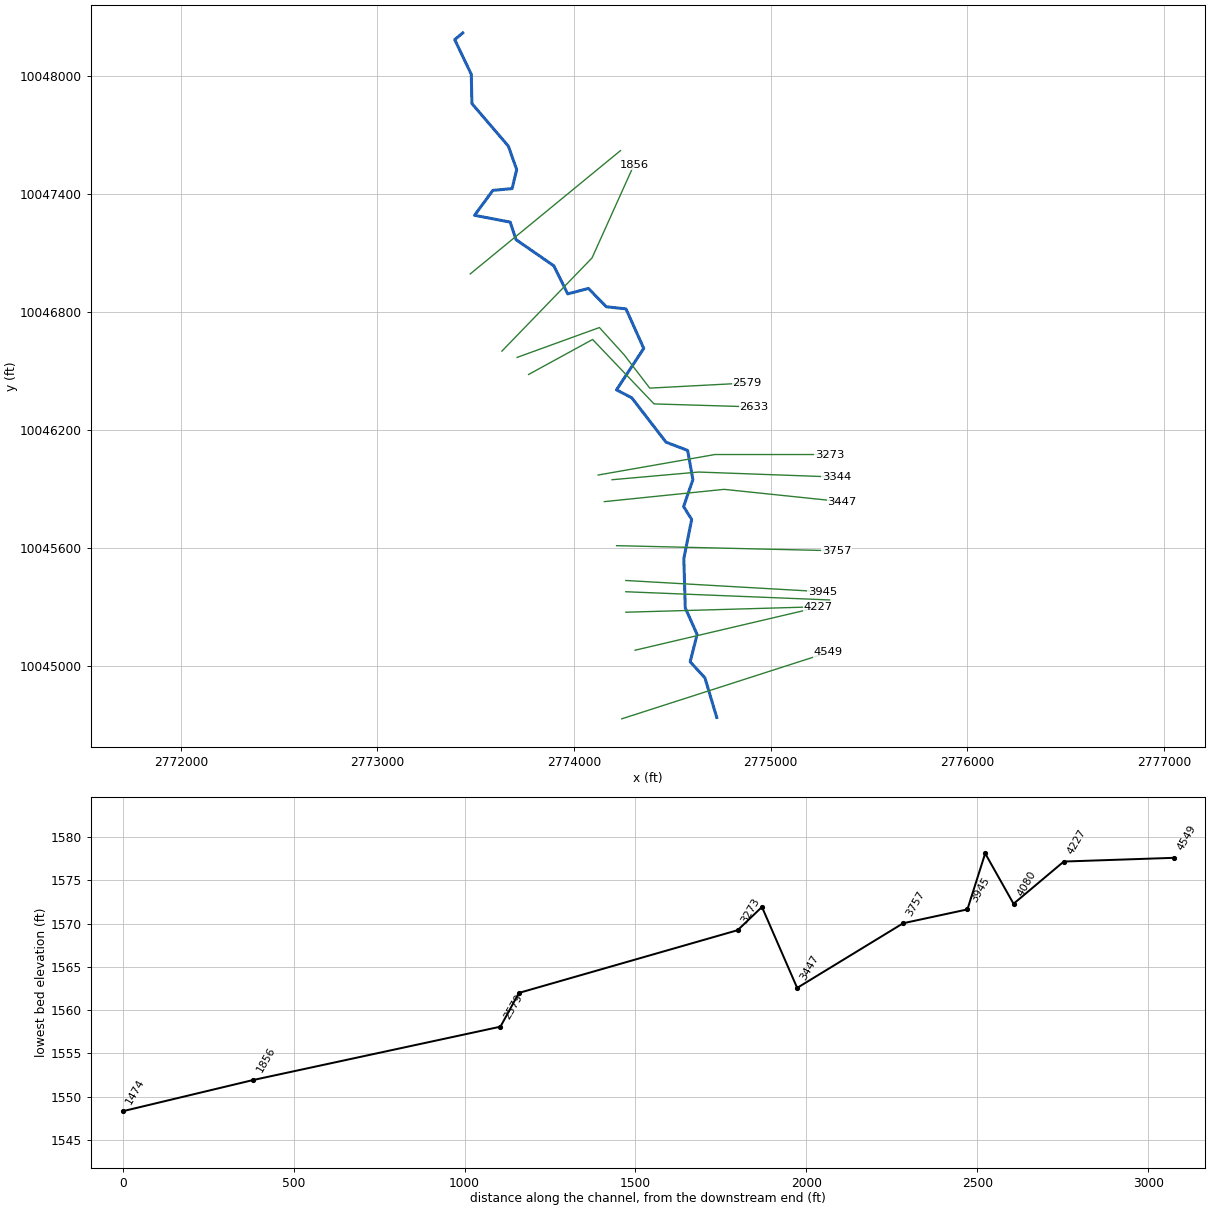
--- UNT004 IN SNOGR.prj (project) ---

Proj Title=UNT004 IN SNOGR Base Level Engineering
Current Plan=p01
Default Exp/Contr=0.3,0.1
English Units
Geom File=g01
Flow File=f01
Plan File=p01
Y Axis Title=Elevation
X Axis Title(PF)=Main Channel Distance
X Axis Title(XS)=Station
BEGIN DESCRIPTION:
UNT004 IN SNOGR
END DESCRIPTION:
DSS Export Rating Curves= 0
DSS Export Rating Curve Sorted= 0
DSS Export Volume Flow Curves= 0
DXF OffsetX= 0
DXF OffsetY= 0
DXF ScaleX= 1
DXF ScaleY= 10

--- UNT004 IN SNOGR.p01 (plan) ---

Plan Title=Multiple Run
Short Identifier=Multiple
Geom File=g01
Flow File=f01
Subcritical Flow
K Sum by GR= 0
Std Step Tol= 0.01
Critical Tol= 0.01
Num of Std Step Trials= 20
Max Error Tol= 0.3
Flow Tol Ratio= 0.001
Split Flow NTrial= 30
Split Flow Tol= 0.02
Split Flow Ratio= 0.02
Log Output Level= 0
Friction Slope Method= 1
Unsteady Friction Slope Method= 2
Unsteady Bridges Friction Slope Method= 1
Parabolic Critical Depth
Global Vel Dist=  1 , 1 , 1
Global Log Level= 0
CheckData=True
Encroach Param= -1, 0, 0, 0
BEGIN DESCRIPTION:
Multiple Run
END DESCRIPTION:

--- UNT004 IN SNOGR.f01 (steady flow) ---

Flow Title=Multiple
Program Version=4.10
Number of Profiles= 7
Profile Names=10-year,25-year,50-year,1pct_min,100-year,1pct_plu,500-year
River Rch & RM=UNT004 IN SNOGR,Reach-1         ,4549
     884    1290    1645    1536    2077    2809    3326
Boundary for River Rch & Prof#=UNT004 IN SNOGR,Reach-1         , 1
Up Type= 0
Dn Type= 3
Dn Slope=0.009
Boundary for River Rch & Prof#=UNT004 IN SNOGR,Reach-1         , 2
Up Type= 0
Dn Type= 3
Dn Slope=0.009
Boundary for River Rch & Prof#=UNT004 IN SNOGR,Reach-1         , 3
Up Type= 0
Dn Type= 3
Dn Slope=0.009
Boundary for River Rch & Prof#=UNT004 IN SNOGR,Reach-1         , 4
Up Type= 0
Dn Type= 3
Dn Slope=0.009
Boundary for River Rch & Prof#=UNT004 IN SNOGR,Reach-1         , 5
Up Type= 0
Dn Type= 3
Dn Slope=0.009
Boundary for River Rch & Prof#=UNT004 IN SNOGR,Reach-1         , 6
Up Type= 0
Dn Type= 3
Dn Slope=0.009
Boundary for River Rch & Prof#=UNT004 IN SNOGR,Reach-1         , 7
Up Type= 0
Dn Type= 3
Dn Slope=0.009
DSS Import GetInterval= 0
DSS Import GetPeak= 0
DSS Import FillOption= 0

--- UNT004 IN SNOGR.g01 (geometry) ---

Geom Title=Existing Conditions
Program Version=4.10

River Reach=UNT004 IN SNOGR ,Reach-1
Reach XY= 30
      2774726.08     10044736.95      2774665.95     10044938.15
      2774590.96     10045019.85      2774626.17     10045159.17
      2774565.94     10045294.09      2774558.58     10045544.66
       2774598.5     10045743.73      2774557.56     10045809.43
      2774604.73     10045946.72      2774577.98     10046095.07
      2774467.88     10046137.14       2774293.7     10046362.92
      2774216.17     10046403.22      2774354.69     10046614.32
      2774264.37     10046815.07      2774164.41      10046825.8
      2774073.22     10046919.11      2773967.88     10046891.26
      2773897.62     10047033.83      2773705.02     10047167.28
      2773675.31     10047256.48      2773494.16     10047290.98
      2773587.22     10047417.82      2773685.11     10047426.88
      2773708.42     10047523.48       2773666.2     10047642.79
       2773480.7     10047859.32       2773477.5     10048008.26
      2773393.19     10048184.77      2773434.47     10048218.89

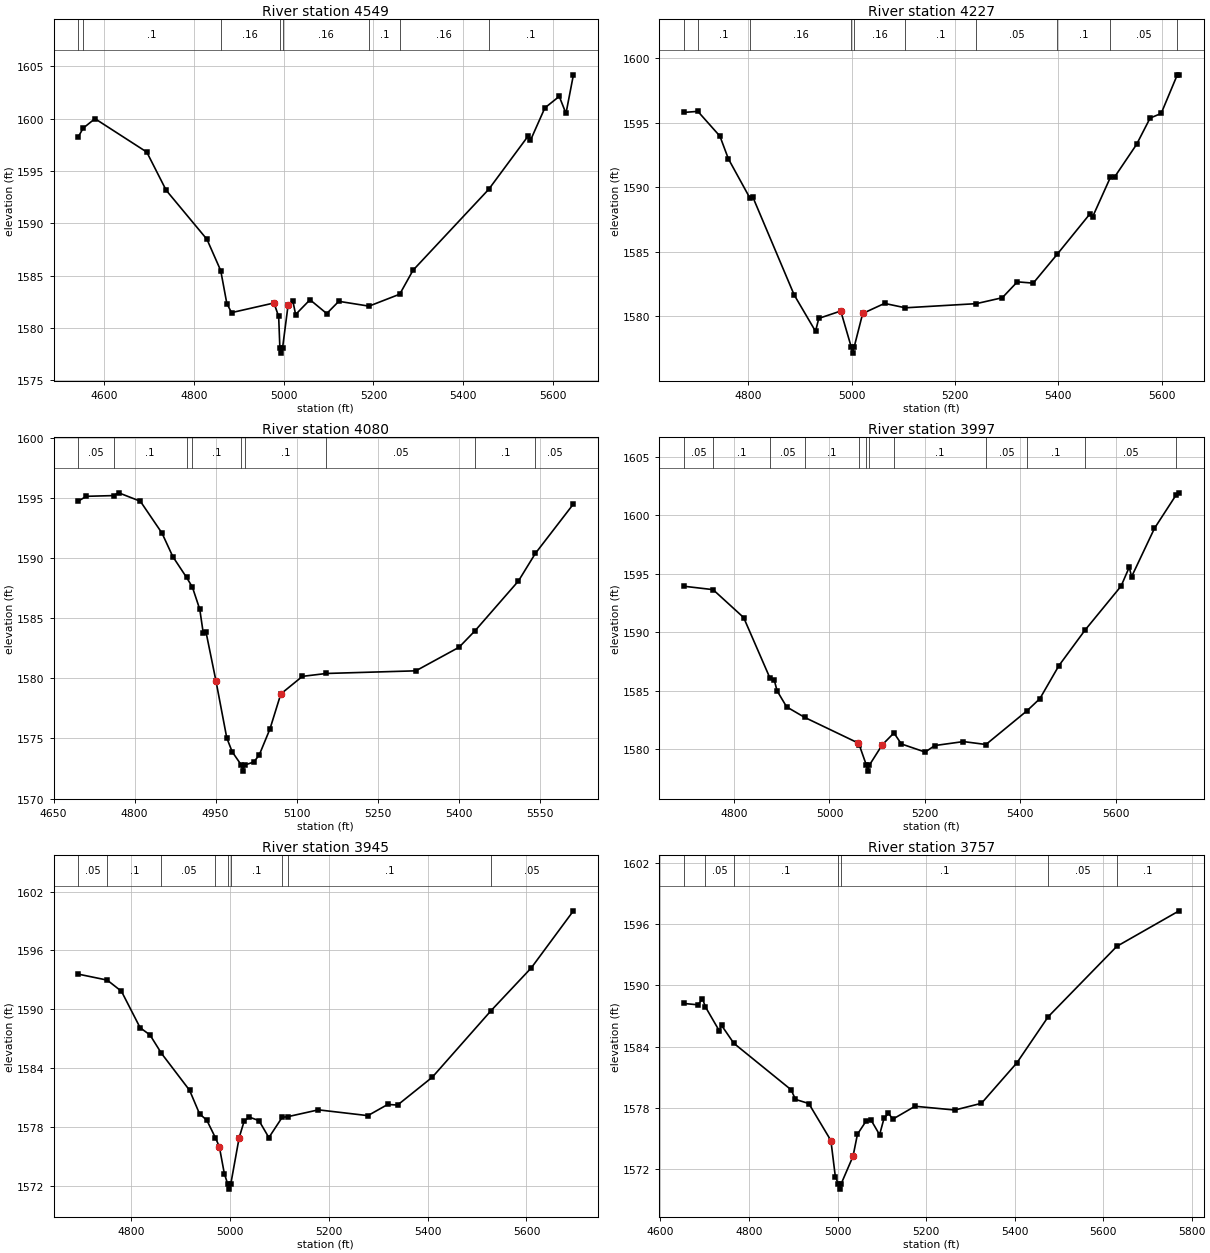
Type RM Length L Ch R = 1 ,4549    ,322,322,322
BEGIN DESCRIPTION:
UNT004 IN SNOGR 8.0
END DESCRIPTION:
XS GIS Cut Line= 2
      2774243.07     10044729.93      2775294.29      10045068.2
#Sta/Elev= 30
  4541.6 1598.26  4552.6 1599.09  4578.8 1599.99  4694.3  1596.8  4737.6 1593.15
  4828.6 1588.46  4859.3 1585.47  4872.9 1582.33  4883.4 1581.46    4978 1582.38
  4988.5 1581.09  4991.2 1578.09    4994 1577.59  4997.2 1578.09  5009.5 1582.17
    5020  1582.6  5026.3 1581.28  5058.4 1582.69  5095.7 1581.37  5122.6 1582.54
    5190 1582.08  5258.5 1583.22  5288.2 1585.51    5457 1593.24  5544.9 1598.33
  5550.1 1597.92  5582.2 1601.02  5614.3 1602.12  5629.3 1600.49  5645.9 1604.18
#Mann= 8 ,-1 , 0
  4541.6     .05       0  4552.6      .1       0  4859.3     .16       0
  4991.2     .07       0  4997.2     .16       0    5190      .1       0
  5258.5     .16       0    5457      .1       0
Bank Sta=4978,5009.5
XS Rating Curve= 0 ,0
Exp/Cntr=0.3,0.1

Type RM Length L Ch R = 1 ,4227    ,147,147,147
BEGIN DESCRIPTION:
UNT004 IN SNOGR 7.0
END DESCRIPTION:
XS GIS Cut Line= 2
      2774310.81      10045078.9      2775243.09     10045297.65
#Sta/Elev= 30
    4676  1595.8  4702.8 1595.88  4745.5 1593.96  4761.9  1592.2  4803.2 1589.19
  4809.4 1589.22  4889.2 1581.66  4930.4 1578.85  4936.7 1579.85  4979.2 1580.42
  4999.3 1577.66    5002 1577.16  5005.3 1577.66  5021.6 1580.23  5063.9 1581.01
  5104.1 1580.67  5241.2 1580.99  5291.6 1581.45  5320.7 1582.68  5351.5 1582.58
  5397.5  1584.8  5461.3 1587.95  5466.4 1587.72  5500.8 1590.78  5508.9  1590.8
  5551.3 1593.32  5577.5 1595.36  5598.9 1595.72  5630.1 1598.71  5633.6 1598.71
#Mann= 10 ,-1 , 0
    4676     .05       0  4702.8      .1       0  4803.2     .16       0
  4999.3     .07       0  5005.3     .16       0  5104.1      .1       0
  5241.2     .05       0  5397.5      .1       0  5500.8     .05       0
  5630.1      .1       0
Bank Sta=4979.2,5021.6
XS Rating Curve= 0 ,0
Exp/Cntr=0.3,0.1

Type RM Length L Ch R = 1 ,4080    ,83,83,83
BEGIN DESCRIPTION:
Mapping XS e73b3c08
END DESCRIPTION:
XS GIS Cut Line= 2
      2774263.56     10045272.11      2775180.19     10045298.16
#Sta/Elev= 30
  4695.7 1594.73  4710.6 1595.13  4760.9 1595.19  4770.6 1595.42  4810.6 1594.72
  4850.7 1592.07  4870.7 1590.12  4896.3 1588.38    4907 1587.58  4920.7 1585.73
  4927.2 1583.73  4932.2 1583.85  4950.7 1579.77  4970.7 1575.04  4980.7 1573.89
  4997.7 1572.78  5000.5 1572.28  5003.7 1572.78  5020.7 1573.04  5030.7 1573.61
  5050.7 1575.79  5070.8  1578.7  5110.8 1580.16  5155.2  1580.4  5320.9 1580.62
  5400.9 1582.58  5430.7 1583.96  5510.9 1588.09  5542.2 1590.38  5612.7 1594.49
#Mann= 9 ,-1 , 0
  4695.7     .05       0  4760.9      .1       0  4896.3     .05       0
    4907      .1       0  4997.7     .07       0  5003.7      .1       0
  5155.2     .05       0  5430.7      .1       0  5542.2     .05       0
Bank Sta=4950.7,5070.8
XS Rating Curve= 0 ,0
Exp/Cntr=0.3,0.1

Type RM Length L Ch R = 1 ,3997    ,52,52,52
BEGIN DESCRIPTION:
Mapping XS 02f1ebe6
END DESCRIPTION:
XS GIS Cut Line= 2
      2774263.54     10045376.28        2775300.     10045334.62
#Sta/Elev= 30
  4695.2 1593.93  4756.1 1593.64  4820.2 1591.25  4875.6 1586.04  4884.2 1585.91
  4890.3 1584.97  4910.3  1583.6  4948.1  1582.7  5060.4  1580.5  5062.8  1580.3
  5077.4  1578.6  5080.2  1578.1  5083.4  1578.6  5110.5 1580.35  5135.1 1581.37
  5150.5 1580.43  5200.5 1579.73  5220.6 1580.29  5280.6 1580.63  5327.8 1580.38
  5413.9 1583.27  5440.7  1584.3  5480.8 1587.14  5535.7 1590.19  5610.9 1593.94
    5628 1595.56    5633 1594.75  5680.9 1598.89  5726.4 1601.76  5732.5 1601.93
#Mann= 12 ,-1 , 0
  4695.2     .05       0  4756.1      .1       0  4875.6     .05       0
  4948.1      .1       0  5062.8     .05       0  5077.4     .07       0
  5083.4     .05       0  5135.1      .1       0  5327.8     .05       0
  5413.9      .1       0  5535.7     .05       0  5726.4      .1       0
Bank Sta=5060.4,5110.5
XS Rating Curve= 0 ,0
Exp/Cntr=0.3,0.1

Type RM Length L Ch R = 1 ,3945    ,188,188,188
BEGIN DESCRIPTION:
Mapping XS 35aa5a45
END DESCRIPTION:
XS GIS Cut Line= 2
      2774263.58     10045433.57      2775263.55     10045376.28
#Sta/Elev= 30
  4693.4 1593.57  4751.9 1592.96  4780.7 1591.82  4818.5  1588.1  4838.5 1587.36
  4861.7 1585.48  4918.6 1581.71  4938.7 1579.31  4953.3 1578.67  4970.8 1576.87
  4978.7 1575.96  4988.8 1573.22  4995.8 1572.13  4998.5 1571.63  5001.8 1572.13
  5018.8 1576.88  5028.8 1578.55  5038.8 1578.99  5058.9 1578.62  5078.9 1576.89
  5105.9 1578.96  5116.9 1579.02  5179.1 1579.72  5279.2 1579.13  5319.3 1580.27
  5339.3 1580.21  5409.5 1583.05  5528.5 1589.85  5609.8 1594.21    5695 1600.03
#Mann= 9 ,-1 , 0
  4693.4     .05       0  4751.9      .1       0  4861.7     .05       0
  4970.8      .1       0  4995.8     .07       0  5001.8      .1       0
  5105.9     .05       0  5116.9      .1       0  5528.5     .05       0
Bank Sta=4978.7,5018.8
XS Rating Curve= 0 ,0
Exp/Cntr=0.3,0.1

Type RM Length L Ch R = 1 ,3757    ,310,310,310
BEGIN DESCRIPTION:
UNT004 IN SNOGR 6.0
END DESCRIPTION:
XS GIS Cut Line= 2
      2774216.68     10045610.66      2775334.97     10045584.65
#Sta/Elev= 30
  4653.1 1588.22  4684.9 1588.09  4694.9 1588.68  4701.5 1587.89  4732.9 1585.54
  4737.9 1586.08  4765.7 1584.32    4895 1579.77    4905 1578.82    4935 1578.42
    4985 1574.79    4995 1571.26    5002 1570.53  5004.7 1570.03    5008 1570.53
    5035 1573.25    5045 1575.41    5065 1576.73    5075 1576.85    5095 1575.36
    5105 1576.96    5115 1577.46    5125 1576.89    5175 1578.15  5265.1 1577.78
  5325.1 1578.44  5405.1  1582.4  5475.9 1586.92    5631 1593.82  5771.7  1597.3
#Mann= 7 ,-1 , 0
  4653.1      .1       0  4701.5     .05       0  4765.7      .1       0
    5002     .07       0    5008      .1       0  5475.9     .05       0
    5631      .1       0
Bank Sta=4985,5035
XS Rating Curve= 0 ,0
Exp/Cntr=0.3,0.1

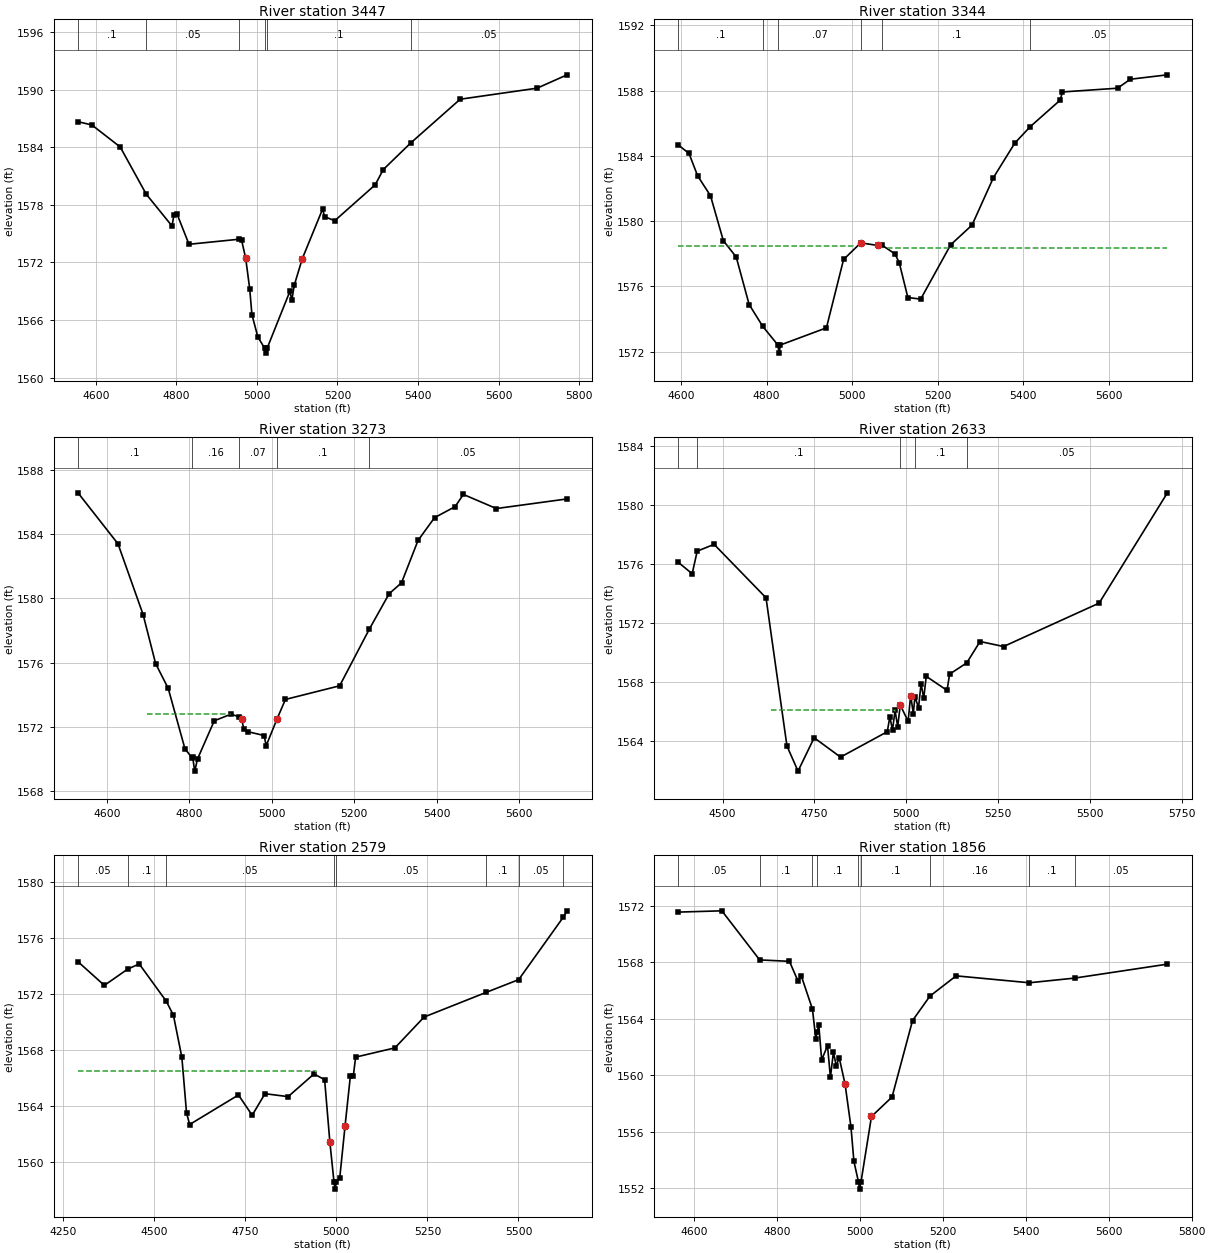
Type RM Length L Ch R = 1 ,3447    ,103,103,103
BEGIN DESCRIPTION:
UNT004 IN SNOGR 5.0
END DESCRIPTION:
XS GIS Cut Line= 3
      2774154.18     10045834.61      2774763.56     10045897.11
      2775362.53     10045834.61
#Sta/Elev= 30
  4555.5 1586.65    4590 1586.31  4660.3 1584.02  4725.1  1579.1  4788.9  1575.8
    4794 1576.96  4801.1 1577.08  4831.2 1573.89  4956.3 1574.42  4961.9 1574.31
    4972 1572.44    4982 1569.26  4987.5 1566.57  5002.1 1564.26  5019.2 1563.06
    5022 1562.56  5025.2 1563.06  5081.7 1568.98  5086.7 1568.09  5092.6 1569.62
  5112.7  1572.4    5163 1577.55    5168 1576.77  5193.1 1576.34  5293.7 1580.08
  5313.8 1581.67    5382 1584.44  5504.8 1588.99  5695.8 1590.14  5770.3 1591.53
#Mann= 6 ,-1 , 0
  4555.5      .1       0  4725.1     .05       0  4956.3      .1       0
  5019.2     .07       0  5025.2      .1       0    5382     .05       0
Bank Sta=4972,5112.7
XS Rating Curve= 0 ,0
Exp/Cntr=0.3,0.1

Type RM Length L Ch R = 1 ,3344    ,71,71,71
BEGIN DESCRIPTION:
Mapping XS 6c534013
END DESCRIPTION:
XS GIS Cut Line= 3
      2774193.56     10045946.08      2774633.71     10045985.14
      2775334.97     10045959.67
#Sta/Elev= 30
  4593.6 1584.67  4618.6 1584.15  4638.7 1582.78  4668.8 1581.56  4698.9  1578.8
    4729  1577.8  4759.2 1574.89    4791 1573.55  4826.4 1572.41  4829.2 1571.91
  4832.4 1572.41  4939.9 1573.46    4980 1577.65  5020.2 1578.67  5060.3 1578.51
  5070.3 1578.52  5100.3 1577.99  5110.3 1577.44  5130.3 1575.32  5160.3 1575.22
  5230.4 1578.55  5280.4 1579.76  5330.4 1582.67  5380.5 1584.79  5416.8  1585.8
  5486.6 1587.42  5491.6 1587.92  5620.6 1588.15  5650.6  1588.7  5737.2 1588.97
#Mann= 6 ,-1 , 0
  4593.6      .1       0    4791     .05       0  4826.4     .07       0
  5020.2     .05       0  5070.3      .1       0  5416.8     .05       0
#XS Ineff= 2 , 0
         5005.33 1578.48 5080.46         1578.38
Permanent Ineff=
       T       T
Bank Sta=5020.2,5060.3
XS Rating Curve= 0 ,0
Exp/Cntr=0.3,0.1

Type RM Length L Ch R = 1 ,3273    ,640,640,640
BEGIN DESCRIPTION:
Mapping XS 14935046
END DESCRIPTION:
XS GIS Cut Line= 3
      2774122.95     10045970.03      2774716.69      10046074.2
      2775299.99      10046074.2
#Sta/Elev= 30
    4530 1586.58    4627  1583.4  4687.9 1578.99  4718.3 1575.93  4748.8 1574.39
  4789.4 1570.62  4806.3 1570.07  4808.2 1570.08  4813.1 1569.23  4819.9 1569.99
  4860.5 1572.37  4901.1 1572.78  4921.4 1572.61    4927 1572.45  4932.1 1571.87
  4941.7 1571.69  4981.3 1571.45  4986.4 1570.82  5012.8 1572.49  5033.1  1573.7
  5164.6 1574.55  5236.5 1578.08  5284.6 1580.29  5314.6 1580.97  5354.6 1583.61
  5394.6 1585.03  5444.6 1585.72  5464.6 1586.48  5544.6  1585.6  5716.1  1586.2
#Mann= 5 ,-1 , 0
    4530      .1       0  4806.3     .16       0  4921.4     .07       0
  5012.8      .1       0  5236.5     .05       0
#XS Ineff= 1 ,-1
 4696.79 4900.93 1572.82
Permanent Ineff=
       T
Bank Sta=4927,5012.8
XS Rating Curve= 0 ,0
Exp/Cntr=0.3,0.1

Type RM Length L Ch R = 1 ,2633    ,54,54,54
BEGIN DESCRIPTION:
Mapping XS 7f32a47f
END DESCRIPTION:
XS GIS Cut Line= 4
      2773769.02     10046481.43      2774094.57      10046659.4
      2774407.07     10046331.71      2774914.21     10046316.54
#Sta/Elev= 30
  4379.5 1576.12  4417.2 1575.35  4430.9 1576.88  4476.9 1577.34  4618.2 1573.72
  4675.2 1563.68  4705.3 1561.98  4749.2 1564.24    4821 1562.93  4948.3 1564.65
  4955.2 1565.67  4962.5 1564.76  4969.4 1566.09  4976.6 1564.99  4983.6 1566.45
    5005 1565.36  5011.9  1567.1  5019.1 1565.88  5023.6 1567.03  5033.3 1566.27
  5040.2 1567.91  5047.4 1566.92  5054.3  1568.4  5110.9 1567.45  5117.9 1568.55
  5164.5 1569.31  5200.7 1570.76  5264.8 1570.42  5524.9 1573.36  5710.7 1580.83
#Mann= 5 ,-1 , 0
  4379.5     .05       0  4430.9      .1       0  4983.6     .05       0
  5023.6      .1       0  5164.5     .05       0
#XS Ineff= 1 ,-1
 4631.49 4968.84 1566.14
Permanent Ineff=
       T
Bank Sta=4983.6,5011.9
XS Rating Curve= 0 ,0
Exp/Cntr=0.3,0.1

Type RM Length L Ch R = 1 ,2579    ,723,723,723
BEGIN DESCRIPTION:
UNT004 IN SNOGR 4.0
END DESCRIPTION:
XS GIS Cut Line= 5
       2773710.5     10046568.27       2774129.3     10046720.16
      2774255.16     10046581.27      2774385.37       10046412.
       2774880.2     10046438.05
#Sta/Elev= 30
  4291.3 1574.31  4363.6 1572.62  4427.6 1573.78  4459.3 1574.15  4533.8 1571.48
  4553.2 1570.48  4576.3 1567.49  4589.1 1563.53  4597.6 1562.69  4731.6  1564.8
  4769.2 1563.35  4804.4 1564.89  4867.9 1564.68  4938.9  1566.3    4968 1565.89
  4982.5 1561.41  4993.8 1558.58  4996.6 1558.08  4999.8 1558.58  5009.6  1558.9
  5024.1 1562.59  5038.6 1566.13  5046.8 1566.16  5053.1  1567.5  5160.9 1568.16
    5241 1570.36  5411.3 1572.12  5500.5 1573.03  5623.3  1577.5  5633.3 1577.94
#Mann= 8 ,-1 , 0
  4291.3     .05       0  4427.6      .1       0  4533.8     .05       0
  4993.8    .035       0  4999.8     .05       0  5411.3      .1       0
  5500.5     .05       0  5623.3      .1       0
#XS Ineff= 2 , 0
         4944.57 1566.52
Permanent Ineff=
       T       T
Bank Sta=4982.5,5024.1
XS Rating Curve= 0 ,0
Exp/Cntr=0.3,0.1

Type RM Length L Ch R = 1 ,1856    ,382,382,382
BEGIN DESCRIPTION:
UNT004 IN SNOGR 3.0
END DESCRIPTION:
XS GIS Cut Line= 3
      2773633.34     10046600.23      2774091.69      10047074.2
      2774305.24     10047548.18
#Sta/Elev= 30
  4562.3 1571.56  4667.3 1571.65  4758.4 1568.17  4830.2 1568.07  4851.3 1566.64
  4858.5 1567.06  4885.7 1564.68  4893.7 1562.59  4897.1 1563.06  4900.9 1563.58
  4907.9 1561.08    4922 1562.09    4929 1559.84  4936.2 1561.62  4943.1 1560.67
  4950.3 1561.23  4964.4 1559.35  4978.6 1556.32  4985.6  1553.9  4996.7 1552.42
  4999.4 1551.92  5002.7 1552.42    5028 1557.07  5077.6 1558.45    5127 1563.87
  5168.8  1565.6  5232.1 1567.04  5408.7 1566.55  5517.6 1566.88  5741.5 1567.87
#Mann= 9 ,-1 , 0
  4562.3     .05       0  4758.4      .1       0  4885.7     .05       0
  4897.1      .1       0  4996.7     .07       0  5002.7      .1       0
  5168.8     .16       0  5408.7      .1       0  5517.6     .05       0
Bank Sta=4964.4,5028
XS Rating Curve= 0 ,0
Exp/Cntr=0.3,0.1

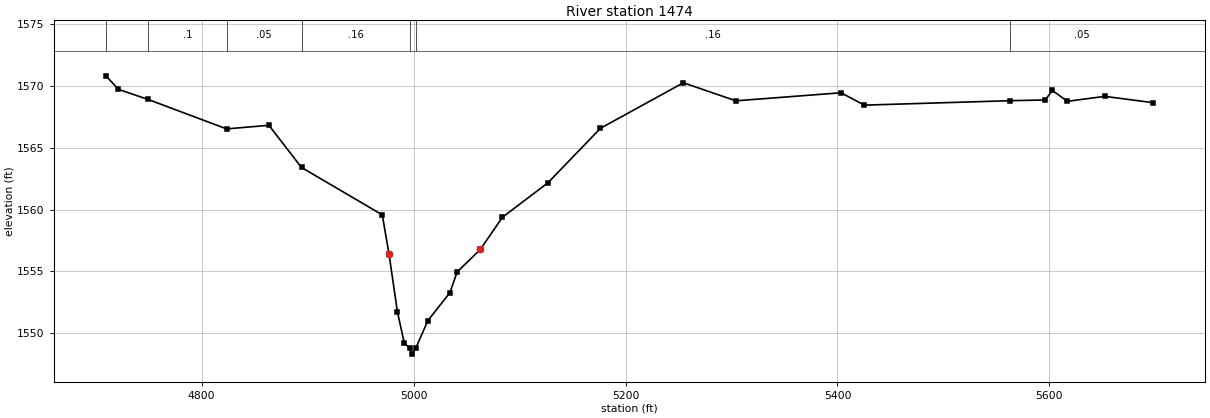
Type RM Length L Ch R = 1 ,1474    ,0,0,0
BEGIN DESCRIPTION:
UNT004 IN SNOGR 2.0
END DESCRIPTION:
XS GIS Cut Line= 2
      2773472.28     10046992.98      2774236.06     10047619.87
#Sta/Elev= 30
  4709.7 1570.81  4721.5 1569.72  4749.5  1568.9  4823.6 1566.52  4863.5 1566.81
  4894.3  1563.4  4970.5 1559.57  4976.9 1556.37  4984.8 1551.72  4991.3 1549.19
  4996.2 1548.81  4998.9 1548.31  5002.2 1548.81  5013.5 1551.02  5034.3 1553.28
  5041.1 1554.95    5063 1556.77  5083.8 1559.37  5126.9 1562.17  5176.4 1566.57
  5254.6 1570.25  5304.1 1568.79  5403.4 1569.44  5425.4 1568.44  5563.1  1568.8
  5596.2 1568.86  5602.7 1569.63    5617 1568.75  5652.2 1569.15  5697.8 1568.64
#Mann= 7 ,-1 , 0
  4709.7     .05       0  4749.5      .1       0  4823.6     .05       0
  4894.3     .16       0  4996.2     .07       0  5002.2     .16       0
  5563.1     .05       0
Bank Sta=4976.9,5063
XS Rating Curve= 0 ,0
Exp/Cntr=0.3,0.1

Chan Stop Cuts=-1
Use User Specified Reach Order=0
Composite Channel Slope=5