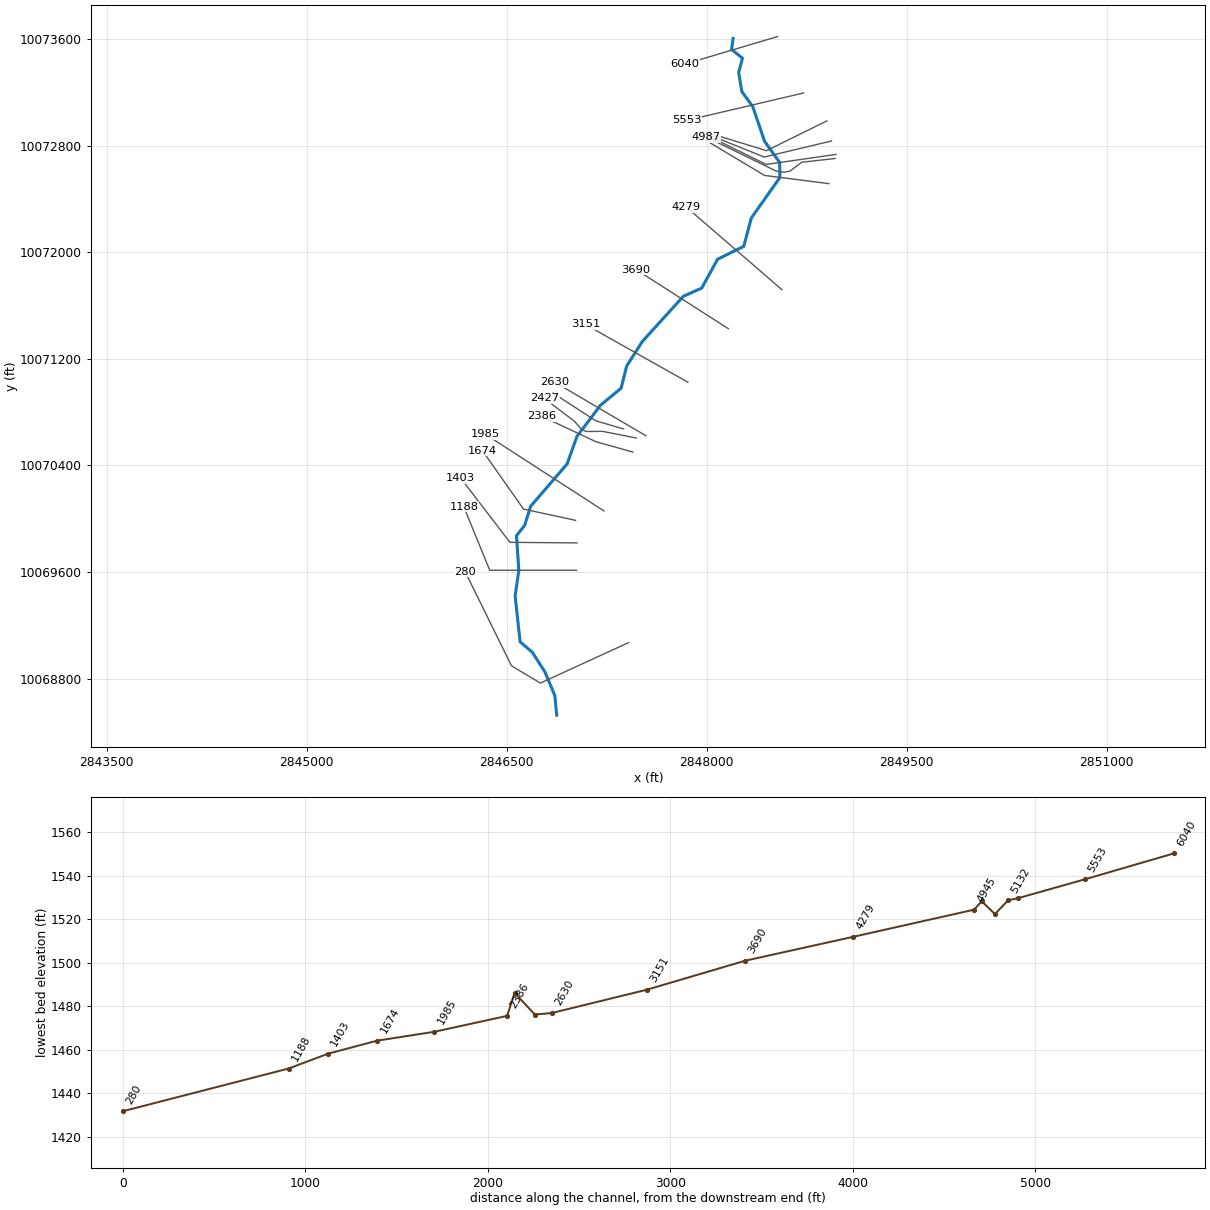
--- UNT005 IN NNOGR.prj (project) ---

Proj Title=UNT005 IN NNOGR Base Level Engineering
Current Plan=p01
Default Exp/Contr=0.3,0.1
English Units
Geom File=g01
Flow File=f01
Plan File=p01
Y Axis Title=Elevation
X Axis Title(PF)=Main Channel Distance
X Axis Title(XS)=Station
BEGIN DESCRIPTION:
UNT005 IN NNOGR
END DESCRIPTION:
DSS Export Rating Curves= 0
DSS Export Rating Curve Sorted= 0
DSS Export Volume Flow Curves= 0
DXF OffsetX= 0
DXF OffsetY= 0
DXF ScaleX= 1
DXF ScaleY= 10

--- UNT005 IN NNOGR.p01 (plan) ---

Plan Title=Multiple Run
Short Identifier=Multiple
Geom File=g01
Flow File=f01
Subcritical Flow
K Sum by GR= 0
Std Step Tol= 0.01
Critical Tol= 0.01
Num of Std Step Trials= 20
Max Error Tol= 0.3
Flow Tol Ratio= 0.001
Split Flow NTrial= 30
Split Flow Tol= 0.02
Split Flow Ratio= 0.02
Log Output Level= 0
Friction Slope Method= 1
Unsteady Friction Slope Method= 2
Unsteady Bridges Friction Slope Method= 1
Parabolic Critical Depth
Global Vel Dist=  1 , 1 , 1
Global Log Level= 0
CheckData=True
Encroach Param= -1, 0, 0, 0
BEGIN DESCRIPTION:
Multiple Run
END DESCRIPTION:

--- UNT005 IN NNOGR.f01 (steady flow) ---

Flow Title=Multiple
Program Version=4.10
Number of Profiles= 7
Profile Names=10-year,25-year,50-year,1pct_min,100-year,1pct_plu,500-year
River Rch & RM=UNT005 IN NNOGR,Reach-1         ,6040
     442     614     758     687     929    1257    1398
Boundary for River Rch & Prof#=UNT005 IN NNOGR,Reach-1         , 1
Up Type= 0
Dn Type= 3
Dn Slope=0.023
Boundary for River Rch & Prof#=UNT005 IN NNOGR,Reach-1         , 2
Up Type= 0
Dn Type= 3
Dn Slope=0.023
Boundary for River Rch & Prof#=UNT005 IN NNOGR,Reach-1         , 3
Up Type= 0
Dn Type= 3
Dn Slope=0.023
Boundary for River Rch & Prof#=UNT005 IN NNOGR,Reach-1         , 4
Up Type= 0
Dn Type= 3
Dn Slope=0.023
Boundary for River Rch & Prof#=UNT005 IN NNOGR,Reach-1         , 5
Up Type= 0
Dn Type= 3
Dn Slope=0.023
Boundary for River Rch & Prof#=UNT005 IN NNOGR,Reach-1         , 6
Up Type= 0
Dn Type= 3
Dn Slope=0.023
Boundary for River Rch & Prof#=UNT005 IN NNOGR,Reach-1         , 7
Up Type= 0
Dn Type= 3
Dn Slope=0.023
DSS Import GetInterval= 0
DSS Import GetPeak= 0
DSS Import FillOption= 0

--- UNT005 IN NNOGR.g01 (geometry) ---

Geom Title=Existing Conditions
Program Version=4.10

River Reach=UNT005 IN NNOGR ,Reach-1
Reach XY= 30
      2848197.86     10073602.82      2848186.09     10073521.42
      2848268.38     10073454.75      2848239.58     10073348.78
      2848263.36     10073204.69      2848345.15     10073092.36
      2848434.23      10072831.4      2848547.33     10072673.25
      2848548.49     10072559.39       2848334.3     10072255.92
        2848278.      10072043.8      2848081.58     10071947.22
      2847962.63     10071730.73       2847825.4     10071669.79
       2847516.9     10071330.08      2847399.88     10071146.34
      2847357.64     10070979.42      2847201.91      10070850.7
      2847026.23     10070617.47      2846952.69     10070411.29
      2846678.98     10070093.64      2846634.12     10069950.79
      2846572.64     10069873.11      2846590.48     10069613.67
      2846562.75      10069420.9      2846600.17     10069076.95
      2846691.84     10068998.63      2846786.97     10068849.61
      2846860.28     10068674.71      2846874.68     10068526.82

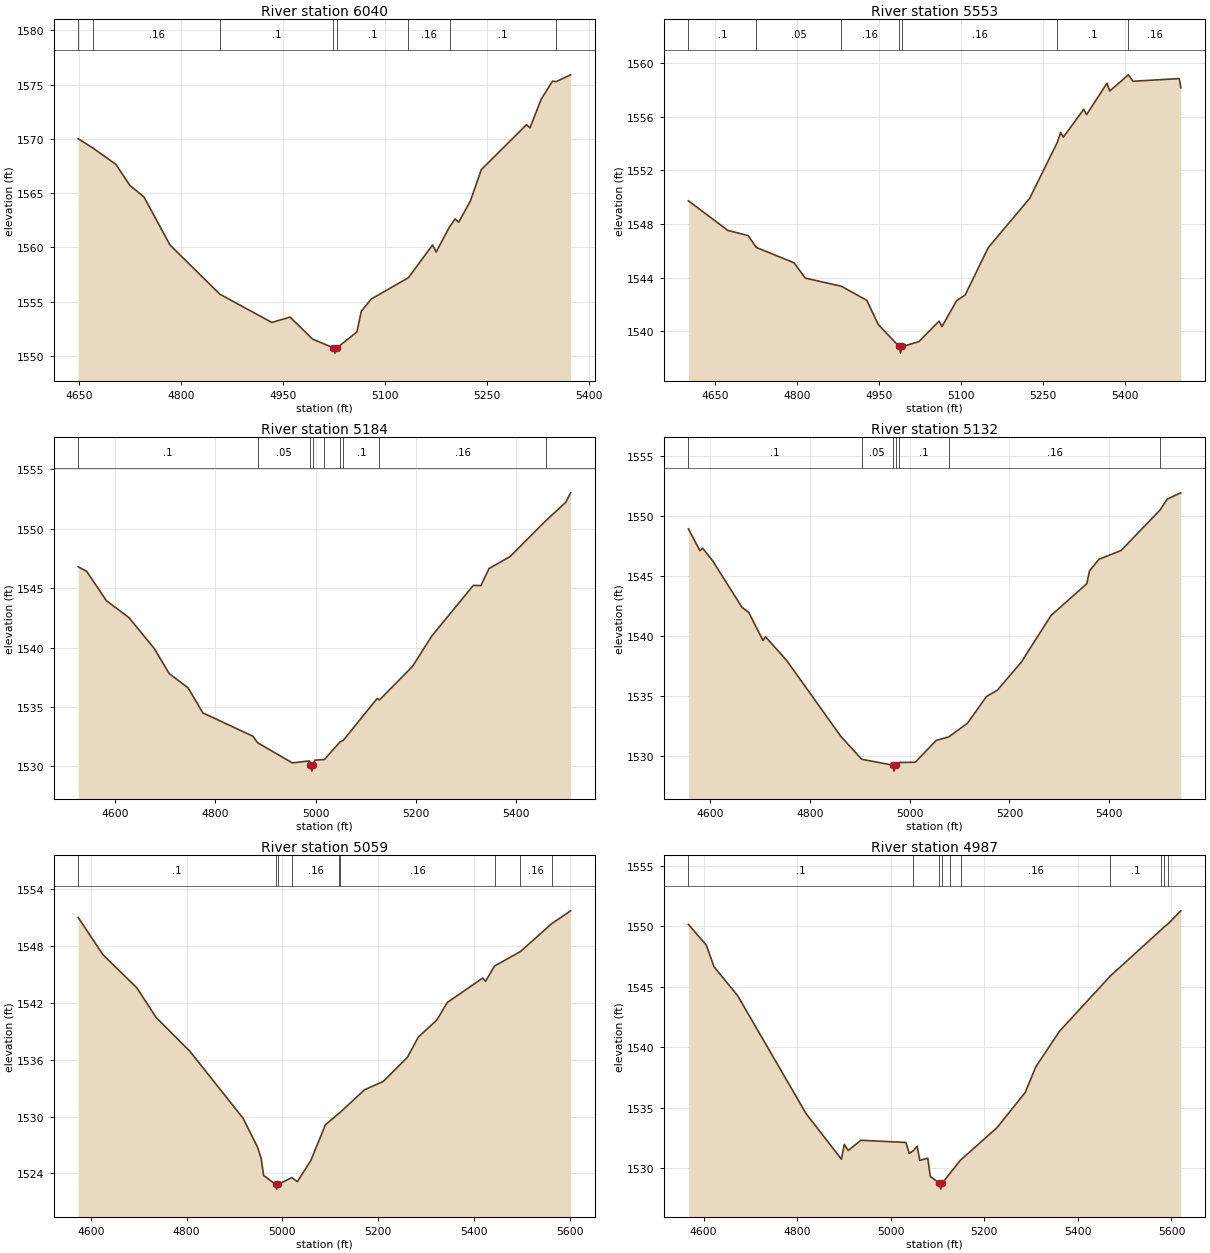
Type RM Length L Ch R = 1 ,6040    ,487,487,487
BEGIN DESCRIPTION:
UNT005 IN NNOGR 11.0
END DESCRIPTION:
XS GIS Cut Line= 2
      2848531.62     10073617.63      2847837.17     10073411.47
#Sta/Elev= 30
  4648.6 1570.02  4670.8 1569.14    4704 1567.66  4724.9  1565.7  4745.3 1564.66
  4783.8 1560.21  4857.2 1555.68  4933.5 1553.08  4960.3 1553.57  4993.5 1551.54
  5023.7 1550.75  5026.5 1550.25  5029.7 1550.75  5058.7 1552.21  5065.1 1554.11
  5079.6 1555.23  5134.5 1557.21    5170 1560.23  5175.2 1559.57  5194.9 1561.88
  5203.2 1562.63  5208.4 1562.32  5225.6 1564.28  5241.7 1567.17  5308.1 1571.31
  5313.3 1571.02  5329.9 1573.68  5346.5 1575.33  5351.7 1575.28    5373 1575.91
#Mann= 8 ,-1 , 0
  4648.6     .05       0  4670.8     .16       0  4857.2      .1       0
  5023.7     .07       0  5029.7      .1       0  5134.5     .16       0
  5194.9      .1       0  5351.7     .16       0
Bank Sta=5023.7,5029.7
XS Rating Curve= 0 ,0
Exp/Cntr=0.3,0.1

Type RM Length L Ch R = 1 ,5553    ,369,369,369
BEGIN DESCRIPTION:
UNT005 IN NNOGR 10.0
END DESCRIPTION:
XS GIS Cut Line= 2
      2848726.96     10073194.46      2847848.99     10072988.52
#Sta/Elev= 30
  4600.6 1549.73  4672.8 1547.52  4710.1 1547.13  4724.9 1546.25  4794.2  1545.1
  4814.7 1543.96  4880.9 1543.35  4927.4  1542.3  4948.3  1540.5  4986.4 1538.86
  4989.1 1538.36  4992.4 1538.86  5022.5 1539.21  5059.8 1540.75    5065 1540.34
  5092.1 1542.29  5107.4 1542.69  5149.9 1546.24  5225.6 1549.91  5275.9 1554.06
  5282.3 1554.82  5287.4 1554.48  5324.7 1556.56  5329.9 1556.16  5367.2  1558.5
  5372.3 1557.92  5406.4 1559.13  5414.8 1558.65  5499.6 1558.85  5502.4 1558.17
#Mann= 7 ,-1 , 0
  4600.6      .1       0  4724.9     .05       0  4880.9     .16       0
  4986.4     .07       0  4992.4     .16       0  5275.9      .1       0
  5406.4     .16       0
Bank Sta=4986.4,4992.4
XS Rating Curve= 0 ,0
Exp/Cntr=0.3,0.1

Type RM Length L Ch R = 1 ,5184    ,52,52,52
BEGIN DESCRIPTION:
Mapping XS be0372d7
END DESCRIPTION:
XS GIS Cut Line= 3
      2848901.24     10072984.99      2848448.77     10072761.46
      2847993.24     10072901.38
#Sta/Elev= 30
  4526.9 1546.81  4543.9 1546.42  4583.2 1543.95  4628.1 1542.53  4678.5 1539.93
  4708.5 1537.81  4745.9 1536.62  4775.4 1534.51  4874.9 1532.55  4884.8 1531.99
  4953.8  1530.3  4987.2 1530.47  4989.7 1530.11  4992.5 1529.61  4995.7 1530.11
  4998.4 1530.53  5017.6 1530.59  5048.5 1532.06  5055.4 1532.21  5122.6 1535.72
  5127.2  1535.6  5193.3 1538.43  5231.2 1540.96  5314.3 1545.24  5329.4 1545.23
  5345.7 1546.66  5387.6 1547.67  5458.4 1550.67  5498.2 1552.22  5508.1 1553.03
#Mann= 9 ,-1 , 0
  4526.9      .1       0  4884.8     .05       0  4989.7     .04       0
  4995.7     .05       0  5017.6      .1       0  5048.5     .05       0
  5055.4      .1       0  5127.2     .16       0  5458.4      .1       0
Bank Sta=4989.7,4995.7
XS Rating Curve= 0 ,0
Exp/Cntr=0.3,0.1

Type RM Length L Ch R = 1 ,5132    ,73,73,73
BEGIN DESCRIPTION:
Mapping XS 370c47ea
END DESCRIPTION:
XS GIS Cut Line= 3
      2848935.94     10072834.16      2848431.41     10072713.72
      2847997.35     10072888.43
#Sta/Elev= 30
  4556.8  1548.9    4580 1547.08  4585.2 1547.29  4605.6 1546.23  4664.2 1542.36
  4677.6 1541.95  4706.3  1539.6  4711.5  1539.9  4753.6 1537.94  4862.6 1531.59
  4904.1  1529.7  4966.2 1529.21  4968.9 1528.71  4972.2 1529.21  4978.2 1529.43
  5011.3 1529.45  5053.4 1531.27  5078.9 1531.57  5116.1 1532.71  5154.1 1534.93
  5175.7 1535.45  5223.5 1537.77  5283.5 1541.68  5355.1 1544.33  5360.5 1545.39
  5379.3 1546.36  5423.6 1547.09  5501.5 1550.45  5516.3 1551.38  5543.4  1551.9
#Mann= 7 ,-1 , 0
  4556.8      .1       0  4904.1     .05       0  4966.2     .07       0
  4972.2     .05       0  4978.2      .1       0  5078.9     .16       0
  5501.5      .1       0
Bank Sta=4966.2,4972.2
XS Rating Curve= 0 ,0
Exp/Cntr=0.3,0.1

Type RM Length L Ch R = 1 ,5059    ,72,72,72
BEGIN DESCRIPTION:
UNT005 IN NNOGR 9.0
END DESCRIPTION:
XS GIS Cut Line= 3
      2848969.63     10072733.26       2848446.6     10072658.38
      2847997.36     10072878.66
#Sta/Elev= 30
  4573.5    1551  4625.2 1547.08  4695.9 1543.59  4736.3 1540.46    4807 1536.88
  4918.1 1529.82  4948.4 1526.76  4955.9 1525.57  4960.9  1523.8  4985.9 1522.85
  4988.6 1522.35  4991.9 1522.85  5019.6 1523.57  5031.6 1523.14  5059.6 1525.37
  5089.9 1529.13    5119 1530.38  5121.4 1530.47  5171.5 1532.82  5210.9 1533.71
  5261.5 1536.26    5284 1538.38  5322.5 1540.17  5344.8 1542.04  5418.9 1544.62
  5424.5 1544.26  5443.4 1545.88  5497.5 1547.41  5563.1 1550.36  5602.2  1551.7
#Mann= 9 ,-1 , 0
  4573.5      .1       0  4985.9     .07       0  4991.9      .1       0
  5019.6     .16       0    5119      .1       0  5121.4     .16       0
  5443.4      .1       0  5497.5     .16       0  5563.1      .1       0
Bank Sta=4985.9,4991.9
XS Rating Curve= 0 ,0
Exp/Cntr=0.3,0.1

Type RM Length L Ch R = 1 ,4987    ,42,42,42
BEGIN DESCRIPTION:
Mapping XS 760ab03a
END DESCRIPTION:
XS GIS Cut Line= 6
      2848963.05     10072702.87      2848712.44     10072674.66
      2848624.55     10072607.39      2848576.81     10072599.79
      2848523.64     10072607.39      2847995.22     10072864.54
#Sta/Elev= 30
  4567.4 1550.16  4605.8 1548.44  4622.3 1546.65  4672.6 1544.27  4819.1  1534.5
  4894.5 1530.74  4900.8 1531.96    4909 1531.46  4936.4  1532.3  5032.3 1532.12
  5039.5 1531.22  5048.6 1531.45  5056.5 1531.81  5062.1 1530.63  5079.1 1530.82
  5084.6  1529.3  5104.2 1528.76  5106.9 1528.26  5110.2 1528.76  5126.6 1529.57
  5149.4 1530.67  5227.1 1533.34  5287.5 1536.26  5310.1 1538.38  5360.7 1541.32
  5469.4 1545.89  5578.3 1549.72  5583.3 1549.91  5593.4 1550.22    5620 1551.28
#Mann= 10 ,-1 , 0
  4567.4      .1       0  5048.6     .16       0  5104.2     .07       0
  5110.2     .16       0  5126.6      .1       0  5149.4     .16       0
  5469.4      .1       0  5578.3     .16       0  5583.3      .1       0
  5593.4     .16       0
Bank Sta=5104.2,5110.2
XS Rating Curve= 0 ,0
Exp/Cntr=0.3,0.1

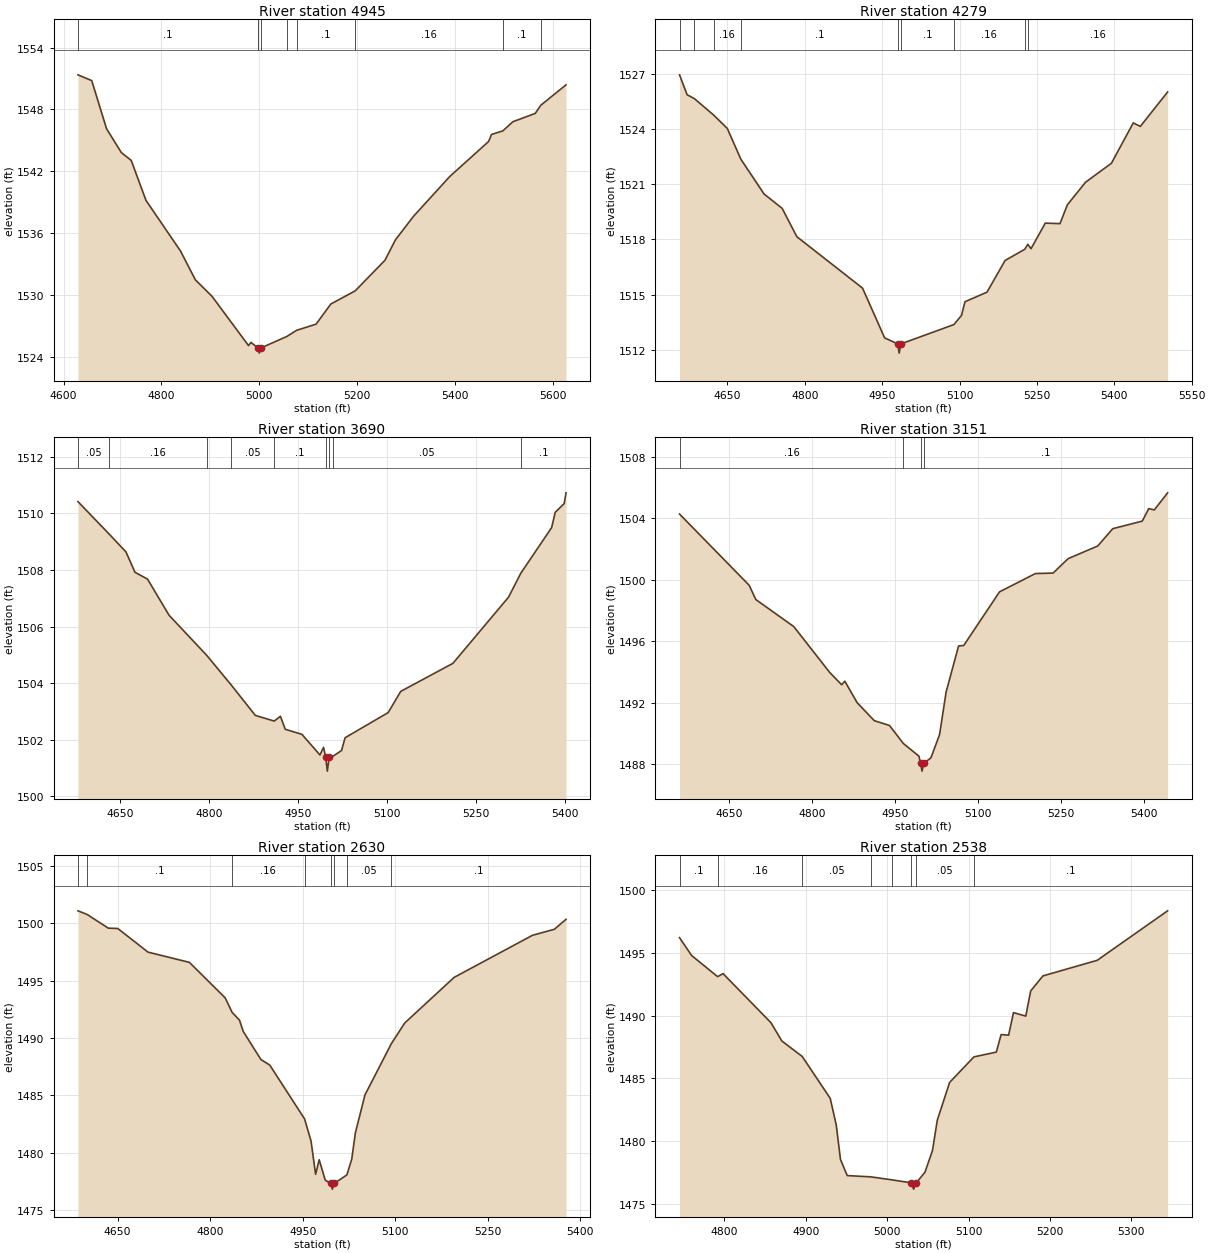
Type RM Length L Ch R = 1 ,4945    ,666,666,666
BEGIN DESCRIPTION:
Mapping XS 27cb4c0a
END DESCRIPTION:
XS GIS Cut Line= 3
      2848916.48     10072514.06      2848433.58     10072575.92
      2847995.25     10072838.48
#Sta/Elev= 30
  4629.3 1551.36  4657.5  1550.8  4687.8 1546.13    4718 1543.82  4738.2 1543.06
  4768.4 1539.18    4839 1534.27  4869.3 1531.48  4903.4 1529.88    4978  1525.1
    4983 1525.41  4997.3 1524.87  5000.1 1524.37  5003.3 1524.87  5056.1 1525.98
  5076.2 1526.58  5116.1 1527.18  5146.2 1529.13  5196.1 1530.41    5257 1533.38
  5278.4 1535.36  5315.3 1537.64  5389.2 1541.49  5468.9  1544.9  5474.8 1545.58
  5497.8 1545.92  5518.4 1546.81  5564.2 1547.62  5575.5 1548.41  5627.1 1550.39
#Mann= 8 ,-1 , 0
  4629.3      .1       0  4997.3     .07       0  5003.3      .1       0
  5056.1     .16       0  5076.2      .1       0  5196.1     .16       0
  5497.8      .1       0  5575.5     .16       0
Bank Sta=4997.3,5003.3
XS Rating Curve= 0 ,0
Exp/Cntr=0.3,0.1

Type RM Length L Ch R = 1 ,4279    ,589,589,589
BEGIN DESCRIPTION:
UNT005 IN NNOGR 7.0
END DESCRIPTION:
XS GIS Cut Line= 2
      2848564.22     10071718.74      2847848.04     10072337.26
#Sta/Elev= 30
  4557.1 1526.94  4571.8 1525.86  4585.8 1525.65  4623.1 1524.76  4649.7 1524.03
    4676 1522.36    4721 1520.47  4756.1 1519.69  4784.6 1518.15  4911.9 1515.36
  4954.7 1512.66  4980.2 1512.33  4982.9 1511.83  4986.2 1512.33    5089 1513.38
  5103.8 1513.88  5110.5 1514.62  5153.2 1515.14  5188.3 1516.86  5226.5 1517.47
  5232.3 1517.74  5238.6  1517.5  5266.2 1518.89  5294.7 1518.86    5309 1519.88
  5344.3 1521.11  5394.5 1522.14  5436.8 1524.33  5450.5 1524.14  5503.4 1526.01
#Mann= 9 ,-1 , 0
  4557.1     .16       0  4585.8      .1       0  4623.1     .16       0
    4676      .1       0  4980.2     .07       0  4986.2      .1       0
    5089     .16       0  5226.5      .1       0  5232.3     .16       0
Bank Sta=4980.2,4986.2
XS Rating Curve= 0 ,0
Exp/Cntr=0.3,0.1

Type RM Length L Ch R = 1 ,3690    ,539,539,539
BEGIN DESCRIPTION:
UNT005 IN NNOGR 6.0
END DESCRIPTION:
XS GIS Cut Line= 2
      2848162.74     10071425.78      2847469.75     10071869.73
#Sta/Elev= 30
  4579.3 1510.42    4632 1509.27  4660.3 1508.64  4675.5 1507.92  4696.6 1507.68
    4733  1506.4  4796.2 1504.99    4838 1503.93  4878.4 1502.86  4910.3 1502.66
  4920.7 1502.83  4928.8 1502.37    4957 1502.19  4987.4 1501.46  4993.4 1501.73
    4997 1501.39  4999.8 1500.89    5003 1501.39  5008.9 1501.41  5023.8 1501.62
  5029.7 1502.07  5102.4 1502.96  5123.6 1503.71  5211.5  1504.7  5305.3 1507.04
  5326.1 1507.89    5378  1509.5    5384 1510.04  5399.2 1510.35  5402.3 1510.73
#Mann= 9 ,-1 , 0
  4579.3     .05       0    4632     .16       0  4796.2      .1       0
    4838     .05       0  4910.3      .1       0    4997     .07       0
    5003      .1       0  5008.9     .05       0  5326.1      .1       0
Bank Sta=4997,5003
XS Rating Curve= 0 ,0
Exp/Cntr=0.3,0.1

Type RM Length L Ch R = 1 ,3151    ,521,521,521
BEGIN DESCRIPTION:
UNT005 IN NNOGR 5.0
END DESCRIPTION:
XS GIS Cut Line= 2
      2847858.87     10071024.34      2847088.51     10071458.34
#Sta/Elev= 30
  4559.5 1504.27  4685.6 1499.64  4697.7 1498.71  4766.5 1496.95  4831.5 1493.97
  4853.2 1493.17  4858.9  1493.4  4881.3    1492  4912.4 1490.83  4939.8 1490.52
  4964.9 1489.35  4993.3 1488.52  4996.1 1488.05  4998.8 1487.55  5002.1 1488.05
    5015 1488.42  5030.6 1489.93  5042.4 1492.69    5065 1495.69  5074.3 1495.72
  5139.2 1499.21  5204.2  1500.4  5236.1 1500.43  5263.5 1501.37    5317 1502.19
  5344.4 1503.32  5397.8 1503.81  5409.4 1504.62  5419.6 1504.54  5443.7 1505.65
#Mann= 4 ,-1 , 0
  4559.5     .16       0  4964.9      .1       0  4996.1     .07       0
  5002.1      .1       0
Bank Sta=4996.1,5002.1
XS Rating Curve= 0 ,0
Exp/Cntr=0.3,0.1

Type RM Length L Ch R = 1 ,2630    ,92,92,92
BEGIN DESCRIPTION:
UNT005 IN NNOGR 4.0
END DESCRIPTION:
XS GIS Cut Line= 2
      2847544.19     10070622.86      2846862.04     10071023.49
#Sta/Elev= 30
  4585.8 1501.09  4600.8 1500.77    4635 1499.58  4650.4 1499.55  4699.4 1497.49
  4766.4  1496.6  4824.4 1493.51  4835.7 1492.24  4847.6 1491.57  4853.7 1490.58
  4882.4 1488.13  4896.7 1487.65  4953.1 1482.96  4963.6 1481.03    4971 1478.13
  4976.8  1479.4  4986.6 1477.62  4995.3 1477.34  4998.1 1476.84  5001.3 1477.34
  5021.7 1478.08  5029.6 1479.46  5035.4 1481.73    5051 1485.05  5093.6  1489.5
  5115.5 1491.32  5195.5 1495.29  5322.6 1498.96  5357.9 1499.48  5376.9 1500.35
#Mann= 8 ,-1 , 0
  4585.8     .16       0  4600.8      .1       0  4835.7     .16       0
  4953.1      .1       0  4995.3     .07       0  5001.3      .1       0
  5021.7     .05       0  5093.6      .1       0
Bank Sta=4995.3,5001.3
XS Rating Curve= 0 ,0
Exp/Cntr=0.3,0.1

Type RM Length L Ch R = 1 ,2538    ,111,111,111
BEGIN DESCRIPTION:
Mapping XS 78cf8463
END DESCRIPTION:
XS GIS Cut Line= 3
      2847376.31      10070674.2      2847168.01     10070734.95
      2846846.83     10070943.28
#Sta/Elev= 30
  4744.9 1496.22  4759.7  1494.8  4791.7 1493.11  4798.4 1493.35  4857.2 1489.44
  4870.6 1487.98  4895.7 1486.74  4930.1  1483.4  4937.5 1481.27  4942.7 1478.52
    4951 1477.24  4979.7 1477.14    5006  1476.9  5029.8 1476.66  5032.6 1476.16
  5035.8 1476.66  5046.5 1477.51  5055.7 1479.23  5061.7 1481.67  5076.8 1484.67
  5106.7 1486.71  5134.2 1487.09  5140.1 1488.49  5149.3 1488.44  5155.3 1490.24
  5170.4 1489.96  5176.4 1491.97  5191.5 1493.17  5258.1 1494.41  5344.7 1498.36
#Mann= 8 ,-1 , 0
  4744.9      .1       0  4791.7     .16       0  4895.7     .05       0
  4979.7      .1       0    5006     .05       0  5029.8     .07       0
  5035.8     .05       0  5106.7      .1       0
Bank Sta=5029.8,5035.8
XS Rating Curve= 0 ,0
Exp/Cntr=0.3,0.1

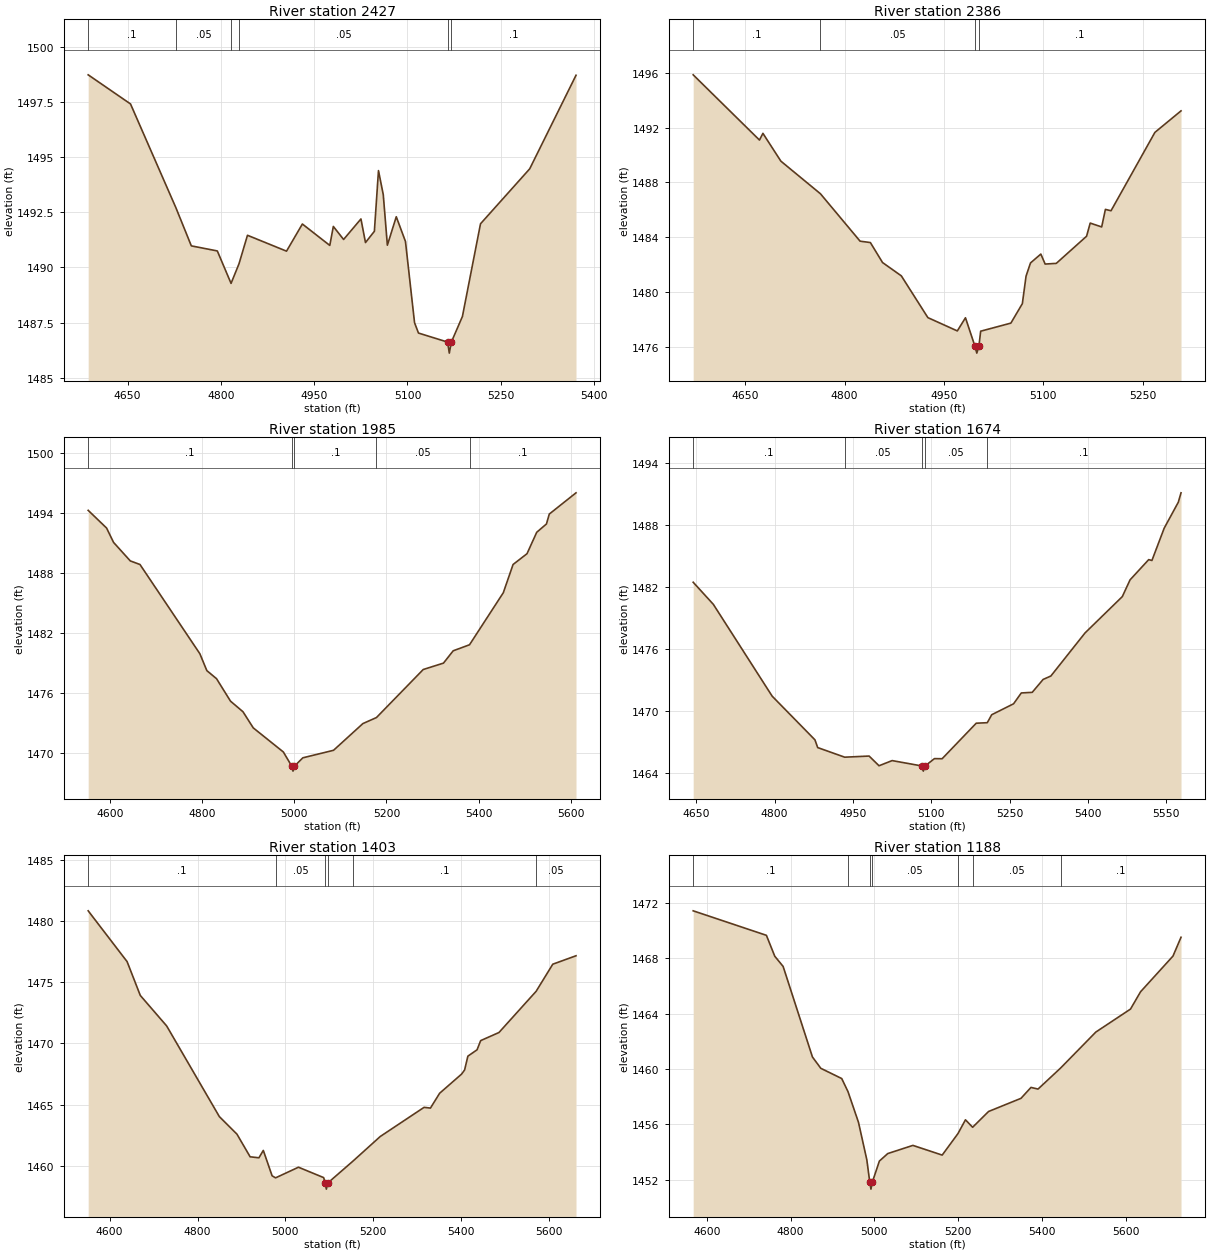
Type RM Length L Ch R = 1 ,2427    ,41,41,41
BEGIN DESCRIPTION:
Mapping XS 686021cd
END DESCRIPTION:
XS GIS Cut Line= 6
       2847472.3     10070605.97      2847218.39     10070655.89
      2847094.69      10070654.8      2847056.72     10070674.33
      2847008.97     10070730.76      2846782.29     10070902.39
#Sta/Elev= 30
  4586.5 1498.73  4654.6 1497.41  4727.7  1492.7  4752.4 1490.98  4794.2 1490.75
  4816.3 1489.28  4829.1 1490.17  4842.7 1491.46  4905.5 1490.74    4931 1491.97
  4975.1    1491  4980.8 1491.86  4997.3 1491.27  5025.2  1492.2  5032.5 1491.13
  5046.8 1491.64  5053.4 1494.39  5061.1  1493.3  5067.7 1491.01    5082  1492.3
  5096.8 1491.18  5111.4  1487.5  5117.7 1487.03  5164.6 1486.62  5167.3 1486.12
  5170.6 1486.62  5188.4 1487.78  5217.5 1491.98  5296.6 1494.47  5371.1 1498.71
#Mann= 6 ,-1 , 0
  4586.5      .1       0  4727.7     .05       0  4816.3     .16       0
  4829.1     .05       0  5164.6    .035       0  5170.6      .1       0
Bank Sta=5164.6,5170.6
XS Rating Curve= 0 ,0
Exp/Cntr=0.3,0.1

Type RM Length L Ch R = 1 ,2386    ,401,401,401
BEGIN DESCRIPTION:
Mapping XS 7ffb4eec
END DESCRIPTION:
XS GIS Cut Line= 3
      2847445.81     10070500.57      2847168.01      10070578.7
      2846762.79     10070768.38
#Sta/Elev= 30
  4571.7 1495.85  4671.7 1491.09  4676.9 1491.58    4704 1489.55  4763.7 1487.17
  4823.5 1483.71    4839 1483.61  4857.4 1482.15  4885.7 1481.18  4925.8 1478.13
  4970.2 1477.16  4982.5 1478.12  4996.8 1476.04  4999.6 1475.54  5002.8 1476.04
  5005.4 1477.14    5051 1477.73  5068.3 1479.15  5073.9 1481.16  5080.6 1482.12
  5096.2 1482.77  5102.7 1482.04  5119.5 1482.09  5165.2 1484.07  5170.7 1485.03
    5188 1484.75  5193.6 1486.03  5202.1 1485.93  5268.3 1491.65  5307.7 1493.22
#Mann= 4 ,-1 , 0
  4571.7      .1       0  4763.7     .05       0  4996.8     .07       0
  5002.8      .1       0
Bank Sta=4996.8,5002.8
XS Rating Curve= 0 ,0
Exp/Cntr=0.3,0.1

Type RM Length L Ch R = 1 ,1985    ,311,311,311
BEGIN DESCRIPTION:
UNT005 IN NNOGR 3.0
END DESCRIPTION:
XS GIS Cut Line= 2
      2847229.52     10070058.64      2846339.78     10070633.71
#Sta/Elev= 30
  4552.3 1494.24  4592.3 1492.47  4607.4 1491.04  4643.7 1489.19  4664.8 1488.83
  4794.8 1479.92    4810 1478.23  4831.1 1477.42  4861.4 1475.18  4888.5 1474.12
  4910.8 1472.51  4976.2  1470.1  4994.3 1468.69  4997.1 1468.19  5000.3 1468.69
  5018.5 1469.52  5085.1 1470.27  5148.9 1472.94  5178.3 1473.54  5279.9 1478.34
  5323.9 1478.98    5345 1480.21  5380.4 1480.81  5453.8 1486.01    5475 1488.83
  5505.3 1489.91  5526.4 1492.05  5547.5 1492.88  5553.7 1493.87  5611.7 1495.99
#Mann= 5 ,-1 , 0
  4552.3      .1       0  4994.3     .07       0  5000.3      .1       0
  5178.3     .05       0  5380.4      .1       0
Bank Sta=4994.3,5000.3
XS Rating Curve= 0 ,0
Exp/Cntr=0.3,0.1

Type RM Length L Ch R = 1 ,1674    ,271,271,271
BEGIN DESCRIPTION:
Mapping XS 4ac9361d
END DESCRIPTION:
XS GIS Cut Line= 3
      2847016.23      10069988.2      2846625.58     10070072.84
      2846318.32     10070509.94
#Sta/Elev= 30
  4644.3 1482.44  4682.9  1480.3  4795.5 1471.41  4877.4 1467.18  4882.7 1466.43
  4934.4  1465.5  4981.1 1465.61  5000.1 1464.67  5025.2 1465.17  5082.2 1464.65
  5084.9 1464.15  5088.2 1464.65  5106.2 1465.36  5120.9 1465.35  5186.2 1468.79
  5207.4 1468.84  5215.8 1469.61  5257.7 1470.67  5272.5 1471.72  5293.4 1471.78
  5314.3 1473.03  5329.1 1473.36  5394.5 1477.53  5465.9 1481.05  5480.7 1482.67
  5516.4 1484.63  5522.6 1484.55  5546.1 1487.68  5573.1 1490.19  5578.3  1491.1
#Mann= 5 ,-1 , 0
  4644.3      .1       0  4934.4     .05       0  5082.2     .04       0
  5088.2     .05       0  5207.4      .1       0
Bank Sta=5082.2,5088.2
XS Rating Curve= 0 ,0
Exp/Cntr=0.3,0.1

Type RM Length L Ch R = 1 ,1403    ,215,215,215
BEGIN DESCRIPTION:
Mapping XS 5124781c
END DESCRIPTION:
XS GIS Cut Line= 3
      2847027.02     10069818.94      2846523.59     10069823.28
      2846154.63     10070305.08
#Sta/Elev= 30
  4551.1 1480.83  4639.7 1476.68  4669.7 1473.92  4729.7 1471.43  4849.7 1464.02
  4889.7 1462.59  4919.7 1460.74  4939.7 1460.66  4949.7 1461.26  4969.7 1459.19
  4977.6 1459.02  5029.7 1459.89  5087.1 1459.04  5090.4  1458.6  5093.2  1458.1
  5096.4  1458.6  5153.5 1460.38  5215.9  1462.4  5315.6 1464.78  5330.1 1464.72
    5351 1465.93  5400.8 1467.49  5407.8 1467.83  5415.3 1468.96  5436.2 1469.48
  5444.4 1470.23    5486 1470.89  5570.7 1474.26  5608.5 1476.47  5661.4 1477.16
#Mann= 6 ,-1 , 0
  4551.1      .1       0  4977.6     .05       0  5090.4     .04       0
  5096.4     .05       0  5153.5      .1       0  5570.7     .05       0
Bank Sta=5090.4,5096.4
XS Rating Curve= 0 ,0
Exp/Cntr=0.3,0.1

Type RM Length L Ch R = 1 ,1188    ,908,908,908
BEGIN DESCRIPTION:
UNT005 IN NNOGR 2.0
END DESCRIPTION:
XS GIS Cut Line= 3
      2847023.37     10069613.73      2846372.35     10069613.73
      2846177.55      10070089.9
#Sta/Elev= 30
  4567.1 1471.42    4742 1469.65    4762 1468.14    4782  1467.4    4852 1460.86
    4872 1460.04    4922  1459.3    4937 1458.35    4962 1456.14    4982 1453.42
    4989 1451.81  4991.8 1451.31    4995 1451.81    5012 1453.34    5032 1453.88
    5092 1454.47    5162 1453.77  5199.6 1455.32  5217.6 1456.32  5234.7 1455.78
  5272.8 1456.92  5350.2 1457.87  5374.2 1458.66    5391 1458.54  5444.9 1460.06
  5529.1 1462.66  5611.9 1464.32  5635.9 1465.57  5713.4 1468.15  5732.6 1469.51
#Mann= 7 ,-1 , 0
  4567.1      .1       0    4937     .05       0    4989     .04       0
    4995     .05       0  5199.6      .1       0  5234.7     .05       0
  5444.9      .1       0
Bank Sta=4989,4995
XS Rating Curve= 0 ,0
Exp/Cntr=0.3,0.1

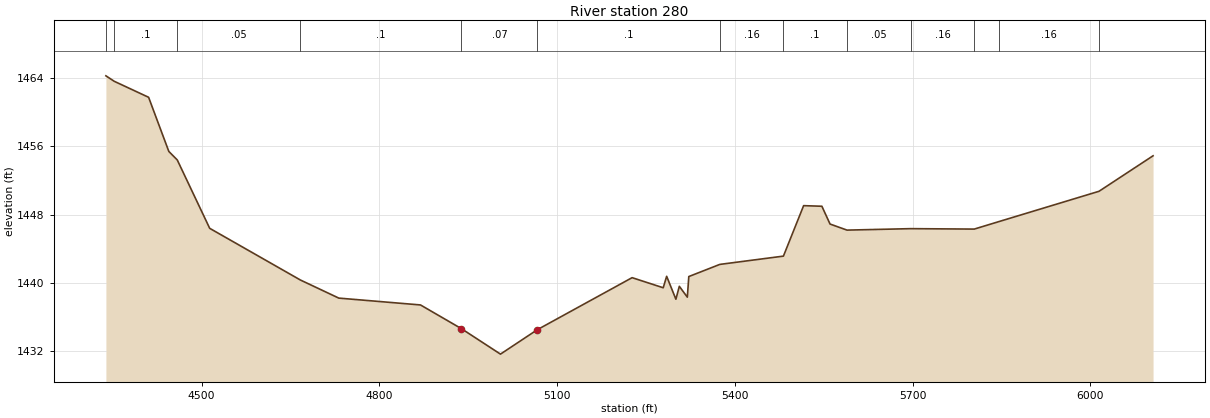
Type RM Length L Ch R = 1 ,280     ,0,0,0
BEGIN DESCRIPTION:
UNT005 IN NNOGR 1.0
END DESCRIPTION:
XS GIS Cut Line= 4
      2847414.01     10069071.19      2846752.13     10068767.38
      2846535.11     10068897.58      2846187.89     10069602.88
#Sta/Elev= 30
  4338.4 1464.23  4352.5 1463.59  4410.5 1461.72  4444.6 1455.39  4458.9 1454.39
  4513.6  1446.4  4666.6 1440.36  4731.5 1438.24  4869.4 1437.44  4938.4 1434.67
  5004.4 1431.69  5066.7 1434.55  5226.6 1440.63  5279.1 1439.45  5284.9 1440.79
  5300.5 1438.11  5306.3 1439.62  5319.8 1438.35  5322.3 1440.76  5374.6 1442.18
    5482 1443.15  5516.1 1449.05  5546.9 1448.98  5560.7  1446.9  5589.3 1446.19
  5696.7 1446.36  5804.1 1446.31  5845.9 1447.19  6014.7 1450.73  6105.9 1454.88
#Mann= 13 ,-1 , 0
  4338.4     .16       0  4352.5      .1       0  4458.9     .05       0
  4666.6      .1       0  4938.4     .07       0  5066.7      .1       0
  5374.6     .16       0    5482      .1       0  5589.3     .05       0
  5696.7     .16       0  5804.1     .05       0  5845.9     .16       0
  6014.7      .1       0
Bank Sta=4938.4,5066.7
XS Rating Curve= 0 ,0
Exp/Cntr=0.3,0.1

Chan Stop Cuts=-1
Use User Specified Reach Order=0
Composite Channel Slope=5