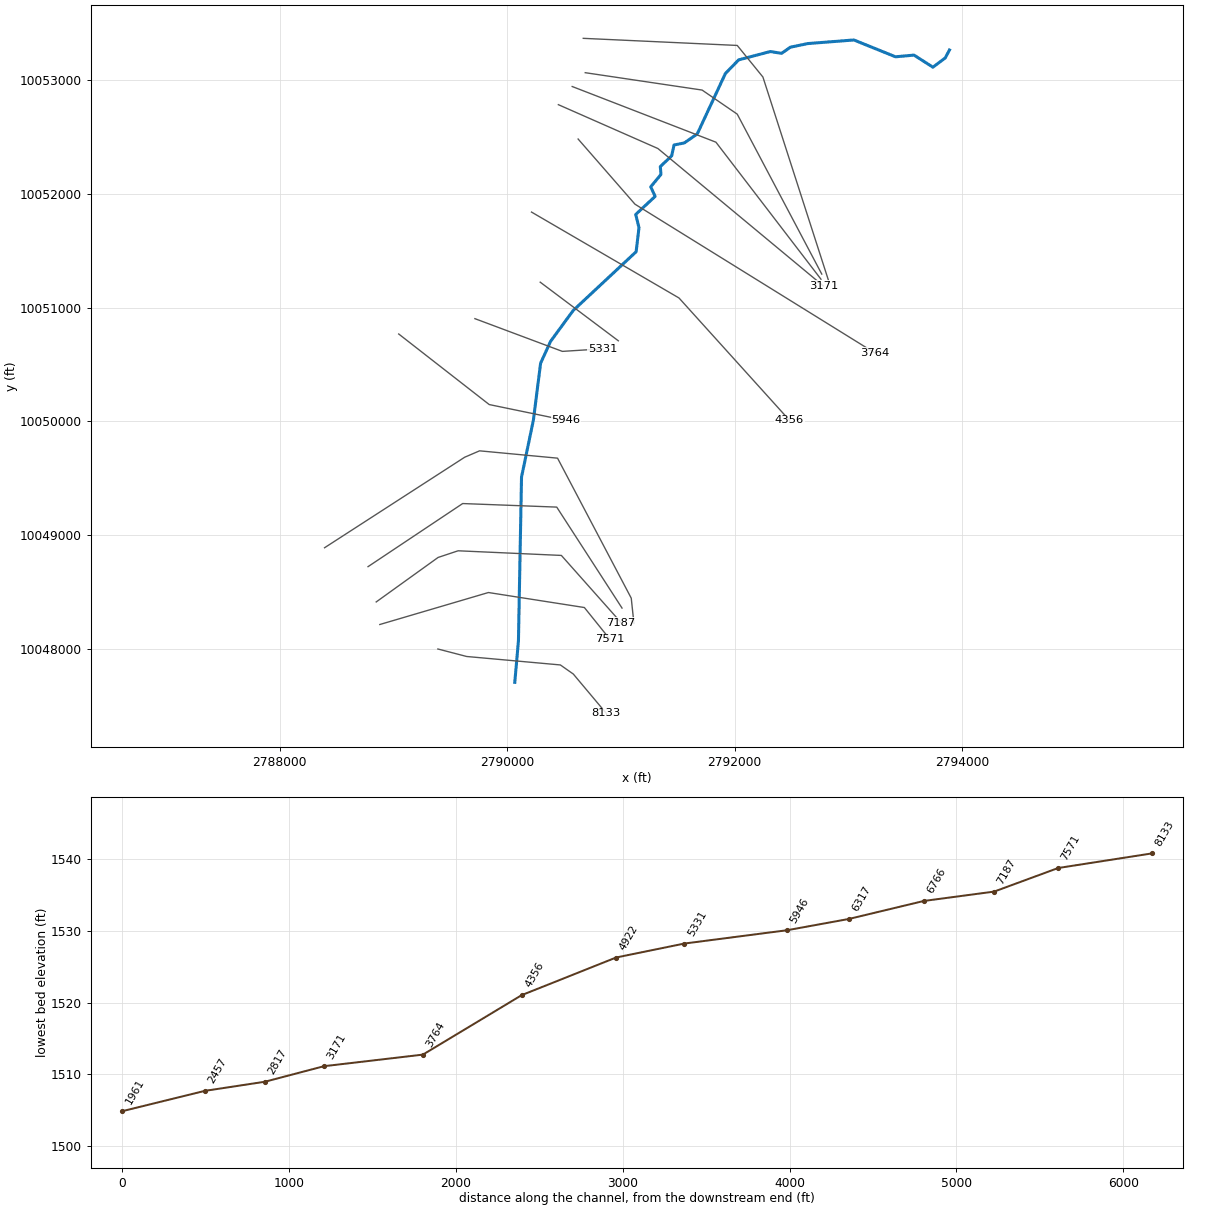
--- UNT005 IN SNOGR.prj (project) ---

Proj Title=UNT005 IN SNOGR Base Level Engineering
Current Plan=p01
Default Exp/Contr=0.3,0.1
English Units
Geom File=g01
Flow File=f01
Plan File=p01
Y Axis Title=Elevation
X Axis Title(PF)=Main Channel Distance
X Axis Title(XS)=Station
BEGIN DESCRIPTION:
UNT005 IN SNOGR
END DESCRIPTION:
DSS Export Rating Curves= 0
DSS Export Rating Curve Sorted= 0
DSS Export Volume Flow Curves= 0
DXF OffsetX= 0
DXF OffsetY= 0
DXF ScaleX= 1
DXF ScaleY= 10

--- UNT005 IN SNOGR.p01 (plan) ---

Plan Title=Multiple Run
Short Identifier=Multiple
Geom File=g01
Flow File=f01
Subcritical Flow
K Sum by GR= 0
Std Step Tol= 0.01
Critical Tol= 0.01
Num of Std Step Trials= 20
Max Error Tol= 0.3
Flow Tol Ratio= 0.001
Split Flow NTrial= 30
Split Flow Tol= 0.02
Split Flow Ratio= 0.02
Log Output Level= 0
Friction Slope Method= 1
Unsteady Friction Slope Method= 2
Unsteady Bridges Friction Slope Method= 1
Parabolic Critical Depth
Global Vel Dist=  1 , 1 , 1
Global Log Level= 0
CheckData=True
Encroach Param= -1, 0, 0, 0
BEGIN DESCRIPTION:
Multiple Run
END DESCRIPTION:

--- UNT005 IN SNOGR.f01 (steady flow) ---

Flow Title=Multiple
Number of Profiles=7
Profile Names=10-year,25-year,50-year,1pct_min,100-year,1pct_plu,500-year
River Rch & RM= UNT005 IN SNOGR,Reach-1,8133
    1164    1720    2211    2078    2811    3801    4564
River Rch & RM= UNT005 IN SNOGR,Reach-1,5331
    1470    2186    2823    2662    3600    4868    5883
Boundary for River Rch & Prof#=UNT005 IN SNOGR,Reach-1,1
Up Type=0
Dn Type=3
Dn Slope=0.005
Boundary for River Rch & Prof#=UNT005 IN SNOGR,Reach-1,2
Up Type=0
Dn Type=3
Dn Slope=0.005
Boundary for River Rch & Prof#=UNT005 IN SNOGR,Reach-1,3
Up Type=0
Dn Type=3
Dn Slope=0.005
Boundary for River Rch & Prof#=UNT005 IN SNOGR,Reach-1,4
Up Type=0
Dn Type=3
Dn Slope=0.005
Boundary for River Rch & Prof#=UNT005 IN SNOGR,Reach-1,5
Up Type=0
Dn Type=3
Dn Slope=0.005
Boundary for River Rch & Prof#=UNT005 IN SNOGR,Reach-1,6
Up Type=0
Dn Type=3
Dn Slope=0.005
Boundary for River Rch & Prof#=UNT005 IN SNOGR,Reach-1,7
Up Type=0
Dn Type=3
Dn Slope=0.005

--- UNT005 IN SNOGR.g01 (geometry) ---

Geom Title=Existing Conditions
Program Version=4.10

River Reach=UNT005 IN SNOGR ,Reach-1
Reach XY= 30
      2790066.63     10047705.09      2790098.73     10048070.82
      2790125.79     10049509.43      2790230.16     10050010.72
      2790293.61     10050510.94      2790380.92     10050702.71
      2790579.67     10050974.06      2791133.53     10051491.08
       2791158.7      10051702.7      2791129.71     10051819.02
      2791300.56     10051977.51      2791261.91     10052062.03
      2791352.02     10052170.98      2791346.37      10052239.9
      2791446.13     10052334.74      2791467.04     10052429.91
      2791556.78     10052447.67      2791671.13     10052527.15
      2791918.61     10053058.68      2792035.28     10053178.39
      2792313.58     10053251.57      2792412.48     10053235.64
      2792490.08     10053289.84      2792643.98     10053321.69
      2793048.32     10053353.27      2793414.31     10053205.41
      2793576.89     10053220.18      2793743.23     10053113.96
       2793851.2     10053194.62      2793888.85     10053265.19

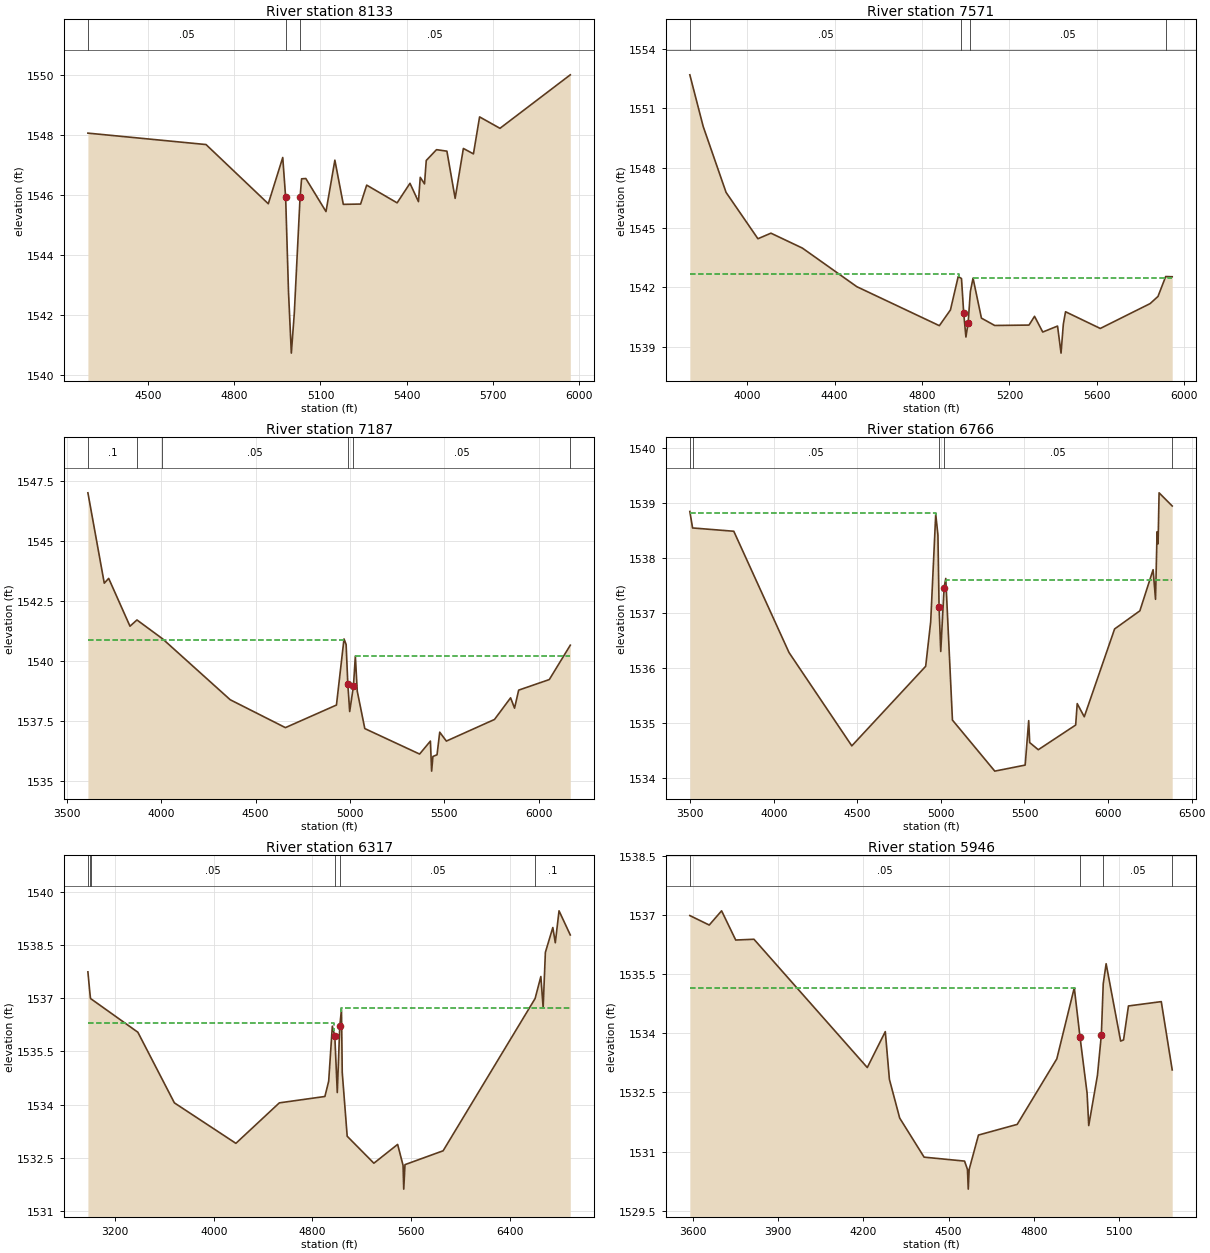
Type RM Length L Ch R = 1 ,8133    ,562,562,562
BEGIN DESCRIPTION:
UNT005 IN SNOGR 15.0
END DESCRIPTION:
XS GIS Cut Line= 5
      2789390.18     10047998.04      2789643.66     10047932.06
      2790467.24     10047857.77      2790581.11     10047777.75
      2790871.43     10047431.87
#Sta/Elev= 30
  4290.2 1548.05  4701.5 1547.67  4918.3  1545.7  4968.6 1547.24  4978.7 1545.91
  4988.7 1542.76  4998.5 1540.73  5008.8 1542.05  5028.9 1545.91  5034.2 1546.53
  5048.9 1546.54  5119.2 1545.44  5150.1 1547.15  5179.5 1545.68  5239.7 1545.69
  5260.9 1546.32  5366.8 1545.73  5411.6 1546.38  5441.2 1545.77  5447.4 1546.58
  5462.2 1546.36  5468.3 1547.14    5504  1547.5  5540.2 1547.45  5568.9 1545.88
  5597.5 1547.54  5632.6 1547.36    5654 1548.59    5725 1548.21  5969.8 1549.99
#Mann= 3 , 0 , 0
  4290.2     .05       0  4978.7    .035       0  5028.9     .05       0
Bank Sta=4978.7,5028.9
XS Rating Curve= 0 ,0
Exp/Cntr=0.3,0.1

Type RM Length L Ch R = 1 ,7571    ,384,384,384
BEGIN DESCRIPTION:
UNT005 IN SNOGR 14.0
END DESCRIPTION:
XS GIS Cut Line= 4
      2788879.78     10048213.32      2789834.63     10048494.56
      2790678.38     10048362.62       2790901.8     10048085.08
#Sta/Elev= 30
  3738.4 1552.69  3799.6 1550.09  3904.1 1546.78  4049.8 1544.45  4109.3 1544.73
  4253.1 1543.98    4502 1542.04  4879.4 1540.08    4930 1540.87  4965.6 1542.55
  4980.6 1542.45  4990.7 1540.71  5000.8 1539.51    5011 1540.22  5021.1 1541.79
  5033.4 1542.47  5071.7 1540.46  5132.4 1540.09  5289.3 1540.11  5314.6 1540.55
  5352.1 1539.76  5419.8 1540.06  5435.8  1538.7  5446.2 1540.15  5456.3 1540.78
  5615.2 1539.94  5843.1 1541.19  5879.1 1541.55  5914.3 1542.55  5944.1 1542.54
#Mann= 4 ,-1 , 0
  3738.4     .05       0  4980.6    .035       0  5021.1     .05       0
  5914.3      .1       0
#XS Ineff= 2 , 0
         4969.84 1542.67 5033.43         1542.47
Permanent Ineff=
       T       T
Bank Sta=4990.7,5011
XS Rating Curve= 0 ,0
Exp/Cntr=0.3,0.1

Type RM Length L Ch R = 1 ,7187    ,421,421,421
BEGIN DESCRIPTION:
UNT005 IN SNOGR 13.0
END DESCRIPTION:
XS GIS Cut Line= 5
      2788848.06     10048411.76      2789392.11     10048802.94
      2789568.28     10048861.56      2790476.14     10048820.73
      2791001.23       10048230.
#Sta/Elev= 30
  3611.8    1547  3698.5 1543.24  3721.8 1543.44  3834.7 1541.45  3871.5 1541.71
  4006.6 1540.93  4365.6 1538.39  4657.9 1537.23  4928.2 1538.17  4968.2 1540.92
  4979.4 1540.69  4988.3 1539.06  4998.3  1537.9  5018.3 1538.96  5028.3 1540.21
  5038.3 1538.75  5078.4 1537.19  5368.6 1536.13  5425.8 1536.67  5432.3 1535.42
  5439.2 1536.03  5460.9  1536.1  5475.2 1537.04  5510.3 1536.67  5765.3 1537.57
  5850.6 1538.47  5871.5 1538.04  5893.3 1538.79  6055.5 1539.23  6166.7 1540.66
#Mann= 6 ,-1 , 0
  3611.8      .1       0  3871.5     .05       0  4006.6     .05       0
  4988.3    .035       0  5018.3     .05       0  6166.7      .1       0
#XS Ineff= 2 , 0
          4967.3 1540.89 5028.34         1540.22
Permanent Ineff=
       T       T
Bank Sta=4988.3,5018.3
XS Rating Curve= 0 ,0
Exp/Cntr=0.3,0.1

Type RM Length L Ch R = 1 ,6766    ,449,449,449
BEGIN DESCRIPTION:
UNT005 IN SNOGR 12.0
END DESCRIPTION:
XS GIS Cut Line= 4
      2788776.08     10048721.99      2789608.25      10049276.9
      2790435.39      10049245.7       2791009.5     10048357.78
#Sta/Elev= 30
  3498.4 1538.85  3514.9 1538.55  3761.3 1538.49  4091.8 1536.28  4467.3 1534.58
  4909.1 1536.03  4939.1 1536.84  4969.2  1538.8  4982.4 1538.42  4989.2 1537.11
  4999.2  1536.3  5019.2 1537.46  5029.2 1537.63  5069.2 1535.05  5322.4 1534.12
  5504.2 1534.23  5525.3 1535.04  5531.2 1534.64  5582.7 1534.51  5806.3 1534.96
  5815.5 1535.35  5857.7 1535.11  6039.1 1536.71  6190.2 1537.04  6269.4 1537.79
  6283.9 1537.25  6293.1 1538.48  6299.1 1538.26  6305.2 1539.19  6383.7 1538.95
#Mann= 5 ,-1 , 0
  3498.4      .1       0  3514.9     .05       0  4989.2     .04       0
  5019.2     .05       0  6383.7      .1       0
#XS Ineff= 2 , 0
         4968.75 1538.83 5032.34         1537.61
Permanent Ineff=
       T       T
Bank Sta=4989.2,5019.2
XS Rating Curve= 0 ,0
Exp/Cntr=0.3,0.1

Type RM Length L Ch R = 1 ,6317    ,371,371,371
BEGIN DESCRIPTION:
Mapping XS 018757e7
END DESCRIPTION:
XS GIS Cut Line= 6
      2788393.89     10048888.35      2789625.92     10049684.23
       2789756.8     10049740.46      2790442.55     10049676.05
      2791090.62     10048444.87      2791114.22     10048222.91
#Sta/Elev= 30
  2979.7 1537.74  2994.8 1537.18  3000.9 1536.99  3384.9 1536.04  3681.2 1534.05
    4180 1532.91  4532.3 1534.05  4901.9 1534.23  4932.6 1534.66  4962.2 1536.21
  4982.3 1535.93  5002.4 1534.34  5022.5 1536.21  5036.3 1536.68  5042.5 1534.91
  5082.7 1533.11  5299.2 1532.35  5491.8 1532.88  5535.9 1532.29  5541.3 1531.62
  5551.5 1532.31  5860.8  1532.7  6606.9 1536.99  6653.5 1537.61  6672.1 1536.73
  6690.2 1538.29  6750.6 1538.99  6770.7 1538.56  6800.9 1539.46  6892.2 1538.78
#Mann= 6 ,-1 , 0
  2979.7     .05       0  2994.8      .1       0  3000.9     .05       0
  4982.3    .035       0  5022.5     .05       0  6606.9      .1       0
#XS Ineff= 2 , 0
         4972.38 1536.31 5034.16         1536.71
Permanent Ineff=
       T       T
Bank Sta=4982.3,5022.5
XS Rating Curve= 0 ,0
Exp/Cntr=0.3,0.1

Type RM Length L Ch R = 1 ,5946    ,615,615,615
BEGIN DESCRIPTION:
Mapping XS c1500de3
END DESCRIPTION:
XS GIS Cut Line= 3
      2789045.87     10050767.87      2789841.75     10050147.36
      2790516.21     10050007.97
#Sta/Elev= 30
  3589.2 1536.98  3657.5 1536.74    3701  1537.1  3750.7 1536.36  3814.9 1536.38
  4213.8 1533.13  4277.2 1534.04  4291.7 1532.83  4327.9 1531.85  4413.8 1530.86
  4556.2 1530.76  4566.4 1530.55  4569.2 1530.05  4572.4 1530.55  4605.2 1531.42
  4741.5 1531.69  4880.9 1533.35  4942.4 1535.15  4962.6  1533.9  4987.5 1532.48
  4993.3 1531.66  5023.9 1532.93  5037.7 1533.96  5044.3 1535.25  5054.5 1535.76
  5105.6  1533.8  5115.8 1533.83  5133.1 1534.69  5248.6  1534.8  5287.1 1533.07
#Mann= 4 ,-1 , 0
  3589.2     .05       0  4962.6    .035       0  5044.3     .05       0
  5287.1     .08       0
#XS Ineff= 2 , 0
          4943.6 1535.15
Permanent Ineff=
       T       T
Bank Sta=4962.6,5037.7
XS Rating Curve= 0 ,0
Exp/Cntr=0.3,0.1

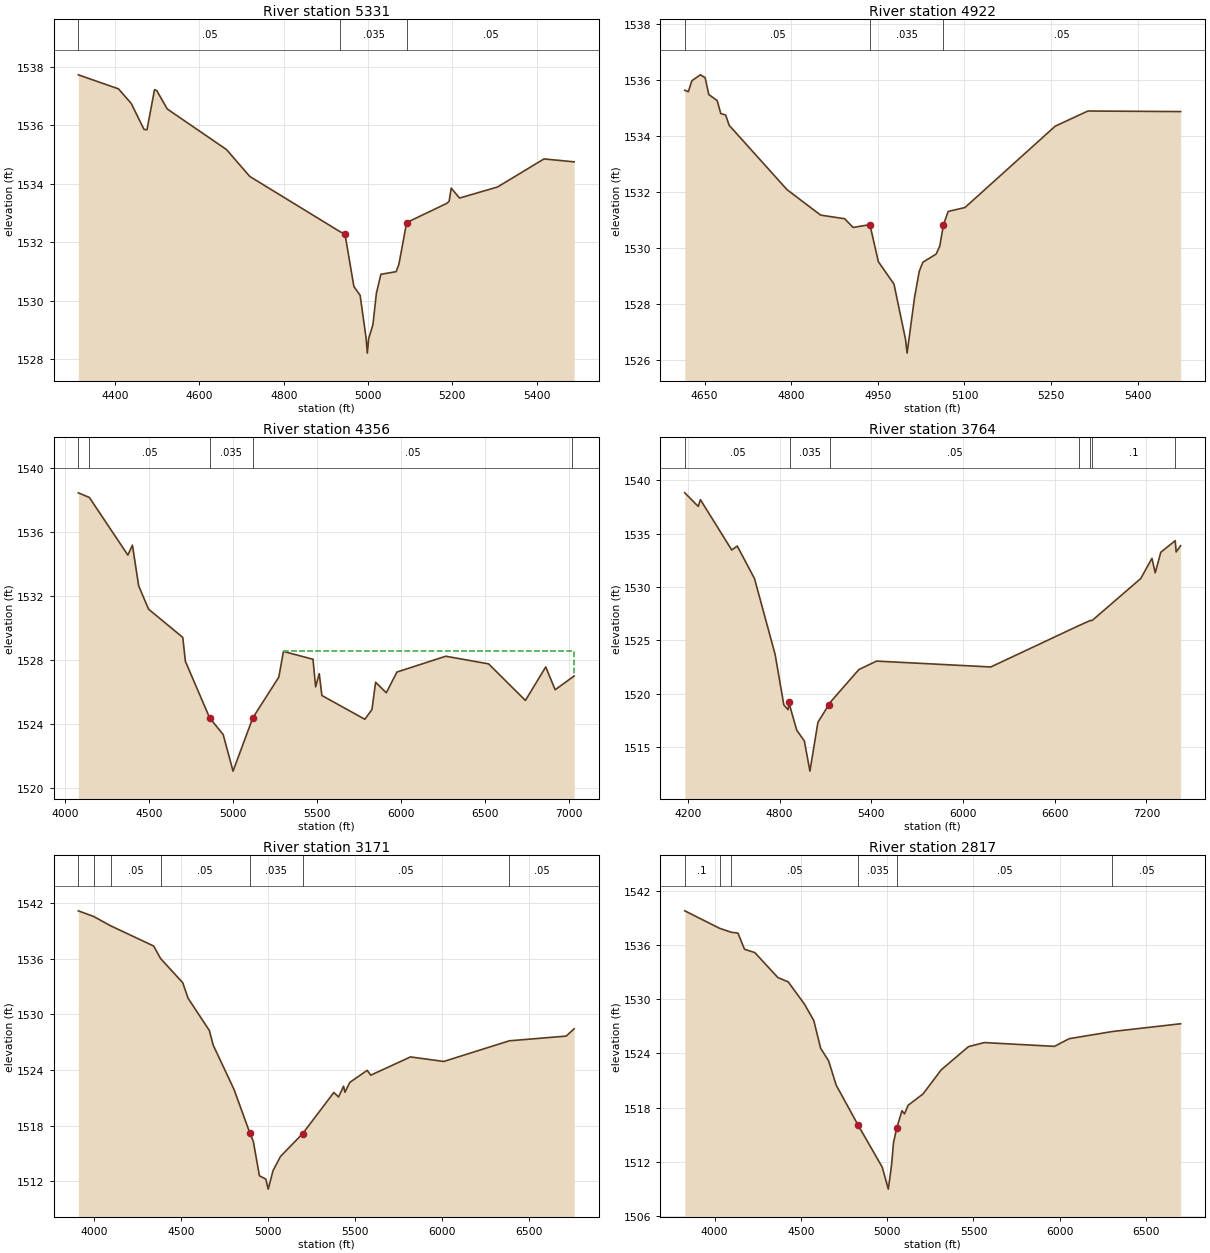
Type RM Length L Ch R = 1 ,5331    ,409,409,409
BEGIN DESCRIPTION:
Mapping XS 159733e5
END DESCRIPTION:
XS GIS Cut Line= 3
      2789715.84     10050902.75      2790484.73     10050614.98
      2790839.94     10050637.46
#Sta/Elev= 30
  4312.4 1537.73  4407.7 1537.25    4438 1536.75  4468.3 1535.86  4475.4 1535.85
  4493.2 1537.22  4498.6 1537.19  4523.5 1536.56  4664.2 1535.17  4719.4 1534.25
  4934.5 1532.35  4945.2 1532.29  4966.5 1530.48  4981.3 1530.18  4995.6  1528.7
  4998.3  1528.2  5001.6  1528.7  5011.6 1529.17  5019.9 1530.25  5030.6  1530.9
  5066.8 1530.99  5073.3 1531.24  5091.7 1532.67  5187.2 1533.33  5192.5  1533.4
  5197.5 1533.85  5217.3 1533.51  5307.5 1533.89  5417.7 1534.85  5489.3 1534.75
#Mann= 3 ,-1 , 0
  4312.4     .05       0  4934.5    .035       0  5091.7     .05       0
Bank Sta=4945.2,5091.7
XS Rating Curve= 0 ,0
Exp/Cntr=0.3,0.1

Type RM Length L Ch R = 1 ,4922    ,566,566,566
BEGIN DESCRIPTION:
UNT005 IN SNOGR 10.0
END DESCRIPTION:
XS GIS Cut Line= 2
      2790290.13     10051223.53      2790976.96     10050708.14
#Sta/Elev= 30
  4615.7 1535.63  4621.8 1535.58    4628 1535.97  4642.6 1536.18  4650.9 1536.08
  4657.2 1535.48  4671.8 1535.26    4678  1534.8  4686.4 1534.75  4692.6 1534.38
  4792.6 1532.09  4850.9 1531.18  4892.6 1531.05  4907.2 1530.74  4936.3 1530.84
  4950.9 1529.52    4978 1528.72  4997.9 1526.76  5000.7 1526.26  5013.7 1528.26
  5021.8 1529.18    5028  1529.5  5050.9 1529.79  5057.2 1530.07  5063.7 1530.84
  5071.8 1531.31  5100.9 1531.45  5257.2 1534.35  5313.8 1534.89  5474.4 1534.87
#Mann= 3 , 0 , 0
  4615.7     .05       0  4936.3    .035       0  5063.7     .05       0
Bank Sta=4936.3,5063.7
XS Rating Curve= 0 ,0
Exp/Cntr=0.3,0.1

Type RM Length L Ch R = 1 ,4356    ,592,592,592
BEGIN DESCRIPTION:
UNT005 IN SNOGR 9.0
END DESCRIPTION:
XS GIS Cut Line= 3
      2790213.68      10051839.9      2791510.49     10051084.55
      2792482.44     10050008.47
#Sta/Elev= 30
  4077.5 1538.47  4143.1 1538.18  4372.2 1534.57  4399.5 1535.19  4436.7 1532.64
  4495.5 1531.18    4699 1529.41  4714.7 1527.91  4859.4 1524.36  4939.7 1523.32
  4998.2 1521.03  5115.9 1524.37  5270.6 1526.92  5298.2 1528.53  5474.1 1528.04
  5489.8 1526.31  5511.3 1527.14    5527 1525.77  5782.4 1524.28    5825 1524.89
  5846.7  1526.6  5910.2 1525.94  5973.7 1527.24  6264.4 1528.23  6519.2 1527.75
  6738.2 1525.46  6859.2 1527.56  6915.3 1526.13  7014.7 1526.89  7028.3 1526.99
#Mann= 5 ,-1 , 0
  4077.5     .05       0  4143.1     .05       0  4859.4    .035       0
  5115.9     .05       0  7014.7     .05       0
#XS Ineff= 2 , 0
                         5299.78         1528.54
Permanent Ineff=
       T       T
Bank Sta=4859.4,5115.9
XS Rating Curve= 0 ,0
Exp/Cntr=0.3,0.1

Type RM Length L Ch R = 1 ,3764    ,593,593,593
BEGIN DESCRIPTION:
UNT005 IN SNOGR 8.0
END DESCRIPTION:
XS GIS Cut Line= 3
      2790623.42     10052482.25      2791123.43     10051909.32
      2793233.99     10050600.64
#Sta/Elev= 30
  4179.7 1538.81  4267.5 1537.54  4281.8 1538.17  4486.8 1533.46  4522.8 1533.83
  4635.8 1530.78  4770.6 1523.69  4827.6 1518.96  4855.1 1518.51  4862.7 1519.19
  4869.4 1518.74  4912.1 1516.59    4962 1515.58  4998.3 1512.76  5050.6 1517.33
  5122.6 1518.99  5129.7 1519.18  5318.7 1522.27  5434.5 1523.06  6181.5 1522.51
  6757.6 1526.38    6833 1526.86  6844.8 1526.86  7162.7 1530.79    7236 1532.68
  7257.2 1531.32  7293.9 1533.25  7388.1 1534.33  7394.3 1533.28  7423.5 1533.86
#Mann= 7 ,-1 , 0
  4179.7     .05       0  4869.4    .035       0  5129.7     .05       0
  6757.6      .1       0    6833     .05       0  6844.8      .1       0
  7388.1     .05       0
Bank Sta=4862.7,5122.6
XS Rating Curve= 0 ,0
Exp/Cntr=0.3,0.1

Type RM Length L Ch R = 1 ,3171    ,354,354,354
BEGIN DESCRIPTION:
UNT005 IN SNOGR 7.0
END DESCRIPTION:
XS GIS Cut Line= 3
      2790449.79     10052784.34      2791324.82      10052398.9
       2792779.7     10051190.56
#Sta/Elev= 30
  3909.5 1541.19  3997.6 1540.58  4094.4 1539.58  4342.4 1537.39    4382 1536.04
    4509 1533.43    4540 1531.75    4662 1528.27  4683.9  1526.7  4804.1 1521.89
  4893.6 1517.26  4914.4 1516.31  4949.5 1512.59    4986 1512.24  5000.1 1511.15
  5027.7 1513.15  5070.6 1514.68  5198.2 1517.15  5376.7 1521.58    5404  1521.1
  5432.6 1522.26  5440.5 1521.61  5468.4 1522.67  5568.1 1523.97  5588.9 1523.45
  5816.8 1525.42  6008.2 1524.93  6384.5 1527.16  6711.3 1527.67  6756.9 1528.46
#Mann= 7 ,-1 , 0
  3909.5     .05       0  3997.6      .1       0  4094.4     .05       0
    4382     .05       0  4893.6    .035       0  5198.2     .05       0
  6384.5     .05       0
Bank Sta=4893.6,5198.2
XS Rating Curve= 0 ,0
Exp/Cntr=0.3,0.1

Type RM Length L Ch R = 1 ,2817    ,360,360,360
BEGIN DESCRIPTION:
UNT005 IN SNOGR 6.0
END DESCRIPTION:
XS GIS Cut Line= 3
      2790571.39     10052944.03      2791835.24     10052454.46
      2792758.86     10051249.59
#Sta/Elev= 30
  3826.9 1539.77  4028.1 1537.84    4096  1537.4  4134.8 1537.31    4173 1535.52
  4232.9 1535.15  4366.4 1532.39  4426.3 1531.91  4520.8 1529.44  4574.4 1527.64
  4614.4 1524.56  4660.2 1523.19  4704.1  1520.5  4831.8 1516.05  4971.2 1511.42
  5006.3 1508.99  5024.9 1511.61  5036.5 1514.14  5055.7 1515.79  5085.6 1517.67
  5099.9 1517.31  5121.4 1518.27  5207.1 1519.51  5313.2 1522.19  5470.9 1524.75
  5562.4  1525.2  5969.5 1524.78  6054.7 1525.63  6304.6 1526.42  6700.4 1527.28
#Mann= 6 ,-1 , 0
  3826.9      .1       0  4028.1     .05       0    4096     .05       0
  4831.8    .035       0  5055.7     .05       0  6304.6     .05       0
Bank Sta=4831.8,5055.7
XS Rating Curve= 0 ,0
Exp/Cntr=0.3,0.1

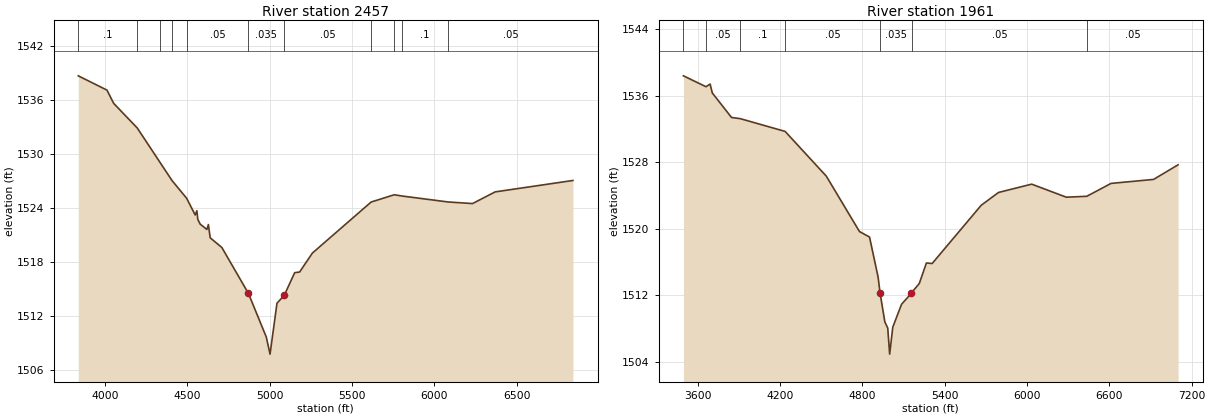
Type RM Length L Ch R = 1 ,2457    ,496,496,496
BEGIN DESCRIPTION:
UNT005 IN SNOGR 5.0
END DESCRIPTION:
XS GIS Cut Line= 4
      2790685.98     10053065.56      2791713.71     10052912.79
      2792022.74     10052700.99      2792765.81      10051294.7
#Sta/Elev= 30
    3838  1538.7  4012.4 1537.11  4052.8 1535.64  4196.4 1532.89  4337.1 1528.99
  4407.5 1527.04  4496.2 1525.07  4548.2 1523.21  4558.3 1523.68    4564 1522.72
  4578.5 1522.19    4619  1521.6  4628.3 1522.14  4639.2 1520.67    4710 1519.59
  4871.7 1514.47  4979.8 1509.63  5002.7 1507.72  5044.9 1513.39  5088.9 1514.26
  5152.5 1516.79  5182.4 1516.86  5259.9 1518.97  5616.6 1524.65  5756.9 1525.46
  5804.8 1525.32  6083.2 1524.66  6232.4 1524.48  6370.1 1525.78  6842.2 1527.05
#Mann= 11 ,-1 , 0
    3838      .1       0  4196.4     .05       0  4337.1      .1       0
  4407.5     .05       0  4496.2     .05       0  4871.7    .035       0
  5088.9     .05       0  5616.6      .1       0  5756.9     .05       0
  5804.8      .1       0  6083.2     .05       0
Bank Sta=4871.7,5088.9
XS Rating Curve= 0 ,0
Exp/Cntr=0.3,0.1

Type RM Length L Ch R = 1 ,1961    ,0,0,0
BEGIN DESCRIPTION:
UNT005 IN SNOGR 4.0
END DESCRIPTION:
XS GIS Cut Line= 4
      2790668.53     10053367.66      2792022.74     10053305.15
      2792248.43     10053027.38      2792828.29      10051228.8
#Sta/Elev= 30
  3497.5 1538.39  3661.7 1537.08  3691.9  1537.4  3707.7 1536.33  3847.8 1533.38
  3912.5 1533.23  4238.2  1531.7  4538.5 1526.31  4779.7 1519.65  4853.2 1518.98
  4915.4 1514.18  4929.7 1512.28  4964.9 1508.75  4985.7 1508.04  4999.8 1504.89
  5022.4 1508.13  5086.3 1510.89  5156.7 1512.19  5164.2 1512.38  5215.6 1513.39
  5267.4 1515.86  5309.5  1515.8  5666.7 1522.81  5792.8 1524.35  6034.4 1525.35
  6286.6 1523.78  6436.1 1523.89  6612.3 1525.44  6922.2 1525.92  7100.8 1527.68
#Mann= 7 ,-1 , 0
  3497.5      .1       0  3661.7     .05       0  3912.5      .1       0
  4238.2     .05       0  4929.7    .035       0  5164.2     .05       0
  6436.1     .05       0
Bank Sta=4929.7,5156.7
XS Rating Curve= 0 ,0
Exp/Cntr=0.3,0.1

Chan Stop Cuts=-1
Use User Specified Reach Order=0
Composite Channel Slope=5

--- UNT005 IN SNOGR.g02 (geometry) ---

Geom Title=Raw Import
Program Version=4.10

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
River Reach=UNT005 IN SNOGR ,Reach-1

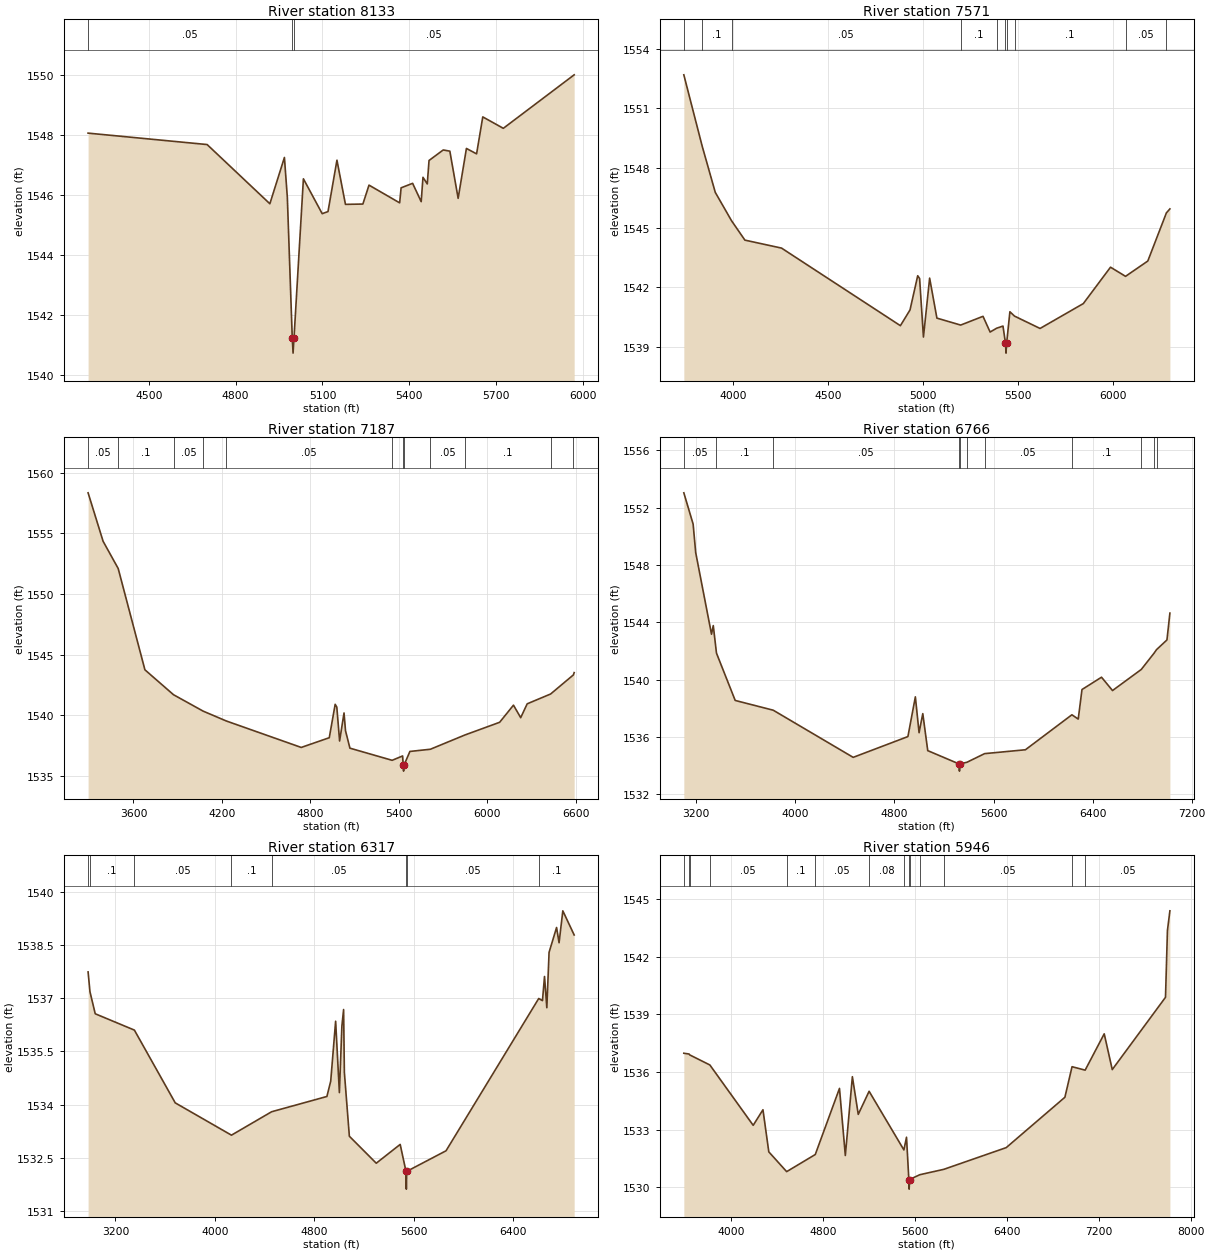
Type RM Length L Ch R = 1 ,8133    ,562,562,562
BEGIN DESCRIPTION:
UNT005 IN SNOGR 15.0
END DESCRIPTION:
XS GIS Cut Line= 5
      2789390.18     10047998.04      2789643.66     10047932.06
      2790467.24     10047857.77      2790581.11     10047777.75
      2790871.43     10047431.87
#Sta/Elev= 30
  4290.2 1548.05  4701.5 1547.67  4918.3  1545.7  4968.6 1547.24  4978.7 1545.91
  4995.7 1541.23  4998.5 1540.73  5001.7 1541.23  5034.2 1546.53  5099.1 1545.37
  5119.2 1545.44  5150.1 1547.15  5179.5 1545.68  5239.7 1545.69  5260.9 1546.32
  5366.8 1545.73  5371.8 1546.23  5411.6 1546.38  5441.2 1545.77  5447.4 1546.58
  5462.2 1546.36  5468.3 1547.14  5517.4 1547.49  5540.2 1547.45  5568.9 1545.88
  5597.5 1547.54  5632.6 1547.36    5654 1548.59    5725 1548.21  5969.8 1549.99
#Mann= 3 ,-1 , 0
  4290.2     .05       0  4995.7     .04       0  5001.7     .05       0
Bank Sta=4995.7,5001.7
XS Rating Curve= 0 ,0
Exp/Cntr=0.3,0.1

Type RM Length L Ch R = 1 ,7571    ,384,384,384
BEGIN DESCRIPTION:
UNT005 IN SNOGR 14.0
END DESCRIPTION:
XS GIS Cut Line= 5
      2788879.78     10048213.32      2789834.63     10048494.56
      2790678.38     10048362.62      2790901.81     10048085.06
      2790989.91     10047740.99
#Sta/Elev= 30
  3738.4 1552.69  3835.2  1549.1  3904.1 1546.78  3990.1 1545.35  4060.2 1544.38
  4253.1 1543.98  4879.4 1540.08    4930 1540.87  4970.6 1542.59  4980.6 1542.45
  5000.8 1539.51  5033.4 1542.47  5071.7 1540.46    5197 1540.11  5314.6 1540.55
  5352.1 1539.76    5386 1539.95  5419.8 1540.06  5433.1  1539.2  5435.8  1538.7
  5439.1  1539.2  5456.3 1540.78  5480.7 1540.56  5615.2 1539.94  5843.1 1541.19
  5986.4 1543.02  6065.5 1542.56  6182.9 1543.33  6280.8 1545.75  6299.3 1545.95
#Mann= 10 ,-1 , 0
  3738.4     .05       0  3835.2      .1       0  3990.1     .05       0
    5197      .1       0    5386     .05       0  5433.1     .04       0
  5439.1     .05       0  5480.7      .1       0  6065.5     .05       0
  6280.8     .08       0
Bank Sta=5433.1,5439.1
XS Rating Curve= 0 ,0
Exp/Cntr=0.3,0.1

Type RM Length L Ch R = 1 ,7187    ,421,421,421
BEGIN DESCRIPTION:
UNT005 IN SNOGR 13.0
END DESCRIPTION:
XS GIS Cut Line= 6
      2788613.96     10048194.03      2789392.11     10048802.94
      2789568.28     10048861.56      2790476.14     10048820.73
      2791001.21     10048230.03      2791091.19     10047816.87
#Sta/Elev= 30
  3292.1 1558.33  3393.9 1554.34  3496.3  1552.1  3677.6 1543.76  3871.5 1541.71
  4072.4 1540.36  4229.2 1539.55    4738 1537.37  4928.2 1538.17  4968.2 1540.92
  4979.4 1540.69  4998.3  1537.9  5028.3 1540.21  5038.3 1538.75  5068.3 1537.31
  5354.8 1536.31  5425.8 1536.67  5429.5 1535.92  5432.3 1535.42  5435.5 1535.92
  5475.2 1537.04  5613.8 1537.22  5847.3 1538.39  6083.9 1539.44  6177.8 1540.85
  6226.8 1539.82  6270.8 1540.96  6429.8 1541.77  6584.1 1543.34  6589.5 1543.53
#Mann= 12 ,-1 , 0
  3292.1     .05       0  3496.3      .1       0  3871.5     .05       0
  4072.4      .1       0  4229.2     .05       0  5354.8      .1       0
  5429.5    .035       0  5435.5      .1       0  5613.8     .05       0
  5847.3      .1       0  6429.8     .05       0  6584.1     .08       0
Bank Sta=5429.5,5435.5
XS Rating Curve= 0 ,0
Exp/Cntr=0.3,0.1

Type RM Length L Ch R = 1 ,6766    ,449,449,449
BEGIN DESCRIPTION:
UNT005 IN SNOGR 12.0
END DESCRIPTION:
XS GIS Cut Line= 6
      2788521.51     10048415.92       2788776.1       10048722.
      2789608.25      10049276.9      2790435.39      10049245.7
      2791010.16     10048356.76      2791202.54     10047750.27
#Sta/Elev= 30
  3100.3 1553.03  3175.3 1550.85  3196.1 1548.86  3323.7 1543.17    3338 1543.77
  3363.8 1541.85  3514.9 1538.55  3821.7 1537.87  4467.3 1534.58  4909.1 1536.03
  4969.2  1538.8  4999.2  1536.3  5029.2 1537.63  5069.2 1535.05  5322.4 1534.12
  5325.1 1533.62  5328.4 1534.12  5386.1 1534.24  5528.3 1534.84  5857.7 1535.11
  6232.8 1537.55  6283.9 1537.25  6314.2 1539.31  6471.8 1540.17  6560.7 1539.24
  6792.7 1540.71  6896.4 1541.85  6915.7 1542.09    7000 1542.77  7023.9 1544.64
#Mann= 11 ,-1 , 0
  3100.3     .05       0  3363.8      .1       0  3821.7     .05       0
  5322.4     .04       0  5328.4     .05       0  5386.1      .1       0
  5528.3     .05       0  6232.8      .1       0  6792.7     .05       0
  6896.4     .08       0  6915.7     .05       0
Bank Sta=5322.4,5328.4
XS Rating Curve= 0 ,0
Exp/Cntr=0.3,0.1

Type RM Length L Ch R = 1 ,6317    ,371,371,371
BEGIN DESCRIPTION:
Mapping XS 018757e7
END DESCRIPTION:
XS GIS Cut Line= 6
      2788393.89     10048888.35      2789625.92     10049684.23
       2789756.8     10049740.46      2790442.55     10049676.05
      2791090.62     10048444.87      2791114.22     10048222.91
#Sta/Elev= 30
  2979.7 1537.74  2994.8 1537.18  3037.2 1536.56  3352.4  1536.1  3681.2 1534.05
  4133.7 1533.14  4457.1  1533.8  4901.9 1534.23  4932.6 1534.66  4972.2 1536.35
  5002.4 1534.34  5022.5 1536.21  5036.3 1536.68  5042.5 1534.91  5082.7 1533.11
  5299.2 1532.35  5491.8 1532.88  5538.5 1532.12  5541.3 1531.62  5544.5 1532.12
  5860.8  1532.7  6606.9 1536.99  6637.1 1536.93  6653.5 1537.61  6672.1 1536.73
  6690.2 1538.29  6750.6 1538.99  6770.7 1538.56  6800.9 1539.46  6892.2 1538.78
#Mann= 8 ,-1 , 0
  2979.7     .05       0  2994.8      .1       0  3352.4     .05       0
  4133.7      .1       0  4457.1     .05       0  5538.5     .04       0
  5544.5     .05       0  6606.9      .1       0
Bank Sta=5538.5,5544.5
XS Rating Curve= 0 ,0
Exp/Cntr=0.3,0.1

Type RM Length L Ch R = 1 ,5946    ,615,615,615
BEGIN DESCRIPTION:
Mapping XS c1500de3
END DESCRIPTION:
XS GIS Cut Line= 5
      2789045.87     10050767.87      2789841.75     10050147.36
       2790516.2     10050007.97      2791137.83     10048970.59
      2791535.36      10047713.3
#Sta/Elev= 30
  3589.2 1536.98  3634.2 1536.94  3641.5 1536.89  3815.5 1536.37  4192.2 1533.23
  4277.2 1534.04  4327.9 1531.85  4483.1 1530.82  4731.9 1531.71  4942.4 1535.15
  4993.3 1531.66  5054.5 1535.76  5105.6  1533.8    5200    1535  5502.4 1531.95
  5525.2 1532.61  5545.4 1530.41  5548.2 1529.91  5551.4 1530.41  5640.8 1530.66
  5849.6 1530.94  6392.2 1532.07  6902.2 1534.69  6964.3 1536.28  7078.2  1536.1
    7244 1537.99  7313.9 1536.13  7776.8 1539.89  7793.7 1543.37  7815.1 1544.39
#Mann= 14 ,-1 , 0
  3589.2      .1       0  3634.2     .05       0  3641.5      .1       0
  3815.5     .05       0  4483.1      .1       0  4731.9     .05       0
    5200     .08       0  5502.4     .05       0  5545.4    .035       0
  5551.4     .05       0  5640.8      .1       0  5849.6     .05       0
  6964.3      .1       0  7078.2     .05       0
Bank Sta=5545.4,5551.4
XS Rating Curve= 0 ,0
Exp/Cntr=0.3,0.1

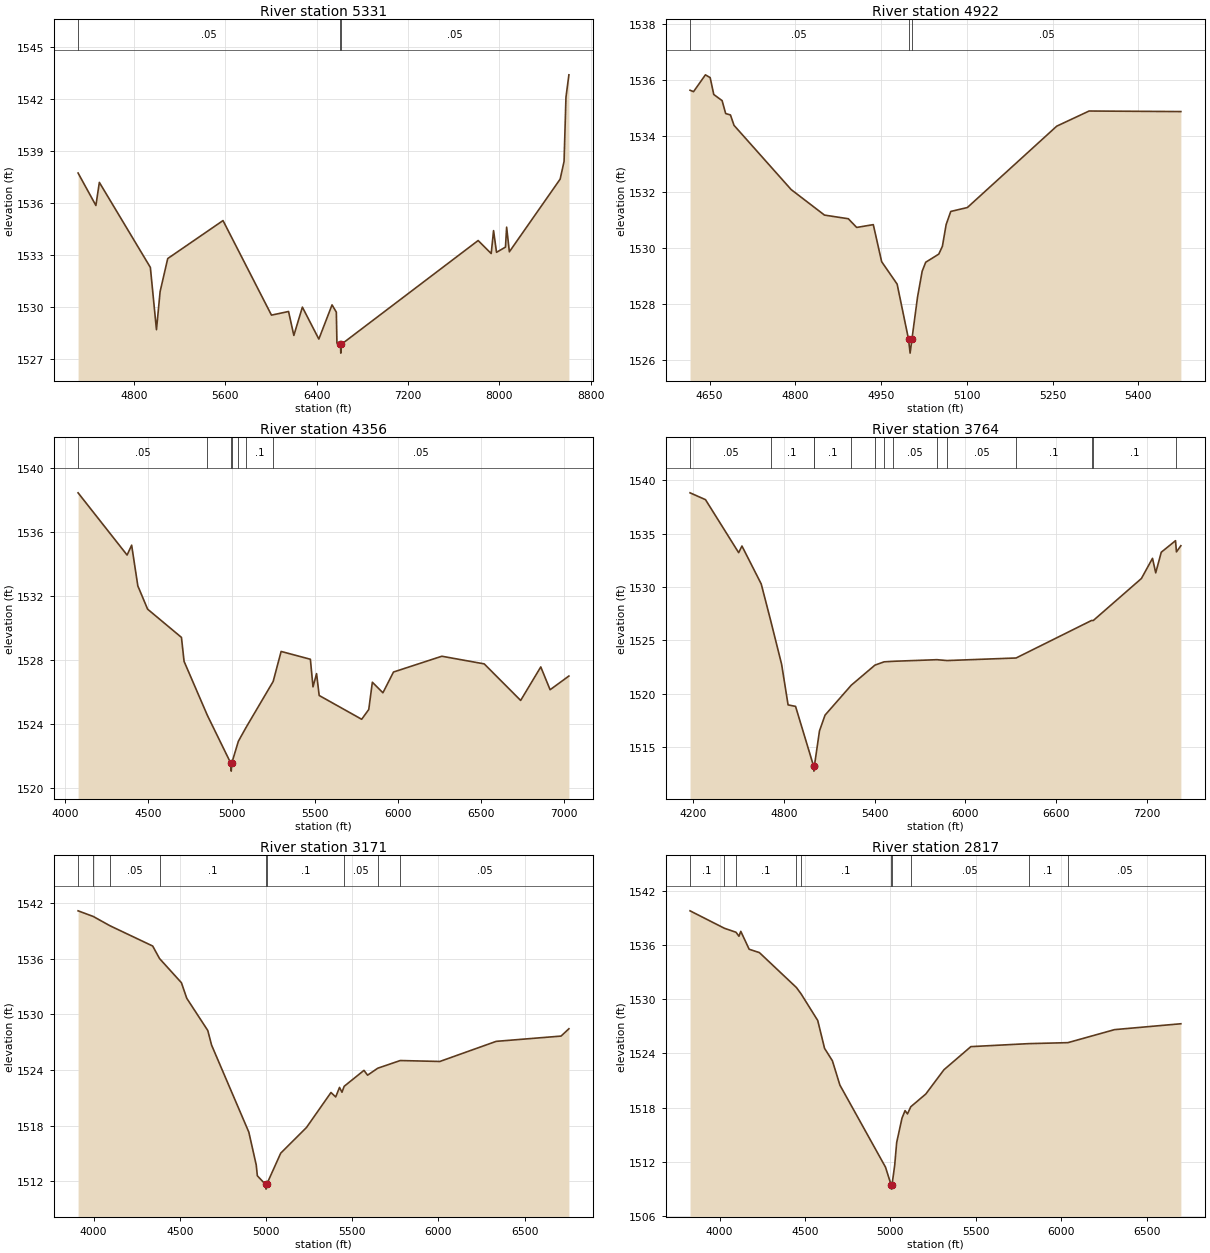
Type RM Length L Ch R = 1 ,5331    ,409,409,409
BEGIN DESCRIPTION:
Mapping XS 159733e5
END DESCRIPTION:
XS GIS Cut Line= 5
      2789715.84     10050902.75      2790484.73     10050614.98
      2790839.94     10050637.46      2791276.51     10049673.21
      2791835.27     10047688.96
#Sta/Elev= 30
  4312.4 1537.73  4468.3 1535.86  4498.6 1537.19  4945.2 1532.29  4998.6  1528.7
  5030.6  1530.9  5097.1  1532.8  5581.2 1534.99  6005.4 1529.54    6155 1529.75
  6201.2 1528.37    6276    1530  6420.1 1528.16  6535.6 1530.13  6573.3 1529.71
  6578.5 1527.93  6609.6 1527.85  6612.3 1527.35  6615.6 1527.85  7814.7 1533.84
    7929 1533.09  7949.7 1534.41  7975.5 1533.16    8054 1533.46    8064 1534.61
    8088 1533.19  8532.7 1537.38  8566.8  1538.4  8583.5  1542.1  8609.2 1543.39
#Mann= 3 ,-1 , 0
  4312.4     .05       0  6609.6    .035       0  6615.6     .05       0
Bank Sta=6609.6,6615.6
XS Rating Curve= 0 ,0
Exp/Cntr=0.3,0.1

Type RM Length L Ch R = 1 ,4922    ,566,566,566
BEGIN DESCRIPTION:
UNT005 IN SNOGR 10.0
END DESCRIPTION:
XS GIS Cut Line= 2
      2790290.13     10051223.53      2790976.96     10050708.14
#Sta/Elev= 30
  4615.7 1535.63  4621.8 1535.58  4642.6 1536.18  4650.9 1536.08  4657.2 1535.48
  4671.8 1535.26    4678  1534.8  4686.4 1534.75  4692.6 1534.38  4792.6 1532.09
  4850.9 1531.18  4892.6 1531.05  4907.2 1530.74  4936.3 1530.84  4950.9 1529.52
    4978 1528.72  4997.9 1526.76  5000.7 1526.26  5003.9 1526.76  5013.7 1528.26
  5021.8 1529.18    5028  1529.5  5050.9 1529.79  5057.2 1530.07  5063.7 1530.84
  5071.8 1531.31  5100.9 1531.45  5257.2 1534.35  5313.8 1534.89  5474.4 1534.87
#Mann= 3 ,-1 , 0
  4615.7     .05       0  4997.9    .035       0  5003.9     .05       0
Bank Sta=4997.9,5003.9
XS Rating Curve= 0 ,0
Exp/Cntr=0.3,0.1

Type RM Length L Ch R = 1 ,4356    ,592,592,592
BEGIN DESCRIPTION:
UNT005 IN SNOGR 9.0
END DESCRIPTION:
XS GIS Cut Line= 3
      2790213.68      10051839.9      2791510.49     10051084.55
      2792482.44     10050008.47
#Sta/Elev= 30
  4077.5 1538.47  4372.2 1534.57  4399.5 1535.19  4436.7 1532.64  4495.5 1531.18
    4699 1529.41  4714.7 1527.91  4854.6 1524.53  4995.4 1521.53  4998.2 1521.03
  5001.4 1521.53  5041.1  1522.9  5086.4 1523.75  5250.4 1526.65  5298.2 1528.53
  5474.1 1528.04  5489.8 1526.31  5511.3 1527.14    5527 1525.77  5782.4 1524.28
    5825 1524.89  5846.7  1526.6  5910.2 1525.94  5973.7 1527.24  6264.4 1528.23
  6519.2 1527.75  6738.2 1525.46  6859.2 1527.56  6915.3 1526.13  7028.3 1526.99
#Mann= 7 ,-1 , 0
  4077.5     .05       0  4854.6      .1       0  4995.4     .07       0
  5001.4      .1       0  5041.1     .05       0  5086.4      .1       0
  5250.4     .05       0
Bank Sta=4995.4,5001.4
XS Rating Curve= 0 ,0
Exp/Cntr=0.3,0.1

Type RM Length L Ch R = 1 ,3764    ,593,593,593
BEGIN DESCRIPTION:
UNT005 IN SNOGR 8.0
END DESCRIPTION:
XS GIS Cut Line= 3
      2790623.42     10052482.25      2791123.43     10051909.32
      2793233.99     10050600.64
#Sta/Elev= 30
  4179.7 1538.81  4281.8 1538.17    4501 1533.21  4522.8 1533.83  4650.1 1530.28
  4712.1 1526.88  4784.9 1522.76  4827.6 1518.96    4877 1518.82  4995.6 1513.26
  4998.3 1512.76  5001.6 1513.26  5035.2 1516.53  5071.8    1518    5245  1520.8
  5401.4 1522.68    5462 1522.99  5520.7 1523.04    5811 1523.19  5878.6 1523.11
  6334.5 1523.35    6833 1526.86  6844.8 1526.86  7162.7 1530.79    7236 1532.68
  7257.2 1531.32  7293.9 1533.25  7388.1 1534.33  7394.3 1533.28  7423.5 1533.86
#Mann= 14 ,-1 , 0
  4179.7     .05       0  4712.1      .1       0  4995.6     .07       0
  5001.6      .1       0    5245     .16       0  5401.4     .05       0
    5462      .1       0  5520.7     .05       0    5811     .16       0
  5878.6     .05       0  6334.5      .1       0    6833     .05       0
  6844.8      .1       0  7388.1     .05       0
Bank Sta=4995.6,5001.6
XS Rating Curve= 0 ,0
Exp/Cntr=0.3,0.1

Type RM Length L Ch R = 1 ,3171    ,354,354,354
BEGIN DESCRIPTION:
UNT005 IN SNOGR 7.0
END DESCRIPTION:
XS GIS Cut Line= 3
      2790449.79     10052784.34      2791324.82      10052398.9
       2792779.7     10051190.56
#Sta/Elev= 30
  3909.5 1541.19  3997.6 1540.58  4094.4 1539.58  4342.4 1537.39    4382 1536.04
    4509 1533.43    4540 1531.75    4662 1528.27  4683.9  1526.7  4900.1  1517.3
    4943 1513.76  4949.5 1512.59  4997.3 1511.65  5000.1 1511.15  5003.3 1511.65
    5085 1515.03  5234.4  1517.8  5376.7 1521.58    5404  1521.1  5426.1 1522.13
  5440.5 1521.61  5453.2 1522.25  5568.1 1523.97  5588.9 1523.45  5647.9  1524.2
  5778.4 1525.03  6008.2 1524.93    6335  1527.1  6711.3 1527.67  6756.9 1528.46
#Mann= 9 ,-1 , 0
  3909.5     .05       0  3997.6      .1       0  4094.4     .05       0
    4382      .1       0  4997.3     .07       0  5003.3      .1       0
  5453.2     .05       0  5647.9      .1       0  5778.4     .05       0
Bank Sta=4997.3,5003.3
XS Rating Curve= 0 ,0
Exp/Cntr=0.3,0.1

Type RM Length L Ch R = 1 ,2817    ,360,360,360
BEGIN DESCRIPTION:
UNT005 IN SNOGR 6.0
END DESCRIPTION:
XS GIS Cut Line= 3
      2790571.39     10052944.03      2791835.24     10052454.46
      2792758.86     10051249.59
#Sta/Elev= 30
  3826.9 1539.77  4028.1 1537.84    4096  1537.4  4113.2 1536.96    4124  1537.5
    4173 1535.52  4232.9 1535.15  4449.5 1531.29  4476.8 1530.59  4574.4 1527.64
  4614.4 1524.56  4660.2 1523.19  4704.1  1520.5  4971.2 1511.42  5003.5 1509.49
  5006.3 1508.99  5009.5 1509.49  5024.9 1511.61  5036.5 1514.14  5067.7 1516.84
  5085.6 1517.67  5099.9 1517.31  5119.1  1518.1  5207.1 1519.51  5313.2 1522.19
  5470.9 1524.75  5808.5 1525.08    6039 1525.19  6312.2 1526.63  6700.4 1527.28
#Mann= 10 ,-1 , 0
  3826.9      .1       0  4028.1     .05       0    4096      .1       0
  4449.5     .05       0  4476.8      .1       0  5003.5     .07       0
  5009.5      .1       0  5119.1     .05       0  5808.5      .1       0
    6039     .05       0
Bank Sta=5003.5,5009.5
XS Rating Curve= 0 ,0
Exp/Cntr=0.3,0.1

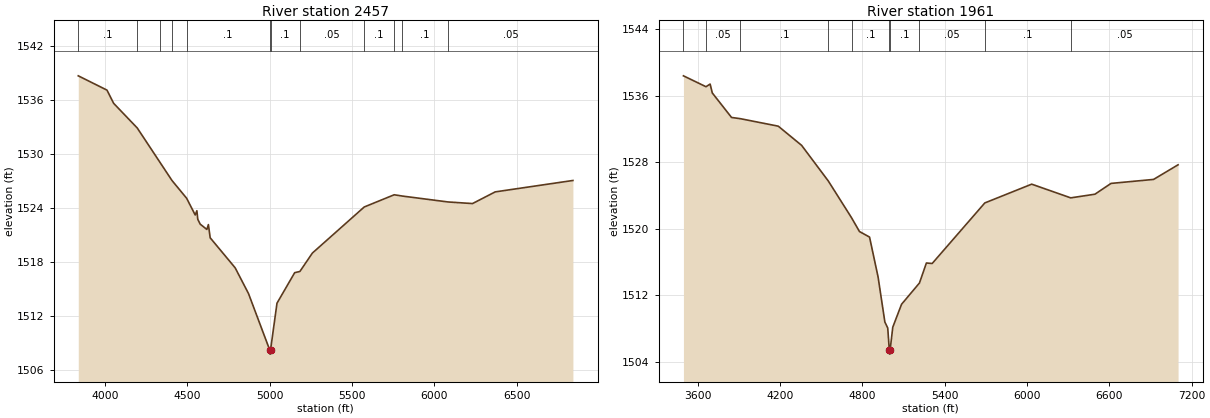
Type RM Length L Ch R = 1 ,2457    ,496,496,496
BEGIN DESCRIPTION:
UNT005 IN SNOGR 5.0
END DESCRIPTION:
XS GIS Cut Line= 4
      2790685.98     10053065.56      2791713.71     10052912.79
      2792022.74     10052700.99      2792765.81      10051294.7
#Sta/Elev= 30
    3838  1538.7  4012.4 1537.11  4052.8 1535.64  4196.4 1532.89  4337.1 1528.99
  4407.5 1527.04  4496.2 1525.07  4548.2 1523.21  4558.3 1523.68    4564 1522.72
  4578.5 1522.19    4619  1521.6  4628.3 1522.14  4639.2 1520.67  4790.8 1517.33
  4871.7 1514.47    5000 1508.22  5002.7 1507.72    5006 1508.22  5044.9 1513.39
  5152.5 1516.79  5183.9 1516.92  5259.9 1518.97  5574.8  1524.1  5756.9 1525.46
  5804.8 1525.32  6083.2 1524.66  6232.4 1524.48  6370.1 1525.78  6842.2 1527.05
#Mann= 12 ,-1 , 0
    3838      .1       0  4196.4     .05       0  4337.1      .1       0
  4407.5     .05       0  4496.2      .1       0    5000     .07       0
    5006      .1       0  5183.9     .05       0  5574.8      .1       0
  5756.9     .05       0  5804.8      .1       0  6083.2     .05       0
Bank Sta=5000,5006
XS Rating Curve= 0 ,0
Exp/Cntr=0.3,0.1

Type RM Length L Ch R = 1 ,1961    ,0,0,0
BEGIN DESCRIPTION:
UNT005 IN SNOGR 4.0
END DESCRIPTION:
XS GIS Cut Line= 4
      2790668.53     10053367.66      2792022.74     10053305.15
      2792248.43     10053027.38      2792828.29      10051228.8
#Sta/Elev= 30
  3497.5 1538.39  3661.7 1537.08  3691.9  1537.4  3707.7 1536.33  3847.8 1533.38
  3912.5 1533.23  4188.2 1532.33  4358.4 1530.02  4552.8 1525.73    4722 1521.31
  4779.7 1519.65  4853.2 1518.98  4915.4 1514.18  4964.9 1508.75  4985.7 1508.04
  4997.1 1505.39  4999.8 1504.89  5003.1 1505.39  5022.4 1508.13  5086.3 1510.89
  5216.7 1513.45  5267.4 1515.86  5309.5  1515.8  5692.9 1523.09  6034.4 1525.35
  6318.8  1523.7    6495 1524.14  6612.3 1525.44  6922.2 1525.92  7100.8 1527.68
#Mann= 10 ,-1 , 0
  3497.5      .1       0  3661.7     .05       0  3912.5      .1       0
  4552.8     .05       0    4722      .1       0  4997.1     .07       0
  5003.1      .1       0  5216.7     .05       0  5692.9      .1       0
  6318.8     .05       0
Bank Sta=4997.1,5003.1
XS Rating Curve= 0 ,0
Exp/Cntr=0.3,0.1