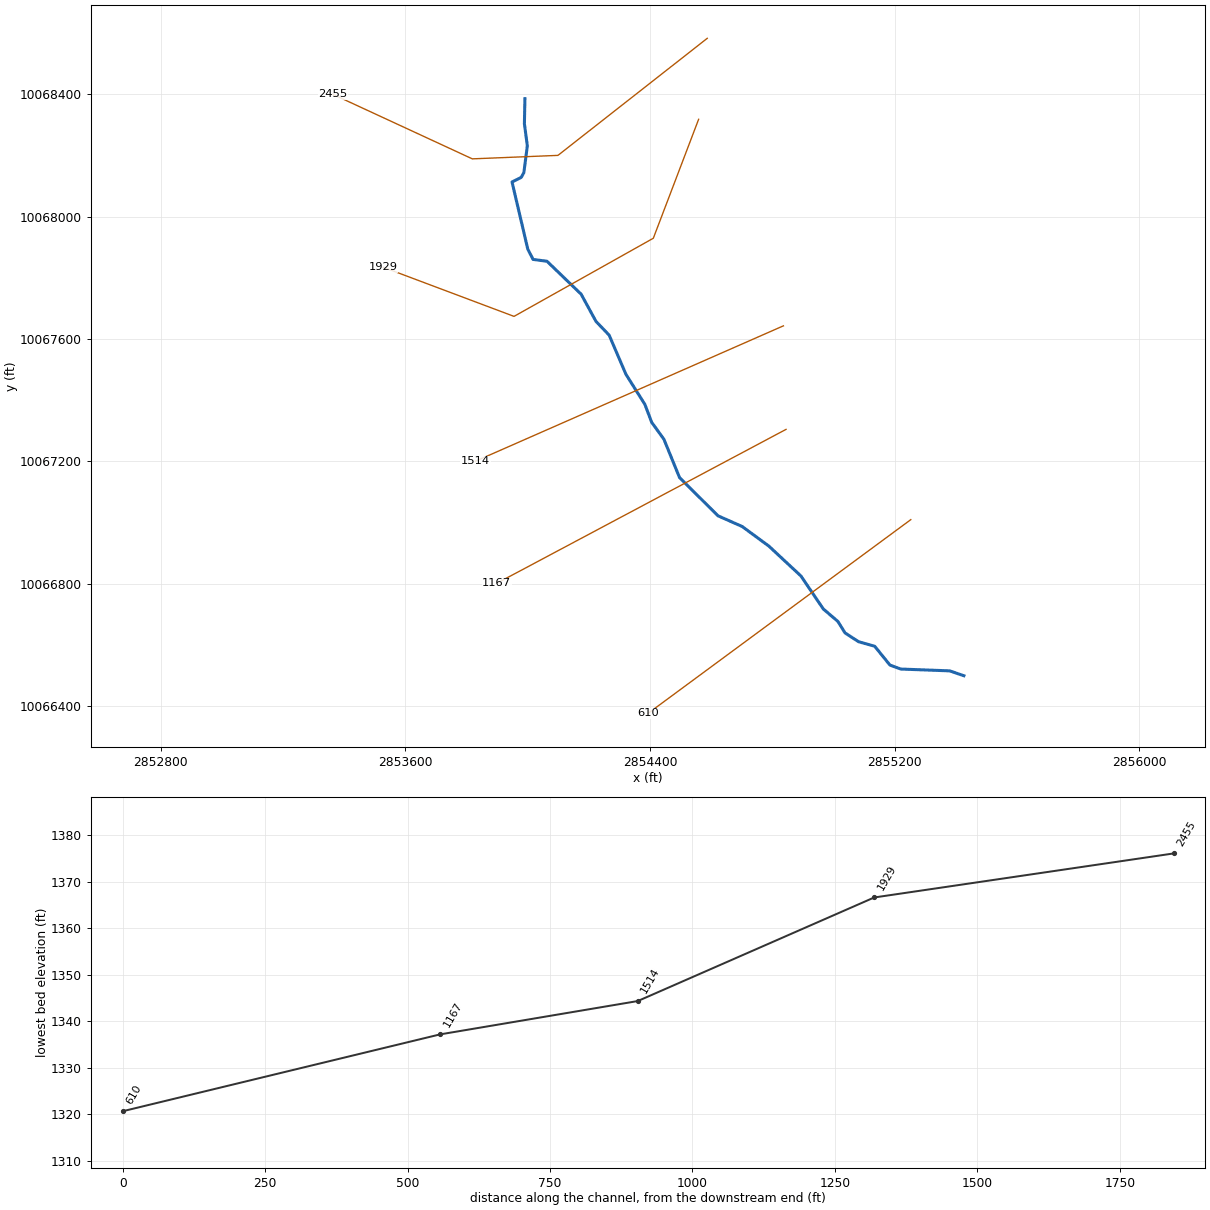
--- UNT006 IN NNOGR.prj (project) ---

Proj Title=UNT006 IN NNOGR Base Level Engineering
Current Plan=p01
Default Exp/Contr=0.3,0.1
English Units
Geom File=g01
Flow File=f01
Plan File=p01
Y Axis Title=Elevation
X Axis Title(PF)=Main Channel Distance
X Axis Title(XS)=Station
BEGIN DESCRIPTION:
UNT006 IN NNOGR
END DESCRIPTION:
DSS Export Rating Curves= 0
DSS Export Rating Curve Sorted= 0
DSS Export Volume Flow Curves= 0
DXF OffsetX= 0
DXF OffsetY= 0
DXF ScaleX= 1
DXF ScaleY= 10

--- UNT006 IN NNOGR.p01 (plan) ---

Plan Title=Multiple Run
Short Identifier=Multiple
Geom File=g01
Flow File=f01
Subcritical Flow
K Sum by GR= 0
Std Step Tol= 0.01
Critical Tol= 0.01
Num of Std Step Trials= 20
Max Error Tol= 0.3
Flow Tol Ratio= 0.001
Split Flow NTrial= 30
Split Flow Tol= 0.02
Split Flow Ratio= 0.02
Log Output Level= 0
Friction Slope Method= 1
Unsteady Friction Slope Method= 2
Unsteady Bridges Friction Slope Method= 1
Parabolic Critical Depth
Global Vel Dist=  1 , 1 , 1
Global Log Level= 0
CheckData=True
Encroach Param= -1, 0, 0, 0
BEGIN DESCRIPTION:
Multiple Run
END DESCRIPTION:

--- UNT006 IN NNOGR.f01 (steady flow) ---

Flow Title=Multiple
Program Version=4.10
Number of Profiles= 7
Profile Names=10-year,25-year,50-year,1pct_min,100-year,1pct_plu,500-year
River Rch & RM=UNT006 IN NNOGR,Reach-1         ,2455
     887    1290    1641    1529    2067    2796    3294
Boundary for River Rch & Prof#=UNT006 IN NNOGR,Reach-1         , 1
Up Type= 0
Dn Type= 3
Dn Slope=0.03
Boundary for River Rch & Prof#=UNT006 IN NNOGR,Reach-1         , 2
Up Type= 0
Dn Type= 3
Dn Slope=0.03
Boundary for River Rch & Prof#=UNT006 IN NNOGR,Reach-1         , 3
Up Type= 0
Dn Type= 3
Dn Slope=0.03
Boundary for River Rch & Prof#=UNT006 IN NNOGR,Reach-1         , 4
Up Type= 0
Dn Type= 3
Dn Slope=0.03
Boundary for River Rch & Prof#=UNT006 IN NNOGR,Reach-1         , 5
Up Type= 0
Dn Type= 3
Dn Slope=0.03
Boundary for River Rch & Prof#=UNT006 IN NNOGR,Reach-1         , 6
Up Type= 0
Dn Type= 3
Dn Slope=0.03
Boundary for River Rch & Prof#=UNT006 IN NNOGR,Reach-1         , 7
Up Type= 0
Dn Type= 3
Dn Slope=0.03
DSS Import GetInterval= 0
DSS Import GetPeak= 0
DSS Import FillOption= 0

--- UNT006 IN NNOGR.g01 (geometry) ---

Geom Title=Existing Conditions
Program Version=4.10

River Reach=UNT006 IN NNOGR ,Reach-1
Reach XY= 30
      2853990.64     10068386.28      2853988.97       10068304.
      2853998.55     10068231.79      2853987.21     10068144.31
      2853978.57     10068128.55      2853948.47     10068113.73
      2854000.11      10067893.8       2854017.4     10067860.44
       2854062.9     10067854.38      2854174.59     10067746.64
      2854223.08     10067657.71      2854266.12     10067612.84
        2854321.     10067484.78      2854383.03     10067386.15
      2854405.23     10067327.68      2854445.12     10067272.43
      2854496.29     10067147.07      2854622.11     10067021.97
       2854701.2     10066987.04      2854788.69     10066922.68
      2854893.11     10066825.36      2854966.26     10066717.54
      2855014.32     10066676.39       2855037.3      10066639.2
      2855081.68     10066610.31      2855134.47     10066595.52
      2855184.22     10066534.02      2855219.79     10066520.91
      2855379.77     10066515.05      2855426.03       10066499.

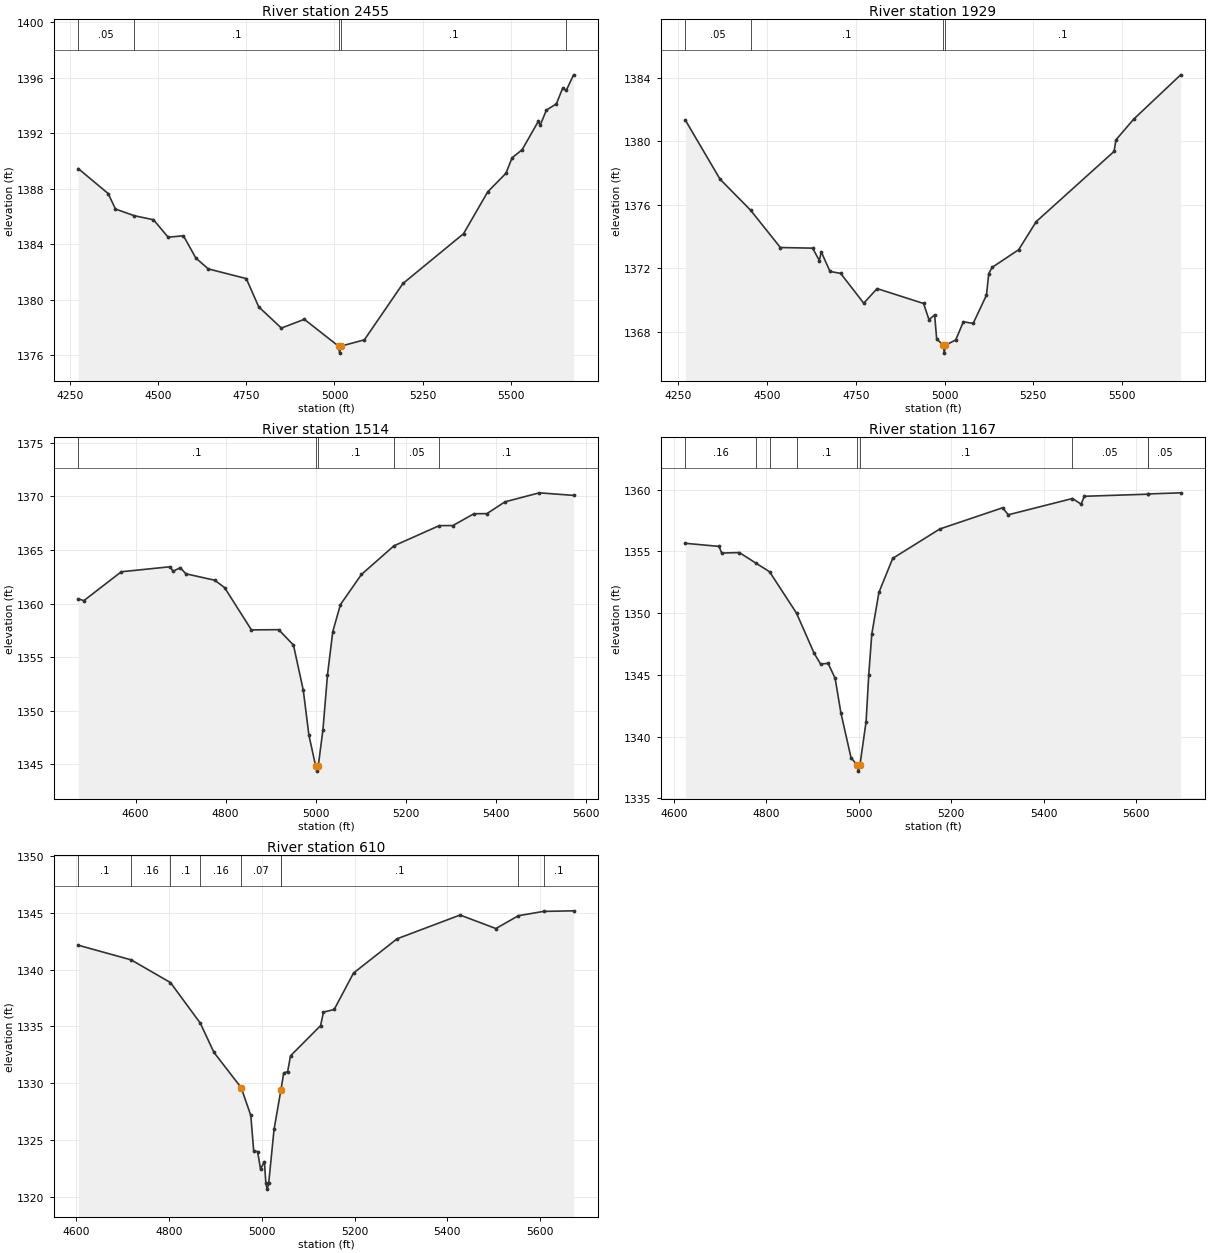
Type RM Length L Ch R = 1 ,2455    ,526,526,526
BEGIN DESCRIPTION:
UNT006 IN NNOGR 5.0
END DESCRIPTION:
XS GIS Cut Line= 4
      2854586.89      10068583.4      2854098.66     10068200.66
      2853818.64     10068189.28      2853362.15     10068400.48
#Sta/Elev= 30
    4274 1389.45  4358.6 1387.65  4379.4 1386.53  4432.6 1386.05    4487 1385.76
  4528.6  1384.5    4572  1384.6  4607.2 1382.99  4642.5 1382.21  4750.1 1381.51
  4785.3 1379.47  4849.5 1377.94  4914.6 1378.57  5011.7 1376.63  5014.4 1376.13
  5017.7 1376.63  5084.7 1377.09  5194.2 1381.16  5365.7 1384.75  5434.5 1387.78
  5485.9 1389.11  5503.3 1390.23  5531.7 1390.81  5577.6 1392.86  5583.1 1392.59
  5600.5 1393.67  5628.9 1394.13  5646.4 1395.24  5656.9  1395.1  5677.6 1396.22
#Mann= 5 ,-1 , 0
    4274     .05       0  4432.6      .1       0  5011.7     .07       0
  5017.7      .1       0  5656.9     .16       0
Bank Sta=5011.7,5017.7
XS Rating Curve= 0 ,0
Exp/Cntr=0.3,0.1

Type RM Length L Ch R = 1 ,1929    ,415,415,415
BEGIN DESCRIPTION:
UNT006 IN NNOGR 4.0
END DESCRIPTION:
XS GIS Cut Line= 4
      2854558.71     10068318.68      2854410.55      10067929.7
      2853955.09      10067674.2      2853527.92      10067834.7
#Sta/Elev= 30
  4270.1 1381.34  4367.7 1377.62  4453.9 1375.66  4537.6 1373.31  4628.5 1373.27
  4647.3 1372.49  4652.7 1373.04  4677.4  1371.8  4707.3 1371.68  4772.4  1369.8
    4810 1370.72    4941 1369.78  4956.1 1368.76  4972.1 1369.06  4977.8 1367.54
  4996.5 1367.15  4999.2 1366.65  5002.5 1367.15  5031.4 1367.48  5053.1 1368.63
  5080.5 1368.52  5118.1 1370.31  5124.4 1371.67  5134.1 1372.06  5208.6 1373.17
  5258.4 1374.95  5477.4 1379.37  5482.7  1380.1  5532.5  1381.4  5664.9  1384.2
#Mann= 4 ,-1 , 0
  4270.1     .05       0  4453.9      .1       0  4996.5     .07       0
  5002.5      .1       0
Bank Sta=4996.5,5002.5
XS Rating Curve= 0 ,0
Exp/Cntr=0.3,0.1

Type RM Length L Ch R = 1 ,1514    ,347,347,347
BEGIN DESCRIPTION:
UNT006 IN NNOGR 3.0
END DESCRIPTION:
XS GIS Cut Line= 2
      2854835.91     10067643.25      2853828.94     10067200.53
#Sta/Elev= 30
  4472.9 1360.43  4485.3 1360.27  4568.4 1362.96  4677.5 1363.43    4683    1363
  4699.5 1363.34  4711.8 1362.77    4776 1362.17  4797.8 1361.48  4857.4 1357.54
    4918 1357.56  4950.8 1356.12  4972.6 1351.91    4985 1347.74  4999.9 1344.87
  5002.7 1344.37  5005.9 1344.87  5016.3 1348.25  5026.3 1353.33  5038.1 1357.38
  5055.1  1359.9  5101.8 1362.71    5174 1365.38  5274.5 1367.26  5304.9 1367.27
  5351.6 1368.37  5380.4 1368.38  5420.5 1369.48  5496.9 1370.32  5572.9 1370.08
#Mann= 5 ,-1 , 0
  4472.9      .1       0  4999.9     .07       0  5005.9      .1       0
    5174     .05       0  5274.5      .1       0
Bank Sta=4999.9,5005.9
XS Rating Curve= 0 ,0
Exp/Cntr=0.3,0.1

Type RM Length L Ch R = 1 ,1167    ,557,557,557
BEGIN DESCRIPTION:
UNT006 IN NNOGR 2.0
END DESCRIPTION:
XS GIS Cut Line= 2
      2854844.55     10067304.69      2853898.37     10066801.22
#Sta/Elev= 30
  4624.9 1355.66  4697.8 1355.41  4703.4 1354.87  4741.7 1354.91  4778.1 1354.04
    4807 1353.36  4865.4    1350  4903.7 1346.74  4917.5 1345.88  4933.8 1345.93
    4949 1344.72  4961.4 1341.93  4983.4 1338.28  4996.7  1337.7  4999.5  1337.2
  5002.7  1337.7    5016 1341.22  5021.7 1344.99  5028.3  1348.3  5043.7 1351.68
  5073.6 1354.44  5175.5 1356.82  5311.5 1358.54  5323.6 1357.97  5462.6 1359.29
  5481.4 1358.83  5488.1 1359.47  5626.3 1359.64  5626.9 1359.66  5696.7 1359.75
#Mann= 9 ,-1 , 0
  4624.9     .16       0  4778.1      .1       0    4807     .16       0
  4865.4      .1       0  4996.7     .07       0  5002.7      .1       0
  5462.6     .05       0  5626.3      .1       0  5626.9     .05       0
Bank Sta=4996.7,5002.7
XS Rating Curve= 0 ,0
Exp/Cntr=0.3,0.1

Type RM Length L Ch R = 1 ,610     ,0,0,0
BEGIN DESCRIPTION:
UNT006 IN NNOGR 1.0
END DESCRIPTION:
XS GIS Cut Line= 2
      2855252.53     10067009.54      2854393.35       10066376.
#Sta/Elev= 30
  4604.6 1342.15  4718.6 1340.86  4803.3 1338.86  4867.5 1335.29    4897 1332.71
  4955.6 1329.61  4976.4 1327.16  4982.6 1324.06  4991.1 1323.97  4997.3 1322.45
  5005.7 1323.09  5008.9 1321.17  5011.7 1320.67  5014.9 1321.17  5026.5 1325.93
    5041 1329.34  5041.2 1329.38  5047.4 1330.91  5055.8 1331.01    5062 1332.41
  5126.8 1335.07    5133 1336.26  5156.1 1336.49  5197.8  1339.7  5291.8 1342.72
  5427.5 1344.81  5504.7 1343.62  5553.1 1344.75  5607.4 1345.13  5672.1 1345.18
#Mann= 9 ,-1 , 0
  4604.6      .1       0  4718.6     .16       0  4803.3      .1       0
  4867.5     .16       0  4955.6     .07       0    5041     .16       0
    5041      .1       0  5553.1     .16       0  5607.4      .1       0
Bank Sta=4955.6,5041.2
XS Rating Curve= 0 ,0
Exp/Cntr=0.3,0.1

Chan Stop Cuts=-1
Use User Specified Reach Order=0
Composite Channel Slope=5