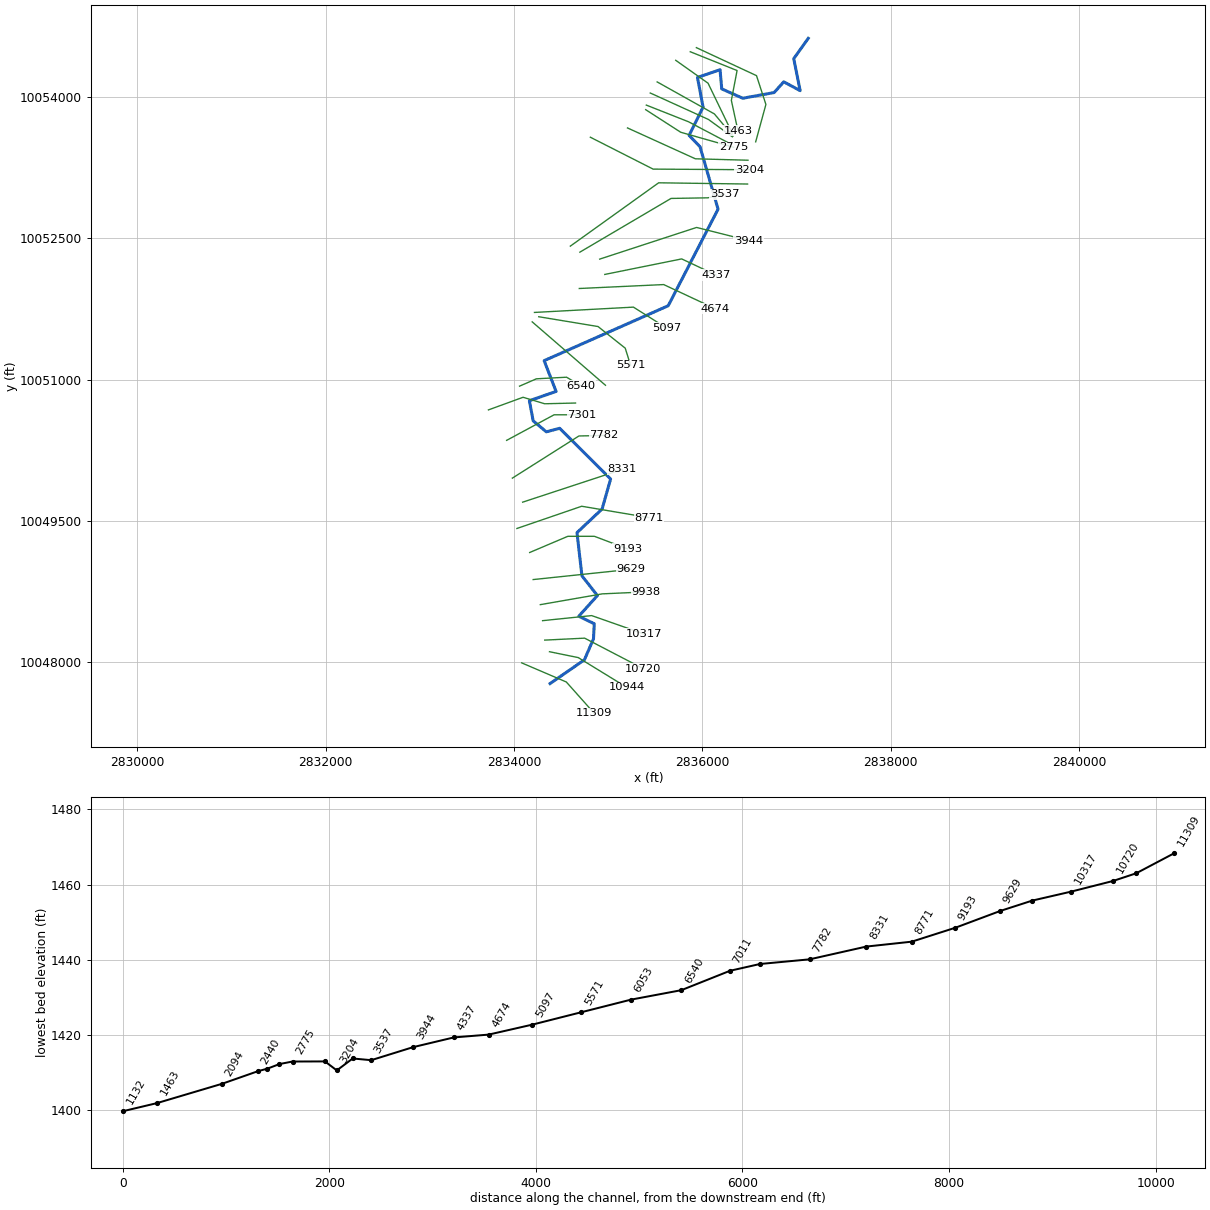
--- UNT006 IN SNOGR.prj (project) ---

Proj Title=UNT006 IN SNOGR Base Level Engineering
Current Plan=p01
Default Exp/Contr=0.3,0.1
English Units
Geom File=g01
Flow File=f01
Plan File=p01
BEGIN DESCRIPTION:
UNT006 IN SNOGR
END DESCRIPTION:

--- UNT006 IN SNOGR.p01 (plan) ---

Plan Title=Multiple Run
Short Identifier=Multiple
Geom File=g01
Flow File=f01
Subcritical Flow
K Sum by GR= 0
Std Step Tol= 0.01
Critical Tol= 0.01
Num of Std Step Trials= 20
Max Error Tol= 0.3
Flow Tol Ratio= 0.001
Split Flow NTrial= 30
Split Flow Tol= 0.02
Split Flow Ratio= 0.02
Log Output Level= 0
Friction Slope Method= 1
Unsteady Friction Slope Method= 2
Unsteady Bridges Friction Slope Method= 1
Parabolic Critical Depth
Global Vel Dist=  1 , 1 , 1
Global Log Level= 0
CheckData=True
Encroach Param= -1, 0, 0, 0
BEGIN DESCRIPTION:
Multiple Run
END DESCRIPTION:

--- UNT006 IN SNOGR.f01 (steady flow) ---

Flow Title=Multiple
Number of Profiles=7
Profile Names=10-year,25-year,50-year,1pct_min,100-year,1pct_plu,500-year
River Rch & RM= UNT006 IN SNOGR,Reach-1,11309
    1026    1496    1907    1779    2405    3253    3841
River Rch & RM= UNT006 IN SNOGR,Reach-1,9193
    1243    1821    2326    2172    2938    3973    4705
River Rch & RM= UNT006 IN SNOGR,Reach-1,3204
    1447    2134    2739    2567    3472    4696    5604
Boundary for River Rch & Prof#=UNT006 IN SNOGR,Reach-1,1
Up Type=0
Dn Type=3
Dn Slope=0.005
Boundary for River Rch & Prof#=UNT006 IN SNOGR,Reach-1,2
Up Type=0
Dn Type=3
Dn Slope=0.005
Boundary for River Rch & Prof#=UNT006 IN SNOGR,Reach-1,3
Up Type=0
Dn Type=3
Dn Slope=0.005
Boundary for River Rch & Prof#=UNT006 IN SNOGR,Reach-1,4
Up Type=0
Dn Type=3
Dn Slope=0.005
Boundary for River Rch & Prof#=UNT006 IN SNOGR,Reach-1,5
Up Type=0
Dn Type=3
Dn Slope=0.005
Boundary for River Rch & Prof#=UNT006 IN SNOGR,Reach-1,6
Up Type=0
Dn Type=3
Dn Slope=0.005
Boundary for River Rch & Prof#=UNT006 IN SNOGR,Reach-1,7
Up Type=0
Dn Type=3
Dn Slope=0.005

--- UNT006 IN SNOGR.g01 (geometry) ---

Geom Title=Existing Conditions

River Reach=UNT006 IN SNOGR,Reach-1
Reach XY= 30
      2834383.65     10047770.73      2834747.60     10048022.34
      2834844.41     10048245.19      2834852.92     10048406.12
      2834688.24     10048485.66      2834886.22     10048705.50
      2834721.71     10048915.25      2834669.45     10049373.85
      2834935.92     10049624.85      2835026.22     10049943.65
      2834485.54     10050481.94      2834343.65     10050444.54
      2834204.23     10050561.24      2834164.03     10050775.06
      2834447.57     10050873.70      2834320.76     10051200.38
      2835637.73     10051783.86      2836166.76     10052809.43
      2835975.32     10053472.18      2835859.44     10053593.68
      2836007.53     10053893.60      2835948.29     10054208.69
      2836187.72     10054290.74      2836206.00     10054086.94
      2836429.15     10053987.83      2836761.57     10054048.06
      2836864.00     10054162.26      2837038.09     10054068.33
      2836969.99     10054408.17      2837123.98     10054624.14

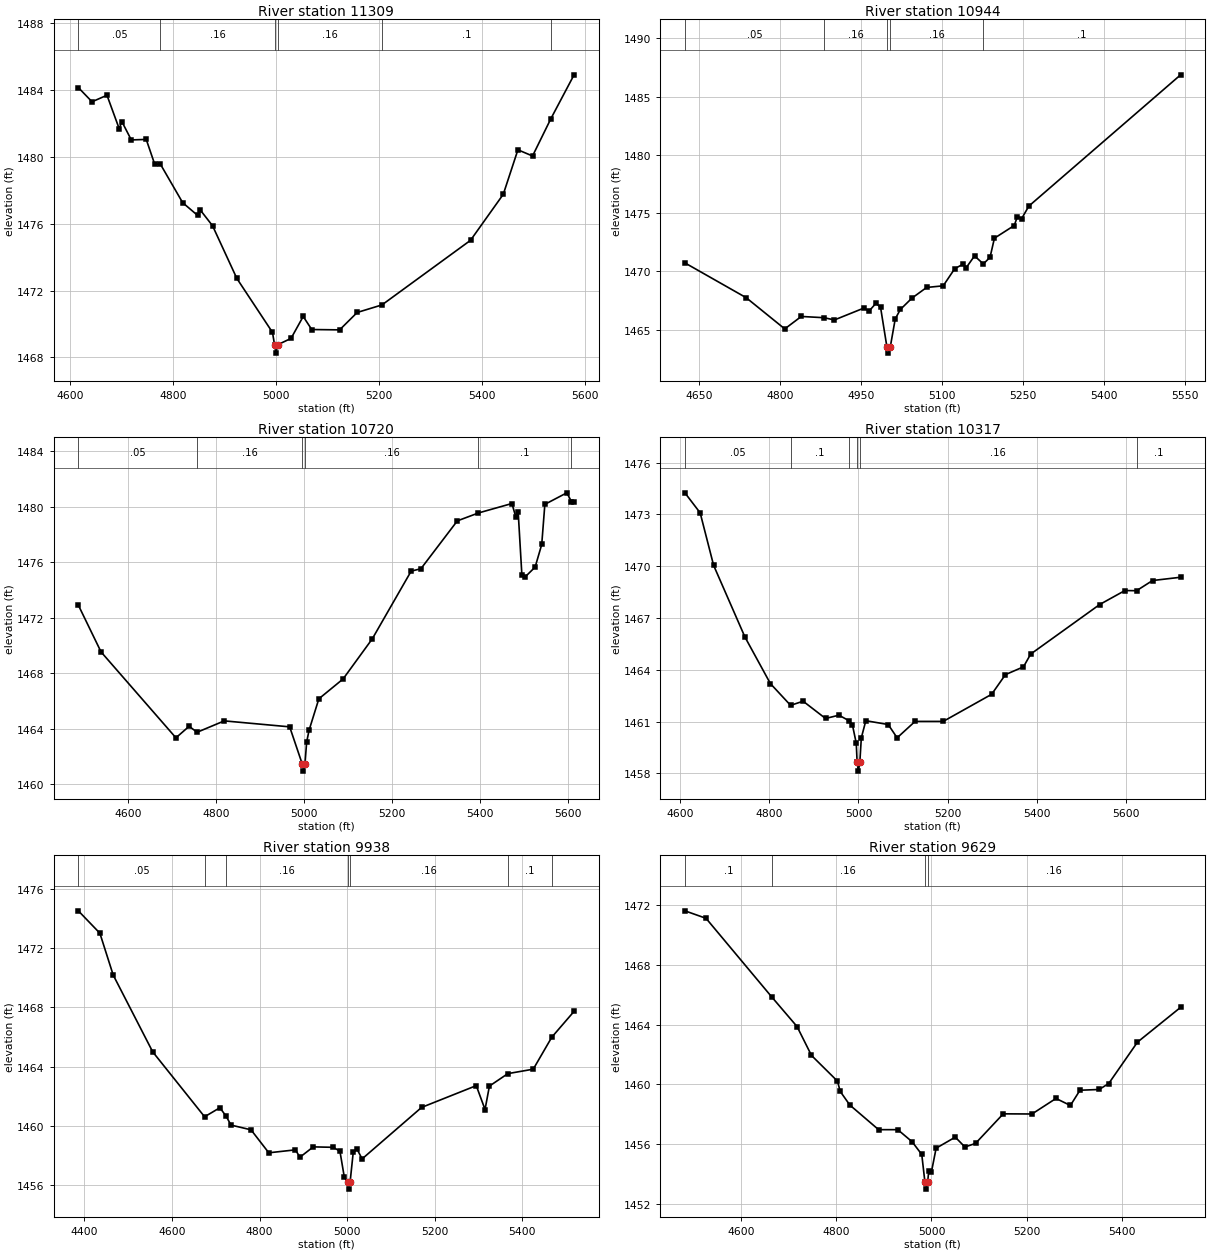
Type RM Length L Ch R = 1,11309,365,365,365
BEGIN DESCRIPTION:
UNT006 IN SNOGR 17.0
END DESCRIPTION:
XS GIS Cut Line= 3
      2834082.13     10047990.56      2834556.12     10047787.42
      2834853.02     10047454.05
#Sta/Elev= 30
  4616.2 1484.13  4642.8 1483.28  4671.8 1483.67  4695.4 1481.68  4700.8 1482.09
  4719.0 1481.00  4748.0 1481.03  4764.5 1479.54  4775.5 1479.55  4818.7 1477.25
  4847.7 1476.49  4853.2 1476.80  4876.7 1475.87  4923.9 1472.72  4993.0 1469.50
  4997.0 1468.76  4999.8 1468.26  5003.0 1468.76  5029.0 1469.14  5052.6 1470.45
  5069.2 1469.67  5123.3 1469.65  5157.4 1470.69  5205.4 1471.14  5377.3 1475.00
  5440.9 1477.75  5469.3 1480.41  5497.7 1480.04  5533.3 1482.27  5578.3 1484.89
#Mann=6,-1,0
  4616.2    0.05       0  4775.5    0.16       0  4997.0    0.07       0
  5003.0    0.16       0  5205.4     0.1       0  5533.3    0.05       0
Bank Sta=4997,5003
Exp/Cntr=0.3,0.1

Type RM Length L Ch R = 1,10944,224,224,224
BEGIN DESCRIPTION:
UNT006 IN SNOGR 16.0
END DESCRIPTION:
XS GIS Cut Line= 3
      2834377.29     10048108.95      2834682.86     10048046.44
      2835199.18     10047729.57
#Sta/Elev= 30
  4623.5 1470.73  4737.0 1467.74  4808.4 1465.06  4839.0 1466.13  4881.4 1466.02
  4900.3 1465.83  4954.9 1466.85  4964.4 1466.59  4977.2 1467.26  4985.7 1466.92
  4997.6 1463.48  5000.4 1462.98  5003.6 1463.48  5012.9 1465.92  5022.4 1466.73
  5043.7 1467.70  5071.0 1468.62  5101.7 1468.76  5123.0 1470.23  5138.4 1470.62
  5144.3 1470.32  5159.7 1471.33  5176.0 1470.64  5188.4 1471.21  5196.5 1472.85
  5233.2 1473.94  5239.0 1474.70  5247.0 1474.54  5260.3 1475.61  5541.2 1486.88
#Mann=5,-1,0
  4623.5    0.05       0  4881.4    0.16       0  4997.6    0.07       0
  5003.6    0.16       0  5176.0     0.1       0
Bank Sta=4997.6,5003.6
Exp/Cntr=0.3,0.1

Type RM Length L Ch R = 1,10720,403,403,403
BEGIN DESCRIPTION:
Mapping XS 4f370bc9
END DESCRIPTION:
XS GIS Cut Line= 3
      2834326.93     10048232.21      2834750.56     10048253.04
      2835373.71     10047928.82
#Sta/Elev= 30
  4487.6 1472.90  4539.2 1469.53  4709.4 1463.34  4739.4 1464.17  4757.5 1463.74
  4819.3 1464.56  4967.9 1464.13  4996.6 1461.44  4999.3 1460.94  5002.6 1461.44
  5006.5 1463.04  5012.1 1463.90  5034.2 1466.15  5089.3 1467.58  5155.6 1470.47
  5244.0 1475.35  5266.1 1475.52  5348.9 1478.97  5396.9 1479.54  5473.0 1480.22
  5481.5 1479.28  5487.2 1479.60  5495.6 1475.06  5503.6 1474.95  5525.7 1475.64
  5540.7 1477.27  5547.8 1480.16  5597.7 1480.99  5608.3 1480.36  5614.2 1480.34
#Mann=6,-1,0
  4487.6    0.05       0  4757.5    0.16       0  4996.6    0.07       0
  5002.6    0.16       0  5396.9     0.1       0  5608.3    0.05       0
Bank Sta=4996.6,5002.6
Exp/Cntr=0.3,0.1

Type RM Length L Ch R = 1,10317,379,379,379
BEGIN DESCRIPTION:
UNT006 IN SNOGR 15.0
END DESCRIPTION:
XS GIS Cut Line= 3
      2834304.34     10048438.80      2834825.22     10048492.62
      2835381.47     10048297.28
#Sta/Elev= 30
  4610.2 1474.25  4644.5 1473.09  4674.7 1470.05  4745.0 1465.90  4802.2 1463.20
  4847.6 1461.94  4875.7 1462.18  4926.0 1461.18  4956.2 1461.37  4979.4 1461.04
  4986.3 1460.82  4995.0 1459.75  4997.0 1458.63  4999.8 1458.13  5003.0 1458.63
  5006.4 1460.06  5016.5 1461.05  5066.7 1460.83  5086.8 1460.06  5127.1 1461.01
  5190.3 1461.01  5299.0 1462.58  5330.0 1463.72  5370.5 1464.17  5386.7 1464.91
  5541.6 1467.78  5598.3 1468.59  5624.4 1468.58  5660.3 1469.17  5723.4 1469.36
#Mann=6,-1,0
  4610.2    0.05       0  4847.6     0.1       0  4979.4    0.16       0
  4997.0    0.07       0  5003.0    0.16       0  5624.4     0.1       0
Bank Sta=4997,5003
Exp/Cntr=0.3,0.1

Type RM Length L Ch R = 1,9938,309,309,309
BEGIN DESCRIPTION:
Mapping XS b1938200
END DESCRIPTION:
XS GIS Cut Line= 3
      2834280.03     10048608.93      2834938.06     10048723.53
      2835401.56     10048744.36
#Sta/Elev= 30
  4386.0 1474.50  4435.2 1472.99  4465.6 1470.17  4555.8 1464.99  4674.3 1460.61
  4709.2 1461.22  4723.4 1460.65  4734.6 1460.05  4780.3 1459.73  4820.9 1458.18
  4881.8 1458.38  4891.9 1457.88  4922.4 1458.58  4967.9 1458.55  4983.3 1458.29
  4993.4 1456.52  5000.6 1456.23  5003.3 1455.73  5006.6 1456.23  5013.7 1458.22
  5022.4 1458.42  5034.0 1457.77  5169.7 1461.24  5294.6 1462.71  5314.6 1461.10
  5324.6 1462.68  5366.7 1463.52  5424.7 1463.82  5467.1 1465.98  5517.9 1467.72
#Mann=7,-1,0
  4386.0    0.05       0  4674.3     0.1       0  4723.4    0.16       0
  5000.6    0.07       0  5006.6    0.16       0  5366.7     0.1       0
  5467.1    0.05       0
Bank Sta=5000.6,5006.6
Exp/Cntr=0.3,0.1

Type RM Length L Ch R = 1,9629,436,436,436
BEGIN DESCRIPTION:
UNT006 IN SNOGR 14.0
END DESCRIPTION:
XS GIS Cut Line= 2
      2834204.42     10048875.41      2835238.44     10048983.95
#Sta/Elev= 30
  4482.9 1471.62  4527.2 1471.12  4665.2 1465.85  4718.2 1463.87  4748.4 1461.94
  4802.9 1460.22  4808.7 1459.53  4828.8 1458.62  4889.2 1456.97  4929.4 1456.97
  4959.5 1456.16  4979.7 1455.31  4986.2 1453.49  4988.9 1452.99  4992.2 1453.49
  4994.2 1454.19  4999.8 1454.11  5009.8 1455.73  5050.0 1456.47  5070.2 1455.81
  5092.4 1456.05  5150.6 1458.03  5210.9 1458.02  5261.2 1459.06  5291.4 1458.59
  5311.5 1459.61  5351.7 1459.66  5371.8 1460.06  5432.1 1462.83  5522.6 1465.16
#Mann=4,-1,0
  4482.9     0.1       0  4665.2    0.16       0  4986.2    0.07       0
  4992.2    0.16       0
Bank Sta=4986.2,4992.2
Exp/Cntr=0.3,0.1

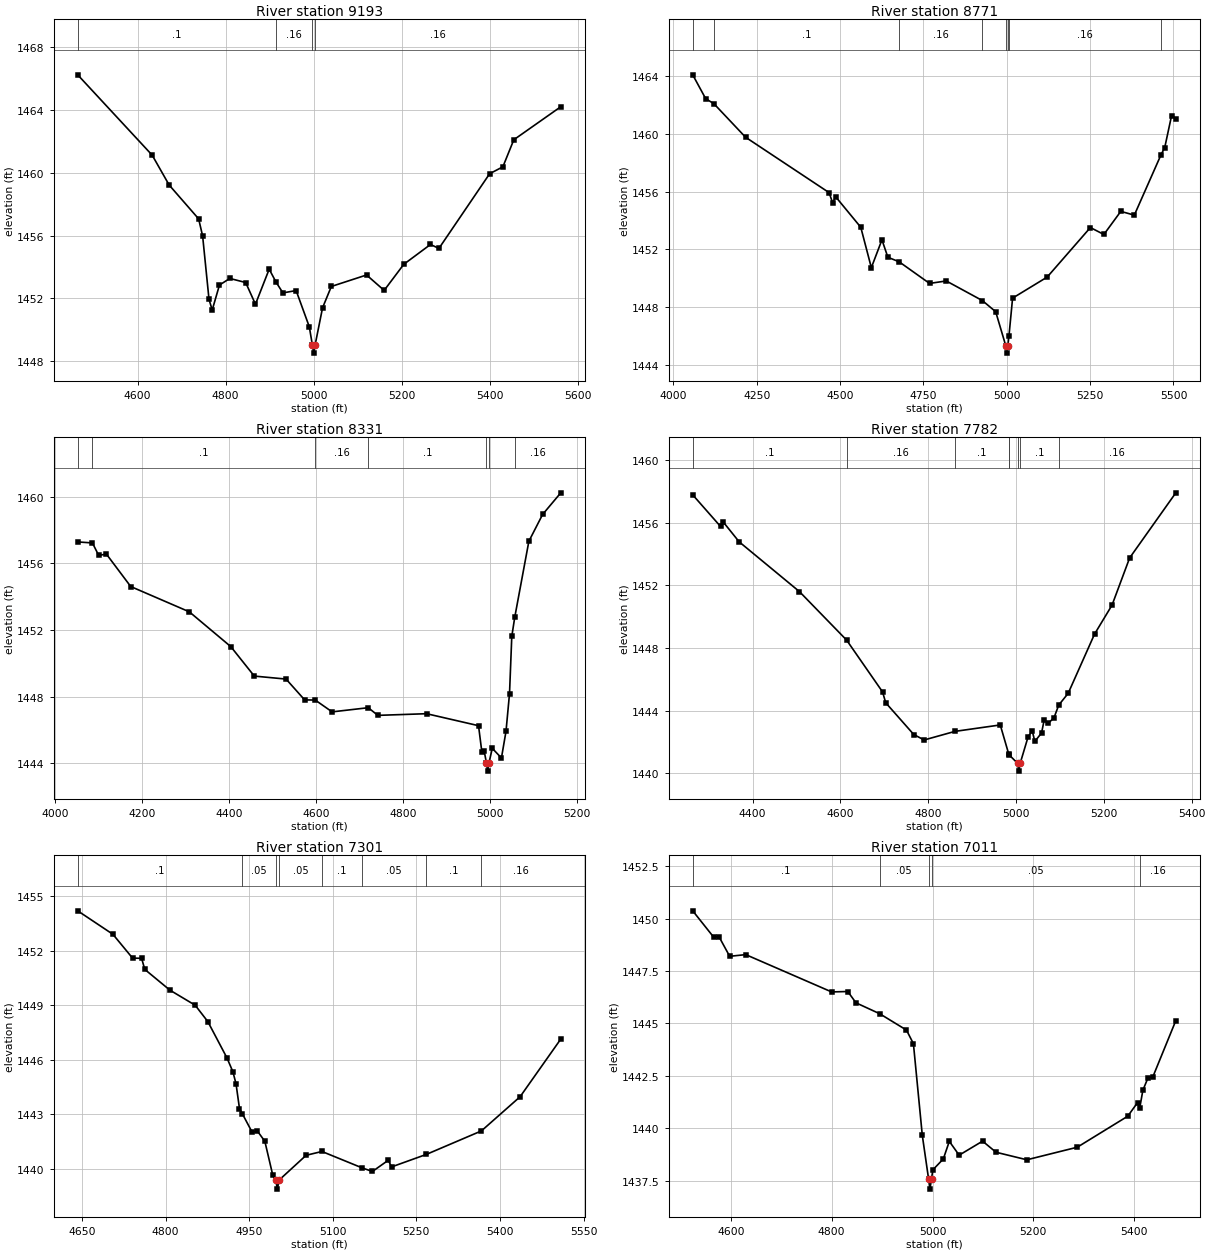
Type RM Length L Ch R = 1,9193,422,422,422
BEGIN DESCRIPTION:
UNT006 IN SNOGR 13.0
END DESCRIPTION:
XS GIS Cut Line= 4
      2834167.24     10049162.77      2834571.74     10049334.64
      2834854.73     10049334.64      2835205.27     10049201.68
#Sta/Elev= 30
  4463.9 1466.22  4633.1 1461.11  4671.7 1459.21  4738.6 1457.06  4747.7 1455.97
  4762.2 1451.94  4769.5 1451.26  4785.9 1452.85  4809.5 1453.27  4845.5 1453.01
  4867.7 1451.63  4898.9 1453.86  4914.4 1453.04  4930.1 1452.35  4960.1 1452.50
  4990.1 1450.19  4997.1 1449.02  4999.9 1448.52  5003.1 1449.02  5020.1 1451.40
  5040.1 1452.76  5120.1 1453.49  5160.1 1452.51  5204.7 1454.17  5265.3 1455.43
  5284.5 1455.18  5399.7 1459.93  5429.8 1460.37  5454.6 1462.09  5561.3 1464.19
#Mann=4,-1,0
  4463.9     0.1       0  4914.4    0.16       0  4997.1    0.07       0
  5003.1    0.16       0
Bank Sta=4997.1,5003.1
Exp/Cntr=0.3,0.1

Type RM Length L Ch R = 1,8771,440,440,440
BEGIN DESCRIPTION:
UNT006 IN SNOGR 12.0
END DESCRIPTION:
XS GIS Cut Line= 3
      2834031.78     10049417.96      2834719.31     10049654.08
      2835431.16     10049534.28
#Sta/Elev= 30
  4058.2 1464.10  4097.0 1462.45  4121.7 1462.10  4216.5 1459.78  4467.1 1455.94
  4477.6 1455.25  4487.3 1455.64  4562.2 1453.54  4593.9 1450.74  4625.7 1452.67
  4643.5 1451.46  4677.1 1451.15  4768.5 1449.65  4818.6 1449.82  4926.9 1448.46
  4966.8 1447.69  4997.2 1445.32  5000.0 1444.82  5003.2 1445.32  5006.6 1446.00
  5017.5 1448.63  5121.3 1450.09  5250.8 1453.52  5291.3 1453.04  5342.0 1454.64
  5382.6 1454.38  5462.8 1458.57  5473.8 1459.06  5494.1 1461.25  5507.0 1461.06
#Mann=8,-1,0
  4058.2    0.16       0  4121.7     0.1       0  4677.1    0.16       0
  4926.9     0.1       0  4997.2    0.07       0  5003.2     0.1       0
  5006.6    0.16       0  5462.8     0.1       0
Bank Sta=4997.2,5003.2
Exp/Cntr=0.3,0.1

Type RM Length L Ch R = 1,8331,549,549,549
BEGIN DESCRIPTION:
Mapping XS 2e9ef5e3
END DESCRIPTION:
XS GIS Cut Line= 2
      2834092.59     10049697.49      2835148.15     10050044.71
#Sta/Elev= 30
  4052.4 1457.29  4086.3 1457.23  4100.7 1456.48  4118.4 1456.56  4174.4 1454.61
  4309.2 1453.09  4404.6 1451.00  4458.6 1449.23  4531.7 1449.05  4574.4 1447.80
  4598.8 1447.79  4637.6 1447.08  4720.7 1447.33  4742.9 1446.87  4854.9 1446.97
  4974.4 1446.25  4982.1 1444.66  4987.3 1444.75  4992.5 1444.02  4995.3 1443.52
  4998.5 1444.02  5006.0 1444.89  5027.1 1444.31  5037.6 1445.91  5045.7 1448.18
  5050.9 1451.61  5057.7 1452.76  5090.2 1457.33  5121.8 1458.94  5163.6 1460.24
#Mann=7,-1,0
  4052.4    0.16       0  4086.3     0.1       0  4598.8    0.16       0
  4720.7     0.1       0  4992.5    0.07       0  4998.5     0.1       0
  5057.7    0.16       0
Bank Sta=4992.5,4998.5
Exp/Cntr=0.3,0.1

Type RM Length L Ch R = 1,7782,481,481,481
BEGIN DESCRIPTION:
Mapping XS 5ec13e83
END DESCRIPTION:
XS GIS Cut Line= 3
      2833983.18     10049952.68      2834689.80     10050400.61
      2834953.62     10050405.82
#Sta/Elev= 30
  4263.4 1457.78  4326.8 1455.76  4332.8 1456.05  4369.2 1454.78  4506.5 1451.60
  4614.0 1448.50  4695.9 1445.19  4703.0 1444.50  4766.9 1442.47  4790.6 1442.12
  4860.9 1442.67  4964.0 1443.08  4983.2 1441.23  4983.5 1441.19  5003.4 1440.63
  5006.1 1440.13  5009.4 1440.63  5027.6 1442.34  5036.9 1442.69  5042.8 1442.03
  5058.1 1442.57  5064.0 1443.39  5073.3 1443.18  5086.6 1443.55  5097.2 1444.35
  5118.7 1445.10  5178.7 1448.88  5218.7 1450.74  5258.7 1453.75  5363.9 1457.91
#Mann=8,-1,0
  4263.4     0.1       0  4614.0    0.16       0  4860.9     0.1       0
  4983.2    0.05       0  4983.5     0.1       0  5003.4    0.07       0
  5009.4     0.1       0  5097.2    0.16       0
Bank Sta=5003.4,5009.4
Exp/Cntr=0.3,0.1

Type RM Length L Ch R = 1,7301,290,290,290
BEGIN DESCRIPTION:
Mapping XS 62fab84c
END DESCRIPTION:
XS GIS Cut Line= 3
      2833922.80     10050354.15      2834426.30     10050625.44
      2834721.47     10050625.44
#Sta/Elev= 30
  4642.1 1454.19  4705.3 1452.90  4740.6 1451.59  4756.8 1451.58  4762.5 1450.97
  4807.6 1449.83  4853.0 1449.00  4875.7 1448.10  4910.1 1446.10  4920.7 1445.34
  4926.3 1444.68  4932.5 1443.32  4937.7 1443.03  4955.2 1442.02  4964.5 1442.09
  4978.0 1441.52  4992.0 1439.69  4997.7 1439.39  5000.4 1438.89  5003.7 1439.39
  5052.1 1440.75  5080.5 1440.96  5152.5 1440.06  5171.1 1439.86  5199.7 1440.48
  5205.4 1440.11  5268.0 1440.80  5366.7 1442.09  5436.2 1443.97  5509.2 1447.14
#Mann=8,-1,0
  4642.1     0.1       0  4937.7    0.05       0  4997.7   0.035       0
  5003.7    0.05       0  5080.5     0.1       0  5152.5    0.05       0
  5268.0     0.1       0  5366.7    0.16       0
Bank Sta=4997.7,5003.7
Exp/Cntr=0.3,0.1

Type RM Length L Ch R = 1,7011,471,471,471
BEGIN DESCRIPTION:
UNT006 IN SNOGR 11.0
END DESCRIPTION:
XS GIS Cut Line= 4
      2833729.65     10050677.51      2834096.87     10050811.63
      2834326.04     10050742.62      2834653.77     10050750.43
#Sta/Elev= 30
  4524.4 1450.37  4565.7 1449.12  4576.4 1449.14  4597.7 1448.20  4629.6 1448.28
  4799.9 1446.50  4831.9 1446.52  4848.2 1445.98  4895.2 1445.46  4948.3 1444.68
  4962.1 1444.03  4979.7 1439.66  4992.1 1437.59  4994.8 1437.09  4998.1 1437.59
  5000.6 1438.01  5021.4 1438.53  5033.3 1439.37  5052.8 1438.71  5099.3 1439.38
  5125.9 1438.85  5187.1 1438.49  5287.1 1439.09  5387.2 1440.57  5406.7 1441.22
  5411.1 1440.98  5417.2 1441.81  5427.2 1442.39  5437.2 1442.46  5482.5 1445.13
#Mann=5,-1,0
  4524.4     0.1       0  4895.2    0.05       0  4992.1   0.035       0
  4998.1    0.05       0  5411.1    0.16       0
Bank Sta=4992.1,4998.1
Exp/Cntr=0.3,0.1

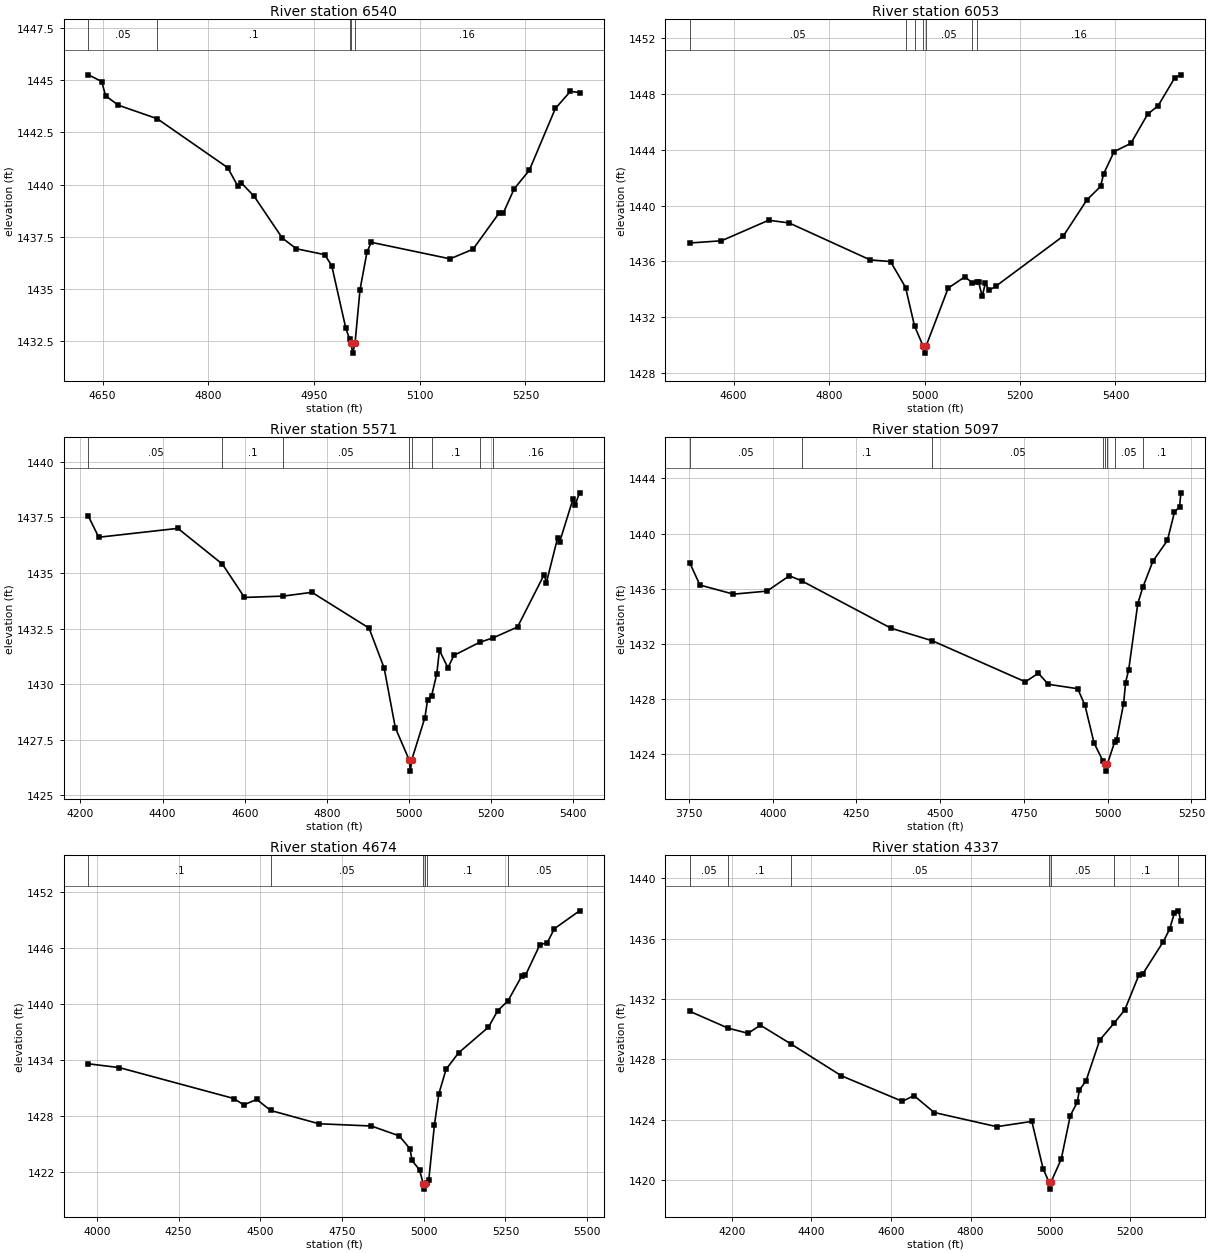
Type RM Length L Ch R = 1,6540,487,487,487
BEGIN DESCRIPTION:
UNT006 IN SNOGR 10.0
END DESCRIPTION:
XS GIS Cut Line= 4
      2834059.59     10050929.62      2834238.37     10051007.73
      2834558.68     10051024.74      2834714.19     10050931.87
#Sta/Elev= 30
  4629.8 1445.25  4648.8 1444.93  4654.2 1444.25  4672.2 1443.80  4727.6 1443.15
  4827.5 1440.81  4841.9 1439.93  4846.9 1440.08  4865.1 1439.44  4905.1 1437.44
  4925.1 1436.93  4965.2 1436.65  4975.2 1436.12  4995.2 1433.12  5000.5 1432.61
  5002.3 1432.44  5005.0 1431.94  5008.3 1432.44  5015.3 1434.97  5025.3 1436.79
  5031.3 1437.24  5143.1 1436.45  5175.7 1436.91  5212.7 1438.64  5218.5 1438.63
  5234.1 1439.80  5255.5 1440.68  5292.5 1443.64  5313.9 1444.46  5326.8 1444.40
#Mann=5,-1,0
  4629.8    0.05       0  4727.6     0.1       0  5000.5    0.16       0
  5002.3    0.07       0  5008.3    0.16       0
Bank Sta=5002.3,5008.3
Exp/Cntr=0.3,0.1

Type RM Length L Ch R = 1,6053,482,482,482
BEGIN DESCRIPTION:
UNT006 IN SNOGR 9.0
END DESCRIPTION:
XS GIS Cut Line= 2
      2834193.69     10051612.82      2834971.45     10050939.22
#Sta/Elev= 30
  4508.1 1437.32  4574.7 1437.48  4673.4 1438.95  4716.2 1438.76  4886.2 1436.11
  4928.9 1435.99  4960.4 1434.13  4979.1 1431.37  4997.2 1429.93  5000.0 1429.43
  5003.2 1429.93  5049.6 1434.09  5084.7 1434.90  5099.8 1434.48  5109.8 1434.50
  5113.2 1434.56  5120.8 1433.49  5127.4 1434.43  5135.1 1433.93  5149.3 1434.22
  5290.8 1437.82  5340.2 1440.41  5368.7 1441.37  5375.3 1442.28  5397.2 1443.87
  5432.3 1444.46  5467.4 1446.55  5489.3 1447.15  5524.5 1449.17  5537.0 1449.37
#Mann=7,-1,0
  4508.1    0.05       0  4960.4     0.1       0  4979.1    0.05       0
  4997.2   0.035       0  5003.2    0.05       0  5099.8     0.1       0
  5109.8    0.16       0
Bank Sta=4997.2,5003.2
Exp/Cntr=0.3,0.1

Type RM Length L Ch R = 1,5571,474,474,474
BEGIN DESCRIPTION:
Mapping XS 2c0ae845
END DESCRIPTION:
XS GIS Cut Line= 4
      2834263.50     10051667.11      2834892.88     10051562.94
      2835181.51     10051332.90      2835237.94     10051152.76
#Sta/Elev= 30
  4219.2 1437.56  4244.5 1436.61  4437.1 1437.01  4545.6 1435.40  4599.3 1433.90
  4693.4 1433.96  4763.5 1434.13  4902.6 1432.52  4939.4 1430.72  4966.6 1428.03
  5000.4 1426.58  5003.2 1426.08  5006.4 1426.58  5038.6 1428.49  5045.0 1429.28
  5055.0 1429.48  5067.5 1430.46  5073.9 1431.52  5094.7 1430.73  5109.1 1431.29
  5171.9 1431.88  5204.7 1432.08  5264.1 1432.57  5329.0 1434.93  5334.3 1434.56
  5361.5 1436.57  5366.7 1436.40  5399.1 1438.33  5404.4 1438.07  5415.0 1438.61
#Mann=8,-1,0
  4219.2    0.05       0  4545.6     0.1       0  4693.4    0.05       0
  5000.4   0.035       0  5006.4    0.05       0  5055.0     0.1       0
  5171.9    0.05       0  5204.7    0.16       0
Bank Sta=5000.4,5006.4
Exp/Cntr=0.3,0.1

Type RM Length L Ch R = 1,5097,423,423,423
BEGIN DESCRIPTION:
Mapping XS d829e76b
END DESCRIPTION:
XS GIS Cut Line= 3
      2834218.00     10051712.68      2835268.32     10051769.10
      2835619.05     10051548.26
#Sta/Elev= 30
  3752.2 1437.89  3782.7 1436.27  3882.9 1435.61  3983.0 1435.83  4049.8 1436.94
  4086.0 1436.58  4353.5 1433.14  4476.9 1432.23  4754.1 1429.26  4793.2 1429.88
  4822.7 1429.08  4910.6 1428.76  4932.2 1427.56  4959.3 1424.83  4985.5 1423.55
  4992.8 1423.29  4995.5 1422.79  4998.8 1423.29  5020.6 1424.88  5026.4 1425.04
  5047.6 1427.68  5053.5 1429.21  5062.9 1430.15  5090.0 1434.93  5105.3 1436.13
  5135.1 1438.00  5178.3 1439.50  5199.5 1441.56  5214.8 1441.95  5218.5 1442.95
#Mann=8,-1,0
  3752.2    0.05       0  4086.0     0.1       0  4476.9    0.05       0
  4985.5     0.1       0  4992.8    0.07       0  4998.8     0.1       0
  5020.6    0.05       0  5105.3     0.1       0
Bank Sta=4992.8,4998.8
Exp/Cntr=0.3,0.1

Type RM Length L Ch R = 1,4674,337,337,337
BEGIN DESCRIPTION:
UNT006 IN SNOGR 8.0
END DESCRIPTION:
XS GIS Cut Line= 3
      2834693.68     10051966.99      2835589.52     10052008.66
      2836138.13     10051751.72
#Sta/Elev= 30
  3974.1 1433.60  4069.0 1433.19  4419.4 1429.87  4449.4 1429.19  4489.4 1429.77
  4531.6 1428.59  4679.6 1427.16  4839.8 1426.92  4925.0 1425.86  4958.1 1424.48
  4964.3 1423.22  4987.2 1422.21  4999.2 1420.64  5002.0 1420.14  5005.2 1420.64
  5011.6 1420.83  5015.5 1421.11  5032.8 1427.03  5046.4 1430.38  5068.5 1433.01
  5106.8 1434.78  5198.2 1437.54  5226.5 1439.30  5258.0 1440.37  5300.5 1443.06
  5311.4 1443.11  5355.6 1446.40  5377.7 1446.59  5399.8 1448.11  5476.7 1450.03
#Mann=6,-1,0
  3974.1     0.1       0  4531.6    0.05       0  4999.2   0.035       0
  5005.2    0.05       0  5011.6     0.1       0  5258.0    0.05       0
Bank Sta=4999.2,5005.2
Exp/Cntr=0.3,0.1

Type RM Length L Ch R = 1,4337,393,393,393
BEGIN DESCRIPTION:
UNT006 IN SNOGR 7.0
END DESCRIPTION:
XS GIS Cut Line= 3
      2834964.53     10052116.33      2835780.47     10052281.25
      2836144.22     10052110.20
#Sta/Elev= 30
  4094.2 1431.18  4191.0 1430.06  4241.0 1429.72  4271.7 1430.26  4348.9 1429.01
  4475.7 1426.90  4628.7 1425.21  4657.9 1425.59  4708.6 1424.47  4866.0 1423.53
  4954.1 1423.88  4982.4 1420.74  4996.7 1419.89  4999.4 1419.39  5002.7 1419.89
  5028.0 1421.38  5050.8 1424.27  5068.1 1425.14  5073.6 1425.96  5090.2 1426.56
  5124.7 1429.27  5160.3 1430.38  5187.6 1431.27  5222.8 1433.56  5233.2 1433.67
  5284.3 1435.79  5300.1 1436.61  5312.6 1437.71  5322.6 1437.84  5328.6 1437.16
#Mann=7,-1,0
  4094.2    0.05       0  4191.0     0.1       0  4348.9    0.05       0
  4996.7   0.035       0  5002.7    0.05       0  5160.3     0.1       0
  5322.6    0.05       0
Bank Sta=4996.7,5002.7
Exp/Cntr=0.3,0.1

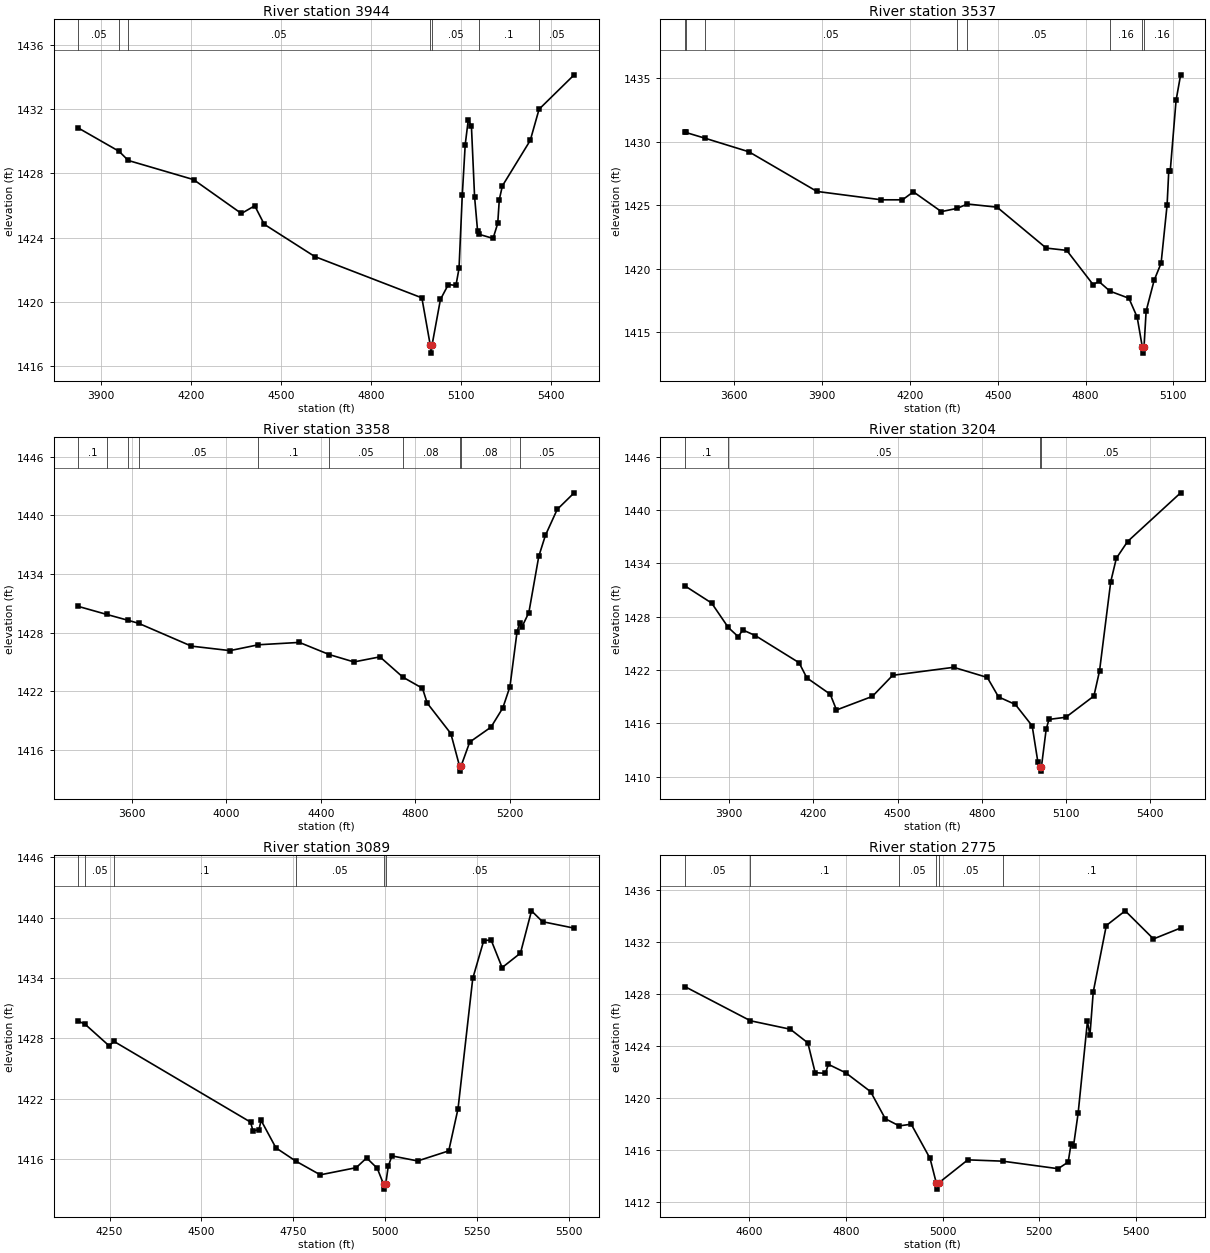
Type RM Length L Ch R = 1,3944,407,407,407
BEGIN DESCRIPTION:
Mapping XS 62f778d2
END DESCRIPTION:
XS GIS Cut Line= 3
      2834910.27     10052279.09      2835938.89     10052615.45
      2836490.14     10052476.55
#Sta/Elev= 30
  3826.1 1430.83  3961.7 1429.38  3992.4 1428.81  4209.6 1427.62  4369.0 1425.51
  4413.4 1425.99  4444.9 1424.84  4613.3 1422.83  4969.8 1420.26  4997.7 1417.32
  5000.4 1416.82  5003.7 1417.32  5031.6 1420.16  5058.0 1421.09  5083.2 1421.03
  5093.5 1422.09  5104.3 1426.64  5114.1 1429.80  5124.4 1431.35  5134.8 1430.94
  5145.3 1426.55  5155.4 1424.40  5161.0 1424.21  5206.9 1423.96  5222.4 1424.90
  5227.6 1426.38  5237.9 1427.23  5330.7 1430.06  5360.0 1432.00  5476.8 1434.14
#Mann=7,-1,0
  3826.1    0.05       0  3961.7     0.1       0  3992.4    0.05       0
  4997.7   0.035       0  5003.7    0.05       0  5161.0     0.1       0
  5360.0    0.05       0
Bank Sta=4997.7,5003.7
Exp/Cntr=0.3,0.1

Type RM Length L Ch R = 1,3537,179,179,179
BEGIN DESCRIPTION:
Mapping XS 28dbc508
END DESCRIPTION:
XS GIS Cut Line= 4
      2834699.75     10052352.87      2835667.62     10052923.61
      2836058.25     10052930.12      2836233.73     10052966.95
#Sta/Elev= 30
  3431.2 1430.73  3433.6 1430.73  3500.2 1430.27  3650.3 1429.20  3882.5 1426.08
  4103.0 1425.42  4174.8 1425.42  4211.9 1426.05  4307.6 1424.49  4361.9 1424.75
  4396.5 1425.09  4497.8 1424.84  4665.7 1421.62  4735.7 1421.44  4825.7 1418.75
  4845.7 1418.99  4883.3 1418.23  4948.2 1417.67  4976.4 1416.18  4993.8 1413.85
  4996.6 1413.35  4999.8 1413.85  5007.0 1416.66  5034.3 1419.08  5058.1 1420.43
  5078.6 1425.02  5084.2 1427.65  5089.3 1427.68  5109.2 1433.24  5124.8 1435.26
#Mann=8,-1,0
  3431.2    0.05       0  3433.6     0.1       0  3500.2    0.05       0
  4361.9     0.1       0  4396.5    0.05       0  4883.3    0.16       0
  4993.8    0.07       0  4999.8    0.16       0
Bank Sta=4993.8,4999.8
Exp/Cntr=0.3,0.1

Type RM Length L Ch R = 1,3358,154,154,154
BEGIN DESCRIPTION:
Mapping XS e35907ef
END DESCRIPTION:
XS GIS Cut Line= 3
      2834598.68     10052416.92      2835536.16     10053089.65
      2836480.19     10053076.63
#Sta/Elev= 30
  3374.4 1430.68  3494.3 1429.86  3582.9 1429.27  3629.3 1428.95  3852.9 1426.61
  4016.2 1426.15  4136.6 1426.75  4309.7 1426.99  4436.7 1425.74  4540.6 1424.99
  4650.6 1425.51  4747.7 1423.43  4830.6 1422.29  4850.6 1420.77  4950.6 1417.65
  4987.6 1414.30  4990.4 1413.80  4993.6 1414.30  5030.6 1416.78  5120.6 1418.31
  5170.6 1420.28  5200.7 1422.46  5230.7 1428.07  5241.4 1428.96  5250.7 1428.54
  5280.7 1430.05  5322.7 1435.81  5350.7 1437.96  5400.7 1440.62  5472.4 1442.32
#Mann=10,-1,0
  3374.4     0.1       0  3494.3    0.05       0  3582.9     0.1       0
  3629.3    0.05       0  4136.6     0.1       0  4436.7    0.05       0
  4747.7    0.08       0  4987.6    0.07       0  4993.6    0.08       0
  5241.4    0.05       0
Bank Sta=4987.6,4993.6
Exp/Cntr=0.3,0.1

Type RM Length L Ch R = 1,3204,115,115,115
BEGIN DESCRIPTION:
Mapping XS e7a312b7
END DESCRIPTION:
XS GIS Cut Line= 3
      2834811.32     10053573.60      2835477.57     10053235.05
      2836497.51     10053228.54
#Sta/Elev= 30
  3741.6 1431.48  3837.2 1429.54  3896.6 1426.79  3931.8 1425.76  3948.5 1426.51
  3993.0 1425.88  4148.8 1422.83  4176.6 1421.12  4260.0 1419.28  4282.3 1417.51
  4410.2 1419.04  4482.6 1421.41  4699.8 1422.31  4819.8 1421.17  4859.8 1418.98
  4919.8 1418.13  4979.8 1415.72  4999.8 1411.71  5006.8 1411.13  5009.6 1410.63
  5012.8 1411.13  5029.8 1415.37  5039.8 1416.45  5099.8 1416.69  5199.8 1419.08
  5219.8 1421.89  5259.8 1431.94  5279.8 1434.58  5319.8 1436.46  5508.9 1441.94
#Mann=4,-1,0
  3741.6     0.1       0  3896.6    0.05       0  5006.8    0.04       0
  5012.8    0.05       0
Bank Sta=5006.8,5012.8
Exp/Cntr=0.3,0.1

Type RM Length L Ch R = 1,3089,314,314,314
BEGIN DESCRIPTION:
Mapping XS fe8cdd60
END DESCRIPTION:
XS GIS Cut Line= 3
      2835205.34     10053672.33      2835925.87     10053344.62
      2836484.61     10053329.46
#Sta/Elev= 30
  4164.9 1429.71  4183.4 1429.40  4248.4 1427.27  4262.3 1427.69  4633.9 1419.68
  4640.7 1418.80  4656.9 1418.93  4662.7 1419.85  4703.1 1417.12  4757.4 1415.80
  4823.9 1414.44  4921.6 1415.15  4950.2 1416.12  4979.1 1415.09  4996.1 1413.52
  4998.8 1413.02  5002.1 1413.52  5009.1 1415.30  5019.1 1416.32  5089.1 1415.82
  5173.8 1416.82  5199.1 1421.01  5239.2 1433.95  5269.2 1437.72  5289.2 1437.77
  5319.2 1435.03  5369.2 1436.47  5399.2 1440.67  5429.2 1439.59  5515.4 1438.95
#Mann=6,-1,0
  4164.9     0.1       0  4183.4    0.05       0  4262.3     0.1       0
  4757.4    0.05       0  4996.1    0.04       0  5002.1    0.05       0
Bank Sta=4996.1,5002.1
Exp/Cntr=0.3,0.1

Type RM Length L Ch R = 1,2775,126,126,126
BEGIN DESCRIPTION:
UNT006 IN SNOGR 6.0
END DESCRIPTION:
XS GIS Cut Line= 3
      2835398.54     10053866.30      2835770.07     10053626.72
      2836332.55     10053467.00
#Sta/Elev= 30
  4466.1 1428.56  4602.0 1425.93  4684.6 1425.28  4720.9 1424.23  4736.1 1421.94
  4757.2 1421.89  4763.5 1422.58  4799.4 1421.93  4850.9 1420.48  4881.3 1418.40
  4910.1 1417.85  4935.0 1417.98  4974.0 1415.35  4986.7 1413.49  4989.4 1412.99
  4992.7 1413.49  5052.2 1415.24  5124.1 1415.14  5239.2 1414.56  5260.0 1415.07
  5266.0 1416.47  5271.2 1416.34  5280.7 1418.84  5299.9 1425.88  5305.1 1424.82
  5311.9 1428.13  5339.0 1433.25  5378.1 1434.38  5436.7 1432.22  5492.9 1433.06
#Mann=6,-1,0
  4466.1    0.05       0  4602.0     0.1       0  4910.1    0.05       0
  4986.7    0.04       0  4992.7    0.05       0  5124.1     0.1       0
Bank Sta=4986.7,4992.7
Exp/Cntr=0.3,0.1

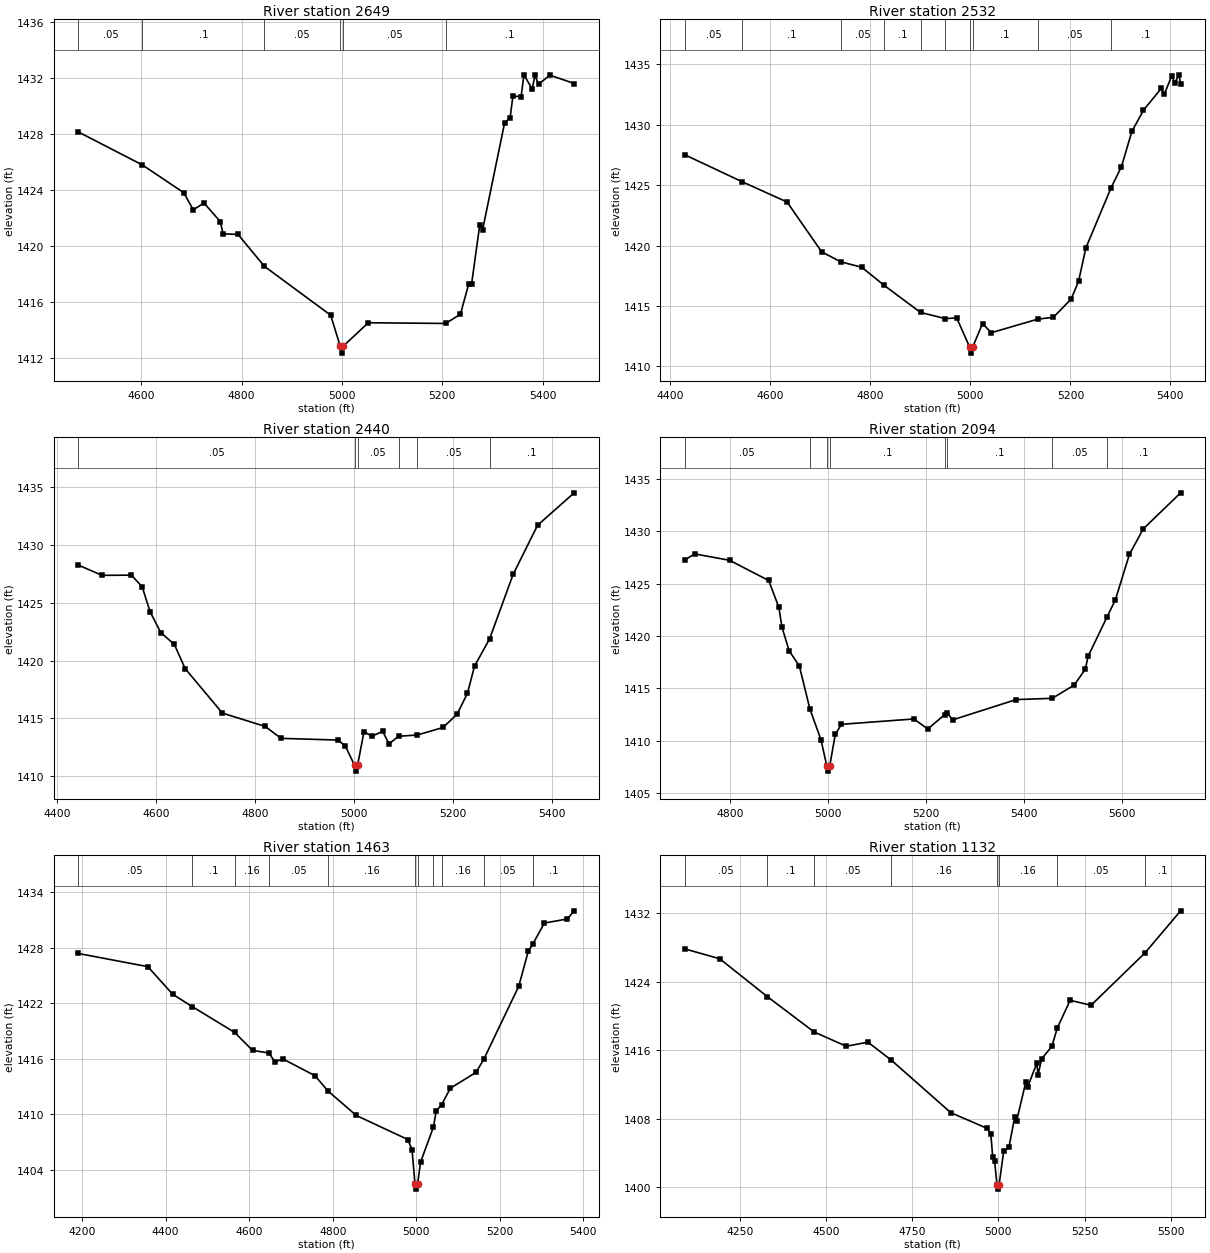
Type RM Length L Ch R = 1,2649,117,117,117
BEGIN DESCRIPTION:
Mapping XS b10b3d68
END DESCRIPTION:
XS GIS Cut Line= 3
      2835405.47     10053914.92      2835853.40     10053737.83
      2836301.31     10053501.72
#Sta/Elev= 30
  4474.8 1428.12  4602.5 1425.76  4684.9 1423.78  4703.8 1422.56  4725.3 1423.04
  4757.6 1421.72  4763.3 1420.84  4793.0 1420.80  4845.6 1418.52  4977.6 1415.03
  4996.6 1412.82  4999.3 1412.32  5002.6 1412.82  5052.6 1414.49  5206.8 1414.44
  5236.2 1415.10  5252.6 1417.25  5258.3 1417.23  5274.6 1421.46  5280.3 1421.12
  5324.3 1428.79  5335.1 1429.10  5340.7 1430.68  5357.1 1430.64  5362.7 1432.20
  5379.1 1431.19  5384.8 1432.16  5391.8 1431.52  5414.4 1432.18  5462.8 1431.58
#Mann=6,-1,0
  4474.8    0.05       0  4602.5     0.1       0  4845.6    0.05       0
  4996.6    0.04       0  5002.6    0.05       0  5206.8     0.1       0
Bank Sta=4996.6,5002.6
Exp/Cntr=0.3,0.1

Type RM Length L Ch R = 1,2532,92,92,92
BEGIN DESCRIPTION:
Mapping XS f9a2fcbb
END DESCRIPTION:
XS GIS Cut Line= 3
      2835447.15     10054043.39      2836065.21     10053762.13
      2836318.21     10053578.44
#Sta/Elev= 30
  4428.8 1427.52  4543.9 1425.28  4633.3 1423.61  4702.5 1419.49  4740.6 1418.66
  4782.7 1418.21  4827.5 1416.71  4900.3 1414.47  4949.4 1413.96  4972.6 1414.01
  4998.6 1411.60  5001.3 1411.10  5004.6 1411.60  5024.3 1413.55  5041.8 1412.79
  5134.4 1413.91  5166.1 1414.07  5201.6 1415.58  5216.3 1417.04  5231.0 1419.81
  5281.4 1424.79  5302.1 1426.53  5323.0 1429.45  5346.2 1431.21  5381.8 1433.02
  5387.9 1432.53  5402.6 1434.05  5408.8 1433.48  5417.3 1434.14  5420.5 1433.37
#Mann=10,-1,0
  4428.8    0.05       0  4543.9     0.1       0  4740.6    0.05       0
  4827.5     0.1       0  4900.3    0.05       0  4949.4     0.1       0
  4998.6    0.07       0  5004.6     0.1       0  5134.4    0.05       0
  5281.4     0.1       0
Bank Sta=4998.6,5004.6
Exp/Cntr=0.3,0.1

Type RM Length L Ch R = 1,2440,346,346,346
BEGIN DESCRIPTION:
UNT006 IN SNOGR 5.0
END DESCRIPTION:
XS GIS Cut Line= 3
      2835520.06     10054161.45      2836127.71     10053821.16
      2836324.58     10053586.30
#Sta/Elev= 30
  4442.3 1428.27  4490.4 1427.38  4549.8 1427.40  4571.5 1426.38  4587.4 1424.23
  4609.1 1422.42  4636.5 1421.40  4658.2 1419.31  4733.6 1415.45  4820.3 1414.29
  4852.3 1413.26  4967.7 1413.11  4982.4 1412.59  5001.1 1410.92  5003.9 1410.42
  5007.1 1410.92  5020.1 1413.84  5036.1 1413.44  5057.8 1413.87  5070.8 1412.79
  5090.3 1413.44  5128.0 1413.55  5179.9 1414.20  5208.6 1415.36  5229.4 1417.17
  5243.7 1419.52  5274.2 1421.88  5321.8 1427.47  5371.2 1431.72  5445.2 1434.53
#Mann=6,-1,0
  4442.3    0.05       0  5001.1    0.04       0  5007.1    0.05       0
  5090.3     0.1       0  5128.0    0.05       0  5274.2     0.1       0
Bank Sta=5001.1,5007.1
Exp/Cntr=0.3,0.1

Type RM Length L Ch R = 1,2094,631,631,631
BEGIN DESCRIPTION:
UNT006 IN SNOGR 4.0
END DESCRIPTION:
XS GIS Cut Line= 3
      2835717.55     10054390.62      2836060.42     10054147.57
      2836318.66     10053613.73
#Sta/Elev= 30
  4707.1 1427.25  4727.1 1427.83  4798.5 1427.22  4878.5 1425.29  4899.4 1422.72
  4905.5 1420.86  4920.3 1418.58  4941.2 1417.13  4962.6 1413.05  4985.5 1410.06
  4997.3 1407.59  5000.1 1407.09  5003.3 1407.59  5014.7 1410.61  5027.3 1411.56
  5175.4 1412.07  5203.6 1411.11  5238.5 1412.49  5243.9 1412.62  5254.3 1411.98
  5384.3 1413.92  5458.0 1414.04  5502.8 1415.30  5525.4 1416.80  5531.6 1418.08
  5569.5 1421.76  5587.1 1423.45  5615.7 1427.78  5643.9 1430.21  5720.4 1433.66
#Mann=8,-1,0
  4707.1    0.05       0  4962.6     0.1       0  4997.3    0.07       0
  5003.3     0.1       0  5238.5    0.16       0  5243.9     0.1       0
  5458.0    0.05       0  5569.5     0.1       0
Bank Sta=4997.3,5003.3
Exp/Cntr=0.3,0.1

Type RM Length L Ch R = 1,1463,331,331,331
BEGIN DESCRIPTION:
UNT006 IN SNOGR 3.0
END DESCRIPTION:
XS GIS Cut Line= 4
      2835871.58     10054481.79      2836368.58     10054282.12
      2836307.81     10053965.28      2836377.25     10053644.12
#Sta/Elev= 30
  4191.0 1427.36  4357.4 1425.94  4416.6 1422.97  4463.7 1421.63  4565.1 1418.85
  4607.9 1416.91  4647.1 1416.63  4661.8 1415.66  4680.0 1416.00  4757.2 1414.19
  4788.9 1412.52  4856.1 1409.90  4979.5 1407.30  4989.7 1406.22  4996.9 1402.45
  4999.6 1401.95  5002.9 1402.45  5010.1 1404.85  5041.0 1408.65  5047.5 1410.36
  5060.4 1411.05  5081.5 1412.83  5142.9 1414.54  5161.7 1415.97  5245.2 1423.83
  5268.0 1427.60  5278.6 1428.37  5306.6 1430.64  5361.4 1431.08  5377.8 1431.96
#Mann=11,-1,0
  4191.0    0.05       0  4463.7     0.1       0  4565.1    0.16       0
  4647.1    0.05       0  4788.9    0.16       0  4996.9    0.07       0
  5002.9    0.16       0  5041.0     0.1       0  5060.4    0.16       0
  5161.7    0.05       0  5278.6     0.1       0
Bank Sta=4996.9,5002.9
Exp/Cntr=0.3,0.1

Type RM Length L Ch R = 1,1132,0,0,0
BEGIN DESCRIPTION:
UNT006 IN SNOGR 2.0
END DESCRIPTION:
XS GIS Cut Line= 4
      2835936.74     10054525.17      2836574.74     10054227.87
      2836674.57     10053921.88      2836566.06     10053524.76
#Sta/Elev= 30
  4090.9 1427.86  4192.1 1426.71  4330.0 1422.29  4465.9 1418.15  4558.8 1416.49
  4621.9 1416.96  4689.3 1414.87  4862.2 1408.72  4967.4 1406.89  4977.9 1406.26
  4983.7 1403.49  4988.9 1403.10  4996.0 1400.29  4998.7 1399.79  5002.0 1400.29
  5015.6 1404.27  5030.5 1404.66  5047.5 1408.26  5052.7 1407.74  5079.4 1412.29
  5084.6 1411.70  5111.3 1414.50  5114.9 1413.13  5125.5 1415.03  5154.9 1416.46
  5170.9 1418.63  5208.0 1421.85  5268.8 1421.28  5424.7 1427.38  5528.3 1432.31
#Mann=8,-1,0
  4090.9    0.05       0  4330.0     0.1       0  4465.9    0.05       0
  4689.3    0.16       0  4996.0    0.07       0  5002.0    0.16       0
  5170.9    0.05       0  5424.7     0.1       0
Bank Sta=4996,5002
Exp/Cntr=0.3,0.1

Chan Stop Cuts=-1