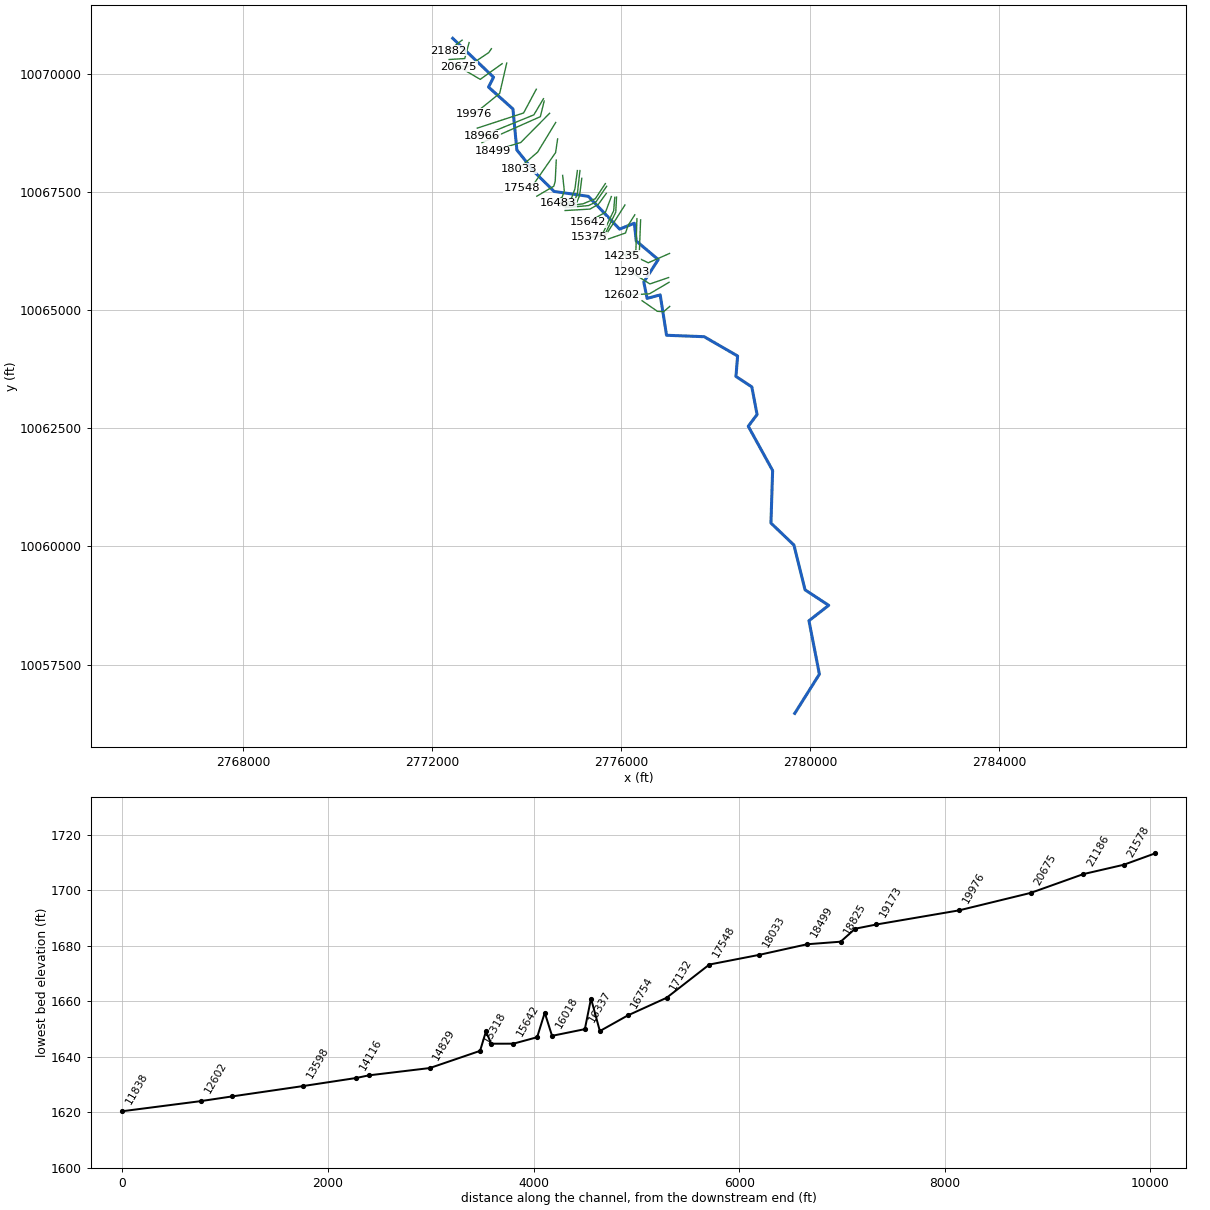
--- UNT007 IN NNOGR.prj (project) ---

Proj Title=UNT007 IN NNOGR Base Level Engineering
Current Plan=p01
Default Exp/Contr=0.3,0.1
English Units
Geom File=g01
Flow File=f01
Plan File=p01
Y Axis Title=Elevation
X Axis Title(PF)=Main Channel Distance
X Axis Title(XS)=Station
BEGIN DESCRIPTION:
UNT007 IN NNOGR
END DESCRIPTION:
DSS Export Rating Curves= 0
DSS Export Rating Curve Sorted= 0
DSS Export Volume Flow Curves= 0
DXF OffsetX= 0
DXF OffsetY= 0
DXF ScaleX= 1
DXF ScaleY= 10

--- UNT007 IN NNOGR.p01 (plan) ---

Plan Title=Multiple Run
Short Identifier=Multiple
Geom File=g01
Flow File=f01
Subcritical Flow
K Sum by GR= 0
Std Step Tol= 0.01
Critical Tol= 0.01
Num of Std Step Trials= 20
Max Error Tol= 0.3
Flow Tol Ratio= 0.001
Split Flow NTrial= 30
Split Flow Tol= 0.02
Split Flow Ratio= 0.02
Log Output Level= 0
Friction Slope Method= 1
Unsteady Friction Slope Method= 2
Unsteady Bridges Friction Slope Method= 1
Parabolic Critical Depth
Global Vel Dist=  1 , 1 , 1
Global Log Level= 0
CheckData=True
Encroach Param= -1, 0, 0, 0
BEGIN DESCRIPTION:
Multiple Run
END DESCRIPTION:

--- UNT007 IN NNOGR.f01 (steady flow) ---

Flow Title=Multiple
Number of Profiles=7
Profile Names=10-year,25-year,50-year,1pct_min,100-year,1pct_plu,500-year
River Rch & RM= UNT007 IN NNOGR,Reach-1,21882
     847    1232    1569    1463    1978    2675    3157
River Rch & RM= UNT007 IN NNOGR,Reach-1,12903
    1053    1538    1962    1829    2474    3346    3954
Boundary for River Rch & Prof#=UNT007 IN NNOGR,Reach-1,1
Up Type=0
Dn Type=3
Dn Slope=0.005
Boundary for River Rch & Prof#=UNT007 IN NNOGR,Reach-1,2
Up Type=0
Dn Type=3
Dn Slope=0.005
Boundary for River Rch & Prof#=UNT007 IN NNOGR,Reach-1,3
Up Type=0
Dn Type=3
Dn Slope=0.005
Boundary for River Rch & Prof#=UNT007 IN NNOGR,Reach-1,4
Up Type=0
Dn Type=3
Dn Slope=0.005
Boundary for River Rch & Prof#=UNT007 IN NNOGR,Reach-1,5
Up Type=0
Dn Type=3
Dn Slope=0.005
Boundary for River Rch & Prof#=UNT007 IN NNOGR,Reach-1,6
Up Type=0
Dn Type=3
Dn Slope=0.005
Boundary for River Rch & Prof#=UNT007 IN NNOGR,Reach-1,7
Up Type=0
Dn Type=3
Dn Slope=0.005

--- UNT007 IN NNOGR.g01 (geometry) ---

Geom Title=Existing Conditions
Program Version=4.10

River Reach=UNT007 IN NNOGR ,Reach-1
Reach XY= 30
      2772433.47     10070758.73      2773297.57     10069935.34
      2773191.32     10069726.22      2773707.99      10069263.2
       2773791.4     10068394.86      2774177.57     10067913.86
      2774580.02      10067516.8      2775304.93     10067413.44
       2775966.2     10066719.16      2776278.55     10066843.68
      2776318.91      10066467.7      2776785.05     10066074.75
      2776478.71     10065598.12      2776549.24     10065252.59
      2776826.58     10065325.77      2776960.83     10064471.38
      2777757.38      10064441.1      2778465.29     10064032.49
      2778430.47     10063598.99      2778766.47     10063378.01
      2778877.47     10062793.19      2778691.14      10062544.9
      2779206.75     10061607.94      2779171.39     10060494.95
      2779658.34     10060028.69      2779893.22     10059080.74
      2780394.71      10058752.8      2779976.14     10058426.97
      2780197.15     10057295.04      2779675.37     10056465.27

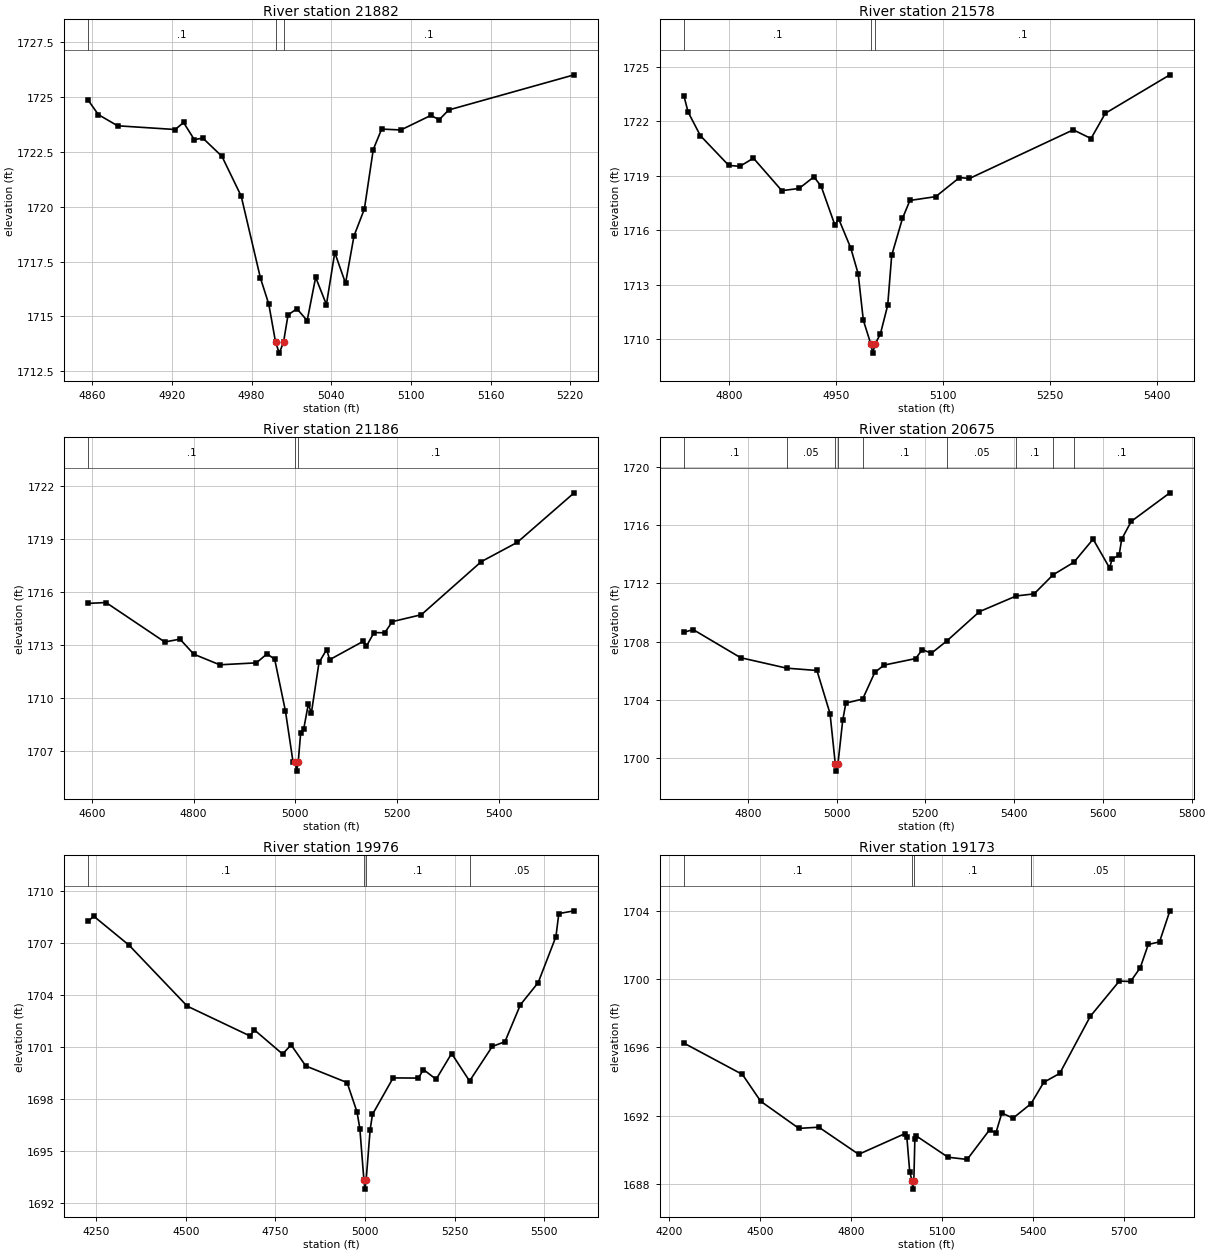
Type RM Length L Ch R = 1 ,21882   ,304,304,304
BEGIN DESCRIPTION:
UNT007 IN NNOGR 44.0
END DESCRIPTION:
XS GIS Cut Line= 2
      2772632.31     10070721.33      2772344.07     10070495.61
#Sta/Elev= 30
  4856.9 1724.85  4864.6 1724.19  4879.1 1723.68  4922.5 1723.51  4928.8 1723.83
  4936.9 1723.05  4943.3 1723.12  4957.7 1722.29  4972.2 1720.48  4986.7 1716.75
    4993 1715.56  4998.1 1713.83  5000.9 1713.33  5004.1 1713.83  5007.5 1715.07
  5014.2 1715.35  5021.9 1714.81  5028.3 1716.78  5036.4 1715.54  5042.7 1717.91
  5050.8 1716.51  5057.2 1718.67    5065 1719.89  5071.7  1722.6    5078 1723.53
  5092.5 1723.49    5115 1724.15  5121.4 1723.96  5128.5  1724.4    5223    1726
#Mann= 3 ,-1 , 0
  4856.9      .1       0  4998.1     .07       0  5004.1      .1       0
Bank Sta=4998.1,5004.1
XS Rating Curve= 0 ,0
Exp/Cntr=0.3,0.1

Type RM Length L Ch R = 1 ,21578   ,392,392,392
BEGIN DESCRIPTION:
UNT007 IN NNOGR 43.0
END DESCRIPTION:
XS GIS Cut Line= 3
        2772780.     10070669.54        2772688.     10070331.04
      2772358.14     10070310.21
#Sta/Elev= 30
  4736.8 1723.42  4742.8 1722.51    4760 1721.21  4799.8 1719.57  4815.4 1719.52
  4834.4 1719.97  4874.2 1718.18  4898.3  1718.3  4919.2 1718.94  4929.4 1718.41
  4948.6 1716.28  4953.8 1716.63  4970.8 1715.02  4981.2  1713.6  4988.4 1711.05
  4998.9 1709.73  5001.6 1709.23  5004.9 1709.73  5012.3 1710.28  5022.6 1711.87
  5028.2 1714.62  5043.3 1716.65  5053.7 1717.64  5089.9 1717.85  5123.2  1718.9
  5137.2 1718.85  5282.7 1721.53  5307.6 1721.05  5327.6 1722.44  5418.1 1724.56
#Mann= 3 ,-1 , 0
  4736.8      .1       0  4998.9     .07       0  5004.9      .1       0
Bank Sta=4998.9,5004.9
XS Rating Curve= 0 ,0
Exp/Cntr=0.3,0.1

Type RM Length L Ch R = 1 ,21186   ,511,511,511
BEGIN DESCRIPTION:
UNT007 IN NNOGR 42.0
END DESCRIPTION:
XS GIS Cut Line= 4
      2773252.25      10070539.4      2773194.95     10070456.04
       2772731.4     10070145.28      2772448.45     10070232.07
#Sta/Elev= 30
  4592.6 1715.35  4627.8  1715.4  4743.2 1713.17  4773.2 1713.33  4800.3 1712.48
  4851.3 1711.88  4923.3 1711.99  4944.4  1712.5  4959.3 1712.19  4980.4 1709.27
  4995.4 1706.38  4999.5 1706.37  5002.3 1705.87  5005.5 1706.37  5010.4 1708.04
  5016.4 1708.26  5025.4 1709.66  5031.4 1709.16  5046.4 1712.01  5061.4 1712.74
  5067.4 1712.17  5133.4 1713.21  5139.4 1712.92  5154.4  1713.7  5175.5 1713.69
  5190.5 1714.32  5247.5 1714.71  5365.3 1717.71    5436  1718.8  5547.8  1721.6
#Mann= 3 ,-1 , 0
  4592.6      .1       0  4999.5     .07       0  5005.5      .1       0
Bank Sta=4999.5,5005.5
XS Rating Curve= 0 ,0
Exp/Cntr=0.3,0.1

Type RM Length L Ch R = 1 ,20675   ,699,699,699
BEGIN DESCRIPTION:
UNT007 IN NNOGR 41.0
END DESCRIPTION:
XS GIS Cut Line= 3
      2773479.64     10070221.64      2773016.13     10069890.07
      2772563.21     10070155.57
#Sta/Elev= 30
    4656 1708.63    4677 1708.82  4783.9 1706.89  4887.7 1706.17  4955.9 1706.01
  4985.4 1703.05  4997.2  1699.6  4999.9  1699.1  5003.2  1699.6    5014  1702.6
    5021 1703.77  5058.9 1704.05  5086.2 1705.88    5107 1706.38  5178.3 1706.83
    5193 1707.44  5213.9  1707.2  5248.9 1708.05  5321.9 1710.05  5404.9 1711.13
    5445 1711.27  5487.8 1712.58  5534.6 1713.44    5578 1715.03  5615.1 1713.05
  5620.9 1713.67  5636.6 1713.93  5642.4 1715.03  5663.9 1716.25  5750.9 1718.21
#Mann= 9 ,-1 , 0
    4656      .1       0  4887.7     .05       0  4997.2    .035       0
  5003.2     .05       0  5058.9      .1       0  5248.9     .05       0
  5404.9      .1       0  5487.8     .05       0  5534.6      .1       0
Bank Sta=4997.2,5003.2
XS Rating Curve= 0 ,0
Exp/Cntr=0.3,0.1

Type RM Length L Ch R = 1 ,19976   ,803,803,803
BEGIN DESCRIPTION:
UNT007 IN NNOGR 40.0
END DESCRIPTION:
XS GIS Cut Line= 3
      2773576.73     10070235.18      2773427.43     10069592.85
      2772885.79     10069155.37
#Sta/Elev= 30
  4227.5 1708.26  4243.2 1708.56  4341.9 1706.88    4504 1703.36  4679.6 1701.63
    4691 1701.99    4770 1700.59  4793.7 1701.12  4834.7  1699.9  4949.9 1698.94
  4977.6 1697.24  4985.5 1696.27  4996.9 1693.28  4999.7 1692.78  5002.9 1693.28
  5014.2 1696.22  5020.7  1697.1  5078.3 1699.21  5148.6  1699.2    5163 1699.69
  5198.2 1699.13  5241.4 1700.62  5291.5 1699.03  5354.9 1701.03  5390.1  1701.3
  5433.3 1703.44  5482.9 1704.72  5532.4 1707.38  5540.4 1708.71  5583.2 1708.87
#Mann= 4 ,-1 , 0
  4227.5      .1       0  4996.9     .07       0  5002.9      .1       0
  5291.5     .05       0
Bank Sta=4996.9,5002.9
XS Rating Curve= 0 ,0
Exp/Cntr=0.3,0.1

Type RM Length L Ch R = 1 ,19173   ,207,207,207
BEGIN DESCRIPTION:
UNT007 IN NNOGR 39.0
END DESCRIPTION:
XS GIS Cut Line= 3
      2774203.09     10069682.06      2773933.97     10069178.54
      2772953.23     10068857.42
#Sta/Elev= 30
  4249.4 1696.25  4442.7 1694.41  4502.9 1692.84  4628.9 1691.25  4694.7 1691.32
  4826.1 1689.73  4979.5 1690.95  4984.8 1690.76  4994.5 1688.69    5002 1688.19
  5004.7 1687.69    5008 1688.19  5011.4 1690.65  5016.7  1690.8  5120.7 1689.56
  5183.9 1689.43  5257.5 1691.16  5278.6 1690.98  5298.1 1692.15  5335.2 1691.85
  5394.6  1692.7  5436.4 1693.95    5489 1694.47    5590 1697.82  5685.5 1699.88
  5722.7 1699.86  5754.5 1700.66  5781.1 1702.03  5818.2 1702.18  5852.3    1704
#Mann= 4 ,-1 , 0
  4249.4      .1       0    5002     .07       0    5008      .1       0
  5394.6     .05       0
Bank Sta=5002,5008
XS Rating Curve= 0 ,0
Exp/Cntr=0.3,0.1

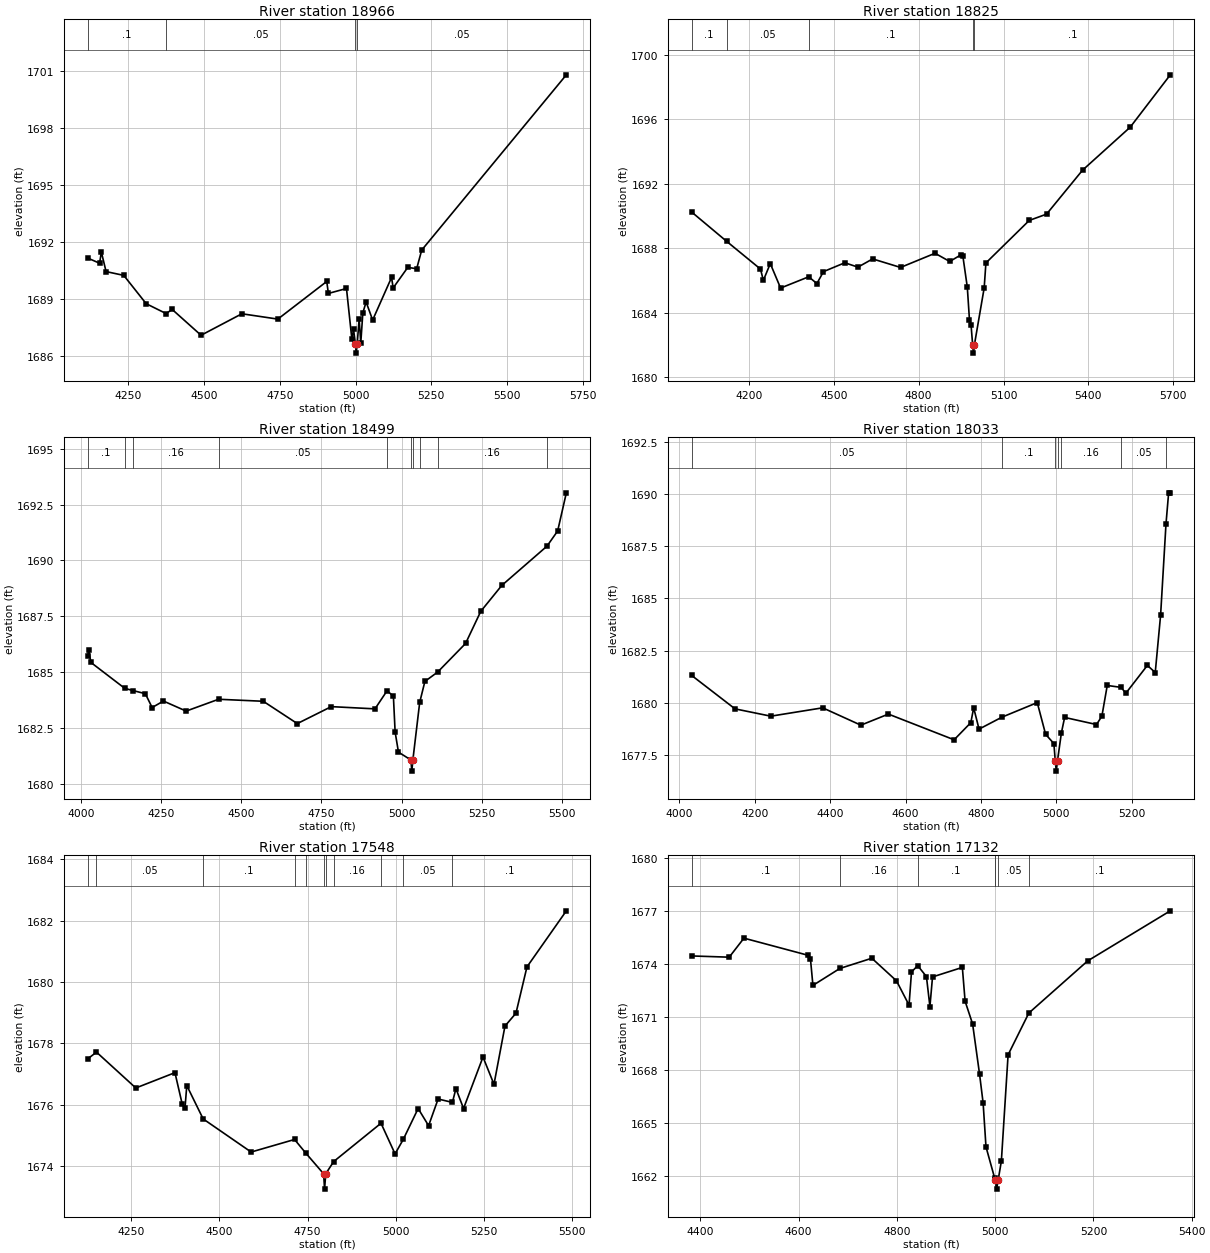
Type RM Length L Ch R = 1 ,18966   ,141,141,141
BEGIN DESCRIPTION:
Mapping XS 3a5122b4
END DESCRIPTION:
XS GIS Cut Line= 3
      2774354.68     10069480.36      2774151.54     10069138.33
      2773056.03     10068692.14
#Sta/Elev= 30
  4115.4 1691.16  4154.6 1690.89  4160.4 1691.48    4176 1690.45  4234.4 1690.25
  4308.5 1688.76  4374.4 1688.24  4394.2 1688.46  4489.7  1687.1  4624.5 1688.23
  4743.3 1687.95  4904.8 1689.93  4910.2  1689.3    4970 1689.56  4987.8 1686.89
  4993.2 1687.41  4999.4 1686.66  5002.2 1686.16  5005.4 1686.66  5011.8 1687.94
  5017.2  1686.7    5024 1688.28  5034.8 1688.85  5056.4  1687.9  5118.8 1690.14
  5124.2 1689.59  5172.4 1690.67  5201.8  1690.6  5218.4 1691.58  5696.1  1700.8
#Mann= 4 ,-1 , 0
  4115.4      .1       0  4374.4     .05       0  4999.4     .04       0
  5005.4     .05       0
Bank Sta=4999.4,5005.4
XS Rating Curve= 0 ,0
Exp/Cntr=0.3,0.1

Type RM Length L Ch R = 1 ,18825   ,326,326,326
BEGIN DESCRIPTION:
Mapping XS a7dea1d5
END DESCRIPTION:
XS GIS Cut Line= 3
      2774369.37     10069429.84      2774288.45     10069100.14
      2773052.99     10068551.71
#Sta/Elev= 30
  3998.1 1690.24  4121.8 1688.42  4241.2  1686.7  4251.5    1686  4275.9 1687.04
  4312.3 1685.52  4411.7 1686.22  4440.6  1685.8  4463.8 1686.54  4539.1 1687.09
  4585.6 1686.82  4637.6 1687.33  4736.2  1686.8    4858 1687.68    4910 1687.17
  4950.3 1687.59  4956.5 1687.49  4972.1 1685.57  4979.7 1683.54  4985.2 1683.25
    4991 1681.98  4993.8 1681.48    4997 1681.98  5031.7 1685.53  5037.8 1687.08
    5191 1689.72  5252.1 1690.11  5379.3 1692.84  5547.7 1695.51  5689.3 1698.76
#Mann= 5 ,-1 , 0
  3998.1      .1       0  4121.8     .05       0  4411.7      .1       0
    4991     .07       0    4997      .1       0
Bank Sta=4991,4997
XS Rating Curve= 0 ,0
Exp/Cntr=0.3,0.1

Type RM Length L Ch R = 1 ,18499   ,466,466,466
BEGIN DESCRIPTION:
UNT007 IN NNOGR 38.0
END DESCRIPTION:
XS GIS Cut Line= 3
      2774484.88     10069171.32      2773873.77     10068553.26
       2773278.1     10068370.62
#Sta/Elev= 30
  4021.4 1685.71  4024.2    1686  4031.3 1685.43  4136.8 1684.27  4162.5 1684.17
    4201 1684.03  4222.2 1683.41  4257.5  1683.7  4328.3 1683.25  4429.4 1683.78
  4568.7 1683.69  4674.8 1682.69  4780.8 1683.45    4917 1683.35  4954.6 1684.16
  4974.4 1683.92  4979.8 1682.31  4990.2 1681.41  5029.1 1681.06  5031.8 1680.56
  5035.1 1681.06  5056.4 1683.64  5072.6 1684.58  5112.5    1685  5199.4 1686.28
  5246.8 1687.72  5312.3 1688.88  5453.2 1690.64  5486.5 1691.32  5513.6 1693.03
#Mann= 10 ,-1 , 0
  4021.4      .1       0  4136.8     .05       0  4162.5     .16       0
  4429.4     .05       0  4954.6     .16       0  5029.1     .07       0
  5035.1     .16       0  5056.4     .05       0  5112.5     .16       0
  5453.2     .05       0
Bank Sta=5029.1,5035.1
XS Rating Curve= 0 ,0
Exp/Cntr=0.3,0.1

Type RM Length L Ch R = 1 ,18033   ,485,485,485
BEGIN DESCRIPTION:
UNT007 IN NNOGR 37.0
END DESCRIPTION:
XS GIS Cut Line= 3
      2774613.34     10068976.85       2774231.4     10068350.14
      2773826.88     10067999.44
#Sta/Elev= 30
  4032.9 1681.31  4147.9 1679.71  4242.8 1679.36  4380.3 1679.76  4481.6 1678.93
  4554.6 1679.46  4728.9 1678.23  4773.2 1679.05  4780.8 1679.76    4795 1678.74
  4855.4 1679.31  4949.4 1680.01  4971.6 1678.49  4993.5 1678.05  4997.1 1677.23
  4999.9 1676.73  5003.1 1677.23  5013.5 1678.57    5022  1679.3  5106.5 1678.96
  5120.8 1679.36    5135 1680.83  5171.5 1680.74  5184.4 1680.46  5241.4 1681.79
  5262.3 1681.45  5276.5 1684.19  5290.8 1688.56  5297.8 1690.05  5302.2 1690.05
#Mann= 7 ,-1 , 0
  4032.9     .05       0  4855.4      .1       0  4997.1     .07       0
  5003.1      .1       0  5013.5     .16       0  5171.5     .05       0
  5290.8      .1       0
Bank Sta=4997.1,5003.1
XS Rating Curve= 0 ,0
Exp/Cntr=0.3,0.1

Type RM Length L Ch R = 1 ,17548   ,416,416,416
BEGIN DESCRIPTION:
UNT007 IN NNOGR 36.0
END DESCRIPTION:
XS GIS Cut Line= 4
      2774654.24     10068628.72      2774611.61     10068339.72
      2774151.54     10067678.26      2773905.06     10067593.21
#Sta/Elev= 30
    4126 1677.49  4150.9 1677.71  4262.5 1676.54  4373.6 1677.04  4393.9 1676.03
  4402.2  1675.9  4407.2 1676.62  4453.7 1675.53  4589.9 1674.45  4713.1 1674.86
  4745.4 1674.41  4795.6 1673.74  4798.3 1673.24  4801.6 1673.74  4824.2 1674.14
  4958.5 1675.39  4998.4 1674.39  5021.6 1674.86  5063.9 1675.87  5093.6 1675.31
  5120.6 1676.18  5161.2 1676.07  5171.2 1676.52  5192.8 1675.87    5248 1677.55
  5279.2 1676.66  5310.4 1678.56  5341.6 1678.98  5372.8 1680.49  5484.6 1682.32
#Mann= 11 ,-1 , 0
    4126     .16       0  4150.9     .05       0  4453.7      .1       0
  4713.1     .16       0  4745.4      .1       0  4795.6     .07       0
  4801.6      .1       0  4824.2     .16       0  4958.5      .1       0
  5021.6     .05       0  5161.2      .1       0
Bank Sta=4795.6,4801.6
XS Rating Curve= 0 ,0
Exp/Cntr=0.3,0.1

Type RM Length L Ch R = 1 ,17132   ,378,378,378
BEGIN DESCRIPTION:
Mapping XS d6df090b
END DESCRIPTION:
XS GIS Cut Line= 4
       2774625.5     10068180.01      2774602.93     10067726.87
      2774573.42     10067627.92      2774214.05     10067416.11
#Sta/Elev= 30
  4382.4 1674.47  4458.8  1674.4  4488.8 1675.48    4619 1674.51  4624.2 1674.29
  4629.2  1672.8    4684 1673.76  4749.1 1674.34  4799.2 1673.06  4824.8 1671.68
  4829.8 1673.56  4842.4 1673.92  4860.2  1673.3  4867.3  1671.6  4872.6 1673.28
  4933.3 1673.82  4938.9  1671.9  4954.2 1670.61  4968.3 1667.77  4975.6 1666.12
  4981.4 1663.64    4999 1661.87  5000.1 1661.74  5002.9 1661.24  5006.1 1661.74
  5012.7 1662.83  5026.4 1668.86  5068.6 1671.23  5188.4 1674.19  5356.5 1677.03
#Mann= 7 ,-1 , 0
  4382.4      .1       0    4684     .16       0  4842.4      .1       0
    4999     .05       0  5000.1    .035       0  5006.1     .05       0
  5068.6      .1       0
Bank Sta=5000.1,5006.1
XS Rating Curve= 0 ,0
Exp/Cntr=0.3,0.1

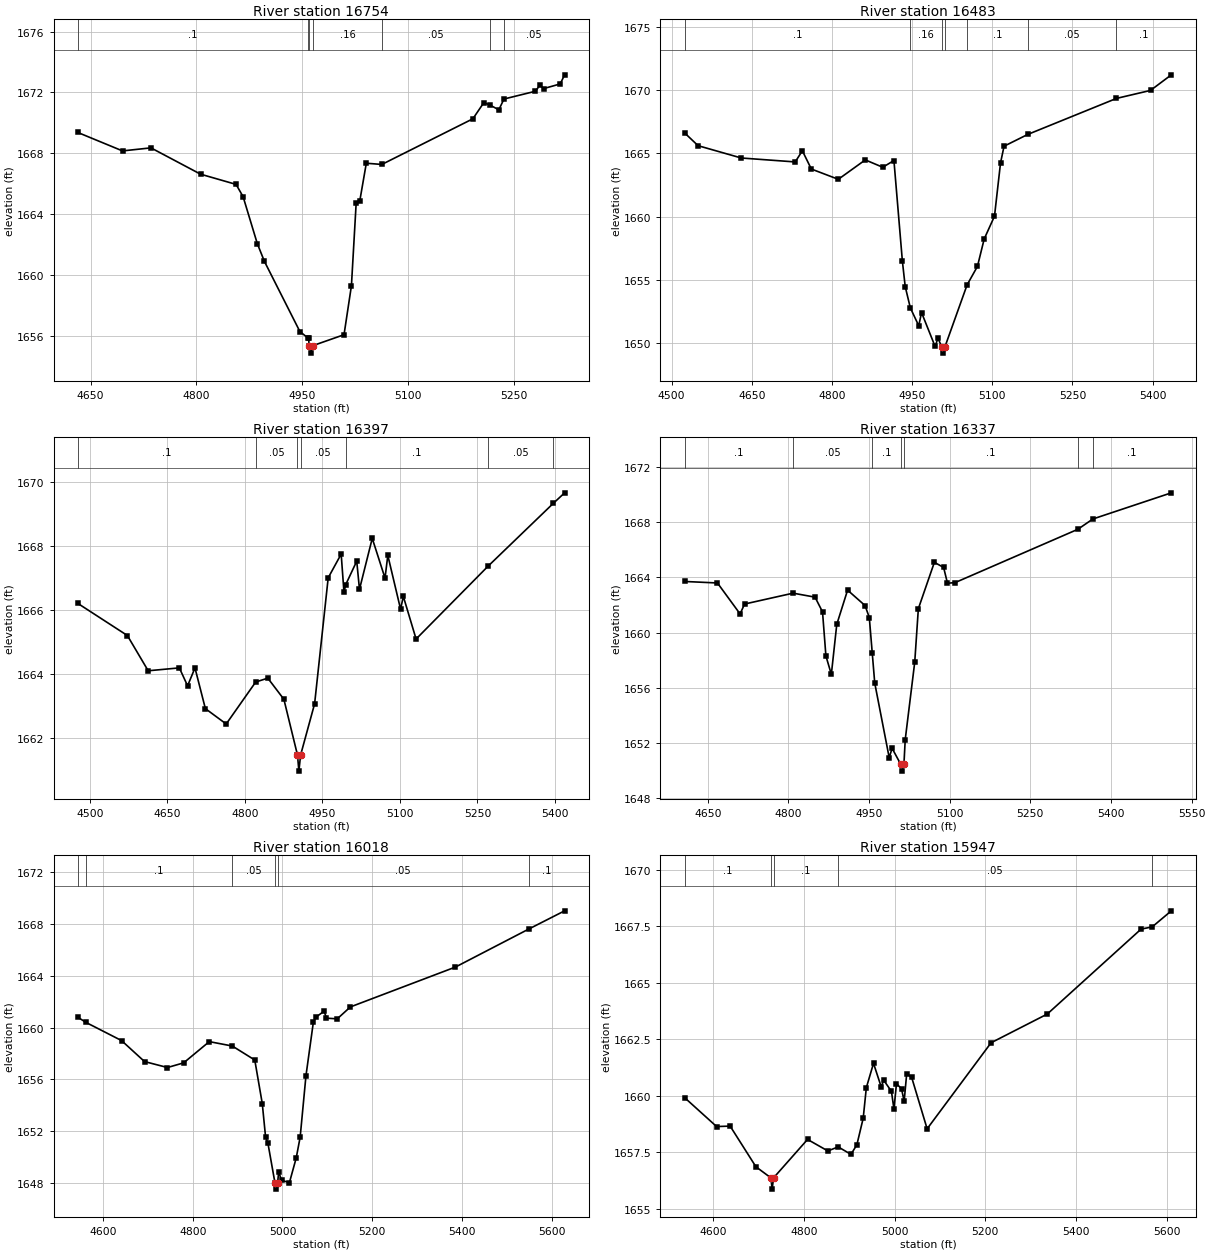
Type RM Length L Ch R = 1 ,16754   ,271,271,271
BEGIN DESCRIPTION:
UNT007 IN NNOGR 35.0
END DESCRIPTION:
XS GIS Cut Line= 4
      2774760.77      10067856.7      2774795.49     10067533.82
      2774750.35     10067394.93      2774563.12     10067280.52
#Sta/Elev= 30
  4632.1 1669.37  4695.4 1668.16  4735.7 1668.36  4806.1 1666.63  4856.4 1665.96
  4866.4 1665.15  4886.5 1662.07  4896.6  1660.9  4946.9 1656.29  4958.2 1655.87
  4959.5 1655.87  4959.8 1655.37  4962.5 1654.87  4965.8 1655.37  5009.5 1656.08
    5020  1659.3  5026.7 1664.72  5031.9 1664.89  5041.1 1667.35  5063.1 1667.27
  5192.2 1670.27  5207.7 1671.33  5215.8 1671.19    5229 1670.86  5236.3 1671.57
  5280.9 1672.08  5287.1 1672.47  5292.9 1672.26    5316 1672.56  5322.3 1673.16
#Mann= 7 ,-1 , 0
  4632.1      .1       0  4958.2     .16       0  4959.8     .07       0
  4965.8     .16       0  5063.1     .05       0  5215.8      .1       0
  5236.3     .05       0
Bank Sta=4959.8,4965.8
XS Rating Curve= 0 ,0
Exp/Cntr=0.3,0.1

Type RM Length L Ch R = 1 ,16483   ,86,86,86
BEGIN DESCRIPTION:
Mapping XS 240e1ce9
END DESCRIPTION:
XS GIS Cut Line= 4
      2775072.68     10067958.85      2775020.59     10067572.56
      2774948.98     10067375.08      2774658.18      10067264.4
#Sta/Elev= 30
  4524.2 1666.61  4549.5  1665.6  4630.3 1664.63  4731.2 1664.32  4744.6  1665.2
  4761.4 1663.76  4811.9 1662.95  4862.4 1664.48  4895.1  1663.9    4916 1664.43
  4931.8  1656.5  4937.1 1654.49  4946.7 1652.81  4962.4  1651.4  4967.7 1652.44
    4993 1649.77  4998.4 1650.41  5005.5 1649.74  5008.2 1649.24  5011.5 1649.74
    5053 1654.63  5072.3 1656.08  5084.9 1658.24  5104.2 1660.04  5115.5 1664.24
  5122.1 1665.56  5166.5 1666.49  5332.5 1669.33  5396.2 1669.96  5435.2 1671.19
#Mann= 7 ,-1 , 0
  4524.2      .1       0  4946.7     .16       0  5005.5     .07       0
  5011.5     .16       0    5053      .1       0  5166.5     .05       0
  5332.5      .1       0
Bank Sta=5005.5,5011.5
XS Rating Curve= 0 ,0
Exp/Cntr=0.3,0.1

Type RM Length L Ch R = 1 ,16397   ,60,60,60
BEGIN DESCRIPTION:
Mapping XS 1843fe18
END DESCRIPTION:
XS GIS Cut Line= 4
      2775126.93     10067958.88      2775073.27     10067474.79
      2775010.77      10067311.6      2774733.23     10067276.91
#Sta/Elev= 30
  4477.1  1666.2  4572.8  1665.2  4613.1  1664.1  4673.4 1664.19  4689.3 1663.63
  4703.6 1664.19  4723.7 1662.92    4764 1662.44  4821.1 1663.75  4844.5 1663.87
  4875.6 1663.21  4901.9 1661.47  4904.6 1660.97  4907.9 1661.47    4935 1663.07
  4961.3    1667  4986.4 1667.74  4991.8 1666.55  4995.3 1666.79  5016.5 1667.52
  5021.8 1666.64  5046.5 1668.23  5071.2 1666.99  5076.6  1667.7  5101.3 1666.02
  5106.6 1666.42  5131.3 1665.09  5270.4 1667.36  5396.6 1669.32  5418.6 1669.65
#Mann= 7 ,-1 , 0
  4477.1      .1       0  4821.1     .05       0  4901.9     .07       0
  4907.9     .05       0  4995.3      .1       0  5270.4     .05       0
  5396.6      .1       0
Bank Sta=4901.9,4907.9
XS Rating Curve= 0 ,0
Exp/Cntr=0.3,0.1

Type RM Length L Ch R = 1 ,16337   ,319,319,319
BEGIN DESCRIPTION:
UNT007 IN NNOGR 34.0
END DESCRIPTION:
XS GIS Cut Line= 4
      2775166.31     10067794.35      2775119.25     10067431.77
      2775061.72     10067285.33       2774686.9     10067210.36
#Sta/Elev= 30
    4607 1663.71  4668.1  1663.6  4710.2 1661.35  4718.5 1662.07  4808.8 1662.86
  4849.6 1662.57  4863.5  1661.5  4869.8  1658.3  4879.9 1656.96    4890 1660.59
  4910.1 1663.08  4942.6 1661.96  4950.5 1661.09    4956  1658.5  4960.6 1656.33
  4987.5 1650.91  4992.9 1651.59  5008.9 1650.43  5011.7 1649.93  5014.9 1650.43
  5017.3 1652.22    5035 1657.85  5041.7 1661.73  5071.5  1665.1  5088.7 1664.73
  5095.9 1663.58  5110.2 1663.63  5338.3  1667.5  5366.3 1668.25  5512.2 1670.15
#Mann= 7 ,-1 , 0
    4607      .1       0  4808.8     .05       0    4956      .1       0
  5008.9     .07       0  5014.9      .1       0  5338.3     .05       0
  5366.3      .1       0
Bank Sta=5008.9,5014.9
XS Rating Curve= 0 ,0
Exp/Cntr=0.3,0.1

Type RM Length L Ch R = 1 ,16018   ,71,71,71
BEGIN DESCRIPTION:
UNT007 IN NNOGR 33.0
END DESCRIPTION:
XS GIS Cut Line= 4
      2775665.11     10067683.21      2775452.45     10067362.06
       2775194.2     10067255.72      2774777.57     10067197.13
#Sta/Elev= 30
  4543.9 1660.79  4562.1 1660.39  4641.3 1658.99  4692.5 1657.37  4743.6 1656.91
  4779.7 1657.27  4836.9 1658.91  4888.2 1658.57  4938.3 1657.49    4955 1654.13
  4962.3 1651.57  4967.7 1651.05  4983.2 1648.02  4985.9 1647.52  4989.2 1648.02
  4991.6 1648.83  4998.3 1648.19  5015.6 1648.03  5030.7 1649.93  5039.5 1651.54
  5052.4 1656.27  5068.9 1660.41  5074.3 1660.79  5092.8 1661.26  5098.2 1660.72
  5122.2 1660.67  5151.5 1661.59  5385.8 1664.67    5549  1667.6  5629.1 1669.01
#Mann= 6 ,-1 , 0
  4543.9     .05       0  4562.1      .1       0  4888.2     .05       0
  4983.2    .035       0  4989.2     .05       0    5549      .1       0
Bank Sta=4983.2,4989.2
XS Rating Curve= 0 ,0
Exp/Cntr=0.3,0.1

Type RM Length L Ch R = 1 ,15947   ,74,74,74
BEGIN DESCRIPTION:
Mapping XS a4a900fe
END DESCRIPTION:
XS GIS Cut Line= 4
      2775693.34     10067626.81      2775465.63     10067294.24
      2775309.38     10067217.85      2774816.32     10067172.71
#Sta/Elev= 30
  4537.6 1659.92  4608.1 1658.64  4637.9 1658.66  4694.7 1656.86  4727.6 1656.37
  4730.4 1655.87  4733.6 1656.37  4808.4 1658.07  4853.2 1657.56  4875.8 1657.74
    4904 1657.41    4917 1657.83    4931 1659.01  4937.9 1660.36  4953.7 1661.44
  4970.6  1660.4  4976.2 1660.69  4993.2  1660.2  4998.7 1659.41  5004.3 1660.54
  5015.4 1660.31  5021.2 1659.76  5026.8 1660.98  5037.7 1660.82  5071.8 1658.54
  5212.7 1662.35  5336.4 1663.62    5543 1667.38  5567.6 1667.48  5609.7 1668.19
#Mann= 5 ,-1 , 0
  4537.6      .1       0  4727.6    .035       0  4733.6      .1       0
  4875.8     .05       0  5567.6      .1       0
Bank Sta=4727.6,4733.6
XS Rating Curve= 0 ,0
Exp/Cntr=0.3,0.1

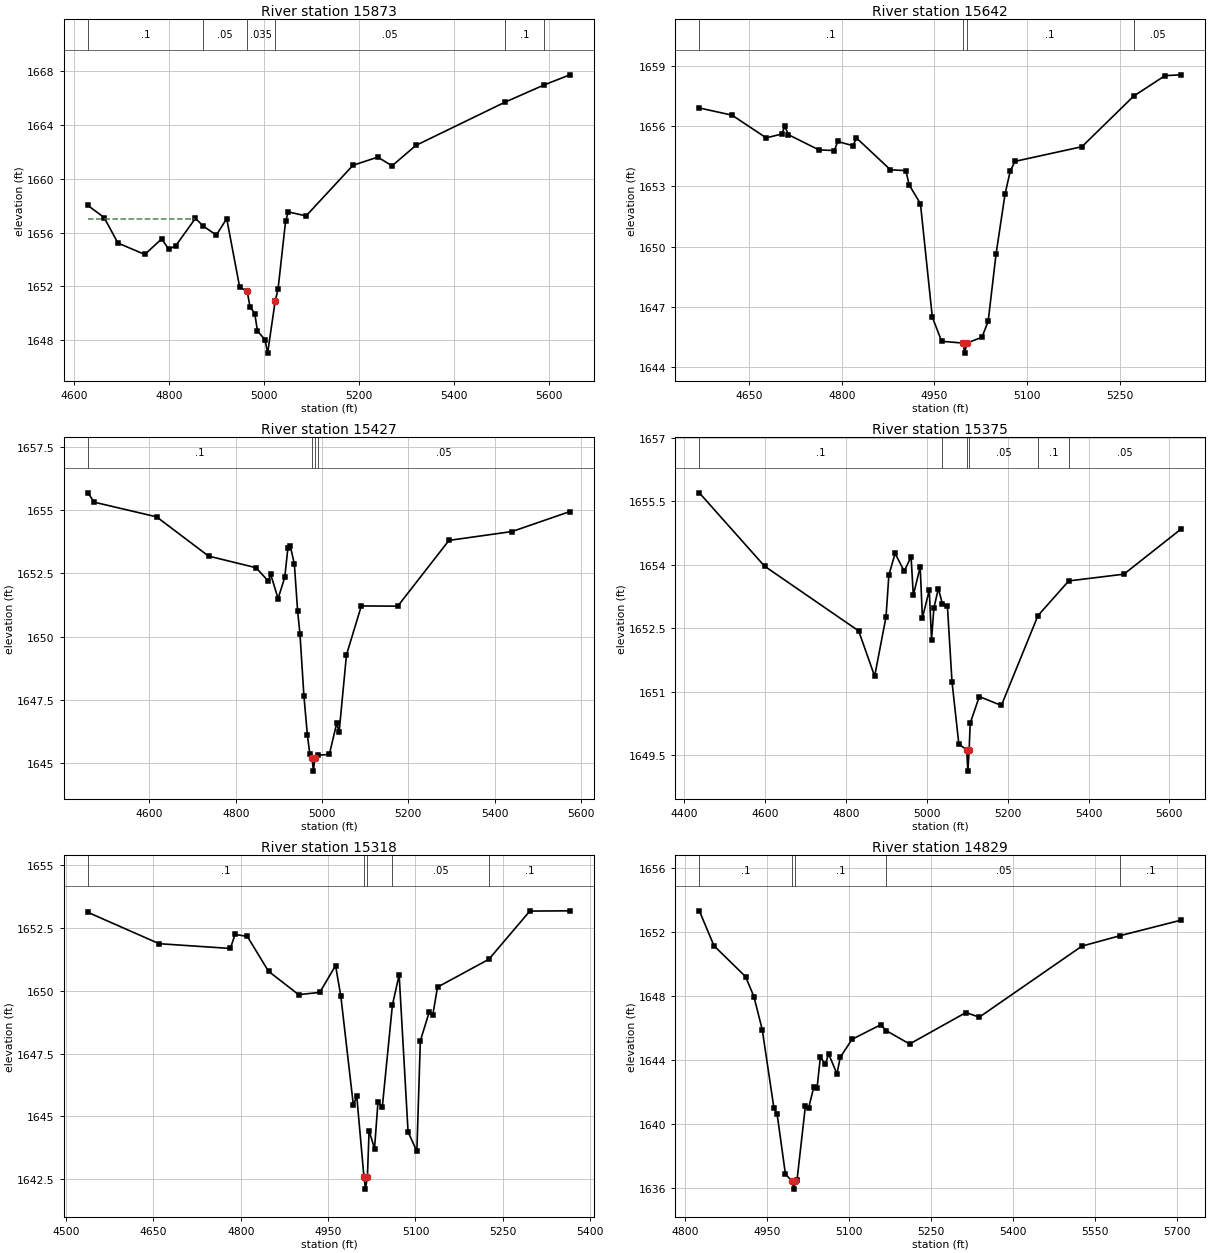
Type RM Length L Ch R = 1 ,15873   ,231,231,231
BEGIN DESCRIPTION:
Mapping XS e341e99b
END DESCRIPTION:
XS GIS Cut Line= 4
      2775684.66      10067474.9      2775515.39      10067242.7
       2775339.6     10067142.87      2774814.38     10067112.49
#Sta/Elev= 30
  4628.3 1658.02  4662.5 1657.12  4691.6 1655.22  4748.2 1654.37  4783.8 1655.53
  4798.4 1654.77  4813.1    1655  4854.8 1657.06  4871.6 1656.48  4898.9 1655.81
  4920.8 1657.04  4948.1 1651.93    4964 1651.63  4969.8 1650.48  4979.9 1649.96
  4985.6 1648.68  5001.5 1648.01    5007 1647.02  5023.1 1650.94  5028.9 1651.77
  5044.8 1656.83  5050.5 1657.54    5088 1657.24  5186.8 1661.01  5239.1 1661.62
  5269.2 1660.97  5319.3 1662.49  5506.4  1665.7  5589.8    1667  5643.9 1667.75
#Mann= 6 ,-1 , 0
  4628.3      .1       0  4871.6     .05       0    4964    .035       0
  5023.1     .05       0  5506.4      .1       0  5589.8     .05       0
#XS Ineff= 2 , 0
          4853.2    1657
Permanent Ineff=
       F       F
Bank Sta=4964,5023.1
XS Rating Curve= 0 ,0
Exp/Cntr=0.3,0.1

Type RM Length L Ch R = 1 ,15642   ,215,215,215
BEGIN DESCRIPTION:
UNT007 IN NNOGR 32.0
END DESCRIPTION:
XS GIS Cut Line= 3
        2775792.     10067408.79      2775667.02     10067075.49
       2775296.9     10066867.95
#Sta/Elev= 30
  4569.3  1656.9  4622.4 1656.54  4677.6 1655.41  4702.5  1655.6  4707.9 1655.98
  4713.5 1655.57    4763 1654.81    4788 1654.78  4793.3 1655.23  4818.2 1655.02
  4823.6 1655.41  4878.7 1653.82  4903.7 1653.78    4909 1653.07  4927.3 1652.13
  4946.5 1646.48  4961.6 1645.28  4996.3 1645.19    4999 1644.69  5002.3 1645.19
  5026.8 1645.48  5036.9 1646.27  5049.7 1649.63  5064.3 1652.62  5072.6 1653.75
  5080.3 1654.24  5188.7 1654.97  5272.5 1657.49  5323.3 1658.51  5349.6 1658.55
#Mann= 4 ,-1 , 0
  4569.3      .1       0  4996.3     .07       0  5002.3      .1       0
  5272.5     .05       0
Bank Sta=4996.3,5002.3
XS Rating Curve= 0 ,0
Exp/Cntr=0.3,0.1

Type RM Length L Ch R = 1 ,15427   ,52,52,52
BEGIN DESCRIPTION:
Mapping XS f4dc39a7
END DESCRIPTION:
XS GIS Cut Line= 4
      2775864.78     10067392.45      2775840.63     10067106.74
       2775594.1     10066592.85      2775335.31     10066561.28
#Sta/Elev= 30
  4457.2 1655.68  4471.9 1655.31  4616.5 1654.73  4736.9 1653.18  4847.1 1652.72
  4875.4 1652.19    4881 1652.46  4898.1  1651.5  4913.6 1652.34  4920.8 1653.49
  4926.3 1653.59  4935.8 1652.87  4943.4 1651.01  4948.9 1650.09    4958 1647.65
  4966.1  1646.1  4971.6 1645.37  4977.2 1645.18  4979.9 1644.68  4983.2 1645.18
  4990.3 1645.31  5016.9 1645.34    5034 1646.57  5039.6 1646.22  5056.7 1649.28
  5091.1 1651.21  5175.5  1651.2  5294.3  1653.8  5440.5 1654.15  5574.6 1654.94
#Mann= 4 ,-1 , 0
  4457.2      .1       0  4977.2    .035       0  4983.2      .1       0
  4990.3     .05       0
Bank Sta=4977.2,4983.2
XS Rating Curve= 0 ,0
Exp/Cntr=0.3,0.1

Type RM Length L Ch R = 1 ,15375   ,57,57,57
BEGIN DESCRIPTION:
Mapping XS 2c630df2
END DESCRIPTION:
XS GIS Cut Line= 4
      2775901.67     10067396.82      2775885.77     10067078.96
      2775641.25     10066578.64      2775326.54     10066541.74
#Sta/Elev= 30
  4437.4  1655.7  4598.6 1653.97  4831.5 1652.44    4871 1651.37  4899.1 1652.77
  4906.2 1653.76  4921.6 1654.27  4944.1 1653.85  4961.1 1654.19  4966.6 1653.28
  4983.6 1653.95  4989.1 1652.75  5006.1  1653.4  5011.7 1652.23  5017.5 1652.98
  5028.6 1653.44  5038.5 1653.08  5050.9 1653.03  5062.3 1651.24  5079.2 1649.77
  5098.7 1649.63  5101.5 1649.13  5104.7 1649.63  5107.3 1650.26  5129.8 1650.89
  5184.4 1650.68  5274.8  1652.8    5351 1653.62  5487.5 1653.78  5629.4 1654.85
#Mann= 6 ,-1 , 0
  4437.4      .1       0  5038.5     .05       0  5098.7     .07       0
  5104.7     .05       0  5274.8      .1       0    5351     .05       0
Bank Sta=5098.7,5104.7
XS Rating Curve= 0 ,0
Exp/Cntr=0.3,0.1

Type RM Length L Ch R = 1 ,15318   ,489,489,489
BEGIN DESCRIPTION:
UNT007 IN NNOGR 31.0
END DESCRIPTION:
XS GIS Cut Line= 2
      2776080.29     10067230.15      2775635.61     10066532.04
#Sta/Elev= 30
  4537.5 1653.13  4659.8 1651.88  4782.2 1651.69  4790.2 1652.25  4811.3 1652.17
  4847.7 1650.78  4899.4 1649.85  4935.8 1649.94  4962.8 1651.01  4971.9 1649.78
  4993.3 1645.46  4999.2  1645.8  5011.5  1642.6  5014.2  1642.1  5017.5  1642.6
  5020.4 1644.43  5029.7 1643.71  5035.6 1645.56  5043.1 1645.38  5060.4 1649.43
    5072 1650.64  5087.3 1644.38  5102.4 1643.61  5108.4 1648.01  5123.7 1649.16
  5129.6 1649.02  5137.9 1650.15  5226.1 1651.26  5296.4 1653.18  5365.2 1653.19
#Mann= 5 ,-1 , 0
  4537.5      .1       0  5011.5     .07       0  5017.5      .1       0
  5060.4     .05       0  5226.1      .1       0
Bank Sta=5011.5,5017.5
XS Rating Curve= 0 ,0
Exp/Cntr=0.3,0.1

Type RM Length L Ch R = 1 ,14829   ,594,594,594
BEGIN DESCRIPTION:
Mapping XS f88daa6f
END DESCRIPTION:
XS GIS Cut Line= 4
      2776287.93      10067021.3      2776144.73     10066793.48
      2776092.64     10066637.23      2775669.43     10066489.65
#Sta/Elev= 30
  4826.7 1653.33  4853.6 1651.14  4911.3 1649.21  4926.6 1647.96  4941.9 1645.88
  4963.1    1641    4969 1640.62  4984.3 1636.83  4996.6  1636.4  4999.4  1635.9
  5002.6  1636.4  5005.6  1636.5  5020.9 1641.13  5026.8 1640.99  5036.2  1642.3
  5042.1 1642.22  5048.2 1644.16  5057.4 1643.73  5063.3 1644.37  5078.6 1643.12
  5084.5 1644.15  5106.1 1645.28  5158.3 1646.19  5169.1 1645.82  5211.5 1644.99
  5314.6 1646.96    5339 1646.67  5526.8 1651.12  5597.4 1651.78  5708.7 1652.75
#Mann= 5 ,-1 , 0
  4826.7      .1       0  4996.6     .07       0  5002.6      .1       0
  5169.1     .05       0  5597.4      .1       0
Bank Sta=4996.6,5002.6
XS Rating Curve= 0 ,0
Exp/Cntr=0.3,0.1

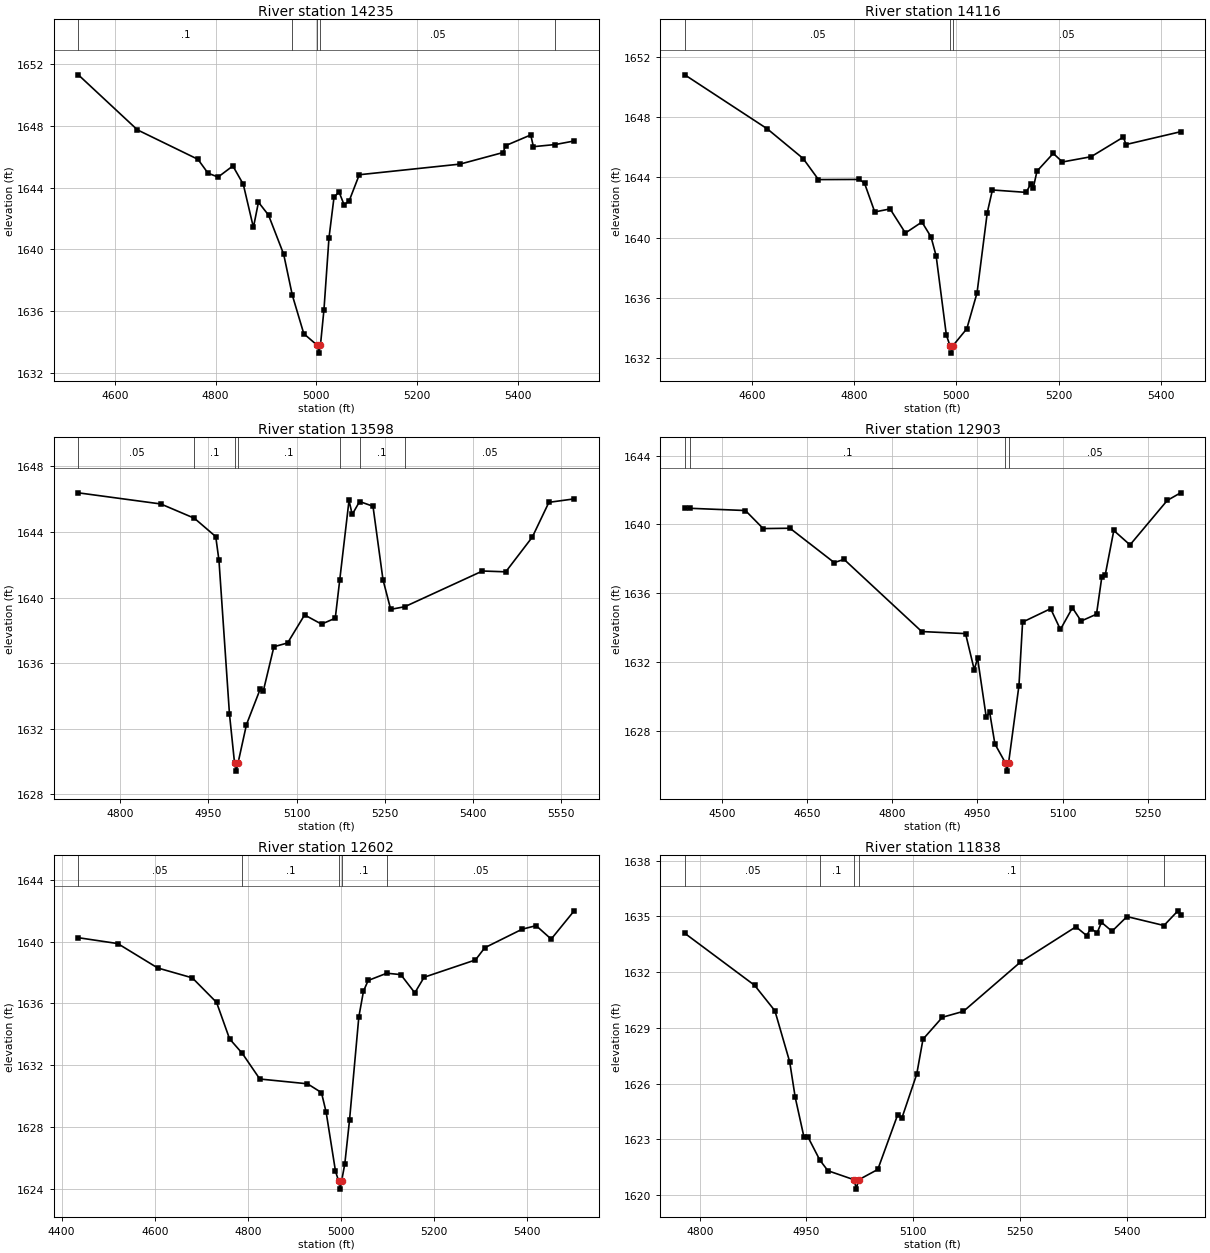
Type RM Length L Ch R = 1 ,14235   ,119,119,119
BEGIN DESCRIPTION:
UNT007 IN NNOGR 30.0
END DESCRIPTION:
XS GIS Cut Line= 3
      2776333.53     10066941.01      2776311.83     10066270.48
      2776018.82     10066159.78
#Sta/Elev= 30
  4527.6 1651.31  4644.9 1647.74    4765 1645.83    4785 1644.93    4805 1644.68
  4834.3  1645.4    4855 1644.21  4875.1 1641.41  4885.1 1643.05  4905.1 1642.21
  4935.1 1639.68  4952.3 1637.02  4975.1 1634.52  5002.1 1633.76  5004.9 1633.26
  5008.1 1633.76  5015.1 1636.07  5025.1 1640.74  5035.1 1643.38  5045.1 1643.71
  5055.2 1642.87  5065.2 1643.14  5085.2 1644.83  5285.3 1645.52  5370.5 1646.27
  5375.8 1646.72  5425.5 1647.41  5430.8 1646.65  5474.5 1646.79  5511.7 1647.02
#Mann= 5 ,-1 , 0
  4527.6      .1       0  4952.3     .05       0  5002.1    .035       0
  5008.1     .05       0  5474.5      .1       0
Bank Sta=5002.1,5008.1
XS Rating Curve= 0 ,0
Exp/Cntr=0.3,0.1

Type RM Length L Ch R = 1 ,14116   ,518,518,518
BEGIN DESCRIPTION:
UNT007 IN NNOGR 29.0
END DESCRIPTION:
XS GIS Cut Line= 3
      2776411.65     10066915.02      2776385.61     10066255.29
      2776093.08     10066153.44
#Sta/Elev= 30
  4468.7 1650.82  4630.1 1647.23  4700.2 1645.26  4730.2 1643.86  4810.3 1643.87
  4820.3 1643.62  4840.3 1641.71  4870.3 1641.91  4900.3 1640.31  4932.6 1641.04
  4950.4 1640.05  4960.4 1638.79  4980.4 1633.53  4987.4 1632.83  4990.1 1632.33
  4993.4 1632.83  5020.4 1633.95  5040.4 1636.33  5060.4 1641.66  5070.5 1643.17
  5136.5 1643.01  5145.3 1643.56  5150.6 1643.33  5157.7 1644.42  5189.5  1645.6
  5207.5 1645.03  5263.6 1645.38  5326.6 1646.68  5331.9 1646.19  5438.7 1647.04
#Mann= 3 ,-1 , 0
  4468.7     .05       0  4987.4     .04       0  4993.4     .05       0
Bank Sta=4987.4,4993.4
XS Rating Curve= 0 ,0
Exp/Cntr=0.3,0.1

Type RM Length L Ch R = 1 ,13598   ,695,695,695
BEGIN DESCRIPTION:
UNT007 IN NNOGR 28.0
END DESCRIPTION:
XS GIS Cut Line= 3
      2777024.63     10066203.95      2776573.27     10066006.04
       2776257.4     10066158.77
#Sta/Elev= 30
  4728.6 1646.39    4869 1645.71    4926 1644.84  4962.4 1643.72  4967.9 1642.27
  4985.8 1632.88  4994.4 1629.91  4997.1 1629.41  5000.4 1629.91  5014.7 1632.25
    5038 1634.41  5043.5 1634.32  5061.4    1637  5084.7 1637.23  5113.6 1638.94
  5142.4 1638.38  5165.8 1638.74  5173.4 1641.07  5189.2 1645.93  5194.6 1645.07
  5207.2 1645.86    5230 1645.57    5247 1641.09  5260.1 1639.28    5284 1639.44
  5416.3 1641.62  5455.9 1641.57  5501.1 1643.69  5529.3 1645.81  5572.3 1646.02
#Mann= 7 ,-1 , 0
  4728.6     .05       0    4926      .1       0  4994.4     .07       0
  5000.4      .1       0  5173.4     .05       0  5207.2      .1       0
    5284     .05       0
Bank Sta=4994.4,5000.4
XS Rating Curve= 0 ,0
Exp/Cntr=0.3,0.1

Type RM Length L Ch R = 1 ,12903   ,301,301,301
BEGIN DESCRIPTION:
UNT007 IN NNOGR 27.0
END DESCRIPTION:
XS GIS Cut Line= 3
      2777003.83     10065693.55      2776607.99     10065558.13
      2776223.02      10065800.9
#Sta/Elev= 30
  4434.5 1640.95  4443.9 1640.94  4541.3 1640.81  4572.6 1639.76  4619.8 1639.78
  4697.8 1637.78    4715 1637.97  4851.9 1633.77  4929.1 1633.65  4944.4 1631.55
  4950.3 1632.22  4965.6 1628.78  4971.5 1629.09  4980.8 1627.23    4999 1626.15
  5001.8 1625.65    5005 1626.15  5023.2 1630.63  5029.6 1634.32    5079  1635.1
  5096.2 1633.89  5117.4 1635.15  5132.7 1634.38  5159.8 1634.78  5169.2 1636.95
  5175.1 1637.05  5190.3 1639.65  5218.8 1638.81  5284.5  1641.4    5308 1641.84
#Mann= 4 ,-1 , 0
  4434.5     .05       0  4443.9      .1       0    4999     .07       0
    5005     .05       0
Bank Sta=4999,5005
XS Rating Curve= 0 ,0
Exp/Cntr=0.3,0.1

Type RM Length L Ch R = 1 ,12602   ,764,764,764
BEGIN DESCRIPTION:
UNT007 IN NNOGR 26.0
END DESCRIPTION:
XS GIS Cut Line= 3
      2777014.25     10065592.86      2776601.04     10065349.79
      2776016.94     10065315.71
#Sta/Elev= 30
    4436 1640.25  4520.6 1639.87  4606.4 1638.29  4680.7 1637.65  4732.8 1636.06
  4760.7  1633.7    4788 1632.76  4825.6  1631.1    4928 1630.79    4958 1630.22
  4968.1 1628.94  4988.1 1625.13  4995.1 1624.47  4997.9 1623.97  5001.1 1624.47
  5008.1 1625.61  5018.2 1628.43  5038.2 1635.12  5048.2 1636.79  5058.2 1637.48
  5098.3 1637.95  5128.3 1637.86  5158.4 1636.68  5178.4 1637.69  5288.6 1638.81
  5308.6  1639.6  5388.8  1640.8  5418.8 1641.03  5451.2 1640.16  5500.5 1641.99
#Mann= 5 ,-1 , 0
    4436     .05       0    4788      .1       0  4995.1     .07       0
  5001.1      .1       0  5098.3     .05       0
Bank Sta=4995.1,5001.1
XS Rating Curve= 0 ,0
Exp/Cntr=0.3,0.1

Type RM Length L Ch R = 1 ,11838   ,46,46,46
BEGIN DESCRIPTION:
Mapping XS 68272c3b
END DESCRIPTION:
XS GIS Cut Line= 4
      2777028.14     10065082.45      2776899.65     10064971.32
      2776767.71     10064978.27      2776443.07     10065202.76
#Sta/Elev= 30
    4779 1634.09  4877.1 1631.29  4905.6 1629.92  4926.4 1627.17  4934.1 1625.27
  4946.4 1623.13    4952 1623.13  4968.8 1621.88  4980.1 1621.31  5017.2 1620.82
  5019.9 1620.32  5023.2 1620.82  5050.2 1621.38  5078.1 1624.32    5084 1624.14
  5104.9 1626.51  5113.7 1628.39  5140.9 1629.57  5170.5 1629.89  5250.3 1632.53
  5328.6 1634.44  5343.5 1633.97  5349.6 1634.34  5358.4 1634.12  5364.5 1634.68
  5379.3  1634.2  5400.3 1634.99  5452.3 1634.51  5471.9  1635.3  5475.7 1635.09
#Mann= 5 ,-1 , 0
    4779     .05       0  4968.8      .1       0  5017.2     .07       0
  5023.2      .1       0  5452.3     .05       0
Bank Sta=5017.2,5023.2
XS Rating Curve= 0 ,0
Exp/Cntr=0.3,0.1