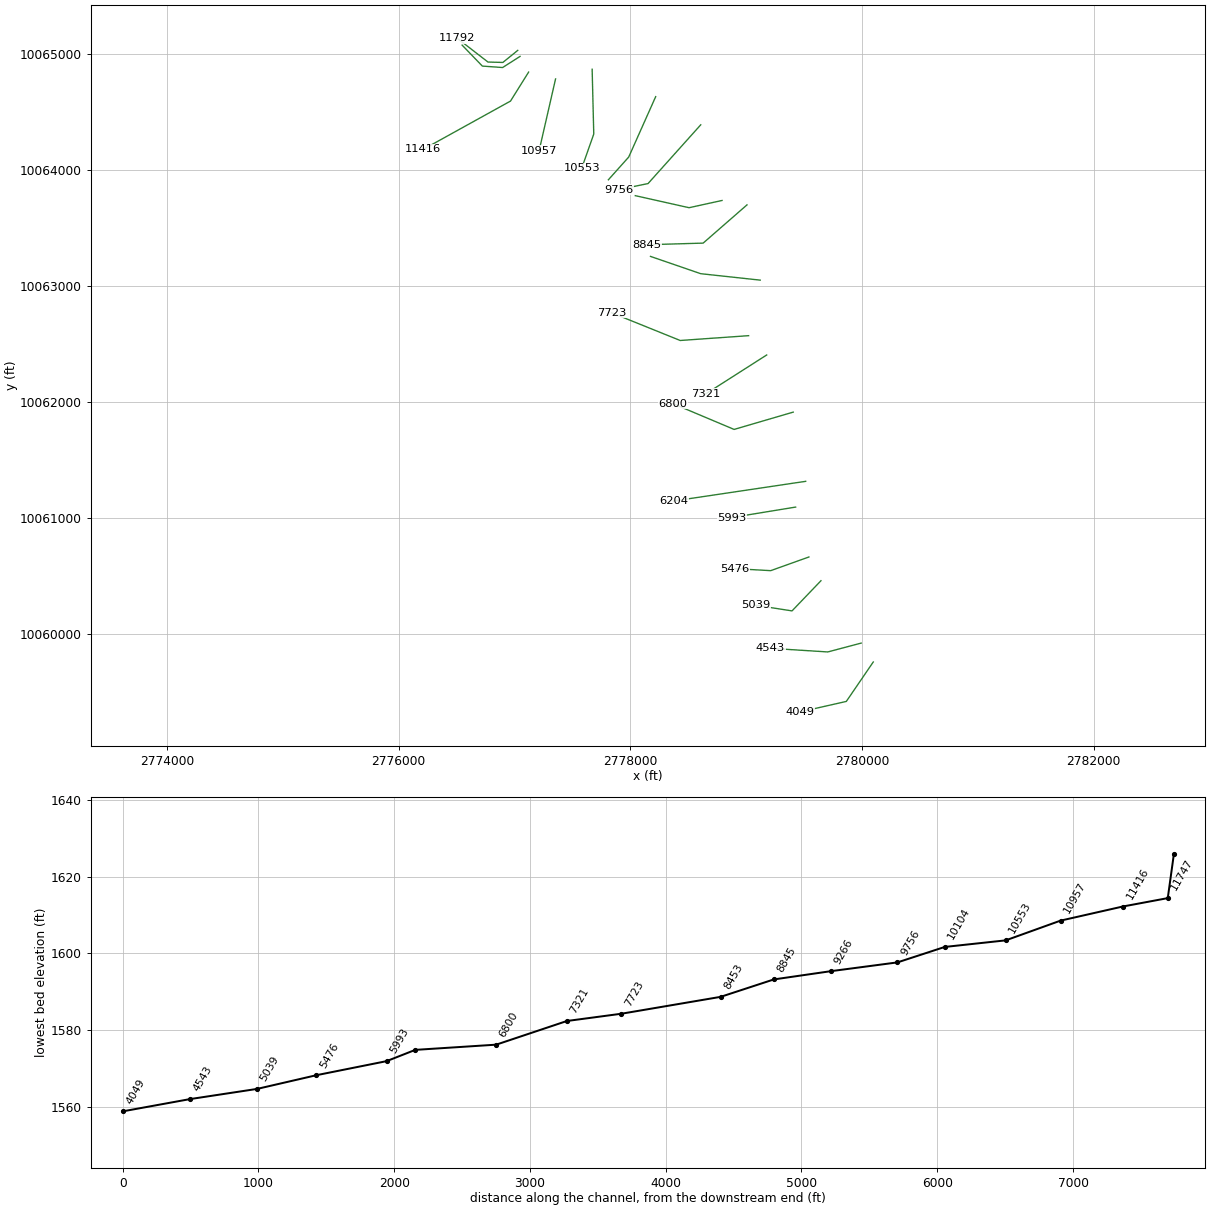
HEC-RAS study UNT007 IN NNOGR.prj: UNT007 IN NNOGR Base Level Engineering

--- UNT007 IN NNOGR.g01 (geometry) --- (continued)

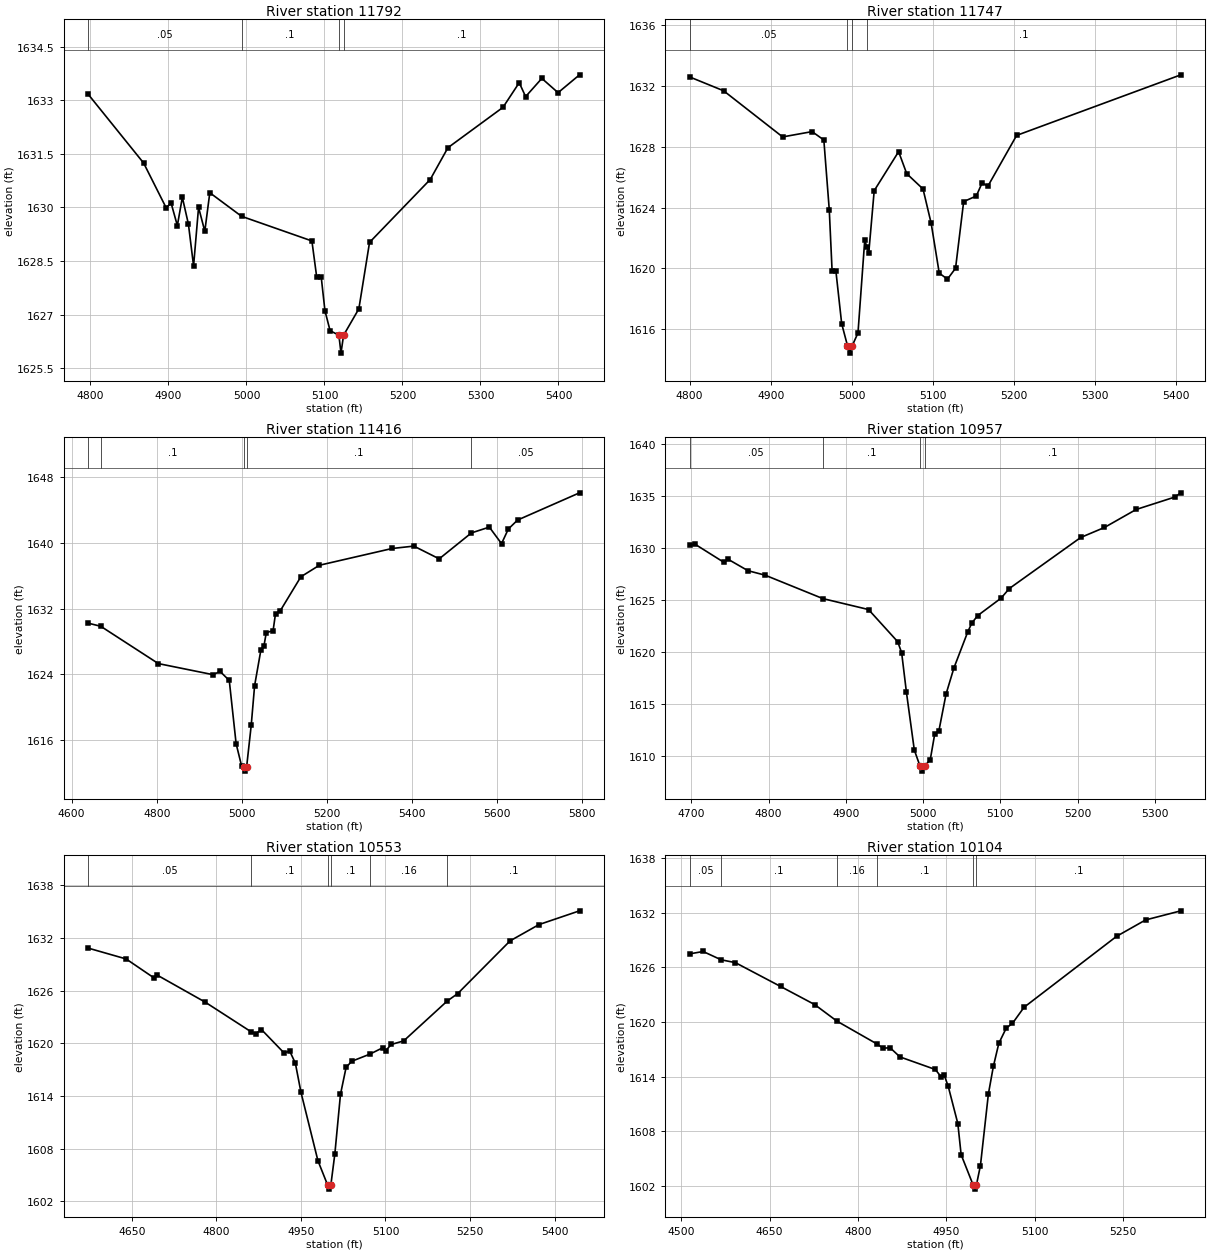
Type RM Length L Ch R = 1 ,11792   ,45,45,45
BEGIN DESCRIPTION:
Mapping XS 468cd450
END DESCRIPTION:
XS GIS Cut Line= 4
       2777028.1      10065033.8      2776899.65     10064929.66
      2776771.18     10064933.13      2776505.33     10065138.31
#Sta/Elev= 30
  4797.3 1633.16  4868.2 1631.24    4897 1629.99  4903.4 1630.12  4911.4 1629.49
  4917.8 1630.28  4925.6 1629.53  4932.2 1628.36  4938.6    1630  4946.6 1629.33
    4953 1630.41  4993.7 1629.75  5083.9 1629.06    5090 1628.06  5095.8 1628.06
  5100.6 1627.11  5107.2 1626.55  5118.5 1626.42  5121.2 1625.92  5124.5 1626.42
  5144.1 1627.16  5157.8 1629.02  5235.6 1630.78  5258.3 1631.67  5328.9  1632.8
  5349.7 1633.49  5357.9  1633.1  5378.7 1633.61  5399.5 1633.21    5427 1633.71
#Mann= 4 ,-1 , 0
  4797.3     .05       0  4993.7      .1       0  5118.5     .07       0
  5124.5      .1       0
Bank Sta=5118.5,5124.5
XS Rating Curve= 0 ,0
Exp/Cntr=0.3,0.1

Type RM Length L Ch R = 1 ,11747   ,331,331,331
BEGIN DESCRIPTION:
UNT007 IN NNOGR 25.0
END DESCRIPTION:
XS GIS Cut Line= 4
      2777047.84      10064981.8      2776897.62     10064885.83
      2776722.32     10064898.35      2776547.56     10065079.35
#Sta/Elev= 30
  4800.2 1632.61    4842  1631.7  4914.8 1628.66  4951.1 1629.01  4965.6 1628.46
  4972.3 1623.86  4975.8 1619.81  4980.5 1619.81  4987.6 1616.36  4994.7 1614.92
  4997.4 1614.42  5000.7 1614.92  5007.7 1615.75    5016 1621.85  5018.7 1621.41
    5021 1621.03  5027.7 1625.12  5057.8 1627.69  5067.8 1626.24  5087.9 1625.23
  5097.9 1622.98  5107.9 1619.69    5118 1619.29    5128 1620.01    5138  1624.4
  5153.6 1624.77  5160.8 1625.64  5167.8 1625.41  5203.3 1628.76  5405.8 1632.75
#Mann= 4 ,-1 , 0
  4800.2     .05       0  4994.7    .035       0  5000.7     .05       0
  5018.7      .1       0
Bank Sta=4994.7,5000.7
XS Rating Curve= 0 ,0
Exp/Cntr=0.3,0.1

Type RM Length L Ch R = 1 ,11416   ,459,459,459
BEGIN DESCRIPTION:
UNT007 IN NNOGR 24.0
END DESCRIPTION:
XS GIS Cut Line= 3
       2777121.9     10064846.36      2776965.63     10064596.32
      2776212.83     10064180.03
#Sta/Elev= 30
  4639.2 1630.22  4668.3 1629.85  4803.8 1625.31  4932.6 1623.96  4948.9 1624.36
  4970.6 1623.26  4986.7 1615.57  4999.4  1612.9  5005.4 1612.73  5008.2 1612.23
  5011.4 1612.73  5022.2 1617.79  5030.2 1622.63  5045.1    1627  5051.9 1627.39
  5057.6 1629.06  5073.7 1629.33  5079.4  1631.4  5089.7 1631.66    5139 1635.87
  5182.5 1637.27  5353.6 1639.31  5404.7  1639.6  5464.3 1638.05  5539.9  1641.2
  5582.2 1641.91  5610.9  1639.9  5626.9 1641.68  5648.7 1642.77  5794.3 1646.08
#Mann= 5 ,-1 , 0
  4639.2     .05       0  4668.3      .1       0  5005.4     .07       0
  5011.4      .1       0  5539.9     .05       0
Bank Sta=5005.4,5011.4
XS Rating Curve= 0 ,0
Exp/Cntr=0.3,0.1

Type RM Length L Ch R = 1 ,10957   ,404,404,404
BEGIN DESCRIPTION:
UNT007 IN NNOGR 23.0
END DESCRIPTION:
XS GIS Cut Line= 2
      2777354.52     10064787.33       2777212.5     10064167.28
#Sta/Elev= 30
  4697.7 1630.22  4704.5 1630.34  4742.3 1628.58  4747.4 1628.89  4773.2 1627.79
  4795.4 1627.36  4870.2 1625.11  4929.3 1624.06  4967.1 1620.97  4972.2 1619.91
  4978.4 1616.11  4988.6 1610.57  4995.9 1609.04  4998.6 1608.54  5001.9 1609.04
  5009.2 1609.62  5015.1 1612.13  5020.3 1612.36  5029.7 1615.94  5039.9 1618.45
    5058 1621.95  5063.2 1622.77  5070.7 1623.48  5100.9 1625.15  5111.7 1626.08
  5204.1 1630.98  5234.8 1631.94  5275.9 1633.67  5325.8 1634.86  5333.8 1635.27
#Mann= 4 ,-1 , 0
  4697.7     .05       0  4870.2      .1       0  4995.9     .07       0
  5001.9      .1       0
Bank Sta=4995.9,5001.9
XS Rating Curve= 0 ,0
Exp/Cntr=0.3,0.1

Type RM Length L Ch R = 1 ,10553   ,449,449,449
BEGIN DESCRIPTION:
UNT007 IN NNOGR 22.0
END DESCRIPTION:
XS GIS Cut Line= 3
      2777670.49     10064870.67      2777684.38      10064311.6
      2777580.62     10064017.62
#Sta/Elev= 30
  4573.1 1630.83  4640.1  1629.6  4689.1 1627.46  4694.1  1627.8  4780.1 1624.69
  4862.1 1621.29  4870.1  1621.1  4880.1 1621.56  4920.1  1618.9  4930.2 1619.11
  4940.2 1617.73  4950.2  1614.4  4980.2 1606.63  4997.2 1603.89  4999.9 1603.39
  5003.2 1603.89  5010.2 1607.39  5020.2 1614.18  5030.2 1617.26  5040.2 1617.95
  5072.3 1618.76  5095.5  1619.5  5100.5 1619.16  5110.2 1619.86  5132.3 1620.27
  5209.5 1624.81    5228 1625.65    5321 1631.66  5372.1 1633.51  5444.1 1635.08
#Mann= 6 ,-1 , 0
  4573.1     .05       0  4862.1      .1       0  4997.2     .07       0
  5003.2      .1       0  5072.3     .16       0  5209.5      .1       0
Bank Sta=4997.2,5003.2
XS Rating Curve= 0 ,0
Exp/Cntr=0.3,0.1

Type RM Length L Ch R = 1 ,10104   ,348,348,348
BEGIN DESCRIPTION:
UNT007 IN NNOGR 21.0
END DESCRIPTION:
XS GIS Cut Line= 3
      2778219.11     10064634.54      2777986.46     10064113.68
      2777810.73     10063917.27
#Sta/Elev= 30
  4514.4 1627.47  4537.2 1627.73  4567.8 1626.82  4591.9 1626.51  4668.6  1623.9
  4726.6 1621.91  4764.5 1620.09  4831.8 1617.61  4842.7 1617.13  4854.8 1617.17
  4871.4 1616.17  4931.5 1614.79    4941 1614.01  4946.5 1614.18  4953.4 1612.94
  4969.7 1608.86  4975.3 1605.45  4995.4 1602.17  4998.1 1601.67  5001.4 1602.17
  5008.1 1604.26  5021.6 1612.11    5030 1615.12  5039.3 1617.66  5051.9 1619.33
  5062.5 1619.85  5082.1 1621.61  5239.2 1629.39  5288.5 1631.19  5348.4 1632.19
#Mann= 6 ,-1 , 0
  4514.4     .05       0  4567.8      .1       0  4764.5     .16       0
  4831.8      .1       0  4995.4     .07       0  5001.4      .1       0
Bank Sta=4995.4,5001.4
XS Rating Curve= 0 ,0
Exp/Cntr=0.3,0.1

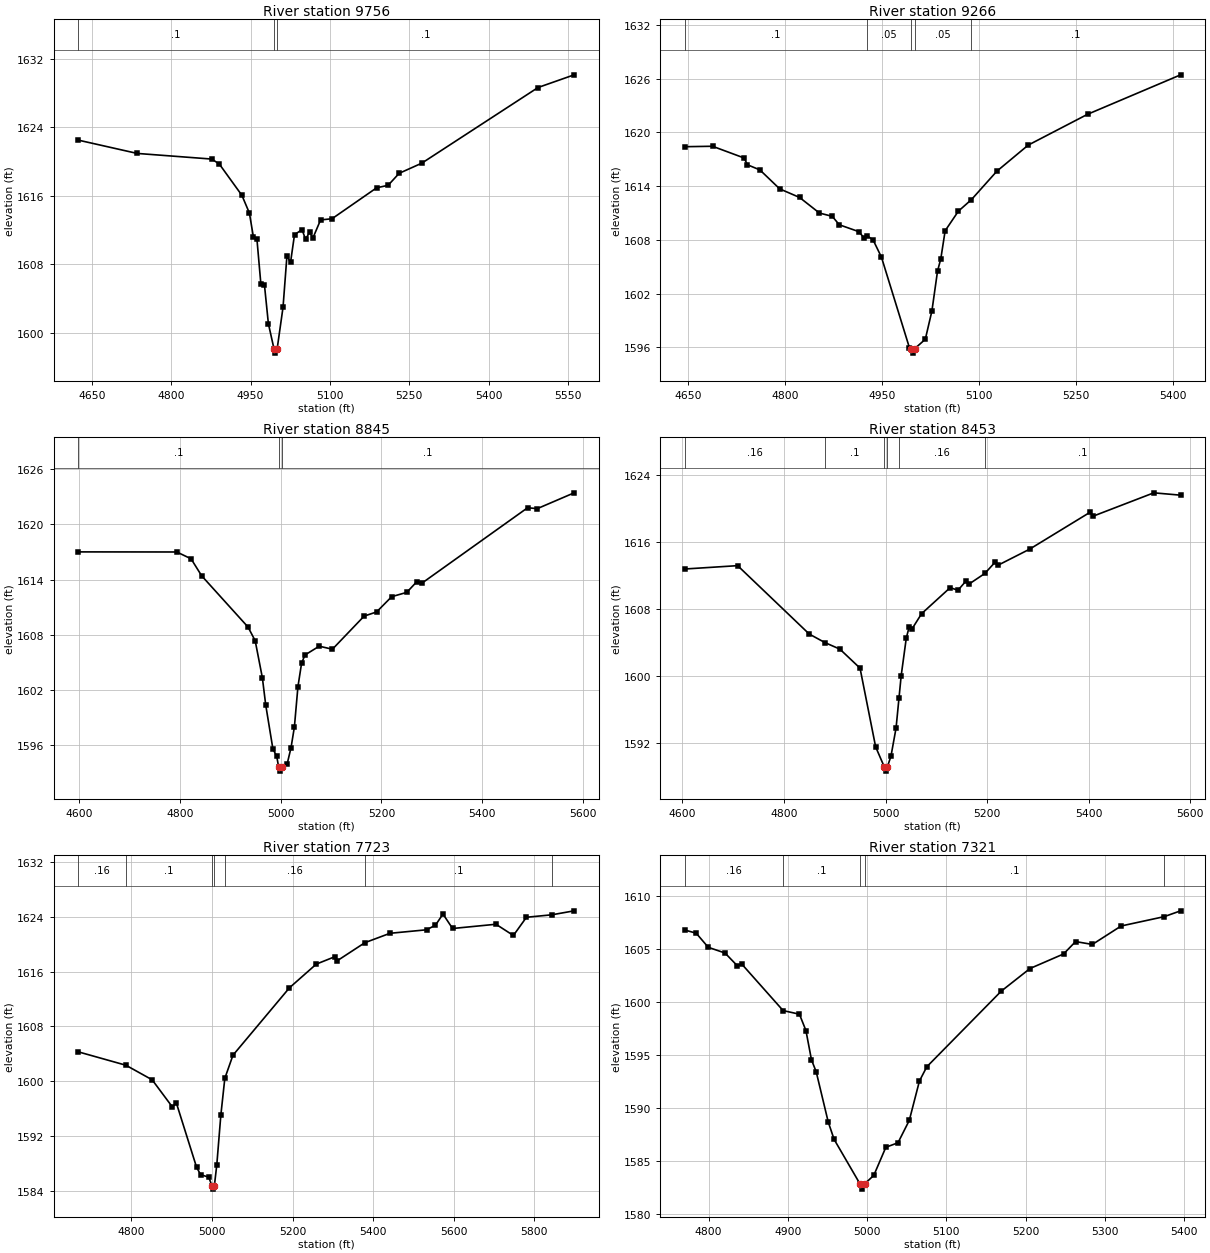
Type RM Length L Ch R = 1 ,9756    ,490,490,490
BEGIN DESCRIPTION:
UNT007 IN NNOGR 20.0
END DESCRIPTION:
XS GIS Cut Line= 3
      2778607.96     10064391.43      2778153.13     10063884.52
      2777901.54     10063832.82
#Sta/Elev= 30
  4624.1 1622.49  4735.4 1620.94  4876.7 1620.28  4890.9 1619.69  4933.5 1616.05
  4947.7 1613.98  4955.2 1611.21  4961.9 1610.97  4969.4 1605.69  4976.1 1605.63
  4983.6 1601.08  4994.2 1598.14  4996.9 1597.64  5000.2 1598.14  5011.3 1602.99
  5018.7    1609  5025.5 1608.22    5033 1611.46  5047.2 1612.05  5053.9 1610.93
  5061.4 1611.72  5068.1 1611.11  5082.3 1613.18    5104 1613.32  5188.4 1616.93
  5210.1 1617.22    5231 1618.62  5273.7  1619.8  5493.7 1628.63    5562 1630.11
#Mann= 3 ,-1 , 0
  4624.1      .1       0  4994.2     .07       0  5000.2      .1       0
Bank Sta=4994.2,5000.2
XS Rating Curve= 0 ,0
Exp/Cntr=0.3,0.1

Type RM Length L Ch R = 1 ,9266    ,421,421,421
BEGIN DESCRIPTION:
UNT007 IN NNOGR 19.0
END DESCRIPTION:
XS GIS Cut Line= 3
      2778791.99     10063738.68      2778507.29     10063676.18
      2778042.77     10063780.18
#Sta/Elev= 30
  4644.4 1618.41  4687.3 1618.46  4736.2 1617.15  4741.4 1616.39  4760.6 1615.82
  4791.3  1613.7  4822.1 1612.74  4852.8    1611  4872.7 1610.63  4883.5 1609.69
  4914.2 1608.91  4921.7 1608.21  4926.5 1608.47  4935.9 1607.99  4948.8 1606.07
  4992.2 1595.93  4994.3 1595.85  4997.1 1595.35  5000.3 1595.85  5016.7  1596.9
  5026.9 1600.06  5035.6 1604.51  5040.7  1605.9  5047.4 1609.02  5067.9 1611.21
  5088.1  1612.5  5127.4 1615.67    5176 1618.59  5267.8 1622.03  5411.9 1626.44
#Mann= 5 ,-1 , 0
  4644.4      .1       0  4926.5     .05       0  4994.3    .035       0
  5000.3     .05       0  5088.1      .1       0
Bank Sta=4994.3,5000.3
XS Rating Curve= 0 ,0
Exp/Cntr=0.3,0.1

Type RM Length L Ch R = 1 ,8845    ,392,392,392
BEGIN DESCRIPTION:
UNT007 IN NNOGR 18.0
END DESCRIPTION:
XS GIS Cut Line= 3
      2779007.28     10063700.48      2778628.82     10063370.63
      2778146.15     10063356.74
#Sta/Elev= 30
  4597.8 1617.02  4793.4 1617.01  4821.7 1616.27  4842.8 1614.42  4934.9 1608.85
  4949.1 1607.36  4963.4 1603.33    4970 1600.39  4984.3  1595.6  4991.9  1594.8
  4995.5 1593.69  4998.2 1593.19  5001.5 1593.69  5012.7 1593.99  5020.3 1595.74
    5027    1598    5034 1602.36  5041.2  1604.9  5047.9 1605.81  5076.3 1606.77
  5102.5 1606.44  5165.5 1610.04  5190.2 1610.49  5220.2 1612.15  5250.2 1612.62
  5270.3 1613.79  5280.3 1613.62  5490.3 1621.82  5509.4 1621.72  5582.7 1623.44
#Mann= 3 ,-1 , 0
  4597.8      .1       0  4995.5     .07       0  5001.5      .1       0
Bank Sta=4995.5,5001.5
XS Rating Curve= 0 ,0
Exp/Cntr=0.3,0.1

Type RM Length L Ch R = 1 ,8453    ,730,730,730
BEGIN DESCRIPTION:
UNT007 IN NNOGR 17.0
END DESCRIPTION:
XS GIS Cut Line= 3
       2779121.9     10063051.18      2778607.99     10063106.74
      2778173.96     10063256.05
#Sta/Elev= 30
  4604.9 1612.76  4708.9 1613.16  4849.8    1605    4881 1603.97  4910.1  1603.2
  4949.8 1600.93  4980.5 1591.54  4997.6 1589.14  5000.4 1588.64  5003.6 1589.14
  5010.7 1590.43  5020.7 1593.78  5026.5 1597.37  5030.8 1600.04  5040.9 1604.54
  5046.6 1605.86  5051.6 1605.56    5071 1607.43  5127.3 1610.54  5142.5 1610.22
  5158.5 1611.34  5163.8 1610.94  5195.5 1612.23  5215.7 1613.58    5221  1613.2
  5283.4 1615.12  5403.1 1619.55  5408.4 1619.06    5528 1621.85  5580.8 1621.57
#Mann= 6 ,-1 , 0
  4604.9     .16       0    4881      .1       0  4997.6     .07       0
  5003.6      .1       0  5026.5     .16       0  5195.5      .1       0
Bank Sta=4997.6,5003.6
XS Rating Curve= 0 ,0
Exp/Cntr=0.3,0.1

Type RM Length L Ch R = 1 ,7723    ,402,402,402
BEGIN DESCRIPTION:
UNT007 IN NNOGR 16.0
END DESCRIPTION:
XS GIS Cut Line= 3
       2779021.2     10062572.02       2778430.9     10062530.35
      2777838.66     10062769.32
#Sta/Elev= 30
  4668.4 1604.28  4786.4 1602.33  4851.6  1600.2  4901.7 1596.24  4911.7 1596.81
  4961.9 1587.42  4971.9 1586.35  4991.9 1585.99    5000 1584.74  5002.8 1584.24
    5006 1584.74    5012 1587.79    5022 1595.02  5031.9 1600.41  5052.1 1603.79
  5192.4 1613.64  5258.9 1617.09  5304.9 1618.17  5310.3 1617.56  5379.5 1620.22
  5441.8 1621.59  5532.4  1622.1  5554.6 1622.77  5573.3  1624.4  5597.1 1622.29
  5704.8 1622.91    5748 1621.27  5780.4 1623.93  5843.4 1624.29  5898.8 1624.87
#Mann= 7 ,-1 , 0
  4668.4     .16       0  4786.4      .1       0    5000     .07       0
    5006      .1       0  5031.9     .16       0  5379.5      .1       0
  5843.4     .05       0
Bank Sta=5000,5006
XS Rating Curve= 0 ,0
Exp/Cntr=0.3,0.1

Type RM Length L Ch R = 1 ,7321    ,521,521,521
BEGIN DESCRIPTION:
UNT007 IN NNOGR 15.0
END DESCRIPTION:
XS GIS Cut Line= 2
      2779177.39     10062405.32      2778649.77     10062068.62
#Sta/Elev= 30
  4769.9 1606.78  4784.3 1606.48  4799.5 1605.15  4820.7 1604.61  4835.9 1603.43
  4841.8 1603.57    4894 1599.18  4914.6 1598.84  4922.8  1597.3  4929.8 1594.54
  4935.8  1593.4    4951 1588.66  4958.4 1587.03    4991 1582.84  4993.8 1582.34
    4997 1582.84  5008.5 1583.64  5023.7 1586.29    5039 1586.71  5053.3 1588.83
  5066.1 1592.54  5075.4 1593.88  5169.3 1601.01  5205.7 1603.15    5248 1604.52
  5263.2 1605.69  5284.4 1605.42  5320.7 1607.16    5375 1608.04  5395.8 1608.59
#Mann= 5 ,-1 , 0
  4769.9     .16       0    4894      .1       0    4991     .07       0
    4997      .1       0    5375     .16       0
Bank Sta=4991,4997
XS Rating Curve= 0 ,0
Exp/Cntr=0.3,0.1

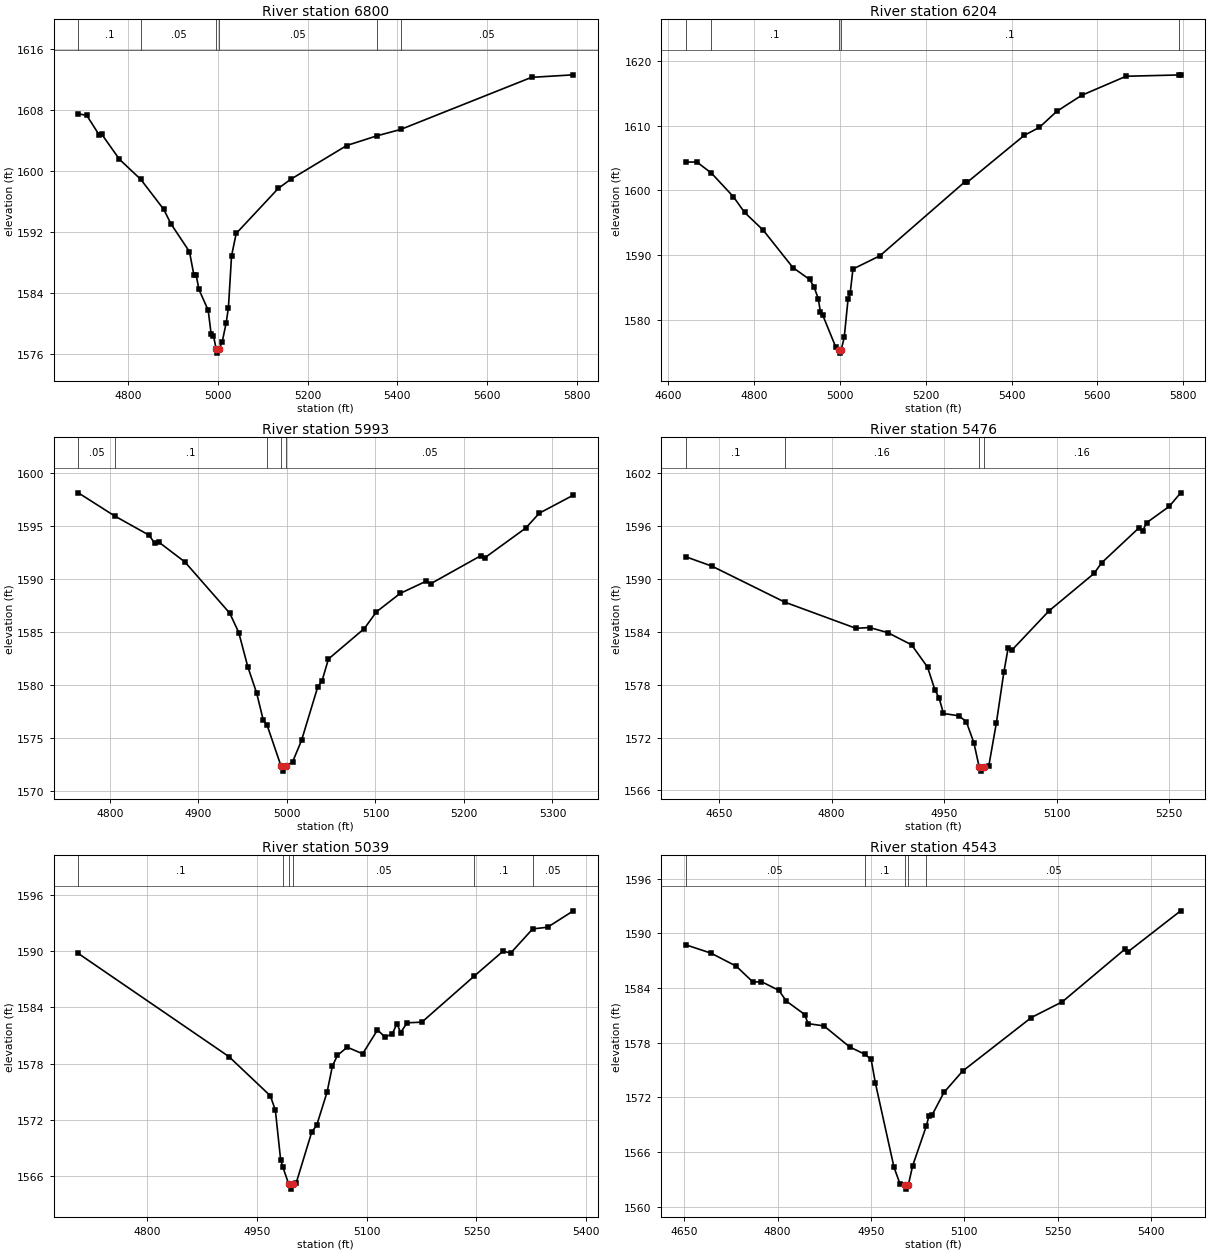
Type RM Length L Ch R = 1 ,6800    ,596,596,596
BEGIN DESCRIPTION:
UNT007 IN NNOGR 14.0
END DESCRIPTION:
XS GIS Cut Line= 3
      2779406.63     10061912.31      2778896.18     10061762.99
       2778368.4     10061985.21
#Sta/Elev= 30
  4688.2 1607.48  4707.1 1607.27  4734.9  1604.7  4740.1 1604.84  4780.1 1601.52
  4827.7 1598.89    4879 1594.96  4894.7  1593.1  4936.3 1589.43  4945.9 1586.44
  4951.1 1586.44  4957.2 1584.51    4978 1581.78  4984.6 1578.67  4989.8 1578.46
  4995.9 1576.66  4998.6 1576.16  5001.9 1576.66  5009.3 1577.64    5018 1580.07
  5023.2 1582.13  5030.1 1588.87  5040.5 1591.82  5134.3 1597.71  5162.2 1598.91
  5287.2 1603.33  5354.7  1604.6  5407.4 1605.43  5699.5 1612.25  5792.7 1612.58
#Mann= 6 ,-1 , 0
  4688.2      .1       0  4827.7     .05       0  4995.9    .035       0
  5001.9     .05       0  5354.7      .1       0  5407.4     .05       0
Bank Sta=4995.9,5001.9
XS Rating Curve= 0 ,0
Exp/Cntr=0.3,0.1

Type RM Length L Ch R = 1 ,6204    ,211,211,211
BEGIN DESCRIPTION:
UNT007 IN NNOGR 13.0
END DESCRIPTION:
XS GIS Cut Line= 2
      2779514.27     10061315.08      2778372.66     10061145.05
#Sta/Elev= 30
  4640.1 1604.38  4666.2  1604.4  4700.4 1602.67  4751.6 1599.01  4777.4  1596.6
  4820.9 1593.85  4890.2 1588.05  4929.1 1586.21  4939.2  1585.1  4949.3 1583.25
  4954.5 1581.13  4959.6 1580.71  4989.7 1575.81  4996.8  1575.3  4999.6  1574.8
  5002.8  1575.3  5009.9 1577.24  5018.8 1583.17  5023.8 1584.09  5030.2 1587.82
  5093.2 1589.88    5291 1601.32  5296.1 1601.23  5429.7 1608.53  5464.9 1609.76
  5505.3 1612.24  5563.3 1614.72  5667.1 1617.68  5790.8 1617.88  5794.3  1617.9
#Mann= 5 ,-1 , 0
  4640.1     .16       0  4700.4      .1       0  4996.8    .035       0
  5002.8      .1       0  5790.8      .1       0
Bank Sta=4996.8,5002.8
XS Rating Curve= 0 ,0
Exp/Cntr=0.3,0.1

Type RM Length L Ch R = 1 ,5993    ,517,517,517
BEGIN DESCRIPTION:
UNT007 IN NNOGR 12.0
END DESCRIPTION:
XS GIS Cut Line= 2
      2779427.43     10061092.85      2778875.37     10061002.58
#Sta/Elev= 30
  4764.2 1598.14  4805.2 1595.96  4844.2 1594.14  4850.5 1593.38  4855.6 1593.46
  4884.7 1591.61  4935.4 1586.77  4945.5 1584.95  4955.7 1581.73  4965.8 1579.22
  4973.2 1576.68  4977.3 1576.26  4993.2 1572.36    4996 1571.86  4999.2 1572.36
  5006.3 1572.72  5016.5 1574.77  5034.6 1579.76  5039.7 1580.41  5046.9 1582.45
  5087.4 1585.32  5101.1  1586.9  5127.9 1588.64  5157.4  1589.8  5162.5 1589.56
  5218.8 1592.19  5223.8 1592.02  5269.8 1594.81  5285.2 1596.22  5323.6 1597.92
#Mann= 5 ,-1 , 0
  4764.2     .05       0  4805.2      .1       0  4977.3     .05       0
  4993.2    .035       0  4999.2     .05       0
Bank Sta=4993.2,4999.2
XS Rating Curve= 0 ,0
Exp/Cntr=0.3,0.1

Type RM Length L Ch R = 1 ,5476    ,437,437,437
BEGIN DESCRIPTION:
UNT007 IN NNOGR 11.0
END DESCRIPTION:
XS GIS Cut Line= 3
      2779541.99     10060662.28      2779212.15     10060544.24
      2778903.26     10060561.59
#Sta/Elev= 30
  4605.6 1592.52  4640.9 1591.44  4737.9 1587.36  4832.4  1584.4  4850.9 1584.48
  4874.9 1583.91  4906.7 1582.52    4928 1579.99  4937.9 1577.38  4943.2 1576.54
  4949.2 1574.73  4969.6 1574.47  4979.6 1573.81  4989.7 1571.42  4996.7 1568.69
  4999.4 1568.19  5002.7 1568.69  5009.7 1568.82  5019.7 1573.66  5029.7 1579.42
  5035.4 1582.17  5040.4 1581.92  5089.8 1586.37  5149.9 1590.62  5159.9 1591.82
  5209.7 1595.79  5214.7 1595.47    5220 1596.38  5250.1 1598.23  5265.3 1599.77
#Mann= 4 ,-1 , 0
  4605.6      .1       0  4737.9     .16       0  4996.7     .07       0
  5002.7     .16       0
Bank Sta=4996.7,5002.7
XS Rating Curve= 0 ,0
Exp/Cntr=0.3,0.1

Type RM Length L Ch R = 1 ,5039    ,496,496,496
BEGIN DESCRIPTION:
UNT007 IN NNOGR 10.0
END DESCRIPTION:
XS GIS Cut Line= 3
      2779646.17     10060457.43      2779396.18     10060197.02
      2779083.72     10060245.62
#Sta/Elev= 30
  4705.4 1589.76  4911.5 1578.75  4968.1 1574.57    4975 1573.03  4982.2 1567.74
  4985.4 1566.93  4993.4 1565.11  4996.2 1564.61  4999.4 1565.11  5003.3 1565.22
  5024.7 1570.69  5031.6 1571.44  5045.8 1574.98    5053 1577.74  5059.9 1578.88
  5073.3 1579.76  5094.4 1579.05  5114.7  1581.6  5124.8 1580.85  5134.9 1581.16
  5141.3 1582.28  5146.3 1581.31  5155.2 1582.36  5175.4 1582.43  5247.4 1587.37
  5286.7 1590.02  5296.8 1589.79    5327 1592.38  5347.4 1592.56  5382.6 1594.31
#Mann= 6 ,-1 , 0
  4705.4      .1       0  4985.4     .05       0  4993.4    .035       0
  4999.4     .05       0  5247.4      .1       0    5327     .05       0
Bank Sta=4993.4,4999.4
XS Rating Curve= 0 ,0
Exp/Cntr=0.3,0.1

Type RM Length L Ch R = 1 ,4543    ,494,494,494
BEGIN DESCRIPTION:
UNT007 IN NNOGR 9.0
END DESCRIPTION:
XS GIS Cut Line= 3
      2779993.37     10059919.23      2779705.21     10059842.85
       2779208.7      10059874.1
#Sta/Elev= 30
  4652.1 1588.74  4693.2 1587.81  4733.4 1586.39  4760.6 1584.63  4773.6  1584.7
    4802 1583.74  4813.8 1582.57  4843.4 1581.09  4848.9 1580.09  4874.4 1579.84
  4915.8 1577.53  4939.8 1576.74  4950.2 1576.18    4957 1573.59    4987 1564.33
    4997 1562.45  5004.1 1562.44  5006.8 1561.94  5010.1 1562.44  5017.1 1564.53
  5039.1 1568.89    5043 1569.95    5048 1570.04  5067.2 1572.54  5097.2 1574.88
  5207.8 1580.76  5257.6 1582.49  5357.5 1588.22  5362.5 1587.94  5447.7 1592.46
#Mann= 5 ,-1 , 0
  4652.1     .05       0  4939.8      .1       0  5004.1     .07       0
  5010.1      .1       0  5039.1     .05       0
Bank Sta=5004.1,5010.1
XS Rating Curve= 0 ,0
Exp/Cntr=0.3,0.1

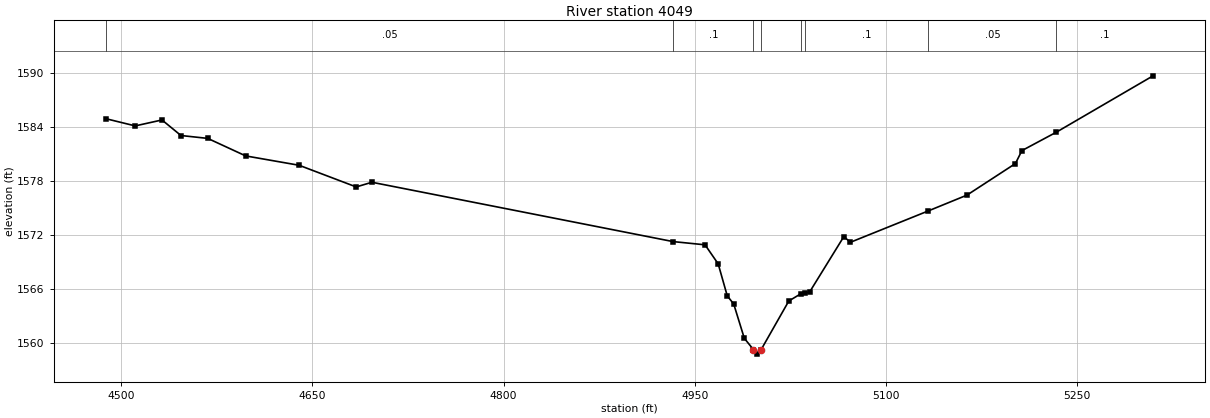
Type RM Length L Ch R = 1 ,4049    ,266,266,266
BEGIN DESCRIPTION:
UNT007 IN NNOGR 8.0
END DESCRIPTION:
XS GIS Cut Line= 3
      2780097.58     10059756.05      2779864.93     10059415.77
      2779465.62     10059325.49
#Sta/Elev= 30
    4488 1584.94    4511 1584.14    4532  1584.8  4546.9 1583.07  4567.9 1582.75
  4597.7  1580.8  4639.6 1579.76  4684.4 1577.35  4696.7 1577.87    4933 1571.27
  4958.1 1570.91  4968.4 1568.79  4975.5 1565.24  4980.6 1564.32  4988.9 1560.51
  4996.1 1559.25  4998.9 1558.75  5002.1 1559.25  5023.8 1564.66  5033.2 1565.46
  5036.7 1565.56  5040.1 1565.65    5067 1571.83  5072.1 1571.19  5133.4 1574.69
  5163.6 1576.44  5201.6 1579.95  5206.7 1581.39  5233.6 1583.43  5309.6 1589.71
#Mann= 8 ,-1 , 0
    4488     .05       0    4933      .1       0  4996.1     .07       0
  5002.1      .1       0  5033.2     .05       0  5036.7      .1       0
  5133.4     .05       0  5233.6      .1       0
Bank Sta=4996.1,5002.1
XS Rating Curve= 0 ,0
Exp/Cntr=0.3,0.1