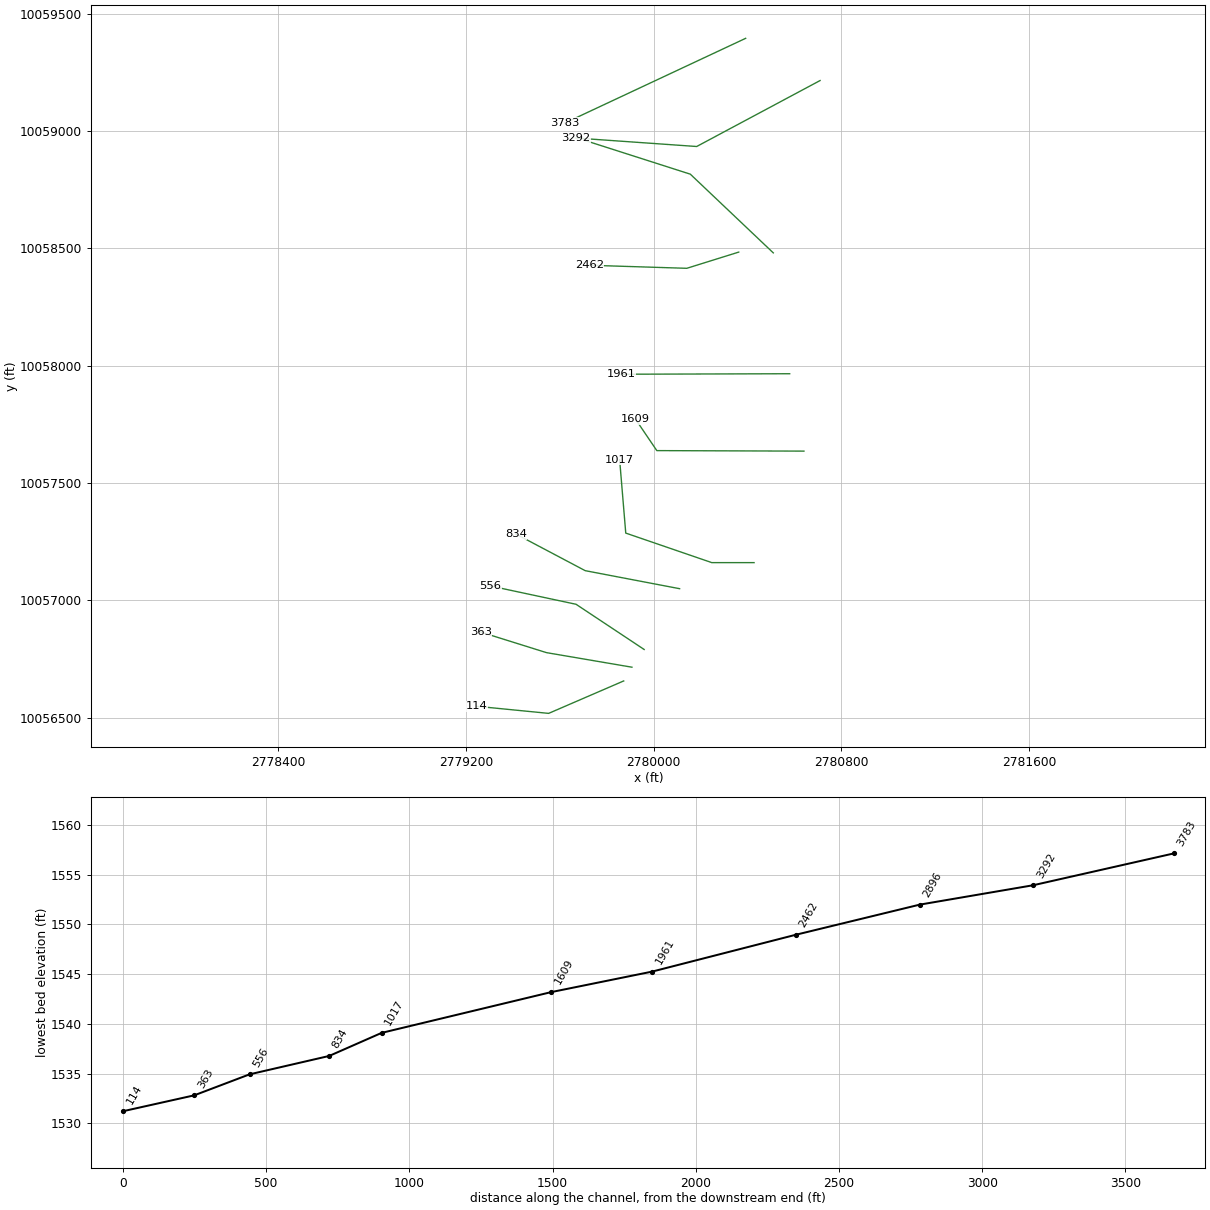
HEC-RAS study UNT007 IN NNOGR.prj: UNT007 IN NNOGR Base Level Engineering

--- UNT007 IN NNOGR.g01 (geometry) --- (continued)

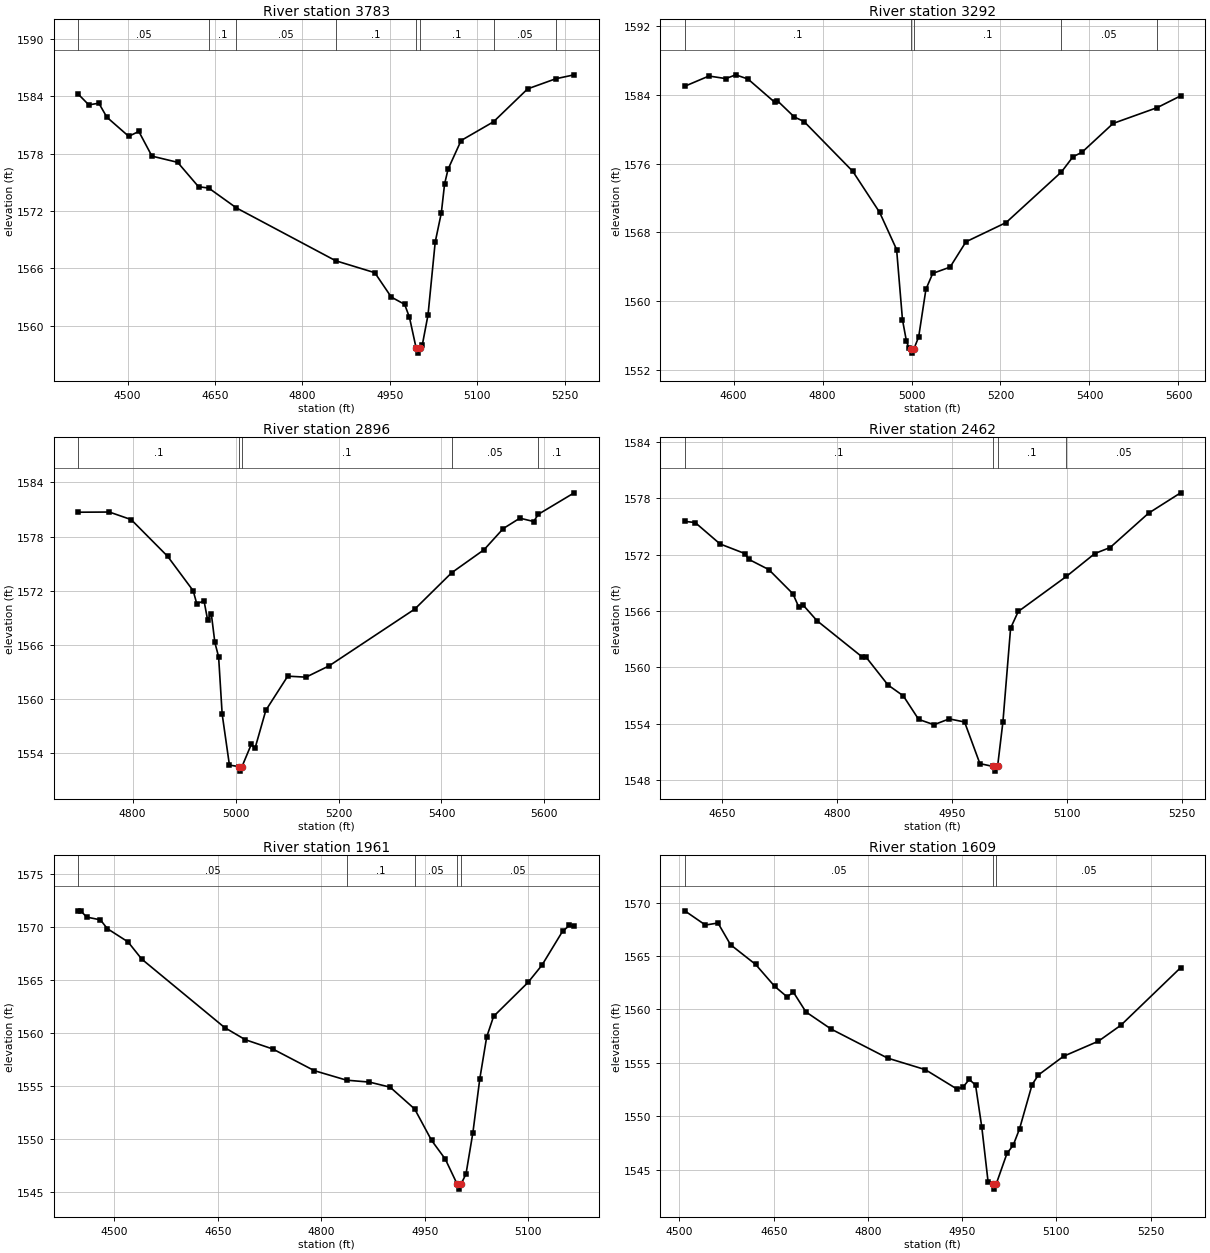
Type RM Length L Ch R = 1 ,3783    ,491,491,491
BEGIN DESCRIPTION:
UNT007 IN NNOGR 7.0
END DESCRIPTION:
XS GIS Cut Line= 2
      2780392.71     10059394.93      2779622.71     10059034.21
#Sta/Elev= 30
  4415.6 1584.21  4433.5  1583.1  4450.8 1583.27  4464.5 1581.81    4502 1579.81
  4519.3 1580.32  4541.8 1577.74  4585.9 1577.09  4621.7 1574.54  4639.2  1574.4
  4686.8 1572.32  4856.9  1566.8    4924 1565.55  4952.3    1563  4975.2 1562.24
  4983.5 1560.87    4995 1557.64  4997.7 1557.14    5001 1557.64  5005.6 1558.03
  5015.3 1561.14  5027.6 1568.75  5038.1  1571.8  5043.7 1574.83  5049.7 1576.38
    5072 1579.37  5127.6 1581.33  5186.1 1584.77  5234.4 1585.83  5265.9 1586.24
#Mann= 8 ,-1 , 0
  4415.6     .05       0  4639.2      .1       0  4686.8     .05       0
  4856.9      .1       0    4995     .07       0    5001      .1       0
  5127.6     .05       0  5234.4      .1       0
Bank Sta=4995,5001
XS Rating Curve= 0 ,0
Exp/Cntr=0.3,0.1

Type RM Length L Ch R = 1 ,3292    ,396,396,396
BEGIN DESCRIPTION:
UNT007 IN NNOGR 6.0
END DESCRIPTION:
XS GIS Cut Line= 3
      2780709.98     10059214.98      2780184.05     10058933.89
      2779667.16     10058970.16
#Sta/Elev= 30
  4490.4 1585.03  4544.6 1586.22  4582.8 1585.92  4604.8 1586.36  4632.4 1585.87
  4692.6 1583.16  4698.2 1583.36  4736.5 1581.45  4758.4 1580.92  4868.1 1575.11
  4928.3 1570.34  4966.5 1566.01  4979.7 1557.82  4988.5 1555.36  4994.1 1554.53
  4999.4 1554.44  5002.1 1553.94  5005.4 1554.44  5016.1 1555.83  5032.4 1561.38
  5047.7 1563.23  5086.7 1563.96  5122.4 1566.91  5212.6 1569.15  5336.9 1575.04
    5363 1576.82    5383 1577.33  5453.2  1580.7  5552.3 1582.54  5604.9 1583.91
#Mann= 5 ,-1 , 0
  4490.4      .1       0  4999.4     .07       0  5005.4      .1       0
  5336.9     .05       0  5552.3      .1       0
Bank Sta=4999.4,5005.4
XS Rating Curve= 0 ,0
Exp/Cntr=0.3,0.1

Type RM Length L Ch R = 1 ,2896    ,434,434,434
BEGIN DESCRIPTION:
UNT007 IN NNOGR 5.0
END DESCRIPTION:
XS GIS Cut Line= 3
      2780510.51     10058480.48      2780156.85       10058816.
      2779703.49     10058961.07
#Sta/Elev= 30
  4694.4  1580.7  4754.6 1580.72  4797.1 1579.88  4867.9 1575.81  4917.6 1571.99
  4924.5 1570.56  4938.7 1570.86  4945.5 1568.79  4952.8 1569.44  4959.7 1566.26
    4967 1564.66  4973.9 1558.31    4988 1552.66  5006.4 1552.49  5009.2 1551.99
  5012.4 1552.49  5030.5 1554.96  5037.7 1554.51  5058.8 1558.74  5101.3 1562.52
  5136.8 1562.41  5181.9 1563.67  5348.2 1569.96  5419.9 1573.99  5482.8 1576.54
  5520.2 1578.89  5552.4 1580.04  5579.2 1579.67  5588.3 1580.47  5657.9 1582.85
#Mann= 5 ,-1 , 0
  4694.4      .1       0  5006.4     .07       0  5012.4      .1       0
  5419.9     .05       0  5588.3      .1       0
Bank Sta=5006.4,5012.4
XS Rating Curve= 0 ,0
Exp/Cntr=0.3,0.1

Type RM Length L Ch R = 1 ,2462    ,501,501,501
BEGIN DESCRIPTION:
Mapping XS 7d9fae32
END DESCRIPTION:
XS GIS Cut Line= 3
      2780363.23     10058483.73      2780141.86     10058414.71
      2779726.54     10058427.73
#Sta/Elev= 30
  4601.2 1575.53  4614.7 1575.41  4647.2 1573.13  4679.5 1572.11    4685 1571.48
  4710.9  1570.4  4742.4 1567.82    4750 1566.42  4755.2 1566.67  4773.8 1564.96
  4832.2 1561.14  4837.3 1561.14  4866.5 1558.12  4886.5 1556.96  4906.5 1554.46
  4926.5 1553.89  4946.5 1554.51  4966.5 1554.18  4986.5 1549.75  5003.6 1549.45
  5006.3 1548.95  5009.6 1549.45  5016.6 1554.21  5026.6 1564.17  5036.6 1565.94
  5099.4 1569.67  5136.6 1572.11  5156.6 1572.75  5206.7  1576.4  5248.6 1578.57
#Mann= 4 ,-1 , 0
  4601.2      .1       0  5003.6     .07       0  5009.6      .1       0
  5099.4     .05       0
Bank Sta=5003.6,5009.6
XS Rating Curve= 0 ,0
Exp/Cntr=0.3,0.1

Type RM Length L Ch R = 1 ,1961    ,352,352,352
BEGIN DESCRIPTION:
UNT007 IN NNOGR 4.0
END DESCRIPTION:
XS GIS Cut Line= 2
      2780580.51     10057965.35      2779861.71     10057963.19
#Sta/Elev= 30
  4447.6 1571.51  4451.1 1571.51  4459.6 1570.92  4479.6 1570.66  4489.6 1569.83
  4519.6 1568.58  4539.6 1566.95  4659.6  1560.5  4689.6 1559.35  4729.6 1558.47
  4789.6 1556.43  4836.5 1555.53  4869.6 1555.35  4899.6 1554.87  4935.2 1552.81
  4959.6 1549.86  4979.6 1548.08  4996.6 1545.75  4999.4 1545.25  5002.6 1545.75
  5009.6 1546.68  5019.6 1550.58  5029.6 1555.66  5039.6 1559.61  5049.6 1561.55
  5099.6 1564.76  5119.6 1566.37  5149.6 1569.58  5159.6 1570.13  5166.4 1570.04
#Mann= 5 ,-1 , 0
  4447.6     .05       0  4836.5      .1       0  4935.2     .05       0
  4996.6    .035       0  5002.6     .05       0
Bank Sta=4996.6,5002.6
XS Rating Curve= 0 ,0
Exp/Cntr=0.3,0.1

Type RM Length L Ch R = 1 ,1609    ,592,592,592
BEGIN DESCRIPTION:
UNT007 IN NNOGR 3.0
END DESCRIPTION:
XS GIS Cut Line= 3
      2780641.25     10057635.49      2780014.08     10057637.66
      2779923.21     10057771.81
#Sta/Elev= 30
  4508.5 1569.23  4541.3  1567.9  4561.3 1568.09  4581.3 1566.06  4621.3 1564.21
  4651.3 1562.18  4671.3 1561.18  4681.3 1561.62  4701.3 1559.77  4741.3 1558.17
  4831.3 1555.45  4891.3 1554.37  4941.3 1552.57  4951.3 1552.73  4961.3 1553.46
  4971.3 1552.92  4981.3 1548.96  4991.3 1543.84  4998.3 1543.69    5001 1543.19
  5004.3 1543.69  5021.3 1546.53  5031.3 1547.31  5041.3 1548.83  5061.3 1552.97
  5071.3 1553.87  5111.3 1555.62  5166.8 1557.03  5202.7 1558.53  5297.7 1563.91
#Mann= 3 ,-1 , 0
  4508.5     .05       0  4998.3    .035       0  5004.3     .05       0
Bank Sta=4998.3,5004.3
XS Rating Curve= 0 ,0
Exp/Cntr=0.3,0.1

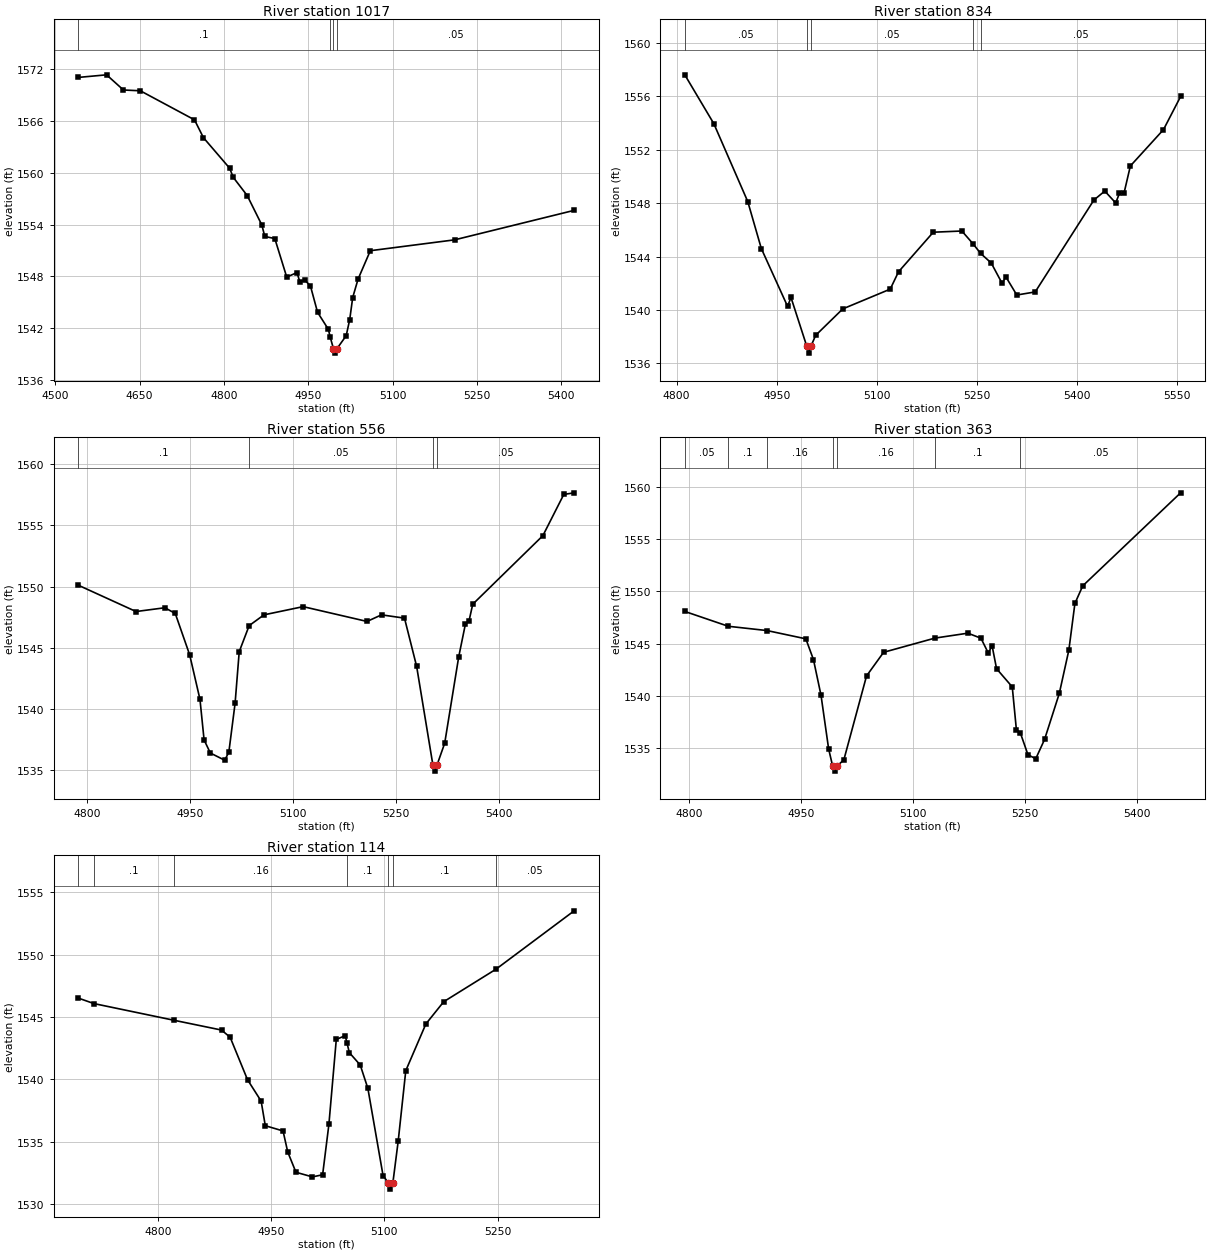
Type RM Length L Ch R = 1 ,1017    ,183,183,183
BEGIN DESCRIPTION:
UNT007 IN NNOGR 1.0
END DESCRIPTION:
XS GIS Cut Line= 4
      2780428.62     10057160.23      2780248.46     10057160.23
       2779881.7      10057286.1      2779855.66     10057598.61
#Sta/Elev= 30
  4541.2 1571.07  4591.4 1571.37  4621.4 1569.61  4651.4 1569.52  4747.7 1566.15
  4763.6 1564.08  4810.2 1560.54  4816.5 1559.49  4841.4 1557.37  4867.4 1553.96
  4872.7 1552.62  4890.5 1552.38  4911.7 1547.91  4929.9 1548.43  4935.2 1547.32
  4943.4  1547.6  4953.9 1546.87  4966.5 1543.83  4985.7 1541.85  4988.8    1541
  4994.8 1539.59  4997.5 1539.09  5000.8 1539.59  5017.4 1541.11  5023.7 1542.99
    5029 1545.54  5038.5 1547.67  5060.3 1550.97  5210.2 1552.23  5422.7 1555.65
#Mann= 4 ,-1 , 0
  4541.2      .1       0  4988.8     .05       0  4994.8    .035       0
  5000.8     .05       0
Bank Sta=4994.8,5000.8
XS Rating Curve= 0 ,0
Exp/Cntr=0.3,0.1

Type RM Length L Ch R = 1 ,834     ,278,278,278
BEGIN DESCRIPTION:
Mapping XS d9343e3a
END DESCRIPTION:
XS GIS Cut Line= 3
      2780111.25     10057049.11      2779708.87     10057125.94
      2779413.36     10057282.15
#Sta/Elev= 30
  4812.2  1557.6  4855.8 1553.94  4906.7 1548.11    4927  1544.6  4966.4 1540.27
  4971.5 1540.94  4995.3 1537.27    4998 1536.77  5001.3 1537.27  5008.5  1538.1
  5049.2 1540.08  5120.4 1541.56  5132.9 1542.86    5185 1545.82  5227.9 1545.91
  5244.5 1544.96  5256.1 1544.23  5271.9 1543.52  5288.3 1541.99  5293.9 1542.48
  5310.3 1541.12  5337.9 1541.35    5426 1548.23  5442.3  1548.9  5458.7 1548.01
  5464.3 1548.73  5471.1 1548.73  5480.7 1550.78  5530.4  1553.5  5556.1 1555.98
#Mann= 5 ,-1 , 0
  4812.2     .05       0  4995.3     .04       0  5001.3     .05       0
  5244.5      .1       0  5256.1     .05       0
Bank Sta=4995.3,5001.3
XS Rating Curve= 0 ,0
Exp/Cntr=0.3,0.1

Type RM Length L Ch R = 1 ,556     ,193,193,193
BEGIN DESCRIPTION:
Mapping XS 5c277068
END DESCRIPTION:
XS GIS Cut Line= 3
       2779960.2     10056789.98       2779669.8     10056982.71
      2779303.89     10057060.84
#Sta/Elev= 30
  4787.4 1550.11  4871.5 1547.96  4913.6 1548.27  4928.7  1547.8  4949.7 1544.42
  4964.7 1540.78  4970.7 1537.47  4979.8  1536.4  5000.8 1535.81  5006.8 1536.48
  5015.9 1540.47  5021.9 1544.68  5036.4 1546.81    5058 1547.69  5115.1 1548.36
  5208.2 1547.15  5229.3 1547.69  5262.8 1547.42  5280.5 1543.48  5304.2 1535.42
    5307 1534.92  5310.2 1535.42  5321.4  1537.2  5341.8 1544.25  5351.6 1546.94
  5356.7 1547.16  5362.3 1548.56  5464.5 1554.16    5495 1557.53  5510.1 1557.66
#Mann= 4 ,-1 , 0
  4787.4      .1       0  5036.4     .05       0  5304.2     .07       0
  5310.2     .05       0
Bank Sta=5304.2,5310.2
XS Rating Curve= 0 ,0
Exp/Cntr=0.3,0.1

Type RM Length L Ch R = 1 ,363     ,249,249,249
BEGIN DESCRIPTION:
Mapping XS 71e55464
END DESCRIPTION:
XS GIS Cut Line= 3
       2779908.1     10056714.48      2779543.89     10056776.54
      2779263.54     10056864.23
#Sta/Elev= 30
  4794.7 1548.09  4852.9 1546.67  4904.7 1546.26  4956.6 1545.47  4966.8 1543.48
  4976.9 1540.07  4987.1 1534.93  4992.4 1533.31  4995.1 1532.81  4998.4 1533.31
  5007.4 1533.88  5037.8 1541.92  5060.6 1544.18  5129.3 1545.54  5173.3 1546.01
  5190.8 1545.53  5200.5 1544.13  5205.8 1544.78  5211.7 1542.61  5232.7 1540.87
  5238.2 1536.79  5243.5 1536.47  5253.7 1534.38  5264.1 1533.99  5275.9 1535.84
  5295.6 1540.24  5308.4 1544.39  5316.5 1548.86    5327 1550.54  5457.9 1559.44
#Mann= 7 ,-1 , 0
  4794.7     .05       0  4852.9      .1       0  4904.7     .16       0
  4992.4     .07       0  4998.4     .16       0  5129.3      .1       0
  5243.5     .05       0
Bank Sta=4992.4,4998.4
XS Rating Curve= 0 ,0
Exp/Cntr=0.3,0.1

Type RM Length L Ch R = 1 ,114     ,0,0,0
BEGIN DESCRIPTION:
UNT007 IN NNOGR 1.1
END DESCRIPTION:
XS GIS Cut Line= 3
      2779872.96      10056655.9      2779553.05     10056517.65
      2779246.64     10056547.82
#Sta/Elev= 30
  4694.9 1546.51  4715.6 1546.07  4821.1 1544.74  4884.5 1543.95  4895.9 1543.37
  4918.9 1539.97  4936.9 1538.26  4942.4 1536.29  4965.9 1535.87  4972.1 1534.19
    4983 1532.56  5004.8 1532.19  5018.3 1532.36  5026.6 1536.39  5036.4  1543.2
  5048.2  1543.5  5050.7 1542.88  5053.7 1542.14  5068.1 1541.15  5078.2 1539.28
  5098.3  1532.3  5105.3 1531.71  5108.1 1531.21  5111.3 1531.71  5118.4 1535.08
  5128.4  1540.7    5155 1544.44  5178.6 1546.22  5247.7 1548.82  5351.3  1553.5
#Mann= 7 ,-1 , 0
  4694.9     .05       0  4715.6      .1       0  4821.1     .16       0
  5050.7      .1       0  5105.3     .07       0  5111.3      .1       0
  5247.7     .05       0
Bank Sta=5105.3,5111.3
XS Rating Curve= 0 ,0
Exp/Cntr=0.3,0.1

Chan Stop Cuts=-1
Use User Specified Reach Order=0
Composite Channel Slope=5