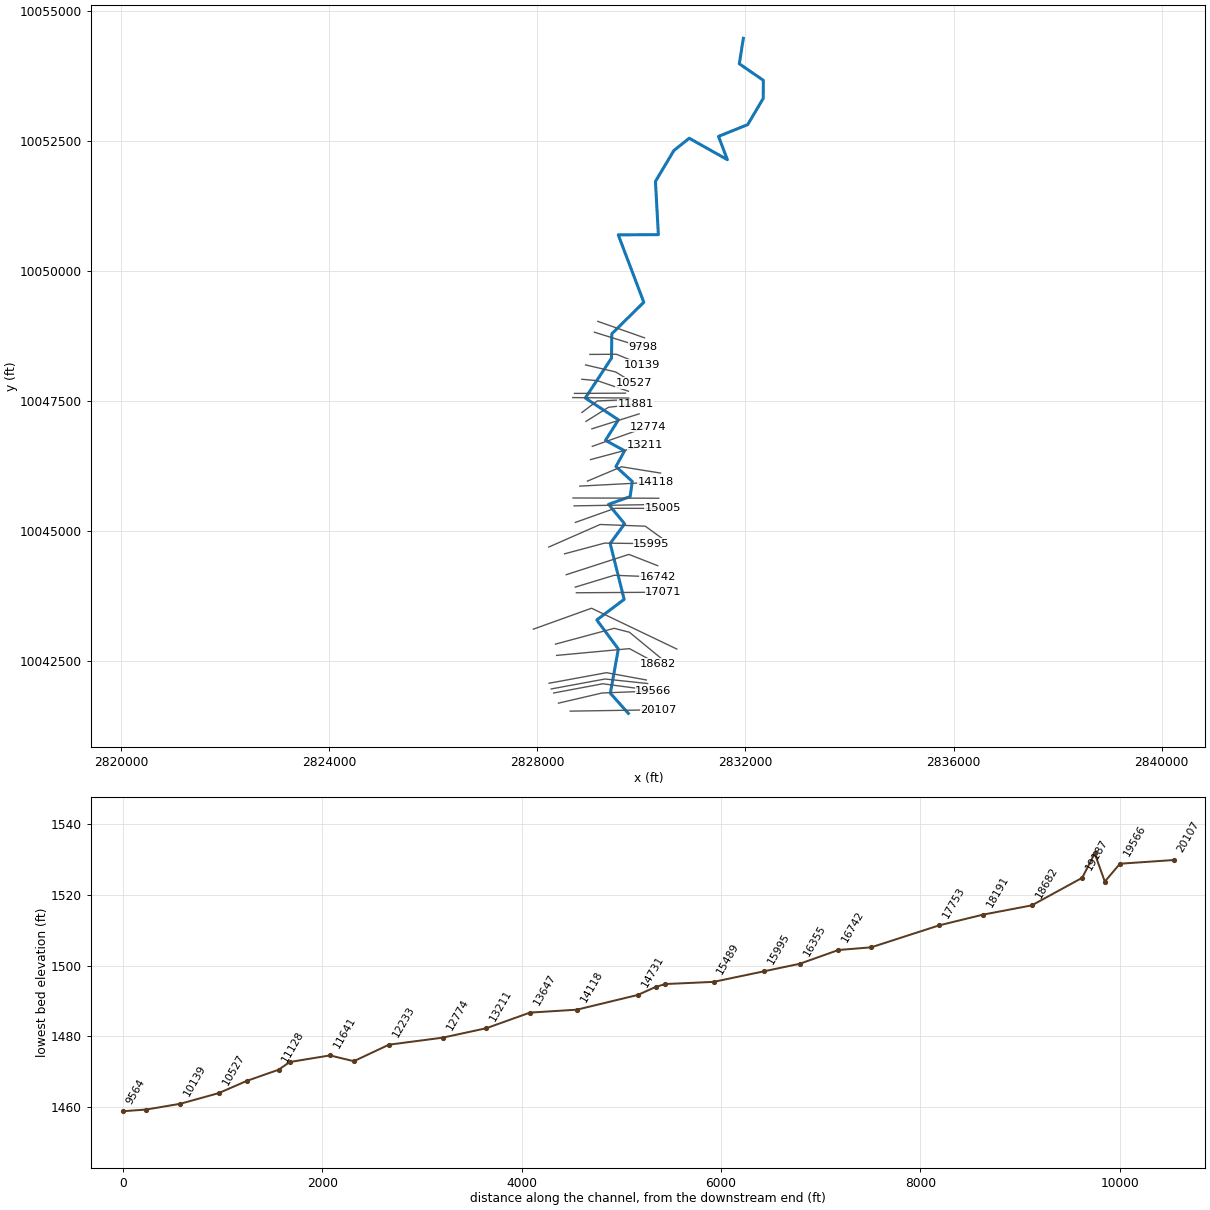
--- UNT007 IN SNOGR.prj (project) ---

Proj Title=UNT007 IN SNOGR Base Level Engineering
Current Plan=p01
Default Exp/Contr=0.3,0.1
English Units
Geom File=g01
Flow File=f01
Plan File=p01
BEGIN DESCRIPTION:
UNT007 IN SNOGR
END DESCRIPTION:

--- UNT007 IN SNOGR.p01 (plan) ---

Plan Title=Multiple Run
Short Identifier=Multiple
Geom File=g01
Flow File=f01
Subcritical Flow
K Sum by GR= 0
Std Step Tol= 0.01
Critical Tol= 0.01
Num of Std Step Trials= 20
Max Error Tol= 0.3
Flow Tol Ratio= 0.001
Split Flow NTrial= 30
Split Flow Tol= 0.02
Split Flow Ratio= 0.02
Log Output Level= 0
Friction Slope Method= 1
Unsteady Friction Slope Method= 2
Unsteady Bridges Friction Slope Method= 1
Parabolic Critical Depth
Global Vel Dist=  1 , 1 , 1
Global Log Level= 0
CheckData=True
Encroach Param= -1, 0, 0, 0
BEGIN DESCRIPTION:
Multiple Run
END DESCRIPTION:

--- UNT007 IN SNOGR.f01 (steady flow) ---

Flow Title=Multiple
Number of Profiles=7
Profile Names=10-year,25-year,50-year,1pct_min,100-year,1pct_plu,500-year
River Rch & RM= UNT007 IN SNOGR,Reach-1,20107
     957    1396    1780    1662    2247    3039    3595
River Rch & RM= UNT007 IN SNOGR,Reach-1,19566
    1337    1968    2522    2362    3194    4319    5144
River Rch & RM= UNT007 IN SNOGR,Reach-1,9259
    1615    2387    3068    2878    3893    5264    6293
Boundary for River Rch & Prof#=UNT007 IN SNOGR,Reach-1,1
Up Type=0
Dn Type=3
Dn Slope=0.005
Boundary for River Rch & Prof#=UNT007 IN SNOGR,Reach-1,2
Up Type=0
Dn Type=3
Dn Slope=0.005
Boundary for River Rch & Prof#=UNT007 IN SNOGR,Reach-1,3
Up Type=0
Dn Type=3
Dn Slope=0.005
Boundary for River Rch & Prof#=UNT007 IN SNOGR,Reach-1,4
Up Type=0
Dn Type=3
Dn Slope=0.005
Boundary for River Rch & Prof#=UNT007 IN SNOGR,Reach-1,5
Up Type=0
Dn Type=3
Dn Slope=0.005
Boundary for River Rch & Prof#=UNT007 IN SNOGR,Reach-1,6
Up Type=0
Dn Type=3
Dn Slope=0.005
Boundary for River Rch & Prof#=UNT007 IN SNOGR,Reach-1,7
Up Type=0
Dn Type=3
Dn Slope=0.005

--- UNT007 IN SNOGR.g01 (geometry) ---

Geom Title=Existing Conditions

River Reach=UNT007 IN SNOGR,Reach-1
Reach XY= 30
      2829748.47     10041493.73      2829403.25     10041880.58
      2829555.73     10042732.43      2829142.14     10043289.95
      2829667.91     10043686.28      2829399.98     10044760.66
      2829676.84     10045138.22      2829369.71     10045513.49
      2829783.35     10045662.06      2829824.39     10045953.08
      2829510.17     10046239.63      2829676.42     10046542.85
      2829309.37     10046744.31      2829558.55     10047138.33
      2828921.96     10047557.77      2829425.10     10048325.15
      2829430.80     10048792.90      2830045.67     10049399.45
      2829554.98     10050695.29      2830325.58     10050699.86
      2830269.57     10051723.28      2830623.61     10052316.60
      2830918.60     10052552.86      2831651.89     10052140.87
      2831481.34     10052588.83      2832042.69     10052814.93
      2832340.75     10053319.10      2832343.56     10053666.41
      2831881.01     10053984.95      2831958.51     10054474.32

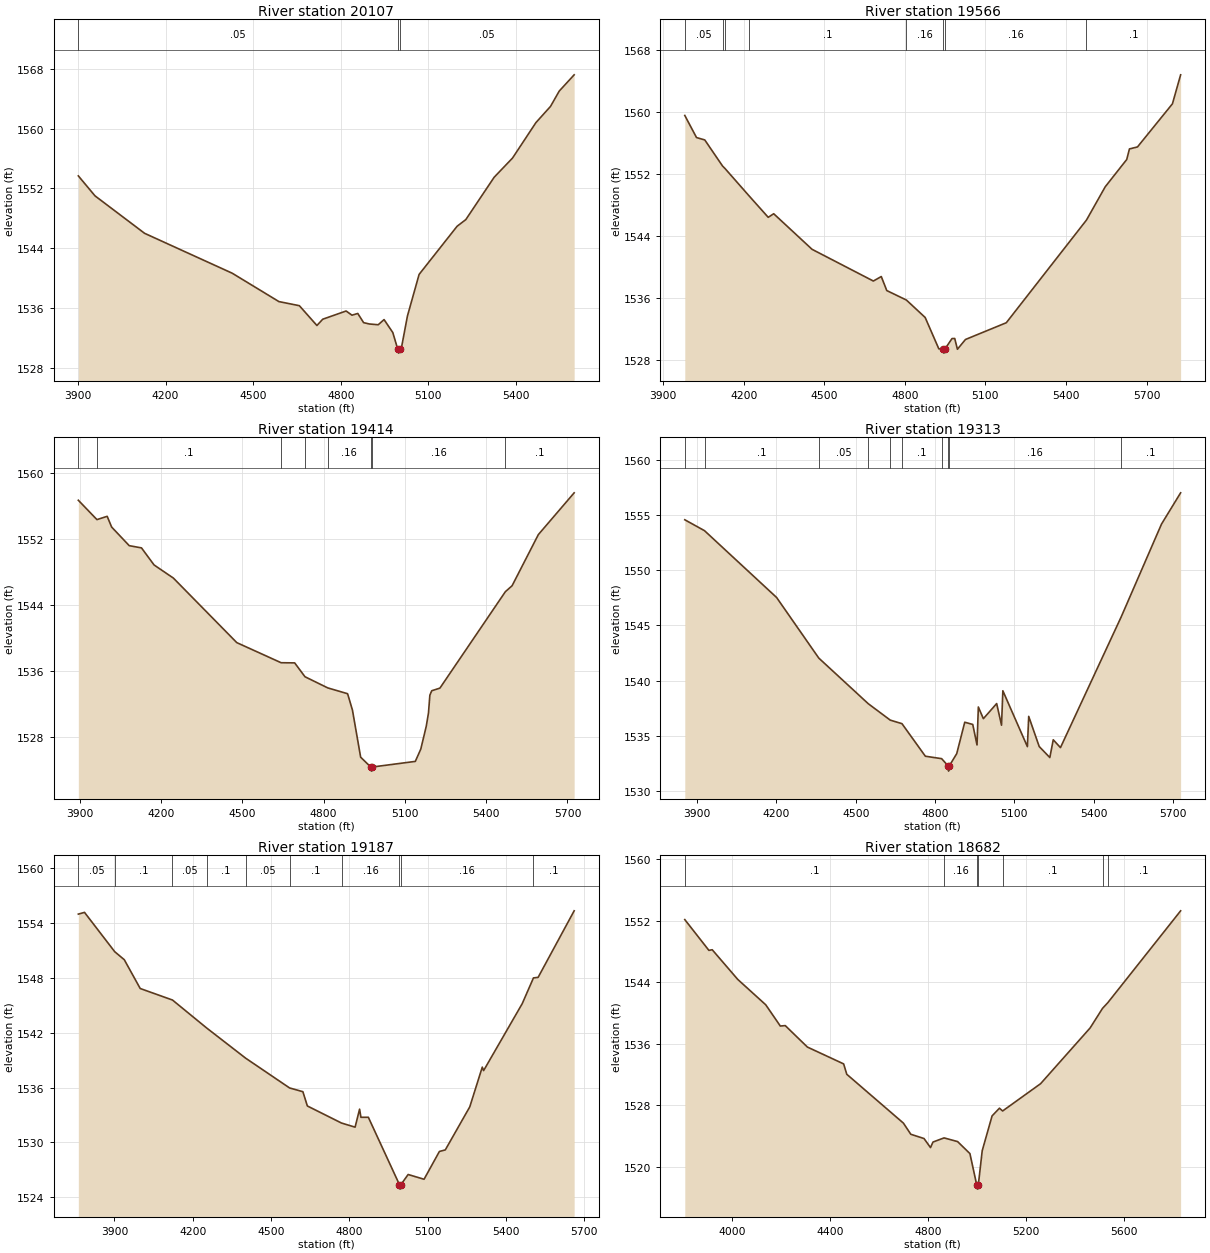
Type RM Length L Ch R = 1,20107,541,541,541
BEGIN DESCRIPTION:
UNT007 IN SNOGR 34.0
END DESCRIPTION:
XS GIS Cut Line= 2
      2828631.51     10041536.87      2830329.41     10041562.91
#Sta/Elev= 30
  3901.4 1553.66  3958.4 1550.99  4128.4 1545.97  4428.4 1540.63  4588.4 1536.83
  4658.4 1536.28  4718.5 1533.63  4738.5 1534.47  4818.5 1535.57  4838.5 1535.01
  4858.5 1535.24  4878.5 1534.01  4898.5 1533.83  4928.5 1533.73  4948.5 1534.42
  4978.5 1532.68  4995.5 1530.43  4998.2 1529.93  5001.5 1530.43  5008.5 1530.75
  5028.5 1534.90  5068.5 1540.47  5198.5 1546.91  5228.5 1547.81  5325.4 1553.47
  5388.5 1556.05  5468.5 1560.79  5518.5 1562.96  5548.5 1565.02  5599.5 1567.19
#Mann=3,-1,0
  3901.4    0.05       0  4995.5    0.04       0  5001.5    0.05       0
Bank Sta=4995.5,5001.5
Exp/Cntr=0.3,0.1

Type RM Length L Ch R = 1,19566,152,152,152
BEGIN DESCRIPTION:
UNT007 IN SNOGR 33.0
END DESCRIPTION:
XS GIS Cut Line= 3
      2828406.00     10041690.18      2829243.71     10041885.51
      2830228.95     10041924.57
#Sta/Elev= 30
  3980.8 1559.54  4024.4 1556.69  4055.2 1556.38  4121.3 1553.02  4130.9 1552.68
  4219.5 1549.19  4291.4 1546.40  4311.9 1546.86  4454.7 1542.27  4682.9 1538.18
  4712.4 1538.76  4732.9 1536.95  4805.9 1535.73  4875.8 1533.48  4926.6 1529.44
  4942.8 1529.38  4945.6 1528.88  4948.8 1529.38  4975.8 1530.76  4985.9 1530.77
  4995.9 1529.38  5025.9 1530.64  5177.9 1532.80  5476.5 1546.05  5546.3 1550.34
  5626.4 1553.86  5636.4 1555.22  5666.4 1555.48  5796.5 1561.04  5827.0 1564.78
#Mann=8,-1,0
  3980.8    0.05       0  4121.3     0.1       0  4130.9    0.05       0
  4219.5     0.1       0  4805.9    0.16       0  4942.8    0.07       0
  4948.8    0.16       0  5476.5     0.1       0
Bank Sta=4942.8,4948.8
Exp/Cntr=0.3,0.1

Type RM Length L Ch R = 1,19414,101,101,101
BEGIN DESCRIPTION:
Mapping XS 0052ca26
END DESCRIPTION:
XS GIS Cut Line= 3
      2828313.78     10041885.83      2829256.47     10042062.91
      2830119.55     10041948.52
#Sta/Elev= 30
  3894.8 1556.68  3963.5 1554.33  4001.3 1554.73  4017.7 1553.43  4082.7 1551.17
  4127.9 1550.90  4174.3 1548.83  4245.5 1547.24  4479.5 1539.41  4643.1 1536.97
  4693.2 1536.95  4731.2 1535.27  4815.0 1533.92  4888.5 1533.21  4906.4 1531.23
  4936.7 1525.51  4974.0 1524.32  4976.8 1523.82  4980.0 1524.32  5138.4 1525.00
  5158.6 1526.49  5178.8 1529.26  5187.0 1530.87  5192.1 1533.03  5199.0 1533.57
  5229.2 1533.89  5470.8 1545.59  5495.6 1546.31  5592.4 1552.51  5724.6 1557.58
#Mann=8,-1,0
  3894.8    0.05       0  3963.5     0.1       0  4643.1    0.05       0
  4731.2     0.1       0  4815.0    0.16       0  4974.0    0.07       0
  4980.0    0.16       0  5470.8     0.1       0
Bank Sta=4974,4980
Exp/Cntr=0.3,0.1

Type RM Length L Ch R = 1,19313,126,126,126
BEGIN DESCRIPTION:
Mapping XS 7ba04b2a
END DESCRIPTION:
XS GIS Cut Line= 3
      2828267.09     10041963.62      2829300.13     10042154.60
      2830120.41     10042067.80
#Sta/Elev= 30
  3853.2 1554.57  3927.8 1553.58  4200.4 1547.53  4360.0 1542.04  4547.0 1537.91
  4630.3 1536.42  4674.6 1536.10  4763.1 1533.15  4824.6 1532.93  4848.2 1532.30
  4851.0 1531.80  4854.2 1532.30  4881.7 1533.38  4912.1 1536.23  4942.3 1536.03
  4958.5 1534.17  4963.5 1537.61  4982.5 1536.55  5032.8 1537.92  5051.2 1535.96
  5056.2 1539.08  5149.0 1534.02  5154.0 1536.76  5193.7 1534.03  5233.9 1533.03
  5246.8 1534.64  5274.1 1533.93  5504.0 1545.78  5656.3 1554.18  5728.6 1557.01
#Mann=10,-1,0
  3853.2    0.05       0  3927.8     0.1       0  4360.0    0.05       0
  4547.0     0.1       0  4630.3    0.05       0  4674.6     0.1       0
  4824.6    0.16       0  4848.2    0.07       0  4854.2    0.16       0
  5504.0     0.1       0
Bank Sta=4848.2,4854.2
Exp/Cntr=0.3,0.1

Type RM Length L Ch R = 1,19187,505,505,505
BEGIN DESCRIPTION:
UNT007 IN SNOGR 32.0
END DESCRIPTION:
XS GIS Cut Line= 3
      2828225.20     10042073.32      2829329.39     10042276.45
      2830094.28     10042135.96
#Sta/Elev= 30
  3761.7 1554.98  3785.4 1555.17  3901.1 1550.87  3937.9 1549.99  3998.9 1546.84
  4122.6 1545.58  4253.6 1542.52  4402.9 1539.22  4571.4 1535.96  4622.4 1535.55
  4639.5 1533.99  4770.5 1532.12  4822.5 1531.67  4839.7 1533.64  4844.8 1532.75
  4873.3 1532.75  4992.3 1525.39  4995.1 1524.89  4998.3 1525.39  5025.8 1526.49
  5086.8 1525.97  5145.6 1529.01  5168.2 1529.18  5262.0 1533.89  5310.0 1538.24
  5315.1 1537.86  5463.0 1545.18  5506.1 1548.00  5524.0 1548.06  5662.1 1555.34
#Mann=10,-1,0
  3761.7    0.05       0  3901.1     0.1       0  4122.6    0.05       0
  4253.6     0.1       0  4402.9    0.05       0  4571.4     0.1       0
  4770.5    0.16       0  4992.3    0.07       0  4998.3    0.16       0
  5506.1     0.1       0
Bank Sta=4992.3,4998.3
Exp/Cntr=0.3,0.1

Type RM Length L Ch R = 1,18682,491,491,491
BEGIN DESCRIPTION:
UNT007 IN SNOGR 31.0
END DESCRIPTION:
XS GIS Cut Line= 3
      2828370.58     10042608.51      2829770.27     10042738.71
      2830312.79     10042445.75
#Sta/Elev= 30
  3807.9 1552.14  3906.2 1548.14  3919.8 1548.22  4024.0 1544.36  4138.2 1541.06
  4197.5 1538.30  4217.6 1538.36  4307.9 1535.57  4455.8 1533.38  4468.6 1532.03
  4699.6 1525.68  4729.8 1524.23  4783.5 1523.68  4810.1 1522.50  4820.1 1523.22
  4865.4 1523.76  4920.6 1523.28  4970.8 1521.72  4998.9 1517.60  5001.7 1517.10
  5004.9 1517.60  5021.0 1522.10  5061.2 1526.62  5091.3 1527.62  5104.2 1527.26
  5259.2 1530.81  5461.0 1538.05  5511.7 1540.60  5533.0 1541.33  5830.2 1553.28
#Mann=7,-1,0
  3807.9     0.1       0  4865.4    0.16       0  4998.9    0.07       0
  5004.9    0.16       0  5104.2     0.1       0  5511.7    0.16       0
  5533.0     0.1       0
Bank Sta=4998.9,5004.9
Exp/Cntr=0.3,0.1

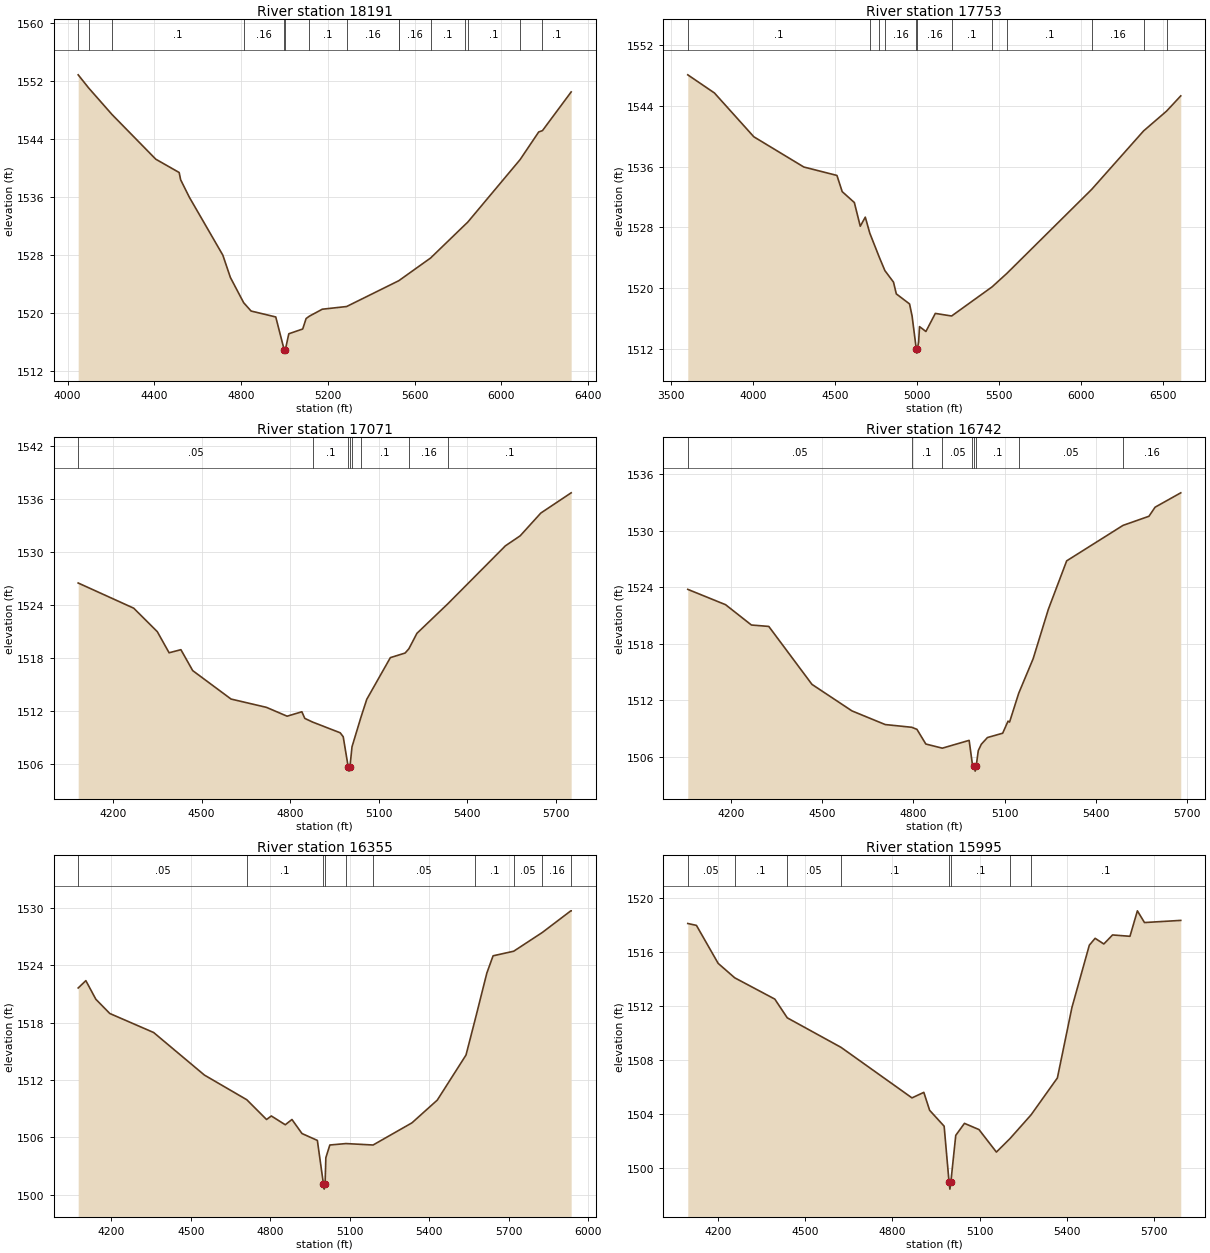
Type RM Length L Ch R = 1,18191,438,438,438
BEGIN DESCRIPTION:
UNT007 IN SNOGR 30.0
END DESCRIPTION:
XS GIS Cut Line= 4
      2828348.84     10042825.52      2829477.30     10043129.34
      2829770.27     10043053.38      2830388.74     10042543.42
#Sta/Elev= 30
  4049.2 1552.86  4097.4 1551.05  4205.6 1547.37  4406.9 1541.22  4514.8 1539.38
  4521.6 1538.38  4561.5 1535.98  4716.1 1527.98  4750.9 1524.90  4812.1 1521.42
  4846.2 1520.27  4960.1 1519.45  4998.6 1514.96  5001.3 1514.46  5004.6 1514.96
  5020.2 1517.13  5084.4 1517.79  5100.0 1519.23  5115.1 1519.56  5174.8 1520.52
  5286.8 1520.89  5526.5 1524.44  5527.2 1524.45  5674.2 1527.59  5831.8 1532.15
  5844.9 1532.52  6086.6 1541.16  6172.5 1544.98  6189.7 1545.16  6322.1 1550.50
#Mann=15,-1,0
  4049.2     0.1       0  4097.4    0.05       0  4205.6     0.1       0
  4812.1    0.16       0  4998.6    0.07       0  5004.6    0.16       0
  5115.1     0.1       0  5286.8    0.16       0  5526.5     0.1       0
  5527.2    0.16       0  5674.2     0.1       0  5831.8    0.16       0
  5844.9     0.1       0  6086.6    0.16       0  6189.7     0.1       0
Bank Sta=4998.6,5004.6
Exp/Cntr=0.3,0.1

Type RM Length L Ch R = 1,17753,682,682,682
BEGIN DESCRIPTION:
Mapping XS 8dd9c879
END DESCRIPTION:
XS GIS Cut Line= 3
      2827922.89     10043112.84      2829040.90     10043515.60
      2830679.78     10042730.89
#Sta/Elev= 30
  3602.2 1548.09  3764.7 1545.70  4004.9 1539.93  4309.6 1535.95  4511.6 1534.84
  4543.5 1532.71  4617.7 1531.27  4653.7 1528.15  4684.4 1529.35  4711.8 1527.24
  4769.7 1524.07  4803.8 1522.31  4856.3 1520.79  4873.5 1519.24  4954.2 1517.92
  4969.7 1516.32  4995.5 1511.94  4998.2 1511.44  5001.5 1511.94  5009.5 1512.91
  5015.0 1514.93  5053.9 1514.29  5111.2 1516.67  5210.6 1516.33  5457.6 1520.17
  5548.0 1521.95  6064.4 1533.00  6380.8 1540.70  6520.9 1543.31  6607.6 1545.32
#Mann=12,-1,0
  3602.2     0.1       0  4711.8    0.16       0  4769.7    0.05       0
  4803.8    0.16       0  4995.5    0.07       0  5001.5    0.16       0
  5210.6     0.1       0  5457.6    0.16       0  5548.0     0.1       0
  6064.4    0.16       0  6380.8     0.1       0  6520.9    0.16       0
Bank Sta=4995.5,5001.5
Exp/Cntr=0.3,0.1

Type RM Length L Ch R = 1,17071,329,329,329
BEGIN DESCRIPTION:
UNT007 IN SNOGR 29.0
END DESCRIPTION:
XS GIS Cut Line= 2
      2828750.26     10043812.93      2830421.33     10043823.78
#Sta/Elev= 30
  4081.7 1526.52  4269.9 1523.67  4349.9 1521.01  4389.9 1518.62  4429.9 1518.97
  4469.9 1516.60  4599.9 1513.38  4719.9 1512.44  4789.9 1511.44  4839.9 1511.94
  4849.9 1511.19  4876.0 1510.78  4969.9 1509.56  4980.1 1509.11  4996.9 1505.72
  4999.7 1505.22  5002.9 1505.72  5008.3 1507.46  5009.9 1507.98  5040.2 1511.32
  5059.9 1513.35  5139.9 1518.07  5189.9 1518.59  5202.8 1519.08  5229.9 1520.82
  5335.1 1524.18  5529.9 1530.73  5579.9 1531.86  5649.9 1534.44  5752.8 1536.73
#Mann=8,-1,0
  4081.7    0.05       0  4876.0     0.1       0  4996.9    0.07       0
  5002.9     0.1       0  5008.3    0.16       0  5040.2     0.1       0
  5202.8    0.16       0  5335.1     0.1       0
Bank Sta=4996.9,5002.9
Exp/Cntr=0.3,0.1

Type RM Length L Ch R = 1,16742,387,387,387
BEGIN DESCRIPTION:
UNT007 IN SNOGR 28.0
END DESCRIPTION:
XS GIS Cut Line= 3
      2828728.57     10043921.43      2829477.30     10044149.30
      2830312.82     10044116.75
#Sta/Elev= 30
  4059.3 1523.78  4183.4 1522.15  4268.3 1519.99  4325.3 1519.84  4467.1 1513.68
  4598.5 1510.86  4707.6 1509.41  4794.8 1509.12  4811.8 1508.90  4841.0 1507.34
  4895.1 1506.90  4983.2 1507.73  4994.0 1505.15  5000.2 1504.96  5003.0 1504.46
  5006.2 1504.96  5013.2 1506.64  5023.2 1507.32  5043.3 1508.03  5093.3 1508.49
  5110.9 1509.77  5115.9 1509.67  5145.9 1512.73  5193.4 1516.41  5243.4 1521.67
  5303.5 1526.81  5488.5 1530.58  5573.7 1531.55  5593.7 1532.51  5678.1 1534.04
#Mann=8,-1,0
  4059.3    0.05       0  4794.8     0.1       0  4895.1    0.05       0
  4994.0     0.1       0  5000.2    0.07       0  5006.2     0.1       0
  5145.9    0.05       0  5488.5    0.16       0
Bank Sta=5000.2,5006.2
Exp/Cntr=0.3,0.1

Type RM Length L Ch R = 1,16355,360,360,360
BEGIN DESCRIPTION:
Mapping XS 3f8f0f48
END DESCRIPTION:
XS GIS Cut Line= 3
      2828555.00     10044160.15      2829759.42     10044550.78
      2830312.81     10044333.76
#Sta/Elev= 30
  4074.7 1521.63  4103.6 1522.40  4141.4 1520.45  4194.0 1518.96  4359.4 1516.97
  4551.2 1512.51  4711.0 1509.93  4785.6 1507.86  4803.7 1508.23  4856.3 1507.31
  4881.5 1507.86  4919.4 1506.39  4977.4 1505.67  5000.5 1501.07  5003.2 1500.57
  5006.5 1501.07  5009.4 1503.86  5024.5 1505.19  5085.4 1505.34  5187.7 1505.19
  5334.4 1507.51  5429.9 1509.89  5538.4 1514.61  5573.4 1518.38  5617.1 1523.20
  5640.6 1525.00  5718.4 1525.48  5826.2 1527.44  5934.0 1529.71  5935.3 1529.71
#Mann=10,-1,0
  4074.7    0.05       0  4711.0     0.1       0  5000.5    0.07       0
  5006.5     0.1       0  5085.4    0.16       0  5187.7    0.05       0
  5573.4     0.1       0  5718.4    0.05       0  5826.2    0.16       0
  5934.0    0.05       0
Bank Sta=5000.5,5006.5
Exp/Cntr=0.3,0.1

Type RM Length L Ch R = 1,15995,506,506,506
BEGIN DESCRIPTION:
UNT007 IN SNOGR 27.0
END DESCRIPTION:
XS GIS Cut Line= 3
      2828522.45     10044561.63      2829292.84     10044767.79
      2830193.47     10044756.94
#Sta/Elev= 30
  4094.9 1518.14  4124.7 1518.00  4199.6 1515.18  4256.6 1514.11  4394.7 1512.53
  4437.6 1511.14  4622.8 1508.95  4867.2 1505.20  4908.0 1505.61  4928.0 1504.28
  4978.0 1503.10  4995.0 1498.93  4997.8 1498.43  5001.0 1498.93  5018.0 1502.42
  5048.0 1503.31  5098.0 1502.85  5158.0 1501.18  5204.4 1502.17  5277.4 1503.94
  5368.1 1506.68  5418.1 1511.90  5478.1 1516.53  5498.1 1517.04  5528.1 1516.62
  5558.1 1517.29  5618.1 1517.19  5643.7 1519.08  5668.1 1518.21  5793.1 1518.37
#Mann=8,-1,0
  4094.9    0.05       0  4256.6     0.1       0  4437.6    0.05       0
  4622.8     0.1       0  4995.0    0.07       0  5001.0     0.1       0
  5204.4    0.05       0  5277.4     0.1       0
Bank Sta=4995,5001
Exp/Cntr=0.3,0.1

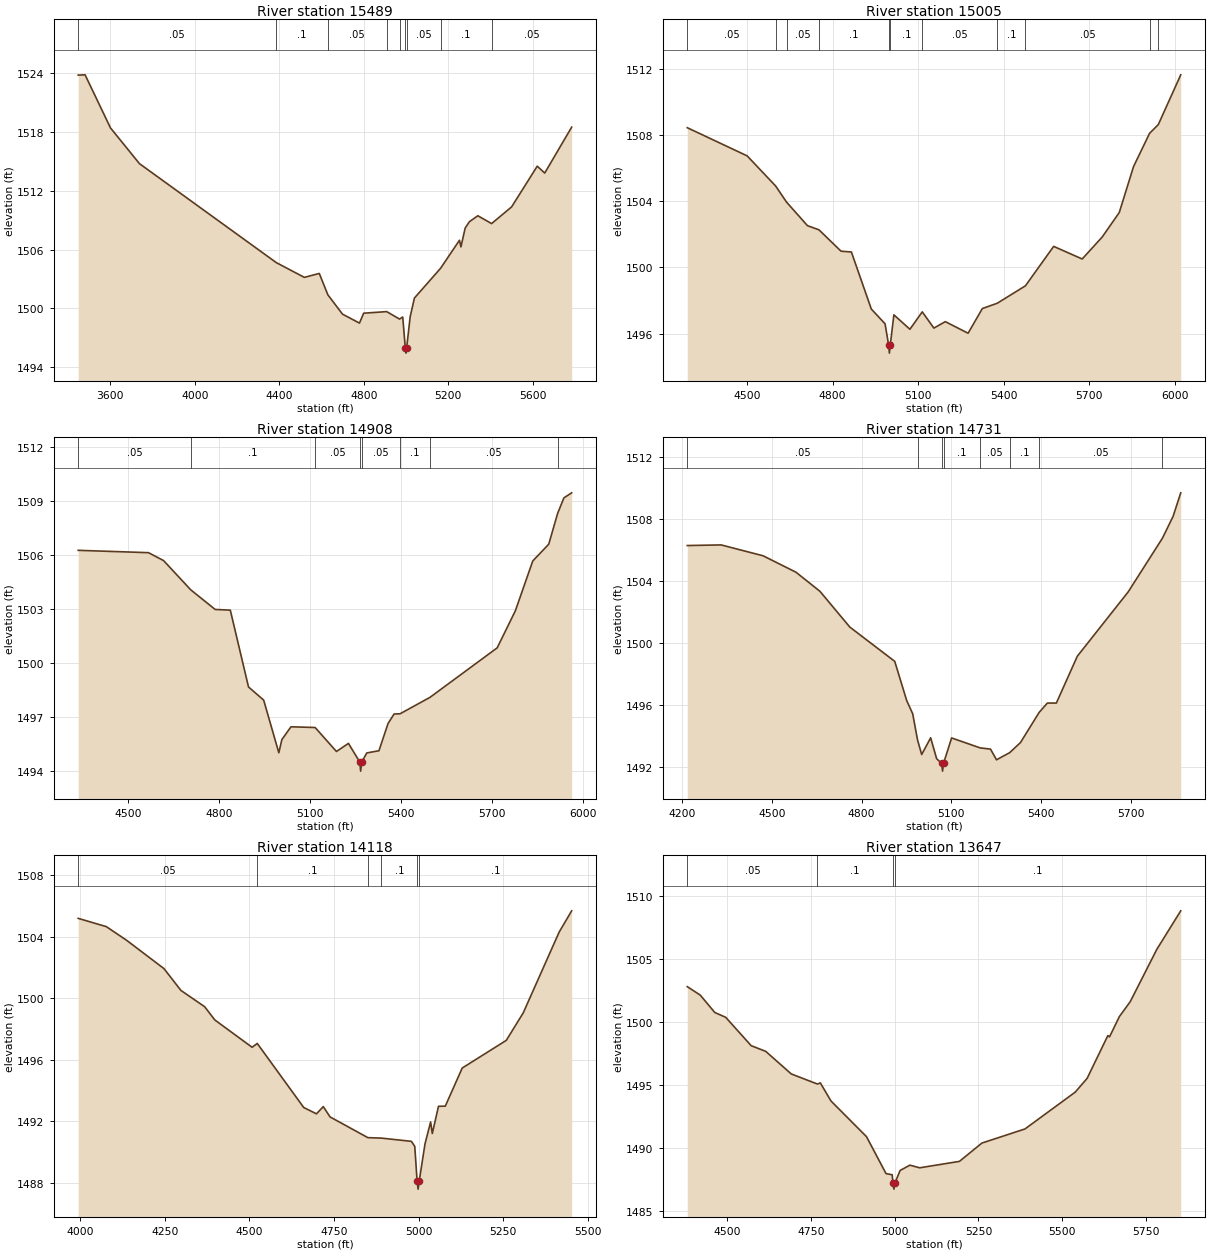
Type RM Length L Ch R = 1,15489,484,484,484
BEGIN DESCRIPTION:
UNT007 IN SNOGR 26.0
END DESCRIPTION:
XS GIS Cut Line= 4
      2828218.58     10044691.82      2829206.04     10045125.86
      2830074.09     10045093.31      2830388.75     10044865.46
#Sta/Elev= 30
  3448.1 1523.77  3480.7 1523.80  3600.9 1518.39  3738.0 1514.75  4386.0 1504.66
  4518.5 1503.16  4589.2 1503.56  4629.9 1501.38  4699.3 1499.41  4779.4 1498.50
  4799.4 1499.51  4908.4 1499.67  4969.0 1498.91  4984.2 1499.12  4996.5 1495.94
  4999.3 1495.44  5002.5 1495.94  5019.5 1499.15  5039.5 1501.05  5163.5 1504.09
  5252.7 1506.94  5259.7 1506.27  5279.7 1508.18  5299.7 1508.83  5339.7 1509.44
  5404.9 1508.64  5499.5 1510.34  5620.9 1514.49  5656.4 1513.79  5783.9 1518.47
#Mann=9,-1,0
  3448.1    0.05       0  4386.0     0.1       0  4629.9    0.05       0
  4908.4     0.1       0  4969.0    0.05       0  4996.5   0.035       0
  5002.5    0.05       0  5163.5     0.1       0  5404.9    0.05       0
Bank Sta=4996.5,5002.5
Exp/Cntr=0.3,0.1

Type RM Length L Ch R = 1,15005,97,97,97
BEGIN DESCRIPTION:
UNT007 IN SNOGR 25.0
END DESCRIPTION:
XS GIS Cut Line= 3
      2828730.61     10045165.89      2829492.32     10045437.16
      2830414.05     10045434.99
#Sta/Elev= 30
  4290.5 1508.43  4500.5 1506.73  4600.5 1504.91  4638.6 1503.94  4711.9 1502.52
  4752.2 1502.27  4829.6 1500.98  4866.0 1500.93  4935.8 1497.49  4984.0 1496.60
  4996.4 1495.33  4999.2 1494.83  5002.4 1495.33  5014.9 1497.14  5071.2 1496.27
  5114.4 1497.32  5155.2 1496.34  5195.2 1496.73  5275.2 1496.03  5325.2 1497.52
  5377.5 1497.84  5476.2 1498.89  5575.2 1501.27  5675.2 1500.51  5745.2 1501.83
  5805.2 1503.31  5855.2 1506.08  5911.5 1508.09  5942.2 1508.62  6020.8 1511.62
#Mann=11,-1,0
  4290.5    0.05       0  4600.5     0.1       0  4638.6    0.05       0
  4752.2     0.1       0  4996.4    0.07       0  5002.4     0.1       0
  5114.4    0.05       0  5377.5     0.1       0  5476.2    0.05       0
  5911.5     0.1       0  5942.2    0.05       0
Bank Sta=4996.4,5002.4
Exp/Cntr=0.3,0.1

Type RM Length L Ch R = 1,14908,177,177,177
BEGIN DESCRIPTION:
Mapping XS 98d2ce23
END DESCRIPTION:
XS GIS Cut Line= 2
      2828706.94     10045483.94      2830334.01     10045510.81
#Sta/Elev= 30
  4335.8 1506.25  4567.4 1506.12  4617.4 1505.68  4706.8 1504.06  4787.4 1502.97
  4837.4 1502.93  4897.4 1498.67  4947.4 1497.94  4997.4 1495.02  5007.4 1495.75
  5037.4 1496.46  5117.1 1496.42  5187.4 1495.09  5227.0 1495.54  5264.5 1494.50
  5267.2 1494.00  5270.5 1494.50  5287.5 1495.01  5327.5 1495.13  5357.5 1496.64
  5377.5 1497.17  5397.0 1497.18  5495.6 1498.09  5717.5 1500.84  5777.5 1502.90
  5834.8 1505.66  5887.5 1506.59  5916.6 1508.29  5937.5 1509.16  5963.1 1509.44
#Mann=8,-1,0
  4335.8    0.05       0  4706.8     0.1       0  5117.1    0.05       0
  5264.5    0.07       0  5270.5    0.05       0  5397.0     0.1       0
  5495.6    0.05       0  5916.6     0.1       0
Bank Sta=5264.5,5270.5
Exp/Cntr=0.3,0.1

Type RM Length L Ch R = 1,14731,613,613,613
BEGIN DESCRIPTION:
Mapping XS ea6c6b66
END DESCRIPTION:
XS GIS Cut Line= 2
      2828685.25     10045635.85      2830334.04     10045630.62
#Sta/Elev= 30
  4217.7 1506.30  4330.9 1506.34  4470.9 1505.64  4580.9 1504.58  4660.9 1503.35
  4760.9 1501.04  4910.9 1498.83  4950.9 1496.30  4970.9 1495.45  4987.0 1493.77
  5000.9 1492.82  5030.9 1493.90  5050.9 1492.55  5067.9 1492.25  5070.7 1491.75
  5073.9 1492.25  5100.9 1493.89  5196.1 1493.25  5230.9 1493.17  5250.9 1492.48
  5294.8 1492.94  5330.9 1493.59  5393.5 1495.54  5420.9 1496.14  5450.9 1496.14
  5520.9 1499.16  5690.9 1503.31  5805.5 1506.78  5840.9 1508.18  5866.5 1509.70
#Mann=8,-1,0
  4217.7    0.05       0  4987.0     0.1       0  5067.9    0.07       0
  5073.9     0.1       0  5196.1    0.05       0  5294.8     0.1       0
  5393.5    0.05       0  5805.5     0.1       0
Bank Sta=5067.9,5073.9
Exp/Cntr=0.3,0.1

Type RM Length L Ch R = 1,14118,471,471,471
BEGIN DESCRIPTION:
UNT007 IN SNOGR 24.0
END DESCRIPTION:
XS GIS Cut Line= 2
      2828815.42     10045863.71      2830271.39     10045940.63
#Sta/Elev= 30
  3994.4 1505.19  4077.6 1504.65  4137.6 1503.76  4247.8 1501.92  4297.9 1500.50
  4368.0 1499.44  4398.0 1498.58  4508.2 1496.80  4523.4 1497.05  4660.8 1492.88
  4698.4 1492.47  4718.5 1492.94  4738.5 1492.27  4850.2 1490.92  4890.1 1490.89
  4978.8 1490.68  4988.8 1490.35  4995.8 1488.07  4998.6 1487.57  5001.8 1488.07
  5018.9 1490.50  5035.6 1491.94  5040.6 1491.19  5058.9 1492.96  5079.0 1492.97
  5129.0 1495.45  5259.2 1497.25  5309.3 1499.04  5415.5 1504.30  5452.4 1505.68
#Mann=6,-1,0
  3994.4    0.05       0  4523.4     0.1       0  4850.2    0.05       0
  4890.1     0.1       0  4995.8    0.07       0  5001.8     0.1       0
Bank Sta=4995.8,5001.8
Exp/Cntr=0.3,0.1

Type RM Length L Ch R = 1,13647,436,436,436
BEGIN DESCRIPTION:
UNT007 IN SNOGR 23.0
END DESCRIPTION:
XS GIS Cut Line= 3
      2828962.84     10045960.17      2829616.02     10046235.77
      2830369.04     10046114.24
#Sta/Elev= 30
  4381.5 1502.79  4420.2 1502.12  4463.6 1500.74  4496.1 1500.36  4572.1 1498.11
  4615.5 1497.66  4691.7 1495.87  4769.6 1495.07  4778.3 1495.16  4810.3 1493.72
  4916.0 1490.90  4974.3 1487.97  4992.6 1487.88  4995.0 1487.24  4997.8 1486.74
  5001.0 1487.24  5016.3 1488.22  5045.4 1488.64  5074.6 1488.43  5193.2 1488.94
  5260.1 1490.39  5388.7 1491.51  5538.6 1494.43  5574.0 1495.52  5635.8 1498.91
  5640.8 1498.81  5670.3 1500.42  5702.6 1501.60  5781.7 1505.74  5853.2 1508.80
#Mann=4,-1,0
  4381.5    0.05       0  4769.6     0.1       0  4995.0    0.07       0
  5001.0     0.1       0
Bank Sta=4995,5001
Exp/Cntr=0.3,0.1

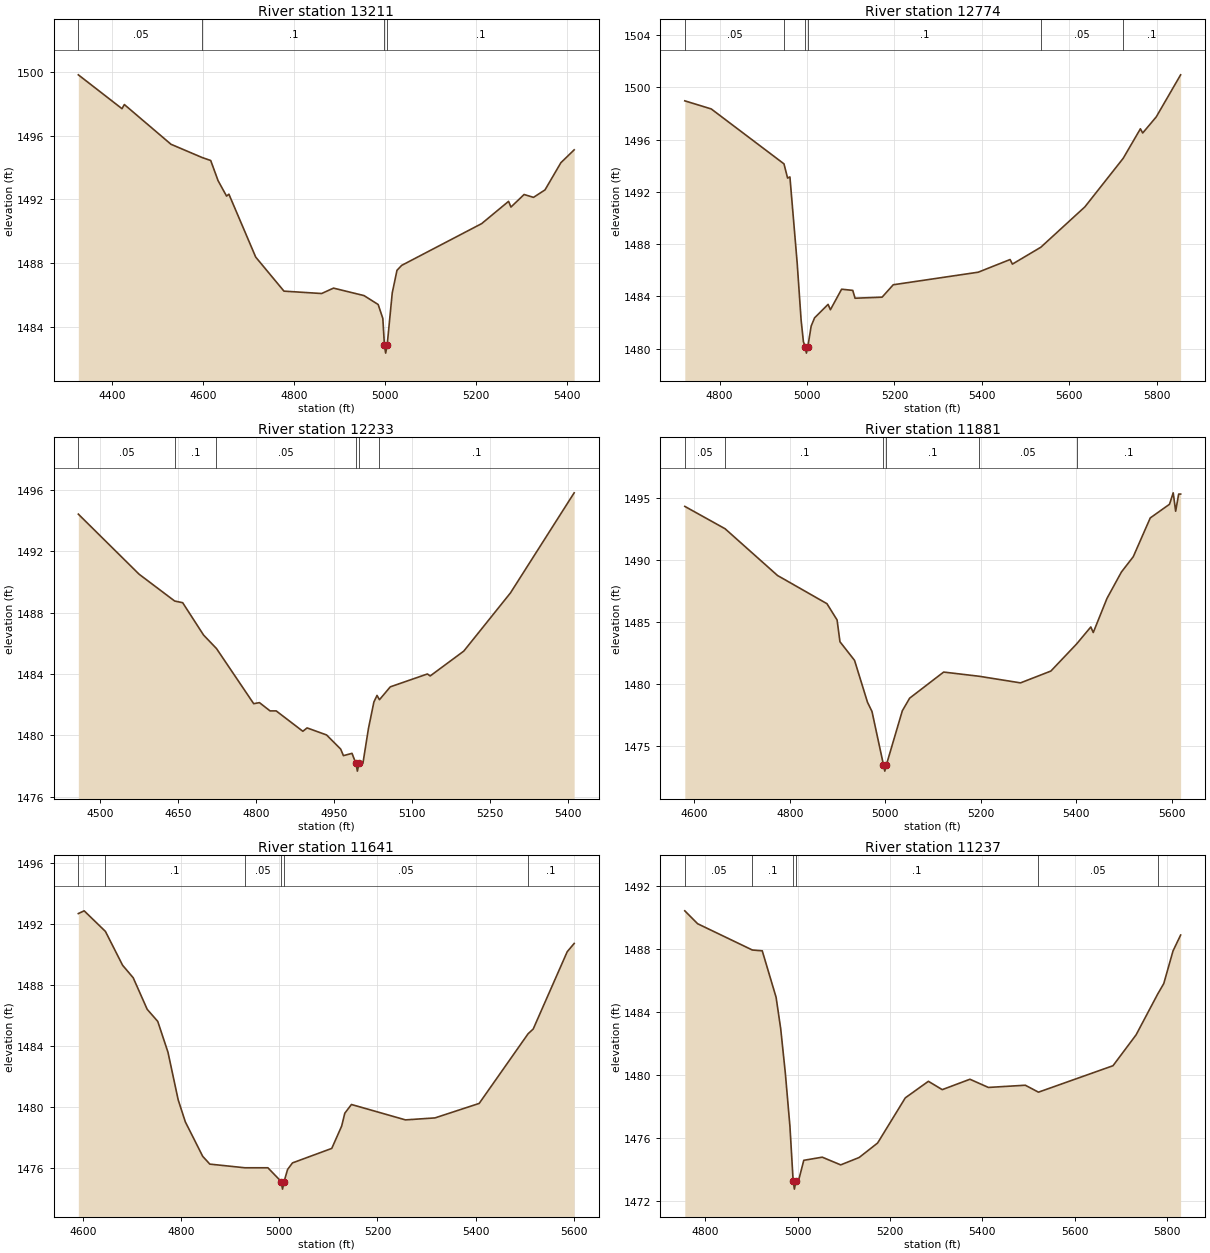
Type RM Length L Ch R = 1,13211,437,437,437
BEGIN DESCRIPTION:
UNT007 IN SNOGR 22.0
END DESCRIPTION:
XS GIS Cut Line= 2
      2829021.59     10046373.70      2830074.86     10046655.44
#Sta/Elev= 30
  4325.7 1499.84  4421.7 1497.71  4426.9 1497.97  4529.5 1495.47  4598.5 1494.63
  4616.8 1494.45  4633.0 1493.18  4651.7 1492.21  4656.8 1492.33  4715.8 1488.37
  4777.9 1486.23  4860.7 1486.08  4886.8 1486.42  4953.9 1485.95  4985.0 1485.39
  4995.3 1484.51  4998.8 1482.83  5001.5 1482.33  5004.8 1482.83  5016.0 1486.12
  5026.4 1487.54  5036.7 1487.85  5212.7 1490.48  5271.8 1491.88  5277.0 1491.52
  5305.9 1492.31  5326.6 1492.13  5351.9 1492.60  5386.8 1494.31  5416.0 1495.12
#Mann=4,-1,0
  4325.7    0.05       0  4598.5     0.1       0  4998.8    0.07       0
  5004.8     0.1       0
Bank Sta=4998.8,5004.8
Exp/Cntr=0.3,0.1

Type RM Length L Ch R = 1,12774,541,541,541
BEGIN DESCRIPTION:
UNT007 IN SNOGR 21.0
END DESCRIPTION:
XS GIS Cut Line= 2
      2829056.15     10046628.57      2830124.72     10047007.88
#Sta/Elev= 30
  4720.5 1498.96  4781.0 1498.34  4947.3 1494.14  4955.6 1493.05  4960.9 1493.14
  4977.6 1486.51  4986.5 1482.19  4991.8 1480.52  4995.9 1480.16  4998.6 1479.66
  5001.9 1480.16  5009.5 1481.73  5017.3 1482.36  5048.2 1483.39  5053.5 1482.98
  5079.1 1484.55  5104.6 1484.46  5109.9 1483.86  5171.7 1483.94  5197.2 1484.89
  5391.5 1485.85  5464.4 1486.82  5469.7 1486.47  5534.7 1487.76  5635.5 1490.85
  5723.0 1494.56  5762.4 1496.82  5767.7 1496.50  5798.6 1497.73  5854.4 1500.95
#Mann=6,-1,0
  4720.5    0.05       0  4947.3     0.1       0  4995.9    0.07       0
  5001.9     0.1       0  5534.7    0.05       0  5723.0     0.1       0
Bank Sta=4995.9,5001.9
Exp/Cntr=0.3,0.1

Type RM Length L Ch R = 1,12233,352,352,352
BEGIN DESCRIPTION:
UNT007 IN SNOGR 20.0
END DESCRIPTION:
XS GIS Cut Line= 2
      2829047.48     10046964.95      2829955.05     10047253.03
#Sta/Elev= 30
  4458.8 1494.43  4575.5 1490.51  4643.8 1488.76  4659.2 1488.65  4699.3 1486.54
  4724.1 1485.66  4795.6 1482.06  4806.6 1482.13  4827.0 1481.59  4838.8 1481.59
  4890.0 1480.26  4898.1 1480.48  4935.6 1480.02  4962.6 1479.10  4967.9 1478.67
  4984.4 1478.82  4991.9 1478.16  4994.7 1477.66  4997.9 1478.16  5005.4 1478.18
  5015.9 1480.43  5026.4 1482.17  5032.4 1482.60  5037.1 1482.32  5057.9 1483.16
  5129.2 1484.00  5134.5 1483.87  5199.0 1485.49  5288.7 1489.29  5411.0 1495.82
#Mann=6,-1,0
  4458.8    0.05       0  4643.8     0.1       0  4724.1    0.05       0
  4991.9   0.035       0  4997.9    0.05       0  5037.1     0.1       0
Bank Sta=4991.9,4997.9
Exp/Cntr=0.3,0.1

Type RM Length L Ch R = 1,11881,240,240,240
BEGIN DESCRIPTION:
UNT007 IN SNOGR 19.0
END DESCRIPTION:
XS GIS Cut Line= 3
      2828934.63     10047108.19      2829366.45     10047379.43
      2829891.61     10047440.19
#Sta/Elev= 30
  4579.9 1494.29  4664.3 1492.49  4774.1 1488.73  4877.7 1486.46  4898.9 1485.15
  4904.9 1483.40  4935.5 1481.90  4962.6 1478.53  4972.0 1477.79  4996.1 1473.49
  4998.8 1472.99  5002.1 1473.49  5035.6 1477.85  5050.9 1478.86  5122.1 1480.96
  5196.8 1480.62  5283.1 1480.09  5346.7 1481.04  5400.6 1483.22  5430.4 1484.59
  5435.5 1484.14  5464.3 1486.89  5494.5 1489.01  5519.3 1490.24  5554.9 1493.36
  5595.2 1494.46  5603.0 1495.38  5608.1 1493.90  5614.4 1495.28  5618.5 1495.28
#Mann=6,-1,0
  4579.9    0.05       0  4664.3     0.1       0  4996.1    0.07       0
  5002.1     0.1       0  5196.8    0.05       0  5400.6     0.1       0
Bank Sta=4996.1,5002.1
Exp/Cntr=0.3,0.1

Type RM Length L Ch R = 1,11641,404,404,404
BEGIN DESCRIPTION:
UNT007 IN SNOGR 18.0
END DESCRIPTION:
XS GIS Cut Line= 3
      2828856.49     10047279.62      2829149.44     10047500.96
      2829791.75     10047529.17
#Sta/Elev= 30
  4590.6 1492.70  4602.5 1492.88  4645.8 1491.53  4680.8 1489.31  4702.4 1488.49
  4730.9 1486.42  4752.4 1485.63  4773.2 1483.61  4794.0 1480.49  4808.6 1479.04
  4844.0 1476.78  4858.5 1476.27  4930.0 1476.03  4976.8 1476.03  5003.8 1475.13
  5006.6 1474.63  5009.8 1475.13  5016.9 1475.92  5026.9 1476.35  5106.9 1477.30
  5127.0 1478.76  5133.5 1479.61  5147.0 1480.18  5257.1 1479.17  5317.1 1479.30
  5407.2 1480.25  5506.9 1484.82  5517.3 1485.13  5586.6 1490.20  5600.7 1490.74
#Mann=6,-1,0
  4590.6    0.05       0  4645.8     0.1       0  4930.0    0.05       0
  5003.8   0.035       0  5009.8    0.05       0  5506.9     0.1       0
Bank Sta=5003.8,5009.8
Exp/Cntr=0.3,0.1

Type RM Length L Ch R = 1,11237,109,109,109
BEGIN DESCRIPTION:
Mapping XS 31e8761e
END DESCRIPTION:
XS GIS Cut Line= 2
      2828680.72     10047566.06      2829754.98     10047557.71
#Sta/Elev= 30
  4755.3 1490.43  4783.1 1489.61  4901.7 1487.94  4923.1 1487.89  4953.1 1484.94
  4963.1 1482.94  4973.1 1480.13  4983.1 1476.74  4990.1 1473.25  4992.8 1472.75
  4996.1 1473.25  5003.1 1473.44  5013.1 1474.58  5053.1 1474.78  5093.1 1474.29
  5133.1 1474.76  5173.1 1475.68  5233.1 1478.55  5283.1 1479.60  5313.1 1479.07
  5373.1 1479.73  5413.1 1479.21  5493.1 1479.35  5521.6 1478.91  5683.1 1480.59
  5733.1 1482.55  5779.5 1485.12  5793.1 1485.81  5813.1 1487.88  5829.6 1488.89
#Mann=6,-1,0
  4755.3    0.05       0  4901.7     0.1       0  4990.1    0.07       0
  4996.1     0.1       0  5521.6    0.05       0  5779.5     0.1       0
Bank Sta=4990.1,4996.1
Exp/Cntr=0.3,0.1

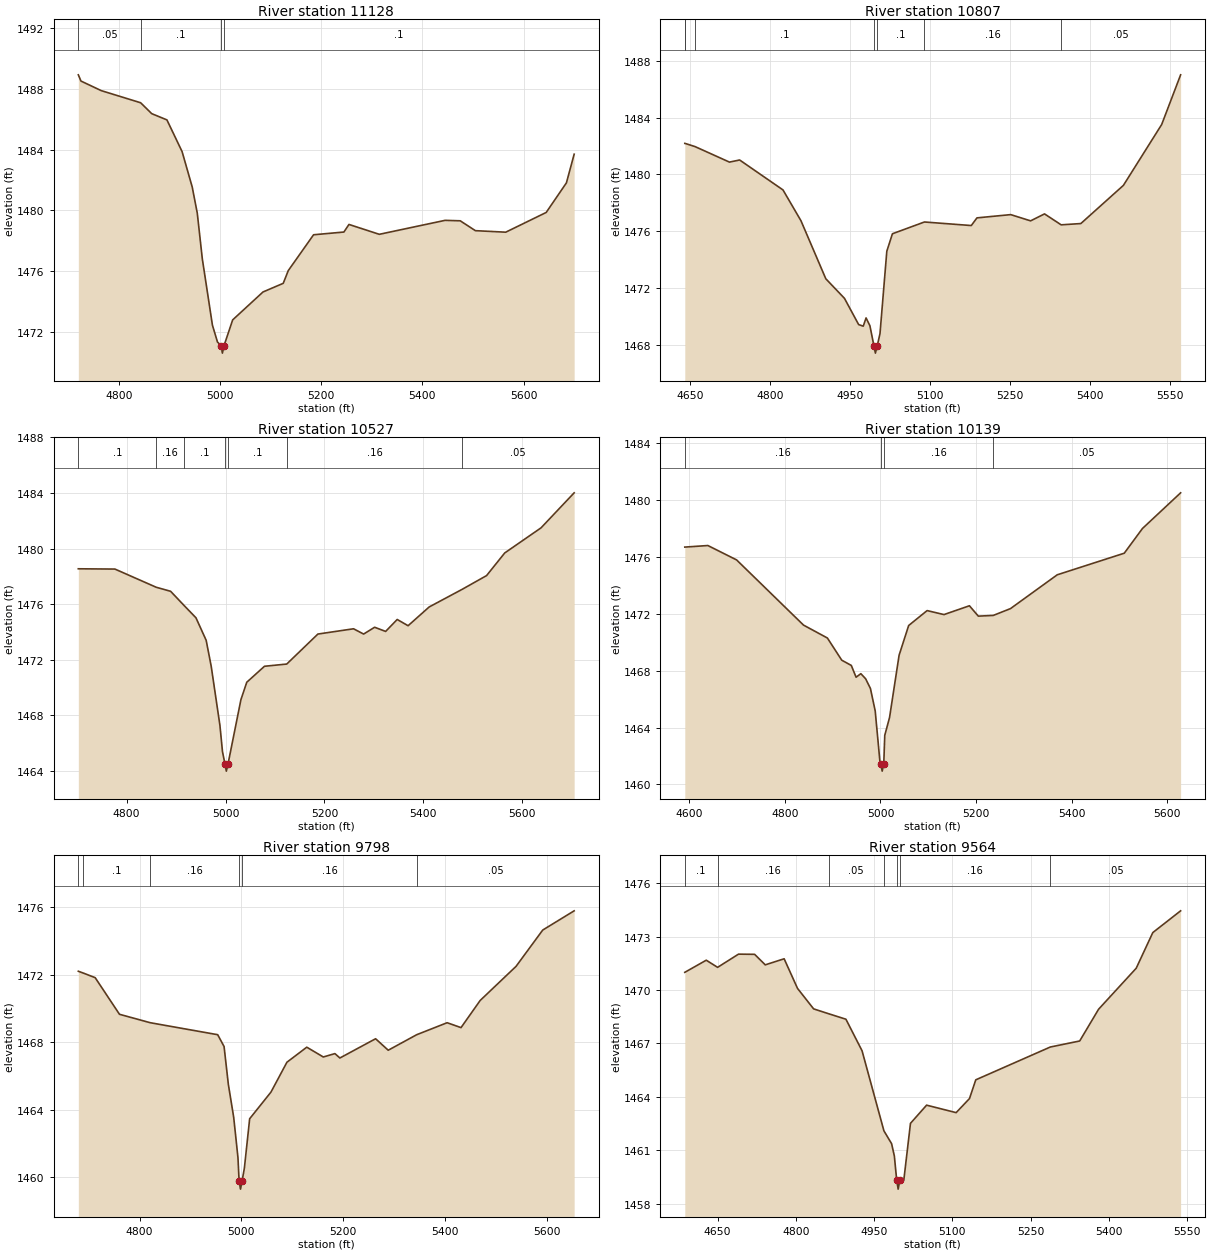
Type RM Length L Ch R = 1,11128,321,321,321
BEGIN DESCRIPTION:
Mapping XS 6d641f23
END DESCRIPTION:
XS GIS Cut Line= 2
      2828713.28     10047646.36      2829693.76     10047651.45
#Sta/Elev= 30
  4719.6 1488.93  4724.8 1488.52  4764.8 1487.89  4842.8 1487.09  4864.8 1486.37
  4894.8 1485.96  4924.8 1483.87  4944.8 1481.54  4954.8 1479.82  4964.8 1476.80
  4984.8 1472.43  4994.8 1471.32  5001.8 1471.09  5004.5 1470.59  5007.8 1471.09
  5024.8 1472.78  5084.8 1474.62  5124.8 1475.19  5134.8 1476.03  5184.8 1478.39
  5244.8 1478.57  5254.8 1479.07  5314.8 1478.42  5444.8 1479.34  5474.8 1479.31
  5504.8 1478.66  5564.8 1478.56  5644.8 1479.86  5684.8 1481.81  5700.1 1483.70
#Mann=4,-1,0
  4719.6    0.05       0  4842.8     0.1       0  5001.8    0.07       0
  5007.8     0.1       0
Bank Sta=5001.8,5007.8
Exp/Cntr=0.3,0.1

Type RM Length L Ch R = 1,10807,280,280,280
BEGIN DESCRIPTION:
UNT007 IN SNOGR 17.0
END DESCRIPTION:
XS GIS Cut Line= 3
      2828855.16     10047918.49      2829153.34     10047891.15
      2829750.07     10047688.31
#Sta/Elev= 30
  4640.1 1482.19  4640.5 1482.19  4659.5 1481.96  4723.8 1480.87  4742.9 1481.02
  4824.2 1478.91  4857.9 1476.74  4904.5 1472.65  4939.5 1471.27  4966.1 1469.42
  4974.7 1469.31  4980.0 1469.89  4987.2 1469.34  4994.8 1467.91  4997.5 1467.41
  5000.8 1467.91  5006.1 1468.78  5018.9 1474.59  5029.4 1475.82  5089.4 1476.65
  5177.3 1476.40  5187.9 1476.94  5251.2 1477.17  5288.5 1476.73  5314.6 1477.22
  5345.8 1476.45  5382.7 1476.54  5462.5 1479.23  5534.3 1483.52  5569.8 1487.02
#Mann=7,-1,0
  4640.1     0.1       0  4640.5    0.16       0  4659.5     0.1       0
  4994.8    0.07       0  5000.8     0.1       0  5089.4    0.16       0
  5345.8    0.05       0
Bank Sta=4994.8,5000.8
Exp/Cntr=0.3,0.1

Type RM Length L Ch R = 1,10527,388,388,388
BEGIN DESCRIPTION:
UNT007 IN SNOGR 16.0
END DESCRIPTION:
XS GIS Cut Line= 3
      2828926.81     10048194.53      2829504.90     10048059.12
      2829853.65     10047845.71
#Sta/Elev= 30
  4702.3 1478.54  4776.3 1478.52  4859.8 1477.21  4888.9 1476.92  4916.6 1475.88
  4940.2 1475.01  4960.8 1473.39  4971.0 1471.52  4988.6 1467.27  4993.8 1465.37
  4998.9 1464.47  5001.6 1463.97  5004.9 1464.47  5031.1 1469.12  5042.9 1470.37
  5078.7 1471.52  5123.7 1471.68  5186.7 1473.84  5258.8 1474.22  5279.2 1473.84
  5301.4 1474.33  5323.7 1474.03  5347.1 1474.89  5369.1 1474.44  5411.7 1475.79
  5478.4 1477.06  5527.8 1478.05  5564.5 1479.68  5638.0 1481.49  5704.9 1484.01
#Mann=7,-1,0
  4702.3     0.1       0  4859.8    0.16       0  4916.6     0.1       0
  4998.9    0.07       0  5004.9     0.1       0  5123.7    0.16       0
  5478.4    0.05       0
Bank Sta=4998.9,5004.9
Exp/Cntr=0.3,0.1

Type RM Length L Ch R = 1,10139,341,341,341
BEGIN DESCRIPTION:
UNT007 IN SNOGR 15.0
END DESCRIPTION:
XS GIS Cut Line= 3
      2829010.14     10048395.92      2829520.53     10048399.39
      2830007.47     10048198.38
#Sta/Elev= 30
  4590.7 1476.70  4639.0 1476.81  4699.0 1475.80  4839.0 1471.21  4889.0 1470.30
  4919.0 1468.74  4939.0 1468.37  4949.0 1467.54  4959.0 1467.79  4969.0 1467.43
  4979.0 1466.75  4989.0 1465.17  4998.9 1461.60  5000.9 1461.43  5003.6 1460.93
  5006.9 1461.43  5009.0 1463.45  5019.0 1464.70  5039.0 1469.09  5059.0 1471.18
  5097.6 1472.23  5132.9 1471.95  5186.1 1472.57  5204.7 1471.84  5236.0 1471.89
  5272.0 1472.37  5369.8 1474.75  5510.0 1476.27  5548.1 1478.01  5627.9 1480.52
#Mann=4,-1,0
  4590.7    0.16       0  5000.9    0.07       0  5006.9    0.16       0
  5236.0    0.05       0
Bank Sta=5000.9,5006.9
Exp/Cntr=0.3,0.1

Type RM Length L Ch R = 1,9798,234,234,234
BEGIN DESCRIPTION:
Mapping XS 925ec11e
END DESCRIPTION:
XS GIS Cut Line= 2
      2829096.89     10048823.02      2830027.46     10048533.08
#Sta/Elev= 30
  4679.6 1472.22  4687.8 1472.13  4712.7 1471.84  4760.5 1469.67  4821.0 1469.17
  4953.6 1468.46  4966.1 1467.76  4974.5 1465.52  4985.0 1463.57  4993.4 1461.18
  4995.6 1459.81  4998.4 1459.31  5001.6 1459.81  5006.0 1460.55  5016.4 1463.48
  5058.3 1465.06  5089.7 1466.83  5128.7 1467.72  5161.2 1467.14  5184.0 1467.34
  5193.8 1467.08  5264.0 1468.22  5288.8 1467.54  5344.8 1468.46  5404.6 1469.17
  5431.9 1468.88  5469.6 1470.49  5540.1 1472.51  5592.5 1474.66  5654.3 1475.80
#Mann=6,-1,0
  4679.6    0.16       0  4687.8     0.1       0  4821.0    0.16       0
  4995.6    0.07       0  5001.6    0.16       0  5344.8    0.05       0
Bank Sta=4995.6,5001.6
Exp/Cntr=0.3,0.1

Type RM Length L Ch R = 1,9564,305,305,305
BEGIN DESCRIPTION:
UNT007 IN SNOGR 14.0
END DESCRIPTION:
XS GIS Cut Line= 2
      2829162.69     10049031.67      2830058.70     10048715.38
#Sta/Elev= 30
  4587.3 1470.99  4628.4 1471.67  4650.2 1471.27  4690.2 1472.01  4721.1 1472.00
  4741.5 1471.41  4777.7 1471.75  4803.3 1470.09  4834.2 1468.94  4862.7 1468.67
  4896.1 1468.36  4927.0 1466.59  4968.9 1462.10  4983.6 1461.38  4988.9 1460.69
  4993.4 1459.33  4996.2 1458.83  4999.4 1459.33  5007.0 1459.33  5019.8 1462.52
  5050.7 1463.54  5107.3 1463.12  5132.9 1463.91  5144.9 1464.96  5287.7 1466.80
  5344.1 1467.14  5380.3 1468.92  5452.4 1471.22  5484.2 1473.22  5537.5 1474.44
#Mann=7,-1,0
  4587.3     0.1       0  4650.2    0.16       0  4862.7    0.05       0
  4968.9    0.16       0  4993.4    0.07       0  4999.4    0.16       0
  5287.7    0.05       0
Bank Sta=4993.4,4999.4
Exp/Cntr=0.3,0.1