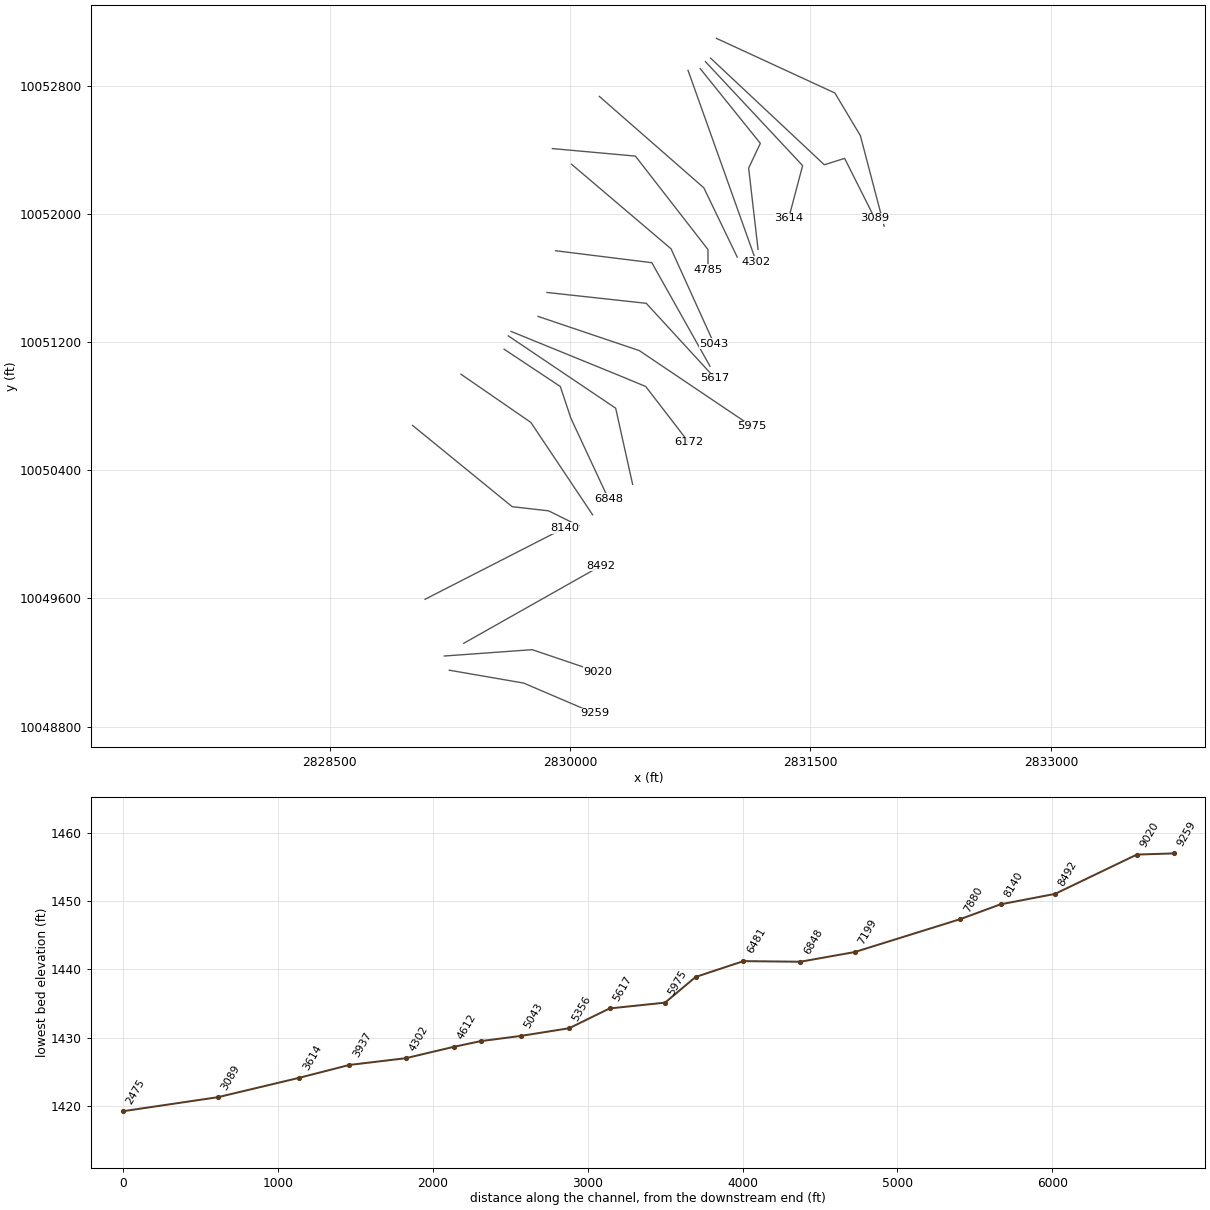
HEC-RAS study UNT007 IN SNOGR.prj: UNT007 IN SNOGR Base Level Engineering

--- UNT007 IN SNOGR.g01 (geometry) --- (continued)

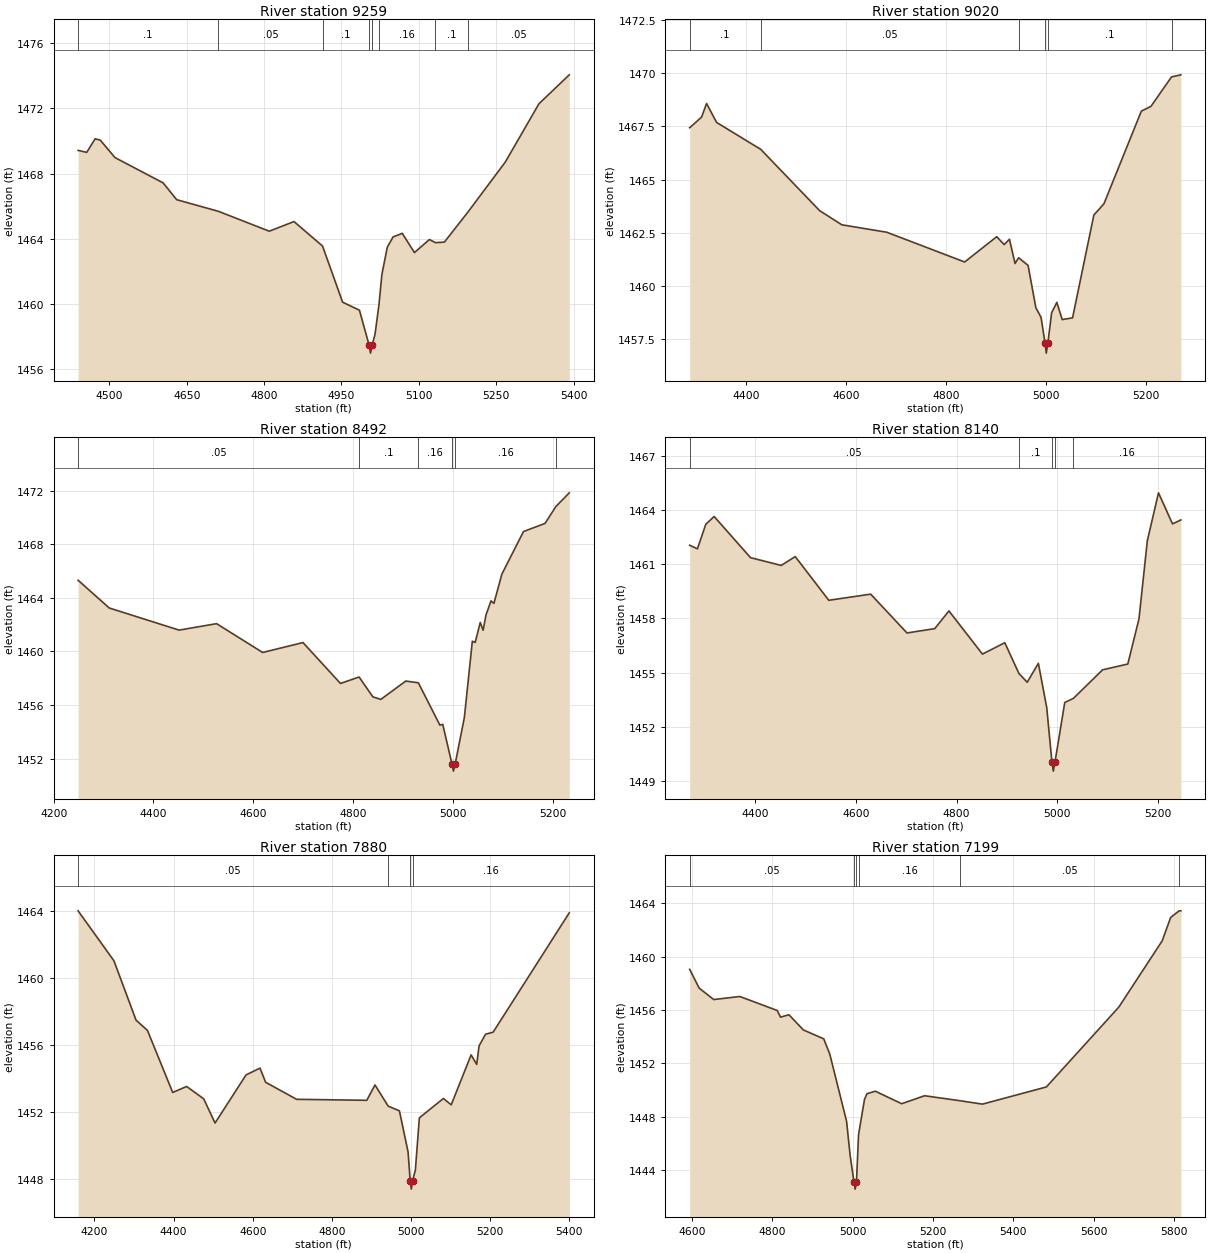
Type RM Length L Ch R = 1,9259,239,239,239
BEGIN DESCRIPTION:
Mapping XS a4b3a6dd
END DESCRIPTION:
XS GIS Cut Line= 3
      2829246.07     10049151.45      2829709.77     10049071.27
      2830152.44     10048882.05
#Sta/Elev= 30
  4439.5 1469.42  4456.3 1469.30  4472.4 1470.13  4482.5 1470.05  4511.0 1468.98
  4604.3 1467.43  4630.6 1466.40  4711.3 1465.69  4810.0 1464.47  4858.0 1465.06
  4913.3 1463.56  4952.2 1460.12  4984.8 1459.63  5003.5 1457.50  5006.3 1457.00
  5009.5 1457.50  5015.1 1458.17  5022.7 1459.98  5028.3 1461.81  5038.7 1463.48
  5050.0 1464.12  5067.8 1464.34  5091.4 1463.16  5120.4 1463.96  5132.0 1463.77
  5149.4 1463.80  5194.8 1465.63  5267.4 1468.70  5332.8 1472.28  5391.5 1474.05
#Mann=8,-1,0
  4439.5     0.1       0  4711.3    0.05       0  4913.3     0.1       0
  5003.5    0.07       0  5009.5     0.1       0  5022.7    0.16       0
  5132.0     0.1       0  5194.8    0.05       0
Bank Sta=5003.5,5009.5
Exp/Cntr=0.3,0.1

Type RM Length L Ch R = 1,9020,528,528,528
BEGIN DESCRIPTION:
Mapping XS 9e747b4e
END DESCRIPTION:
XS GIS Cut Line= 3
      2829214.76     10049239.99      2829763.58     10049279.60
      2830173.33     10049140.70
#Sta/Elev= 30
  4287.2 1467.44  4311.0 1467.94  4321.0 1468.58  4341.0 1467.69  4429.5 1466.42
  4547.1 1463.54  4591.7 1462.87  4681.7 1462.52  4837.4 1461.12  4901.6 1462.31
  4916.5 1461.94  4927.1 1462.19  4938.3 1461.05  4945.4 1461.32  4964.4 1460.96
  4979.9 1458.97  4990.4 1458.51  4998.1 1457.33  5000.8 1456.83  5004.1 1457.33
  5011.5 1458.73  5021.9 1459.22  5032.7 1458.41  5053.4 1458.49  5096.0 1463.33
  5116.2 1463.86  5191.0 1468.22  5210.4 1468.45  5251.4 1469.83  5270.1 1469.93
#Mann=6,-1,0
  4287.2     0.1       0  4429.5    0.05       0  4945.4     0.1       0
  4998.1    0.07       0  5004.1     0.1       0  5251.4    0.05       0
Bank Sta=4998.1,5004.1
Exp/Cntr=0.3,0.1

Type RM Length L Ch R = 1,8492,352,352,352
BEGIN DESCRIPTION:
Mapping XS d843851c
END DESCRIPTION:
XS GIS Cut Line= 2
      2829336.53     10049319.55      2830193.76     10049803.70
#Sta/Elev= 30
  4248.9 1465.31  4311.3 1463.24  4451.3 1461.59  4526.5 1462.07  4618.8 1459.92
  4699.7 1460.66  4774.8 1457.61  4812.1 1458.09  4839.8 1456.61  4855.7 1456.42
  4905.7 1457.79  4930.9 1457.66  4974.1 1454.50  4979.8 1454.56  4998.5 1451.57
  5001.2 1451.07  5004.5 1451.57  5023.1 1455.06  5039.1 1460.76  5044.8 1460.67
  5055.0 1462.16  5060.7 1461.58  5066.5 1462.72  5076.6 1463.77  5082.4 1463.58
  5098.3 1465.76  5141.6 1468.94  5184.9 1469.55  5206.4 1470.80  5233.4 1471.83
#Mann=6,-1,0
  4248.9    0.05       0  4812.1     0.1       0  4930.9    0.16       0
  4998.5    0.07       0  5004.5    0.16       0  5206.4     0.1       0
Bank Sta=4998.5,5004.5
Exp/Cntr=0.3,0.1

Type RM Length L Ch R = 1,8140,260,260,260
BEGIN DESCRIPTION:
UNT007 IN SNOGR 13.0
END DESCRIPTION:
XS GIS Cut Line= 2
      2829094.98     10049594.14      2829963.82     10050038.54
#Sta/Elev= 30
  4269.6 1462.05  4285.0 1461.85  4301.6 1463.21  4318.2 1463.64  4390.5 1461.36
  4451.5 1460.93  4479.3 1461.42  4546.0 1459.00  4629.2 1459.34  4701.4 1457.19
  4756.5 1457.43  4784.7 1458.41  4851.3 1456.02  4895.7 1456.65  4923.7 1454.95
  4940.2 1454.46  4962.4 1455.51  4979.0 1453.06  4989.4 1450.04  4992.1 1449.54
  4995.4 1450.04  5014.8 1453.34  5032.1 1453.57  5090.0 1455.15  5140.1 1455.47
  5162.3 1457.97  5178.9 1462.30  5201.1 1464.95  5228.9 1463.23  5245.5 1463.45
#Mann=5,-1,0
  4269.6    0.05       0  4923.7     0.1       0  4989.4    0.07       0
  4995.4     0.1       0  5032.1    0.16       0
Bank Sta=4989.4,4995.4
Exp/Cntr=0.3,0.1

Type RM Length L Ch R = 1,7880,681,681,681
BEGIN DESCRIPTION:
UNT007 IN SNOGR 12.0
END DESCRIPTION:
XS GIS Cut Line= 4
      2829017.03     10050678.93      2829638.58     10050171.96
      2829866.02     10050145.92      2830054.36     10050052.61
#Sta/Elev= 30
  4158.6 1464.04  4249.1 1461.05  4305.1 1457.49  4333.8 1456.88  4397.7 1453.16
  4432.9 1453.52  4476.0 1452.78  4504.7 1451.33  4583.0 1454.21  4618.2 1454.62
  4632.5 1453.77  4710.8 1452.75  4888.1 1452.69  4908.9 1453.61  4942.2 1452.34
  4970.6 1452.06  4992.5 1449.59  4997.8 1447.87  5000.6 1447.37  5003.8 1447.87
  5010.9 1448.51  5021.0 1451.64  5081.7 1452.80  5101.5 1452.42  5151.8 1455.41
  5165.9 1454.84  5171.9 1455.95  5188.3 1456.65  5207.4 1456.77  5399.8 1463.92
#Mann=4,-1,0
  4158.6    0.05       0  4942.2    0.16       0  4997.8    0.07       0
  5003.8    0.16       0
Bank Sta=4997.8,5003.8
Exp/Cntr=0.3,0.1

Type RM Length L Ch R = 1,7199,351,351,351
BEGIN DESCRIPTION:
UNT007 IN SNOGR 11.0
END DESCRIPTION:
XS GIS Cut Line= 3
      2829319.13     10050998.36      2829754.90     10050698.01
      2830140.30     10050121.65
#Sta/Elev= 30
  4594.6 1459.05  4618.1 1457.64  4654.5 1456.78  4719.3 1457.01  4812.4 1455.96
  4820.8 1455.46  4841.7 1455.64  4877.5 1454.50  4928.3 1453.83  4943.2 1452.70
  4985.1 1447.65  4993.9 1445.10  5003.7 1443.05  5006.5 1442.55  5009.7 1443.05
  5014.8 1446.56  5016.1 1446.85  5029.7 1449.28  5035.8 1449.71  5056.7 1449.90
  5122.3 1448.96  5179.2 1449.56  5268.6 1449.18  5323.3 1448.93  5482.5 1450.22
  5662.7 1456.21  5770.8 1461.19  5791.8 1462.94  5812.9 1463.44  5817.2 1463.44
#Mann=6,-1,0
  4594.6    0.05       0  5003.7   0.035       0  5009.7    0.05       0
  5016.1    0.16       0  5268.6    0.05       0  5812.9    0.16       0
Bank Sta=5003.7,5009.7
Exp/Cntr=0.3,0.1

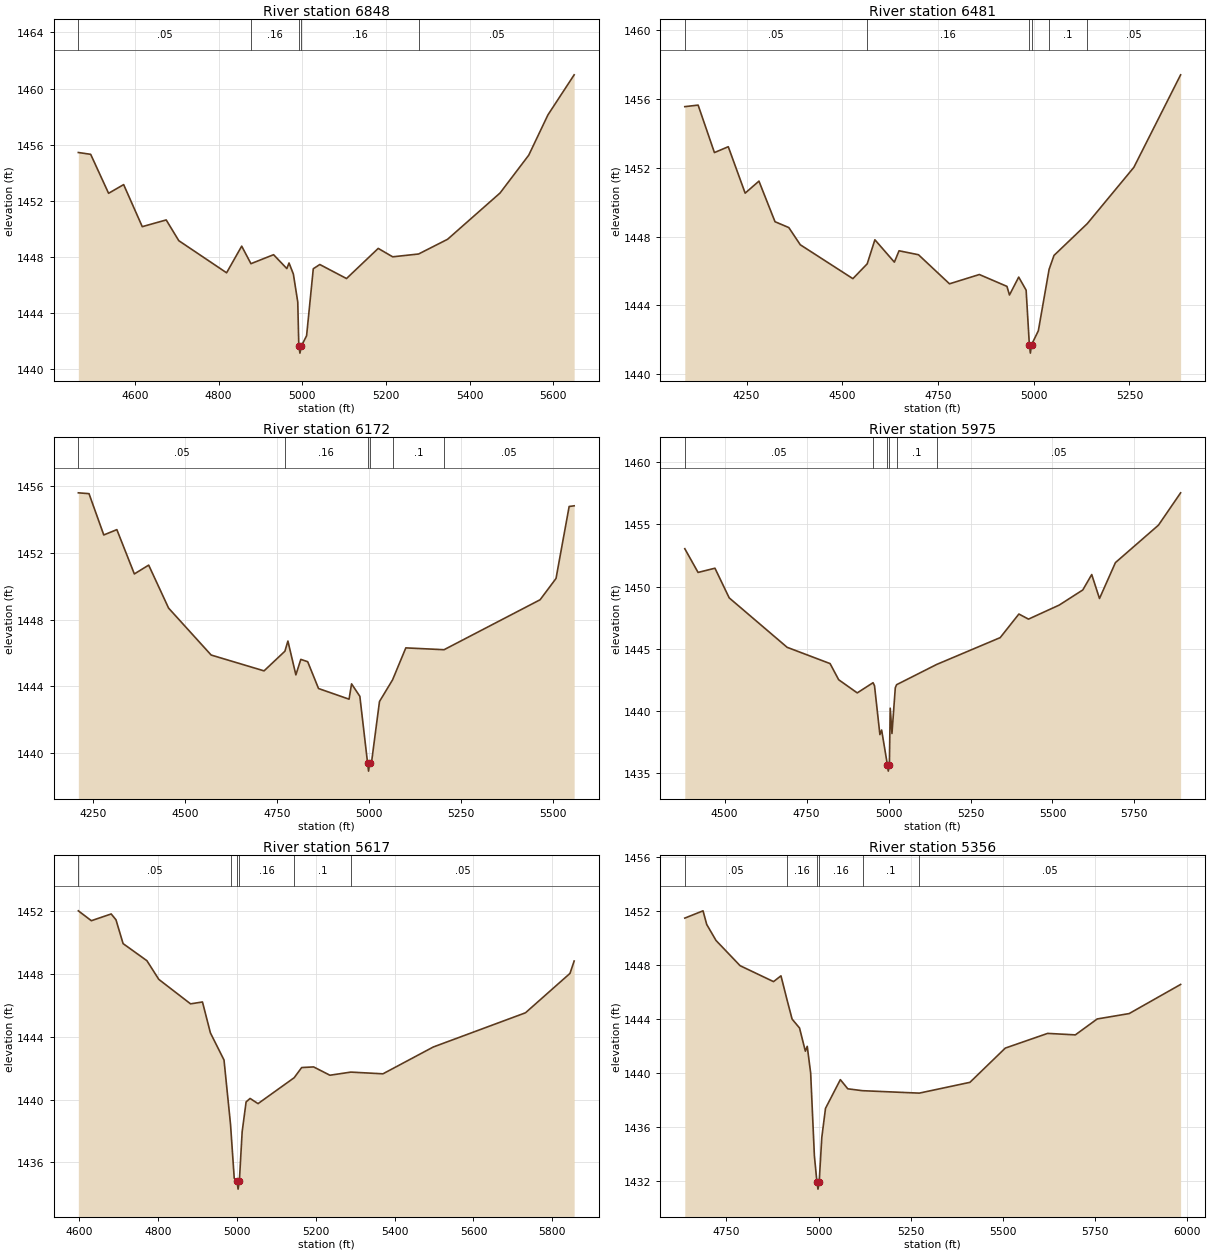
Type RM Length L Ch R = 1,6848,367,367,367
BEGIN DESCRIPTION:
Mapping XS 35d33e52
END DESCRIPTION:
XS GIS Cut Line= 4
      2829588.20     10051154.63      2829938.93     10050921.96
      2830004.90     10050724.05      2830239.30     10050220.54
#Sta/Elev= 30
  4465.0 1455.44  4494.5 1455.31  4537.3 1452.53  4573.3 1453.15  4617.8 1450.15
  4675.0 1450.63  4705.1 1449.15  4819.3 1446.86  4855.4 1448.76  4877.5 1447.51
  4931.6 1448.15  4963.3 1447.16  4968.5 1447.56  4978.9 1446.77  4989.4 1444.77
  4991.9 1441.63  4994.6 1441.13  4997.9 1441.63  5010.5 1442.37  5026.5 1447.15
  5042.1 1447.45  5105.9 1446.45  5181.7 1448.60  5216.2 1448.00  5278.1 1448.20
  5347.4 1449.25  5472.8 1452.55  5541.4 1455.25  5587.2 1458.12  5649.9 1460.98
#Mann=5,-1,0
  4465.0    0.05       0  4877.5    0.16       0  4991.9    0.07       0
  4997.9    0.16       0  5278.1    0.05       0
Bank Sta=4991.9,4997.9
Exp/Cntr=0.3,0.1

Type RM Length L Ch R = 1,6481,309,309,309
BEGIN DESCRIPTION:
UNT007 IN SNOGR 10.0
END DESCRIPTION:
XS GIS Cut Line= 3
      2829614.29     10051237.93      2830284.42     10050786.55
      2830390.32     10050310.87
#Sta/Elev= 30
  4088.5 1455.55  4123.3 1455.64  4165.9 1452.88  4202.1 1453.22  4246.2 1450.52
  4282.2 1451.22  4324.2 1448.86  4360.2 1448.52  4390.2 1447.52  4527.6 1445.55
  4565.0 1446.41  4585.1 1447.81  4636.0 1446.51  4648.2 1447.17  4699.0 1446.94
  4780.0 1445.25  4858.0 1445.79  4930.1 1445.10  4936.7 1444.60  4960.8 1445.64
  4980.2 1444.88  4988.6 1441.72  4991.3 1441.22  4994.6 1441.72  5012.1 1442.52
  5040.2 1446.09  5053.0 1446.90  5140.0 1448.75  5261.6 1452.02  5383.8 1457.40
#Mann=6,-1,0
  4088.5    0.05       0  4565.0    0.16       0  4988.6    0.07       0
  4994.6    0.16       0  5040.2     0.1       0  5140.0    0.05       0
Bank Sta=4988.6,4994.6
Exp/Cntr=0.3,0.1

Type RM Length L Ch R = 1,6172,197,197,197
BEGIN DESCRIPTION:
Mapping XS 1c207162
END DESCRIPTION:
XS GIS Cut Line= 4
      2829631.62     10051265.72      2830308.72     10050989.67
      2830471.92     10050921.96      2830739.26     10050574.77
#Sta/Elev= 30
  4210.3 1455.61  4239.3 1455.56  4279.4 1453.08  4314.9 1453.40  4362.4 1450.74
  4401.3 1451.27  4455.3 1448.69  4570.9 1445.87  4714.5 1444.92  4771.1 1446.10
  4779.3 1446.71  4800.9 1444.68  4814.3 1445.61  4833.0 1445.47  4862.4 1443.86
  4945.3 1443.22  4952.1 1444.14  4974.6 1443.39  4995.5 1439.40  4998.2 1438.90
  5001.5 1439.40  5006.2 1439.41  5027.9 1443.08  5063.4 1444.38  5099.4 1446.30
  5203.2 1446.19  5464.0 1449.19  5507.2 1450.47  5542.8 1454.79  5556.4 1454.83
#Mann=6,-1,0
  4210.3    0.05       0  4771.1    0.16       0  4995.5    0.07       0
  5001.5    0.16       0  5063.4     0.1       0  5203.2    0.05       0
Bank Sta=4995.5,5001.5
Exp/Cntr=0.3,0.1

Type RM Length L Ch R = 1,5975,358,358,358
BEGIN DESCRIPTION:
UNT007 IN SNOGR 9.0
END DESCRIPTION:
XS GIS Cut Line= 3
      2829800.08     10051359.45      2830431.99     10051145.92
      2831133.42     10050673.67
#Sta/Elev= 30
  4378.4 1453.05  4418.9 1451.14  4470.4 1451.48  4513.9 1449.09  4690.6 1445.11
  4821.6 1443.80  4847.8 1442.50  4904.5 1441.44  4952.7 1442.26  4957.2 1442.01
  4973.6 1438.08  4978.9 1438.45  4996.5 1435.64  4999.2 1435.14  5002.5 1435.64
  5005.1 1440.21  5010.4 1438.17  5020.6 1441.86  5024.6 1442.10  5146.8 1443.73
  5340.6 1445.89  5397.6 1447.79  5426.9 1447.38  5520.6 1448.51  5592.6 1449.73
  5619.8 1450.97  5643.5 1449.04  5692.1 1451.93  5823.5 1454.95  5891.0 1457.55
#Mann=6,-1,0
  4378.4    0.05       0  4952.7    0.16       0  4996.5    0.07       0
  5002.5    0.16       0  5024.6     0.1       0  5146.8    0.05       0
Bank Sta=4996.5,5002.5
Exp/Cntr=0.3,0.1

Type RM Length L Ch R = 1,5617,261,261,261
BEGIN DESCRIPTION:
Mapping XS 109d7ebd
END DESCRIPTION:
XS GIS Cut Line= 3
      2829855.64     10051508.77      2830475.39     10051441.06
      2830903.83     10050974.46
#Sta/Elev= 30
  4598.3 1452.03  4631.3 1451.40  4681.6 1451.83  4693.7 1451.46  4711.8 1449.94
  4772.2 1448.85  4802.3 1447.66  4882.8 1446.10  4913.0 1446.22  4933.1 1444.25
  4967.6 1442.52  4984.1 1438.42  4993.5 1434.99  5000.5 1434.79  5003.3 1434.29
  5006.5 1434.79  5013.6 1437.95  5023.6 1439.85  5033.7 1440.07  5053.8 1439.74
  5145.4 1441.39  5164.5 1442.04  5194.7 1442.08  5236.1 1441.55  5289.1 1441.75
  5370.5 1441.64  5498.1 1443.35  5731.8 1445.53  5844.6 1448.04  5855.2 1448.83
#Mann=6,-1,0
  4598.3    0.05       0  4984.1    0.16       0  5000.5    0.07       0
  5006.5    0.16       0  5145.4     0.1       0  5289.1    0.05       0
Bank Sta=5000.5,5006.5
Exp/Cntr=0.3,0.1

Type RM Length L Ch R = 1,5356,313,313,313
BEGIN DESCRIPTION:
Mapping XS cc72ae15
END DESCRIPTION:
XS GIS Cut Line= 3
      2829909.38     10051769.19      2830510.11     10051694.53
      2830872.94     10051048.73
#Sta/Elev= 30
  4636.8 1451.49  4686.3 1452.03  4696.3 1451.02  4721.6 1449.83  4787.0 1447.96
  4877.7 1446.78  4897.9 1447.21  4913.8 1445.49  4928.1 1444.00  4948.3 1443.34
  4964.1 1441.62  4969.2 1441.98  4978.5 1440.00  4988.6 1433.87  4995.6 1431.89
  4998.4 1431.39  5001.6 1431.89  5008.7 1435.21  5018.8 1437.38  5059.1 1439.51
  5079.3 1438.83  5119.4 1438.69  5273.4 1438.51  5410.9 1439.31  5506.9 1441.85
  5621.9 1442.94  5697.1 1442.83  5756.4 1444.01  5843.2 1444.41  5982.9 1446.57
#Mann=6,-1,0
  4636.8    0.05       0  4913.8    0.16       0  4995.6    0.07       0
  5001.6    0.16       0  5119.4     0.1       0  5273.4    0.05       0
Bank Sta=4995.6,5001.6
Exp/Cntr=0.3,0.1

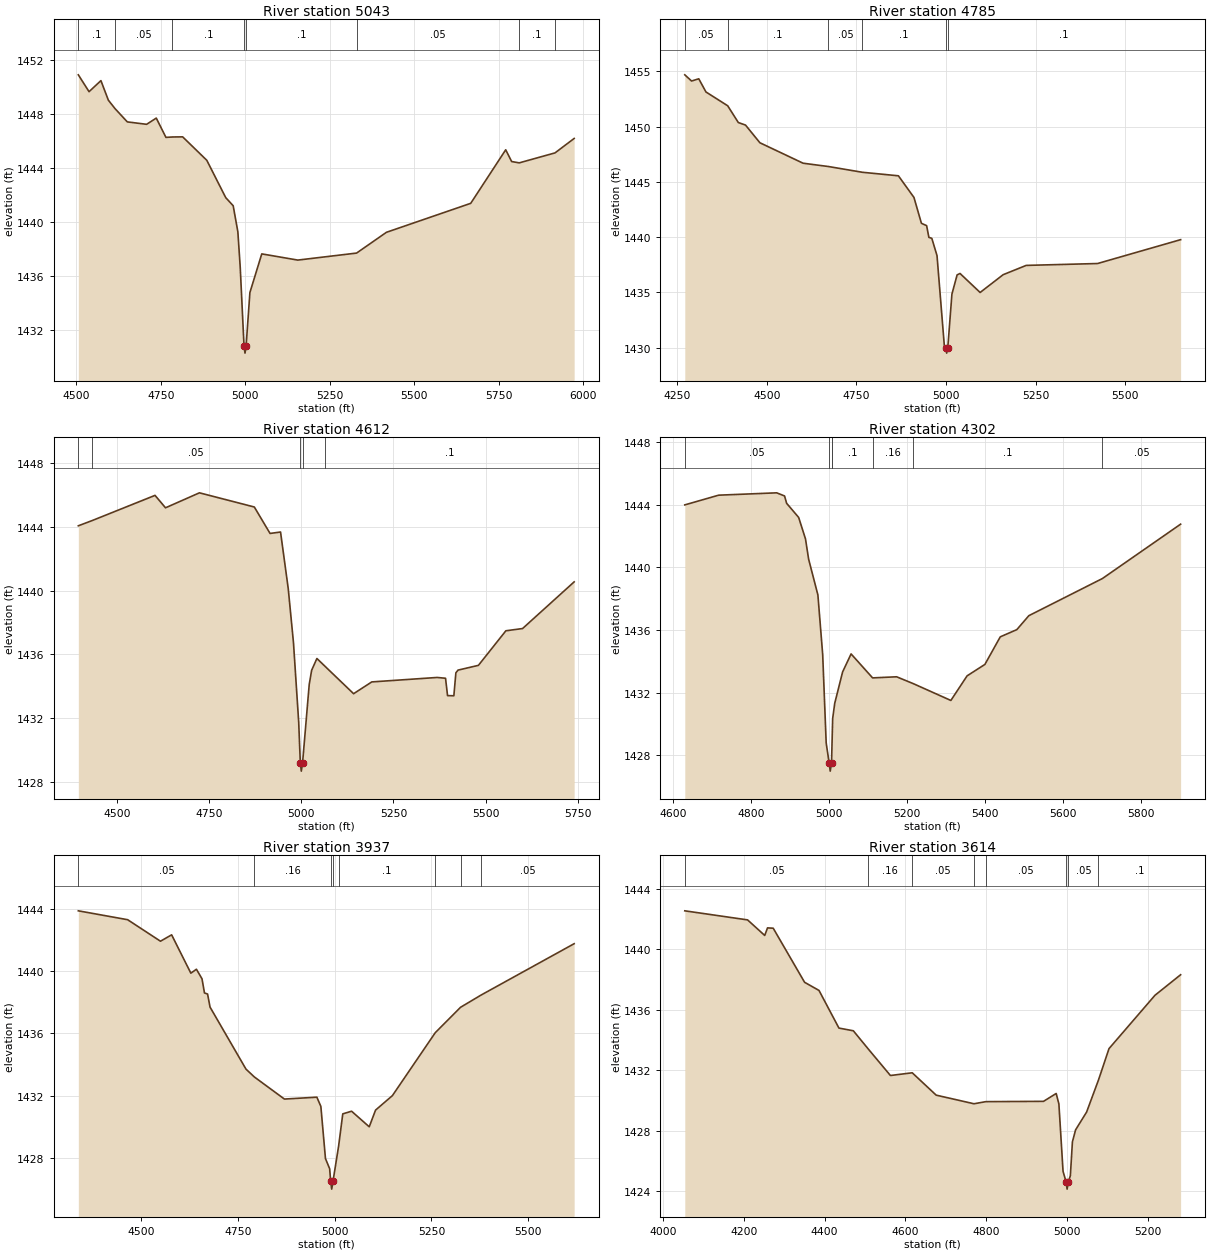
Type RM Length L Ch R = 1,5043,258,258,258
BEGIN DESCRIPTION:
UNT007 IN SNOGR 8.0
END DESCRIPTION:
XS GIS Cut Line= 3
      2830009.00     10052309.01      2830629.90     10051781.34
      2830898.75     10051188.15
#Sta/Elev= 30
  4506.4 1450.90  4538.1 1449.65  4573.2 1450.47  4595.2 1449.02  4614.7 1448.40
  4651.2 1447.41  4708.3 1447.23  4736.9 1447.69  4765.5 1446.26  4784.7 1446.29
  4814.9 1446.30  4886.3 1444.56  4942.3 1441.79  4964.3 1441.19  4978.1 1439.26
  4985.1 1436.63  4996.4 1430.76  4999.2 1430.26  5002.4 1430.76  5013.7 1434.75
  5048.8 1437.62  5155.4 1437.16  5329.2 1437.68  5417.4 1439.22  5666.7 1441.37
  5770.1 1445.34  5787.7 1444.47  5810.0 1444.37  5915.9 1445.11  5972.5 1446.18
#Mann=8,-1,0
  4506.4     0.1       0  4614.7    0.05       0  4784.7     0.1       0
  4996.4    0.07       0  5002.4     0.1       0  5329.2    0.05       0
  5810.0     0.1       0  5915.9    0.05       0
Bank Sta=4996.4,5002.4
Exp/Cntr=0.3,0.1

Type RM Length L Ch R = 1,4785,173,173,173
BEGIN DESCRIPTION:
UNT007 IN SNOGR 7.0
END DESCRIPTION:
XS GIS Cut Line= 4
      2829889.67     10052406.68      2830407.51     10052359.78
      2830860.64     10051776.45      2830860.64     10051651.45
#Sta/Elev= 30
  4270.9 1454.69  4289.8 1454.13  4309.9 1454.33  4329.9 1453.14  4390.6 1451.89
  4420.3 1450.37  4440.4 1450.14  4480.5 1448.54  4601.0 1446.69  4671.7 1446.39
  4766.3 1445.87  4867.0 1445.55  4910.4 1443.59  4931.2 1441.25  4945.7 1441.04
  4952.0 1439.98  4960.2 1439.89  4974.7 1438.33  4995.5 1430.02  4998.8 1430.00
  5001.6 1429.50  5004.8 1430.00  5016.3 1434.84  5030.8 1436.58  5038.9 1436.71
  5095.0 1434.99  5159.3 1436.60  5223.6 1437.44  5422.7 1437.61  5654.5 1439.77
#Mann=6,-1,0
  4270.9    0.05       0  4390.6     0.1       0  4671.7    0.05       0
  4766.3     0.1       0  4998.8    0.07       0  5004.8     0.1       0
Bank Sta=4998.8,5004.8
Exp/Cntr=0.3,0.1

Type RM Length L Ch R = 1,4612,310,310,310
BEGIN DESCRIPTION:
UNT007 IN SNOGR 6.0
END DESCRIPTION:
XS GIS Cut Line= 3
      2830182.59     10052732.21      2830834.59     10052161.86
      2831042.92     10051729.60
#Sta/Elev= 30
  4394.4 1444.07  4432.1 1444.40  4602.6 1445.98  4631.1 1445.20  4723.2 1446.14
  4872.2 1445.25  4914.9 1443.59  4943.4 1443.68  4964.3 1440.12  4978.5 1436.73
  4992.7 1431.73  4997.1 1429.17  4999.8 1428.67  5003.1 1429.17  5021.2 1434.10
  5027.8 1435.00  5042.1 1435.74  5064.6 1435.24  5141.7 1433.53  5191.1 1434.27
  5368.6 1434.55  5391.3 1434.50  5396.8 1433.41  5413.9 1433.40  5419.4 1434.84
  5425.1 1435.01  5480.6 1435.31  5555.1 1437.48  5600.4 1437.62  5740.5 1440.55
#Mann=5,-1,0
  4394.4     0.1       0  4432.1    0.05       0  4997.1   0.035       0
  5003.1    0.05       0  5064.6     0.1       0
Bank Sta=4997.1,5003.1
Exp/Cntr=0.3,0.1

Type RM Length L Ch R = 1,4302,365,365,365
BEGIN DESCRIPTION:
Mapping XS 6c919b58
END DESCRIPTION:
XS GIS Cut Line= 2
      2830735.99     10052894.94      2831162.64     10051698.53
#Sta/Elev= 30
  4630.7 1443.99  4717.4 1444.61  4866.1 1444.76  4886.3 1444.56  4891.6 1444.09
  4922.4 1443.19  4939.9 1441.82  4947.9 1440.53  4971.7 1438.24  4984.0 1434.42
  4992.9 1428.80  5000.6 1427.50  5003.3 1427.00  5006.6 1427.50  5009.0 1429.86
  5009.5 1430.35  5014.8 1431.33  5035.0 1433.33  5056.7 1434.48  5111.8 1432.95
  5173.4 1433.02  5216.3 1432.58  5312.3 1431.51  5353.9 1433.08  5399.5 1433.81
  5438.9 1435.57  5481.3 1436.03  5512.1 1436.92  5700.5 1439.29  5900.9 1442.76
#Mann=7,-1,0
  4630.7    0.05       0  5000.6   0.035       0  5006.6    0.05       0
  5009.0     0.1       0  5111.8    0.16       0  5216.3     0.1       0
  5700.5    0.05       0
Bank Sta=5000.6,5006.6
Exp/Cntr=0.3,0.1

Type RM Length L Ch R = 1,3937,323,323,323
BEGIN DESCRIPTION:
Mapping XS 009f63a6
END DESCRIPTION:
XS GIS Cut Line= 4
      2830811.93     10052905.82      2831187.20     10052439.33
      2831114.28     10052284.81      2831173.01     10051777.56
#Sta/Elev= 30
  4338.4 1443.87  4465.7 1443.30  4550.5 1441.92  4579.3 1442.33  4628.9 1439.87
  4643.3 1440.12  4657.7 1439.51  4664.1 1438.60  4672.1 1438.53  4678.5 1437.69
  4771.3 1433.71  4792.8 1433.21  4870.5 1431.79  4954.3 1431.91  4964.6 1431.32
  4976.5 1427.97  4987.3 1427.32  4989.9 1426.51  4992.6 1426.01  4995.9 1426.51
  5010.5 1428.78  5021.2 1430.84  5043.9 1431.01  5089.5 1430.01  5105.8 1431.08
  5149.3 1432.01  5260.0 1436.05  5325.3 1437.68  5378.7 1438.47  5618.6 1441.76
#Mann=8,-1,0
  4338.4    0.05       0  4792.8    0.16       0  4989.9    0.07       0
  4995.9    0.16       0  5010.5     0.1       0  5260.0    0.05       0
  5325.3     0.1       0  5378.7    0.05       0
Bank Sta=4989.9,4995.9
Exp/Cntr=0.3,0.1

Type RM Length L Ch R = 1,3614,525,525,525
BEGIN DESCRIPTION:
Mapping XS 98c5ba28
END DESCRIPTION:
XS GIS Cut Line= 3
      2830844.48     10052949.22      2831451.08     10052300.44
      2831364.28     10051972.32
#Sta/Elev= 30
  4053.7 1442.55  4209.1 1441.95  4251.6 1440.92  4258.5 1441.42  4272.6 1441.40
  4350.3 1437.82  4386.0 1437.28  4435.3 1434.79  4471.0 1434.61  4508.1 1433.40
  4562.8 1431.65  4616.8 1431.83  4676.1 1430.35  4769.7 1429.78  4799.1 1429.92
  4941.9 1429.94  4973.2 1430.46  4979.9 1429.77  4990.2 1425.31  4997.5 1424.63
  5000.3 1424.13  5003.5 1424.63  5008.3 1425.02  5013.4 1427.26  5021.2 1428.05
  5048.5 1429.23  5077.9 1431.35  5104.0 1433.43  5217.8 1436.96  5281.3 1438.32
#Mann=8,-1,0
  4053.7    0.05       0  4508.1    0.16       0  4616.8    0.05       0
  4769.7     0.1       0  4799.1    0.05       0  4997.5   0.035       0
  5003.5    0.05       0  5077.9     0.1       0
Bank Sta=4997.5,5003.5
Exp/Cntr=0.3,0.1

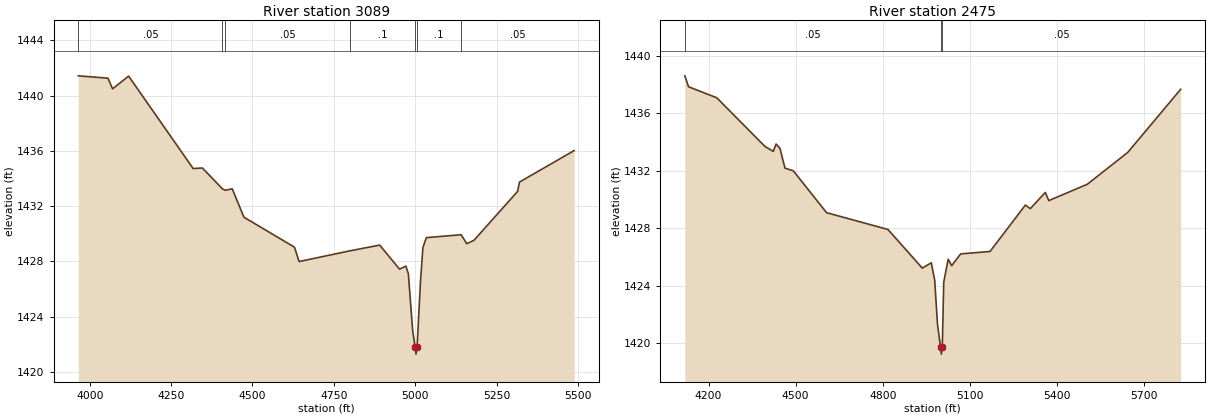
Type RM Length L Ch R = 1,3089,614,614,614
BEGIN DESCRIPTION:
Mapping XS 440869d4
END DESCRIPTION:
XS GIS Cut Line= 4
      2830877.01     10052970.95      2831586.50     10052305.64
      2831713.24     10052345.58      2831900.73     10051972.33
#Sta/Elev= 30
  3965.0 1441.43  4056.0 1441.26  4070.2 1440.49  4119.5 1441.41  4317.8 1434.72
  4346.2 1434.76  4407.7 1433.25  4416.2 1433.15  4438.0 1433.25  4473.6 1431.20
  4629.0 1429.03  4643.2 1427.99  4800.5 1428.77  4890.8 1429.18  4951.7 1427.44
  4971.1 1427.66  4978.8 1427.12  4992.1 1423.00  4999.6 1421.79  5002.3 1421.29
  5005.6 1421.79  5016.4 1426.65  5023.6 1429.00  5034.1 1429.72  5141.0 1429.93
  5158.3 1429.28  5180.6 1429.53  5314.6 1433.07  5320.2 1433.74  5488.2 1436.02
#Mann=7,-1,0
  3965.0    0.05       0  4407.7    0.16       0  4416.2    0.05       0
  4800.5     0.1       0  4999.6    0.07       0  5005.6     0.1       0
  5141.0    0.05       0
Bank Sta=4999.6,5005.6
Exp/Cntr=0.3,0.1

Type RM Length L Ch R = 1,2475,531,531,531
BEGIN DESCRIPTION:
UNT007 IN SNOGR 5.0
END DESCRIPTION:
XS GIS Cut Line= 4
      2830912.92     10053094.69      2831652.47     10052753.56
      2831811.33     10052487.94      2831959.76     10051922.85
#Sta/Elev= 30
  4118.0 1438.61  4130.9 1437.85  4228.2 1437.08  4394.4 1433.69  4422.8 1433.35
  4432.5 1433.86  4445.8 1433.56  4463.2 1432.18  4491.7 1432.00  4606.4 1429.08
  4817.9 1427.91  4936.2 1425.22  4967.2 1425.59  4979.0 1424.37  4988.7 1421.28
  4999.1 1419.73  5001.9 1419.23  5005.1 1419.73  5010.1 1424.25  5025.5 1425.84
  5037.4 1425.39  5068.5 1426.21  5169.6 1426.38  5291.3 1429.61  5308.3 1429.36
  5360.0 1430.49  5372.0 1429.92  5504.8 1431.06  5644.2 1433.28  5826.2 1437.67
#Mann=3,-1,0
  4118.0    0.05       0  4999.1   0.035       0  5005.1    0.05       0
Bank Sta=4999.1,5005.1
Exp/Cntr=0.3,0.1