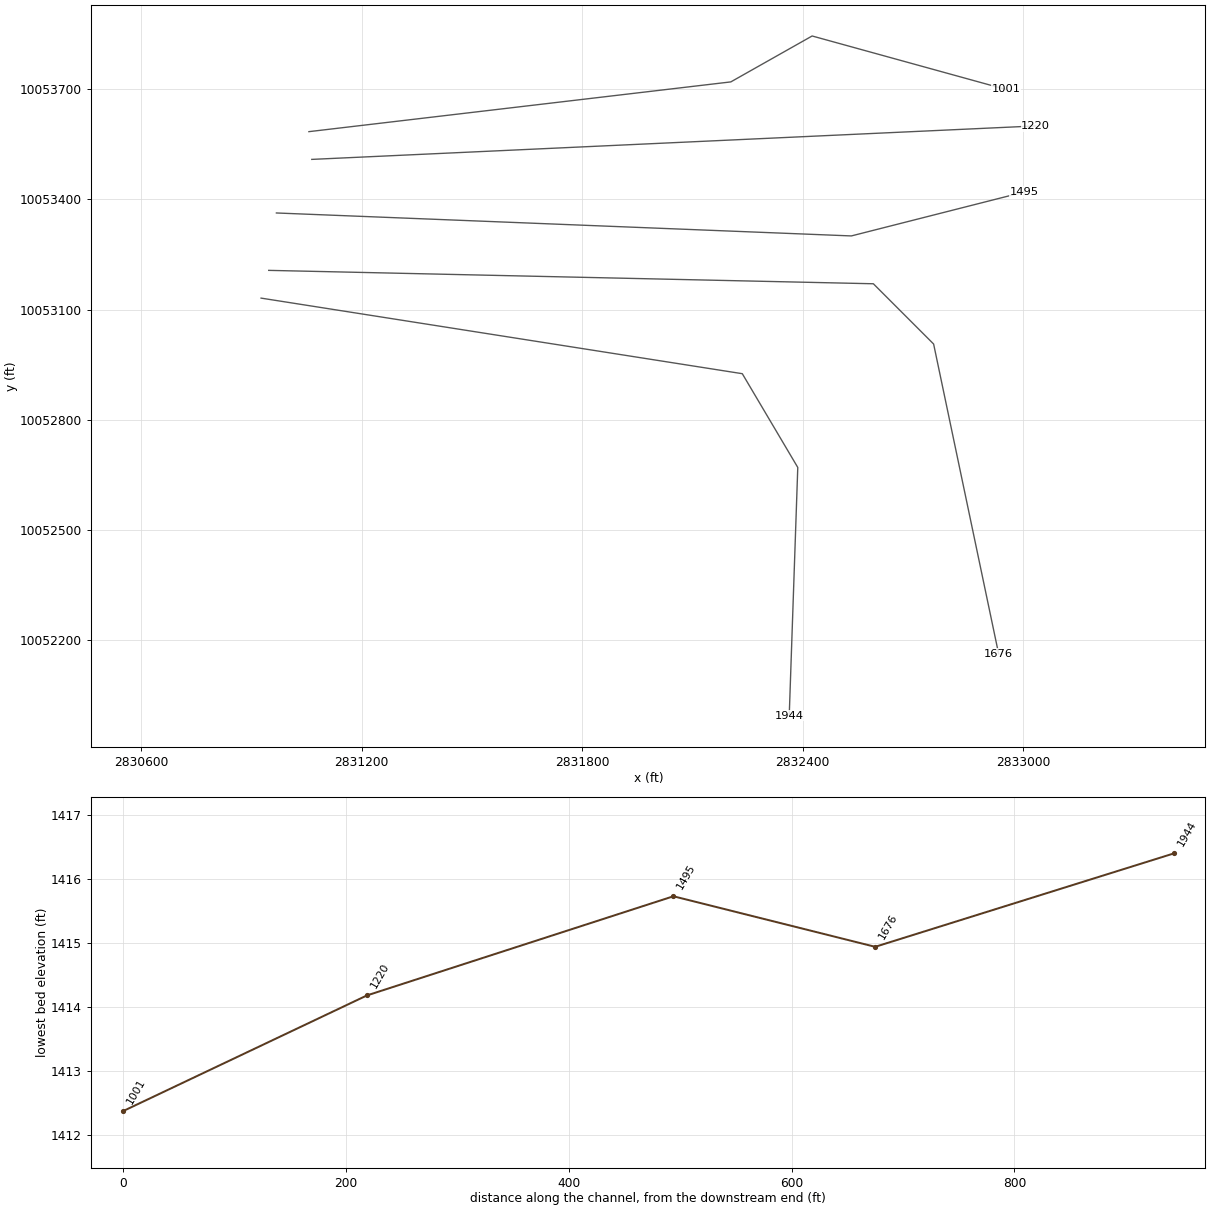
HEC-RAS study UNT007 IN SNOGR.prj: UNT007 IN SNOGR Base Level Engineering

--- UNT007 IN SNOGR.g01 (geometry) --- (continued)

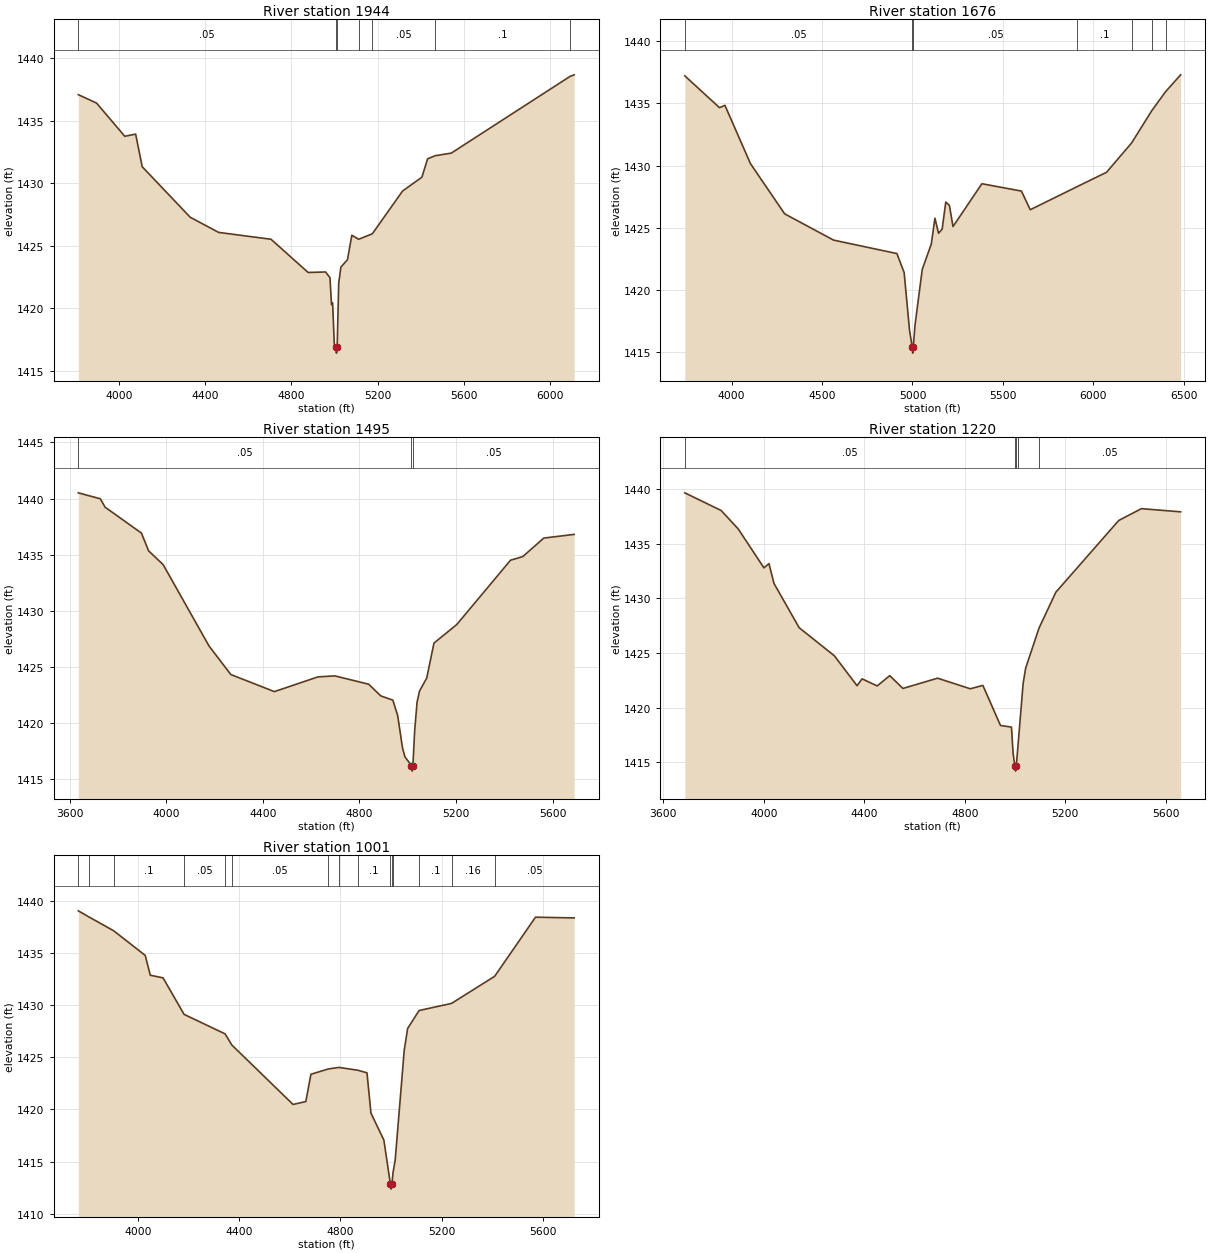
Type RM Length L Ch R = 1,1944,268,268,268
BEGIN DESCRIPTION:
UNT007 IN SNOGR 4.0
END DESCRIPTION:
XS GIS Cut Line= 4
      2830925.87     10053131.17      2832235.81     10052925.44
      2832386.85     10052670.23      2832363.59     10051994.38
#Sta/Elev= 30
  3812.9 1437.10  3897.3 1436.43  4028.1 1433.77  4078.7 1433.94  4109.1 1431.33
  4331.8 1427.28  4463.4 1426.07  4706.3 1425.52  4878.4 1422.86  4959.4 1422.90
  4979.6 1422.44  4986.7 1420.28  4991.8 1420.42  4999.9 1417.05  5007.0 1416.90
  5009.7 1416.40  5013.0 1416.90  5020.1 1422.00  5030.2 1423.29  5060.6 1423.88
  5080.9 1425.84  5113.1 1425.52  5176.0 1425.96  5316.0 1429.38  5405.8 1430.49
  5432.1 1431.96  5467.0 1432.21  5542.0 1432.42  6093.1 1438.57  6111.7 1438.69
#Mann=7,-1,0
  3812.9    0.05       0  5007.0    0.04       0  5013.0    0.05       0
  5113.1     0.1       0  5176.0    0.05       0  5467.0     0.1       0
  6093.1    0.05       0
Bank Sta=5007,5013
Exp/Cntr=0.3,0.1

Type RM Length L Ch R = 1,1676,181,181,181
BEGIN DESCRIPTION:
Mapping XS 6c41f74f
END DESCRIPTION:
XS GIS Cut Line= 4
      2830946.72     10053206.69      2832592.58     10053170.23
      2832756.64     10053006.17      2832933.60     10052163.02
#Sta/Elev= 30
  3741.8 1437.22  3933.6 1434.66  3963.6 1434.85  4104.8 1430.16  4293.7 1426.13
  4563.8 1424.02  4913.8 1422.94  4953.8 1421.42  4983.9 1416.74  4998.5 1415.44
  5001.2 1414.94  5004.5 1415.44  5013.9 1417.19  5053.9 1421.67  5103.9 1423.70
  5123.9 1425.78  5143.9 1424.57  5163.9 1424.90  5183.9 1427.08  5203.9 1426.81
  5223.9 1425.11  5383.5 1428.55  5601.9 1427.96  5650.7 1426.46  5911.6 1428.33
  6072.2 1429.47  6210.4 1431.82  6322.7 1434.43  6398.2 1435.94  6481.6 1437.30
#Mann=7,-1,0
  3741.8    0.05       0  4998.5    0.04       0  5004.5    0.05       0
  5911.6     0.1       0  6210.4    0.05       0  6322.7     0.1       0
  6398.2    0.05       0
Bank Sta=4998.5,5004.5
Exp/Cntr=0.3,0.1

Type RM Length L Ch R = 1,1495,275,275,275
BEGIN DESCRIPTION:
Mapping XS 8d981a19
END DESCRIPTION:
XS GIS Cut Line= 3
      2830967.62     10053362.93      2832532.68     10053300.44
      2833003.70     10053420.14
#Sta/Elev= 30
  3636.4 1440.51  3727.3 1439.98  3747.3 1439.23  3897.4 1436.93  3927.5 1435.34
  3987.4 1434.12  4177.7 1426.86  4267.7 1424.33  4447.9 1422.81  4628.0 1424.12
  4698.1 1424.21  4838.2 1423.47  4888.2 1422.43  4938.3 1422.05  4958.3 1420.67
  4978.3 1417.79  4988.3 1417.00  5015.3 1416.23  5018.1 1415.73  5021.3 1416.23
  5028.4 1419.27  5038.4 1421.86  5048.4 1422.85  5078.4 1424.01  5108.4 1427.13
  5202.7 1428.78  5425.3 1434.51  5475.9 1434.83  5562.9 1436.48  5688.7 1436.81
#Mann=3,-1,0
  3636.4    0.05       0  5015.3    0.04       0  5021.3    0.05       0
Bank Sta=5015.3,5021.3
Exp/Cntr=0.3,0.1

Type RM Length L Ch R = 1,1220,219,219,219
BEGIN DESCRIPTION:
UNT007 IN SNOGR 3.0
END DESCRIPTION:
XS GIS Cut Line= 2
      2831063.95     10053508.77      2833034.35     10053599.87
#Sta/Elev= 30
  3686.0 1439.66  3830.7 1438.04  3898.7 1436.35  4000.8 1432.79  4020.9 1433.18
  4040.9 1431.36  4141.0 1427.31  4281.1 1424.74  4371.2 1422.00  4391.3 1422.63
  4451.3 1421.98  4501.4 1422.92  4553.8 1421.75  4691.6 1422.69  4821.7 1421.72
  4871.8 1422.03  4941.9 1418.36  4985.6 1418.21  4991.9 1415.85  4998.9 1414.68
  5001.7 1414.18  5004.9 1414.68  5010.5 1416.22  5031.9 1422.19  5042.0 1423.61
  5095.3 1427.28  5162.1 1430.56  5412.3 1437.13  5502.5 1438.21  5658.5 1437.92
#Mann=5,-1,0
  3686.0    0.05       0  4998.9    0.04       0  5004.9    0.05       0
  5010.5     0.1       0  5095.3    0.05       0
Bank Sta=4998.9,5004.9
Exp/Cntr=0.3,0.1

Type RM Length L Ch R = 1,1001,0,0,0
BEGIN DESCRIPTION:
UNT007 IN SNOGR 2.0
END DESCRIPTION:
XS GIS Cut Line= 4
      2831056.13     10053584.29      2832204.56     10053719.71
      2832425.91     10053844.71      2832953.99     10053699.03
#Sta/Elev= 30
  3764.6 1439.03  3805.3 1438.46  3904.2 1437.12  4028.8 1434.76  4048.9 1432.86
  4099.2 1432.61  4182.4 1429.11  4344.4 1427.24  4370.8 1426.18  4612.8 1420.48
  4663.1 1420.76  4683.3 1423.37  4751.8 1423.88  4793.8 1424.03  4868.7 1423.76
  4904.8 1423.51  4920.4 1419.65  4971.4 1417.07  4997.2 1412.87  5000.0 1412.37
  5003.2 1412.87  5007.6 1413.95  5016.1 1415.15  5051.8 1425.66  5065.2 1427.75
  5110.5 1429.48  5238.6 1430.16  5409.1 1432.76  5570.3 1438.42  5723.0 1438.35
#Mann=15,-1,0
  3764.6     0.1       0  3805.3    0.05       0  3904.2     0.1       0
  4182.4    0.05       0  4344.4     0.1       0  4370.8    0.05       0
  4751.8     0.1       0  4793.8    0.16       0  4868.7     0.1       0
  4997.2    0.07       0  5003.2     0.1       0  5007.6    0.16       0
  5110.5     0.1       0  5238.6    0.16       0  5409.1    0.05       0
Bank Sta=4997.2,5003.2
Exp/Cntr=0.3,0.1

Chan Stop Cuts=-1