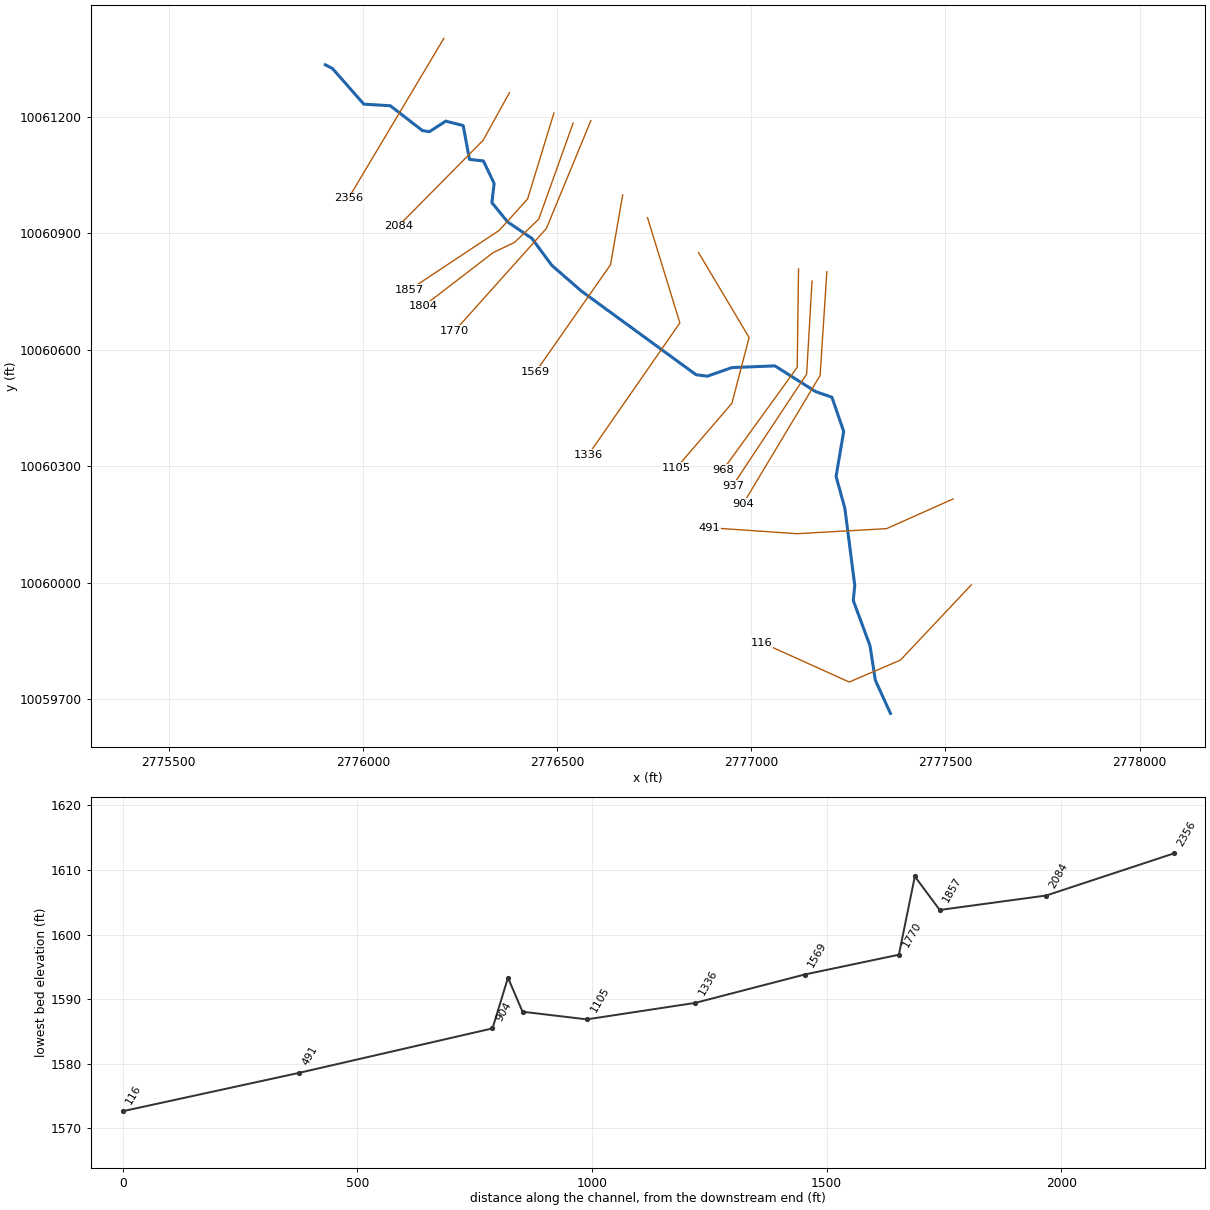
--- UNT009 IN NNOGR.prj (project) ---

Proj Title=UNT009 IN NNOGR Base Level Engineering
Current Plan=p01
Default Exp/Contr=0.3,0.1
English Units
Geom File=g01
Flow File=f01
Plan File=p01
Y Axis Title=Elevation
X Axis Title(PF)=Main Channel Distance
X Axis Title(XS)=Station
BEGIN DESCRIPTION:
UNT009 IN NNOGR
END DESCRIPTION:
DSS Export Rating Curves= 0
DSS Export Rating Curve Sorted= 0
DSS Export Volume Flow Curves= 0
DXF OffsetX= 0
DXF OffsetY= 0
DXF ScaleX= 1
DXF ScaleY= 10

--- UNT009 IN NNOGR.p01 (plan) ---

Plan Title=Multiple Run
Short Identifier=Multiple
Geom File=g01
Flow File=f01
Subcritical Flow
K Sum by GR= 0
Std Step Tol= 0.01
Critical Tol= 0.01
Num of Std Step Trials= 20
Max Error Tol= 0.3
Flow Tol Ratio= 0.001
Split Flow NTrial= 30
Split Flow Tol= 0.02
Split Flow Ratio= 0.02
Log Output Level= 0
Friction Slope Method= 1
Unsteady Friction Slope Method= 2
Unsteady Bridges Friction Slope Method= 1
Parabolic Critical Depth
Global Vel Dist=  1 , 1 , 1
Global Log Level= 0
CheckData=True
Encroach Param= -1, 0, 0, 0
BEGIN DESCRIPTION:
Multiple Run
END DESCRIPTION:

--- UNT009 IN NNOGR.f01 (steady flow) ---

Flow Title=Multiple
Program Version=4.10
Number of Profiles= 7
Profile Names=10-year,25-year,50-year,1pct_min,100-year,1pct_plu,500-year
River Rch & RM=UNT009 IN NNOGR,Reach-1         ,2356
     225     298     355     312     422     571     595
Boundary for River Rch & Prof#=UNT009 IN NNOGR,Reach-1         , 1
Up Type= 0
Dn Type= 3
Dn Slope=0.016
Boundary for River Rch & Prof#=UNT009 IN NNOGR,Reach-1         , 2
Up Type= 0
Dn Type= 3
Dn Slope=0.016
Boundary for River Rch & Prof#=UNT009 IN NNOGR,Reach-1         , 3
Up Type= 0
Dn Type= 3
Dn Slope=0.016
Boundary for River Rch & Prof#=UNT009 IN NNOGR,Reach-1         , 4
Up Type= 0
Dn Type= 3
Dn Slope=0.016
Boundary for River Rch & Prof#=UNT009 IN NNOGR,Reach-1         , 5
Up Type= 0
Dn Type= 3
Dn Slope=0.016
Boundary for River Rch & Prof#=UNT009 IN NNOGR,Reach-1         , 6
Up Type= 0
Dn Type= 3
Dn Slope=0.016
Boundary for River Rch & Prof#=UNT009 IN NNOGR,Reach-1         , 7
Up Type= 0
Dn Type= 3
Dn Slope=0.016
DSS Import GetInterval= 0
DSS Import GetPeak= 0
DSS Import FillOption= 0

--- UNT009 IN NNOGR.g01 (geometry) ---

Geom Title=Existing Conditions
Program Version=4.10

River Reach=UNT009 IN NNOGR ,Reach-1
Reach XY= 30
      2775903.47     10061333.73      2775921.82     10061324.15
      2776002.57     10061232.35      2776070.82      10061228.3
      2776153.42     10061164.26      2776171.55     10061161.58
      2776213.57      10061188.7      2776258.36     10061177.24
      2776274.51     10061090.26      2776310.45      10061086.1
      2776338.05     10061028.28      2776332.32     10060978.81
       2776372.9     10060929.09      2776435.45     10060886.62
      2776486.11     10060817.85      2776561.81     10060751.81
      2776857.84     10060535.77      2776887.01     10060531.93
      2776950.23     10060554.12      2777060.97     10060558.49
      2777165.66     10060492.35      2777207.84     10060477.76
      2777238.16     10060389.72      2777218.57     10060273.91
      2777241.16     10060191.51      2777266.62     10059993.33
      2777262.79     10059954.44      2777305.93     10059837.68
      2777319.55     10059749.18      2777358.47     10059663.73

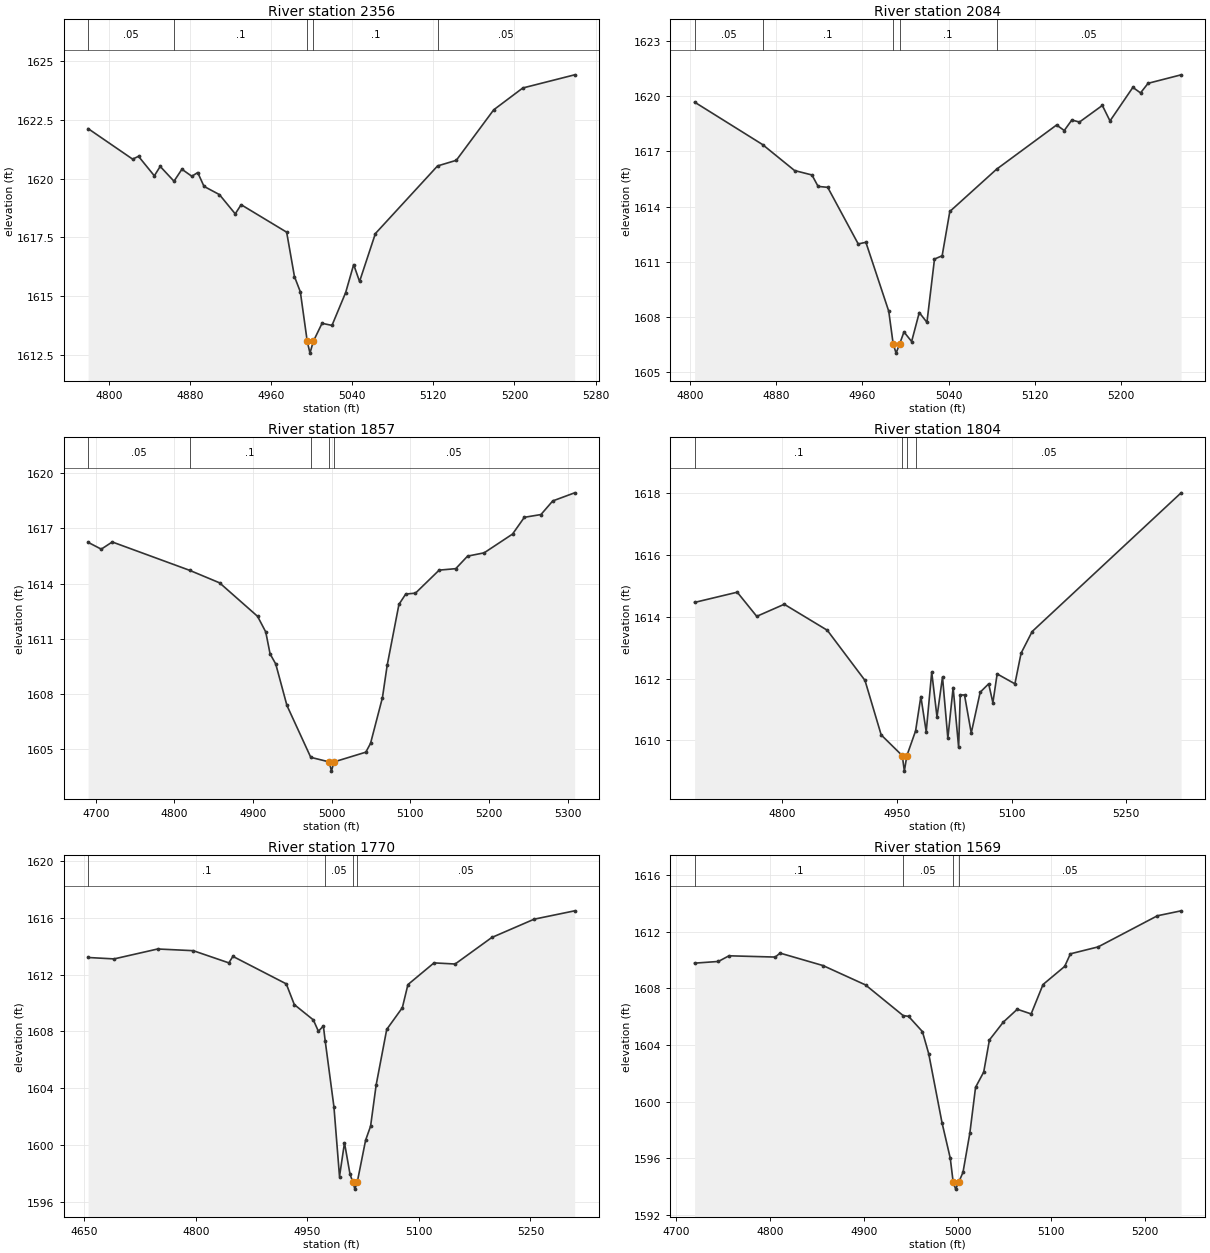
Type RM Length L Ch R = 1 ,2356    ,272,272,272
BEGIN DESCRIPTION:
UNT009 IN NNOGR 5.0
END DESCRIPTION:
XS GIS Cut Line= 2
      2776208.68     10061401.87      2775962.84     10060989.84
#Sta/Elev= 30
  4779.6 1622.13  4823.5 1620.83  4829.3 1620.95  4844.9 1620.12  4850.7 1620.52
  4864.3 1619.89  4872.1  1620.4  4881.9  1620.1  4887.7 1620.26  4893.9 1619.67
  4909.1 1619.32  4924.7  1618.5  4930.5 1618.89  4975.4 1617.72  4983.1 1615.83
  4988.9 1615.18  4995.7 1613.07  4998.4 1612.57  5001.7 1613.07  5010.3 1613.84
  5020.1 1613.75  5033.6 1615.15  5041.5 1616.34  5047.3 1615.62  5062.9 1617.66
  5124.2 1620.54  5142.7 1620.78  5179.6 1622.93  5208.3 1623.86  5259.4 1624.42
#Mann= 5 ,-1 , 0
  4779.6     .05       0  4864.3      .1       0  4995.7     .07       0
  5001.7      .1       0  5124.2     .05       0
Bank Sta=4995.7,5001.7
XS Rating Curve= 0 ,0
Exp/Cntr=0.3,0.1

Type RM Length L Ch R = 1 ,2084    ,227,227,227
BEGIN DESCRIPTION:
Mapping XS 2185c229
END DESCRIPTION:
XS GIS Cut Line= 3
      2776377.37     10061261.68      2776309.69     10061139.33
      2776090.96       10060918.
#Sta/Elev= 30
  4804.4 1619.66  4867.4 1617.36  4897.1 1615.95  4913.2 1615.71  4918.9 1615.09
  4927.8 1615.04  4956.1 1611.97  4963.2 1612.06  4984.4 1608.32  4988.5 1606.55
  4991.2 1606.05  4994.5 1606.55  4998.5  1607.2  5005.6 1606.68  5012.7 1608.25
  5019.8 1607.72  5026.8 1611.15  5033.9 1611.33    5041 1613.73  5084.3 1616.02
    5140 1618.42  5147.1 1618.12  5154.1 1618.69  5161.2 1618.58  5182.4 1619.48
  5189.5 1618.64  5210.7 1620.46  5217.8 1620.16  5224.8 1620.68  5255.4 1621.14
#Mann= 5 ,-1 , 0
  4804.4     .05       0  4867.4      .1       0  4988.5     .07       0
  4994.5      .1       0  5084.3     .05       0
Bank Sta=4988.5,4994.5
XS Rating Curve= 0 ,0
Exp/Cntr=0.3,0.1

Type RM Length L Ch R = 1 ,1857    ,53,53,53
BEGIN DESCRIPTION:
Mapping XS b035ecc2
END DESCRIPTION:
XS GIS Cut Line= 4
      2776491.99     10061209.67      2776424.27     10060988.29
      2776351.35     10060907.56      2776119.55     10060753.89
#Sta/Elev= 30
  4690.3 1616.24    4707 1615.87    4721 1616.26  4819.3 1614.72  4857.4 1614.04
  4905.7 1612.22  4916.1 1611.37  4921.6 1610.18  4928.8 1609.63    4943 1607.38
  4973.3 1604.56  4996.8 1604.31  4999.6 1603.81  5002.8 1604.31  5043.3 1604.84
  5049.3 1605.32  5064.4  1607.8  5070.4 1609.55  5085.4 1612.87    5094 1613.43
  5106.4 1613.48  5136.5 1614.73  5157.6 1614.81  5172.6 1615.49  5193.7 1615.67
  5229.8 1616.69  5244.8  1617.6  5265.9 1617.75  5280.9 1618.49  5308.7 1618.93
#Mann= 5 ,-1 , 0
  4690.3     .05       0  4819.3      .1       0  4973.3     .05       0
  4996.8     .04       0  5002.8     .05       0
Bank Sta=4996.8,5002.8
XS Rating Curve= 0 ,0
Exp/Cntr=0.3,0.1

Type RM Length L Ch R = 1 ,1804    ,34,34,34
BEGIN DESCRIPTION:
Mapping XS 54511fca
END DESCRIPTION:
XS GIS Cut Line= 5
      2776541.44     10061183.56      2776452.92      10060936.2
      2776390.42     10060876.31      2776335.73     10060850.27
      2776156.07     10060712.27
#Sta/Elev= 30
  4685.3 1614.46  4741.1 1614.79  4766.6 1614.01  4802.6  1614.4  4858.9 1613.56
  4908.2 1611.94  4929.4 1610.18    4957 1609.51  4959.7 1609.01    4963 1609.51
  4974.4 1610.31  4981.3 1611.42  4988.3 1610.28  4995.5 1612.21  5002.4 1610.76
  5009.6 1612.05  5016.6 1610.07  5023.5 1611.71  5030.7 1609.78  5032.8 1611.47
  5038.4 1611.47  5047.2 1610.24  5058.9 1611.56    5070 1611.83  5075.5 1611.22
  5081.1 1612.15  5104.3 1611.83  5112.4 1612.82  5126.9 1613.52  5321.7    1618
#Mann= 4 ,-1 , 0
  4685.3      .1       0    4957     .04       0    4963      .1       0
  4974.4     .05       0
Bank Sta=4957,4963
XS Rating Curve= 0 ,0
Exp/Cntr=0.3,0.1

Type RM Length L Ch R = 1 ,1770    ,201,201,201
BEGIN DESCRIPTION:
UNT009 IN NNOGR 4.0
END DESCRIPTION:
XS GIS Cut Line= 3
      2776587.15     10061190.06      2776472.57     10060912.29
      2776236.64      10060648.6
#Sta/Elev= 30
  4655.1 1613.21    4690 1613.11  4748.7 1613.81  4796.5 1613.69  4844.4 1612.83
  4849.8 1613.29  4921.6 1611.35  4932.4 1609.89    4958 1608.81  4964.8 1608.01
  4971.5 1608.38  4973.9 1607.35  4985.7 1602.68  4993.2 1597.77  4999.9 1600.15
  5007.3 1597.94  5011.1 1597.38  5013.9 1596.88  5017.1 1597.38  5028.3 1600.33
    5035 1601.32  5042.5 1604.23  5056.7 1608.14  5077.7 1609.67  5085.2  1611.3
  5120.3 1612.83  5148.7 1612.75    5198 1614.62  5254.9 1615.91  5309.4  1616.5
#Mann= 4 ,-1 , 0
  4655.1      .1       0  4973.9     .05       0  5011.1     .04       0
  5017.1     .05       0
Bank Sta=5011.1,5017.1
XS Rating Curve= 0 ,0
Exp/Cntr=0.3,0.1

Type RM Length L Ch R = 1 ,1569    ,233,233,233
BEGIN DESCRIPTION:
Mapping XS 6bff977c
END DESCRIPTION:
XS GIS Cut Line= 3
      2776669.07     10060998.74      2776637.81     10060819.02
      2776445.09     10060542.96
#Sta/Elev= 30
  4719.4 1609.79  4744.8 1609.91  4756.1 1610.31  4805.5 1610.22  4810.6  1610.5
  4856.4 1609.62  4901.8 1608.25    4942 1606.08  4947.7 1606.03  4962.5 1604.95
  4969.2 1603.39  4983.4 1598.51  4992.2    1596  4995.3 1594.31    4998 1593.81
  5001.3 1594.31  5005.8    1595  5013.1 1597.77  5019.2 1601.01  5027.9 1602.09
    5034 1604.36  5048.8 1605.62  5063.7 1606.53  5078.5  1606.2  5091.2 1608.28
  5114.3 1609.56  5120.4 1610.45    5150 1610.94  5213.2 1613.14  5238.5 1613.49
#Mann= 4 ,-1 , 0
  4719.4      .1       0    4942     .05       0  4995.3     .04       0
  5001.3     .05       0
Bank Sta=4995.3,5001.3
XS Rating Curve= 0 ,0
Exp/Cntr=0.3,0.1

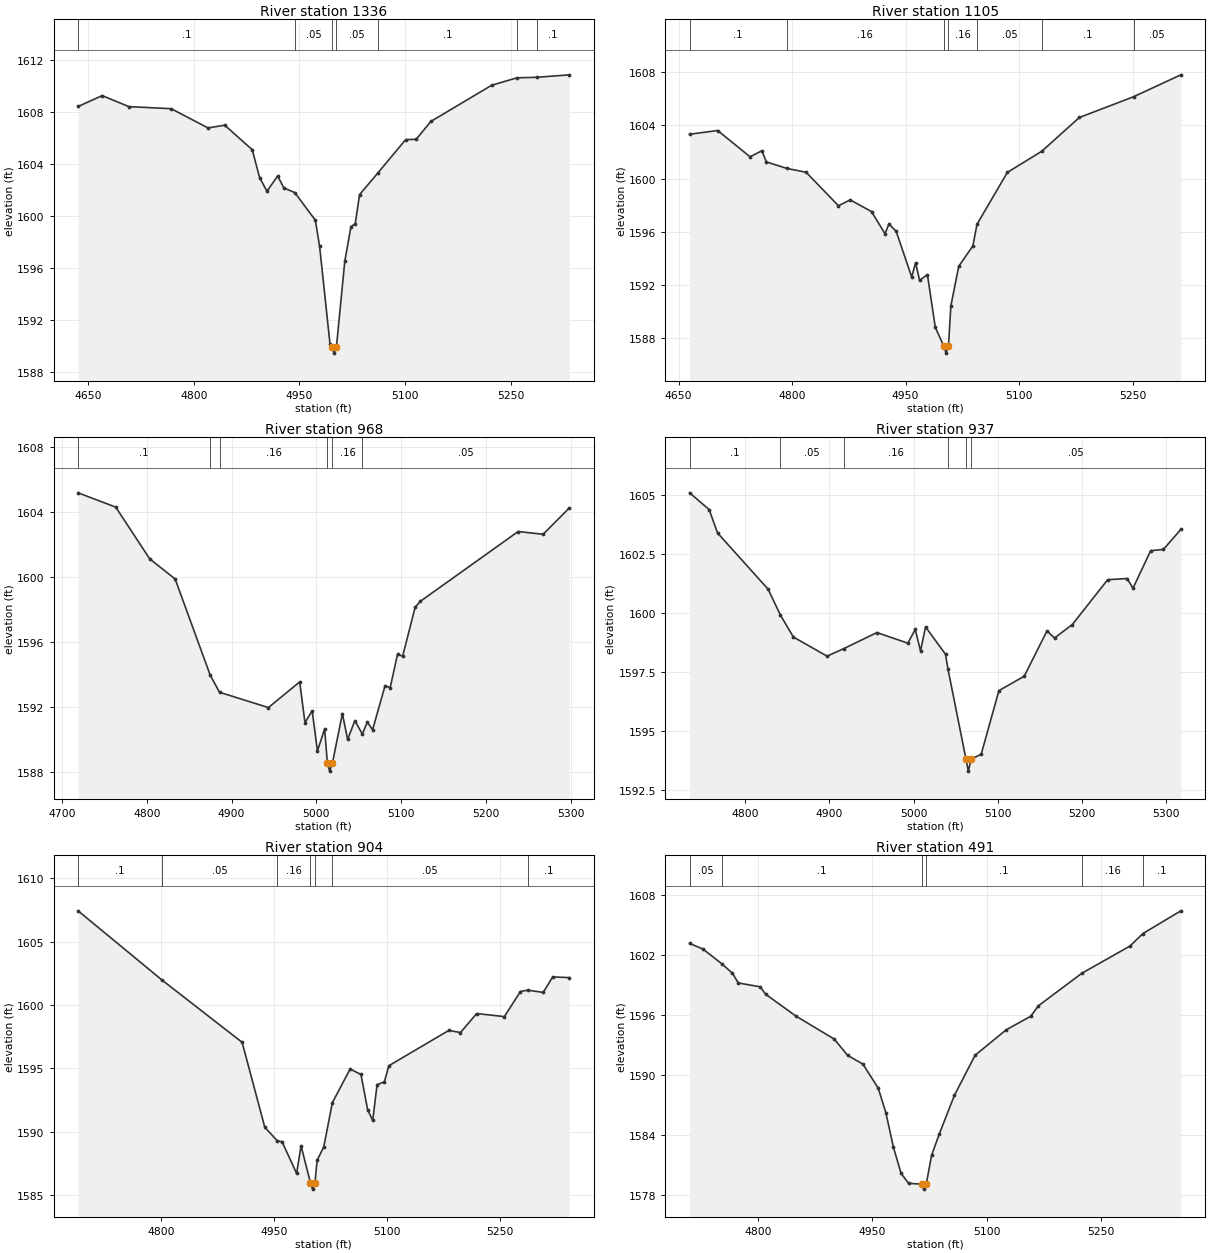
Type RM Length L Ch R = 1 ,1336    ,231,231,231
BEGIN DESCRIPTION:
UNT009 IN NNOGR 3.0
END DESCRIPTION:
XS GIS Cut Line= 3
      2776732.98     10060940.09      2776816.32     10060669.24
      2776580.18     10060328.92
#Sta/Elev= 30
  4635.6 1608.42  4669.8 1609.26  4707.8 1608.41  4767.8 1608.25  4820.1 1606.77
  4843.8 1606.98  4882.9 1605.09  4893.4 1602.93  4903.8  1601.9    4919 1603.06
  4927.9 1602.14  4943.3 1601.79  4972.5 1599.66  4978.5 1597.68  4993.4 1590.09
  4996.5 1589.92  4999.2 1589.42  5002.5 1589.92  5014.3 1596.49  5023.1 1599.16
  5029.2  1599.4  5035.3 1601.63    5061 1603.28  5100.8 1605.87  5115.6 1605.89
  5136.6 1607.27    5223 1610.06    5259 1610.63  5287.4 1610.67  5333.2 1610.86
#Mann= 7 ,-1 , 0
  4635.6      .1       0  4943.3     .05       0  4996.5     .04       0
  5002.5     .05       0    5061      .1       0    5259     .05       0
  5287.4      .1       0
Bank Sta=4996.5,5002.5
XS Rating Curve= 0 ,0
Exp/Cntr=0.3,0.1

Type RM Length L Ch R = 1 ,1105    ,137,137,137
BEGIN DESCRIPTION:
Mapping XS 8cf106eb
END DESCRIPTION:
XS GIS Cut Line= 4
      2776864.35      10060850.3      2776994.58     10060631.52
      2776950.31     10060462.24       2776807.1      10060295.6
#Sta/Elev= 30
  4664.5 1603.34  4701.6 1603.62  4744.4 1601.64    4760  1602.1  4765.8 1601.26
  4792.9 1600.77  4818.4 1600.48  4861.2 1597.96  4876.8  1598.4  4904.9 1597.52
  4922.8 1595.85  4927.9 1596.59  4937.5 1596.04    4958  1592.6  4963.2 1593.67
  4968.5 1592.34  4978.8 1592.78  4989.2 1588.82  5000.6 1587.37  5003.4 1586.87
  5006.6 1587.37  5009.8 1590.42  5020.2  1593.4  5038.9 1594.94  5044.4 1596.57
  5084.5 1600.47    5130 1602.06  5179.6  1604.6  5251.3 1606.16  5313.8 1607.81
#Mann= 7 ,-1 , 0
  4664.5      .1       0  4792.9     .16       0  5000.6     .07       0
  5006.6     .16       0  5044.4     .05       0    5130      .1       0
  5251.3     .05       0
Bank Sta=5000.6,5006.6
XS Rating Curve= 0 ,0
Exp/Cntr=0.3,0.1

Type RM Length L Ch R = 1 ,968     ,31,31,31
BEGIN DESCRIPTION:
UNT009 IN NNOGR 2.0
END DESCRIPTION:
XS GIS Cut Line= 3
      2777121.88     10060808.08       2777118.4     10060554.66
      2776927.43     10060290.76
#Sta/Elev= 30
  4719.1 1605.17  4763.5 1604.29  4803.5 1601.11  4833.5 1599.87  4874.9 1593.95
  4885.9  1592.9  4943.5 1591.96  4980.4 1593.54  4986.6 1591.03  4995.1 1591.76
  5001.3 1589.29  5009.8 1590.65    5013 1588.55  5015.7 1588.05    5019 1588.55
  5030.7 1591.59  5036.9    1590  5045.4 1591.15  5054.3 1590.33  5060.1 1591.07
  5066.3 1590.59    5081  1593.3  5087.1 1593.19  5095.7 1595.23  5101.8 1595.12
  5116.5 1598.13  5122.7  1598.5    5238 1602.79  5267.4 1602.62  5298.3 1604.24
#Mann= 6 ,-1 , 0
  4719.1      .1       0  4874.9     .05       0  4885.9     .16       0
    5013     .07       0    5019     .16       0  5054.3     .05       0
Bank Sta=5013,5019
XS Rating Curve= 0 ,0
Exp/Cntr=0.3,0.1

Type RM Length L Ch R = 1 ,937     ,33,33,33
BEGIN DESCRIPTION:
Mapping XS 0b09d509
END DESCRIPTION:
XS GIS Cut Line= 3
       2777156.6     10060776.92      2777142.71     10060537.29
       2776952.6      10060250.4
#Sta/Elev= 30
  4733.7  1605.1  4756.9 1604.39  4766.9  1603.4    4827 1601.02  4841.7 1599.92
  4857.1 1598.99  4897.2 1598.18    4917  1598.5  4956.5 1599.18  4993.2 1598.73
    5002 1599.31  5008.3  1598.4  5014.3 1599.42    5038 1598.26  5040.9 1597.64
  5062.4 1593.81  5065.2 1593.31  5068.4 1593.81  5080.5 1594.03  5101.5 1596.72
  5131.6 1597.33  5158.7 1599.25  5167.7 1598.95  5188.8 1599.52  5230.9 1601.42
  5253.9 1601.47    5261 1601.06    5282 1602.65  5297.1  1602.7  5317.9 1603.55
#Mann= 6 ,-1 , 0
  4733.7      .1       0  4841.7     .05       0    4917     .16       0
  5040.9     .05       0  5062.4     .07       0  5068.4     .05       0
Bank Sta=5062.4,5068.4
XS Rating Curve= 0 ,0
Exp/Cntr=0.3,0.1

Type RM Length L Ch R = 1 ,904     ,413,413,413
BEGIN DESCRIPTION:
Mapping XS 07337c2b
END DESCRIPTION:
XS GIS Cut Line= 3
      2777194.79     10060801.21      2777177.43     10060533.82
      2776979.53     10060203.99
#Sta/Elev= 30
    4690 1607.44  4801.8 1601.96  4907.9 1597.06    4938 1590.36  4954.7 1589.28
  4960.9 1589.22  4980.3 1586.71  4986.2 1588.89  4998.7 1585.97  5001.5 1585.47
  5004.7 1585.97  5007.5 1587.74  5016.4 1588.81  5027.8  1592.3  5051.4 1594.95
  5065.8 1594.52  5074.7 1591.73  5081.4 1590.89  5087.2 1593.72  5096.9 1593.94
  5102.8 1595.21  5182.5    1598    5198 1597.83  5219.4 1599.33  5256.3 1599.09
  5277.7 1601.07  5287.1 1601.18  5307.9    1601  5320.5 1602.22  5342.6 1602.17
#Mann= 7 ,-1 , 0
    4690      .1       0  4801.8     .05       0  4954.7     .16       0
  4998.7     .07       0  5004.7     .16       0  5027.8     .05       0
  5287.1      .1       0
Bank Sta=4998.7,5004.7
XS Rating Curve= 0 ,0
Exp/Cntr=0.3,0.1

Type RM Length L Ch R = 1 ,491     ,375,375,375
BEGIN DESCRIPTION:
Mapping XS 522f433a
END DESCRIPTION:
XS GIS Cut Line= 4
      2777519.67      10060215.8      2777348.62      10060139.4
      2777117.72     10060126.38      2776891.85     10060141.89
#Sta/Elev= 30
    4710 1603.18  4727.5 1602.62    4752 1601.16  4766.1 1600.21    4774 1599.22
  4802.6 1598.84  4809.9 1598.09  4849.1 1595.93  4899.9  1593.6  4917.5 1591.97
  4937.6 1591.09  4957.6 1588.69  4967.6 1586.24  4977.6 1582.77  4987.6 1580.15
  4997.6 1579.15  5014.7 1579.07  5017.4 1578.57  5020.7 1579.07  5027.7 1581.96
  5037.7 1584.07  5057.7 1587.97  5084.8 1591.98  5125.7 1594.53  5157.9 1595.89
    5168 1596.94  5225.1  1600.2  5288.2 1602.92  5305.1 1604.17    5355 1606.45
#Mann= 6 ,-1 , 0
    4710     .05       0    4752      .1       0  5014.7     .07       0
  5020.7      .1       0  5225.1     .16       0  5305.1      .1       0
Bank Sta=5014.7,5020.7
XS Rating Curve= 0 ,0
Exp/Cntr=0.3,0.1

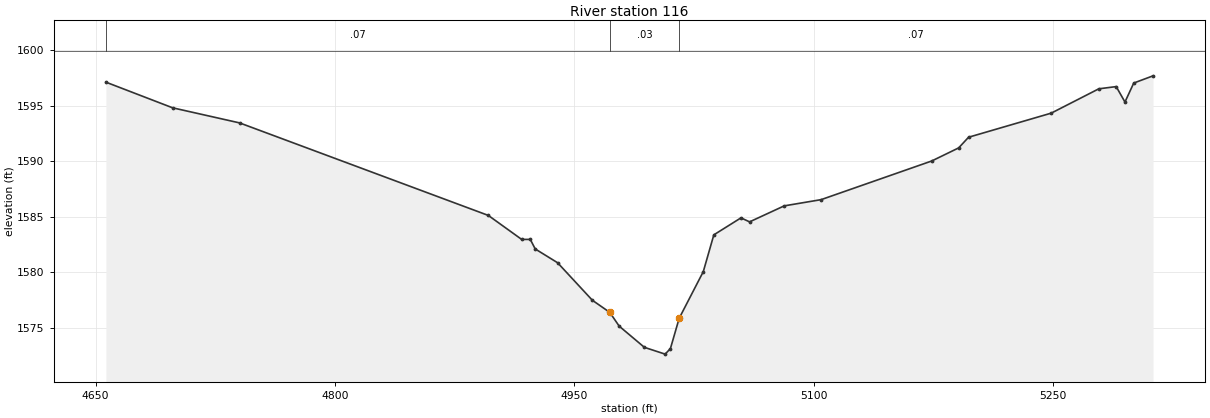
Type RM Length L Ch R = 1 ,116     ,0,0,0
BEGIN DESCRIPTION:
UNT009 IN NNOGR 1.0
END DESCRIPTION:
XS GIS Cut Line= 4
      2777566.52     10059994.44      2777384.21     10059800.85
      2777252.27     10059744.43      2777027.46     10059845.99
#Sta/Elev= 30
  4656.5 1597.13  4698.3 1594.82  4740.3 1593.46  4896.1 1585.13    4917 1582.97
  4922.4 1582.97  4925.5 1582.11  4939.5 1580.87  4961.3 1577.49  4972.2  1576.4
  4978.1 1575.16  4993.9 1573.25  5006.9 1572.64  5010.2 1573.14  5015.7 1575.87
  5030.8 1580.07  5037.4 1583.38  5054.4 1584.91  5059.8 1584.55  5081.5 1585.99
  5104.6 1586.55  5173.9 1590.03  5190.8 1591.21    5197 1592.17  5248.8 1594.34
  5278.6 1596.53  5289.5 1596.73    5295 1595.34  5300.5 1597.05  5312.6  1597.7
#Mann= 3 , 0 , 0
  4656.5     .07       0  4972.2     .03       0  5015.7     .07       0
Bank Sta=4972.2,5015.7
XS Rating Curve= 0 ,0
Exp/Cntr=0.3,0.1

Chan Stop Cuts=-1
Use User Specified Reach Order=0
Composite Channel Slope=5