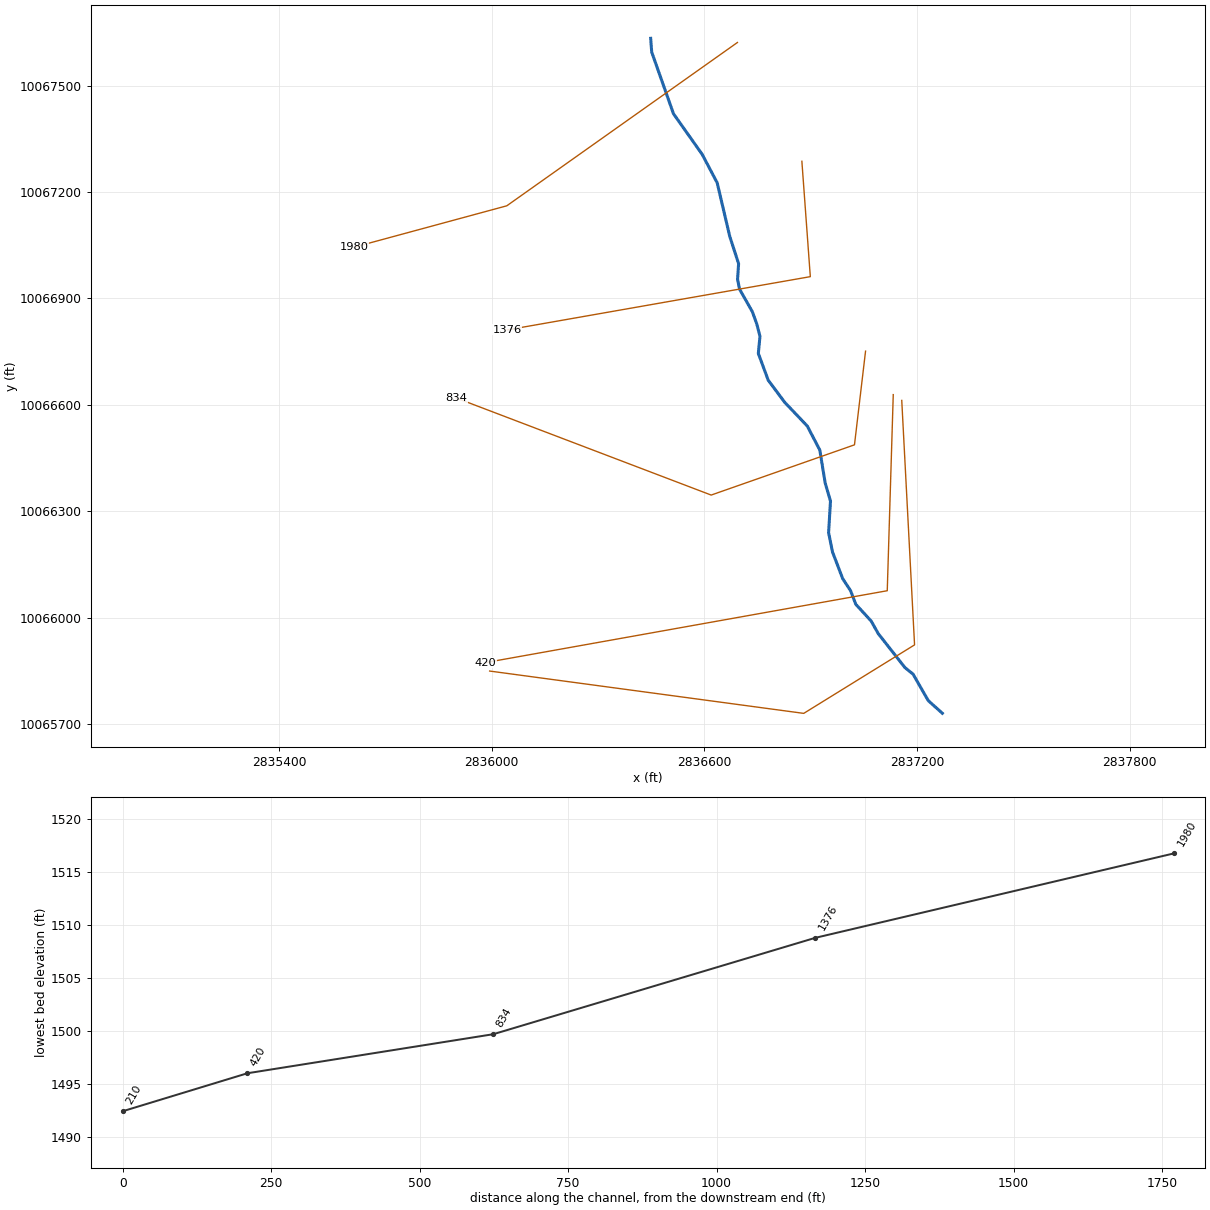
--- UNT011 IN NNOGR.prj (project) ---

Proj Title=UNT011 IN NNOGR Base Level Engineering
Current Plan=p01
Default Exp/Contr=0.3,0.1
English Units
Geom File=g01
Flow File=f01
Plan File=p01
Y Axis Title=Elevation
X Axis Title(PF)=Main Channel Distance
X Axis Title(XS)=Station
BEGIN DESCRIPTION:
UNT011 IN NNOGR
END DESCRIPTION:
DSS Export Rating Curves= 0
DSS Export Rating Curve Sorted= 0
DSS Export Volume Flow Curves= 0
DXF OffsetX= 0
DXF OffsetY= 0
DXF ScaleX= 1
DXF ScaleY= 10

--- UNT011 IN NNOGR.p01 (plan) ---

Plan Title=Multiple Run
Short Identifier=Multiple
Geom File=g01
Flow File=f01
Subcritical Flow
K Sum by GR= 0
Std Step Tol= 0.01
Critical Tol= 0.01
Num of Std Step Trials= 20
Max Error Tol= 0.3
Flow Tol Ratio= 0.001
Split Flow NTrial= 30
Split Flow Tol= 0.02
Split Flow Ratio= 0.02
Log Output Level= 0
Friction Slope Method= 1
Unsteady Friction Slope Method= 2
Unsteady Bridges Friction Slope Method= 1
Parabolic Critical Depth
Global Vel Dist=  1 , 1 , 1
Global Log Level= 0
CheckData=True
Encroach Param= -1, 0, 0, 0
BEGIN DESCRIPTION:
Multiple Run
END DESCRIPTION:

--- UNT011 IN NNOGR.f01 (steady flow) ---

Flow Title=Multiple
Program Version=4.10
Number of Profiles= 7
Profile Names=10-year,25-year,50-year,1pct_min,100-year,1pct_plu,500-year
River Rch & RM=UNT011 IN NNOGR,Reach-1         ,1980
     904    1319    1682    1572    2126    2876    3408
Boundary for River Rch & Prof#=UNT011 IN NNOGR,Reach-1         , 1
Up Type= 0
Dn Type= 3
Dn Slope=0.011
Boundary for River Rch & Prof#=UNT011 IN NNOGR,Reach-1         , 2
Up Type= 0
Dn Type= 3
Dn Slope=0.011
Boundary for River Rch & Prof#=UNT011 IN NNOGR,Reach-1         , 3
Up Type= 0
Dn Type= 3
Dn Slope=0.011
Boundary for River Rch & Prof#=UNT011 IN NNOGR,Reach-1         , 4
Up Type= 0
Dn Type= 3
Dn Slope=0.011
Boundary for River Rch & Prof#=UNT011 IN NNOGR,Reach-1         , 5
Up Type= 0
Dn Type= 3
Dn Slope=0.011
Boundary for River Rch & Prof#=UNT011 IN NNOGR,Reach-1         , 6
Up Type= 0
Dn Type= 3
Dn Slope=0.011
Boundary for River Rch & Prof#=UNT011 IN NNOGR,Reach-1         , 7
Up Type= 0
Dn Type= 3
Dn Slope=0.011
DSS Import GetInterval= 0
DSS Import GetPeak= 0
DSS Import FillOption= 0

--- UNT011 IN NNOGR.g01 (geometry) ---

Geom Title=Existing Conditions
Program Version=4.10

River Reach=UNT011 IN NNOGR ,Reach-1
Reach XY= 30
      2836448.49     10067633.65      2836451.39     10067594.95
      2836512.87     10067420.84      2836593.74     10067306.45
      2836636.03     10067226.33      2836671.54     10067075.05
      2836696.53       10066998.      2836693.58     10066954.35
      2836699.14     10066926.36      2836735.35      10066862.4
      2836747.69     10066828.29      2836756.76     10066793.39
      2836752.14     10066744.89      2836780.02      10066669.4
      2836826.43     10066607.19      2836890.21     10066540.15
       2836925.5      10066472.5      2836940.77     10066379.22
      2836955.71     10066328.25       2836950.3     10066239.25
      2836961.36     10066184.94      2836990.19     10066109.45
      2837012.25     10066075.87      2837027.07     10066037.31
      2837070.26     10065990.32      2837090.45     10065954.55
       2837165.4      10065859.1      2837188.57     10065840.35
       2837231.5     10065765.56      2837271.16     10065729.99

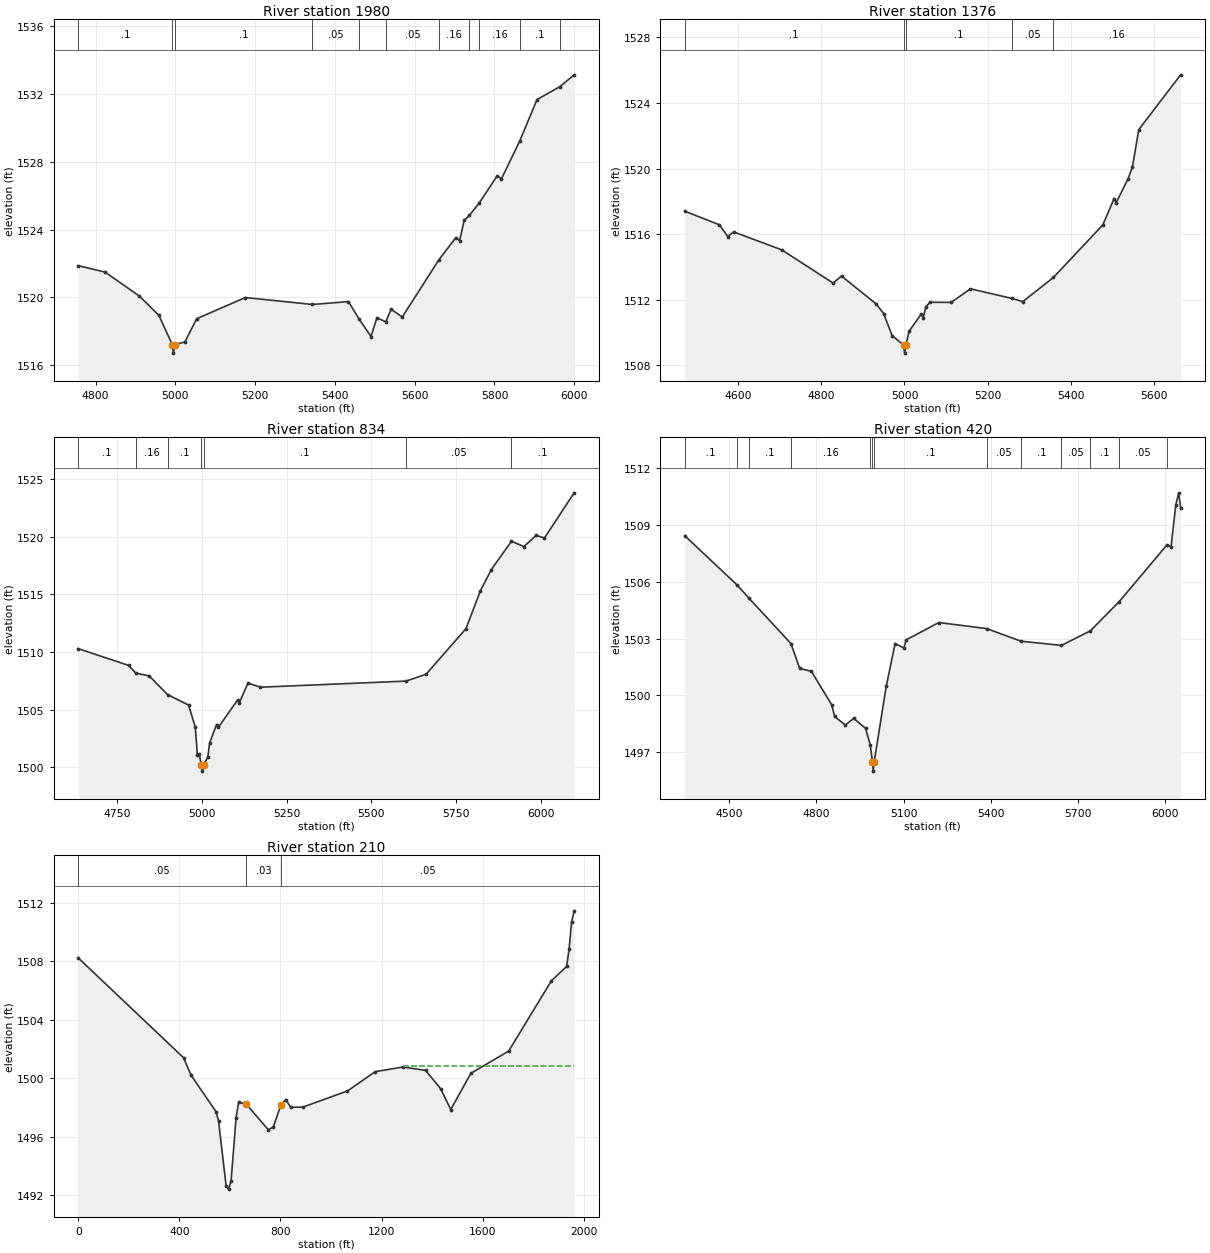
Type RM Length L Ch R = 1 ,1980    ,604,604,604
BEGIN DESCRIPTION:
UNT011 IN NNOGR 3.0
END DESCRIPTION:
XS GIS Cut Line= 3
       2836693.2     10067621.95       2836042.7     10067161.31
      2835612.41     10067044.68
#Sta/Elev= 30
  4756.9 1521.87    4824 1521.49  4909.7 1520.08  4958.8 1518.94  4992.5 1517.21
  4995.3 1516.71  4998.5 1517.21  5024.1 1517.37  5053.6 1518.74  5175.5 1519.99
  5343.8 1519.58  5433.9 1519.75  5460.8 1518.72  5490.5 1517.69  5505.3 1518.79
  5527.7 1518.56    5541  1519.3  5568.9 1518.84  5660.8 1522.22  5703.4 1523.53
  5712.7 1523.35  5724.1 1524.54  5737.3 1524.84  5761.9 1525.57    5807 1527.18
  5817.4 1526.99  5862.9  1529.2  5906.7 1531.67    5964 1532.43  5999.8 1533.13
#Mann= 11 ,-1 , 0
  4756.9      .1       0  4992.5     .07       0  4998.5      .1       0
  5343.8     .05       0  5460.8      .1       0  5527.7     .05       0
  5660.8     .16       0  5737.3      .1       0  5761.9     .16       0
  5862.9      .1       0    5964     .05       0
Bank Sta=4992.5,4998.5
XS Rating Curve= 0 ,0
Exp/Cntr=0.3,0.1

Type RM Length L Ch R = 1 ,1376    ,542,542,542
BEGIN DESCRIPTION:
Mapping XS 8be9abdf
END DESCRIPTION:
XS GIS Cut Line= 3
      2836874.97     10067286.93      2836898.77     10066961.49
      2836044.07     10066811.29
#Sta/Elev= 30
    4471  1517.4  4554.4 1516.57  4574.5 1515.85  4588.5 1516.14  4704.8 1515.04
  4828.1 1513.02  4848.4 1513.45  4931.7 1511.75  4949.9 1511.16  4970.2 1509.82
  4997.7 1509.25  5000.4 1508.75  5003.7 1509.25  5010.8 1510.07  5040.3 1511.13
  5045.4  1510.9  5051.4 1511.58  5061.6 1511.85  5112.4 1511.84    5159 1512.67
  5259.2 1512.08    5285 1511.89  5358.7 1513.36  5477.9 1516.57  5504.9 1518.17
    5510 1517.92  5538.8 1519.39    5549 1520.09  5564.3 1522.37  5665.1 1525.71
#Mann= 5 ,-1 , 0
    4471      .1       0  4997.7     .07       0  5003.7      .1       0
  5259.2     .05       0  5358.7     .16       0
Bank Sta=4997.7,5003.7
XS Rating Curve= 0 ,0
Exp/Cntr=0.3,0.1

Type RM Length L Ch R = 1 ,834     ,414,414,414
BEGIN DESCRIPTION:
Mapping XS 01a8ae3d
END DESCRIPTION:
XS GIS Cut Line= 4
      2837054.57     10066751.41      2837023.32     10066487.12
      2836619.13     10066345.46      2835899.93     10066619.32
#Sta/Elev= 30
  4634.6 1510.29  4783.3 1508.84  4804.2 1508.17  4843.7 1507.93    4898 1506.31
  4960.2  1505.4  4980.1 1503.46    4986 1501.06  4991.3 1501.14  4998.2 1500.17
    5001 1499.67  5004.2 1500.17    5017 1500.91  5022.4 1502.14  5042.7 1503.71
    5048 1503.46  5104.7 1505.84    5110 1505.61  5135.7 1507.31    5172 1506.95
  5602.6 1507.48  5661.5 1508.08  5779.2 1512.03    5822 1515.33  5854.1 1517.15
  5913.4 1519.61  5950.4 1519.15  5986.2 1520.12  6010.9 1519.89  6098.6 1523.81
#Mann= 7 ,-1 , 0
  4634.6      .1       0  4804.2     .16       0    4898      .1       0
  4998.2     .07       0  5004.2      .1       0  5602.6     .05       0
  5913.4      .1       0
Bank Sta=4998.2,5004.2
XS Rating Curve= 0 ,0
Exp/Cntr=0.3,0.1

Type RM Length L Ch R = 1 ,420     ,210,210,210
BEGIN DESCRIPTION:
UNT011 IN NNOGR 1.0
END DESCRIPTION:
XS GIS Cut Line= 3
       2837132.7     10066628.75      2837115.77     10066075.66
      2835981.92     10065872.82
#Sta/Elev= 30
  4347.7 1508.44  4525.9 1505.86  4568.8 1505.13  4712.6 1502.74  4742.9 1501.42
  4782.9 1501.27    4853  1499.5    4863 1498.88  4899.5 1498.43  4928.8 1498.78
  4969.4 1498.25  4985.7 1497.37    4993 1496.49  4995.7 1495.99    4999 1496.49
  5040.5 1500.48    5071 1502.74  5101.5  1502.5  5108.7 1502.93  5221.3 1503.85
  5385.5 1503.53  5504.4 1502.86  5642.9 1502.64  5742.4 1503.41  5841.9 1504.96
  6004.6 1507.93  6020.1 1507.86  6036.1 1510.06  6046.3 1510.71  6052.9 1509.92
#Mann= 13 ,-1 , 0
  4347.7      .1       0  4525.9     .16       0  4568.8      .1       0
  4712.6     .16       0  4985.7      .1       0    4993     .07       0
    4999      .1       0  5385.5     .05       0  5504.4      .1       0
  5642.9     .05       0  5742.4      .1       0  5841.9     .05       0
  6004.6      .1       0
Bank Sta=4993,4999
XS Rating Curve= 0 ,0
Exp/Cntr=0.3,0.1

Type RM Length L Ch R = 1 ,210     ,0,0,0
XS GIS Cut Line= 4
     2837156.666    10066612.453     2837192.793     10065922.91
     2836880.221    10065729.712     2835994.339    10065849.087
#Sta/Elev= 30
       0 1508.23  416.23 1501.41  445.96 1500.21  545.06 1497.71  554.97 1497.07
   584.7 1492.65  594.61 1492.41  604.52 1492.98  624.34  1497.3  634.25 1498.35
  663.98 1498.23  752.36 1496.47  771.92 1496.68  801.24 1498.15  820.79 1498.54
  840.34 1498.01  889.22 1498.03 1065.19 1499.13 1174.82 1500.45 1284.45 1500.77
 1374.15 1500.54 1433.95 1499.28 1473.82 1497.86 1553.55 1500.34 1703.05 1501.86
 1872.49 1506.68 1932.29 1507.65 1942.25 1508.86 1952.22 1510.72 1962.19 1511.46
#Mann= 3 , 0 , 0
       0     .05       0  663.98     .03       0  801.24     .05       0
#XS Ineff= 2 , 0
                         1288.89         1500.82
Permanent Ineff=
       F       F
Bank Sta=663.98,801.24
XS Rating Curve= 0 ,0
Exp/Cntr=0.3,0.1

Chan Stop Cuts=-1
Use User Specified Reach Order=0
Composite Channel Slope=5