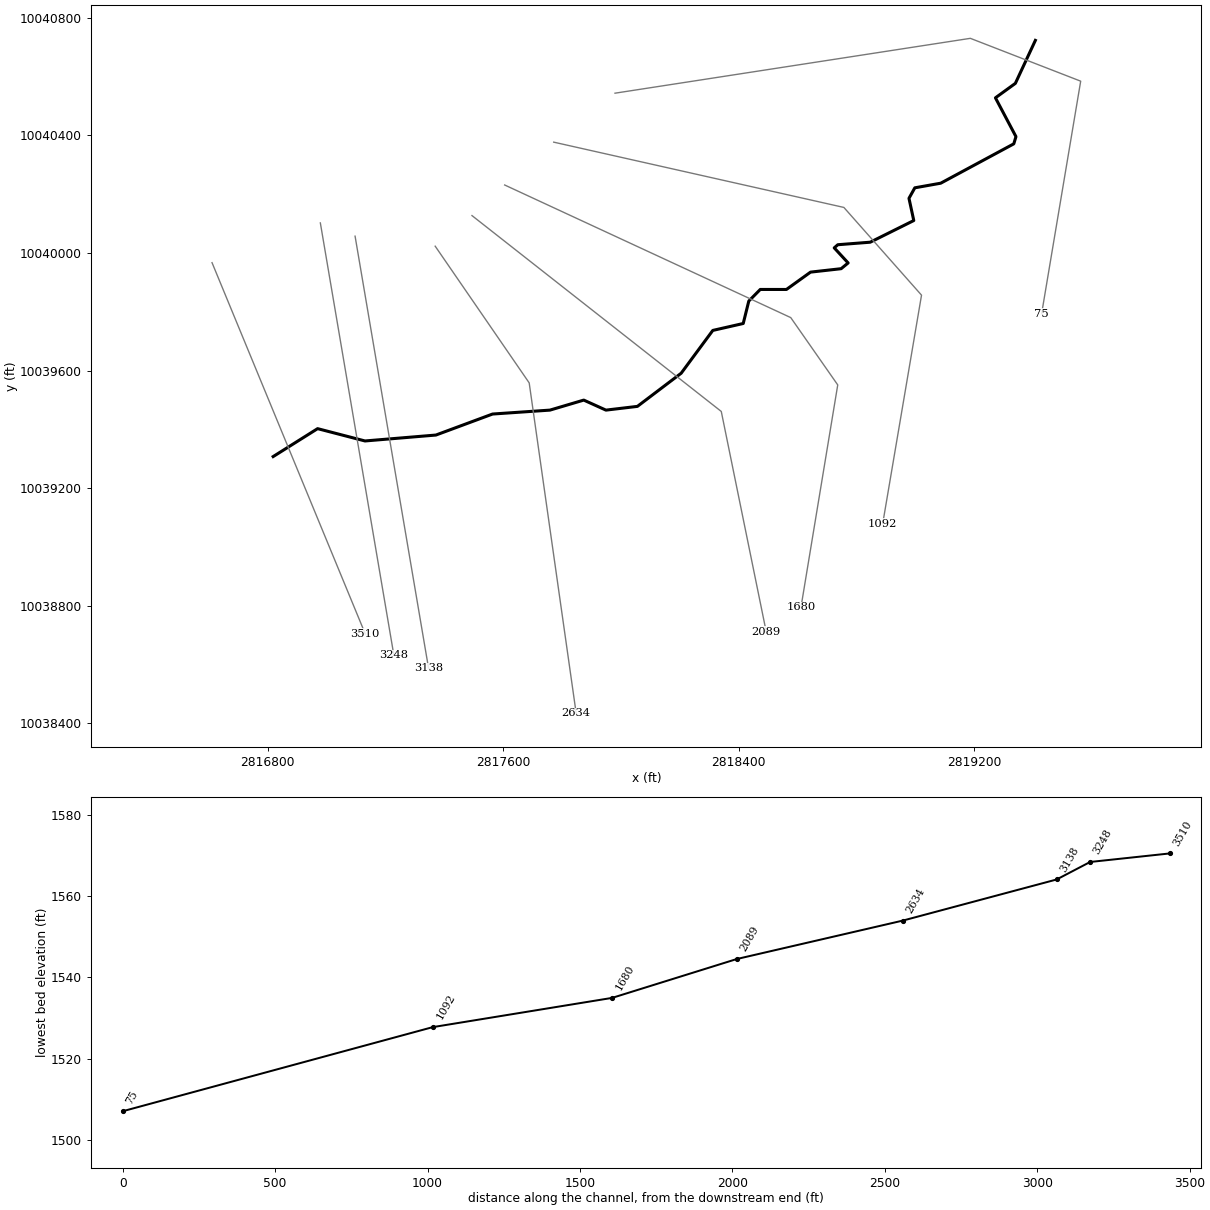
--- UNT011 IN SNOGR.prj (project) ---

Proj Title=UNT011 IN SNOGR Base Level Engineering
Current Plan=p01
Default Exp/Contr=0.3,0.1
English Units
Geom File=g01
Flow File=f01
Plan File=p01
BEGIN DESCRIPTION:
UNT011 IN SNOGR
END DESCRIPTION:

--- UNT011 IN SNOGR.p01 (plan) ---

Plan Title=Multiple Run
Short Identifier=Multiple
Geom File=g01
Flow File=f01
Subcritical Flow
K Sum by GR= 0
Std Step Tol= 0.01
Critical Tol= 0.01
Num of Std Step Trials= 20
Max Error Tol= 0.3
Flow Tol Ratio= 0.001
Split Flow NTrial= 30
Split Flow Tol= 0.02
Split Flow Ratio= 0.02
Log Output Level= 0
Friction Slope Method= 1
Unsteady Friction Slope Method= 2
Unsteady Bridges Friction Slope Method= 1
Parabolic Critical Depth
Global Vel Dist=  1 , 1 , 1
Global Log Level= 0
CheckData=True
Encroach Param= -1, 0, 0, 0
BEGIN DESCRIPTION:
Multiple Run
END DESCRIPTION:

--- UNT011 IN SNOGR.f01 (steady flow) ---

Flow Title=Multiple
Number of Profiles=7
Profile Names=10-year,25-year,50-year,1pct_min,100-year,1pct_plu,500-year
River Rch & RM= UNT011 IN SNOGR,Reach-1,3510
     377     517     634     570     771    1043    1144
Boundary for River Rch & Prof#=UNT011 IN SNOGR,Reach-1,1
Up Type=0
Dn Type=3
Dn Slope=0.005
Boundary for River Rch & Prof#=UNT011 IN SNOGR,Reach-1,2
Up Type=0
Dn Type=3
Dn Slope=0.005
Boundary for River Rch & Prof#=UNT011 IN SNOGR,Reach-1,3
Up Type=0
Dn Type=3
Dn Slope=0.005
Boundary for River Rch & Prof#=UNT011 IN SNOGR,Reach-1,4
Up Type=0
Dn Type=3
Dn Slope=0.005
Boundary for River Rch & Prof#=UNT011 IN SNOGR,Reach-1,5
Up Type=0
Dn Type=3
Dn Slope=0.005
Boundary for River Rch & Prof#=UNT011 IN SNOGR,Reach-1,6
Up Type=0
Dn Type=3
Dn Slope=0.005
Boundary for River Rch & Prof#=UNT011 IN SNOGR,Reach-1,7
Up Type=0
Dn Type=3
Dn Slope=0.005

--- UNT011 IN SNOGR.g01 (geometry) ---

Geom Title=Existing Conditions

River Reach=UNT011 IN SNOGR,Reach-1
Reach XY= 30
      2816818.05     10039307.03      2816969.09     10039402.08
      2817130.16     10039360.15      2817371.14     10039380.29
      2817563.71     10039451.81      2817758.79     10039465.17
      2817873.66     10039499.27      2817948.99     10039465.13
      2818055.94     10039477.87      2818204.72     10039590.75
      2818312.17     10039736.43      2818415.59     10039760.01
      2818434.52     10039836.37      2818473.49     10039875.88
      2818562.44     10039875.85      2818644.35     10039934.88
      2818748.38     10039946.56      2818772.10     10039966.12
      2818724.87     10040017.44      2818737.01     10040028.15
      2818847.22     10040036.74      2818995.22     10040110.49
      2818978.86     10040186.11      2818998.79     10040221.87
      2819086.77     10040237.57      2819335.05     10040371.52
      2819342.48     10040396.05      2819272.67     10040528.19
      2819340.43     10040577.36      2819408.47     10040723.73

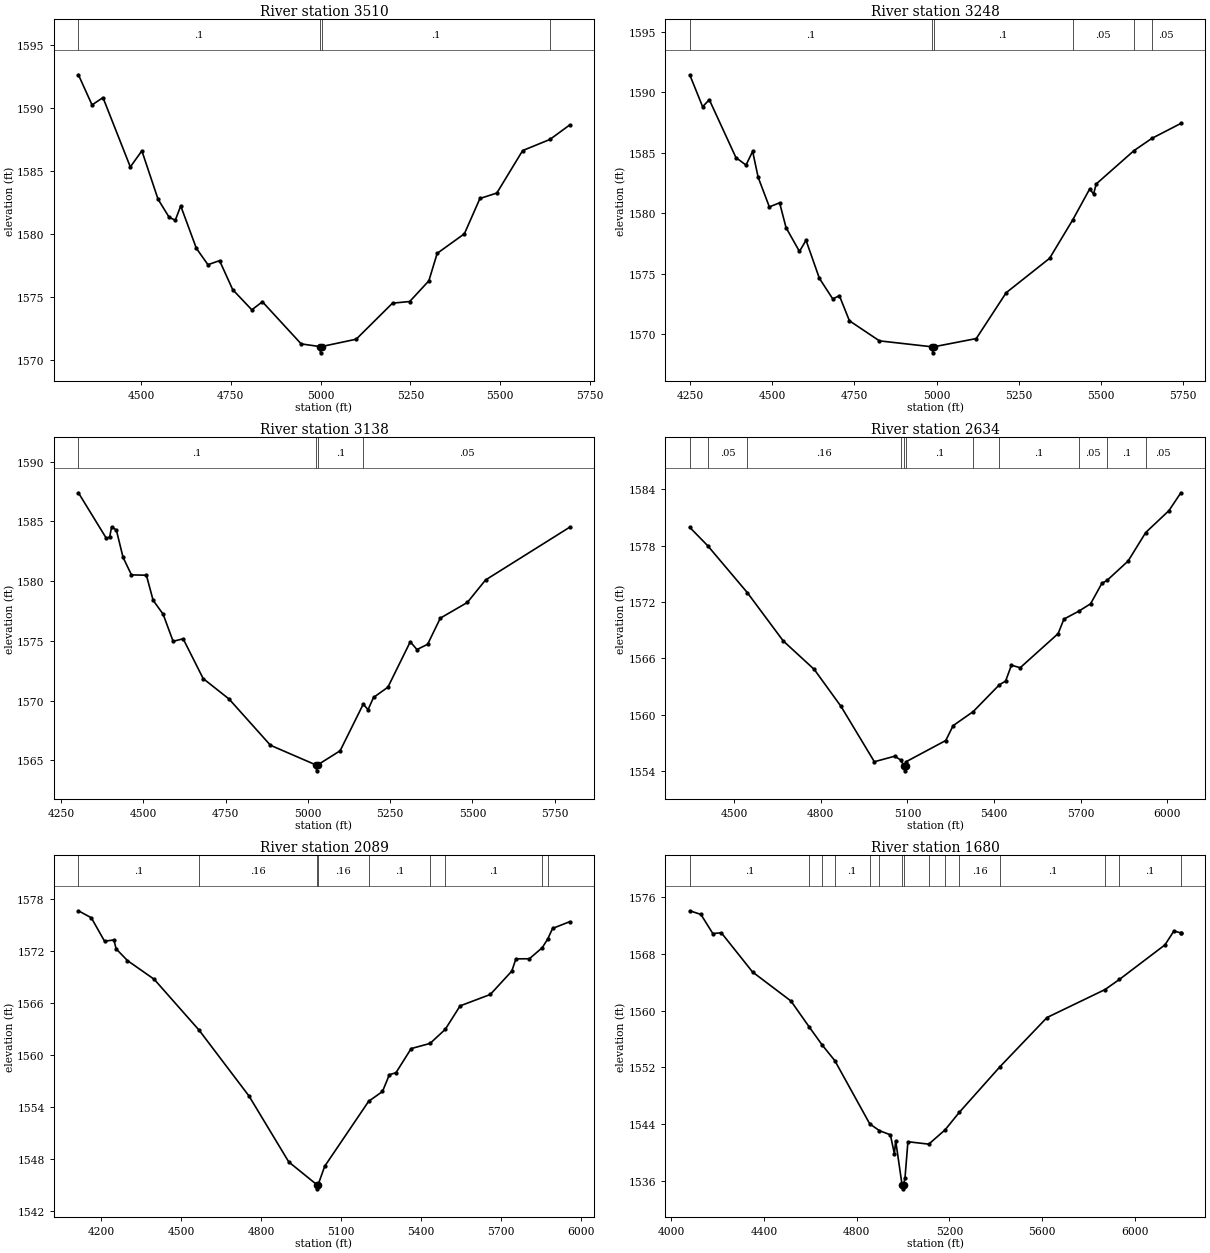
Type RM Length L Ch R = 1,3510,262,262,262
BEGIN DESCRIPTION:
UNT011 IN SNOGR 8.0
END DESCRIPTION:
XS GIS Cut Line= 2
      2816610.34     10039967.01      2817131.18     10038703.12
#Sta/Elev= 30
  4325.9 1592.61  4363.8 1590.22  4394.3 1590.80  4470.4 1585.30  4502.5 1586.58
  4547.6 1582.74  4578.2 1581.32  4595.5 1581.07  4610.7 1582.21  4654.2 1578.85
  4686.4 1577.55  4718.8 1577.87  4755.4 1575.57  4808.6 1573.97  4838.0 1574.61
  4945.9 1571.27  4997.0 1571.06  4999.8 1570.56  5003.0 1571.06  5099.0 1571.64
  5200.2 1574.50  5248.1 1574.63  5301.3 1576.27  5324.5 1578.45  5400.2 1580.00
  5443.5 1582.80  5490.5 1583.23  5562.4 1586.60  5638.2 1587.48  5692.9 1588.62
#Mann=4,-1,0
  4325.9     0.1       0  4997.0    0.07       0  5003.0     0.1       0
  5638.2    0.05       0
Bank Sta=4997,5003
Exp/Cntr=0.3,0.1

Type RM Length L Ch R = 1,3248,110,110,110
BEGIN DESCRIPTION:
UNT011 IN SNOGR 7.0
END DESCRIPTION:
XS GIS Cut Line= 2
      2816978.41     10040102.38      2817228.41     10038630.15
#Sta/Elev= 30
  4249.1 1591.43  4288.3 1588.79  4308.6 1589.37  4389.7 1584.58  4420.2 1583.97
  4440.4 1585.10  4457.1 1582.96  4491.2 1580.51  4522.4 1580.85  4541.9 1578.80
  4582.7 1576.83  4602.7 1577.75  4643.3 1574.61  4683.9 1572.91  4704.2 1573.17
  4734.6 1571.10  4825.9 1569.44  4985.2 1568.95  4987.9 1568.45  4991.2 1568.95
  5120.3 1569.63  5211.3 1573.42  5343.2 1576.26  5413.7 1579.44  5464.9 1581.98
  5477.0 1581.59  5485.2 1582.41  5599.8 1585.16  5654.0 1586.17  5742.4 1587.41
#Mann=6,-1,0
  4249.1     0.1       0  4985.2    0.07       0  4991.2     0.1       0
  5413.7    0.05       0  5599.8     0.1       0  5654.0    0.05       0
Bank Sta=4985.2,4991.2
Exp/Cntr=0.3,0.1

Type RM Length L Ch R = 1,3138,504,504,504
BEGIN DESCRIPTION:
UNT011 IN SNOGR 6.0
END DESCRIPTION:
XS GIS Cut Line= 2
      2817096.45     10040057.31      2817346.15     10038586.86
#Sta/Elev= 30
  4303.3 1587.40  4388.1 1583.59  4398.2 1583.70  4404.1 1584.53  4418.5 1584.29
  4438.8 1582.00  4464.4 1580.53  4509.8 1580.50  4530.1 1578.41  4560.5 1577.24
  4590.9 1574.97  4621.4 1575.18  4682.2 1571.85  4760.8 1570.14  4886.5 1566.27
  5024.1 1564.63  5026.8 1564.13  5030.1 1564.63  5098.1 1565.81  5168.3 1569.71
  5182.9 1569.25  5199.5 1570.27  5243.2 1571.13  5311.1 1574.93  5331.4 1574.28
  5363.8 1574.72  5402.4 1576.91  5484.4 1578.22  5539.6 1580.10  5794.8 1584.51
#Mann=4,-1,0
  4303.3     0.1       0  5024.1    0.07       0  5030.1     0.1       0
  5168.3    0.05       0
Bank Sta=5024.1,5030.1
Exp/Cntr=0.3,0.1

Type RM Length L Ch R = 1,2634,545,545,545
BEGIN DESCRIPTION:
UNT011 IN SNOGR 5.0
END DESCRIPTION:
XS GIS Cut Line= 3
      2817368.72     10040023.18      2817688.19     10039557.86
      2817847.91     10038432.87
#Sta/Elev= 30
  4346.2 1579.94  4407.9 1578.00  4545.3 1573.00  4669.8 1567.85  4777.4 1564.81
  4870.1 1560.87  4985.5 1554.98  5056.2 1555.57  5077.4 1555.15  5088.0 1554.51
  5090.7 1554.01  5094.0 1554.51  5096.6 1555.00  5232.8 1557.24  5258.2 1558.82
  5327.9 1560.32  5418.2 1563.17  5440.0 1563.57  5460.2 1565.26  5490.5 1564.99
  5621.8 1568.62  5642.0 1570.17  5692.8 1571.00  5734.3 1571.80  5773.3 1573.97
  5791.0 1574.28  5864.2 1576.35  5925.3 1579.39  6005.6 1581.72  6046.9 1583.62
#Mann=11,-1,0
  4346.2     0.1       0  4407.9    0.05       0  4545.3    0.16       0
  5077.4     0.1       0  5088.0    0.07       0  5094.0     0.1       0
  5327.9    0.05       0  5418.2     0.1       0  5692.8    0.05       0
  5791.0     0.1       0  5925.3    0.05       0
Bank Sta=5088,5094
Exp/Cntr=0.3,0.1

Type RM Length L Ch R = 1,2089,409,409,409
BEGIN DESCRIPTION:
UNT011 IN SNOGR 4.0
END DESCRIPTION:
XS GIS Cut Line= 3
      2817493.77     10040127.29      2818340.97     10039460.64
      2818493.60     10038711.37
#Sta/Elev= 30
  4113.5 1576.69  4161.9 1575.88  4211.6 1573.17  4246.8 1573.32  4254.9 1572.29
  4297.6 1570.93  4397.7 1568.77  4566.1 1562.89  4753.7 1555.26  4902.8 1547.64
  5007.2 1545.03  5010.0 1544.53  5013.2 1545.03  5037.5 1547.14  5202.4 1554.65
  5254.4 1555.79  5280.2 1557.73  5305.0 1557.96  5361.9 1560.75  5433.0 1561.35
  5490.0 1562.98  5545.6 1565.69  5658.9 1567.01  5739.5 1569.71  5755.0 1571.13
  5805.5 1571.14  5853.8 1572.42  5874.4 1573.43  5892.6 1574.65  5956.2 1575.42
#Mann=9,-1,0
  4113.5     0.1       0  4566.1    0.16       0  5007.2    0.07       0
  5013.2    0.16       0  5202.4     0.1       0  5433.0    0.05       0
  5490.0     0.1       0  5853.8    0.05       0  5874.4     0.1       0
Bank Sta=5007.2,5013.2
Exp/Cntr=0.3,0.1

Type RM Length L Ch R = 1,1680,588,588,588
BEGIN DESCRIPTION:
UNT011 IN SNOGR 3.0
END DESCRIPTION:
XS GIS Cut Line= 4
      2817604.84     10040231.48      2818577.08     10039780.08
      2818736.80     10039550.92      2818611.81     10038794.02
#Sta/Elev= 30
  4079.8 1574.02  4127.9 1573.51  4179.4 1570.82  4216.1 1570.93  4350.7 1565.42
  4516.5 1561.34  4594.0 1557.75  4651.5 1555.14  4705.5 1552.97  4856.3 1544.08
  4897.7 1543.13  4945.2 1542.54  4962.6 1539.88  4968.1 1541.72  4995.9 1535.45
  4998.6 1534.95  5001.9 1535.45  5008.4 1536.51  5020.9 1541.57  5110.8 1541.23
  5181.3 1543.24  5242.3 1545.69  5418.0 1552.11  5620.8 1559.02  5870.5 1562.94
  5933.5 1564.38  6129.6 1569.23  6168.1 1571.17  6196.8 1570.93  6198.2 1570.93
#Mann=15,-1,0
  4079.8     0.1       0  4594.0    0.05       0  4651.5    0.16       0
  4705.5     0.1       0  4856.3    0.05       0  4897.7     0.1       0
  4995.9    0.07       0  5001.9     0.1       0  5110.8    0.16       0
  5181.3     0.1       0  5242.3    0.16       0  5418.0     0.1       0
  5870.5    0.05       0  5933.5     0.1       0  6196.8    0.05       0
Bank Sta=4995.9,5001.9
Exp/Cntr=0.3,0.1

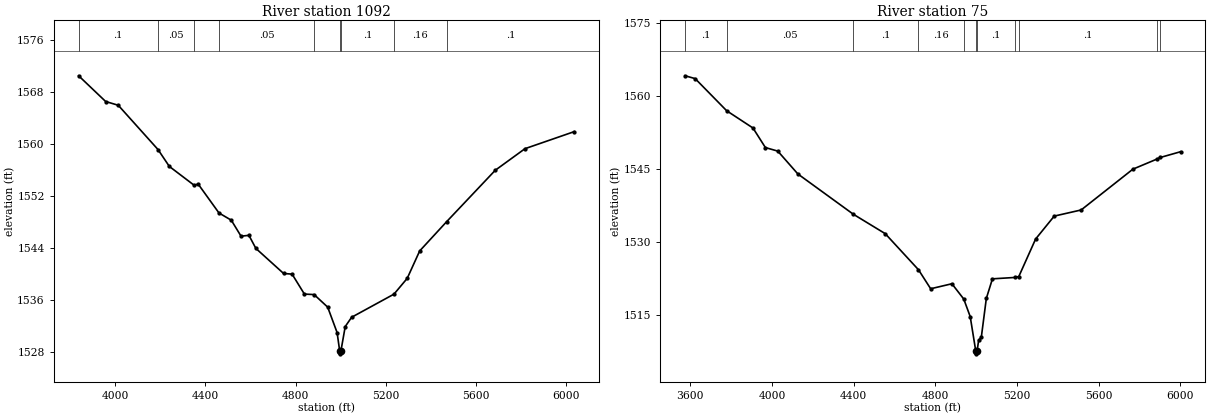
Type RM Length L Ch R = 1,1092,1017,1017,1017
BEGIN DESCRIPTION:
UNT011 IN SNOGR 2.0
END DESCRIPTION:
XS GIS Cut Line= 4
      2817771.54     10040377.30      2818757.64     10040155.08
      2819021.53     10039856.47      2818889.59     10039078.72
#Sta/Elev= 30
  3837.5 1570.55  3957.4 1566.59  4013.3 1566.01  4189.5 1559.20  4239.8 1556.60
  4351.0 1553.67  4367.4 1553.90  4460.1 1549.43  4514.7 1548.32  4557.9 1545.86
  4592.9 1545.99  4623.7 1543.98  4746.7 1540.12  4784.4 1540.02  4838.9 1536.95
  4882.2 1536.87  4942.3 1534.94  4984.1 1531.02  4995.3 1528.25  4998.1 1527.75
  5001.3 1528.25  5020.1 1531.95  5048.5 1533.38  5236.4 1536.94  5295.1 1539.37
  5350.4 1543.59  5470.7 1548.12  5685.8 1556.01  5817.6 1559.33  6035.7 1561.95
#Mann=9,-1,0
  3837.5     0.1       0  4189.5    0.05       0  4351.0     0.1       0
  4460.1    0.05       0  4882.2     0.1       0  4995.3    0.07       0
  5001.3     0.1       0  5236.4    0.16       0  5470.7     0.1       0
Bank Sta=4995.3,5001.3
Exp/Cntr=0.3,0.1

Type RM Length L Ch R = 1,75,0,0,0
BEGIN DESCRIPTION:
UNT011 IN SNOGR 1.0
END DESCRIPTION:
XS GIS Cut Line= 4
      2817979.82     10040543.97      2819187.45     10040730.68
      2819562.45     10040584.85      2819429.63     10039793.15
#Sta/Elev= 30
  3574.7 1564.19  3623.9 1563.61  3778.3 1557.00  3907.2 1553.45  3968.0 1549.43
  4028.7 1548.70  4127.1 1544.00  4399.1 1535.71  4554.9 1531.73  4717.8 1524.31
  4777.5 1520.40  4881.5 1521.43  4939.5 1518.29  4971.2 1514.67  4998.6 1507.52
  5001.4 1507.02  5004.6 1507.52  5012.4 1509.79  5025.6 1510.45  5050.1 1518.41
  5080.0 1522.44  5188.4 1522.72  5209.2 1522.92  5291.4 1530.62  5382.7 1535.34
  5514.5 1536.60  5768.0 1544.99  5885.5 1547.06  5901.9 1547.39  6001.8 1548.58
#Mann=11,-1,0
  3574.7     0.1       0  3778.3    0.05       0  4399.1     0.1       0
  4717.8    0.16       0  4939.5     0.1       0  4998.6    0.07       0
  5004.6     0.1       0  5188.4    0.16       0  5209.2     0.1       0
  5885.5    0.16       0  5901.9     0.1       0
Bank Sta=4998.6,5004.6
Exp/Cntr=0.3,0.1

Chan Stop Cuts=-1