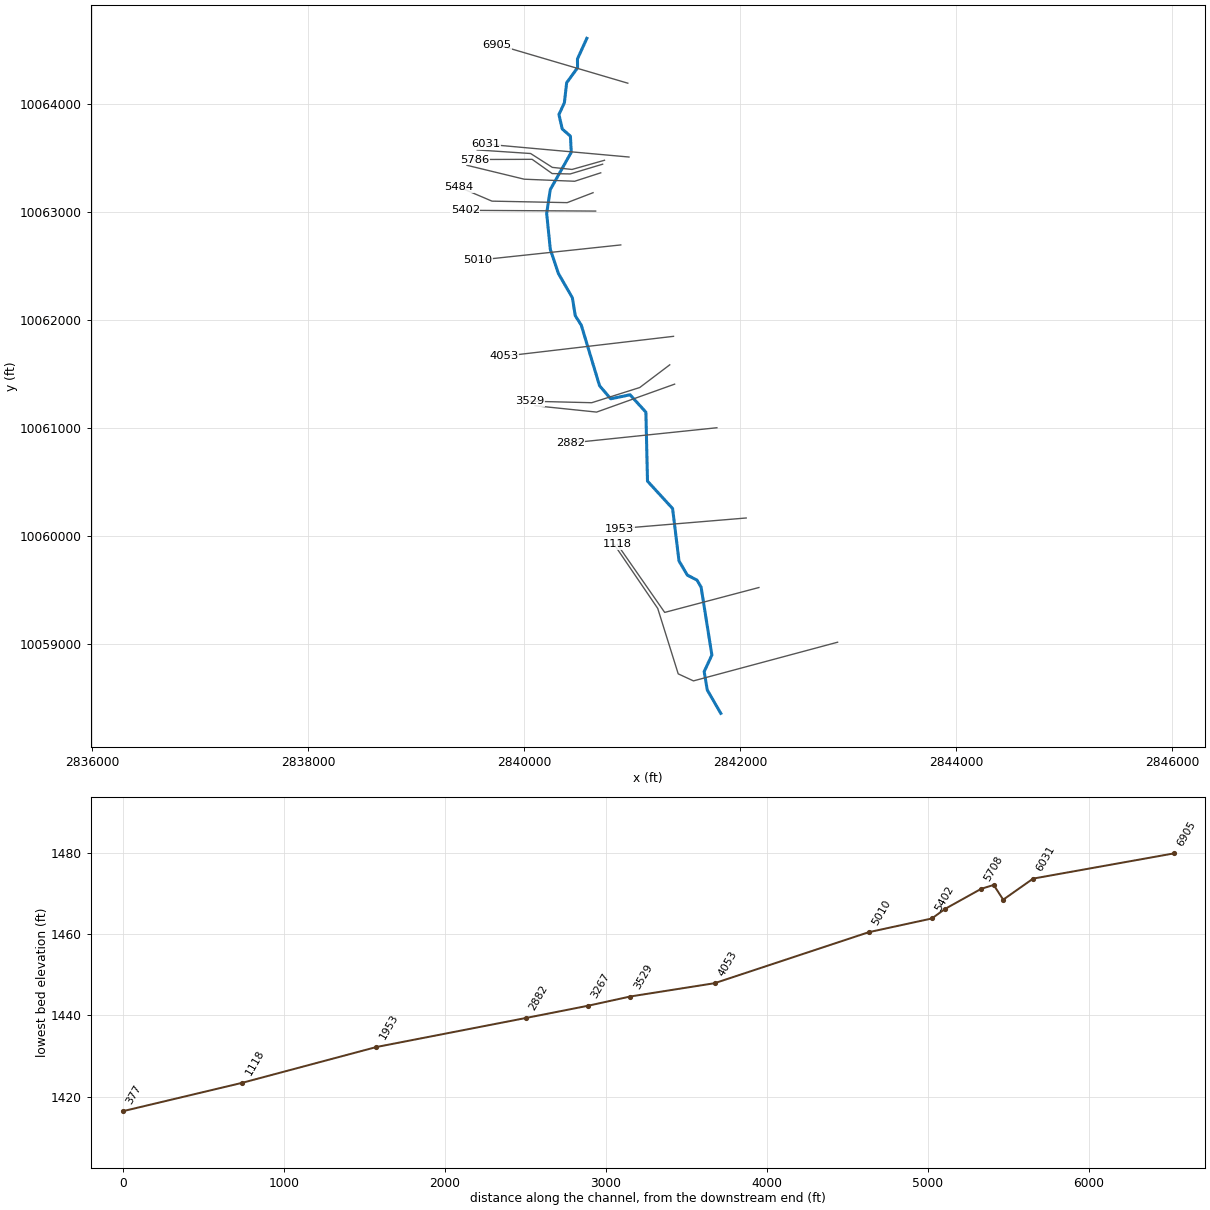
--- UNT012 IN NNOGR.prj (project) ---

Proj Title=UNT012 IN NNOGR Base Level Engineering
Current Plan=p01
Default Exp/Contr=0.3,0.1
English Units
Geom File=g01
Flow File=f01
Plan File=p01
Y Axis Title=Elevation
X Axis Title(PF)=Main Channel Distance
X Axis Title(XS)=Station
BEGIN DESCRIPTION:
UNT012 IN NNOGR
END DESCRIPTION:
DSS Export Rating Curves= 0
DSS Export Rating Curve Sorted= 0
DSS Export Volume Flow Curves= 0
DXF OffsetX= 0
DXF OffsetY= 0
DXF ScaleX= 1
DXF ScaleY= 10

--- UNT012 IN NNOGR.p01 (plan) ---

Plan Title=Multiple Run
Short Identifier=Multiple
Geom File=g01
Flow File=f01
Subcritical Flow
K Sum by GR= 0
Std Step Tol= 0.01
Critical Tol= 0.01
Num of Std Step Trials= 20
Max Error Tol= 0.3
Flow Tol Ratio= 0.001
Split Flow NTrial= 30
Split Flow Tol= 0.02
Split Flow Ratio= 0.02
Log Output Level= 0
Friction Slope Method= 1
Unsteady Friction Slope Method= 2
Unsteady Bridges Friction Slope Method= 1
Parabolic Critical Depth
Global Vel Dist=  1 , 1 , 1
Global Log Level= 0
CheckData=True
Encroach Param= -1, 0, 0, 0
BEGIN DESCRIPTION:
Multiple Run
END DESCRIPTION:

--- UNT012 IN NNOGR.f01 (steady flow) ---

Flow Title=Multiple
Program Version=4.10
Number of Profiles= 7
Profile Names=10-year,25-year,50-year,1pct_min,100-year,1pct_plu,500-year
River Rch & RM=UNT012 IN NNOGR,Reach-1         ,6905
     729    1036    1299    1191    1611    2179    2488
Boundary for River Rch & Prof#=UNT012 IN NNOGR,Reach-1         , 1
Up Type= 0
Dn Type= 3
Dn Slope=0.009
Boundary for River Rch & Prof#=UNT012 IN NNOGR,Reach-1         , 2
Up Type= 0
Dn Type= 3
Dn Slope=0.009
Boundary for River Rch & Prof#=UNT012 IN NNOGR,Reach-1         , 3
Up Type= 0
Dn Type= 3
Dn Slope=0.009
Boundary for River Rch & Prof#=UNT012 IN NNOGR,Reach-1         , 4
Up Type= 0
Dn Type= 3
Dn Slope=0.009
Boundary for River Rch & Prof#=UNT012 IN NNOGR,Reach-1         , 5
Up Type= 0
Dn Type= 3
Dn Slope=0.009
Boundary for River Rch & Prof#=UNT012 IN NNOGR,Reach-1         , 6
Up Type= 0
Dn Type= 3
Dn Slope=0.009
Boundary for River Rch & Prof#=UNT012 IN NNOGR,Reach-1         , 7
Up Type= 0
Dn Type= 3
Dn Slope=0.009
DSS Import GetInterval= 0
DSS Import GetPeak= 0
DSS Import FillOption= 0

--- UNT012 IN NNOGR.g01 (geometry) ---

Geom Title=Existing Conditions
Program Version=4.10

River Reach=UNT012 IN NNOGR ,Reach-1
Reach XY= 30
      2840578.47     10064603.73      2840491.47     10064412.42
      2840492.61     10064331.27      2840391.47     10064192.49
      2840370.41     10064006.28      2840319.91     10063897.93
      2840350.69     10063764.44      2840426.39     10063697.95
      2840434.09     10063548.94      2840239.88     10063203.06
      2840206.46     10062982.66       2840240.3     10062649.49
      2840314.84     10062426.85      2840444.38     10062202.04
      2840471.48     10062034.98      2840526.96     10061948.11
      2840695.98     10061387.41      2840799.51     10061266.24
      2840978.47     10061303.73      2841125.11      10061142.4
      2841140.01     10060503.89      2841372.32     10060250.54
      2841431.69     10059764.98      2841508.95     10059633.78
      2841597.89     10059587.73       2841636.3     10059522.43
      2841736.14     10058893.72      2841664.82      10058740.4
      2841693.22     10058570.76      2841818.47     10058353.73

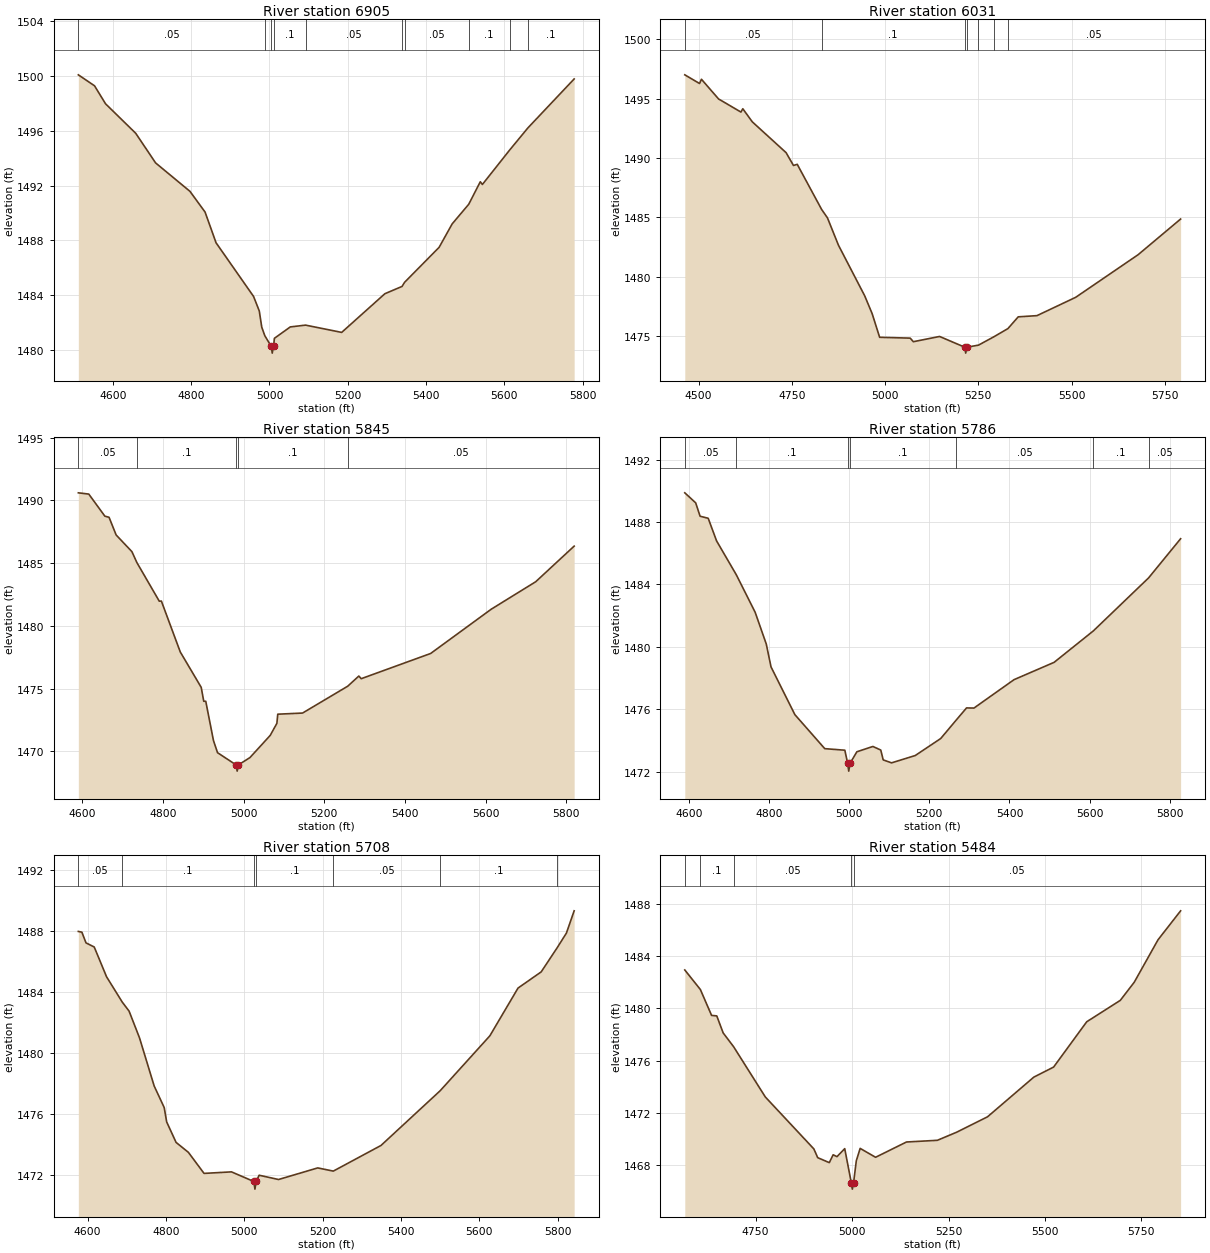
Type RM Length L Ch R = 1 ,6905    ,874,874,874
BEGIN DESCRIPTION:
UNT012 IN NNOGR 8.0
END DESCRIPTION:
XS GIS Cut Line= 2
      2840957.83     10064188.39      2839743.06     10064546.31
#Sta/Elev= 30
  4511.8 1500.07  4553.2 1499.27  4581.3 1497.96  4658.4 1495.81  4709.2 1493.65
  4796.9 1491.58  4835.5 1490.07  4863.6 1487.83  4959.4 1483.92    4974 1482.86
  4980.3 1481.68  4988.1 1481.06  5004.3 1480.29  5007.1 1479.79  5010.3 1480.29
  5012.6 1480.87  5053.2  1481.7  5092.3 1481.83  5184.4  1481.3  5294.8 1484.12
  5338.6 1484.65  5345.1 1484.95  5433.3  1487.5  5466.7 1489.21    5509 1490.64
  5538.5 1492.28  5543.8 1492.08  5613.2 1494.58    5660  1496.2  5778.2 1499.77
#Mann= 10 ,-1 , 0
  4511.8     .05       0  4988.1      .1       0  5004.3     .07       0
  5010.3      .1       0  5092.3     .05       0  5338.6      .1       0
  5345.1     .05       0    5509      .1       0  5613.2     .05       0
    5660      .1       0
Bank Sta=5004.3,5010.3
XS Rating Curve= 0 ,0
Exp/Cntr=0.3,0.1

Type RM Length L Ch R = 1 ,6031    ,186,186,186
BEGIN DESCRIPTION:
UNT012 IN NNOGR 7.0
END DESCRIPTION:
XS GIS Cut Line= 2
      2840968.68     10063504.79      2839644.95     10063624.14
#Sta/Elev= 30
  4463.1 1496.99  4502.7 1496.26  4507.7 1496.62  4553.7 1494.96  4613.6 1493.86
  4618.6 1494.14    4644 1493.04  4734.6 1490.45  4754.5 1489.37  4764.5 1489.47
    4830 1485.67  4845.5 1484.97    4875 1482.67  4945.3 1478.42  4965.3 1476.92
  4985.4 1474.93  5067.3 1474.86  5075.8 1474.56  5146.1    1475  5213.4  1474.1
  5216.1  1473.6  5219.4  1474.1  5250.3 1474.27  5290.8 1474.96  5329.2 1475.66
  5356.9 1476.65  5407.1 1476.75  5510.9 1478.29  5678.2 1481.87  5792.2 1484.87
#Mann= 7 ,-1 , 0
  4463.1     .05       0    4830      .1       0  5213.4     .07       0
  5219.4      .1       0  5250.3     .05       0  5290.8      .1       0
  5329.2     .05       0
Bank Sta=5213.4,5219.4
XS Rating Curve= 0 ,0
Exp/Cntr=0.3,0.1

Type RM Length L Ch R = 1 ,5845    ,59,59,59
BEGIN DESCRIPTION:
Mapping XS ad71abe4
END DESCRIPTION:
XS GIS Cut Line= 5
      2840741.76     10063474.85      2840441.45     10063389.79
      2840259.16     10063408.89      2840057.77     10063537.36
      2839563.25     10063570.33
#Sta/Elev= 30
  4589.7 1490.61  4615.6 1490.51  4655.5 1488.75  4665.9 1488.66  4683.5 1487.25
  4722.6 1485.92  4735.1 1485.04  4790.5 1481.97  4795.7 1481.98  4842.6 1477.92
  4894.5  1475.1  4900.8 1473.99  4905.8 1473.99  4924.9 1470.86    4935 1469.89
  4980.9 1468.92  4983.7 1468.42  4986.9 1468.92  5015.4  1469.5  5065.7 1471.27
  5082.2 1472.23  5084.4 1472.96  5145.9 1473.05  5257.9 1475.19  5285.5    1476
  5291.4 1475.79  5463.6  1477.8  5613.9 1481.33  5724.2 1483.52  5819.6 1486.36
#Mann= 5 ,-1 , 0
  4589.7     .05       0  4735.1      .1       0  4980.9     .07       0
  4986.9      .1       0  5257.9     .05       0
Bank Sta=4980.9,4986.9
XS Rating Curve= 0 ,0
Exp/Cntr=0.3,0.1

Type RM Length L Ch R = 1 ,5786    ,78,78,78
BEGIN DESCRIPTION:
Mapping XS 67da7064
END DESCRIPTION:
XS GIS Cut Line= 5
      2840724.43      10063438.4      2840424.09     10063348.13
      2840257.42      10063351.6      2840071.66     10063483.54
      2839542.83     10063481.81
#Sta/Elev= 30
    4590 1489.87  4617.1 1489.23  4628.2 1488.37  4648.4 1488.24  4669.3 1486.79
  4718.5 1484.62  4765.5 1482.22  4793.3 1480.18  4805.1 1478.72  4864.6 1475.66
  4939.2 1473.48  4989.3 1473.38  4996.3 1472.54    4999 1472.04  5002.3 1472.54
  5019.3 1473.28  5059.3 1473.62  5078.9 1473.39    5085 1472.76  5105.9 1472.57
    5165 1473.04  5228.5 1474.13  5266.8  1475.3  5292.9 1476.09  5311.4 1476.08
  5411.4  1477.9  5511.4 1479.01  5609.1 1481.02  5747.1 1484.42    5827 1486.93
#Mann= 7 ,-1 , 0
    4590     .05       0  4718.5      .1       0  4996.3     .07       0
  5002.3      .1       0  5266.8     .05       0  5609.1      .1       0
  5747.1     .05       0
Bank Sta=4996.3,5002.3
XS Rating Curve= 0 ,0
Exp/Cntr=0.3,0.1

Type RM Length L Ch R = 1 ,5708    ,224,224,224
BEGIN DESCRIPTION:
Mapping XS 82711110
END DESCRIPTION:
XS GIS Cut Line= 4
      2840707.11     10063358.55      2840465.76     10063280.42
      2839998.74     10063299.51      2839469.19       10063428.
#Sta/Elev= 30
  4576.5 1487.96  4585.6 1487.91  4596.1 1487.21  4617.1 1486.94  4648.6 1484.99
  4688.7 1483.33  4706.1 1482.74  4732.7 1480.99  4770.1 1477.84  4795.8 1476.42
  4802.1 1475.48  4826.1 1474.14  4857.5 1473.49  4897.5 1472.11  4967.6 1472.21
  5024.6 1471.58  5027.4 1471.08  5030.6 1471.58  5038.2 1471.99  5087.7 1471.71
  5187.8 1472.47  5227.5 1472.26  5349.3 1473.94  5500.2 1477.52  5627.2 1481.12
  5699.2 1484.25  5758.3 1485.31  5799.1 1486.89  5822.7 1487.85  5842.5 1489.31
#Mann= 7 ,-1 , 0
  4576.5     .05       0  4688.7      .1       0  5024.6     .07       0
  5030.6      .1       0  5227.5     .05       0  5500.2      .1       0
  5799.1     .05       0
Bank Sta=5024.6,5030.6
XS Rating Curve= 0 ,0
Exp/Cntr=0.3,0.1

Type RM Length L Ch R = 1 ,5484    ,82,82,82
BEGIN DESCRIPTION:
Mapping XS b53e52f9
END DESCRIPTION:
XS GIS Cut Line= 4
      2840635.89     10063174.51      2840396.31      10063082.5
      2839700.13     10063096.39      2839394.57      10063226.6
#Sta/Elev= 30
  4566.5 1482.94  4606.9 1481.44  4635.9 1479.46  4649.4 1479.42  4665.9 1478.12
    4693 1477.06  4775.2 1473.21    4901 1469.23    4911 1468.56    4941 1468.18
    4951 1468.78    4961 1468.64    4981 1469.25    4998 1466.65  5000.8 1466.15
    5004 1466.65    5011 1468.32    5021 1469.27    5061 1468.59    5141 1469.76
  5221.1 1469.89  5271.1 1470.51  5351.1 1471.69  5471.1 1474.73  5522.4  1475.5
  5608.2 1478.97  5695.2 1480.61  5731.4    1482    5793 1485.25  5851.6 1487.47
#Mann= 5 ,-1 , 0
  4566.5     .05       0  4606.9      .1       0    4693     .05       0
    4998     .04       0    5004     .05       0
Bank Sta=4998,5004
XS Rating Curve= 0 ,0
Exp/Cntr=0.3,0.1

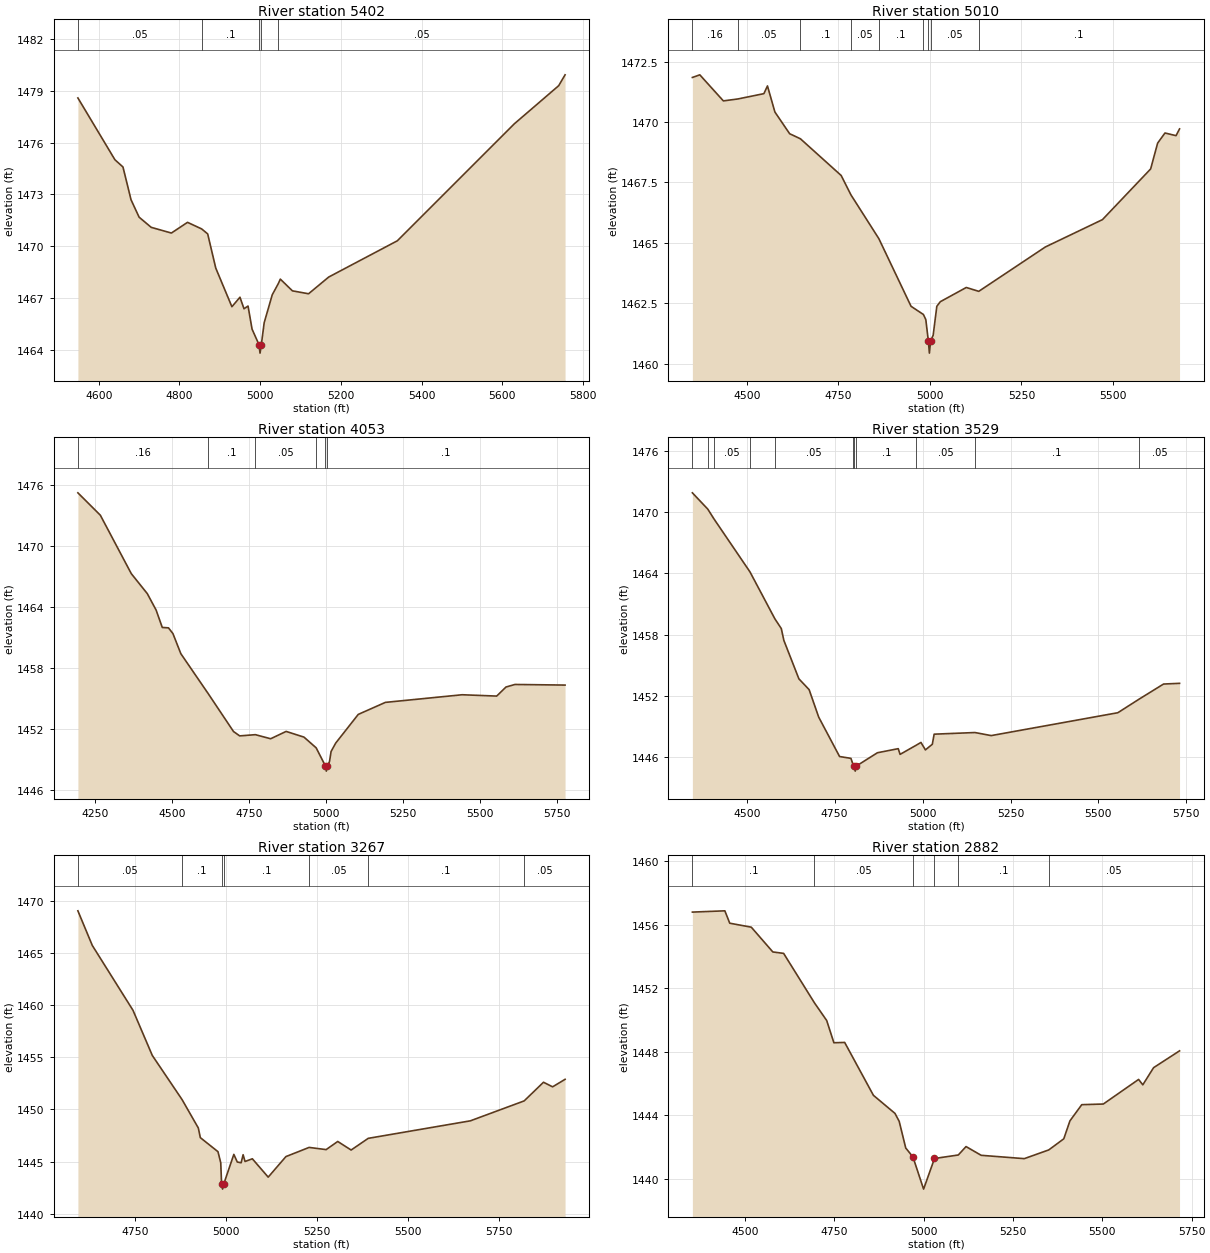
Type RM Length L Ch R = 1 ,5402    ,392,392,392
BEGIN DESCRIPTION:
Mapping XS 1159440f
END DESCRIPTION:
XS GIS Cut Line= 2
      2840660.16     10063004.38      2839452.68     10063011.32
#Sta/Elev= 30
  4548.2 1478.59  4639.9 1475.01  4659.9 1474.59  4679.9 1472.69  4699.9 1471.68
  4729.9 1471.09  4779.9 1470.76  4819.9 1471.38  4854.9    1471  4869.9 1470.71
  4889.9 1468.73  4929.9 1466.49  4949.9 1467.04  4959.9 1466.37  4969.9 1466.53
  4979.9 1465.19  4996.9  1464.3  4999.7  1463.8  5002.9  1464.3  5009.9 1465.56
  5029.9 1467.18  5045.4 1467.85  5049.9 1468.09  5079.9 1467.41  5119.9 1467.24
  5169.9 1468.21  5339.9 1470.31  5629.9 1477.09  5739.9  1479.3  5755.7 1479.93
#Mann= 5 ,-1 , 0
  4548.2     .05       0  4854.9      .1       0  4996.9     .07       0
  5002.9      .1       0  5045.4     .05       0
Bank Sta=4996.9,5002.9
XS Rating Curve= 0 ,0
Exp/Cntr=0.3,0.1

Type RM Length L Ch R = 1 ,5010    ,957,957,957
BEGIN DESCRIPTION:
UNT012 IN NNOGR 6.0
END DESCRIPTION:
XS GIS Cut Line= 2
      2840892.73     10062690.98      2839568.92     10062549.92
#Sta/Elev= 30
  4350.7 1471.85    4371 1471.96  4435.4 1470.88    4475 1470.96  4546.1 1471.18
  4555.9  1471.5  4576.2 1470.42  4616.5 1469.52    4646 1469.31  4757.3 1467.79
  4783.9 1466.99  4860.4 1465.17  4948.3 1462.37  4982.1 1462.03  4988.6 1461.82
  4995.6 1460.93  4998.4 1460.43  5001.6 1460.93  5008.7 1461.17  5018.7 1462.37
  5028.2 1462.56  5099.2 1463.15  5133.3 1462.99  5315.6 1464.83  5471.3 1465.96
    5603 1468.06  5622.1 1469.13  5642.2 1469.55  5672.4 1469.44    5682 1469.72
#Mann= 9 ,-1 , 0
  4350.7     .16       0    4475     .05       0    4646      .1       0
  4783.9     .05       0  4860.4      .1       0  4982.1     .05       0
  4995.6    .035       0  5001.6     .05       0  5133.3      .1       0
Bank Sta=4995.6,5001.6
XS Rating Curve= 0 ,0
Exp/Cntr=0.3,0.1

Type RM Length L Ch R = 1 ,4053    ,524,524,524
BEGIN DESCRIPTION:
UNT012 IN NNOGR 5.0
END DESCRIPTION:
XS GIS Cut Line= 2
      2841380.99     10061844.63      2839807.67     10061660.17
#Sta/Elev= 30
  4192.8 1475.23  4265.8 1473.03  4366.5 1467.29  4418.5 1465.33  4447.1 1463.72
  4467.2 1462.01  4487.3 1461.97  4501.8 1461.41  4527.6 1459.43  4617.2 1455.48
  4698.8 1451.79  4718.9 1451.36  4769.8 1451.48  4819.6 1451.08  4869.9  1451.8
  4927.9 1451.24  4967.5 1450.19  4997.8  1448.4  5000.6  1447.9  5003.8  1448.4
  5010.9 1448.83  5016.1 1449.83    5031 1450.65  5104.4 1453.47  5192.6 1454.65
  5442.3  1455.4  5554.6 1455.27  5584.8 1456.16  5613.7 1456.41  5776.9 1456.35
#Mann= 6 ,-1 , 0
  4192.8     .16       0  4617.2      .1       0  4769.8     .05       0
  4967.5      .1       0  4997.8     .07       0  5003.8      .1       0
Bank Sta=4997.8,5003.8
XS Rating Curve= 0 ,0
Exp/Cntr=0.3,0.1

Type RM Length L Ch R = 1 ,3529    ,262,262,262
BEGIN DESCRIPTION:
Mapping XS c186400c
END DESCRIPTION:
XS GIS Cut Line= 4
      2841345.94     10061580.74      2841068.19      10061370.7
      2840623.74     10061230.07        2840053.     10061243.95
#Sta/Elev= 30
  4345.4 1471.89  4389.3 1470.29  4407.1 1469.32  4509.1 1464.15    4580 1459.55
  4598.3 1458.59  4605.5 1457.44  4648.3 1453.67  4677.4 1452.61  4704.6 1449.92
    4764 1446.06  4796.3 1445.88  4802.9 1445.21  4805.7 1445.13  4808.5 1444.63
  4811.7 1445.13  4871.6 1446.43  4930.8 1446.83    4936 1446.27    4982 1447.17
  4995.4 1447.44    5008 1446.71  5027.7 1447.26  5032.9 1448.25    5149 1448.41
  5195.1 1448.11  5555.2 1450.35  5615.7 1451.68  5685.2 1453.16  5730.7 1453.23
#Mann= 11 ,-1 , 0
  4345.4     .05       0  4389.3     .16       0  4407.1     .05       0
  4509.1     .16       0    4580     .05       0  4802.9      .1       0
  4805.7     .04       0  4811.7      .1       0    4982     .05       0
    5149      .1       0  5615.7     .05       0
Bank Sta=4805.7,4811.7
XS Rating Curve= 0 ,0
Exp/Cntr=0.3,0.1

Type RM Length L Ch R = 1 ,3267    ,385,385,385
BEGIN DESCRIPTION:
Mapping XS e3e06e62
END DESCRIPTION:
XS GIS Cut Line= 3
      2841391.09     10061401.94      2840668.88     10061143.26
      2840099.47     10061202.29
#Sta/Elev= 30
  4592.4 1469.05    4632 1465.73  4743.9 1459.51    4797 1455.18  4878.6 1450.96
  4923.6 1448.22    4929  1447.3  4977.6 1445.95  4985.2 1444.89  4987.5 1442.86
  4990.2 1442.36  4993.5 1442.86  5021.2 1445.69  5030.7 1444.96  5041.3 1444.89
  5046.7 1445.66    5052 1445.01  5072.1 1445.27  5115.7 1443.51  5164.4 1445.48
  5228.2 1446.36    5275 1446.15  5306.9 1446.93  5343.7 1446.11  5390.8 1447.23
  5671.6 1448.91  5819.5 1450.82  5872.7 1452.61  5897.7 1452.17    5932 1452.89
#Mann= 7 ,-1 , 0
  4592.4     .05       0  4878.6      .1       0  4987.5     .07       0
  4993.5      .1       0  5228.2     .05       0  5390.8      .1       0
  5819.5     .05       0
Bank Sta=4987.5,4993.5
XS Rating Curve= 0 ,0
Exp/Cntr=0.3,0.1

Type RM Length L Ch R = 1 ,2882    ,929,929,929
BEGIN DESCRIPTION:
UNT012 IN NNOGR 4.0
END DESCRIPTION:
XS GIS Cut Line= 2
      2841782.49     10060998.28       2840426.2     10060857.22
#Sta/Elev= 30
  4352.6 1456.81  4443.5 1456.89  4457.2 1456.11  4517.5 1455.86  4577.8  1454.3
    4608 1454.21  4694.4 1451.09  4728.6 1449.98  4748.7 1448.58  4778.9  1448.6
  4859.3 1445.27  4919.7 1444.13  4931.5 1443.63  4949.8 1441.95  4969.9 1441.39
  4999.8 1439.36  5030.3 1441.29  5096.9 1441.51  5118.6 1442.04    5161 1441.49
  5281.6 1441.28  5350.2 1441.83  5392.2 1442.53  5409.4 1443.66  5442.5 1444.68
  5502.8 1444.72  5601.6 1446.27  5613.4 1445.93  5643.5 1447.01  5716.2 1448.07
#Mann= 6 ,-1 , 0
  4352.6      .1       0  4694.4     .05       0  4969.9    .035       0
  5030.3     .05       0  5096.9      .1       0  5350.2     .05       0
Bank Sta=4969.9,5030.3
XS Rating Curve= 0 ,0
Exp/Cntr=0.3,0.1

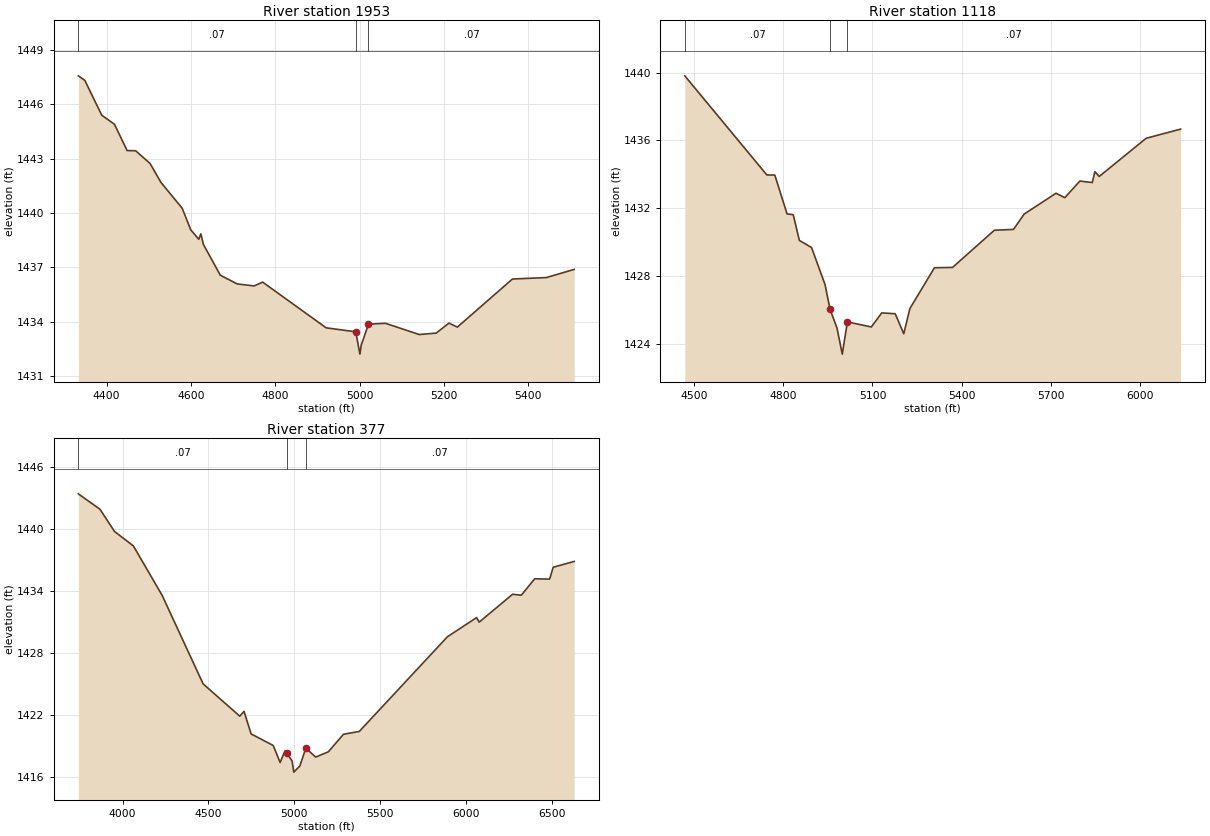
Type RM Length L Ch R = 1 ,1953    ,835,835,835
BEGIN DESCRIPTION:
UNT012 IN NNOGR 3.0
END DESCRIPTION:
XS GIS Cut Line= 2
       2842053.8     10060162.78      2840882.66     10060065.18
#Sta/Elev= 30
  4333.2 1447.56  4348.6 1447.31  4388.7 1445.39  4418.8 1444.89  4448.9 1443.44
    4469 1443.43  4503.2 1442.73  4529.2 1441.68  4579.4 1440.26  4599.5 1439.08
  4618.6 1438.55  4623.6 1438.85  4629.6 1438.27  4669.7 1436.57  4709.8 1436.09
    4750 1435.98    4770 1436.19  4920.6 1433.67  4990.8 1433.45  5000.6 1432.22
  5003.8 1432.72  5020.9 1433.87    5061 1433.92  5141.3  1433.3  5181.5 1433.38
  5211.6 1433.93  5231.6 1433.71  5362.1 1436.36  5442.4 1436.44  5508.4 1436.89
#Mann= 3 ,-1 , 0
  4333.2     .07       0  4990.8     .03       0  5020.9     .07       0
Bank Sta=4990.8,5020.9
XS Rating Curve= 0 ,0
Exp/Cntr=0.3,0.1

Type RM Length L Ch R = 1 ,1118    ,741,741,741
BEGIN DESCRIPTION:
UNT012 IN NNOGR 2.0
END DESCRIPTION:
XS GIS Cut Line= 3
      2842171.58     10059519.02       2841299.2     10059288.56
      2840860.42     10059918.73
#Sta/Elev= 30
  4467.9 1439.81  4744.2 1433.97  4771.1 1433.96  4812.4 1431.67  4833.1 1431.63
  4853.8 1430.11  4894.9 1429.69  4940.3 1427.51  4957.2 1426.05  4980.6 1424.95
  4998.4 1423.41  5015.6 1425.31  5096.2 1425.01  5131.3 1425.84  5176.7 1425.79
  5205.5 1424.61  5226.2  1426.1  5308.9  1428.5  5369.9 1428.52  5510.6 1430.71
  5575.2 1430.76  5610.9 1431.66  5718.3 1432.89    5748 1432.63  5798.6 1433.61
  5840.5 1433.52  5849.2 1434.16  5863.9 1433.88    6022 1436.13  6138.1 1436.67
#Mann= 3 , 0 , 0
  4467.9     .07       0  4957.2     .03       0  5015.6     .07       0
Bank Sta=4957.2,5015.6
XS Rating Curve= 0 ,0
Exp/Cntr=0.3,0.1

Type RM Length L Ch R = 1 ,377     ,0,0,0
BEGIN DESCRIPTION:
UNT012 IN NNOGR 1.0
END DESCRIPTION:
XS GIS Cut Line= 5
      2842900.16     10059012.61      2841565.49     10058654.53
      2841424.44     10058719.63      2841234.85     10059325.25
       2840832.6     10059916.22
#Sta/Elev= 30
  3742.3  1443.4  3868.1 1441.91  3953.3 1439.75  4062.9 1438.35  4230.7 1433.55
  4468.8 1424.99  4682.3 1421.86  4706.9 1422.33  4748.4 1420.14  4877.1 1419.02
  4917.1 1417.37  4945.1 1418.49  4957.1 1418.26  4986.5 1417.53  4996.8 1416.44
  5031.9 1417.03  5066.7 1418.76  5124.2  1417.9    5198 1418.41  5285.9 1420.11
    5378 1420.38  5891.6 1429.56  6061.1 1431.41  6076.1 1430.97  6270.6 1433.67
  6321.4 1433.58  6399.3 1435.17  6486.1 1435.14  6507.1 1436.29    6629 1436.85
#Mann= 3 ,-1 , 0
  3742.3     .07       0  4957.1     .03       0  5066.7     .07       0
Bank Sta=4957.1,5066.7
XS Rating Curve= 0 ,0
Exp/Cntr=0.3,0.1

Chan Stop Cuts=-1
Use User Specified Reach Order=0
Composite Channel Slope=5