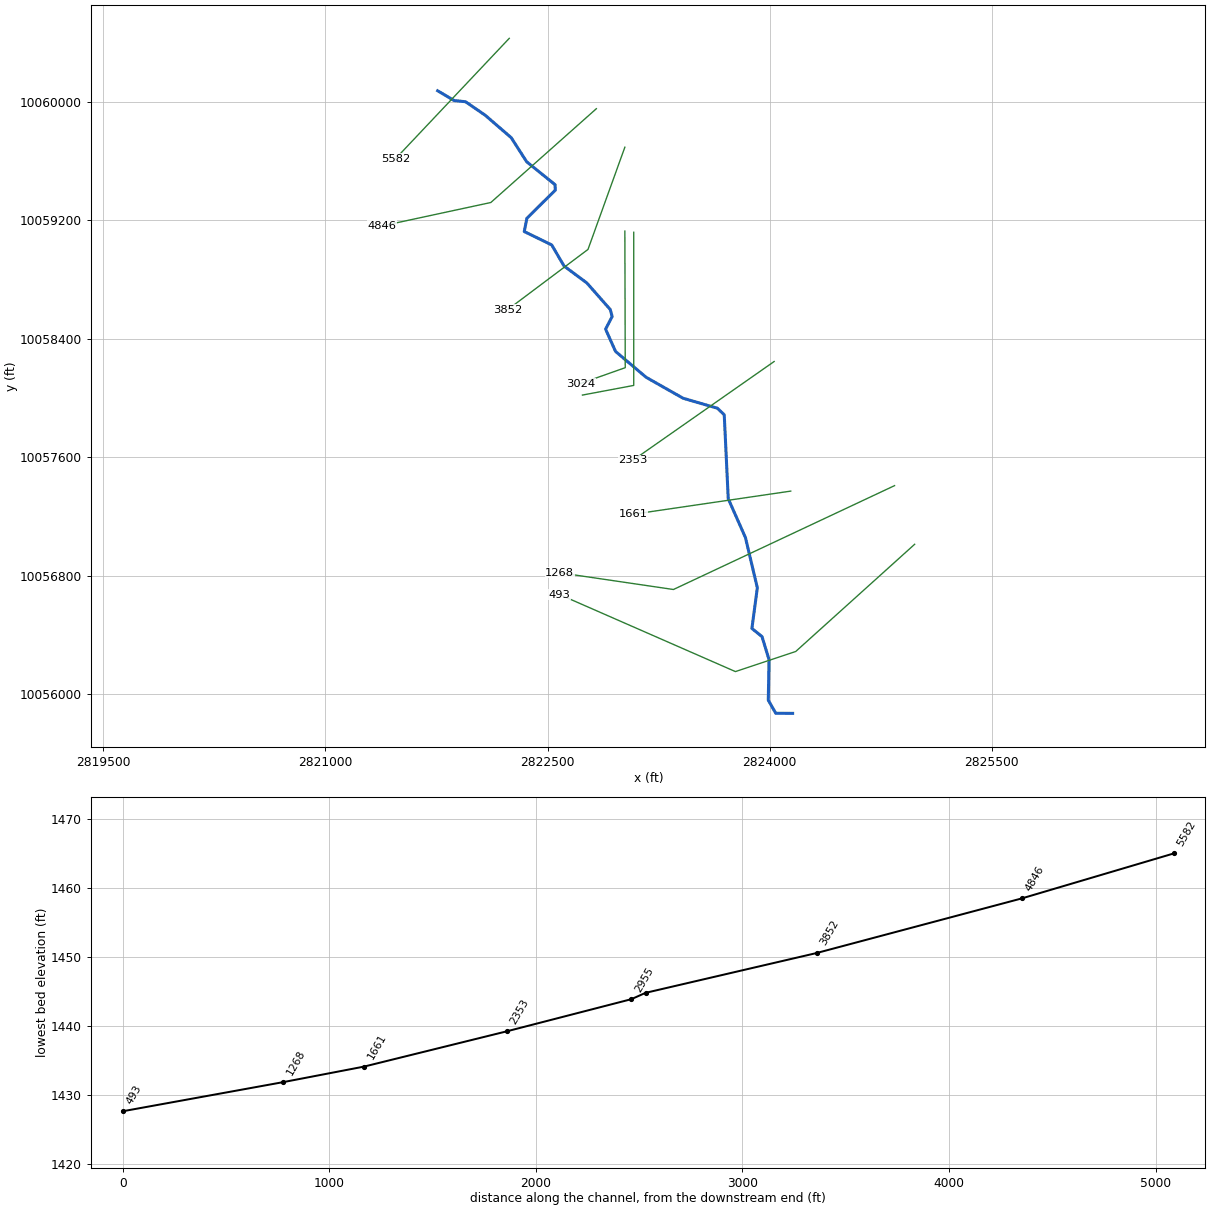
--- UNT013 IN NNOGR.prj (project) ---

Proj Title=UNT013 IN NNOGR Base Level Engineering
Current Plan=p01
Default Exp/Contr=0.3,0.1
English Units
Geom File=g01
Flow File=f01
Plan File=p01
BEGIN DESCRIPTION:
UNT013 IN NNOGR
END DESCRIPTION:

--- UNT013 IN NNOGR.p01 (plan) ---

Plan Title=Multiple Run
Short Identifier=Multiple
Geom File=g01
Flow File=f01
Subcritical Flow
K Sum by GR= 0
Std Step Tol= 0.01
Critical Tol= 0.01
Num of Std Step Trials= 20
Max Error Tol= 0.3
Flow Tol Ratio= 0.001
Split Flow NTrial= 30
Split Flow Tol= 0.02
Split Flow Ratio= 0.02
Log Output Level= 0
Friction Slope Method= 1
Unsteady Friction Slope Method= 2
Unsteady Bridges Friction Slope Method= 1
Parabolic Critical Depth
Global Vel Dist=  1 , 1 , 1
Global Log Level= 0
CheckData=True
Encroach Param= -1, 0, 0, 0
BEGIN DESCRIPTION:
Multiple Run
END DESCRIPTION:

--- UNT013 IN NNOGR.f01 (steady flow) ---

Flow Title=Multiple
Number of Profiles=7
Profile Names=10-year,25-year,50-year,1pct_min,100-year,1pct_plu,500-year
River Rch & RM= UNT013 IN NNOGR,Reach-1,5582
    1424    2105    2707    2543    3439    4651    5575
Boundary for River Rch & Prof#=UNT013 IN NNOGR,Reach-1,1
Up Type=0
Dn Type=3
Dn Slope=0.005
Boundary for River Rch & Prof#=UNT013 IN NNOGR,Reach-1,2
Up Type=0
Dn Type=3
Dn Slope=0.005
Boundary for River Rch & Prof#=UNT013 IN NNOGR,Reach-1,3
Up Type=0
Dn Type=3
Dn Slope=0.005
Boundary for River Rch & Prof#=UNT013 IN NNOGR,Reach-1,4
Up Type=0
Dn Type=3
Dn Slope=0.005
Boundary for River Rch & Prof#=UNT013 IN NNOGR,Reach-1,5
Up Type=0
Dn Type=3
Dn Slope=0.005
Boundary for River Rch & Prof#=UNT013 IN NNOGR,Reach-1,6
Up Type=0
Dn Type=3
Dn Slope=0.005
Boundary for River Rch & Prof#=UNT013 IN NNOGR,Reach-1,7
Up Type=0
Dn Type=3
Dn Slope=0.005

--- UNT013 IN NNOGR.g01 (geometry) ---

Geom Title=Existing Conditions

River Reach=UNT013 IN NNOGR,Reach-1
Reach XY= 30
      2821758.47     10060073.73      2821869.85     10060007.90
      2821946.68     10059999.91      2822079.99     10059908.26
      2822254.91     10059757.14      2822359.27     10059594.56
      2822550.99     10059439.95      2822552.80     10059403.07
      2822360.71     10059212.82      2822342.90     10059123.48
      2822528.30     10059033.20      2822611.92     10058890.30
      2822765.67     10058776.37      2822923.97     10058596.55
      2822936.35     10058549.77      2822892.13     10058464.48
      2822959.21     10058314.10      2823165.94     10058139.36
      2823415.47     10057998.02      2823647.26     10057930.49
      2823693.18     10057886.46      2823720.25     10057319.47
      2823836.21     10057057.80      2823916.69     10056717.91
      2823879.91     10056443.78      2823948.20     10056388.77
      2823995.75     10056232.53      2823990.54     10055959.67
      2824040.94     10055871.09      2824154.92     10055870.39

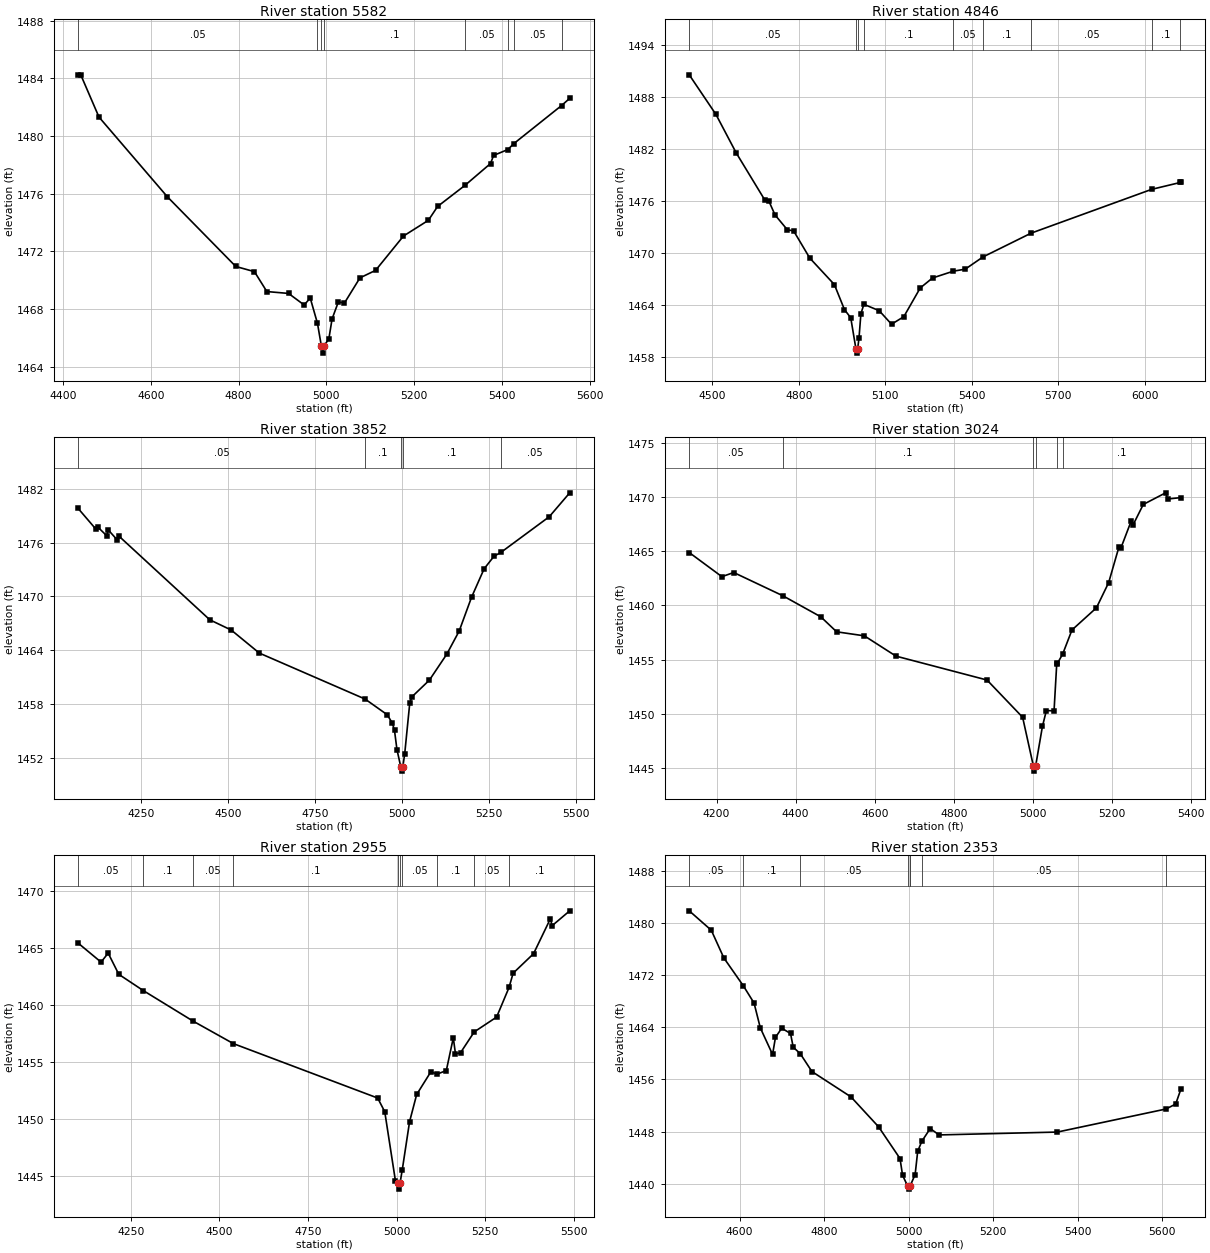
Type RM Length L Ch R = 1,5582,736,736,736
BEGIN DESCRIPTION:
UNT013 IN NNOGR 12.0
END DESCRIPTION:
XS GIS Cut Line= 2
      2822241.73     10060427.92      2821473.05     10059614.03
#Sta/Elev= 30
  4434.7 1484.25  4440.7 1484.25  4482.2 1481.32  4638.0 1475.79  4793.7 1470.96
  4836.2 1470.60  4864.5 1469.22  4913.9 1469.09  4949.4 1468.29  4963.3 1468.77
  4979.8 1467.01  4988.6 1465.45  4991.3 1464.95  4994.6 1465.45  5005.7 1465.94
  5013.0 1467.32  5027.2 1468.49  5041.3 1468.43  5076.5 1470.17  5112.1 1470.69
  5175.6 1473.07  5232.3 1474.16  5253.3 1475.12  5315.9 1476.59  5373.9 1478.10
  5380.8 1478.66  5413.4 1479.07  5426.5 1479.47  5535.6 1482.12  5554.2 1482.62
#Mann=8,-1,0
  4434.7    0.05       0  4979.8     0.1       0  4988.6    0.07       0
  4994.6     0.1       0  5315.9    0.05       0  5413.4     0.1       0
  5426.5    0.05       0  5535.6     0.1       0
Bank Sta=4988.6,4994.6
Exp/Cntr=0.3,0.1

Type RM Length L Ch R = 1,4846,994,994,994
BEGIN DESCRIPTION:
UNT013 IN NNOGR 10.0
END DESCRIPTION:
XS GIS Cut Line= 3
      2822829.86     10059952.87      2822117.31     10059319.49
      2821382.82     10059161.29
#Sta/Elev= 30
  4420.3 1490.58  4513.0 1486.00  4583.2 1481.56  4682.7 1476.10  4697.0 1475.95
  4717.9 1474.39  4760.5 1472.68  4782.3 1472.55  4838.3 1469.41  4923.6 1466.35
  4958.7 1463.45  4980.4 1462.51  4998.3 1458.93  5001.1 1458.43  5004.3 1458.93
  5008.9 1460.14  5015.6 1462.98  5025.9 1464.07  5079.1 1463.33  5121.8 1461.77
  5164.4 1462.64  5221.3 1465.96  5263.9 1467.11  5336.4 1467.90  5377.4 1468.13
  5438.8 1469.54  5605.8 1472.29  6023.8 1477.35  6123.8 1478.15  6125.0 1478.21
#Mann=9,-1,0
  4420.3    0.05       0  4998.3   0.035       0  5004.3    0.05       0
  5025.9     0.1       0  5336.4    0.05       0  5438.8     0.1       0
  5605.8    0.05       0  6023.8     0.1       0  6123.8    0.05       0
Bank Sta=4998.3,5004.3
Exp/Cntr=0.3,0.1

Type RM Length L Ch R = 1,3852,828,828,828
BEGIN DESCRIPTION:
UNT013 IN NNOGR 9.0
END DESCRIPTION:
XS GIS Cut Line= 3
      2823022.15     10059692.70      2822773.33     10059002.79
      2822231.97     10058596.77
#Sta/Elev= 30
  4070.7 1479.82  4121.6 1477.51  4126.9 1477.75  4152.3 1476.79  4157.6 1477.40
  4183.0 1476.30  4188.3 1476.71  4448.5 1467.39  4509.9 1466.25  4590.5 1463.68
  4893.9 1458.55  4957.4 1456.80  4972.0 1455.86  4978.2 1455.05  4985.2 1452.92
  4996.1 1451.01  4998.8 1450.51  5002.1 1451.01  5007.4 1452.41  5022.0 1458.12
  5028.2 1458.80  5078.2 1460.66  5128.2 1463.56  5163.7 1466.14  5199.1 1469.90
  5235.2 1473.08  5263.7 1474.49  5283.3 1474.91  5422.0 1478.89  5480.8 1481.56
#Mann=5,-1,0
  4070.7    0.05       0  4893.9     0.1       0  4996.1    0.07       0
  5002.1     0.1       0  5283.3    0.05       0
Bank Sta=4996.1,5002.1
Exp/Cntr=0.3,0.1

Type RM Length L Ch R = 1,3024,69,69,69
BEGIN DESCRIPTION:
UNT013 IN NNOGR 6.0
END DESCRIPTION:
XS GIS Cut Line= 3
      2823022.24     10059126.19      2823024.84     10058204.32
      2822722.74     10058097.54
#Sta/Elev= 30
  4131.0 1464.87  4213.5 1462.65  4243.5 1463.03  4367.6 1460.89  4463.5 1458.95
  4503.5 1457.57  4573.5 1457.20  4653.5 1455.33  4883.5 1453.13  4973.5 1449.70
  5000.5 1445.24  5003.2 1444.74  5006.5 1445.24  5023.5 1448.85  5033.5 1450.32
  5052.9 1450.29  5059.6 1454.57  5061.6 1454.68  5074.6 1455.51  5098.2 1457.74
  5160.0 1459.78  5190.9 1462.10  5216.6 1465.35  5221.9 1465.29  5247.5 1467.74
  5252.8 1467.43  5278.4 1469.30  5334.9 1470.37  5340.2 1469.80  5373.3 1469.93
#Mann=6,-1,0
  4131.0    0.05       0  4367.6     0.1       0  5000.5    0.07       0
  5006.5     0.1       0  5061.6    0.05       0  5074.6     0.1       0
Bank Sta=5000.5,5006.5
Exp/Cntr=0.3,0.1

Type RM Length L Ch R = 1,2955,602,602,602
BEGIN DESCRIPTION:
Mapping XS 9b500448
END DESCRIPTION:
XS GIS Cut Line= 3
      2823082.14     10059118.41      2823082.14     10058084.52
      2822735.78     10058019.42
#Sta/Elev= 30
  4101.7 1465.40  4166.4 1463.73  4186.4 1464.52  4216.4 1462.66  4285.2 1461.24
  4425.7 1458.56  4539.7 1456.58  4946.4 1451.81  4966.4 1450.61  4996.4 1444.57
  5003.4 1444.32  5006.1 1443.82  5009.4 1444.32  5015.9 1445.54  5036.4 1449.74
  5056.4 1452.12  5096.4 1454.11  5114.2 1453.91  5140.0 1454.22  5159.7 1457.09
  5165.8 1455.69  5180.0 1455.78  5218.7 1457.61  5281.8 1458.91  5316.9 1461.51
  5328.4 1462.76  5386.0 1464.47  5433.4 1467.53  5438.5 1466.93  5488.0 1468.23
#Mann=10,-1,0
  4101.7    0.05       0  4285.2     0.1       0  4425.7    0.05       0
  4539.7     0.1       0  5003.4    0.07       0  5009.4     0.1       0
  5015.9    0.05       0  5114.2     0.1       0  5218.7    0.05       0
  5316.9     0.1       0
Bank Sta=5003.4,5009.4
Exp/Cntr=0.3,0.1

Type RM Length L Ch R = 1,2353,692,692,692
BEGIN DESCRIPTION:
UNT013 IN NNOGR 5.0
END DESCRIPTION:
XS GIS Cut Line= 2
      2824030.08     10058246.00      2823076.90     10057579.30
#Sta/Elev= 30
  4480.9 1481.89  4533.1 1478.91  4562.8 1474.66  4608.9 1470.38  4634.3 1467.73
  4649.1 1463.92  4678.1 1459.84  4684.9 1462.46  4699.7 1463.87  4720.6 1463.06
  4726.9 1460.96  4743.6 1459.96  4771.2 1457.22  4863.6 1453.33  4929.0 1448.73
  4979.6 1443.87  4985.7 1441.29  4997.5 1439.67  5000.3 1439.17  5003.5 1439.67
  5004.0 1439.72  5015.4 1441.41  5021.5 1444.99  5031.3 1446.52  5051.1 1448.47
  5072.0 1447.49  5351.9 1447.93  5609.0 1451.47  5631.9 1452.23  5644.1 1454.49
#Mann=8,-1,0
  4480.9    0.05       0  4608.9     0.1       0  4743.6    0.05       0
  4997.5   0.035       0  5003.5    0.05       0  5004.0     0.1       0
  5031.3    0.05       0  5609.0     0.1       0
Bank Sta=4997.5,5003.5
Exp/Cntr=0.3,0.1

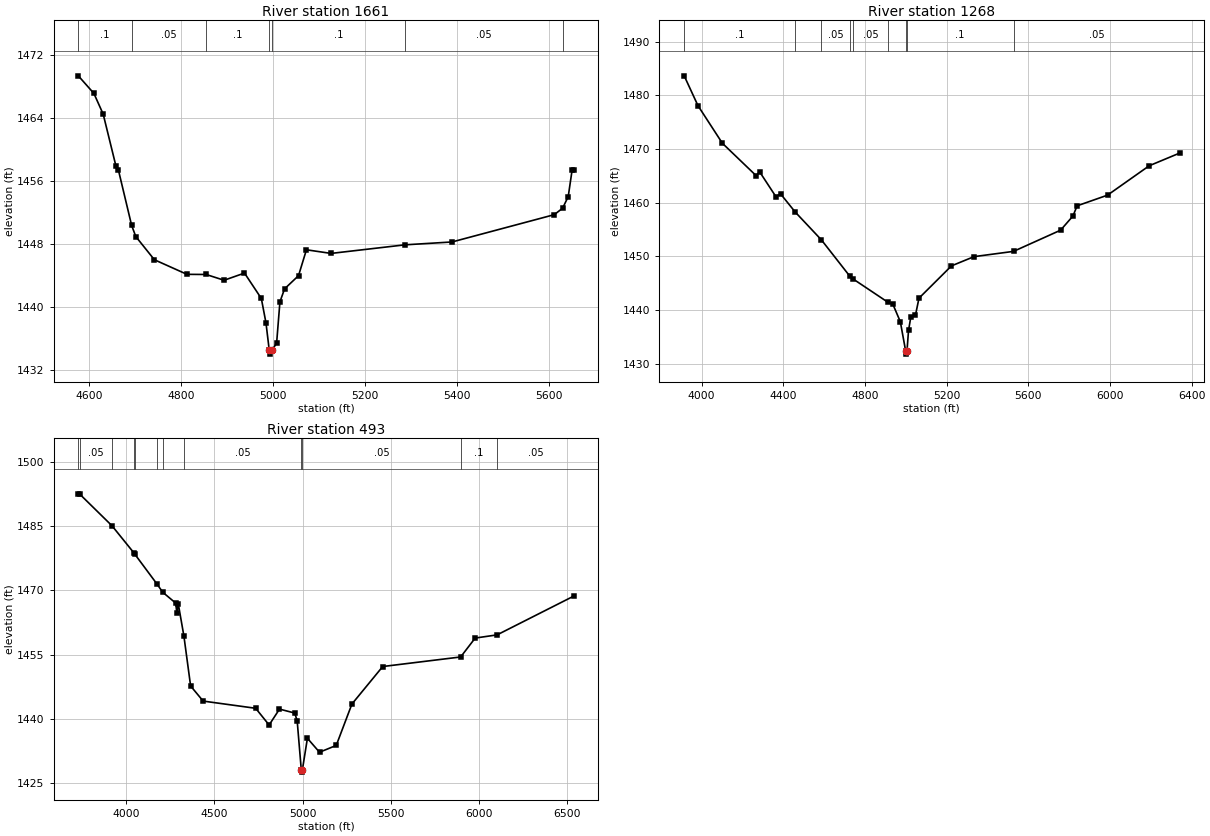
Type RM Length L Ch R = 1,1661,393,393,393
BEGIN DESCRIPTION:
UNT013 IN NNOGR 4.0
END DESCRIPTION:
XS GIS Cut Line= 2
      2824142.03     10057370.98      2823076.93     10057214.73
#Sta/Elev= 30
  4576.4 1469.31  4610.3 1467.08  4630.5 1464.45  4658.3 1457.85  4663.3 1457.44
  4692.3 1450.36  4701.3 1448.95  4741.7 1446.01  4812.5 1444.16  4854.2 1444.14
  4893.3 1443.41  4937.6 1444.32  4974.2 1441.10  4984.3 1438.00  4991.4 1434.55
  4994.1 1434.05  4997.4 1434.55  5007.4 1435.44  5014.6 1440.67  5024.7 1442.32
  5055.0 1443.99  5072.2 1447.27  5125.8 1446.81  5286.8 1447.90  5388.6 1448.26
  5610.9 1451.72  5629.0 1452.54  5641.2 1454.01  5649.6 1457.36  5652.9 1457.36
#Mann=7,-1,0
  4576.4     0.1       0  4692.3    0.05       0  4854.2     0.1       0
  4991.4    0.07       0  4997.4     0.1       0  5286.8    0.05       0
  5629.0     0.1       0
Bank Sta=4991.4,4997.4
Exp/Cntr=0.3,0.1

Type RM Length L Ch R = 1,1268,775,775,775
BEGIN DESCRIPTION:
UNT013 IN NNOGR 2.0
END DESCRIPTION:
XS GIS Cut Line= 3
      2824843.15     10057408.00      2823350.17     10056706.75
      2822582.30     10056819.67
#Sta/Elev= 30
  3915.0 1483.66  3982.4 1478.10  4102.0 1471.09  4267.1 1465.06  4284.4 1465.77
  4363.9 1461.15  4386.7 1461.67  4458.7 1458.27  4587.2 1453.07  4725.5 1446.34
  4742.0 1445.80  4913.0 1441.45  4936.6 1441.12  4973.5 1437.82  4999.9 1432.29
  5002.6 1431.79  5005.9 1432.29  5013.6 1436.20  5025.0 1438.75  5047.5 1439.04
  5064.8 1442.22  5223.9 1448.24  5334.3 1449.96  5527.7 1450.94  5758.2 1454.89
  5818.9 1457.54  5839.1 1459.43  5988.1 1461.42  6192.3 1466.90  6340.6 1469.25
#Mann=9,-1,0
  3915.0     0.1       0  4458.7    0.16       0  4587.2    0.05       0
  4725.5     0.1       0  4742.0    0.05       0  4913.0     0.1       0
  4999.9    0.07       0  5005.9     0.1       0  5527.7    0.05       0
Bank Sta=4999.9,5005.9
Exp/Cntr=0.3,0.1

Type RM Length L Ch R = 1,493,0,0,0
BEGIN DESCRIPTION:
UNT013 IN NNOGR 1.0
END DESCRIPTION:
XS GIS Cut Line= 4
      2824978.89     10057012.13      2824175.84     10056288.25
      2823768.66     10056152.53      2822582.28     10056672.28
#Sta/Elev= 30
  3729.9 1492.49  3737.8 1492.43  3920.9 1485.03  4046.3 1478.64  4048.8 1478.48
  4176.6 1471.39  4208.3 1469.53  4281.7 1467.00  4288.4 1464.58  4295.9 1466.89
  4328.0 1459.33  4366.1 1447.67  4437.1 1444.15  4734.6 1442.47  4810.7 1438.57
  4869.5 1442.28  4955.9 1441.36  4969.7 1439.53  4993.0 1428.08  4995.8 1427.58
  4999.0 1428.08  5027.6 1435.47  5096.2 1432.22  5191.0 1433.81  5279.7 1443.46
  5454.2 1452.21  5895.7 1454.44  5977.9 1458.85  6101.9 1459.59  6535.5 1468.62
#Mann=12,-1,0
  3729.9     0.1       0  3737.8    0.05       0  3920.9    0.16       0
  4046.3     0.1       0  4048.8    0.16       0  4176.6    0.05       0
  4208.3     0.1       0  4328.0    0.05       0  4993.0   0.035       0
  4999.0    0.05       0  5895.7     0.1       0  6101.9    0.05       0
Bank Sta=4993,4999
Exp/Cntr=0.3,0.1

Chan Stop Cuts=-1