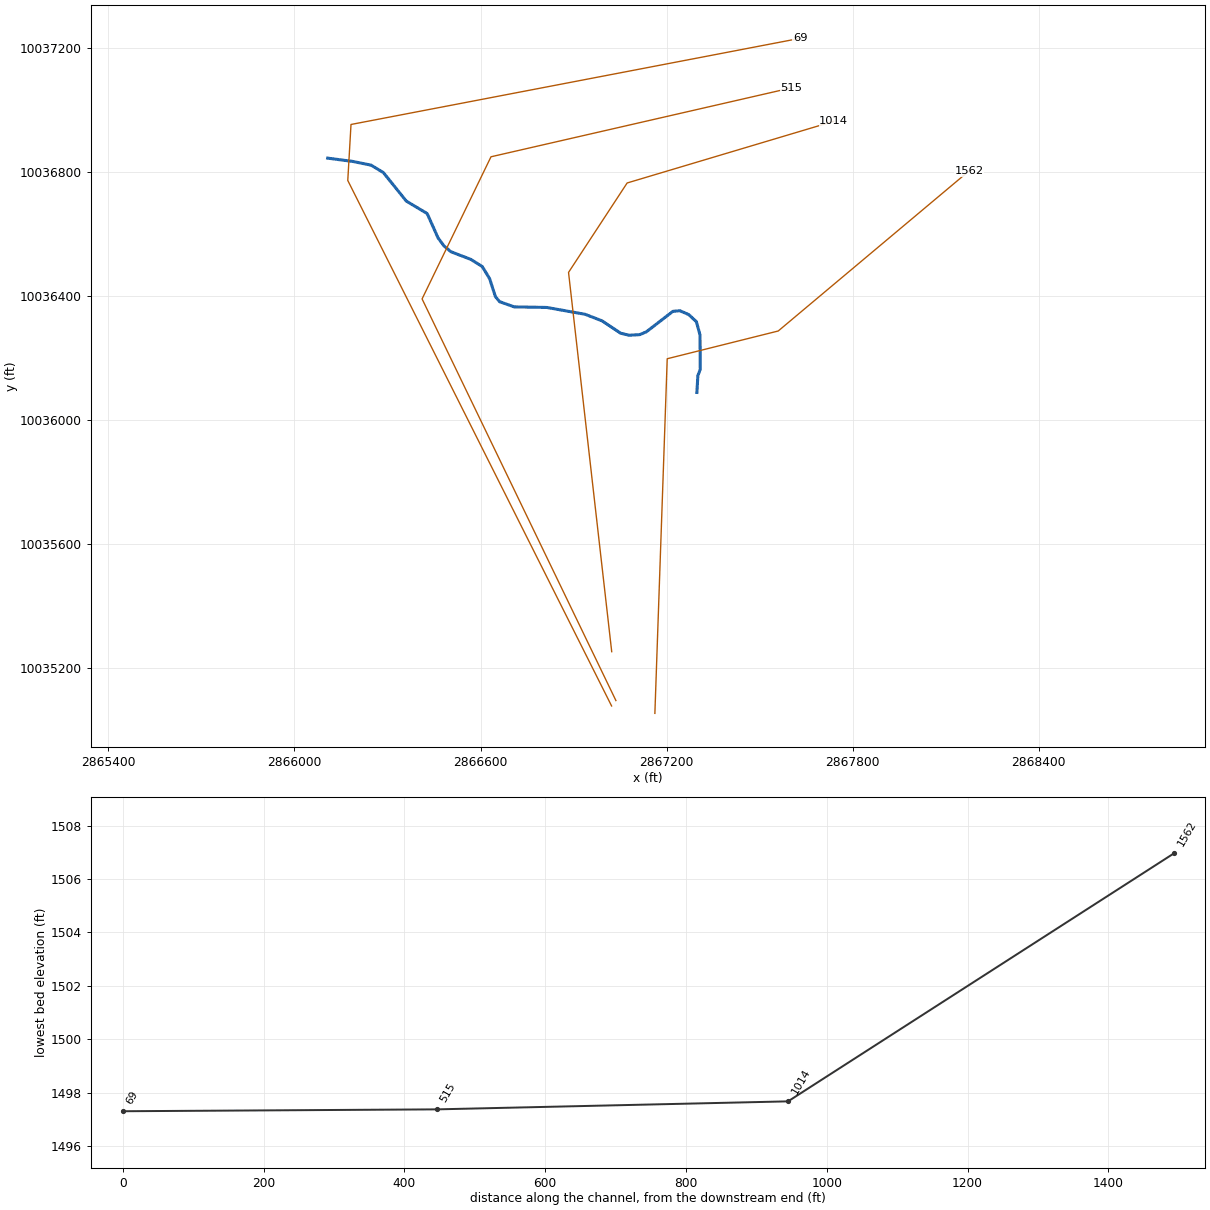
--- UNT013 IN SNOGR.prj (project) ---

Proj Title=UNT013 IN SNOGR Base Level Engineering
Current Plan=p01
Default Exp/Contr=0.3,0.1
English Units
Geom File=g01
Flow File=f01
Plan File=p01
Y Axis Title=Elevation
X Axis Title(PF)=Main Channel Distance
X Axis Title(XS)=Station
BEGIN DESCRIPTION:
UNT013 IN SNOGR
END DESCRIPTION:
DSS Export Rating Curves= 0
DSS Export Rating Curve Sorted= 0
DSS Export Volume Flow Curves= 0
DXF OffsetX= 0
DXF OffsetY= 0
DXF ScaleX= 1
DXF ScaleY= 10

--- UNT013 IN SNOGR.p01 (plan) ---

Plan Title=Multiple Run
Short Identifier=Multiple
Geom File=g01
Flow File=f01
Subcritical Flow
K Sum by GR= 0
Std Step Tol= 0.01
Critical Tol= 0.01
Num of Std Step Trials= 20
Max Error Tol= 0.3
Flow Tol Ratio= 0.001
Split Flow NTrial= 30
Split Flow Tol= 0.02
Split Flow Ratio= 0.02
Log Output Level= 0
Friction Slope Method= 1
Unsteady Friction Slope Method= 2
Unsteady Bridges Friction Slope Method= 1
Parabolic Critical Depth
Global Vel Dist=  1 , 1 , 1
Global Log Level= 0
CheckData=True
Encroach Param= -1, 0, 0, 0
BEGIN DESCRIPTION:
Multiple Run
END DESCRIPTION:

--- UNT013 IN SNOGR.f01 (steady flow) ---

Flow Title=Multiple
Program Version=4.10
Number of Profiles= 7
Profile Names=10-year,25-year,50-year,1pct_min,100-year,1pct_plu,500-year
River Rch & RM=UNT013 IN SNOGR,Reach-1         ,1562
     929    1347    1711    1592    2153    2911    3419
Boundary for River Rch & Prof#=UNT013 IN SNOGR,Reach-1         , 1
Up Type= 0
Dn Type= 3
Dn Slope=0.05
Boundary for River Rch & Prof#=UNT013 IN SNOGR,Reach-1         , 2
Up Type= 0
Dn Type= 3
Dn Slope=0.05
Boundary for River Rch & Prof#=UNT013 IN SNOGR,Reach-1         , 3
Up Type= 0
Dn Type= 3
Dn Slope=0.05
Boundary for River Rch & Prof#=UNT013 IN SNOGR,Reach-1         , 4
Up Type= 0
Dn Type= 3
Dn Slope=0.05
Boundary for River Rch & Prof#=UNT013 IN SNOGR,Reach-1         , 5
Up Type= 0
Dn Type= 3
Dn Slope=0.05
Boundary for River Rch & Prof#=UNT013 IN SNOGR,Reach-1         , 6
Up Type= 0
Dn Type= 3
Dn Slope=0.05
Boundary for River Rch & Prof#=UNT013 IN SNOGR,Reach-1         , 7
Up Type= 0
Dn Type= 3
Dn Slope=0.05
DSS Import GetInterval= 0
DSS Import GetPeak= 0
DSS Import FillOption= 0

--- UNT013 IN SNOGR.g01 (geometry) ---

Geom Title=Existing Conditions
Program Version=4.10

River Reach=UNT013 IN SNOGR ,Reach-1
Reach XY= 30
      2867297.56     10036088.85      2867300.67     10036142.82
      2867308.47     10036163.73      2867307.66     10036273.98
      2867296.06     10036316.75      2867271.58     10036339.83
      2867242.89     10036352.34       2867220.2      10036350.4
      2867134.73     10036284.47      2867112.63     10036275.15
      2867078.64     10036273.39      2867051.73     10036279.83
      2866991.57     10036319.83      2866937.27     10036340.84
      2866813.69     10036362.94      2866708.48     10036364.82
      2866661.46     10036381.53      2866647.72     10036398.03
      2866629.31     10036455.63      2866605.39     10036494.92
      2866568.65     10036517.91      2866504.28     10036542.65
      2866482.17     10036561.13      2866463.11     10036586.94
      2866427.79     10036665.77      2866360.66     10036705.84
      2866286.62     10036797.83      2866247.26     10036821.66
      2866187.21     10036833.95      2866106.77     10036844.42

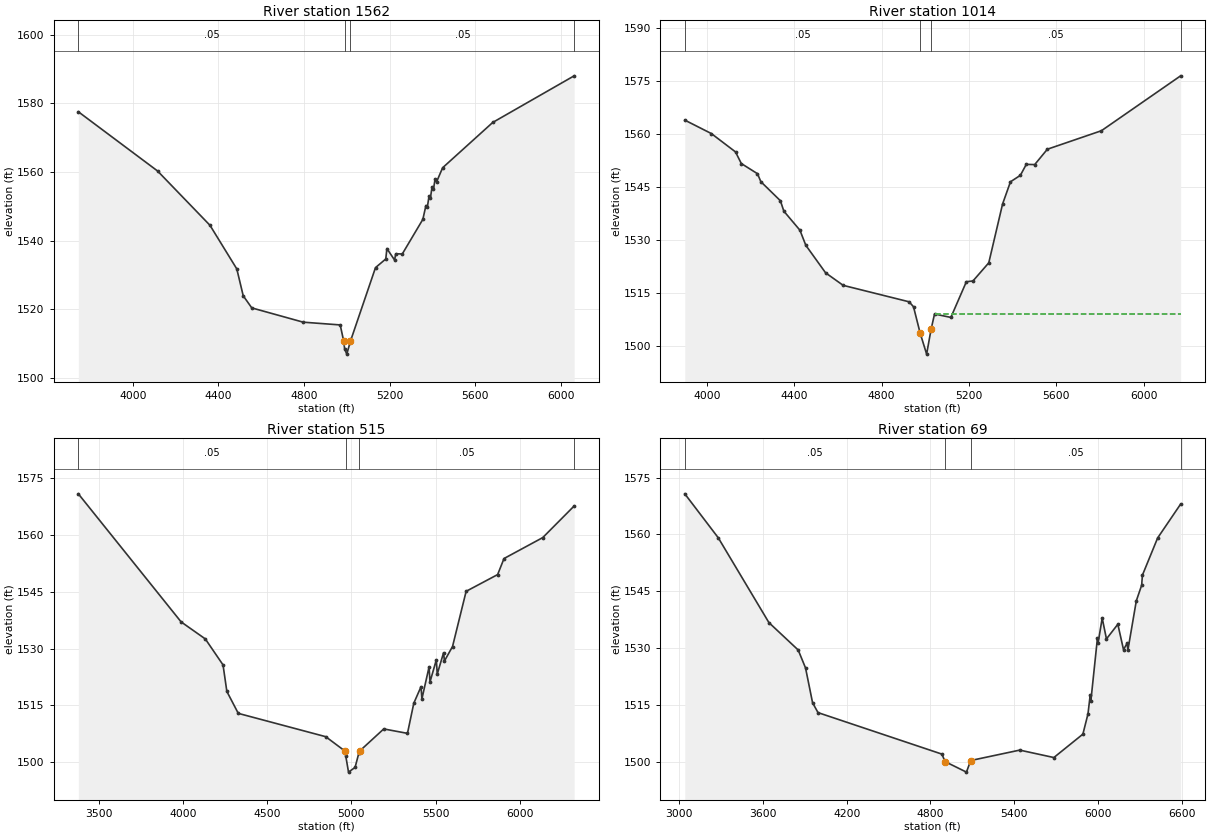
Type RM Length L Ch R = 1 ,1562    ,548,548,548
BEGIN DESCRIPTION:
UNT013 IN SNOGR 2.0
END DESCRIPTION:
XS GIS Cut Line= 4
      2867162.09     10035054.01      2867201.87     10036197.55
      2867559.83     10036287.04      2868174.93     10036802.92
#Sta/Elev= 30
  3745.6 1577.59  4115.5 1560.34  4360.5  1544.5  4485.8 1531.79  4515.8 1523.96
  4555.8 1520.43    4796 1516.27  4968.8 1515.47 4984.66 1510.89  4989.4 1508.51
  4999.5 1506.96  5016.8 1510.76  5133.7 1532.17  5181.7 1534.69  5186.9 1537.72
  5222.9 1534.37  5228.1  1536.2  5258.8 1536.15  5354.9 1546.24  5369.2 1550.26
  5375.7 1549.73  5383.5 1552.92    5390 1552.33  5397.8 1555.73  5404.3 1554.94
  5412.1 1558.03  5418.6 1557.11  5447.2 1561.27  5681.4 1574.48  6061.6 1588.06
#Mann= 4 ,-1 , 0
  3745.6     .05       0  4989.4    .035       0  5016.8     .05       0
  6061.6      .1       0
Bank Sta=4984.66,5016.8
XS Rating Curve= 0 ,0
Exp/Cntr=0.3,0.1

Type RM Length L Ch R = 1 ,1014    ,499,499,499
BEGIN DESCRIPTION:
Mapping XS c739b6bc
END DESCRIPTION:
XS GIS Cut Line= 4
      2867022.89     10035252.95      2866883.68     10036475.96
      2867072.61     10036764.32      2867738.81     10036963.18
#Sta/Elev= 30
  3898.5 1563.82  4020.1 1560.02  4130.8 1554.83  4157.3 1551.55  4231.4 1548.67
  4246.8 1546.42  4336.3 1541.03  4352.2 1538.08  4425.8  1532.7  4452.8 1528.43
  4543.4 1520.65  4623.9 1517.11  4925.9 1512.46    4946 1511.06  4976.2 1503.66
  5006.1 1497.67  5026.5 1504.69  5042.3 1509.01  5117.1 1508.05  5188.1 1518.14
  5218.3 1518.35  5290.7 1523.48  5353.9  1540.1  5390.1 1546.39  5435.4 1548.21
  5462.5 1551.31  5501.1 1551.25    5559 1555.59  5806.6 1560.82  6169.4 1576.34
#Mann= 4 ,-1 , 0
  3898.5     .05       0  4976.2    .035       0  5026.5     .05       0
  6169.4     .16       0
#XS Ineff= 2 , 0
                         5042.72         1509.03
Permanent Ineff=
       T       T
Bank Sta=4976.2,5026.5
XS Rating Curve= 0 ,0
Exp/Cntr=0.3,0.1

Type RM Length L Ch R = 1 ,515     ,446,446,446
BEGIN DESCRIPTION:
Mapping XS 66880a39
END DESCRIPTION:
XS GIS Cut Line= 4
       2867036.4     10035095.34       2866411.4     10036390.48
      2866633.62     10036848.81      2867602.34     10037071.03
#Sta/Elev= 30
  3380.2 1570.88  3989.9 1537.05  4133.5 1532.55  4238.6 1525.69  4261.2 1518.69
    4329 1512.89  4847.8 1506.73 4964.77 1502.84  4966.3 1501.72    4983 1497.37
  5021.9 1498.62  5044.1 1502.38    5051 1503.02    5192 1508.78  5332.7 1507.61
  5370.2 1515.57  5413.1 1519.94  5418.3 1516.71  5461.1 1525.21  5466.3 1521.18
    5504 1527.05  5509.2 1523.24  5546.9 1528.92    5552 1526.73    5600 1530.55
  5680.7 1545.13  5867.6 1549.55  5905.4 1553.79  6135.2 1559.32  6321.5 1567.67
#Mann= 4 ,-1 , 0
  3380.2     .05       0  4966.3    .035       0  5044.1     .05       0
  6321.5      .1       0
Bank Sta=4964.77,5051
XS Rating Curve= 0 ,0
Exp/Cntr=0.3,0.1

Type RM Length L Ch R = 1 ,69      ,0,0,0
BEGIN DESCRIPTION:
UNT013 IN SNOGR 1.0
END DESCRIPTION:
XS GIS Cut Line= 4
      2867022.53     10035077.94      2866171.81     10036772.42
      2866182.23     10036952.98      2867630.13     10037230.75
#Sta/Elev= 30
  3040.8 1570.72  3280.3 1559.13  3643.2 1536.75  3852.9 1529.52  3905.6 1524.78
  3955.9 1515.61  3994.9    1513  4882.4 1502.05  4904.7 1500.08  5058.1  1497.3
  5088.4 1500.36  5439.7 1503.11  5684.1 1501.15    5892 1507.32  5928.5 1512.66
    5944 1517.54  5949.1 1516.08    5996 1532.57  6001.1 1531.42  6030.3 1537.93
  6060.8 1532.44  6142.3 1536.31    6183  1529.6  6209.1 1531.33  6214.2 1529.46
  6274.7  1542.5  6313.1 1546.63  6318.2 1549.25  6427.4 1559.08    6592 1568.01
#Mann= 4 ,-1 , 0
  3040.8     .05       0  4904.7    .035       0  5088.4     .05       0
    6592      .1       0
Bank Sta=4904.7,5088.4
XS Rating Curve= 0 ,0
Exp/Cntr=0.3,0.1

Chan Stop Cuts=-1
Use User Specified Reach Order=0
Composite Channel Slope=5