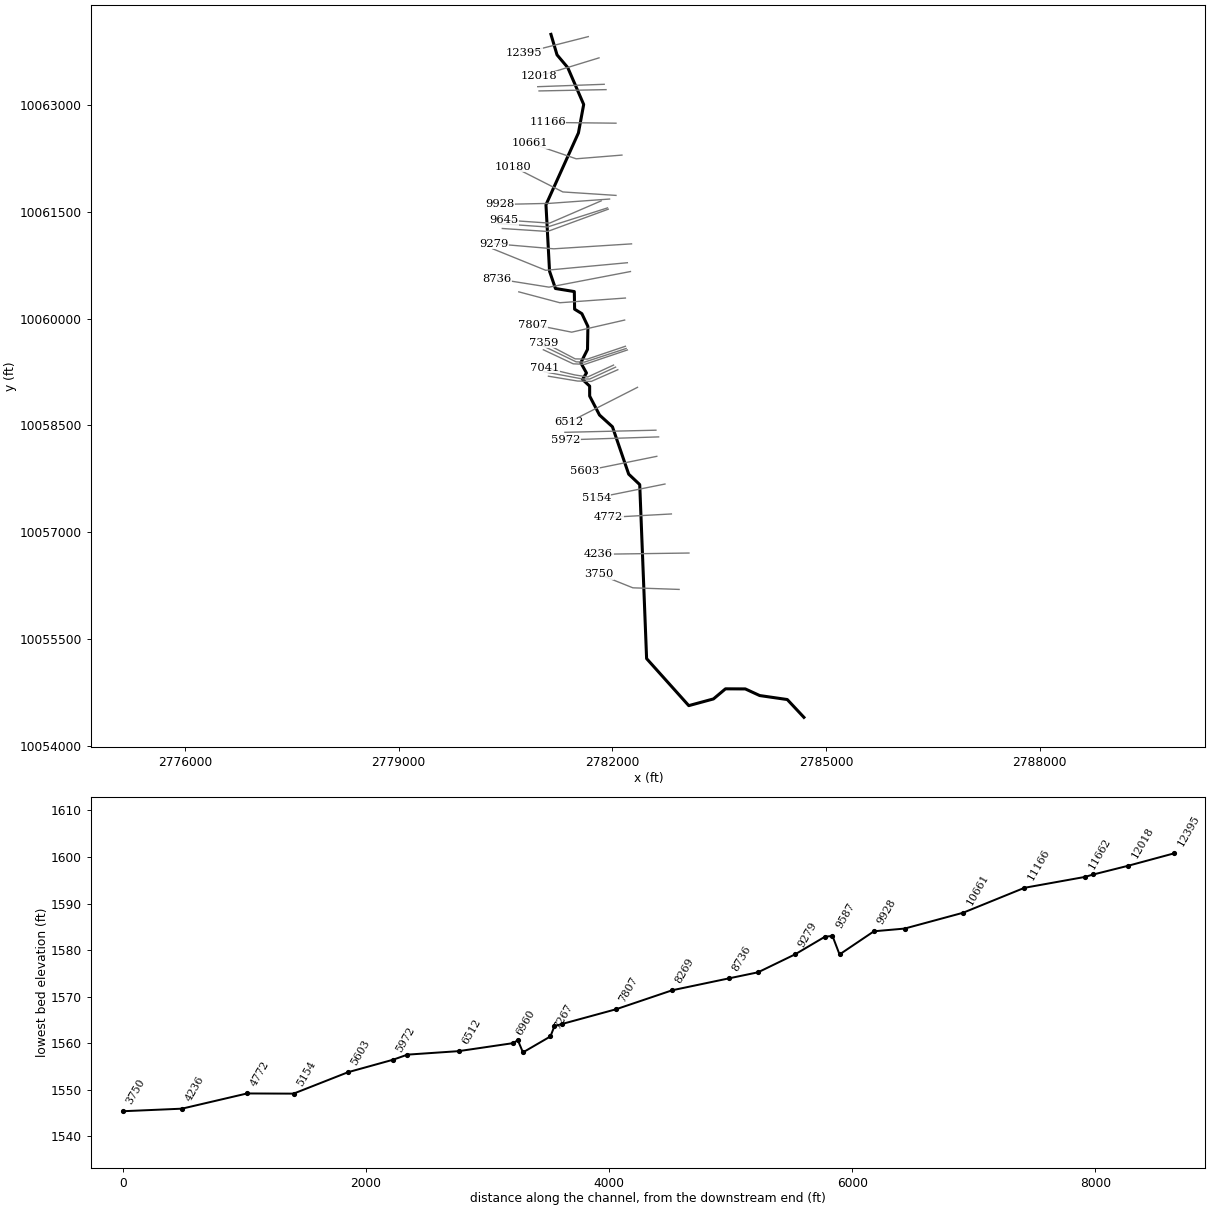
--- UNT014 IN NNOGR.prj (project) ---

Proj Title=UNT014 IN NNOGR Base Level Engineering
Current Plan=p01
Default Exp/Contr=0.3,0.1
English Units
Geom File=g01
Flow File=f01
Plan File=p01
Y Axis Title=Elevation
X Axis Title(PF)=Main Channel Distance
X Axis Title(XS)=Station
BEGIN DESCRIPTION:
UNT014 IN NNOGR
END DESCRIPTION:
DSS Export Rating Curves= 0
DSS Export Rating Curve Sorted= 0
DSS Export Volume Flow Curves= 0
DXF OffsetX= 0
DXF OffsetY= 0
DXF ScaleX= 1
DXF ScaleY= 10

--- UNT014 IN NNOGR.p01 (plan) ---

Plan Title=Multiple Run
Short Identifier=Multiple
Geom File=g01
Flow File=f01
Subcritical Flow
K Sum by GR= 0
Std Step Tol= 0.01
Critical Tol= 0.01
Num of Std Step Trials= 20
Max Error Tol= 0.3
Flow Tol Ratio= 0.001
Split Flow NTrial= 30
Split Flow Tol= 0.02
Split Flow Ratio= 0.02
Log Output Level= 0
Friction Slope Method= 1
Unsteady Friction Slope Method= 2
Unsteady Bridges Friction Slope Method= 1
Parabolic Critical Depth
Global Vel Dist=  1 , 1 , 1
Global Log Level= 0
CheckData=True
Encroach Param= -1, 0, 0, 0
BEGIN DESCRIPTION:
Multiple Run
END DESCRIPTION:

--- UNT014 IN NNOGR.f01 (steady flow) ---

Flow Title=Multiple
Number of Profiles=7
Profile Names=10-year,25-year,50-year,1pct_min,100-year,1pct_plu,500-year
River Rch & RM= UNT014 IN NNOGR,Reach-1,12395
     537     744     915     824    1114    1506    1656
River Rch & RM= UNT014 IN NNOGR,Reach-1,8269
     751    1059    1318    1199    1621    2192    2462
Boundary for River Rch & Prof#=UNT014 IN NNOGR,Reach-1,1
Up Type=0
Dn Type=3
Dn Slope=0.005
Boundary for River Rch & Prof#=UNT014 IN NNOGR,Reach-1,2
Up Type=0
Dn Type=3
Dn Slope=0.005
Boundary for River Rch & Prof#=UNT014 IN NNOGR,Reach-1,3
Up Type=0
Dn Type=3
Dn Slope=0.005
Boundary for River Rch & Prof#=UNT014 IN NNOGR,Reach-1,4
Up Type=0
Dn Type=3
Dn Slope=0.005
Boundary for River Rch & Prof#=UNT014 IN NNOGR,Reach-1,5
Up Type=0
Dn Type=3
Dn Slope=0.005
Boundary for River Rch & Prof#=UNT014 IN NNOGR,Reach-1,6
Up Type=0
Dn Type=3
Dn Slope=0.005
Boundary for River Rch & Prof#=UNT014 IN NNOGR,Reach-1,7
Up Type=0
Dn Type=3
Dn Slope=0.005

--- UNT014 IN NNOGR.g01 (geometry) ---

Geom Title=Existing Conditions
Program Version=4.10

River Reach=UNT014 IN NNOGR ,Reach-1
Reach XY= 30
       2781139.3     10063989.08      2781224.56     10063701.33
       2781375.2     10063522.56      2781598.84     10063004.85
      2781525.06     10062605.37      2781069.37     10061596.36
      2781119.57     10060663.72      2781202.34     10060421.25
      2781467.39     10060378.05      2781471.44     10060130.74
      2781573.35     10060068.07      2781658.04     10059889.44
      2781652.57      10059565.9      2781558.42     10059378.14
      2781638.11     10059235.08      2781582.05     10059145.04
      2781682.44     10059050.74      2781682.87     10058910.87
      2781821.06     10058644.85      2782002.57     10058479.91
      2782230.84     10057814.69      2782385.63     10057668.35
      2782482.24      10055225.3      2783074.08     10054564.94
      2783420.91     10054659.22      2783589.59     10054800.87
      2783867.85     10054799.62      2784069.65     10054706.59
      2784457.14     10054650.53      2784690.93     10054400.56

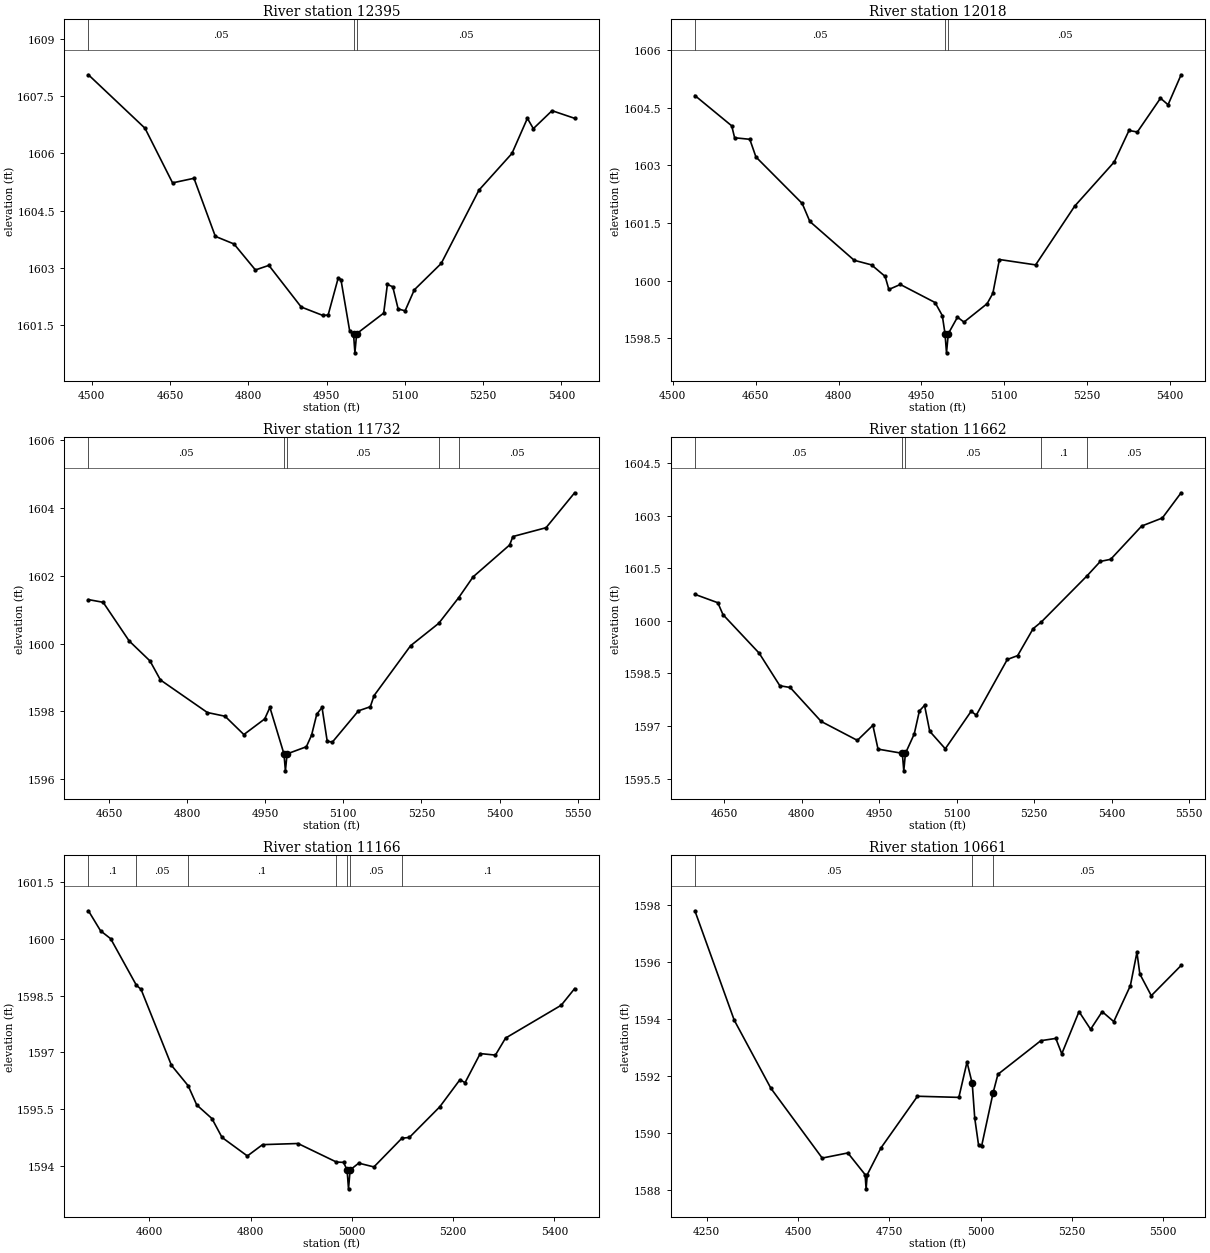
Type RM Length L Ch R = 1 ,12395   ,377,377,377
BEGIN DESCRIPTION:
UNT014 IN NNOGR 26.0
END DESCRIPTION:
XS GIS Cut Line= 2
      2781663.53     10063957.43      2780760.76     10063728.27
#Sta/Elev= 30
  4493.8 1608.06  4602.2 1606.66    4655 1605.23    4696 1605.35  4736.9 1603.83
  4772.7 1603.63  4813.7 1602.95  4839.5 1603.07  4901.4 1601.98  4942.7 1601.76
    4953 1601.77  4972.3 1602.74  4977.5  1602.7  4994.2 1601.36  5001.6 1601.28
  5004.3 1600.78  5007.6 1601.28  5059.4 1601.82  5066.5 1602.57  5076.8 1602.51
  5087.1 1601.93  5100.4 1601.88  5118.1 1602.43  5169.6 1603.12  5241.9 1605.04
  5305.1    1606  5334.7 1606.92  5346.1 1606.65  5381.9 1607.12  5425.2 1606.92
#Mann= 3 ,-1 , 0
  4493.8     .05       0  5001.6    .035       0  5007.6     .05       0
Bank Sta=5001.6,5007.6
XS Rating Curve= 0 ,0
Exp/Cntr=0.3,0.1

Type RM Length L Ch R = 1 ,12018   ,286,286,286
BEGIN DESCRIPTION:
UNT014 IN NNOGR 25.0
END DESCRIPTION:
XS GIS Cut Line= 2
       2781814.1     10063659.25      2780972.78     10063401.22
#Sta/Elev= 30
  4539.9 1604.82  4606.6 1604.03  4611.8 1603.72  4639.3 1603.68  4650.4 1603.22
  4734.1 1602.01    4748 1601.54  4828.2 1600.53  4859.6 1600.41  4884.2 1600.11
    4891 1599.77  4911.7  1599.9  4974.6 1599.43  4987.7 1599.09  4992.6 1598.62
  4995.3 1598.12  4998.6 1598.62  5015.2 1599.05  5026.9 1598.92  5068.8  1599.4
  5079.2 1599.67  5091.1 1600.55  5156.6 1600.41  5227.3 1601.94  5298.9 1603.09
  5325.6 1603.91  5340.7 1603.87  5382.6 1604.75  5396.3 1604.58  5419.9 1605.36
#Mann= 3 ,-1 , 0
  4539.9     .05       0  4992.6    .035       0  4998.6     .05       0
Bank Sta=4992.6,4998.6
XS Rating Curve= 0 ,0
Exp/Cntr=0.3,0.1

Type RM Length L Ch R = 1 ,11732   ,70,70,70
BEGIN DESCRIPTION:
Mapping XS d4e03f43
END DESCRIPTION:
XS GIS Cut Line= 2
      2781886.73     10063288.15      2780953.63     10063254.51
#Sta/Elev= 30
  4610.5  1601.3  4638.8 1601.22  4688.8 1600.08  4728.8 1599.49  4748.8 1598.93
  4838.9 1597.97  4872.9 1597.86    4909 1597.32    4949 1597.78    4959 1598.12
    4986 1596.75  4988.8 1596.25    4992 1596.75    5029 1596.96    5039  1597.3
    5049 1597.92  5059.1 1598.12  5069.1 1597.12  5079.1  1597.1  5129.1 1598.02
  5151.8 1598.14  5159.1 1598.47  5229.2 1599.94  5283.2  1600.6  5321.7 1601.36
  5349.2 1601.97  5419.3 1602.91  5425.7 1603.16  5489.3 1603.42  5544.2 1604.45
#Mann= 5 ,-1 , 0
  4610.5     .05       0    4986    .035       0    4992     .05       0
  5283.2      .1       0  5321.7     .05       0
Bank Sta=4986,4992
XS Rating Curve= 0 ,0
Exp/Cntr=0.3,0.1

Type RM Length L Ch R = 1 ,11662   ,496,496,496
BEGIN DESCRIPTION:
Mapping XS 352de3b6
END DESCRIPTION:
XS GIS Cut Line= 2
      2781912.83     10063213.28      2780972.21     10063194.86
#Sta/Elev= 30
  4593.7 1600.76  4638.1 1600.52  4648.1 1600.18  4718.1 1599.08  4758.1 1598.15
  4778.1  1598.1  4838.1 1597.13  4908.1 1596.59  4938.1 1597.02  4948.1 1596.34
  4995.1 1596.22  4997.9 1595.72  5001.1 1596.22  5018.1 1596.77  5028.1 1597.43
  5038.1 1597.59  5048.1 1596.85  5078.2 1596.35  5128.2 1597.42  5138.2 1597.31
  5198.2  1598.9  5218.2 1599.01  5248.2 1599.78    5264 1599.97  5352.6 1601.29
  5378.2  1601.7  5398.2 1601.76  5458.2 1602.71  5498.2 1602.94  5534.5 1603.66
#Mann= 5 ,-1 , 0
  4593.7     .05       0  4995.1    .035       0  5001.1     .05       0
    5264      .1       0  5352.6     .05       0
Bank Sta=4995.1,5001.1
XS Rating Curve= 0 ,0
Exp/Cntr=0.3,0.1

Type RM Length L Ch R = 1 ,11166   ,505,505,505
BEGIN DESCRIPTION:
UNT014 IN NNOGR 24.0
END DESCRIPTION:
XS GIS Cut Line= 2
      2782052.44     10062742.16        2781092.     10062752.56
#Sta/Elev= 30
  4479.4 1600.75  4503.4 1600.22  4523.4 1600.01  4574.1 1598.78  4583.4 1598.67
  4643.4 1596.66  4676.4 1596.12  4693.4 1595.61  4723.4 1595.25  4743.4 1594.75
  4793.4 1594.26  4823.4 1594.56  4893.4 1594.59  4969.2  1594.1  4983.4 1594.09
  4990.4 1593.89  4993.2 1593.39  4996.4 1593.89  5013.4 1594.07  5043.4 1593.97
  5098.7 1594.73  5113.4 1594.75  5173.4 1595.56  5213.4 1596.28  5223.4  1596.2
  5253.4 1596.97  5283.4 1596.93  5303.4 1597.38  5413.4 1598.25  5439.9 1598.69
#Mann= 7 ,-1 , 0
  4479.4      .1       0  4574.1     .05       0  4676.4      .1       0
  4969.2     .05       0  4990.4    .035       0  4996.4     .05       0
  5098.7      .1       0
Bank Sta=4990.4,4996.4
XS Rating Curve= 0 ,0
Exp/Cntr=0.3,0.1

Type RM Length L Ch R = 1 ,10661   ,481,481,481
BEGIN DESCRIPTION:
UNT014 IN NNOGR 23.0
END DESCRIPTION:
XS GIS Cut Line= 3
      2782135.79     10062294.24       2781493.4     10062242.16
      2780844.07     10062464.39
#Sta/Elev= 30
  4217.9 1597.79  4325.6 1593.95  4425.9 1591.56  4566.4 1589.11  4636.6 1589.29
  4683.8 1588.53  4686.5 1588.03  4689.8 1588.53  4726.9 1589.46  4827.2 1591.28
  4940.4 1591.24  4962.7 1592.48    4977 1591.73  4983.9 1590.51  4994.4 1589.56
    5003 1589.55  5034.3 1591.41  5047.3 1592.05  5164.7 1593.23  5205.8 1593.31
  5222.1 1592.77  5269.3 1594.25    5301 1593.63  5332.7 1594.25  5364.4  1593.9
  5409.8 1595.16  5427.8 1596.33  5435.8 1595.57  5467.1 1594.81  5548.7 1595.87
#Mann= 3 , 0 , 0
  4217.9     .05       0    4977     .03       0  5034.3     .05       0
#Block Obstruct= 2 , 0
          4958.4 1589.54
Bank Sta=4977,5034.3
XS Rating Curve= 0 ,0
Exp/Cntr=0.3,0.1

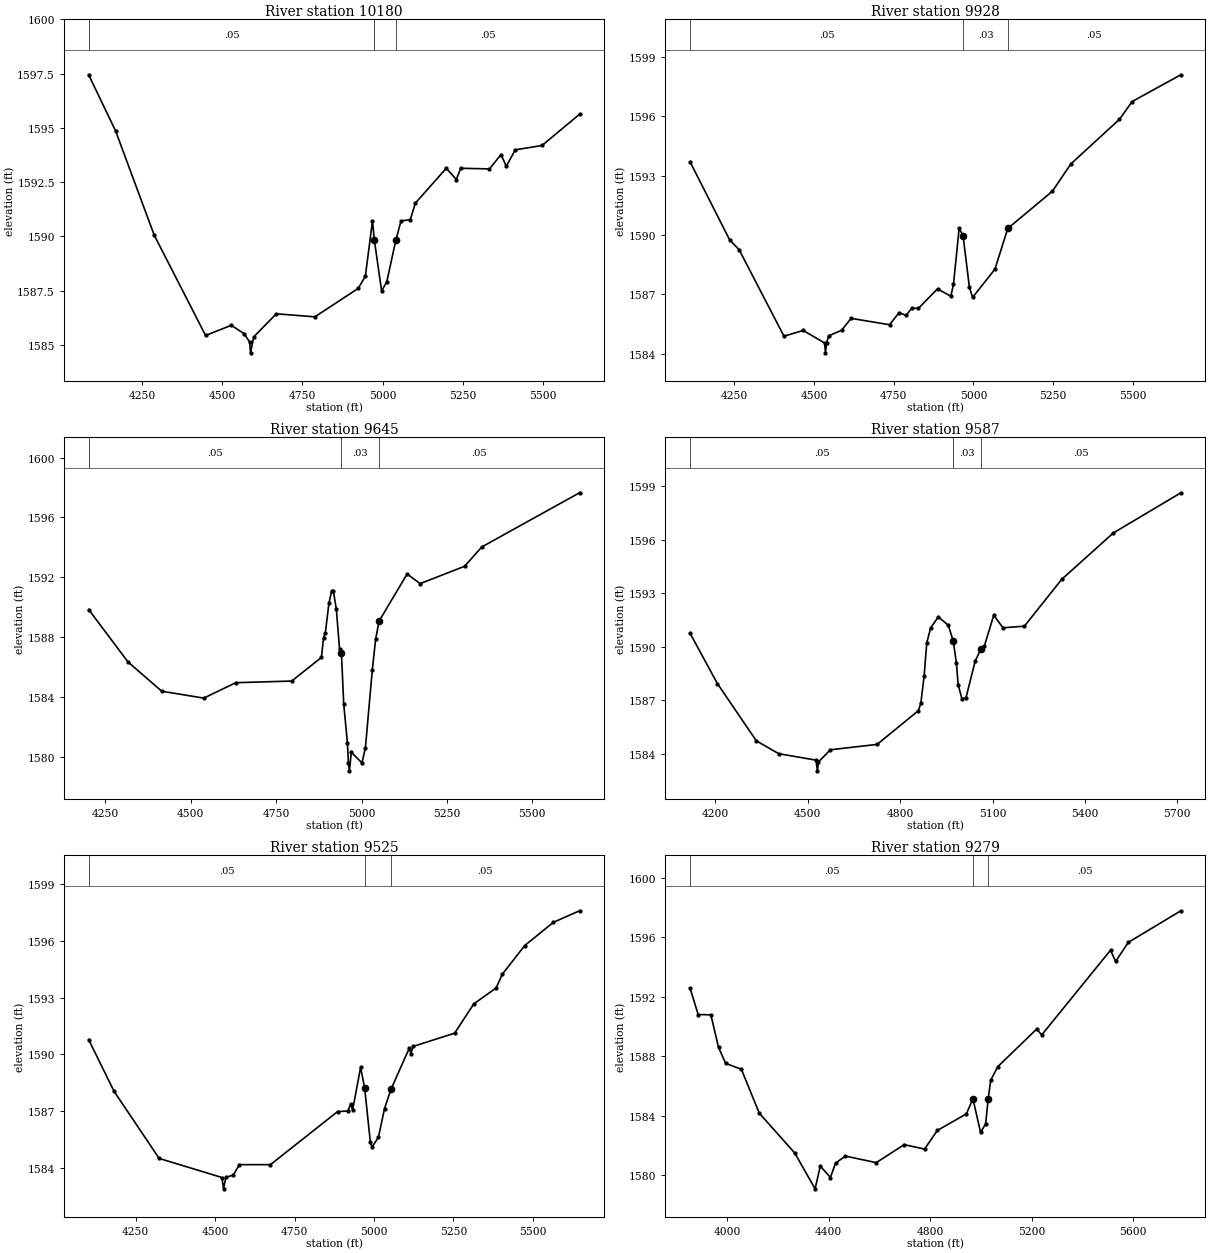
Type RM Length L Ch R = 1 ,10180   ,252,252,252
BEGIN DESCRIPTION:
UNT014 IN NNOGR 22.0
END DESCRIPTION:
XS GIS Cut Line= 3
      2782052.38     10061728.27       2781305.9     10061776.88
      2780607.99     10062131.05
#Sta/Elev= 30
  4083.5 1597.45  4167.6 1594.86  4287.8 1590.06  4448.2 1585.43  4528.4  1585.9
  4568.4 1585.51  4585.5 1585.13  4588.2 1584.63  4598.5 1585.37  4668.7 1586.43
  4788.9 1586.29    4924  1587.6  4946.3 1588.16  4968.6 1590.71  4974.5 1589.82
  4996.9 1587.49  5013.1  1587.9  5041.8 1589.85  5057.6 1590.71  5086.6 1590.77
  5102.1 1591.53  5198.7 1593.14  5230.1 1592.62  5243.6 1593.14  5333.3 1593.11
  5369.3 1593.77  5385.9 1593.23  5413.8 1593.99  5497.3 1594.19  5614.2 1595.63
#Mann= 3 , 0 , 0
  4083.5     .05       0  4974.5     .03       0  5041.8     .05       0
#Block Obstruct= 2 , 0
          4965.3 1587.57
Bank Sta=4974.5,5041.8
XS Rating Curve= 0 ,0
Exp/Cntr=0.3,0.1

Type RM Length L Ch R = 1 ,9928    ,283,283,283
BEGIN DESCRIPTION:
Mapping XS 5d58c632
END DESCRIPTION:
XS GIS Cut Line= 3
      2781962.32     10061677.18      2781118.18     10061616.42
      2780425.87     10061601.23
#Sta/Elev= 30
  4111.3  1593.7  4235.5 1589.76  4265.6 1589.25  4405.9 1584.89  4466.1 1585.18
  4533.3 1584.55    4536 1584.05  4539.3 1584.55  4546.3 1584.91  4586.4 1585.19
  4616.5 1585.79  4736.8 1585.47  4766.8 1586.08    4789 1585.94    4807 1586.32
    4827 1586.29  4887.2 1587.28  4928.9 1586.91  4937.3 1587.51    4955 1590.33
  4967.3 1589.97  4987.3 1587.35  4997.3 1586.85  5067.4 1588.28  5107.4 1590.33
  5247.4 1592.21  5305.3 1593.59  5457.5 1595.84  5497.5 1596.74  5650.1 1598.09
#Mann= 3 , 0 , 0
  4111.3     .05       0  4967.3     .03       0  5107.4     .05       0
#Block Obstruct= 2 , 0
         4947.88 1586.85
Bank Sta=4967.3,5107.4
XS Rating Curve= 0 ,0
Exp/Cntr=0.3,0.1

Type RM Length L Ch R = 1 ,9645    ,58,58,58
BEGIN DESCRIPTION:
Mapping XS b8c66b24
END DESCRIPTION:
XS GIS Cut Line= 3
      2781844.52     10061651.62       2781120.6     10061339.13
      2780472.79     10061383.36
#Sta/Elev= 30
  4200.7 1589.85  4316.2 1586.34  4414.8 1584.39  4537.8 1583.93  4631.8 1584.96
  4795.5 1585.07  4882.6 1586.65  4888.6 1587.95  4894.1  1588.3  4904.4 1590.26
  4912.2 1591.08  4917.6 1591.06  4926.2 1589.87  4935.7 1587.18  4941.1 1586.93
  4947.9 1583.51  4958.8  1580.9  4961.6 1579.57  4964.4 1579.07  4970.1 1580.31
  5001.3  1579.6  5011.4 1580.62  5031.4 1585.79  5041.4 1587.88  5051.5 1589.08
  5133.4 1592.22  5171.7 1591.58    5302 1592.74  5352.2 1594.03  5638.5 1597.65
#Mann= 3 , 0 , 0
  4200.7     .05       0  4941.1     .03       0  5051.5     .05       0
Bank Sta=4941.1,5051.5
XS Rating Curve= 0 ,0
Exp/Cntr=0.3,0.1

Type RM Length L Ch R = 1 ,9587    ,62,62,62
BEGIN DESCRIPTION:
UNT014 IN NNOGR 21.0
END DESCRIPTION:
XS GIS Cut Line= 3
       2781933.1     10061552.68      2781089.35     10061284.45
      2780382.23     10061333.84
#Sta/Elev= 30
  4117.2 1590.76    4206 1587.94  4332.7 1584.73  4405.4 1584.01  4526.2 1583.65
  4531.2 1583.05  4534.4 1583.55  4573.3 1584.23  4724.9 1584.53  4859.1 1586.42
  4867.1 1586.86  4877.6 1588.36  4886.1 1590.21  4898.6 1591.05  4923.6 1591.67
  4955.8 1591.21    4972 1590.33  4982.5 1589.08  4988.1 1587.87  5000.4 1587.08
  5013.5 1587.14  5043.5  1589.2  5061.3 1589.85  5073.6 1590.06  5103.7 1591.76
  5133.8 1591.06  5203.2 1591.15  5324.2 1593.77  5492.1 1596.37  5711.4 1598.62
#Mann= 3 , 0 , 0
  4117.2     .05       0    4972     .03       0  5061.3     .05       0
#Block Obstruct= 2 , 0
         4932.65 1587.04
Bank Sta=4972,5061.3
XS Rating Curve= 0 ,0
Exp/Cntr=0.3,0.1

Type RM Length L Ch R = 1 ,9525    ,246,246,246
BEGIN DESCRIPTION:
Mapping XS 2af308d7
END DESCRIPTION:
XS GIS Cut Line= 3
      2781943.52     10061534.45      2781091.96     10061221.95
      2780456.51     10061263.61
#Sta/Elev= 30
  4102.5 1590.78  4182.5 1588.04  4324.3 1584.49  4521.7 1583.48  4526.8 1582.88
    4534 1583.49  4557.5 1583.61  4576.6 1584.16  4674.2 1584.16  4885.5 1586.97
  4917.4    1587  4927.3 1587.38  4932.6 1587.04  4957.8 1589.31  4970.7 1588.21
  4988.3 1585.38  4993.6 1585.09  5013.8  1585.6  5033.1 1587.13  5053.2 1588.14
  5110.8 1590.32  5115.8 1590.04  5123.3 1590.42  5253.6 1591.12  5313.7 1592.67
  5383.9 1593.51  5403.9 1594.25  5474.1 1595.76  5564.3 1596.99  5646.4  1597.6
#Mann= 3 , 0 , 0
  4102.5     .05       0  4970.7     .03       0  5053.2     .05       0
#Block Obstruct= 2 , 0
         4957.68 1585.05
Bank Sta=4970.7,5053.2
XS Rating Curve= 0 ,0
Exp/Cntr=0.3,0.1

Type RM Length L Ch R = 1 ,9279    ,304,304,304
BEGIN DESCRIPTION:
UNT014 IN NNOGR 20.0
END DESCRIPTION:
XS GIS Cut Line= 3
      2782270.53     10061047.84      2781178.95      10060978.4
      2780342.39     10061049.92
#Sta/Elev= 30
    3854 1592.59  3886.1  1590.8  3936.2 1590.78  3966.3  1588.6  3994.4 1587.52
  4056.5 1587.12  4126.6 1584.18  4266.9 1581.49  4346.8 1579.09  4367.1 1580.62
  4407.2 1579.85  4427.2 1580.82  4466.2 1581.29  4587.5 1580.85  4697.8 1582.06
  4777.9 1581.76    4828 1583.01  4942.9 1584.13  4968.3 1585.15  4998.5 1582.88
  5018.5 1583.46  5028.6 1585.15  5038.6 1586.39  5066.4  1587.3  5219.3 1589.82
  5239.3 1589.43  5510.3 1595.12  5530.4 1594.37  5580.6 1595.65  5787.4 1597.77
#Mann= 3 , 0 , 0
    3854     .05       0  4968.3     .03       0  5028.6     .05       0
#Block Obstruct= 2 , 0
         4951.41 1582.84
Bank Sta=4968.3,5028.6
XS Rating Curve= 0 ,0
Exp/Cntr=0.3,0.1

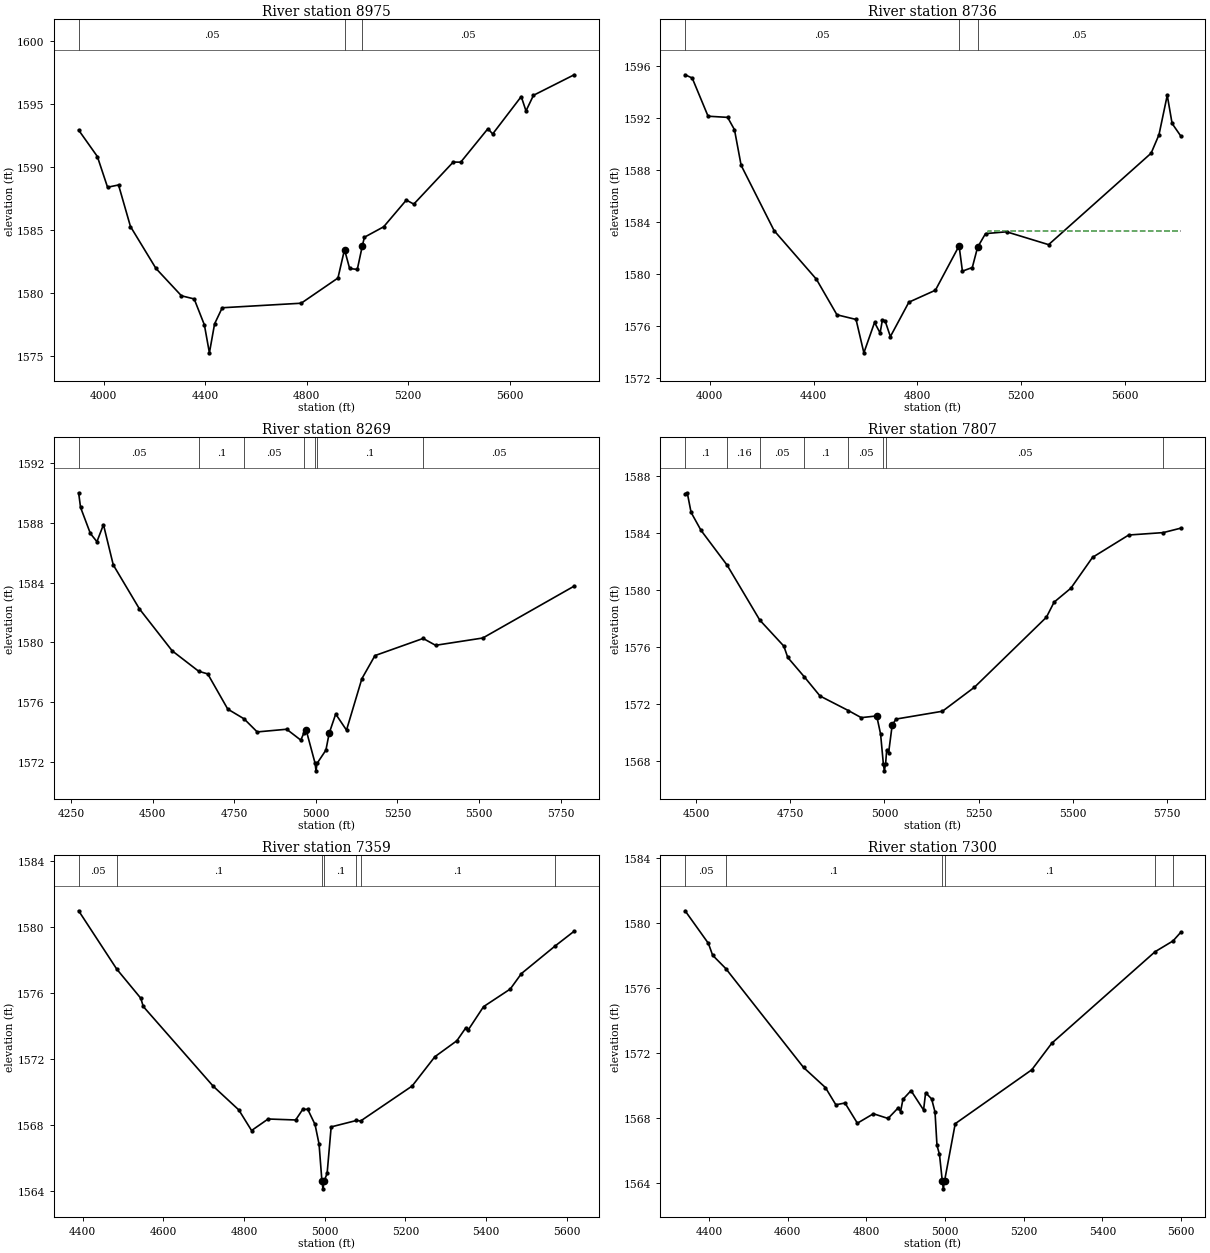
Type RM Length L Ch R = 1 ,8975    ,239,239,239
BEGIN DESCRIPTION:
Mapping XS 7c7920d3
END DESCRIPTION:
XS GIS Cut Line= 3
      2782211.93     10060783.09       2781066.1     10060676.75
      2780322.59     10060978.06
#Sta/Elev= 30
  3901.7 1592.93  3975.5 1590.83  4015.7 1588.39    4059 1588.57    4106 1585.27
  4206.5 1581.94  4306.9 1579.77  4357.1 1579.52  4397.3 1577.46  4417.1 1575.24
  4437.5 1577.54  4467.6 1578.82  4778.9 1579.18  4923.7 1581.18  4949.6 1583.44
  4969.7 1581.94  4999.9 1581.86  5019.9 1583.74    5028 1584.42  5103.9 1585.25
  5193.2 1587.37  5222.7 1587.05  5378.1 1590.39  5407.6 1590.38  5514.8 1593.04
  5533.5 1592.62  5646.1 1595.59  5664.8 1594.45  5694.3 1595.69  5854.7 1597.32
#Mann= 3 , 0 , 0
  3901.7     .05       0  4949.6     .03       0  5019.9     .05       0
#Block Obstruct= 2 , 0
          4947.9 1581.84
Bank Sta=4949.6,5019.9
XS Rating Curve= 0 ,0
Exp/Cntr=0.3,0.1

Type RM Length L Ch R = 1 ,8736    ,467,467,467
BEGIN DESCRIPTION:
UNT014 IN NNOGR 19.0
END DESCRIPTION:
XS GIS Cut Line= 3
      2782255.37      10060659.4      2781111.67     10060440.21
      2780375.96      10060557.4
#Sta/Elev= 30
  3905.1 1595.35  3932.5  1595.1  3993.6 1592.16    4069 1592.07  4095.4 1591.12
    4121 1588.38  4248.1 1583.35    4411 1579.61  4490.2 1576.87  4563.8 1576.51
    4594 1573.94  4635.1 1576.28  4656.5 1575.47  4665.6 1576.49  4675.8  1576.4
  4696.1 1575.19  4767.4 1577.84  4869.6 1578.76  4960.9 1582.18  4973.7 1580.23
  5011.8 1580.51  5032.2 1582.07  5062.7 1583.12  5143.7 1583.26  5305.8 1582.27
  5700.8 1589.31  5731.1 1590.73    5763 1593.77  5781.7  1591.6  5814.6 1590.65
#Mann= 3 , 0 , 0
  3905.1     .05       0  4960.9    .035       0  5032.2     .05       0
#XS Ineff= 2 , 0
                         5071.95         1583.33
Permanent Ineff=
       F       F
#Block Obstruct= 2 , 0
         4940.45 1580.25
Bank Sta=4960.9,5032.2
XS Rating Curve= 0 ,0
Exp/Cntr=0.3,0.1

Type RM Length L Ch R = 1 ,8269    ,462,462,462
BEGIN DESCRIPTION:
UNT014 IN NNOGR 18.0
END DESCRIPTION:
XS GIS Cut Line= 3
      2782184.38      10060287.3      2781264.24     10060221.32
      2780687.85      10060374.1
#Sta/Elev= 30
  4272.8 1590.03  4278.7 1589.05  4308.8  1587.3  4328.9 1586.75  4348.9 1587.89
    4379 1585.19  4459.2 1582.24  4559.5 1579.43  4640.7 1578.06  4668.5 1577.88
  4729.9 1575.52  4779.7 1574.87  4820.1 1573.99  4910.4 1574.17  4953.7 1573.44
  4963.2 1573.92  4970.5 1574.09  4997.6 1571.88  5000.3 1571.38  5003.6 1571.88
  5030.7 1572.77  5040.7  1573.9  5060.7 1575.19  5093.8 1574.11  5140.9 1577.56
    5181 1579.11  5328.7 1580.26  5366.8  1579.8  5511.6 1580.29  5791.6 1583.77
#Mann= 7 ,-1 , 0
  4272.8     .05       0  4640.7      .1       0  4779.7     .05       0
  4963.2      .1       0  4997.6     .07       0  5003.6      .1       0
  5328.7     .05       0
Bank Sta=4970.5,5040.7
XS Rating Curve= 0 ,0
Exp/Cntr=0.3,0.1

Type RM Length L Ch R = 1 ,7807    ,448,448,448
BEGIN DESCRIPTION:
UNT014 IN NNOGR 17.0
END DESCRIPTION:
XS GIS Cut Line= 3
      2782173.99     10059978.27       2781430.9     10059808.13
      2780889.21     10059915.77
#Sta/Elev= 30
  4471.2 1586.77  4476.9 1586.85  4487.1 1585.47  4513.4 1584.21  4582.7 1581.76
  4669.3  1577.9  4733.1 1576.07  4743.6 1575.27  4787.4 1573.91  4829.2 1572.56
  4904.2 1571.54  4938.5 1571.04  4979.5 1571.16  4989.8 1569.89  4997.1  1567.8
  4999.8  1567.3  5003.1  1567.8    5006 1568.75  5011.1 1568.57  5020.6 1570.52
  5030.8 1570.94  5153.9 1571.49  5238.9 1573.18  5429.7  1578.1  5450.1 1579.16
  5494.6 1580.14  5552.1 1582.31    5648 1583.88  5739.6 1584.05  5785.8 1584.36
#Mann= 8 ,-1 , 0
  4471.2      .1       0  4582.7     .16       0  4669.3     .05       0
  4787.4      .1       0  4904.2     .05       0  4997.1    .035       0
  5003.1     .05       0  5739.6      .1       0
Bank Sta=4979.5,5020.6
XS Rating Curve= 0 ,0
Exp/Cntr=0.3,0.1

Type RM Length L Ch R = 1 ,7359    ,59,59,59
BEGIN DESCRIPTION:
Mapping XS bdba9b24
END DESCRIPTION:
XS GIS Cut Line= 4
      2782184.38     10059610.21      2781649.65     10059429.66
      2781479.52     10059433.13      2781042.77      10059661.9
#Sta/Elev= 30
  4390.4 1580.99  4484.8 1577.45  4544.4 1575.68  4550.5 1575.18  4723.8 1570.34
  4787.2  1568.9  4818.8 1567.65  4859.8 1568.35    4928 1568.29  4945.5 1568.93
  4957.9 1568.94    4976 1568.02    4986 1566.83    4993 1564.61  4995.7 1564.11
    4999 1564.61    5006 1565.05    5016 1567.87  5078.7 1568.26    5089 1568.23
  5216.5 1570.35  5272.9 1572.13  5327.4  1573.1  5349.4 1573.88  5355.1 1573.74
  5393.5 1575.17  5459.7 1576.24  5487.4 1577.18  5571.2 1578.86    5618 1579.75
#Mann= 7 ,-1 , 0
  4390.4     .05       0  4484.8      .1       0    4993     .07       0
    4999      .1       0  5078.7     .05       0    5089      .1       0
  5571.2     .05       0
Bank Sta=4993,4999
XS Rating Curve= 0 ,0
Exp/Cntr=0.3,0.1

Type RM Length L Ch R = 1 ,7300    ,33,33,33
BEGIN DESCRIPTION:
Mapping XS f9817525
END DESCRIPTION:
XS GIS Cut Line= 4
      2782194.76     10059578.95      2781611.46     10059387.99
       2781493.4     10059391.46       2781017.7     10059620.63
#Sta/Elev= 30
  4339.2 1580.74  4398.4 1578.74  4409.2 1578.01  4442.7 1577.19  4640.4 1571.12
  4695.9 1569.89  4722.5 1568.83  4745.7 1568.94  4777.2  1567.7    4818 1568.28
  4855.2 1567.99  4881.7 1568.66    4887  1568.4    4893 1569.16  4913.6  1569.7
  4945.5 1568.51  4950.7 1569.57    4966 1569.19  4974.6 1568.39  4979.6 1566.34
    4986 1565.78    4993 1564.17  4995.7 1563.67    4999 1564.17    5026 1567.67
  5220.7 1570.98  5271.5 1572.61  5534.3 1578.23  5579.8 1578.89  5599.1 1579.41
#Mann= 6 ,-1 , 0
  4339.2     .05       0  4442.7      .1       0    4993     .07       0
    4999      .1       0  5534.3     .05       0  5579.8      .1       0
Bank Sta=4993,4999
XS Rating Curve= 0 ,0
Exp/Cntr=0.3,0.1

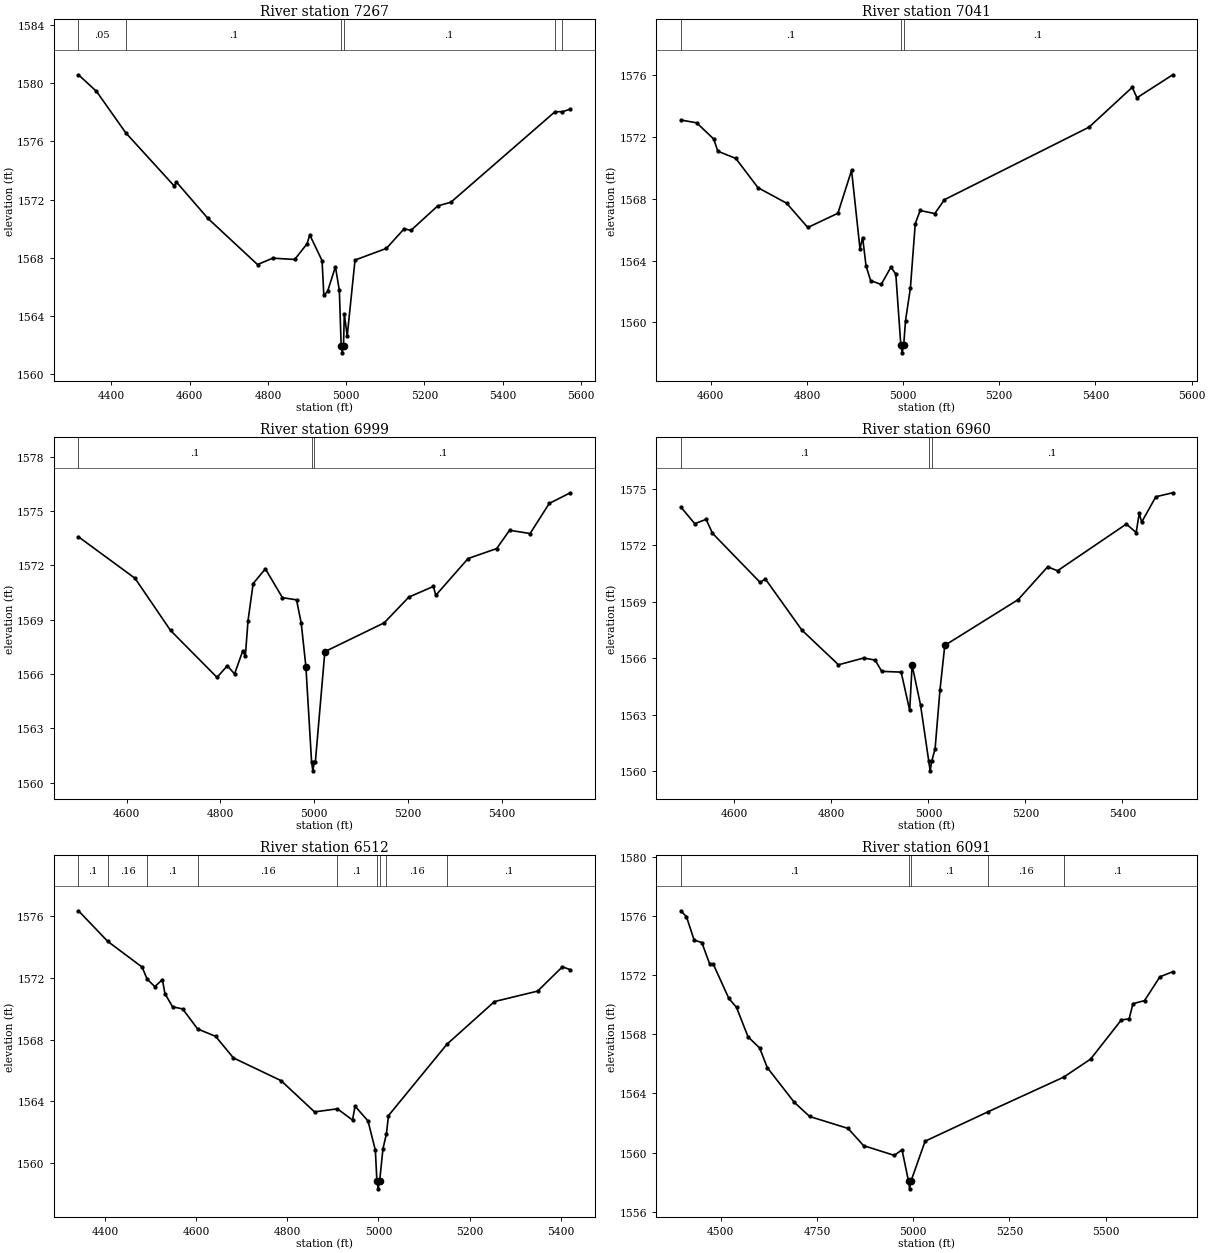
Type RM Length L Ch R = 1 ,7267    ,226,226,226
BEGIN DESCRIPTION:
UNT014 IN NNOGR 16.0
END DESCRIPTION:
XS GIS Cut Line= 4
      2782212.13     10059558.12      2781614.93     10059356.74
      2781451.74     10059363.68      2781032.51     10059561.17
#Sta/Elev= 30
  4315.9 1580.58    4362 1579.44  4436.8 1576.59  4560.8 1572.93  4566.1 1573.21
  4646.9  1570.7  4773.6 1567.53  4812.6 1567.97  4868.5 1567.88  4900.2 1568.96
    4907 1569.57  4938.5  1567.8    4943 1565.41  4952.6 1565.69  4972.6 1567.38
  4982.6 1565.76  4987.3 1561.96  4990.1 1561.46  4993.3 1561.96  4995.3 1564.15
  5002.7 1562.61  5022.7 1567.84  5102.7 1568.64  5148.3 1569.99  5165.6 1569.88
  5233.9 1571.56  5267.9 1571.82  5533.8 1578.04  5552.8 1578.04  5572.9 1578.22
#Mann= 6 ,-1 , 0
  4315.9     .05       0  4436.8      .1       0  4987.3     .07       0
  4993.3      .1       0  5533.8     .05       0  5552.8      .1       0
Bank Sta=4987.3,4993.3
XS Rating Curve= 0 ,0
Exp/Cntr=0.3,0.1

Type RM Length L Ch R = 1 ,7041    ,42,42,42
BEGIN DESCRIPTION:
Mapping XS 186f64ed
END DESCRIPTION:
XS GIS Cut Line= 4
       2782018.2     10059346.09      2781656.19     10059179.41
       2781473.9     10059208.06      2781046.06     10059309.18
#Sta/Elev= 30
    4538 1573.11  4570.7 1572.93  4606.3 1571.88  4614.8 1571.09  4652.3 1570.62
  4698.2 1568.73  4757.9 1567.72  4801.9 1566.15  4864.5 1567.07  4892.9 1569.85
  4910.4 1564.77  4915.9  1565.5    4923 1563.66  4932.5 1562.71  4954.5 1562.46
  4974.7 1563.58  4984.9 1563.13  4995.3 1558.53  4998.1 1558.03  5001.3 1558.53
  5005.1 1560.12  5015.2 1562.22  5025.3 1566.39  5035.5 1567.25  5065.9 1567.05
  5086.1 1567.95  5386.8 1572.65  5476.5 1575.23  5486.3 1574.55  5560.7 1576.04
#Mann= 3 ,-1 , 0
    4538      .1       0  4995.3     .07       0  5001.3      .1       0
Bank Sta=4995.3,5001.3
XS Rating Curve= 0 ,0
Exp/Cntr=0.3,0.1

Type RM Length L Ch R = 1 ,6999    ,39,39,39
BEGIN DESCRIPTION:
Mapping XS 7c8f990c
END DESCRIPTION:
XS GIS Cut Line= 4
      2782046.81     10059317.43      2781684.84     10059150.77
      2781583.28     10059150.77      2781044.22     10059252.33
#Sta/Elev= 30
  4497.5 1573.58  4618.1 1571.29  4693.8 1568.41  4792.9 1565.82  4814.9 1566.46
  4830.3 1566.01  4847.8 1567.28  4853.3 1566.99    4859 1568.95    4870    1571
    4896 1571.81  4932.4 1570.22  4962.4  1570.1  4972.4 1568.82  4982.4 1566.41
  4994.5 1561.16  4997.2 1560.66  5000.5 1561.16  5002.6 1561.16  5022.8 1567.24
  5149.3 1568.83  5201.8 1570.25  5254.2 1570.84  5259.3 1570.35  5328.1 1572.38
  5389.1 1572.93  5416.6 1573.94  5460.4 1573.76  5501.1 1575.42  5546.1 1576.01
#Mann= 3 ,-1 , 0
  4497.5      .1       0  4994.5     .07       0  5000.5      .1       0
Bank Sta=4982.4,5022.8
XS Rating Curve= 0 ,0
Exp/Cntr=0.3,0.1

Type RM Length L Ch R = 1 ,6960    ,448,448,448
BEGIN DESCRIPTION:
UNT014 IN NNOGR 15.0
END DESCRIPTION:
XS GIS Cut Line= 4
       2782078.1     10059280.99      2781705.67     10059116.91
      2781512.96     10059122.12      2781104.08     10059189.83
#Sta/Elev= 30
  4489.5 1574.02  4518.2 1573.14  4541.5 1573.37  4554.7 1572.63    4653 1570.02
  4663.6 1570.21    4739 1567.49  4814.5 1565.65  4866.6 1566.01    4890  1565.9
  4903.7  1565.3  4943.7 1565.26  4961.3 1563.23  4966.3 1565.63  4983.7 1563.51
  5000.7 1560.52  5003.5 1560.02  5006.7 1560.52  5013.7  1561.2  5023.7  1564.3
  5033.7 1566.68    5185 1569.11  5245.8 1570.85  5266.1 1570.64    5408 1573.12
  5428.3 1572.67  5434.6 1573.69  5439.6 1573.22  5468.8 1574.57  5503.7 1574.78
#Mann= 3 ,-1 , 0
  4489.5      .1       0  5000.7     .07       0  5006.7      .1       0
Bank Sta=4966.3,5033.7
XS Rating Curve= 0 ,0
Exp/Cntr=0.3,0.1

Type RM Length L Ch R = 1 ,6512    ,421,421,421
BEGIN DESCRIPTION:
UNT014 IN NNOGR 14.0
END DESCRIPTION:
XS GIS Cut Line= 2
       2782354.5     10059033.81      2781393.08     10058544.43
#Sta/Elev= 30
  4342.1 1576.37  4406.4 1574.38  4481.7 1572.71  4492.7 1571.93  4509.6 1571.44
  4526.2  1571.9  4531.8 1570.99  4548.5 1570.13  4570.7 1569.99  4603.5 1568.69
    4643 1568.21  4681.9 1566.81  4786.5 1565.33  4859.9  1563.3    4910  1563.5
  4943.2 1562.77  4948.8 1563.67  4977.2 1562.71  4993.3 1560.81  4996.7  1558.8
  4999.4  1558.3  5002.7  1558.8    5010 1560.91  5017.6 1561.88  5022.1 1563.06
  5150.4  1567.7  5254.6 1570.47  5349.2 1571.15  5403.6 1572.73  5420.9 1572.54
#Mann= 9 ,-1 , 0
  4342.1      .1       0  4406.4     .16       0  4492.7      .1       0
  4603.5     .16       0    4910      .1       0  4996.7     .07       0
  5002.7      .1       0  5017.6     .16       0  5150.4      .1       0
Bank Sta=4996.7,5002.7
XS Rating Curve= 0 ,0
Exp/Cntr=0.3,0.1

Type RM Length L Ch R = 1 ,6091    ,119,119,119
BEGIN DESCRIPTION:
Mapping XS 260c88ff
END DESCRIPTION:
XS GIS Cut Line= 2
        2782613.     10058431.84      2781335.14     10058402.29
#Sta/Elev= 30
  4396.4 1576.34  4410.9 1575.94  4430.9 1574.36  4450.9 1574.19    4471 1572.76
    4481 1572.71    4521 1570.42    4541 1569.81    4571 1567.82    4601 1567.07
    4621 1565.74    4691  1563.4    4731 1562.44    4831 1561.63  4871.1 1560.47
  4951.1 1559.81  4971.1 1560.19  4988.1 1558.05  4990.8 1557.55  4994.1 1558.05
  5031.1 1560.77  5194.9 1562.76  5391.3  1565.1  5461.2 1566.32  5541.2 1568.97
  5561.2 1569.03  5571.2 1570.06  5601.3 1570.27  5641.3 1571.88  5674.6 1572.22
#Mann= 5 ,-1 , 0
  4396.4      .1       0  4988.1     .07       0  4994.1      .1       0
  5194.9     .16       0  5391.3      .1       0
Bank Sta=4988.1,4994.1
XS Rating Curve= 0 ,0
Exp/Cntr=0.3,0.1

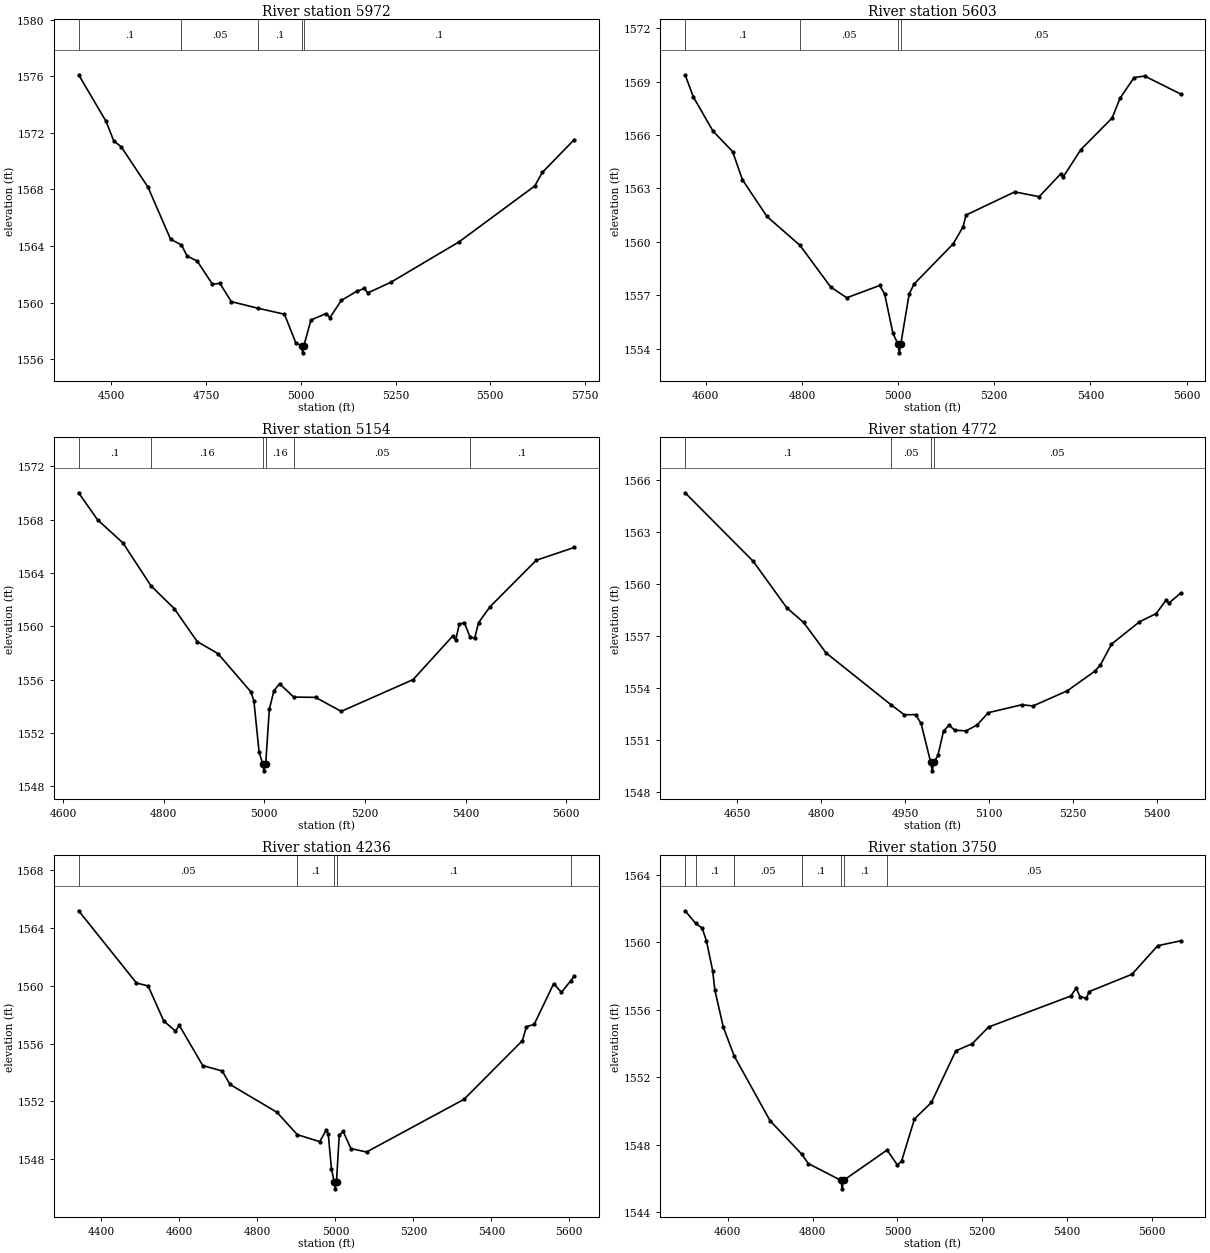
Type RM Length L Ch R = 1 ,5972    ,369,369,369
BEGIN DESCRIPTION:
UNT014 IN NNOGR 13.0
END DESCRIPTION:
XS GIS Cut Line= 2
      2782650.98     10058337.92      2781344.66     10058295.72
#Sta/Elev= 30
  4414.1 1576.11  4486.6 1572.81  4506.7 1571.44  4526.7 1571.01  4596.7 1568.18
  4656.7 1564.48  4685.4 1564.08  4700.2 1563.29  4726.8 1562.94  4766.8 1561.31
  4786.8 1561.36  4816.8 1560.07  4886.2 1559.61  4956.9 1559.18  4986.9 1557.16
  5002.1 1556.95  5004.9 1556.45  5008.1 1556.95  5026.9 1558.77    5067 1559.23
    5077 1558.94    5107 1560.16    5147 1560.79    5167    1561    5177 1560.69
    5237 1561.43  5417.1 1564.29  5617.2 1568.25  5637.2 1569.21  5721.1 1571.52
#Mann= 5 ,-1 , 0
  4414.1      .1       0  4685.4     .05       0  4886.2      .1       0
  5002.1     .07       0  5008.1      .1       0
Bank Sta=5002.1,5008.1
XS Rating Curve= 0 ,0
Exp/Cntr=0.3,0.1

Type RM Length L Ch R = 1 ,5603    ,449,449,449
BEGIN DESCRIPTION:
UNT014 IN NNOGR 12.0
END DESCRIPTION:
XS GIS Cut Line= 2
      2782625.38     10058065.08      2781614.94     10057860.21
#Sta/Elev= 30
  4556.8 1569.38  4574.1 1568.13  4614.9 1566.22  4655.7 1565.07  4676.1 1563.49
  4727.1 1561.43  4795.8 1559.81  4859.8 1557.47  4893.1 1556.87  4961.8 1557.56
    4972 1557.08  4989.3 1554.87  4999.6 1554.28  5002.4 1553.78  5005.6 1554.28
    5023 1557.08  5033.2 1557.64  5114.8  1559.9  5135.3 1560.86  5141.3 1561.51
  5242.7 1562.81  5293.4 1562.54  5338.9 1563.84    5344 1563.67  5380.1 1565.18
  5445.4 1566.96  5461.8 1568.07  5490.9 1569.22  5512.8 1569.31  5587.8  1568.3
#Mann= 4 ,-1 , 0
  4556.8      .1       0  4795.8     .05       0  4999.6    .035       0
  5005.6     .05       0
Bank Sta=4999.6,5005.6
XS Rating Curve= 0 ,0
Exp/Cntr=0.3,0.1

Type RM Length L Ch R = 1 ,5154    ,382,382,382
BEGIN DESCRIPTION:
UNT014 IN NNOGR 11.0
END DESCRIPTION:
XS GIS Cut Line= 2
      2782739.94     10057676.19      2781774.63     10057481.73
#Sta/Elev= 30
  4631.2 1570.02  4668.7    1568  4719.5 1566.25    4775 1563.04  4821.1 1561.34
  4866.9 1558.86  4908.1 1557.96  4973.6 1555.09  4979.5  1554.4  4989.7 1550.61
  4996.9 1549.67  4999.7 1549.17  5002.9 1549.67  5010.1 1553.79  5019.3 1555.18
  5030.5  1555.7  5058.6  1554.7  5101.9 1554.68    5153 1553.63  5295.8 1556.01
  5375.1  1559.3  5380.2 1558.95  5387.6 1560.16  5397.8 1560.28  5408.9  1559.2
  5418.2 1559.12  5425.9 1560.28  5448.8 1561.48  5540.6 1564.96  5615.9 1565.92
#Mann= 6 ,-1 , 0
  4631.2      .1       0    4775     .16       0  4996.9     .07       0
  5002.9     .16       0  5058.6     .05       0  5408.9      .1       0
Bank Sta=4996.9,5002.9
XS Rating Curve= 0 ,0
Exp/Cntr=0.3,0.1

Type RM Length L Ch R = 1 ,4772    ,536,536,536
BEGIN DESCRIPTION:
UNT014 IN NNOGR 10.0
END DESCRIPTION:
XS GIS Cut Line= 2
      2782830.17     10057256.04      2781944.81     10057207.43
#Sta/Elev= 30
  4556.4 1565.28  4678.3 1561.32  4738.4 1558.63  4768.4 1557.79  4808.5 1556.03
  4924.4 1553.04  4948.7 1552.45  4968.7 1552.46  4978.7 1551.95  4995.8 1549.71
  4998.5 1549.21  5001.8 1549.71  5008.8  1550.1  5018.8 1551.51  5028.8 1551.85
  5038.8 1551.56  5059.2 1551.52  5078.9 1551.86  5098.9 1552.57    5159 1553.03
    5179 1552.96  5240.6 1553.84  5289.2 1554.96  5299.2 1555.31  5319.3 1556.53
  5369.3 1557.82  5399.4  1558.3  5416.9 1559.07  5421.9  1558.9  5443.1 1559.48
#Mann= 4 ,-1 , 0
  4556.4      .1       0  4924.4     .05       0  4995.8    .035       0
  5001.8     .05       0
Bank Sta=4995.8,5001.8
XS Rating Curve= 0 ,0
Exp/Cntr=0.3,0.1

Type RM Length L Ch R = 1 ,4236    ,486,486,486
BEGIN DESCRIPTION:
UNT014 IN NNOGR 9.0
END DESCRIPTION:
XS GIS Cut Line= 2
      2783076.76     10056707.43      2781805.88     10056690.07
#Sta/Elev= 30
  4341.4  1565.2  4489.7  1560.2  4519.7 1559.99  4559.7 1557.57  4589.7 1556.87
  4599.7 1557.26  4659.7 1554.48  4709.7  1554.1  4729.7 1553.17  4849.7 1551.25
  4902.4 1549.69  4959.8 1549.21  4976.6 1550.02  4981.6 1549.75  4989.8 1547.32
  4996.8 1546.44  4999.5 1545.94  5002.8 1546.44  5009.8 1549.65  5019.8 1549.92
  5039.8 1548.73  5079.8 1548.49  5329.8 1552.14  5479.8 1556.21  5489.8 1557.17
  5509.8 1557.33  5559.8 1560.15  5579.8 1559.55  5603.4 1560.35  5612.4 1560.65
#Mann= 5 ,-1 , 0
  4341.4     .05       0  4902.4      .1       0  4996.8     .07       0
  5002.8      .1       0  5603.4      .1       0
Bank Sta=4996.8,5002.8
XS Rating Curve= 0 ,0
Exp/Cntr=0.3,0.1

Type RM Length L Ch R = 1 ,3750    ,608,608,608
BEGIN DESCRIPTION:
UNT014 IN NNOGR 8.0
END DESCRIPTION:
XS GIS Cut Line= 3
      2782938.59     10056196.48      2782289.31     10056219.05
      2781808.36     10056411.78
#Sta/Elev= 30
  4499.6 1561.87  4524.2 1561.13  4539.8 1560.84  4549.8  1560.1  4564.5 1558.33
  4569.8 1557.16  4589.8 1554.96  4615.6 1553.25  4699.8 1549.43  4774.2 1547.45
  4789.9 1546.89  4866.9 1545.89  4869.7 1545.39  4872.9 1545.89  4975.6 1547.69
    5000  1546.8    5010 1547.05  5040.1 1549.53  5080.1 1550.51  5137.6 1553.57
  5176.2 1553.99  5214.8 1554.98  5408.7 1556.82  5421.1 1557.28  5430.3 1556.78
  5445.3 1556.69  5451.8 1557.08  5552.9 1558.11  5613.4  1559.8  5667.4 1560.09
#Mann= 7 ,-1 , 0
  4499.6     .05       0  4524.2      .1       0  4615.6     .05       0
  4774.2      .1       0  4866.9    .035       0  4872.9      .1       0
  4975.6     .05       0
Bank Sta=4866.9,4872.9
XS Rating Curve= 0 ,0
Exp/Cntr=0.3,0.1