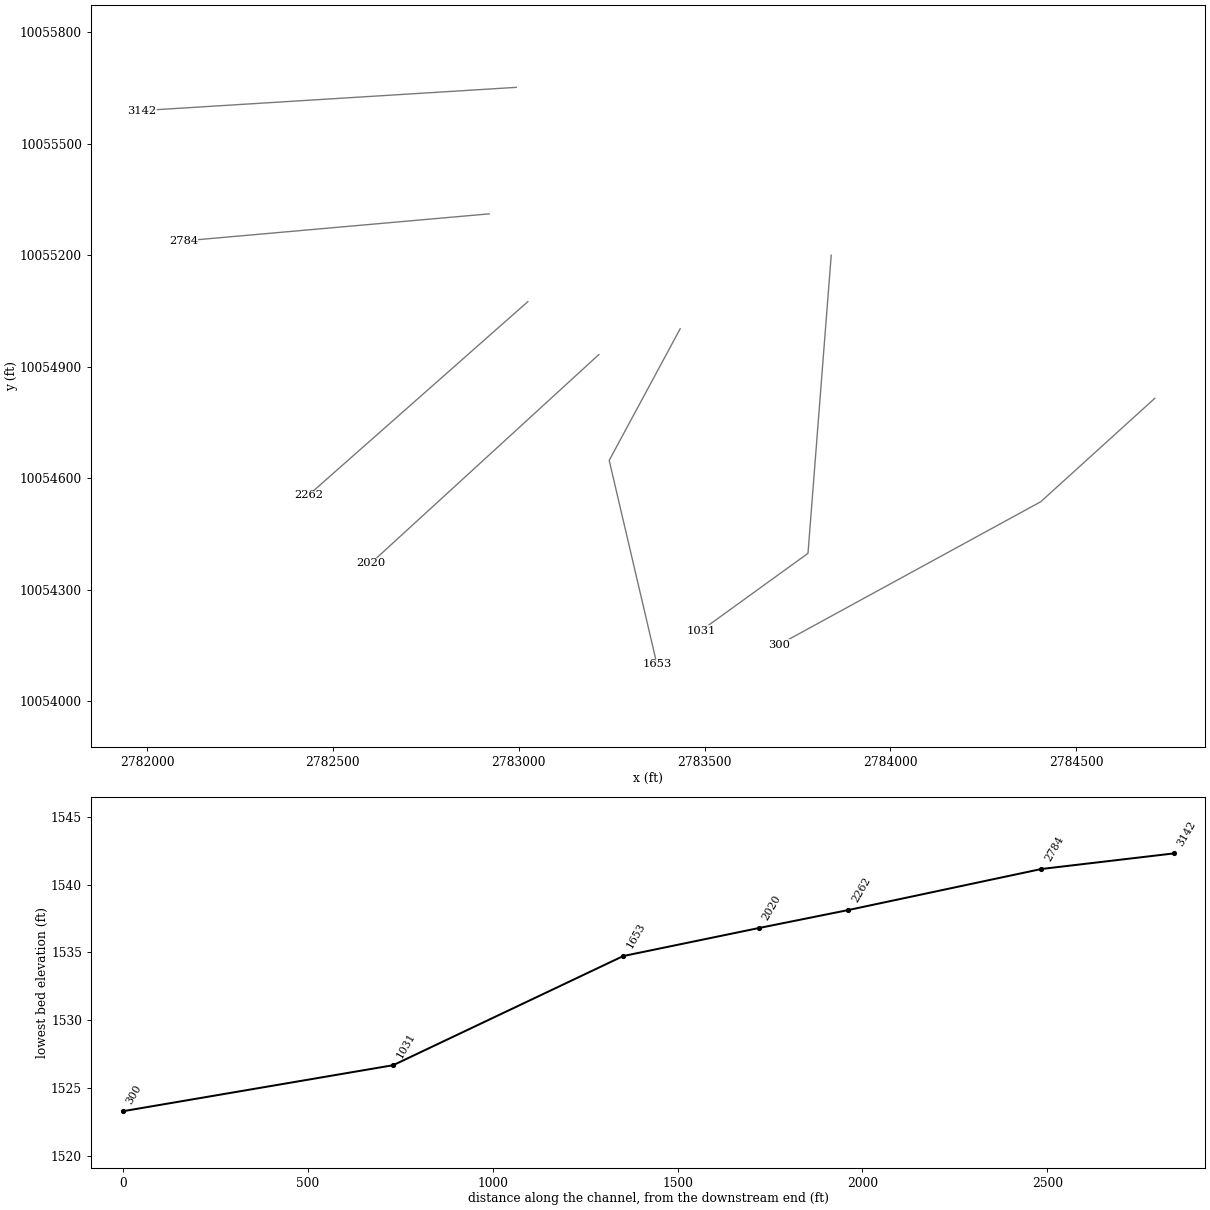
HEC-RAS study UNT014 IN NNOGR.prj: UNT014 IN NNOGR Base Level Engineering

--- UNT014 IN NNOGR.g01 (geometry) --- (continued)

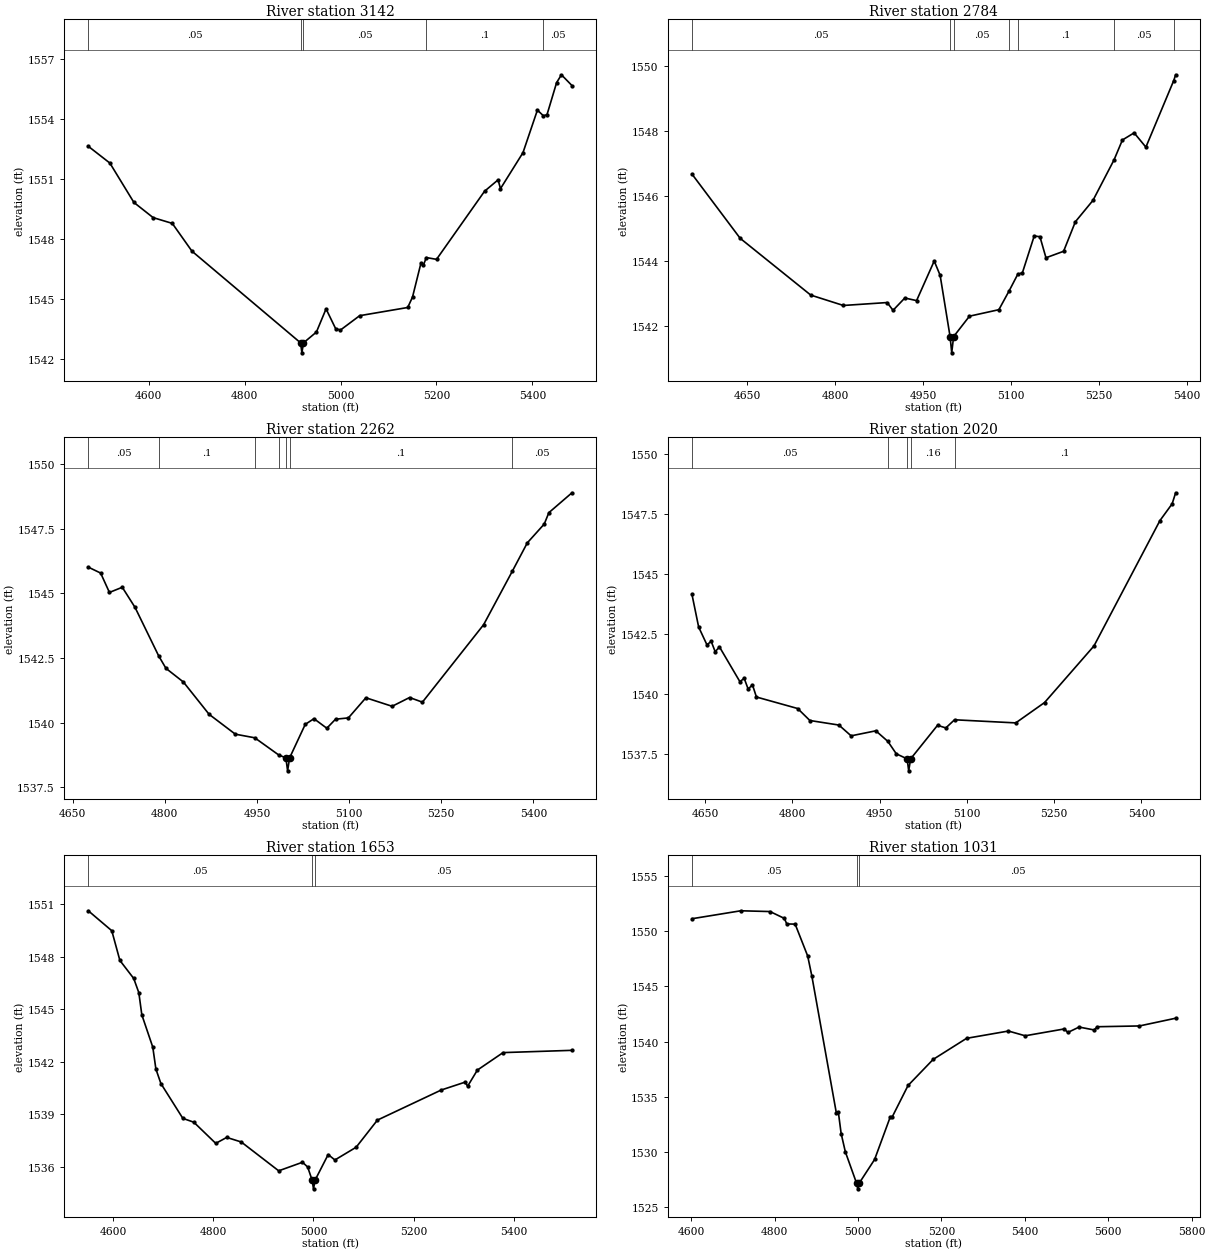
Type RM Length L Ch R = 1 ,3142    ,358,358,358
BEGIN DESCRIPTION:
UNT014 IN NNOGR 7.0
END DESCRIPTION:
XS GIS Cut Line= 2
      2782993.37     10055651.88      2781986.51     10055589.38
#Sta/Elev= 30
  4473.8 1552.65  4518.8 1551.81  4568.9 1549.84    4609 1549.08    4649 1548.79
    4690  1547.4  4916.6 1542.81  4919.3 1542.31  4922.6 1542.81  4949.6 1543.35
  4969.7 1544.51  4989.7 1543.52  4999.7 1543.45  5039.8 1544.17    5140 1544.58
    5150  1545.1  5167.6  1546.8  5172.6 1546.69  5178.8 1547.08  5200.1 1546.99
  5300.3  1550.4  5328.5 1550.97  5333.5 1550.53  5380.4 1552.33  5410.5 1554.46
  5422.9 1554.18  5430.5 1554.23  5450.6 1555.84  5460.6 1556.23  5482.6 1555.69
#Mann= 5 ,-1 , 0
  4473.8     .05       0  4916.6    .035       0  4922.6     .05       0
  5178.8      .1       0  5422.9     .05       0
Bank Sta=4916.6,4922.6
XS Rating Curve= 0 ,0
Exp/Cntr=0.3,0.1

Type RM Length L Ch R = 1 ,2784    ,522,522,522
BEGIN DESCRIPTION:
UNT014 IN NNOGR 6.0
END DESCRIPTION:
XS GIS Cut Line= 2
      2782920.47      10055311.6      2782097.89     10055238.71
#Sta/Elev= 30
  4555.6 1546.67  4637.9 1544.69  4758.4 1542.94  4814.1 1542.62  4888.9 1542.71
  4898.9 1542.47    4919 1542.85  4939.1 1542.77  4969.2 1543.99  4979.3 1543.55
  4996.3 1541.66  4999.1 1541.16  5002.3 1541.66  5029.4 1542.29  5079.6 1542.49
  5097.4 1543.08  5111.8 1543.58  5119.8 1543.63  5139.9 1544.76  5149.7 1544.74
    5160 1544.09  5190.1 1544.29  5210.2  1545.2  5240.3 1545.86  5276.3 1547.11
  5290.5 1547.72  5310.5 1547.94  5330.6  1547.5  5378.1 1549.55  5381.4 1549.73
#Mann= 7 ,-1 , 0
  4555.6     .05       0  4996.3     .07       0  5002.3     .05       0
  5097.4     .05       0  5111.8      .1       0  5276.3     .05       0
  5378.1      .1       0
Bank Sta=4996.3,5002.3
XS Rating Curve= 0 ,0
Exp/Cntr=0.3,0.1

Type RM Length L Ch R = 1 ,2262    ,242,242,242
BEGIN DESCRIPTION:
UNT014 IN NNOGR 5.0
END DESCRIPTION:
XS GIS Cut Line= 2
      2783024.66      10055075.5      2782434.39     10054554.67
#Sta/Elev= 30
  4675.5 1546.02  4695.6 1545.79  4709.9 1545.04  4730.8 1545.24  4751.6 1544.46
  4790.1 1542.58  4801.9  1542.1  4830.3 1541.57  4872.1 1540.32  4914.8 1539.55
  4946.4 1539.41  4985.1 1538.75  4997.1 1538.63  4999.9 1538.13  5003.1 1538.63
  5028.6 1539.93  5042.8 1540.15  5063.7 1539.78  5077.9 1540.13  5098.8 1540.18
  5127.3 1540.96    5170 1540.63  5198.4 1540.97  5219.3 1540.79  5318.9 1543.79
  5365.8 1545.87    5390 1546.96  5417.6 1547.69  5425.1 1548.13  5462.7  1548.9
#Mann= 7 ,-1 , 0
  4675.5     .05       0  4790.1      .1       0  4946.4     .16       0
  4985.1      .1       0  4997.1     .07       0  5003.1      .1       0
  5365.8     .05       0
Bank Sta=4997.1,5003.1
XS Rating Curve= 0 ,0
Exp/Cntr=0.3,0.1

Type RM Length L Ch R = 1 ,2020    ,367,367,367
BEGIN DESCRIPTION:
UNT014 IN NNOGR 4.0
END DESCRIPTION:
XS GIS Cut Line= 2
      2783215.64     10054933.14      2782602.26     10054371.74
#Sta/Elev= 30
  4627.2 1544.16  4638.7  1542.8  4652.9 1542.06  4660.3  1542.2  4667.1 1541.77
  4674.5 1541.97  4709.6 1540.52    4717 1540.66  4723.8 1540.21  4731.2 1540.39
    4738 1539.88  4808.9  1539.4  4829.9  1538.9  4879.8 1538.71  4900.8 1538.26
  4943.3 1538.47  4963.9 1538.03  4978.5 1537.51  4997.1  1537.3  4999.8  1536.8
  5003.1  1537.3  5049.4  1538.7  5063.6 1538.59  5078.6 1538.93  5183.8  1538.8
  5233.4 1539.65  5318.3 1542.01  5431.7 1547.24  5452.7 1547.94  5458.7  1548.4
#Mann= 5 ,-1 , 0
  4627.2     .05       0  4963.9     .16       0  4997.1     .07       0
  5003.1     .16       0  5078.6      .1       0
Bank Sta=4997.1,5003.1
XS Rating Curve= 0 ,0
Exp/Cntr=0.3,0.1

Type RM Length L Ch R = 1 ,1653    ,622,622,622
BEGIN DESCRIPTION:
UNT014 IN NNOGR 3.0
END DESCRIPTION:
XS GIS Cut Line= 3
      2783434.36     10055002.54       2783243.4     10054648.41
      2783371.88     10054099.79
#Sta/Elev= 30
  4550.5 1550.63  4597.4 1549.49  4613.6 1547.79  4641.2 1546.76  4651.4 1545.95
  4657.4 1544.68  4679.3 1542.83  4685.5 1541.58  4695.5 1540.75  4739.3 1538.76
  4761.2 1538.54    4805 1537.33  4826.9 1537.67  4855.9 1537.41  4930.7 1535.76
  4978.2 1536.25  4988.5 1535.98  4997.4 1535.23  5000.2 1534.73  5003.4 1535.23
  5029.5 1536.69  5042.9 1536.38  5085.4 1537.11  5127.8 1538.66  5255.2 1540.38
  5302.8 1540.83    5308  1540.6  5327.4 1541.52  5378.7 1542.52  5516.3 1542.65
#Mann= 3 ,-1 , 0
  4550.5     .05       0  4997.4     .03       0  5003.4     .05       0
Bank Sta=4997.4,5003.4
XS Rating Curve= 0 ,0
Exp/Cntr=0.3,0.1

Type RM Length L Ch R = 1 ,1031    ,731,731,731
BEGIN DESCRIPTION:
UNT014 IN NNOGR 2.0
END DESCRIPTION:
XS GIS Cut Line= 3
      2783840.63     10055200.47      2783778.13     10054398.41
      2783489.94     10054190.08
#Sta/Elev= 30
  4601.5 1551.13  4718.6 1551.85  4788.8 1551.78  4823.1 1551.16  4828.9 1550.66
    4849 1550.64  4879.1 1547.75  4889.1 1545.93  4947.7 1533.56  4952.7 1533.59
  4959.3 1531.68  4969.4 1530.02  4996.4 1527.17  4999.2 1526.67  5002.4 1527.17
  5039.6 1529.33  5077.2 1533.19  5082.3 1533.22  5119.8 1536.03    5180 1538.39
  5260.2  1540.3  5360.5 1540.96  5400.7 1540.53  5494.5 1541.15    5503 1540.83
    5530 1541.32    5566 1541.06  5574.1 1541.35  5674.7 1541.42  5761.6 1542.12
#Mann= 3 ,-1 , 0
  4601.5     .05       0  4996.4     .04       0  5002.4     .05       0
Bank Sta=4996.4,5002.4
XS Rating Curve= 0 ,0
Exp/Cntr=0.3,0.1

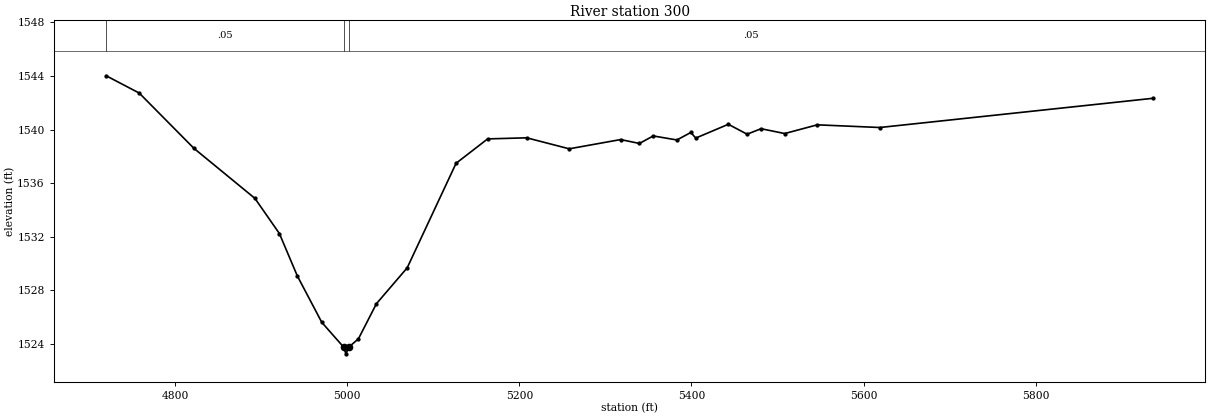
Type RM Length L Ch R = 1 ,300     ,0,0,0
BEGIN DESCRIPTION:
UNT014 IN NNOGR 1.0
END DESCRIPTION:
XS GIS Cut Line= 3
      2784710.96     10054815.37      2784404.19      10054537.2
      2783699.62     10054152.41
#Sta/Elev= 30
  4719.7 1544.02  4758.1 1542.73  4821.6 1538.61  4892.6 1534.87    4921 1532.25
  4941.9 1529.08  4970.3 1525.62  4995.7 1523.77  4998.4 1523.27  5001.7 1523.77
  5012.9 1524.39  5033.8 1527.01  5069.6 1529.69  5126.4 1537.49  5163.1 1539.31
  5208.5 1539.39  5257.9 1538.57  5317.7 1539.26  5339.5 1538.97  5355.6 1539.53
  5383.1 1539.23  5399.3 1539.79    5405 1539.37  5442.9  1540.4  5464.7 1539.66
  5480.9 1540.07  5508.4 1539.71  5546.3 1540.36  5618.9 1540.16  5936.6 1542.34
#Mann= 3 ,-1 , 0
  4719.7     .05       0  4995.7    .035       0  5001.7     .05       0
Bank Sta=4995.7,5001.7
XS Rating Curve= 0 ,0
Exp/Cntr=0.3,0.1

Chan Stop Cuts=-1
Use User Specified Reach Order=0
Composite Channel Slope=5