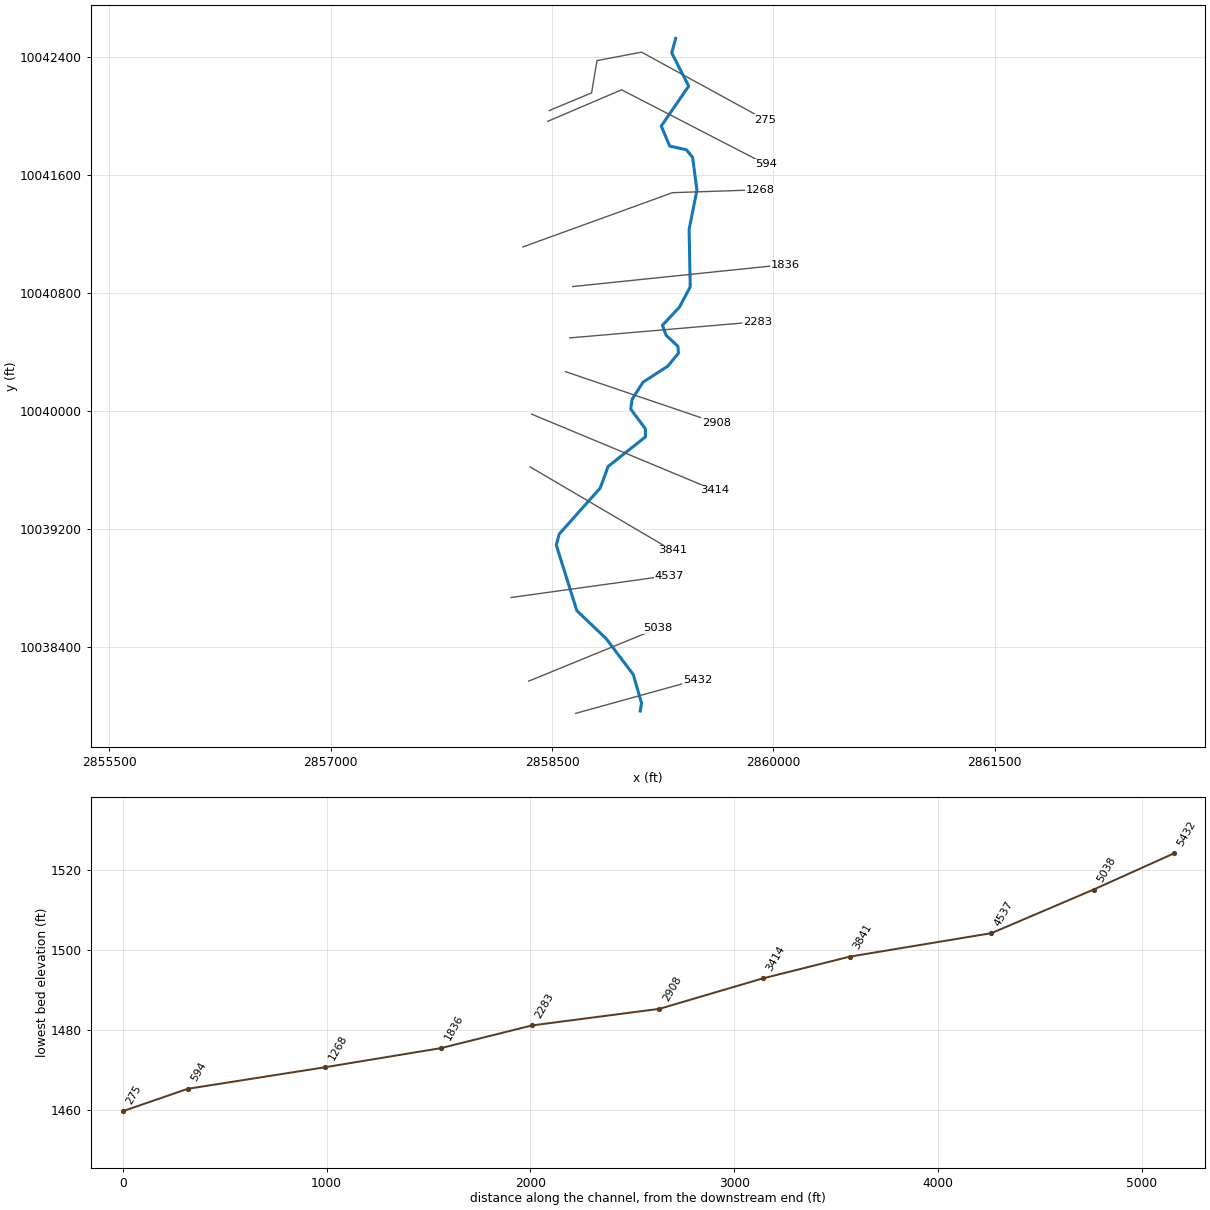
--- UNT015 IN SNOGR.prj (project) ---

Proj Title=UNT015 IN SNOGR Base Level Engineering
Current Plan=p01
Default Exp/Contr=0.3,0.1
English Units
Geom File=g01
Flow File=f01
Plan File=p01
BEGIN DESCRIPTION:
UNT015 IN SNOGR
END DESCRIPTION:

--- UNT015 IN SNOGR.p01 (plan) ---

Plan Title=Multiple Run
Short Identifier=Multiple
Geom File=g01
Flow File=f01
Subcritical Flow
K Sum by GR= 0
Std Step Tol= 0.01
Critical Tol= 0.01
Num of Std Step Trials= 20
Max Error Tol= 0.3
Flow Tol Ratio= 0.001
Split Flow NTrial= 30
Split Flow Tol= 0.02
Split Flow Ratio= 0.02
Log Output Level= 0
Friction Slope Method= 1
Unsteady Friction Slope Method= 2
Unsteady Bridges Friction Slope Method= 1
Parabolic Critical Depth
Global Vel Dist=  1 , 1 , 1
Global Log Level= 0
CheckData=True
Encroach Param= -1, 0, 0, 0
BEGIN DESCRIPTION:
Multiple Run
END DESCRIPTION:

--- UNT015 IN SNOGR.f01 (steady flow) ---

Flow Title=Multiple
Number of Profiles=7
Profile Names=10-year,25-year,50-year,1pct_min,100-year,1pct_plu,500-year
River Rch & RM= UNT015 IN SNOGR,Reach-1,5432
     950    1387    1770    1655    2238    3027    3590
River Rch & RM= UNT015 IN SNOGR,Reach-1,5038
    1256    1856    2387    2247    3038    4109    4940
Boundary for River Rch & Prof#=UNT015 IN SNOGR,Reach-1,1
Up Type=0
Dn Type=3
Dn Slope=0.005
Boundary for River Rch & Prof#=UNT015 IN SNOGR,Reach-1,2
Up Type=0
Dn Type=3
Dn Slope=0.005
Boundary for River Rch & Prof#=UNT015 IN SNOGR,Reach-1,3
Up Type=0
Dn Type=3
Dn Slope=0.005
Boundary for River Rch & Prof#=UNT015 IN SNOGR,Reach-1,4
Up Type=0
Dn Type=3
Dn Slope=0.005
Boundary for River Rch & Prof#=UNT015 IN SNOGR,Reach-1,5
Up Type=0
Dn Type=3
Dn Slope=0.005
Boundary for River Rch & Prof#=UNT015 IN SNOGR,Reach-1,6
Up Type=0
Dn Type=3
Dn Slope=0.005
Boundary for River Rch & Prof#=UNT015 IN SNOGR,Reach-1,7
Up Type=0
Dn Type=3
Dn Slope=0.005

--- UNT015 IN SNOGR.g01 (geometry) ---

Geom Title=Existing Conditions

River Reach=UNT015 IN SNOGR,Reach-1
Reach XY= 30
      2859098.47     10037963.73      2859106.76     10038017.99
      2859051.04     10038210.26      2858867.53     10038453.84
      2858668.47     10038643.73      2858528.98     10039088.50
      2858549.44     10039164.04      2858826.44     10039474.57
      2858880.85     10039622.23      2859133.26     10039821.60
      2859133.25     10039876.14      2859033.49     10040010.57
      2859042.86     10040076.47      2859116.47     10040192.22
      2859284.86     10040301.34      2859357.28     10040389.55
      2859353.17     10040436.33      2859273.23     10040511.28
      2859248.67     10040578.51      2859363.62     10040700.96
      2859436.98     10040839.37      2859429.42     10041228.51
      2859482.43     10041493.70      2859453.21     10041716.44
      2859411.09     10041768.26      2859298.16     10041793.31
      2859240.70     10041929.36      2859426.46     10042199.72
      2859311.57     10042424.90      2859338.47     10042523.73

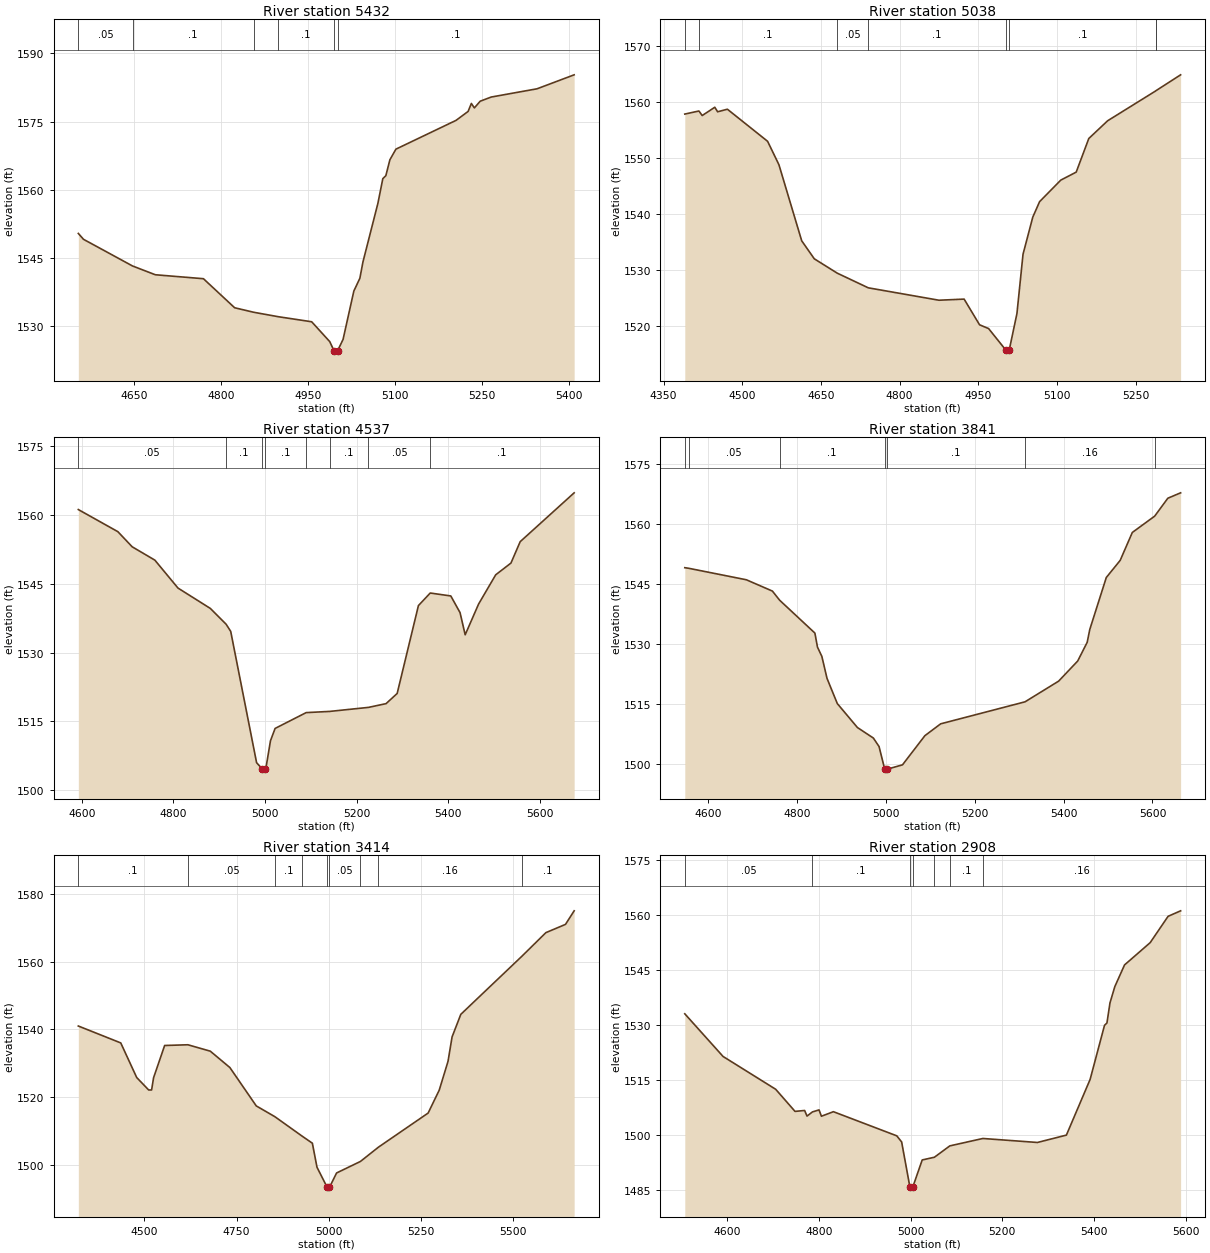
Type RM Length L Ch R = 1,5432,394,394,394
BEGIN DESCRIPTION:
UNT015 IN SNOGR 12.0
END DESCRIPTION:
XS GIS Cut Line= 2
      2858660.54     10037947.58      2859484.68     10038175.96
#Sta/Elev= 30
  4553.8 1550.41  4562.7 1549.12  4647.3 1543.26  4686.6 1541.33  4769.6 1540.46
  4823.4 1534.08  4856.6 1533.08  4898.3 1532.12  4956.3 1531.00  4987.5 1526.63
  4994.9 1524.61  4997.6 1524.11  5000.9 1524.61  5010.4 1527.12  5029.0 1537.75
  5039.4 1540.56  5044.7 1544.14  5070.5 1557.03  5079.0 1562.45  5084.2 1563.10
  5091.2 1566.60  5101.6 1568.93  5205.4 1575.26  5226.1 1577.22  5231.7 1578.97
  5236.9 1577.99  5246.9 1579.46  5266.0 1580.38  5345.0 1582.19  5409.0 1585.26
#Mann=6,-1,0
  4553.8    0.05       0  4647.3     0.1       0  4856.6    0.05       0
  4898.3     0.1       0  4994.9    0.07       0  5000.9     0.1       0
Bank Sta=4994.9,5000.9
Exp/Cntr=0.3,0.1

Type RM Length L Ch R = 1,5038,501,501,501
BEGIN DESCRIPTION:
UNT015 IN SNOGR 11.0
END DESCRIPTION:
XS GIS Cut Line= 2
      2858342.32     10038166.32      2859217.33     10038524.28
#Sta/Elev= 30
  4390.3 1557.81  4417.2 1558.36  4423.5 1557.55  4447.5 1559.03  4452.9 1558.22
  4471.5 1558.68  4548.2 1552.94  4569.8 1548.75  4613.2 1535.15  4637.2 1531.93
  4681.0 1529.36  4740.1 1526.74  4874.9 1524.52  4922.9 1524.72  4952.3 1520.13
  4969.6 1519.45  5002.8 1515.56  5005.5 1515.06  5008.8 1515.56  5023.6 1522.14
  5035.2 1532.74  5053.8 1539.38  5066.8 1542.15  5107.2 1546.00  5136.6 1547.43
  5160.6 1553.44  5196.5 1556.61  5288.0 1561.94  5289.3 1562.03  5335.7 1564.83
#Mann=8,-1,0
  4390.3    0.05       0  4417.2     0.1       0  4681.0    0.05       0
  4740.1     0.1       0  5002.8    0.07       0  5008.8     0.1       0
  5288.0    0.05       0  5289.3     0.1       0
Bank Sta=5002.8,5008.8
Exp/Cntr=0.3,0.1

Type RM Length L Ch R = 1,4537,696,696,696
BEGIN DESCRIPTION:
UNT015 IN SNOGR 10.0
END DESCRIPTION:
XS GIS Cut Line= 2
      2858222.98     10038733.10      2859295.19     10038882.02
#Sta/Elev= 30
  4592.6 1561.20  4678.9 1556.38  4710.2 1553.08  4759.7 1550.17  4810.2 1544.08
  4880.8 1539.64  4915.3 1536.19  4925.3 1534.63  4981.8 1506.00  4994.0 1504.66
  4996.7 1504.16  5000.0 1504.66  5002.0 1504.72  5012.1 1510.78  5022.2 1513.47
  5090.0 1516.92  5141.3 1517.18  5226.0 1518.06  5264.5 1518.88  5288.7 1521.10
  5335.1 1540.26  5360.9 1543.00  5405.8 1542.36  5426.0 1538.72  5437.2 1533.89
  5466.4 1540.58  5503.8 1546.97  5537.1 1549.53  5557.3 1554.20  5675.1 1564.85
#Mann=8,-1,0
  4592.6    0.05       0  4915.3     0.1       0  4994.0    0.07       0
  5000.0     0.1       0  5090.0    0.05       0  5141.3     0.1       0
  5226.0    0.05       0  5360.9     0.1       0
Bank Sta=4994,5000
Exp/Cntr=0.3,0.1

Type RM Length L Ch R = 1,3841,427,427,427
BEGIN DESCRIPTION:
UNT015 IN SNOGR 8.0
END DESCRIPTION:
XS GIS Cut Line= 2
      2858352.31     10039618.05      2859315.08     10039052.29
#Sta/Elev= 30
  4546.7 1549.08  4555.7 1548.93  4685.4 1546.06  4744.0 1543.24  4760.3 1540.96
  4839.7 1532.75  4845.5 1529.25  4855.4 1526.92  4867.0 1521.44  4890.2 1515.14
  4935.5 1509.16  4971.4 1506.53  4984.2 1504.41  4996.9 1498.77  4999.6 1498.27
  5002.9 1498.77  5037.0 1499.84  5087.4 1507.12  5122.9 1510.08  5313.0 1515.58
  5388.6 1520.74  5431.6 1525.77  5453.0 1530.45  5458.8 1533.65  5496.0 1546.63
  5527.3 1550.91  5554.6 1557.88  5605.0 1561.96  5634.6 1566.43  5663.4 1567.78
#Mann=7,-1,0
  4546.7     0.1       0  4555.7    0.05       0  4760.3     0.1       0
  4996.9    0.07       0  5002.9     0.1       0  5313.0    0.16       0
  5605.0     0.1       0
Bank Sta=4996.9,5002.9
Exp/Cntr=0.3,0.1

Type RM Length L Ch R = 1,3414,506,506,506
BEGIN DESCRIPTION:
UNT015 IN SNOGR 7.0
END DESCRIPTION:
XS GIS Cut Line= 2
      2858362.19     10039976.03      2859604.30     10039459.32
#Sta/Elev= 30
  4320.7 1540.98  4435.8 1535.99  4479.1 1525.77  4511.6 1522.09  4519.5 1522.10
  4524.9 1525.72  4554.9 1535.23  4618.0 1535.44  4678.8 1533.55  4731.9 1528.72
  4803.5 1517.39  4853.8 1514.22  4928.8 1508.40  4955.7 1506.38  4968.2 1499.30
  4996.0 1493.32  4998.8 1492.82  5002.0 1493.32  5021.4 1497.59  5086.1 1500.99
  5135.0 1505.21  5269.8 1515.28  5299.9 1522.04  5323.8 1530.57  5334.8 1537.78
  5358.5 1544.43  5524.5 1561.61  5589.3 1568.55  5642.5 1570.99  5666.0 1574.99
#Mann=9,-1,0
  4320.7     0.1       0  4618.0    0.05       0  4853.8     0.1       0
  4928.8    0.05       0  4996.0   0.035       0  5002.0    0.05       0
  5086.1     0.1       0  5135.0    0.16       0  5524.5     0.1       0
Bank Sta=4996,5002
Exp/Cntr=0.3,0.1

Type RM Length L Ch R = 1,2908,625,625,625
BEGIN DESCRIPTION:
UNT015 IN SNOGR 6.0
END DESCRIPTION:
XS GIS Cut Line= 2
      2858590.94     10040264.37      2859614.27     10039916.64
#Sta/Elev= 30
  4508.0 1533.06  4591.4 1521.42  4706.1 1512.47  4748.3 1506.43  4769.2 1506.68
  4774.4 1505.15  4786.3 1506.29  4800.6 1506.84  4805.8 1505.11  4831.9 1506.35
  4970.1 1499.76  4980.7 1498.09  4998.8 1485.72  5001.5 1485.22  5004.8 1485.72
  5025.5 1493.18  5052.1 1493.92  5085.7 1497.02  5157.8 1499.04  5276.6 1497.95
  5339.8 1499.96  5391.5 1515.15  5422.9 1529.92  5428.2 1530.56  5434.8 1536.03
  5445.4 1540.49  5466.5 1546.39  5522.4 1552.47  5561.5 1559.66  5588.8 1561.16
#Mann=7,-1,0
  4508.0    0.05       0  4786.3     0.1       0  4998.8    0.07       0
  5004.8     0.1       0  5052.1    0.05       0  5085.7     0.1       0
  5157.8    0.16       0
Bank Sta=4998.8,5004.8
Exp/Cntr=0.3,0.1

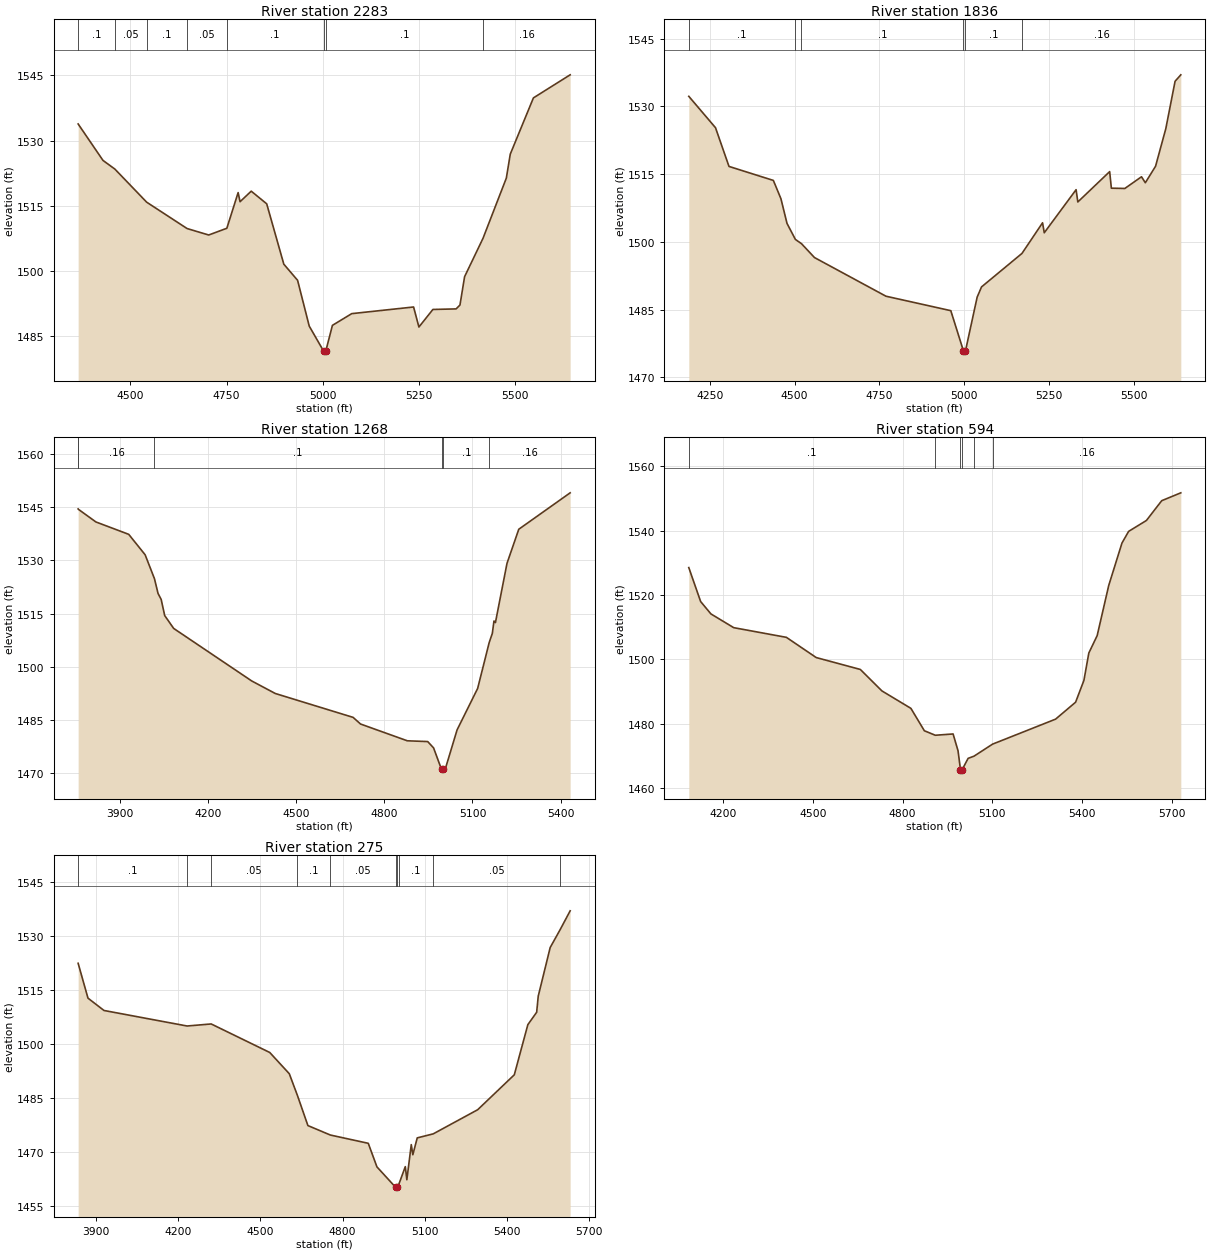
Type RM Length L Ch R = 1,2283,447,447,447
BEGIN DESCRIPTION:
UNT015 IN SNOGR 5.0
END DESCRIPTION:
XS GIS Cut Line= 2
      2858620.71     10040493.08      2859893.52     10040602.46
#Sta/Elev= 30
  4364.6 1533.82  4429.1 1525.43  4459.9 1523.44  4542.6 1515.81  4647.4 1509.75
  4703.6 1508.26  4750.7 1509.81  4780.0 1518.02  4785.0 1515.92  4814.0 1518.35
  4854.2 1515.44  4898.6 1501.55  4934.4 1497.83  4964.6 1487.30  5001.7 1481.57
  5004.5 1481.07  5007.7 1481.57  5024.8 1487.46  5075.0 1490.16  5235.6 1491.69
  5249.4 1487.08  5285.7 1491.12  5346.0 1491.25  5356.0 1492.14  5368.0 1498.66
  5415.9 1507.51  5476.4 1521.36  5486.6 1526.87  5546.7 1539.82  5642.1 1545.13
#Mann=8,-1,0
  4364.6     0.1       0  4459.9    0.05       0  4542.6     0.1       0
  4647.4    0.05       0  4750.7     0.1       0  5001.7    0.07       0
  5007.7     0.1       0  5415.9    0.16       0
Bank Sta=5001.7,5007.7
Exp/Cntr=0.3,0.1

Type RM Length L Ch R = 1,1836,568,568,568
BEGIN DESCRIPTION:
UNT015 IN SNOGR 4.0
END DESCRIPTION:
XS GIS Cut Line= 2
      2858640.65     10040841.10      2860082.46     10040990.25
#Sta/Elev= 30
  4188.2 1532.25  4266.9 1525.30  4306.6 1516.73  4437.3 1513.63  4459.6 1509.59
  4477.6 1504.10  4502.3 1500.56  4520.1 1499.63  4558.5 1496.55  4769.1 1487.99
  4960.1 1484.79  4997.3 1475.89  5000.1 1475.39  5003.3 1475.89  5037.7 1487.78
  5050.6 1490.05  5169.8 1497.47  5230.4 1504.25  5235.4 1502.04  5329.2 1511.58
  5334.3 1508.86  5428.1 1515.58  5433.1 1511.91  5472.8 1511.85  5521.9 1514.44
  5533.2 1513.11  5563.3 1516.77  5593.5 1525.09  5620.8 1535.58  5637.7 1537.01
#Mann=6,-1,0
  4188.2     0.1       0  4502.3    0.05       0  4520.1     0.1       0
  4997.3    0.07       0  5003.3     0.1       0  5169.8    0.16       0
Bank Sta=4997.3,5003.3
Exp/Cntr=0.3,0.1

Type RM Length L Ch R = 1,1268,674,674,674
BEGIN DESCRIPTION:
UNT015 IN SNOGR 3.0
END DESCRIPTION:
XS GIS Cut Line= 3
      2858302.59     10041109.58      2859316.78     10041477.47
      2859913.40     10041497.36
#Sta/Elev= 30
  3756.9 1544.51  3757.7 1544.41  3817.4 1540.84  3929.2 1537.35  3985.1 1531.59
  4016.8 1524.86  4029.1 1520.68  4039.7 1519.01  4051.7 1514.46  4082.3 1510.83
  4348.2 1496.02  4428.4 1492.49  4693.4 1485.76  4718.7 1483.89  4878.0 1479.16
  4947.5 1478.94  4967.5 1477.16  4994.5 1471.11  4997.3 1470.61  5000.5 1471.11
  5007.5 1471.25  5047.6 1482.24  5117.6 1493.91  5157.1 1506.90  5167.6 1509.42
  5173.2 1512.92  5178.2 1512.49  5217.6 1529.18  5257.7 1538.78  5432.7 1549.05
#Mann=6,-1,0
  3756.9     0.1       0  3757.7    0.16       0  4016.8     0.1       0
  4994.5    0.07       0  5000.5     0.1       0  5157.1    0.16       0
Bank Sta=4994.5,5000.5
Exp/Cntr=0.3,0.1

Type RM Length L Ch R = 1,594,319,319,319
BEGIN DESCRIPTION:
UNT015 IN SNOGR 2.0
END DESCRIPTION:
XS GIS Cut Line= 3
      2858471.49     10041961.31      2858971.51     10042174.86
      2859950.65     10041669.67
#Sta/Elev= 30
  4085.2 1528.53  4124.8 1517.97  4159.2 1514.12  4235.5 1509.84  4411.6 1506.83
  4511.4 1500.54  4658.9 1496.84  4731.0 1490.17  4828.0 1484.74  4873.0 1477.77
  4909.6 1476.37  4969.1 1476.77  4985.6 1471.56  4993.8 1465.71  4996.6 1465.21
  4999.8 1465.71  5019.3 1469.18  5039.0 1469.86  5101.2 1473.61  5311.9 1481.38
  5378.8 1486.65  5406.6 1493.42  5423.1 1501.96  5450.9 1507.35  5489.6 1522.96
  5533.9 1536.16  5556.1 1539.79  5615.7 1543.19  5666.8 1549.34  5730.7 1551.79
#Mann=6,-1,0
  4085.2     0.1       0  4909.6    0.05       0  4993.8   0.035       0
  4999.8    0.05       0  5039.0     0.1       0  5101.2    0.16       0
Bank Sta=4993.8,4999.8
Exp/Cntr=0.3,0.1

Type RM Length L Ch R = 1,275,0,0,0
BEGIN DESCRIPTION:
UNT015 IN SNOGR 1.0
END DESCRIPTION:
XS GIS Cut Line= 5
      2858481.95     10042034.25      2858768.38     10042154.03
      2858804.84     10042372.78      2859106.93     10042430.07
      2859944.47     10041972.28
#Sta/Elev= 30
  3835.7 1522.44  3871.6 1512.74  3930.0 1509.31  4233.0 1504.99  4320.9 1505.56
  4534.5 1497.62  4605.7 1491.71  4635.2 1485.70  4673.6 1477.28  4755.6 1474.65
  4893.7 1472.35  4925.3 1465.79  4993.5 1460.10  4996.2 1459.60  4999.5 1460.10
  5005.7 1461.05  5028.7 1465.86  5034.4 1462.21  5050.5 1471.98  5056.2 1469.17
  5072.3 1473.86  5130.7 1474.98  5292.6 1481.69  5426.2 1491.41  5475.6 1505.36
  5507.8 1508.82  5513.5 1513.30  5557.1 1526.83  5593.3 1531.79  5629.9 1537.04
#Mann=10,-1,0
  3835.7     0.1       0  4233.0    0.16       0  4320.9    0.05       0
  4635.2     0.1       0  4755.6    0.05       0  4993.5   0.035       0
  4999.5    0.05       0  5005.7     0.1       0  5130.7    0.05       0
  5593.3     0.1       0
Bank Sta=4993.5,4999.5
Exp/Cntr=0.3,0.1

Chan Stop Cuts=-1