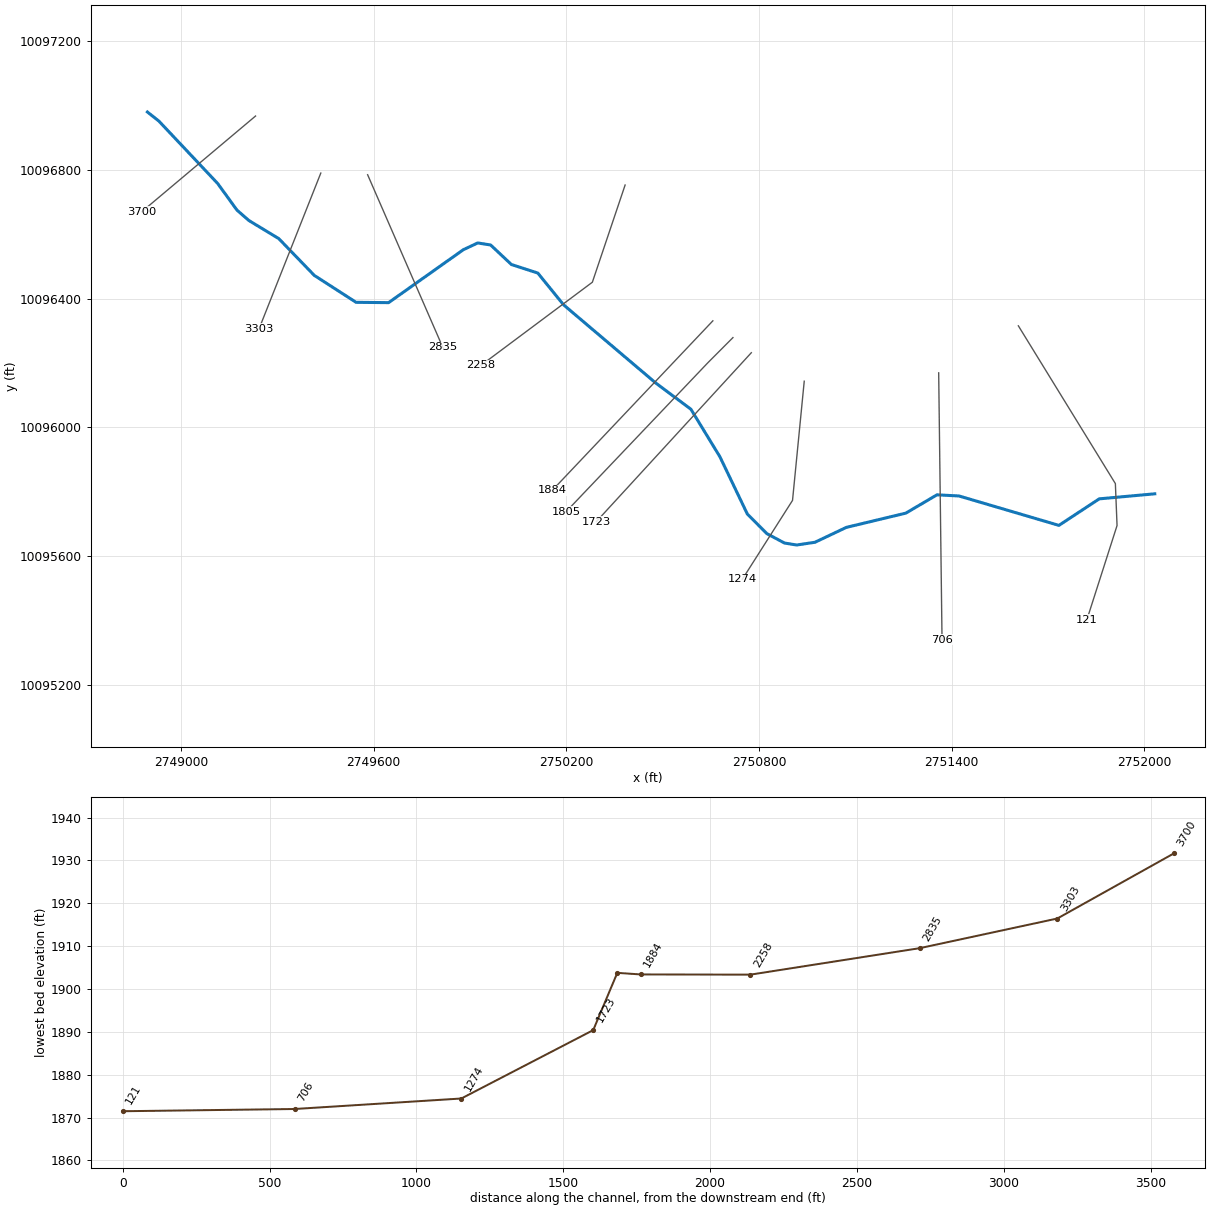
--- UNT016 IN NNOGR.prj (project) ---

Proj Title=UNT016 IN NNOGR Base Level Engineering
Current Plan=p01
Default Exp/Contr=0.3,0.1
English Units
Geom File=g01
Flow File=f01
Plan File=p01
BEGIN DESCRIPTION:
UNT016 IN NNOGR
END DESCRIPTION:

--- UNT016 IN NNOGR.p01 (plan) ---

Plan Title=Multiple Run
Short Identifier=Multiple
Geom File=g01
Flow File=f01
Subcritical Flow
K Sum by GR= 0
Std Step Tol= 0.01
Critical Tol= 0.01
Num of Std Step Trials= 20
Max Error Tol= 0.3
Flow Tol Ratio= 0.001
Split Flow NTrial= 30
Split Flow Tol= 0.02
Split Flow Ratio= 0.02
Log Output Level= 0
Friction Slope Method= 1
Unsteady Friction Slope Method= 2
Unsteady Bridges Friction Slope Method= 1
Parabolic Critical Depth
Global Vel Dist=  1 , 1 , 1
Global Log Level= 0
CheckData=True
Encroach Param= -1, 0, 0, 0
BEGIN DESCRIPTION:
Multiple Run
END DESCRIPTION:

--- UNT016 IN NNOGR.f01 (steady flow) ---

Flow Title=Multiple
Number of Profiles=7
Profile Names=10-year,25-year,50-year,1pct_min,100-year,1pct_plu,500-year
River Rch & RM= UNT016 IN NNOGR,Reach-1,3700
     739    1068    1353    1257    1700    2299    2690
Boundary for River Rch & Prof#=UNT016 IN NNOGR,Reach-1,1
Up Type=0
Dn Type=3
Dn Slope=0.005
Boundary for River Rch & Prof#=UNT016 IN NNOGR,Reach-1,2
Up Type=0
Dn Type=3
Dn Slope=0.005
Boundary for River Rch & Prof#=UNT016 IN NNOGR,Reach-1,3
Up Type=0
Dn Type=3
Dn Slope=0.005
Boundary for River Rch & Prof#=UNT016 IN NNOGR,Reach-1,4
Up Type=0
Dn Type=3
Dn Slope=0.005
Boundary for River Rch & Prof#=UNT016 IN NNOGR,Reach-1,5
Up Type=0
Dn Type=3
Dn Slope=0.005
Boundary for River Rch & Prof#=UNT016 IN NNOGR,Reach-1,6
Up Type=0
Dn Type=3
Dn Slope=0.005
Boundary for River Rch & Prof#=UNT016 IN NNOGR,Reach-1,7
Up Type=0
Dn Type=3
Dn Slope=0.005

--- UNT016 IN NNOGR.g01 (geometry) ---

Geom Title=Existing Conditions

River Reach=UNT016 IN NNOGR,Reach-1
Reach XY= 30
      2748895.91     10096978.84      2748931.86     10096950.45
      2749114.76     10096756.93      2749174.93     10096674.19
      2749212.30     10096641.87      2749305.01     10096585.87
      2749415.56     10096471.79      2749545.67     10096388.23
      2749646.96     10096387.27      2749879.50     10096551.43
      2749924.40     10096572.48      2749964.57     10096566.14
      2750029.48     10096505.47      2750111.47     10096479.06
      2750191.71     10096380.46      2750478.78     10096137.76
      2750588.16     10096056.51      2750678.44     10095909.05
      2750763.95     10095731.17      2750824.62     10095670.57
      2750879.30     10095641.41      2750917.32     10095635.16
      2750974.50     10095643.68      2751072.01     10095689.84
      2751257.43     10095734.11      2751354.30     10095790.89
      2751422.95     10095787.33      2751733.99     10095696.09
      2751859.51     10095778.39      2752032.43     10095794.01

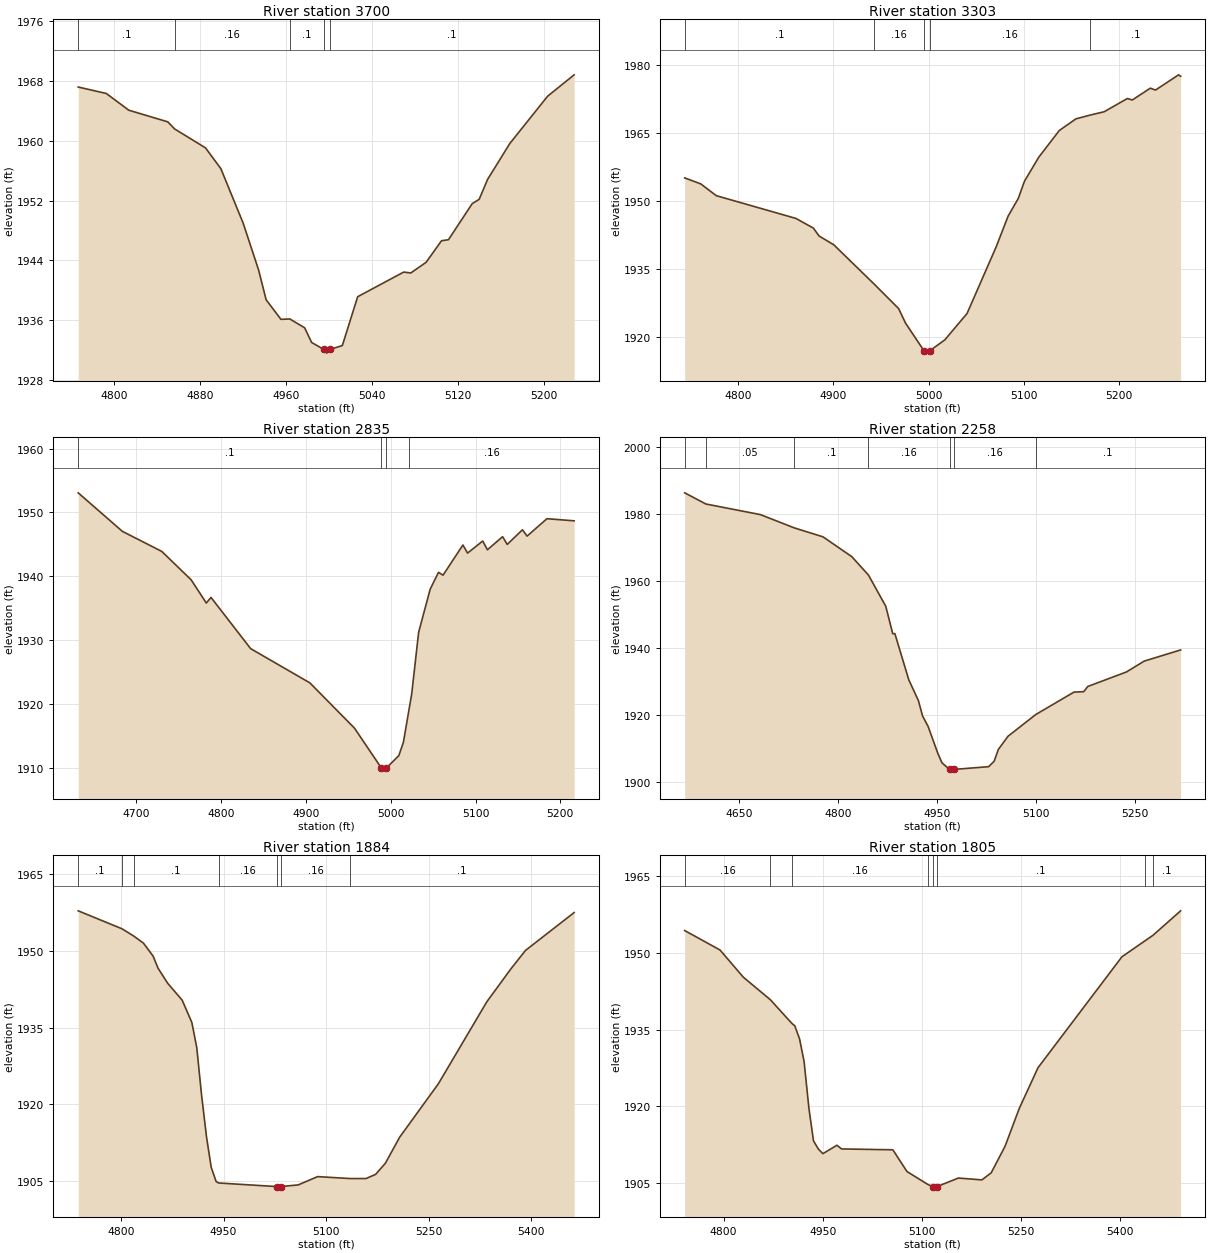
Type RM Length L Ch R = 1,3700,397,397,397
BEGIN DESCRIPTION:
UNT016 IN NNOGR 8.0
END DESCRIPTION:
XS GIS Cut Line= 2
      2749232.67     10096966.35      2748878.53     10096669.50
#Sta/Elev= 30
  4766.2 1967.15  4792.4 1966.29  4813.3 1964.06  4849.7 1962.50  4856.0 1961.56
  4884.8 1959.03  4899.1 1956.26  4919.9 1948.98  4934.3 1942.72  4941.3 1938.75
  4955.1 1936.14  4963.4 1936.19  4977.2 1935.01  4983.7 1933.05  4995.0 1932.13
  4997.8 1931.63  5001.0 1932.13  5012.3 1932.64  5026.6 1939.16  5069.5 1942.45
  5076.1 1942.33  5090.4 1943.76  5104.7 1946.63  5111.2 1946.77  5133.3 1951.58
  5139.8 1952.16  5147.6 1954.81  5168.4 1959.62  5203.6 1965.93  5228.3 1968.78
#Mann=5,-1,0
  4766.2     0.1       0  4856.0    0.16       0  4963.4     0.1       0
  4995.0    0.07       0  5001.0     0.1       0
Bank Sta=4995,5001
Exp/Cntr=0.3,0.1

Type RM Length L Ch R = 1,3303,468,468,468
BEGIN DESCRIPTION:
UNT016 IN NNOGR 7.0
END DESCRIPTION:
XS GIS Cut Line= 2
      2749435.83     10096789.33      2749243.27     10096305.33
#Sta/Elev= 30
  4743.8 1955.07  4760.6 1953.76  4777.0 1951.15  4860.6 1946.14  4879.0 1944.00
  4884.9 1942.27  4900.5 1940.31  4943.1 1931.60  4968.5 1926.27  4975.8 1923.05
  4995.2 1916.94  4998.0 1916.44  5001.2 1916.94  5017.1 1919.38  5040.4 1925.18
  5071.1 1939.93  5083.5 1946.64  5094.2 1950.54  5100.7 1954.34  5115.7 1959.63
  5137.3 1965.52  5154.7 1968.08  5169.4 1968.90  5184.4 1969.65  5208.7 1972.56
  5214.0 1972.25  5232.9 1974.85  5238.3 1974.43  5262.6 1977.79  5264.7 1977.48
#Mann=5,-1,0
  4743.8     0.1       0  4943.1    0.16       0  4995.2    0.07       0
  5001.2    0.16       0  5169.4     0.1       0
Bank Sta=4995.2,5001.2
Exp/Cntr=0.3,0.1

Type RM Length L Ch R = 1,2835,577,577,577
BEGIN DESCRIPTION:
UNT016 IN NNOGR 6.0
END DESCRIPTION:
XS GIS Cut Line= 2
      2749581.63     10096784.12      2749815.80     10096248.14
#Sta/Elev= 30
  4631.4 1953.07  4683.4 1947.05  4730.0 1943.90  4764.6 1939.46  4782.5 1935.83
  4788.0 1936.71  4834.8 1928.69  4904.6 1923.34  4957.2 1916.26  4988.9 1910.03
  4991.7 1909.53  4994.9 1910.03  5009.5 1911.95  5014.9 1914.03  5021.4 1919.04
  5024.7 1921.59  5032.9 1931.25  5046.5 1937.99  5056.3 1940.63  5061.7 1940.19
  5085.1 1944.91  5090.6 1943.64  5108.5 1945.53  5114.0 1944.16  5131.9 1946.21
  5137.4 1945.00  5155.3 1947.29  5160.8 1946.30  5184.2 1949.02  5216.3 1948.69
#Mann=4,-1,0
  4631.4     0.1       0  4988.9    0.07       0  4994.9     0.1       0
  5021.4    0.16       0
Bank Sta=4988.9,4994.9
Exp/Cntr=0.3,0.1

Type RM Length L Ch R = 1,2258,374,374,374
BEGIN DESCRIPTION:
UNT016 IN NNOGR 5.0
END DESCRIPTION:
XS GIS Cut Line= 3
      2750383.32     10096752.26      2750281.32     10096450.60
      2749934.07     10096192.33
#Sta/Elev= 30
  4567.8 1986.46  4600.0 1983.12  4682.4 1979.96  4734.0 1975.98  4777.4 1973.31
  4821.0 1967.39  4846.2 1961.90  4872.4 1952.58  4882.9 1944.41  4886.2 1944.41
  4907.3 1930.61  4921.9 1924.38  4928.1 1919.84  4936.5 1916.71  4951.1 1908.74
  4957.4 1905.86  4969.0 1903.85  4971.7 1903.35  4975.0 1903.85  5028.3 1904.68
  5036.6 1906.33  5042.9 1909.82  5057.5 1913.75  5099.5 1920.24  5157.6 1926.96
  5172.2 1927.07  5178.4 1928.63  5236.9 1932.96  5264.0 1936.22  5319.0 1939.54
#Mann=7,-1,0
  4567.8     0.1       0  4600.0    0.05       0  4734.0     0.1       0
  4846.2    0.16       0  4969.0    0.07       0  4975.0    0.16       0
  5099.5     0.1       0
Bank Sta=4969,4975
Exp/Cntr=0.3,0.1

Type RM Length L Ch R = 1,1884,79,79,79
BEGIN DESCRIPTION:
Mapping XS 62bfcd02
END DESCRIPTION:
XS GIS Cut Line= 2
      2750656.51     10096330.84      2750156.54     10095804.84
#Sta/Elev= 30
  4737.4 1957.88  4801.4 1954.37  4818.6 1952.95  4832.9 1951.55  4847.0 1949.01
  4854.3 1946.63  4868.5 1943.67  4889.5 1940.40  4903.7 1936.02  4910.9 1931.10
  4917.8 1921.94  4925.1 1913.66  4932.0 1907.68  4939.2 1904.90  4942.9 1904.60
  5028.1 1903.90  5030.8 1903.40  5034.1 1903.90  5059.4 1904.23  5087.7 1905.85
  5135.3 1905.47  5158.5 1905.47  5172.6 1906.29  5186.8 1908.45  5207.8 1913.57
  5264.5 1924.04  5335.2 1940.05  5370.5 1946.51  5391.9 1950.13  5463.1 1957.54
#Mann=7,-1,0
  4737.4     0.1       0  4801.4    0.16       0  4818.6     0.1       0
  4942.9    0.16       0  5028.1    0.07       0  5034.1    0.16       0
  5135.3     0.1       0
Bank Sta=5028.1,5034.1
Exp/Cntr=0.3,0.1

Type RM Length L Ch R = 1,1805,82,82,82
BEGIN DESCRIPTION:
UNT016 IN NNOGR 4.0
END DESCRIPTION:
XS GIS Cut Line= 3
      2750719.04     10096278.79      2750640.89     10096200.65
      2750198.95     10095737.90
#Sta/Elev= 30
  4741.2 1954.40  4794.7 1950.59  4830.0 1945.26  4870.9 1940.85  4903.3 1936.23
  4907.8 1935.75  4915.0 1933.21  4921.9 1928.74  4929.2 1919.59  4936.1 1913.24
  4943.3 1911.65  4950.3 1910.71  4971.6 1912.36  4978.6 1911.64  5056.2 1911.47
  5077.6 1907.21  5109.7 1904.64  5117.1 1904.27  5119.8 1903.77  5123.1 1904.27
  5155.3 1905.94  5190.9 1905.58  5205.0 1906.96  5226.1 1912.20  5247.5 1919.58
  5275.8 1927.54  5402.8 1949.26  5438.3 1952.44  5449.9 1953.48  5491.6 1958.26
#Mann=8,-1,0
  4741.2    0.16       0  4870.9     0.1       0  4903.3    0.16       0
  5109.7     0.1       0  5117.1    0.07       0  5123.1     0.1       0
  5438.3    0.16       0  5449.9     0.1       0
Bank Sta=5117.1,5123.1
Exp/Cntr=0.3,0.1

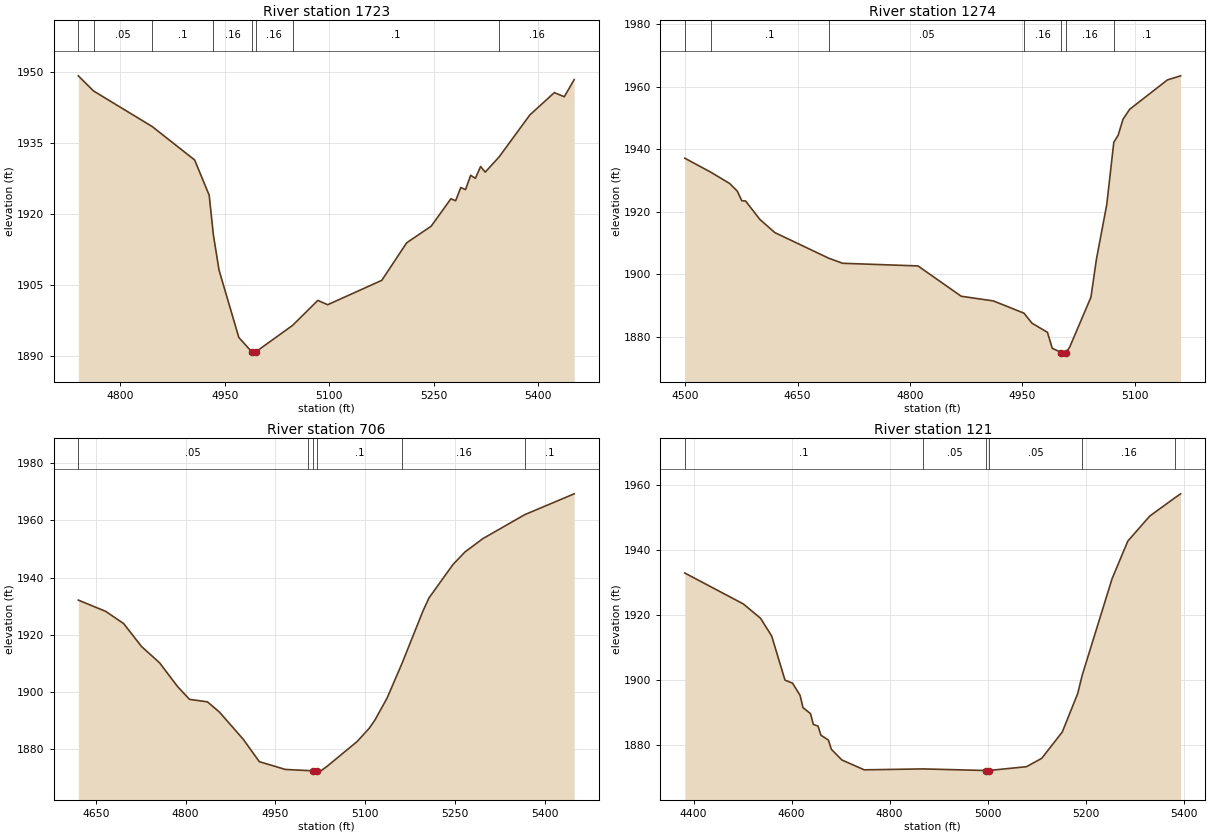
Type RM Length L Ch R = 1,1723,449,449,449
BEGIN DESCRIPTION:
Mapping XS 07826390
END DESCRIPTION:
XS GIS Cut Line= 2
      2750776.28     10096231.87      2750293.99     10095708.09
#Sta/Elev= 30
  4739.9 1949.16  4761.7 1945.97  4846.0 1938.45  4906.9 1931.40  4927.8 1923.96
  4933.9 1915.49  4942.0 1908.12  4970.4 1893.92  4988.9 1890.91  4991.7 1890.41
  4994.9 1890.91  5047.7 1896.49  5083.8 1901.75  5098.0 1900.84  5175.7 1905.99
  5211.4 1913.91  5246.6 1917.42  5274.9 1923.21  5281.7 1922.79  5289.1 1925.58
  5295.9 1925.14  5303.3 1928.16  5310.1 1927.52  5317.5 1930.02  5324.2 1928.83
  5344.2 1932.05  5388.3 1940.91  5423.5 1945.62  5437.7 1944.74  5451.9 1948.35
#Mann=8,-1,0
  4739.9    0.16       0  4761.7    0.05       0  4846.0     0.1       0
  4933.9    0.16       0  4988.9    0.07       0  4994.9    0.16       0
  5047.7     0.1       0  5344.2    0.16       0
Bank Sta=4988.9,4994.9
Exp/Cntr=0.3,0.1

Type RM Length L Ch R = 1,1274,568,568,568
BEGIN DESCRIPTION:
UNT016 IN NNOGR 3.0
END DESCRIPTION:
XS GIS Cut Line= 3
      2750941.03     10096143.49      2750904.57     10095773.66
      2750748.33     10095528.90
#Sta/Elev= 30
  4499.4 1937.10  4534.1 1932.63  4559.4 1928.99  4569.5 1926.57  4575.5 1923.48
  4580.5 1923.43  4599.6 1917.53  4619.7 1913.30  4691.7 1905.11  4710.2 1903.50
  4810.7 1902.66  4868.5 1892.96  4911.4 1891.47  4952.3 1887.55  4963.0 1884.34
  4983.6 1881.43  4990.0 1876.33  5002.3 1874.96  5005.0 1874.46  5008.3 1874.96
  5013.3 1876.71  5041.7 1892.69  5048.9 1904.68  5062.8 1922.30  5072.2 1942.21
  5078.0 1944.42  5084.5 1949.57  5093.3 1952.71  5143.8 1962.13  5161.4 1963.43
#Mann=7,-1,0
  4499.4    0.05       0  4534.1     0.1       0  4691.7    0.05       0
  4952.3    0.16       0  5002.3    0.07       0  5008.3    0.16       0
  5072.2     0.1       0
Bank Sta=5002.3,5008.3
Exp/Cntr=0.3,0.1

Type RM Length L Ch R = 1,706,585,585,585
BEGIN DESCRIPTION:
UNT016 IN NNOGR 2.0
END DESCRIPTION:
XS GIS Cut Line= 2
      2751359.64     10096169.43      2751370.06     10095341.30
#Sta/Elev= 30
  4620.9 1932.15  4666.6 1928.21  4696.6 1923.94  4726.6 1915.90  4756.6 1910.24
  4786.6 1901.94  4806.6 1897.45  4836.6 1896.58  4856.6 1893.00  4896.6 1883.44
  4923.2 1875.67  4966.6 1872.95  5004.5 1872.55  5013.6 1872.51  5016.4 1872.01
  5019.6 1872.51  5026.6 1872.54  5036.6 1874.07  5086.6 1882.71  5106.6 1887.29
  5116.6 1890.31  5136.6 1897.89  5161.6 1910.04  5196.6 1928.35  5206.6 1932.90
  5246.6 1944.56  5266.7 1948.97  5296.7 1953.65  5366.8 1962.04  5449.1 1969.30
#Mann=6,-1,0
  4620.9    0.05       0  5004.5     0.1       0  5013.6   0.035       0
  5019.6     0.1       0  5161.6    0.16       0  5366.8     0.1       0
Bank Sta=5013.6,5019.6
Exp/Cntr=0.3,0.1

Type RM Length L Ch R = 1,121,0,0,0
BEGIN DESCRIPTION:
UNT016 IN NNOGR 1.0
END DESCRIPTION:
XS GIS Cut Line= 4
      2751607.68     10096315.35      2751909.78     10095825.75
      2751914.98     10095695.54      2751821.23     10095403.85
#Sta/Elev= 30
  4382.0 1932.95  4501.4 1923.41  4536.7 1918.96  4559.3 1913.52  4586.5 1899.89
  4601.9 1898.94  4617.3 1895.20  4623.2 1891.41  4638.6 1889.53  4644.4 1886.21
  4654.0 1885.70  4659.8 1882.89  4675.2 1881.38  4681.1 1878.56  4702.4 1875.26
  4748.2 1872.20  4868.3 1872.48  4996.3 1871.99  4999.1 1871.49  5002.3 1871.99
  5079.4 1873.17  5110.5 1875.75  5152.5 1883.88  5184.0 1895.76  5193.0 1901.33
  5254.1 1931.19  5286.2 1942.80  5331.1 1950.54  5382.1 1956.14  5394.0 1957.39
#Mann=6,-1,0
  4382.0     0.1       0  4868.3    0.05       0  4996.3   0.033       0
  5002.3    0.05       0  5193.0    0.16       0  5382.1     0.1       0
Bank Sta=4996.3,5002.3
Exp/Cntr=0.3,0.1

Chan Stop Cuts=-1