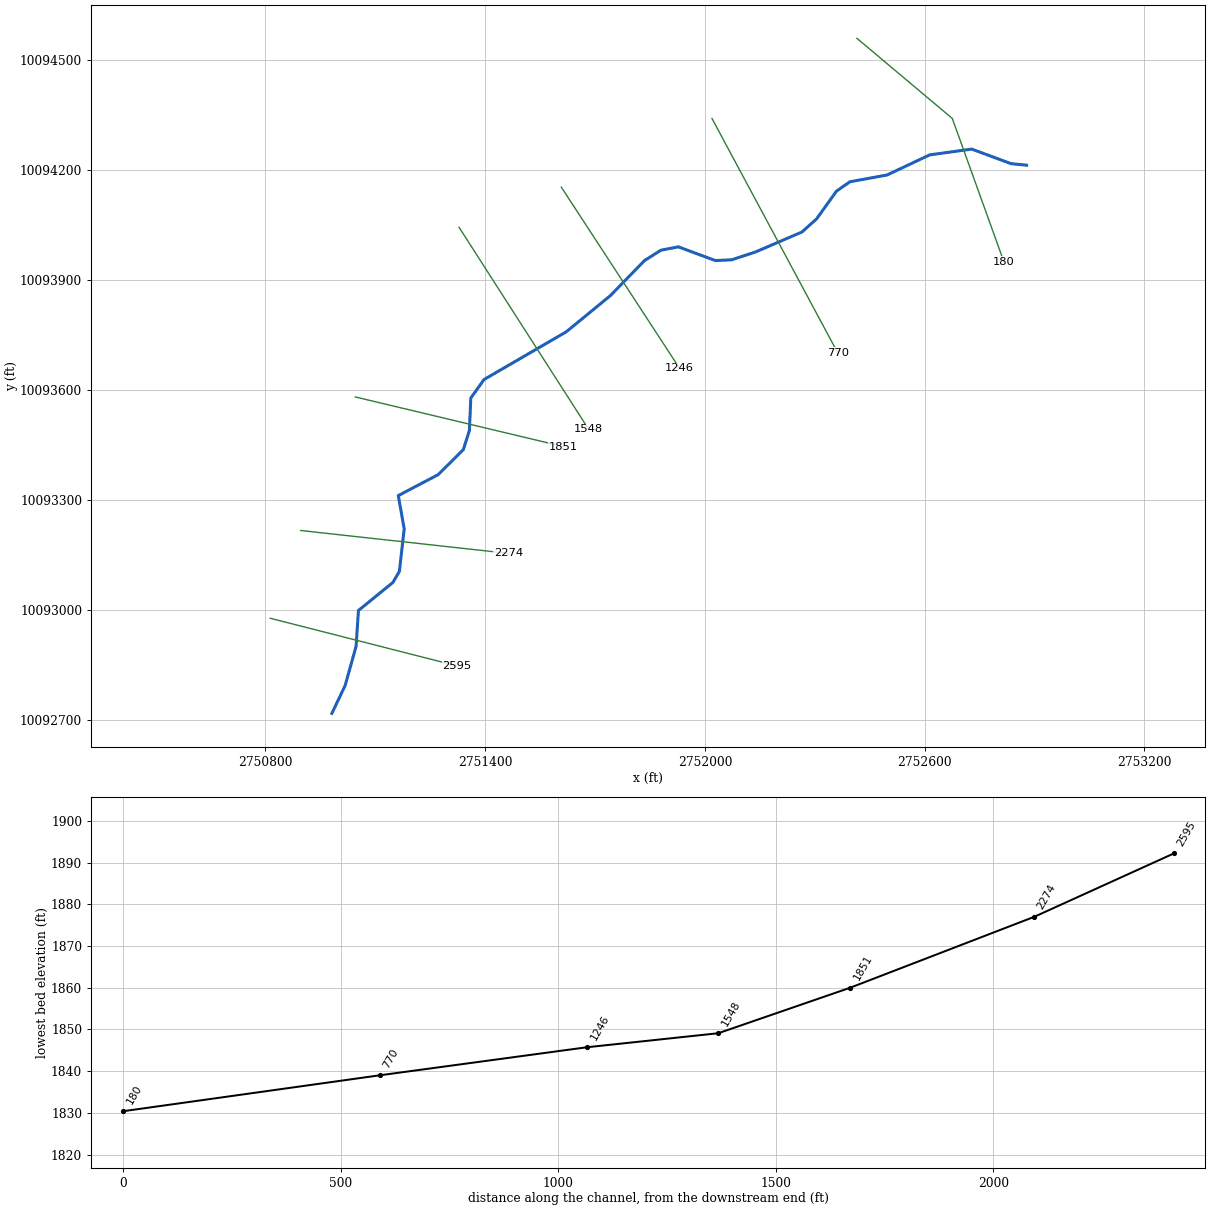
--- UNT017 IN NNOGR.prj (project) ---

Proj Title=UNT017 IN NNOGR Base Level Engineering
Current Plan=p01
Default Exp/Contr=0.3,0.1
English Units
Geom File=g01
Flow File=f01
Plan File=p01
Y Axis Title=Elevation
X Axis Title(PF)=Main Channel Distance
X Axis Title(XS)=Station
BEGIN DESCRIPTION:
UNT017 IN NNOGR
END DESCRIPTION:
DSS Export Rating Curves= 0
DSS Export Rating Curve Sorted= 0
DSS Export Volume Flow Curves= 0
DXF OffsetX= 0
DXF OffsetY= 0
DXF ScaleX= 1
DXF ScaleY= 10

--- UNT017 IN NNOGR.p01 (plan) ---

Plan Title=Multiple Run
Short Identifier=Multiple
Geom File=g01
Flow File=f01
Subcritical Flow
K Sum by GR= 0
Std Step Tol= 0.01
Critical Tol= 0.01
Num of Std Step Trials= 20
Max Error Tol= 0.3
Flow Tol Ratio= 0.001
Split Flow NTrial= 30
Split Flow Tol= 0.02
Split Flow Ratio= 0.02
Log Output Level= 0
Friction Slope Method= 1
Unsteady Friction Slope Method= 2
Unsteady Bridges Friction Slope Method= 1
Parabolic Critical Depth
Global Vel Dist=  1 , 1 , 1
Global Log Level= 0
CheckData=True
Encroach Param= -1, 0, 0, 0
BEGIN DESCRIPTION:
Multiple Run
END DESCRIPTION:

--- UNT017 IN NNOGR.f01 (steady flow) ---

Flow Title=Multiple
Program Version=4.10
Number of Profiles= 7
Profile Names=10-year,25-year,50-year,1pct_min,100-year,1pct_plu,500-year
River Rch & RM=UNT017 IN NNOGR,Reach-1         ,2595
     788    1142    1450    1349    1824    2467    2898
Boundary for River Rch & Prof#=UNT017 IN NNOGR,Reach-1         , 1
Up Type= 0
Dn Type= 3
Dn Slope=0.0133
Boundary for River Rch & Prof#=UNT017 IN NNOGR,Reach-1         , 2
Up Type= 0
Dn Type= 3
Dn Slope=0.0133
Boundary for River Rch & Prof#=UNT017 IN NNOGR,Reach-1         , 3
Up Type= 0
Dn Type= 3
Dn Slope=0.0133
Boundary for River Rch & Prof#=UNT017 IN NNOGR,Reach-1         , 4
Up Type= 0
Dn Type= 3
Dn Slope=0.0133
Boundary for River Rch & Prof#=UNT017 IN NNOGR,Reach-1         , 5
Up Type= 0
Dn Type= 3
Dn Slope=0.0133
Boundary for River Rch & Prof#=UNT017 IN NNOGR,Reach-1         , 6
Up Type= 0
Dn Type= 3
Dn Slope=0.0133
Boundary for River Rch & Prof#=UNT017 IN NNOGR,Reach-1         , 7
Up Type= 0
Dn Type= 3
Dn Slope=0.0133
DSS Import GetInterval= 0
DSS Import GetPeak= 0
DSS Import FillOption= 0

--- UNT017 IN NNOGR.g01 (geometry) ---

Geom Title=Existing Conditions
Program Version=4.10

River Reach=UNT017 IN NNOGR ,Reach-1
Reach XY= 30
       2750981.3      10092716.9      2751017.51     10092792.95
      2751047.37      10092899.9       2751053.8     10092997.84
      2751147.87     10093074.37      2751165.64     10093104.74
      2751178.74     10093220.79      2751162.66      10093311.6
      2751271.37     10093368.64      2751340.34     10093437.23
      2751356.78     10093489.43      2751360.62     10093577.95
      2751396.63     10093628.43      2751621.14     10093758.66
      2751741.68     10093857.55      2751834.99     10093953.32
      2751879.49     10093981.55      2751927.35     10093990.79
      2752028.46     10093953.29      2752072.66     10093955.38
      2752137.32     10093976.48      2752264.88     10094031.32
      2752304.85     10094067.17      2752359.26     10094143.05
      2752395.84     10094168.48      2752497.15     10094186.92
      2752613.68     10094241.92      2752728.42     10094257.71
      2752835.97     10094217.92      2752878.47     10094213.73

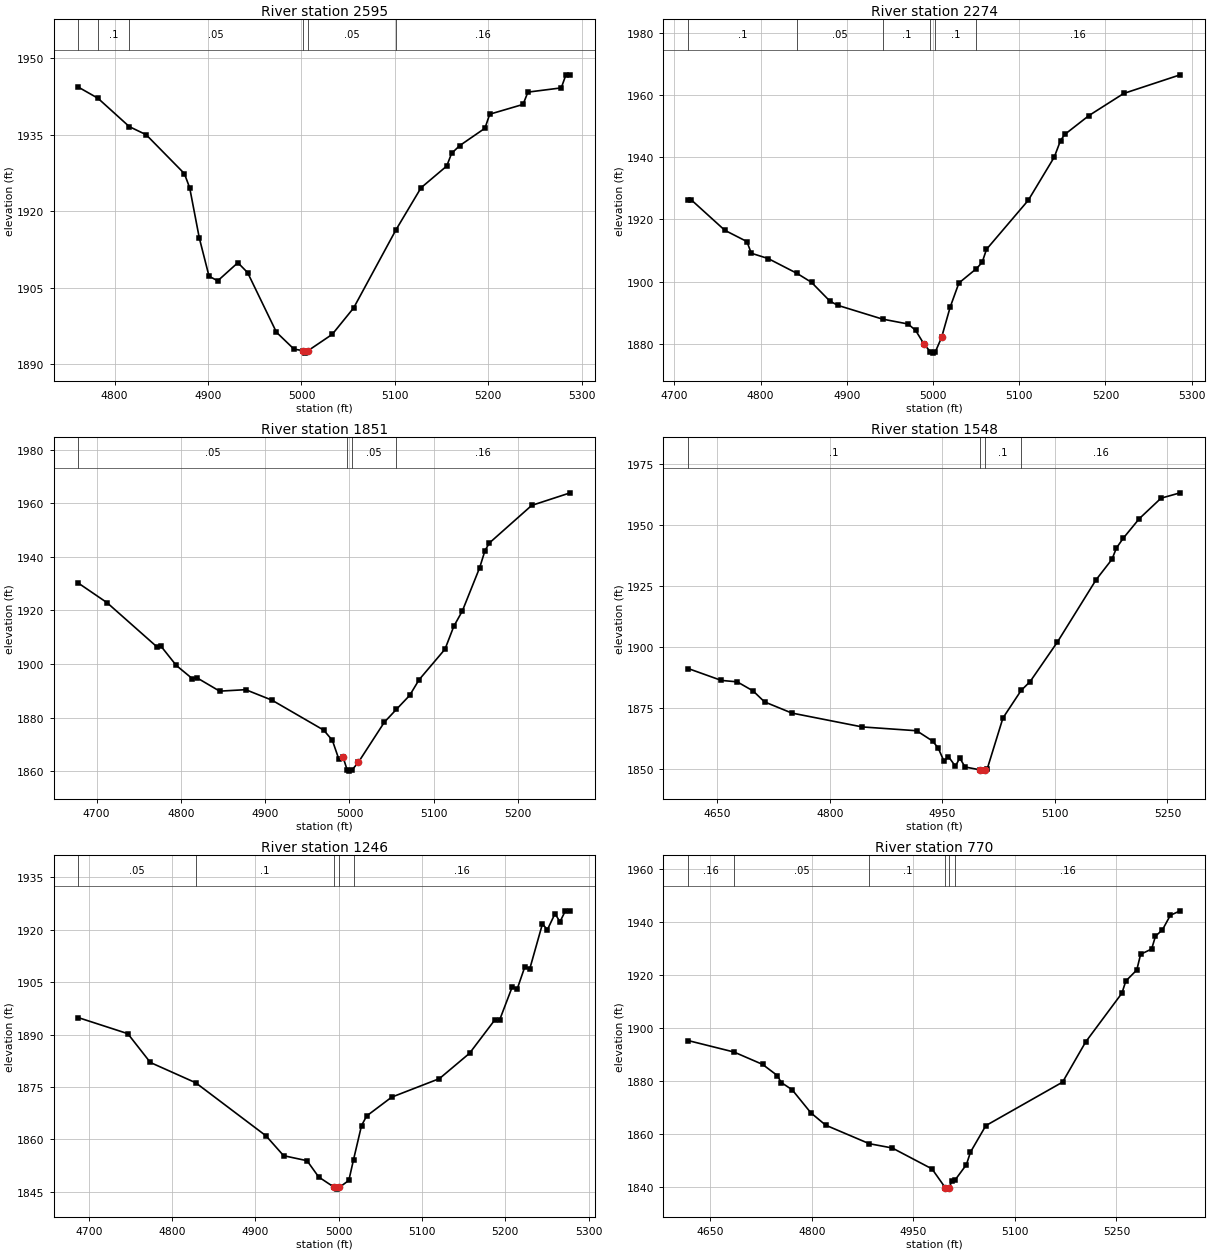
Type RM Length L Ch R = 1 ,2595    ,321,321,321
BEGIN DESCRIPTION:
UNT017 IN NNOGR 5.0
END DESCRIPTION:
XS GIS Cut Line= 2
      2750812.74     10092976.69      2751323.19     10092846.48
#Sta/Elev= 30
  4760.9 1944.35    4782 1942.16  4815.7 1936.58  4833.7    1935  4874.6 1927.38
  4880.3  1924.6  4890.6 1914.76    4901 1907.27  4910.3 1906.35  4931.9 1909.91
  4942.3 1907.97  4973.2 1896.27    4992 1892.96  5001.2 1892.68  5003.9 1892.18
  5007.2 1892.68  5032.9 1895.86  5055.8 1901.03  5101.1 1916.34    5128  1924.6
  5155.5 1928.86  5160.7 1931.34  5169.3 1932.85  5196.4 1936.27  5201.5 1939.02
  5237.2 1940.94  5242.4 1943.35  5278.1 1944.18  5283.1 1946.74  5287.7 1946.74
#Mann= 6 ,-1 , 0
  4760.9     .16       0    4782      .1       0  4815.7     .05       0
  5001.2    .035       0  5007.2     .05       0  5101.1     .16       0
Bank Sta=5001.2,5007.2
XS Rating Curve= 0 ,0
Exp/Cntr=0.3,0.1

Type RM Length L Ch R = 1 ,2274    ,423,423,423
BEGIN DESCRIPTION:
Mapping XS 50b85b68
END DESCRIPTION:
XS GIS Cut Line= 2
      2750896.15     10093216.27      2751463.62     10093153.79
#Sta/Elev= 30
  4715.8 1926.32  4719.5 1926.32  4758.4 1916.53  4784.1 1912.89  4789.1 1909.14
  4808.7 1907.43  4842.4 1902.62    4859 1899.77  4880.1 1893.79  4889.2 1892.39
  4941.4 1887.93    4971 1886.36  4979.7 1884.34  4989.8 1879.76  4996.8 1877.48
  4999.6 1876.98  5002.8 1877.48  5009.9 1882.02  5019.9  1891.8    5030 1899.55
  5050.3 1904.17    5057 1906.19    5062 1910.39  5110.5 1926.19  5140.7 1940.11
  5147.9 1945.42    5153 1947.42  5180.9 1953.46  5221.2 1960.57  5286.7 1966.57
#Mann= 6 ,-1 , 0
  4715.8      .1       0  4842.4     .05       0  4941.4      .1       0
  4996.8     .07       0  5002.8      .1       0  5050.3     .16       0
Bank Sta=4989.8,5009.9
XS Rating Curve= 0 ,0
Exp/Cntr=0.3,0.1

Type RM Length L Ch R = 1 ,1851    ,303,303,303
BEGIN DESCRIPTION:
UNT017 IN NNOGR 4.0
END DESCRIPTION:
XS GIS Cut Line= 2
      2751045.22     10093580.95      2751612.89     10093445.54
#Sta/Elev= 30
  4678.2 1930.26  4712.4 1922.92  4771.4 1906.47  4776.6 1906.59  4794.6 1899.46
  4813.5 1894.56  4818.7 1894.92    4846 1889.86  4876.9 1890.41  4908.1 1886.49
  4969.4 1875.31  4979.7  1871.5  4987.1 1864.69  4992.3 1865.28  4997.2 1860.49
    5000 1859.99  5003.2 1860.49  5010.5 1863.27  5041.4 1878.28  5055.6 1883.05
  5071.4 1888.28  5082.5 1894.11  5113.3 1905.54  5123.7 1914.06  5133.9 1919.84
  5154.4 1935.98  5160.7 1942.35  5165.9  1945.2  5216.1 1959.23  5261.8 1963.93
#Mann= 4 ,-1 , 0
  4678.2     .05       0  4997.2    .035       0  5003.2     .05       0
  5055.6     .16       0
Bank Sta=4992.3,5010.5
XS Rating Curve= 0 ,0
Exp/Cntr=0.3,0.1

Type RM Length L Ch R = 1 ,1548    ,302,302,302
BEGIN DESCRIPTION:
Mapping XS 31480706
END DESCRIPTION:
XS GIS Cut Line= 2
      2751328.41     10094044.38      2751682.56     10093492.31
#Sta/Elev= 30
    4611 1891.22  4655.4 1886.33  4676.5 1885.75  4697.7 1882.01  4712.9 1877.52
  4749.2 1872.94    4843 1867.24  4915.7 1865.67  4936.9 1861.44  4944.4 1858.57
  4952.1 1853.15    4958 1855.08  4967.3 1851.11  4973.2 1854.47  4980.1  1850.8
  5000.6 1849.59  5003.3 1849.09  5006.6 1849.59  5009.5 1849.76  5030.7 1870.91
  5054.9  1882.2    5067 1885.88  5103.4 1902.14  5154.9 1927.68    5176 1936.04
    5182 1940.72  5191.2 1944.76  5212.4 1952.73  5241.4 1961.15  5266.9 1963.35
#Mann= 4 ,-1 , 0
    4611      .1       0  5000.6     .07       0  5006.6      .1       0
  5054.9     .16       0
Bank Sta=5000.6,5006.6
XS Rating Curve= 0 ,0
Exp/Cntr=0.3,0.1

Type RM Length L Ch R = 1 ,1246    ,476,476,476
BEGIN DESCRIPTION:
UNT017 IN NNOGR 3.0
END DESCRIPTION:
XS GIS Cut Line= 2
      2751607.71     10094153.85       2751930.6     10093659.09
#Sta/Elev= 30
  4687.1 1894.85  4746.7 1890.24  4773.8 1881.99  4828.2 1876.19  4912.7 1860.98
  4933.8  1855.3  4961.9 1853.87  4975.9 1849.21  4994.7 1846.23  4997.5 1845.73
  5000.7 1846.23  5012.1 1848.23  5017.7 1854.14  5027.3  1863.9  5033.5 1866.68
  5063.5 1872.06  5120.8 1877.36    5157 1884.62  5187.2 1894.13  5193.2  1894.2
  5208.3 1903.66  5214.3 1903.08  5223.4 1909.39  5229.4 1908.86  5244.5 1921.64
  5250.5 1920.02  5259.6 1924.58  5265.6 1922.28  5272.1 1925.41  5277.9 1925.41
#Mann= 5 ,-1 , 0
  4687.1     .05       0  4828.2      .1       0  4994.7     .07       0
  5000.7      .1       0  5017.7     .16       0
Bank Sta=4994.7,5000.7
XS Rating Curve= 0 ,0
Exp/Cntr=0.3,0.1

Type RM Length L Ch R = 1 ,770     ,590,590,590
BEGIN DESCRIPTION:
UNT017 IN NNOGR 2.0
END DESCRIPTION:
XS GIS Cut Line= 2
      2752019.17     10094341.33      2752362.91     10093700.73
#Sta/Elev= 30
  4617.2 1895.22  4684.9 1890.89  4727.2 1886.21  4749.1 1881.98  4754.8 1879.35
    4771  1876.6  4798.6 1867.88  4820.5 1863.21  4884.9  1856.2  4918.8 1854.58
  4977.6 1846.66  4997.3 1839.51  5000.1 1839.01  5003.3 1839.51  5006.5 1841.99
  5012.1 1842.62  5028.4 1848.26  5034.4    1853  5057.1 1863.03  5170.5  1879.5
  5204.6 1894.69  5258.2 1913.16  5263.9 1917.74  5280.1 1921.91  5285.8 1927.86
  5302.1 1929.86  5307.7 1934.69  5318.1 1937.15  5329.7 1942.61  5344.2  1944.3
#Mann= 6 ,-1 , 0
  4617.2     .16       0  4684.9     .05       0  4884.9      .1       0
  4997.3     .07       0  5003.3      .1       0  5012.1     .16       0
Bank Sta=4997.3,5003.3
XS Rating Curve= 0 ,0
Exp/Cntr=0.3,0.1

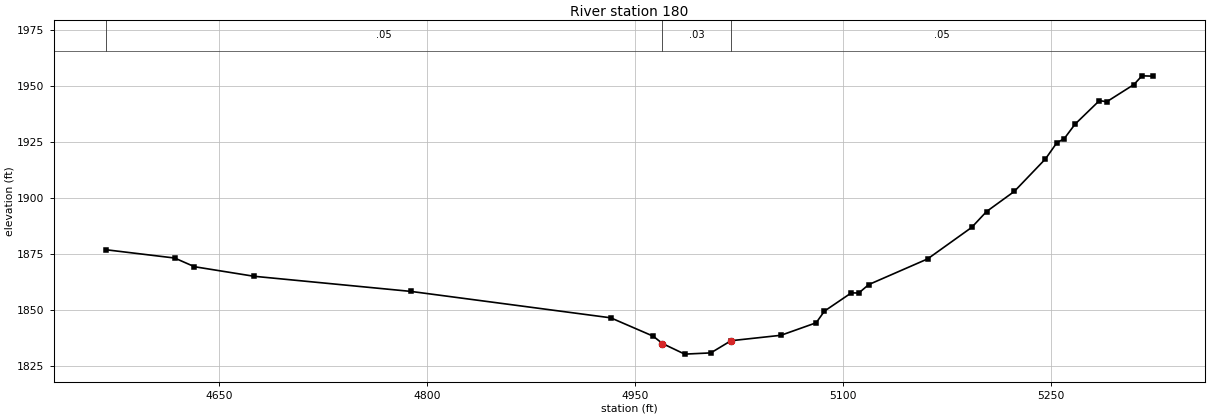
Type RM Length L Ch R = 1 ,180     ,0,0,0
BEGIN DESCRIPTION:
UNT017 IN NNOGR 1.0
END DESCRIPTION:
XS GIS Cut Line= 3
      2752414.96     10094560.14       2752675.4     10094341.37
      2752816.03     10093950.75
#Sta/Elev= 30
  4568.2 1876.99  4617.8 1873.29  4632.1 1869.41    4675 1865.15  4788.2 1858.39
  4932.3 1846.61    4963  1838.4  4969.6 1835.13 4985.69  1830.4  5004.5 1830.95
  5019.1 1836.39  5055.1 1838.81  5080.5 1844.39  5086.5 1849.61  5105.9 1857.75
  5111.2 1857.66  5118.4 1861.43  5160.9  1872.9  5192.7 1886.97  5203.4 1894.04
  5223.4 1903.01  5245.9 1917.53  5254.1 1924.73  5259.4 1926.54  5267.2 1933.01
  5284.8 1943.55  5290.1 1943.04  5309.7 1950.72  5315.5 1954.61  5323.5 1954.46
#Mann= 3 , 0 , 0
  4568.2     .05       0  4969.6     .03       0  5019.1     .05       0
Bank Sta=4969.6,5019.1
XS Rating Curve= 0 ,0
Exp/Cntr=0.3,0.1

Chan Stop Cuts=-1
Use User Specified Reach Order=0
Composite Channel Slope=5