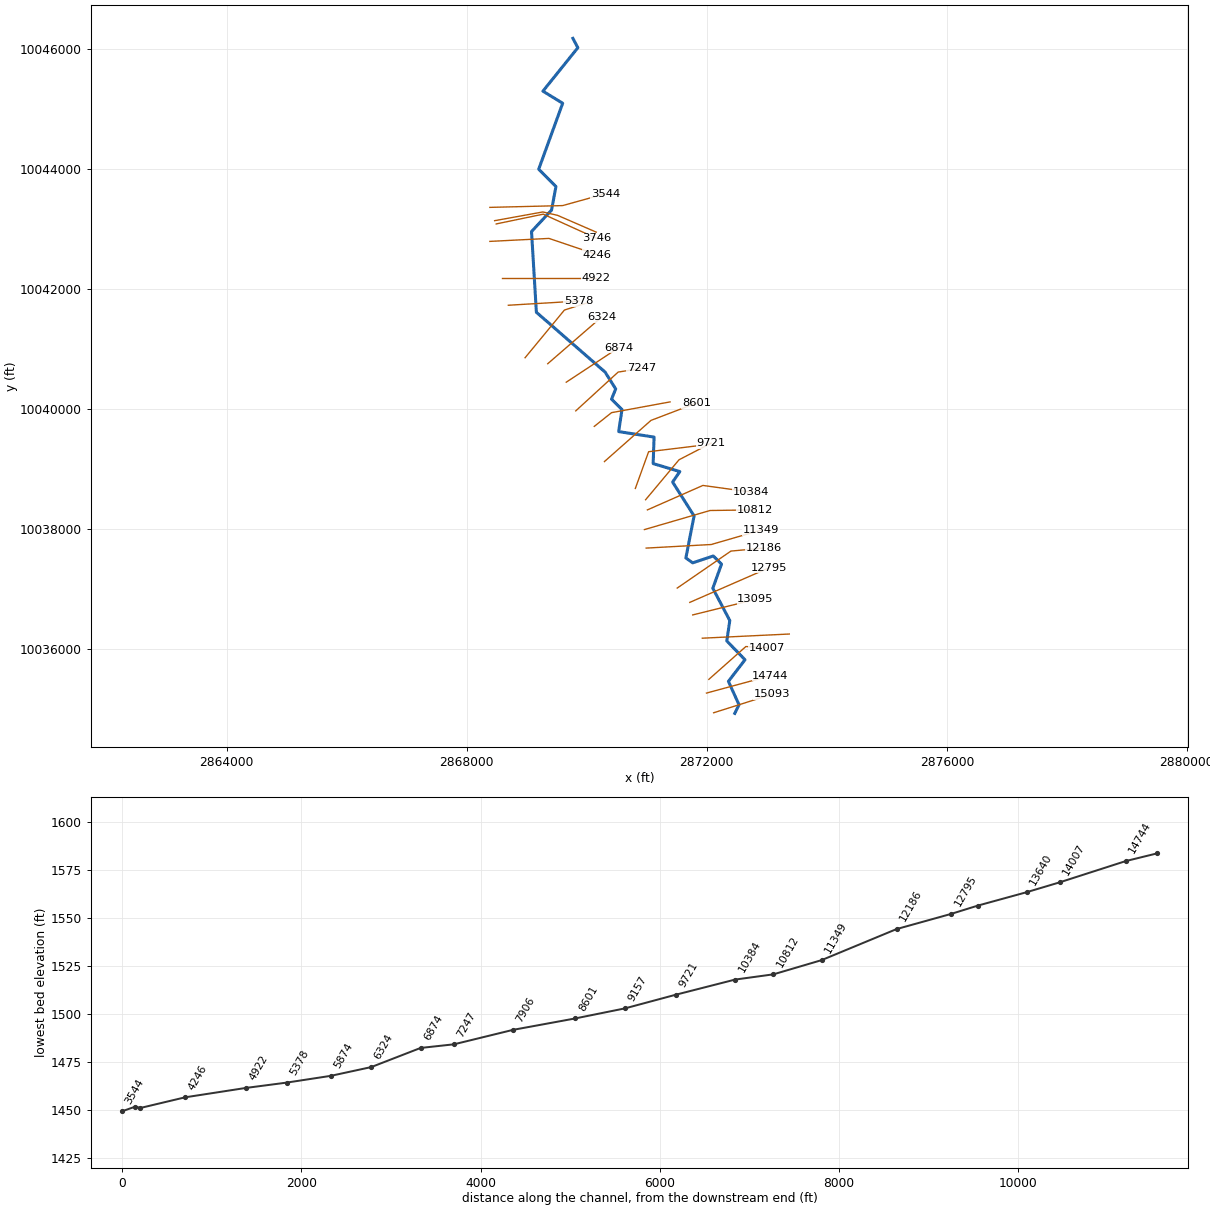
--- UNT017 IN SNOGR.prj (project) ---

Proj Title=UNT017 IN SNOGR Base Level Engineering
Current Plan=p01
Default Exp/Contr=0.3,0.1
English Units
Geom File=g01
Flow File=f01
Plan File=p01
Y Axis Title=Elevation
X Axis Title(PF)=Main Channel Distance
X Axis Title(XS)=Station
BEGIN DESCRIPTION:
UNT017 IN SNOGR
END DESCRIPTION:
DSS File=dss
DSS Export Rating Curves= 0
DSS Export Rating Curve Sorted= 0
DSS Export Volume Flow Curves= 0
DXF OffsetX= 0
DXF OffsetY= 0
DXF ScaleX= 1
DXF ScaleY= 10

--- UNT017 IN SNOGR.p01 (plan) ---

Plan Title=Multiple Run
Program Version=4.10
Short Identifier=Multiple Run
Geom File=g01
Flow File=f01
Subcritical Flow
K Sum by GR= 0
Std Step Tol= 0.01
Critical Tol= 0.01
Num of Std Step Trials= 20
Max Error Tol= 0.3
Flow Tol Ratio= 0.001
Split Flow NTrial= 30
Split Flow Tol= 0.02
Split Flow Ratio= 0.02
Log Output Level= 0
Friction Slope Method= 1
Unsteady Friction Slope Method= 2
Unsteady Bridges Friction Slope Method= 1
Parabolic Critical Depth
Global Vel Dist= 1 , 1 , 1
Global Log Level= 0
CheckData=True
Encroach Param=-1 ,0,0, 0
BEGIN DESCRIPTION:
Multiple Run
END DESCRIPTION:
Computation Interval=1HOUR
Output Interval=1HOUR
Run HTab= 0
Run UNet= 0
Run PostProcess= 0
Run WQNet= 0
UNET Theta= 1
UNET Theta Warmup= 1
UNET ZTol= 0.02
UNET ZSATol= 0.05
UNET MxIter= 20
UNET MaxInSteps= 0
UNET DtIC= 0
UNET DtMin= 0
UNET MaxCRTS= 20
UNET WFStab= 2
UNET SFStab= 1
UNET WFX= 1
UNET SFX= 1
UNET DSS MLevel= 4
UNET DZMax Abort= 100
UNET Convert EG Bridges= 0
UNET Use Existing IB Tables=-1
UNET Froude Reduction=False
UNET Froude Limit= 1
UNET Froude Power= 10
UNET Time Slicing=0,0, 5
UNET Junction Losses=0
Instantaneous Interval=1HOUR
DSS File=dss
Write IC File= 0
Write IC File at Sim End=0
Echo Input=False
Echo Parameters=False
Echo Output=False
Write Detailed= 0
WQ AD Non Conservative
WQ ULTIMATE=-1
WQ Max Comp Step=1HOUR
WQ Output Interval=15MIN
WQ Output Selected Increments= 0
WQ Output face flow=0
WQ Output face velocity=0
WQ Output face area=0
WQ Output face dispersion=0
WQ Output cell volume=0
WQ Output cell surface area=0
WQ Output cell continuity=0
WQ Output cumulative cell continuity=0
WQ Output face conc=0
WQ Output face dconc_dx=0
WQ Output face courant=0
WQ Output face peclet=0
WQ Output face adv mass=0
WQ Output face disp mass=0
WQ Output cell mass=0
WQ Output cell source sink temp=0
WQ Output cell source sink nsm=0
WQ Output MaxMinRange=-1
WQ Daily Max Min Mean=-1
WQ Daily Range=0
WQ Daily Time=0
WQ Create Restart=0
WQ Fixed Restart=0
WQ System Summary=0
WQ Use Fixed Temperature=0
Sorting and Armoring Iterations= 10
XS Update Threshold= 0.02
Hydraulics Update Threshold= 0.02
Energy Slope Method= 1
Volume Change Method= 0
XS Weighting Method= 0
Number of US Weighted Cross Sections= 1
Number of DS Weighted Cross Sections= 1
Upstream XS Weight=0.25
Main XS Weight=0.5
Downstream XS Weight=0.25
Number of DS XS's Weighted with US Boundary= 1
Upstream Boundary Weight= 1
Weight of XSs Associated with US Boundary= 0
Number of US XS's Weighted with DS Boundary= 1
Downstream Boundary Weight= 0.5
Weight of XSs Associated with DS Boundary= 0.5
Sediment Output Level= 4
Mass or Volume Output= 0
Output Increment Type= 1
Profile and TS Output Increment= 10
XS Output Flag= 0
XS Output Increment= 10
Disregard all LS=0
Disregard all Conn=0
Disregard all Breaches=0
Disregard all Pumps=0

--- UNT017 IN SNOGR.f01 (steady flow) ---

Flow Title=Multiple
Program Version=4.10
Number of Profiles= 7
Profile Names=10-year,25-year,50-year,1pct_min,100-year,1pct_plu,500-year
River Rch & RM=UNT017 IN SNOGR,Reach-1         ,15093
    1057    1547    1978    1851    2504    3386    4026
River Rch & RM=UNT017 IN SNOGR,Reach-1         ,12186
    1363    2013    2589    2433    3291    4450    5338
River Rch & RM=UNT017 IN SNOGR,Reach-1         ,3544
    1460    2162    2783    2619    3542    4790    5759
Boundary for River Rch & Prof#=UNT017 IN SNOGR,Reach-1         , 1
Up Type= 0
Dn Type= 3
Dn Slope=0.007
Boundary for River Rch & Prof#=UNT017 IN SNOGR,Reach-1         , 2
Up Type= 0
Dn Type= 3
Dn Slope=0.007
Boundary for River Rch & Prof#=UNT017 IN SNOGR,Reach-1         , 3
Up Type= 0
Dn Type= 3
Dn Slope=0.007
Boundary for River Rch & Prof#=UNT017 IN SNOGR,Reach-1         , 4
Up Type= 0
Dn Type= 3
Dn Slope=0.007
Boundary for River Rch & Prof#=UNT017 IN SNOGR,Reach-1         , 5
Up Type= 0
Dn Type= 3
Dn Slope=0.007
Boundary for River Rch & Prof#=UNT017 IN SNOGR,Reach-1         , 6
Up Type= 0
Dn Type= 3
Dn Slope=0.007
Boundary for River Rch & Prof#=UNT017 IN SNOGR,Reach-1         , 7
Up Type= 0
Dn Type= 3
Dn Slope=0.007
DSS Import GetInterval= 0
DSS Import GetPeak= 0
DSS Import FillOption= 0

--- UNT017 IN SNOGR.g01 (geometry) ---

Geom Title=Existing Conditions
Program Version=4.10

River Reach=UNT017 IN SNOGR ,Reach-1
Reach XY= 30
      2872465.89      10034924.8      2872537.13     10035067.89
      2872360.07     10035458.23      2872636.77     10035818.07
      2872333.77     10036131.27      2872383.19     10036472.01
      2872100.54     10037009.38      2872244.96     10037411.67
       2872108.7     10037547.58      2871764.65     10037433.42
      2871651.26     10037514.83      2871788.16     10038214.77
      2871430.29     10038779.69      2871550.69     10038954.09
       2871106.2     10039087.45      2871121.37     10039528.71
      2870531.61     10039620.33      2870586.61     10039987.96
      2870412.38     10040160.98      2870481.95     10040331.31
      2870305.66     10040611.97      2869160.13     10041609.24
      2869079.44     10042954.43      2869412.75     10043311.22
      2869486.32     10043703.83      2869199.05     10043992.96
      2869598.35      10045091.7       2869269.4     10045293.74
      2869851.36     10046017.52      2869768.47     10046173.73

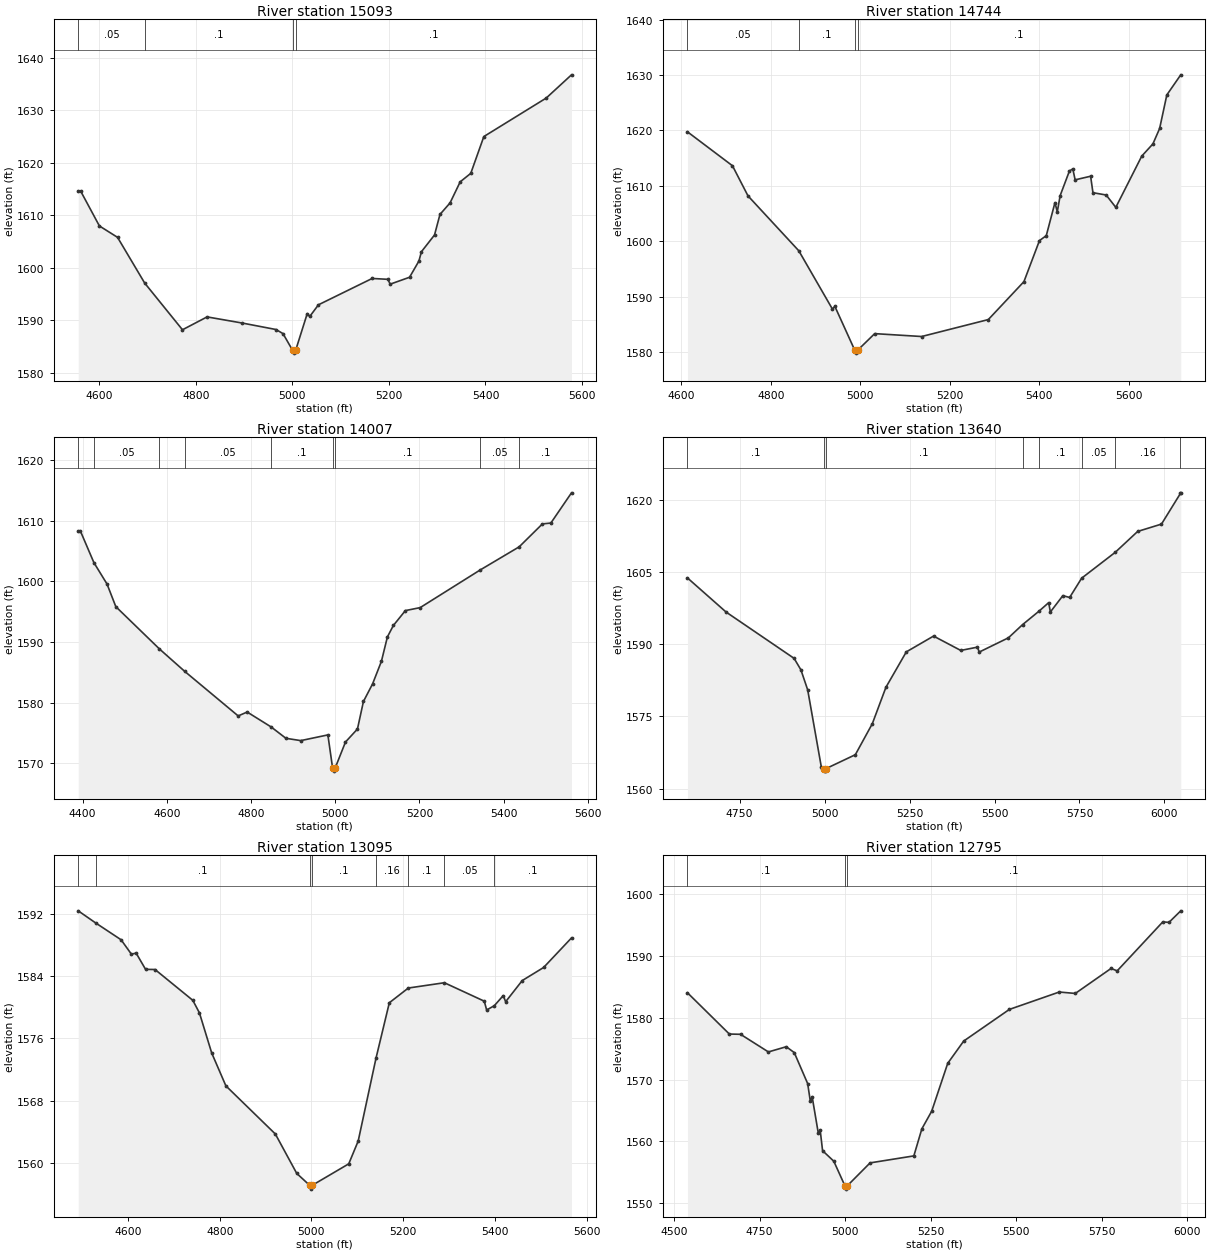
Type RM Length L Ch R = 1 ,15093   ,349,349,349
BEGIN DESCRIPTION:
UNT017 IN SNOGR 31.0
END DESCRIPTION:
XS GIS Cut Line= 2
      2872113.91     10034934.74      2873088.32     10035242.98
#Sta/Elev= 30
  4556.3 1614.62  4561.3 1614.62  4600.2 1607.98  4637.8 1605.81    4694 1597.12
  4772.3 1588.23  4823.3 1590.68  4896.3 1589.51  4966.1 1588.28  4980.6  1587.5
  5000.7 1584.29  5003.4 1583.79  5006.7 1584.29  5030.8 1591.31    5036 1590.76
    5054 1592.98  5165.3 1597.99  5197.6 1597.83  5202.8 1596.91  5242.8 1598.22
  5262.2 1601.31  5267.4 1603.08  5294.5 1606.26  5305.8 1610.17  5326.7 1612.36
  5347.7 1616.37  5369.6 1617.98  5396.7 1624.98  5525.9  1632.3  5578.3 1636.72
#Mann= 4 ,-1 , 0
  4556.3     .05       0    4694      .1       0  5000.7     .07       0
  5006.7      .1       0
Bank Sta=5000.7,5006.7
XS Rating Curve= 0 ,0
Exp/Cntr=0.3,0.1

Type RM Length L Ch R = 1 ,14744   ,737,737,737
BEGIN DESCRIPTION:
UNT017 IN SNOGR 30.0
END DESCRIPTION:
XS GIS Cut Line= 2
       2871994.6     10035262.88      2873058.52     10035551.23
#Sta/Elev= 30
  4613.5 1619.75  4714.1 1613.62  4748.8 1608.18  4862.3 1598.27  4937.6 1587.72
  4942.8 1588.25  4987.5 1580.29  4990.2 1579.79  4993.5 1580.29  5031.9 1583.31
  5136.8 1582.79  5285.8 1585.85  5365.4  1592.7  5400.1 1600.11  5415.3    1601
  5434.7 1606.96  5439.9 1605.31  5446.4 1608.25  5467.1 1612.69  5474.6 1613.05
  5479.8 1611.08  5514.4 1611.73  5519.6 1608.76  5549.1 1608.34  5570.7 1606.11
  5628.7 1615.37  5653.6 1617.57  5668.6 1620.35  5684.7 1626.41  5715.8 1630.04
#Mann= 4 ,-1 , 0
  4613.5     .05       0  4862.3      .1       0  4987.5     .07       0
  4993.5      .1       0
Bank Sta=4987.5,4993.5
XS Rating Curve= 0 ,0
Exp/Cntr=0.3,0.1

Type RM Length L Ch R = 1 ,14007   ,367,367,367
BEGIN DESCRIPTION:
UNT017 IN SNOGR 29.0
END DESCRIPTION:
XS GIS Cut Line= 3
      2872034.33     10035491.55      2872650.83     10036038.45
      2872997.34     10036018.65
#Sta/Elev= 30
  4389.7 1608.27  4395.1 1608.27    4427 1603.09  4458.1 1599.57    4479 1595.84
  4582.7 1588.86  4642.3 1585.19  4769.5 1577.83  4790.9 1578.47  4847.8 1576.01
  4882.9 1574.14  4918.1 1573.76  4982.5  1574.7  4993.7 1569.23  4996.4 1568.73
  4999.7 1569.23  5024.3 1573.53  5052.7 1575.67  5066.9 1580.21  5088.7 1583.12
  5109.6 1586.83  5123.8 1590.85    5138 1592.74  5166.5 1595.19  5201.6 1595.68
  5343.5 1601.86  5436.7  1605.7  5491.9 1609.48  5511.9 1609.62  5560.9  1614.6
#Mann= 9 ,-1 , 0
  4389.7      .1       0    4427     .05       0  4582.7      .1       0
  4642.3     .05       0  4847.8      .1       0  4993.7     .07       0
  4999.7      .1       0  5343.5     .05       0  5436.7      .1       0
Bank Sta=4993.7,4999.7
XS Rating Curve= 0 ,0
Exp/Cntr=0.3,0.1

Type RM Length L Ch R = 1 ,13640   ,545,545,545
BEGIN DESCRIPTION:
UNT017 IN SNOGR 28.0
END DESCRIPTION:
XS GIS Cut Line= 2
      2871924.95     10036177.66      2873375.09     10036247.18
#Sta/Elev= 30
  4596.3 1603.85  4709.9 1596.75  4910.2  1587.1  4930.2 1584.71  4950.2 1580.53
  4990.3 1564.47  4997.3 1564.12    5000 1563.62  5003.3 1564.12  5090.4 1567.04
  5140.4  1573.5  5180.5 1581.09  5240.4 1588.45  5320.6 1591.74  5400.7 1588.75
  5449.9 1589.44  5454.9 1588.41  5540.9 1591.38  5582.5 1594.12  5630.8 1596.92
  5659.4  1598.7  5664.4 1596.76  5701.1 1600.16  5721.1 1599.78  5756.5  1603.8
  5855.1 1609.17  5921.3 1613.53  5991.4 1615.06  6047.3 1621.46  6048.1 1621.57
#Mann= 8 ,-1 , 0
  4596.3      .1       0  4997.3     .07       0  5003.3      .1       0
  5582.5     .05       0  5630.8      .1       0  5756.5     .05       0
  5855.1     .16       0  6047.3      .1       0
Bank Sta=4997.3,5003.3
XS Rating Curve= 0 ,0
Exp/Cntr=0.3,0.1

Type RM Length L Ch R = 1 ,13095   ,300,300,300
BEGIN DESCRIPTION:
UNT017 IN SNOGR 27.0
END DESCRIPTION:
XS GIS Cut Line= 2
      2871765.89     10036565.45      2872809.96     10036823.99
#Sta/Elev= 30
  4491.5  1592.4  4529.4 1590.85    4585 1588.68  4607.5 1586.83  4617.8 1586.97
  4638.4 1584.88    4659 1584.86  4741.4  1580.9  4755.8 1579.29  4782.6 1574.13
  4813.5 1569.91  4921.4 1563.72    4968 1558.66    4996 1557.14  4998.7 1556.64
    5002 1557.14  5081.4 1559.89    5102 1562.82  5140.9 1573.48  5169.9 1580.59
  5211.3 1582.48  5289.9 1583.16  5376.9 1580.79  5382.1 1579.66  5398.8 1580.21
  5418.3 1581.51  5423.5 1580.72  5459.7 1583.44  5506.3 1585.12  5567.1 1588.92
#Mann= 8 ,-1 , 0
  4491.5     .16       0  4529.4      .1       0    4996     .07       0
    5002      .1       0  5140.9     .16       0  5211.3      .1       0
  5289.9     .05       0  5398.8      .1       0
Bank Sta=4996,5002
XS Rating Curve= 0 ,0
Exp/Cntr=0.3,0.1

Type RM Length L Ch R = 1 ,12795   ,609,609,609
BEGIN DESCRIPTION:
UNT017 IN SNOGR 26.0
END DESCRIPTION:
XS GIS Cut Line= 2
      2871716.18     10036774.27       2873038.6     10037350.97
#Sta/Elev= 30
  4538.8 1584.02  4661.3 1577.35    4694 1577.31  4775.5 1574.46  4827.8  1575.3
  4851.2 1574.35  4890.4 1569.34    4898 1566.54  4903.5 1567.22  4921.4 1561.35
  4926.9 1561.86    4934  1558.5  4966.8  1556.8  4999.6 1552.79  5002.4 1552.29
  5005.6 1552.79  5072.9 1556.53  5200.9 1557.66  5224.3 1562.03  5253.1 1564.88
    5300 1572.62  5346.8 1576.22  5480.3 1581.33  5626.2 1584.14  5673.1 1583.91
  5777.7 1587.95  5795.6 1587.56  5929.1 1595.48    5947 1595.39  5981.5 1597.26
#Mann= 3 ,-1 , 0
  4538.8      .1       0  4999.6     .07       0  5005.6      .1       0
Bank Sta=4999.6,5005.6
XS Rating Curve= 0 ,0
Exp/Cntr=0.3,0.1

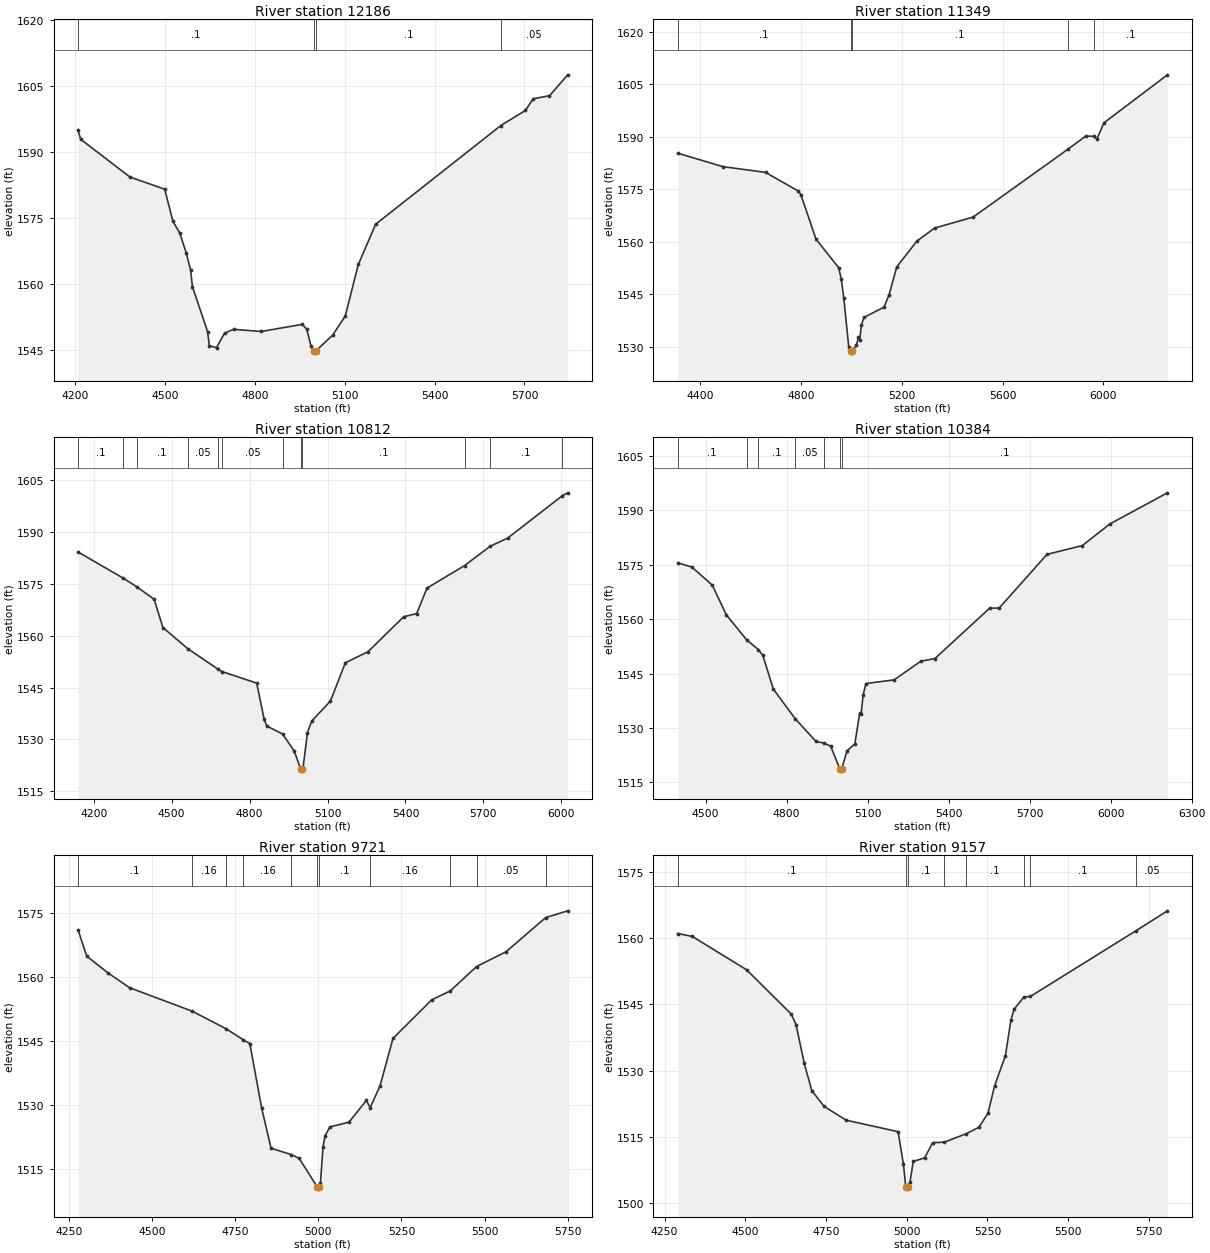
Type RM Length L Ch R = 1 ,12186   ,837,837,837
BEGIN DESCRIPTION:
UNT017 IN SNOGR 24.0
END DESCRIPTION:
XS GIS Cut Line= 3
      2871507.38     10037012.93      2872402.25     10037629.39
      2872949.14     10037679.11
#Sta/Elev= 30
  4208.7 1595.02  4217.5 1592.99  4381.8 1584.42  4498.2 1581.64  4525.7 1574.34
  4548.9 1571.61  4569.9  1567.2  4584.7 1563.33  4590.8 1559.52  4641.5 1549.28
  4647.6 1546.06  4671.3 1545.63  4698.3 1548.93  4728.1  1549.8  4820.8 1549.31
    4958 1550.93  4972.9 1549.81  4987.2 1545.91    4997 1544.89  4999.7 1544.39
    5003 1544.89  5059.5  1548.5  5101.4 1552.81    5145 1564.53  5202.9 1573.68
  5621.2 1596.11  5703.2 1599.53  5729.1 1602.18  5783.6 1602.88  5844.5 1607.63
#Mann= 4 ,-1 , 0
  4208.7      .1       0    4997     .07       0    5003      .1       0
  5621.2     .05       0
Bank Sta=4997,5003
XS Rating Curve= 0 ,0
Exp/Cntr=0.3,0.1

Type RM Length L Ch R = 1 ,11349   ,537,537,537
BEGIN DESCRIPTION:
UNT017 IN SNOGR 23.0
END DESCRIPTION:
XS GIS Cut Line= 3
      2870990.31     10037679.11      2872074.12     10037738.77
      2872899.46     10037977.42
#Sta/Elev= 30
  4309.9 1585.36  4489.2 1581.51  4658.6 1579.87  4788.8 1574.53  4798.8 1573.53
  4858.9 1560.81    4949 1552.63    4959 1549.53  4969.1 1544.06  4989.1 1529.97
  4996.1 1528.72  4998.8 1528.22  5002.1 1528.72  5019.1 1530.43  5027.5  1532.7
  5032.5 1531.92  5039.2 1536.15  5049.2 1538.42  5129.3 1541.37  5149.3 1544.92
  5179.4 1552.83  5259.5 1560.22  5329.6 1563.95  5483.2  1567.1  5859.9 1586.51
  5930.4 1590.26  5961.4 1590.17  5974.4 1589.44  6002.8 1594.05  6254.5 1607.75
#Mann= 5 ,-1 , 0
  4309.9      .1       0  4996.1     .07       0  5002.1      .1       0
  5859.9     .05       0  5961.4      .1       0
Bank Sta=4996.1,5002.1
XS Rating Curve= 0 ,0
Exp/Cntr=0.3,0.1

Type RM Length L Ch R = 1 ,10812   ,428,428,428
BEGIN DESCRIPTION:
UNT017 IN SNOGR 22.0
END DESCRIPTION:
XS GIS Cut Line= 3
      2870960.47     10037987.35      2872054.23     10038305.54
      2872799.96     10038315.48
#Sta/Elev= 30
  4139.6 1584.26  4312.8 1576.71  4365.4 1574.18  4432.6 1570.58  4466.2 1562.39
  4562.1 1556.27  4677.1 1550.41    4694 1549.63  4827.4 1546.31  4855.7 1535.94
  4866.5 1533.89  4927.1 1531.57  4971.9 1526.66  4997.2 1521.34    5000 1520.84
  5003.2 1521.34  5005.4 1521.58  5022.8 1532.01    5039 1535.32  5111.2 1541.12
  5168.6 1552.19  5255.7 1555.38  5392.9  1565.5    5443 1566.42    5483 1573.81
  5627.3 1580.31  5725.9  1585.9    5793 1588.25  6003.6 1600.52  6024.5 1601.37
#Mann= 12 ,-1 , 0
  4139.6      .1       0  4312.8     .05       0  4365.4      .1       0
  4562.1     .05       0  4677.1      .1       0    4694     .05       0
  4927.1      .1       0  4997.2     .07       0  5003.2      .1       0
  5627.3     .16       0  5725.9      .1       0  6003.6     .16       0
Bank Sta=4997.2,5003.2
XS Rating Curve= 0 ,0
Exp/Cntr=0.3,0.1

Type RM Length L Ch R = 1 ,10384   ,663,663,663
BEGIN DESCRIPTION:
UNT017 IN SNOGR 21.0
END DESCRIPTION:
XS GIS Cut Line= 3
       2871010.2     10038315.49      2871934.91     10038723.16
      2872730.34     10038613.79
#Sta/Elev= 30
  4396.7 1575.48  4449.1 1574.32  4524.6 1569.35  4576.7 1561.15  4651.6  1554.3
  4695.8 1551.56  4711.7 1549.99  4750.9 1540.69  4831.9 1532.53  4908.5  1526.3
  4937.8 1525.84  4963.1 1524.97  4997.5 1518.61  5000.3 1518.11  5003.5 1518.61
  5023.8 1523.73  5052.6 1525.58  5070.5  1534.1  5075.9 1533.93  5083.3 1539.09
  5093.8 1542.24    5198 1543.25  5296.8 1548.38  5348.9 1549.11  5552.2 1563.01
  5587.1 1563.02  5764.2 1577.82  5895.4 1580.25  5996.3 1586.16  6210.2 1594.77
#Mann= 7 ,-1 , 0
  4396.7      .1       0  4651.6     .05       0  4695.8      .1       0
  4831.9     .05       0  4937.8      .1       0  4997.5     .07       0
  5003.5      .1       0
Bank Sta=4997.5,5003.5
XS Rating Curve= 0 ,0
Exp/Cntr=0.3,0.1

Type RM Length L Ch R = 1 ,9721    ,564,564,564
BEGIN DESCRIPTION:
UNT017 IN SNOGR 20.0
END DESCRIPTION:
XS GIS Cut Line= 3
      2870980.34     10038484.51      2871537.18     10039150.72
      2872073.39     10039428.76
#Sta/Elev= 30
  4277.5 1571.07  4303.5 1564.88  4367.7 1560.93  4432.3 1557.47  4620.2 1551.97
  4723.6 1547.79  4774.7 1545.22  4794.1 1544.36  4829.3 1529.32  4857.9  1519.8
  4919.3 1518.29  4942.5 1517.42  4996.7 1510.71  4999.5 1510.21  5002.7 1510.71
  5006.3 1511.54  5014.1 1520.13  5020.6 1522.77  5034.9 1524.81  5092.1 1525.92
  5144.5 1531.02  5155.8  1529.3  5185.8 1534.49  5224.4 1545.56  5340.7  1554.6
  5397.2 1556.74  5475.7 1562.43    5564 1565.88  5683.6 1573.91  5749.8  1575.5
#Mann= 11 ,-1 , 0
  4277.5      .1       0  4620.2     .16       0  4723.6      .1       0
  4774.7     .16       0  4919.3      .1       0  4996.7     .07       0
  5002.7      .1       0  5155.8     .16       0  5397.2      .1       0
  5475.7     .05       0  5683.6      .1       0
Bank Sta=4996.7,5002.7
XS Rating Curve= 0 ,0
Exp/Cntr=0.3,0.1

Type RM Length L Ch R = 1 ,9157    ,556,556,556
BEGIN DESCRIPTION:
UNT017 IN SNOGR 18.0
END DESCRIPTION:
XS GIS Cut Line= 3
      2870809.19     10038673.15      2871030.54     10039285.11
      2871889.89     10039389.27
#Sta/Elev= 30
  4290.9 1561.07  4336.1  1560.4  4504.1 1552.85  4642.4 1542.81  4657.3 1540.43
  4682.7 1531.63  4706.2 1525.44    4744  1521.9  4812.6 1518.76  4973.3 1516.16
  4989.9 1508.74    4997 1503.64  4999.8 1503.14    5003 1503.64  5010.1 1504.74
  5020.2 1509.43  5055.2 1510.22  5080.6 1513.66  5116.4 1513.79  5184.2 1515.69
  5223.9 1517.17  5251.8 1520.36    5272 1526.54  5305.7 1533.39  5322.4 1541.37
  5332.4  1543.9  5362.7 1546.66  5383.2 1546.82  5709.4 1561.67  5807.3 1566.21
#Mann= 8 ,-1 , 0
  4290.9      .1       0    4997     .07       0    5003      .1       0
  5116.4     .16       0  5184.2      .1       0  5362.7     .16       0
  5383.2      .1       0  5709.4     .05       0
Bank Sta=4997,5003
XS Rating Curve= 0 ,0
Exp/Cntr=0.3,0.1

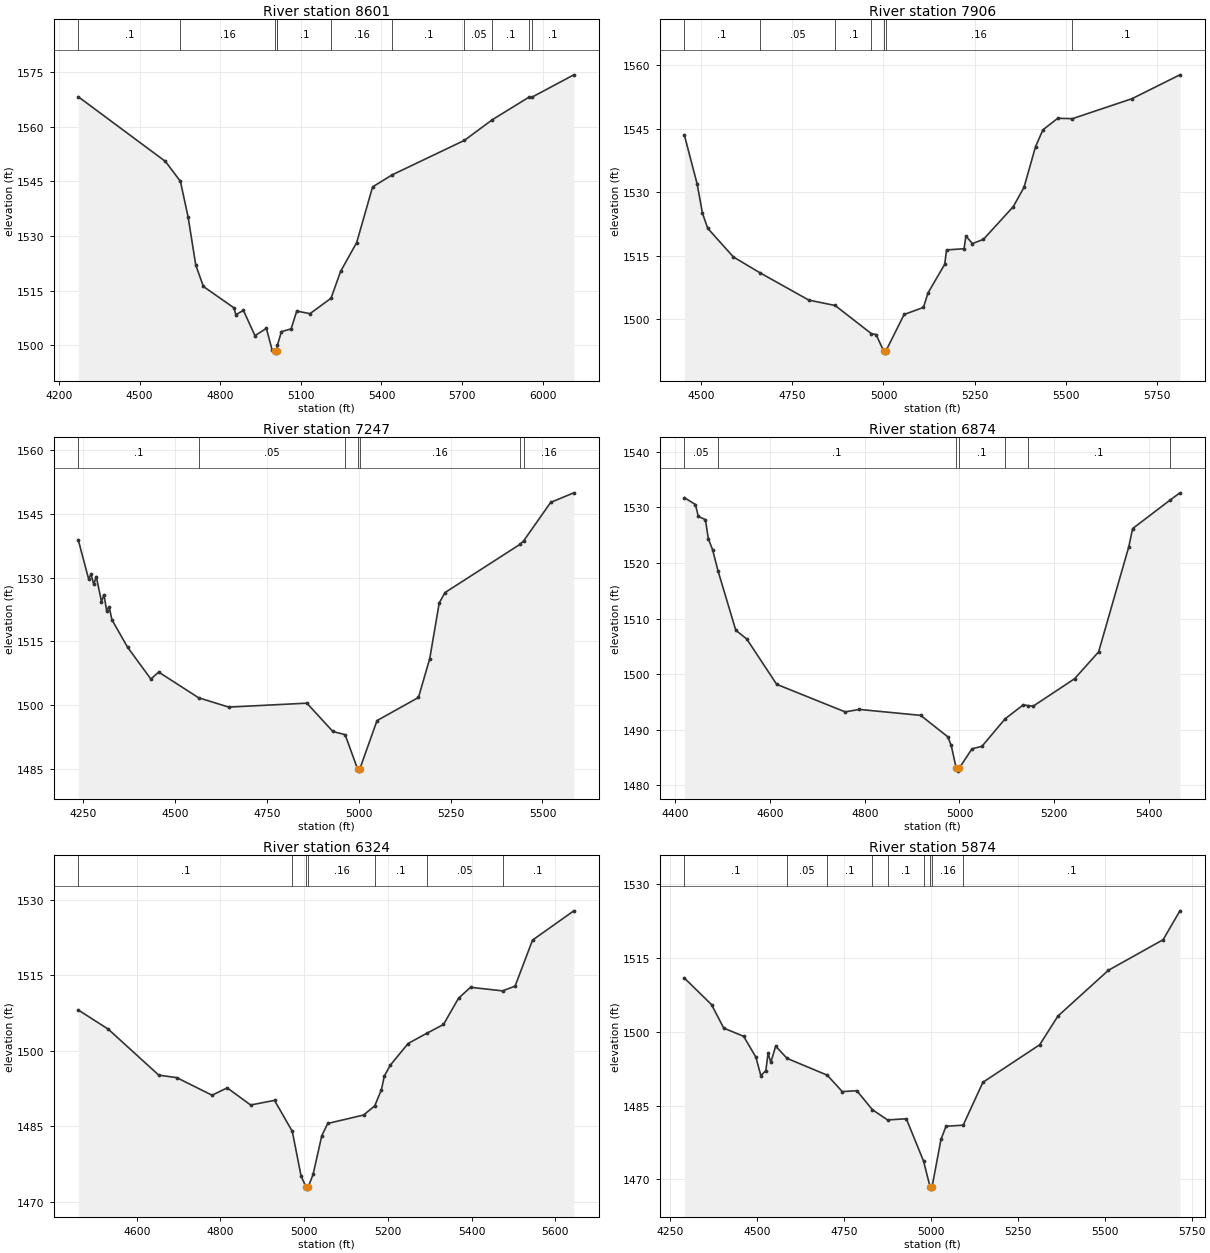
Type RM Length L Ch R = 1 ,8601    ,695,695,695
BEGIN DESCRIPTION:
UNT017 IN SNOGR 17.0
END DESCRIPTION:
XS GIS Cut Line= 3
      2870294.27     10039120.91      2871069.84     10039806.99
      2871824.49     10040094.95
#Sta/Elev= 30
  4272.2 1568.22  4596.3 1550.48    4652 1545.02  4680.7 1535.21  4709.2 1522.01
  4737.6 1516.17  4851.4  1510.3  4858.1 1508.43  4886.5 1509.62  4929.2 1502.69
  4971.8 1504.68  4992.7 1498.88  5003.9 1498.39  5006.7 1497.89  5009.9 1498.39
  5013.1 1500.13  5027.8 1503.78  5063.8 1504.54  5084.7 1509.43  5134.1 1508.72
  5212.3 1512.95  5247.9 1520.32  5307.7 1528.23  5366.9  1543.5  5440.5 1546.83
  5708.7 1556.27  5812.6 1561.94    5949 1568.13  5959.5  1568.1  6115.4 1574.24
#Mann= 11 ,-1 , 0
  4272.2      .1       0    4652     .16       0  5003.9     .07       0
  5009.9     .16       0  5013.1      .1       0  5212.3     .16       0
  5440.5      .1       0  5708.7     .05       0  5812.6      .1       0
    5949     .05       0  5959.5      .1       0
Bank Sta=5003.9,5009.9
XS Rating Curve= 0 ,0
Exp/Cntr=0.3,0.1

Type RM Length L Ch R = 1 ,7906    ,659,659,659
BEGIN DESCRIPTION:
UNT017 IN SNOGR 16.0
END DESCRIPTION:
XS GIS Cut Line= 3
      2870125.25     10039707.58      2870413.58     10039936.25
      2871387.98     10040115.22
#Sta/Elev= 30
  4454.2 1543.43  4489.2 1531.88  4503.7 1524.99  4518.1 1521.44  4588.6 1514.66
  4660.7 1510.96  4795.3 1504.47  4867.5  1503.2    4967 1496.53  4979.7 1496.34
  5000.6 1492.44  5003.3 1491.94  5006.6 1492.44  5056.6 1501.07  5109.7 1502.75
    5122 1506.15  5167.9 1512.93    5173 1516.33    5221 1516.61  5226.1 1519.61
    5244 1517.83  5274.1 1518.83  5355.9 1526.55  5385.4 1531.13  5416.9 1540.71
  5437.2 1544.71  5477.9 1547.44  5518.2 1547.35  5681.2 1552.06  5812.9 1557.71
#Mann= 7 ,-1 , 0
  4454.2      .1       0  4660.7     .05       0  4867.5      .1       0
    4967     .16       0  5000.6     .07       0  5006.6     .16       0
  5518.2      .1       0
Bank Sta=5000.6,5006.6
XS Rating Curve= 0 ,0
Exp/Cntr=0.3,0.1

Type RM Length L Ch R = 1 ,7247    ,373,373,373
BEGIN DESCRIPTION:
UNT017 IN SNOGR 15.0
END DESCRIPTION:
XS GIS Cut Line= 3
        2869817.      10039966.1      2870522.95      10040612.4
      2870910.77     10040672.06
#Sta/Elev= 30
  4235.9 1538.85  4263.8 1529.73  4270.6 1530.79    4278 1528.41  4284.8 1530.25
    4299 1524.34  4305.7 1525.99  4313.1 1522.19  4319.9 1523.13  4327.3 1520.09
  4369.9 1513.63  4433.4 1506.12  4454.8 1507.75  4563.3 1501.71  4645.5  1499.5
  4858.3 1500.43  4929.2 1493.76  4962.5 1493.01  4996.5 1484.92  4999.2 1484.42
  5002.5 1484.92  5049.4 1496.32  5162.3 1501.77    5193 1510.92  5218.8 1524.01
  5234.3 1526.46  5438.8 1537.83  5449.2 1538.71  5522.4 1547.72  5585.4 1549.97
#Mann= 7 ,-1 , 0
  4235.9      .1       0  4563.3     .05       0  4962.5     .16       0
  4996.5     .07       0  5002.5     .16       0  5438.8      .1       0
  5449.2     .16       0
Bank Sta=4996.5,5002.5
XS Rating Curve= 0 ,0
Exp/Cntr=0.3,0.1

Type RM Length L Ch R = 1 ,6874    ,550,550,550
BEGIN DESCRIPTION:
UNT017 IN SNOGR 13.0
END DESCRIPTION:
XS GIS Cut Line= 2
      2869657.87     10040443.35       2870531.9     10041019.42
#Sta/Elev= 30
  4418.9 1531.76  4442.2 1530.52  4448.2 1528.39  4463.3  1527.8  4469.3 1524.38
  4478.4 1522.39  4489.9 1518.57  4527.4 1507.89  4550.6 1506.31  4613.8 1498.15
  4758.4 1493.19  4788.5 1493.63    4918 1492.56  4975.2 1488.71  4982.5 1487.16
  4993.2 1483.02    4996 1482.52  4999.2 1483.02  5026.4 1486.54  5047.5 1486.99
  5096.2 1491.92  5134.8 1494.47  5144.8 1494.31  5155.9 1494.23  5243.2 1499.16
  5293.9 1503.99  5357.6  1522.9  5365.8 1526.19  5443.7 1531.25  5465.7 1532.63
#Mann= 7 ,-1 , 0
  4418.9     .05       0  4489.9      .1       0  4993.2     .07       0
  4999.2      .1       0  5096.2     .16       0  5144.8      .1       0
  5443.7     .05       0
Bank Sta=4993.2,4999.2
XS Rating Curve= 0 ,0
Exp/Cntr=0.3,0.1

Type RM Length L Ch R = 1 ,6324    ,450,450,450
BEGIN DESCRIPTION:
UNT017 IN SNOGR 12.0
END DESCRIPTION:
XS GIS Cut Line= 2
      2869349.63      10040751.6      2870243.99     10041526.71
#Sta/Elev= 30
  4460.5 1508.11  4532.1  1504.3  4652.7 1495.18  4695.5 1494.69    4780  1491.2
  4816.1 1492.66  4872.1 1489.26  4929.1 1490.18  4971.6 1484.03  4992.7 1475.12
    5004 1473.07  5006.7 1472.57    5010 1473.07  5021.2 1475.48  5042.1 1483.19
  5056.3  1485.6  5141.8 1487.27  5168.5 1489.09  5184.6 1492.33  5191.2 1494.96
  5205.5 1497.14  5248.2 1501.46  5292.6 1503.48  5332.7 1505.23  5368.8 1510.46
  5397.3 1512.61  5473.8  1511.9  5503.7 1512.84  5545.4 1521.97    5644 1527.78
#Mann= 7 ,-1 , 0
  4460.5      .1       0  4971.6     .16       0    5004     .07       0
    5010     .16       0  5168.5      .1       0  5292.6     .05       0
  5473.8      .1       0
Bank Sta=5004,5010
XS Rating Curve= 0 ,0
Exp/Cntr=0.3,0.1

Type RM Length L Ch R = 1 ,5874    ,496,496,496
BEGIN DESCRIPTION:
UNT017 IN SNOGR 11.0
END DESCRIPTION:
XS GIS Cut Line= 3
       2868971.8     10040851.06      2869628.05     10041646.51
       2870004.7     10041765.45
#Sta/Elev= 30
  4290.1 1510.87  4368.1 1505.49  4403.2 1500.72  4460.6 1499.05  4495.8 1494.81
  4510.1 1491.06  4524.4 1492.09  4530.9 1495.58  4538.8 1493.78  4552.8 1497.05
  4585.5 1494.57  4701.2 1491.16  4744.6 1487.82  4786.3 1488.01  4831.1 1484.15
  4874.9 1482.07  4928.8 1482.31  4978.4 1473.71    4997 1468.52  4999.7 1468.02
    5003 1468.52  5028.6 1478.14    5043 1480.78  5092.5 1481.01  5149.2 1489.71
  5312.7 1497.34  5365.4 1503.18  5510.5 1512.46  5667.8 1518.66  5716.3 1524.53
#Mann= 9 ,-1 , 0
  4290.1      .1       0  4585.5     .05       0  4701.2      .1       0
  4831.1     .05       0  4874.9      .1       0  4978.4     .16       0
    4997     .07       0    5003     .16       0  5092.5      .1       0
Bank Sta=4997,5003
XS Rating Curve= 0 ,0
Exp/Cntr=0.3,0.1

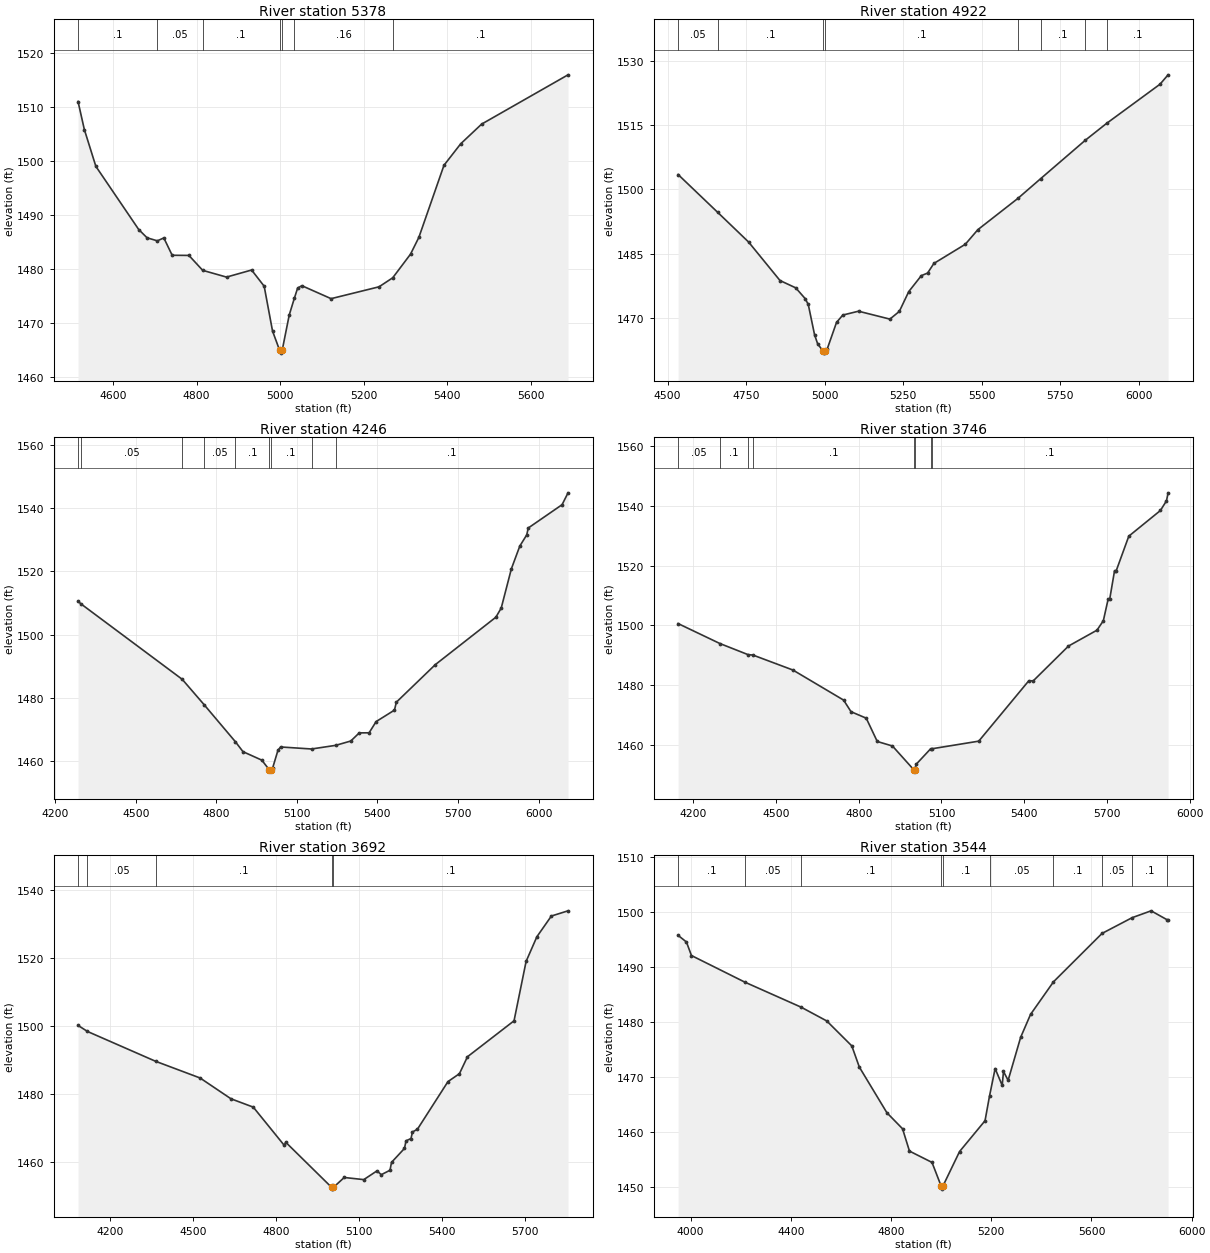
Type RM Length L Ch R = 1 ,5378    ,456,456,456
BEGIN DESCRIPTION:
UNT017 IN SNOGR 10.0
END DESCRIPTION:
XS GIS Cut Line= 2
      2868693.36     10041726.05       2869865.1     10041795.56
#Sta/Elev= 30
    4516 1511.03  4531.1 1505.85  4558.7 1499.03  4661.4 1487.34  4681.4 1485.81
    4706 1485.25  4721.5 1485.79  4741.5 1482.58  4781.6 1482.55  4814.6 1479.79
  4871.7 1478.54  4931.8 1479.85  4961.9 1476.85  4981.9 1468.56    4999 1464.97
  5001.7 1464.47    5005 1464.97    5022 1471.55    5034 1474.58    5042  1476.5
  5052.1 1476.95  5122.2 1474.55    5237 1476.74  5269.8 1478.41  5312.5 1482.79
  5332.5  1485.9  5392.6 1499.23  5432.7 1503.21  5482.8 1506.85  5689.8 1515.97
#Mann= 7 ,-1 , 0
    4516      .1       0    4706     .05       0  4814.6      .1       0
    4999     .07       0    5005      .1       0    5034     .16       0
  5269.8      .1       0
Bank Sta=4999,5005
XS Rating Curve= 0 ,0
Exp/Cntr=0.3,0.1

Type RM Length L Ch R = 1 ,4922    ,676,676,676
BEGIN DESCRIPTION:
UNT017 IN SNOGR 9.0
END DESCRIPTION:
XS GIS Cut Line= 2
      2868593.98     10042183.45      2870154.28     10042183.45
#Sta/Elev= 30
  4533.5 1503.49  4659.1 1494.67    4758 1487.69    4858 1478.68    4908 1476.97
    4938 1474.46    4948 1473.08    4968 1466.01    4978 1463.84    4995 1462.19
  4997.7 1461.69    5001 1462.19    5008 1462.59    5038 1468.88    5058  1470.6
    5108  1471.5    5208 1469.65    5238 1471.46    5268 1476.09    5308 1479.82
    5328 1480.43    5348 1482.68    5448 1487.16    5488 1490.58  5615.5  1497.9
  5688.5 1502.55  5830.5 1511.53  5897.7 1515.44    6068 1524.62  6093.8 1526.82
#Mann= 8 ,-1 , 0
  4533.5     .05       0  4659.1      .1       0    4995     .07       0
    5001      .1       0  5615.5     .05       0  5688.5      .1       0
  5830.5     .05       0  5897.7      .1       0
Bank Sta=4995,5001
XS Rating Curve= 0 ,0
Exp/Cntr=0.3,0.1

Type RM Length L Ch R = 1 ,4246    ,500,500,500
BEGIN DESCRIPTION:
UNT017 IN SNOGR 8.0
END DESCRIPTION:
XS GIS Cut Line= 3
      2868385.09     10042789.99      2869369.52     10042839.71
      2870164.19     10042571.51
#Sta/Elev= 30
  4285.3 1510.52  4297.5 1509.62  4673.2 1485.85  4754.2 1477.88  4871.5 1466.08
  4899.5 1462.97  4969.6 1460.29  4996.6 1457.32  4999.3 1456.82  5002.6 1457.32
  5009.6 1457.73  5029.6  1463.4  5039.6 1464.46  5154.6 1463.82  5244.5 1464.97
  5300.8 1466.34  5332.3 1468.91    5369 1468.94  5395.2 1472.49  5463.4 1476.11
  5470.4 1478.61  5615.5 1490.49    5841 1505.49  5860.9 1508.38  5898.7 1520.79
  5930.1 1527.98  5955.9 1531.52  5961.6  1533.7  6087.5 1541.07  6109.7 1544.82
#Mann= 9 ,-1 , 0
  4285.3      .1       0  4297.5     .05       0  4673.2      .1       0
  4754.2     .05       0  4871.5      .1       0  4996.6     .07       0
  5002.6      .1       0  5154.6     .05       0  5244.5      .1       0
Bank Sta=4996.6,5002.6
XS Rating Curve= 0 ,0
Exp/Cntr=0.3,0.1

Type RM Length L Ch R = 1 ,3746    ,54,54,54
BEGIN DESCRIPTION:
UNT017 IN SNOGR 7.0
END DESCRIPTION:
XS GIS Cut Line= 3
      2868490.82      10043080.9      2869274.23     10043243.66
      2870163.74     10042840.13
#Sta/Elev= 30
    4145 1500.63  4296.5 1493.96  4398.6 1490.24  4416.7 1490.09  4561.4 1485.09
  4745.2 1475.03  4772.1 1471.15  4827.3 1468.98  4867.2 1461.19  4922.4 1459.67
  4999.3 1451.77  5002.1 1451.27  5005.3 1451.77  5007.8 1453.51  5060.8 1458.74
  5065.6 1458.75  5235.3  1461.3  5416.7 1481.49  5432.9 1481.47  5560.7 1493.11
    5664 1498.42  5687.1 1501.58  5704.7  1508.9  5710.2 1508.82  5727.8 1518.34
  5733.3 1518.18  5779.4 1529.87  5894.1 1538.46  5916.1 1541.71  5921.9 1544.37
#Mann= 8 ,-1 , 0
    4145     .05       0  4296.5      .1       0  4398.6     .05       0
  4416.7      .1       0  4999.3     .07       0  5005.3      .1       0
  5060.8     .16       0  5065.6      .1       0
Bank Sta=4999.3,5005.3
XS Rating Curve= 0 ,0
Exp/Cntr=0.3,0.1

Type RM Length L Ch R = 1 ,3692    ,148,148,148
BEGIN DESCRIPTION:
Mapping XS 25f268d1
END DESCRIPTION:
XS GIS Cut Line= 4
      2868464.77     10043135.15      2869267.72     10043280.55
      2869512.95     10043224.13      2870157.43      10042944.2
#Sta/Elev= 30
  4085.6 1500.22  4119.7 1498.43  4365.8 1489.65  4526.4 1484.74  4638.1 1478.61
  4718.7 1476.15  4830.7 1464.89  4835.8 1465.83    5002 1452.51  5004.7 1452.01
    5008 1452.51  5047.3 1455.44  5117.9 1454.81  5165.8 1457.39  5181.1 1456.26
  5212.7 1457.57  5218.1 1459.88    5265    1464  5270.5 1466.22  5288.5 1466.91
  5293.9 1468.83  5311.9 1469.66  5422.1 1483.67  5463.5    1486  5492.5 1490.98
  5660.8 1501.57  5704.4 1519.06  5743.3 1526.31  5795.7 1532.42  5855.9 1533.95
#Mann= 5 ,-1 , 0
  4085.6      .1       0  4119.7     .05       0  4365.8      .1       0
    5002     .07       0    5008      .1       0
Bank Sta=5002,5008
XS Rating Curve= 0 ,0
Exp/Cntr=0.3,0.1

Type RM Length L Ch R = 1 ,3544    ,470,470,470
BEGIN DESCRIPTION:
UNT017 IN SNOGR 6.0
END DESCRIPTION:
XS GIS Cut Line= 3
      2868385.14     10043356.77      2869598.22      10043386.6
      2870313.78     10043585.36
#Sta/Elev= 30
  3949.8 1495.74  3983.1 1494.53  4003.1 1492.07  4215.8 1487.24  4441.2 1482.67
  4543.3 1480.17  4643.3 1475.63  4673.3 1471.78  4783.4 1463.47  4845.8 1460.56
  4873.4  1456.5  4963.4 1454.44  5000.4 1450.08  5003.2 1449.58  5006.4 1450.08
  5073.5 1456.42  5175.1 1462.02    5193 1466.51  5215.4 1471.51  5243.6 1468.45
  5248.8 1470.98  5267.3 1469.37  5317.3 1477.19  5356.8 1481.36  5448.4 1487.29
  5642.2 1496.09  5762.6 1498.96  5838.1  1500.2    5901  1498.6  5905.9 1498.52
#Mann= 10 ,-1 , 0
  3949.8      .1       0  4215.8     .05       0  4441.2      .1       0
  5000.4     .07       0  5006.4      .1       0    5193     .05       0
  5448.4      .1       0  5642.2     .05       0  5762.6      .1       0
    5901     .05       0
Bank Sta=5000.4,5006.4
XS Rating Curve= 0 ,0
Exp/Cntr=0.3,0.1