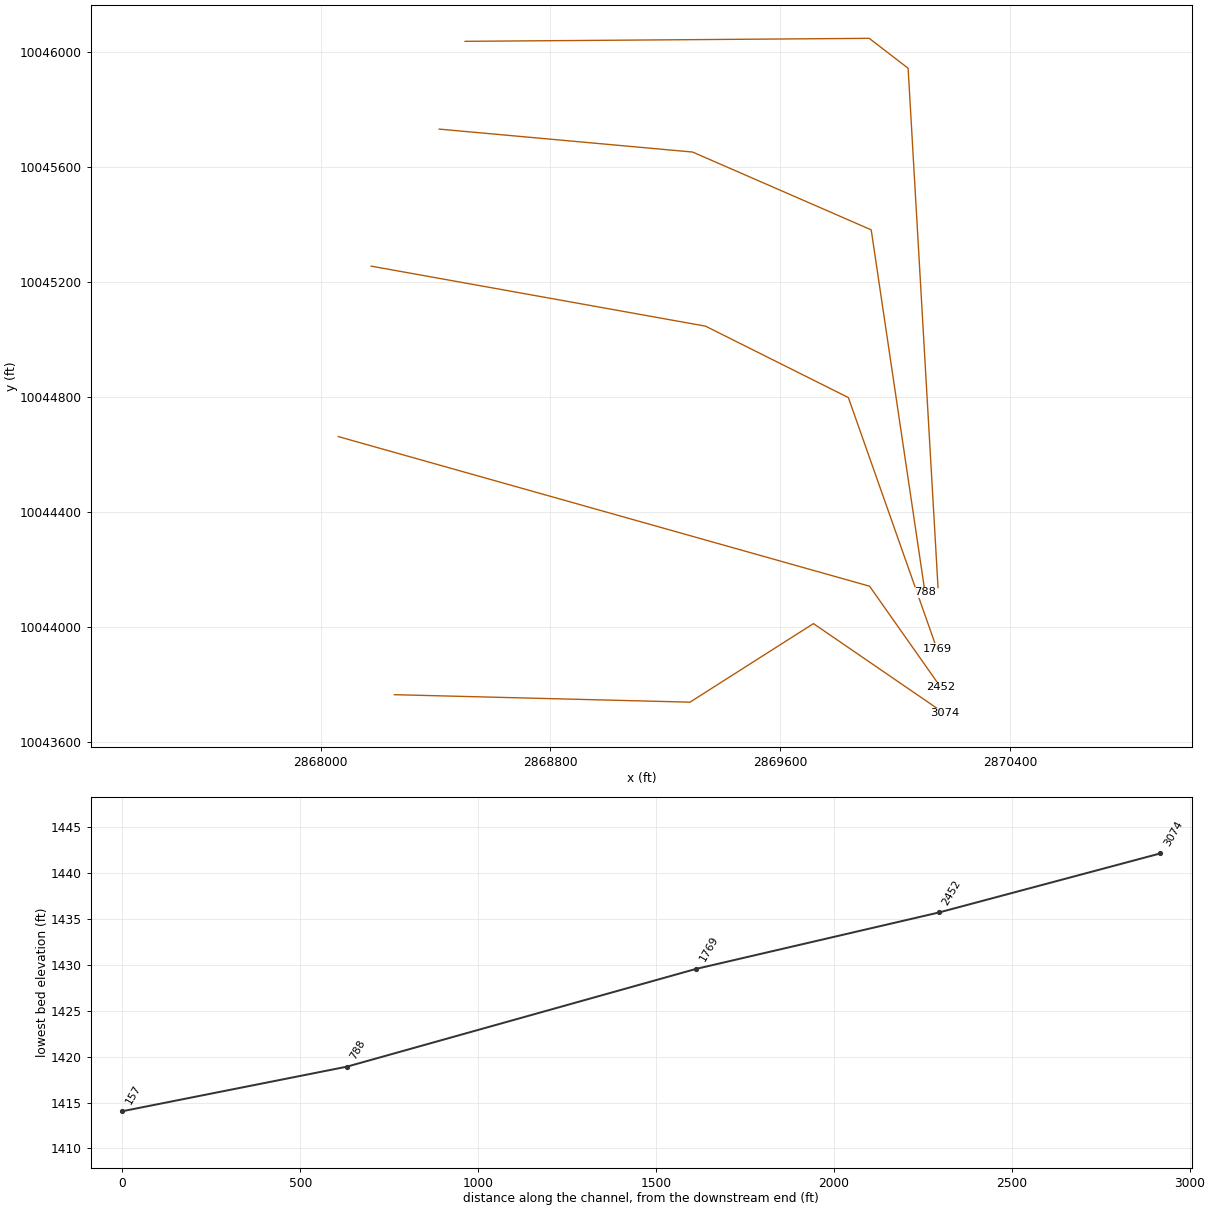
HEC-RAS study UNT017 IN SNOGR.prj: UNT017 IN SNOGR Base Level Engineering

--- UNT017 IN SNOGR.g01 (geometry) --- (continued)

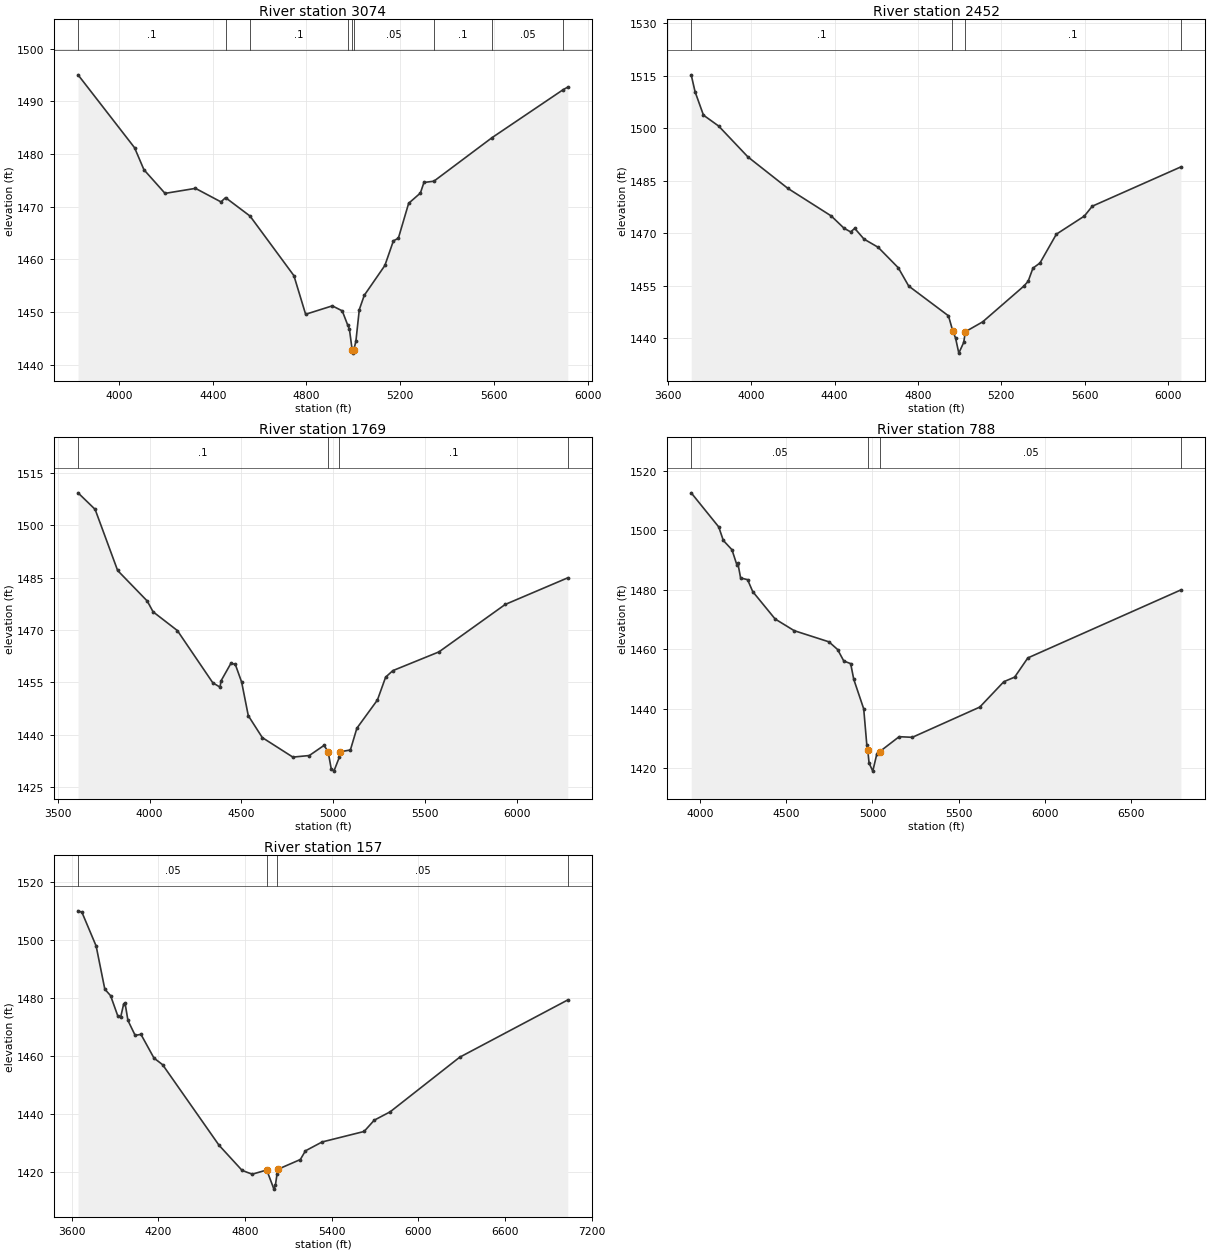
Type RM Length L Ch R = 1 ,3074    ,622,622,622
BEGIN DESCRIPTION:
UNT017 IN SNOGR 5.0
END DESCRIPTION:
XS GIS Cut Line= 4
      2868257.12     10043764.27      2869285.74     10043738.23
      2869715.43     10044011.67      2870171.12      10043699.2
#Sta/Elev= 30
  3824.7 1495.04  4066.1 1481.19  4106.1 1477.01  4196.2 1472.52  4326.2 1473.47
    4435  1470.9  4454.5 1471.71    4559 1468.21  4746.3 1456.89  4796.4 1449.55
  4910.3 1451.15  4952.7  1450.2  4976.4 1447.46  4983.2 1446.76  4995.4 1442.67
  4998.1 1442.17  5001.4 1442.67    5011 1444.43  5025.5 1450.43  5046.7 1453.15
  5134.7 1458.82  5171.1  1463.5  5192.3    1464  5236.2 1470.63  5286.3 1472.58
  5301.5 1474.59  5343.9 1474.83  5591.8 1483.09  5896.5 1492.24  5915.5  1492.7
#Mann= 9 ,-1 , 0
  3824.7      .1       0  4454.5     .05       0    4559      .1       0
  4976.4     .05       0  4995.4    .035       0  5001.4     .05       0
  5343.9      .1       0  5591.8     .05       0  5896.5      .1       0
Bank Sta=4995.4,5001.4
XS Rating Curve= 0 ,0
Exp/Cntr=0.3,0.1

Type RM Length L Ch R = 1 ,2452    ,683,683,683
BEGIN DESCRIPTION:
UNT017 IN SNOGR 3.0
END DESCRIPTION:
XS GIS Cut Line= 3
      2868061.75     10044662.72      2869910.74     10044141.88
      2870158.12     10043790.35
#Sta/Elev= 30
  3711.7 1515.21  3730.3 1510.38  3770.6 1503.69  3843.4 1500.59  3984.1 1491.76
  4175.8 1482.78  4383.6 1474.92  4445.9 1471.37  4477.1 1470.36  4496.8 1471.36
  4541.2  1468.3  4609.3 1465.95  4705.7 1460.11  4755.8 1454.89  4946.7 1446.38
  4965.4 1442.46  4967.4 1441.98  4980.7 1440.05  4996.3 1435.73  5019.9 1438.79
  5027.7 1441.84  5110.8 1444.66  5307.7 1454.83    5329 1456.23  5352.1 1459.99
  5386.1 1461.49  5464.6  1469.7  5599.1 1474.88  5636.9 1477.69  6062.5 1488.92
#Mann= 4 ,-1 , 0
  3711.7      .1       0  4965.4     .05       0  5027.7      .1       0
  6062.5      .1       0
Bank Sta=4967.4,5027.7
XS Rating Curve= 0 ,0
Exp/Cntr=0.3,0.1

Type RM Length L Ch R = 1 ,1769    ,981,981,981
BEGIN DESCRIPTION:
UNT017 IN SNOGR 2.0
END DESCRIPTION:
XS GIS Cut Line= 4
      2868176.35     10045255.94      2869339.69     10045047.14
      2869836.86     10044798.55       2870145.1     10043923.54
#Sta/Elev= 30
  3610.4 1509.33  3703.4 1504.59    3826 1487.07  3987.1 1478.32  4018.9 1475.23
    4151 1469.86  4344.1 1454.88  4383.3 1453.64  4388.4 1455.41  4442.1 1460.42
    4466 1460.22  4500.9 1455.09  4537.1 1445.46  4613.4 1439.18  4779.6 1433.59
  4869.2 1434.04  4949.2 1436.94  4971.5 1435.17  4988.3  1430.3  5003.1 1429.57
    5033  1433.6  5038.6 1435.13  5092.8 1435.63  5128.1 1441.87  5239.9 1449.95
  5284.6  1456.5  5323.7 1458.37  5574.7 1463.74  5935.5 1477.34  6275.9 1484.97
#Mann= 4 ,-1 , 0
  3610.4      .1       0  4971.5     .05       0    5033      .1       0
  6275.9      .1       0
Bank Sta=4971.5,5038.6
XS Rating Curve= 0 ,0
Exp/Cntr=0.3,0.1

Type RM Length L Ch R = 1 ,788     ,631,631,631
BEGIN DESCRIPTION:
Mapping XS ccf00d29
END DESCRIPTION:
XS GIS Cut Line= 4
      2868412.99       10045733.      2869294.89     10045653.14
      2869916.42     10045382.31      2870103.67     10044120.11
#Sta/Elev= 30
  3949.1 1512.65  4108.8 1501.16  4135.3 1496.61  4185.5 1493.48  4214.4  1488.3
  4219.4 1489.02  4235.7 1483.96  4275.9 1483.41    4306 1479.37  4435.8 1470.15
  4546.4 1466.22  4747.8 1462.46    4798 1459.87  4833.9    1456  4873.7 1455.12
  4891.7 1449.83  4949.4 1439.88  4967.4 1427.68  4972.8 1426.09  4980.3 1421.66
  5001.9 1418.91  5025.1 1424.61  5043.1 1425.52  5154.8 1430.51  5231.2  1430.3
  5622.3 1440.48  5761.9 1449.04  5824.5 1450.57  5900.9 1457.04  6788.6 1479.95
#Mann= 4 ,-1 , 0
  3949.1     .05       0  4972.8    .035       0  5043.1     .05       0
  6788.6      .1       0
Bank Sta=4972.8,5043.1
XS Rating Curve= 0 ,0
Exp/Cntr=0.3,0.1

Type RM Length L Ch R = 1 ,157     ,0,0,0
BEGIN DESCRIPTION:
UNT017 IN SNOGR 1.0
END DESCRIPTION:
XS GIS Cut Line= 4
      2868503.18     10046038.56      2869909.47     10046048.98
      2870044.89     10045944.81      2870148.97     10044137.28
#Sta/Elev= 30
  3644.9 1510.05  3671.7 1509.57  3770.2 1497.91  3830.2 1483.02  3870.2 1480.78
  3920.2 1473.76  3940.2 1473.48  3960.2  1477.8  3970.2 1478.19  3990.2 1472.23
  4040.2 1467.08  4080.2 1467.44  4170.2 1459.27  4230.2 1456.96  4620.2 1429.19
  4780.2 1420.49  4850.2  1419.2  4950.2 1420.65    5000 1414.05  5010.2 1415.39
  5021.7  1419.3  5030.2 1420.95  5182.6 1424.26    5218 1427.26  5333.3 1430.32
  5623.8 1433.94  5693.9 1437.83  5804.1 1440.72  6284.9 1459.55  7032.6 1479.31
#Mann= 4 ,-1 , 0
  3644.9     .05       0  4950.2    .035       0  5021.7     .05       0
  7032.6      .1       0
Bank Sta=4950.2,5030.2
XS Rating Curve= 0 ,0
Exp/Cntr=0.3,0.1

Chan Stop Cuts=-1
Use User Specified Reach Order=0
Composite Channel Slope=5