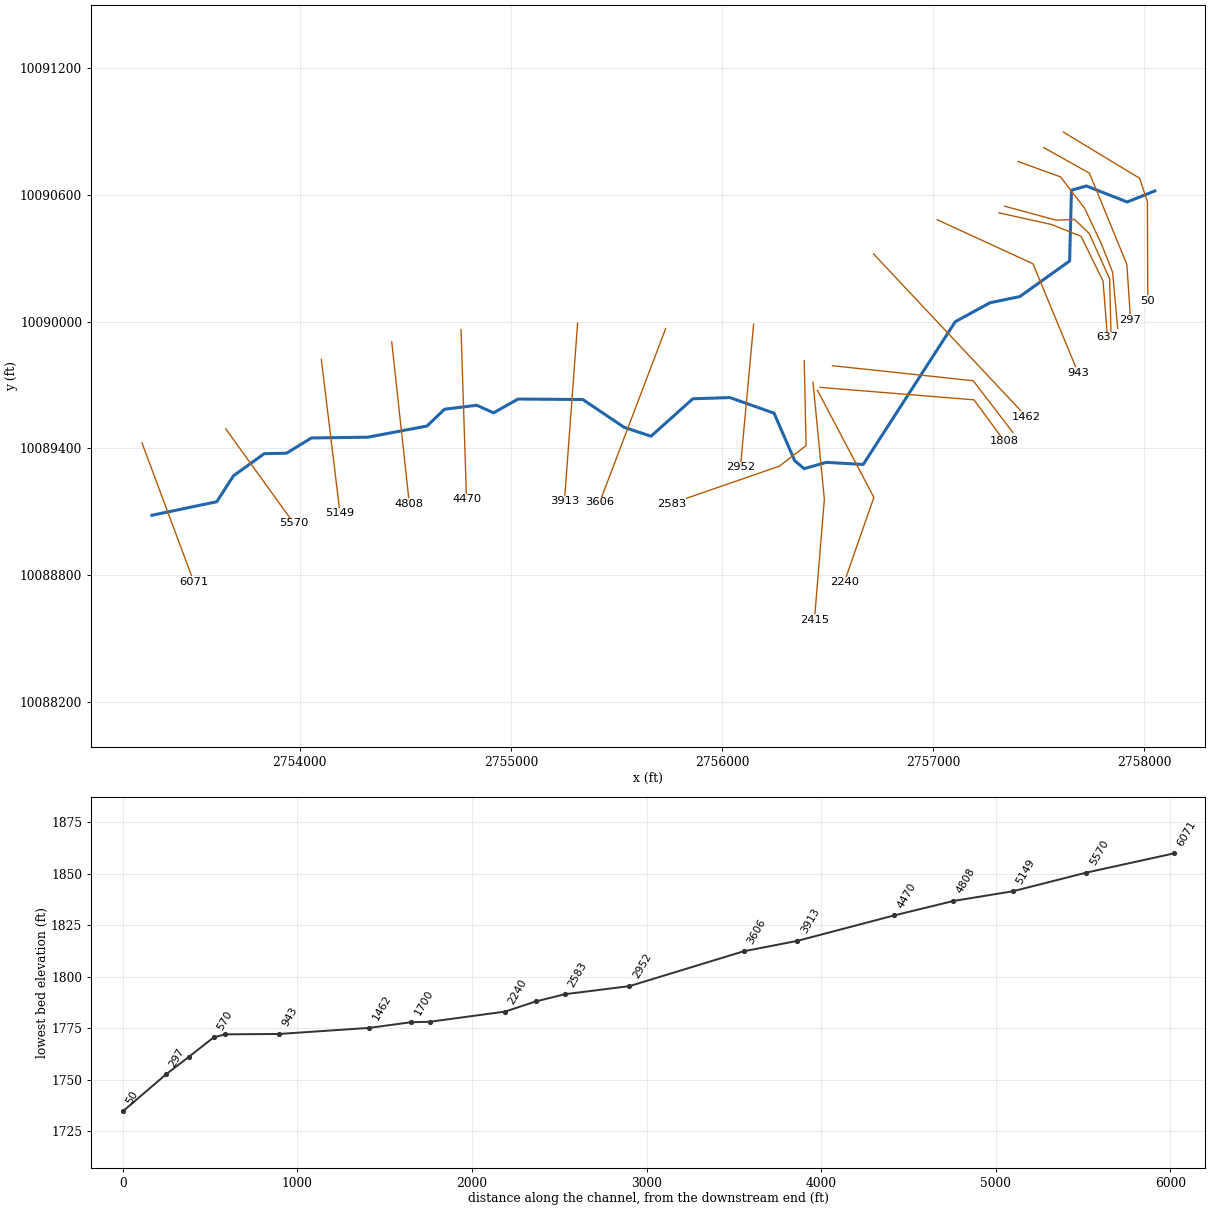
--- UNT018 IN NNOGR.prj (project) ---

Proj Title=UNT018 IN NNOGR Base Level Engineering
Current Plan=p01
Default Exp/Contr=0.3,0.1
English Units
Geom File=g01
Flow File=f01
Plan File=p01
Y Axis Title=Elevation
X Axis Title(PF)=Main Channel Distance
X Axis Title(XS)=Station
BEGIN DESCRIPTION:
UNT018 IN NNOGR
END DESCRIPTION:
DSS Export Rating Curves= 0
DSS Export Rating Curve Sorted= 0
DSS Export Volume Flow Curves= 0
DXF OffsetX= 0
DXF OffsetY= 0
DXF ScaleX= 1
DXF ScaleY= 10

--- UNT018 IN NNOGR.p01 (plan) ---

Plan Title=Multiple Run
Short Identifier=Multiple
Geom File=g01
Flow File=f01
Subcritical Flow
K Sum by GR= 0
Std Step Tol= 0.01
Critical Tol= 0.01
Num of Std Step Trials= 20
Max Error Tol= 0.3
Flow Tol Ratio= 0.001
Split Flow NTrial= 30
Split Flow Tol= 0.02
Split Flow Ratio= 0.02
Log Output Level= 0
Friction Slope Method= 1
Unsteady Friction Slope Method= 2
Unsteady Bridges Friction Slope Method= 1
Parabolic Critical Depth
Global Vel Dist=  1 , 1 , 1
Global Log Level= 0
CheckData=True
Encroach Param= -1, 0, 0, 0
BEGIN DESCRIPTION:
Multiple Run
END DESCRIPTION:

--- UNT018 IN NNOGR.f01 (steady flow) ---

Flow Title=Multiple
Program Version=4.10
Number of Profiles= 7
Profile Names=10-year,25-year,50-year,1pct_min,100-year,1pct_plu,500-year
River Rch & RM=UNT018 IN NNOGR,Reach-1         ,6071
     804    1168    1485    1384    1872    2531    2983
River Rch & RM=UNT018 IN NNOGR,Reach-1         ,2583
    1224    1822    2353    2224    3008    4068    4936
Boundary for River Rch & Prof#=UNT018 IN NNOGR,Reach-1         , 1
Up Type= 0
Dn Type= 3
Dn Slope=0.0687
Boundary for River Rch & Prof#=UNT018 IN NNOGR,Reach-1         , 2
Up Type= 0
Dn Type= 3
Dn Slope=0.0687
Boundary for River Rch & Prof#=UNT018 IN NNOGR,Reach-1         , 3
Up Type= 0
Dn Type= 3
Dn Slope=0.0687
Boundary for River Rch & Prof#=UNT018 IN NNOGR,Reach-1         , 4
Up Type= 0
Dn Type= 3
Dn Slope=0.0687
Boundary for River Rch & Prof#=UNT018 IN NNOGR,Reach-1         , 5
Up Type= 0
Dn Type= 3
Dn Slope=0.0687
Boundary for River Rch & Prof#=UNT018 IN NNOGR,Reach-1         , 6
Up Type= 0
Dn Type= 3
Dn Slope=0.0687
Boundary for River Rch & Prof#=UNT018 IN NNOGR,Reach-1         , 7
Up Type= 0
Dn Type= 3
Dn Slope=0.0687
DSS Import GetInterval= 0
DSS Import GetPeak= 0
DSS Import FillOption= 0

--- UNT018 IN NNOGR.g01 (geometry) ---

Geom Title=Existing Conditions
Program Version=4.10

River Reach=UNT018 IN NNOGR ,Reach-1
Reach XY= 30
      2753300.54     10089082.93      2753607.24     10089146.97
       2753686.2     10089269.67      2753832.04     10089374.42
      2753937.29     10089376.64      2754055.53     10089448.93
      2754321.84     10089452.52      2754603.18     10089505.48
      2754685.42     10089584.83      2754838.39     10089603.74
      2754917.92      10089567.8       2755033.7     10089633.09
      2755340.37     10089631.06      2755536.09     10089499.36
      2755663.57     10089457.06      2755861.48     10089634.45
      2756037.33     10089640.09      2756246.33     10089566.25
      2756343.91     10089341.23      2756388.47     10089303.73
      2756493.74     10089333.38       2756668.4     10089323.49
      2757104.46     10089999.57      2757268.61       10090089.
       2757410.1     10090118.51      2757645.78     10090286.92
      2757654.46     10090621.99      2757724.99     10090641.95
      2757918.57     10090566.21      2758049.02     10090618.36

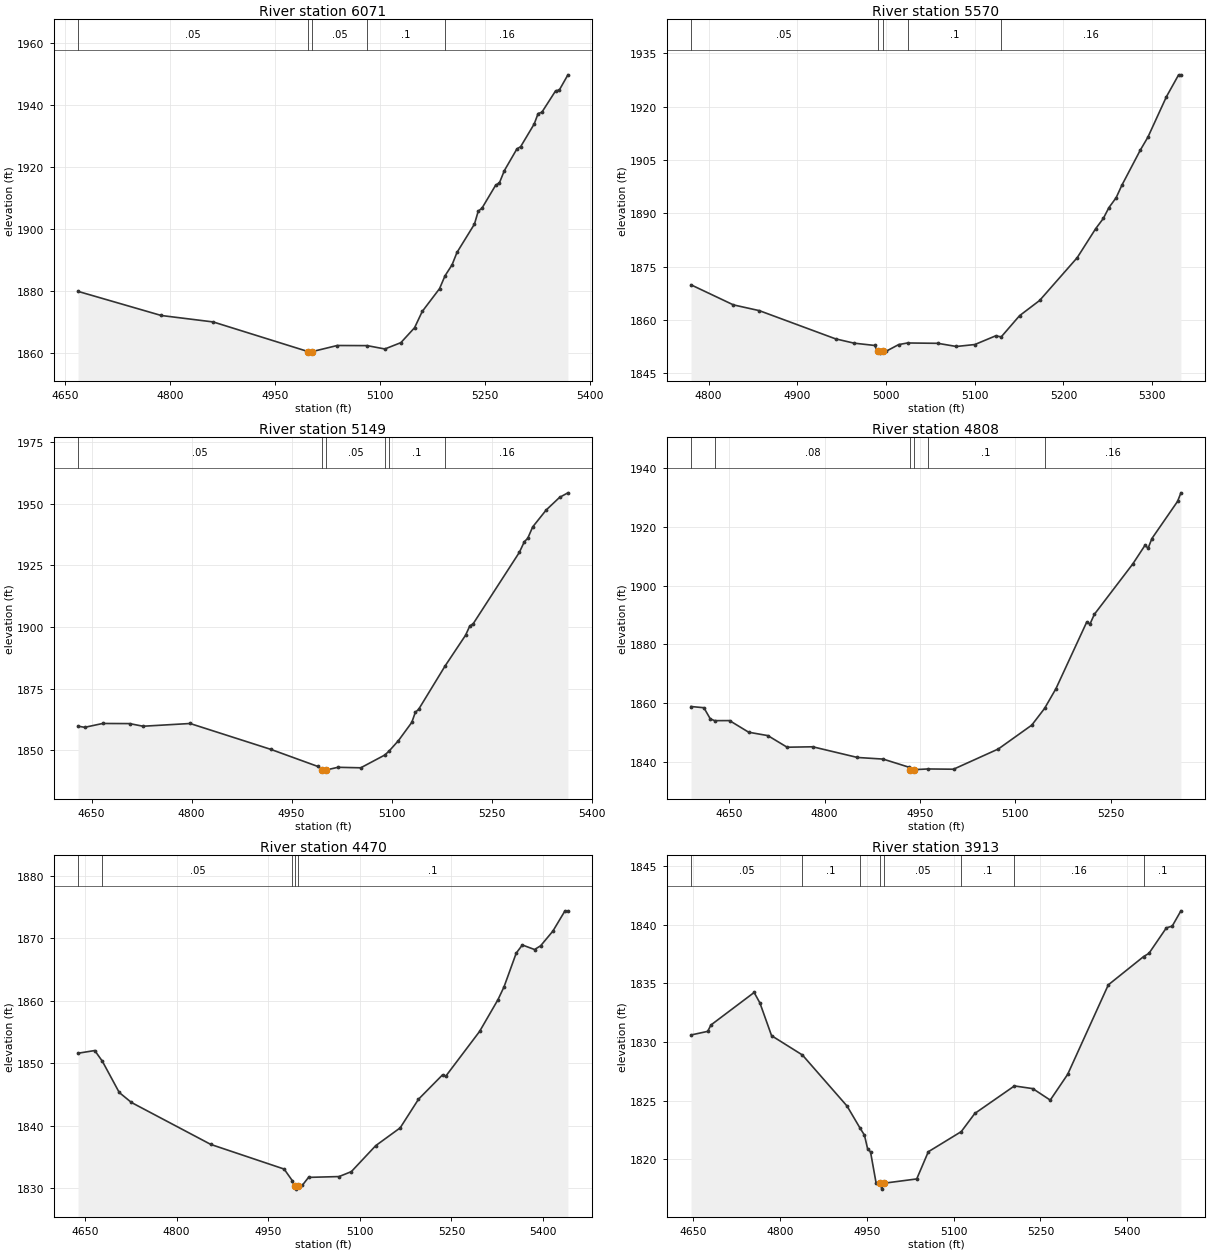
Type RM Length L Ch R = 1 ,6071    ,501,501,501
BEGIN DESCRIPTION:
UNT018 IN NNOGR 14.0
END DESCRIPTION:
XS GIS Cut Line= 2
      2753253.53      10089424.7      2753498.28     10088768.57
#Sta/Elev= 30
  4668.7 1879.86  4787.7 1872.08  4861.9    1870  4997.6 1860.44  5000.4 1859.94
  5003.6 1860.44  5039.2  1862.4  5082.1 1862.36  5107.3 1861.28  5130.2 1863.32
  5149.8 1868.14  5160.7 1873.37  5185.5 1880.75  5193.3 1884.88  5203.4 1888.44
  5210.4 1892.42  5235.4 1901.57  5240.8 1905.75  5246.1 1906.69  5265.7 1914.12
  5271.1 1914.88  5278.1 1918.81  5296.1 1925.83  5301.4 1926.54  5320.8 1933.87
  5326.4 1937.24  5331.7 1937.63  5351.4 1944.56  5356.7 1944.83    5369 1949.72
#Mann= 5 ,-1 , 0
  4668.7     .05       0  4997.6    .035       0  5003.6     .05       0
  5082.1      .1       0  5193.3     .16       0
Bank Sta=4997.6,5003.6
XS Rating Curve= 0 ,0
Exp/Cntr=0.3,0.1

Type RM Length L Ch R = 1 ,5570    ,421,421,421
BEGIN DESCRIPTION:
UNT018 IN NNOGR 13.0
END DESCRIPTION:
XS GIS Cut Line= 2
      2753649.36     10089492.42      2753972.28     10089044.49
#Sta/Elev= 30
  4780.2 1869.85  4827.9 1864.21  4857.2 1862.58  4943.1 1854.64  4963.9 1853.43
  4987.2 1852.78  4990.4 1851.12  4993.1 1850.62  4996.4 1851.12  5000.5  1851.2
  5014.2 1853.02  5024.2 1853.48  5058.4 1853.38  5079.3 1852.49  5100.1 1853.04
  5123.4 1855.47  5129.9 1855.21  5150.5 1861.16  5173.1 1865.44  5215.5  1877.5
  5236.3 1885.66  5244.9 1888.53  5251.1 1891.54  5259.4 1894.39  5265.8 1897.88
  5286.7 1907.82  5295.2 1911.44  5316.1 1922.84  5329.8 1928.98  5332.4 1928.98
#Mann= 5 ,-1 , 0
  4780.2     .05       0  4990.4    .035       0  4996.4     .05       0
  5024.2      .1       0  5129.9     .16       0
Bank Sta=4990.4,4996.4
XS Rating Curve= 0 ,0
Exp/Cntr=0.3,0.1

Type RM Length L Ch R = 1 ,5149    ,341,341,341
BEGIN DESCRIPTION:
UNT018 IN NNOGR 12.0
END DESCRIPTION:
XS GIS Cut Line= 2
      2754102.49     10089820.51      2754191.03     10089091.37
#Sta/Elev= 30
  4629.8 1859.78  4639.8 1859.31  4666.8 1860.87  4707.1 1860.82  4727.3 1859.75
  4797.8 1860.86  4918.7 1850.39  4989.2 1843.47  4996.3 1842.06    4999 1841.56
  5002.3 1842.06  5019.4 1843.11  5053.7 1842.91  5089.6 1848.07    5096 1849.64
  5110.1 1853.89  5130.2 1861.31  5135.5 1865.39  5140.5 1866.62  5180.2  1884.2
  5210.8 1896.62  5217.2 1900.39  5222.3  1901.3  5291.4 1930.18    5299 1934.54
    5304 1935.88  5311.5 1940.53  5331.7 1947.37  5351.8 1952.49  5364.3 1954.33
#Mann= 6 ,-1 , 0
  4629.8     .05       0  4996.3     .07       0  5002.3     .05       0
  5089.6     .05       0    5096      .1       0  5180.2     .16       0
Bank Sta=4996.3,5002.3
XS Rating Curve= 0 ,0
Exp/Cntr=0.3,0.1

Type RM Length L Ch R = 1 ,4808    ,338,338,338
BEGIN DESCRIPTION:
UNT018 IN NNOGR 11.0
END DESCRIPTION:
XS GIS Cut Line= 2
      2754435.82     10089903.83      2754519.13     10089138.45
#Sta/Elev= 30
  4590.2 1858.83  4610.4 1858.42  4620.5 1854.61  4627.4 1854.02  4650.7 1854.04
  4680.8 1850.08    4711 1848.92  4741.2 1844.97  4781.4 1845.12  4851.8 1841.48
  4892.1 1840.93  4932.3 1838.19  4934.7 1837.33  4937.5 1836.83  4940.7 1837.33
  4962.5 1837.57  5002.7 1837.48  5073.1 1844.37  5125.7  1852.5  5145.8 1858.18
  5163.7 1864.92  5212.1 1887.61  5217.2 1886.92    5224 1890.21  5284.4 1907.37
  5303.6 1913.71  5308.6 1912.77  5314.5 1916.04  5354.8 1928.68  5360.1  1931.6
#Mann= 6 ,-1 , 0
  4590.2     .05       0  4627.4     .08       0  4934.7     .07       0
  4940.7     .08       0  4962.5      .1       0  5145.8     .16       0
Bank Sta=4934.7,4940.7
XS Rating Curve= 0 ,0
Exp/Cntr=0.3,0.1

Type RM Length L Ch R = 1 ,4470    ,557,557,557
BEGIN DESCRIPTION:
UNT018 IN NNOGR 10.0
END DESCRIPTION:
XS GIS Cut Line= 2
      2754763.94     10089961.15      2754789.98     10089159.08
#Sta/Elev= 30
  4638.4 1851.59  4665.8 1852.02  4678.3  1850.3  4705.9 1845.31  4725.9 1843.71
  4855.9    1837    4976 1833.06  4989.3 1831.22    4993 1830.35  4995.8 1829.85
    4999 1830.35    5006 1830.49    5016 1831.73    5066 1831.86  5086.1 1832.65
  5126.1 1836.81  5166.1 1839.65  5196.1 1844.23  5235.6 1848.14  5240.6 1847.89
  5296.2 1855.08  5326.2 1860.14  5336.2  1862.2  5356.2  1867.6  5366.2 1868.91
  5386.2 1868.18  5396.2 1868.78  5416.2 1871.12  5436.1 1874.37  5440.9 1874.37
#Mann= 5 ,-1 , 0
  4638.4     .08       0  4678.3     .05       0  4989.3      .1       0
    4993     .07       0    4999      .1       0
Bank Sta=4993,4999
XS Rating Curve= 0 ,0
Exp/Cntr=0.3,0.1

Type RM Length L Ch R = 1 ,3913    ,307,307,307
BEGIN DESCRIPTION:
UNT018 IN NNOGR 9.0
END DESCRIPTION:
XS GIS Cut Line= 2
      2755316.03     10089992.45      2755253.53     10089148.67
#Sta/Elev= 30
  4646.6  1830.6  4675.4 1830.91  4680.9 1831.45  4755.6 1834.23  4765.6 1833.33
  4785.7 1830.54    4839 1828.89  4916.1 1824.53  4937.9  1822.7  4946.1 1822.05
  4951.6 1820.88  4956.6 1820.62  4966.2 1817.97  4973.2 1817.94    4976 1817.44
  4979.2 1817.94  5036.4 1818.31  5056.4 1820.63  5113.3 1822.35  5136.7  1823.9
  5205.1 1826.25  5236.9 1826.02    5267 1825.04  5297.1 1827.24  5367.3 1834.88
  5428.4  1837.3  5437.5 1837.57  5467.6 1839.75  5477.6 1839.89  5492.7  1841.2
#Mann= 8 ,-1 , 0
  4646.6     .05       0    4839      .1       0  4937.9     .05       0
  4973.2    .035       0  4979.2     .05       0  5113.3      .1       0
  5205.1     .16       0  5428.4      .1       0
Bank Sta=4973.2,4979.2
XS Rating Curve= 0 ,0
Exp/Cntr=0.3,0.1

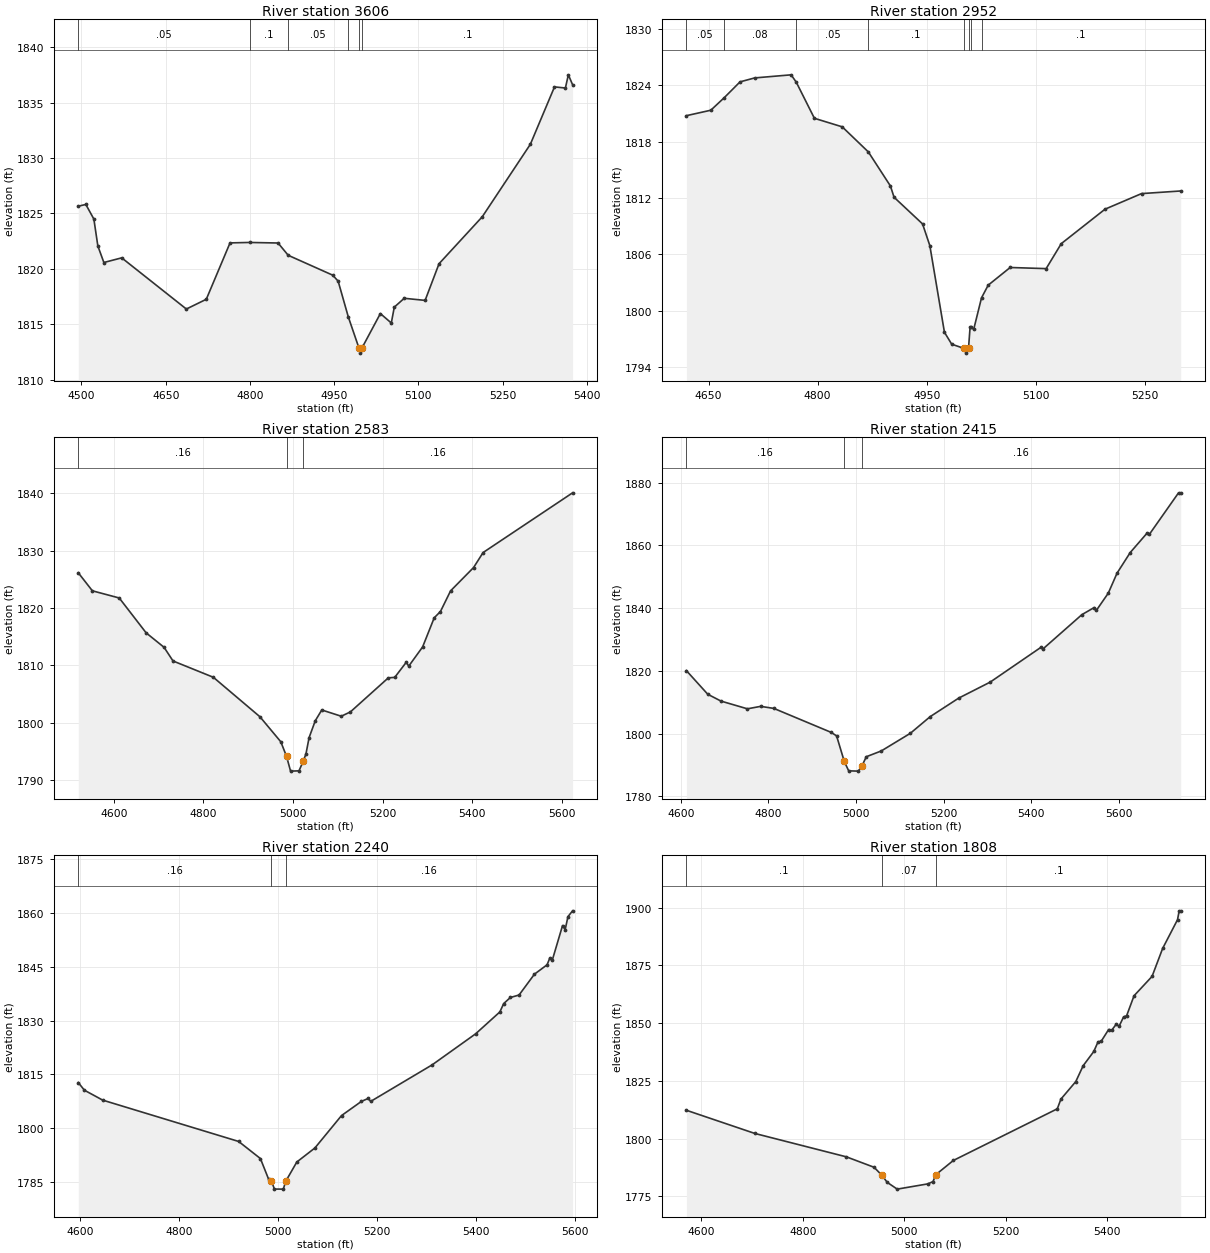
Type RM Length L Ch R = 1 ,3606    ,654,654,654
BEGIN DESCRIPTION:
UNT018 IN NNOGR 8.0
END DESCRIPTION:
XS GIS Cut Line= 2
       2755732.7     10089966.39      2755420.18     10089143.43
#Sta/Elev= 30
  4494.3 1825.65  4507.8 1825.81  4522.1 1824.49  4529.2 1822.06  4539.9 1820.57
  4571.7 1820.99  4686.8 1816.37  4722.3 1817.25  4764.6 1822.34  4799.3 1822.38
  4850.1 1822.33  4868.2 1821.22  4947.3 1819.43  4957.1 1818.89  4975.2 1815.66
  4993.9 1812.89  4996.6 1812.39  4999.9 1812.89  5032.3 1815.96  5051.8 1815.11
  5057.1 1816.54  5074.8 1817.34    5112 1817.15  5136.8 1820.46  5213.8  1824.7
  5299.4 1831.24  5342.4 1836.42  5361.8 1836.32  5367.1 1837.51  5374.6 1836.62
#Mann= 6 ,-1 , 0
  4494.3     .05       0  4799.3      .1       0  4868.2     .05       0
  4975.2      .1       0  4993.9     .07       0  4999.9      .1       0
Bank Sta=4993.9,4999.9
XS Rating Curve= 0 ,0
Exp/Cntr=0.3,0.1

Type RM Length L Ch R = 1 ,2952    ,369,369,369
BEGIN DESCRIPTION:
UNT018 IN NNOGR 7.0
END DESCRIPTION:
XS GIS Cut Line= 2
      2756149.36     10089987.22      2756086.86      10089310.1
#Sta/Elev= 30
  4619.5 1820.76  4653.1 1821.34  4671.5 1822.67  4693.3 1824.36  4713.4 1824.78
  4763.6 1825.11  4770.7 1824.32  4795.6 1820.48  4833.9 1819.57  4869.8  1816.9
  4900.2 1813.27  4905.2 1812.07  4944.4 1809.23  4954.4 1806.92  4974.5 1797.69
  4984.5 1796.42  5001.6 1795.97  5004.4 1795.47  5007.6 1795.97  5009.8 1798.26
  5010.9 1798.21  5014.8 1798.02  5025.5 1801.36  5034.7 1802.71  5064.9 1804.59
  5114.4 1804.47  5135.2 1807.13  5195.4  1810.8  5245.6 1812.46  5299.5 1812.74
#Mann= 8 ,-1 , 0
  4619.5     .05       0  4671.5     .08       0  4770.7     .05       0
  4869.8      .1       0  5001.6     .07       0  5007.6      .1       0
  5010.9     .08       0  5025.5      .1       0
Bank Sta=5001.6,5007.6
XS Rating Curve= 0 ,0
Exp/Cntr=0.3,0.1

Type RM Length L Ch R = 1 ,2583    ,168,168,168
BEGIN DESCRIPTION:
UNT018 IN NNOGR 6.0
END DESCRIPTION:
XS GIS Cut Line= 4
       2756389.1     10089815.26      2756397.78     10089412.51
      2756271.05     10089315.29      2755759.63     10089138.46
#Sta/Elev= 30
  4520.4 1826.13  4551.9 1822.98  4611.9 1821.73    4672 1815.65    4712 1813.13
    4732 1810.75    4822 1807.91    4926 1801.03  4972.6 1796.67  4985.4 1794.14
 4994.43 1791.55 5013.31  1791.6  5022.5 1793.26  5028.8 1794.54  5035.8 1797.39
  5049.6 1800.33  5064.1 1802.21  5107.6 1801.12    5128 1801.87  5212.7 1807.81
    5227 1807.89  5252.9 1810.54  5258.2 1809.84  5289.3  1813.2  5315.2 1818.28
  5329.1 1819.37  5351.7 1822.97  5403.1 1827.04  5424.3 1829.65  5624.1 1840.06
#Mann= 3 , 0 , 0
  4520.4     .16       0  4985.4     .07       0  5022.5     .16       0
Bank Sta=4985.4,5022.5
XS Rating Curve= 0 ,0
Exp/Cntr=0.3,0.1

Type RM Length L Ch R = 1 ,2415    ,175,175,175
BEGIN DESCRIPTION:
Mapping XS 6ec5cd0d
END DESCRIPTION:
XS GIS Cut Line= 3
      2756430.57     10089712.33      2756484.39     10089158.56
      2756437.51     10088589.06
#Sta/Elev= 30
  4612.9 1820.08  4661.7 1812.54  4691.9 1810.36  4752.1  1807.9  4782.3 1808.68
  4812.4 1808.03    4943  1800.4  4955.6 1799.27  4973.2  1791.1  4983.2 1788.12
 5005.28 1788.03  5013.4 1789.68  5023.4 1792.62  5057.5 1794.46  5123.9 1800.09
  5169.2 1805.41  5234.3 1811.32    5306 1816.41  5422.1 1827.53  5427.1 1827.07
  5515.3 1837.93  5543.3 1840.19  5548.3 1839.29  5575.5 1844.78  5595.5 1851.16
  5625.6 1857.74  5664.4 1863.99  5669.4 1863.57  5735.8 1876.77  5740.7 1876.77
#Mann= 3 , 0 , 0
  4612.9     .16       0  4973.2     .07       0  5013.4     .16       0
Bank Sta=4973.2,5013.4
XS Rating Curve= 0 ,0
Exp/Cntr=0.3,0.1

Type RM Length L Ch R = 1 ,2240    ,432,432,432
BEGIN DESCRIPTION:
UNT018 IN NNOGR 5.0
END DESCRIPTION:
XS GIS Cut Line= 3
       2756451.6     10089674.66      2756718.96     10089167.72
      2756578.35     10088764.99
#Sta/Elev= 30
  4596.2 1812.76  4608.6 1810.63  4645.6 1807.87  4920.6 1796.37  4964.6 1791.61
    4981 1785.93  4986.7 1785.45  4992.9 1783.13 5010.94 1783.11  5015.6 1785.24
  5038.2 1790.65  5074.8 1794.56  5128.6 1803.57  5168.8 1807.51  5182.4 1808.33
  5187.7 1807.52  5311.9 1817.68  5399.8 1826.31  5448.9 1832.41  5456.6 1834.73
  5470.1 1836.42  5487.7 1837.11  5518.8 1842.91  5544.3 1845.51  5549.8 1847.37
  5555.1 1846.91  5575.6 1856.43  5580.9 1855.31  5586.6 1858.92  5595.9 1860.53
#Mann= 3 , 0 , 0
  4596.2     .16       0  4986.7     .07       0  5015.6     .16       0
Bank Sta=4986.7,5015.6
XS Rating Curve= 0 ,0
Exp/Cntr=0.3,0.1

Type RM Length L Ch R = 1 ,1808    ,108,108,108
BEGIN DESCRIPTION:
UNT018 IN NNOGR 4.0
END DESCRIPTION:
XS GIS Cut Line= 3
      2756463.78     10089688.55      2757192.92     10089629.53
        2757337.     10089433.38
#Sta/Elev= 30
  4570.2  1812.3  4705.3 1802.25  4885.9 1792.12  4940.4 1787.61  4956.1 1784.08
  4966.2  1781.1    4986 1778.15  5046.4 1780.42  5056.5 1781.41  5062.6 1784.48
  5096.6 1790.55  5301.7 1812.92  5308.9 1817.14  5338.2 1824.72  5352.8 1831.61
  5373.7 1837.75  5382.1 1841.93  5388.3 1842.17    5403 1847.26  5409.2 1847.02
  5417.6 1849.44  5423.8 1848.75  5432.3 1852.65  5438.5 1853.25  5453.1 1861.88
  5488.6 1870.25  5509.5 1882.37  5538.8 1894.79  5542.1 1898.65  5545.1 1898.65
#Mann= 3 , 0 , 0
  4570.2      .1       0  4956.1     .07       0  5062.6      .1       0
Bank Sta=4956.1,5062.6
XS Rating Curve= 0 ,0
Exp/Cntr=0.3,0.1

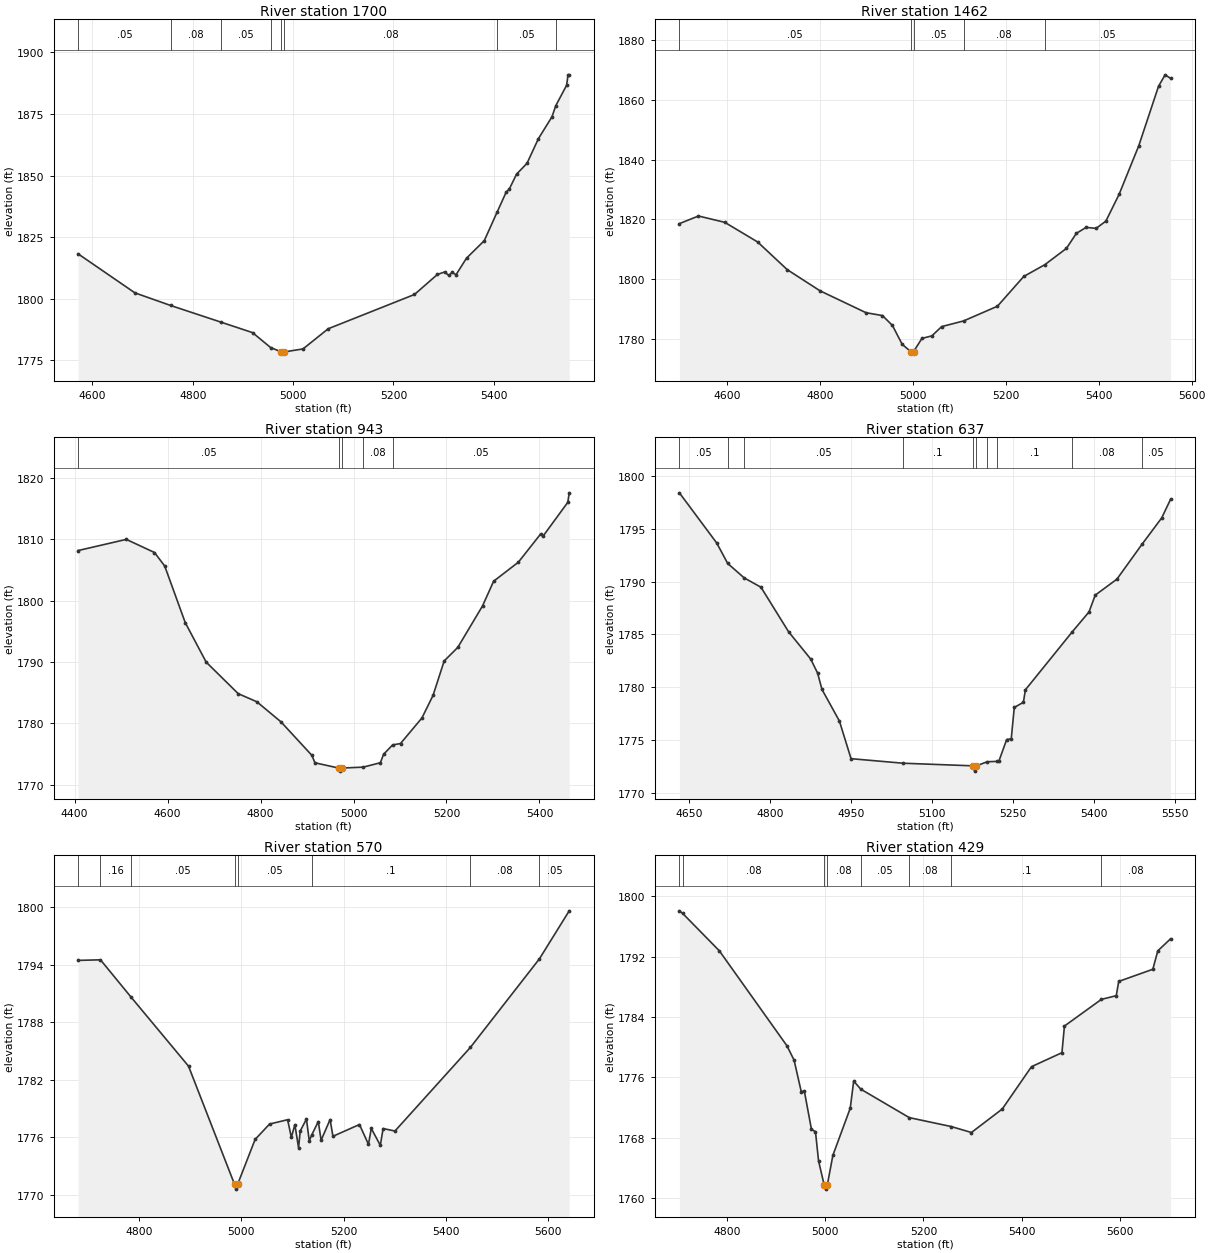
Type RM Length L Ch R = 1 ,1700    ,238,238,238
BEGIN DESCRIPTION:
Mapping XS 86481b06
END DESCRIPTION:
XS GIS Cut Line= 3
      2756522.82     10089790.98      2757189.45     10089719.81
      2757376.97     10089474.99
#Sta/Elev= 30
  4571.5 1818.24  4684.8 1802.39  4755.8 1797.28  4855.5 1790.56  4919.1 1786.26
  4955.2  1780.2  4976.5 1778.43  4979.2 1777.93  4982.5 1778.43  5019.7 1779.63
    5070 1787.83  5241.9 1801.74  5287.5 1809.86  5302.1 1810.89  5310.3 1809.45
  5316.6 1810.67  5324.8 1809.79  5345.6 1816.49    5381 1823.59    5407 1835.37
  5424.5 1843.23  5430.8 1844.52  5445.3 1850.58  5466.2 1855.01  5488.9 1865.02
    5516 1873.91  5523.4 1878.36  5545.1 1886.69  5547.9 1890.92  5550.3 1890.92
#Mann= 8 ,-1 , 0
  4571.5     .05       0  4755.8     .08       0  4855.5     .05       0
  4955.2     .08       0  4976.5     .07       0  4982.5     .08       0
    5407     .05       0  5523.4     .16       0
Bank Sta=4976.5,4982.5
XS Rating Curve= 0 ,0
Exp/Cntr=0.3,0.1

Type RM Length L Ch R = 1 ,1462    ,519,519,519
BEGIN DESCRIPTION:
UNT018 IN NNOGR 3.0
END DESCRIPTION:
XS GIS Cut Line= 2
      2756717.08     10090320.53      2757441.04     10089549.69
#Sta/Elev= 30
    4497  1818.6  4538.1 1821.15  4594.7 1819.03  4665.6 1812.43  4729.1 1803.18
  4799.9 1796.07    4899 1788.73  4934.2 1787.78  4955.7 1784.47  4976.7 1778.14
  4995.2 1775.69  4997.9 1775.19  5001.2 1775.69  5019.2 1780.12  5040.6 1780.98
  5061.7 1784.08  5108.9 1785.98  5181.8 1790.91  5238.5 1800.89  5283.8 1804.83
  5330.3 1810.29  5351.8 1815.34  5372.8 1817.34  5394.3    1817  5415.3 1819.44
  5443.6 1828.36  5486.1 1844.69  5528.6 1864.61  5542.8 1868.47  5554.5  1867.3
#Mann= 5 ,-1 , 0
    4497     .05       0  4995.2     .04       0  5001.2     .05       0
  5108.9     .08       0  5283.8     .05       0
Bank Sta=4995.2,5001.2
XS Rating Curve= 0 ,0
Exp/Cntr=0.3,0.1

Type RM Length L Ch R = 1 ,943     ,306,306,306
BEGIN DESCRIPTION:
UNT018 IN NNOGR 2.0
END DESCRIPTION:
XS GIS Cut Line= 3
      2757019.17     10090481.99      2757472.28     10090273.66
      2757685.67      10089758.4
#Sta/Elev= 30
  4407.6 1808.18  4511.3    1810  4571.9 1807.86  4593.9 1805.66    4638 1796.44
  4683.1 1789.99    4752 1784.85    4792 1783.53  4843.9 1780.26  4910.5 1774.79
    4917 1773.58  4968.2 1772.72  4970.9 1772.22  4974.2 1772.72  5020.9 1772.87
  5057.8 1773.59  5064.7 1774.97  5084.1 1776.49  5101.1 1776.72  5147.2 1780.89
  5171.1 1784.57    5195 1790.18  5224.3 1792.39  5277.5 1799.15  5301.4 1803.18
  5354.6 1806.28  5402.3 1810.86  5407.8 1810.54  5460.9 1816.04    5464 1817.59
#Mann= 5 ,-1 , 0
  4407.6     .05       0  4968.2     .04       0  4974.2     .05       0
  5020.9     .08       0  5084.1     .05       0
Bank Sta=4968.2,4974.2
XS Rating Curve= 0 ,0
Exp/Cntr=0.3,0.1

Type RM Length L Ch R = 1 ,637     ,67,67,67
BEGIN DESCRIPTION:
Mapping XS 8daecc9d
END DESCRIPTION:
XS GIS Cut Line= 5
      2757311.01     10090514.89      2757561.03     10090459.33
      2757699.92     10090403.77      2757804.09     10090191.97
      2757824.92     10089924.62
#Sta/Elev= 30
  4632.3 1798.41  4701.4 1793.66  4721.8 1791.72  4752.4 1790.35  4783.4 1789.47
  4834.6 1785.25  4875.5 1782.67  4888.4 1781.33  4896.4 1779.79  4928.7  1776.8
  4950.3 1773.23  5046.4  1772.8  5176.7 1772.55  5179.4 1772.05  5182.7 1772.55
  5202.6 1772.94    5220 1772.97  5224.6 1773.05  5238.6 1775.04  5247.1 1775.11
  5252.7 1778.08  5269.6 1778.57  5273.3 1779.75  5360.4 1785.26  5391.2 1787.13
  5402.7 1788.72  5442.8 1790.23  5489.1 1793.52  5525.8 1796.03  5542.2 1797.79
#Mann= 10 ,-1 , 0
  4632.3     .05       0  4721.8     .16       0  4752.4     .05       0
  5046.4      .1       0  5176.7     .04       0  5182.7      .1       0
  5202.6     .08       0    5220      .1       0  5360.4     .08       0
  5489.1     .05       0
Bank Sta=5176.7,5182.7
XS Rating Curve= 0 ,0
Exp/Cntr=0.3,0.1

Type RM Length L Ch R = 1 ,570     ,141,141,141
BEGIN DESCRIPTION:
UNT018 IN NNOGR 1.0
END DESCRIPTION:
XS GIS Cut Line= 6
      2757338.81     10090546.13      2757581.87     10090480.16
      2757668.67     10090483.63      2757738.12     10090417.66
      2757835.34     10090202.38      2757842.28     10089914.19
#Sta/Elev= 30
  4681.6 1794.43  4725.3 1794.49    4785  1790.6  4897.2  1783.4  4987.1 1771.07
  4989.8 1770.57  4993.1 1771.07  5027.2 1775.75  5055.5 1777.36  5090.7 1777.81
    5098 1775.97  5104.9  1777.3  5112.1 1774.88  5115.3 1776.63  5127.5 1777.88
    5133  1775.6  5137.6  1776.2  5150.6 1777.62  5156.1 1775.67  5173.7 1777.83
  5179.2 1776.08    5231 1777.31  5248.6 1775.24  5254.1  1776.9  5271.7 1775.14
  5277.2 1776.89  5300.3 1776.63  5447.7 1785.36  5582.5  1794.6  5640.6  1799.6
#Mann= 8 ,-1 , 0
  4681.6     .05       0  4725.3     .16       0    4785     .05       0
  4987.1     .04       0  4993.1     .05       0  5137.6      .1       0
  5447.7     .08       0  5582.5     .05       0
Bank Sta=4987.1,4993.1
XS Rating Curve= 0 ,0
Exp/Cntr=0.3,0.1

Type RM Length L Ch R = 1 ,429     ,132,132,132
BEGIN DESCRIPTION:
Mapping XS b4d5dc9c
END DESCRIPTION:
XS GIS Cut Line= 6
      2757401.31     10090757.94       2757602.7     10090685.02
      2757717.28     10090535.72      2757797.14     10090365.58
      2757849.23     10090233.63      2757873.38     10089967.92
#Sta/Elev= 30
  4703.5 1798.07  4710.1 1797.73  4784.8 1792.77  4922.3 1780.19  4936.8 1778.29
  4951.3 1774.13  4957.6 1774.21  4972.1 1769.13  4980.3 1768.82  4986.6 1764.93
  4998.2 1761.71  5000.9 1761.21  5004.2 1761.71  5015.7 1765.69    5051 1771.92
    5058 1775.52  5072.5 1774.45  5171.1 1770.68  5256.3  1769.5  5297.5 1768.71
  5360.2 1771.82  5419.7 1777.43  5481.6 1779.28  5486.7 1782.81  5561.8 1786.34
  5592.1 1786.83  5597.1 1788.72  5666.5 1790.33  5676.6 1792.77  5702.5 1794.36
#Mann= 8 ,-1 , 0
  4703.5     .05       0  4710.1     .08       0  4998.2     .07       0
  5004.2     .08       0  5072.5     .05       0  5171.1     .08       0
  5256.3      .1       0  5561.8     .08       0
Bank Sta=4998.2,5004.2
XS Rating Curve= 0 ,0
Exp/Cntr=0.3,0.1

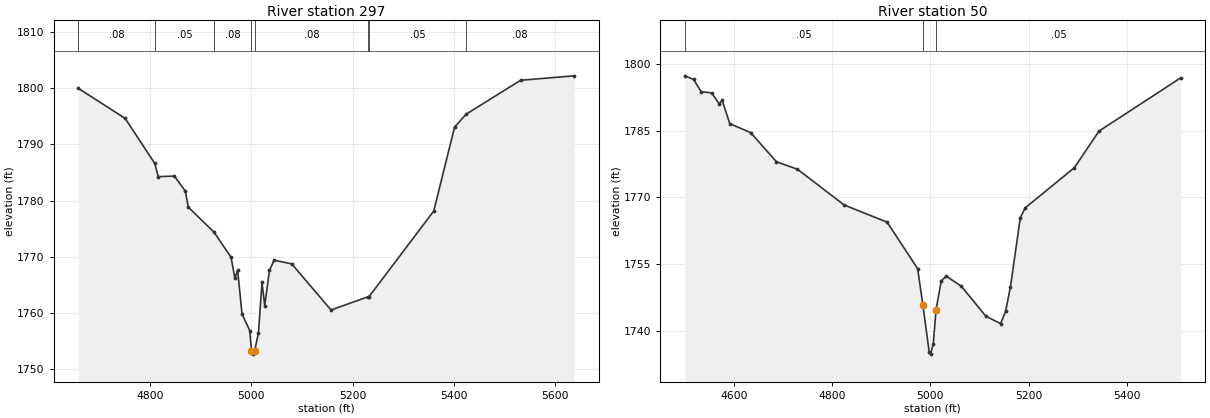
Type RM Length L Ch R = 1 ,297     ,247,247,247
BEGIN DESCRIPTION:
Mapping XS 7d2d1267
END DESCRIPTION:
XS GIS Cut Line= 4
      2757522.81     10090823.96       2757739.8     10090702.44
      2757916.88     10090270.15      2757934.22     10090008.37
#Sta/Elev= 30
  4658.8    1800  4751.3 1794.63  4809.5 1786.62  4816.4 1784.26  4848.3 1784.36
    4870 1781.66  4875.7 1778.83  4926.7 1774.34  4960.1 1769.88  4967.7 1766.13
  4973.1  1767.6  4981.7 1759.81  4997.1 1756.79  5000.4 1753.12  5003.1 1752.62
  5006.4 1753.12  5014.2 1756.43  5021.1 1765.39  5026.5 1761.27  5035.8 1767.54
  5045.1 1769.37  5079.9  1768.7  5157.3 1760.49    5231 1762.86  5232.2 1762.85
    5360 1778.13  5401.1 1793.09  5423.9 1795.39  5531.4 1801.44    5637 1802.23
#Mann= 8 ,-1 , 0
  4658.8     .08       0  4809.5     .05       0  4926.7     .08       0
  5000.4     .07       0  5006.4     .08       0    5231      .1       0
  5232.2     .05       0  5423.9     .08       0
Bank Sta=5000.4,5006.4
XS Rating Curve= 0 ,0
Exp/Cntr=0.3,0.1

Type RM Length L Ch R = 1 ,50      ,0,0,0
BEGIN DESCRIPTION:
Mapping XS 73c4c95a
END DESCRIPTION:
XS GIS Cut Line= 4
      2757616.53     10090896.89      2757977.65     10090678.14
       2758014.1     10090567.03      2758015.84     10090097.67
#Sta/Elev= 30
  4500.4 1797.35  4518.2 1796.53  4533.7 1793.78    4555  1793.5  4570.5    1791
  4576.4 1791.86  4591.8  1786.6  4634.5 1784.55  4686.9    1778  4729.6 1776.31
  4824.6 1768.27  4911.9  1764.4    4974 1753.94 4984.68 1745.72  4997.5 1735.19
  5000.3 1734.69  5005.8 1736.98  5011.4 1744.66    5022 1751.19  5032.4 1752.23
  5062.8 1749.99  5112.8 1743.22  5142.8 1741.56  5152.8 1744.31  5162.8 1749.84
  5182.8  1765.4  5192.8 1767.63  5292.8 1776.66  5342.8  1784.9  5508.9 1796.88
#Mann= 3 , 0 , 0
  4500.4     .05       0 4984.68     .03       0  5011.4     .05       0
#XS Ineff= 2 , 0
                         5032.41         1752.21
Permanent Ineff=
       F       F
Bank Sta=4984.68,5011.4
XS Rating Curve= 0 ,0
Exp/Cntr=0.3,0.1

Chan Stop Cuts=-1
Use User Specified Reach Order=0
Composite Channel Slope=5