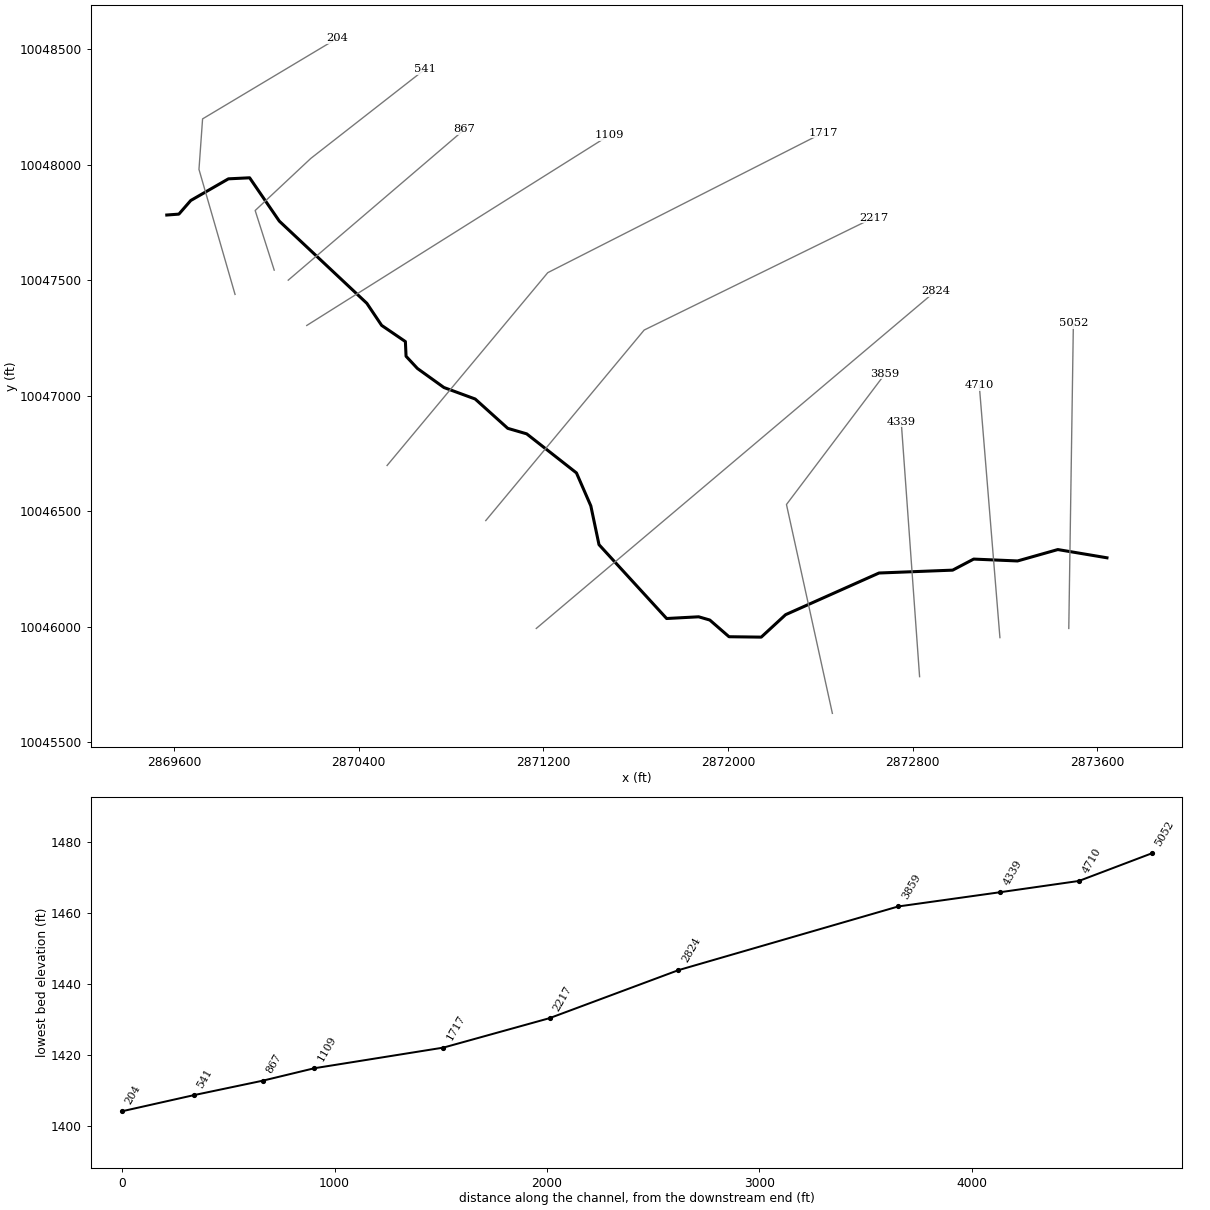
--- UNT018 IN SNOGR.prj (project) ---

Proj Title=UNT018 IN SNOGR Base Level Engineering
Current Plan=p01
Default Exp/Contr=0.3,0.1
English Units
Geom File=g01
Flow File=f01
Plan File=p01
Y Axis Title=Elevation
X Axis Title(PF)=Main Channel Distance
X Axis Title(XS)=Station
BEGIN DESCRIPTION:
UNT018 IN SNOGR
END DESCRIPTION:
DSS Export Rating Curves= 0
DSS Export Rating Curve Sorted= 0
DSS Export Volume Flow Curves= 0
DXF OffsetX= 0
DXF OffsetY= 0
DXF ScaleX= 1
DXF ScaleY= 10

--- UNT018 IN SNOGR.p01 (plan) ---

Plan Title=Multiple Run
Short Identifier=Multiple
Geom File=g01
Flow File=f01
Subcritical Flow
K Sum by GR= 0
Std Step Tol= 0.01
Critical Tol= 0.01
Num of Std Step Trials= 20
Max Error Tol= 0.3
Flow Tol Ratio= 0.001
Split Flow NTrial= 30
Split Flow Tol= 0.02
Split Flow Ratio= 0.02
Log Output Level= 0
Friction Slope Method= 1
Unsteady Friction Slope Method= 2
Unsteady Bridges Friction Slope Method= 1
Parabolic Critical Depth
Global Vel Dist=  1 , 1 , 1
Global Log Level= 0
CheckData=True
Encroach Param= -1, 0, 0, 0
BEGIN DESCRIPTION:
Multiple Run
END DESCRIPTION:

--- UNT018 IN SNOGR.f01 (steady flow) ---

Flow Title=Multiple
Program Version=4.10
Number of Profiles= 7
Profile Names=10-year,25-year,50-year,1pct_min,100-year,1pct_plu,500-year
River Rch & RM=UNT018 IN SNOGR,Reach-1         ,5052
    1040    1535    1975    1862    2518    3405    4106
River Rch & RM=UNT018 IN SNOGR,Reach-1         ,4339
    1286    1916    2478    2347    3174    4293    5225
Boundary for River Rch & Prof#=UNT018 IN SNOGR,Reach-1         , 1
Up Type= 0
Dn Type= 3
Dn Slope=0.01347
Boundary for River Rch & Prof#=UNT018 IN SNOGR,Reach-1         , 2
Up Type= 0
Dn Type= 3
Dn Slope=0.01347
Boundary for River Rch & Prof#=UNT018 IN SNOGR,Reach-1         , 3
Up Type= 0
Dn Type= 3
Dn Slope=0.01347
Boundary for River Rch & Prof#=UNT018 IN SNOGR,Reach-1         , 4
Up Type= 0
Dn Type= 3
Dn Slope=0.01347
Boundary for River Rch & Prof#=UNT018 IN SNOGR,Reach-1         , 5
Up Type= 0
Dn Type= 3
Dn Slope=0.01347
Boundary for River Rch & Prof#=UNT018 IN SNOGR,Reach-1         , 6
Up Type= 0
Dn Type= 3
Dn Slope=0.01347
Boundary for River Rch & Prof#=UNT018 IN SNOGR,Reach-1         , 7
Up Type= 0
Dn Type= 3
Dn Slope=0.01347
DSS Import GetInterval= 0
DSS Import GetPeak= 0
DSS Import FillOption= 0

--- UNT018 IN SNOGR.g01 (geometry) ---

Geom Title=Existing Conditions
Program Version=4.10

River Reach=UNT018 IN SNOGR ,Reach-1
Reach XY= 30
      2873641.53     10046297.79      2873428.69     10046333.49
       2873254.1     10046284.12      2873064.11      10046292.2
      2872973.04     10046244.32      2872654.07     10046231.91
      2872249.35     10046051.39      2872143.82     10045954.13
       2872004.2     10045955.85      2871921.02     10046028.14
      2871872.76     10046042.21      2871733.95     10046034.78
      2871440.96     10046354.73      2871405.58      10046522.7
      2871343.31     10046665.53      2871127.68     10046834.79
      2871045.66     10046858.62      2870904.57     10046985.71
       2870769.2     10047035.49      2870654.37       10047118.
      2870605.12     10047170.91      2870602.24     10047234.52
      2870499.34     10047304.64      2870435.17     10047400.36
      2870056.01     10047756.36      2869927.45     10047944.01
      2869835.56     10047939.51      2869672.28     10047845.59
      2869620.95     10047786.63      2869568.56     10047782.75

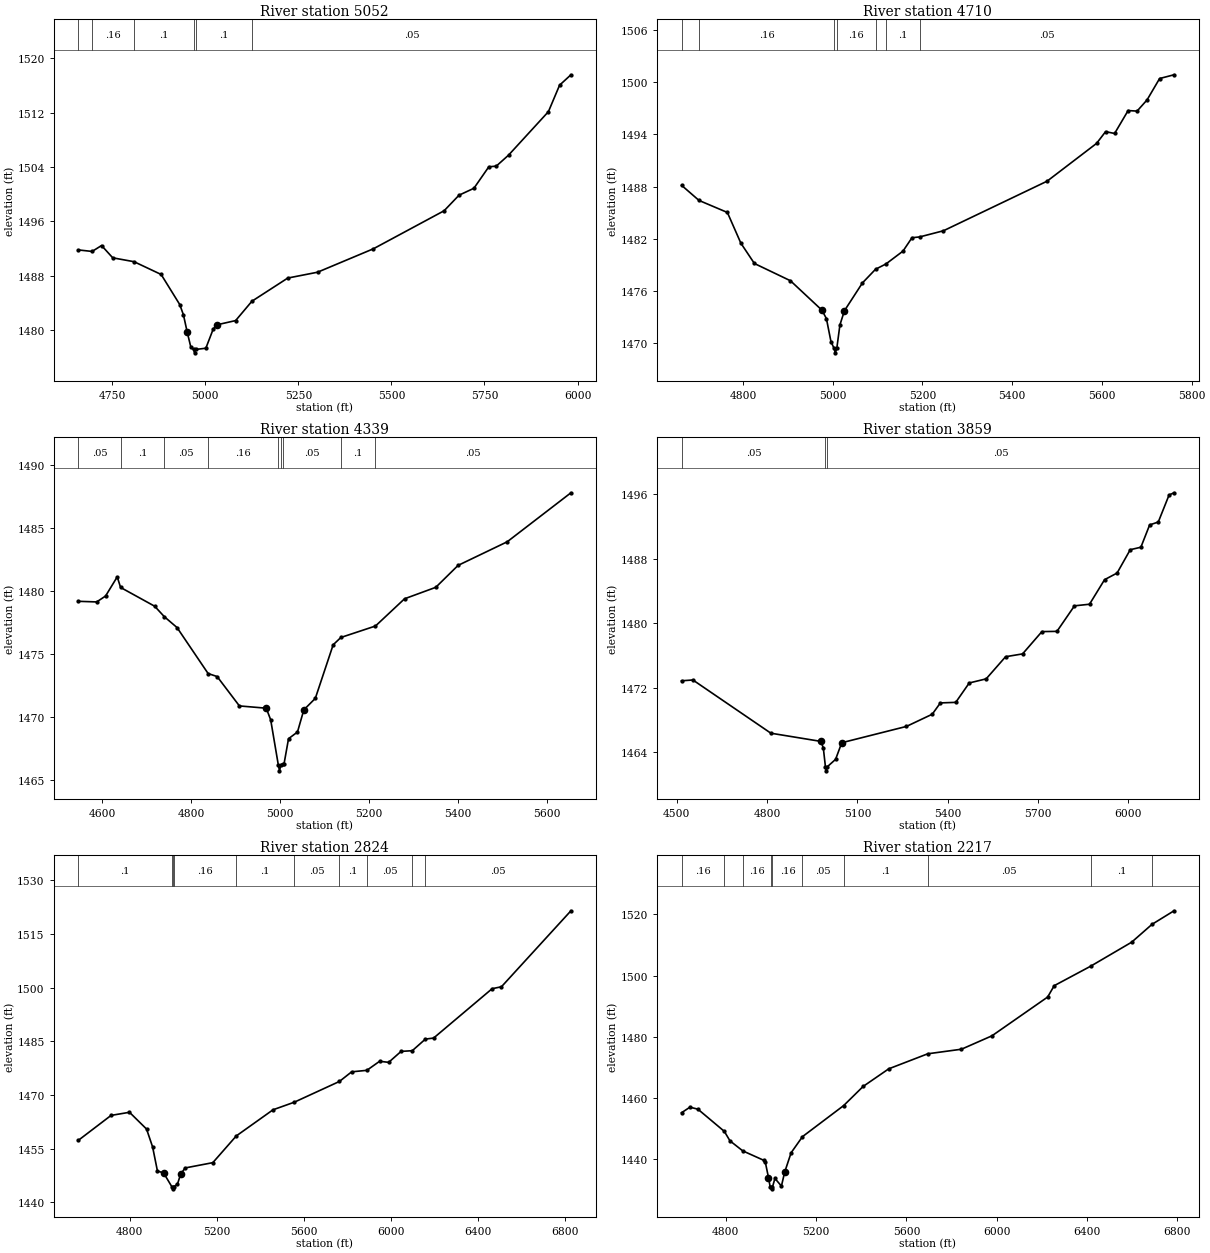
Type RM Length L Ch R = 1 ,5052    ,342,342,342
BEGIN DESCRIPTION:
UNT018 IN SNOGR 10.0
END DESCRIPTION:
XS GIS Cut Line= 2
      2873476.13     10045991.72      2873496.02     10047314.27
#Sta/Elev= 30
  4659.5  1491.8  4696.1 1491.58  4721.5 1492.45  4751.5 1490.64  4808.7 1490.07
  4881.5 1488.19  4931.5 1483.76  4941.5 1482.23  4951.5 1479.71  4961.5 1477.44
  4968.5 1477.15  4971.3 1476.65  4974.5 1477.15  5001.6 1477.33  5021.6 1480.18
  5031.6 1480.78  5081.6  1481.4  5125.4 1484.25  5221.6 1487.66  5301.6 1488.52
  5451.6 1491.97  5641.6 1497.57  5681.6 1499.86  5721.6 1500.88  5761.6 1504.04
  5781.6 1504.14  5814.5 1505.75  5921.7 1512.16  5951.7 1516.06  5982.2 1517.59
#Mann= 6 ,-1 , 0
  4659.5      .1       0  4696.1     .16       0  4808.7      .1       0
  4968.5     .07       0  4974.5      .1       0  5125.4     .05       0
Bank Sta=4951.5,5031.6
XS Rating Curve= 0 ,0
Exp/Cntr=0.3,0.1

Type RM Length L Ch R = 1 ,4710    ,371,371,371
BEGIN DESCRIPTION:
UNT018 IN SNOGR 9.0
END DESCRIPTION:
XS GIS Cut Line= 2
      2873177.83     10045951.98      2873088.34     10047045.72
#Sta/Elev= 30
  4663.3 1488.14  4702.2  1486.4  4765.4 1485.02  4795.5 1481.49  4825.6 1479.16
  4905.9 1477.18  4976.1  1473.8  4986.1 1472.83  4996.2  1470.2  5003.2  1469.4
  5005.9  1468.9  5009.2  1469.4  5016.2 1472.11  5026.3 1473.74  5066.4 1476.93
  5095.6  1478.5  5118.6  1479.1  5156.7 1480.58  5176.8 1482.12  5193.9 1482.21
    5247 1482.92  5477.8 1488.61  5588.1 1492.95  5608.2  1494.3  5628.3 1494.09
  5658.4 1496.72  5678.4 1496.66  5700.7 1497.95  5728.6  1500.4  5760.7 1500.83
#Mann= 7 ,-1 , 0
  4663.3     .05       0  4702.2     .16       0  5003.2     .07       0
  5009.2     .16       0  5095.6     .05       0  5118.6      .1       0
  5193.9     .05       0
Bank Sta=4976.1,5026.3
XS Rating Curve= 0 ,0
Exp/Cntr=0.3,0.1

Type RM Length L Ch R = 1 ,4339    ,480,480,480
BEGIN DESCRIPTION:
UNT018 IN SNOGR 8.0
END DESCRIPTION:
XS GIS Cut Line= 2
      2872829.81     10045782.95      2872750.26     10046886.69
#Sta/Elev= 30
  4546.9 1479.18  4587.8 1479.13  4607.8  1479.6    4634 1481.12  4641.5 1480.28
  4718.1 1478.79  4739.8 1477.96  4768.3  1477.1  4838.2 1473.45  4858.5 1473.21
  4908.5 1470.88  4968.8  1470.7  4978.8 1469.78  4995.8 1466.23  4998.6 1465.73
  5001.8 1466.23  5005.6 1466.27  5008.9  1466.3  5018.9 1468.28    5039 1468.81
  5053.3 1470.57  5079.1 1471.48  5119.2 1475.73  5136.5 1476.31  5214.3 1477.22
  5279.6 1479.38  5349.8 1480.29  5399.9 1482.03  5510.2  1483.9  5653.5 1487.79
#Mann= 9 ,-1 , 0
  4546.9     .05       0  4641.5      .1       0  4739.8     .05       0
  4838.2     .16       0  4995.8     .07       0  5001.8     .16       0
  5005.6     .05       0  5136.5      .1       0  5214.3     .05       0
Bank Sta=4968.8,5053.3
XS Rating Curve= 0 ,0
Exp/Cntr=0.3,0.1

Type RM Length L Ch R = 1 ,3859    ,1035,1035,1035
BEGIN DESCRIPTION:
UNT018 IN SNOGR 7.0
END DESCRIPTION:
XS GIS Cut Line= 3
      2872451.97     10045623.82       2872253.1      10046528.7
      2872680.64     10047095.45
#Sta/Elev= 30
  4515.6 1472.87  4553.3 1472.97  4812.4 1466.38  4977.9 1465.37  4986.5  1464.6
  4993.7 1462.22  4996.5 1461.72  4999.7 1462.22  5027.4 1463.14  5047.9  1465.2
  5262.9 1467.22  5348.6 1468.73  5375.6 1470.13  5426.7  1470.2  5471.5  1472.6
  5527.8 1473.11  5592.3 1475.85  5648.8  1476.2    5713 1478.96    5763 1478.99
  5821.2 1482.15  5871.2 1482.35  5921.2 1485.39  5962.8 1486.21  6006.5  1489.1
  6041.9 1489.41    6071 1492.17  6099.7 1492.53  6135.6 1495.88    6152 1496.15
#Mann= 3 ,-1 , 0
  4515.6     .05       0  4993.7    .035       0  4999.7     .05       0
Bank Sta=4977.9,5047.9
XS Rating Curve= 0 ,0
Exp/Cntr=0.3,0.1

Type RM Length L Ch R = 1 ,2824    ,607,607,607
BEGIN DESCRIPTION:
UNT018 IN SNOGR 6.0
END DESCRIPTION:
XS GIS Cut Line= 2
      2871169.29     10045991.77      2872899.41     10047453.43
#Sta/Elev= 30
  4564.5 1457.37  4714.4  1464.3  4799.1 1465.17  4877.6 1460.49  4905.5 1455.48
  4927.6 1448.79  4956.1 1448.23  4994.8  1444.3  4997.6  1443.8  5000.8  1444.3
  5002.9 1444.36  5019.9 1445.13  5034.2 1447.88    5055 1449.63  5182.4 1451.11
  5290.3 1458.57  5459.3 1465.87  5556.4 1467.97  5764.7 1473.78  5820.8 1476.46
  5890.7 1476.88  5949.5 1479.41  5991.1 1479.11  6048.3 1482.17  6099.7 1482.36
    6160  1485.6  6197.8 1485.89  6466.9 1499.67  6509.8 1500.21  6829.4 1521.42
#Mann= 10 ,-1 , 0
  4564.5      .1       0  4994.8     .07       0  5000.8      .1       0
  5002.9     .16       0  5290.3      .1       0  5556.4     .05       0
  5764.7      .1       0  5890.7     .05       0  6099.7      .1       0
    6160     .05       0
Bank Sta=4956.1,5034.2
XS Rating Curve= 0 ,0
Exp/Cntr=0.3,0.1

Type RM Length L Ch R = 1 ,2217    ,500,500,500
BEGIN DESCRIPTION:
UNT018 IN SNOGR 5.0
END DESCRIPTION:
XS GIS Cut Line= 3
       2870950.5     10046459.07      2871636.61     10047284.39
      2872630.98     10047771.64
#Sta/Elev= 30
  4604.1 1455.16  4641.3 1456.98  4676.5 1456.32  4793.5 1449.07  4818.4 1445.98
    4875  1442.7  4968.2 1439.61  4974.7  1439.1    4989 1433.99  4996.8 1430.79
  5000.3 1430.79  5003.1 1430.29  5006.3 1430.79  5017.6 1433.69  5046.3 1431.19
  5060.6 1435.72  5089.2 1442.08  5139.6 1447.35  5321.9  1457.5  5408.2 1463.76
  5521.5 1469.51  5694.1 1474.42  5843.6 1475.92  5978.6  1480.3  6225.1 1492.97
  6254.2 1496.68  6415.9 1503.06  6597.2  1510.9  6687.3 1516.73  6784.7 1521.16
#Mann= 10 ,-1 , 0
  4604.1     .16       0  4793.5      .1       0    4875     .16       0
  5000.3     .07       0  5006.3     .16       0  5139.6     .05       0
  5321.9      .1       0  5694.1     .05       0  6415.9      .1       0
  6687.3     .05       0
Bank Sta=4989,5060.6
XS Rating Curve= 0 ,0
Exp/Cntr=0.3,0.1

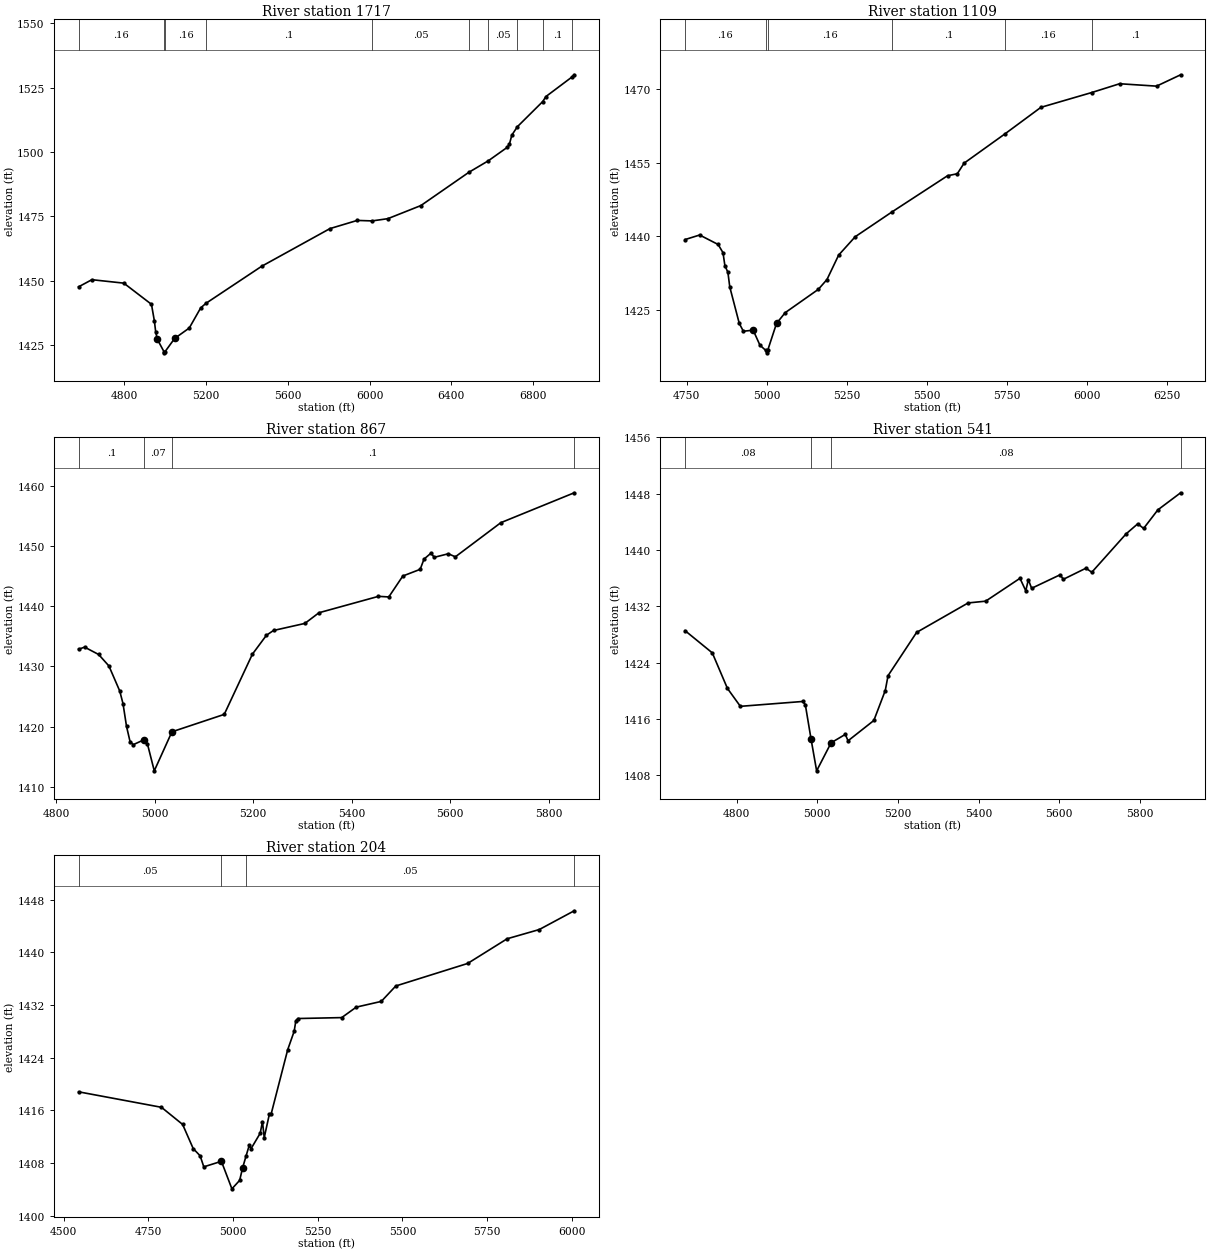
Type RM Length L Ch R = 1 ,1717    ,608,608,608
BEGIN DESCRIPTION:
UNT018 IN SNOGR 4.0
END DESCRIPTION:
XS GIS Cut Line= 3
      2870522.95     10046697.73      2871218.99     10047532.98
      2872411.42     10048139.13
#Sta/Elev= 30
  4576.2 1447.66    4641 1450.42  4797.2 1449.08  4932.6 1440.85  4946.9 1434.35
  4953.4 1430.04  4961.3 1427.25  4993.4  1422.5  4996.2    1422  4999.4  1422.5
  5045.9 1427.59  5117.5 1431.64  5173.4 1439.46  5199.1 1441.24  5471.5 1455.62
  5805.8 1470.27  5939.3 1473.45  6012.1 1473.26  6089.1 1474.13  6250.9 1479.23
  6485.6 1492.15    6581 1496.63  6673.6 1501.86  6683.7 1503.02  6695.9 1506.61
    6723 1509.87  6847.1 1519.65  6862.7 1521.59  6989.6 1529.15  7001.1 1530.04
#Mann= 10 ,-1 , 0
  4576.2     .16       0  4993.4     .07       0  4999.4     .16       0
  5199.1      .1       0  6012.1     .05       0  6485.6      .1       0
    6581     .05       0    6723     .16       0  6847.1      .1       0
  6989.6     .05       0
Bank Sta=4961.3,5045.9
XS Rating Curve= 0 ,0
Exp/Cntr=0.3,0.1

Type RM Length L Ch R = 1 ,1109    ,242,242,242
BEGIN DESCRIPTION:
UNT018 IN SNOGR 3.0
END DESCRIPTION:
XS GIS Cut Line= 2
      2870174.93     10047304.28      2871486.75     10048129.14
#Sta/Elev= 30
  4744.4 1439.32  4790.1 1440.25  4847.8 1438.32  4863.1 1436.64    4869    1434
  4878.4 1432.64  4884.3 1429.64    4914 1422.19  4926.8  1420.6  4957.4 1420.82
  4978.6 1417.75  4996.8 1416.69  4999.5 1416.19  5002.8 1416.69  5030.4 1422.19
  5057.5 1424.39  5161.1 1429.15  5188.2 1431.16  5224.7 1436.15  5276.5  1439.9
  5392.1 1444.99  5565.1 1452.35  5595.7 1452.76  5616.9 1454.92  5745.1 1460.92
  5857.1 1466.32  6015.8 1469.34  6103.2 1471.14  6218.7 1470.65    6294 1472.97
#Mann= 6 ,-1 , 0
  4744.4     .16       0  4996.8     .07       0  5002.8     .16       0
  5392.1      .1       0  5745.1     .16       0  6015.8      .1       0
Bank Sta=4957.4,5030.4
XS Rating Curve= 0 ,0
Exp/Cntr=0.3,0.1

Type RM Length L Ch R = 1 ,867     ,326,326,326
BEGIN DESCRIPTION:
UNT018 IN SNOGR 2.0
END DESCRIPTION:
XS GIS Cut Line= 2
       2870094.7     10047500.56      2870858.59     10048153.78
#Sta/Elev= 30
  4846.1 1432.86  4858.2 1433.21  4886.7 1431.99  4907.5 1430.09  4929.5 1425.93
  4936.1 1423.84  4943.2 1420.08  4950.4 1417.54  4956.9 1417.04  4978.9 1417.86
  4985.5 1417.21  4999.5  1412.7  5035.3 1419.17  5141.4 1422.06  5198.5 1432.04
    5227 1435.18  5241.3 1435.97  5304.9 1437.14  5333.5 1438.91  5454.2 1441.63
  5475.1 1441.53  5503.6    1445  5538.8 1446.11  5546.5  1447.8  5560.7 1448.79
  5567.3  1448.1  5595.9 1448.69  5610.1 1448.18  5702.3 1453.84  5851.2  1458.8
#Mann= 4 ,-1 , 0
  4846.1      .1       0  4978.9     .07       0  5035.3      .1       0
  5851.2      .1       0
Bank Sta=4978.9,5035.3
XS Rating Curve= 0 ,0
Exp/Cntr=0.3,0.1

Type RM Length L Ch R = 1 ,541     ,337,337,337
BEGIN DESCRIPTION:
UNT018 IN SNOGR 1.5
END DESCRIPTION:
XS GIS Cut Line= 4
      2870033.94     10047543.99      2869951.48     10047802.22
      2870192.36     10048027.91      2870687.16      10048414.2
#Sta/Elev= 30
  4671.9 1428.54  4739.5 1425.38    4777 1420.33  4809.1 1417.78  4963.3 1418.47
  4970.1 1418.04  4984.3 1413.15  4998.2 1408.61  5034.1  1412.6  5069.3 1413.79
  5076.1 1412.88  5140.1 1415.77  5168.4 1420.03  5175.3 1422.14  5246.1 1428.29
  5373.9 1432.48  5417.3 1432.73  5502.4 1435.98  5516.8 1434.21  5523.2 1435.79
  5531.3 1434.56  5601.9 1436.48    5610 1435.84  5666.1 1437.42  5680.5 1436.84
  5765.6  1442.3  5794.5 1443.73    5809 1443.07  5844.3 1445.71  5900.8 1448.14
#Mann= 4 ,-1 , 0
  4671.9     .08       0  4984.3     .05       0  5034.1     .08       0
  5900.8      .1       0
Bank Sta=4984.3,5034.1
XS Rating Curve= 0 ,0
Exp/Cntr=0.3,0.1

Type RM Length L Ch R = 1 ,204     ,0,0,0
BEGIN DESCRIPTION:
UNT018 IN SNOGR 1.0
END DESCRIPTION:
XS GIS Cut Line= 4
      2869864.26     10047438.82      2869708.02     10047980.44
      2869723.64     10048199.19      2870307.01     10048548.17
#Sta/Elev= 30
  4544.1 1418.82  4788.6 1416.47    4851 1413.87  4882.3  1410.2  4902.8  1409.1
  4913.5 1407.43  4965.5 1408.27  4996.5 1404.09  5019.4 1405.38    5028 1407.26
  5038.4  1409.1  5047.8 1410.72    5053 1410.19    5080 1412.53  5086.7  1414.3
  5091.9 1411.86  5106.9 1415.39    5112 1415.39  5161.2 1425.22  5180.3 1428.02
  5185.3 1429.63  5191.3 1429.95  5320.6 1430.09  5363.5 1431.68  5437.4 1432.55
  5480.2 1434.89  5692.2 1438.31  5808.9 1442.06  5903.7 1443.46  6006.9 1446.31
#Mann= 4 ,-1 , 0
  4544.1     .05       0  4965.5     .03       0  5038.4     .05       0
  6006.9      .1       0
Bank Sta=4965.5,5028
XS Rating Curve= 0 ,0
Exp/Cntr=0.3,0.1

Chan Stop Cuts=-1
Use User Specified Reach Order=0
Composite Channel Slope=5