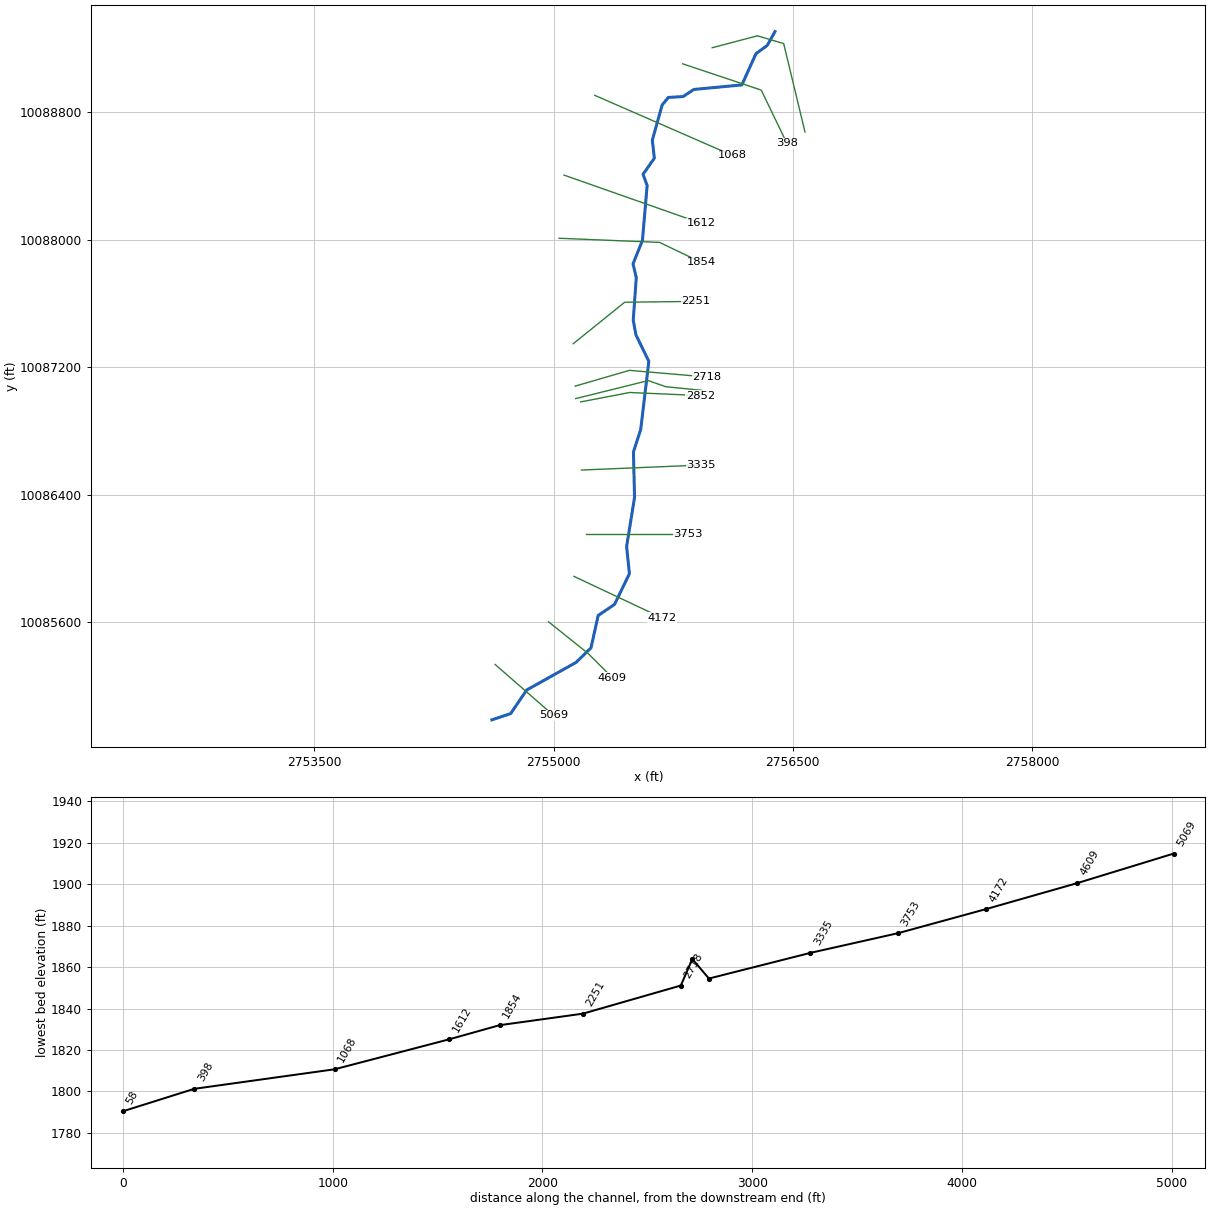
--- UNT019 IN NNOGR.prj (project) ---

Proj Title=UNT019 IN NNOGR Base Level Engineering
Current Plan=p01
Default Exp/Contr=0.3,0.1
English Units
Geom File=g01
Flow File=f01
Plan File=p01
Y Axis Title=Elevation
X Axis Title(PF)=Main Channel Distance
X Axis Title(XS)=Station
BEGIN DESCRIPTION:
UNT019 IN NNOGR
END DESCRIPTION:
DSS Export Rating Curves= 0
DSS Export Rating Curve Sorted= 0
DSS Export Volume Flow Curves= 0
DXF OffsetX= 0
DXF OffsetY= 0
DXF ScaleX= 1
DXF ScaleY= 10

--- UNT019 IN NNOGR.p01 (plan) ---

Plan Title=Multiple Run
Short Identifier=Multiple
Geom File=g01
Flow File=f01
Subcritical Flow
K Sum by GR= 0
Std Step Tol= 0.01
Critical Tol= 0.01
Num of Std Step Trials= 20
Max Error Tol= 0.3
Flow Tol Ratio= 0.001
Split Flow NTrial= 30
Split Flow Tol= 0.02
Split Flow Ratio= 0.02
Log Output Level= 0
Friction Slope Method= 1
Unsteady Friction Slope Method= 2
Unsteady Bridges Friction Slope Method= 1
Parabolic Critical Depth
Global Vel Dist=  1 , 1 , 1
Global Log Level= 0
CheckData=True
Encroach Param= -1, 0, 0, 0
BEGIN DESCRIPTION:
Multiple Run
END DESCRIPTION:

--- UNT019 IN NNOGR.f01 (steady flow) ---

Flow Title=Multiple
Program Version=4.10
Number of Profiles= 7
Profile Names=10-year,25-year,50-year,1pct_min,100-year,1pct_plu,500-year
River Rch & RM=UNT019 IN NNOGR,Reach-1         ,5069
     397     553     683     620     839    1135    1268
River Rch & RM=UNT019 IN NNOGR,Reach-1         ,1854
     552     785     983     904    1223    1653    1896
Boundary for River Rch & Prof#=UNT019 IN NNOGR,Reach-1         , 1
Up Type= 0
Dn Type= 3
Dn Slope=0.0314
Boundary for River Rch & Prof#=UNT019 IN NNOGR,Reach-1         , 2
Up Type= 0
Dn Type= 3
Dn Slope=0.0314
Boundary for River Rch & Prof#=UNT019 IN NNOGR,Reach-1         , 3
Up Type= 0
Dn Type= 3
Dn Slope=0.0314
Boundary for River Rch & Prof#=UNT019 IN NNOGR,Reach-1         , 4
Up Type= 0
Dn Type= 3
Dn Slope=0.0314
Boundary for River Rch & Prof#=UNT019 IN NNOGR,Reach-1         , 5
Up Type= 0
Dn Type= 3
Dn Slope=0.0314
Boundary for River Rch & Prof#=UNT019 IN NNOGR,Reach-1         , 6
Up Type= 0
Dn Type= 3
Dn Slope=0.0314
Boundary for River Rch & Prof#=UNT019 IN NNOGR,Reach-1         , 7
Up Type= 0
Dn Type= 3
Dn Slope=0.0314
DSS Import GetInterval= 0
DSS Import GetPeak= 0
DSS Import FillOption= 0

--- UNT019 IN NNOGR.g01 (geometry) ---

Geom Title=Existing Conditions
Program Version=4.10

River Reach=UNT019 IN NNOGR ,Reach-1
Reach XY= 30
      2754613.47     10084988.73       2754731.5     10085028.29
      2754831.65     10085175.76      2755141.25     10085348.77
      2755234.97     10085439.93      2755280.02     10085643.29
      2755382.43      10085712.3      2755475.84     10085904.94
      2755458.33     10086075.12      2755508.02     10086383.57
      2755501.03     10086668.33      2755546.65     10086809.48
      2755597.69     10087236.42      2755516.93     10087401.75
      2755499.74     10087493.77      2755518.86     10087760.74
      2755498.49     10087847.32      2755557.41     10087993.85
      2755586.96     10088338.75      2755561.31     10088408.96
      2755632.09     10088510.01      2755619.55     10088623.18
      2755680.88     10088842.93      2755719.55     10088890.84
      2755812.39     10088896.21      2755879.55      10088940.9
       2756180.9     10088969.21      2756268.89     10089164.65
      2756340.64      10089217.8      2756388.47     10089303.73

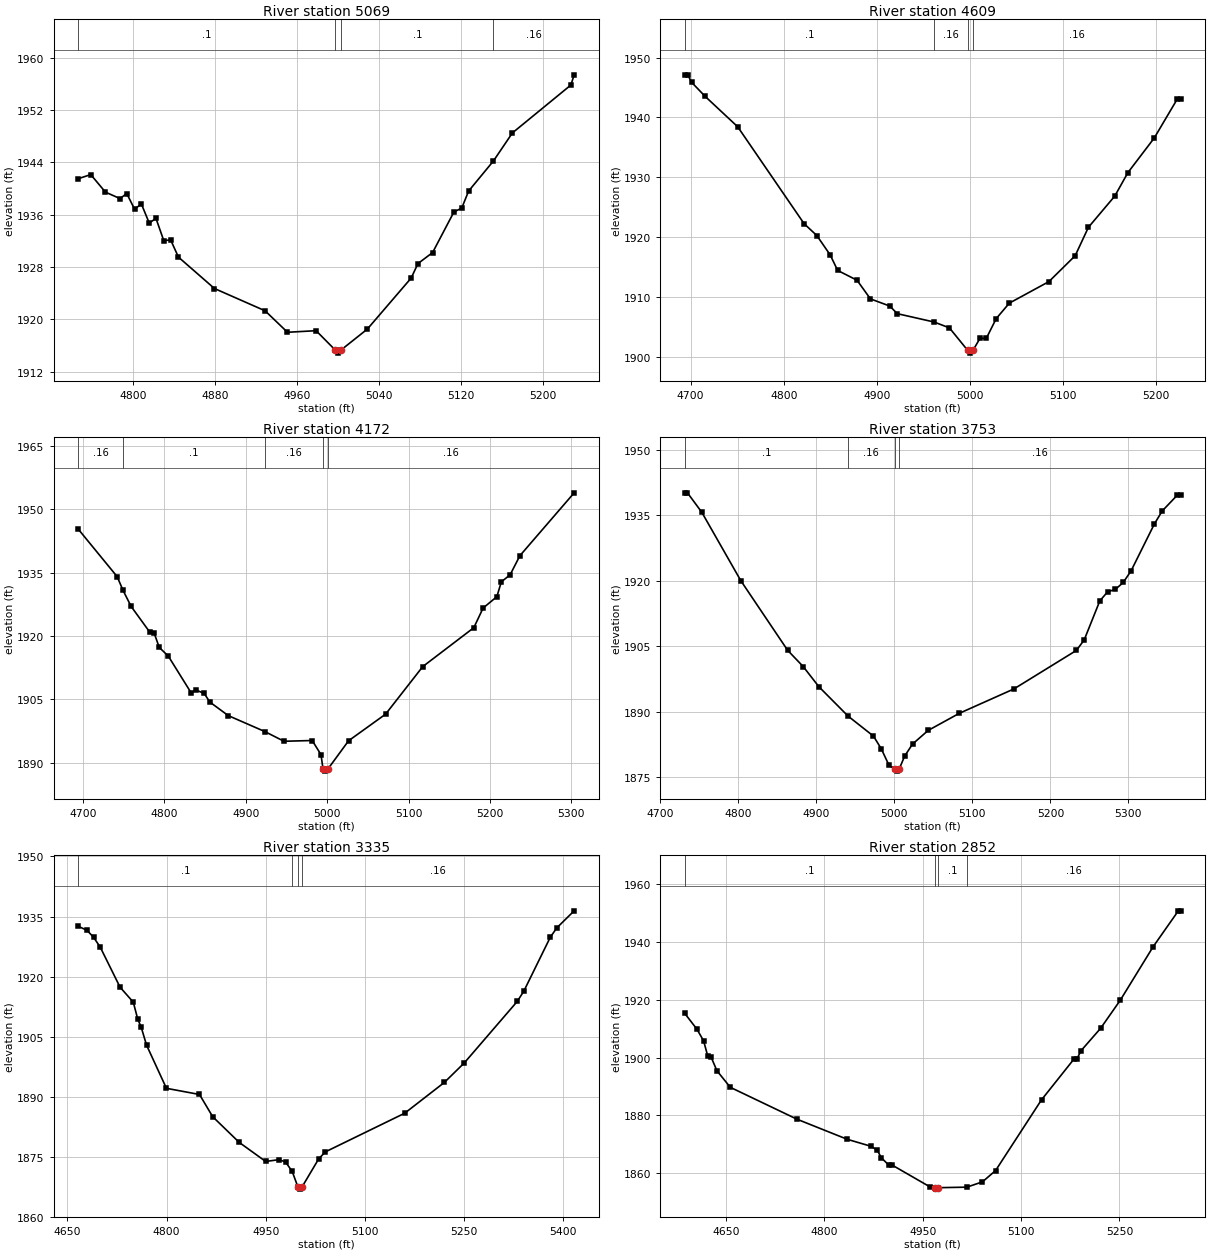
Type RM Length L Ch R = 1 ,5069    ,460,460,460
BEGIN DESCRIPTION:
UNT019 IN NNOGR 11.0
END DESCRIPTION:
XS GIS Cut Line= 2
      2754633.73     10085336.17      2754998.17     10085018.59
#Sta/Elev= 30
  4746.8 1941.52  4758.9 1942.15  4773.2 1939.47  4787.4 1938.48    4794 1939.25
  4801.6 1936.87  4808.3 1937.65  4815.9 1934.74  4822.5 1935.45  4830.1 1932.05
  4836.8 1932.16  4844.4 1929.53  4879.5 1924.73  4928.9 1921.32  4950.7 1918.04
  4978.6 1918.28  4997.1 1915.35  4999.8 1914.85  5003.1 1915.35  5028.6 1918.53
  5071.3 1926.33  5077.9 1928.54  5092.2 1930.23    5113 1936.44  5120.6 1937.02
  5127.3 1939.63  5151.5 1944.23    5170 1948.52    5227 1955.84  5230.2  1957.4
#Mann= 4 ,-1 , 0
  4746.8      .1       0  4997.1     .07       0  5003.1      .1       0
  5151.5     .16       0
Bank Sta=4997.1,5003.1
XS Rating Curve= 0 ,0
Exp/Cntr=0.3,0.1

Type RM Length L Ch R = 1 ,4609    ,437,437,437
BEGIN DESCRIPTION:
UNT019 IN NNOGR 10.0
END DESCRIPTION:
XS GIS Cut Line= 3
      2754968.47     10085603.73      2755218.47     10085403.73
      2755368.48     10085253.72
#Sta/Elev= 30
  4693.8 1947.13    4697 1947.13    4701  1945.9  4715.4 1943.56  4750.6 1938.44
  4821.9 1922.23  4835.5 1920.26  4849.9 1917.01  4857.9 1914.42  4878.7 1912.78
  4893.1 1909.66  4913.9 1908.46  4921.9 1907.19  4961.5 1905.79  4977.9 1904.81
  4997.3 1901.09  5000.1 1900.59  5003.3 1901.09  5010.7 1903.06  5017.5 1903.06
  5028.1 1906.36  5042.2 1908.95  5084.7 1912.55  5112.9 1916.88  5127.1 1921.63
  5155.4 1926.85  5169.5 1930.78  5197.8 1936.57  5222.5 1943.08  5226.1 1943.08
#Mann= 4 ,-1 , 0
  4693.8      .1       0  4961.5     .16       0  4997.3     .07       0
  5003.3     .16       0
Bank Sta=4997.3,5003.3
XS Rating Curve= 0 ,0
Exp/Cntr=0.3,0.1

Type RM Length L Ch R = 1 ,4172    ,419,419,419
BEGIN DESCRIPTION:
UNT019 IN NNOGR 9.0
END DESCRIPTION:
XS GIS Cut Line= 2
      2755128.56     10085888.23      2755679.63     10085628.29
#Sta/Elev= 30
  4694.2 1945.26  4741.9 1934.04  4749.1  1930.8  4759.1 1926.98  4781.9 1920.92
  4787.4 1920.67  4793.6 1917.28  4804.7 1915.24    4833 1906.47  4838.5 1907.22
  4848.9 1906.38  4855.8 1904.34  4878.5 1901.13  4923.7 1897.33  4946.9 1895.06
  4981.6 1895.24  4992.4 1891.89  4994.9 1888.49  4997.7 1887.99  5000.9 1888.49
  5026.3 1895.18  5071.8 1901.48  5117.4 1912.73  5180.2 1921.95  5191.6  1926.6
  5208.5 1929.29    5214  1932.8  5224.8 1934.47  5236.8 1938.99  5303.5 1953.88
#Mann= 5 ,-1 , 0
  4694.2     .16       0  4749.1      .1       0  4923.7     .16       0
  4994.9     .07       0  5000.9     .16       0
Bank Sta=4994.9,5000.9
XS Rating Curve= 0 ,0
Exp/Cntr=0.3,0.1

Type RM Length L Ch R = 1 ,3753    ,418,418,418
BEGIN DESCRIPTION:
UNT019 IN NNOGR 8.0
END DESCRIPTION:
XS GIS Cut Line= 2
      2755206.68     10086153.87      2755842.08     10086153.87
#Sta/Elev= 30
  4731.5 1940.17  4734.9 1940.17  4753.3 1935.71  4803.3 1920.03  4863.3 1904.08
  4883.3 1900.34  4903.3 1895.74  4940.8 1888.99  4973.3 1884.41  4983.3  1881.5
  4993.3 1877.69  5000.3 1876.89    5003 1876.39  5006.3 1876.89  5013.3 1879.85
  5023.3 1882.58  5043.3 1885.71  5083.3 1889.64  5153.3 1895.23  5233.3 1904.05
  5243.3 1906.45  5263.3 1915.39  5273.3 1917.48  5283.3 1918.05  5293.3 1919.62
  5303.3 1922.25  5333.3 1933.05  5343.3 1936.01  5362.6 1939.63  5366.9 1939.63
#Mann= 4 ,-1 , 0
  4731.5      .1       0  4940.8     .16       0  5000.3     .07       0
  5006.3     .16       0
Bank Sta=5000.3,5006.3
XS Rating Curve= 0 ,0
Exp/Cntr=0.3,0.1

Type RM Length L Ch R = 1 ,3335    ,483,483,483
BEGIN DESCRIPTION:
UNT019 IN NNOGR 7.0
END DESCRIPTION:
XS GIS Cut Line= 2
       2755175.4     10086554.91      2755924.45     10086586.12
#Sta/Elev= 30
  4666.6 1932.55  4679.7 1931.55  4689.7  1929.8  4699.7 1927.35  4729.7 1917.33
  4749.7  1913.6  4756.5  1909.3  4761.5 1907.42  4769.8 1902.84  4799.8 1892.07
  4849.8 1890.53  4869.8 1884.97  4909.9 1878.55  4949.9 1873.79  4969.9 1874.24
  4979.9 1873.67    4990 1871.29  4998.7 1867.38  5001.5 1866.88  5004.7 1867.38
    5030 1874.43    5040 1876.18  5160.1 1885.85  5220.1 1893.55  5250.2 1898.42
  5330.2 1913.77  5340.2 1916.35  5380.3 1929.85  5390.3  1932.2  5416.3 1936.42
#Mann= 4 ,-1 , 0
  4666.6      .1       0    4990     .16       0  4998.7     .07       0
  5004.7     .16       0
Bank Sta=4998.7,5004.7
XS Rating Curve= 0 ,0
Exp/Cntr=0.3,0.1

Type RM Length L Ch R = 1 ,2852    ,79,79,79
BEGIN DESCRIPTION:
UNT019 IN NNOGR 6.0
END DESCRIPTION:
XS GIS Cut Line= 3
      2755170.33     10086981.95      2755477.65     10087040.99
       2755920.4     10087021.89
#Sta/Elev= 30
  4587.3 1915.28  4605.8 1909.84    4616  1905.8  4622.1 1900.71  4627.2 1900.31
  4636.3 1895.46  4656.7 1889.73  4758.5 1878.69  4835.1 1871.74  4870.5 1869.38
  4880.7 1868.01    4887 1865.37  4898.1 1862.87  4903.2 1862.87  4961.1  1855.3
  4968.1 1855.01  4970.9 1854.51  4974.1 1855.01  5017.4 1855.19  5041.2 1857.03
  5061.2 1860.93  5131.3 1885.42  5180.4 1899.41  5185.4  1899.6  5191.3 1902.34
  5221.4 1910.15  5251.4 1919.87  5301.4 1938.34  5339.9 1950.79  5343.4 1950.79
#Mann= 4 ,-1 , 0
  4587.3      .1       0  4968.1     .07       0  4974.1      .1       0
  5017.4     .16       0
Bank Sta=4968.1,4974.1
XS Rating Curve= 0 ,0
Exp/Cntr=0.3,0.1

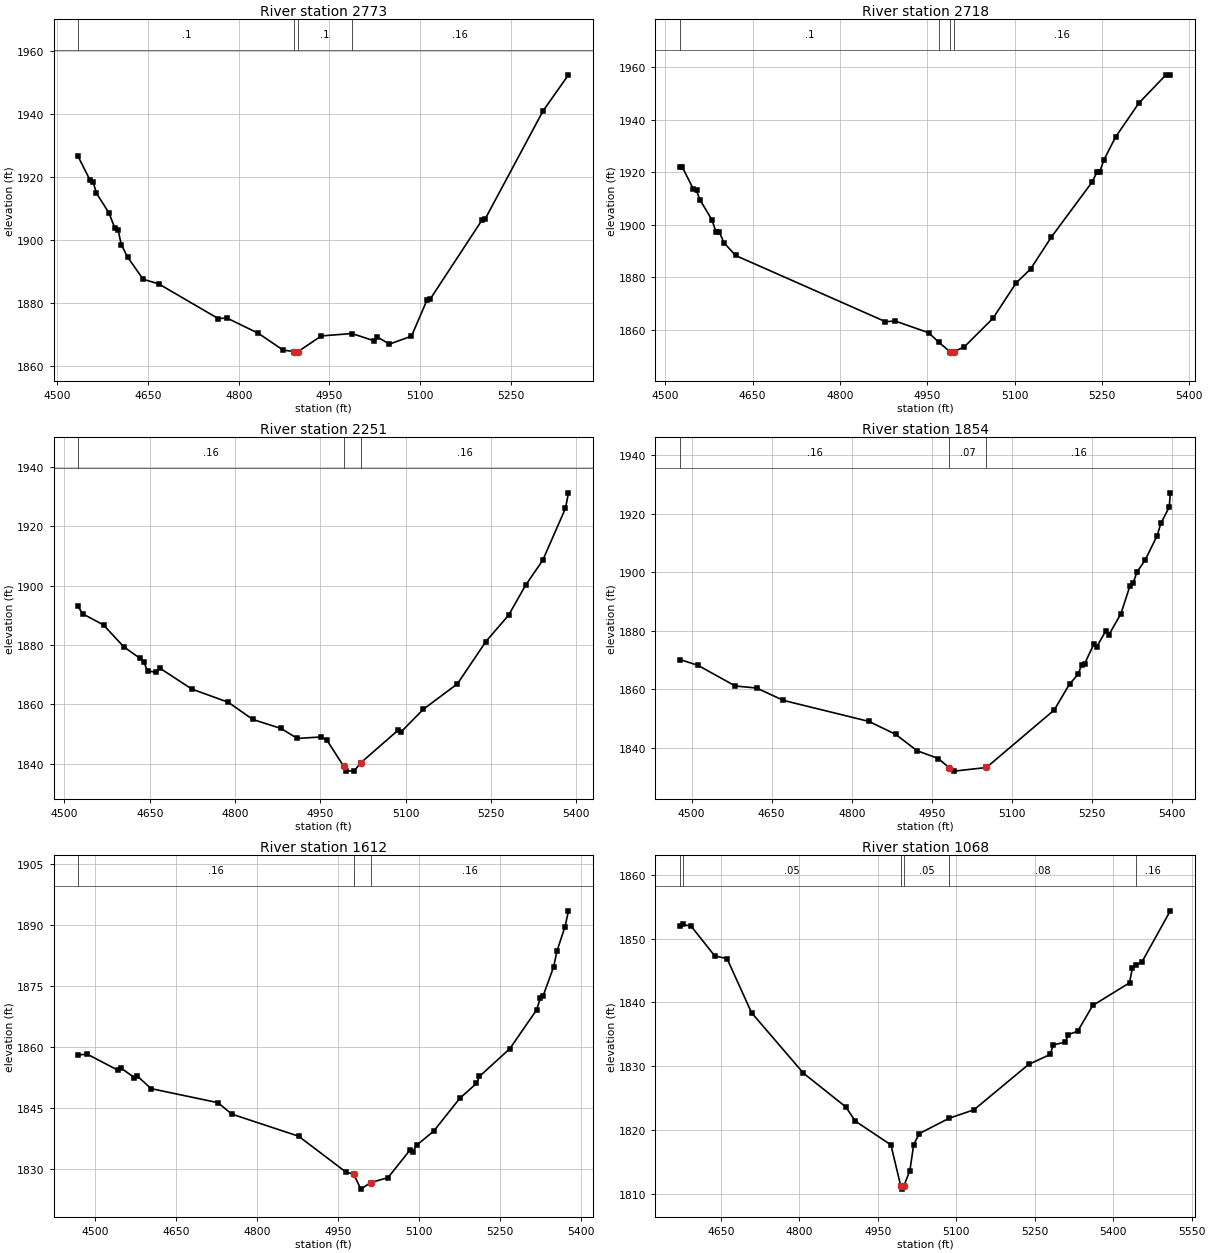
Type RM Length L Ch R = 1 ,2773    ,55,55,55
BEGIN DESCRIPTION:
Mapping XS 6081277f
END DESCRIPTION:
XS GIS Cut Line= 4
       2755139.1     10087002.79      2755593.96     10087115.64
      2755703.34     10087077.44        2755929.     10087054.88
#Sta/Elev= 30
  4534.1 1926.43  4553.8 1918.91    4559 1918.32  4564.4 1914.77    4585 1908.52
  4595.2 1903.56  4600.4 1902.98  4605.6 1898.41  4615.9 1894.48  4641.7  1887.4
  4667.4 1885.94  4765.8 1874.93  4780.7 1875.06  4832.2 1870.25  4873.5 1864.88
  4892.1 1864.44  4894.9 1863.94  4898.1 1864.44  4936.5  1869.4  4987.1 1870.16
  5023.6 1867.88  5028.9 1869.09  5049.3 1866.81  5085.7 1869.32  5111.4 1880.81
  5116.7 1881.11  5202.7 1906.28  5207.7 1906.58  5303.2  1940.8  5345.4 1952.31
#Mann= 4 ,-1 , 0
  4534.1      .1       0  4892.1     .07       0  4898.1      .1       0
  4987.1     .16       0
Bank Sta=4892.1,4898.1
XS Rating Curve= 0 ,0
Exp/Cntr=0.3,0.1

Type RM Length L Ch R = 1 ,2718    ,467,467,467
BEGIN DESCRIPTION:
Mapping XS 04e4e7b2
END DESCRIPTION:
XS GIS Cut Line= 3
      2755135.64     10087080.92      2755475.91     10087179.88
      2755962.06     10087138.21
#Sta/Elev= 30
    4525 1921.93  4529.1 1921.93  4548.3  1913.5  4553.5 1913.04  4559.2  1909.6
    4580 1901.85    4587 1897.27  4592.2  1897.4  4600.8 1893.12  4620.5 1888.31
  4878.1 1863.11  4894.9 1863.35  4952.2 1858.89  4969.9 1855.22  4989.3 1851.64
  4992.1 1851.14  4995.3 1851.64  5013.6 1853.55  5062.6 1864.37  5102.7  1877.9
  5127.4 1883.19    5163 1895.31  5233.2 1916.31  5241.1 1919.94  5246.2 1920.23
  5253.3 1924.73  5273.4 1933.43  5313.5 1946.34  5359.9 1957.05  5367.3 1956.98
#Mann= 4 ,-1 , 0
    4525      .1       0  4969.9     .16       0  4989.3     .07       0
  4995.3     .16       0
Bank Sta=4989.3,4995.3
XS Rating Curve= 0 ,0
Exp/Cntr=0.3,0.1

Type RM Length L Ch R = 1 ,2251    ,397,397,397
BEGIN DESCRIPTION:
UNT019 IN NNOGR 5.0
END DESCRIPTION:
XS GIS Cut Line= 3
      2755123.34      10087346.6      2755446.23       10087607.
       2755893.8      10087612.2
#Sta/Elev= 30
    4524    1893  4532.2 1890.53  4568.9 1886.76  4604.1 1879.46  4632.9 1875.55
  4639.3 1874.38  4646.2 1871.38  4660.2 1870.82  4668.1 1872.19  4724.1 1865.19
  4788.1 1860.75  4831.3 1854.96  4880.9 1851.92  4909.6 1848.57    4951 1849.06
    4961 1848.14    4991 1839.22 4995.02 1837.56  5009.8 1837.67    5021 1840.34
    5087 1851.37    5092 1850.77  5131.1 1858.37  5191.1 1866.95  5241.1 1881.17
  5281.1 1890.06  5311.1 1900.19  5341.1 1908.54  5381.1 1926.04  5386.4 1931.27
#Mann= 3 , 0 , 0
    4524     .16       0    4991     .07       0    5021     .16       0
Bank Sta=4991,5021
XS Rating Curve= 0 ,0
Exp/Cntr=0.3,0.1

Type RM Length L Ch R = 1 ,1854    ,242,242,242
BEGIN DESCRIPTION:
UNT019 IN NNOGR 4.0
END DESCRIPTION:
XS GIS Cut Line= 3
      2755034.75     10088008.04      2755664.98       10087982.
      2755924.47     10087857.44
#Sta/Elev= 30
  4478.2 1870.14  4511.9 1868.17    4582 1861.09    4622  1860.4  4672.1 1856.17
  4832.2 1848.99  4882.3 1844.57  4922.3 1838.99  4962.3 1836.31  4982.3 1833.19
 4992.02    1832  5052.4 1833.24  5179.4  1852.9    5208 1861.74  5223.8 1865.05
  5230.7 1868.19  5236.2 1868.66  5253.3 1875.31  5258.9 1874.47    5276 1879.91
  5281.5 1878.52  5304.2 1885.77  5321.3 1895.37  5326.8 1896.14  5334.7 1900.17
  5349.5 1904.05  5372.1 1912.45    5379 1916.66  5394.8 1922.23  5396.8 1927.11
#Mann= 3 , 0 , 0
  4478.2     .16       0  4982.3     .07       0  5052.4     .16       0
Bank Sta=4982.3,5052.4
XS Rating Curve= 0 ,0
Exp/Cntr=0.3,0.1

Type RM Length L Ch R = 1 ,1612    ,544,544,544
BEGIN DESCRIPTION:
UNT019 IN NNOGR 3.0
END DESCRIPTION:
XS GIS Cut Line= 2
      2755066.03     10088403.87      2755924.44     10088102.13
#Sta/Elev= 30
  4467.7 1858.09  4484.7 1858.27  4541.3 1854.36  4546.6 1854.95  4572.3  1852.5
  4577.6 1852.91  4603.3 1849.81  4727.2 1846.37  4752.9 1843.56  4876.8 1838.14
  4964.4 1829.36  4979.1 1828.81  4992.4 1825.14  5010.9 1826.76  5042.7 1827.95
    5083 1834.64  5088.3 1834.17  5095.7  1835.9  5127.5 1839.37    5176 1847.44
  5206.9  1851.1  5212.3  1852.8  5268.9 1859.64  5318.3 1869.11  5325.5 1872.07
  5330.8 1872.68  5350.1 1879.72  5356.5  1883.7  5371.3 1889.62  5377.6 1893.47
#Mann= 3 , 0 , 0
  4467.7     .16       0  4979.1     .07       0  5010.9     .16       0
Bank Sta=4979.1,5010.9
XS Rating Curve= 0 ,0
Exp/Cntr=0.3,0.1

Type RM Length L Ch R = 1 ,1068    ,670,670,670
BEGIN DESCRIPTION:
UNT019 IN NNOGR 2.0
END DESCRIPTION:
XS GIS Cut Line= 2
      2755258.76     10088903.86       2756118.1     10088528.88
#Sta/Elev= 30
  4571.6 1851.94  4576.9 1852.23  4593.1 1851.96  4638.3 1847.29  4661.7 1846.88
  4708.6 1838.39  4807.7 1828.92  4888.8 1823.62  4906.8  1821.4    4975 1817.67
  4993.8 1811.23  4996.5 1810.73  4999.8 1811.23  5011.3 1813.65  5018.6 1817.72
  5029.3 1819.44  5086.2 1821.84  5133.8 1823.17  5238.4 1830.29  5279.8 1831.86
  5285.2 1833.34  5308.6 1833.79  5314.1 1834.96  5332.1 1835.49  5360.9 1839.53
  5431.2 1843.08  5436.6 1845.37    5444 1845.88  5454.6  1846.3  5509.2 1854.37
#Mann= 6 ,-1 , 0
  4571.6      .1       0  4576.9     .05       0  4993.8     .04       0
  4999.8     .05       0  5086.2     .08       0    5444     .16       0
Bank Sta=4993.8,4999.8
XS Rating Curve= 0 ,0
Exp/Cntr=0.3,0.1

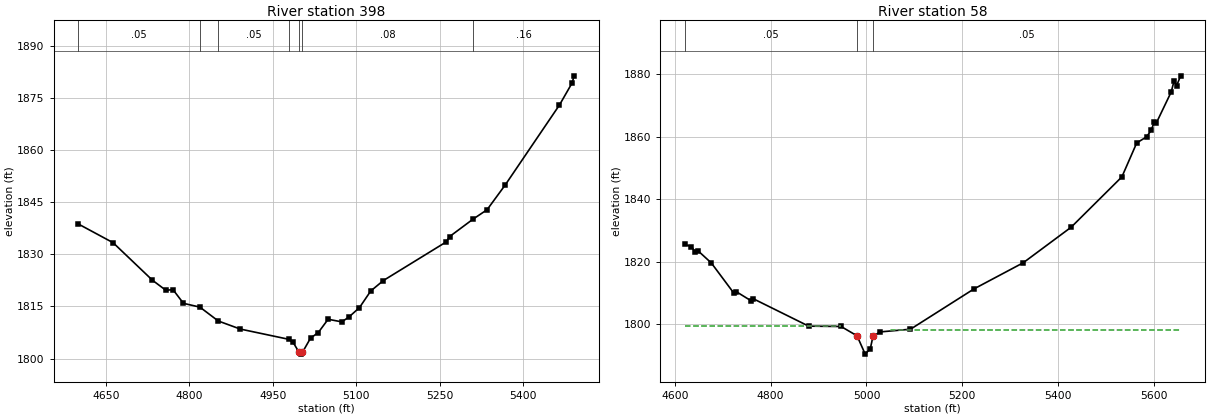
Type RM Length L Ch R = 1 ,398     ,340,340,340
BEGIN DESCRIPTION:
Mapping XS 32184b9a
END DESCRIPTION:
XS GIS Cut Line= 3
      2755809.22     10089101.76       2756302.3     10088936.82
      2756463.59     10088602.09
#Sta/Elev= 30
  4600.5 1838.72    4663 1833.34  4733.8 1822.54  4757.9 1819.65  4770.7 1819.84
  4789.5  1815.9  4819.1 1814.81  4852.1 1810.82  4891.7  1808.5  4978.4 1805.57
  4986.5 1804.73  4997.4 1801.79  5000.2 1801.29  5003.4 1801.79    5018 1805.89
    5032 1807.51  5049.6 1811.32  5074.2 1810.57  5086.5  1811.9  5105.9 1814.65
  5126.3 1819.46  5148.9 1822.45    5262 1833.57  5268.2 1835.12  5310.3 1840.13
  5335.4 1842.82  5368.1 1849.96  5465.5 1872.93  5488.2 1879.26    5492 1881.34
#Mann= 7 ,-1 , 0
  4600.5     .05       0  4819.1      .1       0  4852.1     .05       0
  4978.4     .08       0  4997.4     .07       0  5003.4     .08       0
  5310.3     .16       0
Bank Sta=4997.4,5003.4
XS Rating Curve= 0 ,0
Exp/Cntr=0.3,0.1

Type RM Length L Ch R = 1 ,58      ,0,0,0
BEGIN DESCRIPTION:
UNT019 IN NNOGR 1.0
END DESCRIPTION:
XS GIS Cut Line= 4
      2755995.01     10089202.45      2756277.99      10089277.1
      2756442.92     10089228.49      2756576.45     10088674.67
#Sta/Elev= 30
    4621 1825.57  4634.9 1824.83  4642.9  1823.1    4648  1823.6  4676.3 1819.63
  4723.4 1809.95  4728.6 1810.42  4758.6 1807.59  4763.7 1808.19  4879.4 1799.41
    4947  1799.3  4980.3 1796.32  4997.3 1790.46    5008 1792.21  5013.6 1796.18
  5028.8 1797.57  5091.8 1798.43  5224.2 1811.32  5327.1  1819.7    5427 1831.07
  5532.8 1847.17  5563.7 1858.02  5584.3 1859.98  5594.5 1862.19  5599.8 1864.65
  5604.9  1864.5  5635.7 1874.35  5641.7 1877.92  5646.8 1876.29  5655.3 1879.49
#Mann= 3 , 0 , 0
    4621     .05       0  4980.3     .03       0  5013.6     .05       0
#XS Ineff= 2 , 0
         4946.53 1799.32 5052.17         1798.15
Permanent Ineff=
       F       F
Bank Sta=4980.3,5013.6
XS Rating Curve= 0 ,0
Exp/Cntr=0.3,0.1

Chan Stop Cuts=-1
Use User Specified Reach Order=0
Composite Channel Slope=5