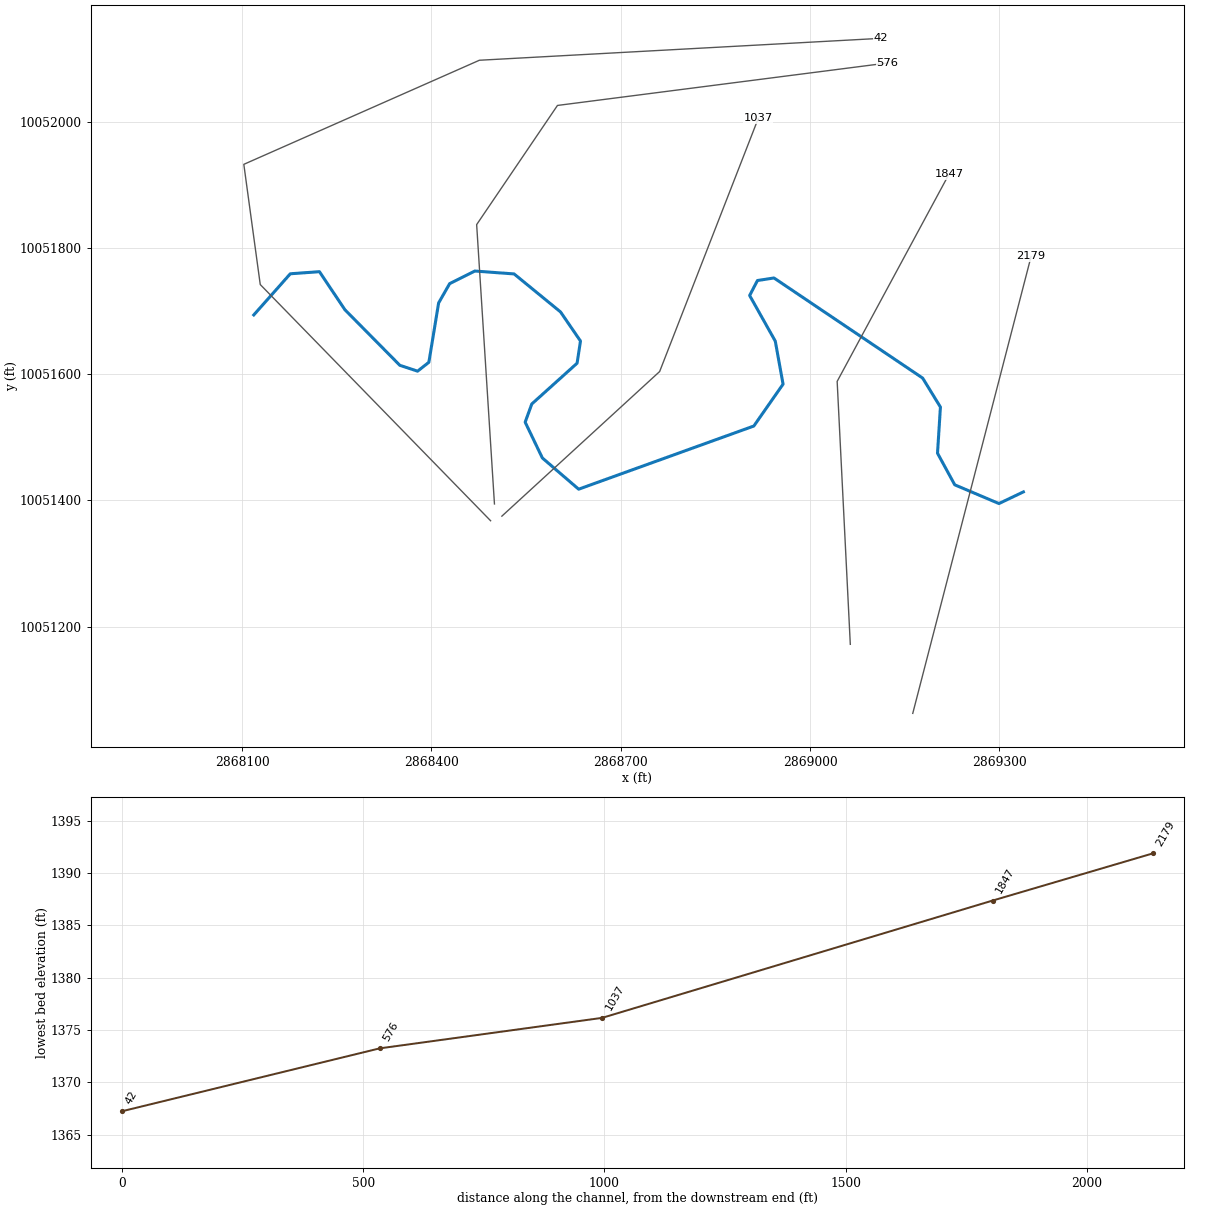
--- UNT019 IN SNOGR.prj (project) ---

Proj Title=UNT019 IN SNOGR Base Level Engineering
Current Plan=p01
Default Exp/Contr=0.3,0.1
English Units
Geom File=g01
Flow File=f01
Plan File=p01
Y Axis Title=Elevation
X Axis Title(PF)=Main Channel Distance
X Axis Title(XS)=Station
BEGIN DESCRIPTION:
UNT019 IN SNOGR
END DESCRIPTION:
DSS Export Rating Curves= 0
DSS Export Rating Curve Sorted= 0
DSS Export Volume Flow Curves= 0
DXF OffsetX= 0
DXF OffsetY= 0
DXF ScaleX= 1
DXF ScaleY= 10

--- UNT019 IN SNOGR.p01 (plan) ---

Plan Title=Multiple Run
Short Identifier=Multiple
Geom File=g01
Flow File=f01
Subcritical Flow
K Sum by GR= 0
Std Step Tol= 0.01
Critical Tol= 0.01
Num of Std Step Trials= 20
Max Error Tol= 0.3
Flow Tol Ratio= 0.001
Split Flow NTrial= 30
Split Flow Tol= 0.02
Split Flow Ratio= 0.02
Log Output Level= 0
Friction Slope Method= 1
Unsteady Friction Slope Method= 2
Unsteady Bridges Friction Slope Method= 1
Parabolic Critical Depth
Global Vel Dist=  1 , 1 , 1
Global Log Level= 0
CheckData=True
Encroach Param= -1, 0, 0, 0
BEGIN DESCRIPTION:
Multiple Run
END DESCRIPTION:

--- UNT019 IN SNOGR.f01 (steady flow) ---

Flow Title=Multiple
Number of Profiles=7
Profile Names=10-year,25-year,50-year,1pct_min,100-year,1pct_plu,500-year
River Rch & RM= UNT019 IN SNOGR,Reach-1,2179
     827    1199    1522    1415    1914    2588    3038
Boundary for River Rch & Prof#=UNT019 IN SNOGR,Reach-1,1
Up Type=0
Dn Type=3
Dn Slope=0.005
Boundary for River Rch & Prof#=UNT019 IN SNOGR,Reach-1,2
Up Type=0
Dn Type=3
Dn Slope=0.005
Boundary for River Rch & Prof#=UNT019 IN SNOGR,Reach-1,3
Up Type=0
Dn Type=3
Dn Slope=0.005
Boundary for River Rch & Prof#=UNT019 IN SNOGR,Reach-1,4
Up Type=0
Dn Type=3
Dn Slope=0.005
Boundary for River Rch & Prof#=UNT019 IN SNOGR,Reach-1,5
Up Type=0
Dn Type=3
Dn Slope=0.005
Boundary for River Rch & Prof#=UNT019 IN SNOGR,Reach-1,6
Up Type=0
Dn Type=3
Dn Slope=0.005
Boundary for River Rch & Prof#=UNT019 IN SNOGR,Reach-1,7
Up Type=0
Dn Type=3
Dn Slope=0.005

--- UNT019 IN SNOGR.g01 (geometry) ---

Geom Title=Existing Conditions
Program Version=4.10

River Reach=UNT019 IN SNOGR ,Reach-1
Reach XY= 30
      2869337.88     10051413.34      2869299.19     10051394.86
      2869229.11     10051424.57      2869201.82     10051474.62
      2869206.42     10051547.79      2869178.23     10051593.72
      2868942.71      10051752.3      2868916.52     10051748.25
      2868904.15     10051724.53      2868944.79     10051652.19
      2868957.09     10051584.05      2868910.78     10051517.72
      2868633.23     10051417.64      2868575.71      10051467.1
      2868548.46     10051523.84      2868558.96     10051552.63
      2868630.74     10051617.23      2868636.11      10051652.4
      2868604.52     10051698.49      2868530.95      10051758.7
      2868468.72      10051763.3      2868428.89     10051743.41
      2868411.36     10051712.75      2868395.88     10051618.72
      2868378.05     10051604.65      2868349.92     10051613.91
      2868262.85     10051701.96      2868222.52     10051762.26
      2868176.34     10051758.95      2868118.47     10051693.73

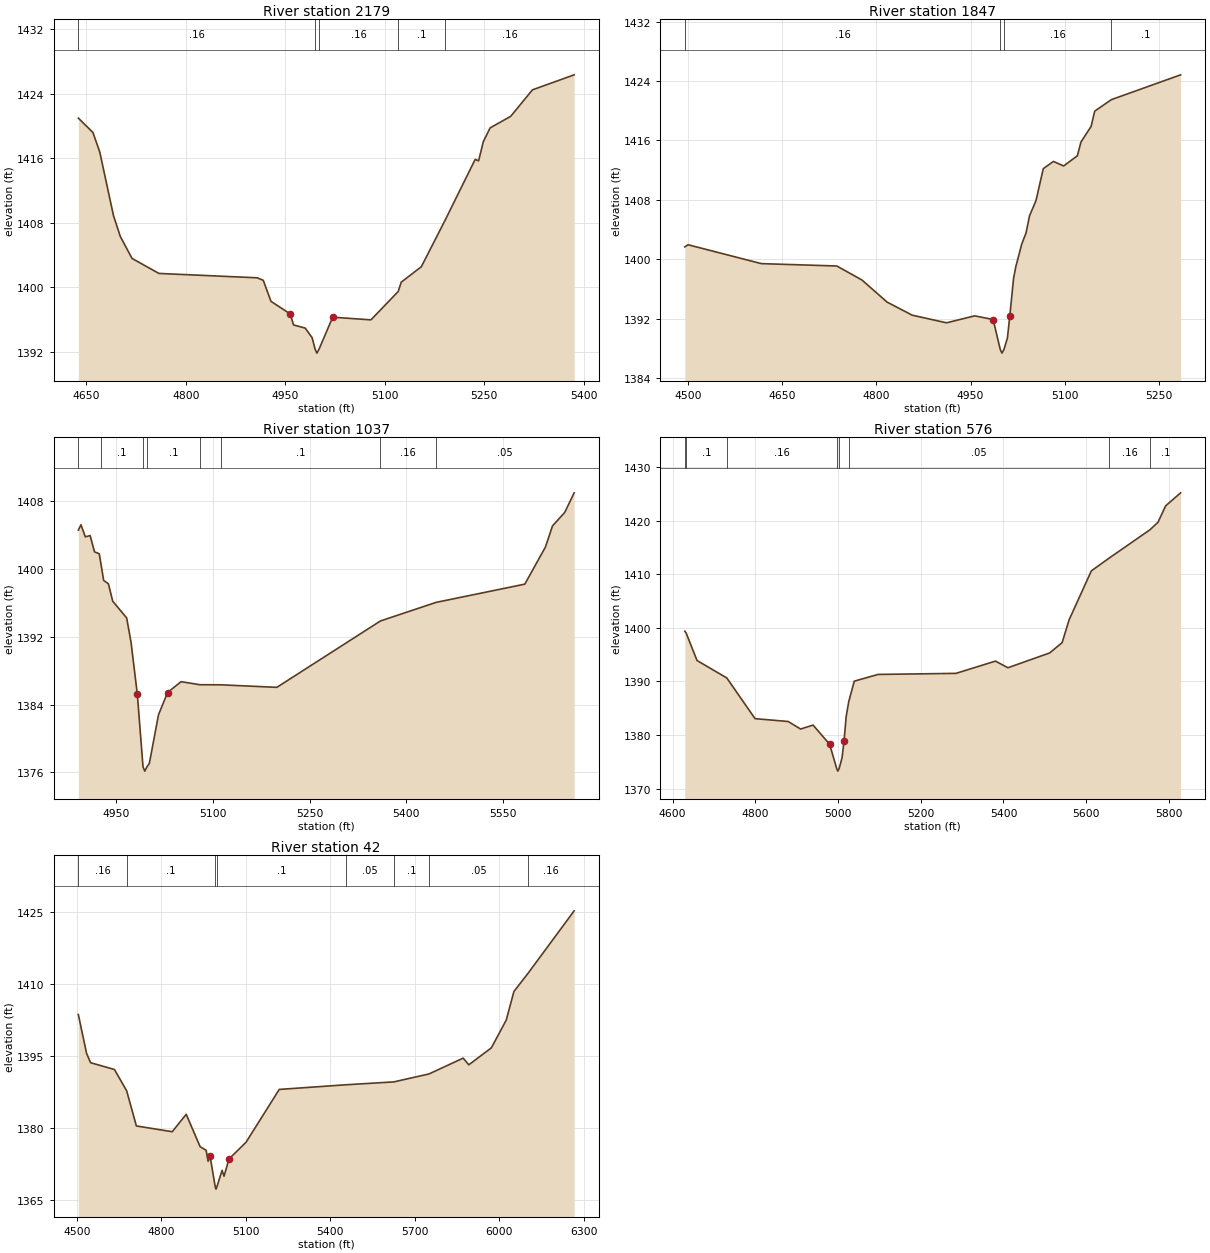
Type RM Length L Ch R = 1 ,2179    ,332,332,332
BEGIN DESCRIPTION:
UNT019 IN SNOGR 4.0
END DESCRIPTION:
XS GIS Cut Line= 2
       2869162.6     10051062.42      2869350.09     10051786.34
#Sta/Elev= 30
    4638 1420.97    4660 1419.19  4670.3 1416.78    4691  1408.9  4701.3 1406.31
    4719 1403.59  4759.6 1401.73  4907.9 1401.19  4916.9 1400.88  4928.6 1398.27
  4957.5 1396.72  4962.6 1395.35  4980.2 1394.96  4990.6 1393.77  4995.1 1392.36
  4997.8 1391.86  5001.1 1392.36  5021.6 1396.31  5079.3 1395.98  5120.4 1399.49
    5125 1400.65  5155.3 1402.56    5191 1408.29  5236.5 1415.85  5241.7 1415.68
  5248.8 1418.05  5259.1 1419.76  5290.1 1421.19  5322.9 1424.47  5385.8 1426.33
#Mann= 5 ,-1 , 0
    4638     .16       0  4995.1     .07       0  5001.1     .16       0
  5120.4      .1       0    5191     .16       0
Bank Sta=4957.5,5021.6
XS Rating Curve= 0 ,0
Exp/Cntr=0.3,0.1

Type RM Length L Ch R = 1 ,1847    ,810,810,810
BEGIN DESCRIPTION:
UNT019 IN SNOGR 3.0
END DESCRIPTION:
XS GIS Cut Line= 3
      2869063.64     10051171.83      2869042.81     10051588.45
      2869219.89     10051916.58
#Sta/Elev= 30
  4494.7 1401.67  4499.9 1401.95  4616.7 1399.41  4736.9 1399.09  4776.9 1397.21
    4817 1394.23    4857 1392.47  4911.8 1391.44  4956.5 1392.38    4986 1391.88
  4997.3 1387.86    5000 1387.36  5003.3 1387.86  5008.7 1389.38  5012.5 1392.31
  5018.5 1397.41  5022.1 1398.99  5031.5 1402.03  5038.4 1403.54    5044 1405.86
  5054.2 1407.88  5065.9  1412.2  5082.1 1413.17  5098.3 1412.56  5120.2 1413.93
  5125.9 1415.78  5142.1 1417.89  5147.8 1419.94  5174.4 1421.49  5284.7 1424.83
#Mann= 4 ,-1 , 0
  4494.7     .16       0  4997.3     .07       0  5003.3     .16       0
  5174.4      .1       0
Bank Sta=4986,5012.5
XS Rating Curve= 0 ,0
Exp/Cntr=0.3,0.1

Type RM Length L Ch R = 1 ,1037    ,461,461,461
BEGIN DESCRIPTION:
UNT019 IN SNOGR 2.0
END DESCRIPTION:
XS GIS Cut Line= 3
      2868511.56     10051374.92      2868761.56     10051604.08
      2868917.79     10052005.08
#Sta/Elev= 30
  4890.8 1404.58  4894.9 1405.21  4901.7 1403.79  4909.1 1403.94  4915.9 1402.02
  4923.3 1401.79  4926.6 1400.27  4930.1 1398.65  4937.5 1398.25  4944.2 1396.19
  4965.8 1394.23  4972.6 1391.36 4982.39 1385.21  4991.2 1376.66  4993.9 1376.16
  4997.2 1376.66    5001 1377.06  5015.2  1382.8  5029.3 1385.43  5050.3 1386.71
  5079.3 1386.35  5111.6 1386.34  5198.9 1386.04  5359.7 1393.87  5446.1 1396.06
  5583.7 1398.21  5615.7 1402.58  5626.7 1405.08  5645.6 1406.66  5660.3 1408.98
#Mann= 8 ,-1 , 0
  4890.8     .16       0  4926.6      .1       0  4991.2     .07       0
  4997.2      .1       0  5079.3     .16       0  5111.6      .1       0
  5359.7     .16       0  5446.1     .05       0
Bank Sta=4982.39,5029.3
XS Rating Curve= 0 ,0
Exp/Cntr=0.3,0.1

Type RM Length L Ch R = 1 ,576     ,534,534,534
BEGIN DESCRIPTION:
Mapping XS 4f1439cf
END DESCRIPTION:
XS GIS Cut Line= 4
      2868499.81     10051394.21       2868471.6     10051836.86
      2868599.64     10052025.67      2869122.65     10052092.94
#Sta/Elev= 30
  4629.4 1399.38  4632.7 1399.04    4659 1393.91    4731 1390.65  4799.3 1383.05
  4879.4 1382.52  4909.5 1381.11  4939.6 1381.85  4979.6 1378.27  4996.7 1373.75
  4999.4 1373.25  5002.7 1373.75  5009.7 1375.75 5014.43 1378.86  5019.7 1383.47
  5025.9 1386.24  5039.2 1390.05  5096.7 1391.31  5285.3 1391.51  5380.6  1393.8
  5410.8 1392.56  5511.6 1395.32  5541.9 1397.25  5558.6 1401.48  5612.5 1410.65
  5655.4 1413.03  5754.3 1418.33  5773.8 1419.74  5792.1 1422.79  5828.4 1425.23
#Mann= 8 ,-1 , 0
  4629.4     .16       0  4632.7      .1       0    4731     .16       0
  4996.7     .07       0  5002.7     .16       0  5025.9     .05       0
  5655.4     .16       0  5754.3      .1       0
Bank Sta=4979.6,5014.43
XS Rating Curve= 0 ,0
Exp/Cntr=0.3,0.1

Type RM Length L Ch R = 1 ,42      ,0,0,0
BEGIN DESCRIPTION:
UNT019 IN SNOGR 1.0
END DESCRIPTION:
XS GIS Cut Line= 5
       2868493.7     10051367.63      2868128.72      10051741.9
      2868102.68     10051932.35      2868475.94     10052097.28
      2869111.82       10052132.
#Sta/Elev= 30
  4505.5 1403.62  4534.7 1395.55  4548.9 1393.59  4633.7 1392.17  4677.1 1387.73
  4711.5 1380.41  4838.8 1379.21  4888.4 1382.84  4937.8 1376.09  4959.1 1375.35
  4966.1 1373.05  4973.2 1374.05  4991.4 1367.75  4994.1 1367.25  4997.4 1367.75
  5015.7 1371.17  5022.7 1369.95  5040.2 1373.52  5100.8 1377.02  5218.7 1388.02
  5455.3 1388.99  5625.1 1389.59  5749.9 1391.24  5871.5 1394.54  5891.5 1393.15
  5971.6 1396.69  6024.3 1402.46  6051.7 1408.44  6102.1 1412.24  6265.4 1425.23
#Mann= 8 ,-1 , 0
  4505.5     .16       0  4677.1      .1       0  4991.4     .07       0
  4997.4      .1       0  5455.3     .05       0  5625.1      .1       0
  5749.9     .05       0  6102.1     .16       0
Bank Sta=4973.2,5040.2
XS Rating Curve= 0 ,0
Exp/Cntr=0.3,0.1

Chan Stop Cuts=-1
Use User Specified Reach Order=0
Composite Channel Slope=5