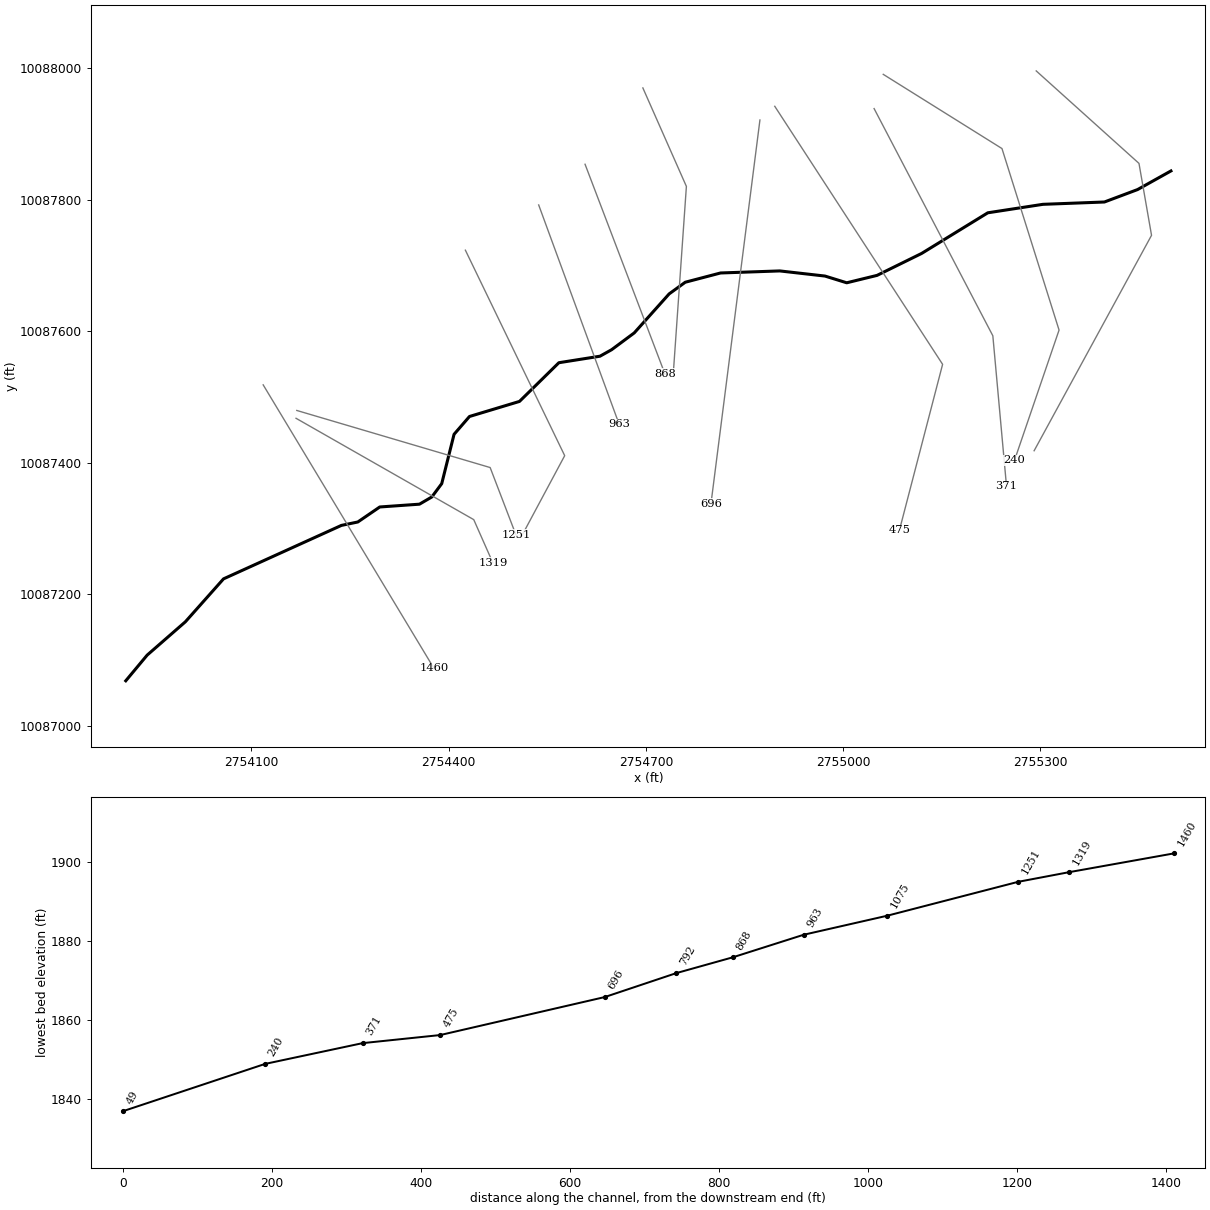
--- UNT020 IN NNOGR.prj (project) ---

Proj Title=UNT020 IN NNOGR Base Level Engineering
Current Plan=p01
Default Exp/Contr=0.3,0.1
English Units
Geom File=g01
Flow File=f01
Plan File=p01
Y Axis Title=Elevation
X Axis Title(PF)=Main Channel Distance
X Axis Title(XS)=Station
BEGIN DESCRIPTION:
UNT020 IN NNOGR
END DESCRIPTION:
DSS Export Rating Curves= 0
DSS Export Rating Curve Sorted= 0
DSS Export Volume Flow Curves= 0
DXF OffsetX= 0
DXF OffsetY= 0
DXF ScaleX= 1
DXF ScaleY= 10

--- UNT020 IN NNOGR.p01 (plan) ---

Plan Title=Multiple Run
Short Identifier=Multiple
Geom File=g01
Flow File=f01
Subcritical Flow
K Sum by GR= 0
Std Step Tol= 0.01
Critical Tol= 0.01
Num of Std Step Trials= 20
Max Error Tol= 0.3
Flow Tol Ratio= 0.001
Split Flow NTrial= 30
Split Flow Tol= 0.02
Split Flow Ratio= 0.02
Log Output Level= 0
Friction Slope Method= 1
Unsteady Friction Slope Method= 2
Unsteady Bridges Friction Slope Method= 1
Parabolic Critical Depth
Global Vel Dist=  1 , 1 , 1
Global Log Level= 0
CheckData=True
Encroach Param= -1, 0, 0, 0
BEGIN DESCRIPTION:
Multiple Run
END DESCRIPTION:

--- UNT020 IN NNOGR.f01 (steady flow) ---

Flow Title=Multiple
Program Version=4.10
Number of Profiles= 7
Profile Names=10-year,25-year,50-year,1pct_min,100-year,1pct_plu,500-year
River Rch & RM=UNT020 IN NNOGR,Reach-1         ,1460
     171     225     267     235     317     429     446
Boundary for River Rch & Prof#=UNT020 IN NNOGR,Reach-1         , 1
Up Type= 0
Dn Type= 3
Dn Slope=0.063
Boundary for River Rch & Prof#=UNT020 IN NNOGR,Reach-1         , 2
Up Type= 0
Dn Type= 3
Dn Slope=0.063
Boundary for River Rch & Prof#=UNT020 IN NNOGR,Reach-1         , 3
Up Type= 0
Dn Type= 3
Dn Slope=0.063
Boundary for River Rch & Prof#=UNT020 IN NNOGR,Reach-1         , 4
Up Type= 0
Dn Type= 3
Dn Slope=0.063
Boundary for River Rch & Prof#=UNT020 IN NNOGR,Reach-1         , 5
Up Type= 0
Dn Type= 3
Dn Slope=0.063
Boundary for River Rch & Prof#=UNT020 IN NNOGR,Reach-1         , 6
Up Type= 0
Dn Type= 3
Dn Slope=0.063
Boundary for River Rch & Prof#=UNT020 IN NNOGR,Reach-1         , 7
Up Type= 0
Dn Type= 3
Dn Slope=0.063
DSS Import GetInterval= 0
DSS Import GetPeak= 0
DSS Import FillOption= 0

--- UNT020 IN NNOGR.g01 (geometry) ---

Geom Title=Existing Conditions
Program Version=4.10

River Reach=UNT020 IN NNOGR ,Reach-1
Reach XY= 30
      2753909.16     10087068.44      2753941.71      10087107.5
      2753999.77     10087158.13      2754057.84     10087223.46
      2754237.02     10087304.72      2754262.02     10087309.93
      2754295.42     10087332.76      2754355.77     10087337.01
      2754374.52     10087347.95      2754389.62     10087368.26
      2754408.37     10087443.26      2754431.81     10087470.35
      2754507.85     10087493.26      2754567.75     10087552.12
      2754630.25     10087562.01      2754647.96     10087571.91
      2754682.33     10087597.43      2754735.46      10087656.8
      2754759.94     10087674.51      2754813.58     10087688.58
      2754903.69      10087691.7      2754972.44     10087683.89
      2755005.43     10087673.66       2755051.6     10087684.93
      2755119.31     10087718.26      2755219.98     10087780.08
      2755303.78     10087792.97      2755397.32     10087796.51
      2755447.76     10087815.43      2755498.47     10087843.73

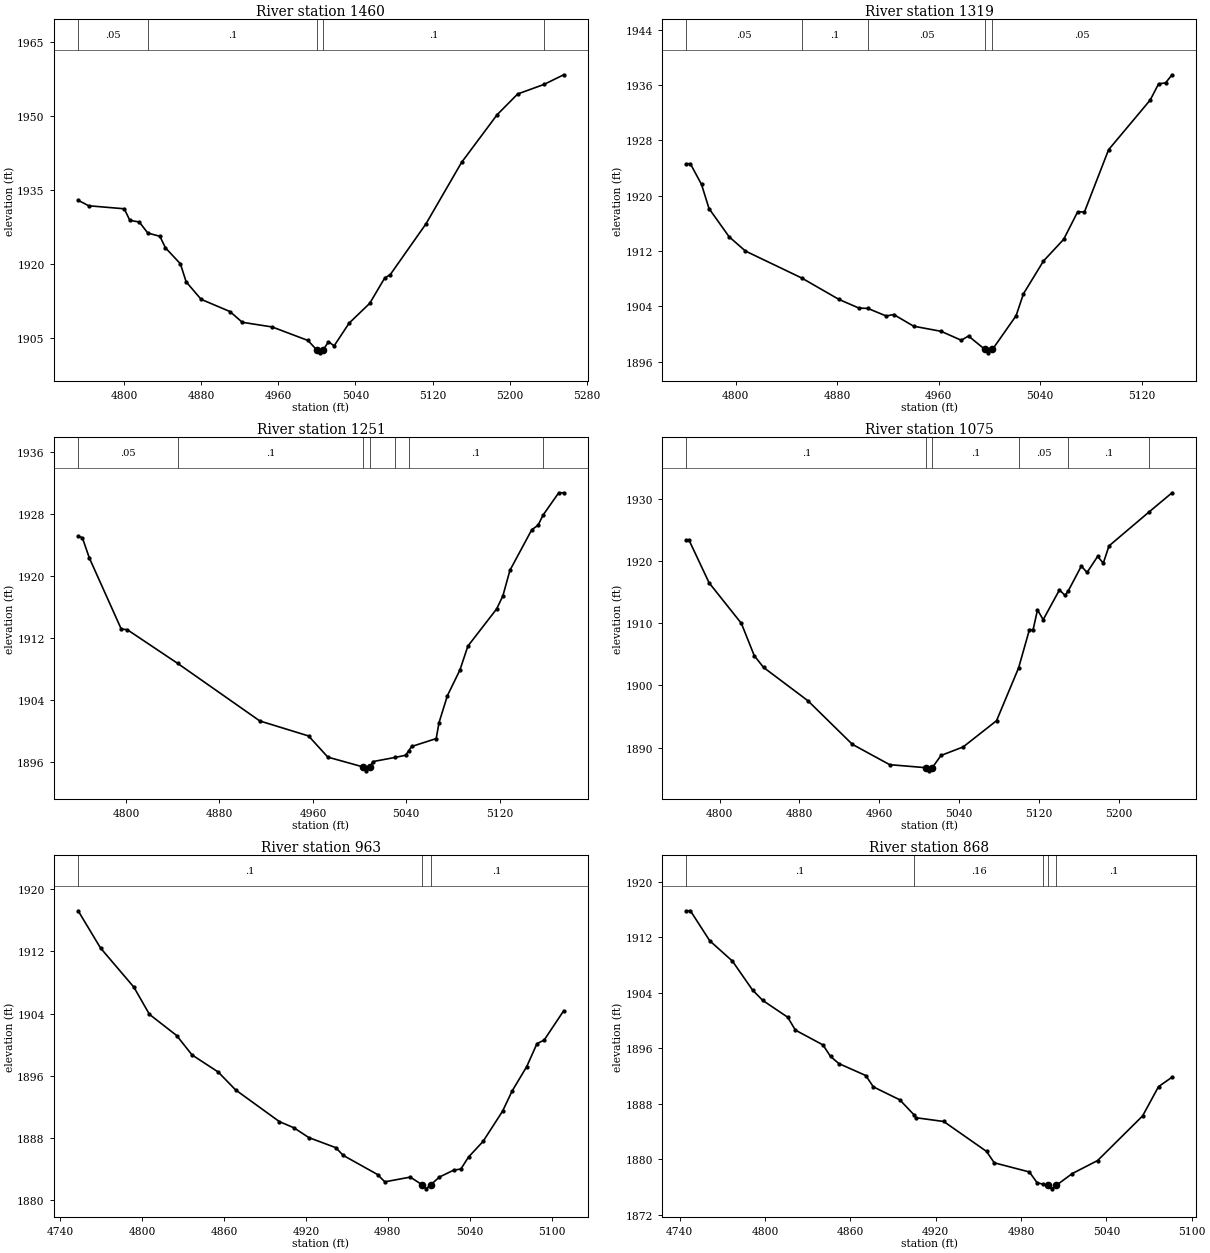
Type RM Length L Ch R = 1 ,1460    ,141,141,141
BEGIN DESCRIPTION:
UNT020 IN NNOGR 4.0
END DESCRIPTION:
XS GIS Cut Line= 2
      2754118.11     10087518.46      2754377.76     10087087.43
#Sta/Elev= 30
  4752.6 1932.99  4763.5 1931.87  4800.4 1931.26  4806.2  1928.9  4815.9 1928.59
  4824.8 1926.34  4837.3 1925.68  4843.1 1923.34  4858.6  1920.1  4864.5 1916.46
    4880 1912.91  4909.9 1910.43  4922.7 1908.25  4953.8  1907.3  4990.7 1904.57
  5000.3 1902.56    5003 1902.06  5006.3 1902.56    5012 1904.31  5017.9 1903.48
  5033.4 1908.08  5054.7 1912.08  5070.3 1917.23  5076.1 1917.93    5113 1928.19
  5149.9 1940.65  5186.8 1950.33  5208.1 1954.53  5235.3 1956.46  5255.8 1958.42
#Mann= 5 ,-1 , 0
  4752.6     .05       0  4824.8      .1       0  5000.3     .07       0
  5006.3      .1       0  5235.3      .1       0
Bank Sta=5000.3,5006.3
XS Rating Curve= 0 ,0
Exp/Cntr=0.3,0.1

Type RM Length L Ch R = 1 ,1319    ,68,68,68
BEGIN DESCRIPTION:
Mapping XS d2fa0b19
END DESCRIPTION:
XS GIS Cut Line= 3
      2754168.09      10087467.6      2754438.31      10087313.5
       2754467.3       10087248.
#Sta/Elev= 30
  4761.2 1924.63  4764.3 1924.63  4773.1 1921.63    4779 1918.15  4794.9 1914.06
  4807.7 1912.01    4852 1908.12  4881.3 1905.03  4897.1 1903.77  4904.2 1903.72
  4918.7 1902.62  4924.5 1902.84  4940.3 1901.15  4961.9 1900.41  4977.8 1899.12
  4983.5 1899.73  4996.4  1897.8  4999.1  1897.3  5002.4  1897.8    5021 1902.66
  5026.8 1905.83  5042.6 1910.57  5058.5  1913.7  5069.5 1917.67  5074.9 1917.67
  5093.9 1926.65  5126.7 1933.83  5133.3 1936.17  5138.8 1936.31  5143.9 1937.48
#Mann= 5 ,-1 , 0
  4761.2     .05       0    4852      .1       0  4904.2     .05       0
  4996.4    .035       0  5002.4     .05       0
Bank Sta=4996.4,5002.4
XS Rating Curve= 0 ,0
Exp/Cntr=0.3,0.1

Type RM Length L Ch R = 1 ,1251    ,176,176,176
BEGIN DESCRIPTION:
Mapping XS b584cf25
END DESCRIPTION:
XS GIS Cut Line= 3
      2754169.24     10087479.51      2754463.26     10087392.71
      2754502.33     10087290.71
#Sta/Elev= 30
    4759 1925.12  4762.6 1924.94  4768.6 1922.32  4795.9 1913.16  4801.1 1913.07
  4844.2 1908.73  4914.6  1901.3  4956.3 1899.37  4972.8 1896.64  5003.1 1895.37
  5005.9 1894.87  5009.1 1895.37  5011.3 1896.06  5030.4  1896.6  5039.4 1896.88
  5042.1 1897.47  5044.6 1898.01  5065.6 1899.03    5068 1901.08  5075.2 1904.57
  5085.9 1907.87  5092.7 1910.95  5117.4 1915.76  5122.7 1917.44  5128.7 1920.72
  5147.4 1925.96  5152.8 1926.54  5157.1 1927.85  5170.5 1930.73  5174.8 1930.73
#Mann= 7 ,-1 , 0
    4759     .05       0  4844.2      .1       0  5003.1     .07       0
  5009.1      .1       0  5030.4     .05       0  5042.1      .1       0
  5157.1     .05       0
Bank Sta=5003.1,5009.1
XS Rating Curve= 0 ,0
Exp/Cntr=0.3,0.1

Type RM Length L Ch R = 1 ,1075    ,112,112,112
BEGIN DESCRIPTION:
UNT020 IN NNOGR 3.0
END DESCRIPTION:
XS GIS Cut Line= 3
      2754425.58     10087723.25       2754576.6     10087410.78
      2754510.94      10087288.1
#Sta/Elev= 30
  4766.8 1923.36  4769.3 1923.36  4789.5 1916.47  4821.8 1909.96  4834.7 1904.78
    4844 1902.89  4888.4 1897.54  4932.9 1890.54  4970.3 1887.27  5006.9 1886.78
  5009.6 1886.28  5012.9 1886.78  5021.7 1888.75  5043.9 1890.12  5077.3 1894.33
  5099.4 1902.82  5110.2 1908.94  5113.9 1908.94  5118.3 1912.13    5124 1910.55
  5140.3 1915.34  5145.9 1914.44  5149.2 1915.21  5162.2 1919.16  5167.9 1918.13
  5178.5 1920.71  5184.2 1919.64  5189.9  1922.4    5230 1927.85    5253 1930.93
#Mann= 6 ,-1 , 0
  4766.8      .1       0  5006.9     .07       0  5012.9      .1       0
  5099.4     .05       0  5149.2      .1       0    5230     .05       0
Bank Sta=5006.9,5012.9
XS Rating Curve= 0 ,0
Exp/Cntr=0.3,0.1

Type RM Length L Ch R = 1 ,963     ,95,95,95
BEGIN DESCRIPTION:
Mapping XS a7b82946
END DESCRIPTION:
XS GIS Cut Line= 2
      2754537.05     10087792.02      2754659.49     10087458.27
#Sta/Elev= 30
  4753.3 1917.23  4769.7 1912.44  4794.1 1907.41  4805.5 1903.91  4825.4 1901.19
  4836.7 1898.69  4855.8  1896.5  4868.6 1894.19  4900.6 1890.12  4911.3 1889.32
  4922.2 1888.06    4942 1886.76  4947.3 1885.78  4972.5 1883.31  4977.8 1882.37
  4996.5 1882.98  5005.3 1881.97  5008.1 1881.47  5011.3 1881.97  5017.8 1882.99
  5028.2 1883.87  5033.5 1884.02  5039.1 1885.56  5049.7 1887.56    5064 1891.45
    5071 1894.05  5081.7 1897.19  5089.2 1900.14  5094.5 1900.61  5108.8 1904.38
#Mann= 3 ,-1 , 0
  4753.3      .1       0  5005.3     .07       0  5011.3      .1       0
Bank Sta=5005.3,5011.3
XS Rating Curve= 0 ,0
Exp/Cntr=0.3,0.1

Type RM Length L Ch R = 1 ,868     ,76,76,76
BEGIN DESCRIPTION:
Mapping XS f5651f44
END DESCRIPTION:
XS GIS Cut Line= 2
      2754607.57     10087853.89      2754729.11     10087534.86
#Sta/Elev= 30
  4744.8 1915.82  4747.6 1915.82  4761.2  1911.5  4777.1 1908.58  4791.3  1904.4
  4798.5  1902.9    4816 1900.49  4821.4 1898.63  4840.8  1896.5  4846.1 1894.84
    4852 1893.81  4870.9 1892.09  4876.2 1890.46  4894.8 1888.59  4904.9 1886.41
  4906.3 1886.01  4925.7 1885.47  4955.8 1881.16  4961.2 1879.52  4985.9  1878.2
  4991.3 1876.66  4995.7 1876.43  4998.8 1876.27  5001.5 1875.77  5004.8 1876.27
    5016 1877.96  5033.9 1879.85  5065.5 1886.27  5076.7 1890.49  5086.2 1891.85
#Mann= 5 ,-1 , 0
  4744.8      .1       0  4904.9     .16       0  4995.7      .1       0
  4998.8     .07       0  5004.8      .1       0
Bank Sta=4998.8,5004.8
XS Rating Curve= 0 ,0
Exp/Cntr=0.3,0.1

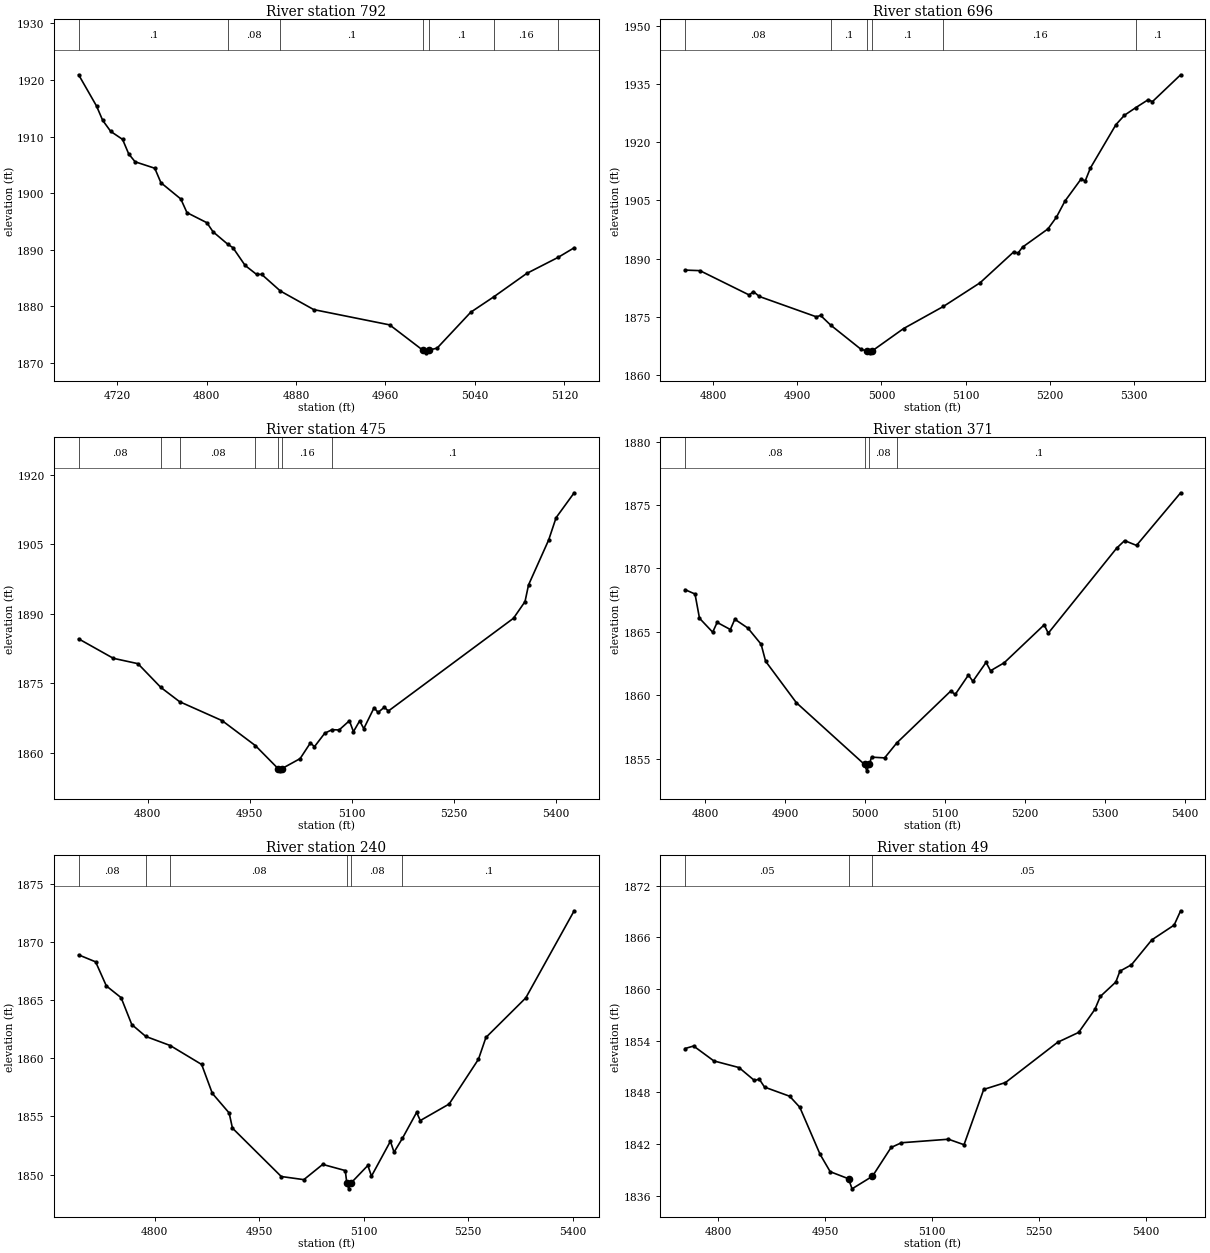
Type RM Length L Ch R = 1 ,792     ,96,96,96
BEGIN DESCRIPTION:
Mapping XS be252a19
END DESCRIPTION:
XS GIS Cut Line= 3
      2754695.47     10087969.96      2754761.66     10087820.23
      2754742.13     10087541.41
#Sta/Elev= 30
  4685.6 1920.91  4701.6 1915.39  4707.1 1912.86  4714.3  1910.9  4724.9 1909.49
  4730.4 1906.92  4736.1 1905.53  4753.7 1904.39  4759.2 1901.83    4777 1898.95
  4782.5 1896.54  4800.3 1894.76  4805.8 1893.16  4819.2 1890.92  4823.6 1890.35
  4834.5 1887.21  4844.7 1885.63  4849.3 1885.63  4866.1 1882.68  4895.9  1879.4
  4963.8  1876.7  4993.2 1872.26  4995.9 1871.76  4999.2 1872.26  5006.2 1872.59
  5036.3 1878.94  5056.9 1881.66  5086.4  1885.8  5114.4 1888.63  5128.8 1890.33
#Mann= 7 ,-1 , 0
  4685.6      .1       0  4819.2     .08       0  4866.1      .1       0
  4993.2     .07       0  4999.2      .1       0  5056.9     .16       0
  5114.4      .1       0
Bank Sta=4993.2,4999.2
XS Rating Curve= 0 ,0
Exp/Cntr=0.3,0.1

Type RM Length L Ch R = 1 ,696     ,221,221,221
BEGIN DESCRIPTION:
UNT020 IN NNOGR 2.0
END DESCRIPTION:
XS GIS Cut Line= 2
      2754873.48     10087921.19      2754798.99     10087337.42
#Sta/Elev= 30
  4766.9 1887.02  4784.5 1886.88    4843 1880.61    4848 1881.49  4855.1 1880.22
  4922.8 1874.98  4927.8 1875.34  4939.6 1872.88    4976 1866.58  4983.1  1866.2
  4985.9  1865.7  4989.1  1866.2  5026.4 1871.96  5073.7 1877.66  5117.2 1883.75
  5157.2 1891.72  5162.3 1891.41  5167.6 1892.93  5197.8 1897.63  5207.9 1900.66
    5218  1904.8  5237.1 1910.47  5242.1    1910  5248.2 1913.31  5278.5 1924.48
  5288.6 1926.91  5302.1 1928.88  5316.9 1930.93  5321.9 1930.43  5355.4 1937.35
#Mann= 6 ,-1 , 0
  4766.9     .08       0  4939.6      .1       0  4983.1     .07       0
  4989.1      .1       0  5073.7     .16       0  5302.1      .1       0
Bank Sta=4983.1,4989.1
XS Rating Curve= 0 ,0
Exp/Cntr=0.3,0.1

Type RM Length L Ch R = 1 ,475     ,104,104,104
BEGIN DESCRIPTION:
Mapping XS 9237e673
END DESCRIPTION:
XS GIS Cut Line= 3
      2754896.05     10087942.02      2755151.26     10087549.67
       2755085.6     10087297.42
#Sta/Elev= 30
  4698.5 1884.58  4749.5 1880.38  4785.7 1879.22  4819.4 1874.09    4847 1871.01
  4909.5 1866.92  4958.5 1861.52  4991.7 1856.58  4994.4 1856.08  4997.7 1856.58
  5024.2 1858.72  5039.3 1862.11  5045.3  1861.3  5060.4  1864.2  5071.2 1864.97
  5081.5  1864.9  5096.7  1866.9  5102.6 1864.53  5111.8 1866.88  5117.8 1865.19
  5132.9 1869.68  5138.9  1868.7    5148 1869.81    5154    1869    5338 1889.03
  5354.9 1892.62  5360.1 1896.23  5389.7 1905.93  5400.6 1910.74  5427.2 1916.12
#Mann= 7 ,-1 , 0
  4698.5     .08       0  4819.4      .1       0    4847     .08       0
  4958.5     .16       0  4991.7     .07       0  4997.7     .16       0
  5071.2      .1       0
Bank Sta=4991.7,4997.7
XS Rating Curve= 0 ,0
Exp/Cntr=0.3,0.1

Type RM Length L Ch R = 1 ,371     ,131,131,131
BEGIN DESCRIPTION:
Mapping XS c5783695
END DESCRIPTION:
XS GIS Cut Line= 3
       2755047.1     10087938.54      2755227.65     10087593.07
      2755248.48     10087363.92
#Sta/Elev= 30
  4775.1 1868.32  4787.5 1867.98  4793.1 1866.07  4809.6 1864.97  4815.2 1865.74
  4831.7 1865.18  4837.3 1865.99  4853.7 1865.29  4870.2 1864.02  4875.8 1862.68
  4914.3 1859.41  4999.6 1854.54  5002.4 1854.04  5005.6 1854.54  5008.3 1855.12
  5024.7 1855.06  5039.9 1856.24  5107.4 1860.33    5113 1860.06  5129.5 1861.59
  5135.1  1861.1  5151.6 1862.59  5157.2 1861.93  5174.3 1862.56  5224.3 1865.55
  5229.4 1864.89  5314.9 1871.59  5324.9 1872.19  5339.8 1871.81    5395 1875.96
#Mann= 4 ,-1 , 0
  4775.1     .08       0  4999.6     .07       0  5005.6     .08       0
  5039.9      .1       0
Bank Sta=4999.6,5005.6
XS Rating Curve= 0 ,0
Exp/Cntr=0.3,0.1

Type RM Length L Ch R = 1 ,240     ,191,191,191
BEGIN DESCRIPTION:
Mapping XS a397c6e2
END DESCRIPTION:
XS GIS Cut Line= 4
      2755061.02     10087990.61      2755241.53     10087877.79
      2755328.34     10087601.75      2755260.64     10087403.85
#Sta/Elev= 30
  4690.6 1868.89    4715 1868.29  4730.4 1866.22  4751.6 1865.21  4766.9  1862.9
    4787 1861.88    4822  1861.1  4867.2 1859.47  4882.5 1856.99  4906.7  1855.3
  4911.4    1854  4981.5 1849.84  5013.9 1849.57    5041 1850.88  5073.4 1850.35
  5075.6 1849.28  5078.4 1848.78  5081.6 1849.28  5105.8 1850.79    5111 1849.87
  5138.2 1852.87  5143.4 1851.93  5155.5 1853.13  5175.8 1855.35  5181.1 1854.65
  5222.5 1856.07  5264.6 1859.92  5275.3 1861.79  5332.5 1865.19    5402 1872.68
#Mann= 6 ,-1 , 0
  4690.6     .08       0    4787     .05       0    4822     .08       0
  5075.6     .07       0  5081.6     .08       0  5155.5      .1       0
Bank Sta=5075.6,5081.6
XS Rating Curve= 0 ,0
Exp/Cntr=0.3,0.1

Type RM Length L Ch R = 1 ,49      ,0,0,0
BEGIN DESCRIPTION:
UNT020 IN NNOGR 1.0
END DESCRIPTION:
XS GIS Cut Line= 4
      2755293.62     10087995.84      2755449.87     10087855.22
      2755468.96     10087745.85      2755290.44     10087418.27
#Sta/Elev= 30
  4753.8 1853.09  4765.7 1853.38  4794.1 1851.65  4829.3 1850.88  4850.9 1849.38
  4857.7 1849.54  4865.1 1848.61  4900.3 1847.55  4914.5 1846.27  4942.9 1840.81
  4957.1 1838.79  4982.8 1837.97  4987.7  1836.8  5016.3 1838.26  5042.4  1841.6
  5056.9 1842.15  5122.8 1842.56  5144.6 1841.92  5172.2 1848.34  5202.7 1849.14
  5275.7 1853.81  5305.2 1854.96    5328 1857.64  5335.5 1859.13  5357.3 1860.81
    5363 1862.07  5379.2 1862.81  5407.7  1865.7    5439 1867.42  5448.1 1869.08
#Mann= 3 , 0 , 0
  4753.8     .05       0  4982.8     .03       0  5016.3     .05       0
Bank Sta=4982.8,5016.3
XS Rating Curve= 0 ,0
Exp/Cntr=0.3,0.1

Chan Stop Cuts=-1
Use User Specified Reach Order=0
Composite Channel Slope=5