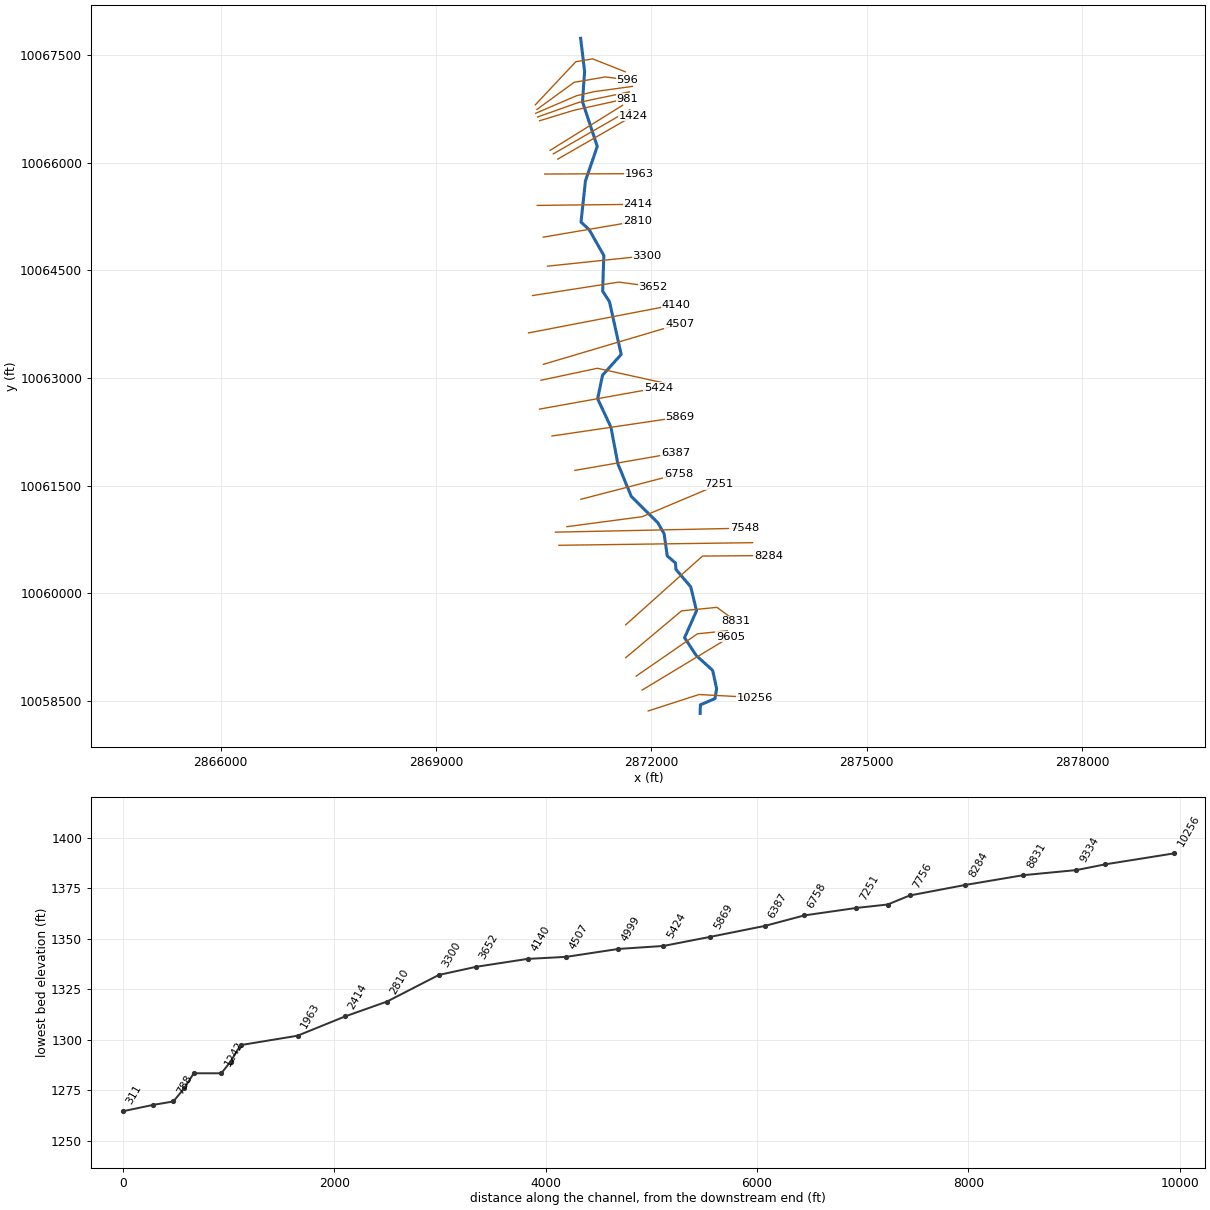
--- UNT020 IN SNOGR.prj (project) ---

Proj Title=UNT020 IN SNOGR Base Level Engineering
Current Plan=p01
Default Exp/Contr=0.3,0.1
English Units
Geom File=g01
Flow File=f01
Plan File=p01
Y Axis Title=Elevation
X Axis Title(PF)=Main Channel Distance
X Axis Title(XS)=Station
BEGIN DESCRIPTION:
UNT020 IN SNOGR
END DESCRIPTION:
DSS Export Rating Curves= 0
DSS Export Rating Curve Sorted= 0
DSS Export Volume Flow Curves= 0
DXF OffsetX= 0
DXF OffsetY= 0
DXF ScaleX= 1
DXF ScaleY= 10

--- UNT020 IN SNOGR.p01 (plan) ---

Plan Title=Multiple Run
Short Identifier=Multiple
Geom File=g01
Flow File=f01
Subcritical Flow
K Sum by GR= 0
Std Step Tol= 0.01
Critical Tol= 0.01
Num of Std Step Trials= 20
Max Error Tol= 0.3
Flow Tol Ratio= 0.001
Split Flow NTrial= 30
Split Flow Tol= 0.02
Split Flow Ratio= 0.02
Log Output Level= 0
Friction Slope Method= 1
Unsteady Friction Slope Method= 2
Unsteady Bridges Friction Slope Method= 1
Parabolic Critical Depth
Global Vel Dist=  1 , 1 , 1
Global Log Level= 0
CheckData=True
Encroach Param= -1, 0, 0, 0
BEGIN DESCRIPTION:
Multiple Run
END DESCRIPTION:

--- UNT020 IN SNOGR.f01 (steady flow) ---

Flow Title=Multiple
Number of Profiles=7
Profile Names=10-year,25-year,50-year,1pct_min,100-year,1pct_plu,500-year
River Rch & RM= UNT020 IN SNOGR,Reach-1,10256
     861    1249    1586    1476    1996    2700    3172
River Rch & RM= UNT020 IN SNOGR,Reach-1,9334
    1350    2005    2587    2441    3301    4465    5399
River Rch & RM= UNT020 IN SNOGR,Reach-1,7548
    1761    2644    3436    3262    4412    5966    7303
Boundary for River Rch & Prof#=UNT020 IN SNOGR,Reach-1,1
Up Type=0
Dn Type=3
Dn Slope=0.005
Boundary for River Rch & Prof#=UNT020 IN SNOGR,Reach-1,2
Up Type=0
Dn Type=3
Dn Slope=0.005
Boundary for River Rch & Prof#=UNT020 IN SNOGR,Reach-1,3
Up Type=0
Dn Type=3
Dn Slope=0.005
Boundary for River Rch & Prof#=UNT020 IN SNOGR,Reach-1,4
Up Type=0
Dn Type=3
Dn Slope=0.005
Boundary for River Rch & Prof#=UNT020 IN SNOGR,Reach-1,5
Up Type=0
Dn Type=3
Dn Slope=0.005
Boundary for River Rch & Prof#=UNT020 IN SNOGR,Reach-1,6
Up Type=0
Dn Type=3
Dn Slope=0.005
Boundary for River Rch & Prof#=UNT020 IN SNOGR,Reach-1,7
Up Type=0
Dn Type=3
Dn Slope=0.005

--- UNT020 IN SNOGR.g01 (geometry) ---

Geom Title=Existing Conditions
Program Version=4.10

River Reach=UNT020 IN SNOGR ,Reach-1
Reach XY= 30
      2872678.47     10058323.73       2872681.6     10058442.24
      2872885.15     10058530.45      2872907.95     10058668.47
      2872852.21     10058924.04      2872623.58      10059131.3
      2872461.42     10059378.76      2872627.77     10059754.23
      2872547.32     10060088.26      2872340.92     10060330.93
      2872335.14     10060420.45      2872219.87     10060519.05
      2872176.97     10060826.32      2872089.95      10060980.2
      2871718.78     10061348.86      2871531.45     10061805.16
      2871436.02     10062312.72      2871250.16     10062709.54
      2871318.65     10063038.65      2871578.06     10063328.34
      2871415.55     10064062.47      2871320.19     10064209.54
      2871336.21     10064707.79      2871133.43     10065066.37
      2871018.47     10065173.73      2871080.56     10065747.87
       2871245.1     10066228.31      2871039.49     10066851.55
      2871068.51     10067275.22      2871013.56     10067735.19

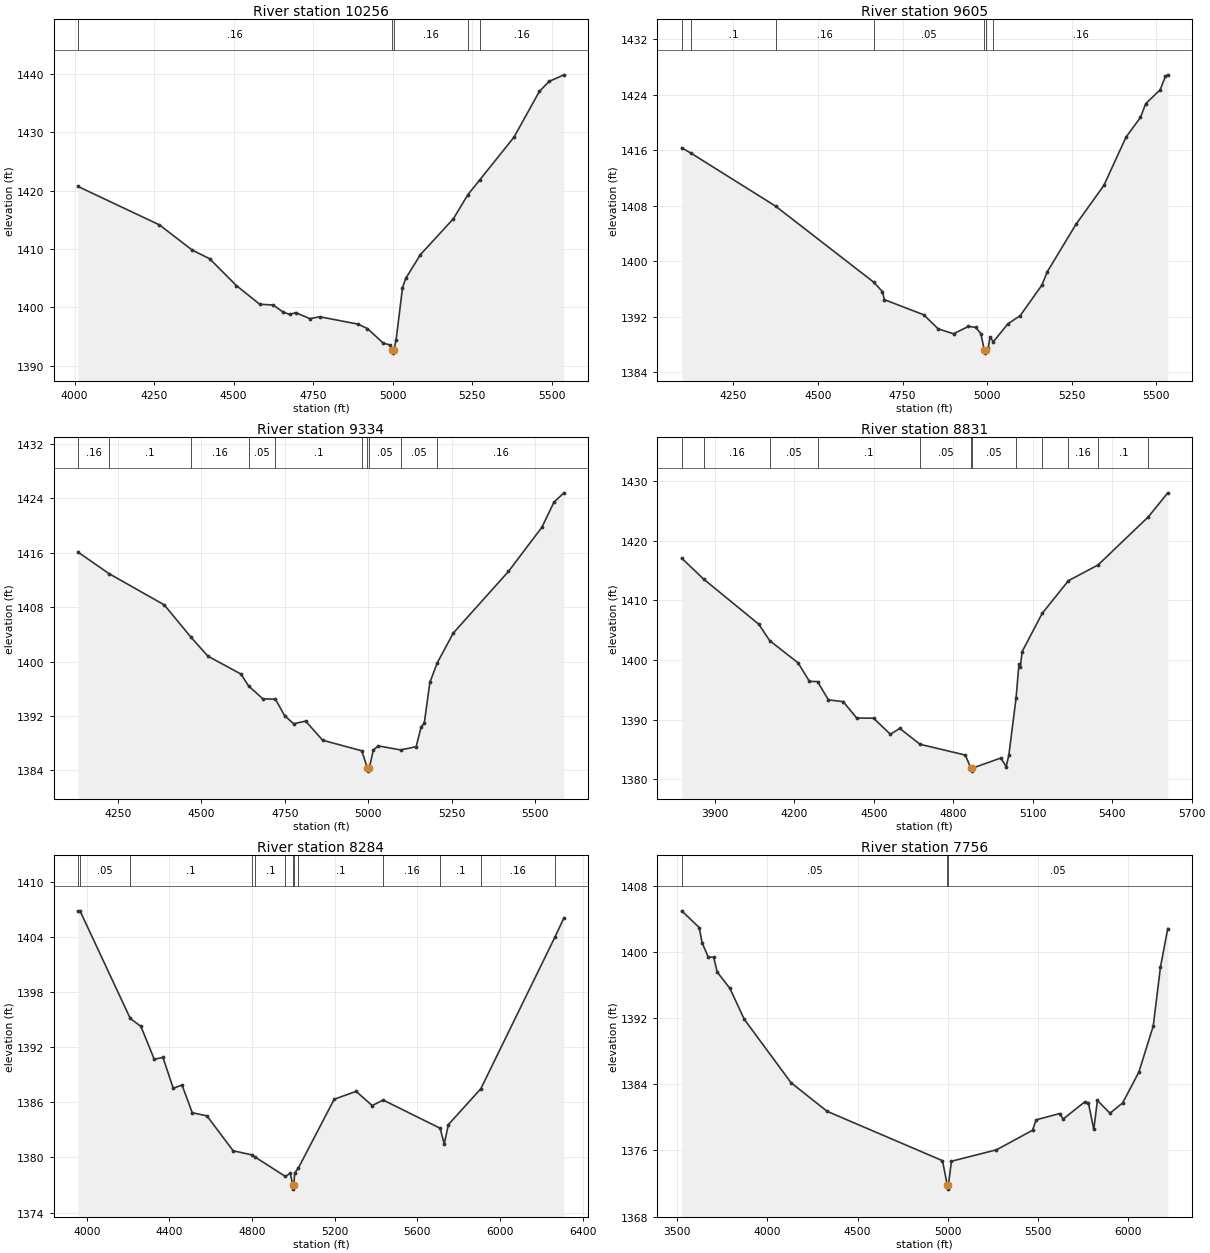
Type RM Length L Ch R = 1 ,10256   ,651,651,651
BEGIN DESCRIPTION:
UNT020 IN SNOGR 23.0
END DESCRIPTION:
XS GIS Cut Line= 3
      2871954.21     10058357.28      2872662.56     10058586.45
      2873445.36     10058544.89
#Sta/Elev= 30
  4010.1 1420.75  4266.8 1414.14  4369.4 1409.83  4424.5 1408.34  4508.6 1403.73
  4582.1 1400.52  4624.2  1400.4  4655.7 1399.18  4676.7 1398.77  4694.8 1399.09
  4739.8 1398.05  4770.5 1398.38  4890.7 1397.12  4920.7 1396.35  4970.8 1393.84
  4990.8 1393.56  4997.9 1392.64  5000.6 1392.14  5003.9 1392.64  5010.9 1394.47
  5030.9 1403.32  5040.9 1404.95  5087.4 1409.05  5191.1 1415.21  5236.5 1419.33
  5274.2 1421.89  5381.4 1429.19  5461.2 1437.03  5491.5 1438.75  5538.5 1439.89
#Mann= 5 ,-1 , 0
  4010.1     .16       0  4997.9     .07       0  5003.9     .16       0
  5236.5      .1       0  5274.2     .16       0
Bank Sta=4997.9,5003.9
XS Rating Curve= 0 ,0
Exp/Cntr=0.3,0.1

Type RM Length L Ch R = 1 ,9605    ,271,271,271
BEGIN DESCRIPTION:
UNT020 IN SNOGR 22.0
END DESCRIPTION:
XS GIS Cut Line= 2
       2871870.9     10058648.96      2873100.06     10059392.01
#Sta/Elev= 30
  4097.3 1416.36  4124.9 1415.58  4374.6 1407.94  4665.8 1396.92  4690.3  1395.6
  4696.2 1394.44  4812.6 1392.25  4855.3 1390.22  4900.7 1389.51  4944.5 1390.58
  4965.9 1390.44  4981.4 1389.53  4991.2 1387.22    4994 1386.72  4997.2 1387.22
  5002.7 1387.42  5008.6 1389.05    5018 1388.36  5060.9 1390.93  5097.8 1392.15
  5161.8 1396.55  5177.3 1398.45    5263 1405.36  5344.8 1410.93  5410.2  1417.9
  5452.9 1420.74  5468.4 1422.73  5511.1 1424.73  5526.6 1426.66  5533.6 1426.89
#Mann= 7 ,-1 , 0
  4097.3     .16       0  4124.9      .1       0  4374.6     .16       0
  4665.8     .05       0  4991.2    .035       0  4997.2     .05       0
    5018     .16       0
Bank Sta=4991.2,4997.2
XS Rating Curve= 0 ,0
Exp/Cntr=0.3,0.1

Type RM Length L Ch R = 1 ,9334    ,503,503,503
BEGIN DESCRIPTION:
UNT020 IN SNOGR 21.0
END DESCRIPTION:
XS GIS Cut Line= 3
      2871787.52     10058843.37      2872641.72     10059433.67
      2873058.42     10059475.34
#Sta/Elev= 30
  4129.9 1416.13  4223.2 1412.95    4389 1408.35  4469.2 1403.58    4520  1400.8
  4618.8 1398.18  4641.7 1396.43  4684.4 1394.54  4722.3 1394.48  4749.9 1392.04
    4777 1390.87  4812.8 1391.26  4863.5 1388.45  4980.9 1386.89  4997.7  1384.4
  5000.5  1383.9  5003.7  1384.4  5015.6 1387.01  5030.4 1387.61  5097.4 1387.02
    5144 1387.49  5158.9  1390.4  5168.2 1390.91  5185.1 1396.94  5206.9 1399.79
  5255.4 1404.21  5420.6 1413.26  5521.1 1419.78  5556.9 1423.44    5587 1424.83
#Mann= 10 ,-1 , 0
  4129.9     .16       0  4223.2      .1       0  4469.2     .16       0
  4641.7     .05       0  4722.3      .1       0  4980.9     .05       0
  4997.7    .035       0  5003.7     .05       0  5097.4     .05       0
  5206.9     .16       0
Bank Sta=4997.7,5003.7
XS Rating Curve= 0 ,0
Exp/Cntr=0.3,0.1

Type RM Length L Ch R = 1 ,8831    ,547,547,547
BEGIN DESCRIPTION:
UNT020 IN SNOGR 20.0
END DESCRIPTION:
XS GIS Cut Line= 4
       2871641.7     10059100.32       2872419.5     10059753.12
      2872912.56     10059801.73      2873173.97     10059609.11
#Sta/Elev= 30
  3774.2 1417.05  3857.7 1413.52  4065.5 1405.98  4106.4 1403.24  4213.9  1399.5
  4256.7 1396.41  4287.1 1396.37  4328.3 1393.31  4384.2 1393.01  4434.9 1390.27
  4498.7 1390.24  4562.4 1387.54  4597.6 1388.53  4674.1 1385.87  4845.4 1384.06
    4866 1381.87  4868.7 1381.37    4872 1381.87  4979.5 1383.57  4999.6 1382.11
  5009.7 1384.08  5036.9 1393.61  5047.8 1399.29  5052.8 1398.78  5059.9 1401.41
  5135.7 1407.81  5234.4 1413.27  5346.7 1415.92  5536.7 1423.99  5609.8    1428
#Mann= 12 ,-1 , 0
  3774.2      .1       0  3857.7     .16       0  4106.4     .05       0
  4287.1      .1       0  4674.1     .05       0    4866    .035       0
    4872     .05       0  5036.9     .16       0  5135.7      .1       0
  5234.4     .16       0  5346.7      .1       0  5536.7     .16       0
Bank Sta=4866,4872
XS Rating Curve= 0 ,0
Exp/Cntr=0.3,0.1

Type RM Length L Ch R = 1 ,8284    ,528,528,528
BEGIN DESCRIPTION:
UNT020 IN SNOGR 19.0
END DESCRIPTION:
XS GIS Cut Line= 3
      2871641.74     10059558.69      2872711.17     10060517.01
      2873627.85     10060523.95
#Sta/Elev= 30
  3957.1 1406.89    3969 1406.82  4210.5 1395.17  4262.6 1394.28  4326.9 1390.71
    4369 1390.91  4418.8 1387.54  4461.4  1387.9  4510.8 1384.88  4581.8 1384.54
  4708.9 1380.73  4798.3 1380.29  4816.9 1380.02  4961.9 1377.93  4985.5 1378.29
  4996.7 1377.05  4999.5 1376.55  5002.7 1377.05  5006.4  1378.3  5024.9 1378.87
  5197.8 1386.35    5304 1387.21  5381.7 1385.66    5435 1386.26  5710.4 1383.19
  5730.4 1381.47  5750.4 1383.58  5907.7  1387.5  6267.1 1404.07  6309.8 1406.12
#Mann= 13 ,-1 , 0
  3957.1     .16       0    3969     .05       0  4210.5      .1       0
  4798.3     .05       0  4816.9      .1       0  4961.9     .05       0
  4996.7    .035       0  5002.7     .05       0  5024.9      .1       0
    5435     .16       0  5710.4      .1       0  5907.7     .16       0
  6267.1      .1       0
Bank Sta=4996.7,5002.7
XS Rating Curve= 0 ,0
Exp/Cntr=0.3,0.1

Type RM Length L Ch R = 1 ,7756    ,208,208,208
BEGIN DESCRIPTION:
Mapping XS 6251a4ec
END DESCRIPTION:
XS GIS Cut Line= 2
      2870711.21     10060667.18      2873409.16     10060703.64
#Sta/Elev= 30
    3524 1404.95  3621.3 1402.93  3637.5 1401.08  3671.3 1399.38  3701.3 1399.35
  3721.3 1397.55  3791.3 1395.59  3871.3 1391.85  4131.3 1384.18  4331.3 1380.73
  4971.4 1374.77  4998.4 1371.83  5001.1 1371.33  5004.4 1371.83  5021.4  1374.7
  5271.4 1376.08  5471.4 1378.44  5491.4  1379.7  5621.4 1380.46  5641.5 1379.79
  5761.5 1381.88  5781.5 1381.76  5811.5 1378.54  5831.5 1382.04  5901.5  1380.5
  5971.5 1381.74  6061.5 1385.46  6141.5 1391.03  6181.5 1398.15  6222.2 1402.81
#Mann= 3 ,-1 , 0
    3524     .05       0  4998.4     .04       0  5004.4     .05       0
Bank Sta=4998.4,5004.4
XS Rating Curve= 0 ,0
Exp/Cntr=0.3,0.1

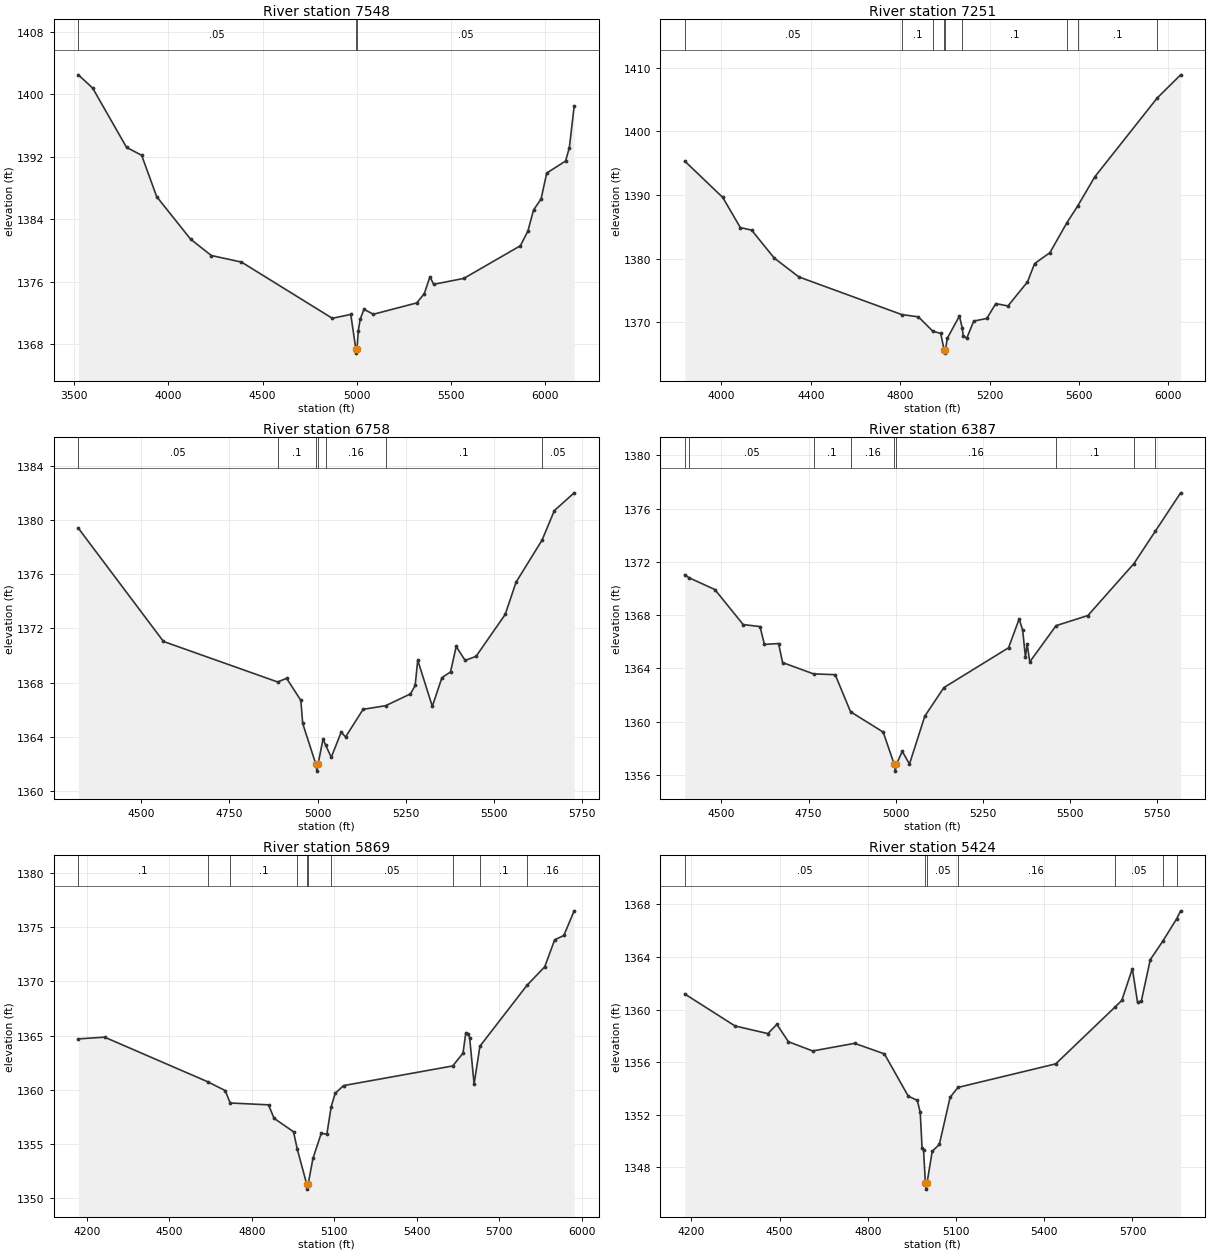
Type RM Length L Ch R = 1 ,7548    ,297,297,297
BEGIN DESCRIPTION:
UNT020 IN SNOGR 18.0
END DESCRIPTION:
XS GIS Cut Line= 2
      2870662.57     10060850.34      2873293.99     10060905.89
#Sta/Elev= 30
  3521.9  1402.5  3597.8 1400.81  3777.9 1393.21  3857.9  1392.2  3937.9  1386.9
  4117.9 1381.45    4228 1379.36    4388 1378.52  4870.2 1371.32  4968.1 1371.82
  4995.1 1367.36  4997.9 1366.86  5001.1 1367.36  5008.1 1369.72  5018.1  1371.2
  5038.1 1372.47  5088.1 1371.84  5318.2 1373.29  5358.2 1374.47  5388.2 1376.63
  5408.2 1375.67  5568.2 1376.43  5868.3 1380.61  5908.3 1382.49  5938.3 1385.19
  5978.3  1386.6  6008.3 1389.92  6108.4 1391.46  6128.4 1393.18  6153.9 1398.48
#Mann= 3 ,-1 , 0
  3521.9     .05       0  4995.1     .04       0  5001.1     .05       0
Bank Sta=4995.1,5001.1
XS Rating Curve= 0 ,0
Exp/Cntr=0.3,0.1

Type RM Length L Ch R = 1 ,7251    ,493,493,493
BEGIN DESCRIPTION:
UNT020 IN SNOGR 17.0
END DESCRIPTION:
XS GIS Cut Line= 3
      2870822.29     10060926.73      2871870.89     10061065.62
      2872940.37     10061517.02
#Sta/Elev= 30
  3835.9 1395.32    4006 1389.61  4084.4 1384.88  4134.7 1384.49  4236.3 1380.09
  4346.5 1377.13  4806.5 1371.22  4881.1 1370.86  4945.6 1368.61  4981.1 1368.25
  4996.3 1365.66  4999.1 1365.16  5002.3 1365.66  5010.4 1367.49  5064.7 1370.98
  5077.7 1369.06  5081.3  1367.9  5097.3 1367.48  5128.8  1370.2    5187  1370.6
  5227.5 1372.94  5281.8 1372.57  5369.3 1376.35  5401.2 1379.23  5469.6 1380.94
    5546 1385.67  5593.7 1388.26  5670.1 1392.84  5949.4 1405.23  6054.5 1408.88
#Mann= 9 ,-1 , 0
  3835.9     .05       0  4806.5      .1       0  4945.6     .16       0
  4996.3     .07       0  5002.3     .16       0  5077.7      .1       0
    5546     .05       0  5593.7      .1       0  5949.4     .16       0
Bank Sta=4996.3,5002.3
XS Rating Curve= 0 ,0
Exp/Cntr=0.3,0.1

Type RM Length L Ch R = 1 ,6758    ,371,371,371
BEGIN DESCRIPTION:
UNT020 IN SNOGR 15.0
END DESCRIPTION:
XS GIS Cut Line= 2
      2871016.76     10061308.68      2872377.84     10061662.84
#Sta/Elev= 30
  4321.6 1379.39  4563.1 1371.03    4887 1368.04  4912.3 1368.31  4952.8 1366.68
    4958 1364.98  4995.5 1361.96  4998.3 1361.46  5001.5 1361.96  5015.7 1363.83
  5023.3 1363.37    5039 1362.48  5067.3 1364.34  5079.6 1363.98  5129.3 1366.02
  5193.3 1366.29  5263.7 1367.16    5277 1367.78  5284.3 1369.65  5325.7 1366.24
  5352.9 1368.36  5377.3 1368.78  5393.4 1370.66  5418.7 1369.63  5449.7 1369.93
  5532.3 1373.02  5563.3 1375.41  5636.9 1378.51  5671.9 1380.69    5728    1382
#Mann= 7 ,-1 , 0
  4321.6     .05       0    4887      .1       0  4995.5     .07       0
  5001.5      .1       0  5023.3     .16       0  5193.3      .1       0
  5636.9     .05       0
Bank Sta=4995.5,5001.5
XS Rating Curve= 0 ,0
Exp/Cntr=0.3,0.1

Type RM Length L Ch R = 1 ,6387    ,518,518,518
BEGIN DESCRIPTION:
UNT020 IN SNOGR 14.0
END DESCRIPTION:
XS GIS Cut Line= 2
      2870933.44     10061711.46      2872334.86     10061954.28
#Sta/Elev= 30
    4395 1371.02  4407.7  1370.8  4481.3 1369.92  4562.5 1367.29  4610.7 1367.14
  4623.4  1365.8    4664 1365.87  4675.5 1364.44  4764.2 1363.59  4826.4 1363.53
  4870.4 1360.75  4964.1 1359.22  4995.9 1356.79  4998.6 1356.29  5001.9 1356.79
  5018.7 1357.78  5039.5 1356.82  5083.5 1360.42  5138.2 1362.56  5323.7 1365.55
  5354.1 1367.71  5364.3 1366.86  5372.1 1364.85  5377.1 1365.82  5384.6 1364.49
    5460 1367.21  5551.3 1367.97  5683.4 1371.87  5744.2 1374.28  5817.3 1377.18
#Mann= 9 ,-1 , 0
    4395      .1       0  4407.7     .05       0  4764.2      .1       0
  4870.4     .16       0  4995.9     .07       0  5001.9     .16       0
    5460      .1       0  5683.4     .16       0  5744.2      .1       0
Bank Sta=4995.9,5001.9
XS Rating Curve= 0 ,0
Exp/Cntr=0.3,0.1

Type RM Length L Ch R = 1 ,5869    ,445,445,445
BEGIN DESCRIPTION:
UNT020 IN SNOGR 13.0
END DESCRIPTION:
XS GIS Cut Line= 2
      2870613.93     10062190.62      2872398.62      10062454.5
#Sta/Elev= 30
  4168.8 1364.69  4264.4 1364.85    4639 1360.75  4703.5 1359.93  4721.2 1358.79
  4860.8 1358.62    4881 1357.38  4951.8 1356.14  4965.3 1354.56  4999.3 1351.36
  5002.1 1350.86  5005.3 1351.36  5022.5 1353.69  5052.8 1356.01  5073.1 1355.91
  5088.8 1358.45  5103.4 1359.68  5133.7 1360.39    5531  1362.2  5568.4 1363.37
  5578.5 1365.22  5587.6 1365.11  5592.6  1364.8  5608.8 1360.54  5630.1 1364.02
  5801.5 1369.63  5865.8 1371.33    5902 1373.81  5935.4 1374.21  5972.9 1376.48
#Mann= 10 ,-1 , 0
  4168.8      .1       0    4639     .05       0  4721.2      .1       0
  4965.3     .16       0  4999.3     .07       0  5005.3     .16       0
  5088.8     .05       0    5531     .16       0  5630.1      .1       0
  5801.5     .16       0
Bank Sta=4999.3,5005.3
XS Rating Curve= 0 ,0
Exp/Cntr=0.3,0.1

Type RM Length L Ch R = 1 ,5424    ,425,425,425
BEGIN DESCRIPTION:
UNT020 IN SNOGR 12.0
END DESCRIPTION:
XS GIS Cut Line= 2
      2870440.31     10062565.61      2872100.06     10062864.23
#Sta/Elev= 30
  4177.4 1361.18  4348.3 1358.75    4460 1358.17  4490.5 1358.87    4530 1357.55
  4612.4 1356.85  4754.7 1357.43  4856.3 1356.63  4937.6 1353.41  4968.1  1353.1
  4978.2 1352.18  4984.5 1349.44  4989.5 1349.29  4995.5 1346.85  4998.3 1346.35
  5001.5 1346.85  5018.9 1349.22  5043.2 1349.75  5079.8 1353.33  5106.6 1354.08
    5439 1355.87  5639.4 1360.16  5663.7 1360.69  5699.6  1363.1  5717.3 1360.55
  5730.1 1360.64  5760.6 1363.79    5803 1365.19  5850.7 1366.91  5863.8  1367.5
#Mann= 7 ,-1 , 0
  4177.4     .05       0  4995.5     .04       0  5001.5     .05       0
  5106.6     .16       0  5639.4     .05       0    5803      .1       0
  5850.7     .05       0
Bank Sta=4995.5,5001.5
XS Rating Curve= 0 ,0
Exp/Cntr=0.3,0.1

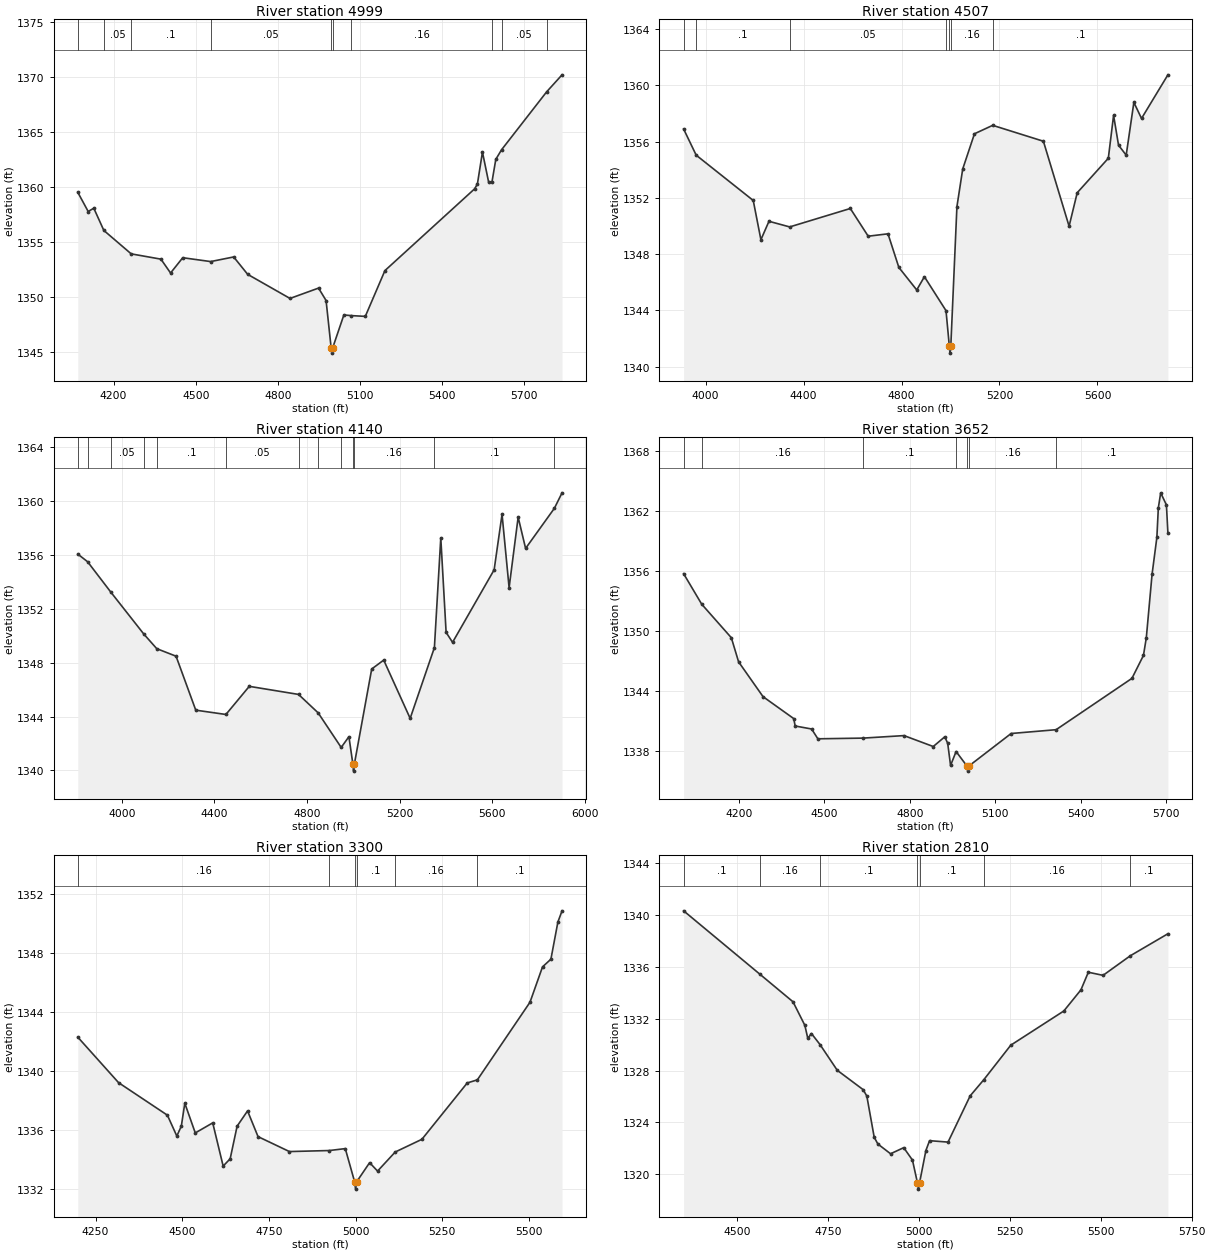
Type RM Length L Ch R = 1 ,4999    ,492,492,492
BEGIN DESCRIPTION:
UNT020 IN SNOGR 11.0
END DESCRIPTION:
XS GIS Cut Line= 3
      2870461.18      10062968.4      2871245.89     10063135.06
      2872190.37     10062926.72
#Sta/Elev= 30
    4069  1359.5  4107.1 1357.75  4127.6 1358.05  4164.3 1356.03  4264.3  1353.9
  4372.9 1353.42  4408.1 1352.16  4452.6 1353.55  4554.6  1353.2  4638.7 1353.62
  4689.8 1352.04  4844.5 1349.85  4948.8 1350.79  4976.3 1349.66  4994.7 1345.38
  4997.4 1344.88  5000.7 1345.38  5041.3 1348.35  5067.9 1348.29  5119.6 1348.22
  5191.3 1352.38    5519 1359.81  5529.2 1360.25  5547.6 1363.15  5570.2 1360.42
  5582.5 1360.45  5596.4 1362.49  5617.4 1363.36    5782 1368.62  5838.4 1370.17
#Mann= 10 ,-1 , 0
    4069     .16       0  4164.3     .05       0  4264.3      .1       0
  4554.6     .05       0  4994.7     .04       0  5000.7     .05       0
  5067.9     .16       0  5582.5      .1       0  5617.4     .05       0
    5782      .1       0
Bank Sta=4994.7,5000.7
XS Rating Curve= 0 ,0
Exp/Cntr=0.3,0.1

Type RM Length L Ch R = 1 ,4507    ,367,367,367
BEGIN DESCRIPTION:
UNT020 IN SNOGR 10.0
END DESCRIPTION:
XS GIS Cut Line= 2
      2870495.88     10063190.62      2872391.69     10063753.11
#Sta/Elev= 30
  3910.2  1356.9  3961.5 1355.04  4194.5 1351.82  4225.8 1349.03  4258.7 1350.34
  4343.3 1349.94  4590.9 1351.25  4663.9 1349.28  4744.7 1349.45  4789.1 1347.06
  4862.1 1345.46  4893.4  1346.4  4981.6 1343.99  4995.2 1341.47  4997.9 1340.97
  5001.2 1341.47  5026.2 1351.38  5049.9 1354.06  5097.8 1356.56  5172.3 1357.16
  5379.3 1356.03  5484.2 1349.99  5517.4 1352.37  5644.4 1354.82  5665.9 1357.87
  5686.1 1355.75  5717.4 1355.04  5748.7 1358.79    5780 1357.65  5887.7 1360.75
#Mann= 7 ,-1 , 0
  3910.2     .05       0  3961.5      .1       0  4343.3     .05       0
  4981.6     .16       0  4995.2     .07       0  5001.2     .16       0
  5172.3      .1       0
Bank Sta=4995.2,5001.2
XS Rating Curve= 0 ,0
Exp/Cntr=0.3,0.1

Type RM Length L Ch R = 1 ,4140    ,488,488,488
BEGIN DESCRIPTION:
UNT020 IN SNOGR 9.0
END DESCRIPTION:
XS GIS Cut Line= 2
      2870287.56     10063628.12      2872343.09     10064023.95
#Sta/Elev= 30
  3809.2 1356.08  3851.7 1355.51  3951.3 1353.27    4095 1350.13  4150.7 1349.05
  4234.1 1348.49  4319.3 1344.48  4449.6 1344.16  4550.6 1346.25  4763.5 1345.65
  4848.3 1344.28  4947.9 1341.71  4981.3 1342.51  4998.6 1340.45  5001.4 1339.95
  5004.6 1340.45  5079.8 1347.54  5131.7  1348.2    5246 1343.87  5350.8 1349.13
  5378.4 1357.28  5401.4 1350.26  5429.3 1349.52    5609 1354.91  5643.2 1359.03
  5673.7 1353.58  5712.8 1358.82    5745  1356.5  5869.4 1359.48  5902.5 1360.63
#Mann= 13 ,-1 , 0
  3809.2     .05       0  3851.7      .1       0  3951.3     .05       0
    4095     .16       0  4150.7      .1       0  4449.6     .05       0
  4763.5      .1       0  4848.3     .05       0  4947.9     .16       0
  4998.6     .07       0  5004.6     .16       0  5350.8      .1       0
  5869.4     .05       0
Bank Sta=4998.6,5004.6
XS Rating Curve= 0 ,0
Exp/Cntr=0.3,0.1

Type RM Length L Ch R = 1 ,3652    ,352,352,352
BEGIN DESCRIPTION:
UNT020 IN SNOGR 8.0
END DESCRIPTION:
XS GIS Cut Line= 3
      2870343.09     10064148.95       2871544.5     10064336.45
      2872023.59     10064273.96
#Sta/Elev= 30
  4006.4 1355.76  4069.9 1352.71  4173.8 1349.36  4199.3 1346.95  4285.1 1343.47
  4392.7 1341.28  4397.8 1340.54  4455.5 1340.24  4477.4 1339.26  4636.3 1339.33
  4779.6 1339.58  4882.2 1338.49  4922.7 1339.46  4932.9 1338.81    4943  1336.6
  4962.4 1337.99  5000.7 1336.53  5003.5 1336.03  5006.7 1336.53  5155.5 1339.79
  5313.3 1340.17  5579.3  1345.3  5619.7 1347.59  5629.7 1349.34  5649.9 1355.69
  5666.8 1359.39  5671.9 1362.33  5680.2 1363.84  5700.3 1362.63  5705.5 1359.81
#Mann= 7 ,-1 , 0
  4006.4      .1       0  4069.9     .16       0  4636.3      .1       0
  4962.4     .16       0  5000.7     .07       0  5006.7     .16       0
  5313.3      .1       0
Bank Sta=5000.7,5006.7
XS Rating Curve= 0 ,0
Exp/Cntr=0.3,0.1

Type RM Length L Ch R = 1 ,3300    ,490,490,490
BEGIN DESCRIPTION:
UNT020 IN SNOGR 7.0
END DESCRIPTION:
XS GIS Cut Line= 2
      2870551.42     10064558.67      2871940.38     10064704.51
#Sta/Elev= 30
  4198.8 1342.29  4316.5 1339.21  4457.3 1337.01  4484.5  1335.6  4497.5 1336.27
  4507.5 1337.82  4537.7 1335.81    4588 1336.49  4618.1 1333.57  4638.3 1334.06
  4658.4 1336.27  4688.5  1337.3  4718.7 1335.56  4809.2 1334.55  4924.5 1334.62
  4970.3 1334.75  4997.2 1332.51    5000 1332.01  5003.2 1332.51  5040.5  1333.8
  5063.4 1333.23  5114.3 1334.52  5191.3 1335.38    5322 1339.19  5351.2  1339.4
    5503 1344.65  5539.1 1347.04  5563.3 1347.56  5583.4 1350.07  5595.4 1350.83
#Mann= 6 ,-1 , 0
  4198.8     .16       0  4924.5      .1       0  4997.2     .07       0
  5003.2      .1       0  5114.3     .16       0  5351.2      .1       0
Bank Sta=4997.2,5003.2
XS Rating Curve= 0 ,0
Exp/Cntr=0.3,0.1

Type RM Length L Ch R = 1 ,2810    ,396,396,396
BEGIN DESCRIPTION:
UNT020 IN SNOGR 6.0
END DESCRIPTION:
XS GIS Cut Line= 2
      2870492.16     10064963.18      2871804.09     10065187.05
#Sta/Elev= 30
  4353.8 1340.33  4563.3 1335.44  4654.4 1333.31    4687 1331.49    4695 1330.49
  4705.1 1330.86  4728.6 1330.01  4776.1 1328.02  4847.1 1326.53  4857.3 1326.03
  4877.6 1322.85  4887.7 1322.33  4922.5 1321.58  4958.7 1322.05  4982.7 1321.09
  4996.3 1319.35  4999.1 1318.85  5002.3 1319.35  5019.6 1321.83  5029.7 1322.59
  5080.5 1322.48  5141.3 1326.05  5178.9  1327.3  5252.9 1329.96  5398.7  1332.6
  5445.7 1334.23    5466 1335.59  5506.5 1335.35  5581.3 1336.86  5684.7 1338.56
#Mann= 7 ,-1 , 0
  4353.8      .1       0  4563.3     .16       0  4728.6      .1       0
  4996.3     .07       0  5002.3      .1       0  5178.9     .16       0
  5581.3      .1       0
Bank Sta=4996.3,5002.3
XS Rating Curve= 0 ,0
Exp/Cntr=0.3,0.1

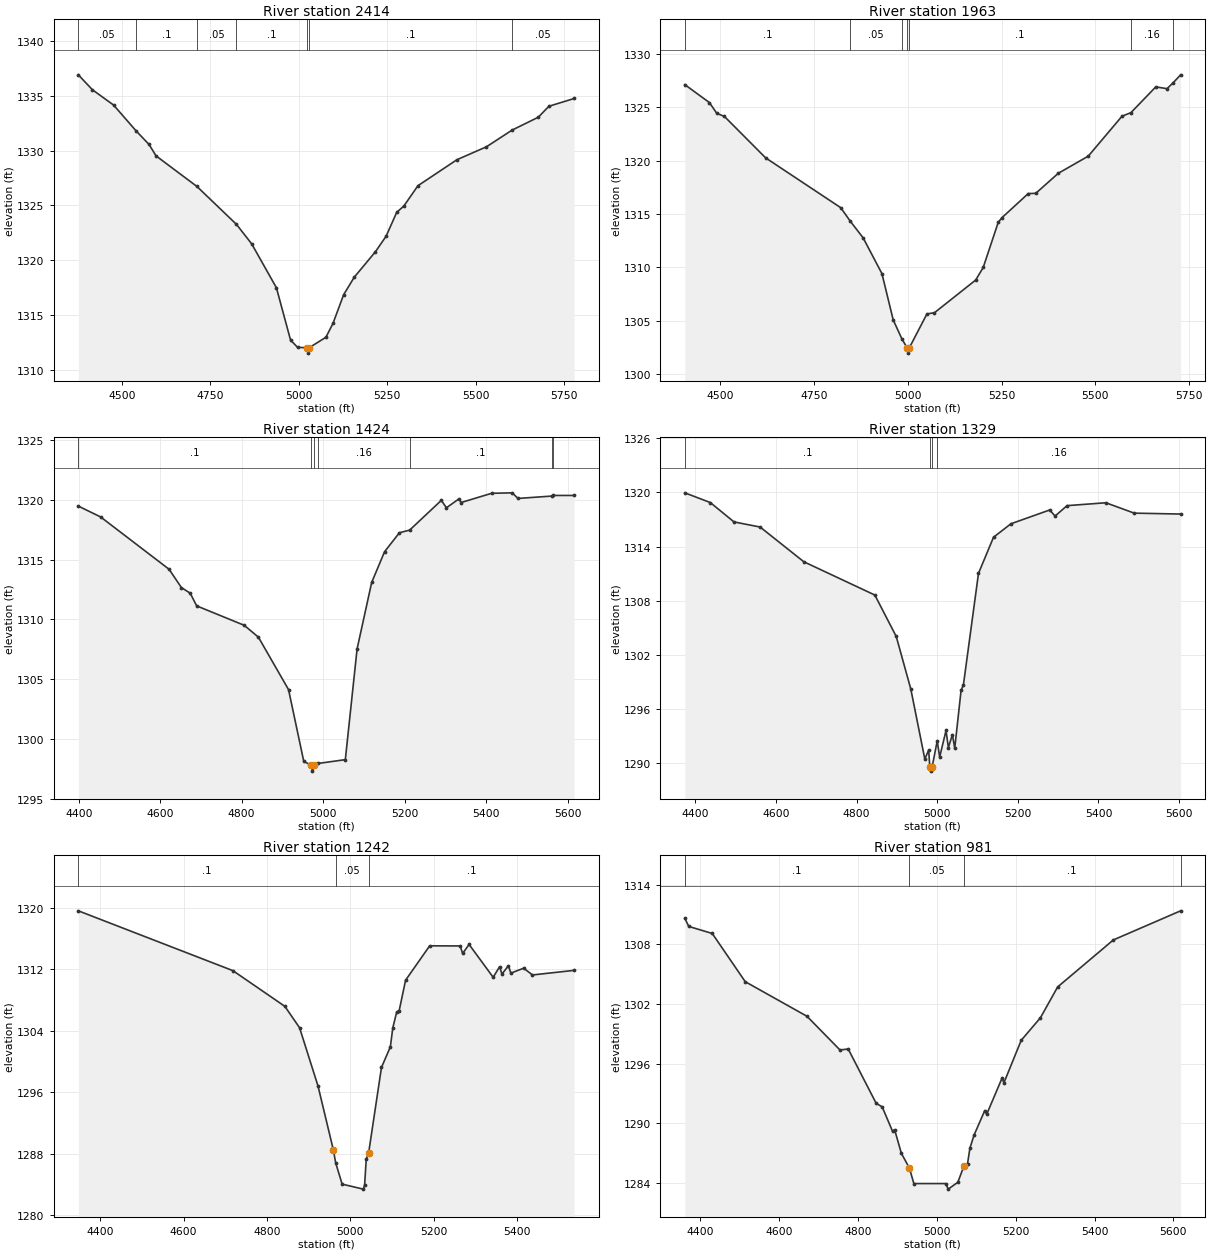
Type RM Length L Ch R = 1 ,2414    ,451,451,451
BEGIN DESCRIPTION:
UNT020 IN SNOGR 5.0
END DESCRIPTION:
XS GIS Cut Line= 2
      2870408.81     10065405.89      2871809.82     10065421.51
#Sta/Elev= 30
  4377.1 1336.91  4416.8 1335.55  4476.8 1334.15  4540.4 1331.79  4576.8 1330.56
  4596.8 1329.51  4712.3 1326.72    4824 1323.26  4866.8 1321.49  4936.8 1317.48
  4976.8  1312.7  4996.8 1312.03  5023.8 1312.01  5026.5 1311.51  5029.8 1312.01
  5076.8 1312.96  5096.8 1314.23  5126.8 1316.84  5156.8 1318.44  5216.8 1320.77
  5246.8 1322.18  5276.8 1324.36  5296.8 1324.93  5336.8 1326.79  5446.8 1329.16
  5530.3 1330.34  5602.5 1331.86  5676.8 1333.04  5706.8 1334.04  5778.2 1334.75
#Mann= 7 ,-1 , 0
  4377.1     .05       0  4540.4      .1       0  4712.3     .05       0
    4824      .1       0  5023.8     .07       0  5029.8      .1       0
  5602.5     .05       0
Bank Sta=5023.8,5029.8
XS Rating Curve= 0 ,0
Exp/Cntr=0.3,0.1

Type RM Length L Ch R = 1 ,1963    ,539,539,539
BEGIN DESCRIPTION:
UNT020 IN SNOGR 4.0
END DESCRIPTION:
XS GIS Cut Line= 2
      2870512.97     10065843.39      2871834.66     10065848.59
#Sta/Elev= 30
  4405.7 1327.14  4471.2 1325.46  4491.2 1324.44  4511.2 1324.16  4621.2 1320.27
  4821.2  1315.6  4847.2 1314.31  4881.2 1312.76  4931.2 1309.41  4961.2 1305.07
  4984.1 1303.31  4998.2 1302.45  5000.9 1301.95  5004.2 1302.45  5051.2 1305.63
  5071.2 1305.74  5181.2 1308.81  5201.2 1309.99  5241.2 1314.22  5251.2 1314.66
  5321.2 1316.92  5341.2 1316.94  5401.2 1318.82  5481.2 1320.43  5571.2 1324.18
  5594.9 1324.51  5661.2 1326.93  5691.2 1326.76  5707.6 1327.32  5727.4 1328.06
#Mann= 7 ,-1 , 0
  4405.7      .1       0  4847.2     .05       0  4984.1      .1       0
  4998.2     .07       0  5004.2      .1       0  5594.9     .16       0
  5707.6     .05       0
Bank Sta=4998.2,5004.2
XS Rating Curve= 0 ,0
Exp/Cntr=0.3,0.1

Type RM Length L Ch R = 1 ,1424    ,95,95,95
BEGIN DESCRIPTION:
UNT020 IN SNOGR 3.0
END DESCRIPTION:
XS GIS Cut Line= 2
       2870695.3     10066051.74      2871750.28     10066659.05
#Sta/Elev= 30
    4399 1319.48  4453.8 1318.57  4621.9 1314.19  4652.1 1312.66  4673.7 1312.19
  4689.5 1311.13  4806.5  1309.5  4841.1 1308.51  4915.1 1304.12  4952.5 1298.11
    4971  1297.8  4973.8  1297.3    4977  1297.8  4987.3 1297.94  5054.5 1298.26
  5083.4 1307.53  5119.2 1313.09  5150.8 1315.66  5187.3 1317.25  5212.4 1317.47
  5290.2 1319.96  5302.7 1319.34  5333.3 1320.08    5339 1319.78  5413.7 1320.55
  5464.2 1320.59  5478.4 1320.12  5561.8 1320.32    5564 1320.37  5616.3 1320.37
#Mann= 7 ,-1 , 0
    4399      .1       0    4971     .07       0    4977      .1       0
  4987.3     .16       0  5212.4      .1       0  5561.8     .16       0
    5564      .1       0
Bank Sta=4971,4977
XS Rating Curve= 0 ,0
Exp/Cntr=0.3,0.1

Type RM Length L Ch R = 1 ,1329    ,87,87,87
BEGIN DESCRIPTION:
Mapping XS 67caff4b
END DESCRIPTION:
XS GIS Cut Line= 2
      2870632.78     10066124.65      2871698.27     10066738.95
#Sta/Elev= 30
  4373.9 1319.95  4437.3 1318.87  4495.9 1316.73  4560.8 1316.16    4669 1312.32
  4845.3 1308.63  4898.4 1304.04  4934.5 1298.22  4969.2 1290.48  4978.8 1291.45
  4981.6 1289.63  4984.3 1289.13  4987.6 1289.63    5000 1292.47  5006.1 1290.69
  5021.9 1293.63  5027.7 1291.74  5037.7 1293.17  5043.5 1291.67  5059.3  1298.1
    5065 1298.67  5102.4 1311.03  5139.7 1315.03  5182.8 1316.52    5279 1318.05
  5292.4 1317.38  5322.1 1318.53  5418.4 1318.85  5488.8  1317.7  5603.8  1317.6
#Mann= 4 ,-1 , 0
  4373.9      .1       0  4981.6     .07       0  4987.6      .1       0
    5000     .16       0
Bank Sta=4981.6,4987.6
XS Rating Curve= 0 ,0
Exp/Cntr=0.3,0.1

Type RM Length L Ch R = 1 ,1242    ,261,261,261
BEGIN DESCRIPTION:
Mapping XS 0cfed62a
END DESCRIPTION:
XS GIS Cut Line= 2
      2870587.64     10066173.26      2871598.04     10066801.72
#Sta/Elev= 30
  4347.5 1319.64  4718.5 1311.84  4843.1 1307.19  4878.4  1304.4  4922.7  1296.8
  4959.3 1288.52  4965.2 1286.76  4980.6 1284.01  5031.3 1283.36  5034.5 1283.86
  5038.4 1287.23  5044.3 1288.12    5075 1299.22  5096.3 1301.91  5102.2 1304.39
  5111.6 1306.46  5117.5 1306.64  5132.9  1310.6  5190.7 1315.08  5263.9 1315.06
  5269.8 1314.08  5285.2 1315.26    5343 1310.98  5358.4 1312.35  5364.2  1311.4
  5379.6 1312.48  5385.5 1311.52  5416.2 1312.16  5437.4 1311.28  5537.4 1311.88
#Mann= 3 ,-1 , 0
  4347.5      .1       0  4965.2     .05       0  5044.3      .1       0
Bank Sta=4959.3,5044.3
XS Rating Curve= 0 ,0
Exp/Cntr=0.3,0.1

Type RM Length L Ch R = 1 ,981     ,91,91,91
BEGIN DESCRIPTION:
UNT020 IN SNOGR 2.0
END DESCRIPTION:
XS GIS Cut Line= 3
      2870441.76     10066586.43      2870920.96     10066732.28
      2871660.56     10066895.48
#Sta/Elev= 30
  4360.2 1310.61  4370.3  1309.8  4429.9 1309.09  4513.6 1304.24  4670.3 1300.76
    4754 1297.37  4774.9 1297.47  4845.9    1292  4861.1 1291.65  4887.6 1289.17
  4892.7 1289.35  4909.8 1286.97  4930.2 1285.49  4941.5 1283.93  5022.4 1283.93
  5028.7 1283.37  5053.1 1284.06 5068.18 1285.65  5077.7 1285.92  5083.8 1287.49
  5094.1 1288.79  5121.4 1291.27  5126.5 1290.91  5165.1 1294.52  5170.2 1294.08
  5213.9 1298.34  5262.7 1300.61  5306.4 1303.71  5447.7 1308.44  5618.5 1311.37
#Mann= 4 ,-1 , 0
  4360.2      .1       0  4930.2     .05       0 5068.18      .1       0
  5618.5      .1       0
Bank Sta=4930.2,5068.18
XS Rating Curve= 0 ,0
Exp/Cntr=0.3,0.1

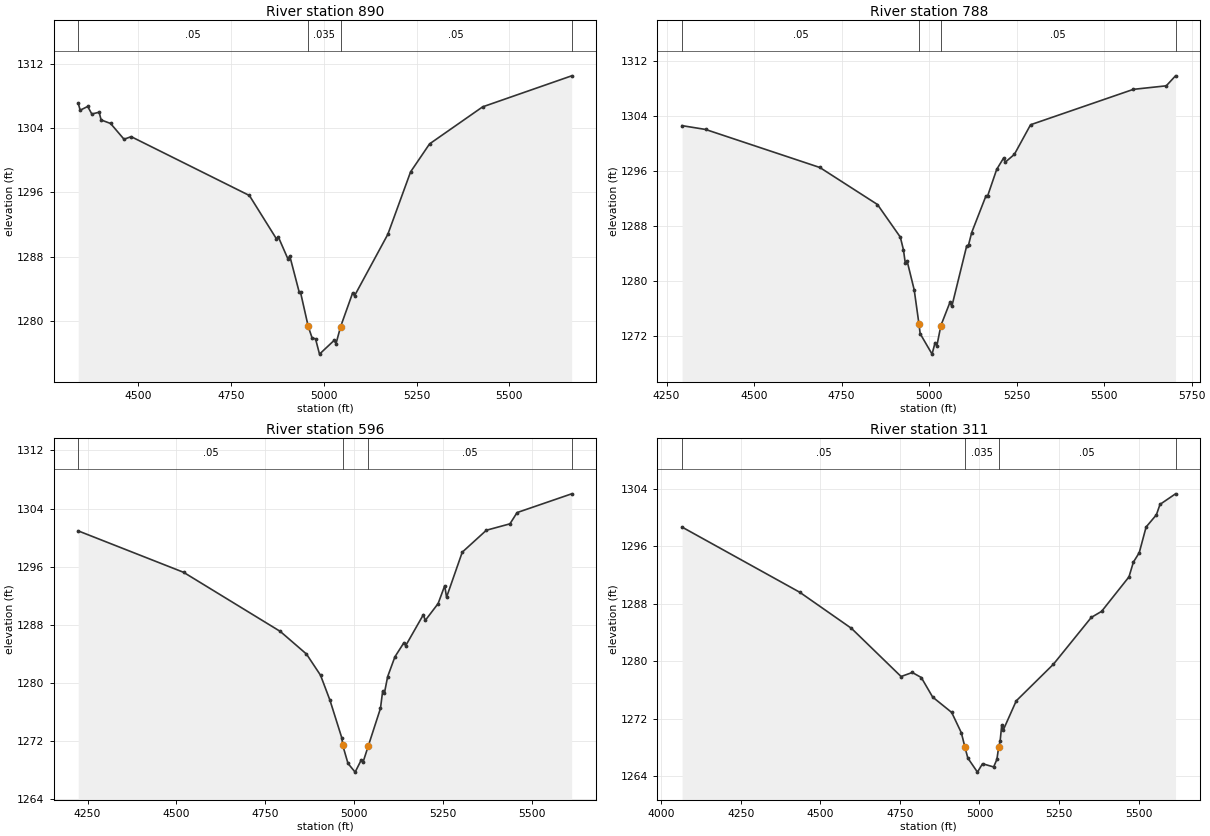
Type RM Length L Ch R = 1 ,890     ,102,102,102
BEGIN DESCRIPTION:
Mapping XS a1e4a516
END DESCRIPTION:
XS GIS Cut Line= 3
      2870414.01     10066638.53      2870979.99     10066839.92
      2871693.17     10066988.79
#Sta/Elev= 30
  4338.5 1307.11  4343.8 1306.23  4364.1  1306.7  4375.1 1305.76  4394.9 1305.98
  4400.2 1305.02  4425.7 1304.58  4461.9 1302.62  4481.2 1302.94  4799.6 1295.62
  4872.3 1290.24  4877.7 1290.45  4903.2 1287.75  4908.5 1288.08    4934 1283.56
  4937.5 1283.55  4958.1 1279.33  4968.3 1277.93  4977.9 1277.77  4988.5 1275.88
  5027.9 1277.59    5033 1277.19 5045.45 1279.31  5077.9 1283.51    5083 1283.15
  5172.6 1290.79  5233.9 1298.56    5285 1302.04    5428 1306.65  5667.8 1310.51
#Mann= 4 ,-1 , 0
  4338.5     .05       0  4958.1    .035       0 5045.45     .05       0
  5667.8      .1       0
Bank Sta=4958.1,5045.45
XS Rating Curve= 0 ,0
Exp/Cntr=0.3,0.1

Type RM Length L Ch R = 1 ,788     ,192,192,192
BEGIN DESCRIPTION:
Mapping XS 8a47759a
END DESCRIPTION:
XS GIS Cut Line= 4
      2870386.83     10066689.91      2870956.29     10066934.71
      2871202.81       10066992.      2871734.61     10067064.75
#Sta/Elev= 30
  4294.2 1302.58  4361.3 1302.03  4687.8 1296.51  4852.4 1291.14  4917.7 1286.41
  4926.6 1284.58  4931.8 1282.68  4936.9 1282.99  4957.4 1278.75 4970.91 1273.83
  4974.4  1272.4  5008.4 1269.43    5017 1271.09  5022.1 1270.63 5033.64 1273.58
  5059.6 1276.96  5064.8 1276.35  5107.4 1285.15  5112.5 1285.25  5121.6 1287.07
  5162.3 1292.38  5167.1 1292.38    5193 1296.23  5212.5 1297.86  5217.5 1297.28
  5243.5 1298.41  5289.8 1302.71  5583.7 1307.85  5677.5 1308.36  5703.9 1309.81
#Mann= 4 ,-1 , 0
  4294.2     .05       0 4970.91    .035       0 5033.64     .05       0
  5703.9      .1       0
Bank Sta=4970.91,5033.64
XS Rating Curve= 0 ,0
Exp/Cntr=0.3,0.1

Type RM Length L Ch R = 1 ,596     ,285,285,285
BEGIN DESCRIPTION:
Mapping XS 675e154d
END DESCRIPTION:
XS GIS Cut Line= 4
      2870404.23     10066743.75       2870923.3     10067122.21
      2871357.33     10067196.86      2871660.85      10067158.7
#Sta/Elev= 30
  4223.6 1300.92  4520.1 1295.22  4792.1 1287.09    4866 1283.97  4905.6 1281.05
  4932.1 1277.61  4965.5 1272.42 4968.18 1271.39  4982.8 1268.92  5002.9 1267.72
  5020.4 1269.42  5025.5 1269.14    5040 1271.33  5074.2 1276.49  5080.3 1278.83
  5085.4 1278.62  5094.5 1280.87  5114.8 1283.58  5140.3 1285.54  5145.4 1285.14
  5195.1  1289.4  5200.2 1288.59  5236.5 1290.92  5255.1 1293.38  5260.2 1291.79
  5304.4 1297.99  5372.3 1301.01  5438.6 1301.89  5458.7 1303.44  5612.3 1306.02
#Mann= 4 ,-1 , 0
  4223.6     .05       0 4968.18    .035       0    5040     .05       0
  5612.3     .16       0
Bank Sta=4968.18,5040
XS Rating Curve= 0 ,0
Exp/Cntr=0.3,0.1

Type RM Length L Ch R = 1 ,311     ,0,0,0
BEGIN DESCRIPTION:
Mapping XS 9d51b746
END DESCRIPTION:
XS GIS Cut Line= 4
      2870381.62     10066807.95      2870945.87     10067408.67
      2871181.98      10067448.6      2871634.32     10067269.04
#Sta/Elev= 30
  4065.6  1298.7  4435.3 1289.63  4597.9  1284.6  4753.7  1277.9  4788.9 1278.46
  4817.2 1277.76  4852.9 1275.04  4912.7  1272.9  4943.1 1270.06  4954.2 1268.08
  4963.4 1266.55  4993.6 1264.59  5009.6 1265.76  5044.5 1265.31  5054.7 1266.36
 5060.57 1268.14  5064.8 1268.87    5070 1271.17    5075 1270.48  5115.5 1274.51
  5232.5 1279.62  5351.4 1286.13  5383.7 1286.97  5469.7 1291.77  5483.5 1293.82
    5502 1295.14  5523.5 1298.71  5555.8 1300.41  5567.2 1301.86  5615.9 1303.33
#Mann= 4 ,-1 , 0
  4065.6     .05       0  4954.2    .035       0 5060.57     .05       0
  5615.9      .1       0
Bank Sta=4954.2,5060.57
XS Rating Curve= 0 ,0
Exp/Cntr=0.3,0.1

Chan Stop Cuts=-1
Use User Specified Reach Order=0
Composite Channel Slope=5