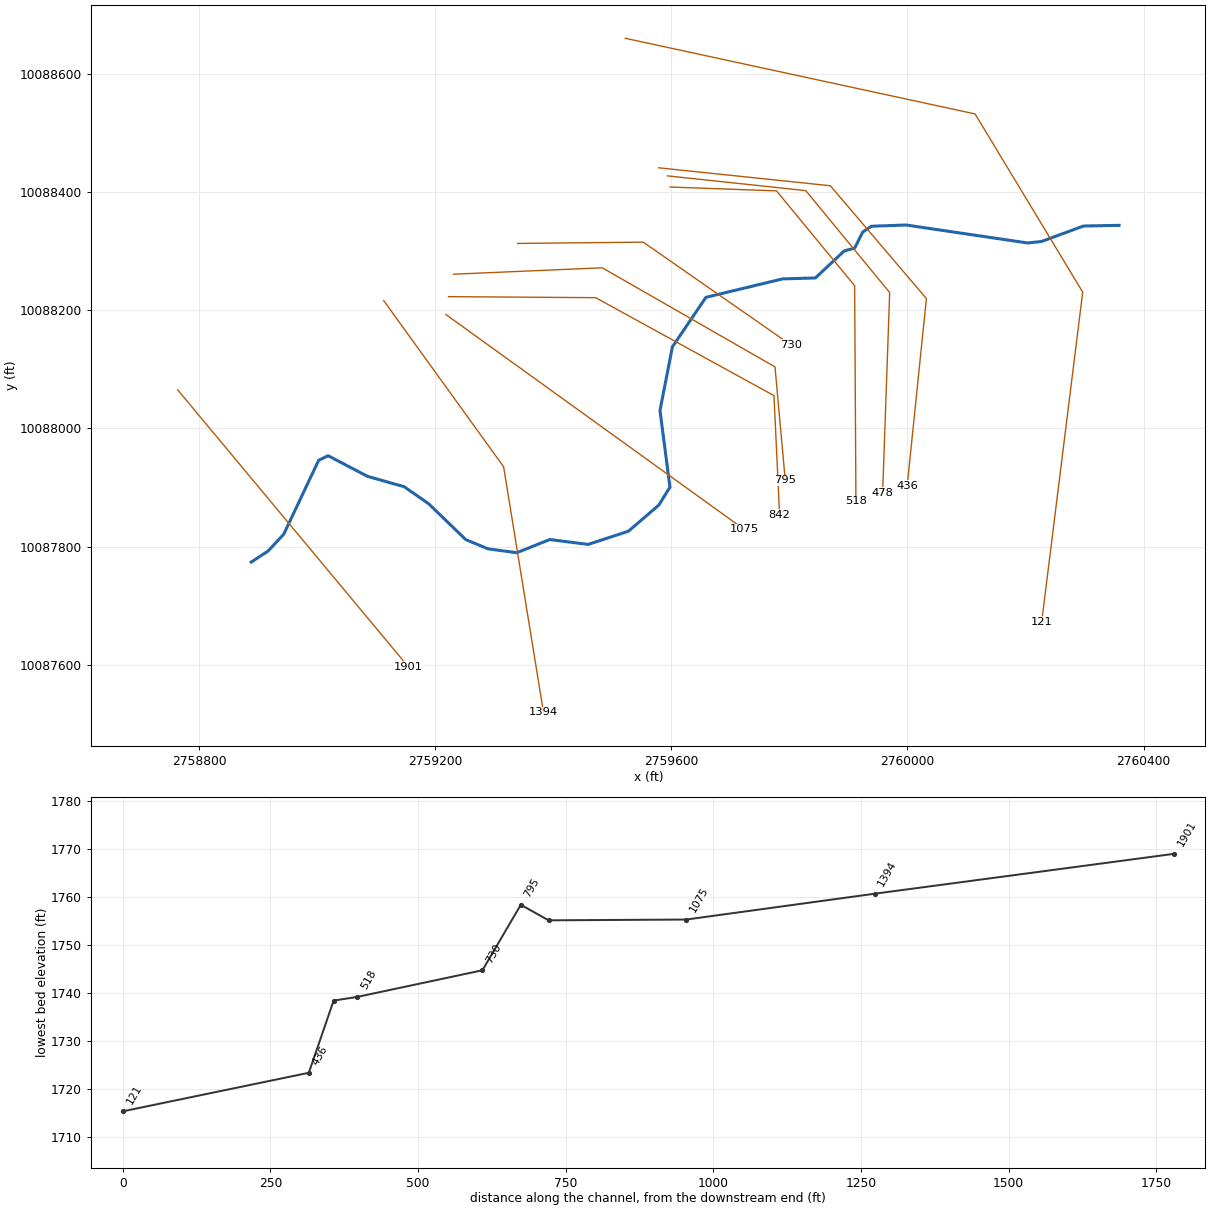
--- UNT021 IN NNOGR.prj (project) ---

Proj Title=UNT021 IN NNOGR Base Level Engineering
Current Plan=p01
Default Exp/Contr=0.3,0.1
English Units
Geom File=g01
Flow File=f01
Plan File=p01
BEGIN DESCRIPTION:
UNT021 IN NNOGR
END DESCRIPTION:

--- UNT021 IN NNOGR.p01 (plan) ---

Plan Title=Multiple Run
Short Identifier=Multiple
Geom File=g01
Flow File=f01
Subcritical Flow
K Sum by GR= 0
Std Step Tol= 0.01
Critical Tol= 0.01
Num of Std Step Trials= 20
Max Error Tol= 0.3
Flow Tol Ratio= 0.001
Split Flow NTrial= 30
Split Flow Tol= 0.02
Split Flow Ratio= 0.02
Log Output Level= 0
Friction Slope Method= 1
Unsteady Friction Slope Method= 2
Unsteady Bridges Friction Slope Method= 1
Parabolic Critical Depth
Global Vel Dist=  1 , 1 , 1
Global Log Level= 0
CheckData=True
Encroach Param= -1, 0, 0, 0
BEGIN DESCRIPTION:
Multiple Run
END DESCRIPTION:

--- UNT021 IN NNOGR.f01 (steady flow) ---

Flow Title=Multiple
Number of Profiles=7
Profile Names=10-year,25-year,50-year,1pct_min,100-year,1pct_plu,500-year
River Rch & RM= UNT021 IN NNOGR,Reach-1,1901
     522     743     933     860    1163    1573    1813
Boundary for River Rch & Prof#=UNT021 IN NNOGR,Reach-1,1
Up Type=0
Dn Type=3
Dn Slope=0.005
Boundary for River Rch & Prof#=UNT021 IN NNOGR,Reach-1,2
Up Type=0
Dn Type=3
Dn Slope=0.005
Boundary for River Rch & Prof#=UNT021 IN NNOGR,Reach-1,3
Up Type=0
Dn Type=3
Dn Slope=0.005
Boundary for River Rch & Prof#=UNT021 IN NNOGR,Reach-1,4
Up Type=0
Dn Type=3
Dn Slope=0.005
Boundary for River Rch & Prof#=UNT021 IN NNOGR,Reach-1,5
Up Type=0
Dn Type=3
Dn Slope=0.005
Boundary for River Rch & Prof#=UNT021 IN NNOGR,Reach-1,6
Up Type=0
Dn Type=3
Dn Slope=0.005
Boundary for River Rch & Prof#=UNT021 IN NNOGR,Reach-1,7
Up Type=0
Dn Type=3
Dn Slope=0.005

--- UNT021 IN NNOGR.g01 (geometry) ---

Geom Title=Existing Conditions

River Reach=UNT021 IN NNOGR,Reach-1
Reach XY= 30
      2758888.47     10087773.73      2758917.16     10087792.53
      2758943.62     10087821.02      2759002.79     10087946.13
      2759018.76     10087953.77      2759085.68     10087918.80
      2759147.50     10087901.41      2759188.70     10087872.80
      2759252.00     10087811.75      2759289.68     10087796.16
      2759338.34     10087789.66      2759394.21     10087811.93
      2759459.21     10087803.67      2759527.42     10087826.04
      2759579.00     10087870.33      2759597.75     10087900.54
      2759580.91     10088030.34      2759601.92     10088138.04
      2759658.69     10088221.89      2759788.67     10088253.13
      2759844.10     10088254.68      2759893.05     10088300.49
      2759910.53     10088305.11      2759924.31     10088332.31
      2759938.90     10088342.21      2759997.75     10088344.29
      2760203.54     10088313.92      2760227.22     10088316.44
      2760298.26     10088342.59      2760358.47     10088343.73

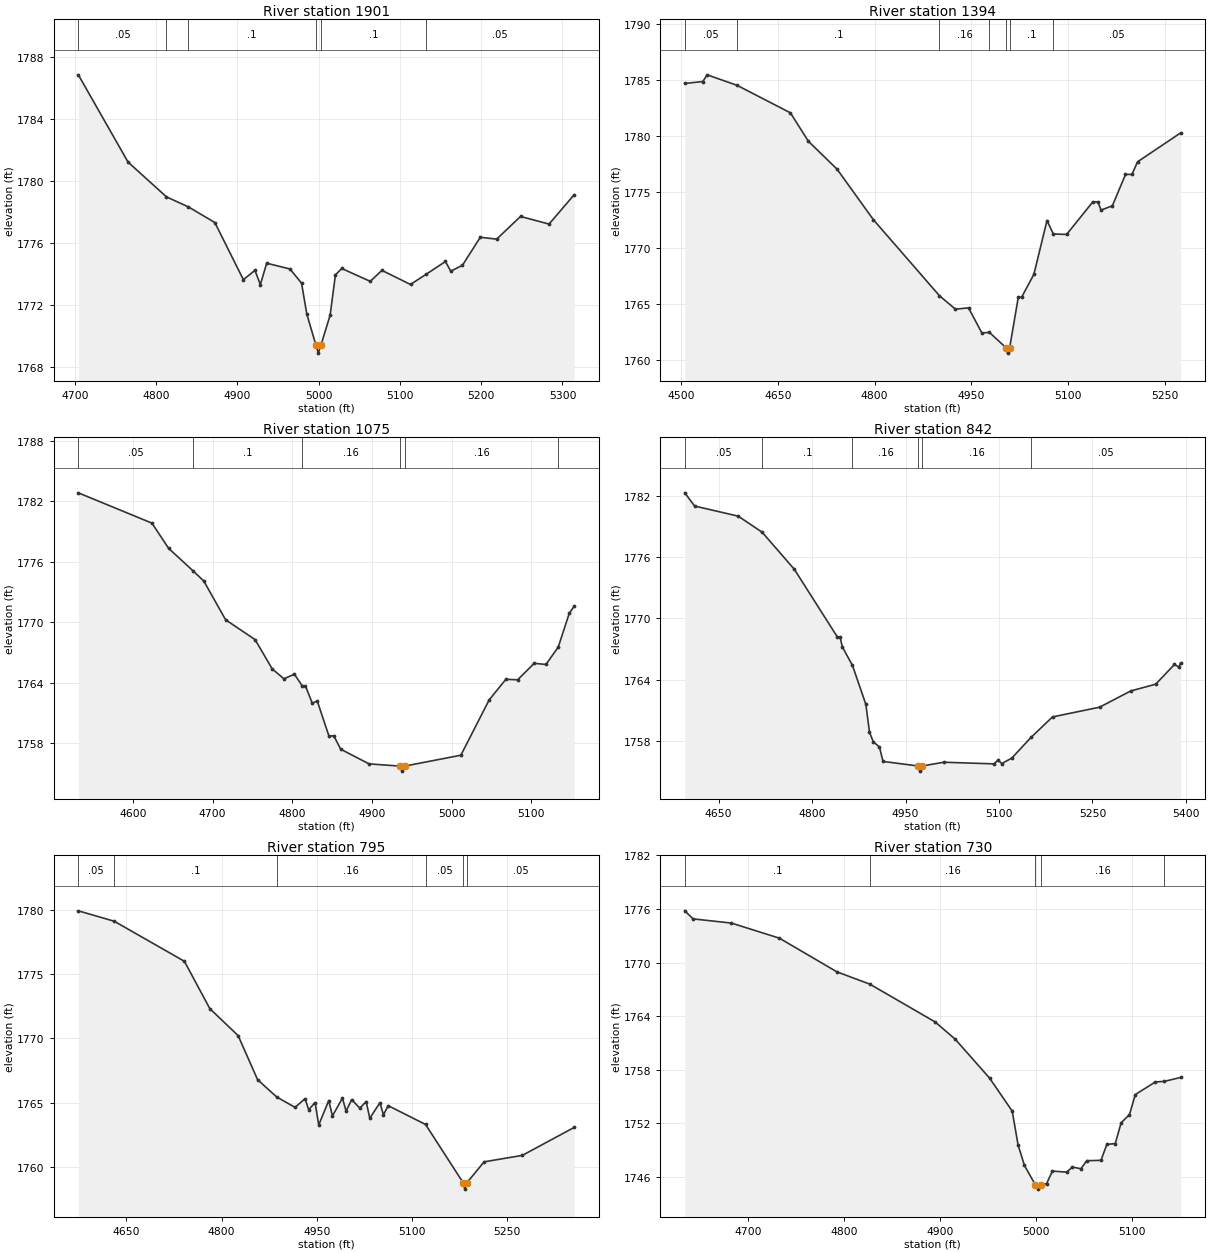
Type RM Length L Ch R = 1,1901,507,507,507
BEGIN DESCRIPTION:
UNT021 IN NNOGR 4.0
END DESCRIPTION:
XS GIS Cut Line= 2
      2758763.92     10088065.36      2759154.56     10087596.59
#Sta/Elev= 30
  4704.2 1786.83  4765.4 1781.21  4812.7 1778.97  4839.5 1778.33  4872.2 1777.32
  4907.3 1773.64  4921.6 1774.24  4928.2 1773.32  4936.0 1774.70  4964.6 1774.33
  4978.9 1773.42  4985.4 1771.42  4996.7 1769.41  4999.5 1768.91  5002.7 1769.41
  5014.1 1771.36  5020.6 1773.95  5028.4 1774.36  5063.5 1773.53  5077.8 1774.24
  5113.0 1773.33  5132.0 1773.98  5156.0 1774.81  5162.5 1774.19  5176.8 1774.56
  5198.9 1776.37  5219.0 1776.25  5248.4 1777.71  5283.5 1777.22  5314.4 1779.11
#Mann=6,-1,0
  4704.2    0.05       0  4812.7    0.16       0  4839.5     0.1       0
  4996.7    0.07       0  5002.7     0.1       0  5132.0    0.05       0
Bank Sta=4996.7,5002.7
Exp/Cntr=0.3,0.1

Type RM Length L Ch R = 1,1394,319,319,319
BEGIN DESCRIPTION:
UNT021 IN NNOGR 3.0
END DESCRIPTION:
XS GIS Cut Line= 3
      2759112.91     10088216.37      2759316.03     10087935.12
      2759383.58     10087519.40
#Sta/Elev= 30
  4505.9 1784.66  4533.8 1784.83  4540.5 1785.43  4587.0 1784.49  4669.5 1782.04
  4697.5 1779.49  4741.7 1777.02  4798.1 1772.50  4900.4 1765.72  4925.2 1764.52
  4945.4 1764.64  4966.1 1762.40  4977.8 1762.45  5003.2 1761.10  5005.9 1760.60
  5009.2 1761.10  5022.6 1765.61  5027.7 1765.59  5046.7 1767.63  5067.0 1772.43
  5076.8 1771.23  5097.4 1771.19  5137.9 1774.09  5145.8 1774.10  5150.8 1773.36
  5168.3 1773.75  5188.6 1776.54  5198.7 1776.55  5207.3 1777.67  5274.0 1780.25
#Mann=7,-1,0
  4505.9    0.05       0  4587.0     0.1       0  4900.4    0.16       0
  4977.8     0.1       0  5003.2    0.07       0  5009.2     0.1       0
  5076.8    0.05       0
Bank Sta=5003.2,5009.2
Exp/Cntr=0.3,0.1

Type RM Length L Ch R = 1,1075,233,233,233
BEGIN DESCRIPTION:
Mapping XS 8e9b6d2a
END DESCRIPTION:
XS GIS Cut Line= 2
      2759218.39     10088192.69      2759723.51     10087829.04
#Sta/Elev= 30
  4531.5 1782.86  4623.9 1779.85  4644.8 1777.35  4675.8 1775.09  4689.0 1774.10
  4716.4 1770.25  4753.4 1768.28  4774.9 1765.37  4789.6 1764.39  4802.7 1764.85
  4812.4 1763.71  4816.6 1763.68  4825.2 1761.96  4831.4 1762.19  4846.1 1758.70
  4852.2 1758.73  4860.8 1757.40  4896.4 1755.94  4935.2 1755.72  4938.0 1755.22
  4941.2 1755.72  5011.7 1756.80  5047.3 1762.31  5068.2 1764.34  5082.9 1764.29
  5103.8 1765.93  5118.5 1765.81  5133.9 1767.54  5147.7 1770.88  5153.9 1771.60
#Mann=6,-1,0
  4531.5    0.05       0  4675.8     0.1       0  4812.4    0.16       0
  4935.2    0.07       0  4941.2    0.16       0  5133.9    0.05       0
Bank Sta=4935.2,4941.2
Exp/Cntr=0.3,0.1

Type RM Length L Ch R = 1,842,47,47,47
BEGIN DESCRIPTION:
UNT021 IN NNOGR 2.0
END DESCRIPTION:
XS GIS Cut Line= 4
      2759222.73     10088223.05      2759471.89     10088221.32
      2759773.97     10088055.52      2759783.49     10087853.80
#Sta/Elev= 30
  4595.8 1782.27  4611.5 1780.98  4681.5 1779.99  4719.9 1778.42  4771.5 1774.80
  4840.8 1768.16  4845.0 1768.16  4848.6 1767.21  4864.9 1765.39  4886.4 1761.58
  4892.2 1758.87  4898.1 1757.95  4908.2 1757.41  4913.9 1756.01  4970.6 1755.56
  4973.4 1755.06  4976.6 1755.56  5011.5 1755.93  5092.0 1755.77  5098.7 1756.14
  5104.4 1755.80  5120.5 1756.33  5151.3 1758.35  5185.9 1760.36  5261.4 1761.31
  5311.5 1762.90  5351.5 1763.56  5381.6 1765.49  5388.7 1765.23  5391.5 1765.64
#Mann=6,-1,0
  4595.8    0.05       0  4719.9     0.1       0  4864.9    0.16       0
  4970.6    0.07       0  4976.6    0.16       0  5151.3    0.05       0
Bank Sta=4970.6,4976.6
Exp/Cntr=0.3,0.1

Type RM Length L Ch R = 1,795,65,65,65
BEGIN DESCRIPTION:
Mapping XS e3ee9804
END DESCRIPTION:
XS GIS Cut Line= 4
      2759231.35     10088261.04      2759483.11     10088271.89
      2759775.71     10088104.13      2759793.07     10087912.29
#Sta/Elev= 30
  4574.1 1779.91  4630.8 1779.10  4741.4 1775.99  4781.4 1772.32  4826.1 1770.22
  4856.8 1766.80  4886.8 1765.46  4915.8 1764.65  4931.6 1765.32  4937.4 1764.47
  4947.4 1765.02  4953.2 1763.28  4969.0 1765.18  4974.8 1763.98  4990.6 1765.37
  4996.3 1764.36  5005.2 1765.25  5017.9 1764.59  5028.0 1765.10  5033.7 1763.81
  5049.6 1765.00  5055.3 1764.08  5062.8 1764.78  5121.7 1763.32  5180.9 1758.80
  5183.6 1758.30  5186.9 1758.80  5214.0 1760.42  5274.2 1760.92  5356.0 1763.09
#Mann=6,-1,0
  4574.1    0.05       0  4630.8     0.1       0  4886.8    0.16       0
  5121.7    0.05       0  5180.9    0.07       0  5186.9    0.05       0
Bank Sta=5180.9,5186.9
Exp/Cntr=0.3,0.1

Type RM Length L Ch R = 1,730,212,212,212
BEGIN DESCRIPTION:
Mapping XS 36db4a57
END DESCRIPTION:
XS GIS Cut Line= 3
      2759339.84     10088313.12      2759552.56     10088315.29
      2759802.09     10088141.70
#Sta/Elev= 30
  4633.7 1775.78  4642.3 1774.88  4682.3 1774.41  4732.3 1772.72  4792.3 1768.95
  4826.5 1767.58  4894.6 1763.35  4915.5 1761.42  4951.3 1757.07  4974.9 1753.38
  4981.0 1749.60  4987.6 1747.31  4998.9 1745.15  5001.7 1744.65  5004.9 1745.15
  5010.7 1745.26  5016.8 1746.67  5031.6 1746.55  5037.7 1747.12  5046.5 1746.93
  5052.6 1747.83  5067.4 1747.87  5073.5 1749.65  5082.3 1749.75  5088.4 1752.07
  5097.1 1752.99  5103.2 1755.23  5124.1 1756.64  5133.2 1756.70  5150.4 1757.14
#Mann=5,-1,0
  4633.7     0.1       0  4826.5    0.16       0  4998.9    0.07       0
  5004.9    0.16       0  5133.2    0.05       0
Bank Sta=4998.9,5004.9
Exp/Cntr=0.3,0.1

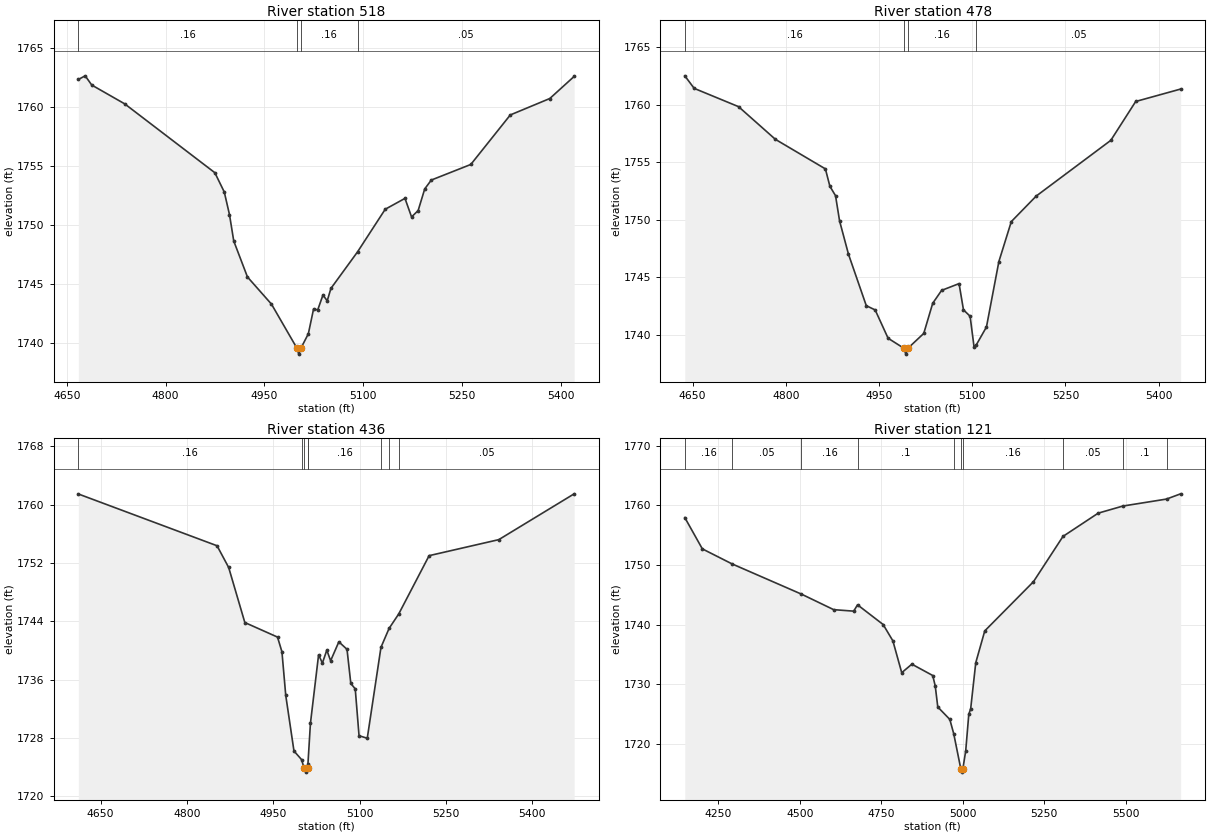
Type RM Length L Ch R = 1,518,40,40,40
BEGIN DESCRIPTION:
Mapping XS 3d32eb3d
END DESCRIPTION:
XS GIS Cut Line= 4
      2759598.09     10088408.61      2759778.25     10088402.10
      2759910.63     10088241.51      2759912.79     10087876.71
#Sta/Elev= 30
  4667.5 1762.34  4677.9 1762.65  4687.9 1761.87  4737.9 1760.28  4874.9 1754.45
  4889.2 1752.82  4897.1 1750.91  4903.6 1748.67  4924.4 1745.63  4960.9 1743.33
  4999.6 1739.60  5002.3 1739.10  5005.6 1739.60  5016.9 1740.82  5024.8 1742.91
  5031.2 1742.85  5039.1 1744.10  5045.6 1743.61  5051.2 1744.66  5091.6 1747.75
  5133.7 1751.36  5163.7 1752.28  5173.7 1750.71  5183.7 1751.25  5193.7 1753.08
  5203.7 1753.83  5263.7 1755.15  5323.7 1759.34  5383.7 1760.73  5420.7 1762.60
#Mann=4,-1,0
  4667.5    0.16       0  4999.6    0.07       0  5005.6    0.16       0
  5091.6    0.05       0
Bank Sta=4999.6,5005.6
Exp/Cntr=0.3,0.1

Type RM Length L Ch R = 1,478,42,42,42
BEGIN DESCRIPTION:
Mapping XS a4d8d638
END DESCRIPTION:
XS GIS Cut Line= 4
      2759593.46     10088427.48      2759827.83     10088402.52
      2759969.97     10088229.99      2759958.04     10087891.44
#Sta/Elev= 30
  4637.4 1762.52  4652.5 1761.43  4723.9 1759.84  4783.2 1757.00  4863.7 1754.43
  4870.9 1752.92  4880.0 1752.10  4886.5 1749.91  4900.8 1747.02  4929.5 1742.54
  4943.8 1742.17  4964.6 1739.71  4990.3 1738.83  4993.1 1738.33  4996.3 1738.83
  5022.0 1740.13  5036.4 1742.75  5050.7 1743.87  5078.8 1744.46  5085.9 1742.18
  5096.6 1741.62  5102.9 1738.97  5106.3 1739.11  5122.9 1740.69  5142.9 1746.38
  5162.9 1749.85  5203.0 1752.07  5323.0 1756.91  5363.1 1760.29  5435.4 1761.37
#Mann=4,-1,0
  4637.4    0.16       0  4990.3    0.07       0  4996.3    0.16       0
  5106.3    0.05       0
Bank Sta=4990.3,4996.3
Exp/Cntr=0.3,0.1

Type RM Length L Ch R = 1,436,315,315,315
BEGIN DESCRIPTION:
Mapping XS e11d2513
END DESCRIPTION:
XS GIS Cut Line= 4
      2759578.62     10088441.16      2759869.40     10088410.78
      2760032.16     10088219.81      2759999.61     10087902.95
#Sta/Elev= 30
  4611.3 1761.48  4852.4 1754.37  4872.6 1751.39  4900.7 1743.83  4957.5 1741.83
  4965.2 1739.81  4971.8 1733.83  4986.1 1726.19  4999.3 1725.01  5003.9 1723.79
  5006.7 1723.29  5009.9 1723.79  5010.4 1724.43  5014.7 1729.97  5028.9 1739.40
  5035.5 1738.26  5043.2 1740.04  5049.8 1738.58  5064.1 1741.18  5078.3 1740.15
  5084.9 1735.46  5092.6 1734.72  5099.2 1728.29  5113.5 1727.94  5137.3 1740.42
  5151.4 1743.02  5168.2 1745.01  5221.0 1753.01  5342.1 1755.21  5473.1 1761.50
#Mann=8,-1,0
  4611.3    0.16       0  4999.3     0.1       0  5003.9    0.07       0
  5009.9     0.1       0  5010.4    0.16       0  5137.3    0.05       0
  5151.4    0.16       0  5168.2    0.05       0
Bank Sta=5003.9,5009.9
Exp/Cntr=0.3,0.1

Type RM Length L Ch R = 1,121,0,0,0
BEGIN DESCRIPTION:
UNT021 IN NNOGR 1.0
END DESCRIPTION:
XS GIS Cut Line= 4
      2759522.14     10088660.35      2760114.62     10088532.31
      2760296.92     10088230.66      2760227.47     10087672.88
#Sta/Elev= 30
  4147.6 1757.94  4201.4 1752.69  4292.6 1750.17  4505.5 1745.10  4604.2 1742.50
  4665.6 1742.25  4677.4 1743.31  4755.9 1740.01  4785.8 1737.27  4812.9 1731.93
  4844.0 1733.36  4908.0 1731.46  4915.7 1729.71  4923.5 1726.18  4960.4 1724.10
  4972.4 1721.70  4994.3 1715.76  4997.0 1715.26  5000.3 1715.76  5009.2 1718.84
  5018.6 1724.95  5024.4 1725.89  5040.0 1733.61  5067.6 1738.94  5217.0 1747.19
  5307.5 1754.78  5415.5 1758.68  5491.1 1759.87  5625.0 1761.04  5668.3 1761.92
#Mann=10,-1,0
  4147.6    0.16       0  4292.6    0.05       0  4505.5    0.16       0
  4677.4     0.1       0  4972.4    0.16       0  4994.3    0.07       0
  5000.3    0.16       0  5307.5    0.05       0  5491.1     0.1       0
  5625.0    0.05       0
Bank Sta=4994.3,5000.3
Exp/Cntr=0.3,0.1

Chan Stop Cuts=-1