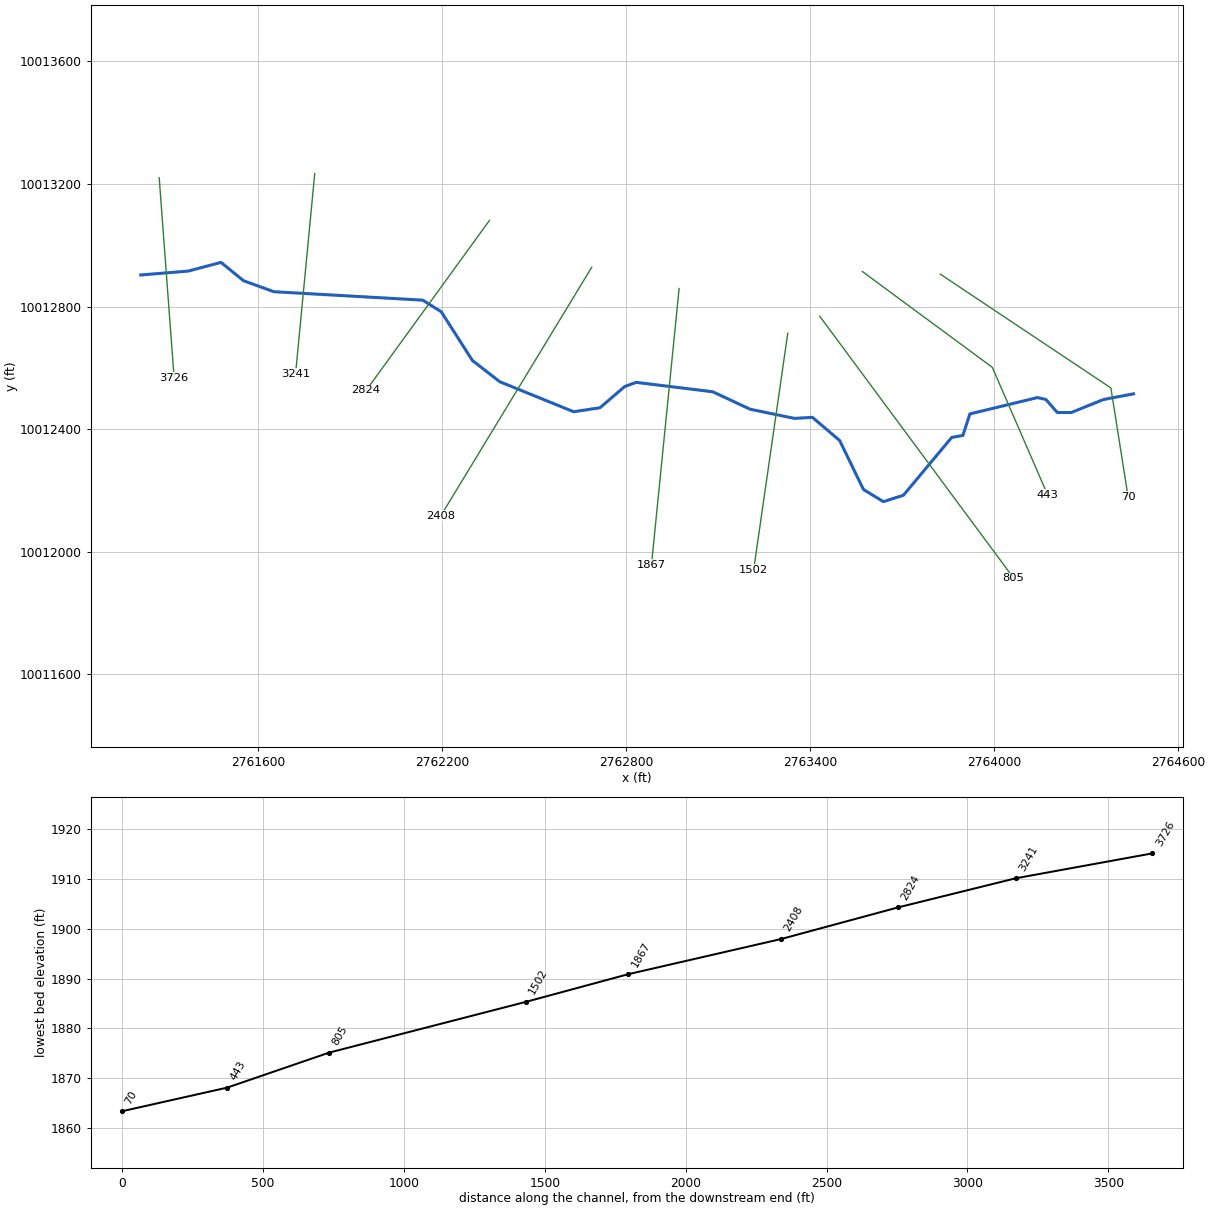
--- UNT021 IN SNOGR.prj (project) ---

Proj Title=UNT021 IN SNOGR Base Level Engineering
Current Plan=p01
Default Exp/Contr=0.3,0.1
English Units
Geom File=g01
Flow File=f01
Plan File=p01
Y Axis Title=Elevation
X Axis Title(PF)=Main Channel Distance
X Axis Title(XS)=Station
BEGIN DESCRIPTION:
UNT021 IN SNOGR
END DESCRIPTION:
DSS Export Rating Curves= 0
DSS Export Rating Curve Sorted= 0
DSS Export Volume Flow Curves= 0
DXF OffsetX= 0
DXF OffsetY= 0
DXF ScaleX= 1
DXF ScaleY= 10

--- UNT021 IN SNOGR.p01 (plan) ---

Plan Title=Multiple Run
Short Identifier=Multiple
Geom File=g01
Flow File=f01
Subcritical Flow
K Sum by GR= 0
Std Step Tol= 0.01
Critical Tol= 0.01
Num of Std Step Trials= 20
Max Error Tol= 0.3
Flow Tol Ratio= 0.001
Split Flow NTrial= 30
Split Flow Tol= 0.02
Split Flow Ratio= 0.02
Log Output Level= 0
Friction Slope Method= 1
Unsteady Friction Slope Method= 2
Unsteady Bridges Friction Slope Method= 1
Parabolic Critical Depth
Global Vel Dist=  1 , 1 , 1
Global Log Level= 0
CheckData=True
Encroach Param= -1, 0, 0, 0
BEGIN DESCRIPTION:
Multiple Run
END DESCRIPTION:

--- UNT021 IN SNOGR.f01 (steady flow) ---

Flow Title=Multiple
Number of Profiles=7
Profile Names=10-year,25-year,50-year,1pct_min,100-year,1pct_plu,500-year
River Rch & RM= UNT021 IN SNOGR,Reach-1,3726
     713    1020    1282    1181    1597    2159    2486
Boundary for River Rch & Prof#=UNT021 IN SNOGR,Reach-1,1
Up Type=0
Dn Type=3
Dn Slope=0.005
Boundary for River Rch & Prof#=UNT021 IN SNOGR,Reach-1,2
Up Type=0
Dn Type=3
Dn Slope=0.005
Boundary for River Rch & Prof#=UNT021 IN SNOGR,Reach-1,3
Up Type=0
Dn Type=3
Dn Slope=0.005
Boundary for River Rch & Prof#=UNT021 IN SNOGR,Reach-1,4
Up Type=0
Dn Type=3
Dn Slope=0.005
Boundary for River Rch & Prof#=UNT021 IN SNOGR,Reach-1,5
Up Type=0
Dn Type=3
Dn Slope=0.005
Boundary for River Rch & Prof#=UNT021 IN SNOGR,Reach-1,6
Up Type=0
Dn Type=3
Dn Slope=0.005
Boundary for River Rch & Prof#=UNT021 IN SNOGR,Reach-1,7
Up Type=0
Dn Type=3
Dn Slope=0.005

--- UNT021 IN SNOGR.g01 (geometry) ---

Geom Title=Existing Conditions
Program Version=4.10

River Reach=UNT021 IN SNOGR ,Reach-1
Reach XY= 30
      2761218.64      10012902.9       2761372.9     10012915.58
      2761479.93     10012943.93      2761553.64     10012884.12
      2761652.24     10012848.34      2762137.31     10012820.83
      2762197.74     10012783.06      2762299.33      10012624.1
      2762388.81     10012554.59      2762629.51     10012456.89
      2762715.28     10012469.93      2762795.57     10012539.03
      2762833.28     10012552.67      2763082.76     10012522.02
      2763204.09     10012465.23      2763349.15     10012435.19
      2763407.47      10012438.7      2763496.38     10012363.03
      2763573.83     10012203.43       2763638.9     10012163.59
      2763704.28     10012184.69      2763861.57     10012373.07
      2763897.96     10012379.58       2763920.9     10012449.83
       2764140.6       10012503.      2764168.27     10012497.09
      2764205.77     10012454.31      2764251.09     10012454.33
      2764356.32     10012496.75      2764454.08     10012515.29

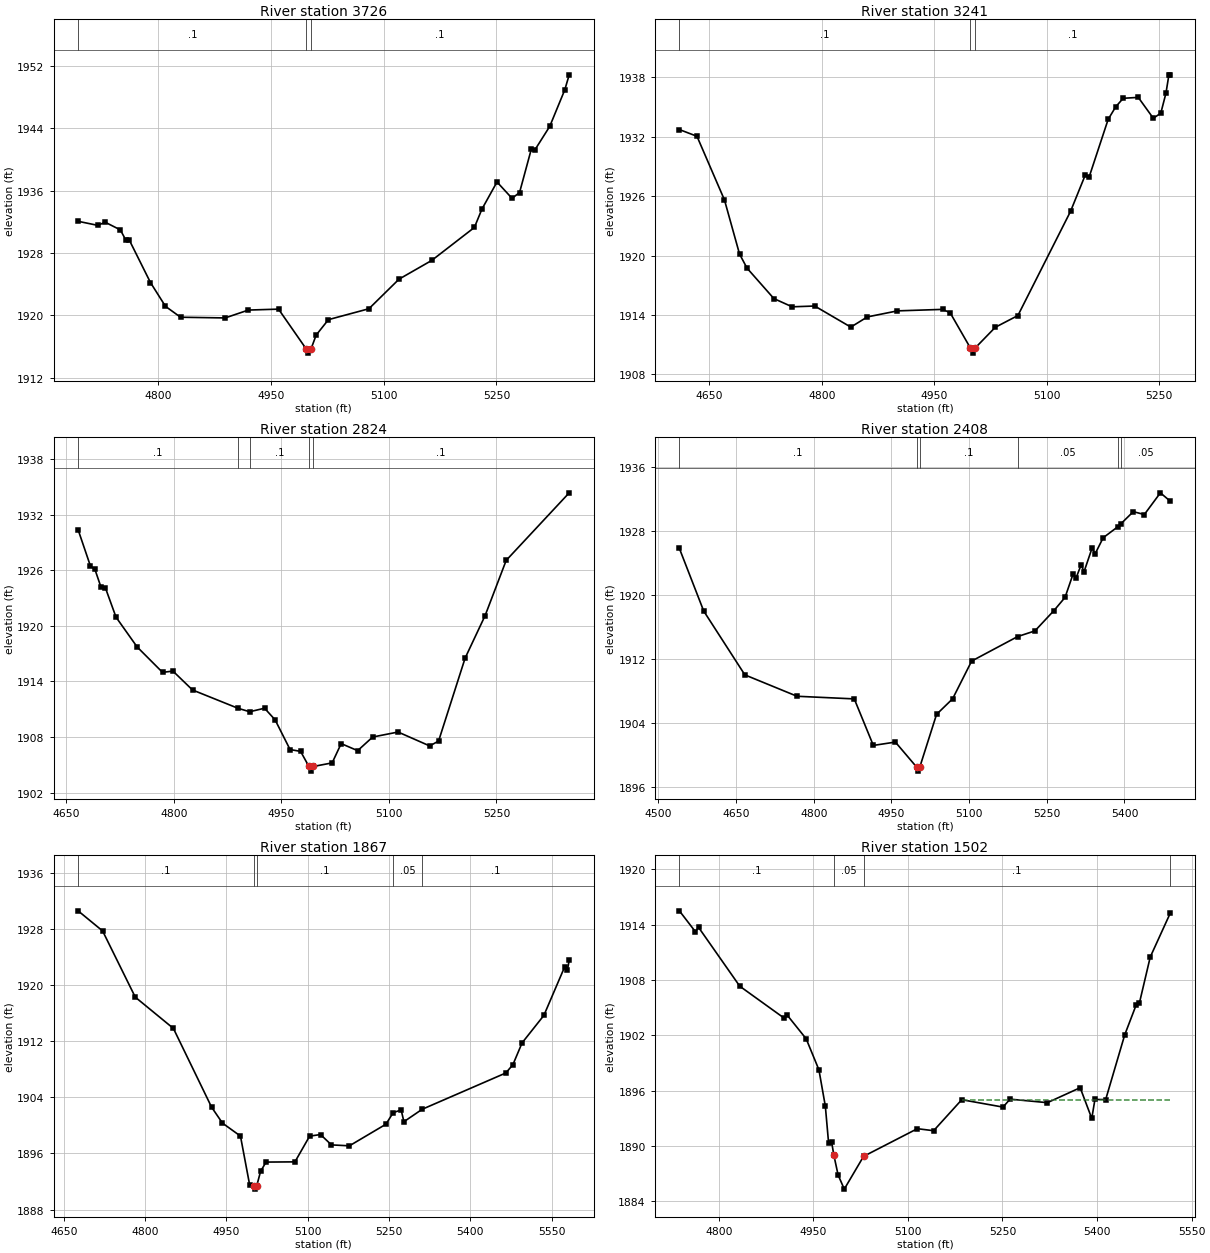
Type RM Length L Ch R = 1 ,3726    ,485,485,485
BEGIN DESCRIPTION:
UNT021 IN SNOGR 8.0
END DESCRIPTION:
XS GIS Cut Line= 2
      2761278.62     10013219.75      2761327.17     10012567.86
#Sta/Elev= 30
  4693.2 1932.08  4719.3 1931.56  4729.3 1931.96  4749.4 1930.98  4756.4 1929.73
  4761.4 1929.66  4789.5 1924.22  4809.5 1921.16  4829.6 1919.76  4888.9 1919.67
  4919.8 1920.68    4960  1920.8  4997.1 1915.65  4999.8 1915.15  5003.1 1915.65
  5010.1 1917.47  5026.4 1919.45  5080.3 1920.85  5120.4 1924.65    5164 1927.06
  5220.7 1931.29  5230.7 1933.64  5250.8 1937.13  5270.8 1935.03  5280.8 1935.77
  5296.5 1941.36  5301.5 1941.29    5321 1944.27    5341 1948.96  5346.9 1950.89
#Mann= 3 ,-1 , 0
  4693.2      .1       0  4997.1     .07       0  5003.1      .1       0
Bank Sta=4997.1,5003.1
XS Rating Curve= 0 ,0
Exp/Cntr=0.3,0.1

Type RM Length L Ch R = 1 ,3241    ,417,417,417
BEGIN DESCRIPTION:
UNT021 IN SNOGR 7.0
END DESCRIPTION:
XS GIS Cut Line= 2
      2761785.56     10013233.63      2761723.07     10012580.92
#Sta/Elev= 30
  4609.8 1932.74  4633.3 1932.06    4670 1925.63  4690.1 1920.17  4700.1 1918.74
    4736 1915.66  4760.4 1914.83  4790.5 1914.91  4838.7 1912.78  4860.8 1913.81
    4901 1914.42  4961.3 1914.57  4971.3 1914.23  4998.5 1910.65  5001.2 1910.15
  5004.5 1910.65  5031.6 1912.76  5061.8 1913.95  5132.1 1924.48  5151.8 1928.16
  5156.8 1927.92  5182.3 1933.77  5192.4 1935.04  5202.4  1935.9  5222.5 1935.99
  5242.6 1933.88  5252.6  1934.4  5259.5 1936.43  5263.4 1938.27  5265.5 1938.27
#Mann= 3 ,-1 , 0
  4609.8      .1       0  4998.5     .07       0  5004.5      .1       0
Bank Sta=4998.5,5004.5
XS Rating Curve= 0 ,0
Exp/Cntr=0.3,0.1

Type RM Length L Ch R = 1 ,2824    ,416,416,416
BEGIN DESCRIPTION:
UNT021 IN SNOGR 6.0
END DESCRIPTION:
XS GIS Cut Line= 2
        2762355.     10013080.87      2761952.87      10012526.2
#Sta/Elev= 30
  4666.4 1930.37  4683.7 1926.43  4689.9 1926.08  4698.4 1924.15  4704.6 1924.07
  4719.3 1920.93  4748.7 1917.72  4784.2 1914.97  4798.7 1915.11    4826 1913.07
  4889.6 1911.09  4905.8 1910.72  4926.5  1911.1  4941.2 1909.85  4962.1 1906.64
  4976.8 1906.44  4988.4 1904.81  4991.2 1904.31  4994.4 1904.81  5020.8  1905.2
  5033.4 1907.28  5056.4 1906.52  5077.3 1907.99  5112.8 1908.53  5156.9 1907.03
  5169.3 1907.56  5206.3 1916.51  5234.2  1921.1  5263.6 1927.06  5351.5 1934.35
#Mann= 5 ,-1 , 0
  4666.4      .1       0  4889.6     .16       0  4905.8      .1       0
  4988.4     .07       0  4994.4      .1       0
Bank Sta=4988.4,4994.4
XS Rating Curve= 0 ,0
Exp/Cntr=0.3,0.1

Type RM Length L Ch R = 1 ,2408    ,541,541,541
BEGIN DESCRIPTION:
UNT021 IN SNOGR 5.0
END DESCRIPTION:
XS GIS Cut Line= 2
      2762688.33     10012928.08      2762196.26      10012117.2
#Sta/Elev= 30
  4540.4 1925.86  4587.4 1918.01  4666.9 1910.01  4767.7 1907.33  4878.2    1907
    4915 1901.17  4957.6 1901.59  4998.7 1898.45  5001.4 1897.95  5004.7 1898.45
  5037.1 1905.06  5068.1 1907.01  5104.9 1911.74  5193.7 1914.81  5227.1 1915.52
  5263.9 1918.07  5285.3 1919.72  5300.7 1922.63  5306.6 1922.16  5316.2 1923.77
  5322.1 1922.96  5337.6 1925.92  5343.4 1925.18  5358.9 1927.19  5386.6 1928.54
  5392.5  1928.9  5417.1 1930.46  5438.4  1930.1  5469.4 1932.82  5488.9 1931.75
#Mann= 6 ,-1 , 0
  4540.4      .1       0  4998.7     .07       0  5004.7      .1       0
  5193.7     .05       0  5386.6      .1       0  5392.5     .05       0
Bank Sta=4998.7,5004.7
XS Rating Curve= 0 ,0
Exp/Cntr=0.3,0.1

Type RM Length L Ch R = 1 ,1867    ,365,365,365
BEGIN DESCRIPTION:
UNT021 IN SNOGR 4.0
END DESCRIPTION:
XS GIS Cut Line= 2
      2762973.07     10012858.68      2762882.93     10011957.27
#Sta/Elev= 30
  4676.3 1930.62  4721.5 1927.75  4781.8  1918.3  4852.1 1913.84  4922.5 1902.61
  4942.6 1900.33  4975.8 1898.48  4992.8 1891.49  4999.9 1891.41  5002.6 1890.91
  5005.9 1891.41  5012.9 1893.44    5023 1894.77  5076.3  1894.8  5103.4 1898.47
  5123.5  1898.7  5143.6 1897.22  5176.8 1897.09  5244.1 1900.17  5257.5 1901.82
  5272.2 1902.21  5277.3 1900.53  5310.9  1902.3  5465.2 1907.48  5478.3 1908.66
  5495.3 1911.78  5535.5  1915.7  5573.7  1922.6  5578.8 1922.15  5582.2 1923.56
#Mann= 5 ,-1 , 0
  4676.3      .1       0  4999.9     .07       0  5005.9      .1       0
  5257.5     .05       0  5310.9      .1       0
Bank Sta=4999.9,5005.9
XS Rating Curve= 0 ,0
Exp/Cntr=0.3,0.1

Type RM Length L Ch R = 1 ,1502    ,697,697,697
BEGIN DESCRIPTION:
UNT021 IN SNOGR 3.0
END DESCRIPTION:
XS GIS Cut Line= 2
      2763327.23     10012712.82      2763216.12     10011941.98
#Sta/Elev= 30
  4737.6 1915.49    4763 1913.23    4768  1913.7  4833.4 1907.32  4903.8 1903.86
  4908.8 1904.17  4938.7 1901.62  4958.9 1898.26  4969.1 1894.31  4974.2 1890.36
  4979.2 1890.39 4982.39 1889.07  4989.3 1886.87  4999.1 1885.33  5029.7 1888.88
    5115 1891.88  5140.8 1891.66  5185.4 1895.02  5250.8 1894.22    5262 1895.08
  5321.2  1894.7  5373.2 1896.32  5391.6 1892.99  5396.6 1895.05  5413.6 1895.03
  5443.9 1902.06    5462 1905.29    5467 1905.46  5484.3 1910.48  5516.4 1915.29
#Mann= 4 ,-1 , 0
  4737.6      .1       0 4982.39     .05       0  5029.7      .1       0
  5516.4      .1       0
#XS Ineff= 2 , 0
                         5186.36         1895.03
Permanent Ineff=
       T       T
Bank Sta=4982.39,5029.7
XS Rating Curve= 0 ,0
Exp/Cntr=0.3,0.1

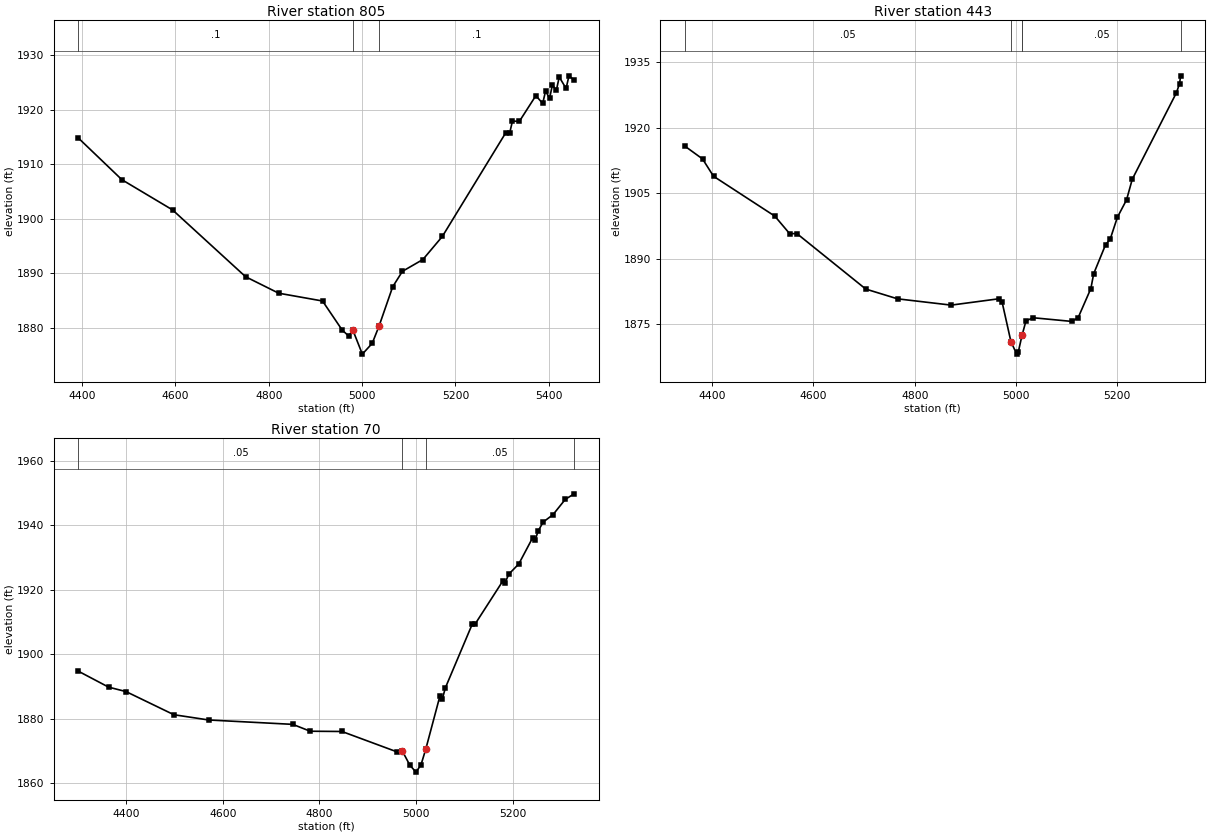
Type RM Length L Ch R = 1 ,805     ,362,362,362
BEGIN DESCRIPTION:
UNT021 IN SNOGR 2.0
END DESCRIPTION:
XS GIS Cut Line= 2
      2763431.42     10012768.35      2764063.35     10011914.21
#Sta/Elev= 30
  4391.8 1914.78  4485.1 1907.14  4593.7  1901.6  4750.2 1889.35  4821.1 1886.33
  4915.1  1884.9  4957.3 1879.56  4971.4 1878.46  4979.8 1879.62  5000.4 1875.16
  5021.5 1877.13  5036.2  1880.3  5065.4  1887.5  5086.3 1890.34  5130.1  1892.5
  5171.8 1896.73  5307.5 1915.71  5315.9 1915.62  5322.1 1917.89  5336.8 1917.82
  5372.2 1922.54  5386.9 1921.12  5393.1 1923.42  5401.5 1922.03  5407.7  1924.5
  5416.1  1923.5  5422.3 1925.96    5437 1923.87  5443.2 1926.18  5454.3 1925.38
#Mann= 3 , 0 , 0
  4391.8      .1       0  4979.8     .05       0  5036.2      .1       0
Bank Sta=4979.8,5036.2
XS Rating Curve= 0 ,0
Exp/Cntr=0.3,0.1

Type RM Length L Ch R = 1 ,443     ,373,373,373
BEGIN DESCRIPTION:
UNT021 IN SNOGR 1.0
END DESCRIPTION:
XS GIS Cut Line= 3
       2763570.3      10012914.2       2763993.9     10012601.71
      2764173.98     10012186.14
#Sta/Elev= 30
  4345.9  1915.8  4380.9 1912.86  4402.6 1908.89  4523.7 1899.75    4553 1895.73
  4567.3 1895.75  4703.3 1883.04  4766.1  1880.8    4872 1879.36  4967.3 1880.83
  4972.7    1880    4990 1871.02  5001.4 1868.13  5004.6 1868.63  5011.8 1872.36
  5012.3 1872.57  5019.7 1875.73  5033.6 1876.47  5109.9 1875.63  5122.7 1876.46
  5147.9 1883.16  5153.5 1886.56  5176.9 1893.18  5186.1 1894.48  5200.3 1899.49
  5218.4 1903.48  5229.7 1908.21  5316.9 1928.03  5323.1 1930.13  5325.2  1931.9
#Mann= 5 ,-1 , 0
  4345.9     .05       0    4990    .035       0  5011.8      .1       0
  5012.3     .05       0  5325.2     .16       0
Bank Sta=4990,5012.3
XS Rating Curve= 0 ,0
Exp/Cntr=0.3,0.1

Type RM Length L Ch R = 1 ,70      ,0,0,0
BEGIN DESCRIPTION:
UNT021 IN SNOGR 9.0
END DESCRIPTION:
XS GIS Cut Line= 3
      2763824.36     10012905.59      2764380.31     10012534.52
       2764436.3     10012180.34
#Sta/Elev= 30
  4300.6 1894.71  4363.3 1889.76  4399.4 1888.38  4498.5  1881.2  4570.6 1879.57
  4744.8 1878.21  4780.9 1876.08  4846.6    1876  4961.1 1869.65  4971.9 1869.88
  4987.1 1865.59  4999.9 1863.39  5010.3 1865.63  5020.4 1870.61  5049.5 1886.97
  5054.6 1886.11  5060.9 1889.57    5117 1909.48    5122 1909.23  5179.4 1922.59
  5184.4 1922.16  5192.5 1924.86  5212.8 1927.96  5241.7 1936.13  5246.8 1935.43
  5253.3 1938.28  5263.4 1940.98  5283.7 1943.26  5309.2 1948.02  5327.6 1949.74
#Mann= 4 ,-1 , 0
  4300.6     .05       0  4971.9    .035       0  5020.4     .05       0
  5327.6      .1       0
Bank Sta=4971.9,5020.4
XS Rating Curve= 0 ,0
Exp/Cntr=0.3,0.1

Chan Stop Cuts=-1
Use User Specified Reach Order=0
Composite Channel Slope=5