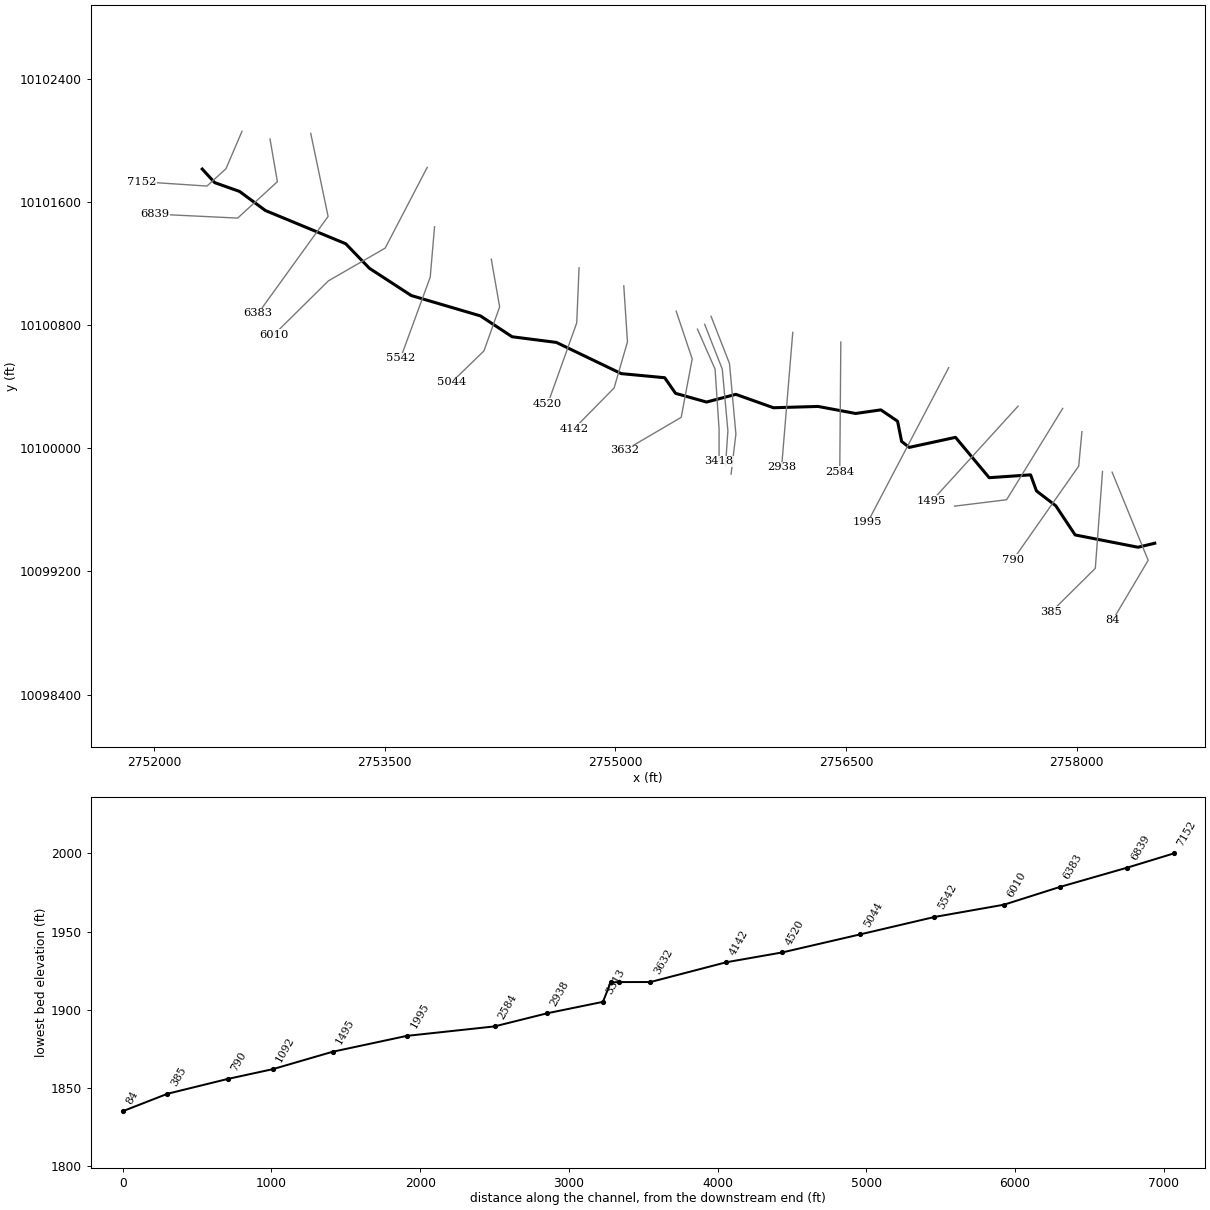
--- UNT023 IN NNOGR.prj (project) ---

Proj Title=UNT023 IN NNOGR Base Level Engineering
Current Plan=p01
Default Exp/Contr=0.3,0.1
English Units
Geom File=g01
Flow File=f01
Plan File=p01
Y Axis Title=Elevation
X Axis Title(PF)=Main Channel Distance
X Axis Title(XS)=Station
BEGIN DESCRIPTION:
UNT023 IN NNOGR
END DESCRIPTION:
DSS Export Rating Curves= 0
DSS Export Rating Curve Sorted= 0
DSS Export Volume Flow Curves= 0
DXF OffsetX= 0
DXF OffsetY= 0
DXF ScaleX= 1
DXF ScaleY= 10

--- UNT023 IN NNOGR.p01 (plan) ---

Plan Title=Multiple Run
Short Identifier=Multiple
Geom File=g01
Flow File=f01
Subcritical Flow
K Sum by GR= 0
Std Step Tol= 0.01
Critical Tol= 0.01
Num of Std Step Trials= 20
Max Error Tol= 0.3
Flow Tol Ratio= 0.001
Split Flow NTrial= 30
Split Flow Tol= 0.02
Split Flow Ratio= 0.02
Log Output Level= 0
Friction Slope Method= 1
Unsteady Friction Slope Method= 2
Unsteady Bridges Friction Slope Method= 1
Parabolic Critical Depth
Global Vel Dist=  1 , 1 , 1
Global Log Level= 0
CheckData=True
Encroach Param= -1, 0, 0, 0
BEGIN DESCRIPTION:
Multiple Run
END DESCRIPTION:

--- UNT023 IN NNOGR.f01 (steady flow) ---

Flow Title=Multiple
Program Version=4.10
Number of Profiles= 7
Profile Names=10-year,25-year,50-year,1pct_min,100-year,1pct_plu,500-year
River Rch & RM=UNT023 IN NNOGR,Reach-1         ,7152
     681     979    1235    1143    1546    2091    2429
Boundary for River Rch & Prof#=UNT023 IN NNOGR,Reach-1         , 1
Up Type= 0
Dn Type= 3
Dn Slope=0.037
Boundary for River Rch & Prof#=UNT023 IN NNOGR,Reach-1         , 2
Up Type= 0
Dn Type= 3
Dn Slope=0.037
Boundary for River Rch & Prof#=UNT023 IN NNOGR,Reach-1         , 3
Up Type= 0
Dn Type= 3
Dn Slope=0.037
Boundary for River Rch & Prof#=UNT023 IN NNOGR,Reach-1         , 4
Up Type= 0
Dn Type= 3
Dn Slope=0.037
Boundary for River Rch & Prof#=UNT023 IN NNOGR,Reach-1         , 5
Up Type= 0
Dn Type= 3
Dn Slope=0.037
Boundary for River Rch & Prof#=UNT023 IN NNOGR,Reach-1         , 6
Up Type= 0
Dn Type= 3
Dn Slope=0.037
Boundary for River Rch & Prof#=UNT023 IN NNOGR,Reach-1         , 7
Up Type= 0
Dn Type= 3
Dn Slope=0.037
DSS Import GetInterval= 0
DSS Import GetPeak= 0
DSS Import FillOption= 0

--- UNT023 IN NNOGR.g01 (geometry) ---

Geom Title=Existing Conditions
Program Version=4.10

River Reach=UNT023 IN NNOGR ,Reach-1
Reach XY= 30
      2752314.55     10101816.84      2752395.57     10101728.67
      2752557.44     10101671.25      2752725.23     10101547.31
      2753247.47     10101331.33      2753402.03     10101171.34
      2753674.08     10100994.34      2754123.73     10100861.95
      2754329.51     10100726.39      2754617.21     10100689.59
      2755039.66     10100486.62      2755321.75     10100460.03
      2755392.43     10100358.36      2755593.87     10100301.84
      2755784.23     10100351.84      2756029.02     10100264.81
      2756318.93     10100273.28      2756563.49     10100227.54
      2756727.26     10100250.93      2756836.01     10100177.24
      2756862.35     10100045.66      2756911.86       10100007.
      2757212.85     10100072.27       2757431.7     10099809.98
      2757701.03     10099828.44      2757739.15     10099723.99
      2757864.96     10099627.15      2757990.64     10099437.71
      2758399.23     10099357.77      2758508.47     10099383.73

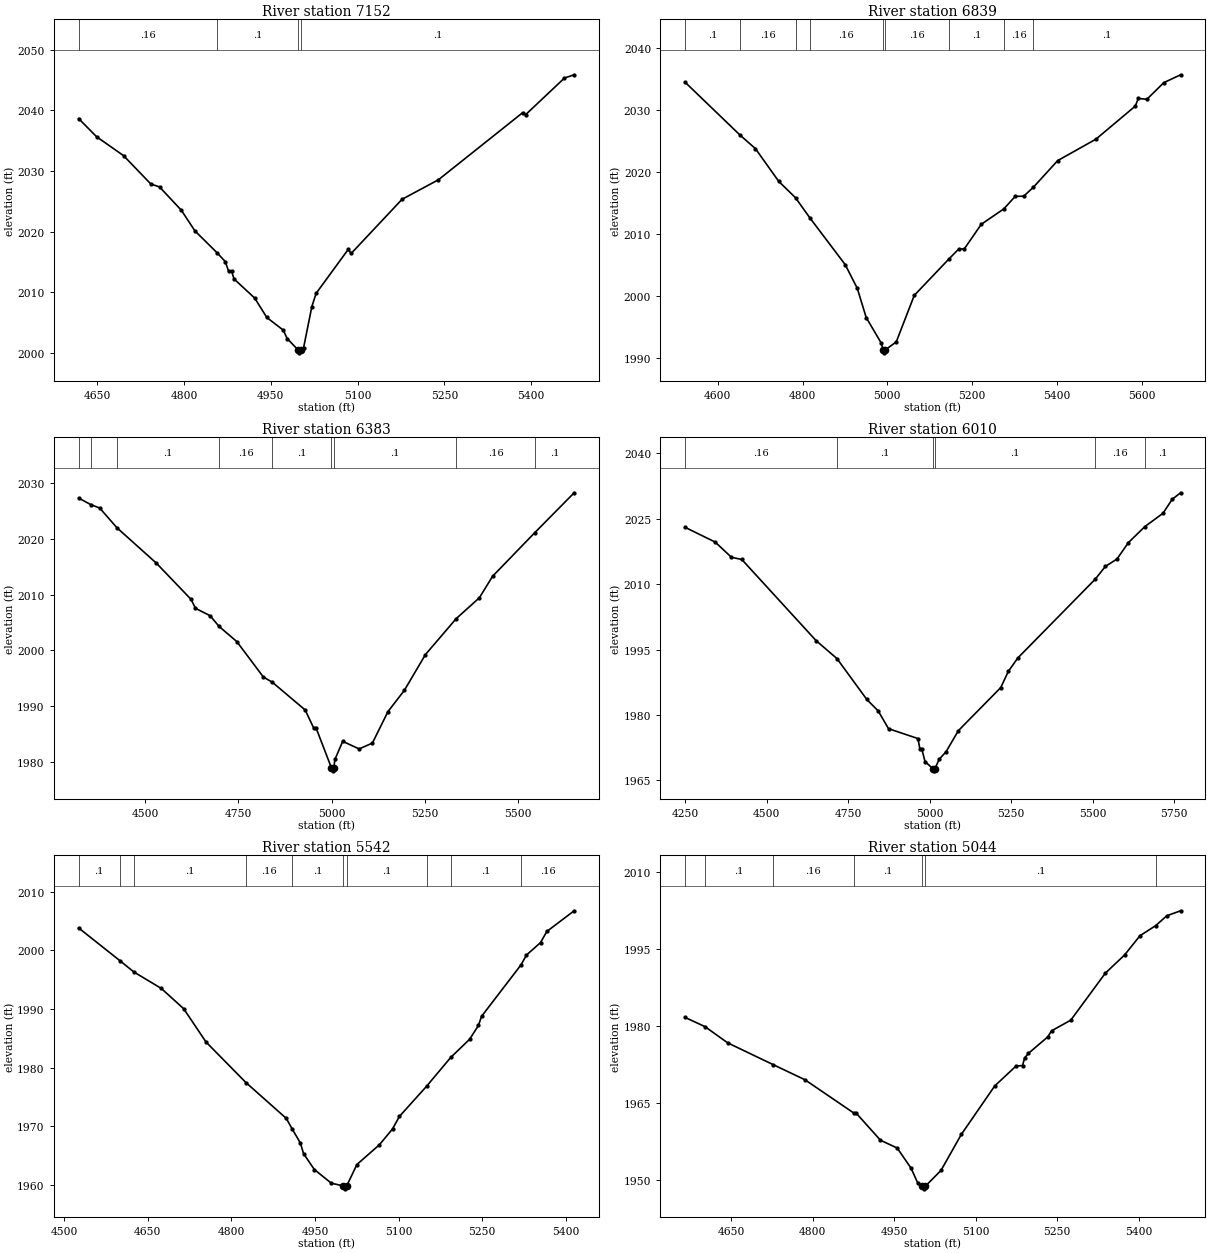
Type RM Length L Ch R = 1 ,7152    ,313,313,313
BEGIN DESCRIPTION:
UNT023 IN NNOGR 16.0
END DESCRIPTION:
XS GIS Cut Line= 4
      2752573.11     10102062.27      2752468.92     10101819.17
      2752345.22     10101706.32      2751921.68     10101734.41
#Sta/Elev= 30
    4618 2038.66    4649 2035.66  4695.6 2032.54  4742.8 2027.85  4757.8 2027.37
  4795.4 2023.53  4818.9 2020.12  4857.2  2016.5  4871.5 2015.03  4877.3 2013.41
  4882.5 2013.41  4886.5 2012.18  4922.3 2009.01  4943.2 2005.81  4971.6 2003.72
  4978.4 2002.33    4997 2000.47  4999.7 1999.97    5003 2000.47  5006.8 2000.83
    5021 2007.59  5028.4 2009.79    5084 2017.06    5089 2016.38    5177 2025.33
  5239.8 2028.55  5385.5 2039.64  5390.5  2039.3  5457.6 2045.35  5474.4 2045.89
#Mann= 4 ,-1 , 0
    4618     .16       0  4857.2      .1       0    4997     .07       0
    5003      .1       0
Bank Sta=4997,5003
XS Rating Curve= 0 ,0
Exp/Cntr=0.3,0.1

Type RM Length L Ch R = 1 ,6839    ,456,456,456
BEGIN DESCRIPTION:
Mapping XS 17c0c31a
END DESCRIPTION:
XS GIS Cut Line= 4
      2752755.38     10102012.28      2752803.12     10101734.53
      2752544.87     10101497.99      2752008.83     10101524.03
#Sta/Elev= 30
  4523.1 2034.49  4652.4 2025.99    4689 2023.79  4743.8 2018.53  4783.6 2015.87
  4817.1 2012.66  4900.9 2005.08  4929.2 2001.28  4950.2 1996.58    4986 1992.43
  4989.7 1991.39  4992.5 1990.89  4995.7 1991.39  5021.1 1992.65  5063.6 2000.15
  5145.7 2006.04  5168.5 2007.62  5181.6 2007.64  5221.6  2011.6  5274.7 2014.08
  5301.7  2016.1  5321.7 2016.13  5344.5 2017.57  5401.8 2021.86  5491.9 2025.31
  5584.8 2030.64    5592 2031.88  5612.1 2031.74  5652.1 2034.42  5691.8 2035.69
#Mann= 9 ,-1 , 0
  4523.1      .1       0  4652.4     .16       0  4783.6      .1       0
  4817.1     .16       0  4989.7     .07       0  4995.7     .16       0
  5145.7      .1       0  5274.7     .16       0  5344.5      .1       0
Bank Sta=4989.7,4995.7
XS Rating Curve= 0 ,0
Exp/Cntr=0.3,0.1

Type RM Length L Ch R = 1 ,6383    ,373,373,373
BEGIN DESCRIPTION:
UNT023 IN NNOGR 15.0
END DESCRIPTION:
XS GIS Cut Line= 3
      2753020.14      10102049.2      2753132.98     10101508.84
      2752677.78     10100878.06
#Sta/Elev= 30
  4321.1 2027.28  4353.5 2026.11  4377.8 2025.48  4423.9 2021.96  4529.5 2015.64
  4622.9 2009.14  4634.6 2007.55    4674 2006.22    4698  2004.3  4745.5  2001.6
    4817 1995.24  4840.9 1994.32  4929.2 1989.34  4952.5 1986.04  4958.7 1986.07
  4999.7 1978.96  5002.5 1978.46  5005.7 1978.96    5009 1980.51  5029.8 1983.74
    5074 1982.38  5109.5 1983.43  5151.3 1989.06  5195.4 1992.88  5251.9 1999.27
  5334.4  2005.7  5396.6 2009.43  5432.2 2013.29  5545.7 2021.11    5651 2028.22
#Mann= 9 ,-1 , 0
  4321.1      .1       0  4353.5     .16       0  4423.9      .1       0
    4698     .16       0  4840.9      .1       0  4999.7     .07       0
  5005.7      .1       0  5334.4     .16       0  5545.7      .1       0
Bank Sta=4999.7,5005.7
XS Rating Curve= 0 ,0
Exp/Cntr=0.3,0.1

Type RM Length L Ch R = 1 ,6010    ,468,468,468
BEGIN DESCRIPTION:
UNT023 IN NNOGR 14.0
END DESCRIPTION:
XS GIS Cut Line= 4
      2753777.53     10101827.88      2753504.08     10101302.68
      2753135.15       10101090.      2752778.35     10100737.53
#Sta/Elev= 30
  4250.3 2023.01  4342.6 2019.63  4392.5 2016.14  4424.1 2015.65    4652 1997.04
    4716 1992.93  4807.4 1983.57  4842.4 1980.93  4874.1 1976.86  4964.3  1974.6
  4970.3 1972.22  4976.1  1972.2  4986.1 1969.31  5010.4  1967.7  5013.1  1967.2
  5016.4  1967.7  5029.2 1969.83  5050.7  1971.6  5088.1  1976.4  5218.3 1986.29
  5241.4 1989.99  5270.3 1993.05  5508.2 2011.15  5539.1 2014.06  5574.4 2015.73
  5609.8 2019.52  5659.8 2023.16  5715.8 2026.24  5744.1 2029.46  5769.8 2030.93
#Mann= 6 ,-1 , 0
  4250.3     .16       0    4716      .1       0  5010.4     .07       0
  5016.4      .1       0  5508.2     .16       0  5659.8      .1       0
Bank Sta=5010.4,5016.4
XS Rating Curve= 0 ,0
Exp/Cntr=0.3,0.1

Type RM Length L Ch R = 1 ,5542    ,498,498,498
BEGIN DESCRIPTION:
UNT023 IN NNOGR 12.0
END DESCRIPTION:
XS GIS Cut Line= 3
      2753825.26     10101441.55      2753797.04     10101113.87
      2753604.31     10100587.65
#Sta/Elev= 30
  4525.8 2003.83  4599.5 1998.28  4624.7 1996.34  4674.2 1993.51  4714.3 1990.06
  4754.5 1984.37    4826 1977.47  4898.5 1971.35    4909 1969.55  4923.7 1967.17
  4929.4 1965.36  4948.8 1962.63  4979.4  1960.3  5000.9 1959.84  5003.7 1959.34
  5006.9 1959.84  5025.2 1963.49  5065.6 1966.86  5089.1 1969.55  5101.4 1971.68
  5150.1 1976.82  5193.5 1981.74  5227.6 1984.86  5243.3 1987.21  5248.9 1988.76
  5319.6 1997.52  5329.5 1999.21  5354.7 2001.33    5366 2003.23  5415.1 2006.76
#Mann= 10 ,-1 , 0
  4525.8      .1       0  4599.5     .16       0  4624.7      .1       0
    4826     .16       0    4909      .1       0  5000.9     .07       0
  5006.9      .1       0  5150.1     .16       0  5193.5      .1       0
  5319.6     .16       0
Bank Sta=5000.9,5006.9
XS Rating Curve= 0 ,0
Exp/Cntr=0.3,0.1

Type RM Length L Ch R = 1 ,5044    ,524,524,524
BEGIN DESCRIPTION:
UNT023 IN NNOGR 11.0
END DESCRIPTION:
XS GIS Cut Line= 4
      2754194.18     10101231.08      2754248.43     10100920.73
      2754146.44     10100634.27       2753935.9     10100430.25
#Sta/Elev= 30
  4564.8 1981.68  4601.3  1979.9  4643.3 1976.72  4726.9 1972.48  4785.4 1969.53
  4875.1 1963.06  4879.9    1963  4924.5 1957.73  4955.3 1956.21  4980.8 1952.28
  4993.4 1949.32    5001 1948.75  5003.8 1948.25    5007 1948.75  5035.9 1951.84
  5073.3 1958.86  5134.9 1968.33  5173.9 1972.19    5186  1972.3    5190  1973.8
  5196.9 1974.68  5232.4 1977.88  5239.4 1979.07  5274.9 1981.16  5338.4 1990.31
  5373.9 1993.87  5402.2 1997.62  5431.3  1999.6  5451.6 2001.52  5477.1 2002.49
#Mann= 7 ,-1 , 0
  4564.8     .16       0  4601.3      .1       0  4726.9     .16       0
  4875.1      .1       0    5001     .07       0    5007      .1       0
  5431.3     .16       0
Bank Sta=5001,5007
XS Rating Curve= 0 ,0
Exp/Cntr=0.3,0.1

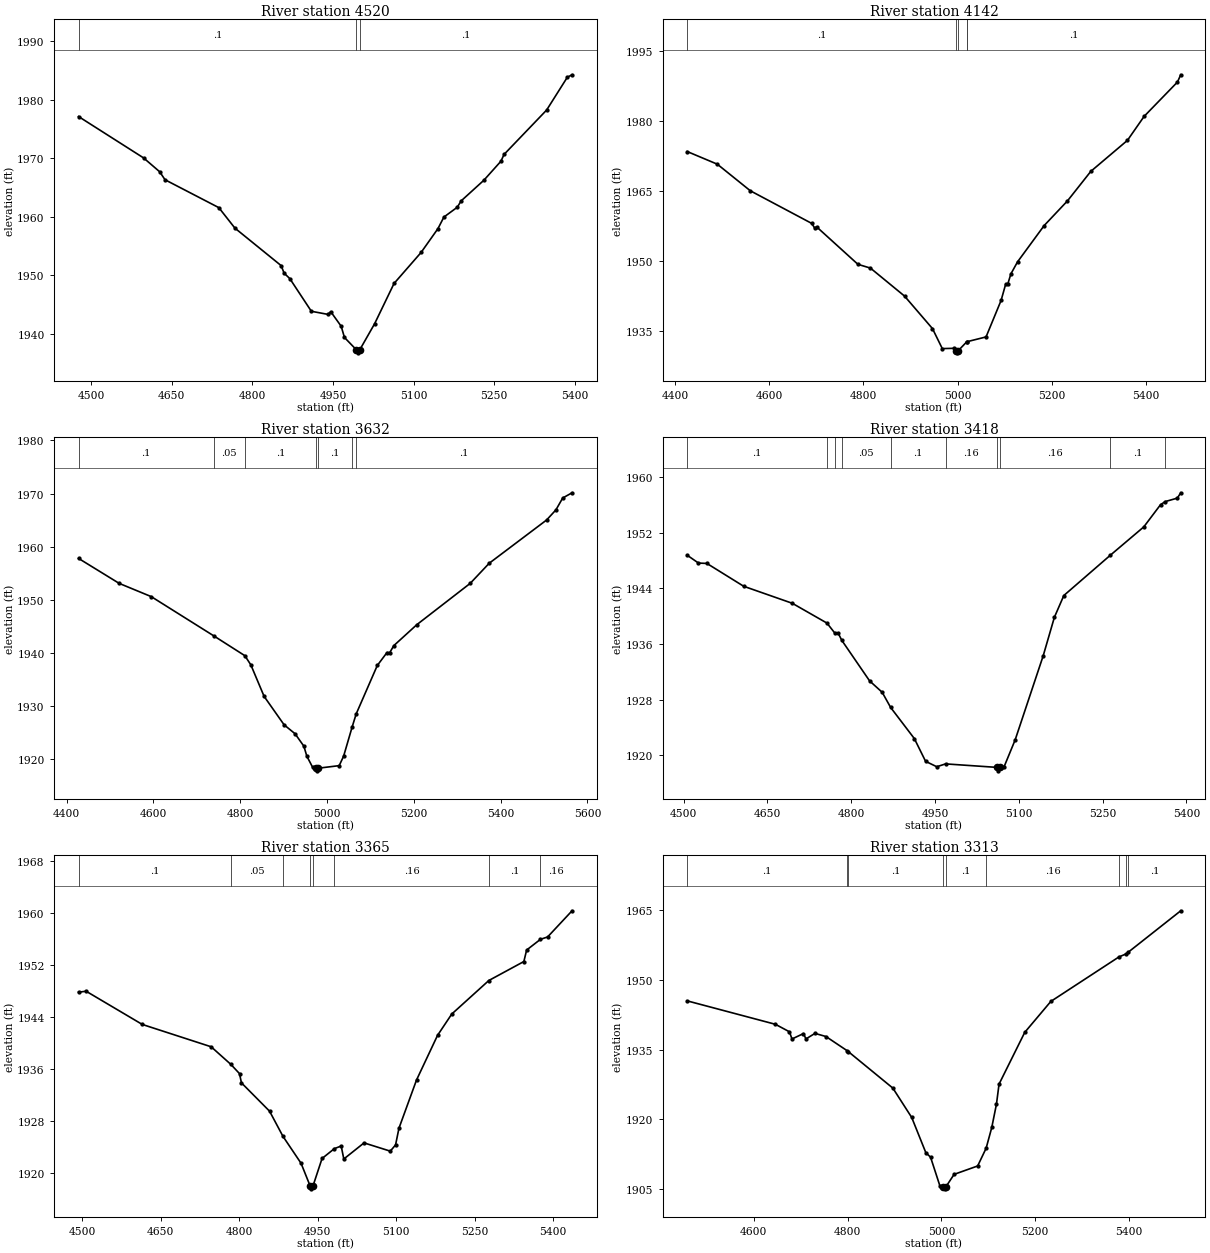
Type RM Length L Ch R = 1 ,4520    ,378,378,378
BEGIN DESCRIPTION:
UNT023 IN NNOGR 10.0
END DESCRIPTION:
XS GIS Cut Line= 3
      2754764.93      10101174.6      2754749.74     10100816.57
      2754560.93      10100289.2
#Sta/Elev= 30
  4476.6 1977.14  4597.6 1970.06  4627.6 1967.69  4637.6 1966.32  4737.7 1961.55
  4767.7 1958.04  4853.7 1951.63  4859.2 1950.34  4869.8 1949.41  4909.9 1943.82
  4940.7 1943.29    4946 1943.75  4965.4 1941.26  4971.5 1939.34  4993.9 1937.21
  4996.7 1936.71  4999.9 1937.21  5027.7  1941.7  5063.8 1948.58  5114.1 1953.88
  5145.5 1957.96  5156.6 1959.94  5181.5 1961.62  5188.5 1962.69    5231 1966.24
  5262.8  1969.5  5268.5 1970.65  5347.8 1978.25  5386.3 1983.86  5395.1 1984.28
#Mann= 3 ,-1 , 0
  4476.6      .1       0  4993.9     .07       0  4999.9      .1       0
Bank Sta=4993.9,4999.9
XS Rating Curve= 0 ,0
Exp/Cntr=0.3,0.1

Type RM Length L Ch R = 1 ,4142    ,510,510,510
BEGIN DESCRIPTION:
UNT023 IN NNOGR 9.0
END DESCRIPTION:
XS GIS Cut Line= 4
      2755055.72     10101057.46       2755079.6     10100692.87
      2754992.79     10100393.39      2754732.97     10100129.24
#Sta/Elev= 30
    4426 1973.54  4489.9 1970.83    4560 1965.13  4690.3 1958.14  4696.4 1957.17
  4701.4 1957.34  4788.4 1949.37    4815 1948.56  4887.3 1942.57  4946.7 1935.59
  4967.5 1931.31  4993.3 1931.37  4995.7  1930.9  4998.5  1930.4  5001.7  1930.9
  5019.3 1932.75  5019.7 1932.78  5060.4 1933.81  5092.4 1941.65    5102  1945.1
  5106.4  1945.1  5113.1 1947.31  5127.2 1949.89  5183.8 1957.68  5233.3 1962.97
  5282.8 1969.29  5360.6 1975.94    5396 1981.08  5466.7 1988.43  5473.7 1989.99
#Mann= 5 ,-1 , 0
    4426      .1       0  4995.7     .07       0  5001.7      .1       0
  5019.3     .05       0  5019.7      .1       0
Bank Sta=4995.7,5001.7
XS Rating Curve= 0 ,0
Exp/Cntr=0.3,0.1

Type RM Length L Ch R = 1 ,3632    ,214,214,214
BEGIN DESCRIPTION:
UNT023 IN NNOGR 8.0
END DESCRIPTION:
XS GIS Cut Line= 4
      2755396.44     10100892.52       2755500.6     10100582.19
      2755428.99     10100202.42      2755063.84     10099988.51
#Sta/Elev= 30
  4427.7 1957.79  4521.4 1953.08  4595.2 1950.59  4739.4 1943.19  4810.9 1939.46
  4824.7 1937.73  4855.2  1931.8  4901.3 1926.44  4926.5 1924.76  4946.8 1922.42
  4953.7 1920.52  4967.2 1918.41  4974.4 1918.27  4977.1 1917.77  4980.4 1918.27
  5028.2 1918.75  5038.4 1920.53    5058 1926.02  5067.4  1928.5    5116 1937.62
  5138.3 1940.05  5144.7 1940.05  5154.1 1941.36    5207  1945.3  5330.1 1953.09
  5373.9 1956.88    5506 1965.02  5527.5 1966.93  5543.2 1969.17  5564.7 1970.15
#Mann= 7 ,-1 , 0
  4427.7      .1       0  4739.4     .05       0  4810.9      .1       0
  4974.4     .07       0  4980.4      .1       0    5058     .16       0
  5067.4      .1       0
Bank Sta=4974.4,4980.4
XS Rating Curve= 0 ,0
Exp/Cntr=0.3,0.1

Type RM Length L Ch R = 1 ,3418    ,53,53,53
BEGIN DESCRIPTION:
Mapping XS 77438580
END DESCRIPTION:
XS GIS Cut Line= 4
      2755534.78     10100775.92      2755649.34     10100515.55
      2755675.38     10100124.92      2755675.38     10099917.68
#Sta/Elev= 30
  4506.6 1948.78  4526.8 1947.65  4541.8  1947.6  4607.7 1944.31  4694.7 1941.86
  4756.7 1939.01  4771.1 1937.54  4776.6 1937.58  4783.3 1936.52    4833 1930.69
  4855.5 1929.05  4870.7 1926.86  4913.1 1922.38  4933.2 1919.11  4953.2 1918.33
    4969 1918.74  5060.5 1918.24  5063.2 1917.74  5066.5 1918.24  5073.5 1918.29
  5093.5  1922.2  5143.7 1934.31  5163.7 1939.85  5180.6 1942.98  5263.8 1948.78
  5323.7 1952.86  5353.7 1956.06  5362.2 1956.51  5383.7    1957  5389.8 1957.77
#Mann= 10 ,-1 , 0
  4506.6      .1       0  4756.7     .05       0  4771.1     .16       0
  4783.3     .05       0  4870.7      .1       0    4969     .16       0
  5060.5     .07       0  5066.5     .16       0  5263.8      .1       0
  5362.2     .16       0
Bank Sta=5060.5,5066.5
XS Rating Curve= 0 ,0
Exp/Cntr=0.3,0.1

Type RM Length L Ch R = 1 ,3365    ,52,52,52
BEGIN DESCRIPTION:
Mapping XS caccc349
END DESCRIPTION:
XS GIS Cut Line= 4
      2755581.64      10100807.2      2755696.22     10100515.55
      2755732.68     10100114.51      2755717.17     10099887.08
#Sta/Elev= 30
  4492.5 1947.75    4507  1947.9  4614.4 1942.79  4746.2 1939.35    4784 1936.63
  4800.4 1935.22  4804.1  1933.8  4857.9 1929.44  4883.5 1925.57  4918.1 1921.43
  4935.2 1917.99    4938 1917.49  4941.2 1917.99  4958.3 1922.16  4981.9 1923.68
  4994.9 1924.08  4999.9 1922.08  5038.6 1924.56  5088.8 1923.29  5098.9 1924.25
  5105.4 1926.82    5139 1934.24  5179.2 1941.11  5206.4 1944.39  5277.3 1949.55
  5344.3 1952.47  5349.6 1954.24  5376.1 1955.89  5389.7 1956.25  5436.5 1960.28
#Mann= 8 ,-1 , 0
  4492.5      .1       0    4784     .05       0  4883.5      .1       0
  4935.2     .07       0  4941.2      .1       0  4981.9     .16       0
  5277.3      .1       0  5376.1     .16       0
Bank Sta=4935.2,4941.2
XS Rating Curve= 0 ,0
Exp/Cntr=0.3,0.1

Type RM Length L Ch R = 1 ,3313    ,375,375,375
BEGIN DESCRIPTION:
Mapping XS db04bbd5
END DESCRIPTION:
XS GIS Cut Line= 4
       2755623.3      10100859.3      2755743.09     10100552.01
      2755784.76     10100093.67      2755753.51     10099833.28
#Sta/Elev= 30
  4457.9 1945.46    4646 1940.43  4675.9 1938.82  4681.3 1937.28  4705.8 1938.44
  4711.1 1937.29  4730.3 1938.48  4753.7 1937.81  4799.4 1934.73  4801.5 1934.56
  4896.4 1926.73  4936.6 1920.43  4966.7 1912.87  4976.8  1911.9  4996.8 1905.71
  5003.9 1905.61  5006.6 1905.11  5009.9 1905.61    5027 1908.22  5077.2 1910.02
  5095.3 1913.84  5107.3 1918.29  5117.3  1923.3  5122.8 1927.59  5177.6  1938.7
  5233.2 1945.34  5378.4 1954.89  5393.4 1955.53  5398.8 1955.95  5510.2  1964.8
#Mann= 9 ,-1 , 0
  4457.9      .1       0  4799.4     .16       0  4801.5      .1       0
  5003.9     .07       0  5009.9      .1       0  5095.3     .16       0
  5378.4      .1       0  5393.4     .16       0  5398.8      .1       0
Bank Sta=5003.9,5009.9
XS Rating Curve= 0 ,0
Exp/Cntr=0.3,0.1

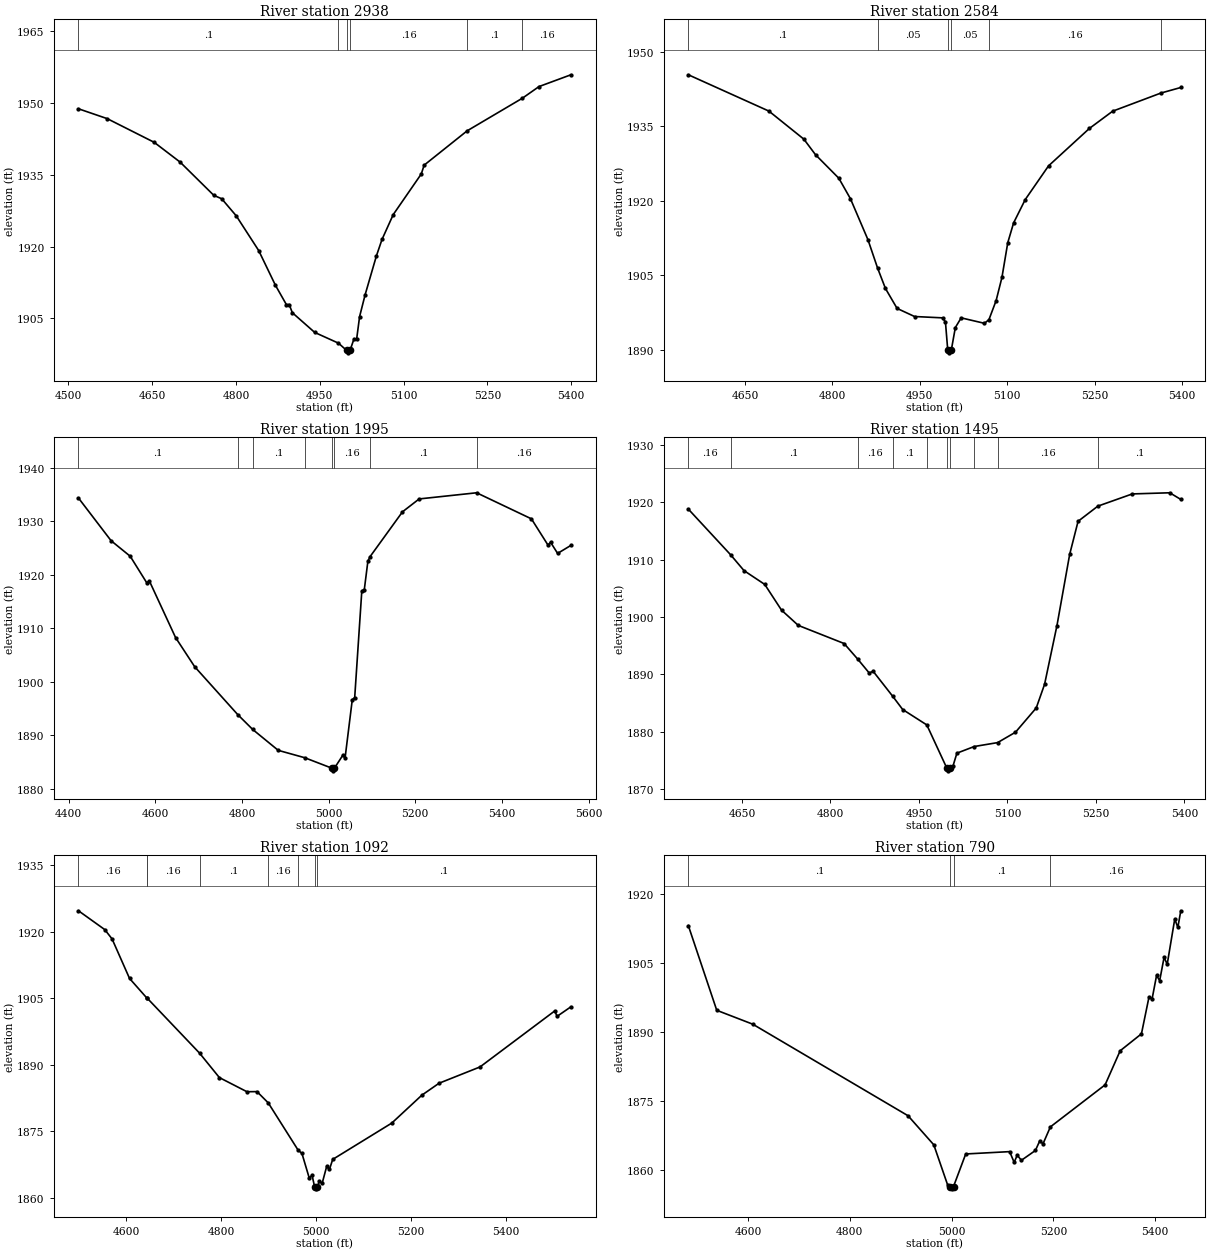
Type RM Length L Ch R = 1 ,2938    ,354,354,354
BEGIN DESCRIPTION:
UNT023 IN NNOGR 7.0
END DESCRIPTION:
XS GIS Cut Line= 2
      2756154.55     10100755.09      2756081.79      10099876.8
#Sta/Elev= 30
  4518.1 1948.75  4569.6 1946.69  4653.6 1941.75  4700.1 1937.61  4760.3 1930.68
  4774.4 1929.97  4800.4 1926.41  4840.6 1919.16  4870.7 1911.88  4890.2 1907.87
  4895.2 1907.89  4900.8 1906.18  4940.9 1902.06  4983.4 1899.82  4998.1  1898.3
  5000.9  1897.8  5004.1  1898.3  5010.9 1900.63  5015.9 1900.64  5021.2 1905.37
  5031.2 1909.97  5051.3 1918.04  5061.3 1921.47  5081.4 1926.66  5131.6 1935.14
  5136.7 1936.98  5213.7 1944.15  5312.7 1950.97  5342.3 1953.39  5399.4 1955.85
#Mann= 6 ,-1 , 0
  4518.1      .1       0  4983.4     .16       0  4998.1     .07       0
  5004.1     .16       0  5213.7      .1       0  5312.7     .16       0
Bank Sta=4998.1,5004.1
XS Rating Curve= 0 ,0
Exp/Cntr=0.3,0.1

Type RM Length L Ch R = 1 ,2584    ,589,589,589
BEGIN DESCRIPTION:
UNT023 IN NNOGR 5.0
END DESCRIPTION:
XS GIS Cut Line= 2
      2756467.07     10100692.03      2756460.14     10099846.75
#Sta/Elev= 30
  4552.6 1945.37  4690.9 1938.06  4750.9 1932.41  4770.9 1929.28  4810.9 1924.55
  4830.9 1920.41  4860.9 1912.18  4877.4 1906.48  4890.9 1902.37  4910.9 1898.35
  4940.9 1896.72  4988.9 1896.45  4993.9 1895.64  4997.9 1889.91  5000.7 1889.41
  5003.9 1889.91  5010.9  1894.5  5020.9 1896.45  5060.9 1895.35  5068.6  1896.1
  5080.9 1899.92  5090.9 1904.59  5100.9 1911.58  5110.9 1915.56  5130.9 1920.26
  5170.9 1927.04  5240.9 1934.56  5280.9 1938.04  5363.7 1941.69  5397.9 1942.81
#Mann= 6 ,-1 , 0
  4552.6      .1       0  4877.4     .05       0  4997.9    .035       0
  5003.9     .05       0  5068.6     .16       0  5363.7      .1       0
Bank Sta=4997.9,5003.9
XS Rating Curve= 0 ,0
Exp/Cntr=0.3,0.1

Type RM Length L Ch R = 1 ,1995    ,500,500,500
BEGIN DESCRIPTION:
UNT023 IN NNOGR 4.0
END DESCRIPTION:
XS GIS Cut Line= 2
      2757168.45     10100525.39      2756640.76      10099518.6
#Sta/Elev= 30
  4422.5 1934.35  4497.8 1926.37  4541.9 1923.47  4580.4 1918.47  4586.1 1918.86
  4646.6 1908.28  4690.7 1902.83  4790.1 1893.88  4824.7  1891.1  4883.6  1887.2
  4944.8 1885.82  5007.3 1883.87  5010.1 1883.37  5013.3 1883.87  5032.4 1886.25
    5038 1885.85  5054.5 1896.66  5060.1 1897.06  5076.5 1916.99  5082.2 1917.18
  5090.5 1922.52  5095.7 1923.41  5170.4 1931.77  5208.9 1934.18  5341.5 1935.33
    5468 1930.46  5506.4 1925.54  5512.1  1926.1  5528.5    1924  5559.2  1925.5
#Mann= 8 ,-1 , 0
  4422.5      .1       0  4790.1     .16       0  4824.7      .1       0
  4944.8     .16       0  5007.3     .07       0  5013.3     .16       0
  5095.7      .1       0  5341.5     .16       0
Bank Sta=5007.3,5013.3
XS Rating Curve= 0 ,0
Exp/Cntr=0.3,0.1

Type RM Length L Ch R = 1 ,1495    ,403,403,403
BEGIN DESCRIPTION:
UNT023 IN NNOGR 3.0
END DESCRIPTION:
XS GIS Cut Line= 2
      2757619.83     10100275.39      2757058.01     10099658.07
#Sta/Elev= 30
  4559.2 1918.81  4630.7 1910.87  4653.6 1908.09  4688.7 1905.69  4717.1 1901.21
  4745.5 1898.55  4823.2 1895.39  4846.7 1892.62  4865.7 1890.26  4872.5 1890.54
  4905.4 1886.22  4922.5 1883.89  4963.4  1881.2  4997.2  1873.7  4999.9  1873.2
  5003.2  1873.7  5007.6 1873.98  5014.4 1876.28  5043.8 1877.44  5083.4 1878.12
  5113.7 1879.93  5148.9 1884.16    5163 1888.28    5184 1898.52  5205.6 1910.95
  5219.8 1916.69  5253.3 1919.33  5311.7 1921.46  5375.2 1921.66  5393.9  1920.5
#Mann= 10 ,-1 , 0
  4559.2     .16       0  4630.7      .1       0  4846.7     .16       0
  4905.4      .1       0  4963.4     .16       0  4997.2     .07       0
  5003.2     .16       0  5043.8      .1       0  5083.4     .16       0
  5253.3      .1       0
Bank Sta=4997.2,5003.2
XS Rating Curve= 0 ,0
Exp/Cntr=0.3,0.1

Type RM Length L Ch R = 1 ,1092    ,302,302,302
BEGIN DESCRIPTION:
Mapping XS 3a73e0e8
END DESCRIPTION:
XS GIS Cut Line= 3
      2757909.77     10100260.36      2757545.18     10099666.59
       2757206.6     10099624.92
#Sta/Elev= 30
  4499.5  1924.7  4554.9 1920.46  4570.3 1918.36  4607.1 1909.46  4643.9 1905.01
  4644.3 1905.02  4754.7 1892.63  4796.5 1887.12  4854.5 1883.94  4875.8 1883.96
  4899.5 1881.42  4962.3  1870.8  4970.5 1870.03  4985.9 1864.49  4991.8 1865.12
  4997.1 1862.56  4999.9 1862.06  5003.1 1862.56  5007.2 1863.78  5013.1 1863.31
  5022.6  1867.1  5028.5 1866.45  5035.3 1868.69  5159.9 1876.88  5223.2 1883.16
  5259.5 1885.85  5345.8 1889.52  5503.2 1902.13  5508.3 1900.92  5537.4 1903.07
#Mann= 8 ,-1 , 0
  4499.5     .16       0  4643.9      .1       0  4644.3     .16       0
  4754.7      .1       0  4899.5     .16       0  4962.3      .1       0
  4997.1     .07       0  5003.1      .1       0
Bank Sta=4997.1,5003.1
XS Rating Curve= 0 ,0
Exp/Cntr=0.3,0.1

Type RM Length L Ch R = 1 ,790     ,405,405,405
BEGIN DESCRIPTION:
UNT023 IN NNOGR 2.0
END DESCRIPTION:
XS GIS Cut Line= 3
      2758034.76     10100109.32      2758013.93     10099885.34
      2757587.81     10099277.34
#Sta/Elev= 30
  4482.9 1913.19  4538.7 1894.74  4609.5 1891.71  4914.5 1871.76  4965.1 1865.42
  4992.1 1856.73  4997.8 1856.33  5000.6 1855.83  5003.8 1856.33  5027.8 1863.43
  5114.1 1863.94  5122.9 1861.61    5129 1863.15  5137.2 1862.05  5164.7 1864.19
  5173.4 1866.33  5179.5 1865.61  5194.1 1869.33  5301.6 1878.49  5331.2 1885.92
    5373 1889.61  5387.9 1897.67    5394 1897.26  5402.7 1902.33  5408.8  1901.2
  5417.5  1906.3  5423.6 1904.76  5438.4 1914.62  5444.5 1912.81  5450.3 1916.43
#Mann= 4 ,-1 , 0
  4482.9      .1       0  4997.8     .07       0  5003.8      .1       0
  5194.1     .16       0
Bank Sta=4997.8,5003.8
XS Rating Curve= 0 ,0
Exp/Cntr=0.3,0.1

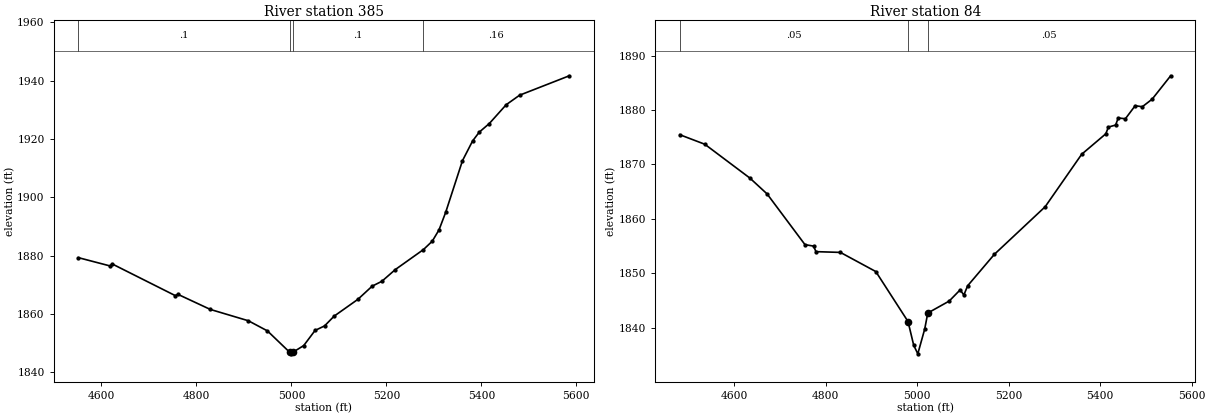
Type RM Length L Ch R = 1 ,385     ,301,301,301
BEGIN DESCRIPTION:
Mapping XS 5febc90a
END DESCRIPTION:
XS GIS Cut Line= 3
      2758168.74     10099850.74      2758121.87     10099220.56
      2757836.41     10098937.69
#Sta/Elev= 30
  4551.4 1879.32  4618.1 1876.48  4623.1 1877.12  4755.7 1866.29  4760.7 1866.77
  4829.2 1861.58  4909.4 1857.69  4949.5 1854.22  4996.6 1846.86  4999.4 1846.36
  5002.6 1846.86  5025.9 1849.19  5049.8 1854.38  5069.8 1855.93  5089.9 1859.27
    5140 1865.04  5170.1 1869.56  5190.5 1871.22  5218.8 1875.24  5278.1  1882.1
  5296.6 1884.96  5310.8 1888.83  5324.9 1894.87  5360.2 1912.55  5381.5  1919.3
  5395.6 1922.34  5416.8 1925.29  5452.2 1931.72  5480.5 1934.99  5585.2 1941.65
#Mann= 4 ,-1 , 0
  4551.4      .1       0  4996.6     .07       0  5002.6      .1       0
  5278.1     .16       0
Bank Sta=4996.6,5002.6
XS Rating Curve= 0 ,0
Exp/Cntr=0.3,0.1

Type RM Length L Ch R = 1 ,84      ,0,0,0
BEGIN DESCRIPTION:
UNT023 IN NNOGR 1.0
END DESCRIPTION:
XS GIS Cut Line= 3
      2758231.24     10099845.58      2758465.62     10099272.64
      2758233.87     10098882.04
#Sta/Elev= 30
  4480.9 1875.47  4535.6 1873.72  4634.2  1867.5  4671.8 1864.59  4754.6 1855.27
  4773.3    1855  4778.7 1853.98  4832.1 1853.84  4909.5 1850.32  4979.9 1841.14
  4992.3 1836.79  5001.3  1835.2  5016.4 1839.76  5023.1  1842.7  5069.8 1844.89
  5093.8 1846.95    5102 1846.02  5110.3 1847.71  5168.6 1853.48  5279.7 1862.23
  5359.6 1871.88  5412.2 1875.63  5418.1 1876.88  5433.7 1877.24  5439.5 1878.55
  5455.1  1878.4  5476.5  1880.8  5492.1 1880.61  5513.6    1882  5554.1  1886.3
#Mann= 3 , 0 , 0
  4480.9     .05       0  4979.9     .03       0  5023.1     .05       0
Bank Sta=4979.9,5023.1
XS Rating Curve= 0 ,0
Exp/Cntr=0.3,0.1

Chan Stop Cuts=-1
Use User Specified Reach Order=0
Composite Channel Slope=5