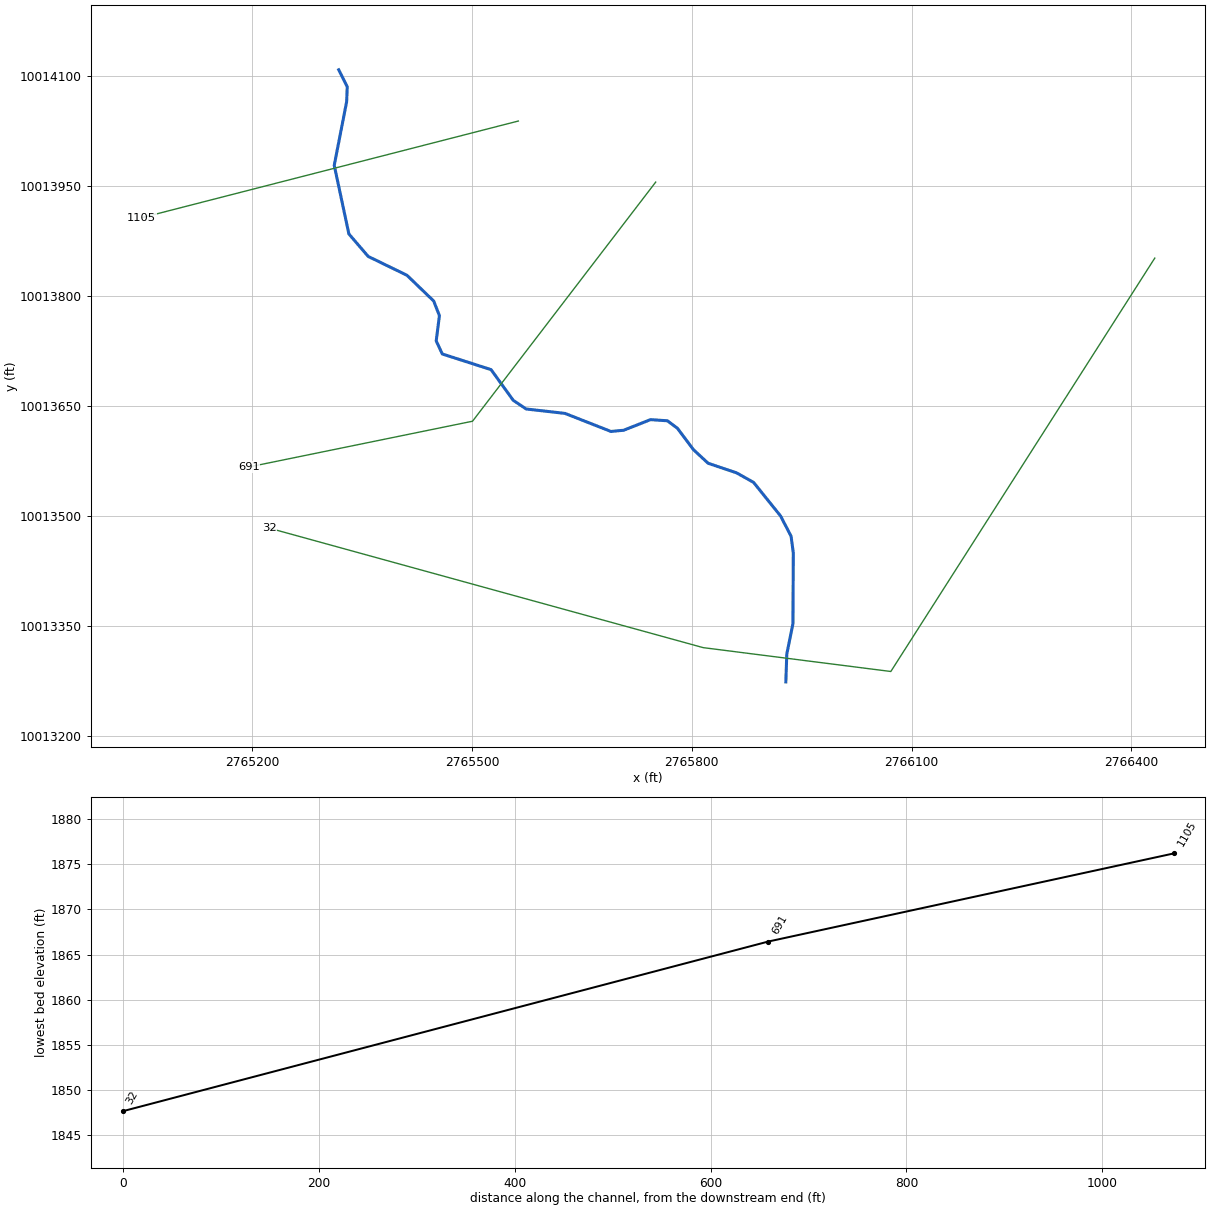
--- UNT023 IN SNOGR.prj (project) ---

Proj Title=UNT023 IN SNOGR Base Level Engineering
Current Plan=p01
Default Exp/Contr=0.3,0.1
English Units
Geom File=g01
Flow File=f01
Plan File=p01
Y Axis Title=Elevation
X Axis Title(PF)=Main Channel Distance
X Axis Title(XS)=Station
BEGIN DESCRIPTION:
UNT023 IN SNOGR
END DESCRIPTION:
DSS Export Rating Curves= 0
DSS Export Rating Curve Sorted= 0
DSS Export Volume Flow Curves= 0
DXF OffsetX= 0
DXF OffsetY= 0
DXF ScaleX= 1
DXF ScaleY= 10

--- UNT023 IN SNOGR.p01 (plan) ---

Plan Title=Multiple Run
Short Identifier=Multiple
Geom File=g01
Flow File=f01
Subcritical Flow
K Sum by GR= 0
Std Step Tol= 0.01
Critical Tol= 0.01
Num of Std Step Trials= 20
Max Error Tol= 0.3
Flow Tol Ratio= 0.001
Split Flow NTrial= 30
Split Flow Tol= 0.02
Split Flow Ratio= 0.02
Log Output Level= 0
Friction Slope Method= 1
Unsteady Friction Slope Method= 2
Unsteady Bridges Friction Slope Method= 1
Parabolic Critical Depth
Global Vel Dist=  1 , 1 , 1
Global Log Level= 0
CheckData=True
Encroach Param= -1, 0, 0, 0
BEGIN DESCRIPTION:
Multiple Run
END DESCRIPTION:

--- UNT023 IN SNOGR.f01 (steady flow) ---

Flow Title=Multiple
Program Version=4.10
Number of Profiles= 7
Profile Names=10-year,25-year,50-year,1pct_min,100-year,1pct_plu,500-year
River Rch & RM=UNT023 IN SNOGR,Reach-1         ,1105
     233     312     376     333     450     609     647
River Rch & RM=UNT023 IN SNOGR,Reach-1         ,32
     912    1321    1676    1555    2103    2844    3326
Boundary for River Rch & Prof#=UNT023 IN SNOGR,Reach-1         , 1
Up Type= 0
Dn Type= 3
Dn Slope=0.005
Boundary for River Rch & Prof#=UNT023 IN SNOGR,Reach-1         , 2
Up Type= 0
Dn Type= 3
Dn Slope=0.005
Boundary for River Rch & Prof#=UNT023 IN SNOGR,Reach-1         , 3
Up Type= 0
Dn Type= 3
Dn Slope=0.005
Boundary for River Rch & Prof#=UNT023 IN SNOGR,Reach-1         , 4
Up Type= 0
Dn Type= 3
Dn Slope=0.005
Boundary for River Rch & Prof#=UNT023 IN SNOGR,Reach-1         , 5
Up Type= 0
Dn Type= 3
Dn Slope=0.005
Boundary for River Rch & Prof#=UNT023 IN SNOGR,Reach-1         , 6
Up Type= 0
Dn Type= 3
Dn Slope=0.005
Boundary for River Rch & Prof#=UNT023 IN SNOGR,Reach-1         , 7
Up Type= 0
Dn Type= 3
Dn Slope=0.005
DSS Import GetInterval= 0
DSS Import GetPeak= 0
DSS Import FillOption= 0

--- UNT023 IN SNOGR.g01 (geometry) ---

Geom Title=Existing Conditions
Program Version=4.10

River Reach=UNT023 IN SNOGR ,Reach-1
Reach XY= 30
       2765318.2     10014109.09      2765329.84     10014086.04
      2765329.05     10014065.72      2765312.09     10013978.78
      2765332.09     10013885.08      2765358.41     10013854.43
      2765411.33     10013828.69      2765447.84     10013793.53
      2765455.66     10013773.54      2765451.26     10013739.04
      2765459.64     10013721.25      2765526.16     10013699.89
      2765556.45     10013657.96      2765574.05      10013646.2
      2765627.06     10013640.16      2765689.84      10013615.5
      2765707.25     10013617.21      2765743.79     10013631.66
      2765766.78      10013630.1      2765780.46     10013619.94
      2765802.26     10013590.76      2765822.44     10013572.09
      2765861.31       10013559.      2765884.44     10013545.98
      2765921.21     10013500.27      2765935.61     10013472.58
      2765938.67     10013449.68      2765938.16      10013353.2
      2765929.76      10013311.6      2765928.47     10013273.73

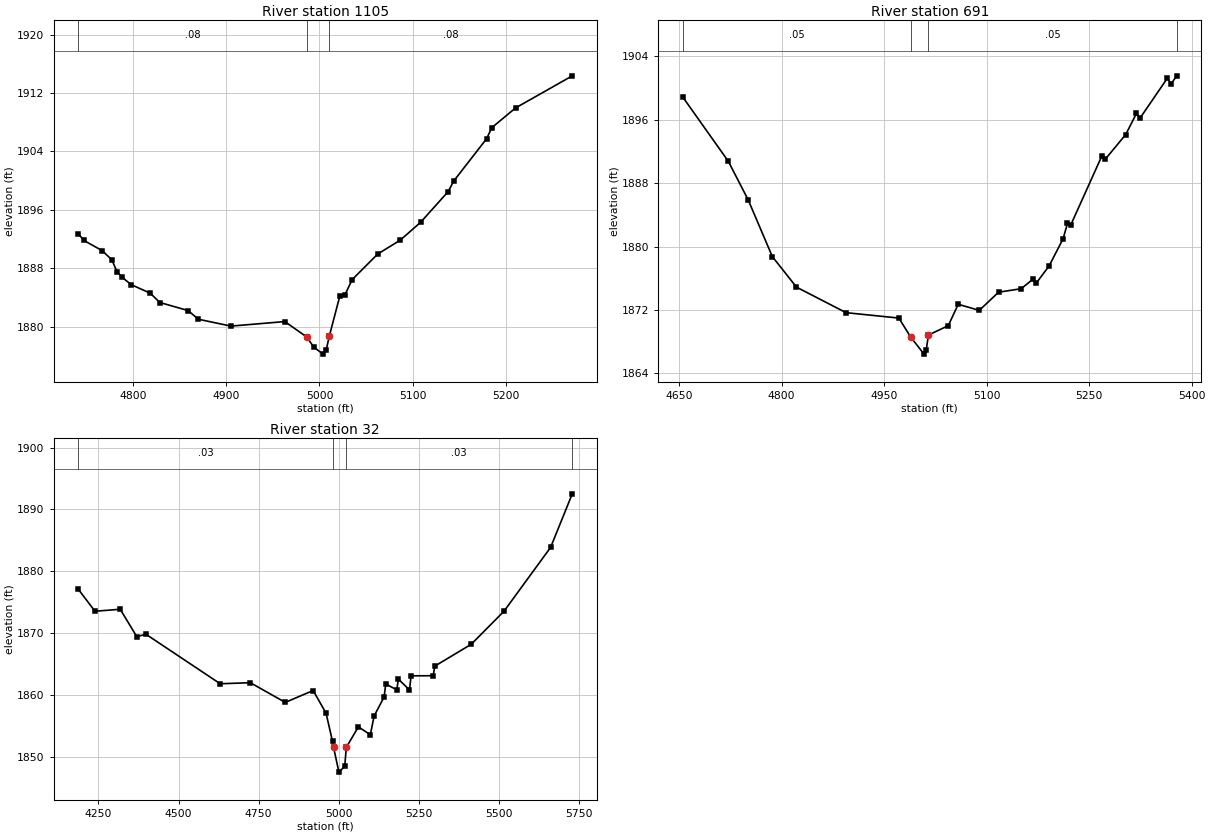
Type RM Length L Ch R = 1 ,1105    ,414,414,414
BEGIN DESCRIPTION:
UNT023 IN SNOGR 2.0
END DESCRIPTION:
XS GIS Cut Line= 2
      2765563.39     10014039.22      2765049.46     10013907.27
#Sta/Elev= 30
  4740.9 1892.74    4747  1891.8  4766.6 1890.41    4777 1889.15  4782.6 1887.51
  4787.8 1886.79  4797.6 1885.76  4818.2 1884.58  4828.6  1883.3  4858.9  1882.2
  4869.9 1881.01  4904.9 1880.07  4962.8 1880.69  4986.4 1878.57  4993.8  1877.2
  5003.8 1876.23  5007.1 1876.73 5010.46 1878.65    5022 1884.26  5027.1 1884.29
  5035.1 1886.44  5062.7 1889.96  5086.7 1891.84  5108.6 1894.29  5138.3 1898.51
  5144.2 1899.95  5179.6 1905.76    5185 1907.25  5210.6 1909.96  5271.5 1914.36
#Mann= 3 , 0 , 0
  4740.9     .08       0  4986.4     .05       0 5010.46     .08       0
Bank Sta=4986.4,5010.46
XS Rating Curve= 0 ,0
Exp/Cntr=0.3,0.1

Type RM Length L Ch R = 1 ,691     ,659,659,659
BEGIN DESCRIPTION:
Mapping XS 4511c723
END DESCRIPTION:
XS GIS Cut Line= 3
      2765750.85     10013955.89      2765500.84     10013629.49
      2765195.32     10013566.99
#Sta/Elev= 30
  4655.2 1898.88  4721.9 1890.77    4751  1885.9  4786.3 1878.75  4821.7 1874.89
  4894.3 1871.67  4971.5 1870.99 4988.55 1868.63  5008.3 1866.44  5011.5 1866.94
  5014.8 1868.85  5043.8 1870.03  5058.4 1872.73  5089.2 1871.96  5117.4 1874.25
  5150.4 1874.69  5167.8 1875.89  5172.9 1875.43  5191.3 1877.56  5211.7 1880.96
  5218.3 1882.93  5223.4 1882.79  5268.8 1891.48  5273.9 1891.06  5303.5 1894.14
  5319.2  1896.8  5324.3 1896.19  5364.6 1901.27  5369.7  1900.5  5378.2 1901.55
#Mann= 4 ,-1 , 0
  4655.2     .05       0 4988.55     .03       0  5014.8     .05       0
  5378.2     .16       0
Bank Sta=4988.55,5014.8
XS Rating Curve= 0 ,0
Exp/Cntr=0.3,0.1

Type RM Length L Ch R = 1 ,32      ,0,0,0
BEGIN DESCRIPTION:
UNT023 IN SNOGR 1.0
END DESCRIPTION:
XS GIS Cut Line= 4
      2766432.01     10013852.13      2766071.77     10013287.91
       2765815.7     10013320.46       2765223.3     10013483.59
#Sta/Elev= 30
  4186.9 1877.13  4239.2 1873.57  4317.9 1873.89  4369.5 1869.48  4398.6 1869.84
    4630 1861.86    4724 1862.03  4833.1 1858.85  4920.1 1860.77  4960.4 1857.11
  4980.6 1852.54 4983.71 1851.64  5000.5 1847.59  5018.7 1848.53  5023.7  1851.6
  5061.3  1854.9  5098.6 1853.63  5110.5 1856.66  5141.6 1859.73  5146.7 1861.81
  5181.1 1860.89  5186.3 1862.61  5220.7 1860.86  5225.9 1863.14  5294.7 1863.16
  5299.9 1864.71  5413.4 1868.23  5516.1 1873.59  5661.3 1883.88  5728.9 1892.53
#Mann= 4 ,-1 , 0
  4186.9     .03       0  4980.6    .025       0  5023.7     .03       0
  5728.9     .16       0
Bank Sta=4983.71,5023.7
XS Rating Curve= 0 ,0
Exp/Cntr=0.3,0.1

Chan Stop Cuts=-1
Use User Specified Reach Order=0
Composite Channel Slope=5