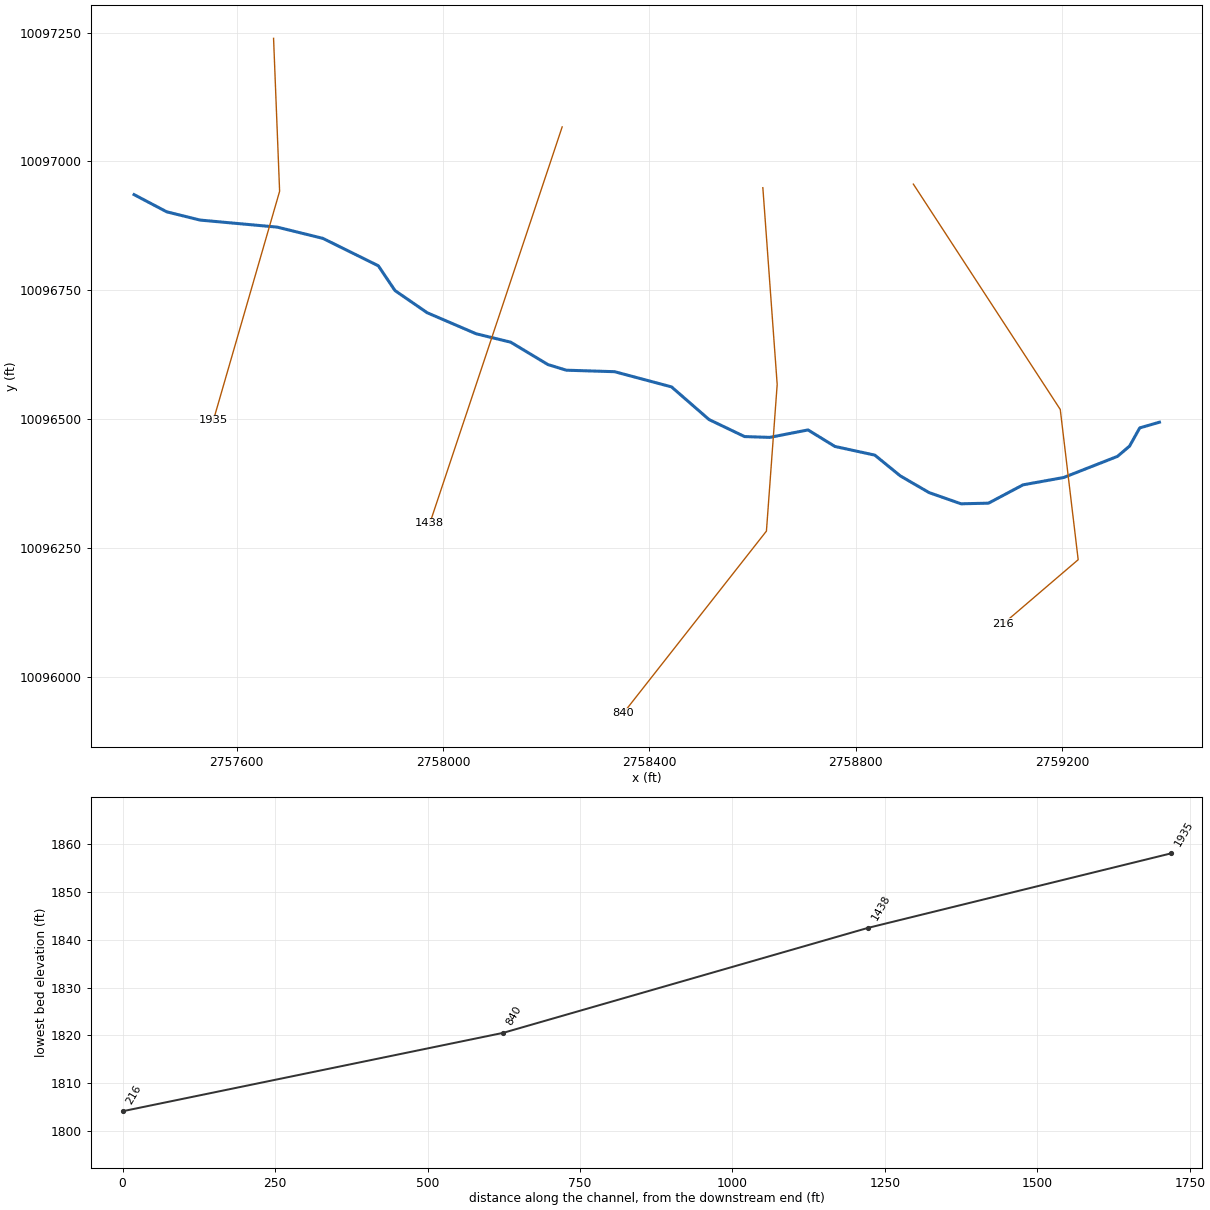
--- UNT024 IN NNOGR.prj (project) ---

Proj Title=UNT024 IN NNOGR Base Level Engineering
Current Plan=p01
Default Exp/Contr=0.3,0.1
English Units
Geom File=g01
Flow File=f01
Plan File=p01
Y Axis Title=Elevation
X Axis Title(PF)=Main Channel Distance
X Axis Title(XS)=Station
BEGIN DESCRIPTION:
UNT024 IN NNOGR
END DESCRIPTION:
DSS Export Rating Curves= 0
DSS Export Rating Curve Sorted= 0
DSS Export Volume Flow Curves= 0
DXF OffsetX= 0
DXF OffsetY= 0
DXF ScaleX= 1
DXF ScaleY= 10

--- UNT024 IN NNOGR.p01 (plan) ---

Plan Title=Multiple Run
Short Identifier=Multiple
Geom File=g01
Flow File=f01
Subcritical Flow
K Sum by GR= 0
Std Step Tol= 0.01
Critical Tol= 0.01
Num of Std Step Trials= 20
Max Error Tol= 0.3
Flow Tol Ratio= 0.001
Split Flow NTrial= 30
Split Flow Tol= 0.02
Split Flow Ratio= 0.02
Log Output Level= 0
Friction Slope Method= 1
Unsteady Friction Slope Method= 2
Unsteady Bridges Friction Slope Method= 1
Parabolic Critical Depth
Global Vel Dist=  1 , 1 , 1
Global Log Level= 0
CheckData=True
Encroach Param= -1, 0, 0, 0
BEGIN DESCRIPTION:
Multiple Run
END DESCRIPTION:

--- UNT024 IN NNOGR.f01 (steady flow) ---

Flow Title=Multiple
Program Version=4.10
Number of Profiles= 7
Profile Names=10-year,25-year,50-year,1pct_min,100-year,1pct_plu,500-year
River Rch & RM=UNT024 IN NNOGR,Reach-1         ,1935
     260     352     428     383     517     700     756
Boundary for River Rch & Prof#=UNT024 IN NNOGR,Reach-1         , 1
Up Type= 0
Dn Type= 3
Dn Slope=0.026
Boundary for River Rch & Prof#=UNT024 IN NNOGR,Reach-1         , 2
Up Type= 0
Dn Type= 3
Dn Slope=0.026
Boundary for River Rch & Prof#=UNT024 IN NNOGR,Reach-1         , 3
Up Type= 0
Dn Type= 3
Dn Slope=0.026
Boundary for River Rch & Prof#=UNT024 IN NNOGR,Reach-1         , 4
Up Type= 0
Dn Type= 3
Dn Slope=0.026
Boundary for River Rch & Prof#=UNT024 IN NNOGR,Reach-1         , 5
Up Type= 0
Dn Type= 3
Dn Slope=0.026
Boundary for River Rch & Prof#=UNT024 IN NNOGR,Reach-1         , 6
Up Type= 0
Dn Type= 3
Dn Slope=0.026
Boundary for River Rch & Prof#=UNT024 IN NNOGR,Reach-1         , 7
Up Type= 0
Dn Type= 3
Dn Slope=0.026
DSS Import GetInterval= 0
DSS Import GetPeak= 0
DSS Import FillOption= 0

--- UNT024 IN NNOGR.g01 (geometry) ---

Geom Title=Existing Conditions
Program Version=4.10

River Reach=UNT024 IN NNOGR ,Reach-1
Reach XY= 30
       2757401.3     10096935.57      2757464.47     10096902.19
      2757529.14     10096886.13      2757678.65     10096872.45
      2757767.13     10096850.62       2757874.6      10096797.4
      2757906.93     10096749.26      2757969.43     10096706.18
      2758064.16     10096665.42      2758131.24     10096649.05
       2758203.3      10096605.6      2758239.04     10096594.67
      2758332.54     10096591.78      2758442.86     10096562.27
      2758515.63     10096498.83      2758584.44     10096465.82
      2758633.13     10096464.25      2758707.36     10096478.72
      2758759.58     10096446.61      2758836.84      10096429.8
      2758886.22     10096389.51      2758941.93     10096357.09
      2759003.89      10096335.3      2759057.14     10096336.54
      2759124.13     10096372.12      2759202.77     10096386.34
      2759307.12     10096427.36      2759330.57     10096447.34
      2759350.26     10096482.64      2759388.47     10096493.73

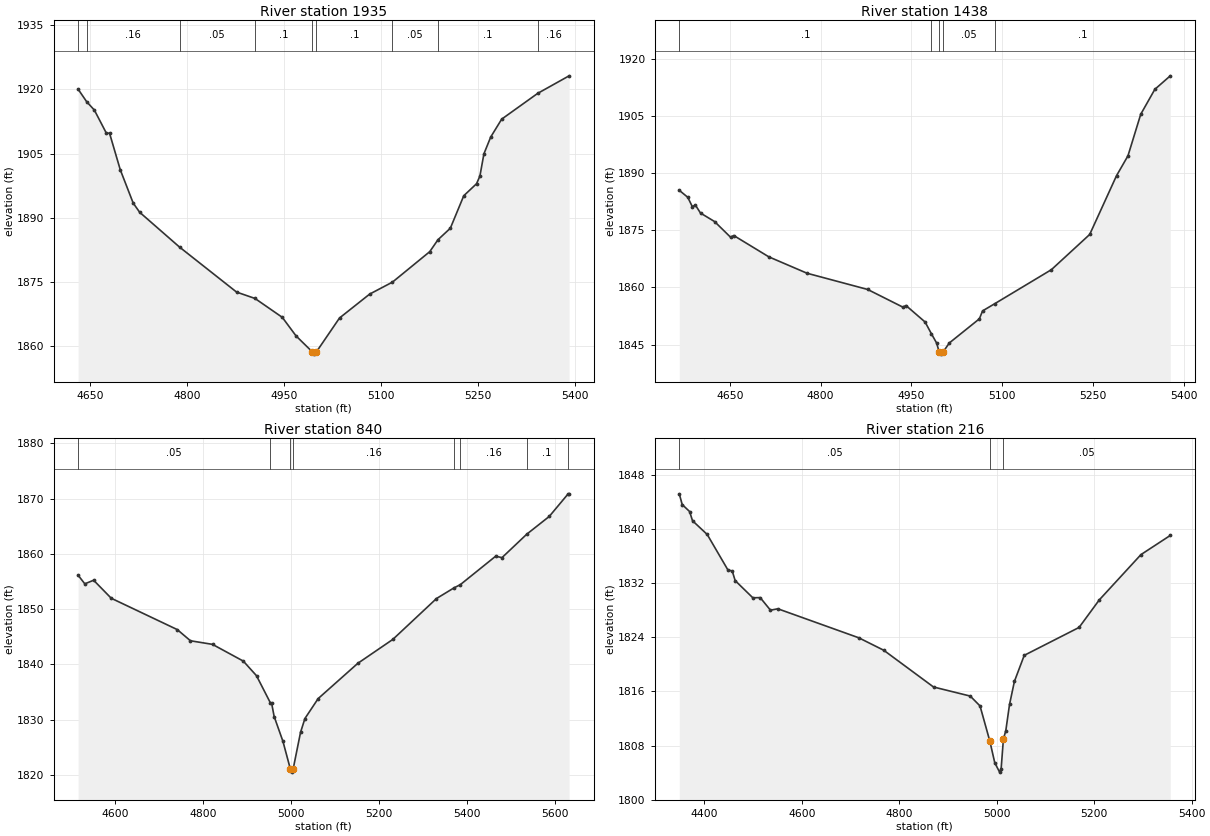
Type RM Length L Ch R = 1 ,1935    ,497,497,497
BEGIN DESCRIPTION:
Mapping XS 02a3a7bb
END DESCRIPTION:
XS GIS Cut Line= 3
      2757671.61     10097238.96      2757683.33     10096942.04
      2757554.89     10096497.05
#Sta/Elev= 30
  4631.1 1920.06  4644.5  1917.1  4656.3 1915.17  4674.8 1909.79  4679.8 1909.76
  4696.4 1901.22  4716.4 1893.43  4726.4 1891.28  4788.2 1883.13  4876.5 1872.61
    4905 1871.12  4947.3  1866.7  4968.6 1862.36    4994  1858.6  4996.8  1858.1
    5000  1858.6  5035.9 1866.55  5082.6 1872.14  5117.9 1874.94  5175.6 1882.06
  5188.4 1884.86  5207.5 1887.54  5228.3 1895.14  5248.1 1897.95  5253.3 1899.75
  5259.5 1904.94    5270 1908.86    5287 1913.05  5342.8 1919.08  5391.4 1923.18
#Mann= 9 ,-1 , 0
  4631.1      .1       0  4644.5     .16       0  4788.2     .05       0
    4905      .1       0    4994     .07       0    5000      .1       0
  5117.9     .05       0  5188.4      .1       0  5342.8     .16       0
Bank Sta=4994,5000
XS Rating Curve= 0 ,0
Exp/Cntr=0.3,0.1

Type RM Length L Ch R = 1 ,1438    ,598,598,598
BEGIN DESCRIPTION:
UNT024 IN NNOGR 3.0
END DESCRIPTION:
XS GIS Cut Line= 2
      2758230.94     10097067.03      2757974.42     10096297.46
#Sta/Elev= 30
  4566.6 1885.54  4580.6 1883.71  4588.1 1881.27  4593.3 1881.65  4601.7 1879.56
    4625 1877.32  4651.3 1873.22  4656.6 1873.66  4714.6 1868.05  4777.8 1863.74
  4877.9 1859.48  4935.9 1854.85  4941.2 1855.26  4972.8 1850.92  4983.2 1847.83
  4991.7 1845.43  4996.2 1842.99  4998.9 1842.49  5002.2 1842.99  5012.8 1845.43
  5062.4 1851.76  5067.7 1853.85  5087.6 1855.72  5181.4 1864.68  5244.7 1873.94
    5289 1889.38  5307.9  1894.6    5329 1905.52  5352.3 1912.07  5377.8 1915.62
#Mann= 5 ,-1 , 0
  4566.6      .1       0  4983.2     .05       0  4996.2    .035       0
  5002.2     .05       0  5087.6      .1       0
Bank Sta=4996.2,5002.2
XS Rating Curve= 0 ,0
Exp/Cntr=0.3,0.1

Type RM Length L Ch R = 1 ,840     ,624,624,624
BEGIN DESCRIPTION:
UNT024 IN NNOGR 2.0
END DESCRIPTION:
XS GIS Cut Line= 4
      2758619.85     10096949.01      2758647.62     10096567.07
      2758626.79     10096282.34      2758349.22     10095928.44
#Sta/Elev= 30
  4514.9 1856.13  4530.2 1854.57  4550.3 1855.22  4590.4 1851.96  4740.8 1846.29
  4770.8 1844.27    4821 1843.62  4891.2 1840.59  4921.2 1837.95  4952.7 1833.06
  4955.6 1832.99  4961.4 1830.57  4981.4 1826.08  4998.5 1821.01  5001.2 1820.51
  5004.5 1821.01  5021.5 1827.71  5031.5 1830.21  5061.6 1833.81  5151.9 1840.19
  5231.7 1844.52  5331.1 1851.91    5371 1853.84  5385.2 1854.41  5465.9 1859.57
  5480.3 1859.31  5536.7 1863.55  5587.9 1866.76  5629.7 1870.73  5633.1 1870.85
#Mann= 8 ,-1 , 0
  4514.9     .05       0  4952.7     .16       0  4998.5     .07       0
  5004.5     .16       0    5371     .05       0  5385.2     .16       0
  5536.7      .1       0  5629.7     .16       0
Bank Sta=4998.5,5004.5
XS Rating Curve= 0 ,0
Exp/Cntr=0.3,0.1

Type RM Length L Ch R = 1 ,216     ,0,0,0
BEGIN DESCRIPTION:
UNT024 IN NNOGR 1.0
END DESCRIPTION:
XS GIS Cut Line= 4
      2758911.54     10096955.92      2759196.23     10096518.46
      2759230.96     10096226.79      2759085.16     10096101.82
#Sta/Elev= 30
  4348.4 1845.15  4354.5 1843.56  4369.6 1842.54  4375.6 1841.18  4405.8 1839.15
    4448 1833.95  4457.2 1833.75  4463.1 1832.35  4499.4 1829.81  4514.5 1829.84
  4535.6 1827.98  4550.7 1828.19  4716.8 1823.91  4768.1 1822.07  4870.2 1816.65
  4945.6 1815.31  4965.7 1813.85  4985.9 1808.63  4995.9 1805.47  5005.8 1804.09
    5009 1804.59  5013.6 1808.93  5018.6 1810.23  5026.2 1814.07  5036.2 1817.47
  5056.4 1821.32    5169 1825.44  5210.3 1829.49  5295.9 1836.18  5356.1 1839.01
#Mann= 3 , 0 , 0
  4348.4     .05       0  4985.9     .03       0  5013.6     .05       0
Bank Sta=4985.9,5013.6
XS Rating Curve= 0 ,0
Exp/Cntr=0.3,0.1

Chan Stop Cuts=-1
Use User Specified Reach Order=0
Composite Channel Slope=5