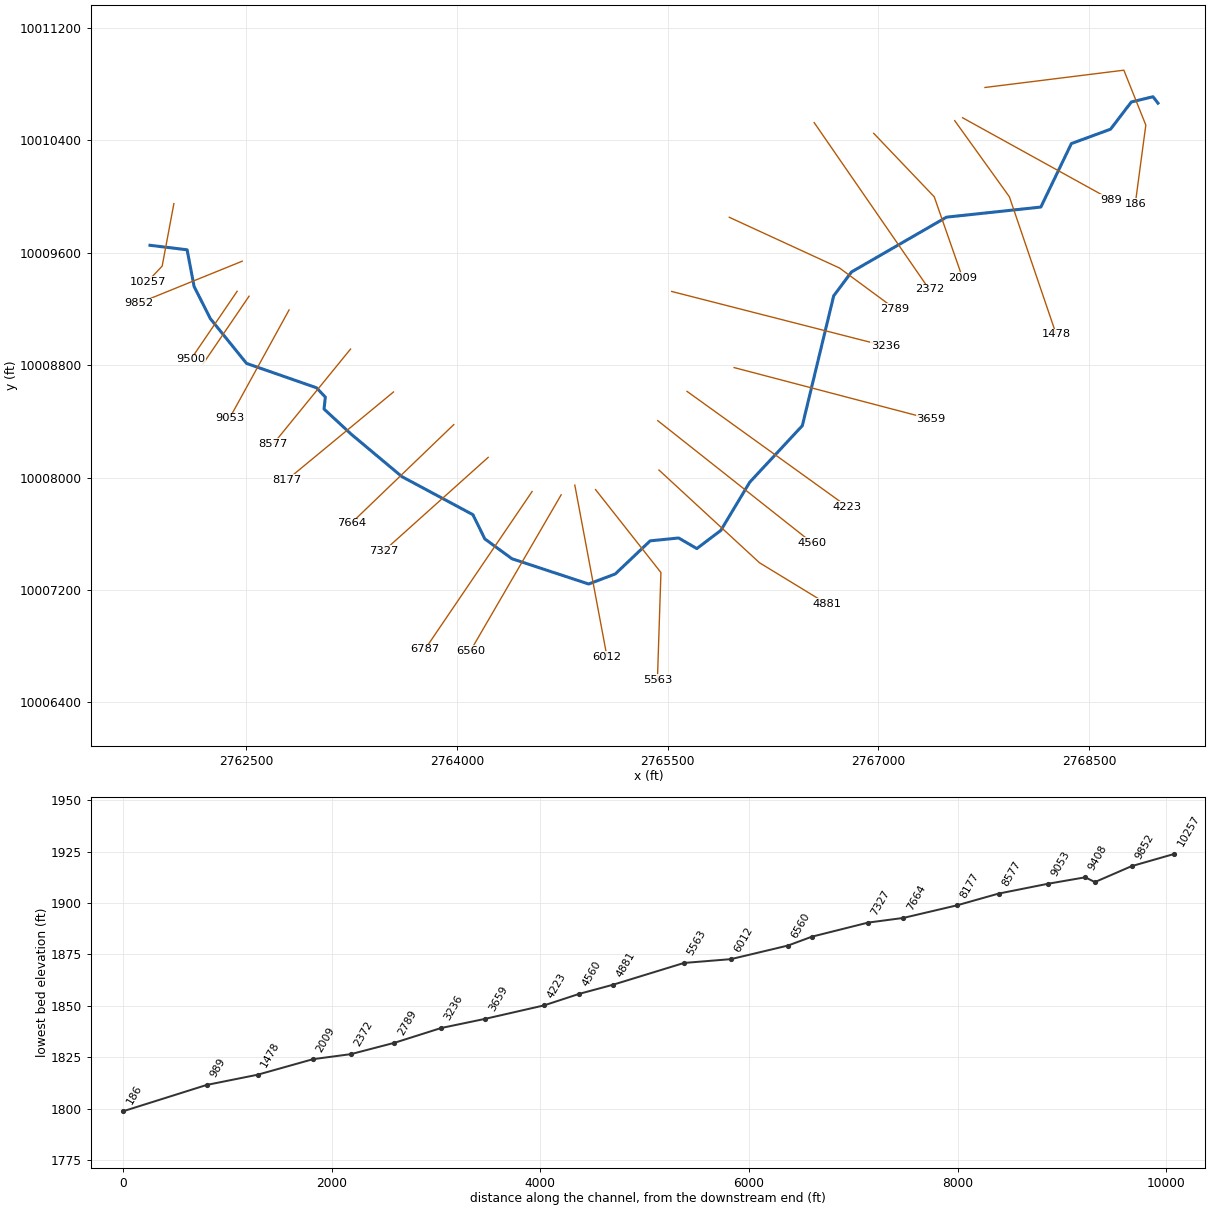
--- UNT024 IN SNOGR.prj (project) ---

Proj Title=UNT024 IN SNOGR Base Level Engineering
Current Plan=p01
Default Exp/Contr=0.3,0.1
English Units
Geom File=g01
Flow File=f01
Plan File=p01
BEGIN DESCRIPTION:
UNT024 IN SNOGR
END DESCRIPTION:

--- UNT024 IN SNOGR.p01 (plan) ---

Plan Title=Multiple Run
Short Identifier=Multiple
Geom File=g01
Flow File=f01
Subcritical Flow
K Sum by GR= 0
Std Step Tol= 0.01
Critical Tol= 0.01
Num of Std Step Trials= 20
Max Error Tol= 0.3
Flow Tol Ratio= 0.001
Split Flow NTrial= 30
Split Flow Tol= 0.02
Split Flow Ratio= 0.02
Log Output Level= 0
Friction Slope Method= 1
Unsteady Friction Slope Method= 2
Unsteady Bridges Friction Slope Method= 1
Parabolic Critical Depth
Global Vel Dist=  1 , 1 , 1
Global Log Level= 0
CheckData=True
Encroach Param= -1, 0, 0, 0
BEGIN DESCRIPTION:
Multiple Run
END DESCRIPTION:

--- UNT024 IN SNOGR.f01 (steady flow) ---

Flow Title=Multiple
Number of Profiles=7
Profile Names=10-year,25-year,50-year,1pct_min,100-year,1pct_plu,500-year
River Rch & RM= UNT024 IN SNOGR,Reach-1,10257
     729    1043    1313    1210    1636    2212    2550
River Rch & RM= UNT024 IN SNOGR,Reach-1,4881
    1020    1487    1893    1763    2384    3224    3796
Boundary for River Rch & Prof#=UNT024 IN SNOGR,Reach-1,1
Up Type=0
Dn Type=3
Dn Slope=0.005
Boundary for River Rch & Prof#=UNT024 IN SNOGR,Reach-1,2
Up Type=0
Dn Type=3
Dn Slope=0.005
Boundary for River Rch & Prof#=UNT024 IN SNOGR,Reach-1,3
Up Type=0
Dn Type=3
Dn Slope=0.005
Boundary for River Rch & Prof#=UNT024 IN SNOGR,Reach-1,4
Up Type=0
Dn Type=3
Dn Slope=0.005
Boundary for River Rch & Prof#=UNT024 IN SNOGR,Reach-1,5
Up Type=0
Dn Type=3
Dn Slope=0.005
Boundary for River Rch & Prof#=UNT024 IN SNOGR,Reach-1,6
Up Type=0
Dn Type=3
Dn Slope=0.005
Boundary for River Rch & Prof#=UNT024 IN SNOGR,Reach-1,7
Up Type=0
Dn Type=3
Dn Slope=0.005

--- UNT024 IN SNOGR.g01 (geometry) ---

Geom Title=Existing Conditions

River Reach=UNT024 IN SNOGR,Reach-1
Reach XY= 30
      2761816.84     10009652.50      2762081.13     10009620.49
      2762130.68     10009359.68      2762246.89     10009129.86
      2762503.88     10008812.02      2763001.46     10008638.72
      2763064.48     10008572.35      2763055.45     10008487.35
      2763247.03     10008309.67      2763609.46     10008006.24
      2764114.44     10007735.66      2764199.42     10007563.12
      2764392.47     10007422.01      2764937.87     10007242.31
      2765127.65     10007313.99      2765375.49     10007549.37
      2765577.89     10007569.80      2765707.62     10007494.51
      2765878.47     10007623.73      2766083.62     10007966.19
      2766458.21     10008368.81      2766681.32     10009292.55
      2766808.07     10009462.68      2767483.93     10009852.61
      2768155.20     10009924.47      2768372.45     10010376.14
      2768651.24     10010478.56      2768798.97     10010672.15
      2768953.12     10010709.59      2768988.47     10010663.73

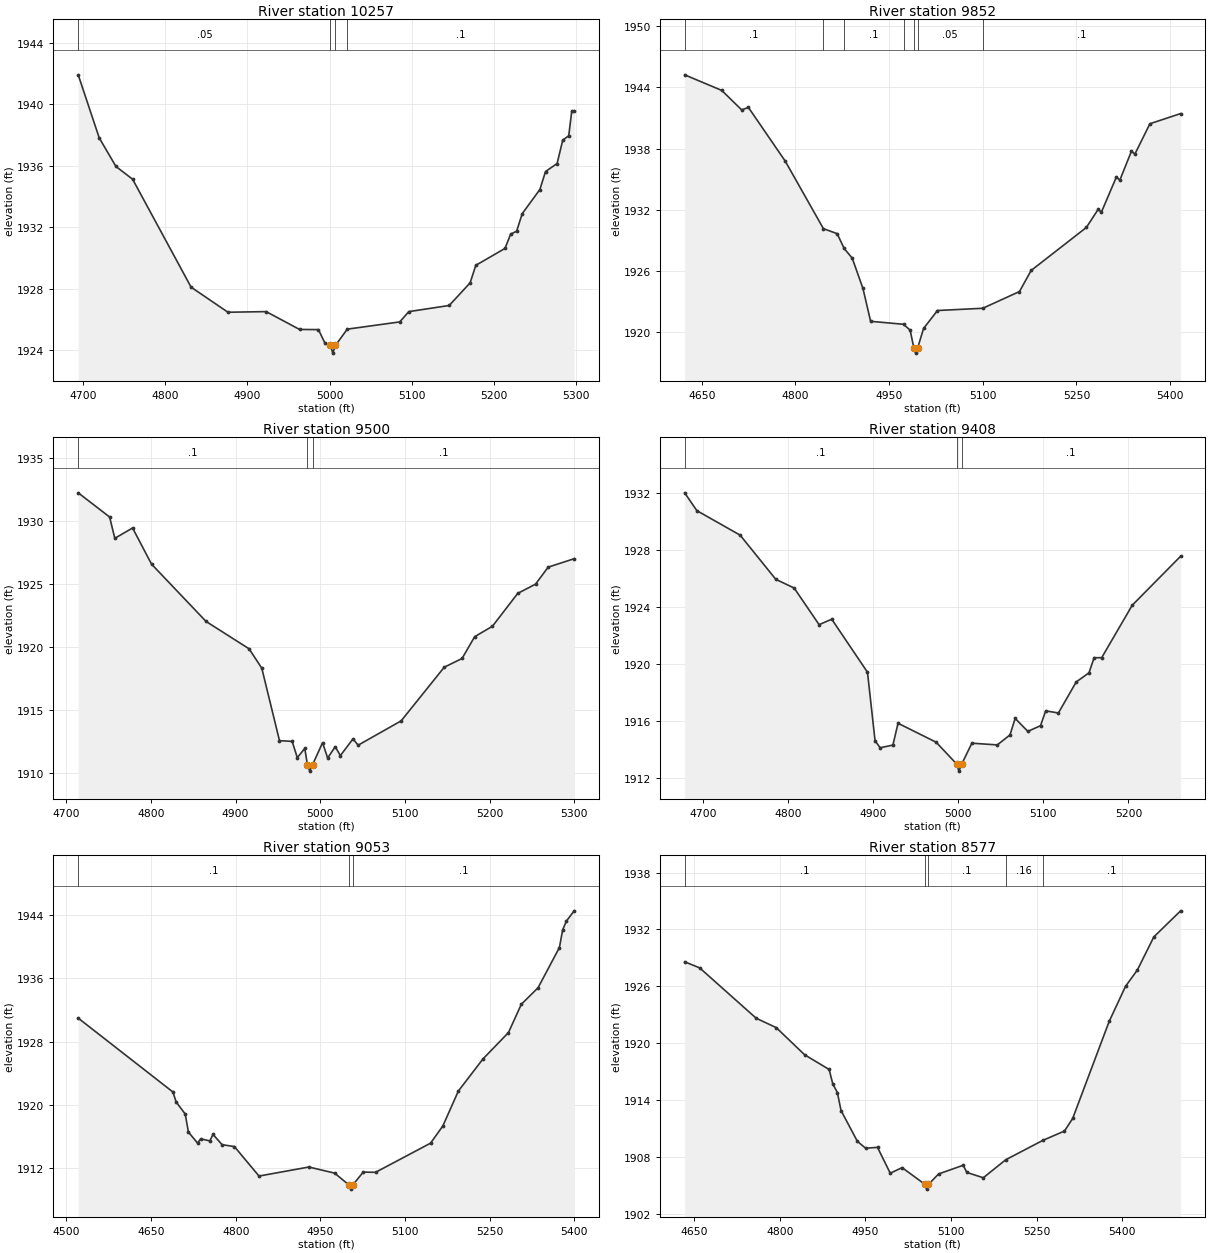
Type RM Length L Ch R = 1,10257,405,405,405
BEGIN DESCRIPTION:
UNT024 IN SNOGR 23.0
END DESCRIPTION:
XS GIS Cut Line= 3
      2761986.96     10009948.94      2761903.62     10009504.49
      2761799.45     10009393.38
#Sta/Elev= 30
  4693.7 1941.91  4719.3 1937.81  4739.7 1935.95  4760.0 1935.12  4831.3 1928.10
  4876.2 1926.47  4922.8 1926.51  4963.5 1925.35  4986.5 1925.34  4994.1 1924.50
  5001.2 1924.31  5004.0 1923.81  5007.2 1924.31  5021.7 1925.37  5085.6 1925.84
  5096.7 1926.51  5145.9 1926.91  5171.4 1928.38  5178.3 1929.52  5213.9 1930.62
  5220.8 1931.55  5228.1 1931.74  5234.9 1932.88  5256.4 1934.45  5263.3 1935.62
  5277.4 1936.14  5284.3 1937.66  5291.6 1937.95  5295.3 1939.56  5298.2 1939.56
#Mann=4,-1,0
  4693.7    0.05       0  5001.2   0.035       0  5007.2    0.05       0
  5021.7     0.1       0
Bank Sta=5001.2,5007.2
Exp/Cntr=0.3,0.1

Type RM Length L Ch R = 1,9852,352,352,352
BEGIN DESCRIPTION:
UNT024 IN SNOGR 22.0
END DESCRIPTION:
XS GIS Cut Line= 2
      2762473.04     10009539.20      2761737.00     10009240.62
#Sta/Elev= 30
  4622.6 1945.23  4682.0 1943.70  4713.9 1941.79  4724.7 1942.03  4783.7 1936.76
  4844.8 1930.14  4866.8 1929.65  4878.0 1928.20  4890.9 1927.25  4908.1 1924.28
  4920.4 1921.05  4973.1 1920.76  4983.7 1920.18  4989.7 1918.43  4992.4 1917.93
  4995.7 1918.43  5005.2 1920.35  5027.5 1922.11  5100.0 1922.33  5158.8 1923.97
  5177.5 1926.04  5266.0 1930.26  5284.7 1932.02  5290.1 1931.77  5314.1 1935.22
  5319.5 1934.89  5338.2 1937.75  5343.6 1937.45  5367.7 1940.43  5416.9 1941.43
#Mann=7,-1,0
  4622.6     0.1       0  4844.8    0.05       0  4878.0     0.1       0
  4973.1    0.05       0  4989.7   0.035       0  4995.7    0.05       0
  5100.0     0.1       0
Bank Sta=4989.7,4995.7
Exp/Cntr=0.3,0.1

Type RM Length L Ch R = 1,9500,92,92,92
BEGIN DESCRIPTION:
UNT024 IN SNOGR 21111.0
END DESCRIPTION:
XS GIS Cut Line= 2
      2762437.16     10009325.33      2762107.78     10008841.02
#Sta/Elev= 30
  4714.1 1932.27  4751.2 1930.35  4757.3 1928.66  4778.3 1929.48  4800.7 1926.61
  4865.1 1922.06  4915.9 1919.89  4930.9 1918.35  4951.8 1912.60  4966.8 1912.54
  4972.8 1911.25  4981.7 1911.98  4984.8 1910.68  4987.5 1910.18  4990.8 1910.68
  5002.7 1912.44  5008.7 1911.22  5017.6 1912.12  5023.7 1911.41  5038.6 1912.74
  5044.7 1912.24  5095.5 1914.17  5146.4 1918.43  5167.4 1919.12  5182.3 1920.85
  5203.3 1921.68  5233.2 1924.29  5254.2 1925.02  5269.1 1926.37  5299.8 1927.04
#Mann=3,-1,0
  4714.1     0.1       0  4984.8    0.07       0  4990.8     0.1       0
Bank Sta=4984.8,4990.8
Exp/Cntr=0.3,0.1

Type RM Length L Ch R = 1,9408,355,355,355
BEGIN DESCRIPTION:
UNT024 IN SNOGR 21.0
END DESCRIPTION:
XS GIS Cut Line= 2
      2762521.79     10009290.16      2762193.92     10008808.09
#Sta/Elev= 30
  4678.3 1932.04  4692.6 1930.79  4743.5 1929.07  4785.4 1925.97  4807.0 1925.36
  4836.3 1922.79  4851.2 1923.17  4893.2 1919.45  4902.1 1914.64  4908.1 1914.15
  4923.1 1914.34  4929.1 1915.87  4973.9 1914.54  4998.0 1913.01  5000.7 1912.51
  5004.0 1913.01  5015.9 1914.47  5045.8 1914.35  5060.7 1915.05  5066.8 1916.21
  5081.7 1915.30  5096.6 1915.70  5102.7 1916.74  5117.6 1916.59  5138.6 1918.77
  5153.6 1919.41  5159.6 1920.47  5168.5 1920.47  5204.4 1924.15  5261.3 1927.59
#Mann=3,-1,0
  4678.3     0.1       0  4998.0    0.07       0  5004.0     0.1       0
Bank Sta=4998,5004
Exp/Cntr=0.3,0.1

Type RM Length L Ch R = 1,9053,476,476,476
BEGIN DESCRIPTION:
UNT024 IN SNOGR 20.0
END DESCRIPTION:
XS GIS Cut Line= 2
      2762806.40     10009192.00      2762383.11     10008421.74
#Sta/Elev= 30
  4520.9 1930.97  4688.7 1921.65  4694.4 1920.40  4710.5 1918.87  4716.2 1916.59
  4732.3 1915.21  4738.0 1915.73  4754.1 1915.48  4759.8 1916.29  4775.9 1915.00
  4797.7 1914.76  4841.3 1911.04  4929.7 1912.18  4975.3 1911.41  5001.2 1909.89
  5004.0 1909.39  5007.2 1909.89  5026.0 1911.54  5047.8 1911.51  5145.3 1915.19
  5167.1 1917.36  5194.6 1921.77  5238.2 1925.82  5283.4 1929.15  5306.2 1932.72
  5335.8 1934.80  5373.7 1939.88  5379.4 1942.10  5386.1 1943.22  5399.8 1944.51
#Mann=3,-1,0
  4520.9     0.1       0  5001.2    0.07       0  5007.2     0.1       0
Bank Sta=5001.2,5007.2
Exp/Cntr=0.3,0.1

Type RM Length L Ch R = 1,8577,400,400,400
BEGIN DESCRIPTION:
UNT024 IN SNOGR 19.0
END DESCRIPTION:
XS GIS Cut Line= 2
      2763243.90     10008914.21      2762695.26     10008240.56
#Sta/Elev= 30
  4633.3 1928.58  4659.5 1927.94  4758.6 1922.62  4793.7 1921.63  4843.3 1918.77
  4886.4 1917.21  4892.8 1915.68  4900.8 1914.78  4907.2 1912.88  4935.9 1909.62
  4950.3 1908.90  4971.1 1908.99  4993.4 1906.26  5014.2 1906.85  5054.3 1905.08
  5057.1 1904.58  5060.3 1905.08  5078.1 1906.18  5121.2 1907.10  5127.7 1906.34
  5156.4 1905.78  5195.7 1907.68  5260.8 1909.73  5298.6 1910.71  5313.0 1912.04
  5376.9 1922.28  5405.6 1925.99  5426.4 1927.72  5455.2 1931.21  5502.1 1933.96
#Mann=5,-1,0
  4633.3     0.1       0  5054.3    0.07       0  5060.3     0.1       0
  5195.7    0.16       0  5260.8     0.1       0
Bank Sta=5054.3,5060.3
Exp/Cntr=0.3,0.1

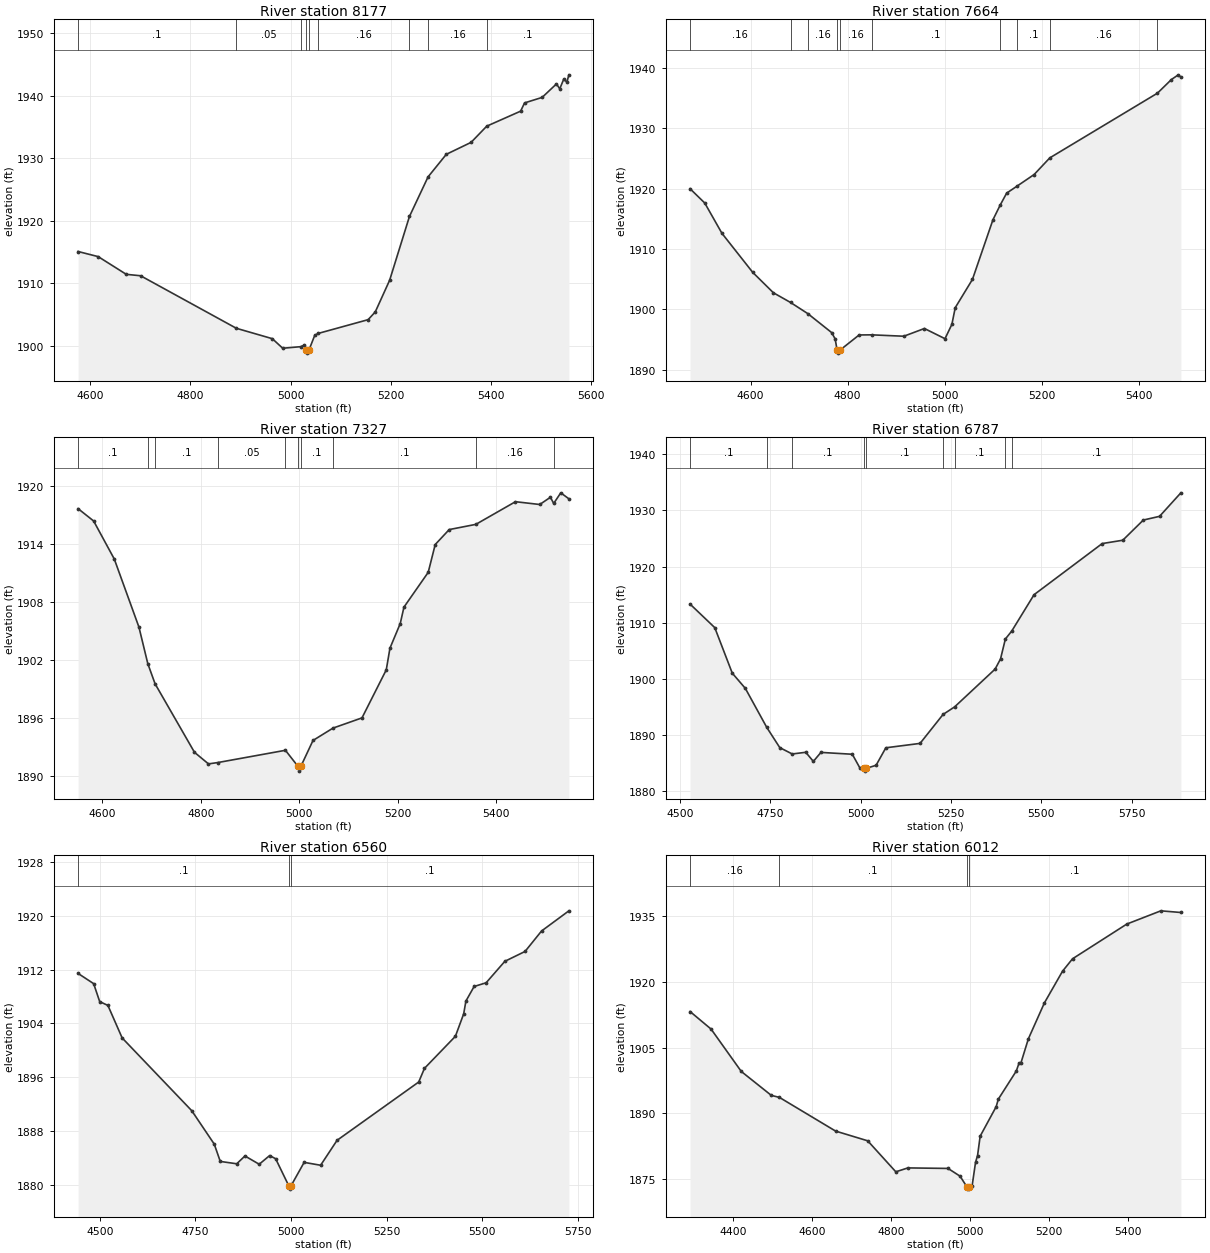
Type RM Length L Ch R = 1,8177,513,513,513
BEGIN DESCRIPTION:
UNT024 IN SNOGR 18.0
END DESCRIPTION:
XS GIS Cut Line= 2
      2763549.47     10008608.67      2762793.01     10007984.07
#Sta/Elev= 30
  4575.4 1915.11  4615.6 1914.29  4671.7 1911.46  4700.4 1911.23  4891.8 1902.83
  4963.6 1901.17  4984.4 1899.64  5020.3 1899.89  5027.4 1900.13  5030.9 1899.36
  5033.7 1898.86  5036.9 1899.36  5048.3 1901.68  5054.9 1902.00  5155.1 1904.21
  5169.4 1905.45  5198.1 1910.51  5237.7 1920.71  5274.9 1927.04  5311.4 1930.65
  5360.9 1932.56  5392.2 1935.15  5459.9 1937.55  5467.8 1938.87  5502.9 1939.75
  5531.6 1941.91  5538.1 1941.12  5546.0 1942.65  5552.4 1942.21  5556.4 1943.36
#Mann=9,-1,0
  4575.4     0.1       0  4891.8    0.05       0  5020.3     0.1       0
  5030.9   0.035       0  5036.9     0.1       0  5054.9    0.16       0
  5237.7     0.1       0  5274.9    0.16       0  5392.2     0.1       0
Bank Sta=5030.9,5036.9
Exp/Cntr=0.3,0.1

Type RM Length L Ch R = 1,7664,337,337,337
BEGIN DESCRIPTION:
UNT024 IN SNOGR 17.0
END DESCRIPTION:
XS GIS Cut Line= 2
      2763978.40     10008376.71      2763249.27     10007675.35
#Sta/Elev= 30
  4475.3 1919.99  4505.6 1917.62  4541.1 1912.59  4604.6 1906.12  4647.1 1902.75
  4682.5 1901.14  4718.1 1899.29  4767.2 1896.15  4774.4 1895.10  4778.4 1893.25
  4781.1 1892.75  4784.4 1893.25  4823.8 1895.76  4849.5 1895.78  4915.9 1895.55
  4958.4 1896.83  5000.8 1895.14  5015.0 1897.52  5021.9 1900.28  5057.4 1904.97
  5099.6 1914.84  5114.7 1917.30  5127.9 1919.26  5149.7 1920.44  5184.5 1922.34
  5216.8 1925.10  5438.7 1935.82  5467.5 1938.08  5481.7 1938.86  5487.0 1938.49
#Mann=10,-1,0
  4475.3    0.16       0  4682.5     0.1       0  4718.1    0.16       0
  4778.4    0.07       0  4784.4    0.16       0  4849.5     0.1       0
  5114.7    0.16       0  5149.7     0.1       0  5216.8    0.16       0
  5438.7     0.1       0
Bank Sta=4778.4,4784.4
Exp/Cntr=0.3,0.1

Type RM Length L Ch R = 1,7327,540,540,540
BEGIN DESCRIPTION:
UNT024 IN SNOGR 16.0
END DESCRIPTION:
XS GIS Cut Line= 2
      2764223.07     10008143.38      2763481.12     10007477.71
#Sta/Elev= 30
  4551.0 1917.70  4582.6 1916.42  4624.5 1912.48  4674.6 1905.42  4692.6 1901.63
  4707.4 1899.54  4787.4 1892.44  4815.8 1891.24  4834.9 1891.38  4972.1 1892.65
  4997.5 1890.99  5000.3 1890.49  5003.5 1890.99  5028.1 1893.67  5068.7 1894.95
  5127.6 1896.01  5176.9 1900.99  5184.4 1903.24  5205.3 1905.79  5212.8 1907.49
  5262.1 1911.10  5276.3 1913.98  5304.7 1915.53  5358.8 1916.07  5439.3 1918.42
  5488.6 1918.13  5510.3 1918.88  5516.9 1918.24  5531.3 1919.34  5547.8 1918.72
#Mann=10,-1,0
  4551.0     0.1       0  4692.6    0.16       0  4707.4     0.1       0
  4834.9    0.05       0  4972.1     0.1       0  4997.5    0.07       0
  5003.5     0.1       0  5068.7     0.1       0  5358.8    0.16       0
  5516.9     0.1       0
Bank Sta=4997.5,5003.5
Exp/Cntr=0.3,0.1

Type RM Length L Ch R = 1,6787,227,227,227
BEGIN DESCRIPTION:
UNT024 IN SNOGR 15.0
END DESCRIPTION:
XS GIS Cut Line= 2
      2764535.58     10007900.34      2763772.55     10006776.61
#Sta/Elev= 30
  4527.6 1913.32  4596.0 1909.13  4644.4 1901.04  4680.6 1898.33  4740.0 1891.38
  4775.9 1887.80  4810.3 1886.67  4847.8 1886.97  4868.8 1885.35  4889.8 1886.95
  4976.6 1886.62  4997.6 1884.18  5009.5 1884.12  5012.3 1883.62  5015.5 1884.12
  5042.4 1884.66  5069.4 1887.77  5164.1 1888.55  5227.8 1893.70  5259.7 1895.04
  5371.8 1901.76  5386.8 1903.57  5400.2 1907.11  5417.8 1908.52  5479.6 1914.99
  5668.2 1924.08  5725.1 1924.67  5782.0 1928.26  5826.9 1928.92  5885.9 1933.10
#Mann=9,-1,0
  4527.6     0.1       0  4740.0    0.05       0  4810.3     0.1       0
  5009.5    0.07       0  5015.5     0.1       0  5227.8    0.05       0
  5259.7     0.1       0  5400.2    0.05       0  5417.8     0.1       0
Bank Sta=5009.5,5015.5
Exp/Cntr=0.3,0.1

Type RM Length L Ch R = 1,6560,548,548,548
BEGIN DESCRIPTION:
UNT024 IN SNOGR 14.0
END DESCRIPTION:
XS GIS Cut Line= 2
      2764742.31     10007876.74      2764097.37     10006767.16
#Sta/Elev= 30
  4443.5 1911.42  4484.2 1909.90  4500.0 1907.23  4521.5 1906.66  4558.7 1901.83
  4740.8 1891.00  4799.6 1886.03  4815.3 1883.46  4858.3 1883.11  4879.9 1884.27
  4917.1 1883.04  4944.4 1884.33  4960.1 1883.86  4994.4 1879.84  4997.1 1879.34
  5000.4 1879.84  5034.6 1883.32  5077.7 1882.89  5120.7 1886.60  5334.2 1895.27
  5349.2 1897.30  5430.1 1902.07  5451.8 1905.41  5457.6 1907.31  5479.1 1909.48
  5510.5 1910.03  5559.4 1913.22  5612.3 1914.69  5655.4 1917.73  5726.9 1920.73
#Mann=3,-1,0
  4443.5     0.1       0  4994.4    0.07       0  5000.4     0.1       0
Bank Sta=4994.4,5000.4
Exp/Cntr=0.3,0.1

Type RM Length L Ch R = 1,6012,449,449,449
BEGIN DESCRIPTION:
UNT024 IN SNOGR 13.0
END DESCRIPTION:
XS GIS Cut Line= 2
      2764839.52     10007946.13      2765068.68     10006723.93
#Sta/Elev= 30
  4290.0 1913.23  4343.3 1909.22  4419.8 1899.56  4495.9 1894.10  4516.3 1893.65
  4658.7 1885.96  4740.1 1883.74  4811.3 1876.67  4841.9 1877.56  4943.6 1877.44
  4974.1 1875.67  4991.5 1873.22  4994.2 1872.72  4997.5 1873.22  5004.6 1873.47
  5013.3 1878.84  5018.4 1880.39  5025.0 1884.80  5065.7 1891.55  5070.9 1893.23
  5116.6 1899.67  5123.5 1901.47  5128.6 1901.60  5147.1 1907.00  5187.8 1915.21
  5233.7 1922.43  5259.0 1925.26  5396.5 1933.18  5482.8 1936.20  5533.5 1935.82
#Mann=4,-1,0
  4290.0    0.16       0  4516.3     0.1       0  4991.5    0.07       0
  4997.5     0.1       0
Bank Sta=4991.5,4997.5
Exp/Cntr=0.3,0.1

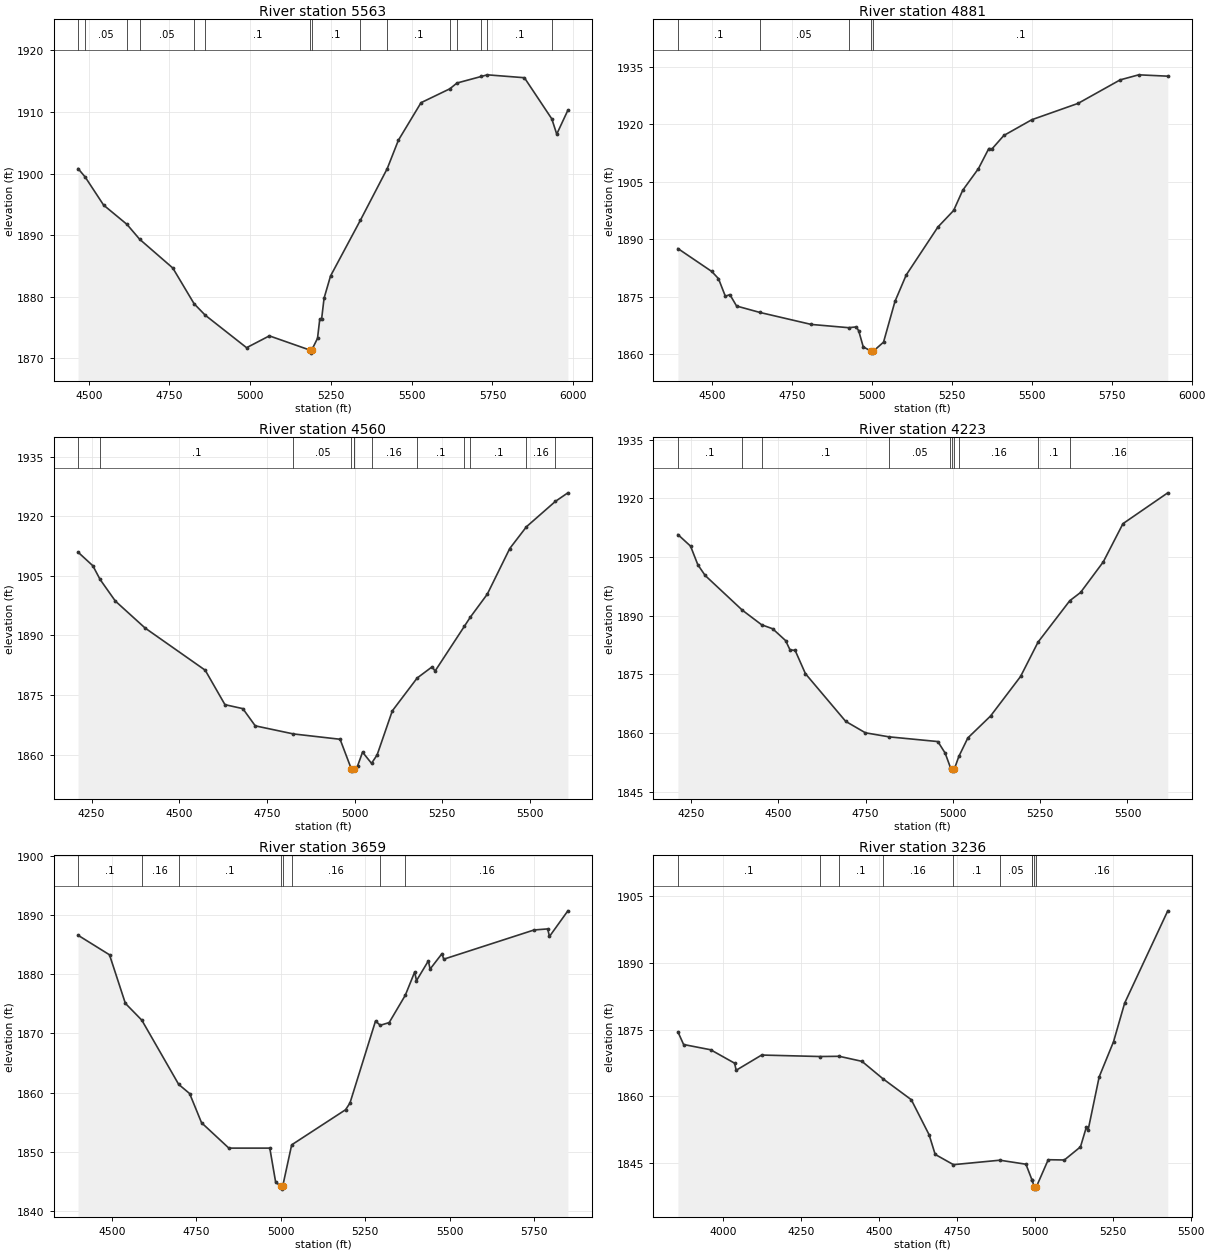
Type RM Length L Ch R = 1,5563,682,682,682
BEGIN DESCRIPTION:
UNT024 IN SNOGR 12.0
END DESCRIPTION:
XS GIS Cut Line= 3
      2764986.97     10007914.20      2765452.23     10007323.93
      2765427.23     10006559.23
#Sta/Elev= 30
  4466.8 1900.81  4489.0 1899.43  4546.0 1894.88  4618.2 1891.76  4657.6 1889.34
  4760.3 1884.67  4826.2 1878.88  4860.5 1877.03  4988.7 1871.75  5059.2 1873.67
  5184.4 1871.37  5187.2 1870.87  5190.4 1871.37  5208.3 1873.27  5215.3 1876.40
  5221.0 1876.40  5228.6 1879.78  5248.6 1883.38  5341.3 1892.45  5424.2 1900.80
  5458.7 1905.40  5528.8 1911.49  5617.9 1913.74  5640.1 1914.68  5715.8 1915.75
  5734.1 1916.01  5848.9 1915.54  5933.8 1908.86  5949.0 1906.39  5983.5 1910.27
#Mann=15,-1,0
  4466.8    0.16       0  4489.0    0.05       0  4618.2     0.1       0
  4657.6    0.05       0  4826.2    0.16       0  4860.5     0.1       0
  5184.4    0.07       0  5190.4     0.1       0  5341.3    0.16       0
  5424.2     0.1       0  5617.9    0.16       0  5640.1     0.1       0
  5715.8    0.16       0  5734.1     0.1       0  5933.8    0.16       0
Bank Sta=5184.4,5190.4
Exp/Cntr=0.3,0.1

Type RM Length L Ch R = 1,4881,321,321,321
BEGIN DESCRIPTION:
UNT024 IN SNOGR 11.0
END DESCRIPTION:
XS GIS Cut Line= 3
      2765438.37     10008053.07      2766153.62     10007393.38
      2766631.68     10007101.77
#Sta/Elev= 30
  4392.2 1887.58  4498.1 1881.59  4519.1 1879.72  4540.6 1875.12  4554.8 1875.54
  4575.8 1872.56  4647.9 1870.90  4809.4 1867.75  4926.1 1866.90  4950.6 1867.10
  4958.0 1866.07  4972.2 1861.88  4997.5 1860.75  5000.3 1860.25  5003.5 1860.75
  5035.7 1863.12  5071.4 1873.75  5106.6 1880.66  5205.8 1893.20  5255.1 1897.53
  5283.5 1902.81  5332.8 1908.48  5365.1 1913.71  5375.5 1913.66  5412.2 1917.13
  5499.8 1921.25  5644.6 1925.52  5776.2 1931.66  5834.3 1932.98  5925.2 1932.63
#Mann=5,-1,0
  4392.2     0.1       0  4647.9    0.05       0  4926.1     0.1       0
  4997.5    0.07       0  5003.5     0.1       0
Bank Sta=4997.5,5003.5
Exp/Cntr=0.3,0.1

Type RM Length L Ch R = 1,4560,337,337,337
BEGIN DESCRIPTION:
UNT024 IN SNOGR 10.0
END DESCRIPTION:
XS GIS Cut Line= 2
      2765429.76     10008404.52      2766525.59     10007537.57
#Sta/Elev= 30
  4211.3 1910.98  4253.6 1907.55  4274.2 1904.11  4317.7 1898.67  4402.6 1891.88
  4574.1 1881.26  4630.4 1872.59  4681.4 1871.59  4716.8 1867.26  4825.9 1865.22
  4958.8 1863.88  4991.1 1856.36  4993.8 1855.86  4997.1 1856.36  4998.0 1856.55
  5008.5 1857.10  5022.9 1860.64  5048.5 1857.82  5064.5 1859.95  5107.8 1871.03
  5178.7 1879.30  5221.6 1882.13  5229.7 1881.04  5313.1 1892.28  5329.9 1894.56
  5378.7 1900.40  5442.8 1911.89  5490.5 1917.38  5573.0 1923.76  5608.6 1925.91
#Mann=12,-1,0
  4211.3    0.05       0  4274.2     0.1       0  4825.9    0.05       0
  4991.1    0.07       0  4997.1    0.05       0  4998.0     0.1       0
  5048.5    0.16       0  5178.7     0.1       0  5313.1    0.16       0
  5329.9     0.1       0  5490.5    0.16       0  5573.0     0.1       0
Bank Sta=4991.1,4997.1
Exp/Cntr=0.3,0.1

Type RM Length L Ch R = 1,4223,564,564,564
BEGIN DESCRIPTION:
UNT024 IN SNOGR 9.0
END DESCRIPTION:
XS GIS Cut Line= 2
      2765638.15     10008612.81      2766776.99     10007793.40
#Sta/Elev= 30
  4212.5 1910.74  4248.7 1907.78  4269.6 1903.01  4290.5 1900.28  4396.9 1891.41
  4452.3 1887.67  4483.9 1886.65  4520.9 1883.63  4533.5 1881.26  4548.2 1881.13
  4577.7 1875.17  4693.0 1862.98  4749.5 1860.05  4816.8 1859.02  4957.0 1857.81
  4977.9 1854.86  4993.1 1851.15  4998.1 1850.75  5000.9 1850.25  5004.1 1850.75
  5017.1 1854.01  5042.9 1858.74  5107.9 1864.34  5193.9 1874.45  5244.0 1883.24
  5334.9 1893.83  5365.7 1895.93  5430.8 1903.75  5487.2 1913.53  5615.5 1921.41
#Mann=10,-1,0
  4212.5     0.1       0  4396.9    0.05       0  4452.3     0.1       0
  4816.8    0.05       0  4993.1     0.1       0  4998.1    0.07       0
  5004.1     0.1       0  5017.1    0.16       0  5244.0     0.1       0
  5334.9    0.16       0
Bank Sta=4998.1,5004.1
Exp/Cntr=0.3,0.1

Type RM Length L Ch R = 1,3659,423,423,423
BEGIN DESCRIPTION:
UNT024 IN SNOGR 8.0
END DESCRIPTION:
XS GIS Cut Line= 2
      2765973.04     10008782.27      2767374.70     10008414.51
#Sta/Elev= 30
  4400.0 1886.55  4493.1 1883.25  4540.0 1875.06  4588.7 1872.22  4697.7 1861.39
  4730.2 1859.83  4765.4 1854.91  4846.2 1850.63  4967.3 1850.63  4984.6 1844.89
  4999.5 1844.21  5002.3 1843.71  5005.5 1844.21  5032.0 1851.18  5191.3 1857.10
  5204.4 1858.23  5280.0 1872.07  5294.2 1871.36  5320.4 1871.81  5368.1 1876.42
  5396.0 1880.36  5401.2 1878.88  5436.4 1882.23  5441.5 1880.84  5476.7 1883.45
  5481.9 1882.51  5749.1 1887.44  5789.4 1887.62  5794.6 1886.34  5849.1 1890.67
#Mann=8,-1,0
  4400.0     0.1       0  4588.7    0.16       0  4697.7     0.1       0
  4999.5    0.07       0  5005.5     0.1       0  5032.0    0.16       0
  5294.2    0.05       0  5368.1    0.16       0
Bank Sta=4999.5,5005.5
Exp/Cntr=0.3,0.1

Type RM Length L Ch R = 1,3236,447,447,447
BEGIN DESCRIPTION:
UNT024 IN SNOGR 7.0
END DESCRIPTION:
XS GIS Cut Line= 2
      2765528.59     10009323.94      2767049.45     10008935.04
#Sta/Elev= 30
  3855.1 1874.48  3873.3 1871.64  3960.1 1870.46  4036.6 1867.46  4041.8 1865.87
  4123.4 1869.28  4310.1 1868.95  4372.0 1869.00  4444.9 1867.87  4512.1 1863.97
  4603.0 1859.27  4660.1 1851.42  4679.5 1847.02  4738.1 1844.72  4886.8 1845.72
  4970.4 1844.82  4989.5 1841.35  4989.8 1841.27  4997.7 1839.74  5000.4 1839.24
  5003.7 1839.74  5041.8 1845.83  5093.6 1845.77  5145.2 1848.71  5164.2 1853.18
  5169.4 1852.39  5205.1 1864.39  5251.1 1872.27  5286.7 1880.91  5424.9 1901.59
#Mann=10,-1,0
  3855.1     0.1       0  4310.1    0.16       0  4372.0     0.1       0
  4512.1    0.16       0  4738.1     0.1       0  4886.8    0.05       0
  4989.5     0.1       0  4989.8    0.16       0  4997.7    0.07       0
  5003.7    0.16       0
Bank Sta=4997.7,5003.7
Exp/Cntr=0.3,0.1

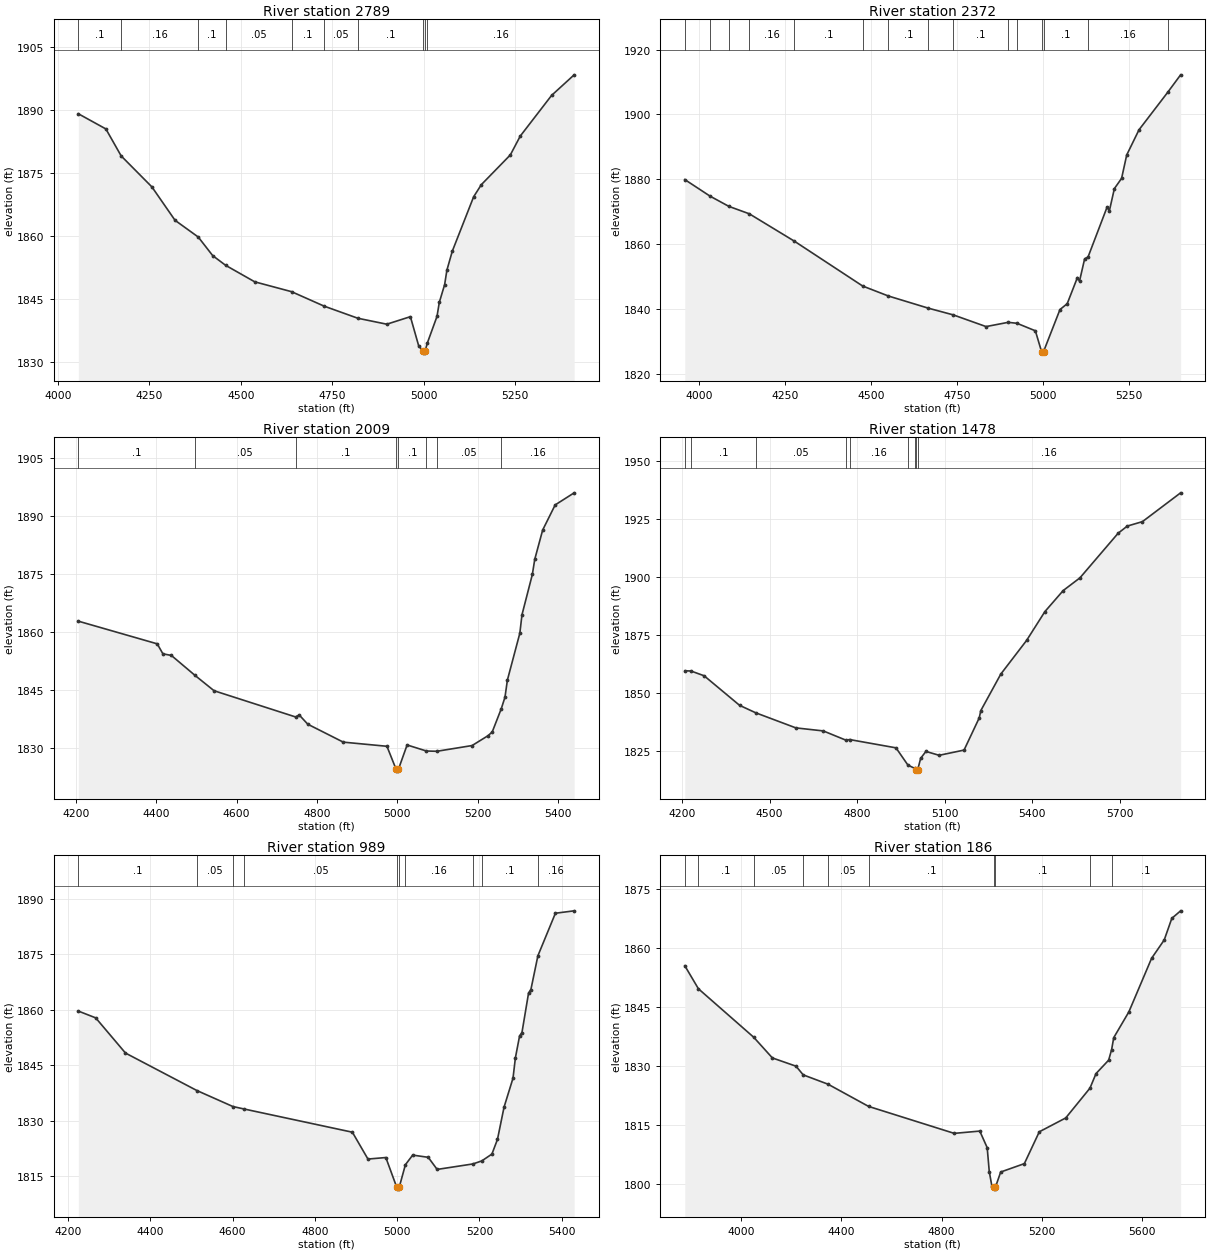
Type RM Length L Ch R = 1,2789,417,417,417
BEGIN DESCRIPTION:
UNT024 IN SNOGR 6.0
END DESCRIPTION:
XS GIS Cut Line= 3
      2765938.32     10009851.72      2766723.07     10009490.60
      2767118.87     10009198.95
#Sta/Elev= 30
  4056.1 1889.17  4131.4 1885.55  4173.2 1879.11  4257.3 1871.71  4320.5 1863.75
  4383.9 1859.76  4423.5 1855.32  4458.8 1853.01  4538.4 1849.07  4639.1 1846.72
  4728.1 1843.27  4820.3 1840.38  4899.4 1838.96  4963.9 1840.76  4986.5 1833.82
  4998.2 1832.56  5000.9 1832.06  5004.2 1832.56  5009.8 1834.37  5036.7 1840.84
  5042.9 1844.16  5057.5 1848.40  5063.7 1851.85  5078.4 1856.37  5136.9 1869.38
  5157.8 1872.25  5237.2 1879.36  5264.2 1883.84  5349.9 1893.55  5411.6 1898.46
#Mann=10,-1,0
  4056.1     0.1       0  4173.2    0.16       0  4383.9     0.1       0
  4458.8    0.05       0  4639.1     0.1       0  4728.1    0.05       0
  4820.3     0.1       0  4998.2    0.07       0  5004.2     0.1       0
  5009.8    0.16       0
Bank Sta=4998.2,5004.2
Exp/Cntr=0.3,0.1

Type RM Length L Ch R = 1,2372,363,363,363
BEGIN DESCRIPTION:
UNT024 IN SNOGR 5.0
END DESCRIPTION:
XS GIS Cut Line= 2
      2766542.51     10010525.32      2767361.62     10009338.31
#Sta/Elev= 30
  3959.1 1879.97  4032.7 1874.86  4087.3 1871.72  4146.8 1869.43  4277.5 1861.03
  4476.5 1847.20  4551.6 1844.12  4667.7 1840.38  4740.0 1838.32  4835.4 1834.72
  4899.8 1836.03  4925.4 1835.73  4978.8 1833.42  4996.7 1827.05  4999.5 1826.55
  5002.7 1827.05  5050.4 1839.97  5071.4 1841.76  5101.1 1849.82  5107.2 1848.70
  5122.1 1855.57  5132.0 1856.14  5187.7 1871.58  5193.8 1870.23  5208.6 1877.19
  5229.6 1880.34  5244.5 1887.54  5280.3 1895.30  5364.1 1906.88  5401.3 1912.21
#Mann=15,-1,0
  3959.1     0.1       0  4032.7    0.16       0  4087.3     0.1       0
  4146.8    0.16       0  4277.5     0.1       0  4476.5    0.05       0
  4551.6     0.1       0  4667.7    0.05       0  4740.0     0.1       0
  4899.8    0.05       0  4925.4     0.1       0  4996.7    0.07       0
  5002.7     0.1       0  5132.0    0.16       0  5364.1     0.1       0
Bank Sta=4996.7,5002.7
Exp/Cntr=0.3,0.1

Type RM Length L Ch R = 1,2009,531,531,531
BEGIN DESCRIPTION:
UNT024 IN SNOGR 4.0
END DESCRIPTION:
XS GIS Cut Line= 3
      2766966.10     10010448.95      2767396.68     10009997.54
      2767598.07     10009421.15
#Sta/Elev= 30
  4206.1 1862.79  4402.5 1856.94  4416.7 1854.36  4437.7 1853.95  4496.7 1848.79
  4544.0 1844.84  4746.9 1838.08  4756.0 1838.59  4777.4 1836.20  4865.7 1831.58
  4974.4 1830.51  4997.1 1824.60  4999.9 1824.10  5003.1 1824.60  5024.6 1830.85
  5072.7 1829.29  5098.6 1829.22  5186.4 1830.70  5225.9 1833.23  5236.5 1834.20
  5259.0 1840.18  5268.3 1843.19  5274.3 1847.60  5305.3 1859.69  5310.6 1864.44
  5336.4 1874.83  5342.4 1878.75  5362.1 1886.30  5393.2 1892.78  5440.5 1895.90
#Mann=8,-1,0
  4206.1     0.1       0  4496.7    0.05       0  4746.9     0.1       0
  4997.1    0.07       0  5003.1     0.1       0  5072.7    0.16       0
  5098.6    0.05       0  5259.0    0.16       0
Bank Sta=4997.1,5003.1
Exp/Cntr=0.3,0.1

Type RM Length L Ch R = 1,1478,489,489,489
BEGIN DESCRIPTION:
UNT024 IN SNOGR 3.0
END DESCRIPTION:
XS GIS Cut Line= 3
      2767542.50     10010539.23      2767931.40     10009997.54
      2768264.03     10009020.45
#Sta/Elev= 30
  4209.6 1859.72  4230.5 1859.64  4275.8 1857.58  4397.4 1844.85  4452.9 1841.63
  4590.2 1835.15  4684.2 1833.84  4762.3 1829.83  4774.2 1830.13  4933.3 1826.56
  4974.2 1819.13  4996.8 1817.77  5001.5 1817.04  5004.2 1816.54  5007.5 1817.04
  5017.8 1822.05  5035.8 1825.02  5081.2 1823.35  5166.5 1825.60  5218.5 1839.45
  5224.0 1842.61  5292.4 1858.30  5380.8 1872.79  5443.5 1885.19  5506.2 1894.25
  5563.7 1899.73  5694.4 1918.91  5725.8 1922.00  5777.9 1923.92  5908.6 1936.31
#Mann=9,-1,0
  4209.6    0.16       0  4230.5     0.1       0  4452.9    0.05       0
  4762.3     0.1       0  4774.2    0.16       0  4974.2     0.1       0
  4996.8    0.16       0  5001.5    0.07       0  5007.5    0.16       0
Bank Sta=5001.5,5007.5
Exp/Cntr=0.3,0.1

Type RM Length L Ch R = 1,989,803,803,803
BEGIN DESCRIPTION:
UNT024 IN SNOGR 2.0
END DESCRIPTION:
XS GIS Cut Line= 2
      2767598.09     10010560.03      2768653.55     10009976.75
#Sta/Elev= 30
  4224.6 1859.64  4266.8 1857.81  4339.3 1848.30  4513.0 1838.18  4600.6 1833.86
  4628.5 1833.18  4891.1 1826.93  4929.0 1819.68  4972.5 1820.09  4999.0 1812.06
  5001.7 1811.56  5005.0 1812.06  5020.1 1818.16  5037.8 1820.75  5075.6 1820.15
  5097.3 1816.88  5184.2 1818.36  5205.9 1819.18  5230.5 1821.03  5244.0 1825.00
  5260.0 1833.70  5281.8 1841.53  5287.6 1847.02  5297.8 1852.94  5303.5 1853.81
  5319.6 1864.51  5325.3 1865.46  5342.3 1874.57  5384.9 1886.06  5430.5 1886.71
#Mann=10,-1,0
  4224.6     0.1       0  4513.0    0.05       0  4600.6     0.1       0
  4628.5    0.05       0  4999.0   0.035       0  5005.0    0.05       0
  5020.1    0.16       0  5184.2    0.05       0  5205.9     0.1       0
  5342.3    0.16       0
Bank Sta=4999,5005
Exp/Cntr=0.3,0.1

Type RM Length L Ch R = 1,186,0,0,0
BEGIN DESCRIPTION:
UNT024 IN SNOGR 1.0
END DESCRIPTION:
XS GIS Cut Line= 4
      2767757.79     10010775.32      2768745.80     10010898.37
      2768902.05     10010507.75      2768827.23     10009948.89
#Sta/Elev= 30
  3774.4 1855.42  3828.8 1849.57  4049.6 1837.27  4124.2 1832.02  4218.5 1829.93
  4247.4 1827.72  4346.3 1825.36  4508.4 1819.72  4850.4 1812.88  4952.5 1813.46
  4982.1 1809.25  4990.4 1803.16  5001.0 1799.44  5009.0 1799.23  5011.7 1798.73
  5015.0 1799.23  5036.0 1803.07  5130.5 1805.20  5190.2 1813.28  5295.7 1816.79
  5392.6 1824.36  5416.8 1828.06  5467.2 1831.46  5479.1 1834.15  5487.4 1837.16
  5547.9 1843.71  5638.7 1857.31  5689.2 1861.97  5719.4 1867.44  5754.6 1869.35
#Mann=10,-1,0
  3774.4    0.16       0  3828.8     0.1       0  4049.6    0.05       0
  4247.4     0.1       0  4346.3    0.05       0  4508.4     0.1       0
  5009.0    0.07       0  5015.0     0.1       0  5392.6    0.16       0
  5479.1     0.1       0
Bank Sta=5009,5015
Exp/Cntr=0.3,0.1

Chan Stop Cuts=-1