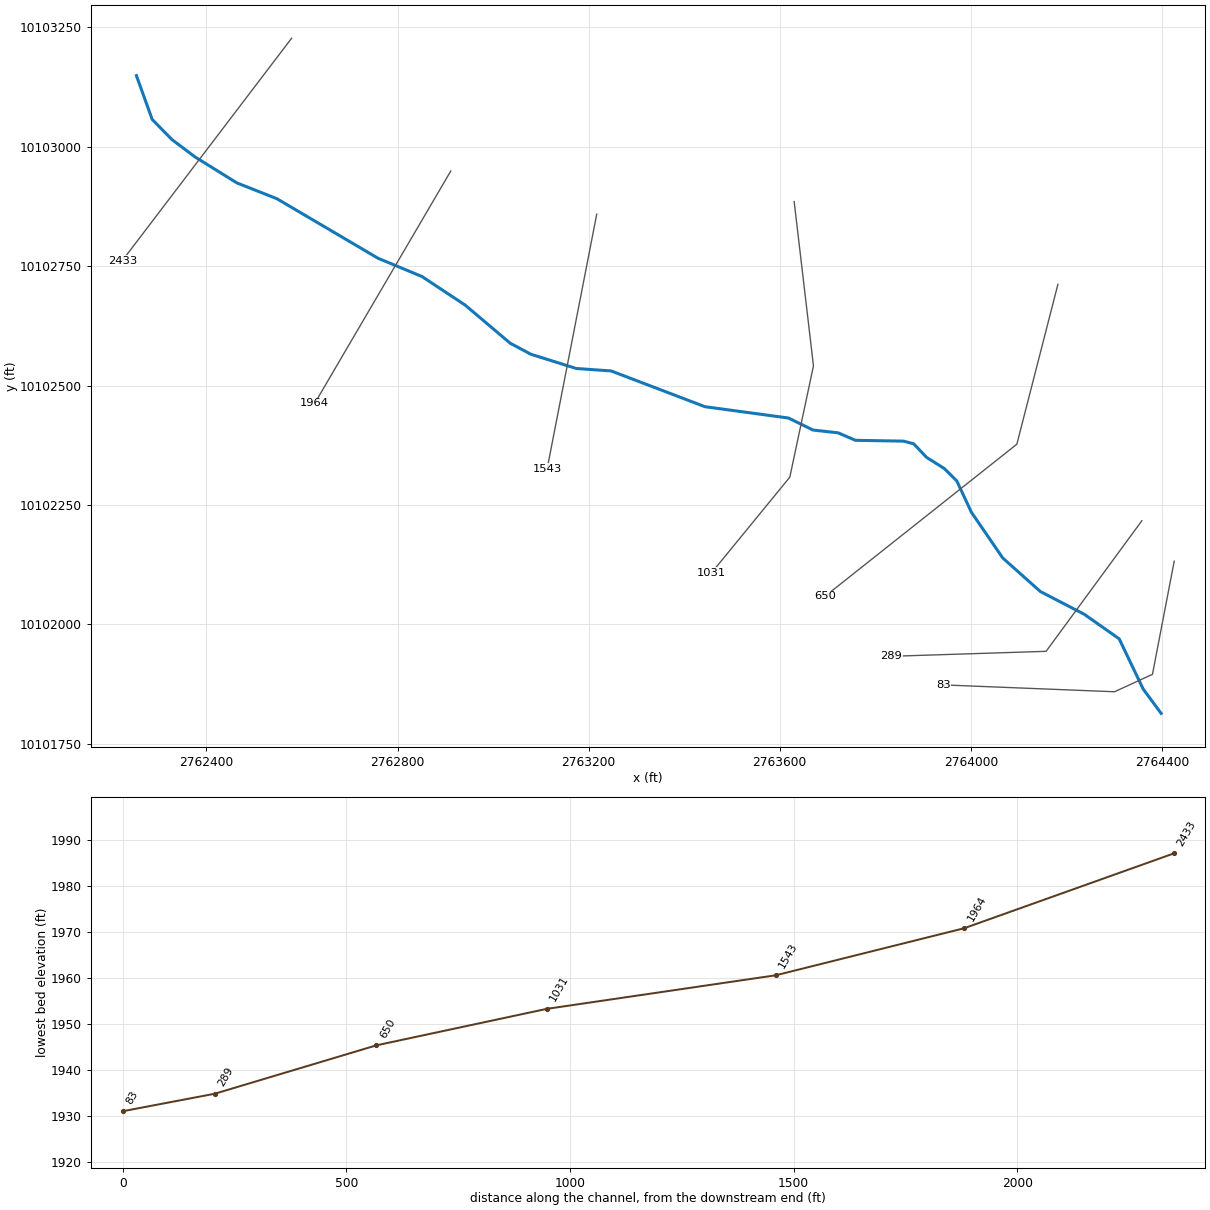
--- UNT025 IN NNOGR.prj (project) ---

Proj Title=UNT025 IN NNOGR Base Level Engineering
Current Plan=p01
Default Exp/Contr=0.3,0.1
English Units
Geom File=g01
Flow File=f01
Plan File=p01
BEGIN DESCRIPTION:
UNT025 IN NNOGR
END DESCRIPTION:

--- UNT025 IN NNOGR.p01 (plan) ---

Plan Title=Multiple Run
Short Identifier=Multiple
Geom File=g01
Flow File=f01
Subcritical Flow
K Sum by GR= 0
Std Step Tol= 0.01
Critical Tol= 0.01
Num of Std Step Trials= 20
Max Error Tol= 0.3
Flow Tol Ratio= 0.001
Split Flow NTrial= 30
Split Flow Tol= 0.02
Split Flow Ratio= 0.02
Log Output Level= 0
Friction Slope Method= 1
Unsteady Friction Slope Method= 2
Unsteady Bridges Friction Slope Method= 1
Parabolic Critical Depth
Global Vel Dist=  1 , 1 , 1
Global Log Level= 0
CheckData=True
Encroach Param= -1, 0, 0, 0
BEGIN DESCRIPTION:
Multiple Run
END DESCRIPTION:

--- UNT025 IN NNOGR.f01 (steady flow) ---

Flow Title=Multiple
Number of Profiles=7
Profile Names=10-year,25-year,50-year,1pct_min,100-year,1pct_plu,500-year
River Rch & RM= UNT025 IN NNOGR,Reach-1,2433
     297     402     489     437     591     799     864
Boundary for River Rch & Prof#=UNT025 IN NNOGR,Reach-1,1
Up Type=0
Dn Type=3
Dn Slope=0.005
Boundary for River Rch & Prof#=UNT025 IN NNOGR,Reach-1,2
Up Type=0
Dn Type=3
Dn Slope=0.005
Boundary for River Rch & Prof#=UNT025 IN NNOGR,Reach-1,3
Up Type=0
Dn Type=3
Dn Slope=0.005
Boundary for River Rch & Prof#=UNT025 IN NNOGR,Reach-1,4
Up Type=0
Dn Type=3
Dn Slope=0.005
Boundary for River Rch & Prof#=UNT025 IN NNOGR,Reach-1,5
Up Type=0
Dn Type=3
Dn Slope=0.005
Boundary for River Rch & Prof#=UNT025 IN NNOGR,Reach-1,6
Up Type=0
Dn Type=3
Dn Slope=0.005
Boundary for River Rch & Prof#=UNT025 IN NNOGR,Reach-1,7
Up Type=0
Dn Type=3
Dn Slope=0.005

--- UNT025 IN NNOGR.g01 (geometry) ---

Geom Title=Existing Conditions

River Reach=UNT025 IN NNOGR,Reach-1
Reach XY= 30
      2762253.47     10103148.73      2762286.50     10103057.00
      2762327.92     10103014.78      2762375.83     10102978.77
      2762463.66     10102924.21      2762547.40     10102891.15
      2762759.52     10102766.28      2762850.96     10102728.36
      2762941.34     10102668.62      2763035.80     10102588.68
      2763079.19     10102565.49      2763174.27     10102535.67
      2763247.16     10102530.57      2763443.71     10102455.67
      2763618.44     10102431.99      2763669.76     10102406.86
      2763722.29     10102400.97      2763758.75     10102385.32
      2763859.24     10102383.62      2763880.61     10102378.00
      2763907.27     10102349.83      2763944.84     10102326.07
      2763970.86     10102300.16      2764001.26     10102234.89
      2764066.80     10102139.16      2764145.62     10102068.84
      2764237.47     10102021.26      2764310.74     10101969.72
      2764360.86     10101864.73      2764398.47     10101813.73

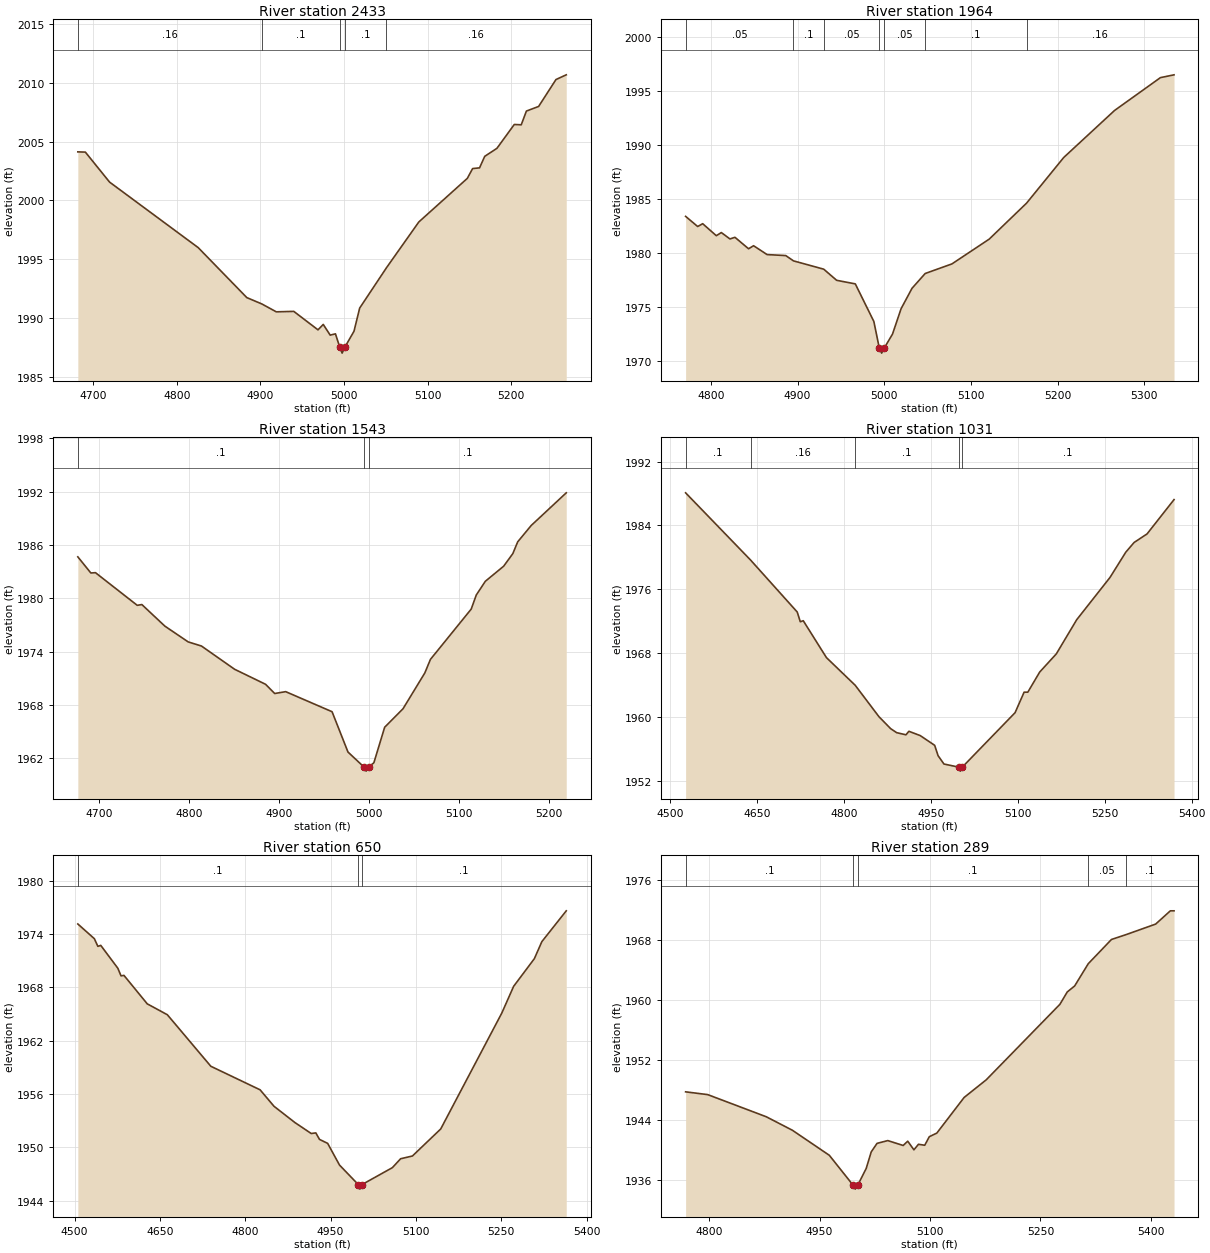
Type RM Length L Ch R = 1,2433,469,469,469
BEGIN DESCRIPTION:
UNT025 IN NNOGR 5.0
END DESCRIPTION:
XS GIS Cut Line= 2
      2762578.18     10103226.79      2762224.04     10102761.54
#Sta/Elev= 30
  4681.4 2004.13  4690.4 2004.11  4719.4 2001.56  4825.5 1995.99  4883.7 1991.74
  4901.7 1991.20  4919.0 1990.53  4939.9 1990.57  4968.9 1989.00  4975.2 1989.46
  4983.5 1988.55  4989.8 1988.66  4995.0 1987.52  4997.8 1987.02  5001.0 1987.52
  5012.0 1988.88  5018.8 1990.85  5050.9 1994.28  5089.6 1998.17  5147.7 2001.88
  5154.0 2002.71  5162.3 2002.77  5168.5 2003.75  5183.1 2004.43  5203.9 2006.46
  5212.2 2006.43  5218.4 2007.60  5233.0 2007.99  5253.8 2010.28  5266.1 2010.68
#Mann=5,-1,0
  4681.4    0.16       0  4901.7     0.1       0  4995.0    0.07       0
  5001.0     0.1       0  5050.9    0.16       0
Bank Sta=4995,5001
Exp/Cntr=0.3,0.1

Type RM Length L Ch R = 1,1964,421,421,421
BEGIN DESCRIPTION:
UNT025 IN NNOGR 4.0
END DESCRIPTION:
XS GIS Cut Line= 2
      2762911.51     10102949.00      2762626.81     10102462.94
#Sta/Elev= 30
  4770.9 1983.41  4784.8 1982.47  4790.6 1982.73  4806.3 1981.62  4812.1 1981.91
  4822.0 1981.32  4827.8 1981.47  4843.5 1980.41  4849.3 1980.69  4864.9 1979.87
  4886.4 1979.78  4895.3 1979.29  4930.2 1978.52  4945.1 1977.49  4966.6 1977.16
  4988.0 1973.68  4994.2 1971.25  4997.0 1970.75  5000.2 1971.25  5009.5 1972.51
  5019.4 1974.86  5032.0 1976.75  5047.2 1978.12  5078.1 1979.01  5121.0 1981.30
  5164.1 1984.63  5207.0 1988.86  5265.6 1993.21  5318.5 1996.25  5334.2 1996.51
#Mann=7,-1,0
  4770.9    0.05       0  4895.3     0.1       0  4930.2    0.05       0
  4994.2   0.035       0  5000.2    0.05       0  5047.2     0.1       0
  5164.1    0.16       0
Bank Sta=4994.2,5000.2
Exp/Cntr=0.3,0.1

Type RM Length L Ch R = 1,1543,512,512,512
BEGIN DESCRIPTION:
UNT025 IN NNOGR 3.0
END DESCRIPTION:
XS GIS Cut Line= 2
      2763217.06     10102858.71      2763113.18     10102325.44
#Sta/Elev= 30
  4676.4 1984.66  4690.9 1982.84  4696.0 1982.88  4742.5 1979.20  4747.6 1979.29
  4773.2 1976.86  4799.2 1975.08  4813.9 1974.62  4850.8 1972.00  4885.2 1970.31
  4895.4 1969.27  4907.6 1969.48  4959.2 1967.22  4976.9 1962.68  4994.3 1961.03
  4997.1 1960.53  5000.3 1961.03  5005.7 1961.47  5017.7 1965.47  5038.1 1967.55
  5062.4 1971.59  5068.6 1973.11  5114.0 1978.78  5119.6 1980.36  5129.7 1981.91
  5150.1 1983.61  5160.3 1985.03  5165.7 1986.35  5180.7 1988.19  5219.7 1991.87
#Mann=3,-1,0
  4676.4     0.1       0  4994.3    0.07       0  5000.3     0.1       0
Bank Sta=4994.3,5000.3
Exp/Cntr=0.3,0.1

Type RM Length L Ch R = 1,1031,381,381,381
BEGIN DESCRIPTION:
UNT025 IN NNOGR 2.0
END DESCRIPTION:
XS GIS Cut Line= 4
      2763630.35     10102885.03      2763670.72     10102541.27
      2763621.24     10102308.20      2763457.60     10102108.20
#Sta/Elev= 30
  4526.8 1988.09  4638.9 1979.67  4719.4 1973.16  4724.7 1971.94  4729.8 1972.07
  4769.8 1967.45  4819.5 1963.98  4860.4 1960.05  4880.6 1958.55  4890.9 1958.05
  4907.0 1957.78  4912.1 1958.22  4931.7 1957.68  4956.6 1956.46  4962.4 1955.17
  4972.6 1954.12  4998.2 1953.73  5000.9 1953.23  5004.2 1953.73  5095.3 1960.55
  5110.9 1963.12  5117.3 1963.12  5137.8 1965.64  5166.5 1967.92  5201.7 1972.20
  5259.1 1977.49  5286.4 1980.66  5300.7 1981.87  5323.0 1982.94  5369.6 1987.24
#Mann=5,-1,0
  4526.8     0.1       0  4638.9    0.16       0  4819.5     0.1       0
  4998.2    0.07       0  5004.2     0.1       0
Bank Sta=4998.2,5004.2
Exp/Cntr=0.3,0.1

Type RM Length L Ch R = 1,650,361,361,361
BEGIN DESCRIPTION:
Mapping XS 9c025441
END DESCRIPTION:
XS GIS Cut Line= 3
      2764182.45     10102711.89      2764096.50     10102377.21
      2763694.47     10102058.45
#Sta/Elev= 30
  4505.8 1975.15  4534.9 1973.49  4541.0 1972.63  4546.1 1972.74  4576.2 1970.16
  4581.7 1969.31  4586.9 1969.36  4627.8 1966.16  4663.2 1964.93  4739.6 1959.13
  4826.2 1956.48  4850.6 1954.63  4887.3 1952.80  4916.1 1951.56  4924.2 1951.63
  4930.6 1950.90  4945.0 1950.45  4965.8 1948.01  4999.0 1945.80  5001.7 1945.30
  5005.0 1945.80  5058.8 1947.72  5073.2 1948.72  5094.0 1949.03  5143.7 1952.07
  5251.1 1965.12  5271.9 1968.13  5308.3 1971.24  5321.5 1973.16  5364.4 1976.63
#Mann=3,-1,0
  4505.8     0.1       0  4999.0    0.07       0  5005.0     0.1       0
Bank Sta=4999,5005
Exp/Cntr=0.3,0.1

Type RM Length L Ch R = 1,289,206,206,206
BEGIN DESCRIPTION:
Mapping XS 7479c835
END DESCRIPTION:
XS GIS Cut Line= 3
      2764358.20     10102217.03      2764157.70     10101943.62
      2763833.51     10101933.20
#Sta/Elev= 30
  4768.1 1947.76  4798.1 1947.39  4877.6 1944.44  4913.1 1942.64  4963.3 1939.30
  4995.8 1935.29  4998.5 1934.79  5001.8 1935.29  5013.4 1937.55  5020.2 1939.75
  5028.1 1940.89  5042.7 1941.26  5063.6 1940.61  5069.8 1941.18  5078.2 1940.03
  5084.4 1940.77  5092.9 1940.64  5099.1 1941.78  5109.3 1942.26  5146.4 1947.01
  5176.4 1949.36  5276.5 1959.43  5286.5 1961.08  5296.5 1961.87  5315.0 1964.84
  5346.5 1968.07  5366.1 1968.71  5406.5 1970.12  5426.5 1971.89  5431.5 1971.89
#Mann=5,-1,0
  4768.1     0.1       0  4995.8    0.07       0  5001.8     0.1       0
  5315.0    0.05       0  5366.1     0.1       0
Bank Sta=4995.8,5001.8
Exp/Cntr=0.3,0.1

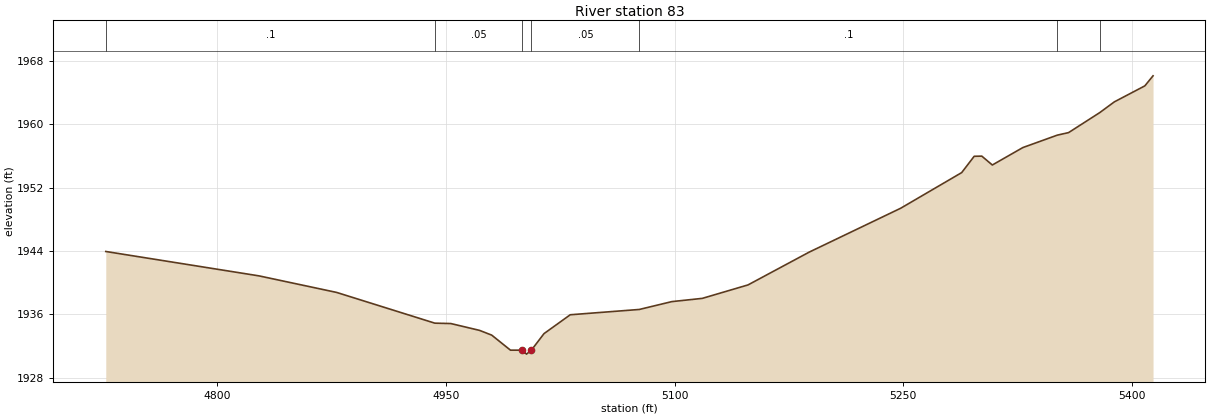
Type RM Length L Ch R = 1,83,0,0,0
BEGIN DESCRIPTION:
UNT025 IN NNOGR 1.0
END DESCRIPTION:
XS GIS Cut Line= 4
      2764425.92     10102132.40      2764380.35     10101895.44
      2764300.92     10101858.98      2763943.11     10101873.30
#Sta/Elev= 30
  4727.0 1943.94  4827.5 1940.86  4878.4 1938.77  4942.8 1934.89  4953.3 1934.84
  4972.1 1933.98  4980.1 1933.38  4992.4 1931.48  5000.1 1931.48  5002.9 1930.98
  5006.1 1931.48  5014.4 1933.57  5031.6 1935.95  5076.9 1936.62  5098.2 1937.61
  5118.2 1938.02  5148.2 1939.72  5188.3 1943.86  5248.3 1949.40  5288.3 1953.90
  5296.5 1955.96  5301.5 1955.98  5308.4 1954.86  5328.4 1957.06  5351.0 1958.63
  5358.4 1958.95  5378.8 1961.47  5388.4 1962.83  5408.4 1964.85  5413.8 1966.12
#Mann=7,-1,0
  4727.0     0.1       0  4942.8    0.05       0  5000.1   0.035       0
  5006.1    0.05       0  5076.9     0.1       0  5351.0    0.05       0
  5378.8     0.1       0
Bank Sta=5000.1,5006.1
Exp/Cntr=0.3,0.1

Chan Stop Cuts=-1