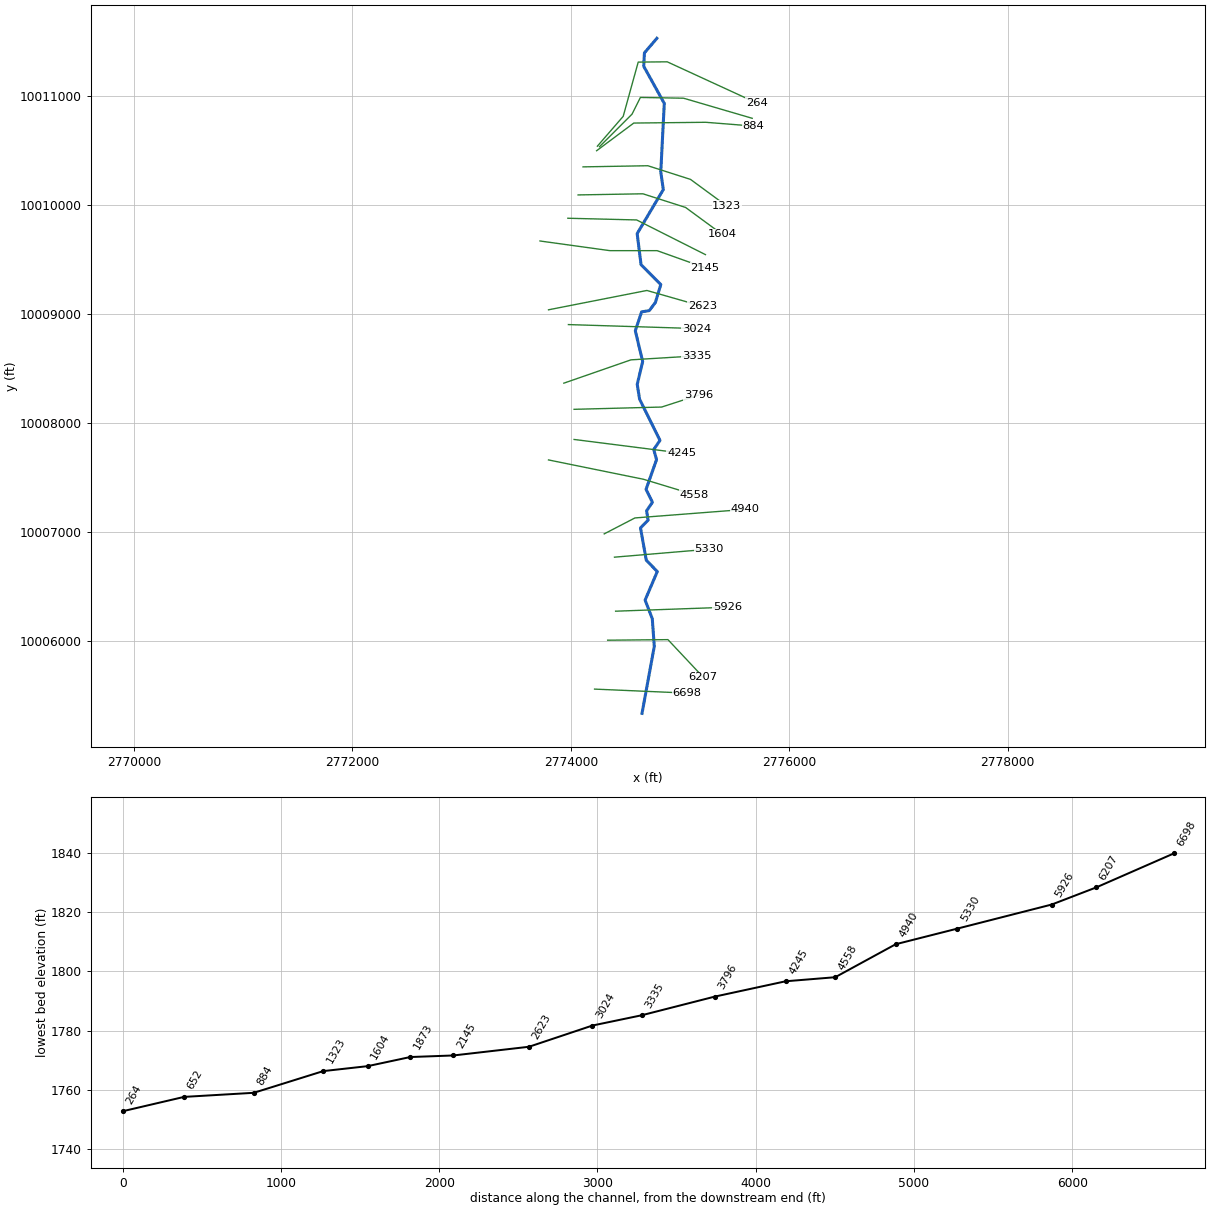
--- UNT025 IN SNOGR.prj (project) ---

Proj Title=UNT025 IN SNOGR Base Level Engineering
Current Plan=p01
Default Exp/Contr=0.3,0.1
English Units
Geom File=g01
Flow File=f01
Plan File=p01
Y Axis Title=Elevation
X Axis Title(PF)=Main Channel Distance
X Axis Title(XS)=Station
BEGIN DESCRIPTION:
UNT025 IN SNOGR
END DESCRIPTION:
DSS Export Rating Curves= 0
DSS Export Rating Curve Sorted= 0
DSS Export Volume Flow Curves= 0
DXF OffsetX= 0
DXF OffsetY= 0
DXF ScaleX= 1
DXF ScaleY= 10

--- UNT025 IN SNOGR.p01 (plan) ---

Plan Title=Multiple Run
Short Identifier=Multiple
Geom File=g01
Flow File=f01
Subcritical Flow
K Sum by GR= 0
Std Step Tol= 0.01
Critical Tol= 0.01
Num of Std Step Trials= 20
Max Error Tol= 0.3
Flow Tol Ratio= 0.001
Split Flow NTrial= 30
Split Flow Tol= 0.02
Split Flow Ratio= 0.02
Log Output Level= 0
Friction Slope Method= 1
Unsteady Friction Slope Method= 2
Unsteady Bridges Friction Slope Method= 1
Parabolic Critical Depth
Global Vel Dist=  1 , 1 , 1
Global Log Level= 0
CheckData=True
Encroach Param= -1, 0, 0, 0
BEGIN DESCRIPTION:
Multiple Run
END DESCRIPTION:

--- UNT025 IN SNOGR.f01 (steady flow) ---

Flow Title=Multiple
Program Version=4.10
Number of Profiles= 7
Profile Names=10-year,25-year,50-year,1pct_min,100-year,1pct_plu,500-year
River Rch & RM=UNT025 IN SNOGR,Reach-1         ,6698
     553     783     979     898    1214    1642    1873
River Rch & RM=UNT025 IN SNOGR,Reach-1         ,4558
     957    1397    1781    1662    2248    3040    3595
River Rch & RM=UNT025 IN SNOGR,Reach-1         ,3796
     957    1397    1781    1662    2248    3040    3595
River Rch & RM=UNT025 IN SNOGR,Reach-1         ,3335
     957    1397    1781    1662    2248    3040    3595
Boundary for River Rch & Prof#=UNT025 IN SNOGR,Reach-1         , 1
Up Type= 0
Dn Type= 3
Dn Slope=0.012
Boundary for River Rch & Prof#=UNT025 IN SNOGR,Reach-1         , 2
Up Type= 0
Dn Type= 3
Dn Slope=0.012
Boundary for River Rch & Prof#=UNT025 IN SNOGR,Reach-1         , 3
Up Type= 0
Dn Type= 3
Dn Slope=0.012
Boundary for River Rch & Prof#=UNT025 IN SNOGR,Reach-1         , 4
Up Type= 0
Dn Type= 3
Dn Slope=0.012
Boundary for River Rch & Prof#=UNT025 IN SNOGR,Reach-1         , 5
Up Type= 0
Dn Type= 3
Dn Slope=0.012
Boundary for River Rch & Prof#=UNT025 IN SNOGR,Reach-1         , 6
Up Type= 0
Dn Type= 3
Dn Slope=0.012
Boundary for River Rch & Prof#=UNT025 IN SNOGR,Reach-1         , 7
Up Type= 0
Dn Type= 3
Dn Slope=0.012
DSS Import GetInterval= 0
DSS Import GetPeak= 0
DSS Import FillOption= 0

--- UNT025 IN SNOGR.g01 (geometry) ---

Geom Title=Existing Conditions
Program Version=4.10

River Reach=UNT025 IN SNOGR ,Reach-1
Reach XY= 30
      2774652.38     10005341.23      2774764.73     10005954.72
      2774746.47     10006208.17      2774680.85     10006379.03
      2774792.17     10006639.98      2774691.25     10006744.75
      2774638.54     10007039.99      2774707.88     10007110.31
      2774694.74     10007197.47      2774747.72     10007274.45
      2774689.37     10007392.86      2774785.43     10007664.94
      2774759.62     10007757.92      2774816.91     10007841.33
      2774630.09      10008219.4      2774608.62     10008354.92
      2774658.37     10008563.55      2774590.98      10008845.5
       2774648.8     10009018.56       2774719.2     10009030.07
      2774775.03      10009105.1      2774824.37      10009268.8
      2774643.68      10009451.1      2774608.01     10009735.16
      2774847.34     10010138.74      2774824.18     10010300.51
      2774856.37     10010927.71      2774668.16      10011267.7
      2774674.54     10011390.64      2774788.47     10011523.73

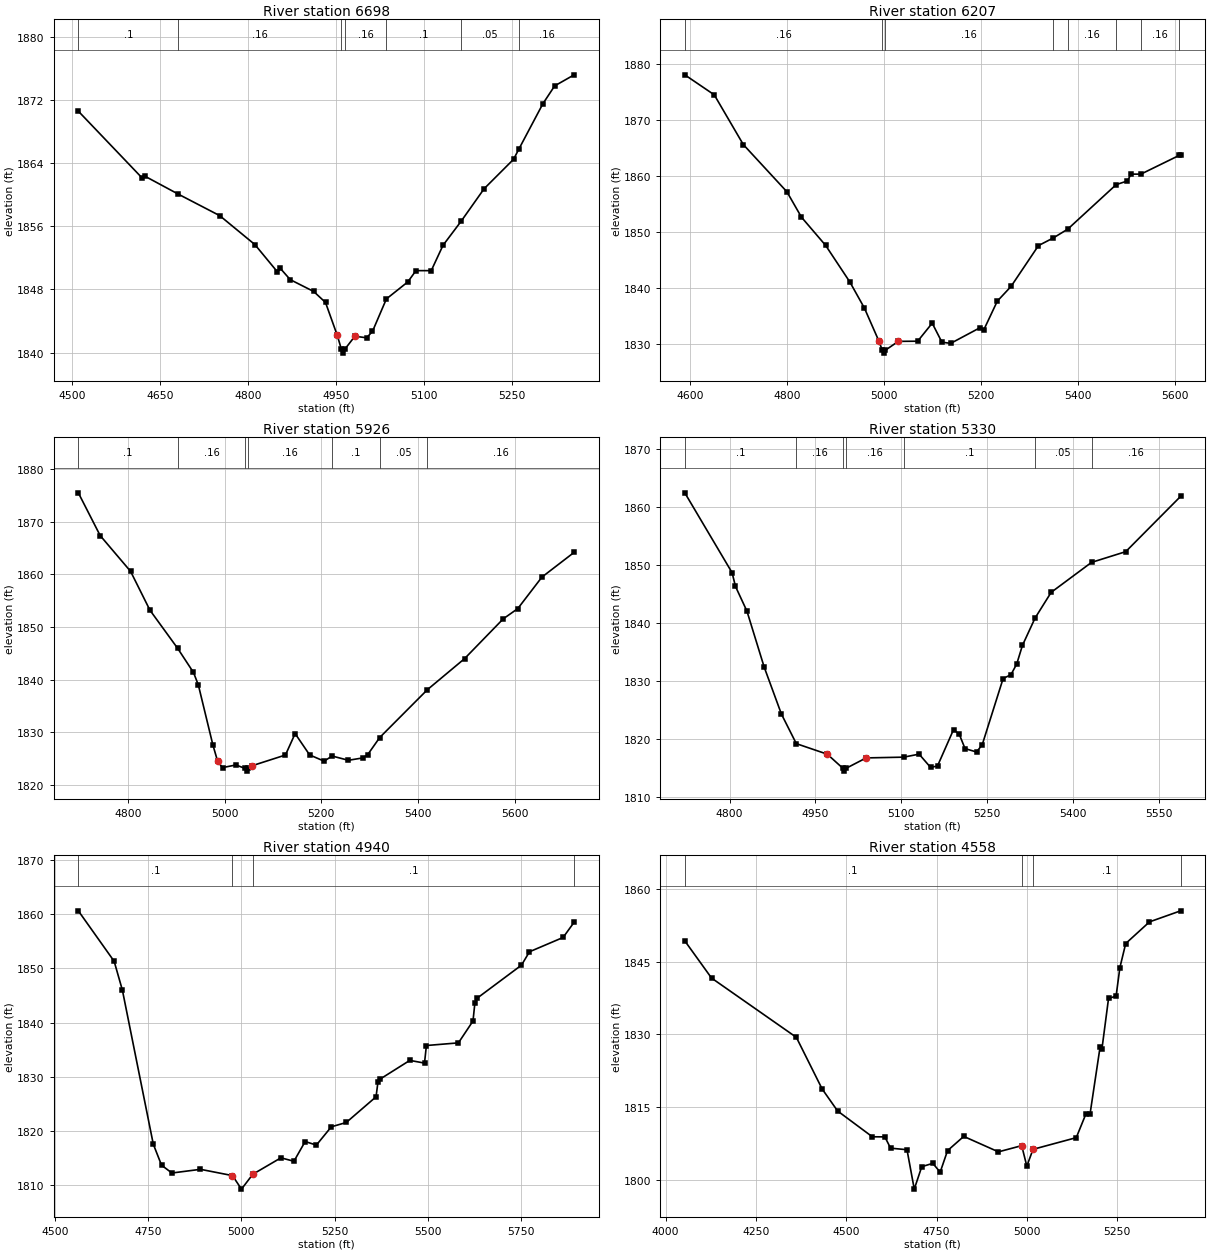
Type RM Length L Ch R = 1 ,6698    ,491,491,491
BEGIN DESCRIPTION:
UNT025 IN SNOGR 17.0
END DESCRIPTION:
XS GIS Cut Line= 2
      2774217.91     10005563.51      2775061.62     10005527.06
#Sta/Elev= 30
  4511.3 1870.55  4619.5 1862.13  4624.5 1862.33  4681.8 1860.04  4752.1 1857.33
  4812.1 1853.66  4850.5  1850.2  4855.5 1850.64  4872.2 1849.23  4912.2 1847.73
  4932.3 1846.34  4952.3 1842.18  4959.3 1840.43    4962 1839.93  4965.3 1840.43
  4982.3 1842.07  5002.3 1841.87  5012.3 1842.68    5036 1846.79  5072.4 1848.94
  5086.4 1850.37  5112.4 1850.37  5132.4 1853.57  5163.1  1856.6  5202.5 1860.74
  5252.6 1864.46  5262.1 1865.82  5302.6  1871.5  5322.6 1873.75  5355.8 1875.15
#Mann= 7 ,-1 , 0
  4511.3      .1       0  4681.8     .16       0  4959.3     .07       0
  4965.3     .16       0    5036      .1       0  5163.1     .05       0
  5262.1     .16       0
Bank Sta=4952.3,4982.3
XS Rating Curve= 0 ,0
Exp/Cntr=0.3,0.1

Type RM Length L Ch R = 1 ,6207    ,281,281,281
BEGIN DESCRIPTION:
UNT025 IN SNOGR 16.0
END DESCRIPTION:
XS GIS Cut Line= 3
      2774337.68     10006011.43      2774889.73     10006016.64
      2775212.64      10005672.9
#Sta/Elev= 30
  4588.6 1878.11  4649.4 1874.54  4709.4 1865.66  4799.4 1857.23  4829.4  1852.7
  4879.4 1847.65  4929.4 1841.12  4959.4 1836.47  4989.4 1830.56  4996.4 1828.92
  4999.2 1828.42  5002.4 1828.92  5029.4 1830.52  5069.4 1830.55  5099.4 1833.77
  5119.4 1830.38  5137.5 1830.16  5198.6 1832.98  5205.5  1832.5  5233.8  1837.7
  5262.1 1840.32  5318.8 1847.62  5349.5 1848.99  5379.3 1850.56  5479.3 1858.51
  5502.5 1859.16  5509.8 1860.38  5530.3 1860.38    5609 1863.71  5612.3 1863.71
#Mann= 8 ,-1 , 0
  4588.6     .16       0  4996.4     .07       0  5002.4     .16       0
  5349.5     .05       0  5379.3     .16       0  5479.3      .1       0
  5530.3     .16       0    5609      .1       0
Bank Sta=4989.4,5029.4
XS Rating Curve= 0 ,0
Exp/Cntr=0.3,0.1

Type RM Length L Ch R = 1 ,5926    ,596,596,596
BEGIN DESCRIPTION:
UNT025 IN SNOGR 15.0
END DESCRIPTION:
XS GIS Cut Line= 2
      2774410.54     10006277.06        2775435.     10006313.46
#Sta/Elev= 30
  4697.6 1875.49  4742.7 1867.38  4805.6 1860.58  4845.6 1853.21    4903 1845.95
  4935.7 1841.37  4945.7 1839.01  4975.7 1827.64  4985.7 1824.48  4995.7 1823.31
  5023.5 1823.81  5042.7 1823.14  5045.5 1822.64  5048.7 1823.14  5055.7 1823.63
  5125.8  1825.7  5145.8 1829.77  5175.8 1825.72  5205.8 1824.53  5222.2 1825.51
  5255.9  1824.7  5285.9 1825.15  5295.9 1825.78  5320.7 1829.02  5419.3 1838.11
    5496 1843.99  5576.1 1851.56  5606.1  1853.5  5656.1 1859.49  5722.7 1864.19
#Mann= 7 ,-1 , 0
  4697.6      .1       0    4903     .16       0  5042.7     .07       0
  5048.7     .16       0  5222.2      .1       0  5320.7     .05       0
  5419.3     .16       0
Bank Sta=4985.7,5055.7
XS Rating Curve= 0 ,0
Exp/Cntr=0.3,0.1

Type RM Length L Ch R = 1 ,5330    ,390,390,390
BEGIN DESCRIPTION:
UNT025 IN SNOGR 14.0
END DESCRIPTION:
XS GIS Cut Line= 2
      2774400.17     10006771.85       2775264.1     10006844.71
#Sta/Elev= 30
  4721.6 1862.51  4804.3 1848.73  4810.2 1846.37  4830.3 1842.09  4860.4 1832.45
  4890.5 1824.35  4916.6 1819.24  4970.8 1817.42  4997.9    1815  5000.6  1814.5
  5003.9    1815  5038.7 1816.78  5104.3 1816.91  5131.3 1817.43  5151.4 1815.14
  5163.5 1815.39  5191.6 1821.68  5201.6 1820.84  5211.6 1818.39  5231.7  1817.8
  5241.7 1819.06  5278.2 1830.47  5291.9 1831.14    5302 1832.98    5312 1836.19
  5334.1 1840.91  5362.2 1845.34  5432.8 1850.51  5492.6 1852.36  5588.6  1861.9
#Mann= 7 ,-1 , 0
  4721.6      .1       0  4916.6     .16       0  4997.9     .07       0
  5003.9     .16       0  5104.3      .1       0  5334.1     .05       0
  5432.8     .16       0
Bank Sta=4970.8,5038.7
XS Rating Curve= 0 ,0
Exp/Cntr=0.3,0.1

Type RM Length L Ch R = 1 ,4940    ,382,382,382
BEGIN DESCRIPTION:
UNT025 IN SNOGR 13.0
END DESCRIPTION:
XS GIS Cut Line= 3
       2774306.4     10006985.39      2774587.65     10007131.22
      2775598.03     10007209.35
#Sta/Elev= 30
  4562.6 1860.66  4658.7 1851.33  4680.8 1845.99  4763.7 1817.52  4785.8 1813.64
  4813.6 1812.19  4890.3 1812.87  4976.1 1811.71  5000.3 1809.21  5030.7 1811.96
  5106.2    1815    5141 1814.36  5171.1 1818.01  5201.2 1817.35  5241.3 1820.73
  5281.4 1821.53  5361.3 1826.28  5366.3 1828.95  5371.7 1829.53  5451.9 1833.01
  5491.3 1832.51  5496.4 1835.76  5582.3 1836.25  5621.4 1840.29  5626.4 1843.58
  5632.5 1844.51  5751.5 1850.62  5772.9 1853.09  5863.2 1855.74  5892.8 1858.56
#Mann= 4 ,-1 , 0
  4562.6      .1       0  4976.1     .07       0  5030.7      .1       0
  5892.8      .1       0
Bank Sta=4976.1,5030.7
XS Rating Curve= 0 ,0
Exp/Cntr=0.3,0.1

Type RM Length L Ch R = 1 ,4558    ,313,313,313
BEGIN DESCRIPTION:
UNT025 IN SNOGR 12.0
END DESCRIPTION:
XS GIS Cut Line= 3
      2773795.97     10007662.48      2774665.77     10007485.39
      2775129.36     10007344.75
#Sta/Elev= 30
    4053 1849.28    4127 1841.61  4361.7 1829.38  4433.1 1818.72  4475.9 1814.18
    4572 1808.86  4606.6 1808.84  4622.5 1806.51  4667.9 1806.19    4688 1798.06
  4708.7 1802.69  4739.3 1803.38  4759.7 1801.56  4780.1    1806  4824.9 1808.94
  4920.9 1805.75  4985.3 1807.03  4999.5  1802.8  5016.6 1806.27  5136.3 1808.68
  5162.9 1813.56  5174.4 1813.54  5202.1 1827.34  5207.3 1826.95  5225.6  1837.4
  5246.5 1837.88    5257 1843.76  5273.1 1848.73  5338.9  1853.2  5425.1 1855.48
#Mann= 4 ,-1 , 0
    4053      .1       0  4985.3     .07       0  5016.6      .1       0
  5425.1     .16       0
#XS Ineff= 1 ,-1
 4602.89  4820.41806.202
Permanent Ineff=
       T
Bank Sta=4985.3,5016.6
XS Rating Curve= 0 ,0
Exp/Cntr=0.3,0.1

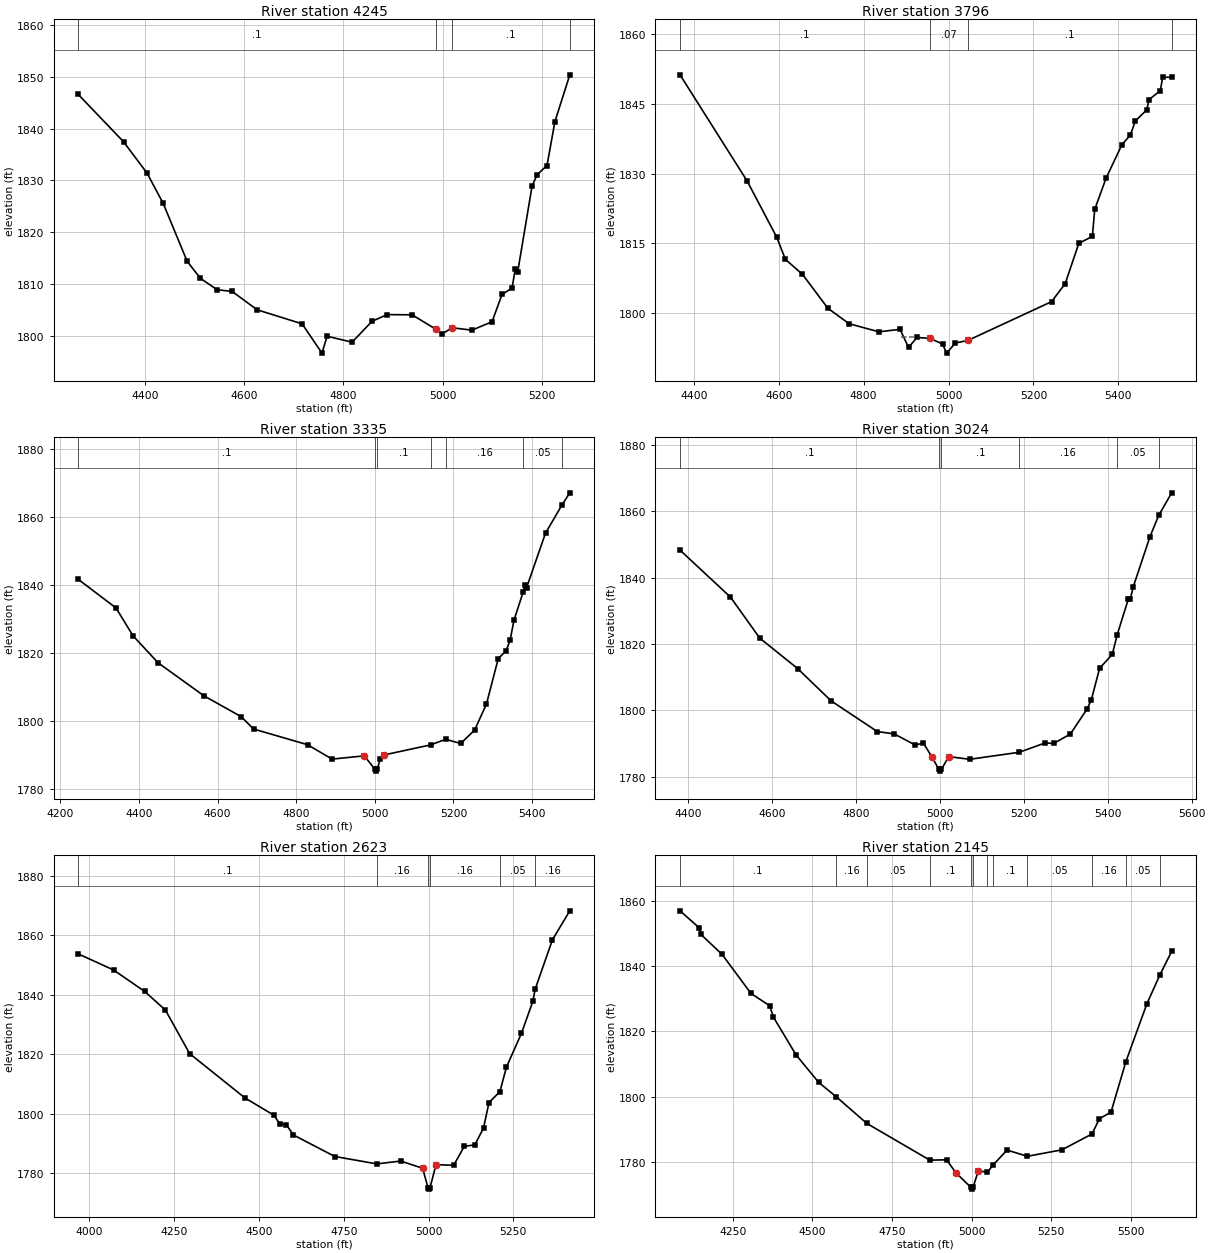
Type RM Length L Ch R = 1 ,4245    ,449,449,449
BEGIN DESCRIPTION:
UNT025 IN SNOGR 11.0
END DESCRIPTION:
XS GIS Cut Line= 2
      2774030.35     10007849.98      2775014.06     10007725.06
#Sta/Elev= 30
    4265 1846.61  4356.6 1837.46  4404.2 1831.38  4436.6 1825.56  4484.9  1814.4
  4511.5 1811.13  4545.3 1808.92  4575.6 1808.59    4626 1805.05  4716.7 1802.34
  4756.8 1796.69  4767.1 1799.95  4817.5  1798.8  4857.8 1802.83  4888.1 1804.12
  4938.5 1804.08  4986.6 1801.29    4999  1800.4  5019.1 1801.58  5059.4 1801.12
  5099.8 1802.75  5119.9 1808.01  5140.1 1809.24  5146.6 1812.87  5151.6 1812.41
  5180.4 1828.85  5190.5  1831.1  5210.6 1832.88  5226.6 1841.35  5256.6 1850.37
#Mann= 4 ,-1 , 0
    4265      .1       0  4986.6     .07       0  5019.1      .1       0
  5256.6     .05       0
#XS Ineff= 1 ,-1
 4632.98 4897.351801.543
Permanent Ineff=
       T
Bank Sta=4986.6,5019.1
XS Rating Curve= 0 ,0
Exp/Cntr=0.3,0.1

Type RM Length L Ch R = 1 ,3796    ,461,461,461
BEGIN DESCRIPTION:
UNT025 IN SNOGR 10.0
END DESCRIPTION:
XS GIS Cut Line= 3
       2774030.4     10008126.02      2774832.44     10008146.85
        2775171.     10008256.23
#Sta/Elev= 30
  4367.5 1851.16  4525.6 1828.39  4595.6 1816.29  4615.6 1811.59  4655.7 1808.41
  4715.7 1801.11  4765.7  1797.8  4835.7 1796.06  4885.7 1796.59  4905.7 1792.72
  4925.8 1794.85  4955.8 1794.66  4985.8 1793.46  4995.5 1791.49  5015.8 1793.65
  5045.8 1794.22  5242.7 1802.53  5274.7 1806.39  5306.8 1815.02  5338.8 1816.53
  5344.3 1822.31  5370.8 1828.95  5408.1 1836.14  5428.4 1838.28  5440.1  1841.3
  5466.9 1843.65  5472.2 1845.84  5498.9 1847.78  5504.2 1850.63  5525.6 1850.65
#Mann= 4 ,-1 , 0
  4367.5      .1       0  4955.8     .07       0  5045.8      .1       0
  5525.6      .1       0
#XS Ineff= 1 ,-1
 4887.97 4926.25 1794.98
Permanent Ineff=
       T
Bank Sta=4955.8,5045.8
XS Rating Curve= 0 ,0
Exp/Cntr=0.3,0.1

Type RM Length L Ch R = 1 ,3335    ,311,311,311
BEGIN DESCRIPTION:
UNT025 IN SNOGR 9.0
END DESCRIPTION:
XS GIS Cut Line= 3
      2773936.56     10008365.58      2774551.19     10008579.14
      2775150.11      10008615.6
#Sta/Elev= 30
  4245.4 1841.71  4341.9 1833.23    4385 1825.06  4448.6 1817.12    4565  1807.4
  4660.3 1801.22    4692 1797.58  4829.1 1792.97  4891.4 1788.73  4973.5 1789.69
  5000.5 1785.69  5003.3 1785.19  5006.5 1785.69  5013.6 1788.76  5023.6 1789.96
  5141.8 1792.91  5180.4 1794.55  5218.7 1793.34    5254 1797.28  5284.1 1804.96
  5314.1 1818.33  5334.2 1820.66  5344.2 1823.72  5354.2 1829.69  5377.5 1837.95
  5381.2 1839.96  5386.2 1839.25  5434.3 1855.29  5476.1 1863.56  5496.1 1867.16
#Mann= 7 ,-1 , 0
  4245.4      .1       0  5000.5     .07       0  5006.5      .1       0
  5141.8     .05       0  5180.4     .16       0  5377.5     .05       0
  5476.1     .16       0
Bank Sta=4973.5,5023.6
XS Rating Curve= 0 ,0
Exp/Cntr=0.3,0.1

Type RM Length L Ch R = 1 ,3024    ,401,401,401
BEGIN DESCRIPTION:
UNT025 IN SNOGR 8.0
END DESCRIPTION:
XS GIS Cut Line= 2
      2773978.23     10008902.06      2775150.16      10008865.6
#Sta/Elev= 30
  4379.9 1848.25  4500.2  1834.1  4570.2 1821.74  4660.3  1812.6  4740.3 1802.86
  4850.4 1793.63  4890.4 1792.94  4940.4  1789.6  4960.4 1790.14  4980.4 1786.02
  4997.4 1782.22  5000.2 1781.72  5003.4 1782.22  5020.4  1786.1  5070.5 1785.28
  5188.7 1787.39  5250.6 1790.21  5270.6 1790.04  5310.6 1792.87  5350.6 1800.42
  5360.6 1803.13  5380.6 1812.72  5410.6 1816.83  5422.6 1822.85  5448.7 1833.39
  5453.7 1833.56  5460.7  1837.2  5500.7 1852.34  5521.4  1858.7  5552.4  1865.5
#Mann= 6 ,-1 , 0
  4379.9      .1       0  4997.4     .07       0  5003.4      .1       0
  5188.7     .16       0  5422.6     .05       0  5521.4     .16       0
Bank Sta=4980.4,5020.4
XS Rating Curve= 0 ,0
Exp/Cntr=0.3,0.1

Type RM Length L Ch R = 1 ,2623    ,478,478,478
BEGIN DESCRIPTION:
UNT025 IN SNOGR 7.0
END DESCRIPTION:
XS GIS Cut Line= 3
      2773796.02     10009037.48      2774697.02     10009214.56
      2775207.46     10009068.72
#Sta/Elev= 30
  3967.3 1853.81  4071.7 1848.36  4163.4 1841.14  4224.6 1834.86  4295.9 1820.19
    4459 1805.26  4544.9  1799.4  4560.9 1796.58  4581.3 1796.19  4601.7 1792.79
    4724 1785.53  4847.5 1783.04  4918.2    1784  4982.7 1781.56  4998.4 1775.04
  5001.2 1774.54  5004.4 1775.04  5022.2 1782.78  5074.2 1782.58  5105.4 1788.93
  5136.6 1789.47  5162.1 1795.11  5178.2  1803.7  5210.3 1807.36  5229.7 1815.64
  5273.9 1827.03  5307.7 1837.87  5314.2 1841.86  5365.4 1858.58  5416.4 1868.29
#Mann= 6 ,-1 , 0
  3967.3      .1       0  4847.5     .16       0  4998.4     .07       0
  5004.4     .16       0  5210.3     .05       0  5314.2     .16       0
Bank Sta=4982.7,5022.2
XS Rating Curve= 0 ,0
Exp/Cntr=0.3,0.1

Type RM Length L Ch R = 1 ,2145    ,272,272,272
BEGIN DESCRIPTION:
UNT025 IN SNOGR 6.0
END DESCRIPTION:
XS GIS Cut Line= 4
      2773717.82     10009667.69      2774358.48     10009579.14
      2774790.77     10009579.14      2775228.27     10009422.89
#Sta/Elev= 30
  4084.7 1856.95  4145.5  1851.7  4150.5 1849.69  4216.6  1843.6  4307.4 1831.62
  4366.1 1827.84  4378.1 1824.32  4448.8 1812.79  4519.9 1804.34    4575 1799.94
  4671.1 1791.76  4868.9 1780.49  4921.4 1780.59  4951.4 1776.54  4998.4  1772.1
  5001.2  1771.6  5004.4  1772.1  5021.4 1777.23  5049.5 1776.79  5068.6  1779.1
  5111.4 1783.58    5175 1781.67  5283.6 1783.65  5378.2 1788.52  5401.5 1793.23
  5437.6 1795.18  5484.6 1810.74  5550.2  1828.4    5591 1837.26  5628.3 1844.55
#Mann= 12 ,-1 , 0
  4084.7      .1       0    4575     .16       0  4671.1     .05       0
  4868.9      .1       0  4998.4     .07       0  5004.4      .1       0
  5049.5     .16       0  5068.6      .1       0    5175     .05       0
  5378.2     .16       0  5484.6     .05       0    5591     .16       0
Bank Sta=4951.4,5021.4
XS Rating Curve= 0 ,0
Exp/Cntr=0.3,0.1

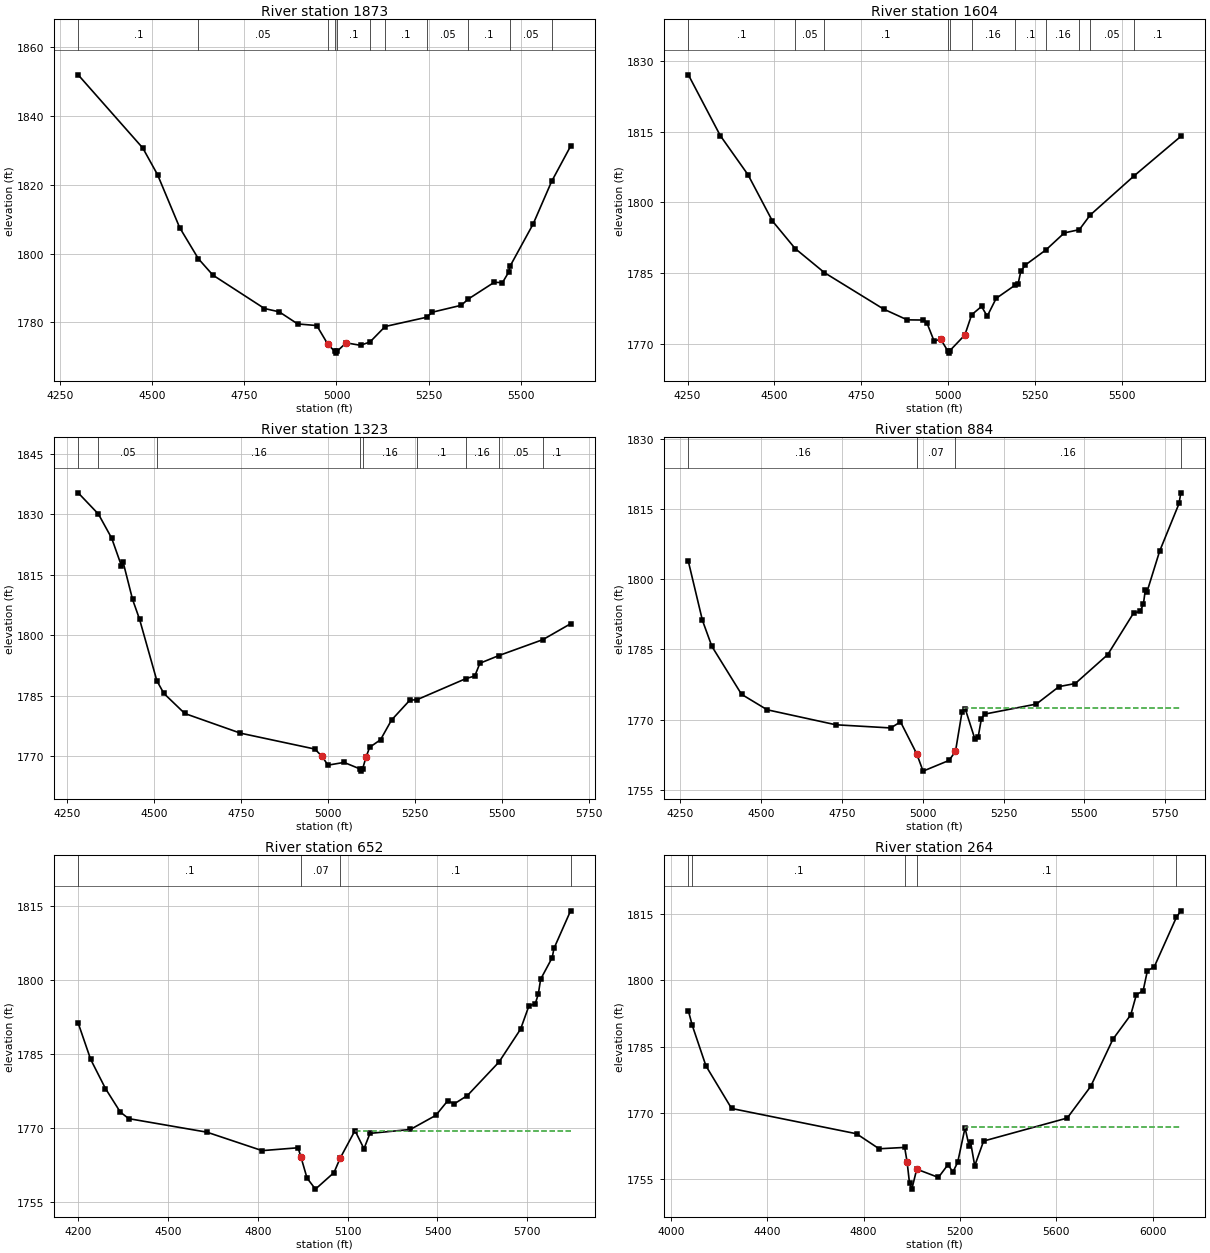
Type RM Length L Ch R = 1 ,1873    ,269,269,269
BEGIN DESCRIPTION:
UNT025 IN SNOGR 5.0
END DESCRIPTION:
XS GIS Cut Line= 3
      2773973.11     10009876.02      2774603.27     10009860.39
      2775233.46     10009542.69
#Sta/Elev= 30
  4299.1 1851.99  4474.5  1830.7  4514.5 1822.95  4574.5 1807.57  4625.3 1798.51
  4664.6 1793.76  4804.6 1784.04  4844.6 1783.08  4894.6 1779.56  4946.5 1779.09
    4976 1773.75  4976.6 1773.64  4995.3 1771.57  4998.1 1771.07  5001.3 1771.57
  5026.2 1774.06  5065.2 1773.34  5091.1 1774.33    5132 1778.81  5244.9 1781.51
    5260 1782.97  5338.5 1784.98  5357.8 1786.81    5428 1791.66  5450.4 1791.58
  5466.8 1794.53  5470.8 1796.31  5533.7 1808.63  5583.7 1820.98  5635.2 1831.24
#Mann= 11 ,-1 , 0
  4299.1      .1       0  4625.3     .05       0  4976.6      .1       0
  4995.3     .07       0  5001.3      .1       0  5091.1     .16       0
    5132      .1       0  5244.9     .05       0  5357.8      .1       0
  5470.8     .05       0  5583.7      .1       0
Bank Sta=4976,5026.2
XS Rating Curve= 0 ,0
Exp/Cntr=0.3,0.1

Type RM Length L Ch R = 1 ,1604    ,281,281,281
BEGIN DESCRIPTION:
UNT025 IN SNOGR 4.0
END DESCRIPTION:
XS GIS Cut Line= 4
       2774066.8     10010089.56      2774660.57     10010099.97
      2775051.19     10009974.97        2775384.     10009730.57
#Sta/Elev= 30
  4252.4 1827.11  4344.1 1814.21  4424.1 1805.87  4494.1 1796.07  4559.6 1790.21
    4644 1785.08  4814.1 1777.35    4882 1775.06    4928 1775.02  4938.5 1774.46
  4959.5 1770.54  4978.4 1770.96  4998.5 1768.49  5001.3 1767.99  5004.5 1768.49
    5048 1771.85  5067.5 1776.14    5096 1777.91  5112.3 1775.83    5138 1779.62
  5191.2 1782.36    5201 1782.64  5208.8 1785.34    5222 1786.71  5281.9 1789.96
  5334.1 1793.53  5377.4 1794.22  5408.3  1797.3  5534.8 1805.64  5669.3 1814.03
#Mann= 11 ,-1 , 0
  4252.4      .1       0  4559.6     .05       0    4644      .1       0
  4998.5     .07       0  5004.5      .1       0  5067.5     .16       0
  5191.2      .1       0  5281.9     .16       0  5377.4      .1       0
  5408.3     .05       0  5534.8      .1       0
Bank Sta=4978.4,5048
XS Rating Curve= 0 ,0
Exp/Cntr=0.3,0.1

Type RM Length L Ch R = 1 ,1323    ,439,439,439
BEGIN DESCRIPTION:
UNT025 IN SNOGR 3.0
END DESCRIPTION:
XS GIS Cut Line= 4
      2774111.96      10010346.5      2774705.71     10010356.92
      2775096.33     10010231.92      2775428.58     10009987.92
#Sta/Elev= 30
    4281 1835.26  4339.3 1829.99  4377.5 1824.01  4405.3 1817.21  4410.3 1818.09
  4437.5 1808.84  4457.5 1803.95  4507.5 1788.66  4527.5 1785.56  4587.6 1780.59
  4747.6 1775.72  4961.7 1771.78  4982.7 1769.94  4999.3 1767.79  5045.7 1768.47
  5092.8 1766.81  5095.5 1766.31  5098.8 1766.81  5108.7 1769.69  5119.2  1772.2
  5150.7  1774.1  5182.2 1778.96  5234.9 1783.89  5255.7 1784.01  5395.5 1789.21
  5421.7 1789.88  5436.4 1793.04  5491.2 1794.95  5617.6 1798.89  5697.2 1802.82
#Mann= 9 ,-1 , 0
    4281      .1       0  4339.3     .05       0  4507.5     .16       0
  5092.8     .07       0  5098.8     .16       0  5255.7      .1       0
  5395.5     .16       0  5491.2     .05       0  5617.6      .1       0
Bank Sta=4982.7,5108.7
XS Rating Curve= 0 ,0
Exp/Cntr=0.3,0.1

Type RM Length L Ch R = 1 ,884     ,440,440,440
BEGIN DESCRIPTION:
UNT025 IN SNOGR 2.0
END DESCRIPTION:
XS GIS Cut Line= 4
      2774236.62     10010494.38      2774576.91     10010747.86
      2775236.63     10010754.81      2775673.77     10010720.11
#Sta/Elev= 30
  4275.4 1803.84  4318.8 1791.25    4348 1785.68  4439.8 1775.41    4519  1772.1
  4731.3 1768.89  4901.3 1768.21  4931.3 1769.52  4981.3  1762.7  5001.1 1758.97
  5081.3 1761.26  5101.3 1763.19  5121.3 1771.53  5131.3 1772.34  5161.3 1765.85
  5171.3 1766.21  5181.3 1770.12  5191.3 1771.17  5351.3 1773.32  5421.5 1777.06
  5471.7 1777.72    5572  1783.9  5652.2 1792.82  5672.3 1793.14  5682.3  1794.7
  5688.2 1797.71  5693.2 1797.28  5732.5 1806.03  5792.7 1816.26    5798 1818.53
#Mann= 4 ,-1 , 0
  4275.4     .16       0  4981.3     .07       0  5101.3     .16       0
    5798      .1       0
#XS Ineff= 2 , 0
                         5129.09         1772.43
Permanent Ineff=
       T       T
Bank Sta=4981.3,5101.3
XS Rating Curve= 0 ,0
Exp/Cntr=0.3,0.1

Type RM Length L Ch R = 1 ,652     ,388,388,388
XS GIS Cut Line= 5
      2774262.52     10010530.91      2774561.11     10010829.51
       2774637.5     10010982.28      2775033.33     10010975.34
      2775661.76     10010791.32
#Sta/Elev= 30
  4200.6 1791.29  4242.2 1783.93  4291.7    1778  4341.2 1773.23  4369.4 1771.89
  4630.7 1769.14  4814.7  1765.4  4934.7 1765.98  4944.7 1764.01  4964.7 1759.82
  4992.7 1757.59  5054.7 1760.95  5074.7 1763.81  5124.7 1769.47  5154.7 1765.78
  5174.7  1768.9  5309.5 1769.69  5394.6 1772.56  5434.6 1775.54  5455.4 1774.87
    5500 1776.58  5605.5 1783.38  5677.6 1790.06  5705.5  1794.8  5726.3 1795.14
  5736.8  1797.2  5744.4 1800.17  5783.1 1804.56  5788.9 1806.42  5844.4 1814.05
#Mann= 4 ,-1 , 0
  4200.6      .1       0  4944.7     .07       0  5074.7      .1       0
  5844.4      .1       0
#XS Ineff= 2 , 0
                          5125.6          1769.4
Permanent Ineff=
       F       F
Bank Sta=4944.7,5074.7
XS Rating Curve= 0 ,0
Exp/Cntr=0.3,0.1

Type RM Length L Ch R = 1 ,264     ,0,0,0
XS GIS Cut Line= 5
      2774243.56     10010536.03      2774480.05     10010809.18
      2774617.54     10011306.07      2774883.16     10011308.67
      2775701.93     10010931.88
#Sta/Elev= 30
  4072.7 1793.08  4088.7 1789.82  4145.7 1780.62  4252.1 1770.99  4770.7 1765.27
  4864.3 1761.87  4970.5 1762.18  4980.5 1758.91  4990.5  1754.1  5000.2 1752.74
  5020.5 1757.26  5110.5 1755.39  5150.5  1758.3  5170.5 1756.59  5190.5 1758.82
    5221 1766.62  5238.3 1762.39  5243.8 1763.45  5261.2 1758.02  5298.1 1763.62
  5645.2 1768.83  5742.6 1775.99  5834.5 1786.64  5908.9 1792.19  5931.9 1796.71
  5960.3 1797.65  5977.8 1802.15  6006.3 1803.04  6098.1 1814.23  6116.5 1815.72
#Mann= 5 ,-1 , 0
  4072.7     .16       0  4088.7      .1       0  4970.5     .07       0
  5020.5      .1       0  6098.1      .1       0
#XS Ineff= 2 , 0
                         5222.14         1766.87
Permanent Ineff=
       F       F
Bank Sta=4980.5,5020.5
XS Rating Curve= 0 ,0
Exp/Cntr=0.3,0.1

Chan Stop Cuts=-1
Use User Specified Reach Order=0
Composite Channel Slope=5