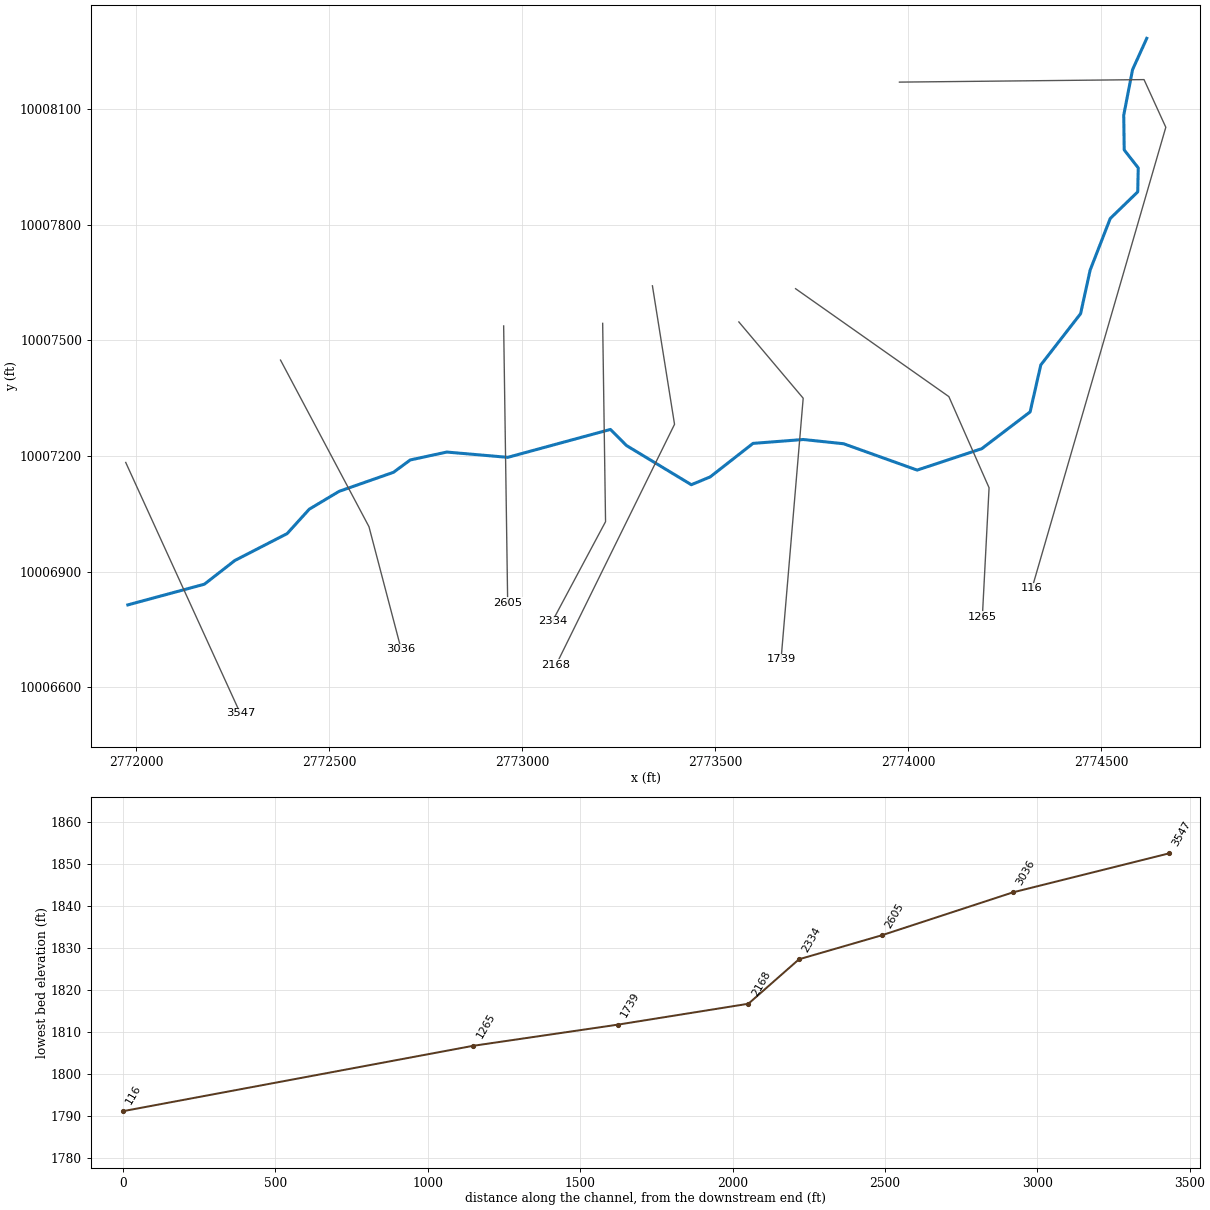
--- UNT026 IN SNOGR.prj (project) ---

Proj Title=UNT026 IN SNOGR Base Level Engineering
Current Plan=p01
Default Exp/Contr=0.3,0.1
English Units
Geom File=g01
Flow File=f01
Plan File=p01
Y Axis Title=Elevation
X Axis Title(PF)=Main Channel Distance
X Axis Title(XS)=Station
BEGIN DESCRIPTION:
UNT026 IN SNOGR
END DESCRIPTION:
DSS Export Rating Curves= 0
DSS Export Rating Curve Sorted= 0
DSS Export Volume Flow Curves= 0
DXF OffsetX= 0
DXF OffsetY= 0
DXF ScaleX= 1
DXF ScaleY= 10

--- UNT026 IN SNOGR.p01 (plan) ---

Plan Title=Multiple Run
Short Identifier=Multiple
Geom File=g01
Flow File=f01
Subcritical Flow
K Sum by GR= 0
Std Step Tol= 0.01
Critical Tol= 0.01
Num of Std Step Trials= 20
Max Error Tol= 0.3
Flow Tol Ratio= 0.001
Split Flow NTrial= 30
Split Flow Tol= 0.02
Split Flow Ratio= 0.02
Log Output Level= 0
Friction Slope Method= 1
Unsteady Friction Slope Method= 2
Unsteady Bridges Friction Slope Method= 1
Parabolic Critical Depth
Global Vel Dist=  1 , 1 , 1
Global Log Level= 0
CheckData=True
Encroach Param= -1, 0, 0, 0
BEGIN DESCRIPTION:
Multiple Run
END DESCRIPTION:

--- UNT026 IN SNOGR.f01 (steady flow) ---

Flow Title=Multiple
Program Version=4.10
Number of Profiles= 7
Profile Names=10-year,25-year,50-year,1pct_min,100-year,1pct_plu,500-year
River Rch & RM=UNT026 IN SNOGR,Reach-1         ,3547
     452     631     780     709     959    1296    1450
Boundary for River Rch & Prof#=UNT026 IN SNOGR,Reach-1         , 1
Up Type= 0
Dn Type= 3
Dn Slope=0.014
Boundary for River Rch & Prof#=UNT026 IN SNOGR,Reach-1         , 2
Up Type= 0
Dn Type= 3
Dn Slope=0.014
Boundary for River Rch & Prof#=UNT026 IN SNOGR,Reach-1         , 3
Up Type= 0
Dn Type= 3
Dn Slope=0.014
Boundary for River Rch & Prof#=UNT026 IN SNOGR,Reach-1         , 4
Up Type= 0
Dn Type= 3
Dn Slope=0.014
Boundary for River Rch & Prof#=UNT026 IN SNOGR,Reach-1         , 5
Up Type= 0
Dn Type= 3
Dn Slope=0.014
Boundary for River Rch & Prof#=UNT026 IN SNOGR,Reach-1         , 6
Up Type= 0
Dn Type= 3
Dn Slope=0.014
Boundary for River Rch & Prof#=UNT026 IN SNOGR,Reach-1         , 7
Up Type= 0
Dn Type= 3
Dn Slope=0.014
DSS Import GetInterval= 0
DSS Import GetPeak= 0
DSS Import FillOption= 0

--- UNT026 IN SNOGR.g01 (geometry) ---

Geom Title=Existing Conditions
Program Version=4.10

River Reach=UNT026 IN SNOGR ,Reach-1
Reach XY= 30
      2771978.47     10006813.73      2772176.93     10006867.45
      2772255.74     10006928.93      2772391.22     10006998.71
      2772448.55     10007062.01       2772525.9     10007108.36
       2772666.8     10007157.77      2772710.15     10007189.77
      2772804.87     10007210.29       2772962.9     10007196.58
      2773228.81       10007269.      2773270.56     10007227.13
      2773438.45     10007125.56      2773487.45     10007145.88
      2773598.34      10007232.8      2773728.47     10007242.88
      2773832.98     10007231.87      2774023.58      10007163.5
      2774190.94     10007219.03      2774316.23      10007314.5
      2774343.83     10007436.22        2774447.     10007569.34
      2774471.72     10007682.38      2774523.84     10007816.35
      2774595.04     10007885.42      2774596.35     10007947.54
        2774560.     10007994.17      2774558.77     10008084.33
      2774581.61     10008202.43      2774618.47     10008283.73

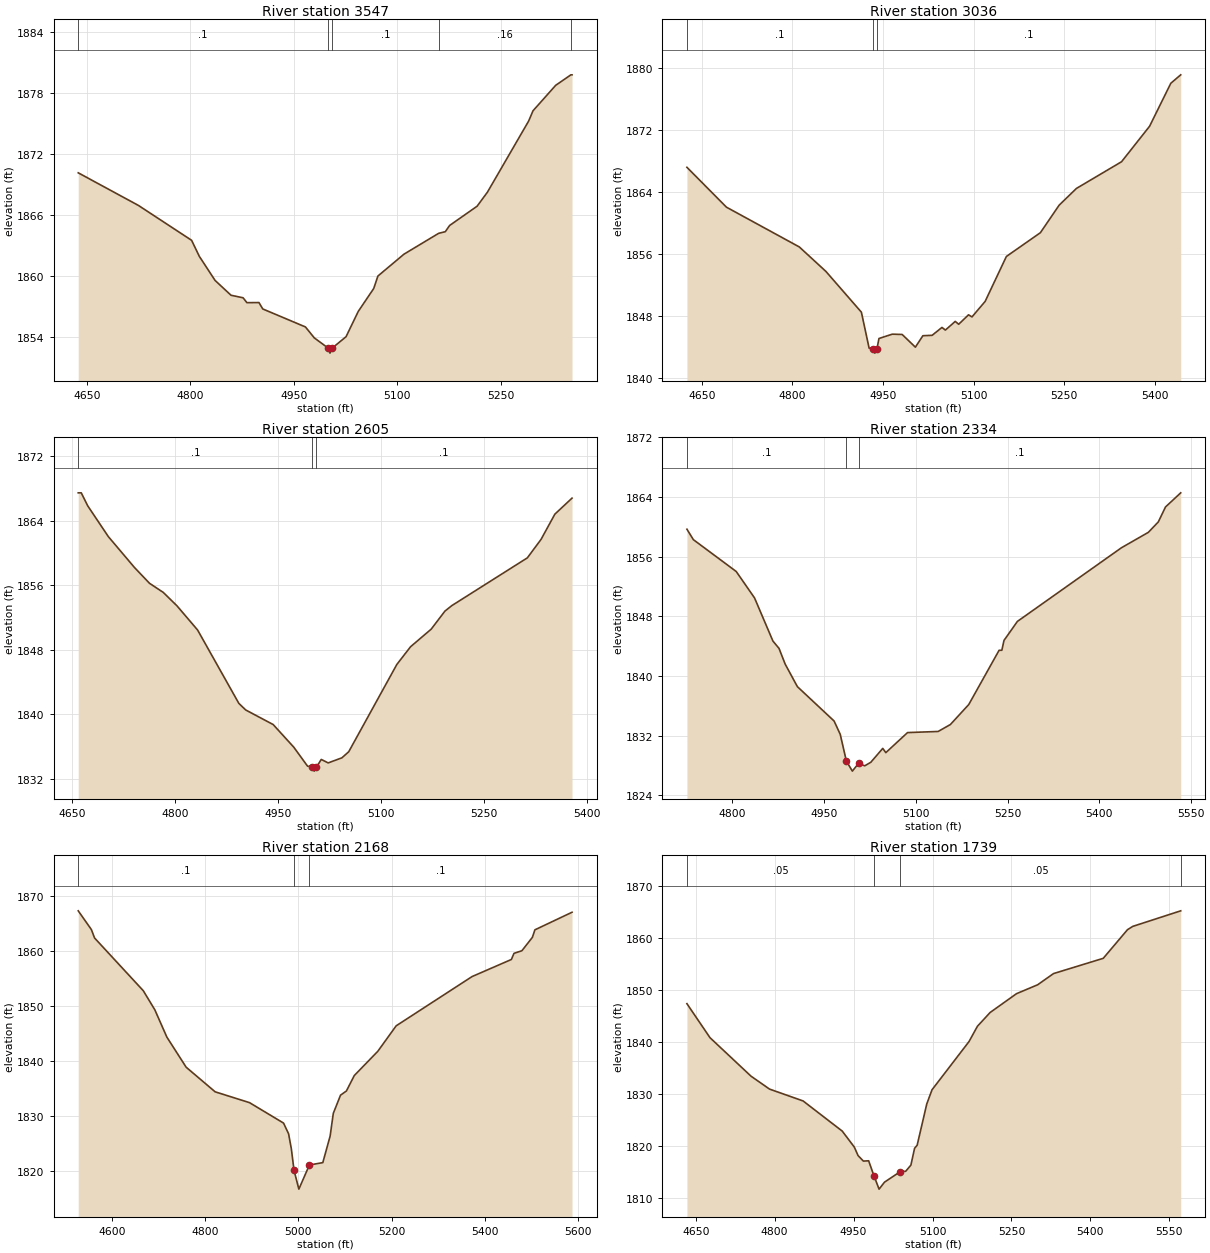
Type RM Length L Ch R = 1 ,3547    ,511,511,511
BEGIN DESCRIPTION:
UNT026 IN SNOGR 5.0
END DESCRIPTION:
XS GIS Cut Line= 2
      2771973.07      10007183.3      2772269.93     10006532.29
#Sta/Elev= 30
  4637.5 1870.18  4724.9 1866.96  4801.8 1863.53  4812.9 1861.96  4835.8 1859.58
  4858.9 1858.12  4876.4 1857.87  4881.9 1857.39  4899.4  1857.4  4904.9 1856.77
  4966.7    1855  4979.6 1853.92  4999.6 1852.92  5002.3 1852.42  5005.6 1852.92
  5025.6 1854.04  5043.2 1856.52  5065.7 1858.79  5071.7 1860.01  5109.6 1862.17
  5159.8 1864.22  5169.4 1864.38  5175.6 1864.99  5215.5 1866.89  5230.5 1868.28
  5290.1 1875.27  5296.5 1876.29  5329.4  1878.8  5351.4 1879.83    5353 1879.83
#Mann= 5 ,-1 , 0
  4637.5      .1       0  4999.6     .07       0  5005.6      .1       0
  5159.8     .16       0  5351.4      .1       0
Bank Sta=4999.6,5005.6
XS Rating Curve= 0 ,0
Exp/Cntr=0.3,0.1

Type RM Length L Ch R = 1 ,3036    ,431,431,431
BEGIN DESCRIPTION:
Mapping XS 6ef60f80
END DESCRIPTION:
XS GIS Cut Line= 3
       2772374.1     10007448.94      2772603.27     10007016.64
       2772686.6     10006698.98
#Sta/Elev= 30
  4625.2 1867.17  4690.6 1862.02  4811.3 1856.88  4855.3 1853.72  4914.1 1848.45
  4926.9  1843.8  4933.7 1843.66  4936.4 1843.16  4939.7 1843.66  4943.2 1845.05
  4965.2 1845.61  4981.6 1845.57  5003.5 1843.93  5015.9 1845.41  5031.2 1845.46
  5047.5 1846.48  5053.2 1846.14  5069.5 1847.26  5075.2 1846.89  5091.5 1848.11
  5097.2 1847.84    5119 1849.84  5154.2 1855.65  5210.5 1858.72  5241.6 1862.28
  5270.2 1864.44  5344.9 1867.89  5391.3 1872.47  5426.5 1878.03  5442.9 1879.12
#Mann= 3 ,-1 , 0
  4625.2      .1       0  4933.7     .07       0  4939.7      .1       0
Bank Sta=4933.7,4939.7
XS Rating Curve= 0 ,0
Exp/Cntr=0.3,0.1

Type RM Length L Ch R = 1 ,2605    ,271,271,271
BEGIN DESCRIPTION:
UNT026 IN SNOGR 4.0
END DESCRIPTION:
XS GIS Cut Line= 2
      2772952.23     10007537.49      2772962.65     10006818.76
#Sta/Elev= 30
  4658.8 1867.47  4663.2 1867.47  4672.6 1865.86  4702.6 1862.04  4740.7  1858.2
  4762.6 1856.24  4782.6 1855.11  4802.6 1853.44  4832.6 1850.44  4892.6 1841.34
  4902.6 1840.52  4942.6 1838.71  4972.6  1835.9  4992.6 1833.55  4999.6 1833.43
  5002.3 1832.93  5005.6 1833.43  5012.6 1834.38  5022.6 1833.95  5042.6 1834.58
  5052.6 1835.34  5122.6 1846.17  5142.6 1848.37  5172.6 1850.55  5192.6 1852.79
  5202.6 1853.47  5312.6  1859.4  5332.6  1861.7  5352.6 1864.82  5377.6 1866.81
#Mann= 3 ,-1 , 0
  4658.8      .1       0  4999.6     .07       0  5005.6      .1       0
Bank Sta=4999.6,5005.6
XS Rating Curve= 0 ,0
Exp/Cntr=0.3,0.1

Type RM Length L Ch R = 1 ,2334    ,166,166,166
BEGIN DESCRIPTION:
UNT026 IN SNOGR 444.0
END DESCRIPTION:
XS GIS Cut Line= 3
      2773208.76     10007544.23      2773216.22     10007029.66
      2773078.69     10006771.76
#Sta/Elev= 30
    4726 1859.68  4736.5 1858.28  4806.5 1854.01  4836.5 1850.46  4866.5 1844.68
  4876.5 1843.69  4886.5 1841.59  4906.5 1838.56  4966.5 1833.95  4976.5 1832.17
  4986.5 1828.59  4996.3 1827.23  5006.5 1828.28  5016.5 1827.94  5026.5 1828.42
    5046 1830.28    5051 1829.71  5086.5  1832.4  5136.5 1832.55  5156.5 1833.48
  5186.5 1836.16  5236.1 1843.44  5240.6 1843.44  5244.1 1844.76    5266 1847.31
    5436 1857.19    5480 1859.26  5496.3 1860.66    5508 1862.66  5532.9 1864.56
#Mann= 3 , 0 , 0
    4726      .1       0  4986.5     .05       0  5006.5      .1       0
Bank Sta=4986.5,5006.5
XS Rating Curve= 0 ,0
Exp/Cntr=0.3,0.1

Type RM Length L Ch R = 1 ,2168    ,429,429,429
BEGIN DESCRIPTION:
UNT026 IN SNOGR 3.0
END DESCRIPTION:
XS GIS Cut Line= 3
      2773337.66      10007641.6      2773394.94     10007282.27
      2773088.02     10006658.01
#Sta/Elev= 30
  4527.8 1867.33    4556 1863.92  4562.9 1862.38  4667.4 1852.78  4692.2  1849.3
    4718 1844.33  4759.4 1838.85  4821.6 1834.37  4895.3  1832.4  4968.3 1828.68
  4979.2 1826.72  4985.2 1823.93  4990.8 1820.08  5001.2 1816.65  5023.8 1821.04
  5052.6 1821.48  5068.3 1826.31  5075.1 1830.45  5090.6 1833.76  5103.2 1834.52
  5120.1 1837.33  5170.6 1841.75    5210 1846.39  5372.9 1855.36  5457.2 1858.47
  5462.8 1859.59  5479.7 1860.06  5502.2 1862.49  5507.7 1863.87  5587.3 1867.07
#Mann= 3 , 0 , 0
  4527.8      .1       0  4990.8     .05       0  5023.8      .1       0
Bank Sta=4990.8,5023.8
XS Rating Curve= 0 ,0
Exp/Cntr=0.3,0.1

Type RM Length L Ch R = 1 ,1739    ,474,474,474
BEGIN DESCRIPTION:
UNT026 IN SNOGR 2.0
END DESCRIPTION:
XS GIS Cut Line= 3
       2773561.6      10007547.9      2773728.27     10007349.97
      2773670.98     10006672.85
#Sta/Elev= 30
  4633.3  1847.4  4677.1 1840.85  4755.1 1833.43  4790.3 1830.94    4854 1828.66
  4928.4 1822.85  4951.3 1819.78  4958.5 1818.13  4968.6 1817.07  4978.6 1817.13
  4988.6 1814.26  4998.4 1811.67  5008.7 1813.01  5038.8 1815.05  5048.9  1815.1
  5058.9  1816.3  5065.8 1819.52  5070.8 1820.14    5089 1828.07    5099 1830.81
  5169.3  1840.1  5185.3 1843.05  5209.4  1845.7  5259.6 1849.33  5299.7 1851.04
  5329.9  1853.2  5424.4 1856.14  5470.4 1861.65  5480.4 1862.29  5571.6 1865.29
#Mann= 4 ,-1 , 0
  4633.3     .05       0  4988.6    .035       0  5038.8     .05       0
  5571.6      .1       0
Bank Sta=4988.6,5038.8
XS Rating Curve= 0 ,0
Exp/Cntr=0.3,0.1

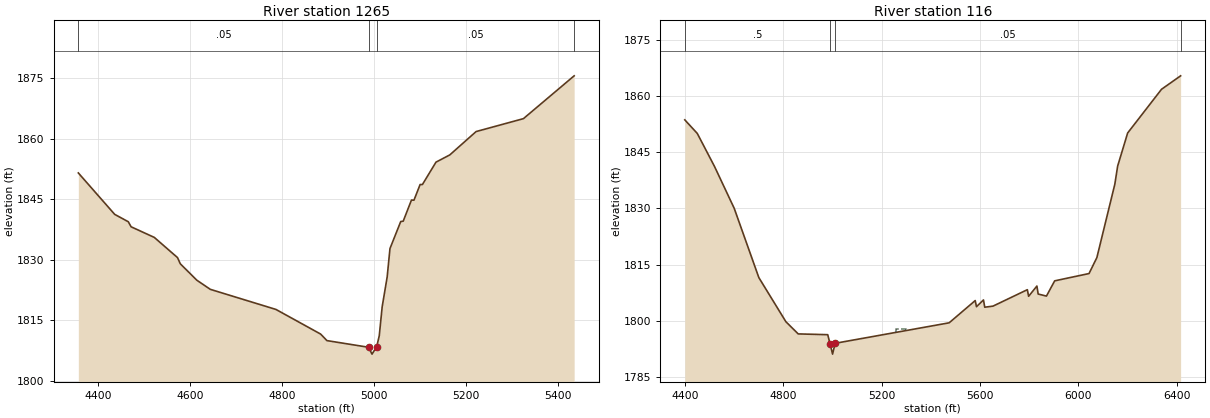
Type RM Length L Ch R = 1 ,1265    ,1149,1149,1149
BEGIN DESCRIPTION:
Mapping XS 10856167
END DESCRIPTION:
XS GIS Cut Line= 4
      2773708.55     10007634.13       2774105.7     10007354.17
      2774209.87     10007117.63      2774192.51     10006783.45
#Sta/Elev= 30
    4357 1851.53  4436.1 1841.27  4465.7 1839.44  4471.8 1838.19  4522.3 1835.56
  4572.8 1830.56  4578.9 1829.03  4614.7 1824.97  4644.2 1822.69  4787.1 1817.71
  4884.3 1811.61    4898 1809.99  4988.6 1808.34  4996.1 1806.64  5006.4 1808.51
  5011.9 1811.21  5018.2 1818.35  5029.1 1825.77  5035.2  1832.8  5058.6 1839.49
    5064 1839.58  5081.9  1844.8  5087.4 1844.78  5100.8 1848.66  5105.8 1848.66
  5135.3  1854.2  5165.4    1856  5222.6 1861.78  5325.6 1864.98    5436 1875.59
#Mann= 4 ,-1 , 0
    4357     .05       0  4988.6    .035       0  5006.4     .05       0
    5436      .1       0
Bank Sta=4988.6,5006.4
XS Rating Curve= 0 ,0
Exp/Cntr=0.3,0.1

Type RM Length L Ch R = 1 ,116     ,0,0,0
BEGIN DESCRIPTION:
UNT026 IN SNOGR 1.0
END DESCRIPTION:
XS GIS Cut Line= 4
      2773977.63     10008170.14      2774611.35     10008176.65
      2774667.77     10008052.96      2774321.09      10006856.9
#Sta/Elev= 30
  4400.2 1853.64    4451 1850.01    4521 1841.19    4601 1830.02  4701.1 1811.52
  4811.1 1799.73  4861.1 1796.48  4981.1 1796.27  4991.1 1793.68  5000.8 1791.08
  5011.1 1793.97  5474.5 1799.44  5580.4 1805.38  5585.6 1803.75    5614 1805.55
  5619.2 1803.61  5652.8  1803.9  5792.3 1808.29  5797.5 1806.53  5831.1 1809.26
  5836.3 1807.13  5869.9 1806.58  5903.4 1810.65    6043  1812.6  6074.9 1816.87
  6147.8 1836.45  6159.3  1841.3  6199.9 1850.13  6337.6 1861.81  6415.2  1865.4
#Mann= 4 ,-1 , 0
  4400.2      .5       0  4991.1    .035       0  5011.1     .05       0
  6415.2      .1       0
#XS Ineff= 2 ,-1
  4863.6  4980.5 1796.22 5257.18 5298.81 1797.75
Permanent Ineff=
       T       T
Bank Sta=4991.1,5011.1
XS Rating Curve= 0 ,0
Exp/Cntr=0.3,0.1

Chan Stop Cuts=-1
Use User Specified Reach Order=0
Composite Channel Slope=5