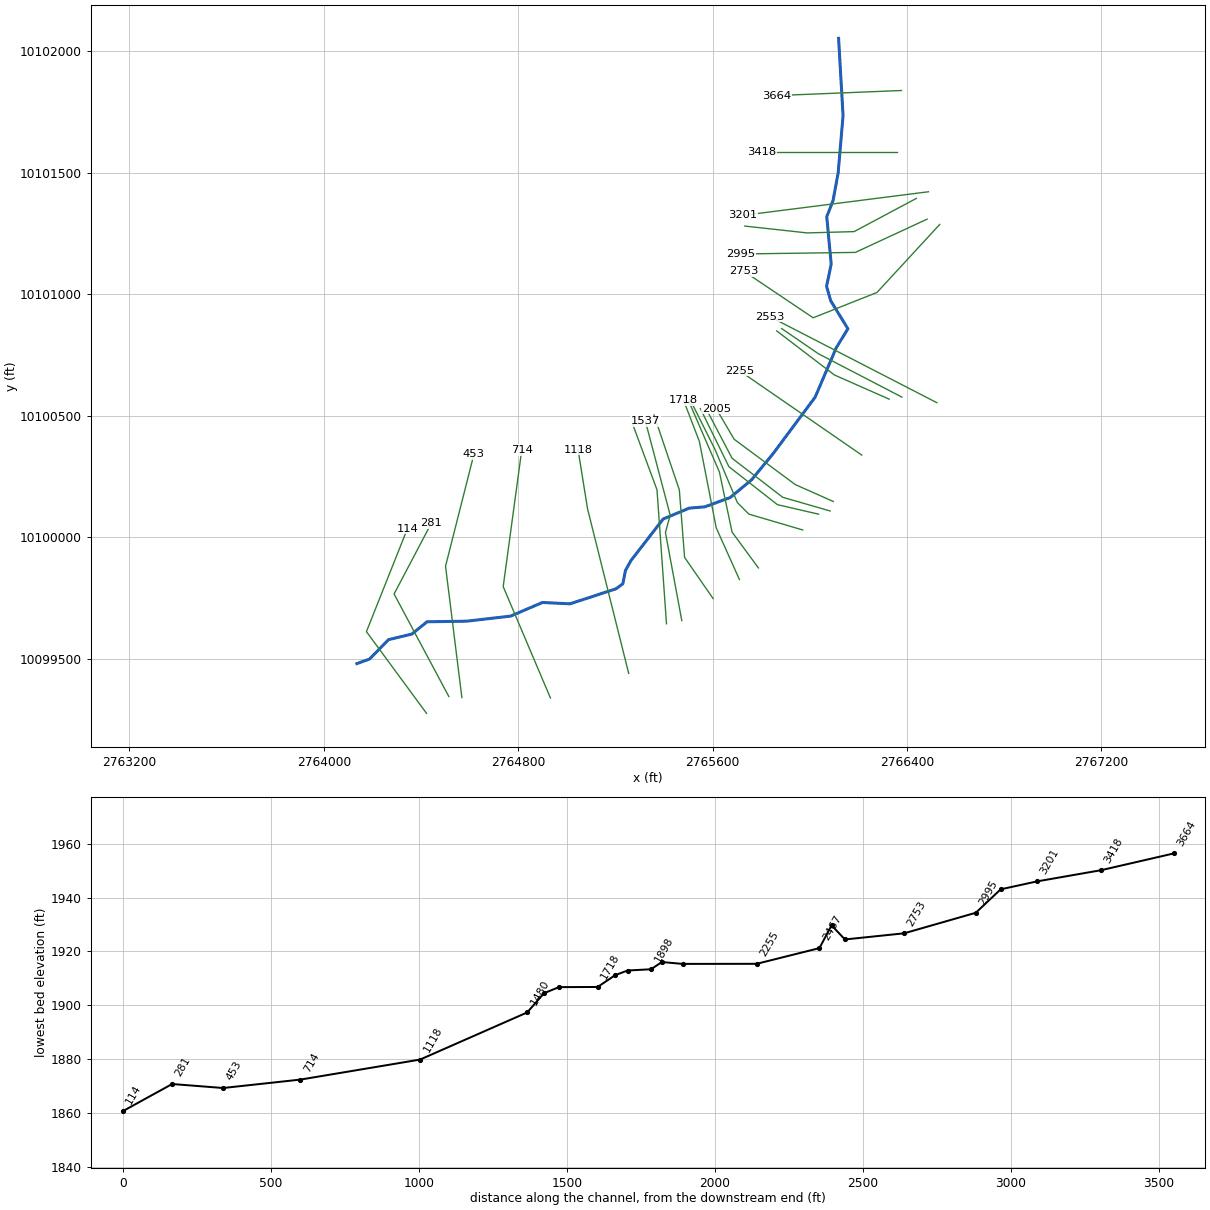
--- UNT027 IN NNOGR.prj (project) ---

Proj Title=UNT027 IN NNOGR Base Level Engineering
Current Plan=p01
Default Exp/Contr=0.3,0.1
English Units
Geom File=g01
Flow File=f01
Plan File=p01
Y Axis Title=Elevation
X Axis Title(PF)=Main Channel Distance
X Axis Title(XS)=Station
BEGIN DESCRIPTION:
UNT027 IN NNOGR
END DESCRIPTION:
DSS Export Rating Curves= 0
DSS Export Rating Curve Sorted= 0
DSS Export Volume Flow Curves= 0
DXF OffsetX= 0
DXF OffsetY= 0
DXF ScaleX= 1
DXF ScaleY= 10

--- UNT027 IN NNOGR.p01 (plan) ---

Plan Title=Multiple Run
Short Identifier=Multiple
Geom File=g01
Flow File=f01
Subcritical Flow
K Sum by GR= 0
Std Step Tol= 0.01
Critical Tol= 0.01
Num of Std Step Trials= 20
Max Error Tol= 0.3
Flow Tol Ratio= 0.001
Split Flow NTrial= 30
Split Flow Tol= 0.02
Split Flow Ratio= 0.02
Log Output Level= 0
Friction Slope Method= 1
Unsteady Friction Slope Method= 2
Unsteady Bridges Friction Slope Method= 1
Parabolic Critical Depth
Global Vel Dist=  1 , 1 , 1
Global Log Level= 0
CheckData=True
Encroach Param= -1, 0, 0, 0
BEGIN DESCRIPTION:
Multiple Run
END DESCRIPTION:

--- UNT027 IN NNOGR.f01 (steady flow) ---

Flow Title=Multiple
Program Version=4.10
Number of Profiles= 7
Profile Names=10-year,25-year,50-year,1pct_min,100-year,1pct_plu,500-year
River Rch & RM=UNT027 IN NNOGR,Reach-1         ,3664
     536     759     948     870    1177    1591    1816
Boundary for River Rch & Prof#=UNT027 IN NNOGR,Reach-1         , 1
Up Type= 0
Dn Type= 3
Dn Slope=0.0181
Boundary for River Rch & Prof#=UNT027 IN NNOGR,Reach-1         , 2
Up Type= 0
Dn Type= 3
Dn Slope=0.0181
Boundary for River Rch & Prof#=UNT027 IN NNOGR,Reach-1         , 3
Up Type= 0
Dn Type= 3
Dn Slope=0.0181
Boundary for River Rch & Prof#=UNT027 IN NNOGR,Reach-1         , 4
Up Type= 0
Dn Type= 3
Dn Slope=0.0181
Boundary for River Rch & Prof#=UNT027 IN NNOGR,Reach-1         , 5
Up Type= 0
Dn Type= 3
Dn Slope=0.0181
Boundary for River Rch & Prof#=UNT027 IN NNOGR,Reach-1         , 6
Up Type= 0
Dn Type= 3
Dn Slope=0.0181
Boundary for River Rch & Prof#=UNT027 IN NNOGR,Reach-1         , 7
Up Type= 0
Dn Type= 3
Dn Slope=0.0181
DSS Import GetInterval= 0
DSS Import GetPeak= 0
DSS Import FillOption= 0

--- UNT027 IN NNOGR.g01 (geometry) ---

Geom Title=Existing Conditions
Program Version=4.10

River Reach=UNT027 IN NNOGR ,Reach-1
Reach XY= 30
      2766118.14     10102052.63      2766136.57     10101734.16
      2766116.43     10101499.28      2766095.37     10101384.99
      2766069.41     10101318.51       2766087.7     10101123.67
      2766068.72      10101032.1      2766085.71     10100972.63
      2766156.46      10100857.4       2766108.3     10100778.66
      2766021.48     10100575.72       2765848.3     10100343.08
      2765759.33     10100235.01      2765672.09     10100162.96
      2765568.36     10100124.76      2765503.25     10100119.12
      2765396.05     10100074.42      2765263.67     10099903.41
       2765241.1     10099863.04      2765230.18     10099807.85
      2765202.13      10099787.3      2765012.66     10099725.44
      2764899.68     10099731.05       2764768.5     10099674.93
       2764588.8     10099654.16      2764424.26     10099651.51
      2764362.37     10099601.13      2764266.03     10099578.03
      2764188.34     10099498.55      2764135.76     10099479.48

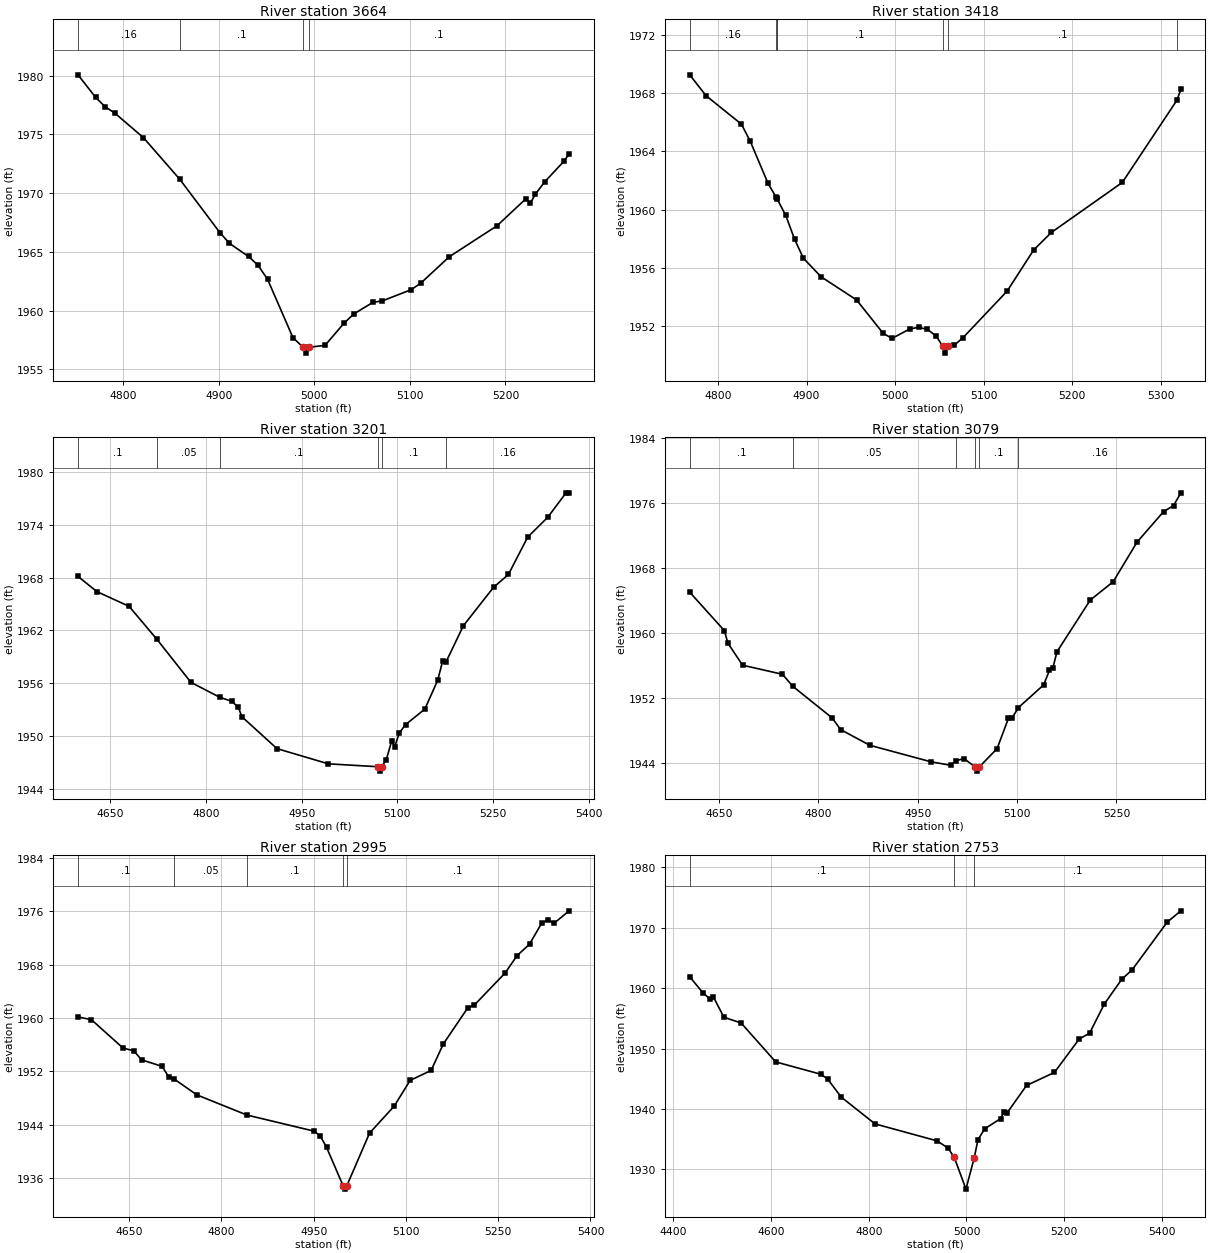
Type RM Length L Ch R = 1 ,3664    ,246,246,246
BEGIN DESCRIPTION:
UNT027 IN NNOGR 8.0
END DESCRIPTION:
XS GIS Cut Line= 2
      2766376.84      10101837.9      2765863.16     10101817.08
#Sta/Elev= 30
  4752.6 1980.08    4771 1978.17    4781 1977.36    4791 1976.83    4821 1974.74
  4859.1 1971.19  4901.1 1966.65  4911.1 1965.73  4931.1 1964.61  4941.1 1963.86
  4951.1 1962.66  4977.6  1957.7  4988.2 1956.88  4990.9 1956.38  4994.2 1956.88
  5011.2 1957.04  5031.2 1958.94  5041.2 1959.71  5061.2  1960.7  5071.2 1960.83
  5101.3 1961.78  5111.3 1962.33  5141.3 1964.59  5191.3 1967.23  5221.1  1969.5
  5226.1 1969.15  5231.4 1969.92  5241.4 1970.99  5261.4 1972.73  5266.7 1973.36
#Mann= 4 ,-1 , 0
  4752.6     .16       0  4859.1      .1       0  4988.2     .07       0
  4994.2      .1       0
Bank Sta=4988.2,4994.2
XS Rating Curve= 0 ,0
Exp/Cntr=0.3,0.1

Type RM Length L Ch R = 1 ,3418    ,217,217,217
BEGIN DESCRIPTION:
Mapping XS 51fd88cf
END DESCRIPTION:
XS GIS Cut Line= 2
      2766356.82     10101583.26      2765802.32     10101583.26
#Sta/Elev= 30
  4768.1 1969.26  4786.5 1967.83  4826.5 1965.87  4836.5 1964.69  4856.5 1961.81
  4865.8 1960.84  4866.1 1960.81  4866.7 1960.75  4876.5 1959.61  4886.5 1957.97
  4896.5 1956.66  4916.5 1955.39  4956.5  1953.8  4986.5 1951.51  4996.5 1951.16
  5016.5 1951.81  5026.5 1951.92  5036.5 1951.78  5046.5 1951.31  5053.5 1950.65
  5056.2 1950.15  5059.5 1950.65  5066.5 1950.68  5076.5  1951.2  5126.5 1954.41
  5156.5 1957.24  5176.5 1958.44  5256.5 1961.87  5318.2 1967.52  5322.6 1968.26
#Mann= 7 ,-1 , 0
  4768.1     .16       0  4865.8      .1       0  4866.1     .16       0
  4866.7      .1       0  5053.5     .07       0  5059.5      .1       0
  5318.2     .16       0
Bank Sta=5053.5,5059.5
XS Rating Curve= 0 ,0
Exp/Cntr=0.3,0.1

Type RM Length L Ch R = 1 ,3201    ,122,122,122
BEGIN DESCRIPTION:
UNT027 IN NNOGR 7.0
END DESCRIPTION:
XS GIS Cut Line= 2
      2766487.95     10101421.24      2765724.01     10101324.01
#Sta/Elev= 30
  4599.1 1968.13  4628.8  1966.4  4679.2 1964.73  4722.7 1960.99  4776.2 1956.08
  4821.7 1954.37  4840.5 1953.92  4850.6 1953.22  4856.1 1952.17  4911.1 1948.54
  4991.7 1946.81  5069.4 1946.48  5072.1 1945.98  5075.4 1946.48  5082.5 1947.28
  5090.8 1949.36  5095.9 1948.78  5102.6 1950.28  5112.7 1951.27  5142.9 1953.03
  5163.1 1956.31  5170.8 1958.48  5175.8 1958.34  5203.4 1962.52  5250.7 1966.89
    5274 1968.35  5304.2  1972.6  5335.7 1974.86  5364.4 1977.64  5369.2 1977.64
#Mann= 6 ,-1 , 0
  4599.1      .1       0  4722.7     .05       0  4821.7      .1       0
  5069.4     .07       0  5075.4      .1       0  5175.8     .16       0
Bank Sta=5069.4,5075.4
XS Rating Curve= 0 ,0
Exp/Cntr=0.3,0.1

Type RM Length L Ch R = 1 ,3079    ,84,84,84
BEGIN DESCRIPTION:
Mapping XS bb0251e7
END DESCRIPTION:
XS GIS Cut Line= 4
       2766438.2     10101393.97      2766182.14     10101257.26
        2765989.     10101251.84      2765732.62     10101279.97
#Sta/Elev= 30
  4605.8 1965.06    4658 1960.34  4663.6 1958.77  4685.6 1956.08  4745.8 1954.96
  4761.6 1953.47  4820.9 1949.59  4833.6 1948.16  4877.6 1946.23  4969.8  1944.2
  4999.8 1943.77  5007.3 1944.32  5019.8  1944.6  5036.8 1943.55  5039.5 1943.05
  5042.8 1943.55  5069.8 1945.82    5087 1949.56  5092.1 1949.56  5102.1 1950.87
  5140.1 1953.66  5148.8 1955.44  5153.9 1955.71  5160.2 1957.73  5210.5  1964.1
    5245 1966.34    5281 1971.21  5321.2 1974.98  5336.1  1975.7  5347.2 1977.28
#Mann= 6 ,-1 , 0
  4605.8      .1       0  4761.6     .05       0  5007.3      .1       0
  5036.8    .035       0  5042.8      .1       0  5102.1     .16       0
Bank Sta=5036.8,5042.8
XS Rating Curve= 0 ,0
Exp/Cntr=0.3,0.1

Type RM Length L Ch R = 1 ,2995    ,242,242,242
BEGIN DESCRIPTION:
Mapping XS 4e93eeeb
END DESCRIPTION:
XS GIS Cut Line= 3
      2766482.28     10101308.44       2766187.1      10101171.7
      2765714.06     10101165.19
#Sta/Elev= 30
  4566.9 1960.18  4588.8 1959.75  4640.2  1955.5  4657.6 1955.09  4670.3 1953.74
  4703.4 1952.76  4714.4  1951.2  4723.7 1950.83  4760.2 1948.48  4841.5 1945.46
  4950.9 1943.04  4960.9 1942.28  4970.9 1940.64  4997.9 1934.85  5000.6 1934.35
  5003.9 1934.85  5040.9 1942.75  5080.9 1946.79  5106.9 1950.66  5140.9 1952.14
  5160.9 1956.13  5200.9 1961.58  5210.9 1961.92  5260.9 1966.72  5280.9 1969.38
  5300.9 1971.08  5320.9 1974.26  5330.9 1974.71  5340.9 1974.22  5365.3 1976.08
#Mann= 5 ,-1 , 0
  4566.9      .1       0  4723.7     .05       0  4841.5      .1       0
  4997.9     .07       0  5003.9      .1       0
Bank Sta=4997.9,5003.9
XS Rating Curve= 0 ,0
Exp/Cntr=0.3,0.1

Type RM Length L Ch R = 1 ,2753    ,200,200,200
BEGIN DESCRIPTION:
Mapping XS d567be32
END DESCRIPTION:
XS GIS Cut Line= 4
      2766534.29     10101286.69      2766276.08     10101006.77
      2766013.49      10100902.6       2765729.2     10101093.58
#Sta/Elev= 30
  4433.2 1961.88  4460.8 1959.18  4474.9 1958.22  4481.8 1958.53  4503.3 1955.18
  4538.5 1954.23  4609.3 1947.79  4701.2 1945.76  4715.4 1944.98  4743.7 1941.95
  4812.7 1937.53  4939.7 1934.72  4962.1 1933.54  4974.8 1932.02  4998.9 1926.73
  5015.9 1931.93  5023.5 1934.91  5037.4 1936.73  5069.7 1938.39  5077.5 1939.58
  5082.8 1939.31    5123 1943.89  5180.1 1946.05  5231.1 1951.61  5252.1 1952.54
    5282 1957.34  5318.1 1961.48  5339.1 1963.02  5411.1 1970.94    5439  1972.8
#Mann= 3 , 0 , 0
  4433.2      .1       0  4974.8     .07       0  5015.9      .1       0
Bank Sta=4974.8,5015.9
XS Rating Curve= 0 ,0
Exp/Cntr=0.3,0.1

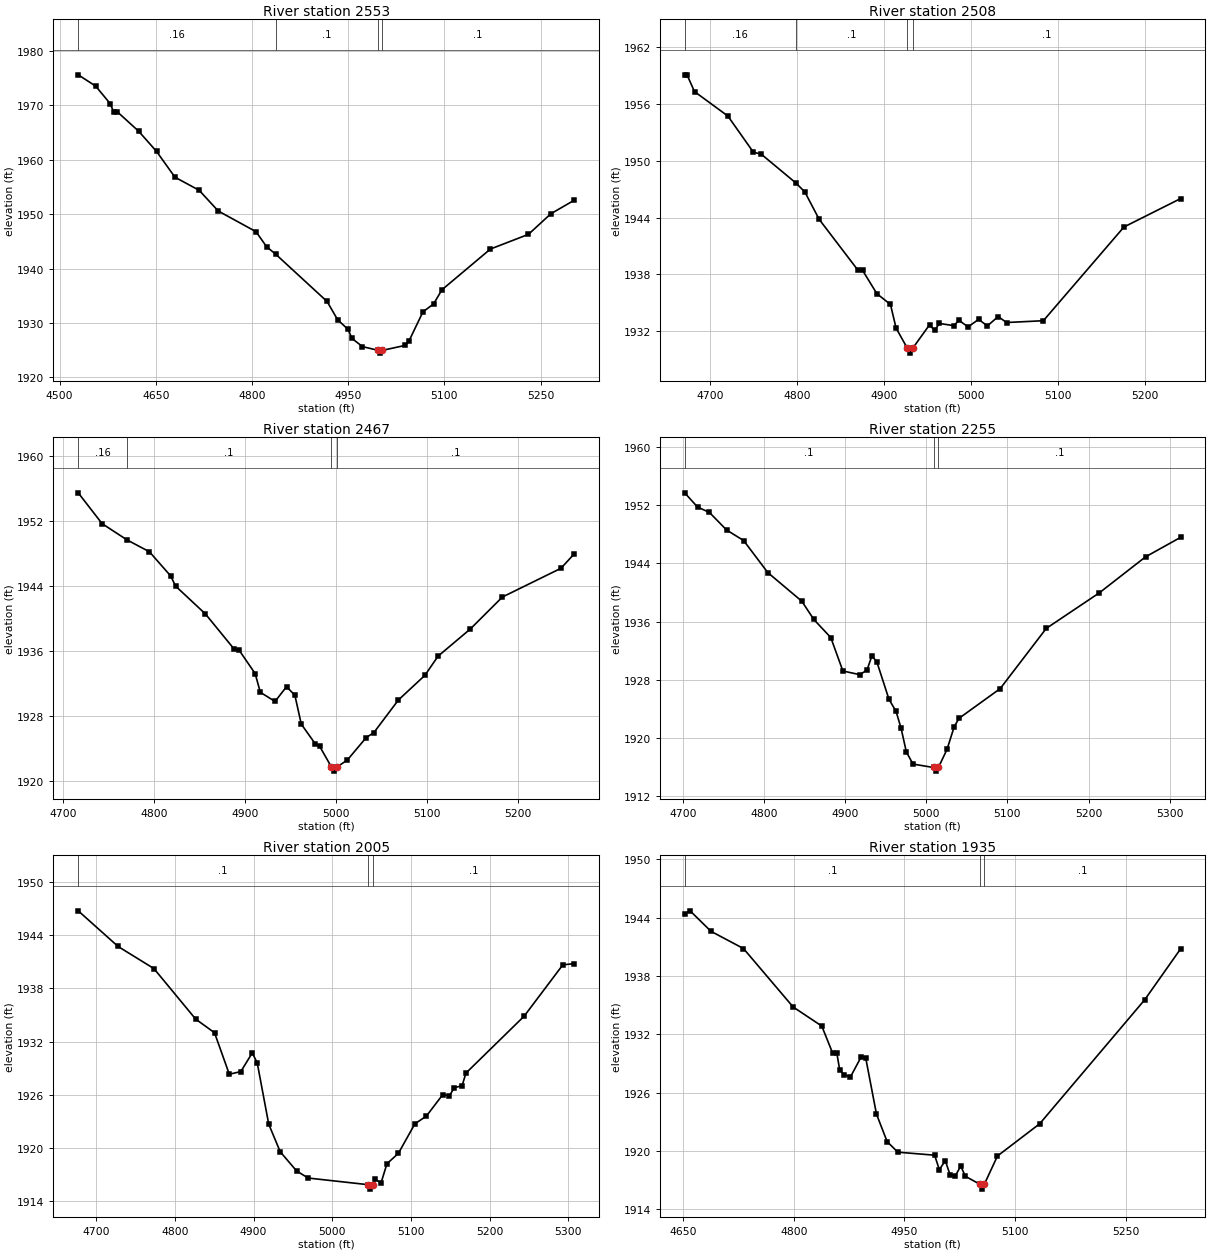
Type RM Length L Ch R = 1 ,2553    ,45,45,45
BEGIN DESCRIPTION:
UNT027 IN NNOGR 6.0
END DESCRIPTION:
XS GIS Cut Line= 2
      2766522.66     10100553.16      2765835.12     10100907.35
#Sta/Elev= 30
    4529  1975.6  4556.2 1973.53  4578.7 1970.33  4584.6 1968.72  4590.2 1968.78
  4623.3 1965.23  4651.1 1961.53  4679.9 1956.78  4717.6 1954.38  4747.4 1950.57
  4806.3 1946.77  4822.8    1944  4836.9 1942.64  4917.1 1933.94  4933.6 1930.58
  4949.9  1928.8  4955.8 1927.16  4972.3 1925.65  4997.1 1924.95  4999.9 1924.45
  5003.1 1924.95  5038.8 1925.87  5044.5  1926.6  5066.6 1932.04  5083.2 1933.49
  5096.2 1936.09  5171.8 1943.58  5231.1 1946.28  5266.1 1950.07  5302.4 1952.54
#Mann= 4 ,-1 , 0
    4529     .16       0  4836.9      .1       0  4997.1     .07       0
  5003.1      .1       0
Bank Sta=4997.1,5003.1
XS Rating Curve= 0 ,0
Exp/Cntr=0.3,0.1

Type RM Length L Ch R = 1 ,2508    ,41,41,41
BEGIN DESCRIPTION:
Mapping XS 4f92a683
END DESCRIPTION:
XS GIS Cut Line= 3
      2766378.54      10100576.3      2766035.63     10100754.26
      2765883.74     10100858.41
#Sta/Elev= 30
  4670.3 1959.07    4673 1959.07  4681.6  1957.3    4720 1954.72  4749.2 1950.92
  4758.6 1950.68  4798.3 1947.65  4808.5 1946.71    4825 1943.82  4869.3 1938.49
  4874.9 1938.44  4891.4 1935.97    4907 1934.84  4913.5 1932.34  4926.5  1930.2
  4929.3  1929.7  4932.5  1930.2    4952 1932.69  4957.7  1932.1  4963.4 1932.83
  4979.9  1932.6  4985.8 1933.16  4996.3 1932.47  5008.4 1933.26  5018.5 1932.57
  5030.9 1933.56  5040.6 1932.93  5082.9 1933.12  5175.6 1943.01  5240.8 1946.01
#Mann= 4 ,-1 , 0
  4670.3     .16       0  4798.3      .1       0  4926.5     .07       0
  4932.5      .1       0
Bank Sta=4926.5,4932.5
XS Rating Curve= 0 ,0
Exp/Cntr=0.3,0.1

Type RM Length L Ch R = 1 ,2467    ,212,212,212
BEGIN DESCRIPTION:
Mapping XS 0293229e
END DESCRIPTION:
XS GIS Cut Line= 3
      2766326.44     10100567.62      2766100.73     10100667.46
      2765863.41     10100848.68
#Sta/Elev= 30
  4716.6 1955.43  4742.9 1951.64  4770.2 1949.65  4794.9 1948.19  4818.2 1945.23
  4823.7 1943.97  4856.5 1940.55  4888.1 1936.23  4893.6 1936.09  4911.2 1933.22
  4916.9 1930.92  4933.1  1929.8  4945.7 1931.62  4954.9 1930.55  4961.9 1927.02
  4977.3 1924.59    4982 1924.31  4995.1 1921.74  4997.8 1921.24  5001.1 1921.74
  5012.6 1922.61  5033.4 1925.37  5041.7 1925.97  5068.8 1929.99  5097.8    1933
  5112.4 1935.37  5147.7 1938.69  5183.1 1942.63  5247.5 1946.16    5262 1947.92
#Mann= 4 ,-1 , 0
  4716.6     .16       0  4770.2      .1       0  4995.1     .07       0
  5001.1      .1       0
Bank Sta=4995.1,5001.1
XS Rating Curve= 0 ,0
Exp/Cntr=0.3,0.1

Type RM Length L Ch R = 1 ,2255    ,250,250,250
BEGIN DESCRIPTION:
Mapping XS 118fe277
END DESCRIPTION:
XS GIS Cut Line= 2
      2766213.55     10100337.62      2765710.07     10100684.84
#Sta/Elev= 30
    4702 1953.73  4717.9 1951.77  4732.5 1951.03  4753.7 1948.61  4774.7 1947.16
  4804.5 1942.75  4846.4 1938.81  4861.3 1936.29  4882.2  1933.8  4897.1  1929.2
    4918 1928.69  4926.8 1929.33  4932.9 1931.27    4939 1930.45  4953.9 1925.31
  4962.7 1923.63  4968.8 1921.34  4975.4 1918.04  4983.6 1916.38  5008.9 1915.91
  5011.6 1915.41  5014.9 1915.91  5025.5  1918.4  5034.4 1921.53  5040.4 1922.69
  5091.1 1926.77  5147.9 1935.06  5213.5 1939.97  5270.3 1944.91  5313.6  1947.6
#Mann= 3 ,-1 , 0
    4702      .1       0  5008.9     .07       0  5014.9      .1       0
Bank Sta=5008.9,5014.9
XS Rating Curve= 0 ,0
Exp/Cntr=0.3,0.1

Type RM Length L Ch R = 1 ,2005    ,70,70,70
BEGIN DESCRIPTION:
Mapping XS 3d4fc73e
END DESCRIPTION:
XS GIS Cut Line= 4
      2766096.38     10100146.63      2765940.14     10100216.07
      2765688.41      10100402.7      2765614.65     10100528.53
#Sta/Elev= 30
  4677.2 1946.75  4727.9 1942.73  4773.4 1940.24  4826.4 1934.55  4850.4 1933.01
  4869.2 1928.33  4883.8 1928.63  4898.4 1930.74  4904.7  1929.6  4919.3  1922.7
  4933.9 1919.59  4954.7 1917.43  4969.4 1916.63  5045.7 1915.88  5048.4 1915.38
  5051.7 1915.88  5054.9  1916.5  5061.9 1916.05  5069.5 1918.24  5084.1 1919.42
    5105 1922.74  5119.6 1923.61  5140.4 1926.03  5148.8 1925.89  5155.1 1926.81
    5165 1927.04  5169.9 1928.46  5243.9 1934.88    5293 1940.66  5307.4  1940.8
#Mann= 3 ,-1 , 0
  4677.2      .1       0  5045.7     .07       0  5051.7      .1       0
Bank Sta=5045.7,5051.7
XS Rating Curve= 0 ,0
Exp/Cntr=0.3,0.1

Type RM Length L Ch R = 1 ,1935    ,37,37,37
BEGIN DESCRIPTION:
Mapping XS 4d5d7767
END DESCRIPTION:
XS GIS Cut Line= 4
      2766083.37     10100107.56      2765888.06     10100163.98
      2765679.72     10100324.58      2765584.25     10100506.84
#Sta/Elev= 30
  4652.1  1944.4  4659.4 1944.69  4687.8 1942.58  4731.8 1940.81  4799.1  1934.8
  4837.9 1932.84  4852.6 1930.06  4858.3 1930.06  4862.2 1928.32  4868.5 1927.83
  4876.7  1927.6  4891.2 1929.66  4897.5 1929.54    4912 1923.79  4926.5 1920.95
    4941 1919.87  4990.8 1919.56  4997.2 1918.08  5005.3 1918.99  5011.7 1917.56
    5019 1917.45  5026.2 1918.44  5032.5 1917.39  5052.2 1916.57  5054.9 1916.07
  5058.2 1916.57    5076 1919.48  5133.2 1922.79  5275.5 1935.54  5324.2 1940.78
#Mann= 3 ,-1 , 0
  4652.1      .1       0  5052.2     .07       0  5058.2      .1       0
Bank Sta=5052.2,5058.2
XS Rating Curve= 0 ,0
Exp/Cntr=0.3,0.1

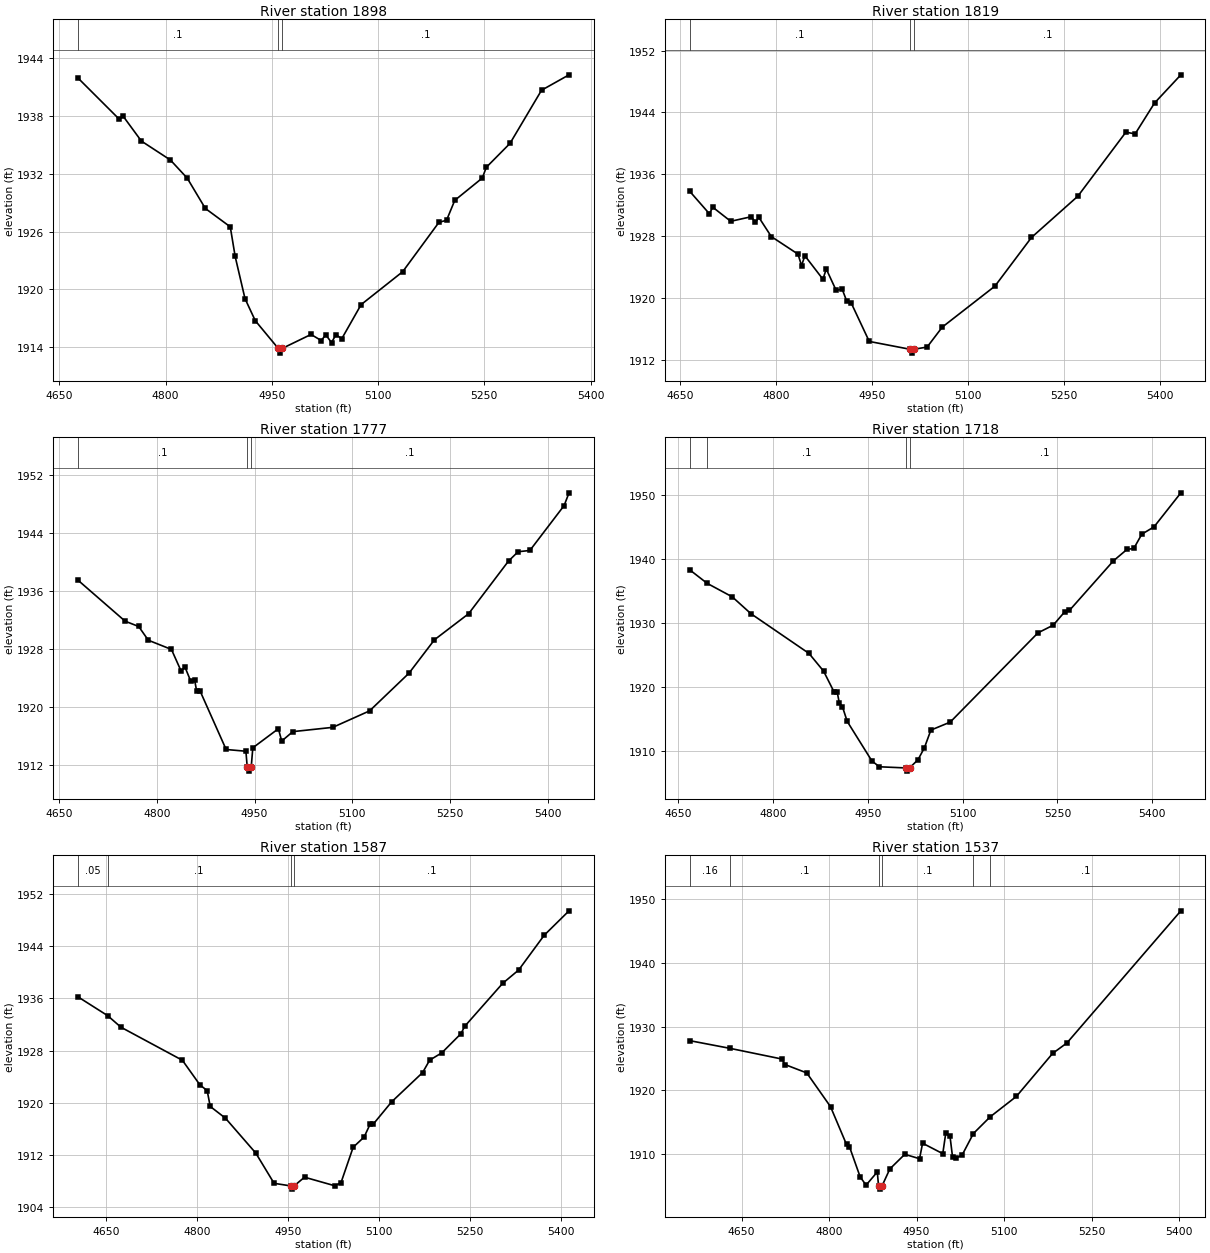
Type RM Length L Ch R = 1 ,1898    ,79,79,79
BEGIN DESCRIPTION:
Mapping XS 787018cb
END DESCRIPTION:
XS GIS Cut Line= 4
      2766035.67     10100094.53      2765866.36      10100133.6
       2765666.7     10100289.85      2765549.52     10100528.55
#Sta/Elev= 30
  4676.4 1941.97  4734.8 1937.68  4739.9 1938.03  4765.9 1935.42  4806.9 1933.45
  4830.6 1931.57  4856.2 1928.42  4891.4 1926.51  4898.3 1923.43  4912.2 1919.05
  4926.7 1916.76    4959 1913.89  4961.7 1913.39    4965 1913.89  5005.4 1915.33
  5019.8  1914.7  5026.2 1915.29  5034.3 1914.49  5040.6  1915.3  5048.8 1914.89
  5076.1 1918.43  5134.8 1921.85    5186 1926.98  5196.7 1927.19  5208.3 1929.26
  5247.2 1931.58  5252.8 1932.69  5286.3 1935.18  5330.8  1940.7  5369.6  1942.3
#Mann= 3 ,-1 , 0
  4676.4      .1       0    4959     .07       0    4965      .1       0
Bank Sta=4959,4965
XS Rating Curve= 0 ,0
Exp/Cntr=0.3,0.1

Type RM Length L Ch R = 1 ,1819    ,42,42,42
BEGIN DESCRIPTION:
Mapping XS 75cb27ad
END DESCRIPTION:
XS GIS Cut Line= 5
      2765970.51     10100029.44      2765749.17     10100094.54
      2765701.43     10100142.28      2765610.28      10100359.3
      2765506.13     10100567.59
#Sta/Elev= 30
  4665.6 1933.81  4696.2 1930.92  4701.4 1931.77  4729.5 1929.95  4761.5 1930.54
  4768.1  1929.8  4773.3 1930.47  4792.8 1927.98  4834.5 1925.71    4840 1924.23
  4845.2  1925.5  4873.4 1922.47  4878.6 1923.79  4894.1 1921.02  4903.3 1921.21
  4910.4 1919.68  4917.5 1919.41  4945.7 1914.44  5009.2 1913.43    5012 1912.93
  5015.2 1913.43    5036 1913.71  5059.7 1916.29  5141.9 1921.58  5198.9 1927.86
  5271.3 1933.19  5346.3 1941.46  5360.7 1941.23    5391 1945.22  5432.1 1948.86
#Mann= 3 ,-1 , 0
  4665.6      .1       0  5009.2     .07       0  5015.2      .1       0
Bank Sta=5009.2,5015.2
XS Rating Curve= 0 ,0
Exp/Cntr=0.3,0.1

Type RM Length L Ch R = 1 ,1777    ,59,59,59
BEGIN DESCRIPTION:
Mapping XS 741262af
END DESCRIPTION:
XS GIS Cut Line= 4
      2765788.23     10099873.19      2765679.72     10100020.76
      2765627.64     10100268.15      2765501.84     10100558.81
#Sta/Elev= 30
  4679.3 1937.49  4751.6 1931.84  4772.4 1931.11  4787.1 1929.22  4822.6 1927.95
  4837.2 1925.01  4843.4  1925.5  4851.8 1923.66  4858.1 1923.75  4861.2 1922.22
  4866.5 1922.22  4906.4 1914.17  4936.7 1913.93  4938.8 1911.69  4941.5 1911.19
  4944.8 1911.69  4947.3  1914.4  4986.5 1917.03  4991.6 1915.33  5008.6 1916.63
  5069.9 1917.22  5126.3 1919.49  5186.7 1924.68  5225.7 1929.28  5278.1 1932.87
  5339.3 1940.13    5354 1941.41    5372 1941.58  5424.5 1947.77    5432 1949.52
#Mann= 3 ,-1 , 0
  4679.3      .1       0  4938.8     .07       0  4944.8      .1       0
Bank Sta=4938.8,4944.8
XS Rating Curve= 0 ,0
Exp/Cntr=0.3,0.1

Type RM Length L Ch R = 1 ,1718    ,131,131,131
BEGIN DESCRIPTION:
Mapping XS 751dba66
END DESCRIPTION:
XS GIS Cut Line= 4
      2765710.11     10099825.43      2765614.62     10100038.12
      2765545.18     10100394.02      2765480.08     10100563.27
#Sta/Elev= 30
  4668.3 1938.31  4695.7 1936.21  4735.5 1934.09  4765.1 1931.45  4856.9 1925.24
    4880 1922.47  4896.3 1919.27  4901.4 1919.27  4904.8 1917.53  4909.9 1916.88
  4917.4  1914.6  4956.4 1908.42  4968.3  1907.5    5010 1907.32  5012.8 1906.82
    5016 1907.32  5029.4  1908.6  5039.6 1910.49  5049.8 1913.24  5080.4 1914.49
  5219.3 1928.46  5243.4 1929.66  5261.4 1931.73    5269 1931.96  5338.7 1939.73
  5360.2 1941.52  5370.9 1941.66  5383.6  1943.9  5402.9 1945.04  5445.4 1950.37
#Mann= 4 ,-1 , 0
  4668.3     .05       0  4695.7      .1       0    5010     .07       0
    5016      .1       0
Bank Sta=5010,5016
XS Rating Curve= 0 ,0
Exp/Cntr=0.3,0.1

Type RM Length L Ch R = 1 ,1587    ,50,50,50
BEGIN DESCRIPTION:
Mapping XS d9efe952
END DESCRIPTION:
XS GIS Cut Line= 4
      2765601.62     10099747.29      2765484.41     10099916.59
      2765462.71     10100194.37      2765358.55      10100502.5
#Sta/Elev= 30
  4603.7 1936.25  4652.7 1933.36  4674.6 1931.59  4775.9 1926.52  4804.8 1922.75
  4816.8 1921.86  4821.8 1919.44  4846.9 1917.64    4897 1912.28  4927.1 1907.65
  4954.2 1907.26    4957 1906.76  4960.2 1907.26  4977.3 1908.59  5027.4 1907.27
  5037.5 1907.76  5057.5 1913.18  5075.6 1914.75  5085.4 1916.71  5090.5 1916.71
  5120.8 1920.13    5172 1924.63  5183.7 1926.54  5203.7 1927.66  5235.4 1930.61
  5241.3 1931.71  5304.2 1938.33  5330.4 1940.36  5372.6  1945.7  5413.5 1949.44
#Mann= 4 ,-1 , 0
  4603.7     .05       0  4652.7      .1       0  4954.2     .07       0
  4960.2      .1       0
Bank Sta=4954.2,4960.2
XS Rating Curve= 0 ,0
Exp/Cntr=0.3,0.1

Type RM Length L Ch R = 1 ,1537    ,57,57,57
BEGIN DESCRIPTION:
Mapping XS e6725afb
END DESCRIPTION:
XS GIS Cut Line= 4
      2765472.85     10099656.59      2765405.58     10100018.99
      2765425.11     10100090.61      2765323.28     10100476.26
#Sta/Elev= 30
  4561.3 1927.79    4631 1926.57  4719.2 1924.91  4724.3 1924.05  4761.8 1922.73
  4802.5 1917.44  4829.9 1911.51    4835 1911.15  4853.4  1906.4  4863.5 1905.14
  4882.7 1907.21  4884.8 1905.01  4887.6 1904.51  4890.8 1905.01  4904.2 1907.68
  4929.8 1909.97  4955.1 1909.28  4960.3 1911.71  4994.9 1910.07    5000 1913.27
  5007.3 1912.79  5011.6  1909.6  5017.7 1909.39    5028 1909.84  5047.4 1913.23
  5076.2 1915.85  5121.1 1919.05  5183.2 1925.79  5207.7 1927.43    5403 1948.15
#Mann= 6 ,-1 , 0
  4561.3     .16       0    4631      .1       0  4884.8     .07       0
  4890.8      .1       0  5047.4     .05       0  5076.2      .1       0
Bank Sta=4884.8,4890.8
XS Rating Curve= 0 ,0
Exp/Cntr=0.3,0.1

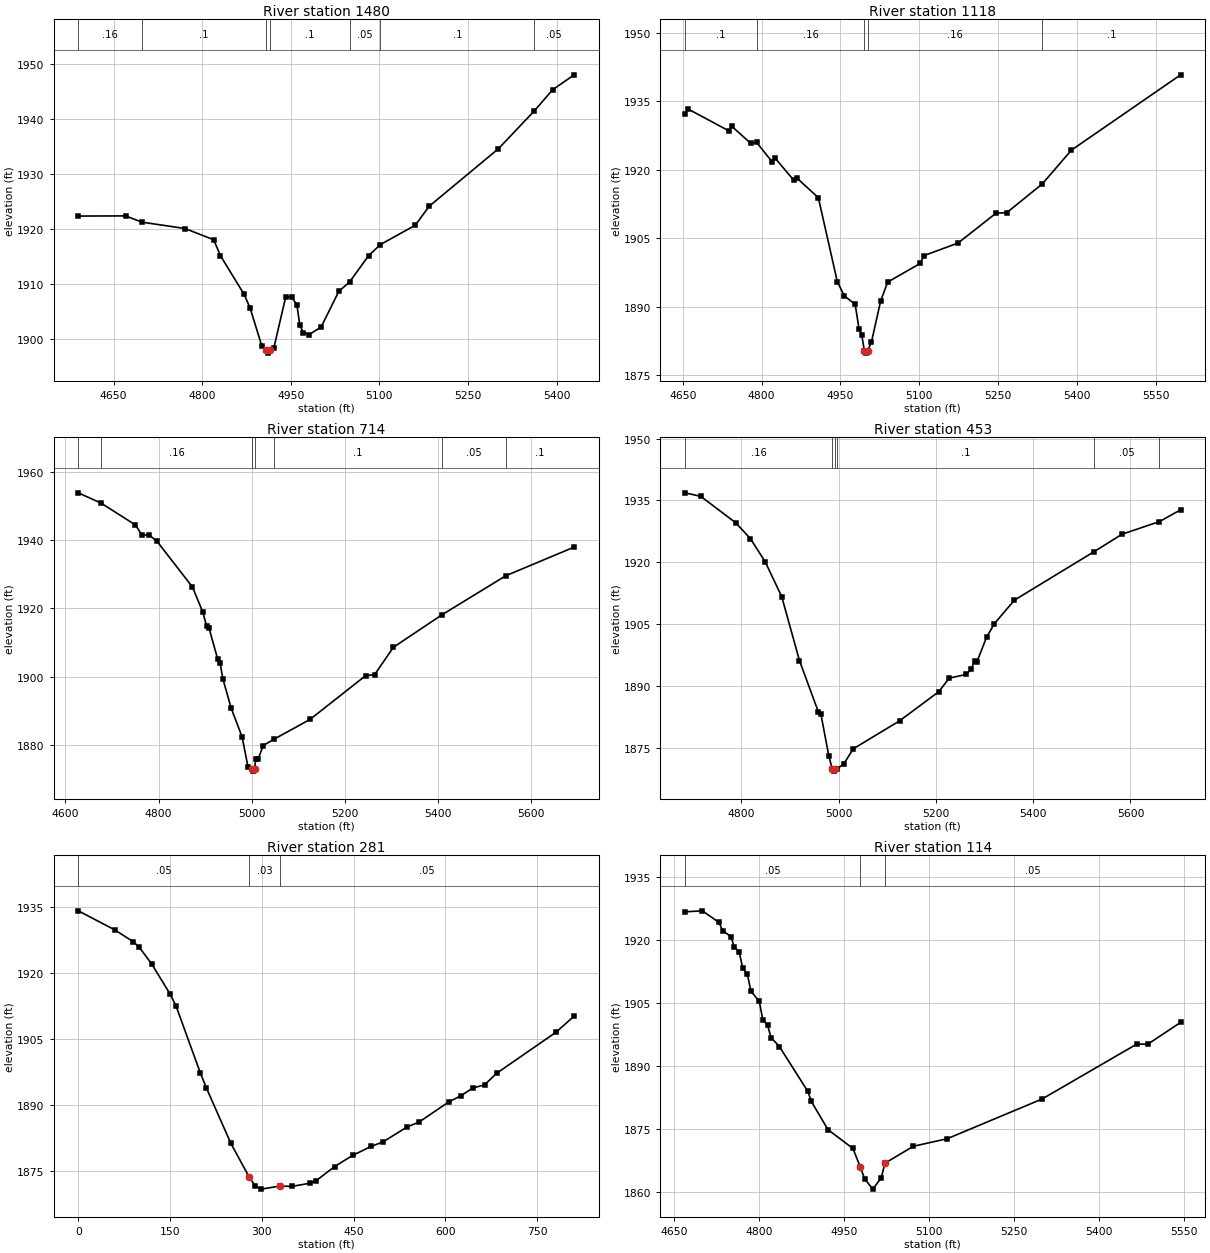
Type RM Length L Ch R = 1 ,1480    ,362,362,362
BEGIN DESCRIPTION:
UNT027 IN NNOGR 4.0
END DESCRIPTION:
XS GIS Cut Line= 3
      2765409.92     10099643.59      2765370.86     10100194.78
      2765271.03     10100463.88
#Sta/Elev= 30
  4590.3 1922.36  4670.6 1922.39  4697.8 1921.25  4770.9 1920.09  4819.5 1918.04
    4831 1915.12  4871.1 1908.07  4881.2 1905.59  4901.2  1898.6  4908.2 1897.87
    4911 1897.37  4914.2 1897.87  4921.3 1898.29  4941.3 1907.54  4951.3 1907.63
  4960.4 1906.17  4965.4 1902.41  4971.4 1901.11  4981.4 1900.76  5001.5 1902.14
  5031.5 1908.66  5049.5 1910.32  5081.7 1915.13  5101.9 1917.17  5160.9 1920.69
  5184.4 1924.15  5301.7 1934.64  5362.6 1941.55  5393.3 1945.38  5429.9 1948.11
#Mann= 7 ,-1 , 0
  4590.3     .16       0  4697.8      .1       0  4908.2     .07       0
  4914.2      .1       0  5049.5     .05       0  5101.9      .1       0
  5362.6     .05       0
Bank Sta=4908.2,4914.2
XS Rating Curve= 0 ,0
Exp/Cntr=0.3,0.1

Type RM Length L Ch R = 1 ,1118    ,404,404,404
BEGIN DESCRIPTION:
UNT027 IN NNOGR 3.0
END DESCRIPTION:
XS GIS Cut Line= 3
      2765254.38     10099439.15      2765085.11     10100116.24
      2765046.09     10100358.99
#Sta/Elev= 30
    4654 1932.28  4660.8 1933.28  4738.1 1928.52  4743.3 1929.55  4779.4 1925.81
  4790.5 1926.03  4820.6  1921.7  4825.7 1922.59  4861.8 1917.67    4867 1918.23
  4908.2 1913.91  4944.3 1895.52  4957.6  1892.4  4978.3 1890.56  4985.5 1885.26
  4990.7 1883.88  4995.9 1880.37  4998.6 1879.87  5001.9 1880.37  5009.2 1882.26
  5026.8 1891.28  5040.1 1895.42    5102  1899.5  5109.2 1901.22  5174.1 1903.97
  5246.3  1910.5  5266.9 1910.63  5334.6 1916.93  5389.9 1924.31  5597.8  1940.8
#Mann= 5 ,-1 , 0
    4654      .1       0  4790.5     .16       0  4995.9    .035       0
  5001.9     .16       0  5334.6      .1       0
Bank Sta=4995.9,5001.9
XS Rating Curve= 0 ,0
Exp/Cntr=0.3,0.1

Type RM Length L Ch R = 1 ,714     ,261,261,261
BEGIN DESCRIPTION:
UNT027 IN NNOGR 2.0
END DESCRIPTION:
XS GIS Cut Line= 3
      2764932.34     10099337.91       2764737.9     10099796.23
      2764814.29     10100358.71
#Sta/Elev= 30
  4627.6 1953.78  4676.4 1950.78  4750.4 1944.39  4764.3 1941.41  4779.5 1941.51
  4796.9 1939.57  4872.9 1926.24  4894.6 1919.09  4903.2 1914.95  4908.6 1914.21
  4926.9 1905.25  4932.3 1904.04  4938.1  1899.5    4956 1890.86  4979.6 1882.41
  4992.4 1873.55  5000.3 1872.95    5003 1872.45  5006.3 1872.95  5008.7 1875.89
  5014.2 1876.04    5025 1879.93  5048.4  1881.8  5125.5 1887.56  5245.1 1900.37
  5264.2 1900.63  5304.6 1908.63  5409.7  1918.2  5546.7 1929.58  5693.1 1937.92
#Mann= 7 ,-1 , 0
  4627.6      .1       0  4676.4     .16       0  5000.3     .07       0
  5006.3     .16       0  5048.4      .1       0  5409.7     .05       0
  5546.7      .1       0
Bank Sta=5000.3,5006.3
XS Rating Curve= 0 ,0
Exp/Cntr=0.3,0.1

Type RM Length L Ch R = 1 ,453     ,172,172,172
BEGIN DESCRIPTION:
Mapping XS 1387e536
END DESCRIPTION:
XS GIS Cut Line= 3
       2764567.9     10099339.75      2764500.63     10099880.11
      2764617.35     10100340.51
#Sta/Elev= 30
  4683.6 1936.85  4716.2 1936.01  4788.4 1929.58  4818.6 1925.72  4848.9 1920.12
  4882.8 1911.69  4919.4 1896.14  4958.5  1883.6  4963.5 1883.15  4979.9  1872.9
  4986.9 1869.83  4989.7 1869.33  4992.9 1869.83  4996.3 1869.88  5010.1 1871.01
  5030.2 1874.76  5125.1 1881.52  5205.9 1888.61  5227.4  1891.9  5262.8  1892.8
  5273.1 1894.15  5279.3 1896.17  5284.5 1895.92  5304.1 1901.83  5320.3 1905.12
  5361.3 1910.81  5525.5  1922.6  5582.6 1926.81  5659.6 1929.87  5703.1 1932.73
#Mann= 6 ,-1 , 0
  4683.6     .16       0  4986.9     .07       0  4992.9     .16       0
  4996.3      .1       0  5525.5     .05       0  5659.6      .1       0
Bank Sta=4986.9,4992.9
XS Rating Curve= 0 ,0
Exp/Cntr=0.3,0.1

Type RM Length L Ch R = 1 ,281     ,167,167,167
XS GIS Cut Line= 3
      2764514.14    10099344.116      2764288.88    10099765.991
     2764442.526    10100057.658
#Sta/Elev= 30
       0 1934.08   59.85 1929.73   89.77 1927.06   99.75 1925.78   119.7 1922.05
  149.62 1915.26   159.6 1912.51  199.49 1897.22  209.47 1893.78  249.37 1881.23
  279.29 1873.58  289.27 1871.52  299.24 1870.81  329.17  1871.5  349.11 1871.43
  379.04 1872.16  389.01 1872.74  418.94 1875.94  448.86  1878.5  478.79 1880.52
  498.31 1881.55  537.37 1884.94   556.9 1886.03  605.71 1890.64  625.24    1892
  644.77 1893.79   664.3 1894.52  683.82 1897.13  781.46 1906.52  810.75 1910.15
#Mann= 3 , 0 , 0
       0     .05       0  279.29     .03       0  329.17     .05       0
Bank Sta=279.29,329.17
XS Rating Curve= 0 ,0
Exp/Cntr=0.3,0.1

Type RM Length L Ch R = 1 ,114     ,0,0,0
BEGIN DESCRIPTION:
UNT027 IN NNOGR 1.0
END DESCRIPTION:
XS GIS Cut Line= 3
       2764422.5     10099274.65      2764175.11     10099611.01
      2764343.93     10100035.22
#Sta/Elev= 30
  4669.4  1926.8  4700.4 1927.04  4729.7 1924.27  4735.9 1922.34  4750.5 1920.92
  4756.8 1918.42  4765.2 1917.29  4771.4 1913.47  4779.8 1911.87    4786 1907.87
  4800.7 1905.47  4806.9 1901.06  4815.3 1899.77  4821.5 1896.84  4836.2 1894.68
  4886.3    1884  4892.5  1881.6  4921.8 1874.89  4965.8  1870.4  4978.6 1866.02
  4986.6 1863.11    5001 1860.71  5015.8 1863.43  5022.1 1866.88  5072.3 1870.92
  5132.1 1872.73  5299.3 1882.19  5466.6 1895.31  5485.4 1895.23  5543.5 1900.45
#Mann= 3 , 0 , 0
  4669.4     .05       0  4978.6     .03       0  5022.1     .05       0
Bank Sta=4978.6,5022.1
XS Rating Curve= 0 ,0
Exp/Cntr=0.3,0.1

Chan Stop Cuts=-1
Use User Specified Reach Order=0
Composite Channel Slope=5