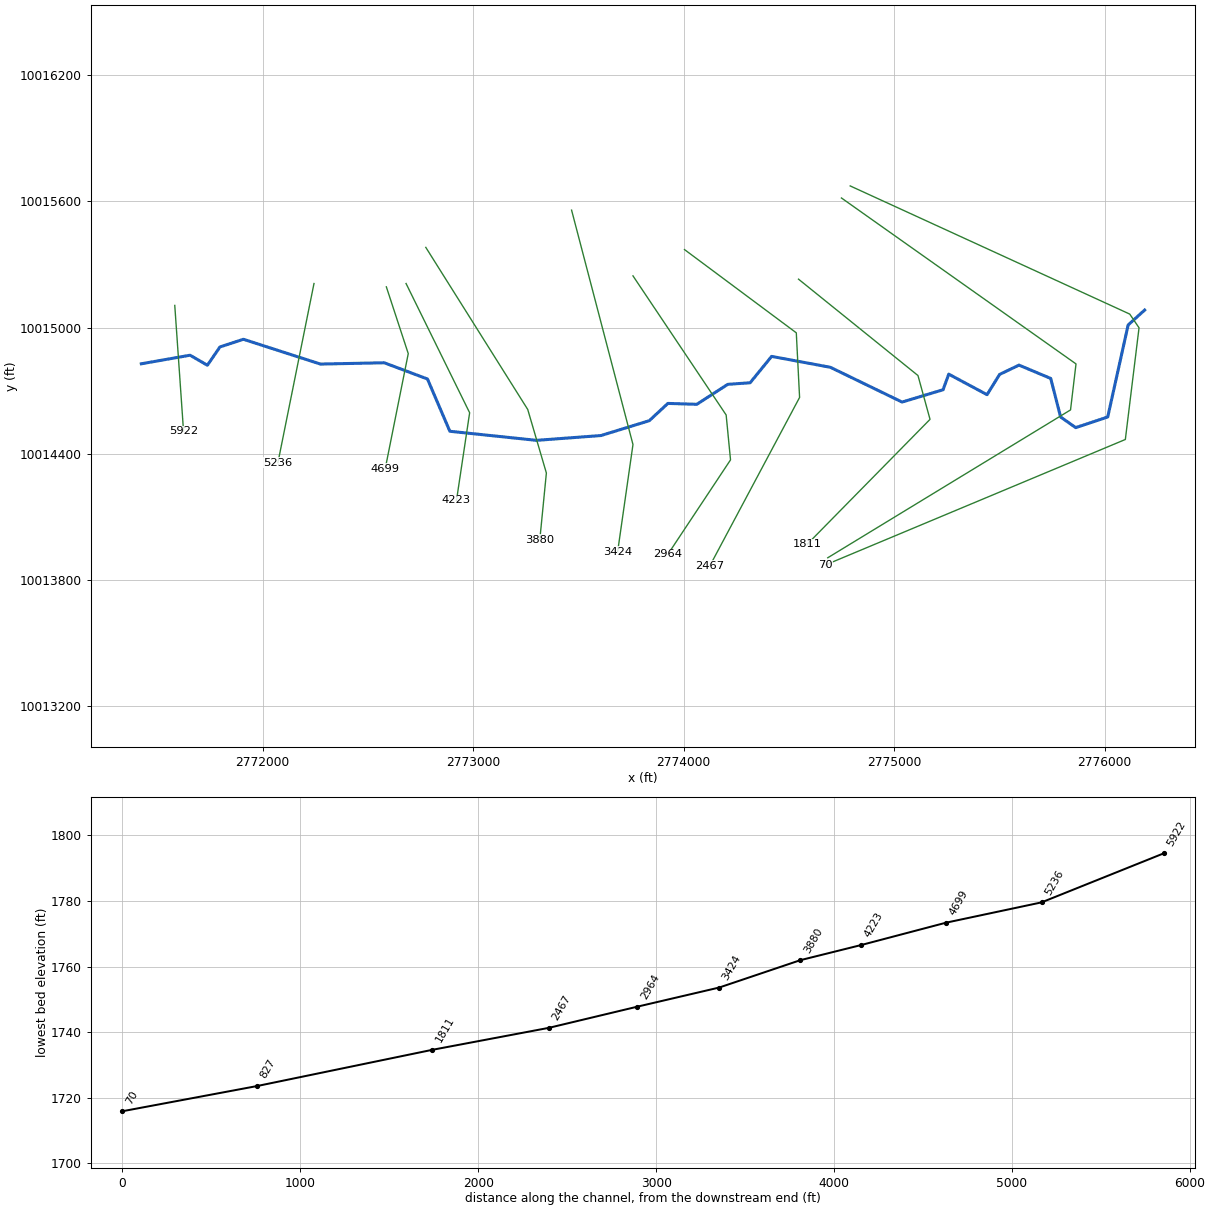
--- UNT027 IN SNOGR.prj (project) ---

Proj Title=UNT027 IN SNOGR Base Level Engineering
Current Plan=p01
Default Exp/Contr=0.3,0.1
English Units
Geom File=g01
Flow File=f01
Plan File=p01
BEGIN DESCRIPTION:
UNT027 IN SNOGR
END DESCRIPTION:

--- UNT027 IN SNOGR.p01 (plan) ---

Plan Title=Multiple Run
Short Identifier=Multiple
Geom File=g01
Flow File=f01
Subcritical Flow
K Sum by GR= 0
Std Step Tol= 0.01
Critical Tol= 0.01
Num of Std Step Trials= 20
Max Error Tol= 0.3
Flow Tol Ratio= 0.001
Split Flow NTrial= 30
Split Flow Tol= 0.02
Split Flow Ratio= 0.02
Log Output Level= 0
Friction Slope Method= 1
Unsteady Friction Slope Method= 2
Unsteady Bridges Friction Slope Method= 1
Parabolic Critical Depth
Global Vel Dist=  1 , 1 , 1
Global Log Level= 0
CheckData=True
Encroach Param= -1, 0, 0, 0
BEGIN DESCRIPTION:
Multiple Run
END DESCRIPTION:

--- UNT027 IN SNOGR.f01 (steady flow) ---

Flow Title=Multiple
Number of Profiles=7
Profile Names=10-year,25-year,50-year,1pct_min,100-year,1pct_plu,500-year
River Rch & RM= UNT027 IN SNOGR,Reach-1,5922
     702    1006    1267    1170    1582    2140    2474
Boundary for River Rch & Prof#=UNT027 IN SNOGR,Reach-1,1
Up Type=0
Dn Type=3
Dn Slope=0.005
Boundary for River Rch & Prof#=UNT027 IN SNOGR,Reach-1,2
Up Type=0
Dn Type=3
Dn Slope=0.005
Boundary for River Rch & Prof#=UNT027 IN SNOGR,Reach-1,3
Up Type=0
Dn Type=3
Dn Slope=0.005
Boundary for River Rch & Prof#=UNT027 IN SNOGR,Reach-1,4
Up Type=0
Dn Type=3
Dn Slope=0.005
Boundary for River Rch & Prof#=UNT027 IN SNOGR,Reach-1,5
Up Type=0
Dn Type=3
Dn Slope=0.005
Boundary for River Rch & Prof#=UNT027 IN SNOGR,Reach-1,6
Up Type=0
Dn Type=3
Dn Slope=0.005
Boundary for River Rch & Prof#=UNT027 IN SNOGR,Reach-1,7
Up Type=0
Dn Type=3
Dn Slope=0.005

--- UNT027 IN SNOGR.g01 (geometry) ---

Geom Title=Existing Conditions

River Reach=UNT027 IN SNOGR,Reach-1
Reach XY= 30
      2771423.53     10014827.71      2771655.27     10014868.47
      2771737.33     10014820.69      2771797.07     10014907.70
      2771908.42     10014944.24      2772274.39     10014826.35
      2772577.64     10014832.55      2772783.16     10014755.28
      2772889.46     10014506.79      2773301.16     10014463.63
      2773607.32     10014486.47      2773837.06     10014557.14
      2773925.40     10014639.26      2774062.81     10014634.99
      2774210.00     10014729.96      2774316.21     10014737.48
      2774418.31     10014862.87      2774697.36     10014811.05
      2775038.28     10014645.70      2775232.93     10014704.19
      2775259.97     10014778.32      2775441.94     10014680.79
      2775501.51     10014777.10      2775593.74     10014821.29
      2775744.36     10014758.03      2775791.44     10014574.77
      2775862.96     10014524.15      2776015.29     10014574.76
      2776112.29     10015012.22      2776190.74     10015083.18

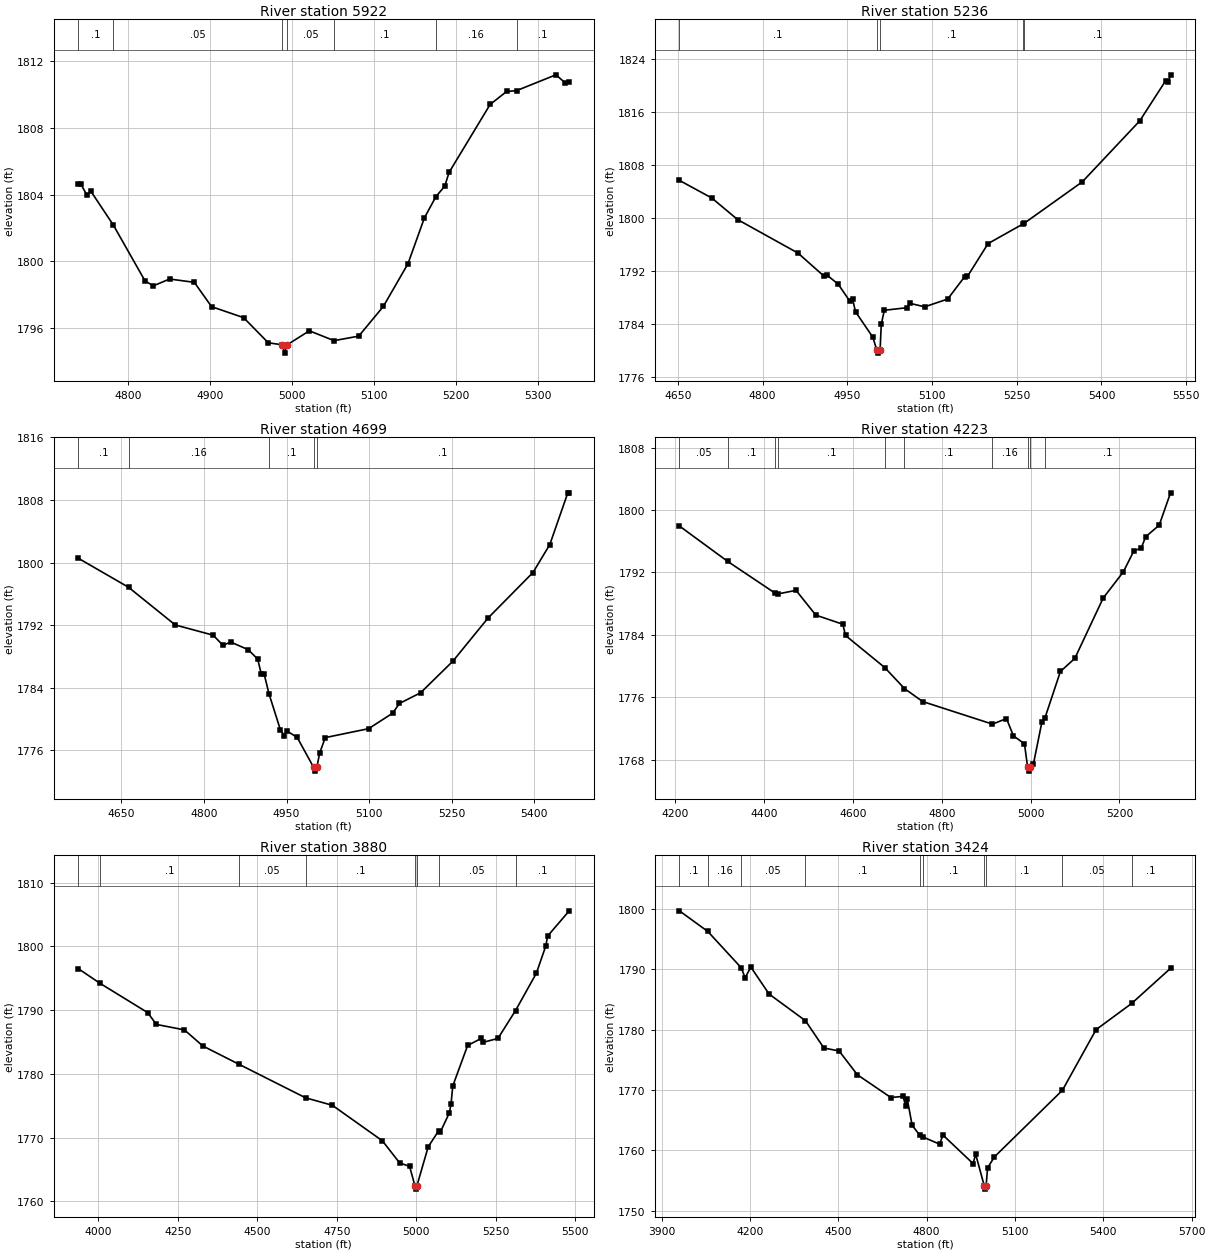
Type RM Length L Ch R = 1,5922,686,686,686
BEGIN DESCRIPTION:
UNT027 IN SNOGR 10.0
END DESCRIPTION:
XS GIS Cut Line= 2
      2771582.44     10015105.17      2771624.02     10014507.51
#Sta/Elev= 30
  4738.6 1804.64  4741.8 1804.64  4749.2 1803.98  4754.2 1804.20  4781.7 1802.16
  4820.2 1798.82  4830.3 1798.52  4850.3 1798.93  4880.4 1798.73  4901.4 1797.27
  4940.5 1796.61  4970.6 1795.10  4987.6 1794.98  4990.4 1794.48  4993.6 1794.98
  5020.7 1795.82  5050.8 1795.23  5080.9 1795.50  5110.9 1797.28  5141.0 1799.85
  5161.1 1802.61  5175.0 1803.87  5185.9 1804.51  5191.1 1805.33  5241.2 1809.41
  5261.3 1810.19  5273.4 1810.24  5321.4 1811.19  5333.1 1810.70  5337.7 1810.78
#Mann=7,-1,0
  4738.6     0.1       0  4781.7    0.05       0  4987.6   0.035       0
  4993.6    0.05       0  5050.8     0.1       0  5175.0    0.16       0
  5273.4     0.1       0
Bank Sta=4987.6,4993.6
Exp/Cntr=0.3,0.1

Type RM Length L Ch R = 1,5236,537,537,537
BEGIN DESCRIPTION:
UNT027 IN SNOGR 9.0
END DESCRIPTION:
XS GIS Cut Line= 2
      2772243.90     10015209.37      2772072.38     10014356.95
#Sta/Elev= 30
  4652.8 1805.67  4710.2 1803.00  4755.9 1799.74  4862.7 1794.68  4908.5 1791.21
  4913.6 1791.38  4934.0 1789.97  4954.2 1787.44  4959.3 1787.73  4964.6 1785.80
  4995.2 1781.96  5002.1 1780.05  5004.8 1779.55  5008.1 1780.05  5010.2 1783.95
  5015.6 1786.03  5055.9 1786.42  5061.0 1787.08  5087.0 1786.55  5127.8 1787.73
  5157.6 1791.09  5162.7 1791.14  5199.2 1796.11  5261.3 1799.09  5262.8 1799.16
  5366.1 1805.45  5467.8 1814.67  5513.5 1820.72  5518.6 1820.58  5522.3 1821.63
#Mann=5,-1,0
  4652.8     0.1       0  5002.1    0.07       0  5008.1     0.1       0
  5261.3    0.16       0  5262.8     0.1       0
Bank Sta=5002.1,5008.1
Exp/Cntr=0.3,0.1

Type RM Length L Ch R = 1,4699,476,476,476
BEGIN DESCRIPTION:
UNT027 IN SNOGR 8.0
END DESCRIPTION:
XS GIS Cut Line= 3
      2772587.65     10015193.73      2772691.82     10014876.02
      2772582.43     10014329.10
#Sta/Elev= 30
  4571.3 1800.56  4662.9 1796.84  4747.7 1792.03  4816.6 1790.72  4834.4 1789.43
  4848.5 1789.84  4880.3 1788.87  4897.5 1787.67  4904.2 1785.71  4909.4 1785.71
  4918.1 1783.22  4938.6 1778.67  4946.0 1777.87  4951.1 1778.46  4969.2 1777.67
  4999.0 1773.86  5001.8 1773.36  5005.0 1773.86  5010.0 1775.65  5020.2 1777.64
  5098.9 1778.78  5142.5 1780.75  5155.0 1782.00  5193.5 1783.37  5251.9 1787.39
  5315.9 1792.91  5397.5 1798.72  5428.1 1802.29  5460.8 1808.90  5463.4 1808.90
#Mann=5,-1,0
  4571.3     0.1       0  4662.9    0.16       0  4918.1     0.1       0
  4999.0    0.07       0  5005.0     0.1       0
Bank Sta=4999,5005
Exp/Cntr=0.3,0.1

Type RM Length L Ch R = 1,4223,343,343,343
BEGIN DESCRIPTION:
UNT027 IN SNOGR 7.0
END DESCRIPTION:
XS GIS Cut Line= 3
      2772681.40     10015209.36      2772983.48     10014594.77
      2772921.03     10014178.44
#Sta/Elev= 30
  4209.4 1797.95  4318.3 1793.41  4425.7 1789.32  4431.7 1789.26  4472.0 1789.71
  4516.5 1786.54  4577.3 1785.37  4583.4 1783.93  4671.6 1779.83  4716.0 1777.14
  4757.1 1775.47  4914.2 1772.58  4945.8 1773.29  4961.4 1771.08  4986.3 1770.06
  4993.4 1767.06  4996.1 1766.56  4999.4 1767.06  5006.5 1767.47  5025.4 1772.81
  5032.1 1773.32  5067.2 1779.32  5099.6 1780.99  5163.6 1788.73  5208.7 1792.06
  5232.7 1794.77  5249.2 1795.13  5259.3 1796.58  5289.6 1798.05  5315.2 1802.20
#Mann=10,-1,0
  4209.4    0.05       0  4318.3     0.1       0  4425.7    0.16       0
  4431.7     0.1       0  4671.6    0.05       0  4716.0     0.1       0
  4914.2    0.16       0  4993.4    0.07       0  4999.4    0.16       0
  5032.1     0.1       0
Bank Sta=4993.4,4999.4
Exp/Cntr=0.3,0.1

Type RM Length L Ch R = 1,3880,456,456,456
BEGIN DESCRIPTION:
UNT027 IN SNOGR 6.0
END DESCRIPTION:
XS GIS Cut Line= 4
      2772775.16     10015381.21      2773259.52     10014610.39
      2773348.07     10014308.31      2773316.82     10013990.60
#Sta/Elev= 30
  3936.7 1796.54  4006.1 1794.20  4155.6 1789.62  4182.7 1787.77  4271.1 1786.91
  4328.8 1784.39  4441.3 1781.55  4651.9 1776.26  4736.3 1775.08  4893.6 1769.51
  4947.8 1766.04  4979.1 1765.50  4996.0 1762.43  4998.7 1761.93  5002.0 1762.43
  5037.6 1768.57  5070.4 1771.08  5076.2 1770.93  5104.1 1773.89  5109.6 1775.36
  5114.8 1778.10  5161.6 1784.47  5205.2 1785.59  5210.3 1784.96  5256.9 1785.57
  5312.3 1789.95  5377.5 1795.78  5407.6 1800.10  5412.9 1801.62  5481.1 1805.59
#Mann=8,-1,0
  3936.7    0.05       0  4006.1     0.1       0  4441.3    0.05       0
  4651.9     0.1       0  4996.0    0.07       0  5002.0     0.1       0
  5070.4    0.05       0  5312.3     0.1       0
Bank Sta=4996,5002
Exp/Cntr=0.3,0.1

Type RM Length L Ch R = 1,3424,460,460,460
BEGIN DESCRIPTION:
UNT027 IN SNOGR 5.0
END DESCRIPTION:
XS GIS Cut Line= 3
      2773467.85     10015558.33      2773759.52     10014443.72
      2773686.61     10013933.34
#Sta/Elev= 30
  3960.6 1799.68  4057.1 1796.26  4170.2 1790.27  4183.9 1788.59  4203.1 1790.37
  4265.1 1785.90  4388.6 1781.48  4451.2 1776.96  4502.9 1776.47  4564.9 1772.53
  4678.6 1768.76  4719.9 1768.95  4729.2 1767.35  4734.4 1768.47  4750.9 1764.16
  4777.2 1762.49  4786.8 1762.24  4844.0 1761.04  4855.6 1762.54  4957.7 1757.82
  4966.6 1759.36  4996.0 1754.09  4998.8 1753.59  5002.0 1754.09  5007.0 1757.10
  5030.0 1758.92  5261.1 1769.96  5375.4 1780.00  5496.2 1784.34  5628.3 1790.16
#Mann=10,-1,0
  3960.6     0.1       0  4057.1    0.16       0  4170.2    0.05       0
  4388.6     0.1       0  4777.2    0.16       0  4786.8     0.1       0
  4996.0    0.07       0  5002.0     0.1       0  5261.1    0.05       0
  5496.2     0.1       0
Bank Sta=4996,5002
Exp/Cntr=0.3,0.1

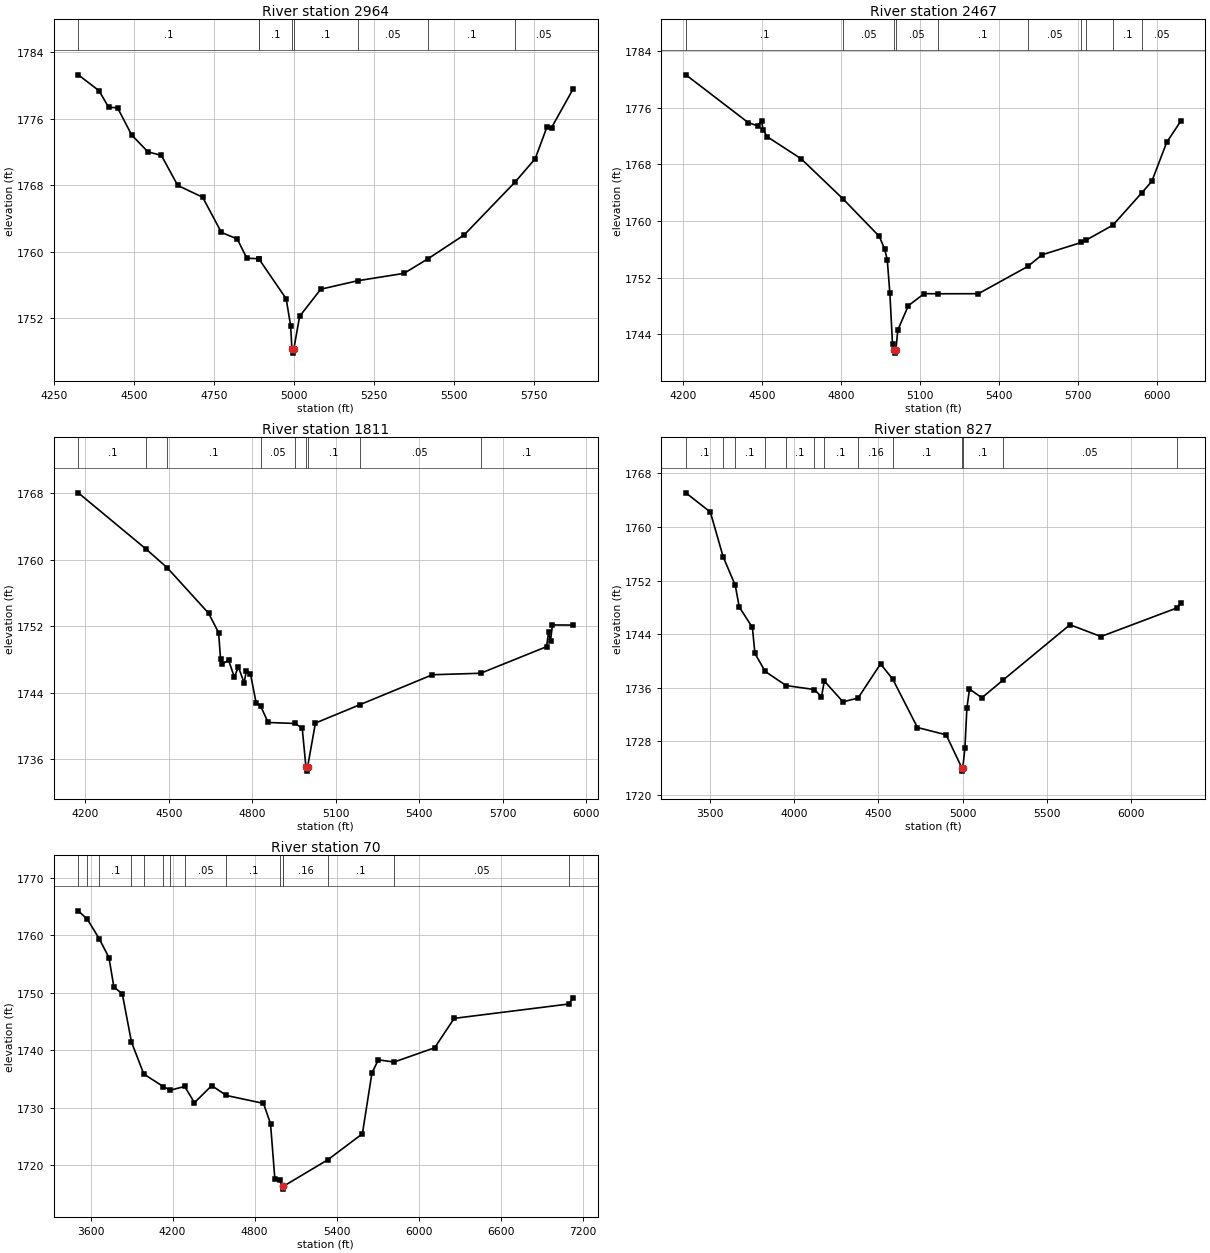
Type RM Length L Ch R = 1,2964,497,497,497
BEGIN DESCRIPTION:
UNT027 IN SNOGR 4.0
END DESCRIPTION:
XS GIS Cut Line= 4
      2773759.53     10015245.80      2774202.23     10014584.35
      2774223.07     10014370.81      2773926.17     10013922.85
#Sta/Elev= 30
  4325.3 1781.29  4390.1 1779.38  4420.2 1777.38  4448.1 1777.32  4492.2 1774.05
  4543.2 1772.01  4585.3 1771.58  4636.3 1767.97  4714.4 1766.54  4773.0 1762.30
  4822.5 1761.52  4852.5 1759.20  4890.0 1759.13  4890.4 1759.11  4975.6 1754.31
  4989.6 1751.07  4993.6 1748.26  4996.4 1747.76  4999.6 1748.26  5017.6 1752.18
  5083.7 1755.46  5200.5 1756.49  5344.3 1757.37  5420.2 1759.15  5532.2 1761.99
  5692.0 1768.38  5754.8 1771.19  5790.9 1774.95  5805.9 1774.93  5873.2 1779.58
#Mann=8,-1,0
  4325.3     0.1       0  4890.0    0.05       0  4890.4     0.1       0
  4993.6    0.07       0  4999.6     0.1       0  5200.5    0.05       0
  5420.2     0.1       0  5692.0    0.05       0
Bank Sta=4993.6,4999.6
Exp/Cntr=0.3,0.1

Type RM Length L Ch R = 1,2467,656,656,656
BEGIN DESCRIPTION:
UNT027 IN SNOGR 3.0
END DESCRIPTION:
XS GIS Cut Line= 4
      2774004.32     10015370.81      2774535.57     10014974.97
      2774551.19     10014667.68      2774124.95     10013867.18
#Sta/Elev= 30
  4211.0 1780.65  4447.8 1773.89  4483.3 1773.44  4497.9 1774.14  4504.1 1772.91
  4518.7 1771.92  4648.0 1768.79  4807.7 1763.09  4944.8 1757.81  4964.9 1756.02
  4974.9 1754.54  4984.9 1749.75  4994.9 1742.58  5001.9 1741.81  5004.7 1741.31
  5007.9 1741.81  5014.9 1744.56  5055.0 1748.02  5115.1 1749.72  5165.9 1749.70
  5320.6 1749.71  5507.8 1753.56  5562.3 1755.21  5711.8 1756.96  5730.1 1757.30
  5830.9 1759.40  5941.5 1764.01  5978.7 1765.60  6035.4 1771.13  6088.1 1774.08
#Mann=10,-1,0
  4211.0     0.1       0  4807.7    0.05       0  5001.9   0.035       0
  5007.9    0.05       0  5165.9     0.1       0  5507.8    0.05       0
  5711.8     0.1       0  5730.1    0.05       0  5830.9     0.1       0
  5941.5    0.05       0
Bank Sta=5001.9,5007.9
Exp/Cntr=0.3,0.1

Type RM Length L Ch R = 1,1811,984,984,984
BEGIN DESCRIPTION:
UNT027 IN SNOGR 2.0
END DESCRIPTION:
XS GIS Cut Line= 4
      2774546.02     10015230.16      2775113.69     10014771.85
      2775170.98     10014563.52      2774587.66     10013969.78
#Sta/Elev= 30
  4174.5 1768.01  4418.7 1761.24  4494.0 1759.02  4642.6 1753.56  4678.9 1751.21
  4685.7 1748.01  4692.2 1747.46  4714.5 1747.93  4735.3 1745.88  4749.7 1747.11
  4770.5 1745.20  4778.5 1746.66  4792.9 1746.31  4813.7 1742.78  4829.6 1742.42
  4856.8 1740.44  4954.4 1740.32  4979.3 1739.74  4992.5 1735.10  4995.2 1734.60
  4998.5 1735.10  5026.6 1740.37  5185.5 1742.56  5447.0 1746.17  5620.3 1746.35
  5857.2 1749.54  5864.2 1751.26  5871.4 1750.25  5878.4 1752.15  5952.5 1752.13
#Mann=9,-1,0
  4174.5     0.1       0  4418.7    0.05       0  4494.0     0.1       0
  4829.6    0.05       0  4954.4     0.1       0  4992.5    0.07       0
  4998.5     0.1       0  5185.5    0.05       0  5620.3     0.1       0
Bank Sta=4992.5,4998.5
Exp/Cntr=0.3,0.1

Type RM Length L Ch R = 1,827,757,757,757
BEGIN DESCRIPTION:
Mapping XS 3965a13c
END DESCRIPTION:
XS GIS Cut Line= 4
      2774750.03     10015616.15      2775864.60     10014827.10
      2775838.56     10014608.35      2774684.94     10013905.23
#Sta/Elev= 30
  3357.0 1765.11  3502.1 1762.24  3578.2 1755.57  3650.2 1751.30  3673.6 1748.08
  3751.9 1745.01  3766.7 1741.15  3827.6 1738.45  3952.3 1736.34  4119.3 1735.75
  4161.8 1734.67  4178.9 1737.01  4289.7 1733.91  4379.0 1734.48  4512.5 1739.57
  4584.6 1737.31  4731.6 1730.08  4901.8 1728.99  4994.7 1724.07  4997.5 1723.57
  5000.7 1724.07  5013.2 1726.99  5025.0 1732.98  5040.4 1735.82  5113.9 1734.52
  5237.1 1737.11  5636.8 1745.42  5820.7 1743.66  6272.9 1747.94  6293.9 1748.66
#Mann=13,-1,0
  3357.0     0.1       0  3578.2    0.05       0  3650.2     0.1       0
  3827.6    0.05       0  3952.3     0.1       0  4119.3    0.05       0
  4178.9     0.1       0  4379.0    0.16       0  4584.6     0.1       0
  4994.7    0.07       0  5000.7     0.1       0  5237.1    0.05       0
  6272.9     0.1       0
Bank Sta=4994.7,5000.7
Exp/Cntr=0.3,0.1

Type RM Length L Ch R = 1,70,0,0,0
BEGIN DESCRIPTION:
UNT027 IN SNOGR 1.0
END DESCRIPTION:
XS GIS Cut Line= 5
      2774791.72     10015673.43      2776119.81     10015064.07
      2776164.08     10014998.97      2776098.98     10014467.72
      2774674.53     10013871.38
#Sta/Elev= 30
  3510.3 1764.26  3576.2 1762.80  3662.6 1759.45  3734.8 1756.12  3770.8 1751.01
  3832.3 1749.83  3899.3 1741.46  3989.4 1735.90  4133.6 1733.69  4183.6 1733.09
  4288.6 1733.73  4360.1 1730.91  4486.1 1733.88  4593.8 1732.17  4865.0 1730.79
  4916.5 1727.27  4948.0 1717.71  4987.9 1717.40  5004.9 1716.39  5007.6 1715.89
  5010.9 1716.39  5336.2 1721.00  5588.5 1725.51  5658.5 1736.11  5705.3 1738.36
  5820.4 1737.98  6117.2 1740.46  6259.9 1745.57  7097.5 1748.06  7129.7 1749.15
#Mann=15,-1,0
  3510.3     0.1       0  3576.2    0.05       0  3662.6     0.1       0
  3899.3    0.05       0  3989.4     0.1       0  4133.6    0.05       0
  4183.6     0.1       0  4288.6    0.05       0  4593.8     0.1       0
  4987.9    0.16       0  5004.9    0.07       0  5010.9    0.16       0
  5336.2     0.1       0  5820.4    0.05       0  7097.5     0.1       0
Bank Sta=5004.9,5010.9
Exp/Cntr=0.3,0.1

Chan Stop Cuts=-1