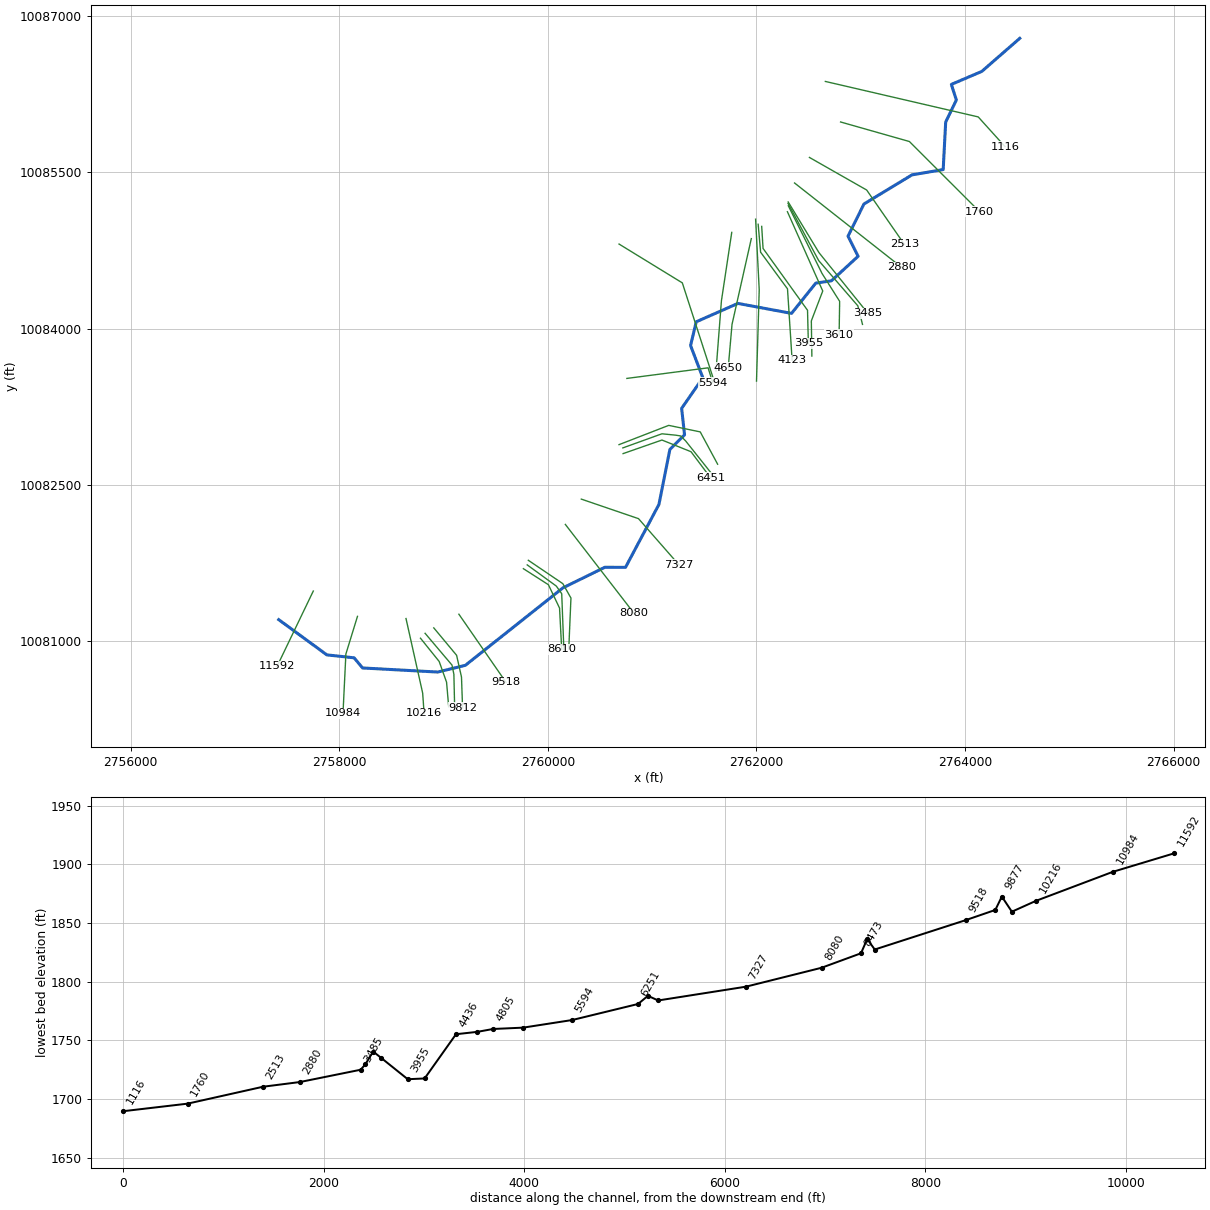
--- UNT028 IN NNOGR.prj (project) ---

Proj Title=UNT028 IN NNOGR Base Level Engineering
Current Plan=p01
Default Exp/Contr=0.3,0.1
English Units
Geom File=g01
Flow File=f01
Plan File=p01
Y Axis Title=Elevation
X Axis Title(PF)=Main Channel Distance
X Axis Title(XS)=Station
BEGIN DESCRIPTION:
UNT028 IN NNOGR
END DESCRIPTION:
DSS Export Rating Curves= 0
DSS Export Rating Curve Sorted= 0
DSS Export Volume Flow Curves= 0
DXF OffsetX= 0
DXF OffsetY= 0
DXF ScaleX= 1
DXF ScaleY= 10

--- UNT028 IN NNOGR.p01 (plan) ---

Plan Title=Multiple Run
Short Identifier=Multiple
Geom File=g01
Flow File=f01
Subcritical Flow
K Sum by GR= 0
Std Step Tol= 0.01
Critical Tol= 0.01
Num of Std Step Trials= 20
Max Error Tol= 0.3
Flow Tol Ratio= 0.001
Split Flow NTrial= 30
Split Flow Tol= 0.02
Split Flow Ratio= 0.02
Log Output Level= 0
Friction Slope Method= 1
Unsteady Friction Slope Method= 2
Unsteady Bridges Friction Slope Method= 1
Parabolic Critical Depth
Global Vel Dist=  1 , 1 , 1
Global Log Level= 0
CheckData=True
Encroach Param= -1, 0, 0, 0
BEGIN DESCRIPTION:
Multiple Run
END DESCRIPTION:

--- UNT028 IN NNOGR.f01 (steady flow) ---

Flow Title=Multiple
Program Version=4.10
Number of Profiles= 7
Profile Names=10-year,25-year,50-year,1pct_min,100-year,1pct_plu,500-year
River Rch & RM=UNT028 IN NNOGR,Reach-1         ,11592
     501     706     880     805    1089    1473    1672
River Rch & RM=UNT028 IN NNOGR,Reach-1         ,5105
     984    1445    1849    1732    2343    3168    3777
Boundary for River Rch & Prof#=UNT028 IN NNOGR,Reach-1         , 1
Up Type= 0
Dn Type= 3
Dn Slope=0.0125
Boundary for River Rch & Prof#=UNT028 IN NNOGR,Reach-1         , 2
Up Type= 0
Dn Type= 3
Dn Slope=0.0125
Boundary for River Rch & Prof#=UNT028 IN NNOGR,Reach-1         , 3
Up Type= 0
Dn Type= 3
Dn Slope=0.0125
Boundary for River Rch & Prof#=UNT028 IN NNOGR,Reach-1         , 4
Up Type= 0
Dn Type= 3
Dn Slope=0.0125
Boundary for River Rch & Prof#=UNT028 IN NNOGR,Reach-1         , 5
Up Type= 0
Dn Type= 3
Dn Slope=0.0125
Boundary for River Rch & Prof#=UNT028 IN NNOGR,Reach-1         , 6
Up Type= 0
Dn Type= 3
Dn Slope=0.0125
Boundary for River Rch & Prof#=UNT028 IN NNOGR,Reach-1         , 7
Up Type= 0
Dn Type= 3
Dn Slope=0.0125
DSS Import GetInterval= 0
DSS Import GetPeak= 0
DSS Import FillOption= 0

--- UNT028 IN NNOGR.g01 (geometry) ---

Geom Title=Existing Conditions
Program Version=4.10

River Reach=UNT028 IN NNOGR ,Reach-1
Reach XY= 30
      2757420.09     10081209.42      2757882.04     10080871.13
      2758143.15     10080843.13      2758223.93     10080745.75
      2758944.53     10080706.55      2759209.64     10080771.14
      2760144.53     10081513.85      2760547.88     10081711.94
      2760745.07     10081710.75      2761065.76     10082314.85
       2761170.6     10082841.79      2761311.11     10082982.12
      2761283.38     10083236.31      2761486.63     10083529.73
      2761368.89      10083838.9      2761423.29     10084066.73
      2761822.82     10084243.06      2762337.09     10084147.47
      2762569.46     10084437.82      2762719.41     10084460.05
      2762975.47     10084695.35      2762878.45     10084888.47
      2763031.61     10085197.13      2763492.11     10085476.38
      2763790.98     10085527.19      2763814.93     10085983.29
      2763917.24     10086194.14       2763869.2     10086344.27
      2764161.28     10086468.96      2764525.05      10086786.2

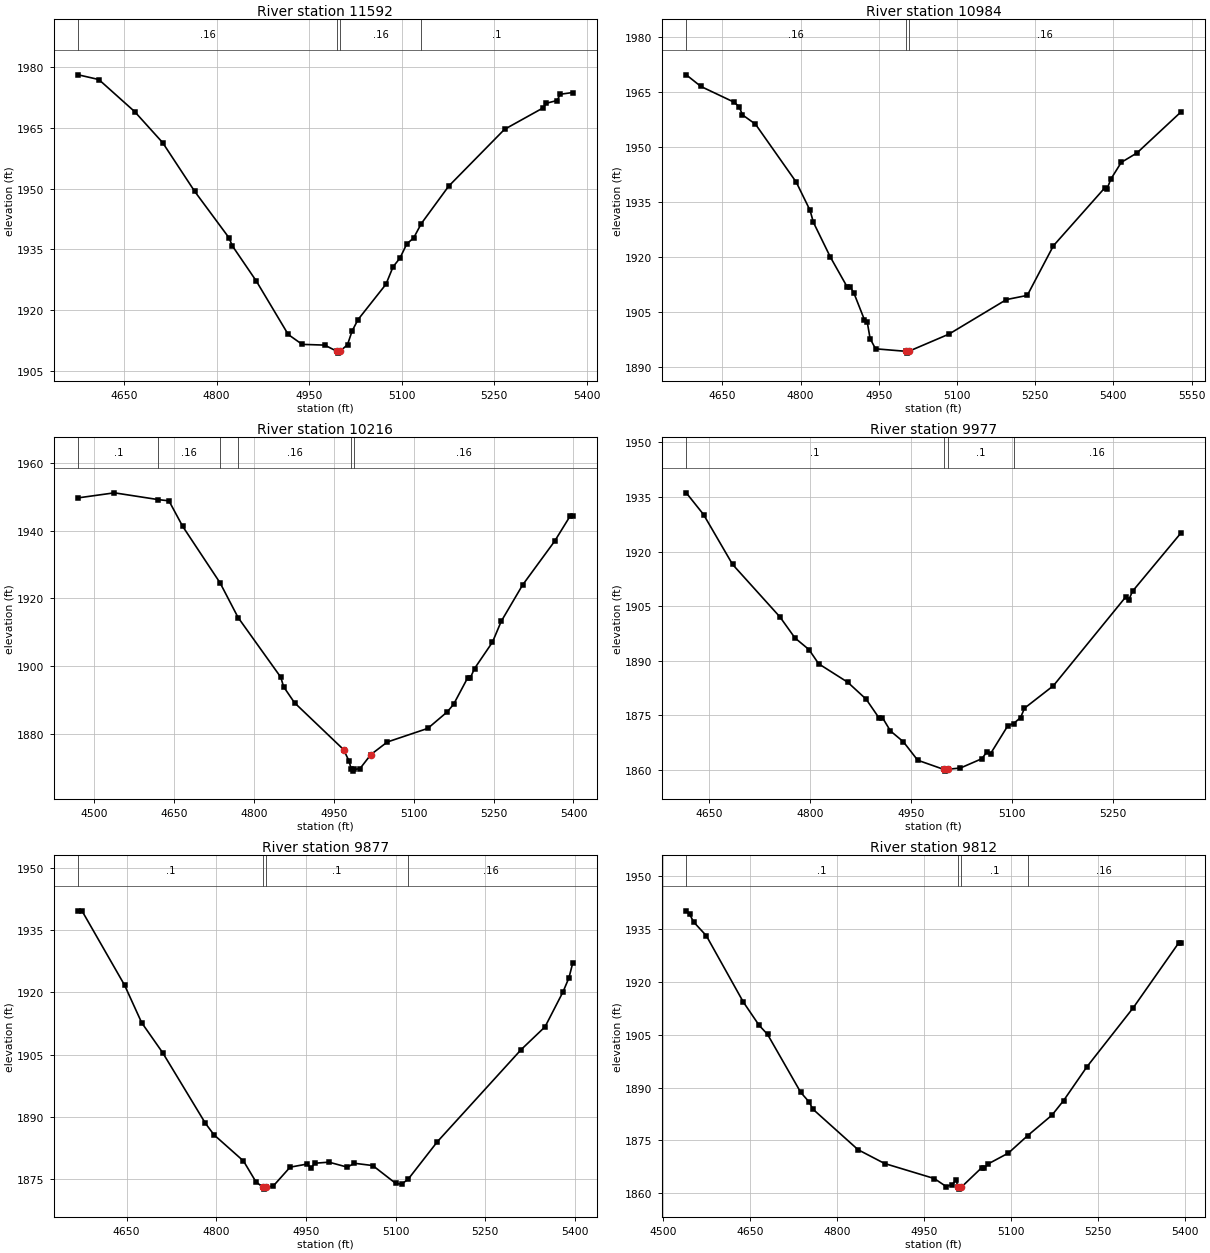
Type RM Length L Ch R = 1 ,11592   ,608,608,608
BEGIN DESCRIPTION:
UNT028 IN NNOGR 24.0
END DESCRIPTION:
XS GIS Cut Line= 2
       2757751.8     10081483.76      2757404.56     10080761.49
#Sta/Elev= 30
  4575.8  1978.1  4609.1 1976.94  4667.2 1969.02  4712.5 1961.38  4764.5 1949.33
  4819.9 1937.92  4825.7 1935.85  4864.3 1927.22  4916.2 1913.99  4938.8 1911.55
  4975.3 1911.37  4994.5 1909.89  4997.2 1909.39  5000.5 1909.89  5012.3 1911.48
  5019.7 1914.85  5029.4 1917.68  5074.6 1926.39  5086.2 1930.72  5097.3 1932.84
  5108.4 1936.37  5119.5 1937.82  5131.9 1941.37  5176.3 1950.61  5266.8 1964.64
  5329.2 1969.92  5334.7 1971.09  5351.8 1971.75  5357.4 1973.31  5377.2 1973.73
#Mann= 4 ,-1 , 0
  4575.8     .16       0  4994.5     .07       0  5000.5     .16       0
  5131.9      .1       0
Bank Sta=4994.5,5000.5
XS Rating Curve= 0 ,0
Exp/Cntr=0.3,0.1

Type RM Length L Ch R = 1 ,10984   ,768,768,768
BEGIN DESCRIPTION:
UNT028 IN NNOGR 23.0
END DESCRIPTION:
XS GIS Cut Line= 3
      2758175.41     10081240.71      2758064.29     10080879.57
      2758036.51     10080310.09
#Sta/Elev= 30
  4580.9 1969.67  4609.1 1966.49  4671.9 1962.25  4682.4 1960.99  4688.6 1958.75
  4713.7 1956.19  4791.9 1940.36  4818.4 1932.65  4824.6 1929.44  4857.3 1919.91
    4890 1911.65  4895.2 1911.75  4902.1 1910.21  4922.7 1902.77  4927.9 1902.25
  4933.5 1897.66  4943.9 1894.88  5001.6  1894.2  5004.4  1893.7  5007.6  1894.2
  5084.7 1898.89  5194.9 1908.32  5234.9 1909.46    5285 1923.01  5383.1 1938.75
  5388.1 1938.63  5395.1 1941.19  5415.1 1945.77  5445.2 1948.34  5528.9 1959.44
#Mann= 3 ,-1 , 0
  4580.9     .16       0  5001.6     .07       0  5007.6     .16       0
Bank Sta=5001.6,5007.6
XS Rating Curve= 0 ,0
Exp/Cntr=0.3,0.1

Type RM Length L Ch R = 1 ,10216   ,239,239,239
BEGIN DESCRIPTION:
UNT028 IN NNOGR 22.0
END DESCRIPTION:
XS GIS Cut Line= 3
      2758640.67     10081219.87       2758800.4     10080504.57
      2758814.29     10080310.08
#Sta/Elev= 30
  4470.5 1949.76  4538.3 1951.25  4620.8 1949.24  4640.7 1948.88  4666.6  1941.3
  4736.6 1924.63  4770.5 1914.35  4850.6 1896.69  4855.9 1893.87  4876.4 1889.13
  4968.6 1875.25  4978.9 1871.81    4983 1869.39  4985.8 1868.89    4989 1869.39
  4999.3 1869.64  5019.8  1873.8  5050.6 1877.51  5126.6 1881.54  5163.3 1886.45
  5175.1 1888.69  5201.3 1896.46  5206.3 1896.46  5214.3 1899.25  5247.9 1907.04
  5264.4 1913.22  5304.5 1923.97  5364.7 1936.94    5394 1944.44  5398.4 1944.44
#Mann= 6 ,-1 , 0
  4470.5      .1       0  4620.8     .16       0  4736.6      .1       0
  4770.5     .16       0    4983     .07       0    4989     .16       0
Bank Sta=4968.6,5019.8
XS Rating Curve= 0 ,0
Exp/Cntr=0.3,0.1

Type RM Length L Ch R = 1 ,9977    ,100,100,100
BEGIN DESCRIPTION:
Mapping XS aa7c7d05
END DESCRIPTION:
XS GIS Cut Line= 4
      2758779.42     10081031.35      2758959.08     10080807.42
      2759029.39      10080609.5      2759050.22     10080372.55
#Sta/Elev= 30
  4615.6 1936.15  4641.3 1930.19  4684.5 1916.47  4754.9 1902.05  4777.3 1896.26
  4798.1 1893.07  4812.5 1889.17  4855.7  1884.1    4883 1879.46  4901.9 1874.38
  4907.3 1874.38  4919.2 1870.72  4938.4 1867.75  4959.7 1862.68  4998.1 1860.18
  5000.9 1859.68  5004.1 1860.18  5023.3 1860.54  5055.2  1863.1  5062.8 1865.04
  5068.1 1864.49  5093.7 1872.15  5102.3 1872.76  5112.7  1874.4  5118.5 1876.97
  5161.5 1883.15  5268.8 1907.49  5273.8 1906.83  5279.1  1909.1  5350.6    1925
#Mann= 4 ,-1 , 0
  4615.6      .1       0  4998.1     .07       0  5004.1      .1       0
  5102.3     .16       0
Bank Sta=4998.1,5004.1
XS Rating Curve= 0 ,0
Exp/Cntr=0.3,0.1

Type RM Length L Ch R = 1 ,9877    ,65,65,65
BEGIN DESCRIPTION:
Mapping XS fe065d21
END DESCRIPTION:
XS GIS Cut Line= 4
      2758823.66     10081078.25      2759081.48     10080773.57
      2759099.71     10080685.02      2759107.49     10080347.64
#Sta/Elev= 30
    4569 1939.66  4575.2 1939.66  4646.5 1921.74  4675.1 1912.69  4710.2 1905.47
  4781.7 1888.45    4796 1885.68  4845.4 1879.36  4866.3 1874.33  4877.5 1873.08
  4880.3 1872.58  4883.5 1873.08  4894.8 1873.26  4923.4 1877.87    4952 1878.63
  4958.5 1877.69  4964.7 1878.82  4988.4 1879.08    5019 1877.88    5031 1878.81
  5061.7 1878.26  5099.8 1873.99  5109.8 1873.77    5121 1874.99  5169.8 1884.02
  5309.9 1906.21  5349.9 1911.71  5379.9 1920.11  5389.9 1923.53    5396 1926.97
#Mann= 4 ,-1 , 0
    4569      .1       0  4877.5     .07       0  4883.5      .1       0
    5121     .16       0
Bank Sta=4877.5,4883.5
XS Rating Curve= 0 ,0
Exp/Cntr=0.3,0.1

Type RM Length L Ch R = 1 ,9812    ,294,294,294
BEGIN DESCRIPTION:
Mapping XS 30f527d3
END DESCRIPTION:
XS GIS Cut Line= 4
      2758907.01     10081130.32      2759125.75     10080867.32
      2759172.62     10080658.98      2759183.04     10080362.08
#Sta/Elev= 30
  4539.6 1940.13  4545.7  1939.1  4552.2 1936.99  4574.2 1933.07  4638.1 1914.24
  4665.4 1907.63  4679.8 1905.09  4737.1 1888.62  4751.4 1885.94  4757.9 1883.89
    4836 1872.36  4881.7 1868.45  4967.4 1864.19  4987.9 1861.92  4998.1 1862.47
  5005.6 1863.88  5007.7 1861.68  5010.5 1861.18  5013.7 1861.68  5048.9 1867.21
    5054 1867.17  5059.6 1868.27  5095.2  1871.4  5128.5 1876.36  5170.5 1882.18
  5190.5 1886.31  5230.6 1895.86  5310.6 1912.63    5389 1931.02  5392.3 1931.02
#Mann= 4 ,-1 , 0
  4539.6      .1       0  5007.7     .07       0  5013.7      .1       0
  5128.5     .16       0
Bank Sta=5007.7,5013.7
XS Rating Curve= 0 ,0
Exp/Cntr=0.3,0.1

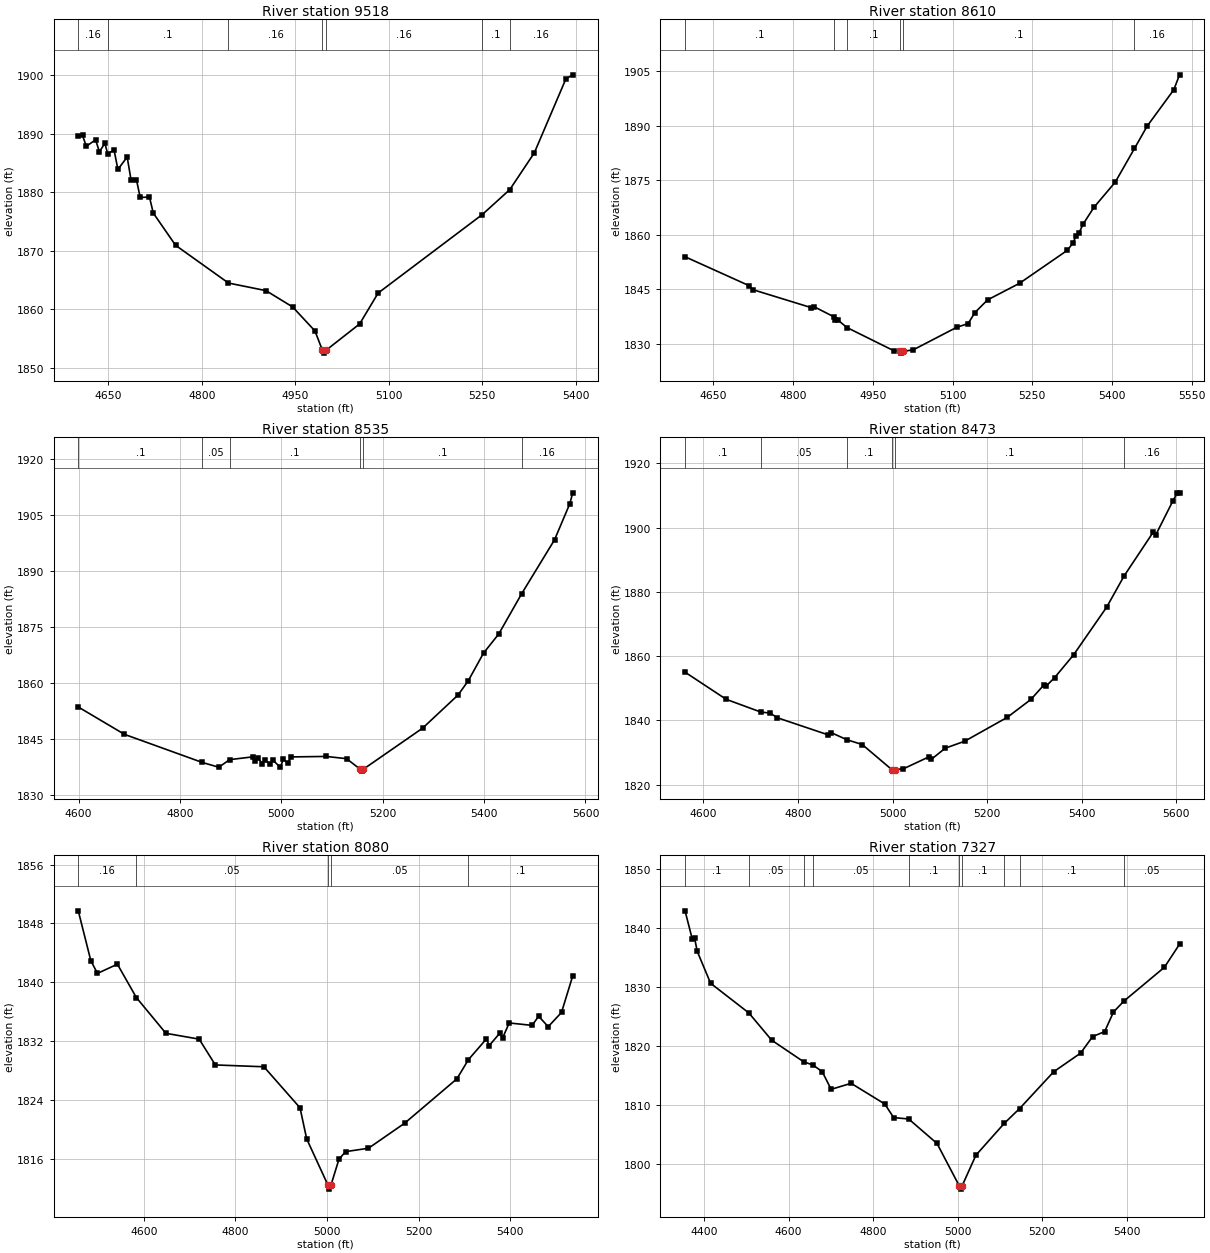
Type RM Length L Ch R = 1 ,9518    ,908,908,908
BEGIN DESCRIPTION:
UNT028 IN NNOGR 20.0
END DESCRIPTION:
XS GIS Cut Line= 2
       2759147.6     10081261.54      2759599.03     10080608.71
#Sta/Elev= 30
  4601.9 1889.68  4608.8 1889.72  4614.8 1887.86  4629.7 1888.98  4635.8 1886.92
  4644.6 1888.39  4649.1  1886.6  4659.4 1887.21  4665.5 1883.91  4680.4 1886.03
  4686.5 1882.18  4695.3 1882.14  4701.3 1879.12  4716.2 1879.18  4722.3 1876.45
  4758.1 1870.94    4843 1864.49  4903.2 1863.19    4946  1860.4  4981.8  1856.3
  4993.7 1853.01  4996.4 1852.51  4999.7 1853.01  5053.5  1857.5  5083.2 1862.78
  5250.3 1876.19  5294.5 1880.46  5333.9 1886.75  5384.6  1899.4  5395.6 1900.08
#Mann= 7 ,-1 , 0
  4601.9     .16       0  4649.1      .1       0    4843     .16       0
  4993.7     .07       0  4999.7     .16       0  5250.3      .1       0
  5294.5     .16       0
Bank Sta=4993.7,4999.7
XS Rating Curve= 0 ,0
Exp/Cntr=0.3,0.1

Type RM Length L Ch R = 1 ,8610    ,75,75,75
BEGIN DESCRIPTION:
UNT028 IN NNOGR 18.0
END DESCRIPTION:
XS GIS Cut Line= 4
      2759766.38     10081698.04      2760005.96      10081544.4
      2760112.73     10081320.44      2760133.51      10080922.9
#Sta/Elev= 30
  4596.5 1853.93  4717.8 1845.93  4724.3 1844.87  4833.3 1839.97  4839.3  1840.2
  4876.8 1837.41  4879.6 1836.53  4884.2 1836.53  4901.2 1834.47  4989.3  1828.1
  5000.7 1827.93  5003.5 1827.43  5006.7 1827.93  5025.9 1828.32  5108.3 1834.56
  5129.2 1835.53  5142.2  1838.6    5166 1842.07  5226.1 1846.63  5316.2 1855.71
  5326.2 1857.61    5333 1859.77  5338.1 1860.51  5346.2    1863  5366.2 1867.52
  5406.3 1874.45  5442.5 1883.71  5466.4 1889.86  5516.4 1899.83  5527.3 1903.95
#Mann= 6 ,-1 , 0
  4596.5      .1       0  4876.8     .05       0  4901.2      .1       0
  5000.7     .07       0  5006.7      .1       0  5442.5     .16       0
Bank Sta=5000.7,5006.7
XS Rating Curve= 0 ,0
Exp/Cntr=0.3,0.1

Type RM Length L Ch R = 1 ,8535    ,62,62,62
BEGIN DESCRIPTION:
Mapping XS 3a8febd1
END DESCRIPTION:
XS GIS Cut Line= 4
      2759802.79     10081734.53      2760081.48     10081531.38
      2760133.56     10081458.46      2760154.36     10080917.74
#Sta/Elev= 30
  4599.4 1853.55  4690.5 1846.23  4844.1 1838.71  4876.7 1837.43    4898 1839.46
  4944.3 1840.22  4947.6 1839.13  4953.8  1839.9  4962.4 1838.42  4968.5 1839.29
  4977.1 1838.29  4983.2 1839.36    4998  1837.4  5004.1 1839.61  5012.7 1838.47
  5018.9 1840.19  5088.6 1840.32  5128.7 1839.72  5155.7 1836.89  5158.4 1836.39
  5161.7 1836.89  5278.8 1847.89  5348.8 1856.77  5368.9 1860.58  5398.9 1867.96
  5428.9 1873.07  5474.2 1883.86    5539 1898.27    5569 1907.88    5575 1910.84
#Mann= 6 ,-1 , 0
  4599.4      .1       0  4844.1     .05       0    4898      .1       0
  5155.7     .07       0  5161.7      .1       0  5474.2     .16       0
Bank Sta=5155.7,5161.7
XS Rating Curve= 0 ,0
Exp/Cntr=0.3,0.1

Type RM Length L Ch R = 1 ,8473    ,393,393,393
BEGIN DESCRIPTION:
Mapping XS 5e017922
END DESCRIPTION:
XS GIS Cut Line= 4
      2759813.26     10081778.76      2760143.98     10081554.82
       2760222.1      10081416.8      2760201.27     10080929.84
#Sta/Elev= 30
  4561.3 1855.01  4648.3 1846.56  4721.5  1842.6  4741.2 1842.28  4756.2 1840.84
    4864  1835.5    4870 1836.22  4902.7 1834.03  4935.9 1832.49  4998.2 1824.72
    5001 1824.22  5004.2 1824.72  5022.9 1824.94  5076.3 1828.62    5082 1827.89
  5111.3 1831.35  5152.4 1833.52  5242.5 1840.95  5292.5 1846.53  5319.4 1850.94
  5324.4 1850.64  5342.6 1853.31  5382.6 1860.38  5452.7 1875.26  5489.5 1884.95
  5551.5 1898.68  5556.5 1897.74  5592.8 1908.35  5602.3 1910.81  5606.7 1910.81
#Mann= 6 ,-1 , 0
  4561.3      .1       0  4721.5     .05       0  4902.7      .1       0
  4998.2     .07       0  5004.2      .1       0  5489.5     .16       0
Bank Sta=4998.2,5004.2
XS Rating Curve= 0 ,0
Exp/Cntr=0.3,0.1

Type RM Length L Ch R = 1 ,8080    ,753,753,753
BEGIN DESCRIPTION:
UNT028 IN NNOGR 16.0
END DESCRIPTION:
XS GIS Cut Line= 2
      2760168.43     10082122.65      2760828.05     10081268.63
#Sta/Elev= 30
    4457 1849.72  4484.4 1842.94  4498.9 1841.21  4542.4 1842.46  4583.7 1837.93
  4648.3 1833.06  4720.8 1832.27  4756.1 1828.76  4862.1 1828.51  4940.9 1822.93
  4955.4 1818.71  5002.2 1812.37  5004.9 1811.87  5008.2 1812.37    5026 1815.96
  5040.5 1816.97  5090.3 1817.43  5169.1 1820.83  5283.2 1826.87  5308.4 1829.48
  5347.5 1832.29  5353.9  1831.4  5376.5 1833.06  5382.9 1832.42  5397.4 1834.47
  5447.2 1834.14  5461.7 1835.38  5482.5 1833.96  5511.5  1835.9  5536.1 1840.89
#Mann= 5 ,-1 , 0
    4457     .16       0  4583.7     .05       0  5002.2    .035       0
  5008.2     .05       0  5308.4      .1       0
Bank Sta=5002.2,5008.2
XS Rating Curve= 0 ,0
Exp/Cntr=0.3,0.1

Type RM Length L Ch R = 1 ,7327    ,876,876,876
BEGIN DESCRIPTION:
UNT028 IN NNOGR 15.0
END DESCRIPTION:
XS GIS Cut Line= 3
      2760321.21     10082365.69      2760869.85     10082178.18
      2761258.76      10081733.7
#Sta/Elev= 30
  4354.8 1842.88    4372 1838.07  4377.3 1838.32  4383.6 1836.03  4415.3 1830.61
  4505.8 1825.59  4559.9 1820.97  4635.7 1817.31  4657.6 1816.77  4679.5 1815.64
  4700.6 1812.65  4747.8 1813.67  4827.5 1810.17  4848.6 1807.86  4884.1 1807.63
  4951.2 1803.48  5004.2 1796.25    5007 1795.75  5010.2 1796.25  5043.3  1801.5
  5110.5  1806.9  5146.7  1809.4  5227.4 1815.63    5291 1818.78  5319.5 1821.59
  5347.9 1822.42  5368.8 1825.74    5393 1827.56  5489.4 1833.32  5525.2 1837.23
#Mann= 10 ,-1 , 0
  4354.8      .1       0  4505.8     .05       0  4635.7      .1       0
  4657.6     .05       0  4884.1      .1       0  5004.2     .07       0
  5010.2      .1       0  5110.5     .05       0  5146.7      .1       0
    5393     .05       0
Bank Sta=5004.2,5010.2
XS Rating Curve= 0 ,0
Exp/Cntr=0.3,0.1

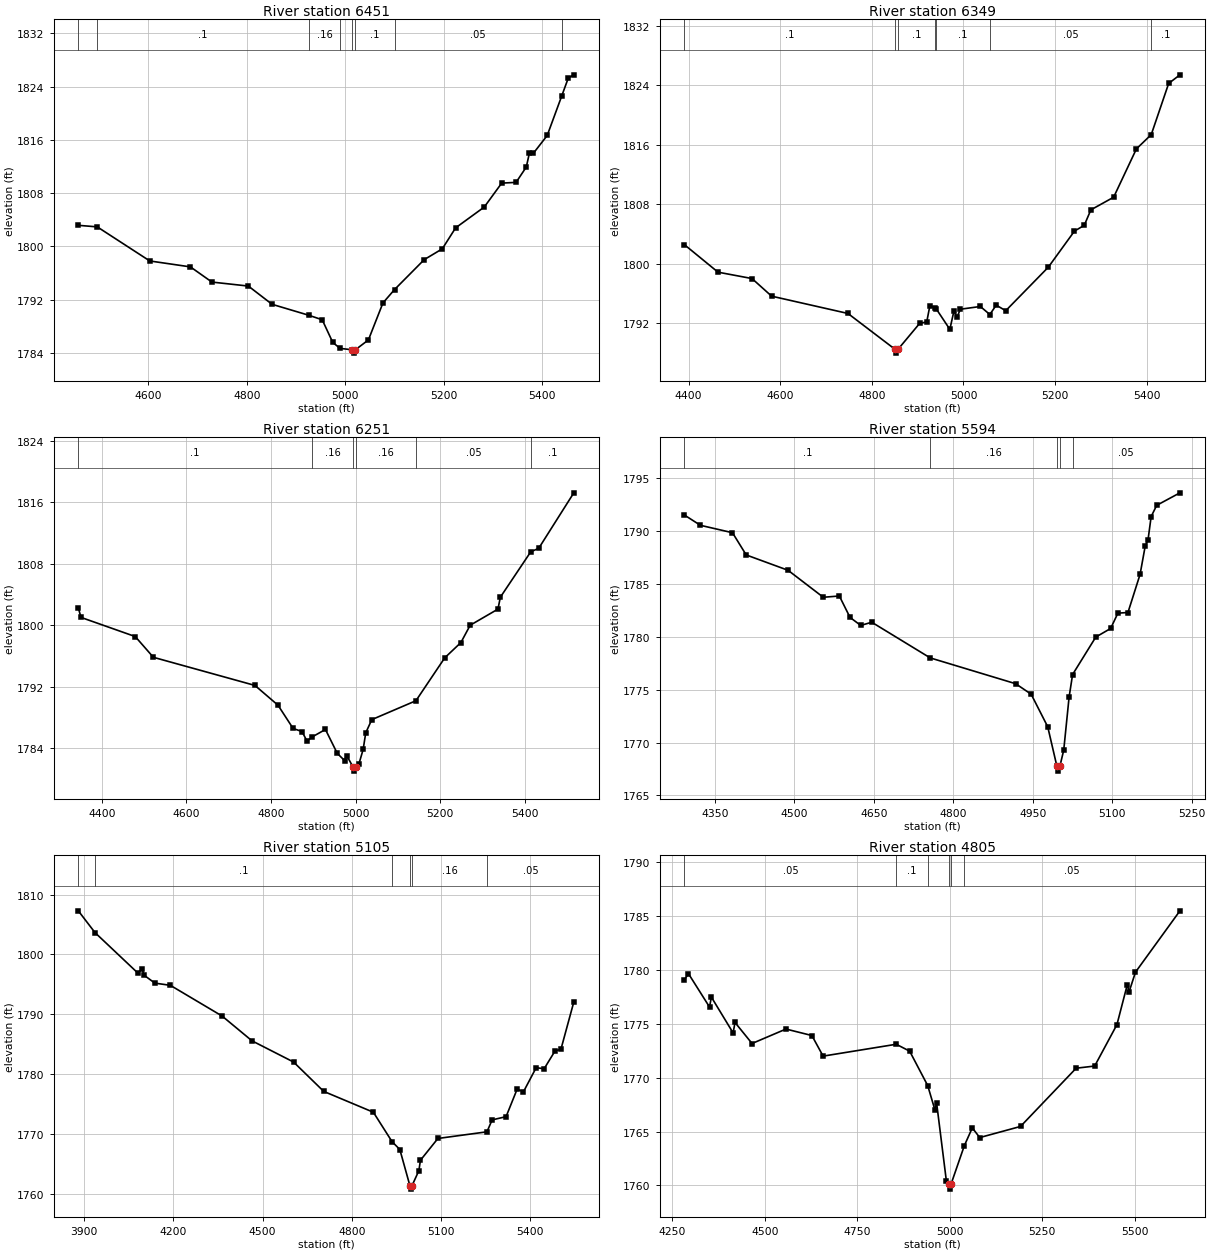
Type RM Length L Ch R = 1 ,6451    ,102,102,102
BEGIN DESCRIPTION:
UNT028 IN NNOGR 13.0
END DESCRIPTION:
XS GIS Cut Line= 4
      2760722.12     10082802.22       2761094.5     10082932.42
      2761373.14     10082820.44      2761560.65     10082570.43
#Sta/Elev= 30
  4457.6 1803.17  4496.1 1802.94  4602.9 1797.82  4685.5 1796.93  4729.2 1794.65
  4803.3 1794.05  4851.5 1791.31    4926 1789.67  4953.4 1788.99  4974.9 1785.58
  4989.8 1784.69  5014.8 1784.48  5017.5 1783.98  5020.8 1784.48  5047.3 1785.96
  5076.9 1791.52  5100.5 1793.53  5160.8 1798.02  5197.5 1799.64  5224.6 1802.79
  5282.9 1805.92  5318.3 1809.51  5347.5 1809.62  5368.3 1811.93  5374.6 1814.02
  5382.9 1814.01  5410.8 1816.66    5440 1822.53  5453.7  1825.3  5464.9 1825.77
#Mann= 8 ,-1 , 0
  4457.6     .05       0  4496.1      .1       0    4926     .16       0
  4989.8      .1       0  5014.8     .07       0  5020.8      .1       0
  5100.5     .05       0    5440      .1       0
Bank Sta=5014.8,5020.8
XS Rating Curve= 0 ,0
Exp/Cntr=0.3,0.1

Type RM Length L Ch R = 1 ,6349    ,98,98,98
BEGIN DESCRIPTION:
Mapping XS 72150d99
END DESCRIPTION:
XS GIS Cut Line= 6
      2760719.52     10082856.91       2761094.5     10082992.32
      2761224.71      10082979.3      2761274.18     10082971.48
      2761321.06     10082924.61      2761591.89     10082583.46
#Sta/Elev= 30
    4391 1802.54  4464.3 1798.84  4538.5 1797.98  4581.3 1795.61  4747.9 1793.28
    4851 1788.44  4853.7 1787.94    4857 1788.44  4904.2 1791.93  4919.9 1792.15
  4926.8 1794.35  4938.6    1794  4940.8 1793.88  4970.3 1791.14  4979.1 1793.58
  4986.2 1792.81  4993.3 1793.85  5036.9 1794.22  5057.6 1793.14  5071.5  1794.4
  5092.3 1793.65  5185.2 1799.51  5242.3 1804.37  5263.7 1805.15  5278.1 1807.23
  5327.8 1808.93  5377.5 1815.44  5409.9 1817.36  5447.9 1824.25  5472.5 1825.41
#Mann= 7 ,-1 , 0
    4391      .1       0    4851     .07       0    4857      .1       0
  4938.6     .16       0  4940.8      .1       0  5057.6     .05       0
  5409.9      .1       0
Bank Sta=4851,4857
XS Rating Curve= 0 ,0
Exp/Cntr=0.3,0.1

Type RM Length L Ch R = 1 ,6251    ,657,657,657
BEGIN DESCRIPTION:
UNT028 IN NNOGR 12.0
END DESCRIPTION:
XS GIS Cut Line= 4
      2760682.99     10082888.13       2761159.6     10083073.05
      2761461.68     10083010.55      2761628.36     10082700.63
#Sta/Elev= 30
  4344.5 1802.22  4350.9 1800.99  4479.1  1798.5    4522  1795.8  4762.1 1792.14
  4816.6 1789.57  4852.4 1786.54  4873.4 1786.14  4885.2  1784.9  4897.1 1785.43
  4928.8 1786.41  4956.7 1783.31  4973.9 1782.37    4979 1783.02  4994.5 1781.49
  4997.3 1780.99  5000.5 1781.49  5007.7 1781.87    5018 1783.82  5024.1 1785.97
  5038.4 1787.69  5142.8 1790.15  5210.9 1795.73  5249.1 1797.72    5271 1799.97
  5336.7 1802.07  5342.4 1803.62  5414.2 1809.52  5433.1 1809.98  5516.1  1817.2
#Mann= 6 ,-1 , 0
  4344.5      .1       0  4897.1     .16       0  4994.5     .07       0
  5000.5     .16       0  5142.8     .05       0  5414.2      .1       0
Bank Sta=4994.5,5000.5
XS Rating Curve= 0 ,0
Exp/Cntr=0.3,0.1

Type RM Length L Ch R = 1 ,5594    ,489,489,489
BEGIN DESCRIPTION:
UNT028 IN NNOGR 11.0
END DESCRIPTION:
XS GIS Cut Line= 3
      2760758.56     10083523.57      2761537.21     10083625.13
      2761581.49     10083481.86
#Sta/Elev= 30
  4292.6  1791.5  4322.8 1790.53  4383.3 1789.83  4409.2 1787.73  4488.2 1786.28
  4554.7 1783.73    4585 1783.85  4605.1 1781.83  4625.3 1781.07  4646.2 1781.37
  4756.5    1778  4917.8 1775.56    4947 1774.57  4978.3 1771.49  4995.4  1767.8
  4998.2  1767.3  5001.4  1767.8  5008.5 1769.29  5018.6 1774.29  5025.2 1776.43
    5069 1779.97    5097 1780.78  5110.7 1782.23  5129.7 1782.29  5152.6  1785.9
  5162.3 1788.58  5167.5 1789.13  5173.5 1791.36    5184 1792.42  5227.8  1793.6
#Mann= 5 ,-1 , 0
  4292.6      .1       0  4756.5     .16       0  4995.4     .07       0
  5001.4     .16       0  5025.2     .05       0
Bank Sta=4995.4,5001.4
XS Rating Curve= 0 ,0
Exp/Cntr=0.3,0.1

Type RM Length L Ch R = 1 ,5105    ,300,300,300
BEGIN DESCRIPTION:
Mapping XS 09f9bf50
END DESCRIPTION:
XS GIS Cut Line= 3
      2760683.03     10084812.63      2761289.81     10084440.23
      2761583.76     10083532.37
#Sta/Elev= 30
  3880.4 1807.28  3936.4 1803.65  4079.7 1796.93  4095.1 1797.58    4101 1796.55
  4137.7 1795.21  4189.9 1794.84  4363.9 1789.71  4464.5 1785.57  4604.3 1782.03
  4705.6 1777.13  4872.5 1773.65  4935.2 1768.75  4961.6 1767.42  4995.8 1761.31
  4998.6 1760.81  5001.8 1761.31  5025.6  1763.9  5030.8 1765.63  5089.6 1769.27
  5254.5 1770.38  5271.9 1772.37  5318.8 1772.91  5356.1 1777.52    5377 1777.04
    5420 1781.09  5446.8 1780.91    5484 1783.93  5503.1 1784.13  5546.6 1792.07
#Mann= 6 ,-1 , 0
  3880.4     .16       0  3936.4      .1       0  4935.2     .16       0
  4995.8     .07       0  5001.8     .16       0  5254.5     .05       0
Bank Sta=4995.8,5001.8
XS Rating Curve= 0 ,0
Exp/Cntr=0.3,0.1

Type RM Length L Ch R = 1 ,4805    ,155,155,155
BEGIN DESCRIPTION:
Mapping XS 7df2719e
END DESCRIPTION:
XS GIS Cut Line= 3
      2761763.77      10084924.6      2761664.81     10084268.36
      2761612.72     10083593.83
#Sta/Elev= 30
  4282.5 1779.08  4293.5 1779.63  4350.4 1776.54  4355.4 1777.46  4414.2 1774.14
  4419.3 1775.11  4465.4 1773.16  4557.1  1774.5  4627.2  1773.9  4657.6 1771.99
  4855.4 1773.09  4891.7 1772.45  4940.5 1769.26  4959.7 1767.04  4964.7 1767.62
  4990.9 1760.44    4998 1760.16  5000.7 1759.66    5004 1760.16  5039.6 1763.69
  5061.1 1765.34  5081.2 1764.44  5191.5 1765.47    5342 1770.87  5392.1 1771.07
  5452.3 1774.91  5480.3 1778.61  5485.3 1777.96  5502.4 1779.77  5622.7 1785.46
#Mann= 6 ,-1 , 0
  4282.5     .05       0  4855.4      .1       0  4940.5     .16       0
    4998     .07       0    5004     .16       0  5039.6     .05       0
Bank Sta=4998,5004
XS Rating Curve= 0 ,0
Exp/Cntr=0.3,0.1

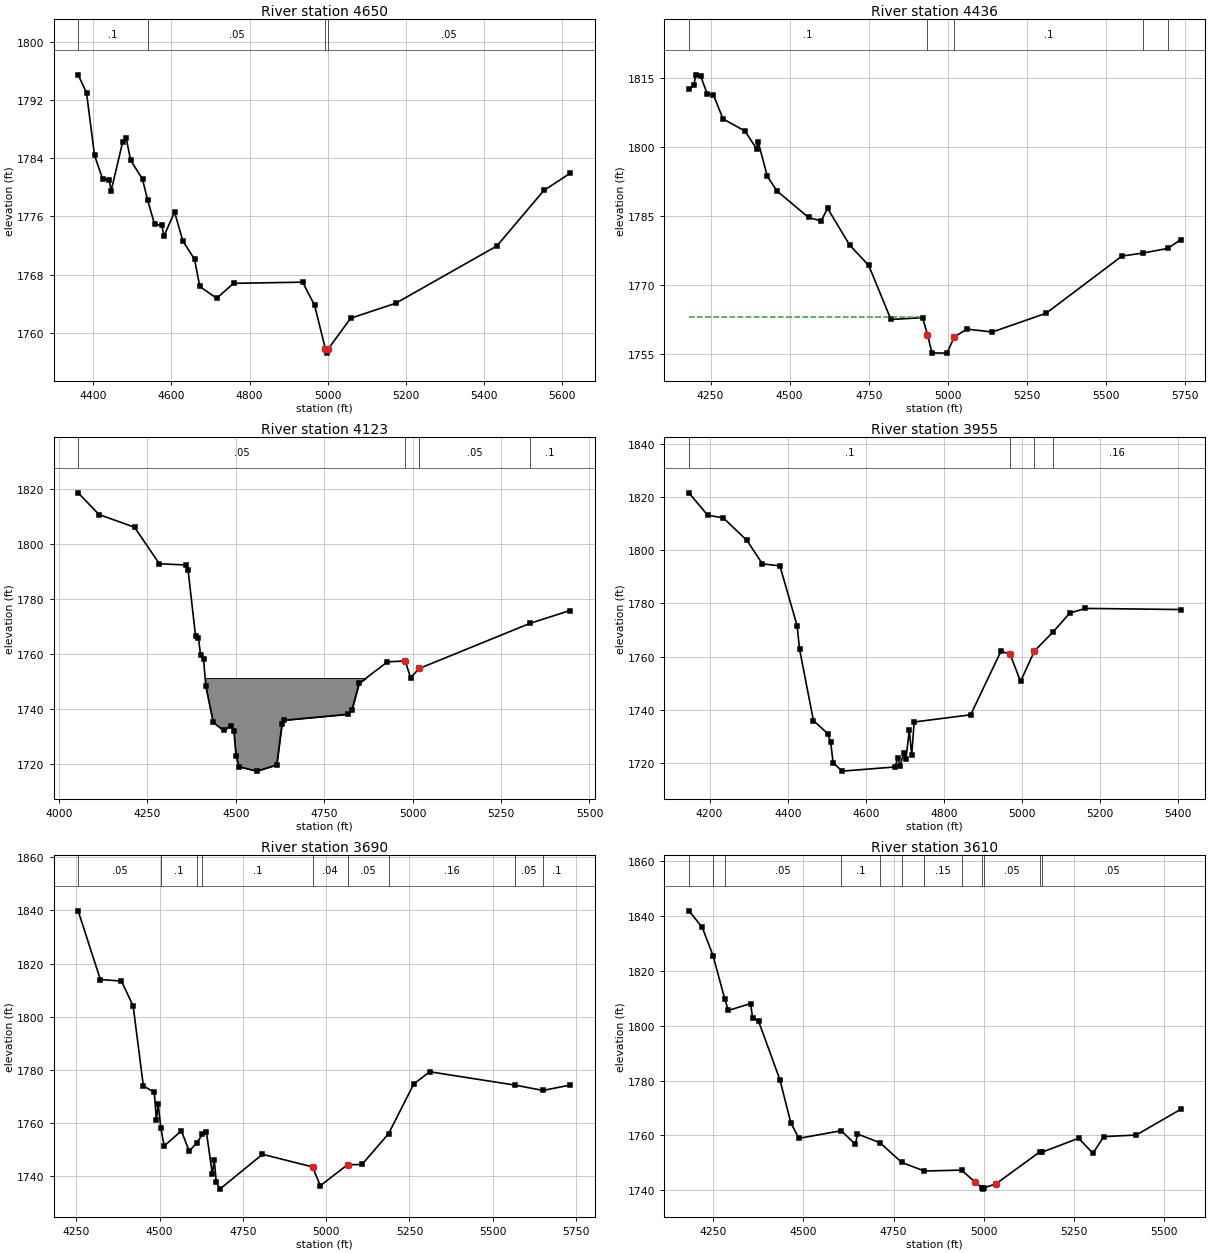
Type RM Length L Ch R = 1 ,4650    ,214,214,214
BEGIN DESCRIPTION:
UNT028 IN NNOGR 10.0
END DESCRIPTION:
XS GIS Cut Line= 3
      2761951.27     10084864.73      2761766.37      10084041.8
      2761730.07     10083626.93
#Sta/Elev= 30
  4360.9 1795.43  4382.4 1792.95  4402.9 1784.37  4423.4 1781.17  4440.5 1780.96
  4445.6 1779.54  4474.7 1786.16  4483.8 1786.79  4495.2 1783.73  4525.9 1781.08
  4538.9 1778.22  4556.7 1774.92  4575.5 1774.76  4580.6 1773.29  4607.9 1776.59
  4629.1 1772.62  4659.2 1770.09  4672.4 1766.38  4715.7 1764.76    4759 1766.81
  4935.9 1766.97  4966.6 1763.78  4994.4 1757.73  4997.1 1757.23  5000.4 1757.73
  5058.9 1762.02  5174.4 1764.08  5433.3 1771.94  5553.7 1779.56  5620.8 1781.91
#Mann= 4 ,-1 , 0
  4360.9      .1       0  4538.9     .05       0  4994.4     .04       0
  5000.4     .05       0
Bank Sta=4994.4,5000.4
XS Rating Curve= 0 ,0
Exp/Cntr=0.3,0.1

Type RM Length L Ch R = 1 ,4436    ,313,313,313
BEGIN DESCRIPTION:
UNT028 IN NNOGR 9.0
END DESCRIPTION:
XS GIS Cut Line= 3
      2761992.46     10085051.33      2762027.18     10084374.26
      2762001.15     10083498.11
#Sta/Elev= 30
  4181.6  1812.6  4197.8 1813.41  4202.8 1815.67  4219.2 1815.37  4239.3 1811.55
  4259.3 1811.31  4289.3  1806.1  4359.4 1803.43  4395.5 1799.57  4400.5 1801.12
  4429.5 1793.64  4459.6 1790.46  4559.7 1784.67  4599.7 1783.93  4619.8 1786.66
  4689.9 1778.66  4749.9 1774.26    4820 1762.51  4920.1 1762.91 4935.57 1759.21
 4949.84 1755.25 4997.14  1755.2  5020.2 1758.73  5060.2 1760.42  5140.2 1759.79
  5310.3 1763.86  5550.4  1776.3  5615.8 1776.93  5694.6 1777.95  5736.1 1779.86
#Mann= 5 ,-1 , 0
  4181.6      .1       0 4935.57     .05       0  5020.2      .1       0
  5615.8     .05       0  5694.6      .1       0
#XS Ineff= 2 , 0
       0 4909.94 1762.97               0
Permanent Ineff=
       F       F
Bank Sta=4935.57,5020.2
XS Rating Curve= 0 ,0
Exp/Cntr=0.3,0.1

Type RM Length L Ch R = 1 ,4123    ,168,168,168
BEGIN DESCRIPTION:
Mapping XS be337264
END DESCRIPTION:
XS GIS Cut Line= 4
      2762017.05     10085002.59      2762040.48     10084734.39
       2762298.3     10084382.82      2762342.54     10083698.35
#Sta/Elev= 30
  4054.1 1818.53  4113.2 1810.64  4213.6 1806.03  4283.8 1792.77  4358.7 1792.32
  4364.9  1790.6  4386.1 1766.52  4394.2 1765.93  4400.4  1759.5  4408.8 1758.13
    4415 1748.41  4435.9 1735.18  4465.2 1732.23  4486.1 1733.93  4494.5    1732
  4500.7 1722.81  4509.2 1719.05  4559.1 1717.46  4615.7 1719.73  4630.4 1734.43
  4636.6 1735.95  4818.5 1738.13  4828.5 1739.79  4848.6 1749.31  4928.7 1757.14
  4978.8 1757.48  4994.2 1751.42  5018.9 1754.75  5332.1 1771.14  5445.2 1775.79
#Mann= 4 ,-1 , 0
  4054.1     .05       0  4978.8    .035       0  5018.9     .05       0
  5332.1      .1       0
#Block Obstruct= 2 , 0
       0 4951.41 1751.25               0
Bank Sta=4978.8,5018.9
XS Rating Curve= 0 ,0
Exp/Cntr=0.3,0.1

Type RM Length L Ch R = 1 ,3955    ,265,265,265
BEGIN DESCRIPTION:
Mapping XS 61e5e31a
END DESCRIPTION:
XS GIS Cut Line= 4
       2762050.9     10084981.75      2762063.92     10084770.85
      2762490.33     10084177.21      2762498.14     10083859.52
#Sta/Elev= 30
  4146.9 1821.65    4195 1813.23  4235.1 1812.21  4295.2 1803.78  4335.3  1794.9
    4380 1794.14  4424.2 1771.56  4430.3 1762.79  4465.9 1735.87  4502.4 1730.96
  4510.1 1727.67  4516.3 1720.07  4539.1 1716.83  4674.8  1718.4    4682 1721.81
  4688.2  1718.7  4696.7  1723.7  4702.9 1721.46  4711.5 1732.29  4717.6 1722.88
    4724 1735.34  4868.6 1738.04    4946 1761.93  4969.3 1760.97  4996.4  1750.6
    5032 1762.09    5080 1769.28  5122.6 1776.38  5162.6 1778.12  5406.9 1777.69
#Mann= 4 ,-1 , 0
  4146.9      .1       0  4969.3     .04       0    5032     .05       0
    5080     .16       0
#XS Ineff= 2 , 0
         4946.14 1761.89
Permanent Ineff=
       F       F
#Block Obstruct= 2 , 0
         4950.36 1750.75
Bank Sta=4969.3,5032
XS Rating Curve= 0 ,0
Exp/Cntr=0.3,0.1

Type RM Length L Ch R = 1 ,3690    ,80,80,80
BEGIN DESCRIPTION:
UNT028 IN NNOGR 8.0
END DESCRIPTION:
XS GIS Cut Line= 4
      2762297.61     10085122.56      2762636.16     10084362.11
      2762526.79     10084075.65      2762531.98     10083737.93
#Sta/Elev= 30
  4255.6 1839.87  4322.3 1813.99  4385.7  1813.4  4420.8 1803.99  4451.3 1773.91
  4484.2 1771.48  4490.5 1761.18  4495.9 1766.99    4504 1757.98  4513.7 1751.28
  4565.7 1756.96  4588.9 1749.32  4612.7 1752.56  4628.8 1755.74  4640.9 1756.35
  4658.6  1740.6  4664.1 1746.16  4670.3 1737.61    4681 1735.01    4809 1748.14
  4959.4 1743.38  4982.6 1736.28  5064.3 1744.21  5107.7 1744.29  5187.8 1755.96
  5263.3 1774.65  5311.1 1779.23  5568.3 1774.18  5650.7 1772.19  5732.4 1774.21
#Mann= 9 ,-1 , 0
  4255.6     .05       0    4504      .1       0  4612.7     .15       0
  4628.8      .1       0  4959.4     .04       0  5064.3     .05       0
  5187.8     .16       0  5568.3     .05       0  5650.7      .1       0
#XS Ineff= 2 , 0
         4808.95 1748.13
Permanent Ineff=
       F       F
Bank Sta=4959.4,5064.3
XS Rating Curve= 0 ,0
Exp/Cntr=0.3,0.1

Type RM Length L Ch R = 1 ,3610    ,78,78,78
BEGIN DESCRIPTION:
Mapping XS c9815514
END DESCRIPTION:
XS GIS Cut Line= 4
      2762306.11      10085179.7      2762629.03     10084531.26
       2762798.3     10084263.03      2762793.09     10083940.14
#Sta/Elev= 30
  4182.2 1841.81    4219 1835.87  4249.3 1825.47  4282.1 1809.52  4291.7 1805.53
  4353.3 1808.02  4358.9 1802.87  4375.7 1801.57  4434.6  1780.3  4465.2 1764.49
  4487.6 1758.94  4604.7  1761.7  4644.3 1756.75  4649.9 1760.52  4712.3 1757.32
  4772.6 1750.15  4835.4 1747.03  4938.5 1747.36  4975.8 1743.02  4995.3 1740.93
    4998 1740.43  5001.3 1740.93  5033.7 1742.32  5154.8 1753.92  5162.8 1753.94
  5263.1 1758.96  5303.1 1753.49  5333.1 1759.58  5423.1 1760.13  5546.7 1769.53
#Mann= 12 ,-1 , 0
  4182.2     .05       0  4249.3      .1       0  4282.1     .05       0
  4604.7      .1       0  4712.3     .15       0  4772.6      .1       0
  4835.4     .15       0  4938.5     .05       0  4995.3    .035       0
  5001.3     .05       0  5154.8     .16       0  5162.8     .05       0
Bank Sta=4975.8,5033.7
XS Rating Curve= 0 ,0
Exp/Cntr=0.3,0.1

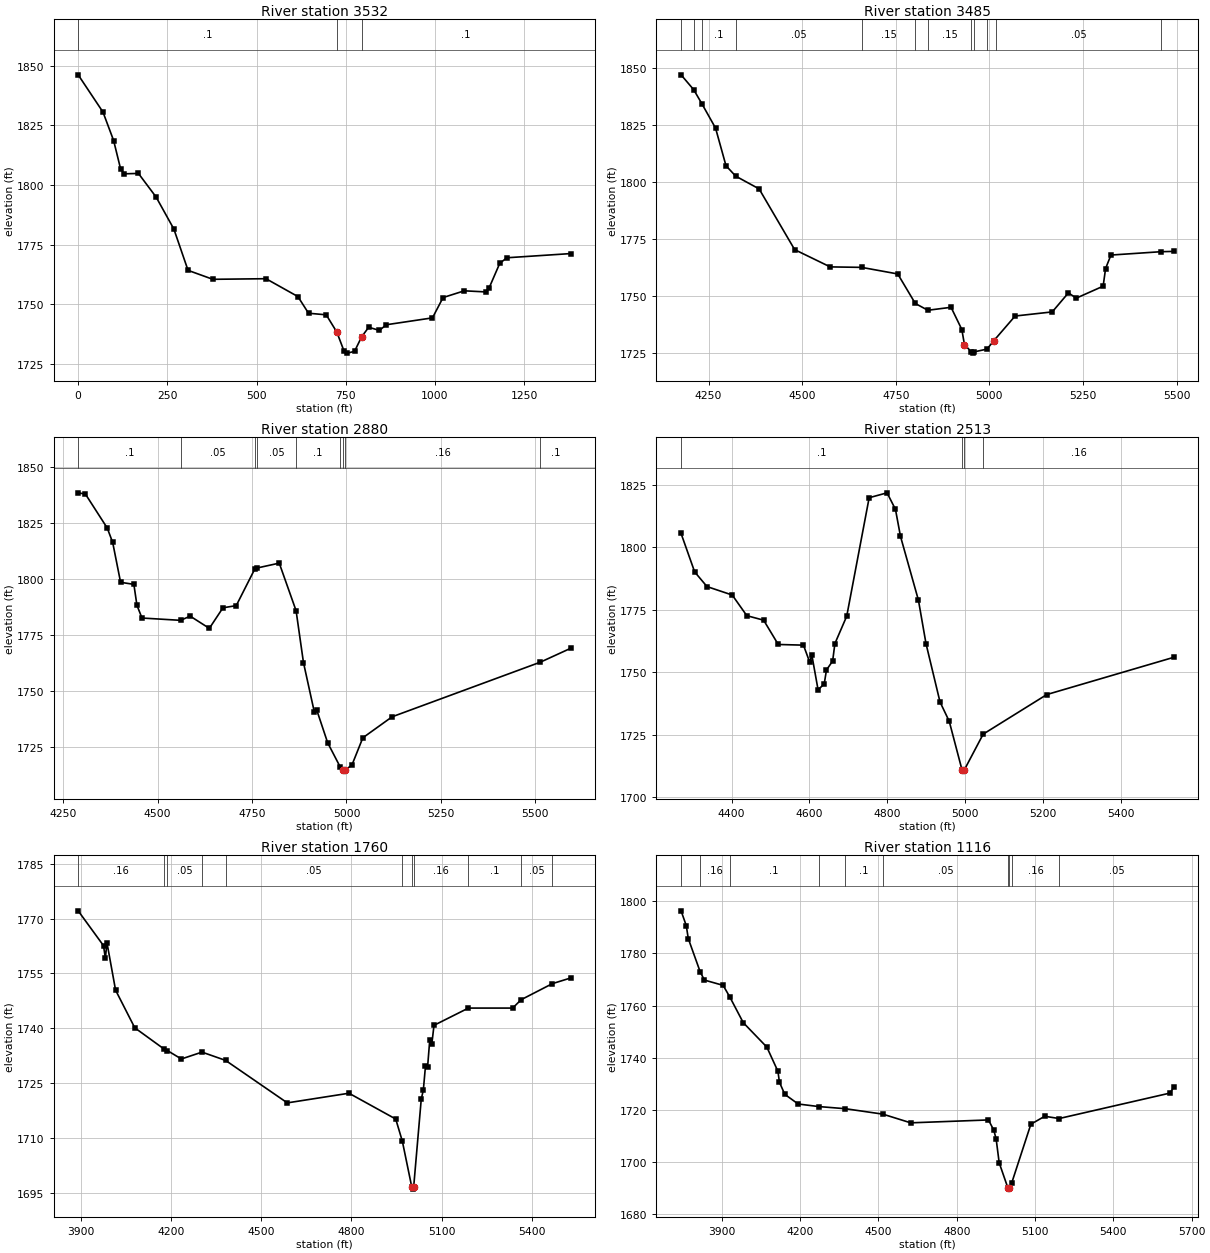
Type RM Length L Ch R = 1 ,3532    ,47,47,47
XS GIS Cut Line= 4
     2762303.298    10085202.911     2762597.352    10084653.866
     2762972.786    10084219.838     2763017.274    10084041.887
#Sta/Elev= 30
       0 1846.27   69.53 1830.63   99.33  1818.7  119.19  1806.6  129.13 1804.71
  168.86 1804.88  218.52 1794.94  268.19 1781.53  307.92 1764.19  377.45 1760.43
  526.44 1760.68  615.84 1753.18  645.61 1746.19  695.23 1745.52     725 1738.24
  744.84 1730.41  754.76 1729.44  774.61  1730.2  794.45 1736.29   814.3 1740.31
  844.07 1738.98  863.91 1741.36  992.91 1744.24 1022.68 1752.77 1082.21  1755.6
 1141.75 1755.14 1151.67  1756.8 1181.44  1767.1 1201.29 1769.47 1380.51 1771.23
#Mann= 3 , 0 , 0
       0      .1       0     725     .07       0  794.45      .1       0
Bank Sta=725,794.45
XS Rating Curve= 0 ,0
Exp/Cntr=0.3,0.1

Type RM Length L Ch R = 1 ,3485    ,605,605,605
BEGIN DESCRIPTION:
Mapping XS b2c4225d
END DESCRIPTION:
XS GIS Cut Line= 3
      2762304.94     10085216.29       2762600.1     10084730.16
      2763068.78     10084148.64
#Sta/Elev= 30
  4176.7 1847.15  4210.5 1840.61  4232.5 1834.39  4268.8 1823.75  4296.7 1807.22
  4322.6 1802.65  4385.1 1797.05  4480.1 1770.36    4575 1762.78  4658.9 1762.57
  4755.4 1759.68  4802.3 1746.71  4835.9 1743.73  4897.8 1745.03  4926.6 1735.27
  4933.5 1728.69  4952.3  1725.4  4955.1  1724.9  4958.3  1725.4    4994 1726.68
  5011.4 1730.24  5068.9  1741.2  5168.1 1743.01  5211.3 1751.38  5232.1 1749.04
    5304 1754.31  5310.5 1762.04  5324.8 1767.98  5458.1 1769.45  5492.3 1769.59
#Mann= 12 ,-1 , 0
  4176.7     .16       0  4210.5     .05       0  4232.5      .1       0
  4322.6     .05       0  4658.9     .15       0  4802.3      .1       0
  4835.9     .15       0  4952.3     .07       0  4958.3     .15       0
    4994     .16       0  5017.4     .05       0  5458.1      .1       0
Bank Sta=4933.5,5011.4
XS Rating Curve= 0 ,0
Exp/Cntr=0.3,0.1

Type RM Length L Ch R = 1 ,2880    ,367,367,367
BEGIN DESCRIPTION:
UNT028 IN NNOGR 6.0
END DESCRIPTION:
XS GIS Cut Line= 2
      2762365.73     10085398.55      2763390.04     10084591.26
#Sta/Elev= 30
  4289.7 1838.48  4308.9 1837.93  4366.7 1822.78  4381.1 1816.34    4402 1798.59
  4437.2 1797.68  4445.3 1788.33  4458.7 1782.67  4560.8 1781.64  4586.3 1783.51
    4637 1778.06    4673 1787.23  4708.2 1788.19  4756.7 1804.31  4763.6 1804.98
  4822.1 1807.14  4866.7 1785.92  4886.2 1762.84  4915.1 1740.66  4921.4 1741.65
  4950.3 1727.06  4983.8 1716.18  4990.5 1714.92  4993.2 1714.42  4996.5 1714.92
  5014.5 1717.12  5043.4 1729.28  5120.8 1738.63  5513.8 1763.02  5593.9 1769.19
#Mann= 9 ,-1 , 0
  4289.7      .1       0  4560.8     .05       0  4756.7      .1       0
  4763.6     .05       0  4866.7      .1       0  4983.8     .16       0
  4990.5     .07       0  4996.5     .16       0  5513.8      .1       0
Bank Sta=4990.5,4996.5
XS Rating Curve= 0 ,0
Exp/Cntr=0.3,0.1

Type RM Length L Ch R = 1 ,2513    ,753,753,753
BEGIN DESCRIPTION:
UNT028 IN NNOGR 5.0
END DESCRIPTION:
XS GIS Cut Line= 3
      2762508.72     10085643.47      2763057.35     10085330.96
      2763418.48     10084810.09
#Sta/Elev= 30
  4270.4 1805.49  4305.3 1790.11    4337 1784.24  4401.8 1780.86  4439.3  1772.6
  4482.5  1770.8    4520 1761.08  4584.8 1760.81  4600.7 1754.05  4606.4 1756.77
  4622.3 1742.96  4638.1  1745.3  4643.9 1750.91  4659.7 1754.43  4665.5 1761.43
  4695.9 1772.39  4753.5 1819.78  4799.5 1821.74  4821.1 1815.11    4834 1804.32
  4880.1 1778.78  4899.6 1761.37  4935.5 1738.09  4959.2 1730.35    4992 1710.92
  4994.7 1710.42    4998 1710.92  5046.4 1725.22  5209.8 1741.05  5535.6 1755.93
#Mann= 4 ,-1 , 0
  4270.4      .1       0    4992     .07       0    4998      .1       0
  5046.4     .16       0
Bank Sta=4992,4998
XS Rating Curve= 0 ,0
Exp/Cntr=0.3,0.1

Type RM Length L Ch R = 1 ,1760    ,644,644,644
BEGIN DESCRIPTION:
UNT028 IN NNOGR 3.0
END DESCRIPTION:
XS GIS Cut Line= 3
      2762807.33     10085983.74      2763467.07     10085796.23
      2764140.68     10085122.62
#Sta/Elev= 30
  3890.9 1772.13  3975.2  1762.6  3981.4 1759.11  3986.6 1763.43  4015.3 1750.43
  4079.2 1740.12  4177.8 1734.24  4187.3 1733.91  4234.2 1731.59  4302.8 1733.47
  4381.1 1731.21  4586.6 1719.58  4791.7 1722.22  4947.2 1715.16  4969.2  1709.1
  5000.8 1696.48  5003.5 1695.98  5006.8 1696.48  5032.1 1720.59  5039.1 1723.12
  5046.2 1729.69  5053.3 1729.51  5060.4  1736.8  5067.4 1735.78  5074.5  1740.8
    5189 1745.52  5336.1 1745.52  5364.4 1747.81  5468.3 1752.21  5529.4 1753.76
#Mann= 11 ,-1 , 0
  3890.9     .16       0  4177.8      .1       0  4187.3     .05       0
  4302.8      .1       0  4381.1     .05       0  4969.2     .16       0
  5000.8     .07       0  5006.8     .16       0    5189      .1       0
  5364.4     .05       0  5468.3      .1       0
Bank Sta=5000.8,5006.8
XS Rating Curve= 0 ,0
Exp/Cntr=0.3,0.1

Type RM Length L Ch R = 1 ,1116    ,971,971,971
BEGIN DESCRIPTION:
UNT028 IN NNOGR 2.0
END DESCRIPTION:
XS GIS Cut Line= 3
      2762661.49     10086372.63      2764126.79     10086032.34
      2764383.13      10085748.3
#Sta/Elev= 30
  3744.1 1796.36    3764 1790.69  3771.8 1785.69  3817.2 1772.98  3833.4 1769.78
  3905.2 1767.75  3930.7 1763.31  3982.3 1753.43  4072.7 1744.04  4115.3 1734.71
  4120.8  1730.6  4141.4 1725.91  4192.7  1722.2  4271.2 1721.22  4373.5 1720.39
  4516.9 1718.31  4623.9 1714.97  4921.6 1716.08  4942.1 1712.15  4951.1 1708.75
  4962.7 1699.64  4995.9 1690.02  4998.6 1689.52  5001.9 1690.02  5010.8 1691.92
  5084.1 1714.45  5137.2 1717.49  5192.3 1716.62  5616.8 1726.39    5631 1728.56
#Mann= 10 ,-1 , 0
  3744.1      .1       0  3817.2     .16       0  3930.7      .1       0
  4271.2     .05       0  4373.5      .1       0  4516.9     .05       0
  4995.9    .035       0  5001.9     .05       0  5010.8     .16       0
  5192.3     .05       0
Bank Sta=4995.9,5001.9
XS Rating Curve= 0 ,0
Exp/Cntr=0.3,0.1