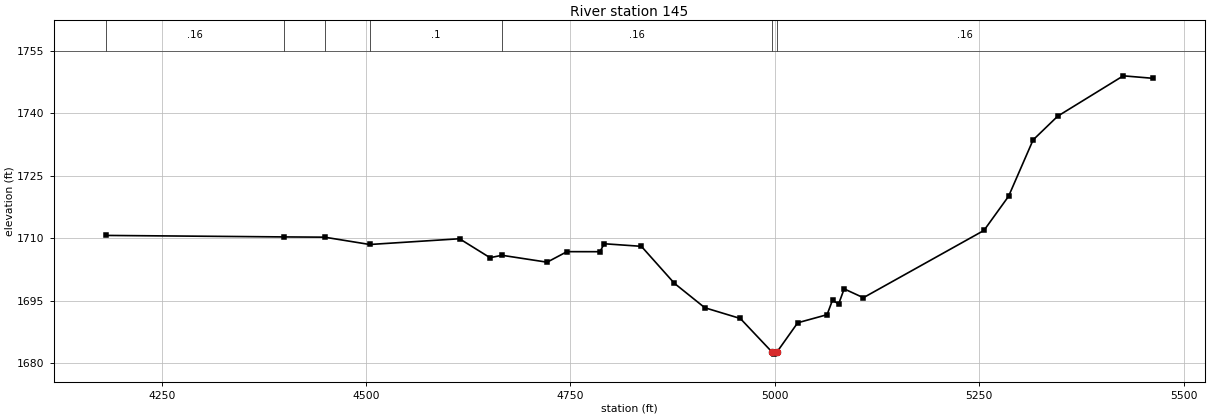
HEC-RAS study UNT028 IN NNOGR.prj: UNT028 IN NNOGR Base Level Engineering

--- UNT028 IN NNOGR.g01 (geometry) --- (continued)

Type RM Length L Ch R = 1 ,145     ,0,0,0
BEGIN DESCRIPTION:
UNT028 IN NNOGR 1.0
END DESCRIPTION:
XS GIS Cut Line= 4
      2763620.52     10086867.32       2764347.1     10086760.55
      2764487.73     10086632.94      2764461.78     10086277.46
#Sta/Elev= 30
  4181.8 1710.69  4399.2 1710.33  4449.2 1710.27  4504.5 1708.51  4614.3 1709.89
  4651.6 1705.34  4666.2 1705.92  4721.4 1704.26  4745.7 1706.79  4786.1 1706.78
  4791.2 1708.69  4836.7 1708.07  4877.1 1699.18  4914.3 1693.32  4957.7 1690.74
  4996.5 1682.68  4999.3 1682.18  5002.5 1682.68  5027.9 1689.71  5063.8 1691.65
  5070.5 1695.17  5077.9 1694.19  5084.7 1697.85  5108.2 1695.73  5255.7 1711.89
  5285.8 1720.09  5315.8 1733.63  5345.9 1739.33  5426.1 1749.02  5462.5 1748.42
#Mann= 7 ,-1 , 0
  4181.8     .16       0  4399.2      .1       0  4449.2     .16       0
  4504.5      .1       0  4666.2     .16       0  4996.5     .07       0
  5002.5     .16       0
Bank Sta=4996.5,5002.5
XS Rating Curve= 0 ,0
Exp/Cntr=0.3,0.1

Chan Stop Cuts=-1
Use User Specified Reach Order=0
Composite Channel Slope=5