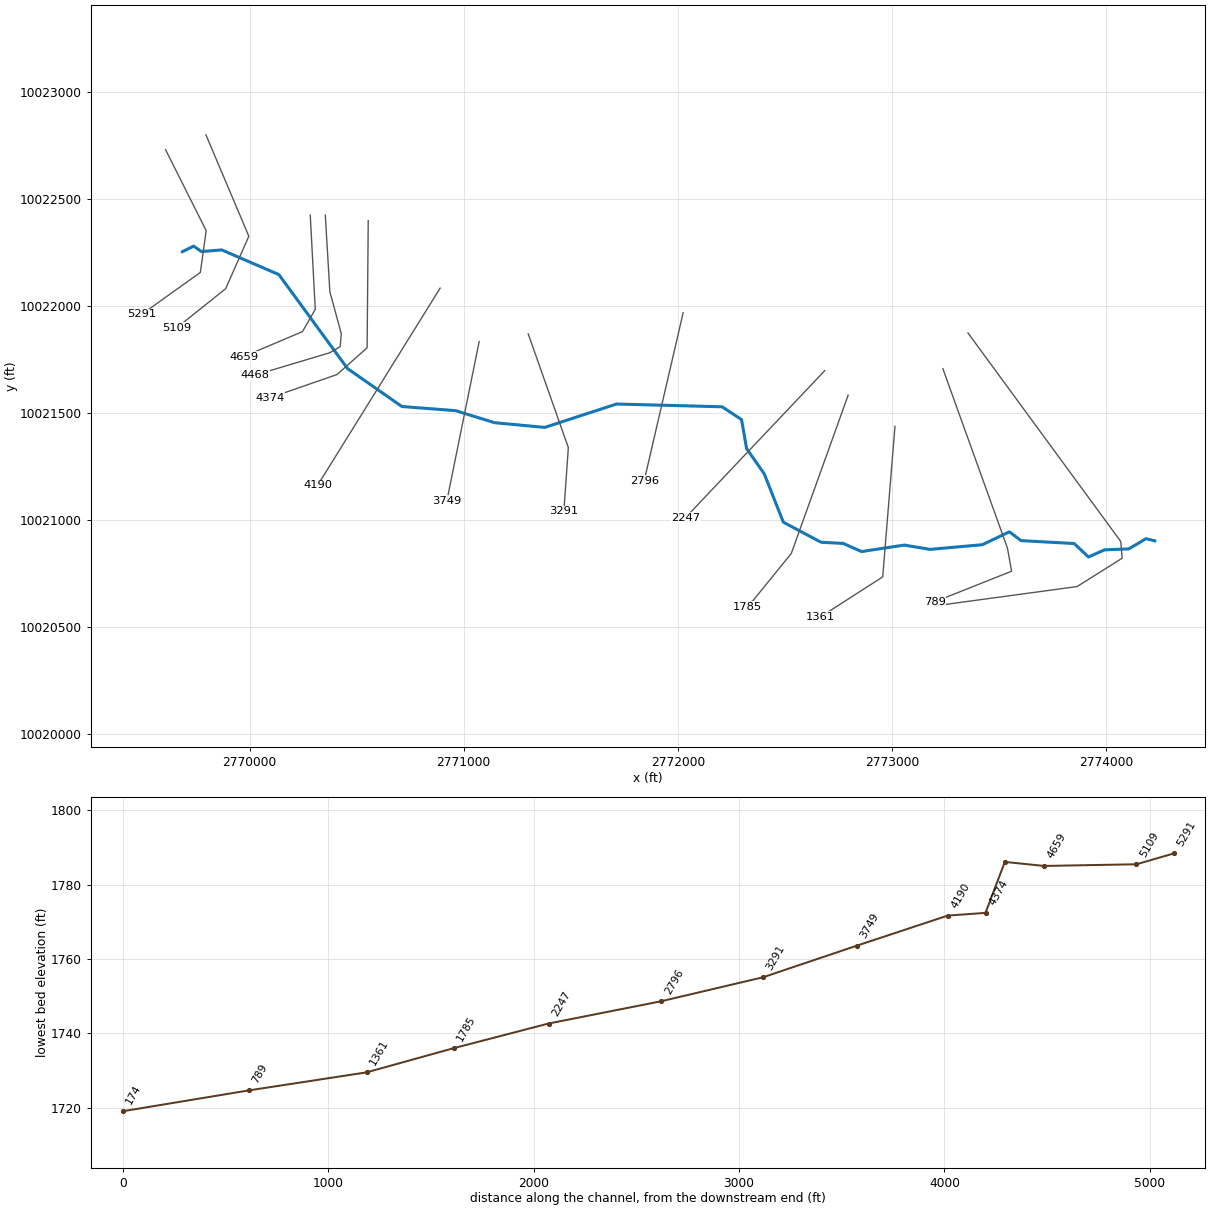
--- UNT028 IN SNOGR.prj (project) ---

Proj Title=UNT028 IN SNOGR Base Level Engineering
Current Plan=p01
Default Exp/Contr=0.3,0.1
English Units
Geom File=g01
Flow File=f01
Plan File=p01
BEGIN DESCRIPTION:
UNT028 IN SNOGR
END DESCRIPTION:

--- UNT028 IN SNOGR.p01 (plan) ---

Plan Title=Multiple Run
Short Identifier=Multiple
Geom File=g01
Flow File=f01
Subcritical Flow
K Sum by GR= 0
Std Step Tol= 0.01
Critical Tol= 0.01
Num of Std Step Trials= 20
Max Error Tol= 0.3
Flow Tol Ratio= 0.001
Split Flow NTrial= 30
Split Flow Tol= 0.02
Split Flow Ratio= 0.02
Log Output Level= 0
Friction Slope Method= 1
Unsteady Friction Slope Method= 2
Unsteady Bridges Friction Slope Method= 1
Parabolic Critical Depth
Global Vel Dist=  1 , 1 , 1
Global Log Level= 0
CheckData=True
Encroach Param= -1, 0, 0, 0
BEGIN DESCRIPTION:
Multiple Run
END DESCRIPTION:

--- UNT028 IN SNOGR.f01 (steady flow) ---

Flow Title=Multiple
Number of Profiles=7
Profile Names=10-year,25-year,50-year,1pct_min,100-year,1pct_plu,500-year
River Rch & RM= UNT028 IN SNOGR,Reach-1,5291
     952    1394    1782    1667    2254    3049    3623
River Rch & RM= UNT028 IN SNOGR,Reach-1,4659
    1540    2309    2998    2844    3846    5201    6360
Boundary for River Rch & Prof#=UNT028 IN SNOGR,Reach-1,1
Up Type=0
Dn Type=3
Dn Slope=0.005
Boundary for River Rch & Prof#=UNT028 IN SNOGR,Reach-1,2
Up Type=0
Dn Type=3
Dn Slope=0.005
Boundary for River Rch & Prof#=UNT028 IN SNOGR,Reach-1,3
Up Type=0
Dn Type=3
Dn Slope=0.005
Boundary for River Rch & Prof#=UNT028 IN SNOGR,Reach-1,4
Up Type=0
Dn Type=3
Dn Slope=0.005
Boundary for River Rch & Prof#=UNT028 IN SNOGR,Reach-1,5
Up Type=0
Dn Type=3
Dn Slope=0.005
Boundary for River Rch & Prof#=UNT028 IN SNOGR,Reach-1,6
Up Type=0
Dn Type=3
Dn Slope=0.005
Boundary for River Rch & Prof#=UNT028 IN SNOGR,Reach-1,7
Up Type=0
Dn Type=3
Dn Slope=0.005

--- UNT028 IN SNOGR.g01 (geometry) ---

Geom Title=Existing Conditions

River Reach=UNT028 IN SNOGR,Reach-1
Reach XY= 30
      2769685.57     10022254.73      2769738.25     10022280.52
      2769774.60     10022255.36      2769869.36     10022262.95
      2770136.40     10022147.58      2770457.21     10021708.38
      2770711.14     10021531.36      2770962.59     10021511.87
      2771143.89     10021455.68      2771378.52     10021433.71
      2771713.81     10021542.99      2772206.97     10021530.04
      2772297.90     10021470.31      2772321.57     10021335.08
      2772404.01     10021216.60      2772493.18     10020990.78
      2772669.78     10020897.00      2772772.58     10020891.79
      2772858.57     10020853.71      2773058.53     10020884.03
      2773178.25     10020863.84      2773422.67     10020885.63
      2773549.31     10020945.80      2773603.83     10020904.78
      2773852.11     10020891.16      2773918.69     10020828.35
      2773994.29     10020861.79      2774107.34     10020866.18
      2774187.45     10020913.88      2774228.47     10020903.73

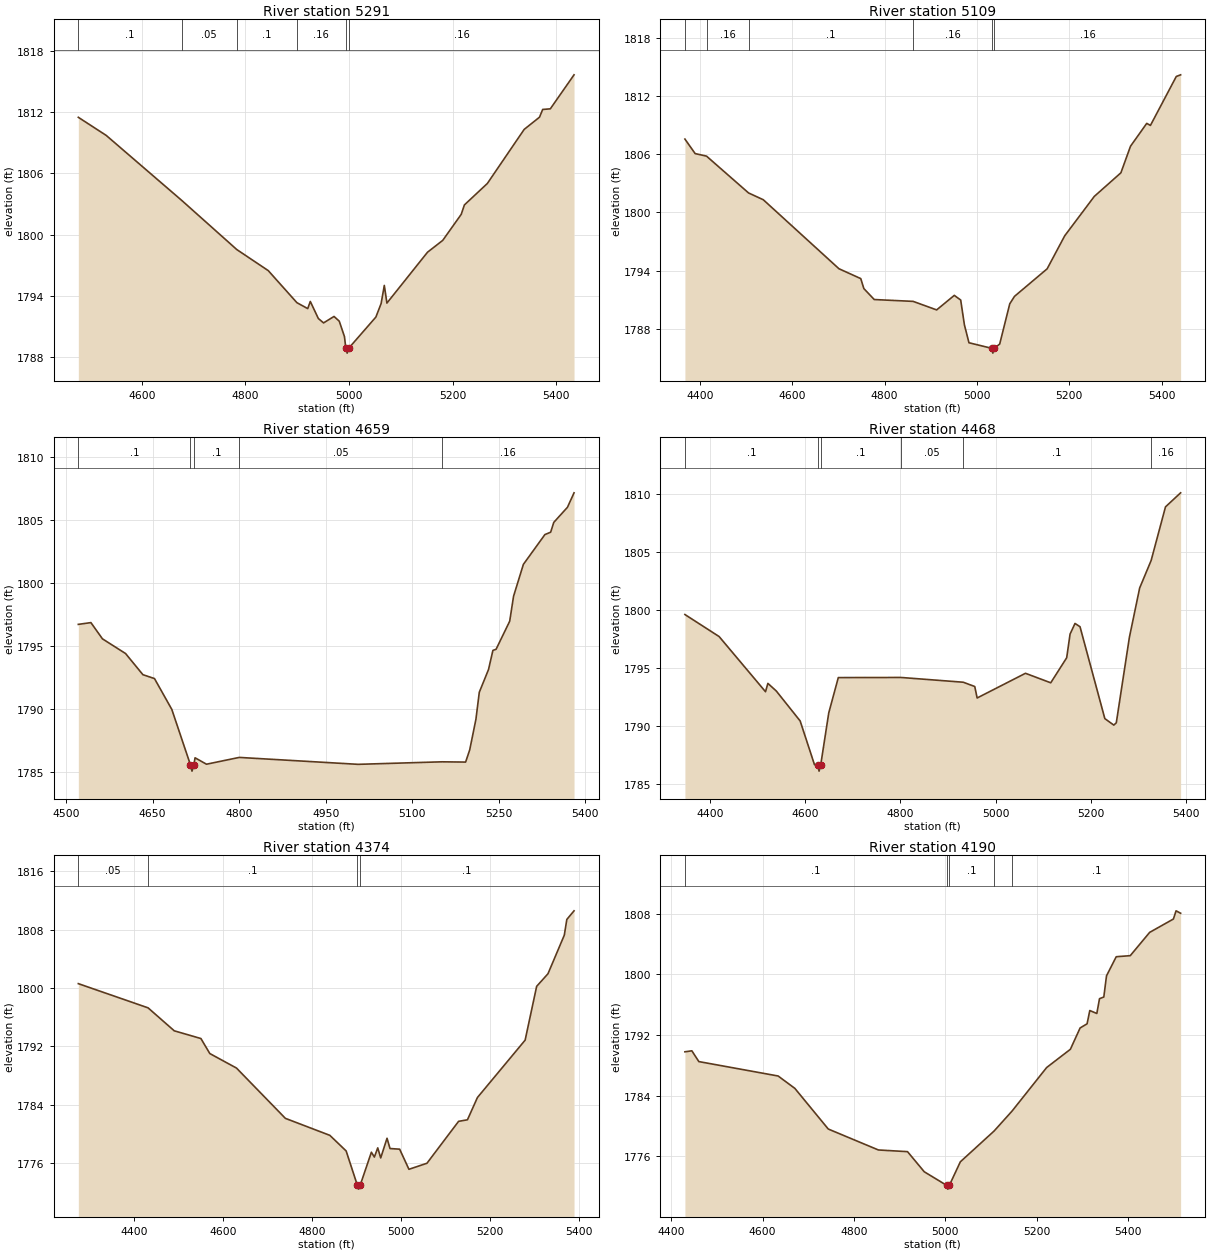
Type RM Length L Ch R = 1,5291,182,182,182
BEGIN DESCRIPTION:
UNT028 IN SNOGR 10.0
END DESCRIPTION:
XS GIS Cut Line= 4
      2769606.67     10022731.77      2769796.76     10022352.91
      2769769.41     10022157.59      2769495.99     10021962.30
#Sta/Elev= 30
  4477.3 1811.49  4531.1 1809.72  4676.8 1803.36  4783.3 1798.54  4844.0 1796.48
  4899.3 1793.34  4920.2 1792.76  4925.2 1793.46  4940.7 1791.79  4950.8 1791.36
  4971.0 1791.99  4981.1 1791.53  4991.2 1790.01  4993.7 1788.90  4996.4 1788.40
  4999.7 1788.90  5051.8 1791.93  5061.9 1793.25  5068.1 1795.03  5073.1 1793.30
  5151.5 1798.28  5180.9 1799.44  5216.6 1801.99  5222.7 1802.91  5267.0 1805.01
  5338.2 1810.31  5367.7 1811.50  5373.9 1812.26  5388.6 1812.32  5434.4 1815.65
#Mann=6,-1,0
  4477.3     0.1       0  4676.8    0.05       0  4783.3     0.1       0
  4899.3    0.16       0  4993.7    0.07       0  4999.7    0.16       0
Bank Sta=4993.7,4999.7
Exp/Cntr=0.3,0.1

Type RM Length L Ch R = 1,5109,450,450,450
BEGIN DESCRIPTION:
Mapping XS c42b31af
END DESCRIPTION:
XS GIS Cut Line= 4
      2769795.47     10022800.78      2769995.97     10022326.86
      2769887.90     10022082.07      2769660.02     10021899.77
#Sta/Elev= 30
  4367.4 1807.57  4389.6 1806.07  4414.2 1805.81  4505.3 1802.01  4537.2 1801.31
  4701.1 1794.19  4748.4 1793.17  4755.1 1792.14  4777.6 1791.01  4861.9 1790.82
  4912.8 1789.94  4951.0 1791.44  4964.9 1790.96  4972.9 1788.41  4982.8 1786.55
  5031.9 1785.98  5034.6 1785.48  5037.9 1785.98  5049.4 1786.42  5071.2 1790.57
  5081.5 1791.34  5152.2 1794.18  5190.3 1797.59  5254.3 1801.65  5312.0 1804.09
  5332.8 1806.83  5368.0 1809.19  5376.0 1808.98  5432.0 1814.03  5441.4 1814.20
#Mann=6,-1,0
  4367.4     0.1       0  4414.2    0.16       0  4505.3     0.1       0
  4861.9    0.16       0  5031.9    0.07       0  5037.9    0.16       0
Bank Sta=5031.9,5037.9
Exp/Cntr=0.3,0.1

Type RM Length L Ch R = 1,4659,191,191,191
BEGIN DESCRIPTION:
Mapping XS db65d527
END DESCRIPTION:
XS GIS Cut Line= 4
      2770282.96     10022425.50      2770306.40     10021985.39
      2770246.50     10021881.22      2769972.00     10021764.69
#Sta/Elev= 30
  4521.4 1796.70  4543.2 1796.84  4563.2 1795.55  4603.3 1794.38  4633.3 1792.70
  4653.4 1792.39  4683.4 1789.94  4715.7 1785.53  4718.4 1785.03  4721.7 1785.53
  4723.7 1786.09  4743.5 1785.58  4800.3 1786.12  5006.3 1785.57  5151.6 1785.77
  5192.6 1785.75  5199.7 1786.72  5210.5 1789.16  5216.3 1791.30  5232.3 1793.11
  5239.9 1794.63  5245.4 1794.72  5269.0 1796.95  5275.7 1798.94  5292.7 1801.47
  5330.0 1803.84  5340.0 1804.03  5345.4 1804.81  5369.1 1806.01  5380.5 1807.16
#Mann=5,-1,0
  4521.4     0.1       0  4715.7   0.033       0  4721.7     0.1       0
  4800.3    0.05       0  5151.6    0.16       0
Bank Sta=4715.7,4721.7
Exp/Cntr=0.3,0.1

Type RM Length L Ch R = 1,4468,94,94,94
BEGIN DESCRIPTION:
Mapping XS c0765ddf
END DESCRIPTION:
XS GIS Cut Line= 6
      2770353.27     10022425.51      2770374.54     10022067.76
      2770427.92     10021871.14      2770422.72     10021811.25
      2770374.54     10021782.60      2770026.21     10021678.42
#Sta/Elev= 30
  4347.2 1799.62  4419.1 1797.72  4516.6 1792.96  4521.6 1793.68  4539.3 1793.02
  4589.4 1790.44  4619.5 1786.67  4626.5 1786.61  4629.2 1786.11  4632.5 1786.61
  4649.5 1791.13  4669.6 1794.18  4801.5 1794.19  4932.2 1793.78  4956.4 1793.41
  4961.4 1792.42  5063.0 1794.55  5116.1 1793.73  5149.6 1795.89  5156.7 1797.93
  5167.1 1798.85  5177.6 1798.57  5229.8 1790.64  5248.7 1790.08  5253.9 1790.28
  5281.4 1797.65  5303.0 1801.91  5327.1 1804.28  5357.3 1808.91  5389.1 1810.12
#Mann=6,-1,0
  4347.2     0.1       0  4626.5    0.07       0  4632.5     0.1       0
  4801.5    0.05       0  4932.2     0.1       0  5327.1    0.16       0
Bank Sta=4626.5,4632.5
Exp/Cntr=0.3,0.1

Type RM Length L Ch R = 1,4374,184,184,184
BEGIN DESCRIPTION:
UNT028 IN SNOGR 9.0
END DESCRIPTION:
XS GIS Cut Line= 4
      2770553.80     10022399.49      2770548.59     10021805.70
      2770407.96     10021680.70      2770093.15     10021571.43
#Sta/Elev= 30
  4273.8 1800.60  4430.7 1797.28  4489.6 1794.13  4549.6 1793.07  4569.6 1791.01
  4629.6 1789.02  4739.6 1782.12  4839.6 1779.79  4876.3 1777.65  4901.7 1772.91
  4904.5 1772.41  4907.7 1772.91  4933.1 1777.47  4939.8 1776.81  4947.4 1778.07
  4954.1 1776.69  4968.3 1779.39  4975.0 1777.98  4996.7 1777.89  5017.6 1775.13
  5058.1 1775.96  5129.3 1781.71  5149.2 1781.92  5171.7 1784.98  5279.0 1792.85
  5304.9 1800.23  5330.4 1801.96  5367.1 1807.25  5372.8 1809.41  5389.0 1810.59
#Mann=4,-1,0
  4273.8    0.05       0  4430.7     0.1       0  4901.7    0.07       0
  4907.7     0.1       0
Bank Sta=4901.7,4907.7
Exp/Cntr=0.3,0.1

Type RM Length L Ch R = 1,4190,441,441,441
BEGIN DESCRIPTION:
UNT028 IN SNOGR 8.0
END DESCRIPTION:
XS GIS Cut Line= 2
      2770889.75     10022084.37      2770316.83     10021162.49
#Sta/Elev= 30
  4430.1 1789.78  4445.3 1789.91  4460.6 1788.49  4634.2 1786.59  4670.8 1784.96
  4744.0 1779.60  4853.8 1776.84  4917.5 1776.62  4954.1 1773.97  5003.1 1772.18
  5005.9 1771.68  5009.1 1772.18  5033.2 1775.28  5107.1 1779.34  5146.3 1781.96
  5222.2 1787.71  5274.1 1790.11  5295.4 1792.92  5310.7 1793.47  5316.6 1795.22
  5332.0 1794.83  5337.9 1796.78  5347.3 1797.00  5353.2 1799.79  5374.5 1802.31
  5405.2 1802.45  5447.7 1805.52  5499.7 1807.28  5505.5 1808.36  5515.5 1808.04
#Mann=5,-1,0
  4430.1     0.1       0  5003.1    0.07       0  5009.1     0.1       0
  5107.1    0.16       0  5146.3     0.1       0
Bank Sta=5003.1,5009.1
Exp/Cntr=0.3,0.1

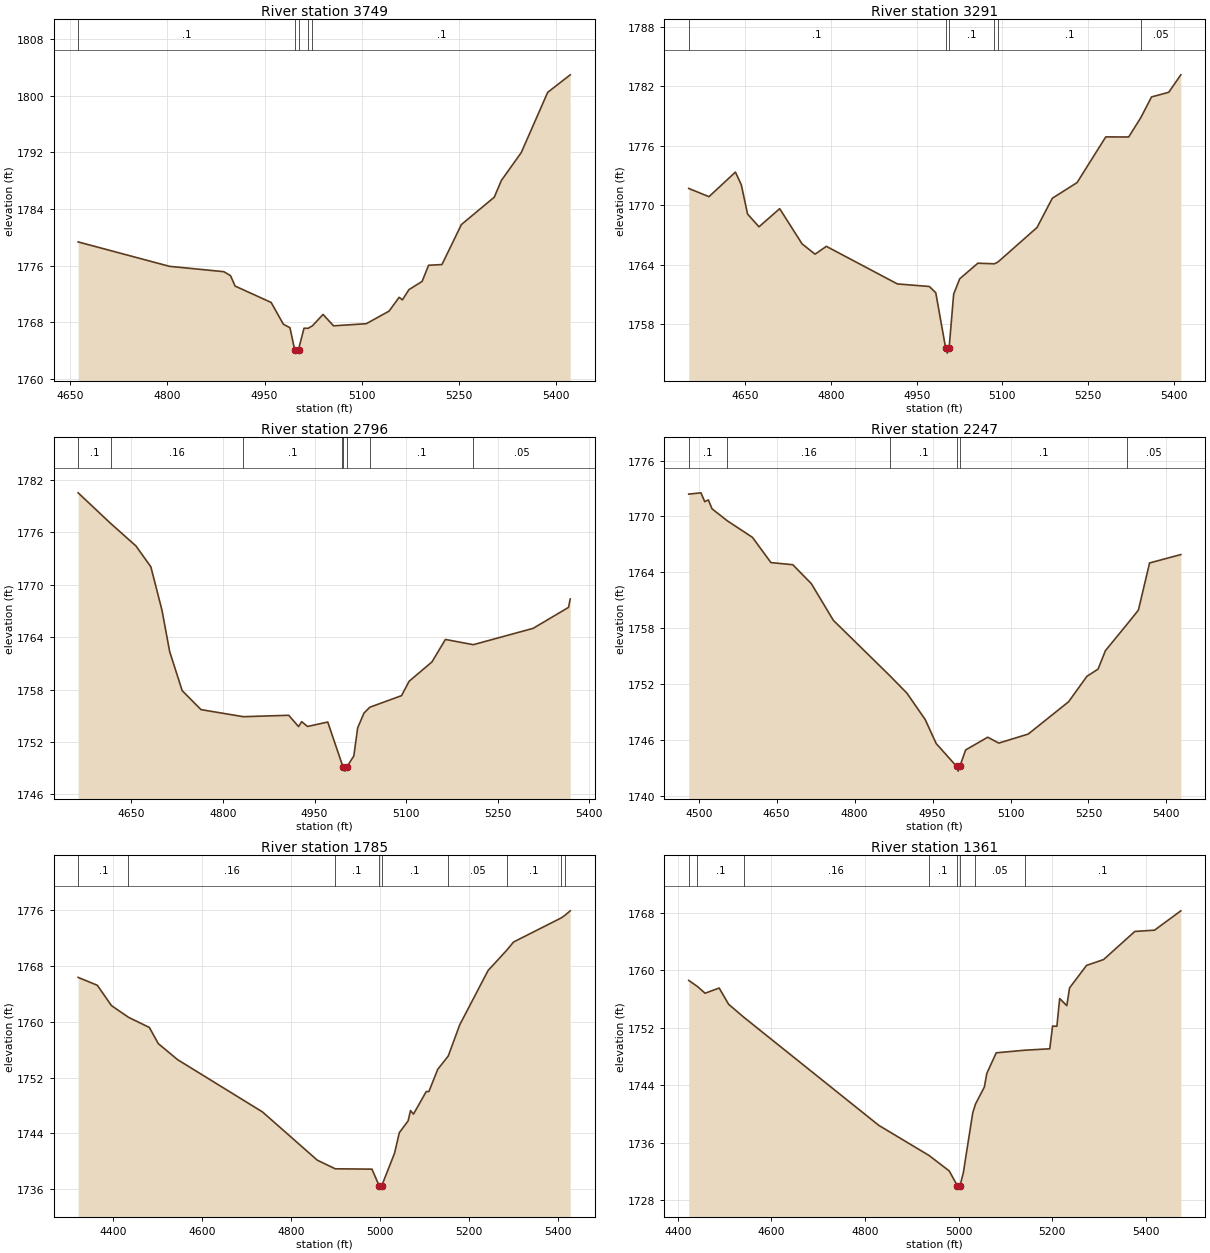
Type RM Length L Ch R = 1,3749,458,458,458
BEGIN DESCRIPTION:
UNT028 IN SNOGR 7.0
END DESCRIPTION:
XS GIS Cut Line= 2
      2771072.02     10021834.34      2770920.99     10021089.60
#Sta/Elev= 30
  4662.1 1779.34  4803.1 1775.89  4887.2 1775.13  4897.4 1774.57  4904.5 1773.10
  4960.2 1770.78  4979.0 1767.71  4989.2 1767.21  4996.4 1764.12  4999.2 1763.62
  5002.4 1764.12  5010.9 1767.14  5017.3 1767.13  5023.9 1767.48  5040.3 1769.09
  5056.5 1767.48  5107.1 1767.78  5142.3 1769.56  5157.8 1771.51  5162.9 1771.15
  5172.9 1772.59  5193.3 1773.76  5203.3 1776.04  5223.9 1776.14  5254.0 1781.80
  5304.7 1785.66  5315.7 1788.03  5346.4 1791.97  5387.2 1800.48  5422.0 1802.96
#Mann=5,-1,0
  4662.1     0.1       0  4996.4    0.07       0  5002.4     0.1       0
  5017.3    0.16       0  5023.9     0.1       0
Bank Sta=4996.4,5002.4
Exp/Cntr=0.3,0.1

Type RM Length L Ch R = 1,3291,495,495,495
BEGIN DESCRIPTION:
UNT028 IN SNOGR 6.0
END DESCRIPTION:
XS GIS Cut Line= 3
      2771301.21     10021870.76      2771488.69     10021339.56
      2771467.86     10021042.71
#Sta/Elev= 30
  4551.3 1771.71  4586.7 1770.88  4633.0 1773.36  4643.3 1772.07  4654.2 1769.13
  4674.2 1767.84  4710.4 1769.67  4749.6 1766.12  4772.3 1765.08  4792.1 1765.87
  4916.3 1762.08  4972.3 1761.82  4983.5 1761.19  5000.8 1755.60  5003.6 1755.10
  5006.8 1755.60  5014.8 1761.05  5025.4 1762.60  5057.2 1764.17  5086.1 1764.11
  5092.3 1764.29  5160.6 1767.77  5187.4 1770.72  5230.7 1772.30  5280.9 1776.91
  5321.0 1776.90  5342.2 1778.85  5361.0 1780.94  5391.1 1781.41  5412.2 1783.17
#Mann=6,-1,0
  4551.3     0.1       0  5000.8    0.07       0  5006.8     0.1       0
  5086.1    0.16       0  5092.3     0.1       0  5342.2    0.05       0
Bank Sta=5000.8,5006.8
Exp/Cntr=0.3,0.1

Type RM Length L Ch R = 1,2796,549,549,549
BEGIN DESCRIPTION:
UNT028 IN SNOGR 5.0
END DESCRIPTION:
XS GIS Cut Line= 2
      2772025.14     10021969.72      2771843.17     10021184.63
#Sta/Elev= 30
  4562.8 1780.51  4616.5 1776.98  4657.5 1774.43  4681.9 1772.04  4700.2 1767.05
  4712.7 1762.34  4733.2 1757.87  4764.0 1755.70  4833.3 1754.89  4907.7 1755.05
  4923.8 1753.76  4928.9 1754.32  4938.5 1753.77  4971.6 1754.28  4994.9 1749.48
  4997.1 1749.16  4999.8 1748.66  5003.1 1749.16  5014.3 1750.40  5020.6 1753.61
  5030.9 1755.30  5040.4 1755.97  5092.5 1757.30  5104.8 1758.94  5142.3 1761.16
  5164.3 1763.73  5209.9 1763.13  5308.0 1765.00  5365.9 1767.40  5368.7 1768.36
#Mann=8,-1,0
  4562.8     0.1       0  4616.5    0.16       0  4833.3     0.1       0
  4994.9    0.16       0  4997.1    0.07       0  5003.1    0.16       0
  5040.4     0.1       0  5209.9    0.05       0
Bank Sta=4997.1,5003.1
Exp/Cntr=0.3,0.1

Type RM Length L Ch R = 1,2247,462,462,462
BEGIN DESCRIPTION:
UNT028 IN SNOGR 4.0
END DESCRIPTION:
XS GIS Cut Line= 2
      2772686.64     10021698.96      2772035.55     10021011.42
#Sta/Elev= 30
  4480.8 1772.40  4504.3 1772.54  4511.6 1771.59  4518.5 1771.78  4525.7 1770.82
  4555.2 1769.53  4603.4 1767.76  4639.0 1765.05  4681.1 1764.82  4716.7 1762.79
  4759.1 1758.85  4868.4 1752.87  4900.7 1751.03  4935.9 1748.19  4957.0 1745.62
  4996.4 1743.16  4999.2 1742.66  5002.4 1743.16  5013.6 1744.93  5056.1 1746.30
  5077.5 1745.67  5134.1 1746.64  5211.8 1750.11  5247.0 1752.84  5268.4 1753.61
  5282.6 1755.59  5325.0 1758.48  5346.1 1759.95  5367.6 1765.01  5427.7 1765.91
#Mann=6,-1,0
  4480.8     0.1       0  4555.2    0.16       0  4868.4     0.1       0
  4996.4    0.07       0  5002.4     0.1       0  5325.0    0.05       0
Bank Sta=4996.4,5002.4
Exp/Cntr=0.3,0.1

Type RM Length L Ch R = 1,1785,424,424,424
BEGIN DESCRIPTION:
UNT028 IN SNOGR 3.0
END DESCRIPTION:
XS GIS Cut Line= 3
      2772796.00     10021584.39      2772530.36     10020844.77
      2772327.23     10020594.77
#Sta/Elev= 30
  4320.6 1766.34  4363.8 1765.21  4395.7 1762.30  4433.9 1760.63  4481.0 1759.17
  4501.1 1756.86  4544.4 1754.57  4735.7 1747.08  4859.2 1740.17  4899.5 1738.94
  4982.2 1738.89  4998.3 1736.53  5001.1 1736.03  5004.3 1736.53  5033.0 1741.16
  5043.8 1744.11  5063.7 1745.81  5069.0 1747.28  5075.7 1746.77  5104.4 1750.00
  5110.4 1750.00  5130.2 1753.17  5154.0 1755.09  5179.8 1759.55  5243.7 1767.33
  5285.4 1770.21  5301.1 1771.41  5407.3 1774.82  5416.8 1775.23  5428.6 1775.87
#Mann=9,-1,0
  4320.6     0.1       0  4433.9    0.16       0  4899.5     0.1       0
  4998.3    0.07       0  5004.3     0.1       0  5154.0    0.05       0
  5285.4     0.1       0  5407.3    0.05       0  5416.8     0.1       0
Bank Sta=4998.3,5004.3
Exp/Cntr=0.3,0.1

Type RM Length L Ch R = 1,1361,572,572,572
BEGIN DESCRIPTION:
UNT028 IN SNOGR 2.0
END DESCRIPTION:
XS GIS Cut Line= 3
      2773014.73     10021438.53      2772957.44     10020735.39
      2772666.45     10020548.33
#Sta/Elev= 30
  4423.2 1758.56  4441.5 1757.73  4458.1 1756.78  4488.2 1757.50  4508.3 1755.25
  4540.5 1753.46  4829.3 1738.40  4936.7 1734.21  4979.8 1732.06  4996.9 1730.03
  4999.7 1729.53  5002.9 1730.03  5009.9 1731.80  5030.0 1740.13  5035.8 1741.35
  5054.8 1743.73  5060.1 1745.63  5080.2 1748.49  5140.8 1748.85  5194.6 1749.05
  5200.6 1752.21  5209.8 1752.18  5215.8 1756.04  5231.0 1755.05  5236.9 1757.52
  5273.2 1760.65  5309.6 1761.46  5376.3 1765.37  5418.5 1765.55  5474.6 1768.24
#Mann=8,-1,0
  4423.2    0.05       0  4441.5     0.1       0  4540.5    0.16       0
  4936.7     0.1       0  4996.9    0.07       0  5002.9     0.1       0
  5035.8    0.05       0  5140.8     0.1       0
Bank Sta=4996.9,5002.9
Exp/Cntr=0.3,0.1

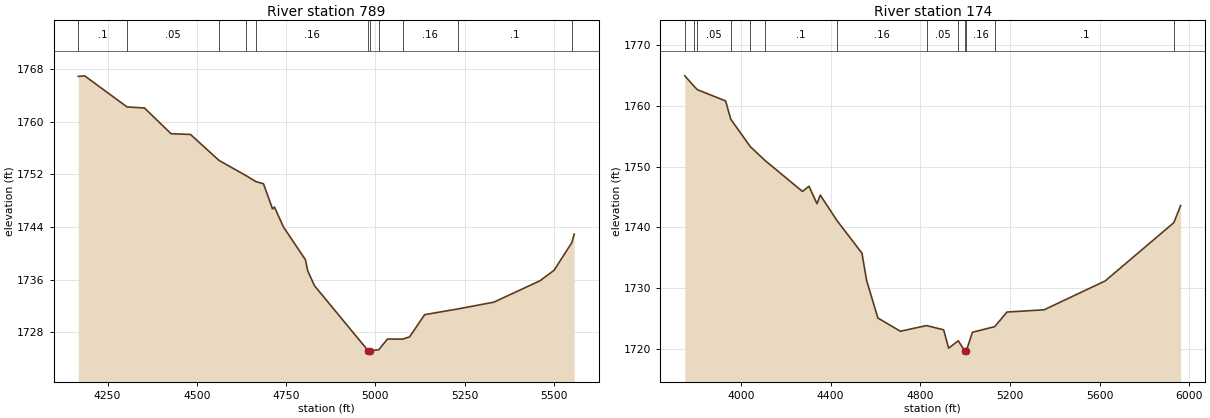
Type RM Length L Ch R = 1,789,615,615,615
BEGIN DESCRIPTION:
Mapping XS 85d81aab
END DESCRIPTION:
XS GIS Cut Line= 4
      2773238.44     10021708.02      2773540.09     10020870.35
      2773559.62     10020761.84      2773199.53     10020618.67
#Sta/Elev= 30
  4168.3 1766.91  4186.0 1767.00  4304.7 1762.27  4353.5 1762.11  4427.9 1758.20
  4482.3 1758.09  4562.2 1754.14  4637.4 1751.84  4665.1 1750.93  4686.6 1750.59
  4712.0 1746.77  4717.3 1747.05  4742.7 1744.01  4804.1 1739.04  4810.6 1737.33
  4829.5 1735.09  4980.0 1725.19  4982.7 1724.69  4986.0 1725.19  5009.6 1725.37
  5033.8 1726.99  5076.3 1726.97  5095.8 1727.32  5137.8 1730.69  5229.9 1731.55
  5331.6 1732.59  5460.7 1735.84  5500.2 1737.44  5550.0 1741.65  5556.4 1742.93
#Mann=11,-1,0
  4168.3     0.1       0  4304.7    0.05       0  4562.2     0.1       0
  4637.4    0.05       0  4665.1    0.16       0  4980.0    0.07       0
  4986.0    0.16       0  5009.6    0.05       0  5076.3    0.16       0
  5229.9     0.1       0  5550.0    0.05       0
Bank Sta=4980,4986
Exp/Cntr=0.3,0.1

Type RM Length L Ch R = 1,174,0,0,0
BEGIN DESCRIPTION:
UNT028 IN SNOGR 1.0
END DESCRIPTION:
XS GIS Cut Line= 5
      2773355.61     10021875.16      2774069.61     10020900.73
      2774076.12     10020822.60      2773865.61     10020690.22
      2773195.06     10020599.08
#Sta/Elev= 30
  3749.6 1764.97  3789.3 1763.32  3805.5 1762.69  3931.6 1760.83  3954.6 1757.82
  4041.9 1753.29  4107.8 1751.00  4274.4 1745.91  4303.7 1746.76  4339.2 1743.89
  4353.8 1745.31  4428.9 1741.08  4539.9 1735.73  4560.7 1731.22  4610.9 1725.04
  4711.3 1722.85  4827.8 1723.79  4904.3 1723.09  4926.6 1720.07  4969.6 1721.28
  4998.9 1719.58  5001.7 1719.08  5004.9 1719.58  5032.9 1722.69  5132.1 1723.61
  5186.8 1726.02  5352.4 1726.39  5624.9 1731.15  5931.2 1740.76  5961.4 1743.58
#Mann=13,-1,0
  3749.6    0.05       0  3789.3     0.1       0  3805.5    0.05       0
  3954.6     0.1       0  4041.9    0.05       0  4107.8     0.1       0
  4428.9    0.16       0  4827.8    0.05       0  4969.6    0.16       0
  4998.9    0.07       0  5004.9    0.16       0  5132.1     0.1       0
  5931.2    0.05       0
Bank Sta=4998.9,5004.9
Exp/Cntr=0.3,0.1

Chan Stop Cuts=-1