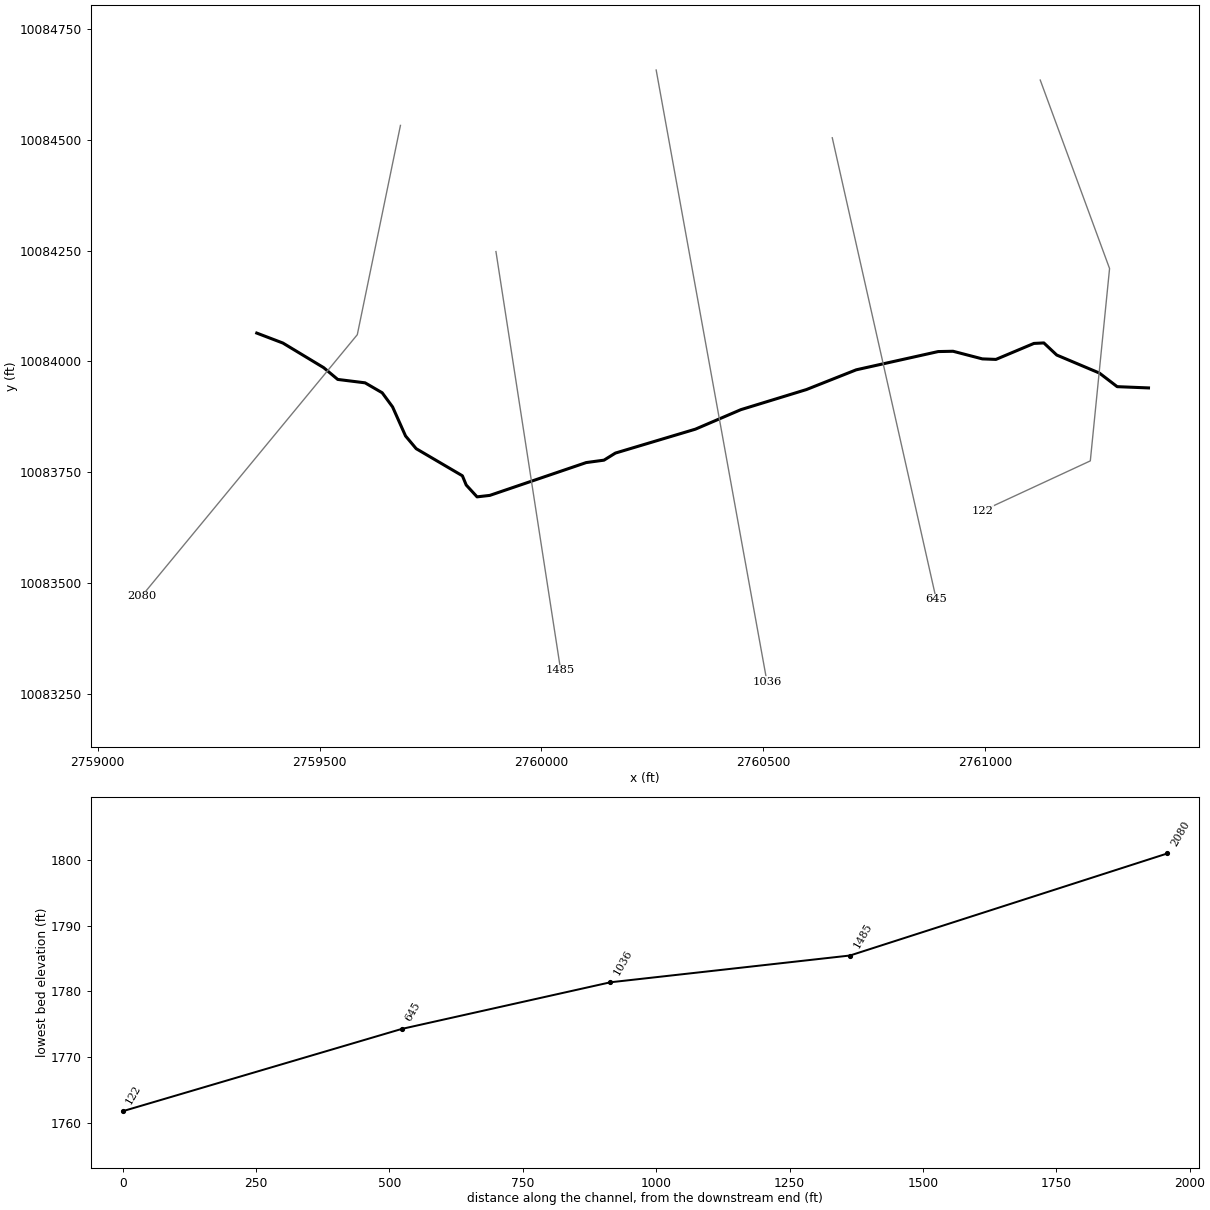
--- UNT029 IN NNOGR.prj (project) ---

Proj Title=UNT029 IN NNOGR Base Level Engineering
Current Plan=p01
Default Exp/Contr=0.3,0.1
English Units
Geom File=g01
Flow File=f01
Plan File=p01
Y Axis Title=Elevation
X Axis Title(PF)=Main Channel Distance
X Axis Title(XS)=Station
BEGIN DESCRIPTION:
UNT029 IN NNOGR
END DESCRIPTION:
DSS Export Rating Curves= 0
DSS Export Rating Curve Sorted= 0
DSS Export Volume Flow Curves= 0
DXF OffsetX= 0
DXF OffsetY= 0
DXF ScaleX= 1
DXF ScaleY= 10

--- UNT029 IN NNOGR.p01 (plan) ---

Plan Title=Multiple Run
Short Identifier=Multiple
Geom File=g01
Flow File=f01
Subcritical Flow
K Sum by GR= 0
Std Step Tol= 0.01
Critical Tol= 0.01
Num of Std Step Trials= 20
Max Error Tol= 0.3
Flow Tol Ratio= 0.001
Split Flow NTrial= 30
Split Flow Tol= 0.02
Split Flow Ratio= 0.02
Log Output Level= 0
Friction Slope Method= 1
Unsteady Friction Slope Method= 2
Unsteady Bridges Friction Slope Method= 1
Parabolic Critical Depth
Global Vel Dist=  1 , 1 , 1
Global Log Level= 0
CheckData=True
Encroach Param= -1, 0, 0, 0
BEGIN DESCRIPTION:
Multiple Run
END DESCRIPTION:

--- UNT029 IN NNOGR.f01 (steady flow) ---

Flow Title=Multiple
Number of Profiles=7
Profile Names=10-year,25-year,50-year,1pct_min,100-year,1pct_plu,500-year
River Rch & RM= UNT029 IN NNOGR,Reach-1,2080
     586     840    1060     982    1328    1796    2090
Boundary for River Rch & Prof#=UNT029 IN NNOGR,Reach-1,1
Up Type=0
Dn Type=3
Dn Slope=0.005
Boundary for River Rch & Prof#=UNT029 IN NNOGR,Reach-1,2
Up Type=0
Dn Type=3
Dn Slope=0.005
Boundary for River Rch & Prof#=UNT029 IN NNOGR,Reach-1,3
Up Type=0
Dn Type=3
Dn Slope=0.005
Boundary for River Rch & Prof#=UNT029 IN NNOGR,Reach-1,4
Up Type=0
Dn Type=3
Dn Slope=0.005
Boundary for River Rch & Prof#=UNT029 IN NNOGR,Reach-1,5
Up Type=0
Dn Type=3
Dn Slope=0.005
Boundary for River Rch & Prof#=UNT029 IN NNOGR,Reach-1,6
Up Type=0
Dn Type=3
Dn Slope=0.005
Boundary for River Rch & Prof#=UNT029 IN NNOGR,Reach-1,7
Up Type=0
Dn Type=3
Dn Slope=0.005

--- UNT029 IN NNOGR.g01 (geometry) ---

Geom Title=Existing Conditions
Program Version=4.10

River Reach=UNT029 IN NNOGR ,Reach-1
Reach XY= 30
      2759358.47     10084063.73      2759417.43     10084041.22
      2759509.28      10083985.7        2759541.     10083959.11
      2759602.62     10083951.45      2759641.19     10083929.03
      2759664.66     10083897.04      2759693.86      10083831.5
      2759717.82     10083802.86      2759821.99     10083741.66
      2759830.58     10083720.83      2759855.03     10083694.11
       2759883.8     10083697.44      2760101.04     10083771.49
      2760141.13     10083776.93      2760166.81      10083792.9
      2760347.16     10083846.88      2760449.64      10083890.9
      2760597.42     10083936.26      2760709.67     10083980.82
      2760894.34     10084021.99      2760927.93     10084022.67
      2760993.94     10084005.46       2761024.5      10084004.3
      2761110.14     10084040.36      2761132.52     10084041.48
      2761161.54     10084014.17       2761257.7     10083973.52
      2761297.74     10083942.81      2761368.39     10083939.95

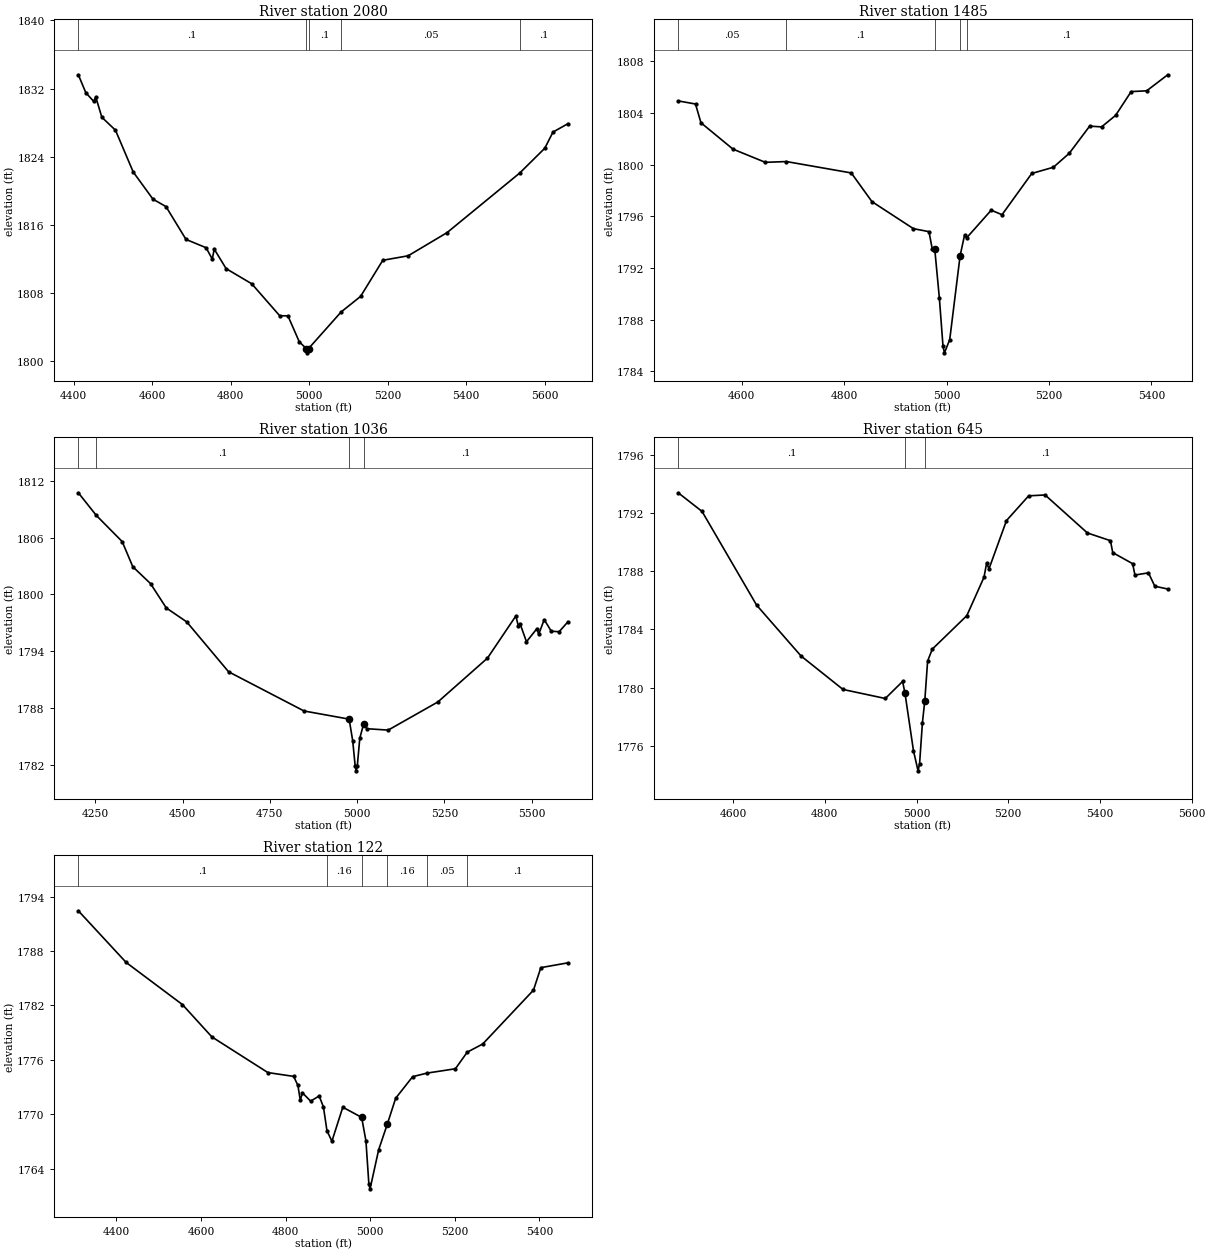
Type RM Length L Ch R = 1 ,2080    ,595,595,595
BEGIN DESCRIPTION:
UNT029 IN NNOGR 4.0
END DESCRIPTION:
XS GIS Cut Line= 3
      2759682.35     10084532.35      2759585.12     10084060.12
      2759099.02     10083469.86
#Sta/Elev= 30
  4412.1 1833.62  4431.1 1831.52  4451.3 1830.49  4456.4 1831.02    4472 1828.63
  4506.7 1827.11  4551.9  1822.2  4602.2 1819.01  4635.3 1818.14  4686.4 1814.28
  4737.4 1813.31  4753.2 1811.98  4758.3 1813.14  4788.5 1810.85  4853.8 1809.07
  4925.1 1805.31  4945.9 1805.31  4974.6 1802.28  4992.4 1801.46  4995.2 1800.96
  4998.4 1801.46  5081.4 1805.76    5131 1807.59  5187.5 1811.83  5252.2 1812.36
  5351.2 1815.08  5536.3 1822.08  5600.1 1824.99    5621 1826.89  5658.9 1827.87
#Mann= 5 ,-1 , 0
  4412.1      .1       0  4992.4     .07       0  4998.4      .1       0
  5081.4     .05       0  5536.3      .1       0
Bank Sta=4992.4,4998.4
XS Rating Curve= 0 ,0
Exp/Cntr=0.3,0.1

Type RM Length L Ch R = 1 ,1485    ,449,449,449
BEGIN DESCRIPTION:
UNT029 IN NNOGR 3.0
END DESCRIPTION:
XS GIS Cut Line= 2
      2759897.62     10084247.65      2760043.46     10083303.14
#Sta/Elev= 30
    4476 1804.92  4509.8 1804.68  4520.4 1803.23    4583 1801.19  4646.1 1800.17
  4687.3 1800.23  4813.9 1799.35  4854.3 1797.13  4935.3 1795.04  4965.6 1794.81
  4971.9 1793.49  4976.9 1793.45  4985.9 1789.66    4993 1785.94  4995.8 1785.44
  5006.1 1786.46  5026.4 1792.96    5035 1794.53  5039.1 1794.33  5087.1 1796.47
  5108.2 1796.12  5166.3 1799.31  5208.5 1799.79  5239.5 1800.87  5279.3 1802.97
  5302.6 1802.91  5329.9  1803.8  5360.3 1805.64  5390.6  1805.7  5431.7 1806.94
#Mann= 5 ,-1 , 0
    4476     .05       0  4687.3      .1       0  4976.9     .07       0
  5026.4     .16       0  5039.1      .1       0
Bank Sta=4976.9,5026.4
XS Rating Curve= 0 ,0
Exp/Cntr=0.3,0.1

Type RM Length L Ch R = 1 ,1036    ,391,391,391
BEGIN DESCRIPTION:
UNT029 IN NNOGR 2.0
END DESCRIPTION:
XS GIS Cut Line= 2
      2760258.74     10084657.33      2760508.44     10083277.03
#Sta/Elev= 30
  4201.2 1810.73  4252.5 1808.35  4326.8 1805.58  4357.3 1802.92  4408.1 1801.14
  4453.2 1798.57  4511.7  1797.1  4631.7 1791.83  4847.9 1787.69  4977.2 1786.83
  4987.4 1784.54  4994.5 1781.87  4997.3 1781.37  5000.5 1781.87  5007.7 1784.82
  5018.6  1786.3    5028 1785.82    5089 1785.67  5231.3 1788.64  5373.5 1793.27
  5454.8 1797.72  5461.8  1796.7  5466.8 1796.92  5485.3    1795  5515.3 1796.39
  5520.3 1795.78  5536.1 1797.34  5556.4 1796.11  5578.9 1796.06  5603.9  1797.1
#Mann= 4 ,-1 , 0
  4201.2     .05       0  4252.5      .1       0  4977.2     .07       0
  5018.6      .1       0
Bank Sta=4977.2,5018.6
XS Rating Curve= 0 ,0
Exp/Cntr=0.3,0.1

Type RM Length L Ch R = 1 ,645     ,523,523,523
BEGIN DESCRIPTION:
Mapping XS 89141899
END DESCRIPTION:
XS GIS Cut Line= 2
      2760655.65     10084504.45      2760890.03      10083462.8
#Sta/Elev= 30
  4480.1 1793.38  4532.1  1792.1  4651.2 1785.66    4748 1782.17  4839.6 1779.87
  4931.8 1779.25  4969.5 1780.42  4974.6 1779.64  4993.3 1775.65  5003.3 1774.28
  5006.6 1774.78  5012.8  1777.6  5017.9 1779.08  5024.1 1781.82  5034.3 1782.64
  5109.6 1784.94  5147.1 1787.58  5152.8 1788.55    5158 1788.16  5196.1 1791.47
  5244.5 1793.17  5280.3 1793.23  5372.6 1790.62  5422.8 1790.09  5427.9 1789.27
  5471.2 1788.51  5476.3 1787.73  5505.8 1787.88  5519.6 1786.96  5547.8 1786.77
#Mann= 3 , 0 , 0
  4480.1      .1       0  4974.6     .07       0  5017.9      .1       0
Bank Sta=4974.6,5017.9
XS Rating Curve= 0 ,0
Exp/Cntr=0.3,0.1

Type RM Length L Ch R = 1 ,122     ,0,0,0
BEGIN DESCRIPTION:
UNT029 IN NNOGR 1.0
END DESCRIPTION:
XS GIS Cut Line= 4
       2761124.4     10084634.67      2761280.65     10084209.33
      2761237.25      10083775.3       2760994.2     10083662.45
#Sta/Elev= 30
  4310.1 1792.43  4423.2 1786.73  4556.1 1782.09  4625.9 1778.52  4758.2 1774.59
  4819.1 1774.17  4829.2 1773.17  4834.8 1771.53  4839.8 1772.36  4859.3 1771.44
  4879.4 1772.01  4889.5 1770.81  4897.9 1768.17  4909.6 1767.02  4935.3 1770.77
  4979.9 1769.65    4990 1767.06    4997 1762.27  4999.8 1761.77  5020.1 1766.08
  5040.8 1768.94  5060.3 1771.76  5100.5 1774.14  5134.2 1774.53  5201.5 1775.01
  5229.5 1776.84  5266.1 1777.74  5386.1 1783.68  5403.5 1786.16  5467.4 1786.69
#Mann= 6 ,-1 , 0
  4310.1      .1       0  4897.9     .16       0  4979.9     .07       0
  5040.8     .16       0  5134.2     .05       0  5229.5      .1       0
Bank Sta=4979.9,5040.8
XS Rating Curve= 0 ,0
Exp/Cntr=0.3,0.1

Chan Stop Cuts=-1
Use User Specified Reach Order=0
Composite Channel Slope=5