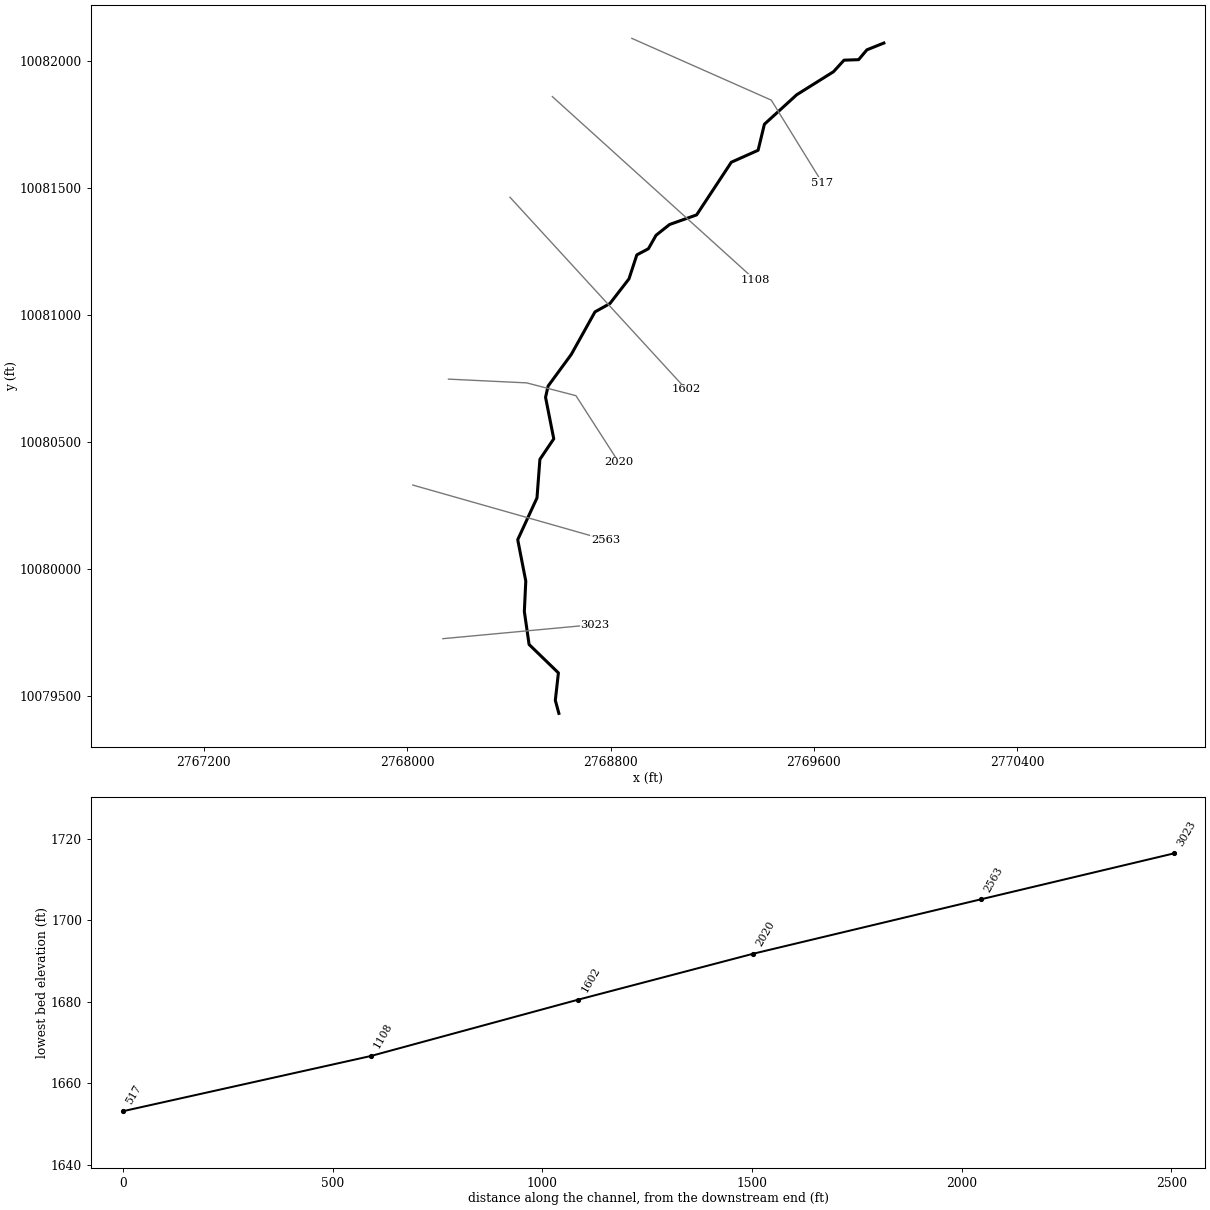
--- UNT031 IN NNOGR.prj (project) ---

Proj Title=UNT031 IN NNOGR Base Level Engineering
Current Plan=p01
Default Exp/Contr=0.3,0.1
English Units
Geom File=g01
Flow File=f01
Plan File=p01
BEGIN DESCRIPTION:
UNT031 IN NNOGR
END DESCRIPTION:

--- UNT031 IN NNOGR.p01 (plan) ---

Plan Title=Multiple Run
Short Identifier=Multiple
Geom File=g01
Flow File=f01
Subcritical Flow
K Sum by GR= 0
Std Step Tol= 0.01
Critical Tol= 0.01
Num of Std Step Trials= 20
Max Error Tol= 0.3
Flow Tol Ratio= 0.001
Split Flow NTrial= 30
Split Flow Tol= 0.02
Split Flow Ratio= 0.02
Log Output Level= 0
Friction Slope Method= 1
Unsteady Friction Slope Method= 2
Unsteady Bridges Friction Slope Method= 1
Parabolic Critical Depth
Global Vel Dist=  1 , 1 , 1
Global Log Level= 0
CheckData=True
Encroach Param= -1, 0, 0, 0
BEGIN DESCRIPTION:
Multiple Run
END DESCRIPTION:

--- UNT031 IN NNOGR.f01 (steady flow) ---

Flow Title=Multiple
Number of Profiles=7
Profile Names=10-year,25-year,50-year,1pct_min,100-year,1pct_plu,500-year
River Rch & RM= UNT031 IN NNOGR,Reach-1,3023
     424     595     738     674     912    1233    1393
Boundary for River Rch & Prof#=UNT031 IN NNOGR,Reach-1,1
Up Type=0
Dn Type=3
Dn Slope=0.005
Boundary for River Rch & Prof#=UNT031 IN NNOGR,Reach-1,2
Up Type=0
Dn Type=3
Dn Slope=0.005
Boundary for River Rch & Prof#=UNT031 IN NNOGR,Reach-1,3
Up Type=0
Dn Type=3
Dn Slope=0.005
Boundary for River Rch & Prof#=UNT031 IN NNOGR,Reach-1,4
Up Type=0
Dn Type=3
Dn Slope=0.005
Boundary for River Rch & Prof#=UNT031 IN NNOGR,Reach-1,5
Up Type=0
Dn Type=3
Dn Slope=0.005
Boundary for River Rch & Prof#=UNT031 IN NNOGR,Reach-1,6
Up Type=0
Dn Type=3
Dn Slope=0.005
Boundary for River Rch & Prof#=UNT031 IN NNOGR,Reach-1,7
Up Type=0
Dn Type=3
Dn Slope=0.005

--- UNT031 IN NNOGR.g01 (geometry) ---

Geom Title=Existing Conditions

River Reach=UNT031 IN NNOGR,Reach-1
Reach XY= 30
      2768596.87     10079433.02      2768582.91     10079484.26
      2768595.06     10079592.29      2768479.75     10079703.96
      2768461.08     10079833.76      2768466.77     10079953.38
      2768435.03     10080115.98      2768510.80     10080280.48
      2768522.26     10080432.09      2768576.79     10080512.82
      2768544.51     10080676.07      2768554.58     10080720.41
      2768645.79     10080844.84      2768738.93     10081012.07
      2768797.53     10081044.71      2768872.49     10081141.70
      2768903.50     10081236.22      2768949.04     10081260.41
      2768979.10     10081313.38      2769032.29     10081355.73
      2769138.63     10081393.48      2769275.13     10081600.67
      2769380.44     10081647.69      2769405.19     10081750.01
      2769532.22     10081865.96      2769676.77     10081956.51
      2769718.43     10082002.04      2769775.74     10082004.00
      2769808.30     10082042.67      2769875.00     10082069.44

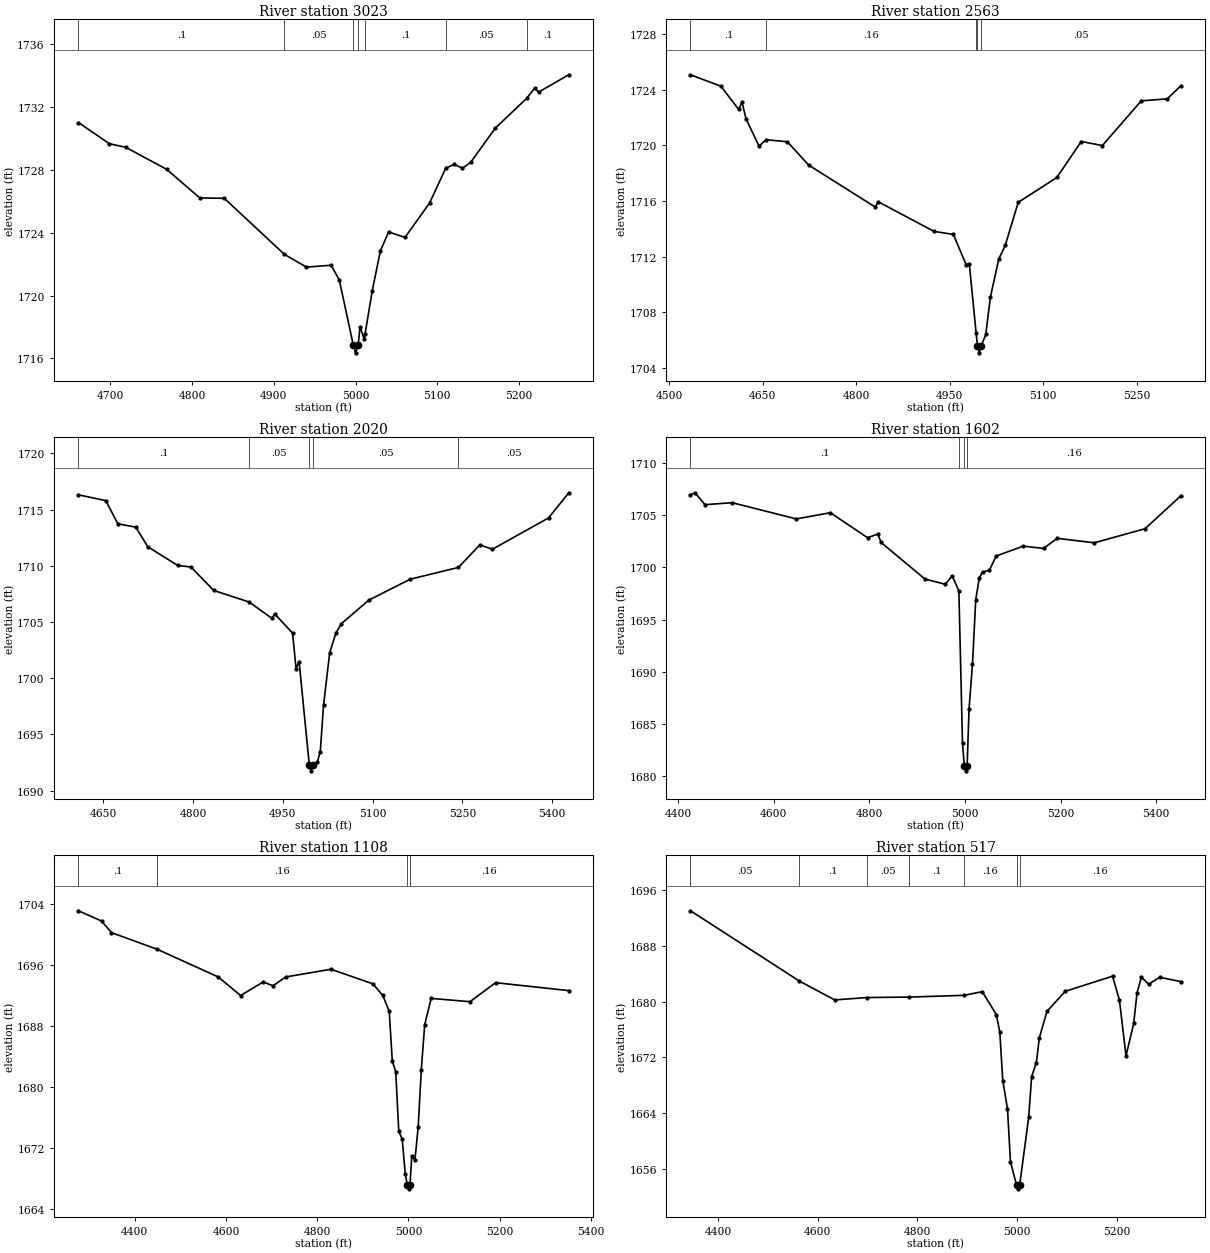
Type RM Length L Ch R = 1,3023,460,460,460
BEGIN DESCRIPTION:
UNT031 IN NNOGR 6.0
END DESCRIPTION:
XS GIS Cut Line= 2
      2768140.71     10079726.79      2768737.93     10079782.35
#Sta/Elev= 30
  4661.0 1731.02  4698.9 1729.67  4719.0 1729.44  4769.2 1728.03  4809.4 1726.22
  4839.5 1726.19  4913.0 1722.62  4940.0 1721.81  4970.1 1721.93  4980.1 1721.00
  4997.2 1716.85  5000.0 1716.35  5003.2 1716.85  5005.5 1718.01  5010.6 1717.22
  5011.7 1717.57  5020.3 1720.27  5030.3 1722.83  5040.4 1724.05  5060.5 1723.70
  5090.6 1725.90  5110.4 1728.12  5120.7 1728.35  5130.8 1728.11  5140.8 1728.48
  5170.9 1730.66  5209.1 1732.55  5219.0 1733.20  5224.0 1732.96  5260.8 1734.06
#Mann=7,-1,0
  4661.0     0.1       0  4913.0    0.05       0  4997.2   0.035       0
  5003.2    0.05       0  5011.7     0.1       0  5110.4    0.05       0
  5209.1     0.1       0
Bank Sta=4997.2,5003.2
Exp/Cntr=0.3,0.1

Type RM Length L Ch R = 1,2563,543,543,543
BEGIN DESCRIPTION:
UNT031 IN NNOGR 5.0
END DESCRIPTION:
XS GIS Cut Line= 2
      2768022.63     10080330.95      2768779.61     10080115.67
#Sta/Elev= 30
  4534.2 1725.06  4583.0 1724.24  4611.6 1722.57  4616.8 1723.11  4623.4 1721.89
  4644.2 1719.94  4655.7 1720.40  4689.8 1720.25  4723.7 1718.58  4830.5 1715.57
  4835.7 1715.94  4924.9 1713.82  4956.1 1713.60  4976.4 1711.44  4981.6 1711.49
  4992.6 1706.52  4994.7 1705.60  4997.5 1705.10  5000.7 1705.60  5008.1 1706.42
  5015.4 1709.08  5028.9 1711.83  5039.3 1712.81  5060.1 1715.90  5122.2 1717.69
  5161.3 1720.27  5195.2 1719.98  5257.6 1723.19  5299.2 1723.33  5321.2 1724.27
#Mann=5,-1,0
  4534.2     0.1       0  4655.7    0.16       0  4992.6    0.05       0
  4994.7   0.035       0  5000.7    0.05       0
Bank Sta=4994.7,5000.7
Exp/Cntr=0.3,0.1

Type RM Length L Ch R = 1,2020,418,418,418
BEGIN DESCRIPTION:
UNT031 IN NNOGR 4.0
END DESCRIPTION:
XS GIS Cut Line= 4
      2768162.68     10080747.62      2768470.37     10080732.81
      2768663.97     10080682.52      2768832.16     10080421.01
#Sta/Elev= 30
  4608.7 1716.32  4654.5 1715.80  4674.6 1713.74  4704.6 1713.44  4724.6 1711.70
  4774.7 1710.03  4796.7 1709.90  4834.7 1707.81  4893.9 1706.78  4931.6 1705.34
  4936.8 1705.71  4966.4 1704.02  4972.2 1700.86  4977.3 1701.48  4994.4 1692.26
  4997.2 1691.76  5000.4 1692.26  5007.6 1692.52  5012.7 1693.47  5018.1 1697.58
  5028.4 1702.26  5038.8 1704.02  5048.1 1704.86  5093.8 1706.95  5162.9 1708.81
  5243.5 1709.86  5279.0 1711.86  5300.2 1711.48  5393.9 1714.26  5427.7 1716.50
#Mann=5,-1,0
  4608.7     0.1       0  4893.9    0.05       0  4994.4    0.07       0
  5000.4    0.05       0  5243.5    0.05       0
Bank Sta=4994.4,5000.4
Exp/Cntr=0.3,0.1

Type RM Length L Ch R = 1,1602,494,494,494
BEGIN DESCRIPTION:
UNT031 IN NNOGR 3.0
END DESCRIPTION:
XS GIS Cut Line= 2
      2768404.57     10081462.89      2769097.71     10080707.38
#Sta/Elev= 30
  4426.3 1706.96  4435.7 1707.16  4456.7 1706.02  4513.4 1706.21  4647.8 1704.65
  4718.7 1705.25  4796.4 1702.85  4818.0 1703.20  4824.8 1702.39  4916.7 1698.88
  4959.2 1698.38  4973.4 1699.20  4987.4 1697.74  4995.0 1683.15  4998.7 1680.98
  5001.5 1680.48  5004.7 1680.98  5008.7 1686.44  5015.9 1690.75  5022.7 1696.91
  5030.1 1698.99  5036.9 1699.56  5051.1 1699.72  5065.3 1701.09  5122.0 1702.04
  5164.5 1701.82  5192.9 1702.79  5270.6 1702.36  5376.6 1703.71  5451.6 1706.88
#Mann=4,-1,0
  4426.3     0.1       0  4987.4    0.16       0  4998.7    0.07       0
  5004.7    0.16       0
Bank Sta=4998.7,5004.7
Exp/Cntr=0.3,0.1

Type RM Length L Ch R = 1,1108,591,591,591
BEGIN DESCRIPTION:
UNT031 IN NNOGR 2.0
END DESCRIPTION:
XS GIS Cut Line= 2
      2768571.25     10081858.72      2769368.64     10081137.61
#Sta/Elev= 30
  4276.4 1703.11  4327.2 1701.77  4348.9 1700.25  4449.8 1698.05  4582.7 1694.45
  4632.1 1692.01  4681.4 1693.78  4703.1 1693.29  4731.1 1694.44  4830.1 1695.45
  4922.0 1693.54  4943.7 1692.02  4957.9 1689.92  4964.6 1683.42  4972.1 1682.05
  4978.8 1674.23  4986.3 1673.20  4993.0 1668.66  4997.4 1667.18  5000.2 1666.68
  5003.4 1667.18  5007.2 1670.92  5014.2 1670.47  5021.4 1674.81  5028.1 1682.21
  5035.6 1688.18  5049.8 1691.63  5135.0 1691.20  5191.0 1693.69  5351.5 1692.65
#Mann=4,-1,0
  4276.4     0.1       0  4449.8    0.16       0  4997.4    0.07       0
  5003.4    0.16       0
Bank Sta=4997.4,5003.4
Exp/Cntr=0.3,0.1

Type RM Length L Ch R = 1,517,0,0,0
BEGIN DESCRIPTION:
UNT031 IN NNOGR 1.0
END DESCRIPTION:
XS GIS Cut Line= 3
      2768883.73     10082087.90      2769432.35     10081844.84
      2769633.49     10081518.85
#Sta/Elev= 30
  4345.1 1693.01  4563.5 1682.93  4634.2 1680.23  4698.4 1680.57  4783.6 1680.64
  4893.6 1680.89  4930.0 1681.42  4958.2 1678.13  4965.2 1675.62  4971.1 1668.66
  4980.6 1664.63  4986.5 1657.05  4998.9 1653.65  5001.6 1653.15  5004.9 1653.65
  5023.1 1663.42  5029.0 1669.25  5038.5 1671.25  5044.4 1674.79  5059.8 1678.60
  5096.5 1681.47  5191.1 1683.63  5205.0 1680.21  5218.2 1672.21  5233.6 1676.87
  5240.2 1681.23  5249.0 1683.51  5263.7 1682.48  5285.7 1683.48  5328.2 1682.85
#Mann=7,-1,0
  4345.1    0.05       0  4563.5     0.1       0  4698.4    0.05       0
  4783.6     0.1       0  4893.6    0.16       0  4998.9    0.07       0
  5004.9    0.16       0
Bank Sta=4998.9,5004.9
Exp/Cntr=0.3,0.1

Chan Stop Cuts=-1