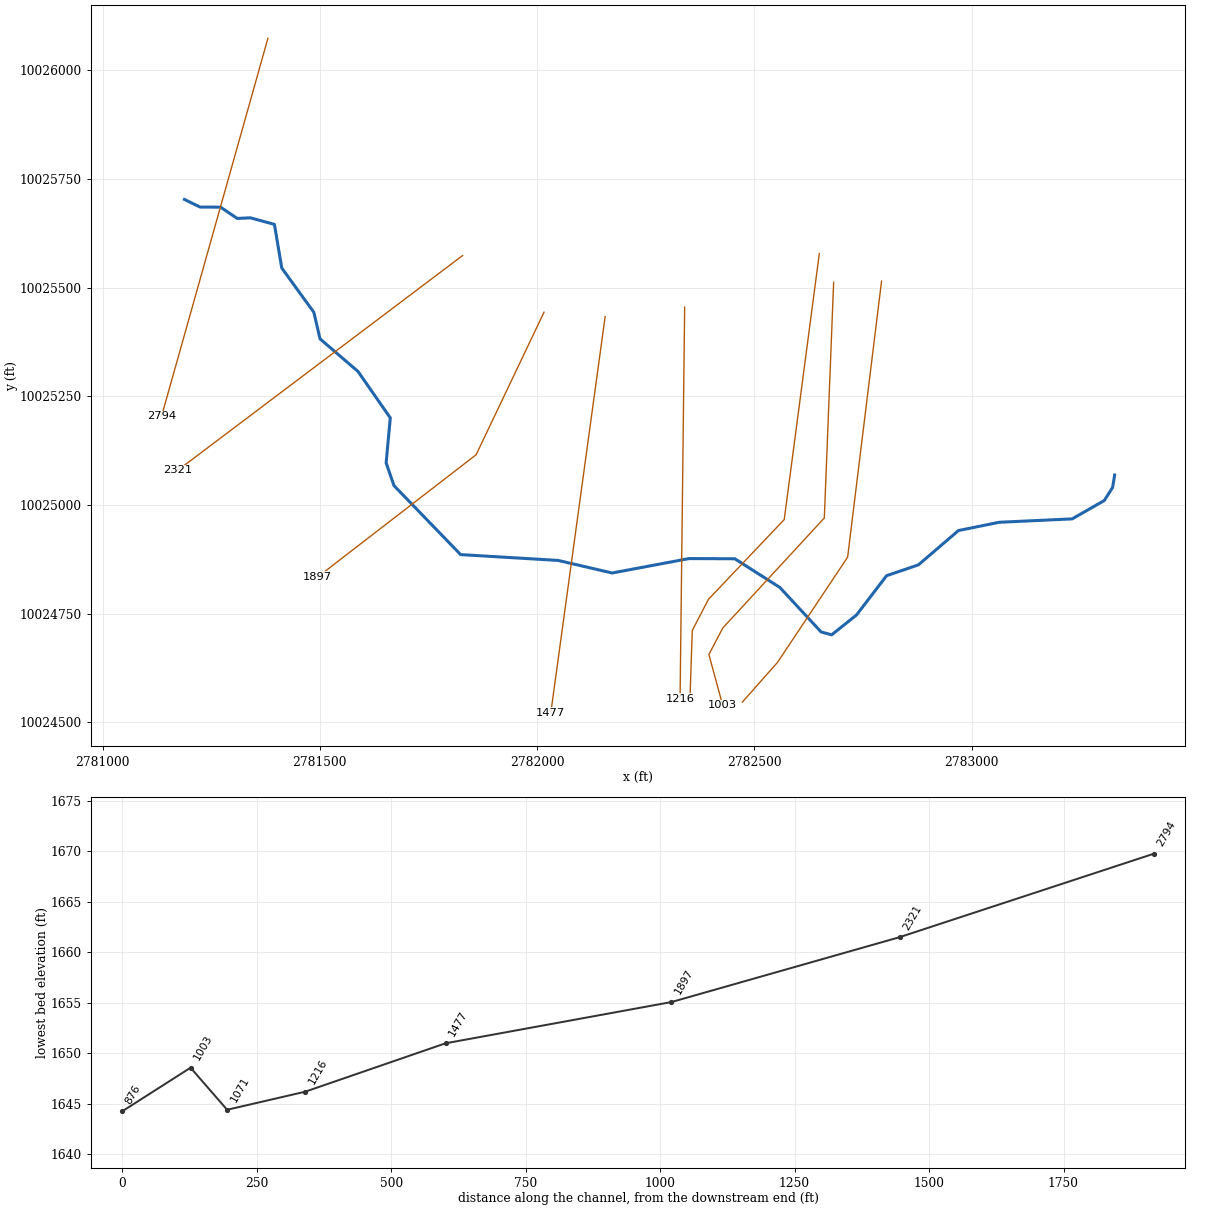
--- UNT031 IN SNOGR.prj (project) ---

Proj Title=UNT031 IN SNOGR Base Level Engineering
Current Plan=p01
Default Exp/Contr=0.3,0.1
English Units
Geom File=g01
Flow File=f01
Plan File=p01
Y Axis Title=Elevation
X Axis Title(PF)=Main Channel Distance
X Axis Title(XS)=Station
BEGIN DESCRIPTION:
UNT031 IN SNOGR
END DESCRIPTION:
DSS Export Rating Curves= 0
DSS Export Rating Curve Sorted= 0
DSS Export Volume Flow Curves= 0
DXF OffsetX= 0
DXF OffsetY= 0
DXF ScaleX= 1
DXF ScaleY= 10

--- UNT031 IN SNOGR.p01 (plan) ---

Plan Title=Multiple Run
Short Identifier=Multiple
Geom File=g01
Flow File=f01
Subcritical Flow
K Sum by GR= 0
Std Step Tol= 0.01
Critical Tol= 0.01
Num of Std Step Trials= 20
Max Error Tol= 0.3
Flow Tol Ratio= 0.001
Split Flow NTrial= 30
Split Flow Tol= 0.02
Split Flow Ratio= 0.02
Log Output Level= 0
Friction Slope Method= 1
Unsteady Friction Slope Method= 2
Unsteady Bridges Friction Slope Method= 1
Parabolic Critical Depth
Global Vel Dist=  1 , 1 , 1
Global Log Level= 0
CheckData=True
Encroach Param= -1, 0, 0, 0
BEGIN DESCRIPTION:
Multiple Run
END DESCRIPTION:

--- UNT031 IN SNOGR.f01 (steady flow) ---

Flow Title=Multiple
Number of Profiles=7
Profile Names=10-year,25-year,50-year,1pct_min,100-year,1pct_plu,500-year
River Rch & RM= UNT031 IN SNOGR,Reach-1,2794
     977    1436    1839    1724    2332    3153    3765
Boundary for River Rch & Prof#=UNT031 IN SNOGR,Reach-1,1
Up Type=0
Dn Type=3
Dn Slope=0.005
Boundary for River Rch & Prof#=UNT031 IN SNOGR,Reach-1,2
Up Type=0
Dn Type=3
Dn Slope=0.005
Boundary for River Rch & Prof#=UNT031 IN SNOGR,Reach-1,3
Up Type=0
Dn Type=3
Dn Slope=0.005
Boundary for River Rch & Prof#=UNT031 IN SNOGR,Reach-1,4
Up Type=0
Dn Type=3
Dn Slope=0.005
Boundary for River Rch & Prof#=UNT031 IN SNOGR,Reach-1,5
Up Type=0
Dn Type=3
Dn Slope=0.005
Boundary for River Rch & Prof#=UNT031 IN SNOGR,Reach-1,6
Up Type=0
Dn Type=3
Dn Slope=0.005
Boundary for River Rch & Prof#=UNT031 IN SNOGR,Reach-1,7
Up Type=0
Dn Type=3
Dn Slope=0.005

--- UNT031 IN SNOGR.g01 (geometry) ---

Geom Title=Existing Conditions
Program Version=4.10

River Reach=UNT031 IN SNOGR ,Reach-1
Reach XY= 30
       2781188.4     10025703.27      2781224.26     10025685.74
      2781271.58     10025685.46      2781309.76     10025659.57
      2781340.26     10025660.94       2781395.5     10025645.87
      2781412.39     10025545.37      2781486.24     10025443.47
      2781500.43     10025382.44      2781587.95     10025307.21
      2781662.14      10025200.6      2781652.57     10025097.04
      2781670.69      10025044.6      2781824.01     10024885.92
      2782048.42     10024872.51      2782172.72      10024843.6
      2782349.48     10024876.79      2782454.97     10024876.33
      2782558.64      10024810.3      2782653.55     10024707.96
      2782677.93     10024701.31      2782735.08     10024746.99
       2782804.3     10024837.42      2782877.45     10024862.26
      2782969.61     10024941.23       2783063.2     10024960.29
      2783231.39     10024968.12      2783305.16     10025010.31
      2783324.44     10025040.48      2783329.03     10025069.02

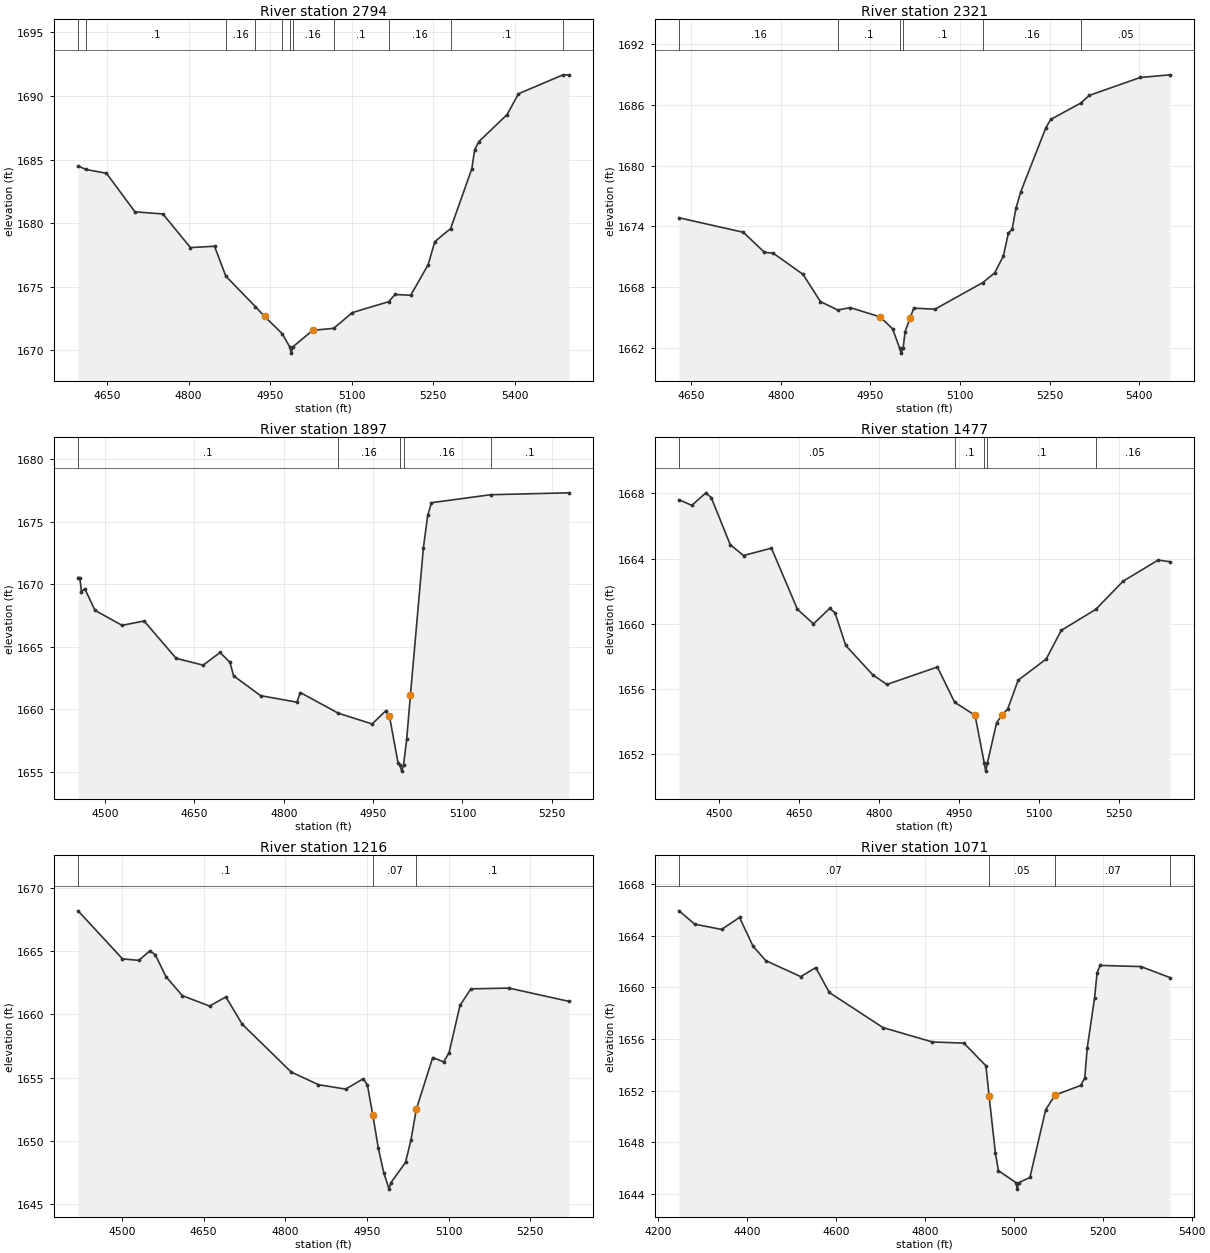
Type RM Length L Ch R = 1 ,2794    ,473,473,473
BEGIN DESCRIPTION:
UNT031 IN SNOGR 7.0
END DESCRIPTION:
XS GIS Cut Line= 2
      2781380.53     10026074.07      2781135.74     10025204.27
#Sta/Elev= 30
  4596.4  1684.5  4610.6 1684.22  4648.7 1683.92  4701.1 1680.89  4752.6 1680.72
  4803.2 1678.08  4847.6 1678.18  4868.4 1675.83  4922.8 1673.44  4939.6 1672.67
  4971.9 1671.32    4986 1670.28  4988.7 1669.78    4992 1670.28  5028.2 1671.57
  5066.9 1671.73  5101.5 1672.97  5168.1 1673.82  5179.9 1674.39  5208.8 1674.33
  5240.8 1676.73  5253.2 1678.55  5282.2 1679.57  5321.3 1684.28  5326.5 1685.77
  5334.3 1686.41  5386.3 1688.54  5407.1 1690.17  5489.2 1691.66    5500 1691.65
#Mann= 11 ,-1 , 0
  4596.4     .05       0  4610.6      .1       0  4868.4     .16       0
  4922.8      .1       0  4971.9     .16       0    4986     .07       0
    4992     .16       0  5066.9      .1       0  5168.1     .16       0
  5282.2      .1       0  5489.2     .05       0
Bank Sta=4939.6,5028.2
XS Rating Curve= 0 ,0
Exp/Cntr=0.3,0.1

Type RM Length L Ch R = 1 ,2321    ,424,424,424
BEGIN DESCRIPTION:
UNT031 IN SNOGR 6.0
END DESCRIPTION:
XS GIS Cut Line= 2
      2781828.46     10025574.08      2781172.84     10025079.75
#Sta/Elev= 30
  4629.9 1674.85  4737.4 1673.42  4772.8 1671.44  4787.4 1671.36  4837.3 1669.27
  4866.5 1666.58  4895.6 1665.75  4916.4 1665.99  4966.4 1665.07  4987.2 1663.89
  4998.8    1662  5001.5  1661.5  5004.8    1662    5008  1663.6  5016.3 1664.95
  5022.6 1665.94    5058 1665.83    5138 1668.46  5157.9 1669.41  5172.5 1671.09
  5180.8 1673.33  5187.1 1673.71  5193.5 1675.79  5201.6 1677.43  5243.6 1683.74
  5251.6 1684.55  5301.9 1686.16  5316.1 1686.92  5401.5 1688.69    5451 1688.95
#Mann= 6 ,-1 , 0
  4629.9     .16       0  4895.6      .1       0  4998.8     .07       0
  5004.8      .1       0    5138     .16       0  5301.9     .05       0
Bank Sta=4966.4,5016.3
XS Rating Curve= 0 ,0
Exp/Cntr=0.3,0.1

Type RM Length L Ch R = 1 ,1897    ,420,420,420
BEGIN DESCRIPTION:
UNT031 IN SNOGR 5.0
END DESCRIPTION:
XS GIS Cut Line= 3
      2782015.93     10025443.81       2781859.7     10025115.73
      2781495.15      10024834.5
#Sta/Elev= 30
  4454.8 1670.54  4457.6 1670.54  4460.5 1669.42    4466 1669.65  4483.2 1667.92
  4528.6 1666.72  4565.6 1667.07  4619.4 1664.08  4664.8 1663.54  4693.1 1664.55
  4709.6 1663.77  4715.8 1662.69  4761.2  1661.1  4822.1 1660.58  4827.8 1661.35
  4891.5  1659.7  4948.3 1658.84    4971 1659.88  4977.3 1659.49  4991.8 1655.74
  4995.1 1655.57  4997.9 1655.07  5001.1 1655.57  5006.3  1657.6  5012.6 1661.15
  5034.4 1672.94  5041.6 1675.51  5047.9 1676.52  5147.4 1677.16  5278.6 1677.31
#Mann= 5 ,-1 , 0
  4454.8      .1       0  4891.5     .16       0  4995.1     .07       0
  5001.1     .16       0  5147.4      .1       0
Bank Sta=4977.3,5012.6
XS Rating Curve= 0 ,0
Exp/Cntr=0.3,0.1

Type RM Length L Ch R = 1 ,1477    ,261,261,261
BEGIN DESCRIPTION:
UNT031 IN SNOGR 4.0
END DESCRIPTION:
XS GIS Cut Line= 2
      2782156.57     10025433.44      2782031.57     10024521.97
#Sta/Elev= 30
  4425.1 1667.61    4449 1667.26  4475.3 1668.03  4485.4 1667.74  4521.1 1664.85
  4545.9 1664.19  4598.3 1664.64  4646.9  1660.9  4677.1    1660  4707.4 1660.95
  4717.5 1660.68  4737.5 1658.68  4788.2 1656.88  4814.7 1656.29  4909.3 1657.36
  4941.6  1655.2    4980  1654.4  4997.1 1651.48  4999.9 1650.98  5003.1 1651.48
  5020.3 1653.94  5030.4 1654.42  5041.2 1654.79  5060.7 1656.55  5113.3 1657.85
  5141.4  1659.6  5206.2 1660.89  5257.5 1662.62  5323.1 1663.91  5345.1 1663.81
#Mann= 5 ,-1 , 0
  4425.1     .05       0  4941.6      .1       0  4997.1     .07       0
  5003.1      .1       0  5206.2     .16       0
Bank Sta=4980,5030.4
XS Rating Curve= 0 ,0
Exp/Cntr=0.3,0.1

Type RM Length L Ch R = 1 ,1216    ,145,145,145
BEGIN DESCRIPTION:
UNT031 IN SNOGR 3.0
END DESCRIPTION:
XS GIS Cut Line= 2
      2782339.56     10025455.33      2782329.01      10024553.6
#Sta/Elev= 30
  4419.3 1668.19  4500.9 1664.39  4530.9 1664.27  4550.9 1665.02  4560.9 1664.73
  4580.9 1662.98  4610.9 1661.48  4660.9 1660.66  4690.9 1661.38  4720.9 1659.22
  4810.9 1655.44  4860.9 1654.44  4910.9 1654.09  4943.1 1654.91  4950.9 1654.42
  4960.9 1652.01  4970.9 1649.43  4980.9 1647.48  4990.7 1646.18  4993.9 1646.68
  5020.9 1648.29  5030.9 1650.08  5040.9 1652.52  5070.9 1656.59  5090.9 1656.24
  5100.9 1656.97    5121 1660.71    5141 1662.02    5211 1662.08  5321.1 1661.03
#Mann= 3 , 0 , 0
  4419.3      .1       0  4960.9     .07       0  5040.9      .1       0
Bank Sta=4960.9,5040.9
XS Rating Curve= 0 ,0
Exp/Cntr=0.3,0.1

Type RM Length L Ch R = 1 ,1071    ,68,68,68
BEGIN DESCRIPTION:
UNT031 IN SNOGR 2.0
END DESCRIPTION:
XS GIS Cut Line= 5
      2782649.46     10025578.61      2782568.73     10024966.65
      2782394.39     10024783.05      2782357.14      10024711.5
      2782351.93      10024558.7
#Sta/Elev= 30
    4247 1665.91  4282.2 1664.88  4342.7 1664.47    4383  1665.4  4413.3 1663.18
  4442.1 1662.06  4520.7 1660.82  4554.5 1661.52  4584.8  1659.6  4705.8 1656.88
  4816.8 1655.77  4887.7 1655.68  4937.2 1653.93  4944.3  1651.6  4958.5 1647.19
  4965.4 1645.82  5004.8 1644.89  5007.6 1644.39  5010.8 1644.89  5036.2 1645.29
  5071.7 1650.54  5092.8 1651.66  5150.5 1652.41  5159.5 1652.98  5165.1  1655.3
  5181.6 1659.16  5187.2  1661.1    5194 1661.69  5285.9  1661.6    5351 1660.75
#Mann= 4 ,-1 , 0
    4247     .07       0  4944.3     .05       0  5092.8     .07       0
    5351      .1       0
Bank Sta=4944.3,5092.8
XS Rating Curve= 0 ,0
Exp/Cntr=0.3,0.1

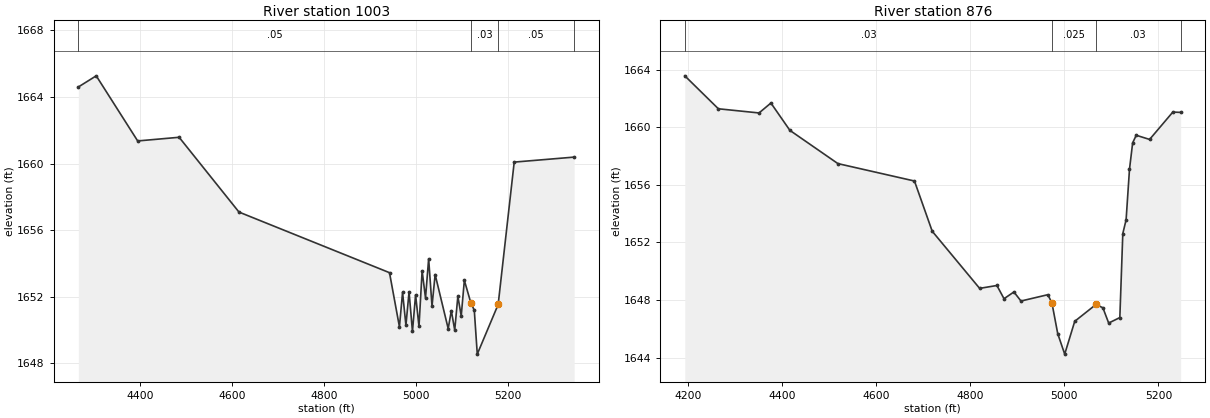
Type RM Length L Ch R = 1 ,1003    ,127,127,127
BEGIN DESCRIPTION:
UNT031 IN SNOGR 222.0
END DESCRIPTION:
XS GIS Cut Line= 5
      2782682.44     10025512.63      2782660.96     10024970.18
      2782427.38     10024717.08      2782395.33     10024655.94
      2782427.23     10024538.72
#Sta/Elev= 30
  4265.8  1664.6  4304.7 1665.27  4394.8 1661.36  4484.9 1661.58    4615 1657.09
  4942.2 1653.45  4963.8  1650.2  4970.6 1652.27  4977.9 1650.29  4984.7  1652.3
  4992.1 1649.92  4998.9 1652.12  5006.3 1650.22  5013.1 1653.56  5020.5 1651.93
  5027.3 1654.29  5034.6 1651.44  5041.4 1653.34  5069.8 1650.09  5076.6 1651.17
    5084    1650  5090.8 1652.04  5098.1 1650.85  5104.9 1652.99  5119.1 1651.63
  5126.5  1651.2    5133 1648.56  5178.4 1651.54  5213.3 1660.09  5343.6 1660.39
#Mann= 4 ,-1 , 0
  4265.8     .05       0  5119.1     .03       0  5178.4     .05       0
  5343.6      .1       0
Bank Sta=5119.1,5178.4
XS Rating Curve= 0 ,0
Exp/Cntr=0.3,0.1

Type RM Length L Ch R = 1 ,876     ,0,0,0
BEGIN DESCRIPTION:
UNT031 IN SNOGR 1.0
END DESCRIPTION:
XS GIS Cut Line= 4
      2782792.69      10025515.3      2782714.56     10024879.84
       2782553.1     10024637.65      2782472.36     10024546.49
#Sta/Elev= 30
  4193.9 1663.58  4265.2 1661.29  4351.6    1661  4376.8 1661.69  4417.1 1659.79
  4519.1 1657.48  4681.7 1656.27  4719.4 1652.78  4820.1 1648.81  4856.8 1649.01
  4871.9 1648.09  4892.9 1648.56  4907.9 1647.93    4965 1648.37  4973.7 1647.79
    4986 1645.66  5000.8 1644.24  5022.1 1646.52  5067.2 1647.69  5081.9 1647.46
  5094.2  1646.4  5117.9 1646.78  5124.2 1652.62  5131.2 1653.57  5138.4 1657.09
  5145.1 1658.92  5152.7 1659.45  5181.1 1659.16  5230.4 1661.06    5247 1661.04
#Mann= 4 ,-1 , 0
  4193.9     .03       0  4973.7    .025       0  5067.2     .03       0
    5247     .16       0
Bank Sta=4973.7,5067.2
XS Rating Curve= 0 ,0
Exp/Cntr=0.3,0.1

Chan Stop Cuts=-1
Use User Specified Reach Order=0
Composite Channel Slope=5