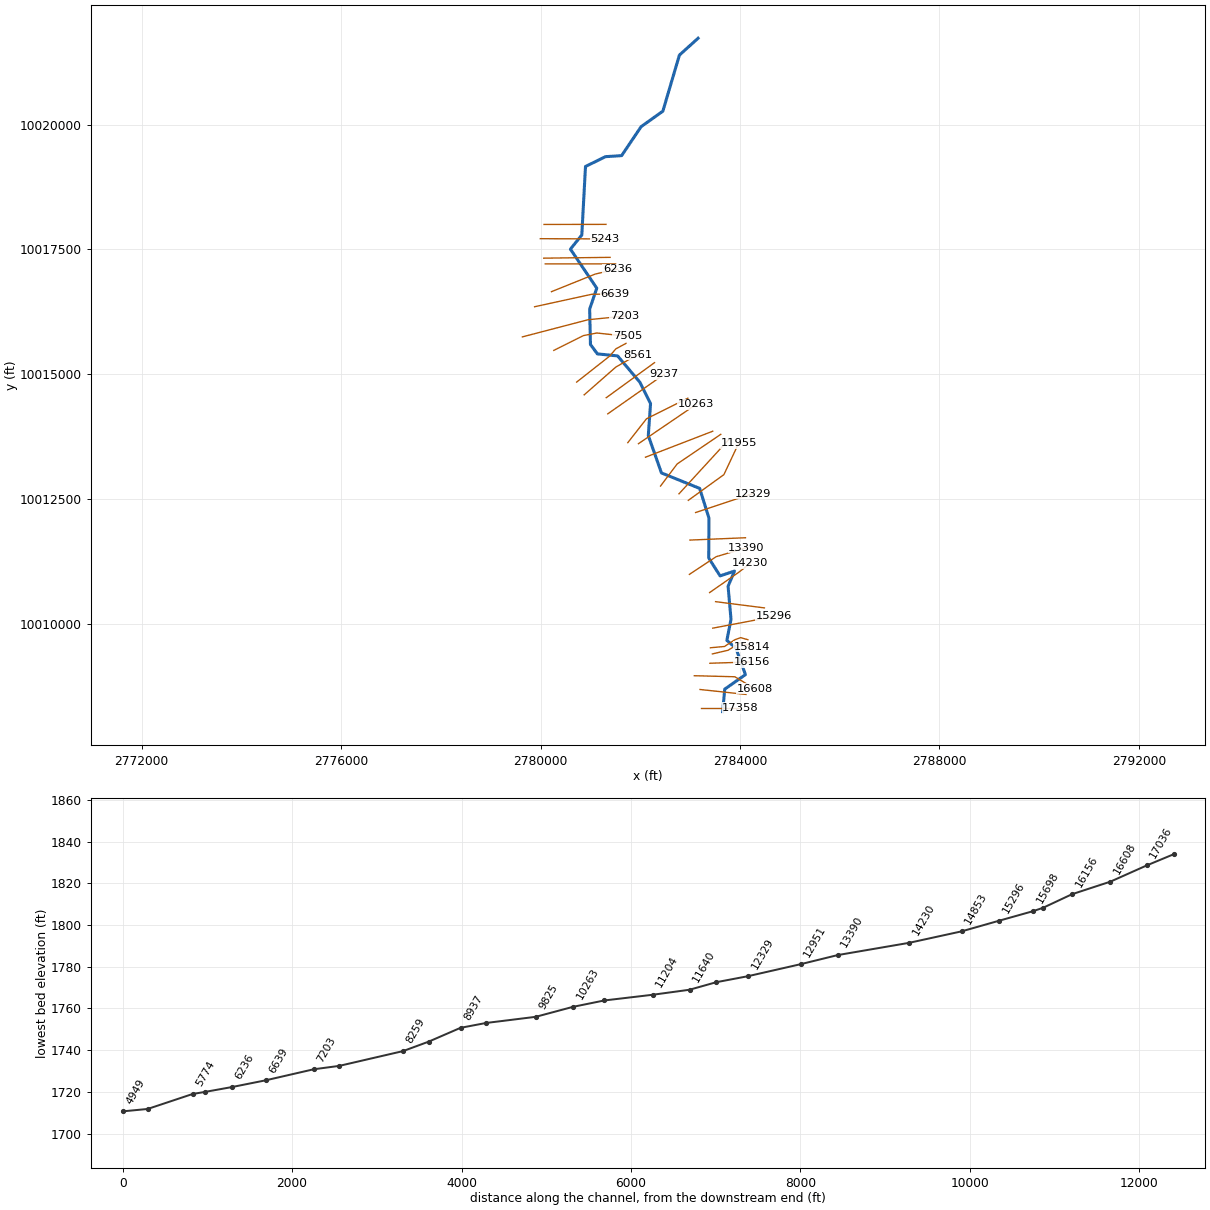
--- UNT032 IN SNOGR.prj (project) ---

Proj Title=UNT032 IN SNOGR Base Level Engineering
Current Plan=p01
Default Exp/Contr=0.3,0.1
English Units
Geom File=g01
Flow File=f01
Plan File=p01
Y Axis Title=Elevation
X Axis Title(PF)=Main Channel Distance
X Axis Title(XS)=Station
BEGIN DESCRIPTION:
UNT032 IN SNOGR
END DESCRIPTION:
DSS Export Rating Curves= 0
DSS Export Rating Curve Sorted= 0
DSS Export Volume Flow Curves= 0
DXF OffsetX= 0
DXF OffsetY= 0
DXF ScaleX= 1
DXF ScaleY= 10

--- UNT032 IN SNOGR.p01 (plan) ---

Plan Title=Multiple Run
Short Identifier=Multiple
Geom File=g01
Flow File=f01
Subcritical Flow
K Sum by GR= 0
Std Step Tol= 0.01
Critical Tol= 0.01
Num of Std Step Trials= 20
Max Error Tol= 0.3
Flow Tol Ratio= 0.001
Split Flow NTrial= 30
Split Flow Tol= 0.02
Split Flow Ratio= 0.02
Log Output Level= 0
Friction Slope Method= 1
Unsteady Friction Slope Method= 2
Unsteady Bridges Friction Slope Method= 1
Parabolic Critical Depth
Global Vel Dist=  1 , 1 , 1
Global Log Level= 0
CheckData=True
Encroach Param= -1, 0, 0, 0
BEGIN DESCRIPTION:
Multiple Run
END DESCRIPTION:

--- UNT032 IN SNOGR.f01 (steady flow) ---

Flow Title=Multiple
Number of Profiles=7
Profile Names=10-year,25-year,50-year,1pct_min,100-year,1pct_plu,500-year
River Rch & RM= UNT032 IN SNOGR,Reach-1,17358
     988    1447    1848    1729    2338    3162    3755
River Rch & RM= UNT032 IN SNOGR,Reach-1,14853
    1329    1969    2534    2384    3225    4361    5245
River Rch & RM= UNT032 IN SNOGR,Reach-1,9825
    1715    2563    3317    3134    4239    5733    6957
Boundary for River Rch & Prof#=UNT032 IN SNOGR,Reach-1,1
Up Type=0
Dn Type=3
Dn Slope=0.005
Boundary for River Rch & Prof#=UNT032 IN SNOGR,Reach-1,2
Up Type=0
Dn Type=3
Dn Slope=0.005
Boundary for River Rch & Prof#=UNT032 IN SNOGR,Reach-1,3
Up Type=0
Dn Type=3
Dn Slope=0.005
Boundary for River Rch & Prof#=UNT032 IN SNOGR,Reach-1,4
Up Type=0
Dn Type=3
Dn Slope=0.005
Boundary for River Rch & Prof#=UNT032 IN SNOGR,Reach-1,5
Up Type=0
Dn Type=3
Dn Slope=0.005
Boundary for River Rch & Prof#=UNT032 IN SNOGR,Reach-1,6
Up Type=0
Dn Type=3
Dn Slope=0.005
Boundary for River Rch & Prof#=UNT032 IN SNOGR,Reach-1,7
Up Type=0
Dn Type=3
Dn Slope=0.005

--- UNT032 IN SNOGR.g01 (geometry) ---

Geom Title=Existing Conditions
Program Version=4.10

River Reach=UNT032 IN SNOGR ,Reach-1
Reach XY= 30
      2783651.63     10008235.04      2783692.99     10008686.61
      2784108.28     10008978.17      2783916.44     10009509.35
        2783736.     10009663.74      2783818.68     10010087.12
      2783760.23     10010748.09      2783888.47     10011053.73
      2783600.16     10010956.78      2783371.96     10011315.25
      2783377.15     10012113.62      2783190.69     10012710.19
      2782423.97     10013020.99      2782160.12     10013769.42
      2782205.19     10014408.82      2781992.91      10014836.3
       2781544.9      10015366.2      2781139.97     10015407.08
      2781000.04     10015594.39      2780984.11     10016303.79
      2781126.88     10016723.98      2780598.03     10017506.64
      2780826.56     10017789.64      2780900.55     10019163.17
      2781300.94     10019359.86      2781625.55     10019381.15
      2782015.55     10019960.97      2782452.38     10020272.41
      2782783.97     10021396.17      2783158.47     10021733.73

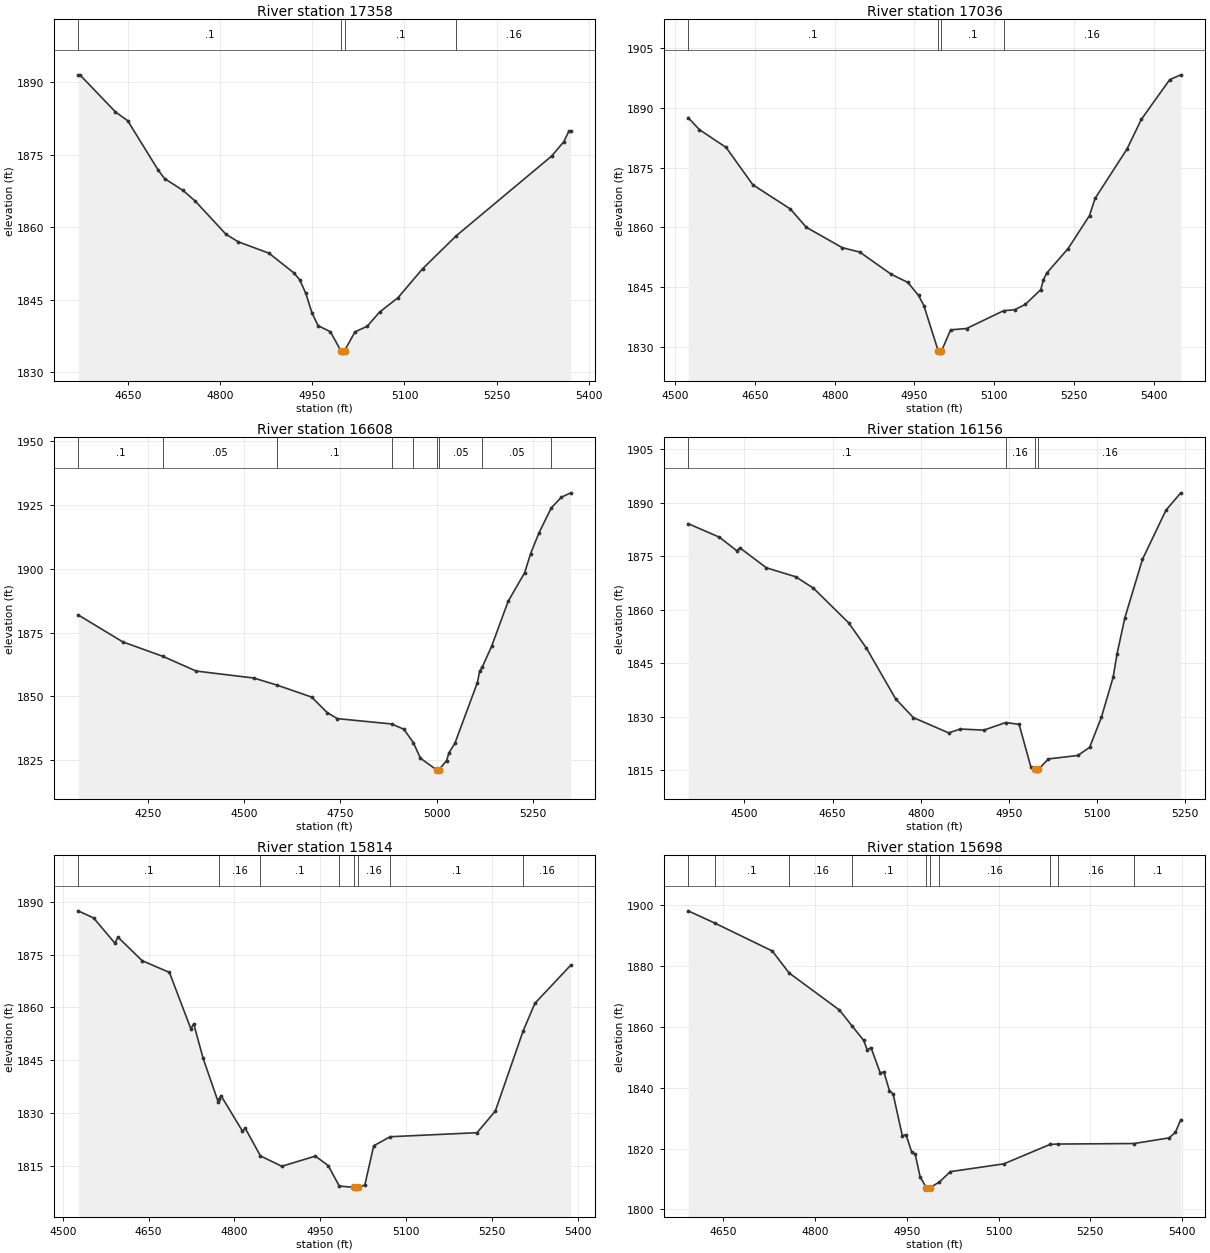
Type RM Length L Ch R = 1 ,17358   ,322,322,322
BEGIN DESCRIPTION:
UNT032 IN SNOGR 37.0
END DESCRIPTION:
XS GIS Cut Line= 2
       2783207.8     10008310.17       2784009.9     10008310.17
#Sta/Elev= 30
  4568.7 1891.56  4571.5 1891.56  4629.4 1883.89  4649.4 1882.06  4699.4 1871.77
  4709.4  1870.1  4739.4 1867.64  4759.4 1865.43  4809.4 1858.57  4829.4 1857.02
  4879.4 1854.66  4919.4 1850.64  4929.4 1849.18  4939.4 1846.33  4949.4  1842.3
  4959.4 1839.67  4979.4 1838.42  4996.4 1834.49  4999.1 1833.99  5002.4 1834.49
  5019.4 1838.38  5039.4 1839.56  5059.4 1842.47  5089.4 1845.45  5129.4 1851.43
  5184.7 1858.31  5339.4 1874.73  5359.4 1877.71  5367.6 1879.88  5370.8 1879.88
#Mann= 4 ,-1 , 0
  4568.7      .1       0  4996.4     .07       0  5002.4      .1       0
  5184.7     .16       0
Bank Sta=4996.4,5002.4
XS Rating Curve= 0 ,0
Exp/Cntr=0.3,0.1

Type RM Length L Ch R = 1 ,17036   ,428,428,428
BEGIN DESCRIPTION:
UNT032 IN SNOGR 36.0
END DESCRIPTION:
XS GIS Cut Line= 2
      2783197.37     10008679.97      2784119.28       10008581.
#Sta/Elev= 30
  4524.1 1887.47  4545.3 1884.47  4595.6 1880.01  4645.9 1870.67  4716.3 1864.64
  4746.5 1860.04  4814.3 1854.94    4847 1853.85  4906.4 1848.28  4937.6 1846.25
  4957.7 1842.99  4967.7 1840.47  4994.9 1829.06  4997.7 1828.56  5000.9 1829.06
    5018 1834.38  5048.2 1834.72  5117.7 1839.17  5138.7 1839.42  5158.8 1840.76
  5187.7 1844.44  5192.8 1846.92    5199 1848.59  5239.3 1854.73  5279.5 1862.99
  5289.9 1867.25  5349.9 1879.59    5377 1887.03  5430.4 1896.98  5451.3 1898.19
#Mann= 4 ,-1 , 0
  4524.1      .1       0  4994.9     .07       0  5000.9      .1       0
  5117.7     .16       0
Bank Sta=4994.9,5000.9
XS Rating Curve= 0 ,0
Exp/Cntr=0.3,0.1

Type RM Length L Ch R = 1 ,16608   ,452,452,452
BEGIN DESCRIPTION:
UNT032 IN SNOGR 35.0
END DESCRIPTION:
XS GIS Cut Line= 3
      2783082.81     10008956.01      2783895.29     10008935.17
      2784294.87     10008696.46
#Sta/Elev= 30
  4069.6 1881.91  4185.3 1871.36  4290.1 1865.66  4375.4 1859.96  4525.4 1857.22
  4586.5  1854.4  4675.5 1849.76  4715.5 1843.73    4742 1841.34  4882.9 1839.25
  4914.8 1837.18  4939.3 1831.94  4957.6 1825.87  4999.5  1821.3  5002.3  1820.8
  5005.5  1821.3  5025.7 1824.94  5031.5 1827.91  5047.1 1831.71  5105.5 1855.44
  5111.3 1859.89  5118.2 1861.56  5142.3  1869.6  5185.2 1887.21    5228 1898.38
  5243.6 1905.89    5265 1913.92  5297.1 1923.75  5323.4 1927.97  5347.8 1929.67
#Mann= 9 ,-1 , 0
  4069.6      .1       0  4290.1     .05       0  4586.5      .1       0
  4882.9     .16       0  4939.3     .05       0  4999.5     .04       0
  5005.5     .05       0  5118.2     .05       0  5297.1     .16       0
Bank Sta=4999.5,5005.5
XS Rating Curve= 0 ,0
Exp/Cntr=0.3,0.1

Type RM Length L Ch R = 1 ,16156   ,342,342,342
BEGIN DESCRIPTION:
UNT032 IN SNOGR 34.0
END DESCRIPTION:
XS GIS Cut Line= 2
      2783395.32     10009206.01      2784233.61     10009232.04
#Sta/Elev= 30
  4404.1 1884.12  4457.3 1880.33  4487.1 1876.51  4492.1 1877.35  4537.3 1871.75
  4587.3 1869.24  4617.4 1866.04  4677.4 1856.33  4707.4  1849.3  4757.4 1835.02
  4787.4  1829.8  4847.5 1825.51  4867.5 1826.59  4907.5 1826.28  4944.7 1828.41
  4967.5 1827.89  4987.5    1816  4994.5 1815.29  4997.3 1814.79  5000.5 1815.29
  5017.5 1818.21  5067.6 1819.18  5087.6 1821.46  5107.6 1829.85  5127.6 1841.07
  5134.4 1847.73  5147.6 1857.76  5177.6 1874.15  5217.6  1887.9  5242.8 1892.76
#Mann= 4 ,-1 , 0
  4404.1      .1       0  4944.7     .16       0  4994.5     .07       0
  5000.5     .16       0
Bank Sta=4994.5,5000.5
XS Rating Curve= 0 ,0
Exp/Cntr=0.3,0.1

Type RM Length L Ch R = 1 ,15814   ,116,116,116
BEGIN DESCRIPTION:
UNT032 IN SNOGR 333.0
END DESCRIPTION:
XS GIS Cut Line= 4
      2783445.84     10009392.91      2783759.87     10009466.42
      2784006.62     10009616.87      2784243.89     10009539.46
#Sta/Elev= 30
    4527 1887.47    4554 1885.44  4591.3 1878.25  4596.4 1880.01  4638.9 1873.27
  4686.5 1869.95  4723.9 1853.93    4729  1855.3  4745.4  1845.5  4771.5 1833.21
    4774 1834.04  4776.6  1834.9    4814 1824.84  4819.1 1825.58  4845.7 1817.72
    4883 1814.78  4941.6 1817.68  4964.2 1814.96  4983.4 1809.15  5009.7 1808.78
  5012.4 1808.28  5015.7 1808.78  5028.1 1809.45  5043.6 1820.61  5072.4 1823.19
  5224.3 1824.34  5256.2  1830.5  5304.5 1853.16  5325.3 1861.14  5388.1 1872.02
#Mann= 8 ,-1 , 0
    4527      .1       0    4774     .16       0  4845.7      .1       0
  4983.4     .16       0  5009.7     .07       0  5015.7     .16       0
  5072.4      .1       0  5304.5     .16       0
Bank Sta=5009.7,5015.7
XS Rating Curve= 0 ,0
Exp/Cntr=0.3,0.1

Type RM Length L Ch R = 1 ,15698   ,402,402,402
BEGIN DESCRIPTION:
UNT032 IN SNOGR 33.0
END DESCRIPTION:
XS GIS Cut Line= 5
      2783405.88     10009516.17      2783688.91     10009542.22
      2783893.77      10009675.9      2784011.83      10009719.3
      2784157.01     10009678.24
#Sta/Elev= 30
  4592.4 1897.97  4635.6 1893.98    4730 1884.79  4757.3 1877.61  4839.8 1865.42
  4859.9 1860.33  4879.3  1855.5  4885.3 1852.31  4891.3 1853.13  4906.4 1844.84
  4912.4 1845.11  4921.5    1839  4927.5 1837.91  4942.6 1824.18  4948.6 1824.56
  4957.7 1818.96  4963.7 1818.09  4971.6 1810.75  4981.8 1807.18  4984.5 1806.68
  4987.8 1807.18  5003.1 1808.99    5021 1812.41  5108.5 1814.97  5184.3 1821.36
  5197.4 1821.47  5321.4 1821.64  5378.6 1823.48    5389 1825.27  5397.9 1829.48
#Mann= 10 ,-1 , 0
  4592.4     .16       0  4635.6      .1       0  4757.3     .16       0
  4859.9      .1       0  4981.8     .07       0  4987.8      .1       0
  5003.1     .16       0  5184.3      .1       0  5197.4     .16       0
  5321.4      .1       0
Bank Sta=4981.8,4987.8
XS Rating Curve= 0 ,0
Exp/Cntr=0.3,0.1

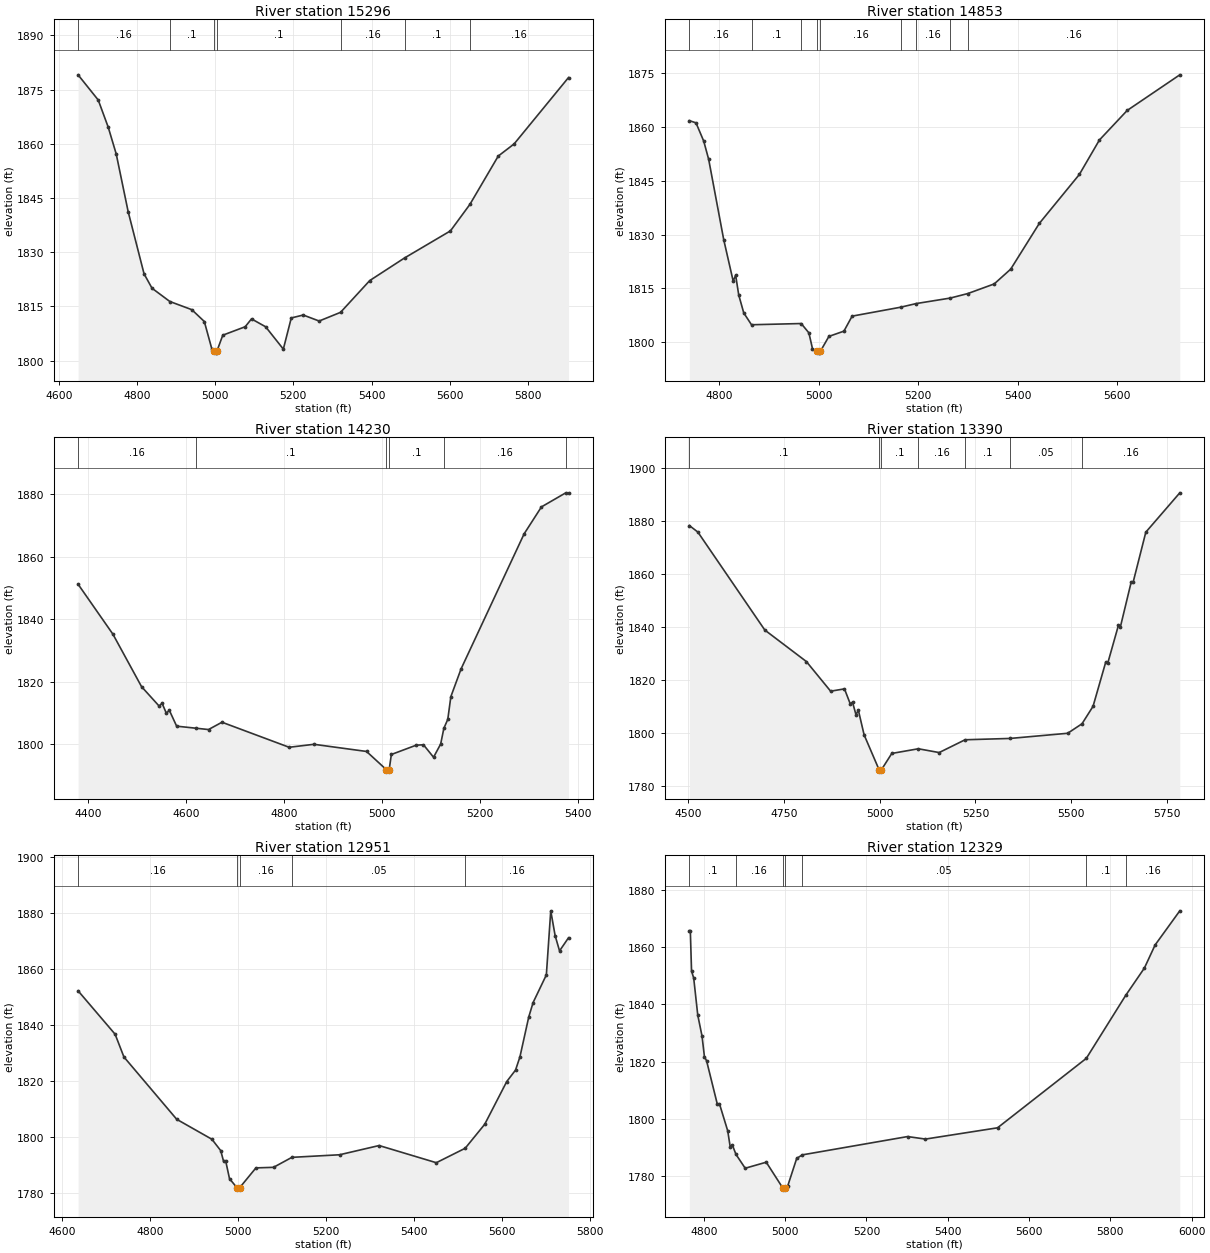
Type RM Length L Ch R = 1 ,15296   ,443,443,443
BEGIN DESCRIPTION:
UNT032 IN SNOGR 32.0
END DESCRIPTION:
XS GIS Cut Line= 2
       2783452.6     10009909.14      2784685.18     10010143.17
#Sta/Elev= 30
  4649.3 1879.08  4700.9 1872.11  4726.5 1864.58  4746.9 1857.19  4777.4 1841.25
  4818.1 1824.03  4838.5 1820.04  4884.1 1816.37  4940.3 1814.11  4972.3 1810.83
  4991.2 1803.36  4998.3 1802.59  5001.1 1802.09  5004.3 1802.59  5019.5 1807.05
  5076.8 1809.39    5093 1811.56  5129.1 1809.38  5174.4  1803.2  5194.7 1811.82
  5225.3 1812.63    5266 1810.97  5320.7 1813.37  5395.4 1822.16  5484.5 1828.42
  5601.9 1835.91  5651.6 1843.23  5724.2 1856.61  5764.7 1859.96  5903.9 1878.33
#Mann= 7 ,-1 , 0
  4649.3     .16       0  4884.1      .1       0  4998.3     .07       0
  5004.3      .1       0  5320.7     .16       0  5484.5      .1       0
  5651.6     .16       0
Bank Sta=4998.3,5004.3
XS Rating Curve= 0 ,0
Exp/Cntr=0.3,0.1

Type RM Length L Ch R = 1 ,14853   ,623,623,623
BEGIN DESCRIPTION:
UNT032 IN SNOGR 31.0
END DESCRIPTION:
XS GIS Cut Line= 2
      2783509.84     10010440.39      2784488.99     10010315.39
#Sta/Elev= 30
  4739.4 1861.71  4752.8  1861.1  4768.3 1856.02  4778.3 1850.93  4808.6 1828.56
  4827.6 1817.04  4832.6 1818.66  4838.8 1813.16  4848.9 1808.17  4864.5 1804.88
  4964.5 1805.22    4980 1802.62  4987.2 1798.24  4997.1 1797.48  4999.9 1796.98
  5003.1 1797.48  5020.3 1801.64  5050.5  1803.1    5067 1807.28  5164.5 1809.76
    5196 1810.78  5264.5 1812.31  5299.9 1813.57    5353 1816.25  5386.2 1820.37
  5443.7 1833.09  5524.3 1846.72  5564.7 1856.32  5620.6 1864.55  5726.5 1874.47
#Mann= 9 ,-1 , 0
  4739.4     .16       0  4864.5      .1       0  4964.5     .16       0
  4997.1     .07       0  5003.1     .16       0  5164.5      .1       0
    5196     .16       0  5264.5      .1       0  5299.9     .16       0
Bank Sta=4997.1,5003.1
XS Rating Curve= 0 ,0
Exp/Cntr=0.3,0.1

Type RM Length L Ch R = 1 ,14230   ,840,840,840
BEGIN DESCRIPTION:
UNT032 IN SNOGR 30.0
END DESCRIPTION:
XS GIS Cut Line= 3
       2783390.1     10010622.69      2783973.41     10011028.92
      2784202.62     10011206.04
#Sta/Elev= 30
  4379.9 1851.24    4451 1835.25  4509.4 1818.47  4545.2 1812.27  4551.3 1813.15
    4560 1809.96  4566.1  1810.9    4581 1805.83  4620.1 1805.18    4646 1804.75
  4673.5 1807.09  4810.5 1799.08  4861.1 1800.03  4968.4 1797.74  5008.6 1791.95
  5011.3 1791.45  5014.6 1791.95    5019 1796.77  5069.7 1799.75  5084.5 1799.88
  5105.1 1795.89  5119.6 1800.12  5126.1 1805.14  5134.1    1808  5140.4 1815.28
  5161.2 1824.14  5289.8 1867.33  5325.2 1875.96  5374.8 1880.46  5380.4 1880.46
#Mann= 6 ,-1 , 0
  4379.9     .16       0  4620.1      .1       0  5008.6     .07       0
  5014.6      .1       0  5126.1     .16       0  5374.8      .1       0
Bank Sta=5008.6,5014.6
XS Rating Curve= 0 ,0
Exp/Cntr=0.3,0.1

Type RM Length L Ch R = 1 ,13390   ,439,439,439
BEGIN DESCRIPTION:
UNT032 IN SNOGR 29.0
END DESCRIPTION:
XS GIS Cut Line= 3
      2782983.83     10010987.26      2783520.29     10011341.42
      2784129.68     10011523.72
#Sta/Elev= 30
    4504 1878.32  4526.2 1875.85  4700.8 1838.86  4809.1 1826.98  4872.4 1815.78
  4908.5 1816.65  4923.5 1811.02  4929.5 1811.64  4938.6 1806.85  4944.6 1808.66
  4959.7  1799.3  4998.8  1786.1  5001.5  1785.6  5004.8  1786.1  5031.9 1792.28
  5101.1 1794.04  5155.4 1792.61    5223 1797.44  5340.4 1797.94  5490.5 1799.89
  5527.9 1803.48  5556.7 1810.07  5589.8 1826.78    5595 1826.35  5622.9 1840.65
  5628.1 1840.12    5656 1856.88  5661.2 1856.91  5694.3 1875.82  5782.9 1890.67
#Mann= 7 ,-1 , 0
    4504      .1       0  4998.8     .07       0  5004.8      .1       0
  5101.1     .16       0    5223      .1       0  5340.4     .05       0
  5527.9     .16       0
Bank Sta=4998.8,5004.8
XS Rating Curve= 0 ,0
Exp/Cntr=0.3,0.1

Type RM Length L Ch R = 1 ,12951   ,622,622,622
BEGIN DESCRIPTION:
UNT032 IN SNOGR 28.0
END DESCRIPTION:
XS GIS Cut Line= 2
      2782994.24     10011674.76      2784108.85     10011721.63
#Sta/Elev= 30
  4635.5 1852.11  4719.8 1836.58  4739.8 1828.46  4859.9 1806.18    4940 1799.04
    4960 1794.98  4966.5 1791.15  4971.5 1791.14    4980 1784.94    4997 1781.72
  4999.8 1781.22    5003 1781.72  5040.1 1788.81  5080.1 1789.01  5121.9 1792.58
  5230.3  1793.5  5320.3  1796.8  5450.4 1790.66  5516.1 1795.83  5560.5  1804.4
  5610.6 1819.67  5630.6 1823.77  5640.6 1828.49  5660.6 1842.72  5670.6 1847.92
  5700.7 1857.79  5710.7 1880.69  5720.7  1871.8  5730.7 1866.37  5751.1 1871.06
#Mann= 5 ,-1 , 0
  4635.5     .16       0    4997     .07       0    5003     .16       0
  5121.9     .05       0  5516.1     .16       0
Bank Sta=4997,5003
XS Rating Curve= 0 ,0
Exp/Cntr=0.3,0.1

Type RM Length L Ch R = 1 ,12329   ,374,374,374
BEGIN DESCRIPTION:
UNT032 IN SNOGR 27.0
END DESCRIPTION:
XS GIS Cut Line= 2
      2783108.86     10012226.85      2784254.06     10012606.85
#Sta/Elev= 30
  4764.3 1865.76  4766.7 1865.76  4769.7 1851.68    4775 1849.23    4785 1836.26
  4795.5 1828.94  4801.4 1821.74  4806.7 1820.31  4833.1 1805.15  4838.3 1805.31
  4858.7 1795.83  4864.8 1790.24    4870 1790.92    4879  1787.6  4901.7 1782.76
  4953.5 1784.87  4993.7 1775.96  4996.5 1775.46  4999.7 1775.96  5006.2 1776.52
  5028.4 1786.19  5042.1 1787.43  5301.2 1793.83  5345.2 1792.95  5522.5 1796.89
  5740.9 1821.16  5837.7 1843.15  5883.8 1852.72  5910.2  1860.8  5970.9 1872.72
#Mann= 7 ,-1 , 0
  4764.3      .1       0    4879     .16       0  4993.7     .07       0
  4999.7     .16       0  5042.1     .05       0  5740.9      .1       0
  5837.7     .16       0
Bank Sta=4993.7,4999.7
XS Rating Curve= 0 ,0
Exp/Cntr=0.3,0.1

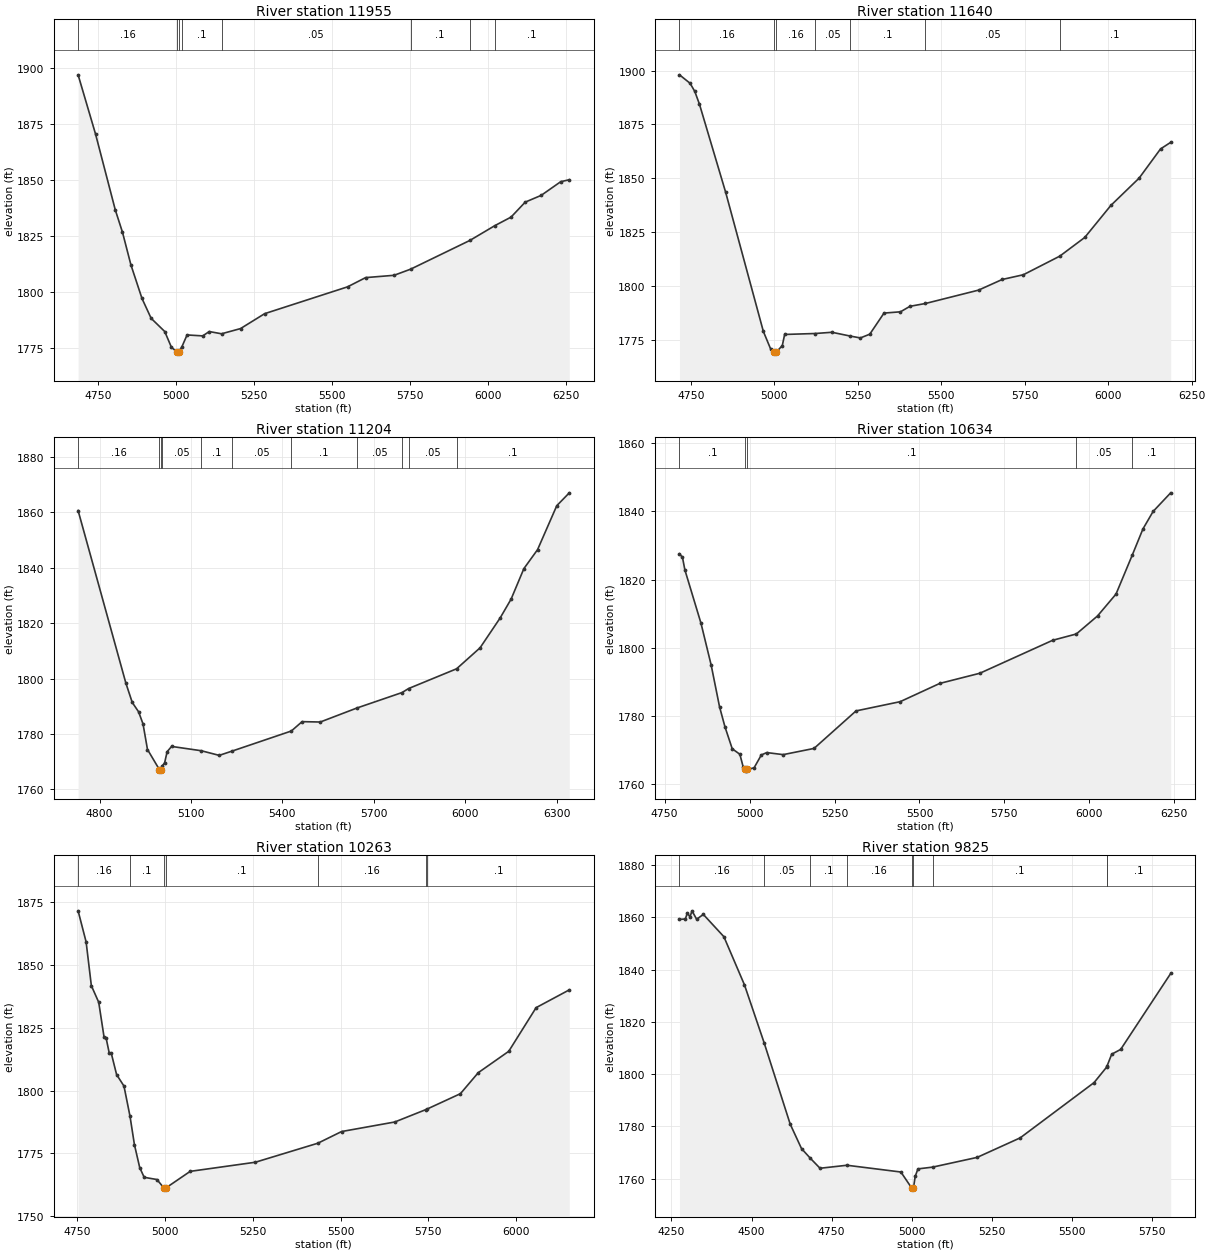
Type RM Length L Ch R = 1 ,11955   ,315,315,315
BEGIN DESCRIPTION:
UNT032 IN SNOGR 26.0
END DESCRIPTION:
XS GIS Cut Line= 3
        2782963.     10012471.64      2783676.54     10012987.26
      2783973.42     10013617.49
#Sta/Elev= 30
  4685.2 1896.74  4741.3 1870.27  4804.5 1836.52  4827.7  1826.5  4854.7 1811.98
  4890.3 1796.97  4919.7 1788.11  4963.4 1782.21  4984.7 1775.22  5002.6 1773.08
  5005.3 1772.58  5008.6 1773.08  5018.8 1775.53    5035 1780.69  5085.3 1780.27
  5106.2 1782.21  5145.7 1781.21  5206.7 1783.53  5284.2 1790.19  5550.2 1802.15
  5608.3 1806.27  5699.5  1807.3  5752.5 1810.02    5943 1822.86  6023.3 1829.47
  6075.1 1833.26  6120.7 1839.95  6171.8 1842.95  6234.6 1849.06  6262.2 1849.94
#Mann= 8 ,-1 , 0
  4685.2     .16       0  5002.6     .07       0  5008.6     .16       0
  5018.8      .1       0  5145.7     .05       0  5752.5      .1       0
    5943     .16       0  6023.3      .1       0
Bank Sta=5002.6,5008.6
XS Rating Curve= 0 ,0
Exp/Cntr=0.3,0.1

Type RM Length L Ch R = 1 ,11640   ,436,436,436
BEGIN DESCRIPTION:
UNT032 IN SNOGR 25.0
END DESCRIPTION:
XS GIS Cut Line= 2
      2782775.47     10012601.82      2783770.27     10013685.16
#Sta/Elev= 30
  4716.2 1898.02  4747.8 1894.12    4762 1890.34  4776.1 1884.35  4854.4 1843.59
  4967.3 1779.05  4988.8 1771.03    5000 1769.47  5002.8 1768.97    5006 1769.47
    5024 1772.43  5031.1 1777.63  5122.7 1778.07  5172.6 1778.64    5226 1776.93
  5257.7 1776.01    5286 1777.75  5328.6 1787.54  5377.9 1788.13  5406.3 1790.68
  5452.8 1791.99  5611.6 1798.18  5682.5 1803.12    5746 1805.32    5855 1813.95
  5929.7 1822.61    6008 1837.48  6092.5 1850.12  6156.6 1863.66    6187 1866.71
#Mann= 7 ,-1 , 0
  4716.2     .16       0    5000     .07       0    5006     .16       0
  5122.7     .05       0    5226      .1       0  5452.8     .05       0
    5855      .1       0
Bank Sta=5000,5006
XS Rating Curve= 0 ,0
Exp/Cntr=0.3,0.1

Type RM Length L Ch R = 1 ,11204   ,570,570,570
BEGIN DESCRIPTION:
UNT032 IN SNOGR 24.0
END DESCRIPTION:
XS GIS Cut Line= 3
      2782405.69     10012758.07      2782739.04      10013200.8
      2783613.77     10013794.37
#Sta/Elev= 30
  4729.8 1860.67  4886.6 1798.31  4907.4 1791.37  4928.3 1787.97  4942.8 1783.59
  4957.4 1774.37  4996.8 1767.06  4999.5 1766.56  5002.8 1767.06  5006.3 1768.51
  5013.6 1769.56  5021.9 1773.59  5036.5 1775.48  5133.6 1773.93  5192.7 1772.25
  5234.5 1773.78  5429.3 1781.05  5464.6 1784.43  5524.3  1784.3    5644 1789.34
  5792.5 1794.94  5813.8 1796.38  5971.4 1803.52  6048.4  1811.1  6114.2 1821.87
  6150.2 1828.69  6192.1  1839.7    6237 1846.55    6300 1862.42  6341.1 1867.07
#Mann= 11 ,-1 , 0
  4729.8     .16       0  4996.8     .07       0  5002.8     .16       0
  5006.3     .05       0  5133.6      .1       0  5234.5     .05       0
  5429.3      .1       0    5644     .05       0  5792.5      .1       0
  5813.8     .05       0  5971.4      .1       0
Bank Sta=4996.8,5002.8
XS Rating Curve= 0 ,0
Exp/Cntr=0.3,0.1

Type RM Length L Ch R = 1 ,10634   ,371,371,371
BEGIN DESCRIPTION:
UNT032 IN SNOGR 23.0
END DESCRIPTION:
XS GIS Cut Line= 2
      2782103.63     10013336.22      2783452.58     10013857.05
#Sta/Elev= 30
  4793.6 1827.59  4802.4 1826.54  4809.5 1822.85  4856.9 1807.21  4886.9 1794.93
  4911.5 1782.71  4927.4 1776.85  4948.9 1770.38  4971.4 1768.77    4981  1765.1
  4987.6 1764.33  4990.4 1763.83  4993.6 1764.33  5013.2  1764.8  5034.6 1768.58
  5050.6 1769.27  5098.9 1768.67  5189.7 1770.49  5313.3 1781.49  5443.2  1784.2
  5559.9 1789.56  5677.8 1792.54  5892.2 1802.21  5961.9 1804.06  6024.2 1809.34
  6078.7 1815.77  6126.3 1827.15  6157.9 1834.86  6187.8 1839.99  6239.6 1845.46
#Mann= 5 ,-1 , 0
  4793.6      .1       0  4987.6     .07       0  4993.6      .1       0
  5961.9     .05       0  6126.3      .1       0
Bank Sta=4987.6,4993.6
XS Rating Curve= 0 ,0
Exp/Cntr=0.3,0.1

Type RM Length L Ch R = 1 ,10263   ,438,438,438
BEGIN DESCRIPTION:
UNT032 IN SNOGR 22.0
END DESCRIPTION:
XS GIS Cut Line= 2
      2781962.97     10013607.03      2783119.24     10014393.51
#Sta/Elev= 30
  4752.8 1871.68  4775.6  1859.3  4790.5 1841.86  4811.5 1835.23  4826.5 1821.54
  4832.5    1821  4841.4 1815.03  4847.4 1814.82  4862.4 1806.41  4883.4 1801.83
  4900.6 1789.79  4913.2 1778.45  4928.2 1769.35  4940.9 1765.47  4977.1 1764.59
    4997 1761.26  4999.8 1760.76    5003 1761.26  5071.9 1767.84  5257.5 1771.48
  5435.4 1779.06  5502.9 1783.71  5654.4 1787.52  5742.5 1792.44  5747.2 1792.73
  5841.2  1798.8    5892 1807.17  5978.8 1815.69  6056.7 1833.09  6151.2 1840.18
#Mann= 7 ,-1 , 0
  4752.8     .16       0  4900.6      .1       0    4997     .07       0
    5003      .1       0  5435.4     .16       0  5742.5     .05       0
  5747.2      .1       0
Bank Sta=4997,5003
XS Rating Curve= 0 ,0
Exp/Cntr=0.3,0.1

Type RM Length L Ch R = 1 ,9825    ,588,588,588
BEGIN DESCRIPTION:
UNT032 IN SNOGR 21.0
END DESCRIPTION:
XS GIS Cut Line= 3
      2781749.43     10013627.85      2782124.46     10014107.05
      2782952.57      10014518.5
#Sta/Elev= 30
  4275.2 1859.26  4293.5 1859.41  4299.8 1861.73    4308  1860.2  4314.3 1862.54
  4328.8 1859.31  4349.6 1861.17  4413.8 1852.63    4478  1834.2  4539.4 1812.03
  4620.8 1780.87  4656.1 1771.51    4684 1767.76  4713.9 1763.98    4798 1765.13
  4966.3 1762.54  4999.6 1756.49  5002.4 1755.99  5005.6 1756.49    5011 1760.89
  5019.5 1763.74  5065.2 1764.41  5204.3 1768.14  5338.7 1775.62  5569.3 1796.78
    5609 1802.78    5610 1803.19  5624.3 1807.65  5652.3 1809.48  5808.4 1838.55
#Mann= 9 ,-1 , 0
  4275.2     .16       0  4539.4     .05       0    4684      .1       0
    4798     .16       0  4999.6     .07       0  5005.6     .16       0
  5065.2      .1       0    5609     .05       0    5610      .1       0
Bank Sta=4999.6,5005.6
XS Rating Curve= 0 ,0
Exp/Cntr=0.3,0.1

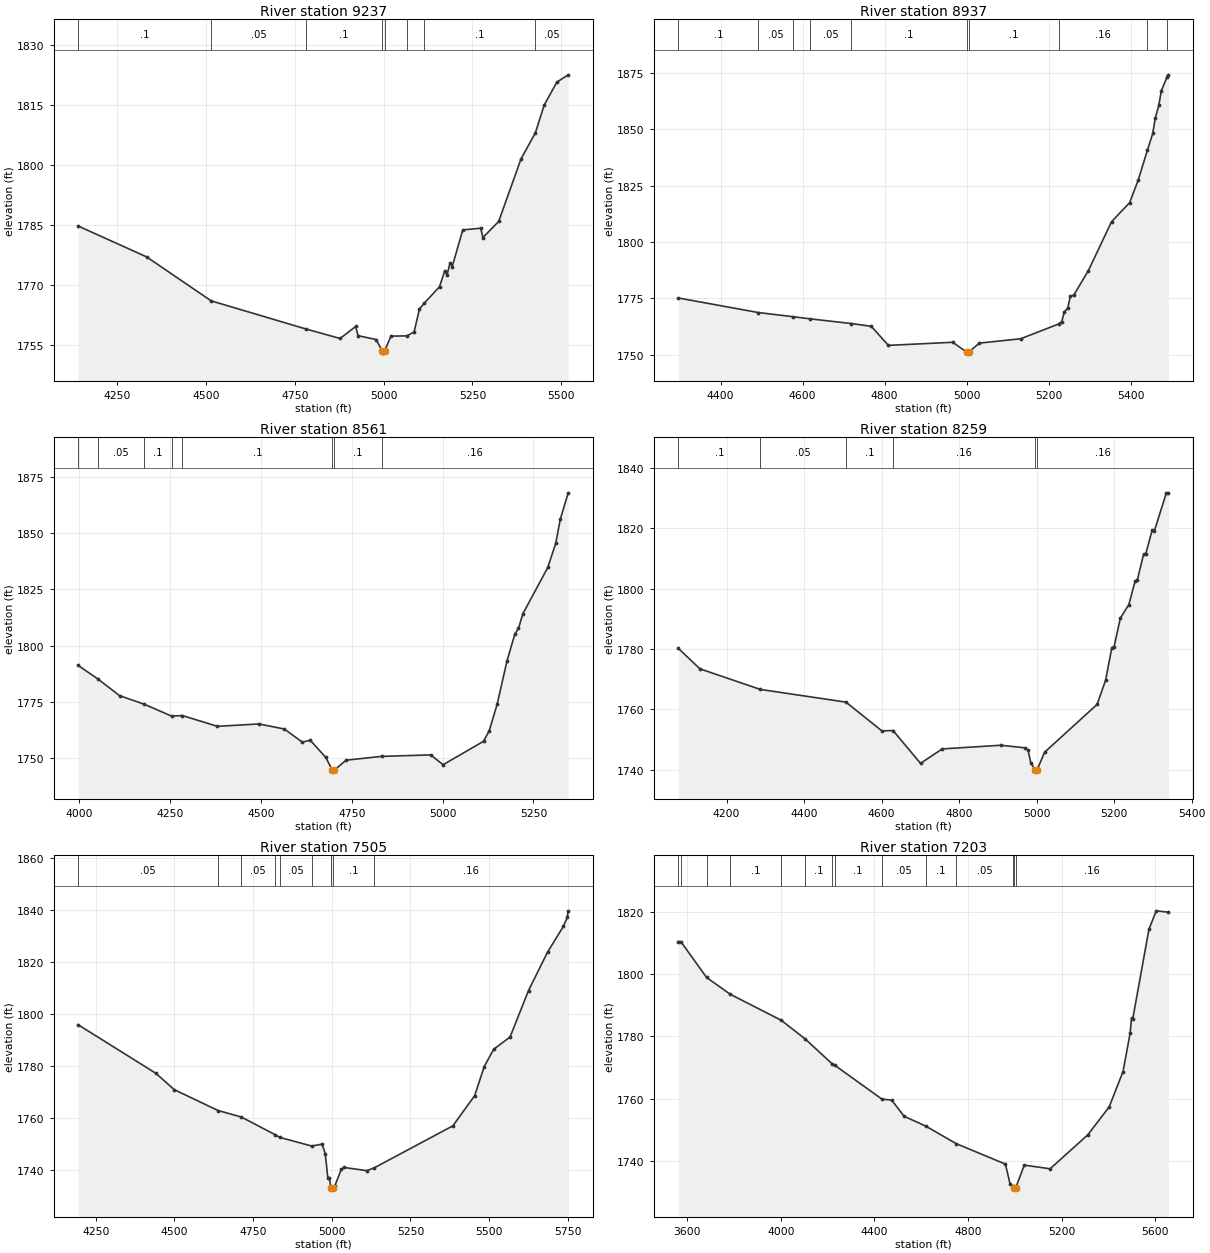
Type RM Length L Ch R = 1 ,9237    ,300,300,300
BEGIN DESCRIPTION:
UNT032 IN SNOGR 20.0
END DESCRIPTION:
XS GIS Cut Line= 2
       2781348.4       10014206.      2782478.61     10014997.67
#Sta/Elev= 30
  4139.6 1784.84  4332.5 1777.11  4514.5  1766.1  4780.7 1759.08  4877.4 1756.69
  4921.1  1759.7    4928 1757.39  4978.5 1756.43  4996.4 1753.53  4999.2 1753.03
  5002.4 1753.53  5020.4 1757.28  5065.2 1757.35  5085.7 1758.34  5100.6 1764.06
  5113.9 1765.49  5157.2 1769.65  5172.1 1773.68  5178.2 1772.53  5186.9 1775.66
    5193 1774.69  5222.6 1783.86  5273.2 1784.28  5279.3 1781.95  5323.7 1785.97
  5386.5 1801.59  5427.2 1808.18  5451.9  1815.1  5487.6 1820.83  5519.5 1822.65
#Mann= 8 ,-1 , 0
  4139.6      .1       0  4514.5     .05       0  4780.7      .1       0
  4996.4     .07       0  5002.4      .1       0  5065.2     .16       0
  5113.9      .1       0  5427.2     .05       0
Bank Sta=4996.4,5002.4
XS Rating Curve= 0 ,0
Exp/Cntr=0.3,0.1

Type RM Length L Ch R = 1 ,8937    ,376,376,376
BEGIN DESCRIPTION:
UNT032 IN SNOGR 19.0
END DESCRIPTION:
XS GIS Cut Line= 2
      2781317.17     10014528.93      2782284.68     10015231.16
#Sta/Elev= 30
  4296.8 1775.19  4492.1 1768.73    4577 1766.87  4617.2 1765.96  4718.6 1763.85
  4767.5 1762.61  4809.2 1754.15  4966.1 1755.53  4999.7 1751.21  5002.5 1750.71
  5005.7 1751.21  5031.1 1755.17  5131.6 1757.08  5224.4 1763.64  5232.1 1764.73
  5238.2 1769.05  5246.7 1770.74  5252.9 1775.96  5261.4  1776.5    5297 1787.39
  5353.4 1809.05  5397.5 1817.51  5418.4  1827.5  5440.9 1840.82  5453.9 1848.23
  5460.1 1855.04  5468.6 1860.66  5474.8 1867.11  5489.1 1873.49  5492.3 1874.27
#Mann= 10 ,-1 , 0
  4296.8      .1       0  4492.1     .05       0    4577      .1       0
  4617.2     .05       0  4718.6      .1       0  4999.7     .07       0
  5005.7      .1       0  5224.4     .16       0  5440.9      .1       0
  5489.1     .05       0
Bank Sta=4999.7,5005.7
XS Rating Curve= 0 ,0
Exp/Cntr=0.3,0.1

Type RM Length L Ch R = 1 ,8561    ,302,302,302
BEGIN DESCRIPTION:
UNT032 IN SNOGR 18.0
END DESCRIPTION:
XS GIS Cut Line= 3
      2780874.43     10014586.19      2781509.87     10015143.51
      2781947.37     10015393.51
#Sta/Elev= 30
  3996.5 1791.17  4051.3 1785.09  4110.7 1777.69  4178.6 1773.87  4253.8  1768.6
  4283.7 1768.82  4380.2 1764.03    4494 1765.09  4564.3 1762.84  4613.7 1756.98
  4635.5 1757.84  4678.2 1750.23  4696.1 1744.59  4698.8 1744.09  4702.1 1744.59
  4734.2 1748.96  4831.9 1750.65  4966.8 1751.31  5001.3 1746.95  5112.5 1757.37
    5128    1762  5149.9 1773.81  5177.3 1793.32  5198.9 1805.17  5208.7  1807.6
  5220.5 1814.06  5289.3 1834.74  5311.2 1845.49  5323.8 1856.27  5345.6 1867.97
#Mann= 8 ,-1 , 0
  3996.5      .1       0  4051.3     .05       0  4178.6      .1       0
  4253.8     .05       0  4283.7      .1       0  4696.1     .07       0
  4702.1      .1       0  4831.9     .16       0
Bank Sta=4696.1,4702.1
XS Rating Curve= 0 ,0
Exp/Cntr=0.3,0.1

Type RM Length L Ch R = 1 ,8259    ,754,754,754
BEGIN DESCRIPTION:
UNT032 IN SNOGR 17.0
END DESCRIPTION:
XS GIS Cut Line= 4
       2780723.4     10014841.42      2781384.87     10015362.26
      2781509.87     10015508.09      2781713.01     10015617.47
#Sta/Elev= 30
  4075.5 1780.25  4131.2 1773.46  4287.1 1766.63  4508.1 1762.42    4601 1752.87
  4629.5 1753.02  4700.4 1742.14  4756.5 1746.92  4907.3 1748.13  4971.1 1747.27
  4977.7 1746.56  4985.2 1742.26  4995.5 1740.06  4998.3 1739.56  5001.5 1740.06
  5020.5 1745.81    5156 1761.66  5177.9 1769.65  5194.1  1780.5  5199.8 1780.75
    5216 1790.26  5237.9 1794.74  5254.2 1802.55  5259.9 1802.95  5276.1 1811.48
  5281.8 1811.66    5298 1819.34  5303.7 1819.11  5334.8 1831.77  5340.2 1831.77
#Mann= 6 ,-1 , 0
  4075.5      .1       0  4287.1     .05       0  4508.1      .1       0
  4629.5     .16       0  4995.5     .07       0  5001.5     .16       0
Bank Sta=4995.5,5001.5
XS Rating Curve= 0 ,0
Exp/Cntr=0.3,0.1

Type RM Length L Ch R = 1 ,7505    ,302,302,302
BEGIN DESCRIPTION:
UNT032 IN SNOGR 16.0
END DESCRIPTION:
XS GIS Cut Line= 4
      2780265.05     10015476.83      2780858.83     10015773.72
      2781129.66      10015825.8      2781743.89     10015758.13
#Sta/Elev= 30
  4193.9 1795.84  4441.1 1777.11  4499.6  1770.8  4638.6 1762.76  4712.7 1760.26
  4819.5 1753.48  4834.1 1752.43  4936.5 1749.06  4969.4 1749.81  4979.6 1746.07
  4987.5 1736.84  4992.5 1736.89    4997 1732.96  4999.7 1732.46    5003 1732.96
  5010.1 1733.81  5030.5  1740.1  5039.4  1740.8    5112 1739.58  5134.8 1740.65
  5384.8 1756.84  5454.3  1768.5  5484.5  1779.7  5514.7 1786.37  5566.7  1791.1
  5625.3 1809.01  5685.7 1823.78    5736 1833.71  5748.5 1837.26  5751.5 1839.72
#Mann= 9 ,-1 , 0
  4193.9     .05       0  4638.6      .1       0  4712.7     .05       0
  4819.5      .1       0  4834.1     .05       0  4936.5      .1       0
    4997     .07       0    5003      .1       0  5134.8     .16       0
Bank Sta=4997,5003
XS Rating Curve= 0 ,0
Exp/Cntr=0.3,0.1

Type RM Length L Ch R = 1 ,7203    ,564,564,564
BEGIN DESCRIPTION:
UNT032 IN SNOGR 15.0
END DESCRIPTION:
XS GIS Cut Line= 3
      2779634.85     10015747.67      2780952.58     10016091.42
      2781681.71     10016164.34
#Sta/Elev= 30
  3562.4 1810.53  3573.5 1810.49  3683.3 1798.96  3784.1 1793.57  4002.4 1785.18
  4104.2 1779.19  4220.2 1771.14  4229.9 1770.77  4432.7 1759.79  4474.1  1759.5
  4527.3 1754.28  4619.8 1751.12  4750.2 1745.46  4960.3 1738.88  4980.4 1732.38
  4992.4 1731.81  4998.6 1731.33  5001.3 1730.83  5004.6 1731.33  5040.7 1738.56
  5151.2 1737.38    5312  1748.3  5403.6  1757.3  5462.8 1768.69  5492.9 1780.94
  5499.1 1785.93  5504.1 1785.55  5573.3 1814.42  5604.6 1820.42    5657 1819.96
#Mann= 14 ,-1 , 0
  3562.4     .05       0  3573.5      .1       0  3683.3     .16       0
  3784.1      .1       0  4002.4     .05       0  4104.2      .1       0
  4220.2     .05       0  4229.9      .1       0  4432.7     .05       0
  4619.8      .1       0  4750.2     .05       0  4992.4     .16       0
  4998.6     .07       0  5004.6     .16       0
Bank Sta=4998.6,5004.6
XS Rating Curve= 0 ,0
Exp/Cntr=0.3,0.1

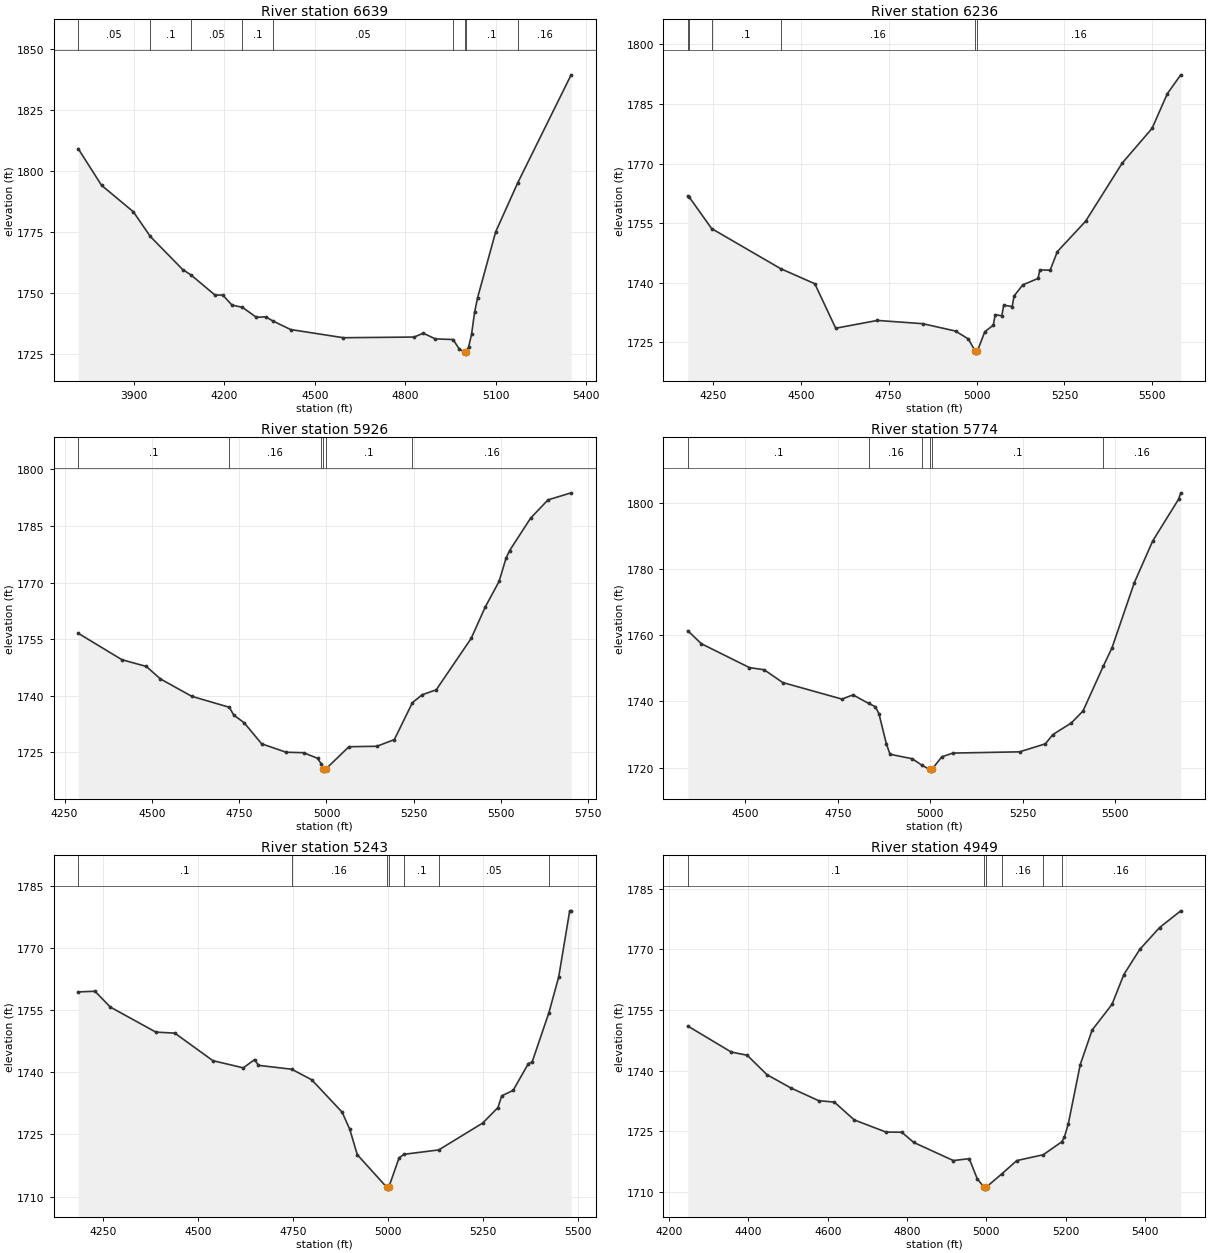
Type RM Length L Ch R = 1 ,6639    ,403,403,403
BEGIN DESCRIPTION:
UNT032 IN SNOGR 14.0
END DESCRIPTION:
XS GIS Cut Line= 3
      2779879.62     10016351.83       2781025.5     10016601.84
      2781489.03     10016607.05
#Sta/Elev= 30
  3714.5 1809.35  3791.9 1794.34  3897.6 1783.48  3953.9 1773.37  4061.3 1759.82
  4089.5 1757.56  4168.9 1749.32  4194.4 1749.37  4225.1 1745.25  4259.9 1744.32
  4305.8 1740.25  4337.7 1740.42  4359.9  1738.8  4419.6 1735.23    4595 1731.87
    4830 1732.15  4859.7 1733.72  4900.3  1731.4    4959 1731.13  4980.3 1727.12
  4997.3 1726.06  5000.1 1725.56  5003.3 1726.06  5010.3 1727.96  5020.3 1733.22
  5030.3 1742.25  5040.3 1748.22  5100.3 1775.23  5173.4 1795.29  5350.9 1839.59
#Mann= 9 ,-1 , 0
  3714.5     .05       0  3953.9      .1       0  4089.5     .05       0
  4259.9      .1       0  4359.9     .05       0    4959      .1       0
  4997.3     .07       0  5003.3      .1       0  5173.4     .16       0
Bank Sta=4997.3,5003.3
XS Rating Curve= 0 ,0
Exp/Cntr=0.3,0.1

Type RM Length L Ch R = 1 ,6236    ,310,310,310
BEGIN DESCRIPTION:
UNT032 IN SNOGR 13.0
END DESCRIPTION:
XS GIS Cut Line= 3
      2780218.19     10016653.92      2781098.41     10017008.09
      2781541.08     10017107.04
#Sta/Elev= 30
  4178.6 1761.86  4183.3 1761.48  4246.3 1753.64  4442.4 1743.56  4539.9 1739.75
  4599.3 1728.56  4717.9 1730.52  4847.2  1729.7  4940.2 1727.84  4976.6 1725.86
  4996.3 1722.79  4999.1 1722.29  5002.3 1722.79  5023.5 1727.68  5047.7 1729.33
  5053.1 1731.99  5071.9 1731.68  5077.3 1734.36  5101.4 1734.01  5106.8 1736.68
  5131.5 1739.47  5174.9 1741.08    5180 1743.23  5209.4 1743.17  5229.9 1747.84
  5310.2 1755.48  5414.4 1770.12  5499.3 1778.85  5542.7 1787.57    5581 1792.33
#Mann= 6 ,-1 , 0
  4178.6      .1       0  4183.3     .16       0  4246.3      .1       0
  4442.4     .16       0  4996.3     .07       0  5002.3     .16       0
Bank Sta=4996.3,5002.3
XS Rating Curve= 0 ,0
Exp/Cntr=0.3,0.1

Type RM Length L Ch R = 1 ,5926    ,152,152,152
BEGIN DESCRIPTION:
UNT032 IN SNOGR 12.0
END DESCRIPTION:
XS GIS Cut Line= 2
      2780093.21     10017211.22      2781504.81     10017210.05
#Sta/Elev= 30
  4289.1 1756.57  4414.4 1749.55  4484.4 1747.76  4524.4 1744.47  4614.4 1739.85
    4722 1736.94  4734.4 1734.89  4764.4 1732.84  4814.4 1727.27  4884.4 1725.03
  4934.4 1724.91  4974.4 1723.42  4984.7 1722.01  4991.4 1720.52  4994.1 1720.02
  4997.4 1720.52  5064.4 1726.49  5144.4 1726.61  5194.4 1728.38  5246.4  1738.2
  5274.4 1740.27  5314.4 1741.58  5414.4  1755.2  5454.4 1763.46  5494.4 1770.32
  5514.4 1776.51  5524.4 1778.46  5584.4 1787.05  5634.4 1791.92  5700.7 1793.79
#Mann= 6 ,-1 , 0
  4289.1      .1       0    4722     .16       0  4984.7      .1       0
  4991.4     .07       0  4997.4      .1       0  5246.4     .16       0
Bank Sta=4991.4,4997.4
XS Rating Curve= 0 ,0
Exp/Cntr=0.3,0.1

Type RM Length L Ch R = 1 ,5774    ,531,531,531
BEGIN DESCRIPTION:
Mapping XS ce651759
END DESCRIPTION:
XS GIS Cut Line= 2
      2780061.98      10017325.8      2781394.28     10017341.98
#Sta/Elev= 30
  4344.3 1761.35  4380.8 1757.44  4510.8 1750.23  4550.8 1749.57  4600.8 1745.72
  4760.8 1740.72  4790.8    1742  4833.2  1739.4  4850.8 1738.46  4860.8 1736.35
  4880.8 1727.29  4890.8 1724.07  4950.8 1722.72    4978 1720.71  4997.8 1719.48
  5000.6 1718.98  5003.8 1719.48  5030.8  1723.3  5060.8 1724.43  5240.9  1724.8
  5310.9 1727.23  5330.9 1730.01  5380.9 1733.52  5412.4 1737.12  5467.2 1750.63
  5490.9 1756.22  5550.9 1775.79  5600.9 1788.46  5670.9 1801.06  5676.7 1802.97
#Mann= 6 ,-1 , 0
  4344.3      .1       0  4833.2     .16       0    4978      .1       0
  4997.8     .07       0  5003.8      .1       0  5467.2     .16       0
Bank Sta=4997.8,5003.8
XS Rating Curve= 0 ,0
Exp/Cntr=0.3,0.1

Type RM Length L Ch R = 1 ,5243    ,294,294,294
BEGIN DESCRIPTION:
UNT032 IN SNOGR 11.0
END DESCRIPTION:
XS GIS Cut Line= 2
       2779994.2     10017716.42      2781291.09     10017711.22
#Sta/Elev= 30
  4184.1 1759.45  4228.4 1759.61  4268.4  1755.8  4388.4 1749.74  4438.4 1749.49
  4538.4 1742.84  4618.4  1741.1  4648.4 1743.11  4658.4 1741.71  4745.7 1740.77
  4798.4 1738.23  4878.4 1730.41  4898.4 1726.31  4918.4 1720.12  4995.4  1712.3
  4998.1  1711.8  5001.4  1712.3  5028.4 1719.38  5041.7 1720.22  5132.6 1721.27
  5248.4 1727.77  5288.4  1731.5  5298.4 1734.34  5328.4 1735.66  5368.4 1742.13
  5378.4 1742.52  5422.6 1754.45  5448.4 1763.12  5477.2 1779.04    5481 1779.04
#Mann= 7 ,-1 , 0
  4184.1      .1       0  4745.7     .16       0  4995.4     .07       0
  5001.4     .16       0  5041.7      .1       0  5132.6     .05       0
  5422.6     .16       0
Bank Sta=4995.4,5001.4
XS Rating Curve= 0 ,0
Exp/Cntr=0.3,0.1

Type RM Length L Ch R = 1 ,4949    ,452,452,452
BEGIN DESCRIPTION:
UNT032 IN SNOGR 10.0
END DESCRIPTION:
XS GIS Cut Line= 2
      2780068.73     10018001.72      2781311.93     10018002.88
#Sta/Elev= 30
  4247.1 1751.01  4356.8 1744.57  4396.8 1743.79  4446.8 1738.97  4506.8  1735.7
  4576.8 1732.55  4616.8 1732.18  4666.8 1727.78  4746.8 1724.78  4786.8 1724.73
  4816.8 1722.21  4916.8 1717.72  4956.8 1718.19  4976.8 1713.26  4993.8 1711.15
  4996.6 1710.65  4999.8 1711.15  5038.9 1714.42  5076.8 1717.72  5143.5 1719.16
  5189.7 1722.33  5196.8 1723.51  5206.8 1726.87  5236.8 1741.49  5266.8 1750.03
  5316.8 1756.37  5346.8 1763.77  5386.8 1769.97  5436.8 1775.39  5490.3 1779.53
#Mann= 6 ,-1 , 0
  4247.1      .1       0  4993.8     .07       0  4999.8      .1       0
  5038.9     .16       0  5143.5      .1       0  5189.7     .16       0
Bank Sta=4993.8,4999.8
XS Rating Curve= 0 ,0
Exp/Cntr=0.3,0.1