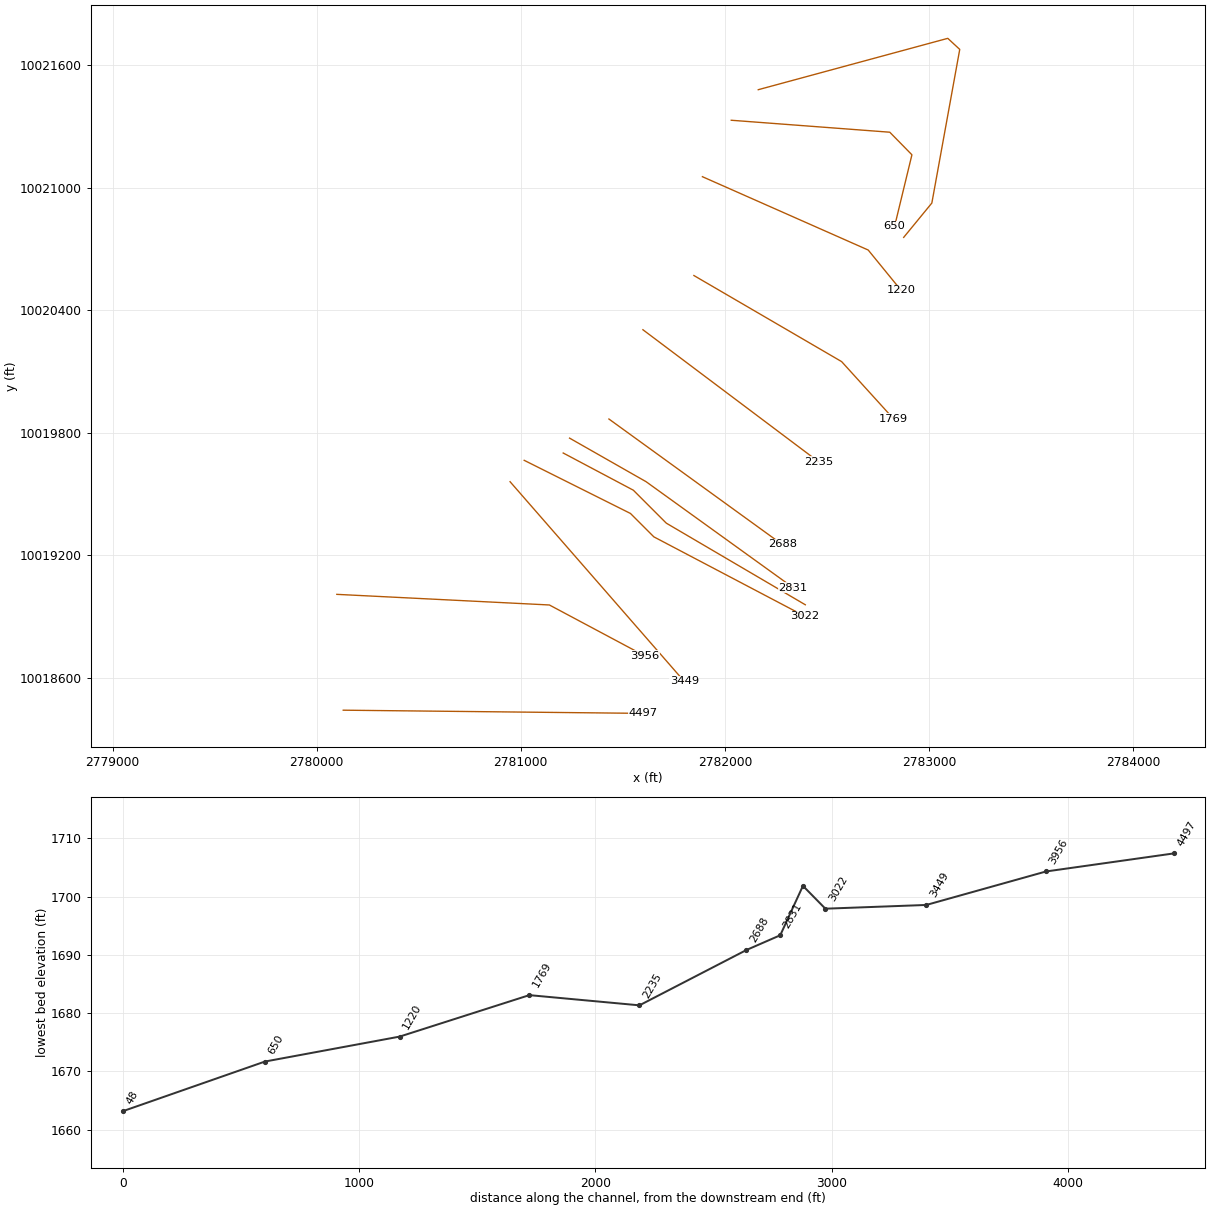
HEC-RAS study UNT032 IN SNOGR.prj: UNT032 IN SNOGR Base Level Engineering

--- UNT032 IN SNOGR.g01 (geometry) --- (continued)

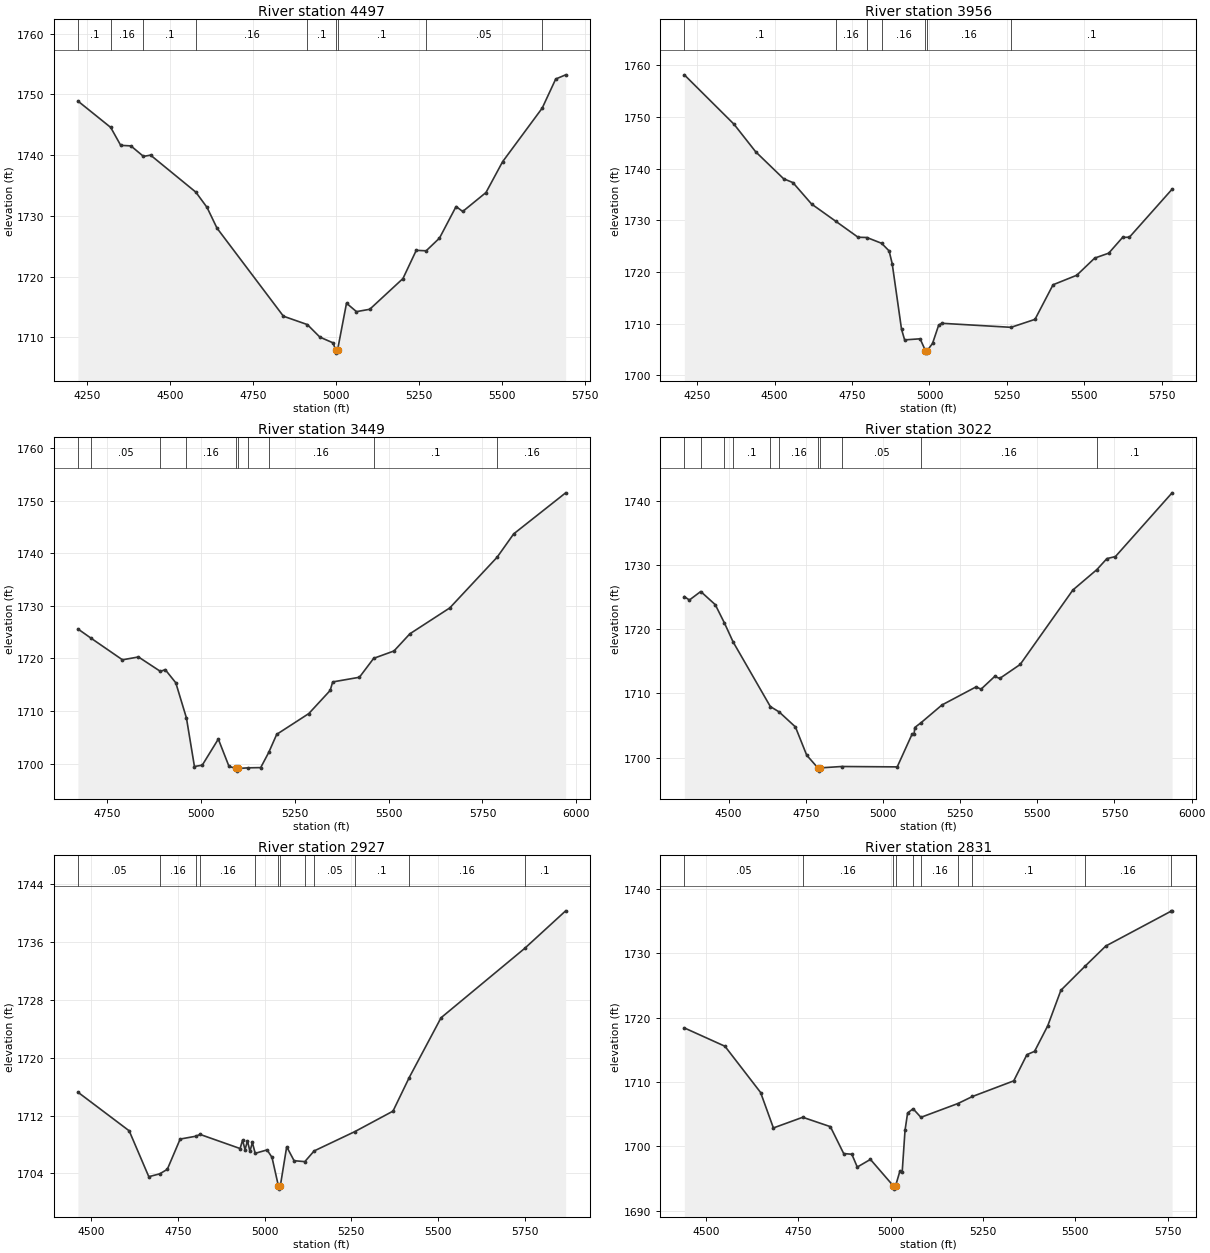
Type RM Length L Ch R = 1 ,4497    ,541,541,541
BEGIN DESCRIPTION:
UNT032 IN SNOGR 9.0
END DESCRIPTION:
XS GIS Cut Line= 2
       2780129.7     10018440.38      2781598.42     10018424.76
#Sta/Elev= 30
  4222.6  1748.9  4321.3 1744.56  4351.4 1741.61  4382.1 1741.52    4420 1739.79
  4441.4    1740  4577.6 1733.91  4611.4 1731.39  4641.4 1727.98  4841.4 1713.48
  4913.5  1712.1  4951.4 1710.03  4991.4 1709.08  4998.4  1707.9  5001.2  1707.4
  5004.4  1707.9  5031.4 1715.62  5061.4 1714.23  5101.4 1714.62  5201.4 1719.68
  5241.4 1724.32  5271.4 1724.25  5311.4 1726.34  5361.4 1731.54  5381.4 1730.72
  5451.4 1733.84  5501.4 1738.91  5620.7 1747.74  5661.4 1752.53  5691.4 1753.22
#Mann= 9 ,-1 , 0
  4222.6      .1       0  4321.3     .16       0    4420      .1       0
  4577.6     .16       0  4913.5      .1       0  4998.4     .07       0
  5004.4      .1       0  5271.4     .05       0  5620.7     .16       0
Bank Sta=4998.4,5004.4
XS Rating Curve= 0 ,0
Exp/Cntr=0.3,0.1

Type RM Length L Ch R = 1 ,3956    ,507,507,507
BEGIN DESCRIPTION:
UNT032 IN SNOGR 8.0
END DESCRIPTION:
XS GIS Cut Line= 3
      2780098.37     10019008.09      2781140.08     10018956.01
      2781608.87     10018705.99
#Sta/Elev= 30
  4208.8 1758.12  4369.1 1748.57  4439.2 1743.23  4529.3 1738.02  4559.3 1737.28
  4619.4 1733.14  4697.1 1729.82  4769.6 1726.71  4797.9 1726.66  4845.6 1725.54
  4869.7 1724.07  4879.7 1721.61  4909.8 1708.93  4919.8 1706.86  4969.8 1707.07
  4986.9  1704.8  4989.6  1704.3  4992.9  1704.8  5009.9 1706.18  5029.9 1709.74
  5039.9 1710.07  5263.3 1709.29  5340.6 1710.83  5398.9 1717.52  5475.4 1719.36
  5533.3 1722.68  5578.6 1723.63  5623.4 1726.68  5645.4 1726.72  5783.1    1736
#Mann= 7 ,-1 , 0
  4208.8      .1       0  4697.1     .16       0  4797.9      .1       0
  4845.6     .16       0  4986.9     .07       0  4992.9     .16       0
  5263.3      .1       0
Bank Sta=4986.9,4992.9
XS Rating Curve= 0 ,0
Exp/Cntr=0.3,0.1

Type RM Length L Ch R = 1 ,3449    ,427,427,427
BEGIN DESCRIPTION:
UNT032 IN SNOGR 7.0
END DESCRIPTION:
XS GIS Cut Line= 2
      2780947.35      10019560.2      2781801.54     10018581.01
#Sta/Elev= 30
  4672.3  1725.6  4706.9 1723.86  4790.9 1719.73  4833.6 1720.27  4892.2 1717.52
  4904.8 1717.87    4933 1715.36  4961.4 1708.66  4982.7 1699.43  5003.5 1699.68
  5046.3 1704.65  5074.7 1699.47  5092.6 1699.05  5095.4 1698.55  5098.6 1699.05
  5126.2 1699.18  5159.2 1699.22  5180.7 1702.12  5201.9 1705.55  5287.4  1709.5
  5344.3  1713.9    5351 1715.52  5422.2 1716.41  5460.2 1720.01  5514.3 1721.41
  5556.7 1724.68  5662.9  1729.6  5789.1 1739.25  5833.2 1743.69  5971.7  1751.5
#Mann= 10 ,-1 , 0
  4672.3      .1       0  4706.9     .05       0  4892.2      .1       0
  4961.4     .16       0  5092.6     .07       0  5098.6     .16       0
  5126.2      .1       0  5180.7     .16       0  5460.2      .1       0
  5789.1     .16       0
Bank Sta=5092.6,5098.6
XS Rating Curve= 0 ,0
Exp/Cntr=0.3,0.1

Type RM Length L Ch R = 1 ,3022    ,95,95,95
BEGIN DESCRIPTION:
Mapping XS c583c237
END DESCRIPTION:
XS GIS Cut Line= 4
      2781016.62      10019664.9      2781537.43     10019404.49
      2781652.02     10019289.91      2782391.58     10018901.03
#Sta/Elev= 30
  4356.7 1725.08    4373 1724.54  4409.8 1725.87  4456.9 1723.82  4486.6 1720.97
  4514.7 1718.02  4635.3 1707.96  4663.7 1707.13  4716.5 1704.79  4753.1 1700.39
  4789.3 1698.41    4792 1697.91  4795.3 1698.41  4866.3 1698.63  5046.3 1698.57
    5095 1703.73    5101 1703.73  5103.1  1704.7  5123.3 1705.44  5191.3 1708.21
  5301.5 1711.02  5317.9 1710.67    5362 1712.65  5378.4 1712.34  5444.5 1714.51
  5615.2  1726.1    5693 1729.28  5725.4 1730.99  5753.1 1731.31  5936.6 1741.23
#Mann= 11 ,-1 , 0
  4356.7     .05       0  4409.8      .1       0  4486.6     .05       0
  4514.7      .1       0  4635.3     .05       0  4663.7     .16       0
  4789.3    .035       0  4795.3     .16       0  4866.3     .05       0
  5123.3     .16       0    5693      .1       0
Bank Sta=4789.3,4795.3
XS Rating Curve= 0 ,0
Exp/Cntr=0.3,0.1

Type RM Length L Ch R = 1 ,2927    ,96,96,96
BEGIN DESCRIPTION:
Mapping XS 9cc636a5
END DESCRIPTION:
XS GIS Cut Line= 4
      2781207.83     10019700.78      2781551.54     10019518.51
        2781713.     10019357.05      2782394.27     10018957.05
#Sta/Elev= 30
  4461.3 1715.23  4609.2 1709.89  4665.8 1703.55  4697.3 1703.94  4719.2 1704.57
  4756.3 1708.75  4801.2 1709.14  4813.9 1709.39  4929.3 1707.44  4936.4 1708.61
  4943.5 1707.29  4950.5 1708.51  4957.6 1707.06  4964.7 1708.28  4972.8 1706.78
  5007.1 1707.25  5021.3 1706.22  5039.5 1702.33  5042.2 1701.83  5045.5 1702.33
  5063.7 1707.69    5085 1705.76    5116 1705.63  5142.9 1707.11  5260.3 1709.78
  5370.4 1712.61  5417.2 1717.25  5509.1 1725.52  5750.2  1735.1  5868.7  1740.3
#Mann= 12 ,-1 , 0
  4461.3     .05       0  4697.3     .16       0  4801.2     .05       0
  4813.9     .16       0  4972.8     .05       0  5039.5    .035       0
  5045.5     .05       0    5116     .16       0  5142.9     .05       0
  5260.3      .1       0  5417.2     .16       0  5750.2      .1       0
Bank Sta=5039.5,5045.5
XS Rating Curve= 0 ,0
Exp/Cntr=0.3,0.1

Type RM Length L Ch R = 1 ,2831    ,143,143,143
BEGIN DESCRIPTION:
UNT032 IN SNOGR 6.0
END DESCRIPTION:
XS GIS Cut Line= 3
      2781239.03     10019773.72      2781614.04     10019560.17
      2782334.77     10019040.83
#Sta/Elev= 30
    4442 1718.41  4551.9 1715.56  4648.4 1708.37    4683 1702.86  4762.4 1704.52
  4837.2 1703.06  4873.2 1698.88  4895.3 1698.77    4910 1696.78  4945.6 1697.97
  5007.6 1693.85  5010.4 1693.35  5013.6 1693.85  5025.4 1696.16  5031.5 1695.98
  5039.2 1702.48  5046.2 1705.19  5061.1 1705.84  5082.2 1704.51  5182.5 1706.66
  5221.7 1707.75  5333.4 1710.18    5369 1714.25  5389.8 1714.77  5425.4 1718.74
    5461 1724.26  5525.6 1727.96  5582.5 1731.14  5758.7 1736.54  5761.9 1736.61
#Mann= 10 ,-1 , 0
    4442     .05       0  4762.4     .16       0  5007.6     .07       0
  5013.6     .16       0  5061.1      .1       0  5082.2     .16       0
  5182.5     .05       0  5221.7      .1       0  5525.6     .16       0
  5758.7      .1       0
Bank Sta=5007.6,5013.6
XS Rating Curve= 0 ,0
Exp/Cntr=0.3,0.1

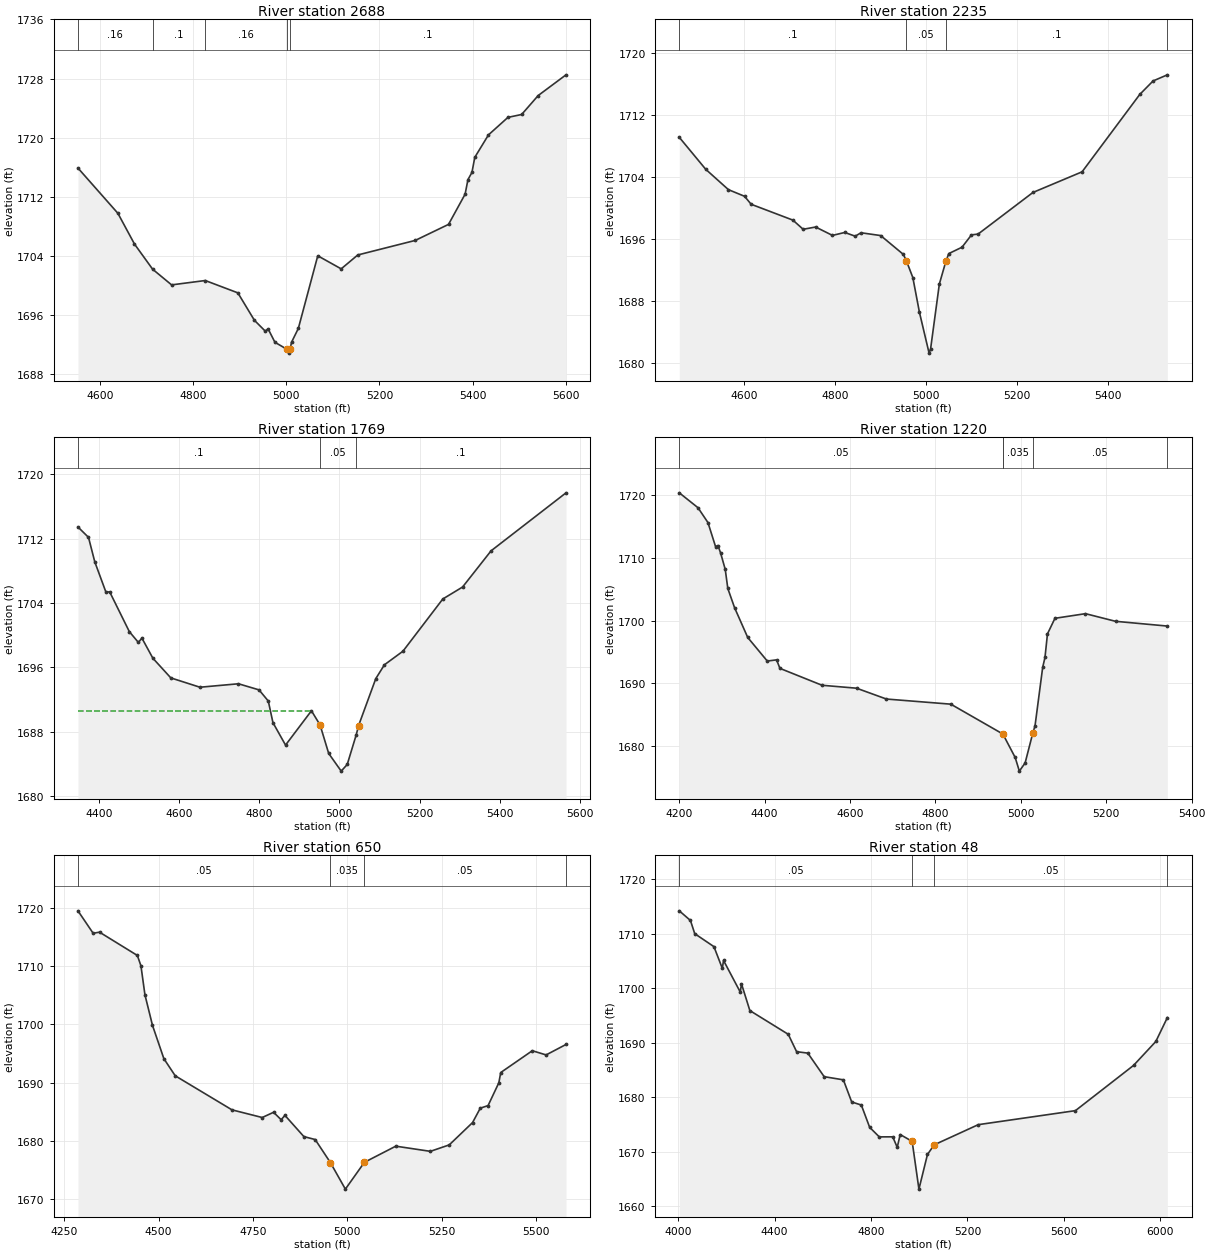
Type RM Length L Ch R = 1 ,2688    ,453,453,453
BEGIN DESCRIPTION:
UNT032 IN SNOGR 5.0
END DESCRIPTION:
XS GIS Cut Line= 2
      2781431.74     10019867.47      2782280.72     10019252.87
#Sta/Elev= 30
  4552.5 1715.88  4638.3 1709.75  4673.9 1705.59  4712.9 1702.18  4753.6 1700.06
  4825.9 1700.65  4895.9 1698.98  4931.4 1695.27  4954.7  1693.8  4960.8 1694.11
  4975.5 1692.29  5001.9 1691.32  5004.7 1690.82  5007.9 1691.32  5011.1 1692.28
  5025.8 1694.17  5067.5    1704  5117.8 1702.23  5153.4 1704.11  5276.8 1706.08
  5348.3 1708.25  5383.9 1712.34    5390 1714.31  5398.6 1715.29  5404.7 1717.33
  5434.1 1720.37  5475.9 1722.74  5505.3 1723.13  5540.9  1725.7  5600.6  1728.5
#Mann= 5 ,-1 , 0
  4552.5     .16       0  4712.9      .1       0  4825.9     .16       0
  5001.9     .07       0  5007.9      .1       0
Bank Sta=5001.9,5007.9
XS Rating Curve= 0 ,0
Exp/Cntr=0.3,0.1

Type RM Length L Ch R = 1 ,2235    ,466,466,466
BEGIN DESCRIPTION:
UNT032 IN SNOGR 4.0
END DESCRIPTION:
XS GIS Cut Line= 2
      2781598.43     10020304.95       2782457.8     10019659.12
#Sta/Elev= 30
  4456.7 1709.11    4515 1704.99    4565 1702.37  4600.4 1701.52    4615 1700.49
  4706.9 1698.45  4729.5 1697.27    4757 1697.56  4794.1 1696.48  4821.2 1696.86
  4844.1 1696.38    4857 1696.82  4900.3 1696.46  4950.3 1694.03  4957.1 1693.18
  4971.1 1691.05  4985.7 1686.56  5006.9 1681.32  5010.1 1681.82  5029.5 1690.22
    5044 1693.17  5050.3 1694.14  5079.4 1694.96  5100.3 1696.55  5114.8 1696.65
  5235.6 1702.01  5343.9 1704.67    5471 1714.64  5500.2 1716.37  5531.7 1717.16
#Mann= 4 ,-1 , 0
  4456.7      .1       0  4957.1     .05       0    5044      .1       0
  5531.7     .16       0
Bank Sta=4957.1,5044
XS Rating Curve= 0 ,0
Exp/Cntr=0.3,0.1

Type RM Length L Ch R = 1 ,1769    ,549,549,549
BEGIN DESCRIPTION:
UNT032 IN SNOGR 3.0
END DESCRIPTION:
XS GIS Cut Line= 3
      2781848.38     10020570.61      2782572.37     10020148.72
      2782827.02     10019868.08
#Sta/Elev= 30
  4348.1 1713.45  4374.4 1712.16  4390.1 1709.11  4417.6 1705.38  4427.4 1705.36
  4476.2 1700.43  4498.7 1699.09  4507.6 1699.62  4534.9 1697.12  4579.7 1694.67
  4652.3 1693.51  4748.3 1693.94  4799.6 1693.18  4822.7 1691.79  4834.3  1689.1
  4865.7 1686.31  4930.3 1690.58  4951.8 1688.81  4973.3 1685.27  5004.5 1683.07
  5019.5  1683.9  5041.9 1687.58  5047.7 1688.72  5090.7 1694.58  5112.2  1696.3
  5158.4 1697.99  5257.8 1704.49  5307.1 1705.98  5378.1 1710.48    5565  1717.7
#Mann= 3 ,-1 , 0
  4348.1      .1       0  4951.8     .05       0  5041.9      .1       0
#XS Ineff= 2 , 0
         4930.23 1690.61
Permanent Ineff=
       T       T
Bank Sta=4951.8,5047.7
XS Rating Curve= 0 ,0
Exp/Cntr=0.3,0.1

Type RM Length L Ch R = 1 ,1220    ,570,570,570
BEGIN DESCRIPTION:
UNT032 IN SNOGR 2.0
END DESCRIPTION:
XS GIS Cut Line= 3
       2781890.1     10021054.96      2782702.58     10020695.59
      2782863.33     10020498.55
#Sta/Elev= 30
  4200.4 1720.42  4244.2 1718.04  4267.5 1715.67  4285.3 1711.83  4290.8    1712
    4297 1710.84    4308 1708.18    4314 1705.14  4329.8 1702.07  4360.6 1697.31
  4406.4 1693.54  4428.2 1693.73    4436 1692.37  4534.6 1689.67  4615.5  1689.2
  4685.3 1687.47  4836.1 1686.65    4958 1681.88  4986.8 1678.13  4996.6 1675.95
  5010.1 1677.26  5027.9 1681.99  5033.3  1683.2  5051.2 1692.53  5056.6 1694.12
  5062.4 1697.88  5079.9 1700.37  5151.4 1701.11  5221.7 1699.89  5343.1 1699.13
#Mann= 5 ,-1 , 0
  4200.4     .05       0    4958      .1       0    4958    .035       0
  5027.9     .05       0  5343.1     .16       0
Bank Sta=4958,5027.9
XS Rating Curve= 0 ,0
Exp/Cntr=0.3,0.1

Type RM Length L Ch R = 1 ,650     ,602,602,602
BEGIN DESCRIPTION:
Mapping XS ad781556
END DESCRIPTION:
XS GIS Cut Line= 4
       2782031.4     10021331.63      2782808.29     10021273.03
       2782916.8     10021162.36      2782832.16     10020812.96
#Sta/Elev= 30
  4286.3 1719.55  4326.6 1715.69  4343.5 1715.88  4443.8 1711.87  4453.3 1710.08
  4463.9 1705.09  4483.9 1699.84    4514 1694.12  4544.1 1691.17  4694.5 1685.31
  4774.7 1683.99  4804.8 1684.89  4824.9 1683.61  4834.9 1684.36  4885.1 1680.71
  4915.1  1680.2  4955.3 1676.25  4995.1 1671.67  5045.5 1676.28  5128.7 1679.06
  5220.4 1678.17  5270.4 1679.28  5332.2 1683.12  5352.7  1685.6  5373.3 1686.04
  5401.8 1689.96  5406.9 1691.73  5490.5 1695.48  5527.2 1694.76  5579.9 1696.56
#Mann= 4 ,-1 , 0
  4286.3     .05       0  4955.3    .035       0  5045.5     .05       0
  5579.9     .16       0
Bank Sta=4955.3,5045.5
XS Rating Curve= 0 ,0
Exp/Cntr=0.3,0.1

Type RM Length L Ch R = 1 ,48      ,0,0,0
BEGIN DESCRIPTION:
UNT032 IN SNOGR 1.0
END DESCRIPTION:
XS GIS Cut Line= 5
      2782163.74     10021481.36      2783092.58      10021733.1
      2783151.18     10021678.85      2783014.46     10020925.81
      2782876.46     10020757.63
#Sta/Elev= 30
  4004.2 1714.17  4050.5  1712.4  4068.3 1709.98    4148  1707.6  4182.7 1703.62
  4187.8 1705.07  4257.2 1699.27  4262.3 1700.78    4297 1695.88  4456.3 1691.53
    4491 1688.34  4537.5 1688.08  4605.3 1683.76    4685 1683.18  4719.6 1679.12
  4759.5 1678.56  4794.1 1674.47    4834 1672.72  4889.8 1672.73  4908.5  1670.8
  4920.8 1673.15  4970.4  1671.9  4998.5 1663.14  5033.9 1669.49  5061.8 1671.26
  5244.7 1674.96  5647.8 1677.53  5888.9 1685.82  5981.4 1690.21  6029.3  1694.6
#Mann= 4 ,-1 , 0
  4004.2     .05       0  4970.4    .035       0  5061.8     .05       0
  6029.3     .05       0
Bank Sta=4970.4,5061.8
XS Rating Curve= 0 ,0
Exp/Cntr=0.3,0.1

Chan Stop Cuts=-1
Use User Specified Reach Order=0
Composite Channel Slope=5