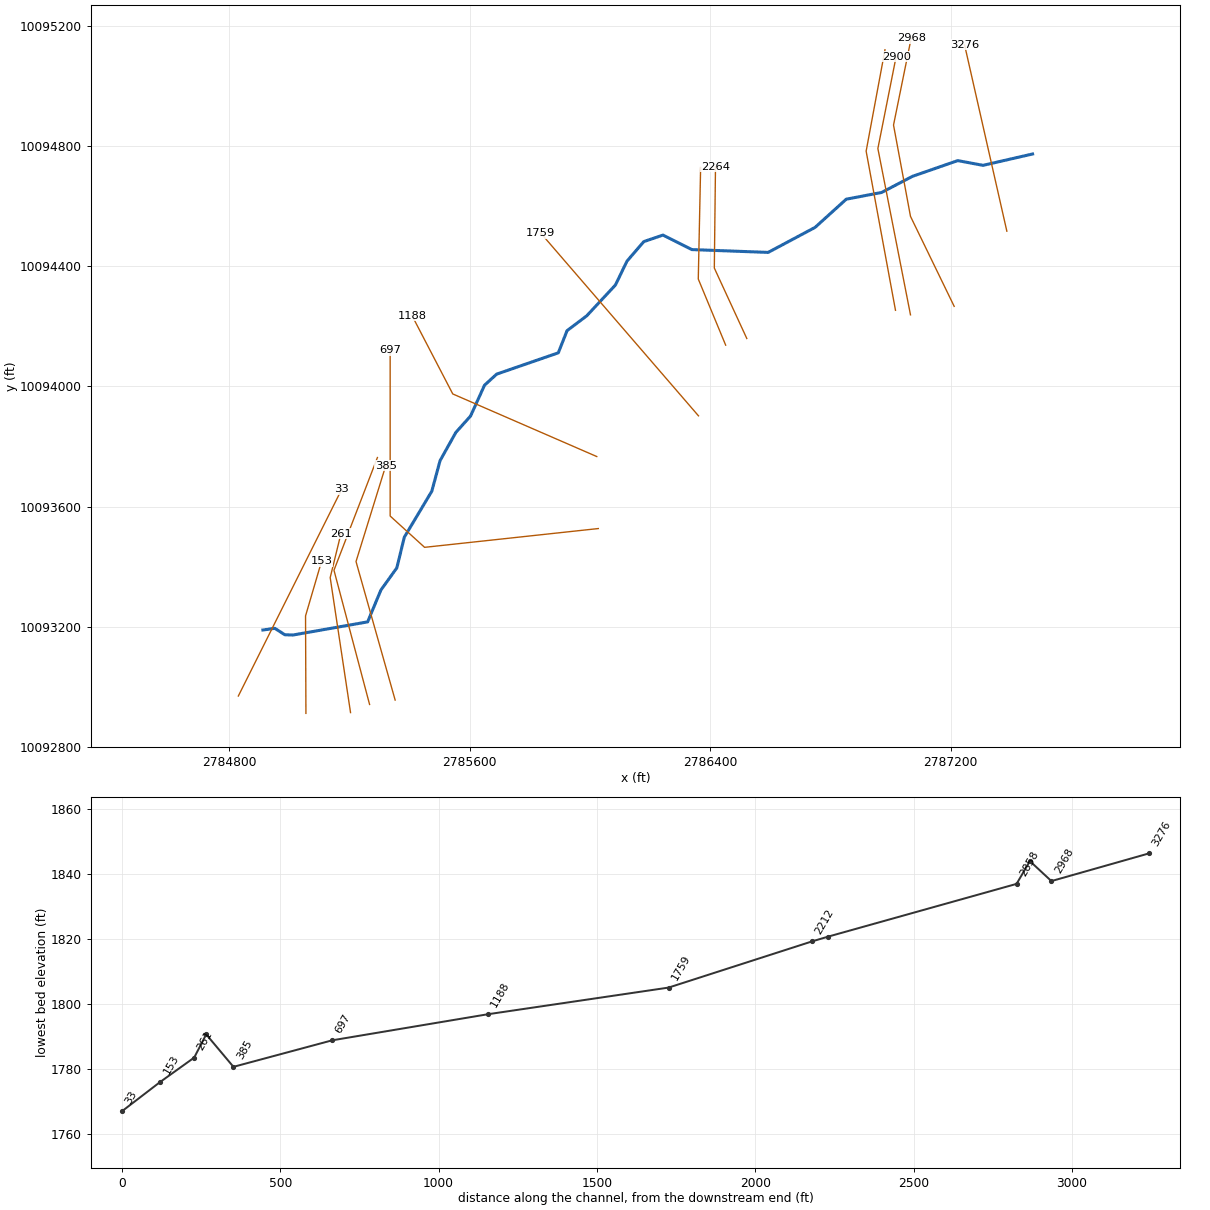
--- UNT033 IN NNOGR.prj (project) ---

Proj Title=UNT033 IN NNOGR Base Level Engineering
Current Plan=p01
Default Exp/Contr=0.3,0.1
English Units
Geom File=g01
Flow File=f01
Plan File=p01
Y Axis Title=Elevation
X Axis Title(PF)=Main Channel Distance
X Axis Title(XS)=Station
BEGIN DESCRIPTION:
UNT033 IN NNOGR
END DESCRIPTION:
DSS Export Rating Curves= 0
DSS Export Rating Curve Sorted= 0
DSS Export Volume Flow Curves= 0
DXF OffsetX= 0
DXF OffsetY= 0
DXF ScaleX= 1
DXF ScaleY= 10

--- UNT033 IN NNOGR.p01 (plan) ---

Plan Title=Multiple Run
Short Identifier=Multiple
Geom File=g01
Flow File=f01
Subcritical Flow
K Sum by GR= 0
Std Step Tol= 0.01
Critical Tol= 0.01
Num of Std Step Trials= 20
Max Error Tol= 0.3
Flow Tol Ratio= 0.001
Split Flow NTrial= 30
Split Flow Tol= 0.02
Split Flow Ratio= 0.02
Log Output Level= 0
Friction Slope Method= 1
Unsteady Friction Slope Method= 2
Unsteady Bridges Friction Slope Method= 1
Parabolic Critical Depth
Global Vel Dist=  1 , 1 , 1
Global Log Level= 0
CheckData=True
Encroach Param= -1, 0, 0, 0
BEGIN DESCRIPTION:
Multiple Run
END DESCRIPTION:

--- UNT033 IN NNOGR.f01 (steady flow) ---

Flow Title=Multiple
Program Version=4.10
Number of Profiles= 7
Profile Names=10-year,25-year,50-year,1pct_min,100-year,1pct_plu,500-year
River Rch & RM=UNT033 IN NNOGR,Reach-1         ,3276
     569     806    1009     927    1253    1695    1938
Boundary for River Rch & Prof#=UNT033 IN NNOGR,Reach-1         , 1
Up Type= 0
Dn Type= 3
Dn Slope=0.075
Boundary for River Rch & Prof#=UNT033 IN NNOGR,Reach-1         , 2
Up Type= 0
Dn Type= 3
Dn Slope=0.075
Boundary for River Rch & Prof#=UNT033 IN NNOGR,Reach-1         , 3
Up Type= 0
Dn Type= 3
Dn Slope=0.075
Boundary for River Rch & Prof#=UNT033 IN NNOGR,Reach-1         , 4
Up Type= 0
Dn Type= 3
Dn Slope=0.075
Boundary for River Rch & Prof#=UNT033 IN NNOGR,Reach-1         , 5
Up Type= 0
Dn Type= 3
Dn Slope=0.075
Boundary for River Rch & Prof#=UNT033 IN NNOGR,Reach-1         , 6
Up Type= 0
Dn Type= 3
Dn Slope=0.075
Boundary for River Rch & Prof#=UNT033 IN NNOGR,Reach-1         , 7
Up Type= 0
Dn Type= 3
Dn Slope=0.075
DSS Import GetInterval= 0
DSS Import GetPeak= 0
DSS Import FillOption= 0

--- UNT033 IN NNOGR.g01 (geometry) ---

Geom Title=Existing Conditions
Program Version=4.10

River Reach=UNT033 IN NNOGR ,Reach-1
Reach XY= 30
      2787472.86     10094773.11      2787308.06     10094735.34
       2787223.8      10094751.1       2787073.2     10094698.73
      2786970.59     10094645.09      2786852.89     10094622.69
      2786749.24     10094528.94      2786592.96     10094445.61
      2786339.08     10094454.97      2786243.14     10094503.27
      2786179.29     10094481.65      2786123.16     10094416.54
      2786084.88     10094337.28      2785989.31      10094234.6
       2785923.8     10094185.26       2785894.7     10094111.44
      2785689.55     10094040.56      2785649.13     10094003.65
      2785602.68     10093901.14      2785553.69     10093846.56
      2785501.27     10093752.77      2785473.73     10093651.04
      2785382.19     10093497.86      2785357.32      10093395.8
       2785304.2     10093321.84      2785260.19     10093216.11
      2785011.94     10093172.47      2784984.72     10093173.22
      2784951.44     10093194.68      2784911.53     10093189.05

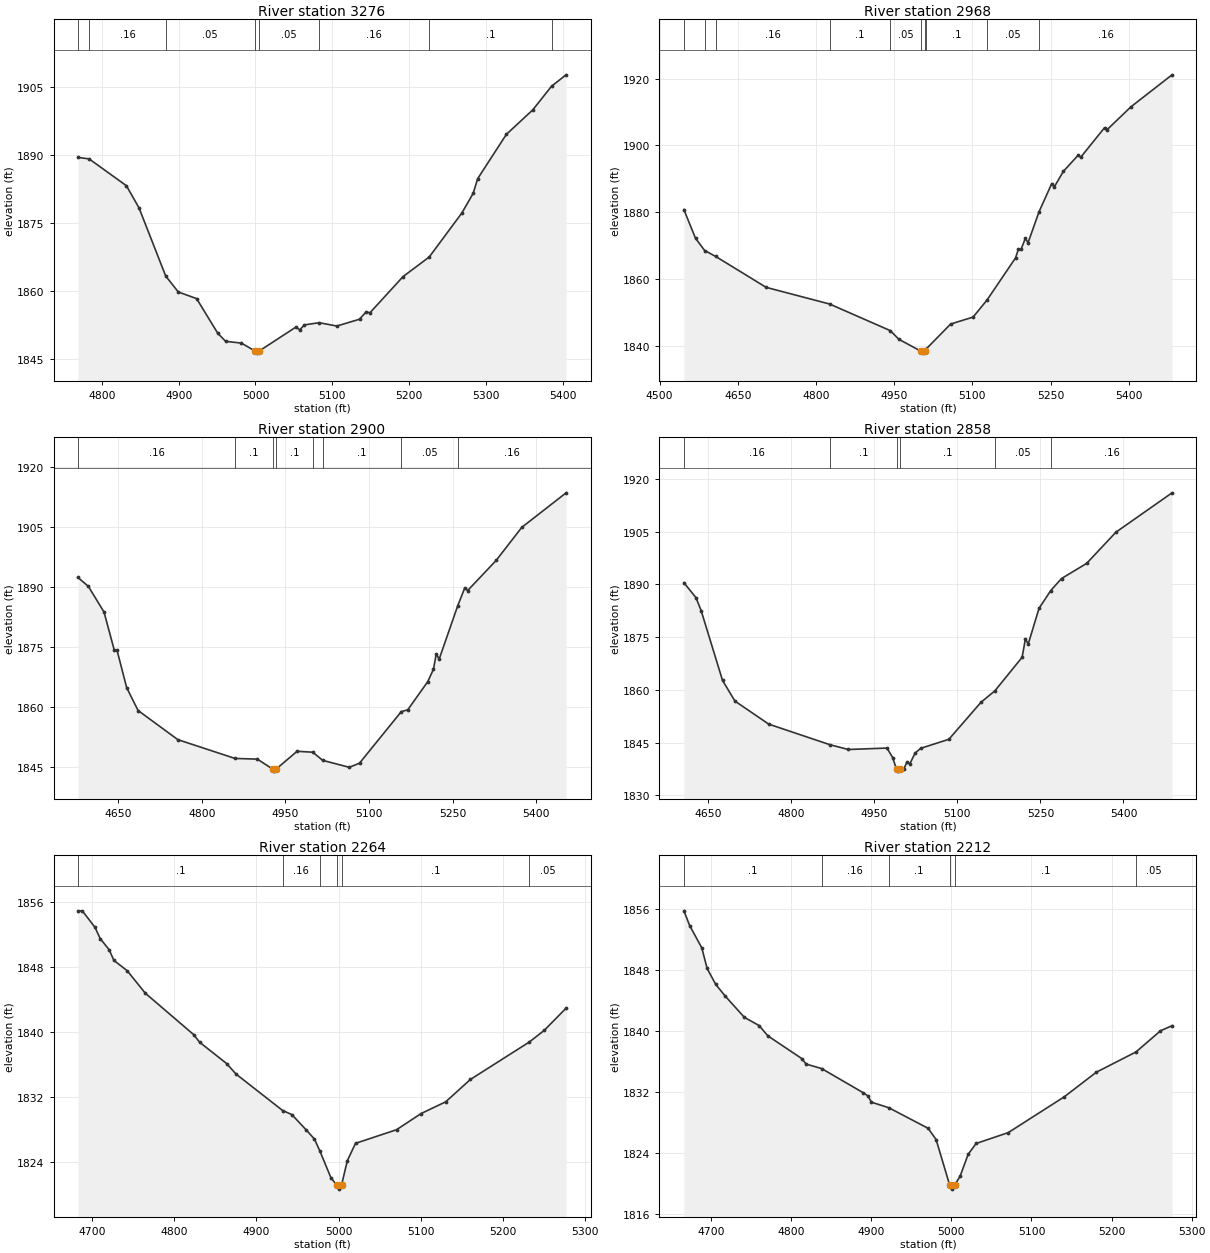
Type RM Length L Ch R = 1 ,3276    ,308,308,308
BEGIN DESCRIPTION:
UNT033 IN NNOGR 7.0
END DESCRIPTION:
XS GIS Cut Line= 2
      2787387.22     10094516.24      2787246.58     10095136.08
#Sta/Elev= 30
  4768.9 1889.38  4783.4 1889.07    4832 1883.15  4848.4 1878.27  4883.2 1863.24
  4899.6 1859.74  4923.4 1858.28  4950.9 1850.66  4961.2 1848.87  4981.7 1848.48
  4999.2 1846.77  5001.9 1846.27  5005.2 1846.77  5052.7 1852.01  5057.8  1851.4
  5063.7 1852.49    5083 1852.97    5106 1852.24  5135.5 1853.74    5144 1855.35
  5149.1 1855.16  5192.2 1863.13  5226.3 1867.45  5268.8 1877.15  5283.6  1881.5
  5289.3 1884.69  5326.7 1894.46  5361.1 1899.86  5385.6 1905.08  5404.5 1907.58
#Mann= 8 ,-1 , 0
  4768.9      .1       0  4783.4     .16       0  4883.2     .05       0
  4999.2    .035       0  5005.2     .05       0    5083     .16       0
  5226.3      .1       0  5385.6     .16       0
Bank Sta=4999.2,5005.2
XS Rating Curve= 0 ,0
Exp/Cntr=0.3,0.1

Type RM Length L Ch R = 1 ,2968    ,68,68,68
BEGIN DESCRIPTION:
Mapping XS df7b265e
END DESCRIPTION:
XS GIS Cut Line= 4
      2787211.97     10094266.06      2787066.57     10094565.53
      2787010.14     10094869.35      2787068.73     10095157.94
#Sta/Elev= 30
  4546.5 1880.79  4568.8 1872.19  4586.4 1868.51  4607.5 1866.74  4704.2 1857.48
  4826.2 1852.47  4942.5  1844.5  4958.9 1841.91  5002.3 1838.26  5005.1 1837.76
  5008.3 1838.26  5011.6 1839.05  5058.1 1846.47  5101.3 1848.57  5127.8 1853.63
  5182.7  1866.3  5188.1 1868.84  5193.2 1868.84  5201.6 1872.18  5206.7 1870.83
  5227.8 1880.14  5252.2 1888.58  5257.3 1887.65  5274.5 1892.25  5302.8 1897.07
  5307.9  1896.5  5353.5 1905.34  5358.6 1904.77  5404.1 1911.59  5482.9 1921.17
#Mann= 10 ,-1 , 0
  4546.5     .16       0  4586.4      .1       0  4607.5     .16       0
  4826.2      .1       0  4942.5     .05       0  5002.3    .035       0
  5008.3     .05       0  5011.6      .1       0  5127.8     .05       0
  5227.8     .16       0
Bank Sta=5002.3,5008.3
XS Rating Curve= 0 ,0
Exp/Cntr=0.3,0.1

Type RM Length L Ch R = 1 ,2900    ,42,42,42
BEGIN DESCRIPTION:
Mapping XS f056e26d
END DESCRIPTION:
XS GIS Cut Line= 3
      2787066.57     10094237.85      2786958.06     10094791.23
      2787018.83     10095097.24
#Sta/Elev= 30
  4577.8  1892.3  4596.5 1890.07  4624.6 1883.65  4642.9 1874.17    4648 1874.06
  4665.3 1864.74  4685.7 1859.05    4757 1851.77  4859.6 1847.07  4899.7  1846.9
  4927.3  1844.4    4930  1843.9  4933.3  1844.4    4971 1848.86  4999.1 1848.63
    5017 1846.59  5064.7 1844.85  5083.1  1845.9  5157.9 1858.76  5169.6 1859.23
  5205.4 1866.25  5215.6 1869.32  5220.8  1873.2  5225.9 1871.88  5259.1 1885.17
  5271.9  1889.7    5277 1889.02  5328.2 1896.56  5374.2 1904.82  5453.7 1913.45
#Mann= 8 ,-1 , 0
  4577.8     .16       0  4859.6      .1       0  4927.3    .035       0
  4933.3      .1       0  4999.1     .05       0    5017      .1       0
  5157.9     .05       0  5259.1     .16       0
Bank Sta=4927.3,4933.3
XS Rating Curve= 0 ,0
Exp/Cntr=0.3,0.1

Type RM Length L Ch R = 1 ,2858    ,594,594,594
BEGIN DESCRIPTION:
UNT033 IN NNOGR 6.0
END DESCRIPTION:
XS GIS Cut Line= 3
      2787016.66     10094253.02        2786919.     10094782.55
      2786981.71     10095119.91
#Sta/Elev= 30
  4606.1 1890.48    4628 1886.22  4637.3 1882.53  4675.9  1862.7  4698.3 1856.82
  4759.4 1850.26  4869.9 1844.41  4903.1 1843.05  4972.9 1843.46  4983.1 1840.77
  4990.2  1837.4    4993  1836.9  4996.2  1837.4  5003.4 1837.49  5009.1 1839.55
  5014.2 1838.97  5023.7 1842.05  5033.9 1843.39  5084.7 1845.95  5142.6 1856.46
  5167.9 1859.75    5217 1869.28  5222.9 1874.49    5228 1873.04  5247.5 1883.18
  5268.7 1888.25  5288.2 1891.67  5333.5 1895.96  5386.3 1904.83  5487.7 1916.03
#Mann= 6 ,-1 , 0
  4606.1     .16       0  4869.9      .1       0  4990.2     .07       0
  4996.2      .1       0  5167.9     .05       0  5268.7     .16       0
Bank Sta=4990.2,4996.2
XS Rating Curve= 0 ,0
Exp/Cntr=0.3,0.1

Type RM Length L Ch R = 1 ,2264    ,52,52,52
BEGIN DESCRIPTION:
UNT033 IN NNOGR 5.0
END DESCRIPTION:
XS GIS Cut Line= 3
      2786521.87     10094159.13       2786413.8      10094393.5
      2786417.69     10094730.39
#Sta/Elev= 30
  4682.4 1854.87  4687.7 1854.87  4703.2 1852.84  4709.5 1851.47  4720.5 1850.08
  4726.2 1848.79  4742.5 1847.51  4764.5 1844.76  4823.5 1839.67  4830.6 1838.75
  4863.7 1836.12  4874.9 1834.85  4931.9 1830.36  4943.1 1829.86  4960.7 1827.97
  4970.7 1826.85  4977.4 1825.36  4990.7 1822.12  4997.7 1821.21  5000.5 1820.71
  5003.7 1821.21  5010.7 1824.19  5020.7 1826.33  5070.7    1828  5100.7 1829.99
  5130.7 1831.43  5160.7 1834.17  5232.3 1838.75  5250.7 1840.19  5277.4 1842.93
#Mann= 6 ,-1 , 0
  4682.4      .1       0  4931.9     .16       0  4977.4      .1       0
  4997.7     .07       0  5003.7      .1       0  5232.3     .05       0
Bank Sta=4997.7,5003.7
XS Rating Curve= 0 ,0
Exp/Cntr=0.3,0.1

Type RM Length L Ch R = 1 ,2212    ,453,453,453
BEGIN DESCRIPTION:
Mapping XS 2fa3e3e8
END DESCRIPTION:
XS GIS Cut Line= 3
      2786451.57     10094136.97      2786360.42     10094357.04
      2786368.23     10094728.16
#Sta/Elev= 30
  4666.1 1855.77  4673.4 1853.82  4688.5  1850.9  4695.1  1848.2  4705.9  1846.1
  4717.8 1844.56  4741.7 1841.77    4760  1840.7    4771 1839.34  4813.3 1836.36
  4818.7 1835.64  4838.2 1835.04  4889.9 1831.88  4895.8 1831.46  4900.3 1830.63
  4921.8 1829.91    4971  1827.2    4981 1825.72    4998 1819.71  5000.8 1819.21
    5004 1819.71    5011 1820.92    5021 1823.79    5031 1825.21    5071 1826.63
    5141 1831.34    5181 1834.57  5230.5 1837.23  5261.1 1840.01  5275.5 1840.68
#Mann= 6 ,-1 , 0
  4666.1      .1       0  4838.2     .16       0  4921.8      .1       0
    4998     .07       0    5004      .1       0  5230.5     .05       0
Bank Sta=4998,5004
XS Rating Curve= 0 ,0
Exp/Cntr=0.3,0.1

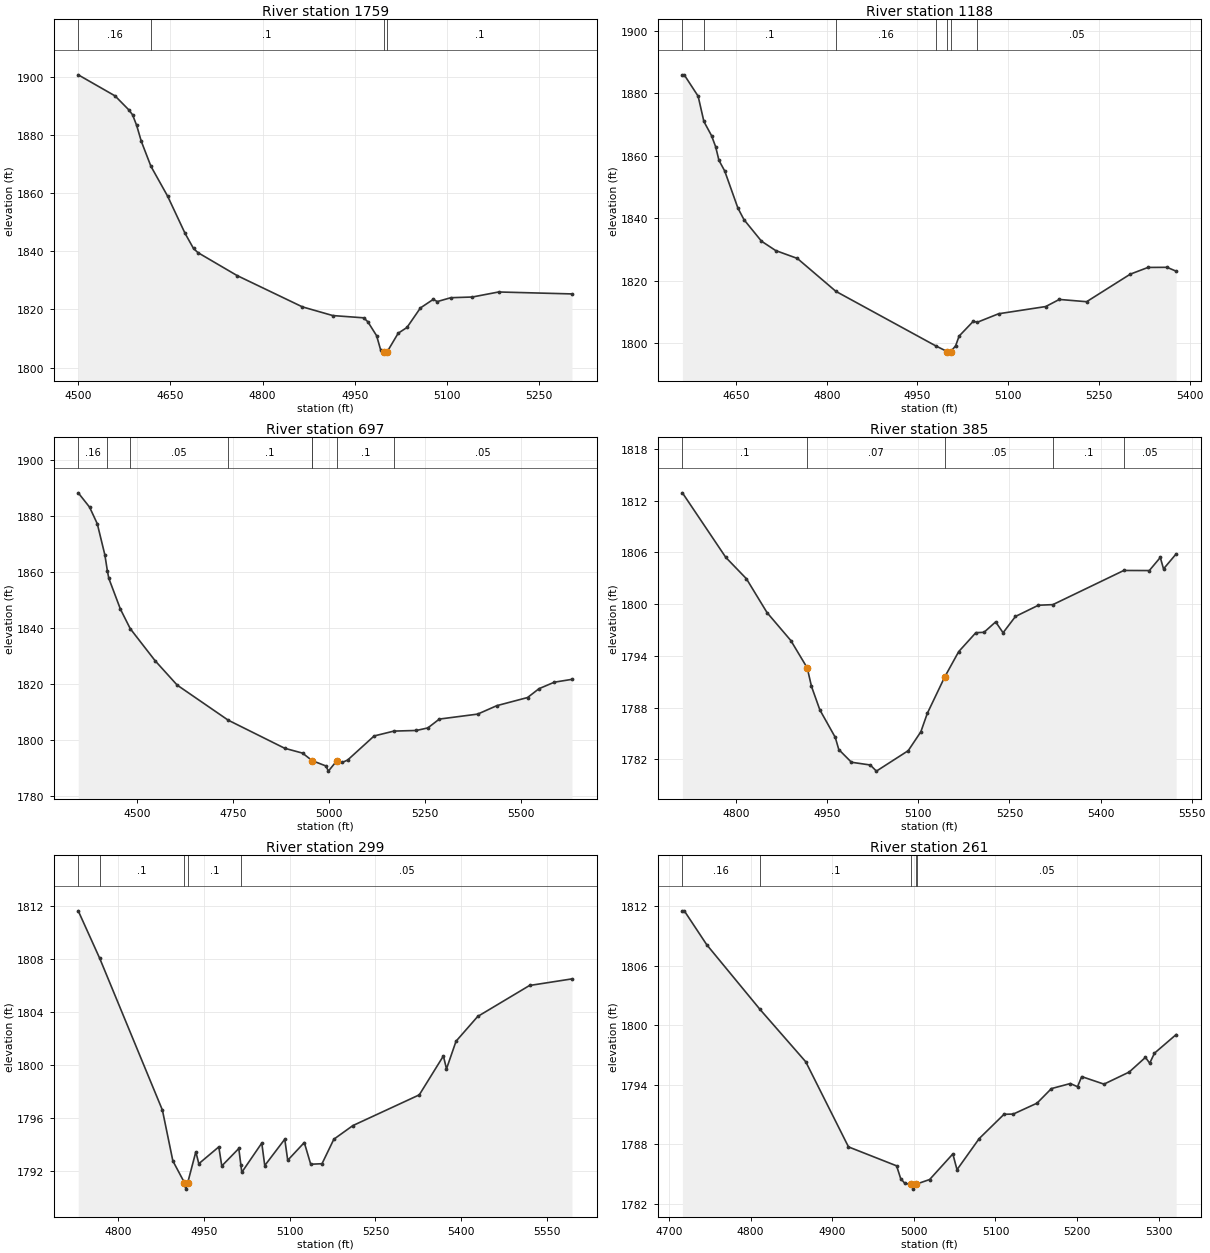
Type RM Length L Ch R = 1 ,1759    ,571,571,571
BEGIN DESCRIPTION:
UNT033 IN NNOGR 4.0
END DESCRIPTION:
XS GIS Cut Line= 2
      2786361.15     10093901.72      2785836.16     10094509.87
#Sta/Elev= 30
    4500 1900.58  4559.9 1893.35  4581.8 1888.66  4588.4 1886.87  4595.1 1883.19
  4602.7  1877.7  4618.3 1869.17  4645.4 1858.93  4673.9 1846.11  4687.6 1840.94
  4694.8 1839.52  4758.4 1831.66  4864.8 1820.89  4914.2 1817.91  4964.6 1817.13
  4971.2 1815.78  4985.5 1810.99  4992.1  1806.1  4996.8 1805.51  4999.5 1805.01
  5002.8 1805.51  5020.6 1811.84  5034.9 1813.82  5056.8 1820.53  5077.6 1823.46
  5084.3 1822.72  5106.2 1824.04  5141.3 1824.28  5184.1 1826.01  5303.4 1825.34
#Mann= 4 ,-1 , 0
    4500     .16       0  4618.3      .1       0  4996.8     .07       0
  5002.8      .1       0
Bank Sta=4996.8,5002.8
XS Rating Curve= 0 ,0
Exp/Cntr=0.3,0.1

Type RM Length L Ch R = 1 ,1188    ,491,491,491
BEGIN DESCRIPTION:
UNT033 IN NNOGR 3.0
END DESCRIPTION:
XS GIS Cut Line= 3
       2786022.6      10093766.3      2785543.46     10093974.62
      2785408.04     10094235.04
#Sta/Elev= 30
  4561.5  1885.9  4564.5  1885.9  4587.5 1879.05    4597 1870.96  4609.6 1866.44
  4616.4 1862.89  4621.9 1858.52  4631.4 1855.12  4653.2 1843.25  4663.3 1839.52
  4692.2 1832.64  4715.7 1829.64  4751.4 1827.13  4815.2 1816.58  4980.7 1799.08
  4999.2 1797.31  5001.9 1796.81  5005.2 1797.31  5013.1 1799.19  5018.8 1802.27
  5042.2    1807    5049  1806.7    5084 1809.41  5161.9 1811.72  5184.4    1814
  5229.5 1813.27  5301.7 1822.09  5330.9 1824.24  5362.4 1824.28  5377.5 1823.04
#Mann= 7 ,-1 , 0
  4561.5     .16       0    4597      .1       0  4815.2     .16       0
  4980.7      .1       0  4999.2     .07       0  5005.2      .1       0
    5049     .05       0
Bank Sta=4999.2,5005.2
XS Rating Curve= 0 ,0
Exp/Cntr=0.3,0.1

Type RM Length L Ch R = 1 ,697     ,312,312,312
BEGIN DESCRIPTION:
UNT033 IN NNOGR 2.0
END DESCRIPTION:
XS GIS Cut Line= 4
      2786027.85      10093526.7      2785449.71      10093464.2
      2785335.12     10093568.37      2785335.12      10094119.6
#Sta/Elev= 30
  4346.6 1888.26  4376.2 1883.14  4396.3  1877.2  4416.1 1866.06  4422.7 1860.31
  4426.4 1857.68  4456.6  1846.7  4482.2 1839.72  4547.1 1828.26  4604.7 1819.54
  4737.6 1807.02    4885 1796.97  4931.5 1795.24  4956.8 1792.54  4992.5 1790.65
    4999  1788.8  5020.8 1792.49    5035 1791.89  5049.2 1792.77  5118.3 1801.37
  5169.9 1803.11  5228.3 1803.33  5258.3 1804.24  5288.3  1807.4  5388.3 1809.18
  5438.3  1812.2  5518.3  1815.1  5548.3 1818.27  5588.3 1820.59  5634.2  1821.6
#Mann= 8 ,-1 , 0
  4346.6     .16       0  4422.7      .1       0  4482.2     .05       0
  4737.6      .1       0  4956.8     .05       0  4956.8     .07       0
  5020.8      .1       0  5169.9     .05       0
Bank Sta=4956.8,5020.8
XS Rating Curve= 0 ,0
Exp/Cntr=0.3,0.1

Type RM Length L Ch R = 1 ,385     ,86,86,86
BEGIN DESCRIPTION:
Mapping XS 5bec4200
END DESCRIPTION:
XS GIS Cut Line= 3
      2785351.72     10092955.95      2785221.52     10093416.88
      2785320.48     10093735.92
#Sta/Elev= 30
  4711.5  1812.9  4782.9 1805.42  4816.9 1802.94  4850.9 1799.01    4890 1795.78
    4917 1792.61    4924 1790.47  4937.8 1787.74  4963.2 1784.55    4969 1783.14
  4989.8 1781.67  5020.9 1781.35  5030.9 1780.64  5083.3 1783.01  5104.1  1785.2
  5114.7 1787.33  5143.5 1791.57  5166.4 1794.49  5194.7 1796.69  5208.1 1796.73
  5227.3 1797.94  5239.5 1796.68  5259.9 1798.57  5297.7 1799.87  5321.5 1799.94
  5438.3  1803.9  5480.3 1803.89  5498.4 1805.41  5503.7 1804.08  5524.5 1805.82
#Mann= 5 ,-1 , 0
  4711.5      .1       0    4917     .07       0  5143.5     .05       0
  5321.5      .1       0  5438.3     .05       0
Bank Sta=4917,5143.5
XS Rating Curve= 0 ,0
Exp/Cntr=0.3,0.1

Type RM Length L Ch R = 1 ,299     ,38,38,38
BEGIN DESCRIPTION:
Mapping XS 94e23362
END DESCRIPTION:
XS GIS Cut Line= 3
      2785266.65     10092941.36      2785148.17     10093387.97
      2785292.71     10093763.02
#Sta/Elev= 30
  4729.9 1811.64  4767.4 1808.06  4877.2 1796.59  4895.5 1792.75  4915.6 1791.12
  4918.3 1790.62  4921.6 1791.12  4935.7 1793.44  4940.9 1792.54  4975.9 1793.81
  4981.1 1792.37  5010.9 1793.69  5014.4 1792.48  5016.1 1791.89  5051.1  1794.1
  5056.3  1792.4  5091.3 1794.39  5096.5  1792.8  5125.5 1794.14  5136.7  1792.5
  5156.5 1792.54  5177.2 1794.39  5210.5 1795.42  5326.7 1797.74  5368.9 1800.68
  5374.3  1799.7    5391 1801.79  5428.9 1803.66  5519.6    1806  5593.9  1806.5
#Mann= 5 ,-1 , 0
  4729.9     .16       0  4767.4      .1       0  4915.6     .07       0
  4921.6      .1       0  5014.4     .05       0
Bank Sta=4915.6,4921.6
XS Rating Curve= 0 ,0
Exp/Cntr=0.3,0.1

Type RM Length L Ch R = 1 ,261     ,108,108,108
BEGIN DESCRIPTION:
Mapping XS 5bb3e28c
END DESCRIPTION:
XS GIS Cut Line= 3
      2785203.29     10092914.27      2785135.58     10093363.49
      2785171.33     10093509.59
#Sta/Elev= 30
  4716.6 1811.55  4718.9 1811.55  4746.4 1808.13  4811.6 1801.61  4867.7 1796.32
    4920 1787.74  4978.9 1785.83  4983.9 1784.55  4989.1 1784.05  4996.2 1783.98
    4999 1783.48  5002.2 1783.98  5003.3 1783.99  5019.4 1784.45  5047.8 1787.03
  5052.9 1785.44  5080.1 1788.58  5110.5 1791.03  5121.8 1791.05  5150.9 1792.15
  5168.5 1793.62  5191.7 1794.13  5200.5 1793.81  5205.6 1794.83  5232.9 1794.07
  5263.8 1795.29  5283.7 1796.77  5288.9 1796.18  5294.7 1797.19  5321.3 1799.07
#Mann= 5 ,-1 , 0
  4716.6     .16       0  4811.6      .1       0  4996.2     .07       0
  5002.2      .1       0  5003.3     .05       0
Bank Sta=4996.2,5002.2
XS Rating Curve= 0 ,0
Exp/Cntr=0.3,0.1

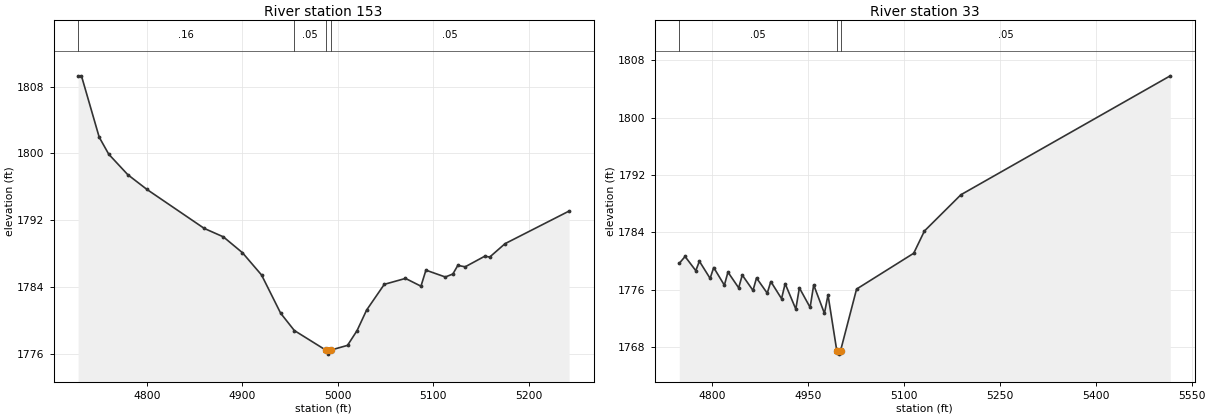
Type RM Length L Ch R = 1 ,153     ,120,120,120
BEGIN DESCRIPTION:
Mapping XS a83a6b93
END DESCRIPTION:
XS GIS Cut Line= 3
      2785054.85     10092911.67      2785053.55     10093235.89
      2785106.96      10093418.1
#Sta/Elev= 30
  4728.1 1809.28  4731.6 1809.28  4750.2 1801.93  4760.2 1799.89  4780.2 1797.43
  4800.2 1795.67  4860.2    1791  4880.2 1789.99  4900.2 1788.09  4920.2 1785.42
  4940.2 1780.84  4954.5 1778.77  4987.2 1776.44  4989.9 1775.94  4993.2 1776.44
  5010.2 1776.99  5020.2 1778.76  5030.2 1781.22  5048.7  1784.3  5070.9 1785.01
  5087.1 1784.08  5092.3    1786  5112.6 1785.18  5120.5 1785.54  5125.7 1786.57
  5133.4  1786.4  5153.9 1787.67  5159.1 1787.57  5175.1 1789.17  5242.2 1793.08
#Mann= 4 ,-1 , 0
  4728.1     .16       0  4954.5     .05       0  4987.2     .04       0
  4993.2     .05       0
Bank Sta=4987.2,4993.2
XS Rating Curve= 0 ,0
Exp/Cntr=0.3,0.1

Type RM Length L Ch R = 1 ,33      ,0,0,0
BEGIN DESCRIPTION:
UNT033 IN NNOGR 1.0
END DESCRIPTION:
XS GIS Cut Line= 2
      2784829.93     10092969.44      2785173.57     10093656.72
#Sta/Elev= 30
  4748.1 1779.66  4757.2 1780.62    4774 1778.64  4779.6 1779.96  4796.4 1777.56
    4802 1779.08  4818.7 1776.61  4824.3 1778.44  4841.1 1776.24  4846.7 1778.03
  4863.5 1775.88    4869 1777.62  4885.8  1775.5  4891.4 1777.12  4908.2 1774.73
  4913.8 1776.83  4930.5 1773.28  4936.1 1776.24  4952.9 1773.51  4958.5 1776.65
  4975.3 1772.68  4980.9 1775.26  4994.6 1767.49  4997.4 1766.99  5000.6 1767.49
  5025.6 1776.07    5115 1781.07  5131.8 1784.18  5188.9 1789.24  5516.5 1805.84
#Mann= 3 ,-1 , 0
  4748.1     .05       0  4994.6     .04       0  5000.6     .05       0
Bank Sta=4994.6,5000.6
XS Rating Curve= 0 ,0
Exp/Cntr=0.3,0.1

Chan Stop Cuts=-1
Use User Specified Reach Order=0
Composite Channel Slope=5