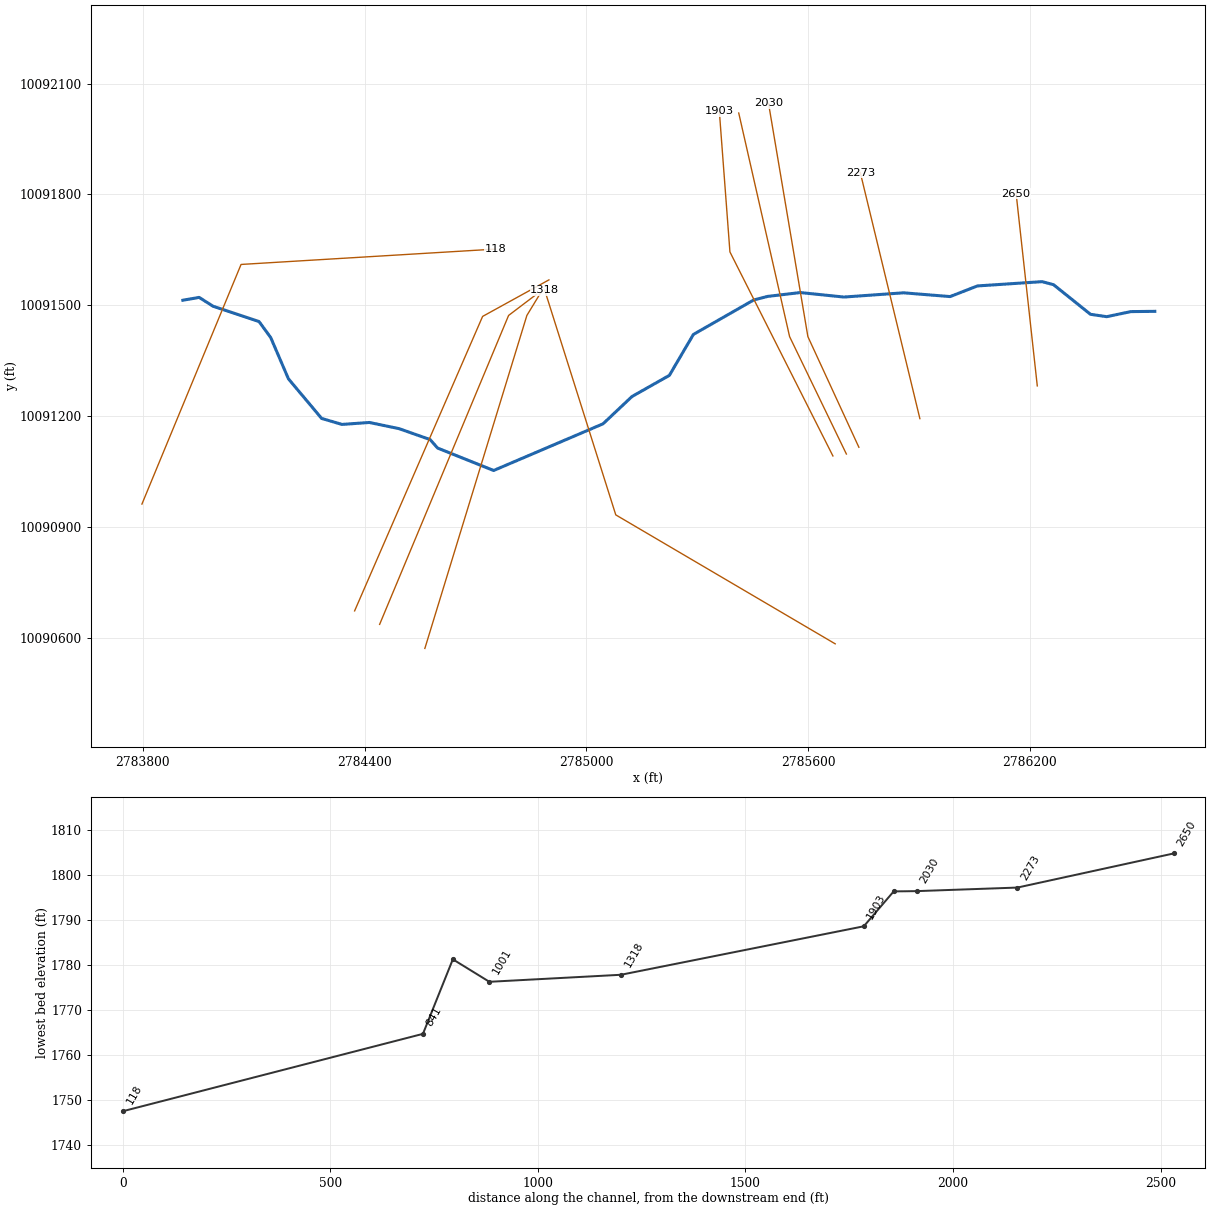
--- UNT034 IN NNOGR.prj (project) ---

Proj Title=UNT034 IN NNOGR Base Level Engineering
Current Plan=p01
Default Exp/Contr=0.3,0.1
English Units
Geom File=g01
Flow File=f01
Plan File=p01
Y Axis Title=Elevation
X Axis Title(PF)=Main Channel Distance
X Axis Title(XS)=Station
BEGIN DESCRIPTION:
UNT034 IN NNOGR
END DESCRIPTION:
DSS Export Rating Curves= 0
DSS Export Rating Curve Sorted= 0
DSS Export Volume Flow Curves= 0
DXF OffsetX= 0
DXF OffsetY= 0
DXF ScaleX= 1
DXF ScaleY= 10

--- UNT034 IN NNOGR.p01 (plan) ---

Plan Title=Multiple Run
Short Identifier=Multiple
Geom File=g01
Flow File=f01
Subcritical Flow
K Sum by GR= 0
Std Step Tol= 0.01
Critical Tol= 0.01
Num of Std Step Trials= 20
Max Error Tol= 0.3
Flow Tol Ratio= 0.001
Split Flow NTrial= 30
Split Flow Tol= 0.02
Split Flow Ratio= 0.02
Log Output Level= 0
Friction Slope Method= 1
Unsteady Friction Slope Method= 2
Unsteady Bridges Friction Slope Method= 1
Parabolic Critical Depth
Global Vel Dist=  1 , 1 , 1
Global Log Level= 0
CheckData=True
Encroach Param= -1, 0, 0, 0
BEGIN DESCRIPTION:
Multiple Run
END DESCRIPTION:

--- UNT034 IN NNOGR.f01 (steady flow) ---

Flow Title=Multiple
Program Version=4.10
Number of Profiles= 7
Profile Names=10-year,25-year,50-year,1pct_min,100-year,1pct_plu,500-year
River Rch & RM=UNT034 IN NNOGR,Reach-1         ,2650
     745    1081    1375    1283    1735    2346    2769
Boundary for River Rch & Prof#=UNT034 IN NNOGR,Reach-1         , 1
Up Type= 0
Dn Type= 3
Dn Slope=0.024
Boundary for River Rch & Prof#=UNT034 IN NNOGR,Reach-1         , 2
Up Type= 0
Dn Type= 3
Dn Slope=0.024
Boundary for River Rch & Prof#=UNT034 IN NNOGR,Reach-1         , 3
Up Type= 0
Dn Type= 3
Dn Slope=0.024
Boundary for River Rch & Prof#=UNT034 IN NNOGR,Reach-1         , 4
Up Type= 0
Dn Type= 3
Dn Slope=0.024
Boundary for River Rch & Prof#=UNT034 IN NNOGR,Reach-1         , 5
Up Type= 0
Dn Type= 3
Dn Slope=0.024
Boundary for River Rch & Prof#=UNT034 IN NNOGR,Reach-1         , 6
Up Type= 0
Dn Type= 3
Dn Slope=0.024
Boundary for River Rch & Prof#=UNT034 IN NNOGR,Reach-1         , 7
Up Type= 0
Dn Type= 3
Dn Slope=0.024
DSS Import GetInterval= 0
DSS Import GetPeak= 0
DSS Import FillOption= 0

--- UNT034 IN NNOGR.g01 (geometry) ---

Geom Title=Existing Conditions
Program Version=4.10

River Reach=UNT034 IN NNOGR ,Reach-1
Reach XY= 30
      2786538.47     10091483.73      2786473.63       10091483.
      2786408.36     10091469.28      2786364.44     10091475.72
       2786264.6     10091555.83      2786233.53     10091564.06
      2786058.51     10091552.46      2785984.71     10091523.68
      2785858.52     10091533.86      2785697.16      10091522.4
      2785579.11     10091534.56      2785490.91     10091524.14
      2785453.06     10091514.42      2785289.96     10091421.21
      2785224.93     10091310.42       2785123.9     10091253.31
      2785045.43     10091179.35       2784749.4     10091053.05
      2784597.66     10091113.81      2784577.52     10091136.73
      2784493.52     10091166.27      2784413.14     10091182.99
      2784338.98     10091177.73      2784283.92     10091193.94
      2784194.14     10091301.13      2784146.11      10091412.9
      2784114.54     10091456.12      2783990.06     10091497.62
       2783952.5     10091521.47      2783908.47     10091513.73

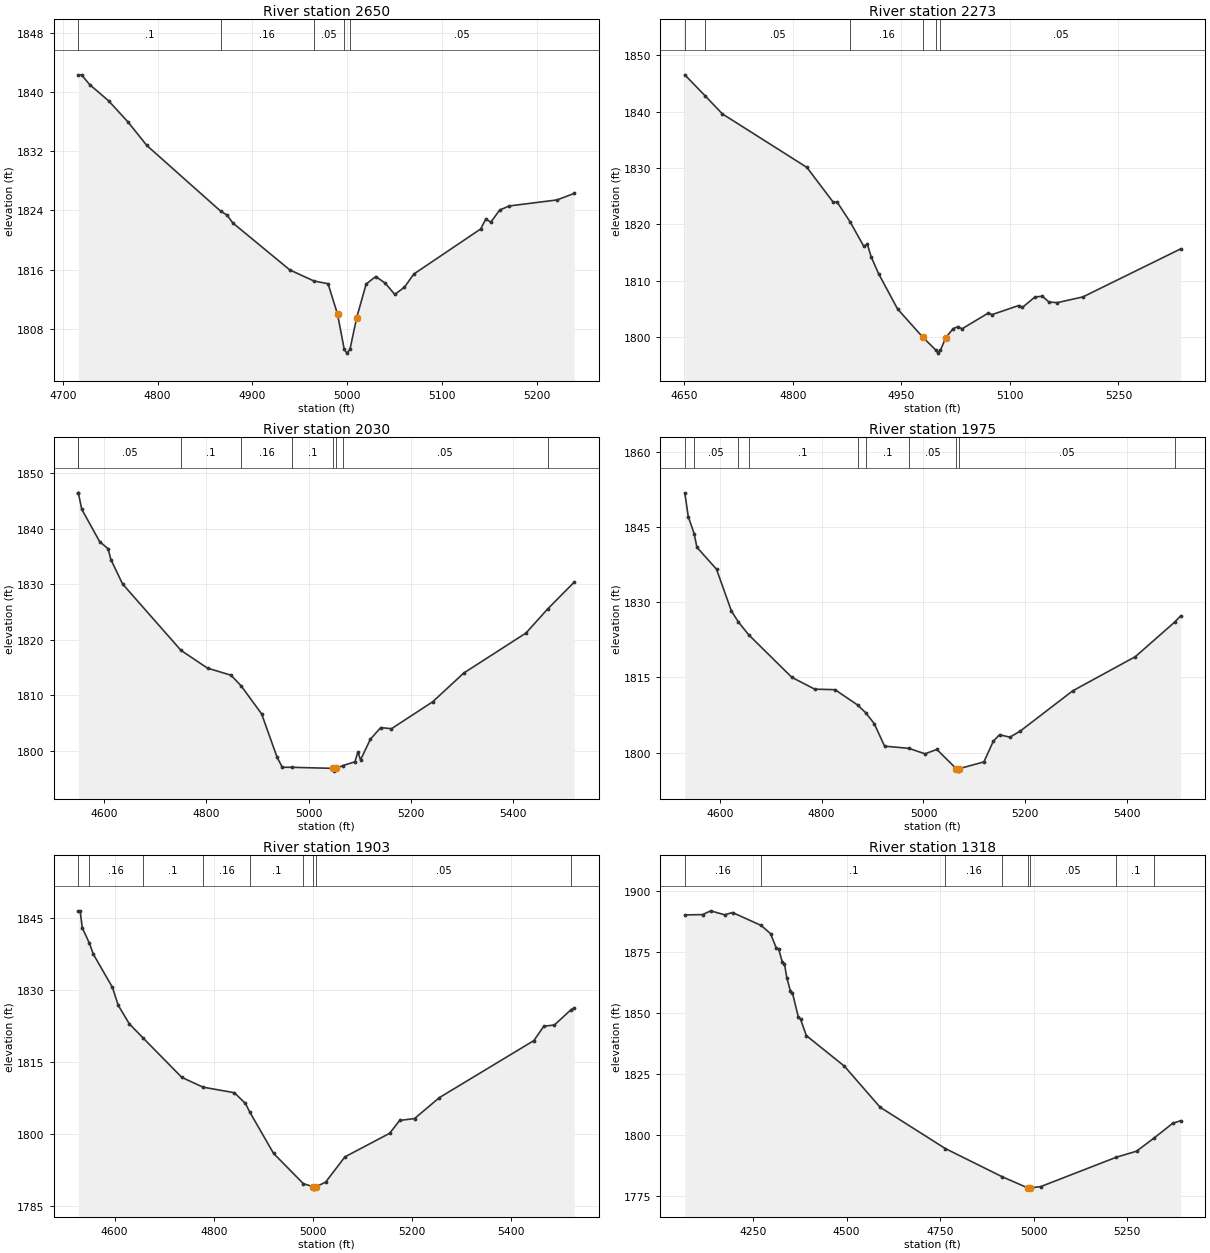
Type RM Length L Ch R = 1 ,2650    ,377,377,377
BEGIN DESCRIPTION:
UNT034 IN NNOGR 6.0
END DESCRIPTION:
XS GIS Cut Line= 2
      2786220.54     10091281.93      2786163.35      10091801.8
#Sta/Elev= 30
  4716.3 1842.32  4719.7 1842.32  4728.2 1841.01  4748.3  1838.8  4768.4 1835.99
  4788.5 1832.78  4866.3 1823.91  4873.2 1823.36  4879.1 1822.32  4939.4 1815.95
  4964.8 1814.46  4979.7 1814.09  4989.7 1809.98  4996.8 1805.21  4999.5 1804.71
  5002.8 1805.21  5009.9  1809.5  5019.9 1814.05    5030 1815.06    5040 1814.17
  5050.1 1812.64  5060.3 1813.62  5070.2  1815.4  5140.6 1821.48  5146.2 1822.85
  5151.3  1822.4  5160.8 1824.05  5170.8  1824.6  5221.1 1825.41  5239.3 1826.29
#Mann= 5 ,-1 , 0
  4716.3      .1       0  4866.3     .16       0  4964.8     .05       0
  4996.8    .035       0  5002.8     .05       0
Bank Sta=4989.7,5009.9
XS Rating Curve= 0 ,0
Exp/Cntr=0.3,0.1

Type RM Length L Ch R = 1 ,2273    ,243,243,243
BEGIN DESCRIPTION:
UNT034 IN NNOGR 5.0
END DESCRIPTION:
XS GIS Cut Line= 2
      2785902.83     10091193.39      2785741.54     10091859.34
#Sta/Elev= 30
  4650.8 1846.53  4679.3 1842.75  4702.6 1839.61  4819.5  1830.1  4856.1 1823.89
  4861.3 1823.95  4879.6 1820.36    4898 1816.12  4903.1 1816.46  4908.4  1814.2
  4918.7 1811.21  4944.9 1804.96  4979.7 1799.96    4998 1797.63  5000.7 1797.13
    5004 1797.63  5011.3 1799.83  5021.6 1801.48  5028.6 1801.84  5033.7 1801.43
  5070.4 1804.26  5075.5 1803.97  5112.2 1805.58  5117.4 1805.25  5134.7  1807.1
    5145 1807.23    5154  1806.2  5165.6 1806.09    5201 1807.11    5336 1815.63
#Mann= 6 ,-1 , 0
  4650.8      .1       0  4679.3     .05       0  4879.6     .16       0
  4979.7     .05       0    4998    .035       0    5004     .05       0
Bank Sta=4979.7,5011.3
XS Rating Curve= 0 ,0
Exp/Cntr=0.3,0.1

Type RM Length L Ch R = 1 ,2030    ,55,55,55
BEGIN DESCRIPTION:
Mapping XS bdf17bf4
END DESCRIPTION:
XS GIS Cut Line= 3
      2785737.78     10091115.86      2785599.77     10091415.32
      2785493.23     10092046.76
#Sta/Elev= 30
  4549.4  1846.5  4549.5 1846.46  4556.1 1843.54  4591.1 1837.71  4607.6 1836.42
  4613.1 1834.47    4636 1830.07  4750.3  1818.1  4802.2  1814.9  4848.1 1813.63
    4868  1811.7    4908 1806.66  4938.4 1798.81  4948.5 1797.04  4967.7 1797.03
  5046.9 1796.84  5049.7 1796.34  5052.9 1796.84  5066.7 1797.33  5090.5 1798.02
  5096.5 1799.81  5101.5 1798.35  5120.9 1802.12  5141.2 1804.19    5162 1803.98
  5242.6 1808.83  5303.5 1814.02  5425.2 1821.23  5467.4 1825.54  5519.5  1830.4
#Mann= 9 ,-1 , 0
  4549.4      .1       0  4549.5     .05       0  4750.3      .1       0
    4868     .16       0  4967.7      .1       0  5046.9     .07       0
  5052.9      .1       0  5066.7     .05       0  5467.4      .1       0
Bank Sta=5046.9,5052.9
XS Rating Curve= 0 ,0
Exp/Cntr=0.3,0.1

Type RM Length L Ch R = 1 ,1975    ,72,72,72
BEGIN DESCRIPTION:
Mapping XS ce97c400
END DESCRIPTION:
XS GIS Cut Line= 3
      2785703.94     10091097.61      2785550.29     10091415.32
      2785412.64     10092020.45
#Sta/Elev= 30
  4531.4 1851.87  4538.2 1847.12  4549.7 1843.74  4555.2 1840.99  4593.7 1836.61
  4622.9 1828.27  4636.3 1826.12  4656.7 1823.53  4741.5 1815.02  4786.6 1812.65
  4826.3 1812.55  4870.7 1809.49  4886.4 1807.96  4903.2 1805.79  4923.7 1801.27
  4971.5 1800.83  5002.9 1799.74  5026.3 1800.61  5064.3 1796.78    5067 1796.28
  5070.3 1796.78  5118.6 1798.12  5137.2 1802.27  5149.3 1803.55  5169.8 1803.06
  5190.5 1804.32  5292.9 1812.31  5416.1 1819.15  5493.1 1826.04  5504.9 1827.27
#Mann= 10 ,-1 , 0
  4531.4      .1       0  4549.7     .05       0  4636.3     .16       0
  4656.7      .1       0  4870.7     .16       0  4886.4      .1       0
  4971.5     .05       0  5064.3    .035       0  5070.3     .05       0
  5493.1      .1       0
Bank Sta=5064.3,5070.3
XS Rating Curve= 0 ,0
Exp/Cntr=0.3,0.1

Type RM Length L Ch R = 1 ,1903    ,585,585,585
BEGIN DESCRIPTION:
UNT034 IN NNOGR 4.0
END DESCRIPTION:
XS GIS Cut Line= 3
      2785667.49     10091092.38      2785388.83     10091644.48
      2785360.19     10092024.67
#Sta/Elev= 30
  4526.9 1846.58  4530.5 1846.58  4534.9 1843.04  4549.4 1839.78  4557.2 1837.53
  4595.6 1830.63  4607.4 1826.87  4629.7 1823.01  4657.2 1820.09  4735.6 1811.84
  4778.4  1809.8  4841.5 1808.65  4863.8 1806.41  4872.8 1804.57  4920.5    1796
  4980.6 1789.68  5000.2 1789.04  5002.9 1788.54  5006.2 1789.04  5025.5    1790
  5064.5 1795.28  5154.6 1800.18  5174.7 1802.86  5204.8 1803.26  5254.9 1807.63
  5445.4 1819.52  5465.5 1822.52  5486.8 1822.77  5519.4 1825.88  5526.6 1826.34
#Mann= 9 ,-1 , 0
  4526.9      .1       0  4549.4     .16       0  4657.2      .1       0
  4778.4     .16       0  4872.8      .1       0  4980.6     .05       0
  5000.2    .035       0  5006.2     .05       0  5519.4      .1       0
Bank Sta=5000.2,5006.2
XS Rating Curve= 0 ,0
Exp/Cntr=0.3,0.1

Type RM Length L Ch R = 1 ,1318    ,317,317,317
BEGIN DESCRIPTION:
UNT034 IN NNOGR 3.0
END DESCRIPTION:
XS GIS Cut Line= 3
      2785673.64     10090584.01      2785079.91     10090932.95
      2784887.78     10091540.52
#Sta/Elev= 30
  4067.1  1890.3  4114.8 1890.42  4136.3 1891.97  4173.4 1890.35  4194.9 1891.27
  4271.5 1885.95  4296.4 1882.59  4312.1  1876.6  4317.9 1876.37  4327.7 1871.08
  4333.5 1870.33  4339.9 1864.54  4349.2 1859.22    4355 1858.28  4370.7 1848.39
  4376.5 1847.57  4392.1 1840.77  4493.7 1828.26  4589.4 1811.39  4763.8 1794.43
  4915.7 1782.87  4984.3 1778.28  4987.1 1777.78  4990.3 1778.28  5018.8 1778.81
    5221 1790.87  5275.2 1793.35  5322.7 1798.83  5372.1 1804.82    5393 1805.84
#Mann= 8 ,-1 , 0
  4067.1     .16       0  4271.5      .1       0  4763.8     .16       0
  4915.7     .05       0  4984.3    .035       0  4990.3     .05       0
    5221      .1       0  5322.7     .16       0
Bank Sta=4984.3,4990.3
XS Rating Curve= 0 ,0
Exp/Cntr=0.3,0.1

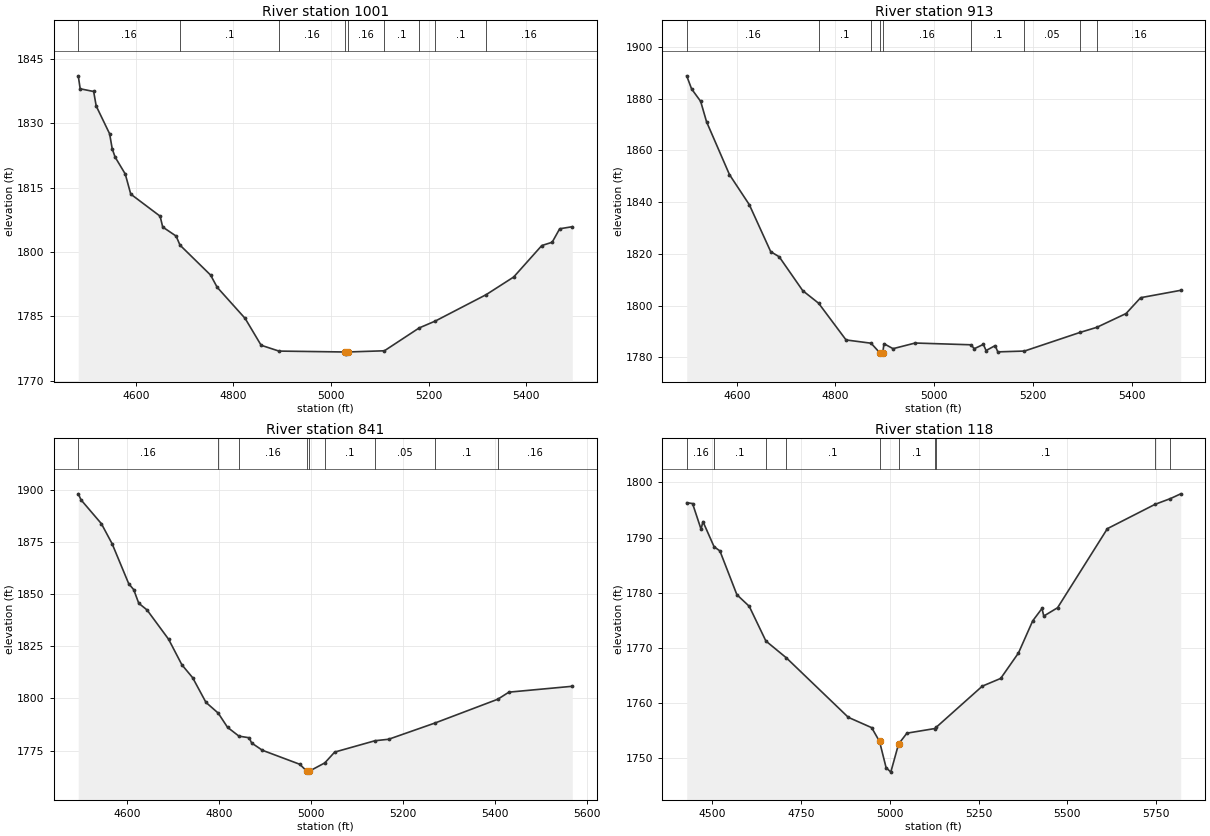
Type RM Length L Ch R = 1 ,1001    ,88,88,88
BEGIN DESCRIPTION:
Mapping XS 1e6ef0e3
END DESCRIPTION:
XS GIS Cut Line= 3
       2784563.3     10090571.53      2784839.35     10091472.61
      2784875.79     10091532.47
#Sta/Elev= 30
    4482 1841.05    4486 1838.03  4513.6  1837.4  4518.8 1834.02  4546.3 1827.55
  4551.6 1824.07  4557.5 1822.13  4578.4 1818.17  4589.6  1813.5  4649.8 1808.35
  4655.1 1805.83  4682.6 1803.72  4690.5 1801.62  4753.3 1794.63  4766.7  1791.8
  4824.1 1784.53  4856.8 1778.29  4893.3 1776.93  5028.1 1776.72  5030.8 1776.22
  5034.1 1776.72  5109.5    1777  5180.9 1782.33  5213.7 1783.92    5318 1790.07
  5374.4 1794.18    5432 1801.51  5453.3 1802.28  5468.7 1805.42  5494.5  1805.9
#Mann= 9 ,-1 , 0
    4482     .16       0  4690.5      .1       0  4893.3     .16       0
  5028.1     .07       0  5034.1     .16       0  5109.5      .1       0
  5180.9     .05       0  5213.7      .1       0    5318     .16       0
Bank Sta=5028.1,5034.1
XS Rating Curve= 0 ,0
Exp/Cntr=0.3,0.1

Type RM Length L Ch R = 1 ,913     ,72,72,72
BEGIN DESCRIPTION:
Mapping XS 447cd3fe
END DESCRIPTION:
XS GIS Cut Line= 3
       2784440.9     10090636.64      2784789.88     10091472.61
      2784865.41     10091529.91
#Sta/Elev= 30
  4498.7 1888.77  4508.6 1883.72    4527 1878.89  4538.9 1871.02  4585.4 1850.57
  4625.6 1838.95  4668.9 1820.81  4686.1 1818.83  4733.8 1805.73  4765.9 1800.89
  4821.5 1786.69  4872.2 1785.43  4889.9 1781.71  4892.7 1781.21  4895.9 1781.71
  4898.3 1785.24  4916.7 1783.32  4961.5  1785.5  5074.4 1784.82  5081.3 1783.31
  5099.7 1784.98  5105.1 1782.59  5123.5  1784.5  5128.9 1782.08  5182.9  1782.4
  5295.3 1789.59  5329.5 1791.57  5388.7  1796.9  5418.2 1803.02  5499.4 1805.87
#Mann= 9 ,-1 , 0
  4498.7     .16       0  4765.9      .1       0  4872.2     .16       0
  4889.9     .07       0  4895.9     .16       0  5074.4      .1       0
  5182.9     .05       0  5295.3      .1       0  5329.5     .16       0
Bank Sta=4889.9,4895.9
XS Rating Curve= 0 ,0
Exp/Cntr=0.3,0.1

Type RM Length L Ch R = 1 ,841     ,723,723,723
BEGIN DESCRIPTION:
UNT034 IN NNOGR 2.0
END DESCRIPTION:
XS GIS Cut Line= 3
      2784373.21     10090673.13      2784719.56       10091470.
      2784899.06     10091568.86
#Sta/Elev= 30
  4493.8 1897.98  4499.9 1895.08  4544.1 1883.68  4567.5 1874.04  4603.5 1854.93
  4614.4 1852.07  4625.3 1845.57  4643.3 1842.36  4690.2 1828.32  4719.1 1816.08
  4742.5  1809.9  4771.4 1798.08    4798 1792.95  4818.3 1786.14  4843.1 1781.91
  4865.2 1781.14  4870.7 1778.62  4894.1 1775.14  4975.4 1768.42  4990.4 1765.17
  4993.1 1764.67  4996.4 1765.17  5029.7 1769.09  5051.2 1774.27    5139 1779.72
  5168.4 1780.41  5269.8 1788.24  5405.6 1799.58  5429.9 1802.98  5567.6 1805.79
#Mann= 9 ,-1 , 0
  4493.8     .16       0    4798      .1       0  4843.1     .16       0
  4990.4     .07       0  4996.4     .16       0  5029.7      .1       0
    5139     .05       0  5269.8      .1       0  5405.6     .16       0
Bank Sta=4990.4,4996.4
XS Rating Curve= 0 ,0
Exp/Cntr=0.3,0.1

Type RM Length L Ch R = 1 ,118     ,0,0,0
BEGIN DESCRIPTION:
UNT034 IN NNOGR 1.0
END DESCRIPTION:
XS GIS Cut Line= 3
      2783797.69     10090962.19      2784065.92     10091610.63
      2784754.74     10091652.22
#Sta/Elev= 30
  4427.8 1796.32  4444.3 1796.17  4468.2 1791.53  4473.6  1792.9  4504.9 1788.35
  4521.4 1787.58  4569.2 1779.65    4604 1777.55  4650.9 1771.26  4708.4 1768.22
  4883.1 1757.43  4948.9 1755.56  4971.1 1753.06  4989.5 1748.33  5002.8  1747.5
  5024.7 1752.59  5048.2 1754.56  5126.1 1755.39  5130.5 1755.61  5260.6 1763.08
  5312.4 1764.48  5362.5 1769.09  5402.6 1774.91  5428.8 1777.16  5433.8 1775.78
  5472.7 1777.29    5613 1791.62  5747.1 1796.02  5790.7 1797.07  5819.6 1797.93
#Mann= 10 ,-1 , 0
  4427.8     .16       0  4504.9      .1       0  4650.9     .16       0
  4708.4      .1       0  4971.1     .07       0  5024.7      .1       0
  5126.1     .05       0  5130.5      .1       0  5747.1     .16       0
  5790.7      .1       0
Bank Sta=4971.1,5024.7
XS Rating Curve= 0 ,0
Exp/Cntr=0.3,0.1

Chan Stop Cuts=-1
Use User Specified Reach Order=0
Composite Channel Slope=5