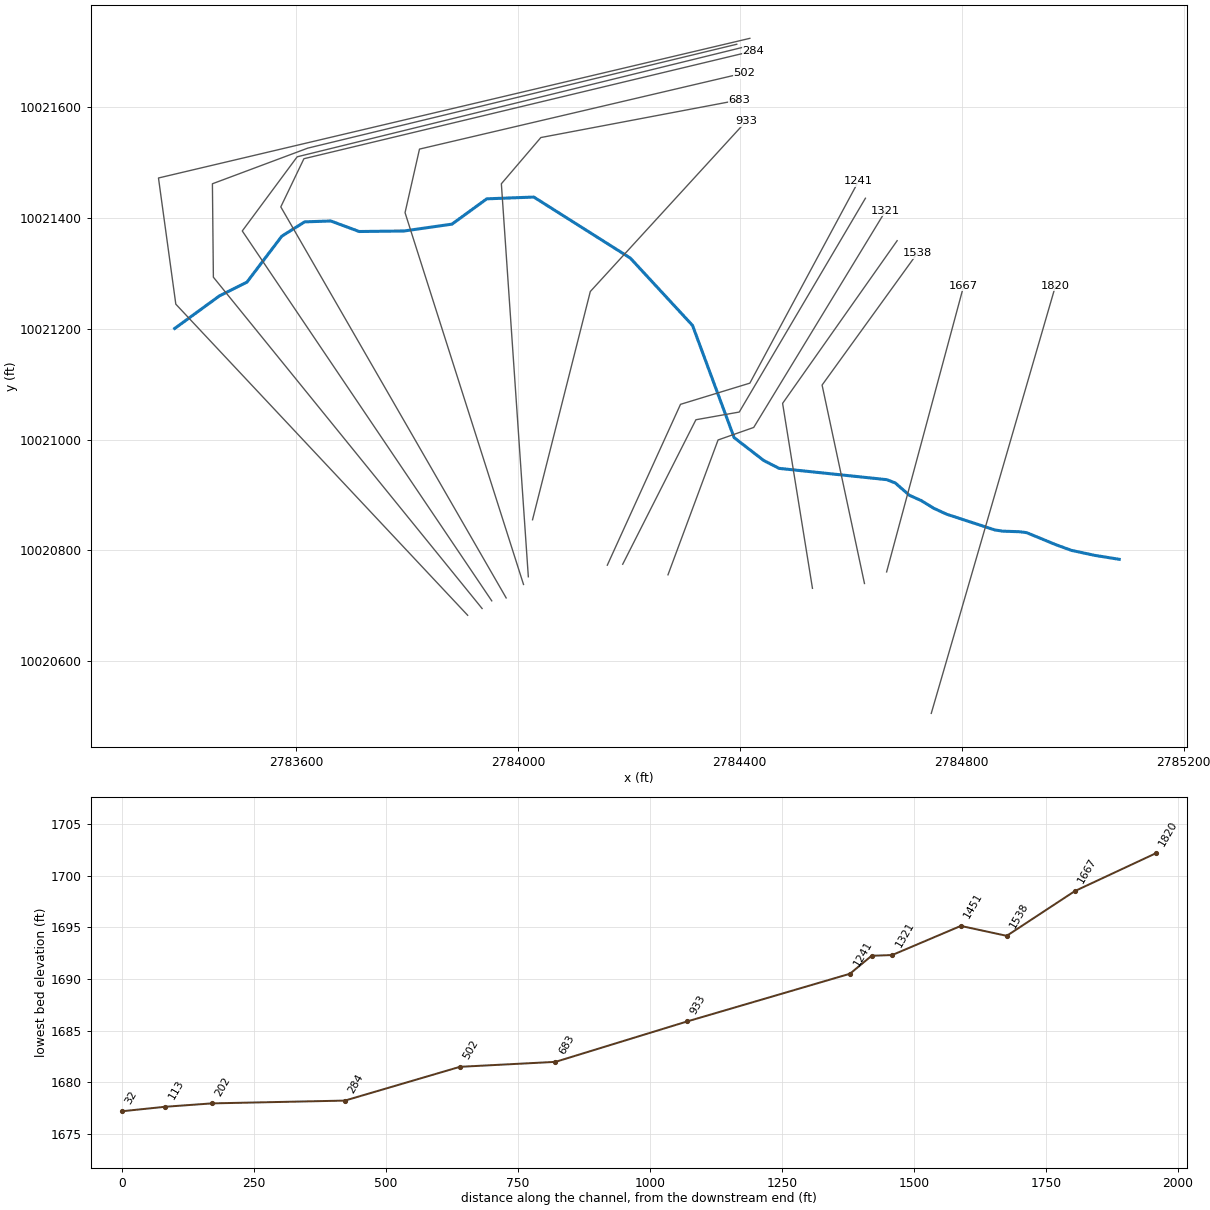
--- UNT034 IN SNOGR.prj (project) ---

Proj Title=UNT034 IN SNOGR Base Level Engineering
Current Plan=p01
Default Exp/Contr=0.3,0.1
English Units
Geom File=g01
Flow File=f01
Plan File=p01
Y Axis Title=Elevation
X Axis Title(PF)=Main Channel Distance
X Axis Title(XS)=Station
BEGIN DESCRIPTION:
UNT034 IN SNOGR
END DESCRIPTION:
DSS File=dss
DSS Export Rating Curves= 0
DSS Export Rating Curve Sorted= 0
DSS Export Volume Flow Curves= 0
DXF OffsetX= 0
DXF OffsetY= 0
DXF ScaleX= 1
DXF ScaleY= 10

--- UNT034 IN SNOGR.p01 (plan) ---

Plan Title=Multiple Run
Program Version=4.10
Short Identifier=Multiple Run
Geom File=g01
Flow File=f01
Subcritical Flow
K Sum by GR= 0
Std Step Tol= 0.01
Critical Tol= 0.01
Num of Std Step Trials= 20
Max Error Tol= 0.3
Flow Tol Ratio= 0.001
Split Flow NTrial= 30
Split Flow Tol= 0.02
Split Flow Ratio= 0.02
Log Output Level= 0
Friction Slope Method= 1
Unsteady Friction Slope Method= 2
Unsteady Bridges Friction Slope Method= 1
Parabolic Critical Depth
Global Vel Dist= 1 , 1 , 1
Global Log Level= 0
CheckData=True
Encroach Param=-1 ,0,0, 0
BEGIN DESCRIPTION:
Multiple Run
END DESCRIPTION:
Computation Interval=1HOUR
Output Interval=1HOUR
Run HTab= 0
Run UNet= 0
Run PostProcess= 0
Run WQNet= 0
UNET Theta= 1
UNET Theta Warmup= 1
UNET ZTol= 0.02
UNET ZSATol= 0.05
UNET MxIter= 20
UNET MaxInSteps= 0
UNET DtIC= 0
UNET DtMin= 0
UNET MaxCRTS= 20
UNET WFStab= 2
UNET SFStab= 1
UNET WFX= 1
UNET SFX= 1
UNET DSS MLevel= 4
UNET DZMax Abort= 100
UNET Convert EG Bridges= 0
UNET Use Existing IB Tables=-1
UNET Froude Reduction=False
UNET Froude Limit= 1
UNET Froude Power= 10
UNET Time Slicing=0,0, 5
UNET Junction Losses=0
Instantaneous Interval=1HOUR
DSS File=dss
Write IC File= 0
Write IC File at Sim End=0
Echo Input=False
Echo Parameters=False
Echo Output=False
Write Detailed= 0
WQ AD Non Conservative
WQ ULTIMATE=-1
WQ Max Comp Step=1HOUR
WQ Output Interval=15MIN
WQ Output Selected Increments= 0
WQ Output face flow=0
WQ Output face velocity=0
WQ Output face area=0
WQ Output face dispersion=0
WQ Output cell volume=0
WQ Output cell surface area=0
WQ Output cell continuity=0
WQ Output cumulative cell continuity=0
WQ Output face conc=0
WQ Output face dconc_dx=0
WQ Output face courant=0
WQ Output face peclet=0
WQ Output face adv mass=0
WQ Output face disp mass=0
WQ Output cell mass=0
WQ Output cell source sink temp=0
WQ Output cell source sink nsm=0
WQ Output MaxMinRange=-1
WQ Daily Max Min Mean=-1
WQ Daily Range=0
WQ Daily Time=0
WQ Create Restart=0
WQ Fixed Restart=0
WQ System Summary=0
WQ Use Fixed Temperature=0
Sorting and Armoring Iterations= 10
XS Update Threshold= 0.02
Hydraulics Update Threshold= 0.02
Energy Slope Method= 1
Volume Change Method= 0
XS Weighting Method= 0
Number of US Weighted Cross Sections= 1
Number of DS Weighted Cross Sections= 1
Upstream XS Weight=0.25
Main XS Weight=0.5
Downstream XS Weight=0.25
Number of DS XS's Weighted with US Boundary= 1
Upstream Boundary Weight= 1
Weight of XSs Associated with US Boundary= 0
Number of US XS's Weighted with DS Boundary= 1
Downstream Boundary Weight= 0.5
Weight of XSs Associated with DS Boundary= 0.5
Sediment Output Level= 4
Mass or Volume Output= 0
Output Increment Type= 1
Profile and TS Output Increment= 10
XS Output Flag= 0
XS Output Increment= 10
Disregard all LS=0
Disregard all Conn=0
Disregard all Breaches=0
Disregard all Pumps=0

--- UNT034 IN SNOGR.f01 (steady flow) ---

Flow Title=Multiple
Program Version=4.10
Number of Profiles= 7
Profile Names=10-year,25-year,50-year,1pct_min,100-year,1pct_plu,500-year
River Rch & RM=UNT034 IN SNOGR,Reach-1         ,1820
     344     474     581     524     708     957    1053
Boundary for River Rch & Prof#=UNT034 IN SNOGR,Reach-1         , 1
Up Type= 0
Dn Type= 3
Dn Slope=0.007
Boundary for River Rch & Prof#=UNT034 IN SNOGR,Reach-1         , 2
Up Type= 0
Dn Type= 3
Dn Slope=0.007
Boundary for River Rch & Prof#=UNT034 IN SNOGR,Reach-1         , 3
Up Type= 0
Dn Type= 3
Dn Slope=0.007
Boundary for River Rch & Prof#=UNT034 IN SNOGR,Reach-1         , 4
Up Type= 0
Dn Type= 3
Dn Slope=0.007
Boundary for River Rch & Prof#=UNT034 IN SNOGR,Reach-1         , 5
Up Type= 0
Dn Type= 3
Dn Slope=0.007
Boundary for River Rch & Prof#=UNT034 IN SNOGR,Reach-1         , 6
Up Type= 0
Dn Type= 3
Dn Slope=0.007
Boundary for River Rch & Prof#=UNT034 IN SNOGR,Reach-1         , 7
Up Type= 0
Dn Type= 3
Dn Slope=0.007
DSS Import GetInterval= 0
DSS Import GetPeak= 0
DSS Import FillOption= 0

--- UNT034 IN SNOGR.g01 (geometry) ---

Geom Title=Existing Conditions
Program Version=4.10

River Reach=UNT034 IN SNOGR ,Reach-1
Reach XY= 30
      2785083.93     10020784.02      2785039.05     10020791.29
      2784997.79     10020800.17      2784970.06     10020810.25
      2784917.01     10020832.11      2784903.48     10020833.79
      2784874.04     10020834.77      2784859.88      10020836.9
      2784773.09     10020865.23      2784749.46     10020876.12
      2784726.91     10020889.97      2784705.81     10020899.37
      2784680.12     10020921.73      2784664.81     10020927.61
      2784470.86     10020947.97      2784443.11     10020962.16
      2784389.73     10021003.42      2784314.78      10021205.6
      2784202.61     10021327.02      2784028.69     10021437.03
      2783943.88     10021433.82      2783881.18     10021388.21
      2783794.73     10021375.86      2783713.97     10021374.91
      2783662.67     10021393.91      2783615.58     10021392.28
      2783574.41     10021366.47      2783511.61     10021283.71
      2783462.13     10021258.94      2783381.38     10021200.11

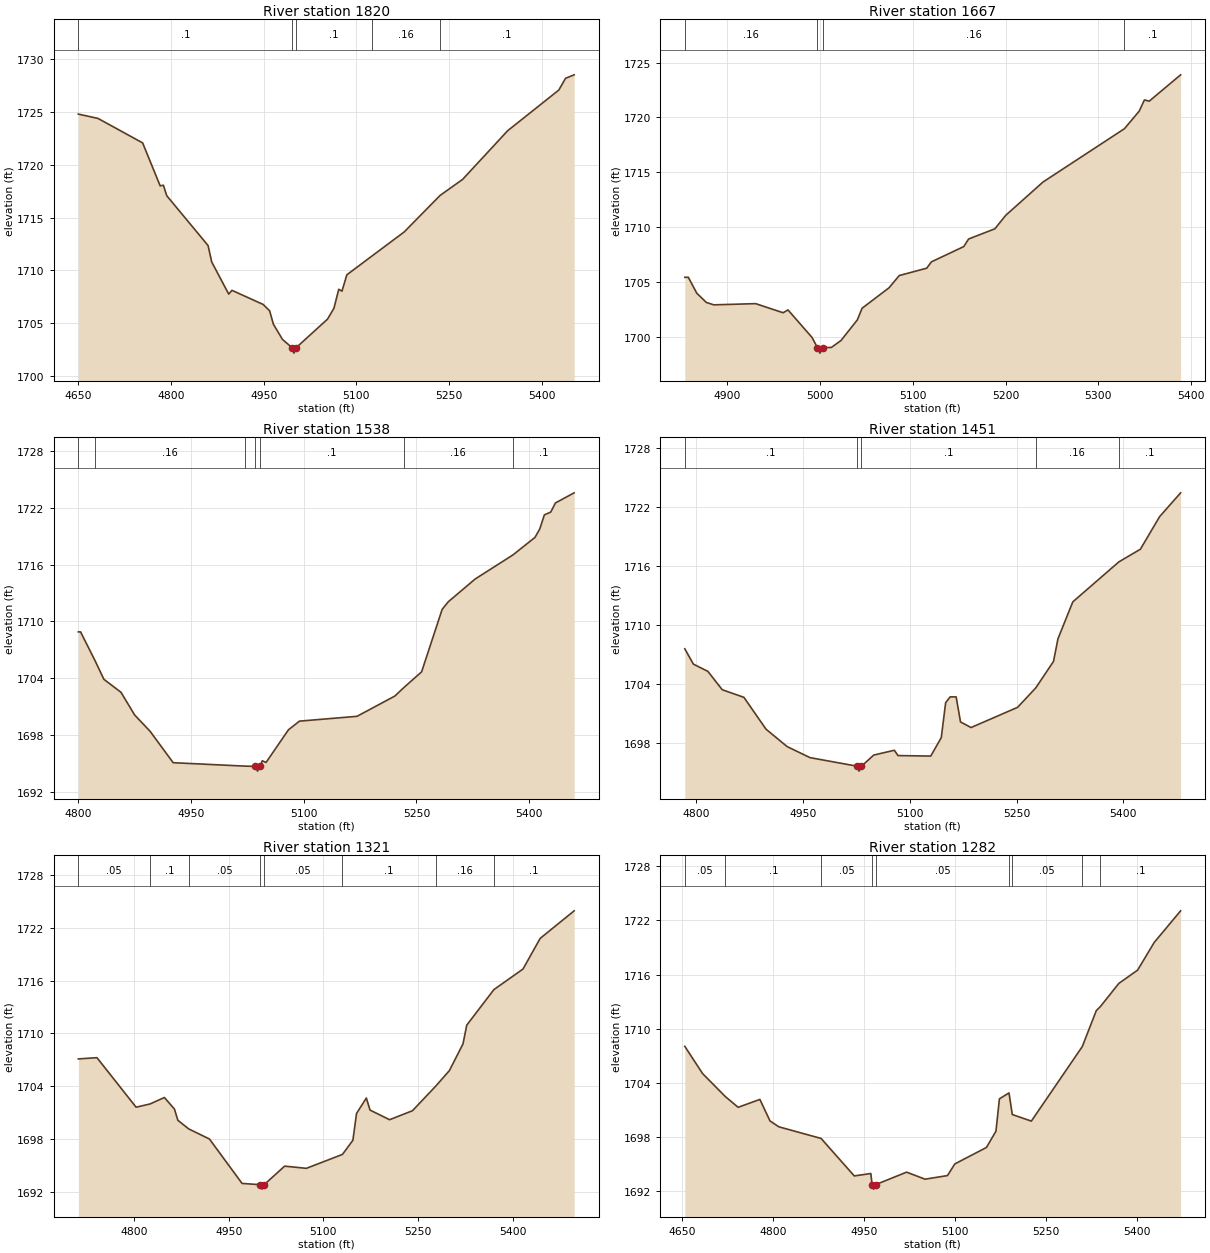
Type RM Length L Ch R = 1 ,1820    ,153,153,153
BEGIN DESCRIPTION:
UNT034 IN SNOGR 4.0
END DESCRIPTION:
XS GIS Cut Line= 2
      2784745.11     10020506.34      2784969.07     10021277.16
#Sta/Elev= 30
    4650 1724.82  4681.8 1724.41  4754.1 1722.09  4782.5 1718.02  4787.7 1718.08
  4793.1 1717.09    4860 1712.37    4866  1710.8  4893.5 1707.76  4898.7 1708.12
  4949.3 1706.78  4959.7 1706.18  4965.8 1704.91  4980.5 1703.47  4996.3 1702.67
  4999.1 1702.17  5002.3 1702.67  5053.4 1705.39  5063.8 1706.42  5071.6 1708.22
  5076.8 1708.04  5084.7 1709.59  5124.9 1711.35  5177.5 1713.65  5235.8 1717.12
  5272.1 1718.63    5345 1723.24  5427.9  1727.1  5438.7 1728.21  5452.7 1728.54
#Mann= 5 ,-1 , 0
    4650      .1       0  4996.3     .07       0  5002.3      .1       0
  5124.9     .16       0  5235.8      .1       0
Bank Sta=4996.3,5002.3
XS Rating Curve= 0 ,0
Exp/Cntr=0.3,0.1

Type RM Length L Ch R = 1 ,1667    ,129,129,129
BEGIN DESCRIPTION:
Mapping XS 3c6016ae
END DESCRIPTION:
XS GIS Cut Line= 2
      2784664.63     10020761.31      2784803.49     10021276.83
#Sta/Elev= 30
  4854.6 1705.43  4858.4 1705.43  4867.5 1703.98  4877.8 1703.14  4885.8 1702.92
  4930.9 1703.03  4960.5  1702.2  4965.7 1702.46  4991.7 1699.94  4997.4 1699.02
  5000.2 1698.52  5003.4 1699.02  5012.5 1699.04  5022.8 1699.67  5040.4 1701.55
  5045.5 1702.61  5074.6 1704.48  5085.5 1705.59  5115.1 1706.26  5120.2 1706.84
    5155 1708.23  5160.2 1708.92  5188.5 1709.85  5200.1 1711.07  5240.3 1714.11
    5328 1718.97  5343.9 1720.57  5349.5 1721.59  5354.7 1721.48  5388.5 1723.88
#Mann= 4 ,-1 , 0
  4854.6     .16       0  4997.4     .07       0  5003.4     .16       0
    5328      .1       0
Bank Sta=4997.4,5003.4
XS Rating Curve= 0 ,0
Exp/Cntr=0.3,0.1

Type RM Length L Ch R = 1 ,1538    ,87,87,87
BEGIN DESCRIPTION:
Mapping XS 23a867a3
END DESCRIPTION:
XS GIS Cut Line= 3
      2784624.71     10020740.45      2784548.31     10021098.12
      2784720.19     10021335.98
#Sta/Elev= 30
  4800.5  1708.9  4803.5  1708.9    4823 1705.81  4834.5 1703.89  4857.2 1702.52
  4875.4 1700.12  4895.9  1698.4  4926.6 1695.08  5021.7 1694.72    5036 1694.69
  5038.8 1694.19    5042 1694.69    5045 1695.28  5050.1 1695.11  5079.9 1698.56
  5094.5 1699.47    5171 1699.98  5221.3 1702.12  5232.9 1702.99  5256.9 1704.68
  5284.2 1711.28  5292.5 1712.09    5328 1714.48  5378.3 1717.03  5407.6 1718.88
  5413.9 1719.76  5420.1 1721.26  5428.6 1721.56  5434.8 1722.52  5459.7 1723.59
#Mann= 7 ,-1 , 0
  4800.5      .1       0    4823     .16       0  5021.7      .1       0
    5036     .07       0    5042      .1       0  5232.9     .16       0
  5378.3      .1       0
Bank Sta=5036,5042
XS Rating Curve= 0 ,0
Exp/Cntr=0.3,0.1

Type RM Length L Ch R = 1 ,1451    ,130,130,130
BEGIN DESCRIPTION:
Mapping XS d96475b9
END DESCRIPTION:
XS GIS Cut Line= 3
      2784530.95     10020731.78      2784477.13     10021065.13
       2784683.6     10021358.36
#Sta/Elev= 30
  4784.1 1707.58  4796.2 1706.02  4816.5 1705.29  4836.7 1703.42  4867.1 1702.65
  4898.2 1699.41  4927.9 1697.64    4960 1696.52  5026.2 1695.65  5028.9 1695.15
  5032.2 1695.65  5049.4 1696.78  5078.4 1697.27  5083.5 1696.73  5129.5 1696.68
  5144.3 1698.56  5150.4  1702.1  5156.8  1702.7  5165.2 1702.69  5171.3 1700.15
  5186.1 1699.58  5251.4 1701.63    5277 1703.61  5301.9  1706.3  5308.1 1708.59
    5329 1712.35  5393.6 1716.41  5423.9  1717.7  5450.9 1721.01  5480.4 1723.43
#Mann= 5 ,-1 , 0
  4784.1      .1       0  5026.2     .07       0  5032.2      .1       0
    5277     .16       0  5393.6      .1       0
Bank Sta=5026.2,5032.2
XS Rating Curve= 0 ,0
Exp/Cntr=0.3,0.1

Type RM Length L Ch R = 1 ,1321    ,39,39,39
BEGIN DESCRIPTION:
UNT034 IN SNOGR 3.0
END DESCRIPTION:
XS GIS Cut Line= 4
      2784270.53     10020756.09      2784360.81     10020999.16
      2784425.05     10021021.73      2784662.88     10021412.34
#Sta/Elev= 30
  4712.1 1707.11  4741.6 1707.25  4803.5 1701.63  4825.7    1702  4848.3 1702.73
  4864.2 1701.42  4869.6 1700.15  4886.9 1699.16  4919.6 1698.02  4971.2 1692.98
  5000.1 1692.83  5002.9 1692.33  5006.1 1692.83  5038.6 1694.94    5073 1694.69
  5130.1 1696.27  5146.6 1697.87  5152.4 1700.92  5167.9 1702.67  5173.8  1701.3
  5204.7 1700.21  5240.9 1701.23    5278 1704.04  5299.4 1705.79  5320.9 1708.82
  5326.8 1710.94  5369.8 1714.98  5415.8 1717.31    5443 1720.79  5496.8 1723.92
#Mann= 8 ,-1 , 0
  4712.1     .05       0  4825.7      .1       0  4886.9     .05       0
  5000.1    .035       0  5006.1     .05       0  5130.1      .1       0
    5278     .16       0  5369.8      .1       0
Bank Sta=5000.1,5006.1
XS Rating Curve= 0 ,0
Exp/Cntr=0.3,0.1

Type RM Length L Ch R = 1 ,1282    ,41,41,41
BEGIN DESCRIPTION:
Mapping XS 8a45a9f8
END DESCRIPTION:
XS GIS Cut Line= 4
      2784188.92     10020775.18      2784320.88     10021035.62
      2784399.01     10021049.51      2784626.42      10021434.9
#Sta/Elev= 30
  4653.8 1708.07  4683.1 1705.06    4721 1702.49  4741.9 1701.32  4777.8 1702.19
  4794.5 1699.81  4809.1 1699.16  4878.9 1697.87  4933.7 1693.72    4961 1693.99
  4963.1 1692.76  4965.9 1692.26  4969.1 1692.76  5020.1 1694.14  5050.5 1693.36
  5087.6 1693.76  5099.7 1695.05  5151.9 1696.87  5167.6 1698.67  5173.4 1702.26
  5189.2 1702.91  5194.6 1700.52  5226.1 1699.79  5310.2 1708.04  5333.4 1712.03
  5340.1 1712.47  5370.5 1715.03  5401.6 1716.51    5429 1719.57  5472.6 1723.07
#Mann= 9 ,-1 , 0
  4653.8     .05       0    4721      .1       0  4878.9     .05       0
  4963.1    .035       0  4969.1     .05       0  5189.2      .1       0
  5194.6     .05       0  5310.2     .16       0  5340.1      .1       0
Bank Sta=4963.1,4969.1
XS Rating Curve= 0 ,0
Exp/Cntr=0.3,0.1

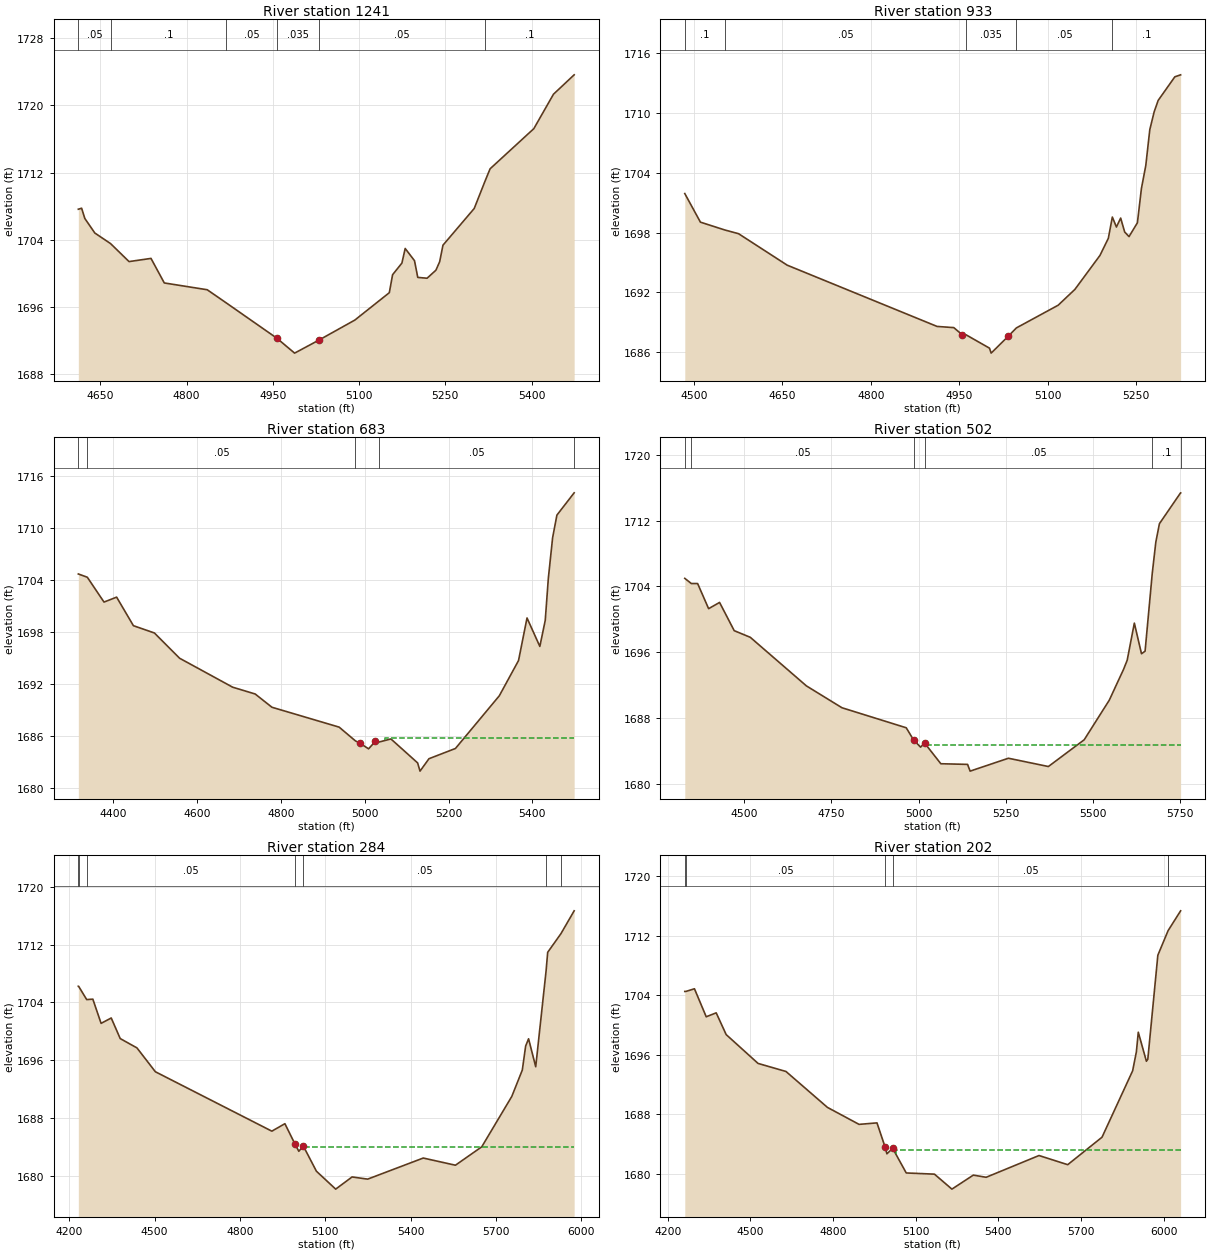
Type RM Length L Ch R = 1 ,1241    ,308,308,308
BEGIN DESCRIPTION:
Mapping XS a06b57f8
END DESCRIPTION:
XS GIS Cut Line= 4
      2784161.17     10020773.48       2784293.1      10021063.4
       2784418.1     10021101.59      2784613.88     10021465.43
#Sta/Elev= 30
  4611.6 1707.64  4617.3 1707.76  4622.9 1706.54  4640.3 1704.81  4667.7 1703.55
  4699.8 1701.41    4738 1701.79  4761.1 1698.87  4835.8 1698.06  4868.8  1696.5
  4956.6 1692.31  4987.8 1690.52  5029.8 1692.06  5092.5 1694.45  5152.5 1697.71
  5158.2 1699.85  5174.4 1701.23  5180.1 1702.97  5196.3 1701.52    5202 1699.53
  5218.2 1699.43  5233.6 1700.39  5240.1  1701.4  5245.8 1703.36  5300.2 1707.73
  5319.1    1711  5327.8 1712.45  5403.9 1717.23    5438 1721.32    5474 1723.63
#Mann= 6 ,-1 , 0
  4611.6     .05       0  4667.7      .1       0  4868.8     .05       0
  4956.6    .035       0  5029.8     .05       0  5319.1      .1       0
Bank Sta=4956.6,5029.8
XS Rating Curve= 0 ,0
Exp/Cntr=0.3,0.1

Type RM Length L Ch R = 1 ,933     ,250,250,250
BEGIN DESCRIPTION:
UNT034 IN SNOGR 2.0
END DESCRIPTION:
XS GIS Cut Line= 3
      2784026.37     10020855.32      2784130.53     10021266.77
      2784411.78     10021574.06
#Sta/Elev= 30
  4484.7 1701.93  4511.2 1699.06  4552.2 1698.28  4575.9  1697.9  4658.4 1694.74
  4912.6 1688.59    4941 1688.47  4955.2 1687.76    4962 1687.74  5001.5 1686.41
  5004.3 1685.91  5032.9 1687.58  5047.1 1688.44    5118 1690.72  5146.4 1692.31
  5188.9 1695.72  5203.1 1697.44  5209.9 1699.57  5216.8 1698.57    5224 1699.47
  5230.8 1698.07  5238.2 1697.61  5252.4    1699  5259.2 1702.43  5266.6 1704.74
  5273.4 1708.34  5280.8 1710.13  5287.6 1711.28  5315.9 1713.65  5325.7 1713.85
#Mann= 5 ,-1 , 0
  4484.7      .1       0  4552.2     .05       0    4962    .035       0
  5047.1     .05       0  5209.9      .1       0
Bank Sta=4955.2,5032.9
XS Rating Curve= 0 ,0
Exp/Cntr=0.3,0.1

Type RM Length L Ch R = 1 ,683     ,181,181,181
BEGIN DESCRIPTION:
Mapping XS 5f3700e6
END DESCRIPTION:
XS GIS Cut Line= 4
       2784018.8     10020752.59      2783970.19     10021460.97
      2784041.37      10021544.3      2784398.97       10021612.
#Sta/Elev= 30
  4316.1 1704.71  4337.6 1704.33  4377.4 1701.47  4407.5 1702.04  4447.6 1698.75
  4497.7 1697.91  4557.8    1695  4684.6 1691.66  4738.2 1690.88  4778.3 1689.35
  4938.7 1687.06  4977.4 1685.48  4988.8  1685.2  5008.9 1684.56    5025 1685.41
  5033.8 1685.34  5062.3  1685.7    5126 1682.94  5131.8 1681.99  5153.1 1683.42
  5216.3  1684.6    5321 1690.67  5366.9 1694.73  5387.2 1699.64  5417.8 1696.36
  5430.7 1699.37  5438.1 1704.23  5448.3 1708.89  5458.5 1711.49  5499.7 1714.06
#Mann= 5 ,-1 , 0
  4316.1     .05       0  4337.6     .05       0  4977.4    .035       0
  5033.8     .05       0  5499.7      .1       0
#XS Ineff= 2 , 0
                         5048.06         1685.81
Permanent Ineff=
       T       T
Bank Sta=4988.8,5025
XS Rating Curve= 0 ,0
Exp/Cntr=0.3,0.1

Type RM Length L Ch R = 1 ,502     ,218,218,218
BEGIN DESCRIPTION:
Mapping XS 30ad180d
END DESCRIPTION:
XS GIS Cut Line= 4
      2784010.13      10020738.7      2783796.58     10021408.88
      2783822.62     10021523.47      2784407.67     10021660.62
#Sta/Elev= 30
  4329.5 1704.99  4348.3 1704.36  4366.3 1704.36  4397.8  1701.3  4429.2 1702.06
  4471.2 1698.62  4517.3 1697.81  4678.3 1691.89  4780.2 1689.23  4964.5 1686.79
  4985.5 1685.31  5005.7 1684.43    5017 1684.94  5063.7 1682.41  5140.4 1682.33
  5147.7 1681.51  5257.5 1683.08  5372.1 1682.07  5474.8 1685.33  5546.7 1690.15
  5587.8 1693.92  5598.1 1695.02  5618.6 1699.54  5639.1 1695.81  5649.4 1696.12
    5670 1705.62  5680.2 1709.41  5690.5 1711.65  5751.2 1715.41  5751.3 1715.41
#Mann= 6 ,-1 , 0
  4329.5     .05       0  4348.3     .05       0  4985.5    .035       0
    5017     .05       0    5670      .1       0  5751.2     .05       0
#XS Ineff= 2 , 0
                         5022.73         1684.66
Permanent Ineff=
       T       T
Bank Sta=4985.5,5017
XS Rating Curve= 0 ,0
Exp/Cntr=0.3,0.1

Type RM Length L Ch R = 1 ,284     ,252,252,252
BEGIN DESCRIPTION:
Mapping XS 575c5996
END DESCRIPTION:
XS GIS Cut Line= 4
      2783978.86     10020714.44      2783572.62      10021419.3
      2783614.28     10021506.11      2784424.28     10021700.37
#Sta/Elev= 30
  4232.2 1706.24  4233.2 1706.24  4261.6  1704.4  4283.2 1704.46  4312.2 1701.12
  4347.9 1701.86  4379.4 1699.02  4438.3 1697.73    4503 1694.44  4912.4 1686.24
  4958.3 1687.27  4993.2  1684.5  5007.2 1683.46    5023 1684.19  5069.1 1680.71
  5136.8 1678.24  5194.4 1679.92  5249.2 1679.62  5444.6 1682.53  5557.7 1681.54
  5650.2 1684.08  5755.9 1691.04  5792.8 1694.68  5804.5 1697.99  5814.8 1698.99
  5839.9 1695.13  5876.5 1708.42  5881.9 1710.92  5928.6  1713.5    5975 1716.65
#Mann= 7 ,-1 , 0
  4232.2     .05       0  4233.2      .1       0  4261.6     .05       0
  4993.2    .035       0    5023     .05       0  5876.5      .1       0
  5928.6     .05       0
#XS Ineff= 2 , 0
                         5027.39         1684.08
Permanent Ineff=
       T       T
Bank Sta=4993.2,5023
XS Rating Curve= 0 ,0
Exp/Cntr=0.3,0.1

Type RM Length L Ch R = 1 ,202     ,89,89,89
BEGIN DESCRIPTION:
Mapping XS 3394c5eb
END DESCRIPTION:
XS GIS Cut Line= 4
      2783952.85      10020709.2      2783503.17      10021375.9
      2783602.13     10021509.58      2784407.68     10021707.49
#Sta/Elev= 30
  4261.8  1704.5  4265.6  1704.5  4296.9 1704.86  4339.6  1701.1  4375.8 1701.63
    4412 1698.71  4527.8 1694.84  4629.1 1693.76  4779.6 1688.94  4894.5 1686.66
  4959.5 1686.86  4989.4 1683.57  4995.5 1682.71  5016.5 1683.44  5065.7 1680.14
  5168.2 1679.98  5231.5 1677.97  5309.2 1679.85  5355.9 1679.56  5547.7 1682.48
  5651.9 1681.25  5776.5 1684.94  5887.6 1693.85  5901.2  1696.4  5908.1 1699.03
  5937.6 1695.13  5942.7 1695.41  5979.1 1709.36  6016.3 1712.66  6061.8 1715.32
#Mann= 6 ,-1 , 0
  4261.8     .05       0  4265.6     .05       0  4989.4    .035       0
  5016.5     .05       0  6016.3      .1       0  6016.3     .05       0
#XS Ineff= 2 , 0
                         5027.52          1683.2
Permanent Ineff=
       T       T
Bank Sta=4989.4,5016.5
XS Rating Curve= 0 ,0
Exp/Cntr=0.3,0.1

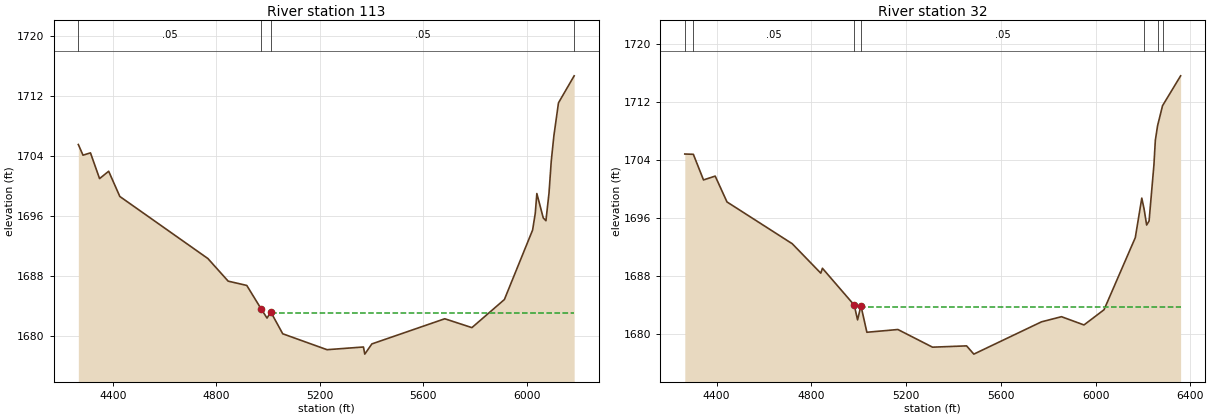
Type RM Length L Ch R = 1 ,113     ,81,81,81
BEGIN DESCRIPTION:
Mapping XS fa768ff2
END DESCRIPTION:
XS GIS Cut Line= 5
      2783935.46     10020695.35      2783451.09     10021292.57
      2783449.35     10021460.97      2783621.23      10021525.2
      2784394.53     10021712.46
#Sta/Elev= 30
  4266.9 1705.56    4285 1704.14  4313.8 1704.45    4349 1701.02  4384.2    1702
  4427.3 1698.64  4767.8 1690.37  4846.1 1687.36    4918 1686.79    4974 1683.64
  4996.3 1682.44  5010.7 1683.26    5057 1680.35  5228.2 1678.23    5369 1678.59
  5374.1 1677.64  5401.5    1679  5683.3 1682.35  5788.2 1681.17  5913.7 1684.91
  6022.8 1694.17  6033.1  1696.4  6039.2 1699.03    6064 1695.78  6074.3 1695.41
  6086.1 1699.06  6094.9 1703.36  6105.1 1706.74  6122.8 1711.11  6183.4 1714.71
#Mann= 4 ,-1 , 0
  4266.9     .05       0    4974    .035       0  5010.7     .05       0
  6183.4     .05       0
#XS Ineff= 2 , 0
                         5015.49         1683.06
Permanent Ineff=
       T       T
Bank Sta=4974,5010.7
XS Rating Curve= 0 ,0
Exp/Cntr=0.3,0.1

Type RM Length L Ch R = 1 ,32      ,0,0,0
BEGIN DESCRIPTION:
UNT034 IN SNOGR 1.0
END DESCRIPTION:
XS GIS Cut Line= 4
      2783909.45     10020683.16      2783383.38     10021243.95
      2783352.13     10021471.38      2784418.12     10021723.12
#Sta/Elev= 30
  4265.6 1704.85  4301.7 1704.81  4344.6 1701.27    4394  1701.8  4443.8 1698.23
  4719.3 1692.46  4839.9 1688.39  4846.8 1689.07  4981.1 1683.98  4995.2 1681.94
  5009.4 1683.89  5034.5 1680.23  5165.5 1680.61  5311.7 1678.17  5455.6 1678.35
  5486.1 1677.21  5771.8 1681.67  5856.3 1682.38  5951.3 1681.24  6035.9 1683.34
    6168  1693.3  6195.4 1698.76  6205.1 1697.26  6215.9 1695.04  6226.2  1695.6
  6246.7 1703.36  6252.6 1706.74    6262 1708.75    6283 1711.52  6359.4 1715.65
#Mann= 7 ,-1 , 0
  4265.6     .05       0  4301.7     .05       0  4981.1    .035       0
  5009.4     .05       0  6205.1     .05       0    6262      .1       0
    6283     .05       0
#XS Ineff= 2 , 0
                         5012.78          1683.7
Permanent Ineff=
       T       T
Bank Sta=4981.1,5009.4
XS Rating Curve= 0 ,0
Exp/Cntr=0.3,0.1

Chan Stop Cuts=-1
Use User Specified Reach Order=0
Composite Channel Slope=5