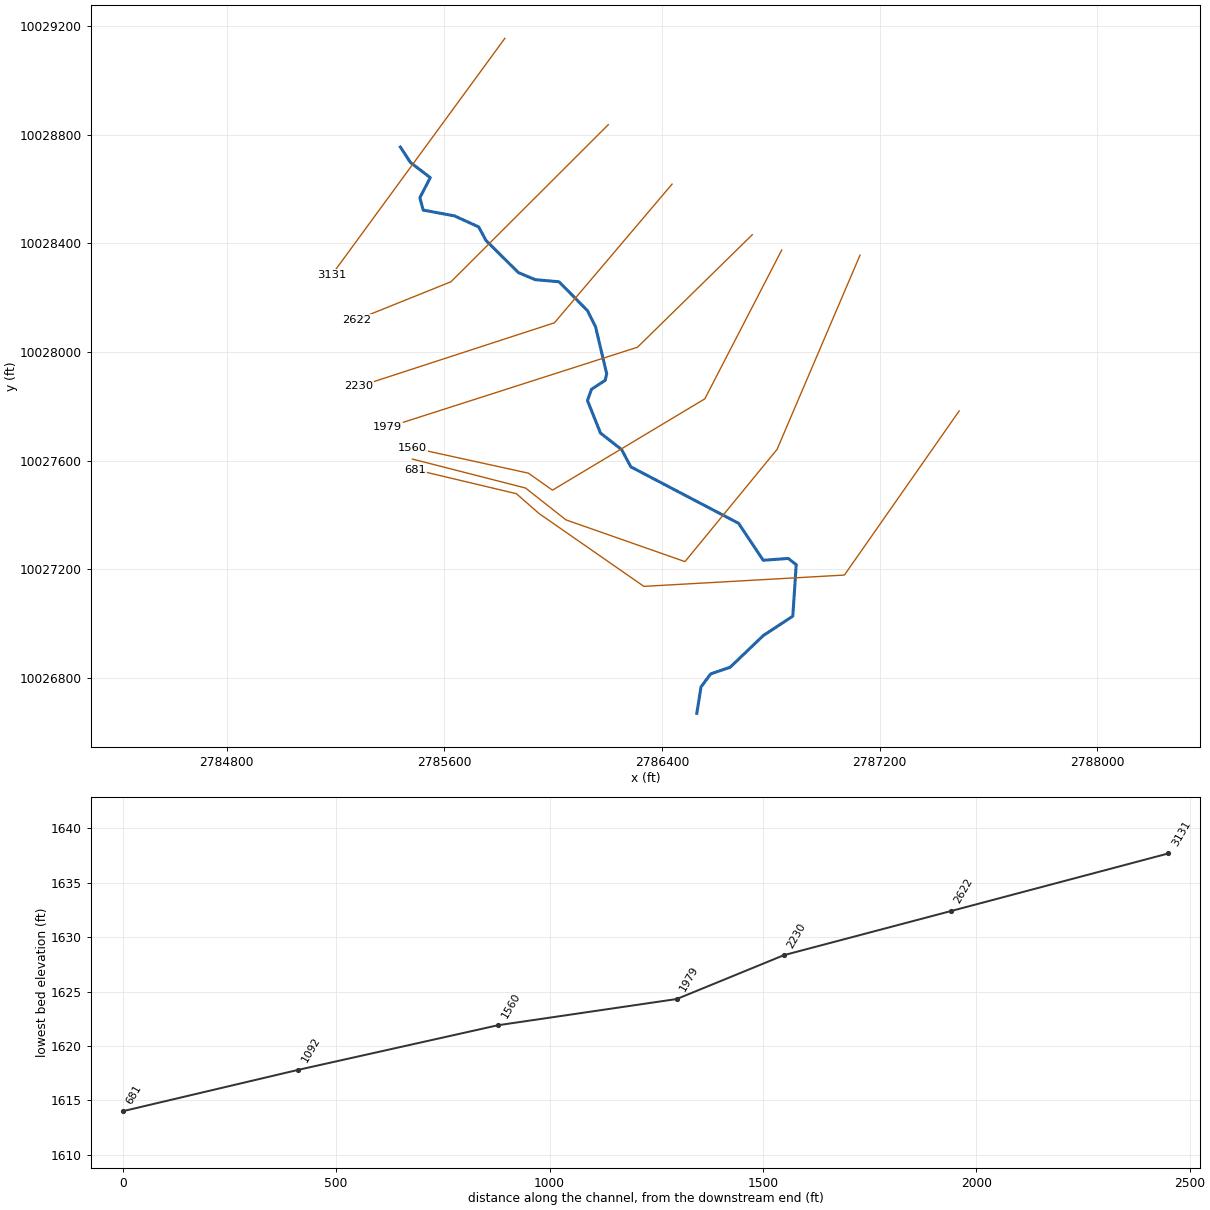
--- UNT035 IN SNOGR.prj (project) ---

Proj Title=UNT035 IN SNOGR Base Level Engineering
Current Plan=p01
Default Exp/Contr=0.3,0.1
English Units
Geom File=g01
Flow File=f01
Plan File=p01
Y Axis Title=Elevation
X Axis Title(PF)=Main Channel Distance
X Axis Title(XS)=Station
BEGIN DESCRIPTION:
UNT035 IN SNOGR
END DESCRIPTION:
DSS Export Rating Curves= 0
DSS Export Rating Curve Sorted= 0
DSS Export Volume Flow Curves= 0
DXF OffsetX= 0
DXF OffsetY= 0
DXF ScaleX= 1
DXF ScaleY= 10

--- UNT035 IN SNOGR.p01 (plan) ---

Plan Title=Multiple Run
Short Identifier=Multiple
Geom File=g01
Flow File=f01
Subcritical Flow
K Sum by GR= 0
Std Step Tol= 0.01
Critical Tol= 0.01
Num of Std Step Trials= 20
Max Error Tol= 0.3
Flow Tol Ratio= 0.001
Split Flow NTrial= 30
Split Flow Tol= 0.02
Split Flow Ratio= 0.02
Log Output Level= 0
Friction Slope Method= 1
Unsteady Friction Slope Method= 2
Unsteady Bridges Friction Slope Method= 1
Parabolic Critical Depth
Global Vel Dist=  1 , 1 , 1
Global Log Level= 0
CheckData=True
Encroach Param= -1, 0, 0, 0
BEGIN DESCRIPTION:
Multiple Run
END DESCRIPTION:

--- UNT035 IN SNOGR.f01 (steady flow) ---

Flow Title=Multiple
Program Version=4.10
Number of Profiles= 7
Profile Names=10-year,25-year,50-year,1pct_min,100-year,1pct_plu,500-year
River Rch & RM=UNT035 IN SNOGR,Reach-1         ,3131
     937    1372    1754    1642    2220    3003    3573
Boundary for River Rch & Prof#=UNT035 IN SNOGR,Reach-1         , 1
Up Type= 0
Dn Type= 3
Dn Slope=0.00929
Boundary for River Rch & Prof#=UNT035 IN SNOGR,Reach-1         , 2
Up Type= 0
Dn Type= 3
Dn Slope=0.00929
Boundary for River Rch & Prof#=UNT035 IN SNOGR,Reach-1         , 3
Up Type= 0
Dn Type= 3
Dn Slope=0.00929
Boundary for River Rch & Prof#=UNT035 IN SNOGR,Reach-1         , 4
Up Type= 0
Dn Type= 3
Dn Slope=0.00929
Boundary for River Rch & Prof#=UNT035 IN SNOGR,Reach-1         , 5
Up Type= 0
Dn Type= 3
Dn Slope=0.00929
Boundary for River Rch & Prof#=UNT035 IN SNOGR,Reach-1         , 6
Up Type= 0
Dn Type= 3
Dn Slope=0.00929
Boundary for River Rch & Prof#=UNT035 IN SNOGR,Reach-1         , 7
Up Type= 0
Dn Type= 3
Dn Slope=0.00929
DSS Import GetInterval= 0
DSS Import GetPeak= 0
DSS Import FillOption= 0

--- UNT035 IN SNOGR.g01 (geometry) ---

Geom Title=Existing Conditions
Program Version=4.10

River Reach=UNT035 IN SNOGR ,Reach-1
Reach XY= 30
      2785438.47     10028753.73      2785475.41     10028697.03
      2785548.34     10028641.22      2785509.99     10028567.49
      2785522.15     10028521.82      2785637.14     10028500.51
       2785726.1     10028459.95      2785752.97     10028410.11
      2785871.94     10028291.88      2785934.03     10028265.73
      2786021.08     10028258.11      2786125.98     10028152.09
      2786155.65      10028092.6       2786196.7     10027919.38
      2786190.92     10027895.01      2786140.73     10027862.46
      2786126.06     10027820.78      2786173.86     10027701.15
      2786251.61     10027640.35      2786285.22     10027576.93
      2786681.51     10027369.07      2786772.09     10027233.05
      2786863.84     10027239.79      2786893.21     10027216.79
      2786880.66     10027027.45      2786771.84     10026955.64
       2786650.6     10026839.43      2786578.74     10026814.73
      2786543.47     10026767.14      2786527.83     10026669.56

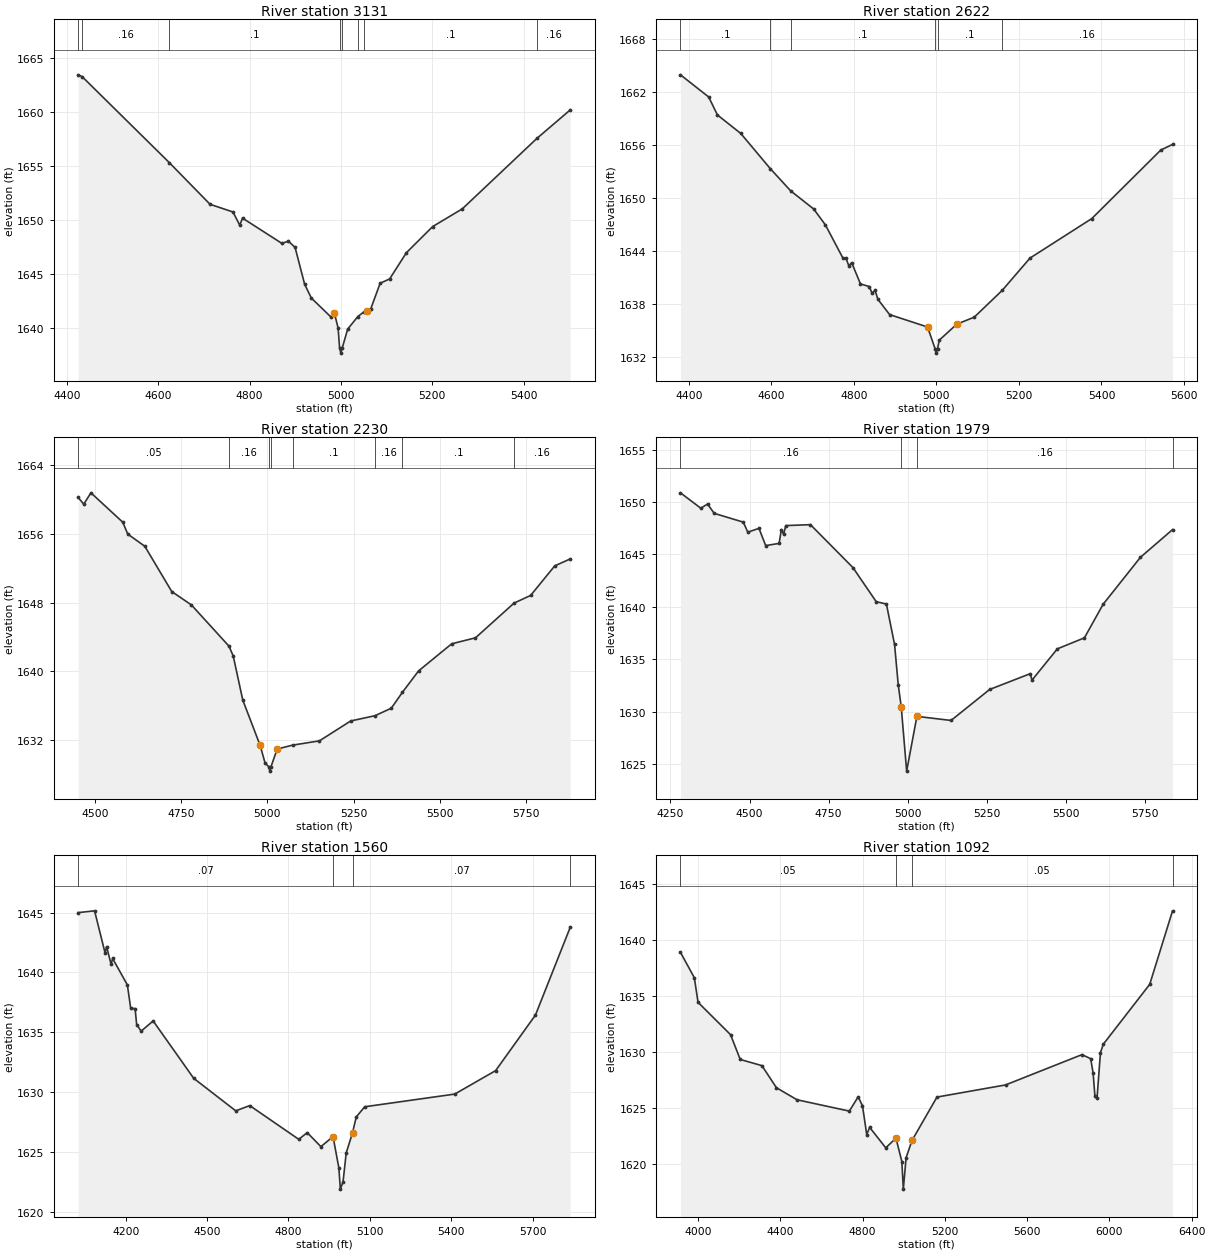
Type RM Length L Ch R = 1 ,3131    ,509,509,509
BEGIN DESCRIPTION:
UNT035 IN SNOGR 7.0
END DESCRIPTION:
XS GIS Cut Line= 2
      2785822.39     10029153.95      2785186.95     10028284.13
#Sta/Elev= 30
  4424.7 1663.46  4433.5 1663.29  4624.5 1655.32  4713.5 1651.47  4763.7 1650.76
  4778.4 1649.54  4784.6 1650.19  4870.8 1647.85    4885 1648.06  4899.6 1647.48
  4920.5 1644.07  4935.2 1642.79  4979.2 1640.99  4985.4 1641.43  4993.8 1640.02
    4997 1638.19  4999.8 1637.69    5003 1638.19  5014.7 1639.91    5037 1641.08
    5050  1641.5  5056.6 1641.58  5064.9 1641.75  5085.8 1644.16  5106.6 1644.56
  5143.3 1646.99  5200.8 1649.41  5265.7 1651.05  5429.4 1657.59  5501.9 1660.21
#Mann= 8 ,-1 , 0
  4424.7      .1       0  4433.5     .16       0  4624.5      .1       0
    4997     .07       0    5003      .1       0    5037     .16       0
    5050      .1       0  5429.4     .16       0
Bank Sta=4985.4,5056.6
XS Rating Curve= 0 ,0
Exp/Cntr=0.3,0.1

Type RM Length L Ch R = 1 ,2622    ,392,392,392
BEGIN DESCRIPTION:
UNT035 IN SNOGR 6.0
END DESCRIPTION:
XS GIS Cut Line= 3
      2786202.56     10028836.19      2785624.46     10028258.09
      2785277.06      10028118.1
#Sta/Elev= 30
  4380.1 1663.96  4448.4 1661.45  4469.6 1659.41  4526.2 1657.31  4597.7 1653.32
  4647.1  1650.8  4702.9 1648.74  4731.2 1646.94  4773.6 1643.18  4780.7 1643.19
  4787.8 1642.32  4794.9 1642.65  4816.1 1640.25  4837.3 1639.95  4844.3 1639.19
  4851.4 1639.52  4858.5 1638.49  4886.8 1636.77  4978.7 1635.36  4996.9  1632.9
  4999.7  1632.4  5002.9  1632.9    5007 1633.87  5049.4 1635.68  5091.8 1636.48
  5159.4 1639.51  5226.9 1643.18  5376.6 1647.66  5543.7 1655.43  5572.2 1656.07
#Mann= 6 ,-1 , 0
  4380.1      .1       0  4597.7     .05       0  4647.1      .1       0
  4996.9     .07       0  5002.9      .1       0  5159.4     .16       0
Bank Sta=4978.7,5049.4
XS Rating Curve= 0 ,0
Exp/Cntr=0.3,0.1

Type RM Length L Ch R = 1 ,2230    ,251,251,251
BEGIN DESCRIPTION:
UNT035 IN SNOGR 5.0
END DESCRIPTION:
XS GIS Cut Line= 3
      2786436.95     10028617.46      2786004.66     10028107.05
      2785285.89     10027872.67
#Sta/Elev= 30
  4451.9 1660.26  4468.1 1659.48  4488.9  1660.8  4581.2 1657.37  4595.5 1655.99
  4644.9 1654.57  4722.9 1649.29    4780 1647.72  4888.6 1642.92  4900.9 1641.78
  4928.6 1636.63  4978.9 1631.34  4993.2 1629.28  5004.2 1628.84  5006.9 1628.34
  5010.2 1628.84  5028.3 1630.92  5072.7 1631.37  5150.6 1631.87  5241.1 1634.19
  5311.9 1634.81  5358.7 1635.68    5391 1637.54  5437.7 1640.03  5533.5 1643.19
  5602.5 1643.89  5714.2 1647.94  5762.1 1648.83    5832 1652.28  5876.8 1653.09
#Mann= 8 ,-1 , 0
  4451.9     .05       0  4888.6     .16       0  5004.2     .07       0
  5010.2     .16       0  5072.7      .1       0  5311.9     .16       0
    5391      .1       0  5714.2     .16       0
Bank Sta=4978.9,5028.3
XS Rating Curve= 0 ,0
Exp/Cntr=0.3,0.1

Type RM Length L Ch R = 1 ,1979    ,419,419,419
BEGIN DESCRIPTION:
UNT035 IN SNOGR 4.0
END DESCRIPTION:
XS GIS Cut Line= 3
      2786731.78     10028431.23       2786309.9     10028017.17
      2785391.77     10027722.46
#Sta/Elev= 30
  4281.6 1650.89  4345.8 1649.42  4367.1 1649.82  4388.2 1648.93  4480.2 1648.09
  4494.4 1647.13  4529.7  1647.5  4550.9 1645.85  4593.4 1646.06  4600.4 1647.38
  4607.5 1646.94  4614.5 1647.76  4692.4 1647.85  4826.7 1643.75  4900.4 1640.49
  4932.5 1640.27  4958.3 1636.41  4969.9 1632.55  4979.3 1630.48  4996.5 1624.31
  5028.9 1629.54  5136.8 1629.15  5258.9 1632.11  5387.4 1633.62  5392.6    1633
  5472.9 1635.99  5558.4 1637.04  5617.4 1640.24  5735.4 1644.73    5837 1647.38
#Mann= 4 ,-1 , 0
  4281.6     .16       0  4979.3     .07       0  5028.9     .16       0
    5837     .16       0
Bank Sta=4979.3,5028.9
XS Rating Curve= 0 ,0
Exp/Cntr=0.3,0.1

Type RM Length L Ch R = 1 ,1560    ,468,468,468
BEGIN DESCRIPTION:
UNT035 IN SNOGR 3.0
END DESCRIPTION:
XS GIS Cut Line= 5
      2786840.05     10028374.99       2786557.3     10027827.06
       2785997.4     10027491.13      2785908.86     10027553.63
      2785482.61     10027647.19
#Sta/Elev= 30
  4024.6    1645  4085.2 1645.15  4123.9 1641.63  4129.5 1642.16  4146.1 1640.68
  4151.7 1641.17  4206.1 1638.96  4218.2 1637.04  4234.7 1636.97  4240.3 1635.65
  4256.9  1635.1  4301.2 1635.95  4450.6 1631.16  4605.7 1628.44  4657.3 1628.88
  4838.1 1626.06  4869.2 1626.62  4919.7 1625.45  4964.4 1626.29  4985.8 1623.68
  4991.4  1621.9  5001.3 1622.51    5013 1624.93  5036.3 1626.61    5050 1627.93
  5081.1 1628.78  5413.1 1629.84  5563.9  1631.8  5710.7 1636.44  5838.9 1643.77
#Mann= 4 ,-1 , 0
  4024.6     .07       0  4964.4     .05       0  5036.3     .07       0
  5838.9      .1       0
Bank Sta=4964.4,5036.3
XS Rating Curve= 0 ,0
Exp/Cntr=0.3,0.1

Type RM Length L Ch R = 1 ,1092    ,411,411,411
BEGIN DESCRIPTION:
UNT035 IN SNOGR 2.0
END DESCRIPTION:
XS GIS Cut Line= 6
      2787127.63     10028355.75      2786822.68     10027640.96
      2786484.38     10027228.11      2786046.88     10027381.75
      2785898.44     10027498.94      2785482.67     10027605.48
#Sta/Elev= 30
  3914.2 1638.89  3981.6 1636.63  3999.6 1634.44  4157.6 1631.56  4204.8 1629.35
  4310.1  1628.8    4381 1626.83  4480.9 1625.76  4735.2 1624.75  4778.2 1626.02
  4799.1 1625.24  4819.9 1622.66  4834.2  1623.3  4912.5 1621.48    4962 1622.34
  4990.7 1620.26  4997.8  1617.8  5011.5 1620.61  5040.2 1622.14  5161.5    1626
  5494.8 1627.08  5866.5 1629.78  5908.8 1629.42  5920.8 1628.15  5929.5 1626.11
  5939.8 1625.89  5956.5 1629.97  5970.8 1630.72    6196 1636.04  6307.1 1642.59
#Mann= 4 ,-1 , 0
  3914.2     .05       0    4962     .03       0  5040.2     .05       0
  6307.1      .1       0
Bank Sta=4962,5040.2
XS Rating Curve= 0 ,0
Exp/Cntr=0.3,0.1

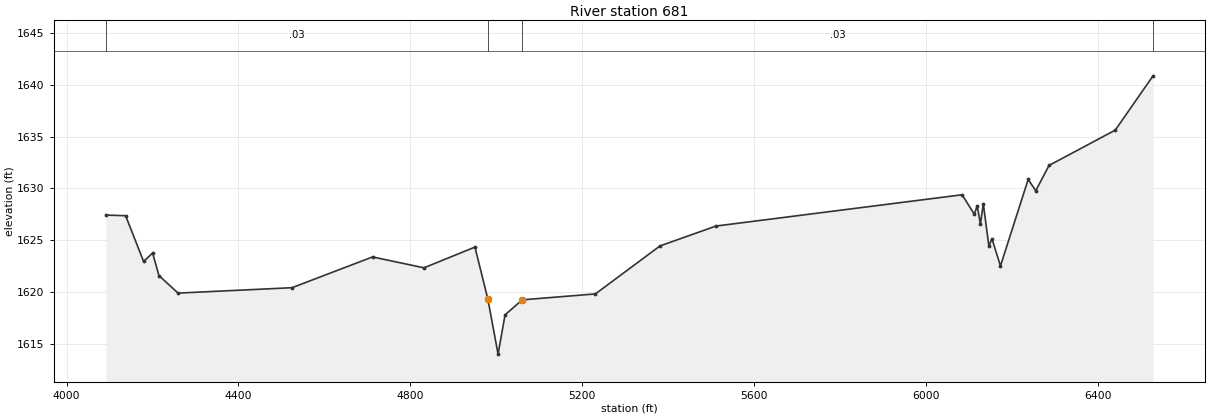
Type RM Length L Ch R = 1 ,681     ,0,0,0
BEGIN DESCRIPTION:
UNT035 IN SNOGR 1.0
END DESCRIPTION:
XS GIS Cut Line= 6
      2787492.22     10027782.83      2787070.32     10027178.63
      2786333.34     10027136.96      2785947.92     10027405.19
      2785864.59     10027478.11      2785492.86     10027566.49
#Sta/Elev= 30
  4091.5 1627.42  4137.4 1627.36  4179.3 1622.94  4200.2 1623.76    4215 1621.58
  4259.5 1619.89  4524.7 1620.41  4712.2 1623.38  4831.9 1622.33  4950.5 1624.33
  4980.5 1619.33  5004.4    1614  5020.6 1617.79  5060.7 1619.24  5230.9 1619.81
  5381.2 1624.44  5511.4 1626.36  6084.5 1629.38    6113  1627.5  6119.7 1628.32
  6127.2 1626.55  6133.9 1628.51  6146.9 1624.41    6154 1625.14  6173.8 1622.51
  6238.3 1630.86    6256 1629.77  6286.8 1632.21    6441 1635.62    6529 1640.86
#Mann= 4 ,-1 , 0
  4091.5     .03       0  4980.5    .025       0  5060.7     .03       0
    6529      .1       0
Bank Sta=4980.5,5060.7
XS Rating Curve= 0 ,0
Exp/Cntr=0.3,0.1

Chan Stop Cuts=-1
Use User Specified Reach Order=0
Composite Channel Slope=5