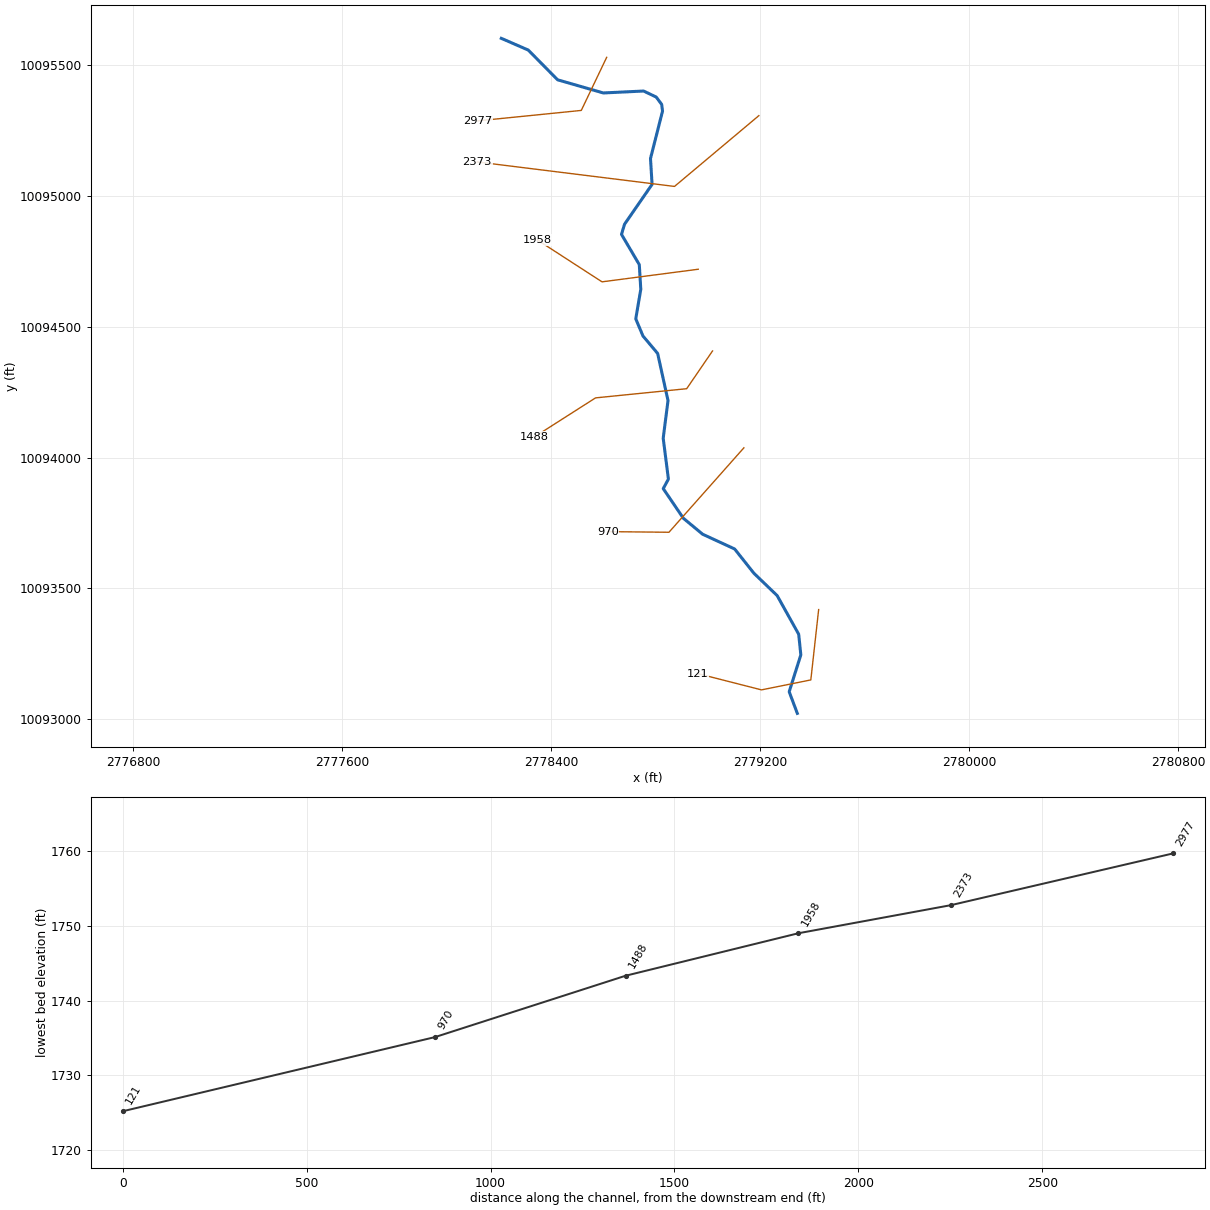
--- UNT036 IN NNOGR.prj (project) ---

Proj Title=UNT036 IN NNOGR Base Level Engineering
Current Plan=p01
Default Exp/Contr=0.3,0.1
English Units
Geom File=g01
Flow File=f01
Plan File=p01
Y Axis Title=Elevation
X Axis Title(PF)=Main Channel Distance
X Axis Title(XS)=Station
BEGIN DESCRIPTION:
UNT036 IN NNOGR
END DESCRIPTION:
DSS Export Rating Curves= 0
DSS Export Rating Curve Sorted= 0
DSS Export Volume Flow Curves= 0
DXF OffsetX= 0
DXF OffsetY= 0
DXF ScaleX= 1
DXF ScaleY= 10

--- UNT036 IN NNOGR.p01 (plan) ---

Plan Title=Multiple Run
Short Identifier=Multiple
Geom File=g01
Flow File=f01
Subcritical Flow
K Sum by GR= 0
Std Step Tol= 0.01
Critical Tol= 0.01
Num of Std Step Trials= 20
Max Error Tol= 0.3
Flow Tol Ratio= 0.001
Split Flow NTrial= 30
Split Flow Tol= 0.02
Split Flow Ratio= 0.02
Log Output Level= 0
Friction Slope Method= 1
Unsteady Friction Slope Method= 2
Unsteady Bridges Friction Slope Method= 1
Parabolic Critical Depth
Global Vel Dist=  1 , 1 , 1
Global Log Level= 0
CheckData=True
Encroach Param= -1, 0, 0, 0
BEGIN DESCRIPTION:
Multiple Run
END DESCRIPTION:

--- UNT036 IN NNOGR.f01 (steady flow) ---

Flow Title=Multiple
Program Version=4.10
Number of Profiles= 7
Profile Names=10-year,25-year,50-year,1pct_min,100-year,1pct_plu,500-year
River Rch & RM=UNT036 IN NNOGR,Reach-1         ,2977
     702    1011    1278    1185    1602    2167    2527
Boundary for River Rch & Prof#=UNT036 IN NNOGR,Reach-1         , 1
Up Type= 0
Dn Type= 3
Dn Slope=0.0128
Boundary for River Rch & Prof#=UNT036 IN NNOGR,Reach-1         , 2
Up Type= 0
Dn Type= 3
Dn Slope=0.0128
Boundary for River Rch & Prof#=UNT036 IN NNOGR,Reach-1         , 3
Up Type= 0
Dn Type= 3
Dn Slope=0.0128
Boundary for River Rch & Prof#=UNT036 IN NNOGR,Reach-1         , 4
Up Type= 0
Dn Type= 3
Dn Slope=0.0128
Boundary for River Rch & Prof#=UNT036 IN NNOGR,Reach-1         , 5
Up Type= 0
Dn Type= 3
Dn Slope=0.0128
Boundary for River Rch & Prof#=UNT036 IN NNOGR,Reach-1         , 6
Up Type= 0
Dn Type= 3
Dn Slope=0.0128
Boundary for River Rch & Prof#=UNT036 IN NNOGR,Reach-1         , 7
Up Type= 0
Dn Type= 3
Dn Slope=0.0128
DSS Import GetInterval= 0
DSS Import GetPeak= 0
DSS Import FillOption= 0

--- UNT036 IN NNOGR.g01 (geometry) ---

Geom Title=Existing Conditions
Program Version=4.10

River Reach=UNT036 IN NNOGR ,Reach-1
Reach XY= 30
      2778208.47     10095603.73      2778311.47     10095558.97
      2778423.96      10095445.1      2778598.93     10095394.75
      2778753.19     10095402.13      2778801.56     10095379.06
      2778822.53     10095350.89      2778825.69     10095325.07
       2778779.6     10095143.92      2778785.67     10095044.97
       2778680.4     10094892.69      2778668.54     10094853.72
      2778736.72     10094737.97      2778742.45     10094643.72
      2778723.26      10094530.4      2778750.89     10094464.78
      2778806.98     10094398.12      2778846.71     10094217.86
      2778828.27     10094073.78      2778848.18     10093917.37
      2778828.43     10093880.88      2778905.47     10093767.53
      2778979.51     10093706.28       2779101.8     10093650.05
      2779175.46     10093557.22       2779264.6     10093471.62
      2779347.02     10093323.83      2779355.21     10093244.73
      2779310.62     10093103.78       2779341.8     10093021.02

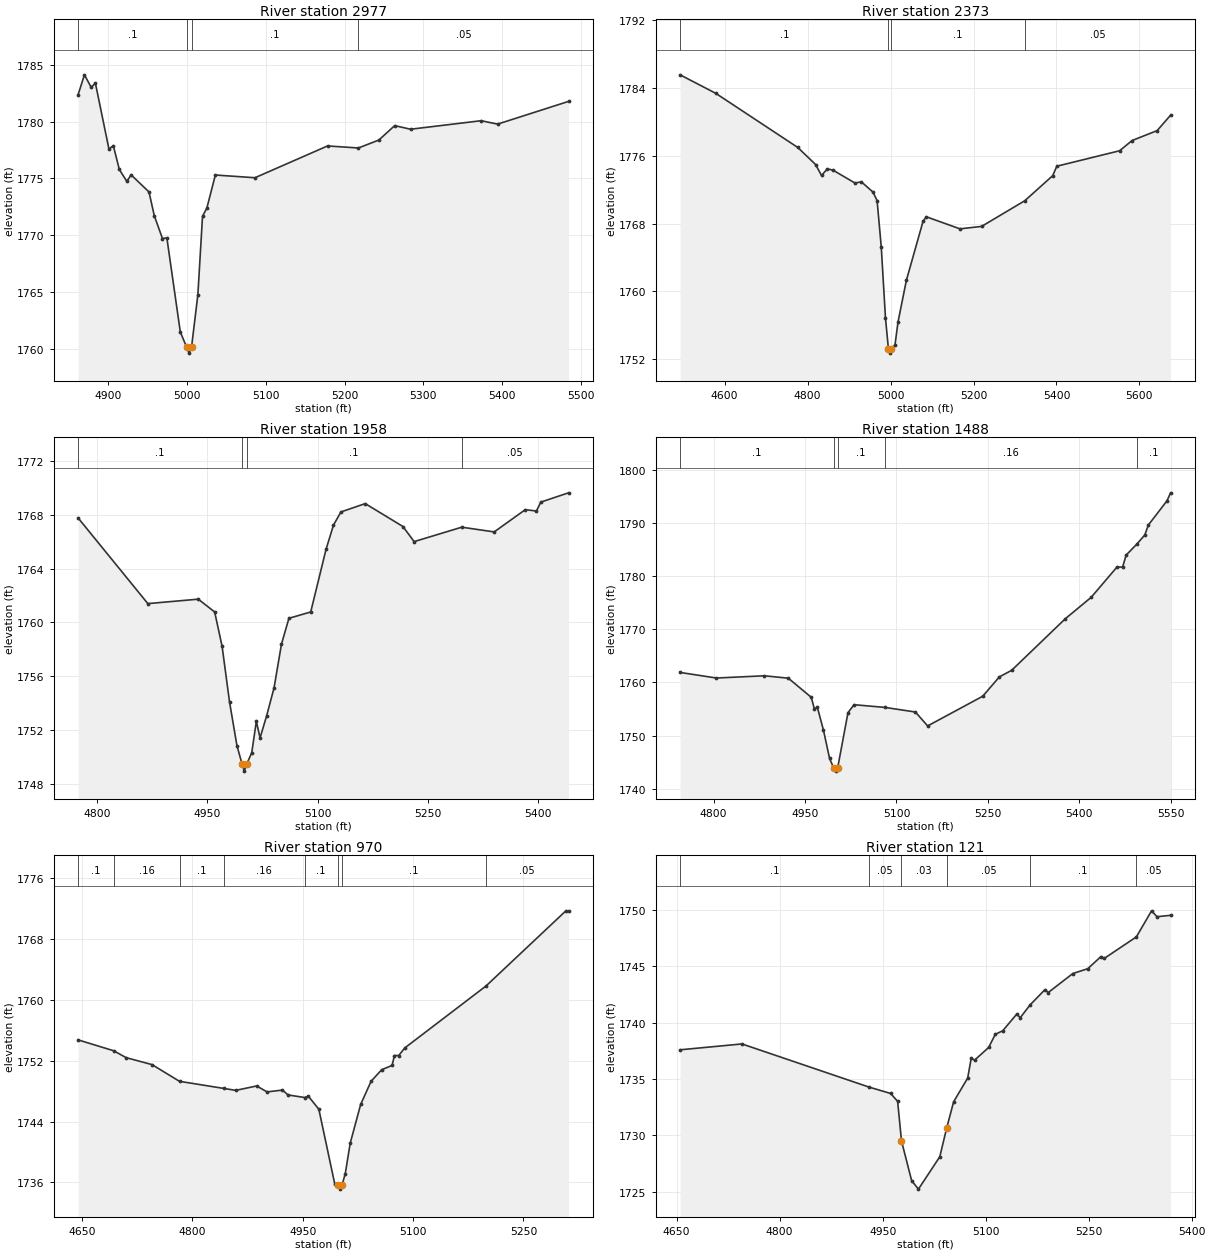
Type RM Length L Ch R = 1 ,2977    ,604,604,604
BEGIN DESCRIPTION:
UNT036 IN NNOGR 6.0
END DESCRIPTION:
XS GIS Cut Line= 3
      2778611.87     10095531.04      2778514.66     10095327.94
      2778118.83     10095288.01
#Sta/Elev= 30
  4861.5 1782.36  4869.6 1784.12    4878 1783.04  4883.6 1783.36  4900.7 1777.59
  4906.3 1777.88  4913.9 1775.79  4923.4 1774.74  4928.9 1775.31  4951.6 1773.81
  4958.3 1771.72  4968.7 1769.71  4974.3 1769.77  4991.4 1761.47  4999.6 1760.12
  5002.4 1759.62  5005.6 1760.12  5013.7 1764.78  5019.6 1771.67  5025.1 1772.39
  5035.9  1775.3  5086.2 1775.06  5178.4 1777.86  5217.6 1777.68  5243.6 1778.38
  5263.7 1779.65  5283.8 1779.33  5373.5 1780.08  5394.4 1779.78  5484.5 1781.78
#Mann= 4 ,-1 , 0
  4861.5      .1       0  4999.6     .07       0  5005.6      .1       0
  5217.6     .05       0
Bank Sta=4999.6,5005.6
XS Rating Curve= 0 ,0
Exp/Cntr=0.3,0.1

Type RM Length L Ch R = 1 ,2373    ,415,415,415
BEGIN DESCRIPTION:
UNT036 IN NNOGR 5.0
END DESCRIPTION:
XS GIS Cut Line= 3
      2779194.47     10095307.93      2778871.58     10095037.12
       2778116.4     10095130.87
#Sta/Elev= 30
  4492.7 1785.55  4578.6 1783.37  4776.4 1776.98  4819.3 1774.97  4833.6 1773.68
  4847.9 1774.47  4862.2 1774.28  4914.1 1772.79  4929.8 1772.92  4957.6 1771.72
  4967.6 1770.72  4977.7  1765.2  4987.8 1756.86  4994.9 1753.22  4997.6 1752.72
  5000.9 1753.22  5010.7 1753.67    5018 1756.38  5038.2 1761.31  5078.5 1768.29
  5086.5  1768.8  5167.4 1767.38  5219.6 1767.67  5323.7  1770.7  5390.9 1773.65
  5400.9 1774.77  5552.1 1776.59  5582.3  1777.8  5642.8 1778.97  5675.1 1780.79
#Mann= 4 ,-1 , 0
  4492.7      .1       0  4994.9     .07       0  5000.9      .1       0
  5323.7     .05       0
Bank Sta=4994.9,5000.9
XS Rating Curve= 0 ,0
Exp/Cntr=0.3,0.1

Type RM Length L Ch R = 1 ,1958    ,470,470,470
BEGIN DESCRIPTION:
UNT036 IN NNOGR 4.0
END DESCRIPTION:
XS GIS Cut Line= 3
      2778962.51     10094720.28      2778594.01      10094672.1
      2778346.57     10094832.29
#Sta/Elev= 30
  4774.5 1767.76  4869.3  1761.4  4937.8 1761.73  4960.1 1760.78  4970.2 1758.23
  4980.3  1754.1  4990.4 1750.85  4997.5 1749.47  5000.2 1748.97  5003.5 1749.47
  5010.5 1750.34  5016.7 1752.66  5021.8 1751.44  5030.7 1753.07  5040.8 1755.15
  5050.9  1758.4    5061 1760.31  5090.6 1760.78  5111.4 1765.42  5121.5 1767.22
  5131.6  1768.2  5164.7 1768.82  5215.9 1767.12  5231.1    1766  5295.8 1767.07
  5339.9 1766.72  5382.1 1768.37  5397.3 1768.27  5403.2 1768.93  5440.9 1769.62
#Mann= 4 ,-1 , 0
  4774.5      .1       0  4997.5     .07       0  5003.5      .1       0
  5295.8     .05       0
Bank Sta=4997.5,5003.5
XS Rating Curve= 0 ,0
Exp/Cntr=0.3,0.1

Type RM Length L Ch R = 1 ,1488    ,518,518,518
BEGIN DESCRIPTION:
UNT036 IN NNOGR 3.0
END DESCRIPTION:
XS GIS Cut Line= 4
      2779017.17     10094407.75      2778918.23     10094263.25
      2778569.27     10094228.09      2778334.21     10094078.27
#Sta/Elev= 30
  4745.1 1761.86  4804.6 1760.81  4883.3 1761.23  4922.6 1760.78  4960.2 1757.19
  4965.3 1755.03  4970.3 1755.28  4980.3 1750.99  4990.3 1745.68  4997.4  1743.8
  5000.1  1743.3  5003.4  1743.8  5020.5  1754.3  5030.5 1755.79  5080.6 1755.29
  5131.1 1754.42  5151.2  1751.8  5241.6 1757.39  5268.8 1761.02    5289 1762.26
    5377 1771.96  5419.4 1775.98  5461.7 1781.67    5471 1781.69  5476.9 1783.94
  5493.8 1785.93  5507.4 1787.71  5513.3 1789.59  5543.8 1794.14  5549.7 1795.64
#Mann= 5 ,-1 , 0
  4745.1      .1       0  4997.4     .07       0  5003.4      .1       0
  5080.6     .16       0  5493.8      .1       0
Bank Sta=4997.4,5003.4
XS Rating Curve= 0 ,0
Exp/Cntr=0.3,0.1

Type RM Length L Ch R = 1 ,970     ,849,849,849
BEGIN DESCRIPTION:
UNT036 IN NNOGR 2.0
END DESCRIPTION:
XS GIS Cut Line= 3
      2779137.21     10094037.12      2778850.31     10093713.95
      2778616.17     10093716.37
#Sta/Elev= 30
  4644.9 1754.74  4693.5  1753.3  4710.2  1752.4  4745.3 1751.49  4782.7 1749.29
  4842.6 1748.36  4859.1  1748.1  4887.5 1748.68  4901.7  1747.9  4922.6 1748.14
  4930.1  1747.5  4952.8 1747.16  4957.7 1747.34    4972 1745.62  4993.7 1735.76
  4997.4 1735.62  5000.1 1735.12  5003.4 1735.62  5007.9 1737.16  5014.6 1741.15
  5028.8 1746.25    5043  1749.3  5057.3 1750.81  5071.5 1751.38  5074.7 1752.68
  5080.5 1752.68  5088.9 1753.69  5199.1 1761.82  5307.6  1771.7  5311.2  1771.7
#Mann= 8 ,-1 , 0
  4644.9      .1       0  4693.5     .16       0  4782.7      .1       0
  4842.6     .16       0  4952.8      .1       0  4997.4     .07       0
  5003.4      .1       0  5199.1     .05       0
Bank Sta=4997.4,5003.4
XS Rating Curve= 0 ,0
Exp/Cntr=0.3,0.1

Type RM Length L Ch R = 1 ,121     ,0,0,0
BEGIN DESCRIPTION:
UNT036 IN NNOGR 1.0
END DESCRIPTION:
XS GIS Cut Line= 4
      2779423.44     10093418.23      2779393.47     10093149.02
      2779204.69     10093110.91      2778961.64     10093172.96
#Sta/Elev= 30
    4655 1737.58  4745.1  1738.1  4929.9 1734.28  4961.6 1733.71  4971.8 1733.01
  4977.4 1729.51  4992.2 1725.98  5002.1 1725.23  5033.2  1728.1  5043.2 1730.64
  5053.4 1732.98  5073.8 1735.07  5078.9 1736.81    5084 1736.67  5104.4 1737.79
    5114 1738.95  5124.9 1739.27  5145.2 1740.74  5150.4 1740.43  5164.7 1741.56
  5186.1  1742.9  5191.2 1742.66  5226.9 1744.34  5248.7 1744.77  5267.8 1745.84
  5272.9 1745.69  5319.5 1747.59  5341.6  1749.9  5349.5 1749.38  5369.3  1749.5
#Mann= 6 ,-1 , 0
    4655      .1       0  4929.9     .05       0  4977.4     .03       0
  5043.2     .05       0  5164.7      .1       0  5319.5     .05       0
Bank Sta=4977.4,5043.2
XS Rating Curve= 0 ,0
Exp/Cntr=0.3,0.1

Chan Stop Cuts=-1
Use User Specified Reach Order=0
Composite Channel Slope=5