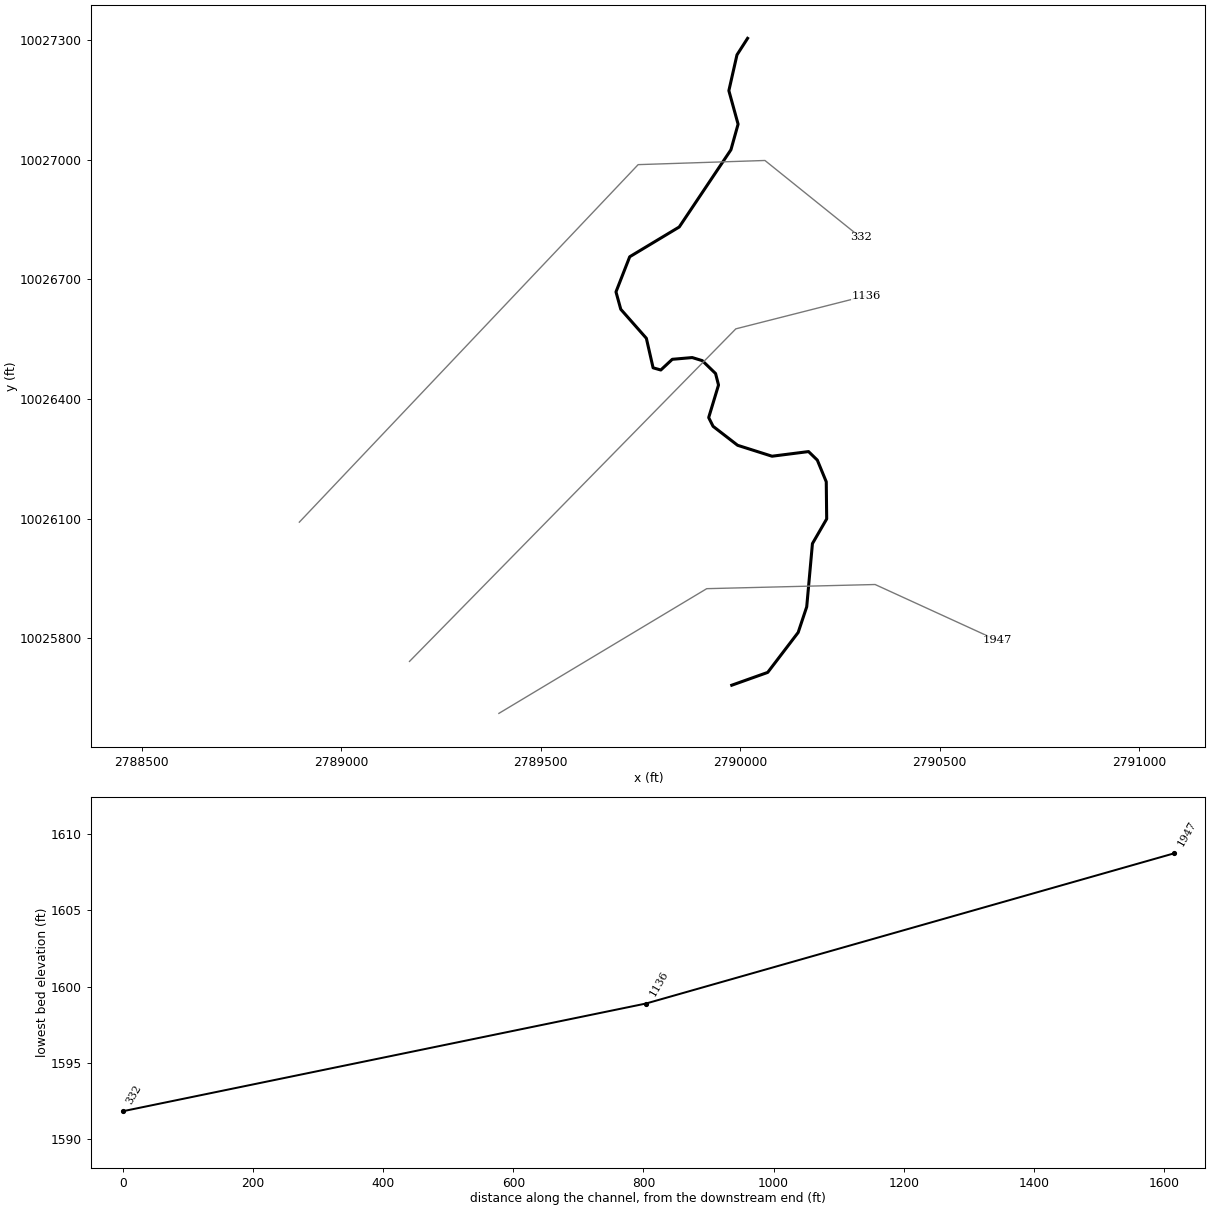
--- UNT036 IN SNOGR.prj (project) ---

Proj Title=UNT036 IN SNOGR Base Level Engineering
Current Plan=p01
Default Exp/Contr=0.3,0.1
English Units
Geom File=g01
Flow File=f01
Plan File=p01
Y Axis Title=Elevation
X Axis Title(PF)=Main Channel Distance
X Axis Title(XS)=Station
BEGIN DESCRIPTION:
UNT036 IN SNOGR
END DESCRIPTION:
DSS Export Rating Curves= 0
DSS Export Rating Curve Sorted= 0
DSS Export Volume Flow Curves= 0
DXF OffsetX= 0
DXF OffsetY= 0
DXF ScaleX= 1
DXF ScaleY= 10

--- UNT036 IN SNOGR.p01 (plan) ---

Plan Title=Multiple Run
Short Identifier=Multiple
Geom File=g01
Flow File=f01
Subcritical Flow
K Sum by GR= 0
Std Step Tol= 0.01
Critical Tol= 0.01
Num of Std Step Trials= 20
Max Error Tol= 0.3
Flow Tol Ratio= 0.001
Split Flow NTrial= 30
Split Flow Tol= 0.02
Split Flow Ratio= 0.02
Log Output Level= 0
Friction Slope Method= 1
Unsteady Friction Slope Method= 2
Unsteady Bridges Friction Slope Method= 1
Parabolic Critical Depth
Global Vel Dist=  1 , 1 , 1
Global Log Level= 0
CheckData=True
Encroach Param= -1, 0, 0, 0
BEGIN DESCRIPTION:
Multiple Run
END DESCRIPTION:

--- UNT036 IN SNOGR.f01 (steady flow) ---

Flow Title=Multiple
Number of Profiles=7
Profile Names=10-year,25-year,50-year,1pct_min,100-year,1pct_plu,500-year
River Rch & RM= UNT036 IN SNOGR,Reach-1,1947
     816    1186    1507    1404    1899    2568    3025
Boundary for River Rch & Prof#=UNT036 IN SNOGR,Reach-1,1
Up Type=0
Dn Type=3
Dn Slope=0.005
Boundary for River Rch & Prof#=UNT036 IN SNOGR,Reach-1,2
Up Type=0
Dn Type=3
Dn Slope=0.005
Boundary for River Rch & Prof#=UNT036 IN SNOGR,Reach-1,3
Up Type=0
Dn Type=3
Dn Slope=0.005
Boundary for River Rch & Prof#=UNT036 IN SNOGR,Reach-1,4
Up Type=0
Dn Type=3
Dn Slope=0.005
Boundary for River Rch & Prof#=UNT036 IN SNOGR,Reach-1,5
Up Type=0
Dn Type=3
Dn Slope=0.005
Boundary for River Rch & Prof#=UNT036 IN SNOGR,Reach-1,6
Up Type=0
Dn Type=3
Dn Slope=0.005
Boundary for River Rch & Prof#=UNT036 IN SNOGR,Reach-1,7
Up Type=0
Dn Type=3
Dn Slope=0.005

--- UNT036 IN SNOGR.g01 (geometry) ---

Geom Title=Existing Conditions
Program Version=4.10

River Reach=UNT036 IN SNOGR ,Reach-1
Reach XY= 30
      2789978.81     10025682.84       2790068.9     10025714.93
      2790145.25     10025815.06      2790166.64     10025879.27
      2790180.98     10026037.69      2790216.69     10026099.53
      2790215.61     10026192.58      2790193.22     10026246.89
      2790171.24     10026268.27      2790079.73     10026256.64
       2789993.5     10026284.01      2789932.02     10026331.54
      2789920.99     10026353.49      2789945.66       10026435.
      2789938.24     10026463.87        2789905.     10026496.11
      2789879.74     10026503.83       2789829.8     10026499.47
      2789801.05     10026472.66      2789781.71     10026478.15
      2789764.86     10026552.09      2789700.71     10026624.89
      2789688.71     10026668.39      2789723.13     10026756.43
      2789847.23     10026831.03      2789976.77     10027024.53
      2789994.69     10027088.64      2789971.56     10027172.62
      2789991.88     10027262.29      2790018.47     10027303.73

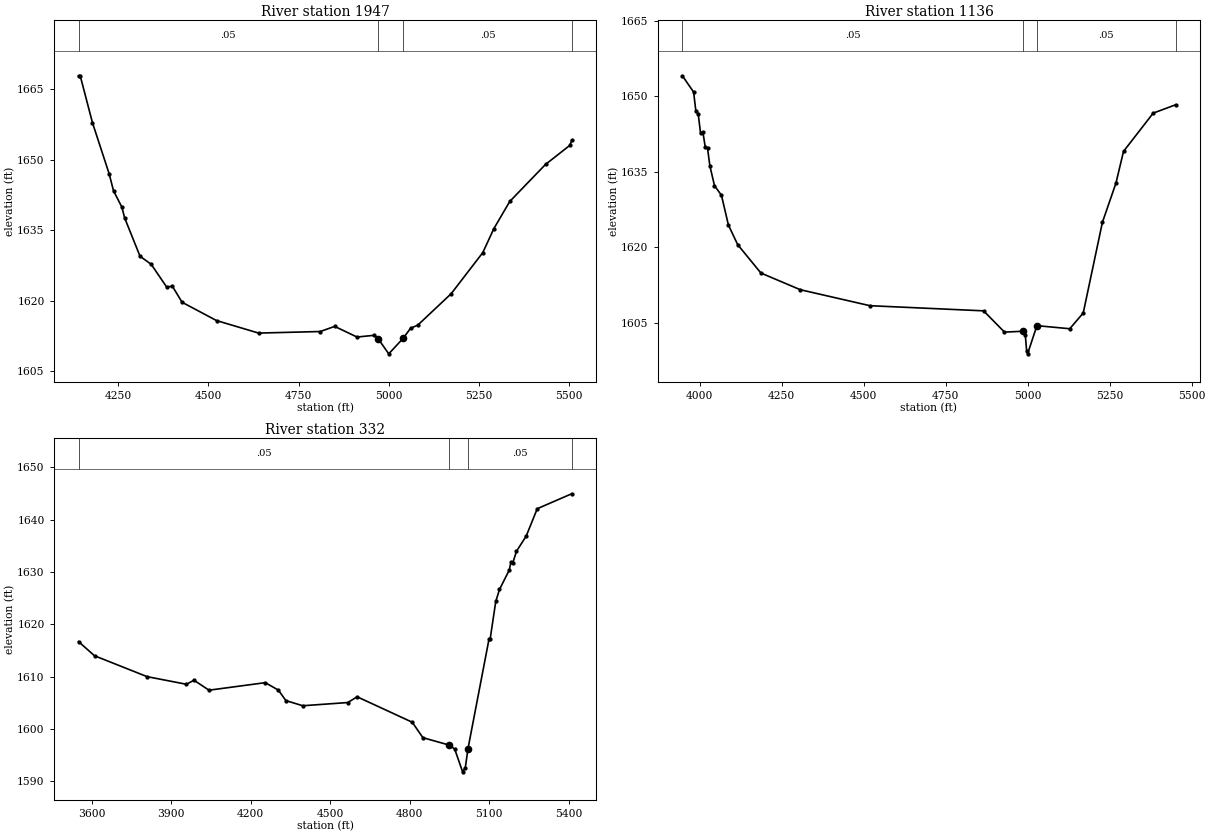
Type RM Length L Ch R = 1 ,1947    ,811,811,811
BEGIN DESCRIPTION:
UNT036 IN SNOGR 2.0
END DESCRIPTION:
XS GIS Cut Line= 4
      2789395.33     10025612.28      2789916.12     10025924.76
        2790338.     10025935.17      2790644.39     10025794.96
#Sta/Elev= 30
  4140.2  1667.8  4144.9  1667.8  4178.8 1657.84  4225.1 1646.98  4237.2 1643.36
  4260.5 1639.88  4267.8 1637.65  4310.6 1629.47  4341.7 1627.75  4384.5 1622.91
    4400 1623.12  4427.2 1619.69  4522.5 1615.81  4639.1 1613.15  4809.9 1613.48
  4849.9 1614.57  4911.7 1612.31    4960 1612.68    4970 1611.99  4999.7 1608.74
    5040 1612.07    5060 1614.17    5080 1614.83  5172.6 1621.51  5260.3 1630.25
    5291 1635.35    5335 1641.11    5434 1648.97  5501.5 1653.03  5506.5 1654.08
#Mann= 4 ,-1 , 0
  4140.2     .05       0    4970     .03       0    5040     .05       0
  5506.5      .1       0
Bank Sta=4970,5040
XS Rating Curve= 0 ,0
Exp/Cntr=0.3,0.1

Type RM Length L Ch R = 1 ,1136    ,804,804,804
BEGIN DESCRIPTION:
Mapping XS 07a233a6
END DESCRIPTION:
XS GIS Cut Line= 3
      2789171.33     10025742.47      2789989.04      10026575.8
      2790314.49     10026658.45
#Sta/Elev= 30
  3947.6 1654.05  3981.8 1650.83  3988.9 1646.98  3995.9 1646.49  4003.1  1642.6
  4010.1 1642.91  4017.2 1639.95  4024.2 1639.72  4031.4 1636.19  4045.5 1632.25
  4066.7 1630.35  4087.9 1624.45  4116.2 1620.55    4187 1614.92  4307.1 1611.61
  4519.3 1608.44  4865.7 1607.42  4929.5  1603.2    4986 1603.37    4993 1602.57
  4997.1 1599.39  4999.9 1598.89  5028.3 1604.48  5128.5 1603.87  5169.5 1606.99
    5228 1624.99  5269.3 1632.77  5292.3 1639.05  5382.8 1646.64  5450.9 1648.29
#Mann= 4 ,-1 , 0
  3947.6     .05       0    4986     .03       0  5028.3     .05       0
  5450.9      .1       0
Bank Sta=4986,5028.3
XS Rating Curve= 0 ,0
Exp/Cntr=0.3,0.1

Type RM Length L Ch R = 1 ,332     ,0,0,0
BEGIN DESCRIPTION:
UNT036 IN SNOGR 1.0
END DESCRIPTION:
XS GIS Cut Line= 4
      2788895.28     10026091.42      2789744.25     10026987.26
      2790061.96     10026997.67      2790301.58     10026804.94
#Sta/Elev= 30
  3550.8 1616.71  3611.1    1614  3809.3 1610.01  3957.8 1608.55  3986.1 1609.33
  4042.8 1607.42  4255.1 1608.86  4304.5 1607.43  4332.8 1605.43  4396.3 1604.45
  4566.2 1605.06  4601.4 1606.16  4809.2  1601.3  4849.3 1598.35  4949.3 1596.92
  4969.3 1596.17  4999.1 1591.82  5009.3 1592.61  5019.4 1596.25  5098.6 1617.16
  5102.9 1617.16  5124.1 1624.37  5138.2 1626.67    5175 1630.37  5181.4  1631.9
  5188.2 1631.71  5202.2 1633.96    5239 1636.88  5280.6  1642.1  5410.4 1644.95
#Mann= 4 ,-1 , 0
  3550.8     .05       0  4949.3     .03       0  5019.4     .05       0
  5410.4      .1       0
Bank Sta=4949.3,5019.4
XS Rating Curve= 0 ,0
Exp/Cntr=0.3,0.1

Chan Stop Cuts=-1
Use User Specified Reach Order=0
Composite Channel Slope=5