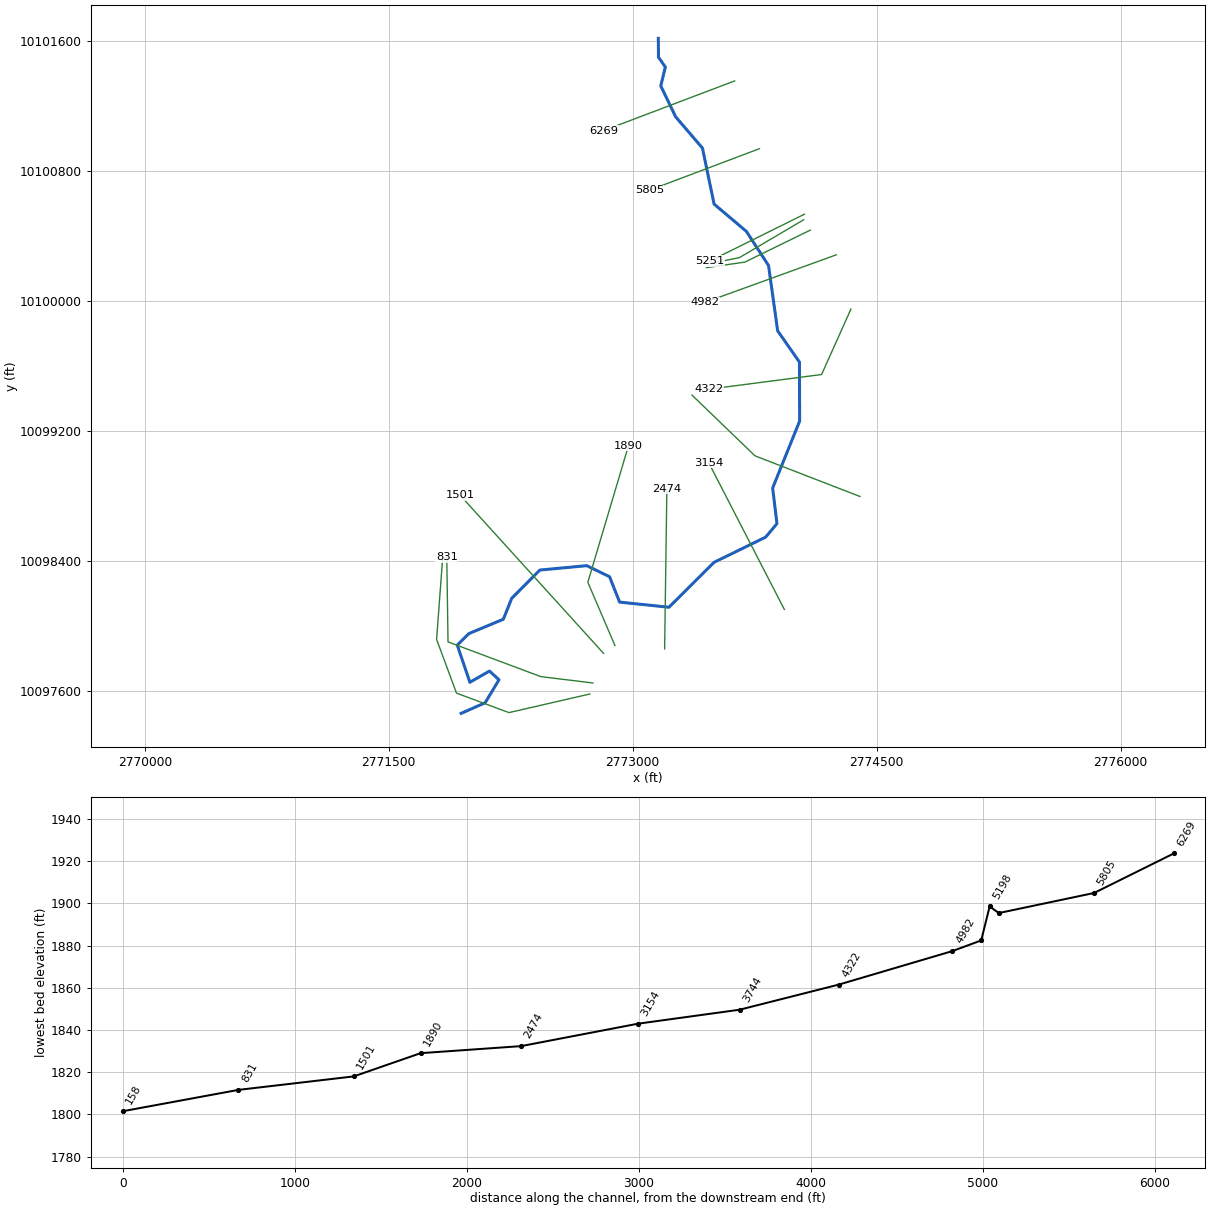
--- UNT038 IN NNOGR.prj (project) ---

Proj Title=UNT038 IN NNOGR Base Level Engineering
Current Plan=p01
Default Exp/Contr=0.3,0.1
English Units
Geom File=g01
Flow File=f01
Plan File=p01
Y Axis Title=Elevation
X Axis Title(PF)=Main Channel Distance
X Axis Title(XS)=Station
BEGIN DESCRIPTION:
UNT038 IN NNOGR
END DESCRIPTION:
DSS Export Rating Curves= 0
DSS Export Rating Curve Sorted= 0
DSS Export Volume Flow Curves= 0
DXF OffsetX= 0
DXF OffsetY= 0
DXF ScaleX= 1
DXF ScaleY= 10

--- UNT038 IN NNOGR.p01 (plan) ---

Plan Title=Multiple Run
Short Identifier=Multiple
Geom File=g01
Flow File=f01
Subcritical Flow
K Sum by GR= 0
Std Step Tol= 0.01
Critical Tol= 0.01
Num of Std Step Trials= 20
Max Error Tol= 0.3
Flow Tol Ratio= 0.001
Split Flow NTrial= 30
Split Flow Tol= 0.02
Split Flow Ratio= 0.02
Log Output Level= 0
Friction Slope Method= 1
Unsteady Friction Slope Method= 2
Unsteady Bridges Friction Slope Method= 1
Parabolic Critical Depth
Global Vel Dist=  1 , 1 , 1
Global Log Level= 0
CheckData=True
Encroach Param= -1, 0, 0, 0
BEGIN DESCRIPTION:
Multiple Run
END DESCRIPTION:

--- UNT038 IN NNOGR.f01 (steady flow) ---

Flow Title=Multiple
Program Version=4.10
Number of Profiles= 7
Profile Names=10-year,25-year,50-year,1pct_min,100-year,1pct_plu,500-year
River Rch & RM=UNT038 IN NNOGR,Reach-1         ,6269
     375     518     637     576     779    1054    1167
River Rch & RM=UNT038 IN NNOGR,Reach-1         ,3744
     778    1124    1425    1324    1790    2421    2834
Boundary for River Rch & Prof#=UNT038 IN NNOGR,Reach-1         , 1
Up Type= 0
Dn Type= 3
Dn Slope=0.0126
Boundary for River Rch & Prof#=UNT038 IN NNOGR,Reach-1         , 2
Up Type= 0
Dn Type= 3
Dn Slope=0.0126
Boundary for River Rch & Prof#=UNT038 IN NNOGR,Reach-1         , 3
Up Type= 0
Dn Type= 3
Dn Slope=0.0126
Boundary for River Rch & Prof#=UNT038 IN NNOGR,Reach-1         , 4
Up Type= 0
Dn Type= 3
Dn Slope=0.0126
Boundary for River Rch & Prof#=UNT038 IN NNOGR,Reach-1         , 5
Up Type= 0
Dn Type= 3
Dn Slope=0.0126
Boundary for River Rch & Prof#=UNT038 IN NNOGR,Reach-1         , 6
Up Type= 0
Dn Type= 3
Dn Slope=0.0126
Boundary for River Rch & Prof#=UNT038 IN NNOGR,Reach-1         , 7
Up Type= 0
Dn Type= 3
Dn Slope=0.0126
DSS Import GetInterval= 0
DSS Import GetPeak= 0
DSS Import FillOption= 0

--- UNT038 IN NNOGR.g01 (geometry) ---

Geom Title=Existing Conditions
Program Version=4.10

River Reach=UNT038 IN NNOGR ,Reach-1
Reach XY= 30
      2773157.48     10101613.68      2773158.58     10101497.32
       2773200.6     10101437.23       2773172.6     10101320.94
        2773264.     10101131.16      2773428.83     10100938.88
      2773500.45     10100594.34       2773698.8      10100426.8
      2773835.24     10100216.75      2773891.36     10099814.93
      2774025.43     10099622.84      2774026.46     10099259.56
      2773860.53     10098848.28      2773887.07      10098629.3
      2773817.51     10098546.24      2773500.09      10098391.2
      2773222.77     10098115.19      2772919.47     10098146.55
       2772857.5     10098302.93      2772717.18     10098370.78
      2772428.47     10098343.73       2772255.9     10098170.16
      2772204.49     10098041.39      2771992.12     10097952.82
      2771921.14     10097882.29      2771998.61     10097653.66
      2772119.15     10097722.69      2772177.67     10097669.09
      2772092.54     10097527.75      2771944.75     10097462.42

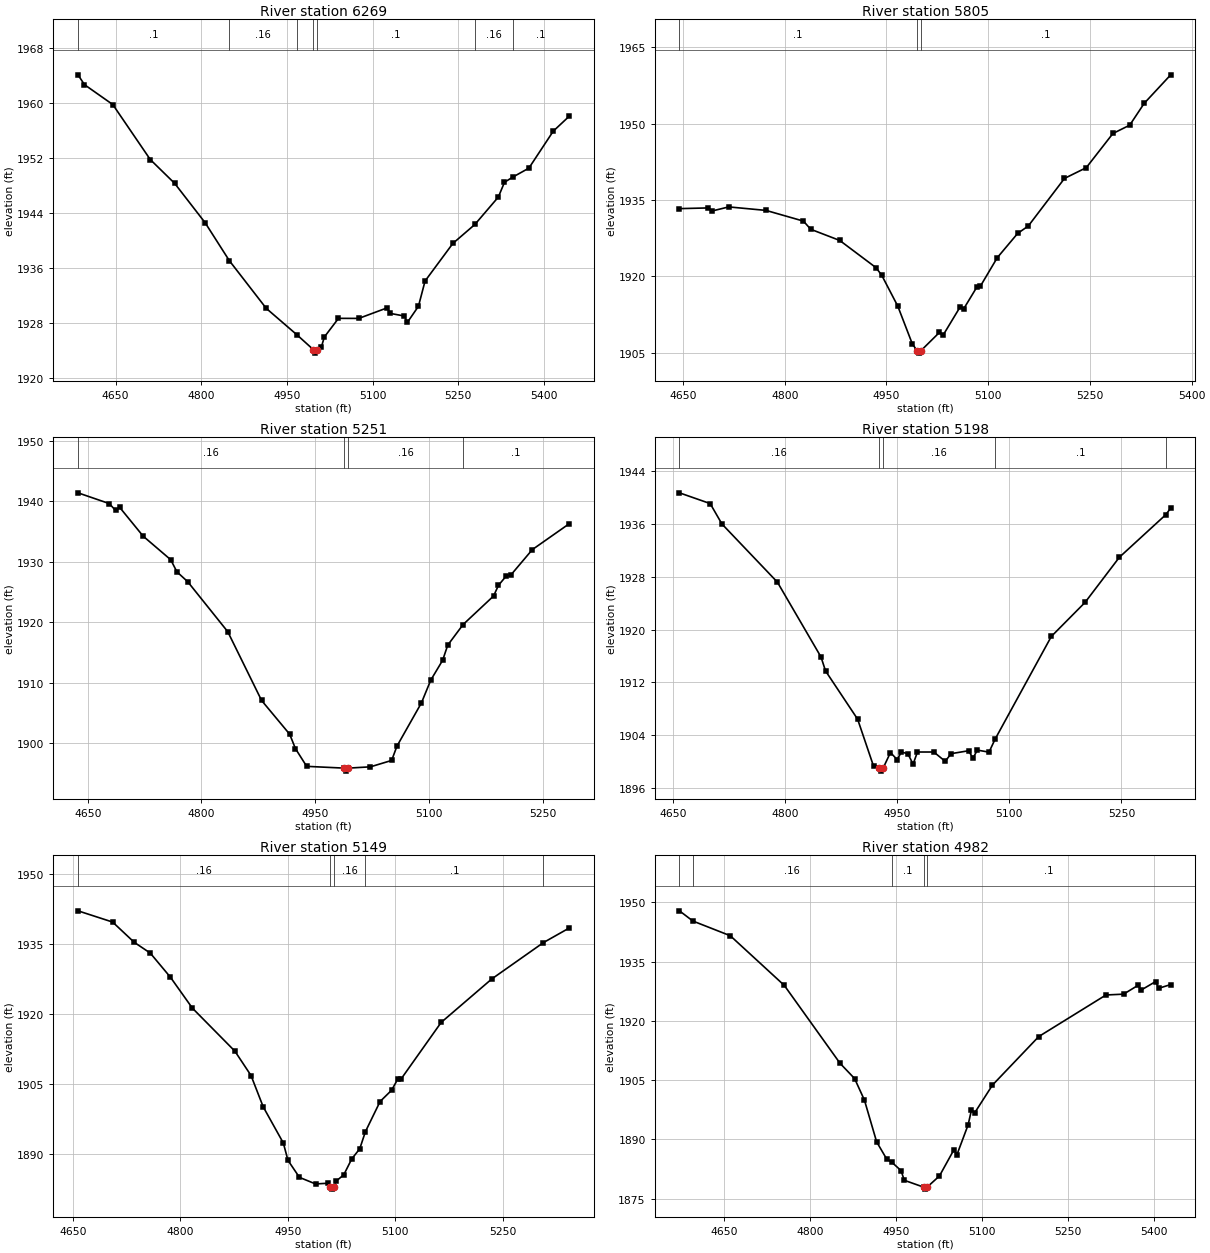
Type RM Length L Ch R = 1 ,6269    ,464,464,464
BEGIN DESCRIPTION:
UNT038 IN NNOGR 13.0
END DESCRIPTION:
XS GIS Cut Line= 2
      2773626.76     10101351.78      2772822.38     10101046.67
#Sta/Elev= 30
  4584.2 1964.05  4595.6 1962.62  4645.2 1959.73  4710.8 1951.75  4753.5 1948.29
    4807 1942.56  4849.3 1937.06  4913.9 1930.14  4967.9 1926.28  4996.5 1924.14
  4999.2 1923.64  5002.5 1924.14  5010.2 1924.46  5015.6 1925.98  5040.4 1928.69
  5075.9 1928.68  5125.5 1930.21  5130.9 1929.41  5155.6 1929.03    5161  1928.1
  5180.4 1930.44    5192 1934.11  5240.7 1939.57  5279.2 1942.32  5320.3  1946.3
  5331.1 1948.45  5345.4 1949.19  5373.8  1950.5  5416.6 1955.88  5444.5 1958.04
#Mann= 7 ,-1 , 0
  4584.2      .1       0  4849.3     .16       0  4967.9      .1       0
  4996.5     .07       0  5002.5      .1       0  5279.2     .16       0
  5345.4      .1       0
Bank Sta=4996.5,5002.5
XS Rating Curve= 0 ,0
Exp/Cntr=0.3,0.1

Type RM Length L Ch R = 1 ,5805    ,554,554,554
BEGIN DESCRIPTION:
UNT038 IN NNOGR 12.0
END DESCRIPTION:
XS GIS Cut Line= 2
      2773779.58     10100935.13      2773101.97     10100679.29
#Sta/Elev= 30
  4644.8 1933.29  4687.3 1933.43  4692.7 1932.82  4717.5 1933.63  4772.5 1932.94
  4827.6 1930.84  4838.4 1929.23  4881.1 1927.04  4934.6 1921.69    4943 1920.21
  4966.7 1914.13    4988 1906.76    4995 1905.39  4997.8 1904.89    5001 1905.39
  5028.2 1908.97  5033.5 1908.41  5058.4 1913.91  5063.7 1913.55  5083.2 1917.85
  5088.6 1918.07  5113.4 1923.65  5143.6 1928.44  5159.1 1929.87  5212.5 1939.23
  5244.6 1941.34  5283.9 1948.06  5308.7  1949.7  5330.1    1954  5369.1 1959.59
#Mann= 3 ,-1 , 0
  4644.8      .1       0    4995     .07       0    5001      .1       0
Bank Sta=4995,5001
XS Rating Curve= 0 ,0
Exp/Cntr=0.3,0.1

Type RM Length L Ch R = 1 ,5251    ,53,53,53
BEGIN DESCRIPTION:
UNT038 IN NNOGR 11.0
END DESCRIPTION:
XS GIS Cut Line= 2
      2774055.51     10100531.83      2773474.79     10100244.08
#Sta/Elev= 30
  4637.1 1941.41  4678.4 1939.63  4686.6 1938.51  4692.2 1938.99  4723.1 1934.24
  4759.4 1930.35  4767.7 1928.33  4781.8 1926.72  4834.7 1918.44  4879.3 1907.07
  4916.4 1901.48    4924  1899.1  4938.8 1896.17  4987.9 1895.88  4990.7 1895.38
  4993.9 1895.88  5022.9 1896.09  5050.9 1897.15  5057.9 1899.51  5090.2 1906.67
  5102.5 1910.43  5118.2 1913.72  5124.9 1916.22  5145.2 1919.63  5185.4 1924.35
  5191.8 1926.11  5202.3 1927.69  5207.9 1927.78  5236.5 1932.02  5285.2  1936.3
#Mann= 4 ,-1 , 0
  4637.1     .16       0  4987.9     .07       0  4993.9     .16       0
  5145.2      .1       0
Bank Sta=4987.9,4993.9
XS Rating Curve= 0 ,0
Exp/Cntr=0.3,0.1

Type RM Length L Ch R = 1 ,5198    ,49,49,49
BEGIN DESCRIPTION:
Mapping XS 2eb9a06e
END DESCRIPTION:
XS GIS Cut Line= 3
      2774051.61     10100497.98      2773655.74     10100264.89
      2773461.97     10100226.14
#Sta/Elev= 30
  4658.9 1940.76    4700 1939.13  4715.7 1936.04  4789.9 1927.21  4848.2 1915.86
  4854.3 1913.74  4897.2 1906.42  4918.6 1899.26  4925.5 1899.04  4928.2 1898.54
  4931.5 1899.04  4941.1 1901.36    4950  1900.3  4955.8 1901.43  4964.3 1901.19
  4971.4  1899.6  4977.2 1901.44  4999.1 1901.44  5014.3 1900.03  5022.3 1901.19
  5045.5 1901.63  5051.5 1900.52  5057.3 1901.73  5072.9 1901.42  5081.2 1903.42
  5156.3 1918.98  5201.4 1924.14  5247.3 1930.99  5309.4 1937.45  5315.9 1938.45
#Mann= 5 ,-1 , 0
  4658.9     .16       0  4925.5     .07       0  4931.5     .16       0
  5081.2      .1       0  5309.4     .05       0
Bank Sta=4925.5,4931.5
XS Rating Curve= 0 ,0
Exp/Cntr=0.3,0.1

Type RM Length L Ch R = 1 ,5149    ,167,167,167
BEGIN DESCRIPTION:
Mapping XS 3614bc07
END DESCRIPTION:
XS GIS Cut Line= 3
      2774091.92     10100434.15       2773689.6     10100237.55
       2773453.9     10100203.69
#Sta/Elev= 30
  4657.2 1942.04  4705.6 1939.63  4735.6 1935.31  4758.1 1932.99  4786.2 1927.83
  4816.9  1921.2  4876.3 1911.97  4898.8 1906.76  4915.8 1900.05  4943.9  1892.3
  4950.4 1888.58  4966.4 1884.94  4988.9 1883.53  5005.8 1883.68  5008.4 1882.92
  5011.2 1882.42  5014.4 1882.92  5017.2 1884.08  5028.3 1885.49  5039.5 1888.91
  5050.6 1891.06  5058.5 1894.73    5079 1901.19  5095.1 1903.61  5103.6 1905.97
  5108.1 1905.97  5164.3 1918.14  5234.9 1927.44  5307.1 1935.24  5343.1 1938.36
#Mann= 5 ,-1 , 0
  4657.2     .16       0  5008.4     .07       0  5014.4     .16       0
  5058.5      .1       0  5307.1     .05       0
Bank Sta=5008.4,5014.4
XS Rating Curve= 0 ,0
Exp/Cntr=0.3,0.1

Type RM Length L Ch R = 1 ,4982    ,660,660,660
BEGIN DESCRIPTION:
UNT038 IN NNOGR 10.0
END DESCRIPTION:
XS GIS Cut Line= 2
      2774251.79     10100282.34      2773446.26     10099990.69
#Sta/Elev= 30
  4572.3 1947.85  4595.8 1945.26  4660.9 1941.55  4755.2 1928.96  4852.5 1909.22
  4877.8 1905.37  4894.9 1899.92  4916.2 1889.34  4933.8 1884.98  4942.4 1884.22
  4958.7 1882.08  4964.4 1879.62  4998.2 1877.88    5001 1877.38  5004.2 1877.88
  5025.7 1880.71    5051 1887.36  5056.3 1886.12  5075.7 1893.65  5081.6 1897.43
    5087 1896.66  5118.2 1903.73  5198.9 1916.01  5316.1 1926.54  5346.8 1926.75
  5372.1 1928.99  5377.4 1927.78  5402.7 1929.94    5408 1928.23    5429 1929.18
#Mann= 5 ,-1 , 0
  4572.3      .1       0  4595.8     .16       0  4942.4      .1       0
  4998.2     .07       0  5004.2      .1       0
Bank Sta=4998.2,5004.2
XS Rating Curve= 0 ,0
Exp/Cntr=0.3,0.1

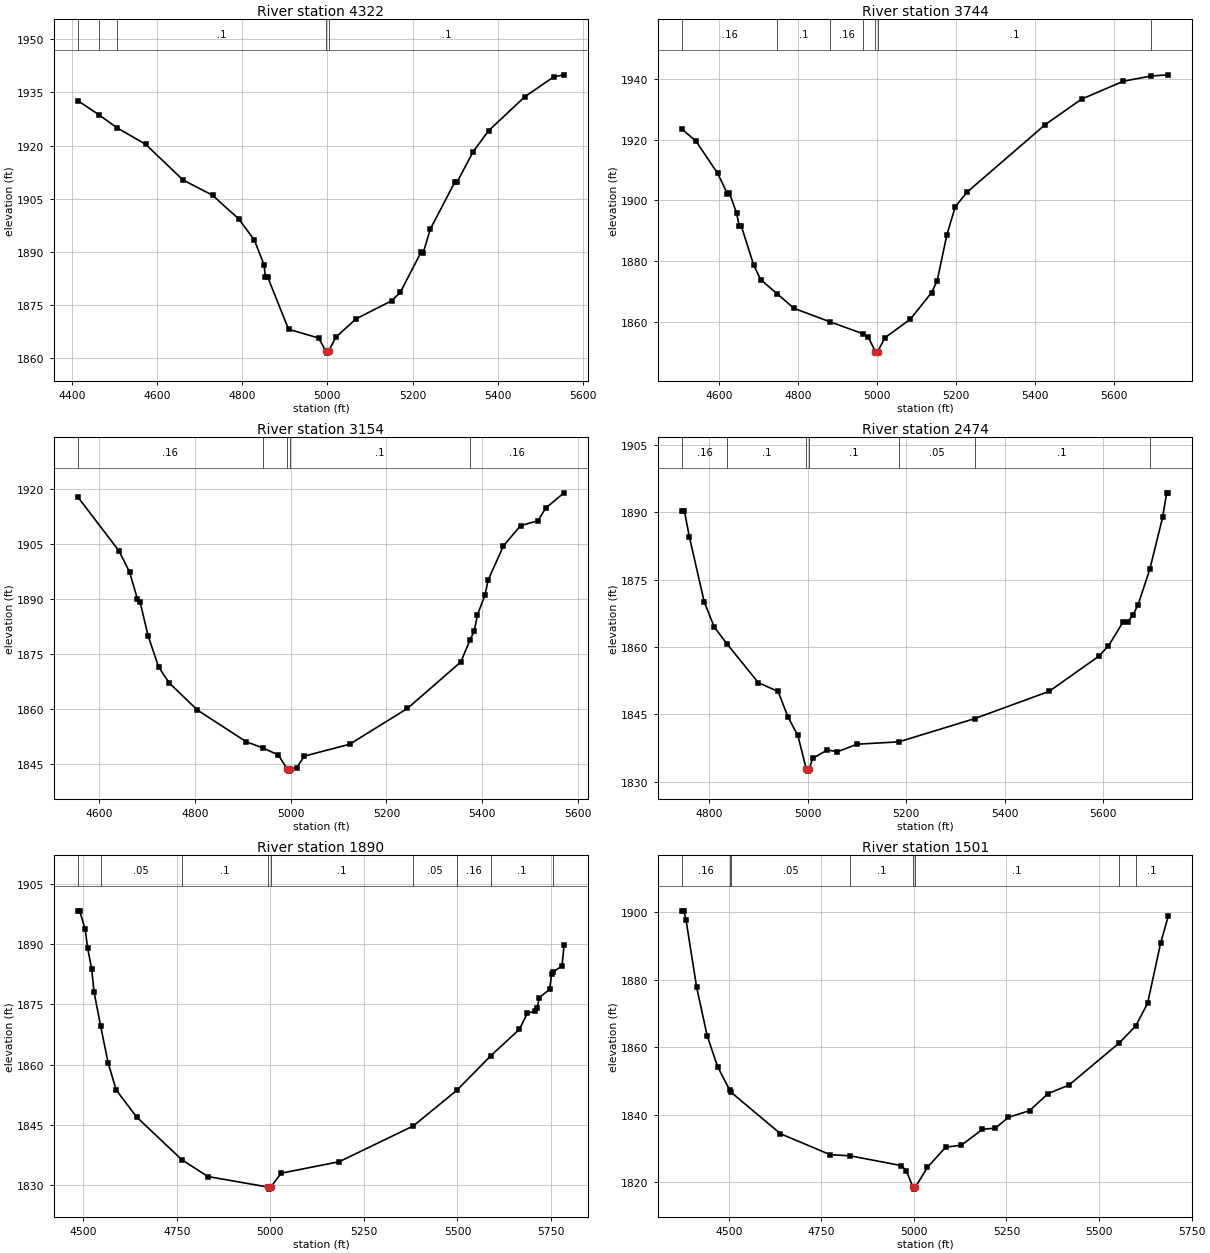
Type RM Length L Ch R = 1 ,4322    ,578,578,578
BEGIN DESCRIPTION:
UNT038 IN NNOGR 9.0
END DESCRIPTION:
XS GIS Cut Line= 3
      2774342.07     10099949.01      2774161.51     10099546.23
      2773467.05     10099455.95
#Sta/Elev= 30
  4414.1 1932.63  4464.5 1928.57  4505.2 1925.06  4573.3 1920.34    4661 1910.29
  4730.3 1905.99  4792.5 1899.24  4828.6 1893.35  4851.7 1886.27  4854.1 1883.04
  4859.5 1883.04  4908.8 1868.24  4979.6 1865.76  4996.7 1862.01  4999.5 1861.51
  5002.7 1862.01  5019.9 1865.99  5067.1 1871.14  5151.2 1876.28  5171.2 1878.61
  5220.3    1890  5225.3 1889.84  5241.8 1896.46  5299.4 1909.71  5304.4 1909.66
  5342.6  1918.3  5378.5 1924.14  5463.6 1933.73  5531.7 1939.34  5555.8 1939.91
#Mann= 5 ,-1 , 0
  4414.1      .1       0  4464.5     .16       0  4505.2      .1       0
  4996.7     .07       0  5002.7      .1       0
Bank Sta=4996.7,5002.7
XS Rating Curve= 0 ,0
Exp/Cntr=0.3,0.1

Type RM Length L Ch R = 1 ,3744    ,590,590,590
BEGIN DESCRIPTION:
UNT038 IN NNOGR 8.0
END DESCRIPTION:
XS GIS Cut Line= 3
      2774397.62     10098796.24      2773751.79     10099046.23
      2773364.46     10099419.73
#Sta/Elev= 30
  4505.8 1923.45  4541.4 1919.45  4595.9 1908.91  4620.5 1902.22  4625.9 1902.37
  4644.3 1895.63  4650.4 1891.63  4655.8 1891.56  4687.2 1878.65  4704.9 1873.83
  4746.9 1869.13  4789.4 1864.35  4879.5 1859.95  4964.6 1855.93  4976.7 1855.04
  4995.2 1850.08  4997.9 1849.58  5001.2 1850.08  5019.6 1854.66  5083.9 1860.78
  5137.6 1869.56  5151.7 1873.45  5176.3 1888.64  5197.4 1897.82  5227.3 1902.67
  5425.2 1924.94  5517.2 1933.35  5623.2 1939.26  5693.1 1940.97  5736.4 1941.36
#Mann= 7 ,-1 , 0
  4505.8     .16       0  4746.9      .1       0  4879.5     .16       0
  4964.6      .1       0  4995.2     .07       0  5001.2      .1       0
  5693.1     .16       0
Bank Sta=4995.2,5001.2
XS Rating Curve= 0 ,0
Exp/Cntr=0.3,0.1

Type RM Length L Ch R = 1 ,3154    ,680,680,680
BEGIN DESCRIPTION:
UNT038 IN NNOGR 6.0
END DESCRIPTION:
XS GIS Cut Line= 2
      2773932.34      10098101.8      2773467.07     10099004.56
#Sta/Elev= 30
  4555.4 1917.73  4641.1 1903.07  4663.3 1897.31  4679.8 1889.92  4685.4  1889.1
    4702 1879.94  4724.1 1871.37  4746.3 1867.02  4805.1 1859.63  4907.1 1850.99
  4941.4  1849.3  4973.8 1847.42  4993.3 1843.47  4996.1 1842.97  4999.3 1843.47
  5012.3 1843.89  5028.8 1847.08  5123.1  1850.3  5243.8 1860.06  5355.6 1872.77
  5374.4 1878.72  5383.4 1881.14  5390.1 1885.62  5405.6 1890.89  5412.6 1895.13
  5444.3 1904.37  5480.1 1909.92  5516.4 1911.24    5533 1914.75    5571 1918.87
#Mann= 5 ,-1 , 0
  4555.4     .16       0  4941.4      .1       0  4993.3     .07       0
  4999.3      .1       0  5374.4     .16       0
Bank Sta=4993.3,4999.3
XS Rating Curve= 0 ,0
Exp/Cntr=0.3,0.1

Type RM Length L Ch R = 1 ,2474    ,584,584,584
BEGIN DESCRIPTION:
UNT038 IN NNOGR 5.0
END DESCRIPTION:
XS GIS Cut Line= 2
      2773196.23     10097858.76      2773210.12     10098844.86
#Sta/Elev= 30
  4745.4 1890.19  4750.4 1890.19  4760.4  1884.5  4790.4 1870.08  4810.4 1864.51
  4836.3 1860.72  4900.4 1852.03  4940.4 1850.08  4960.4  1844.4  4980.4 1840.28
  4997.4 1832.84  5000.1 1832.34  5003.4 1832.84  5010.4 1835.17  5040.4 1837.06
  5060.4 1836.64  5100.4 1838.34  5185.3 1838.86    5339 1844.03  5490.4 1850.12
  5590.5  1857.9  5610.5 1860.23  5640.5 1865.63  5650.5 1865.66  5660.5 1867.19
  5670.5  1869.4  5694.4 1877.33  5720.5 1888.95  5728.5 1894.32  5731.6 1894.32
#Mann= 7 ,-1 , 0
  4745.4     .16       0  4836.3      .1       0  4997.4     .07       0
  5003.4      .1       0  5185.3     .05       0    5339      .1       0
  5694.4     .16       0
Bank Sta=4997.4,5003.4
XS Rating Curve= 0 ,0
Exp/Cntr=0.3,0.1

Type RM Length L Ch R = 1 ,1890    ,389,389,389
BEGIN DESCRIPTION:
UNT038 IN NNOGR 3.0
END DESCRIPTION:
XS GIS Cut Line= 3
      2772890.68     10097879.58      2772724.01     10098268.46
      2772973.74     10099107.81
#Sta/Elev= 30
  4485.9 1898.25  4490.9 1898.25  4505.5 1893.61  4512.2  1888.9  4523.1  1883.7
    4529 1878.13  4546.6 1869.67  4566.6 1860.47  4588.3 1853.68  4642.7 1846.96
  4764.1 1836.28  4833.7 1832.12    4995  1829.5  4997.7    1829    5001  1829.5
  5029.3 1832.97  5184.1 1835.82  5381.9 1844.72    5498 1853.57  5589.7 1862.25
  5665.7 1868.79  5686.6 1872.79  5707.4 1873.25  5713.1 1874.01  5718.3 1876.63
  5746.3 1878.71  5751.5 1882.58  5755.4    1883  5779.5 1884.57  5784.7  1889.8
#Mann= 9 ,-1 , 0
  4485.9     .16       0  4546.6     .05       0  4764.1      .1       0
    4995     .07       0    5001      .1       0  5381.9     .05       0
    5498     .16       0  5589.7      .1       0  5755.4     .16       0
Bank Sta=4995,5001
XS Rating Curve= 0 ,0
Exp/Cntr=0.3,0.1

Type RM Length L Ch R = 1 ,1501    ,670,670,670
BEGIN DESCRIPTION:
UNT038 IN NNOGR 2.0
END DESCRIPTION:
XS GIS Cut Line= 2
      2772821.26     10097830.93      2771939.28     10098803.19
#Sta/Elev= 30
  4373.9 1900.38  4379.2 1900.38    4385 1897.55  4413.3 1877.85  4441.7 1863.47
  4470.1 1854.23    4503 1847.26    4506  1846.7  4639.7  1834.4  4774.2 1828.18
  4827.6 1827.86  4965.5 1824.97  4979.7 1823.46  4997.6 1818.49  5000.4 1817.99
  5003.6 1818.49  5036.4 1824.43  5085.8 1830.41  5128.3 1830.99  5185.1 1835.69
  5220.3 1836.06  5255.4 1839.26  5312.2 1841.21  5362.2 1846.27  5418.3 1848.77
  5553.6 1861.18    5599  1866.3  5631.1 1873.05  5666.3 1890.89  5686.6 1898.72
#Mann= 8 ,-1 , 0
  4373.9     .16       0    4503      .1       0    4506     .05       0
  4827.6      .1       0  4997.6     .07       0  5003.6      .1       0
  5553.6     .05       0    5599      .1       0
Bank Sta=4997.6,5003.6
XS Rating Curve= 0 ,0
Exp/Cntr=0.3,0.1

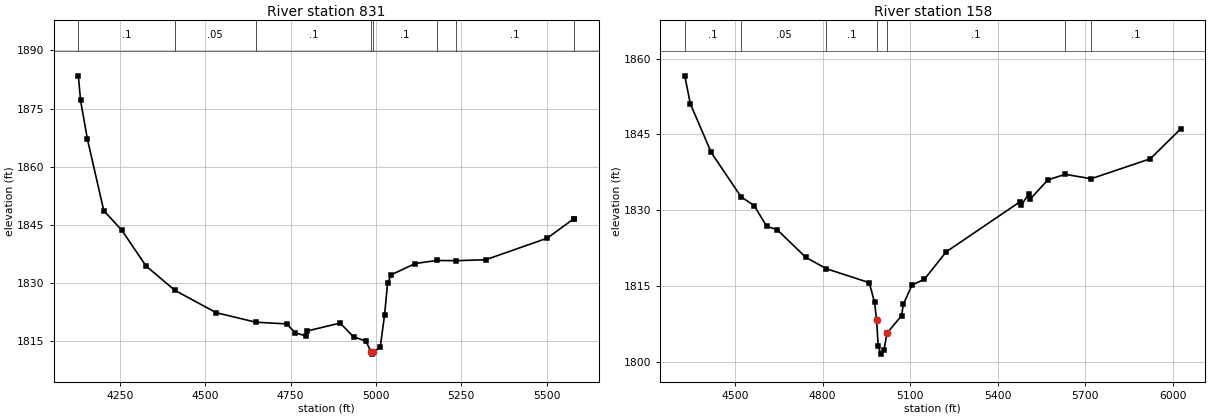
Type RM Length L Ch R = 1 ,831     ,673,673,673
BEGIN DESCRIPTION:
Mapping XS 40458a29
END DESCRIPTION:
XS GIS Cut Line= 4
      2772754.93     10097649.41      2772434.59     10097688.48
      2771864.28     10097902.02      2771856.47     10098422.88
#Sta/Elev= 30
  4128.4 1883.44  4134.9 1877.11  4155.1 1867.05  4202.9 1848.66  4255.8 1843.58
  4326.3 1834.41  4411.1 1828.08  4532.2 1822.31  4648.1 1819.85  4738.8 1819.41
  4763.8 1817.12    4794 1816.33  4799.4 1817.59  4895.4 1819.63  4934.7 1816.08
  4970.3 1814.99  4986.9 1812.11  4989.7 1811.61  4992.9 1812.11  5012.9 1813.36
  5025.6 1821.73  5034.3 1829.84  5044.9 1832.08  5115.6    1835  5178.2 1835.78
  5235.4 1835.73  5321.8 1835.97  5501.8 1841.53  5580.2 1846.57    5581 1846.57
#Mann= 8 ,-1 , 0
  4128.4      .1       0  4411.1     .05       0  4648.1      .1       0
  4986.9     .07       0  4992.9      .1       0  5178.2     .05       0
  5235.4      .1       0  5580.2     .05       0
Bank Sta=4986.9,4992.9
XS Rating Curve= 0 ,0
Exp/Cntr=0.3,0.1

Type RM Length L Ch R = 1 ,158     ,0,0,0
BEGIN DESCRIPTION:
UNT038 IN NNOGR 1.0
END DESCRIPTION:
XS GIS Cut Line= 5
       2772736.7     10097581.71      2772239.28     10097467.13
      2771916.37     10097586.92      2771793.97     10097917.65
      2771830.43     10098407.27
#Sta/Elev= 30
  4327.7 1856.61  4346.4 1851.12  4418.2 1841.43  4520.5 1832.64  4565.4 1830.91
  4608.2 1826.78    4644 1826.15  4741.7 1820.68    4813  1818.4  4959.7 1815.64
  4977.7 1811.73  4984.8 1808.19  4990.1 1803.16  4998.8 1801.49  5009.7 1802.23
  5020.5 1805.66  5070.6 1809.12  5075.9 1811.32  5106.3 1815.18  5148.3 1816.31
  5223.4 1821.76  5475.7 1831.65  5481.1 1831.06  5506.1 1833.19  5511.5 1832.23
  5571.4    1836  5630.9  1837.1  5719.7 1836.23  5922.4 1840.18  6026.2 1846.09
#Mann= 7 ,-1 , 0
  4327.7      .1       0  4520.5     .05       0    4813      .1       0
  4984.8     .07       0  5020.5      .1       0  5630.9     .05       0
  5719.7      .1       0
Bank Sta=4984.8,5020.5
XS Rating Curve= 0 ,0
Exp/Cntr=0.3,0.1

Chan Stop Cuts=-1
Use User Specified Reach Order=0
Composite Channel Slope=5