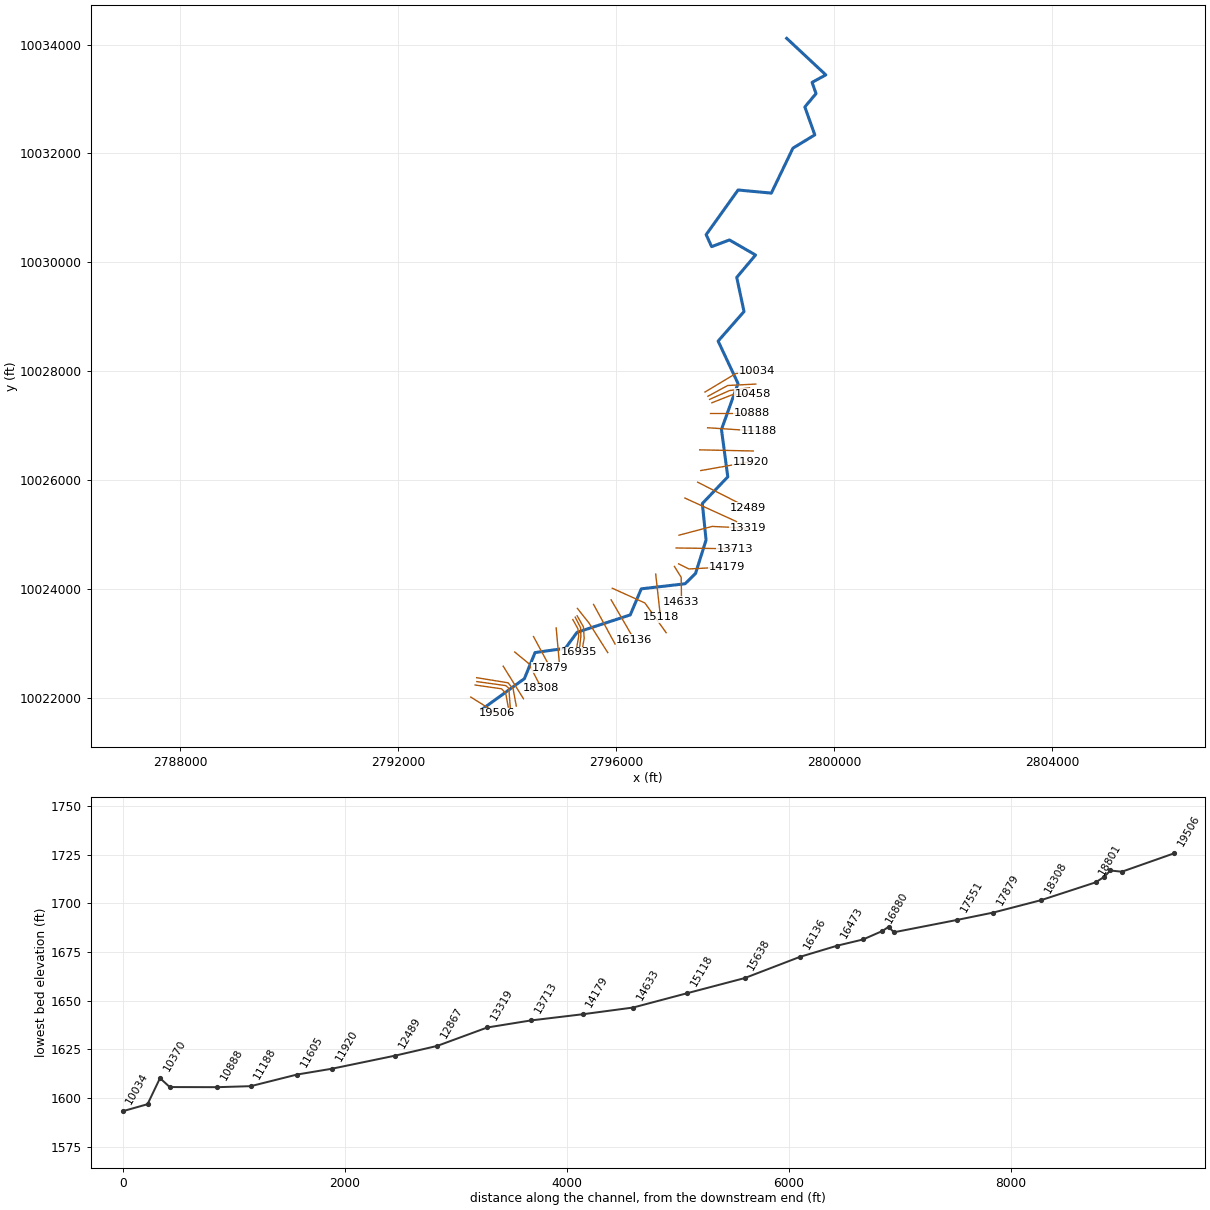
--- UNT038 IN SNOGR.prj (project) ---

Proj Title=UNT038 IN SNOGR Base Level Engineering
Current Plan=p01
Default Exp/Contr=0.3,0.1
English Units
Geom File=g01
Flow File=f01
Plan File=p01
BEGIN DESCRIPTION:
UNT038 IN SNOGR
END DESCRIPTION:

--- UNT038 IN SNOGR.p01 (plan) ---

Plan Title=Multiple Run
Short Identifier=Multiple
Geom File=g01
Flow File=f01
Subcritical Flow
K Sum by GR= 0
Std Step Tol= 0.01
Critical Tol= 0.01
Num of Std Step Trials= 20
Max Error Tol= 0.3
Flow Tol Ratio= 0.001
Split Flow NTrial= 30
Split Flow Tol= 0.02
Split Flow Ratio= 0.02
Log Output Level= 0
Friction Slope Method= 1
Unsteady Friction Slope Method= 2
Unsteady Bridges Friction Slope Method= 1
Parabolic Critical Depth
Global Vel Dist=  1 , 1 , 1
Global Log Level= 0
CheckData=True
Encroach Param= -1, 0, 0, 0
BEGIN DESCRIPTION:
Multiple Run
END DESCRIPTION:

--- UNT038 IN SNOGR.f01 (steady flow) ---

Flow Title=Multiple
Number of Profiles=7
Profile Names=10-year,25-year,50-year,1pct_min,100-year,1pct_plu,500-year
River Rch & RM= UNT038 IN SNOGR,Reach-1,19506
     766    1104    1395    1291    1746    2361    2747
River Rch & RM= UNT038 IN SNOGR,Reach-1,18877
    1235    1819    2333    2187    2958    4000    4776
River Rch & RM= UNT038 IN SNOGR,Reach-1,9088
    1409    2082    2675    2511    3395    4592    5496
Boundary for River Rch & Prof#=UNT038 IN SNOGR,Reach-1,1
Up Type=0
Dn Type=3
Dn Slope=0.005
Boundary for River Rch & Prof#=UNT038 IN SNOGR,Reach-1,2
Up Type=0
Dn Type=3
Dn Slope=0.005
Boundary for River Rch & Prof#=UNT038 IN SNOGR,Reach-1,3
Up Type=0
Dn Type=3
Dn Slope=0.005
Boundary for River Rch & Prof#=UNT038 IN SNOGR,Reach-1,4
Up Type=0
Dn Type=3
Dn Slope=0.005
Boundary for River Rch & Prof#=UNT038 IN SNOGR,Reach-1,5
Up Type=0
Dn Type=3
Dn Slope=0.005
Boundary for River Rch & Prof#=UNT038 IN SNOGR,Reach-1,6
Up Type=0
Dn Type=3
Dn Slope=0.005
Boundary for River Rch & Prof#=UNT038 IN SNOGR,Reach-1,7
Up Type=0
Dn Type=3
Dn Slope=0.005

--- UNT038 IN SNOGR.g01 (geometry) ---

Geom Title=Existing Conditions

River Reach=UNT038 IN SNOGR,Reach-1
Reach XY= 30
      2793528.47     10021783.73      2794313.40     10022351.95
      2794509.33     10022831.31      2795065.63     10022910.20
      2795279.66     10023202.94      2796256.60     10023523.64
      2796458.92     10024002.12      2797263.36     10024095.16
      2797455.12     10024285.23      2797648.14     10024898.16
      2797579.75     10025569.32      2798046.63     10026058.88
      2797930.99     10026928.97      2798234.90     10027774.04
      2797869.61     10028552.95      2798344.79     10029095.68
      2798211.24     10029722.66      2798556.49     10030133.68
      2798077.42     10030410.39      2797749.86     10030287.35
      2797649.95     10030508.30      2798236.09     10031327.88
      2798845.99     10031270.74      2799243.02     10032096.90
      2799644.22     10032340.77      2799461.25     10032852.75
      2799666.64     10033099.23      2799593.98     10033304.68
      2799846.09     10033442.30      2799128.47     10034113.73

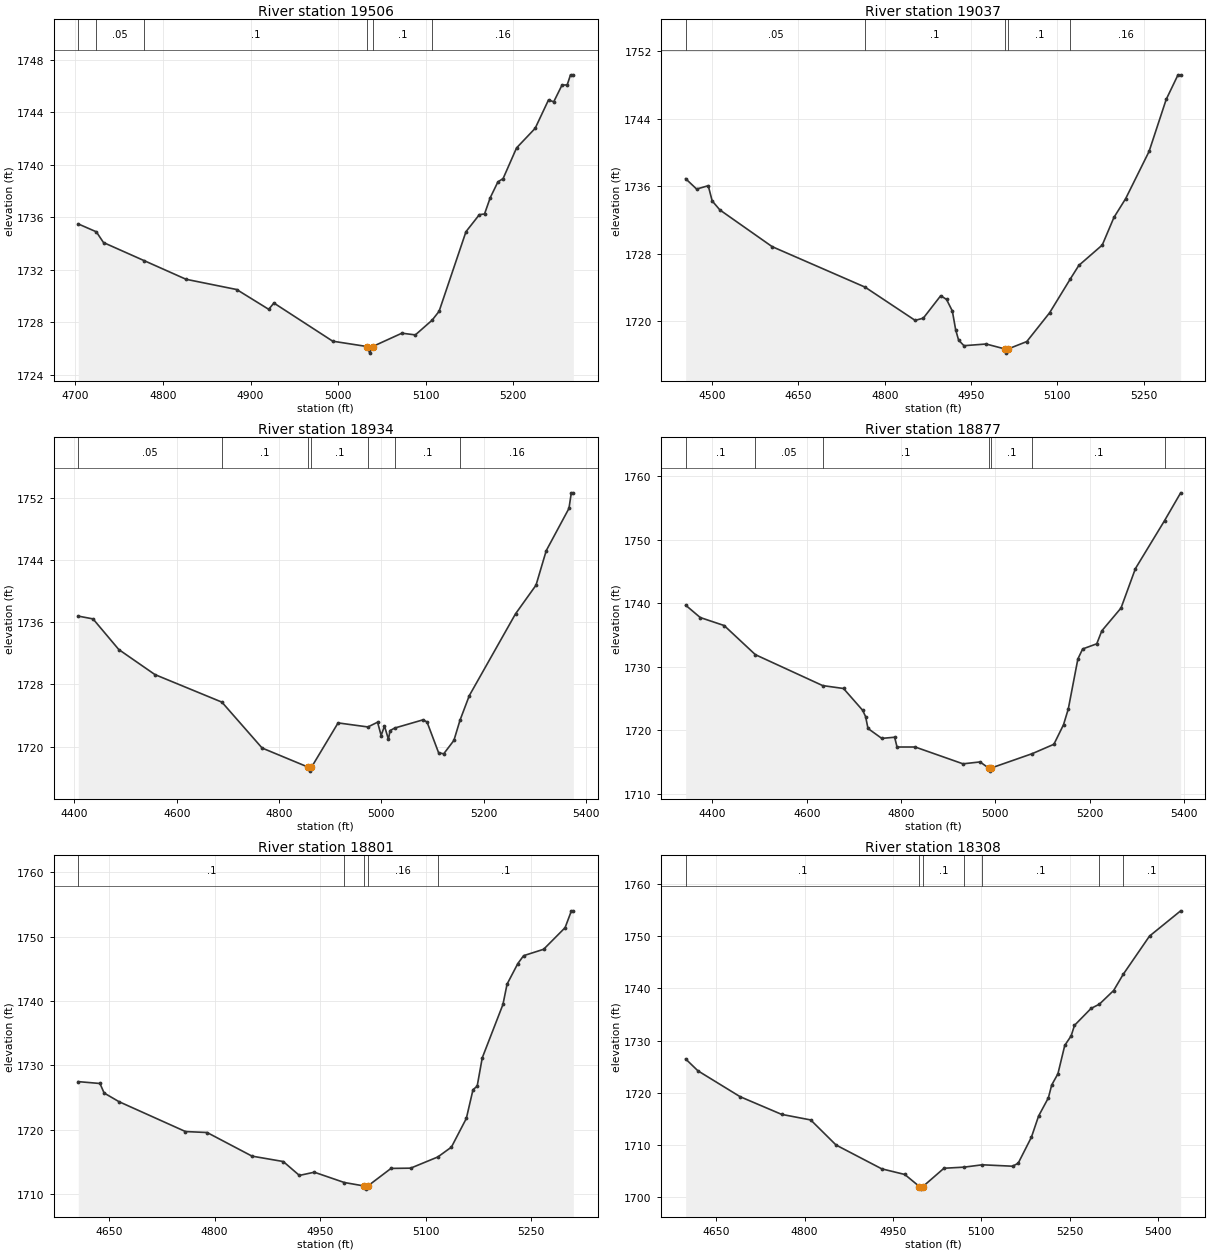
Type RM Length L Ch R = 1,19506,469,469,469
BEGIN DESCRIPTION:
UNT038 IN SNOGR 41.0
END DESCRIPTION:
XS GIS Cut Line= 2
      2793329.35     10022014.15      2793808.93     10021714.68
#Sta/Elev= 30
  4703.3 1735.49  4723.9 1734.89  4732.1 1734.07  4778.6 1732.69  4826.4 1731.27
  4884.2 1730.49  4920.8 1728.98  4926.7 1729.46  4993.9 1726.55  5033.4 1726.14
  5036.1 1725.64  5039.4 1726.14  5072.9 1727.16  5088.3 1727.03  5107.4 1728.15
  5115.4 1728.83  5146.1 1734.90  5161.4 1736.20  5167.3 1736.25  5173.8 1737.49
  5182.6 1738.70  5188.5 1738.95  5203.9 1741.29  5225.1 1742.78  5240.4 1744.95
  5246.3 1744.80  5255.8 1746.08  5261.7 1746.09  5265.5 1746.86  5268.7 1746.86
#Mann=6,-1,0
  4703.3     0.1       0  4723.9    0.05       0  4778.6     0.1       0
  5033.4    0.07       0  5039.4     0.1       0  5107.4    0.16       0
Bank Sta=5033.4,5039.4
Exp/Cntr=0.3,0.1

Type RM Length L Ch R = 1,19037,103,103,103
BEGIN DESCRIPTION:
Mapping XS 123a5553
END DESCRIPTION:
XS GIS Cut Line= 4
      2793409.59     10022235.52      2793893.55     10022166.08
      2793969.51     10022087.95      2794017.25     10021829.71
#Sta/Elev= 30
  4453.9 1736.89  4473.0 1735.66  4493.2 1736.06  4500.0 1734.26  4513.4 1733.19
  4604.3 1728.84  4765.7 1724.05  4852.8 1720.11  4867.0 1720.37  4897.3 1723.03
  4907.4 1722.59  4917.5 1721.22  4923.3 1718.99  4928.4 1717.77  4937.7 1717.11
  4976.2 1717.31  5008.6 1716.73  5011.4 1716.23  5014.6 1716.73  5046.9 1717.60
  5086.6 1721.01  5122.7 1725.03  5137.4 1726.62  5178.1 1729.03  5198.4 1732.30
  5218.8 1734.53  5259.5 1740.12  5289.2 1746.27  5309.8 1749.19  5314.4 1749.19
#Mann=5,-1,0
  4453.9    0.05       0  4765.7     0.1       0  5008.6    0.07       0
  5014.6     0.1       0  5122.7    0.16       0
Bank Sta=5008.6,5014.6
Exp/Cntr=0.3,0.1

Type RM Length L Ch R = 1,18934,57,57,57
BEGIN DESCRIPTION:
Mapping XS c53c7e1f
END DESCRIPTION:
XS GIS Cut Line= 4
      2793439.97     10022298.46      2793971.68     10022224.67
      2794028.10     10022176.93      2794054.15     10021820.99
#Sta/Elev= 30
  4407.5 1736.79  4436.3 1736.43  4486.7 1732.49  4557.4 1729.27  4688.2 1725.73
  4766.8 1719.83  4857.3 1717.36  4860.0 1716.86  4863.3 1717.36  4915.3 1723.06
  4973.6 1722.54  4992.5 1723.15  4999.5 1721.44  5006.0 1722.66  5013.8 1720.94
  5016.8 1722.07  5026.0 1722.40  5081.6 1723.46  5089.2 1723.17  5111.7 1719.24
  5121.7 1719.08  5141.7 1720.81  5153.6 1723.40  5171.8 1726.57  5262.1 1737.08
  5302.2 1740.77  5322.2 1745.21  5366.6 1750.64  5371.2 1752.64  5375.1 1752.64
#Mann=7,-1,0
  4407.5    0.05       0  4688.2     0.1       0  4857.3    0.07       0
  4863.3     0.1       0  4973.6    0.16       0  5026.0     0.1       0
  5153.6    0.16       0
Bank Sta=4857.3,4863.3
Exp/Cntr=0.3,0.1

Type RM Length L Ch R = 1,18877,76,76,76
BEGIN DESCRIPTION:
UNT038 IN SNOGR 40.0
END DESCRIPTION:
XS GIS Cut Line= 4
      2793437.85     10022370.07      2794012.91     10022276.75
      2794106.23     10022168.25      2794164.81     10021849.28
#Sta/Elev= 30
  4343.2 1739.71  4374.2 1737.76  4424.9 1736.50  4491.1 1731.91  4633.8 1727.04
  4678.1 1726.58  4718.7 1723.14  4724.9 1722.15  4730.0 1720.28  4759.2 1718.72
  4786.5 1718.90  4791.6 1717.36  4830.1 1717.36  4931.5 1714.71  4967.7 1715.01
  4985.6 1714.06  4988.3 1713.56  4991.6 1714.06  5078.6 1716.32  5124.3 1717.79
  5144.7 1720.87  5154.8 1723.34  5175.2 1731.24  5185.3 1732.81  5215.2 1733.62
  5226.0 1735.67  5266.7 1739.26  5297.2 1745.47  5359.1 1753.04  5393.2 1757.41
#Mann=7,-1,0
  4343.2     0.1       0  4491.1    0.05       0  4633.8     0.1       0
  4985.6    0.07       0  4991.6     0.1       0  5078.6     0.1       0
  5359.1    0.16       0
Bank Sta=4985.6,4991.6
Exp/Cntr=0.3,0.1

Type RM Length L Ch R = 1,18801,493,493,493
BEGIN DESCRIPTION:
UNT038 IN SNOGR 39.0
END DESCRIPTION:
XS GIS Cut Line= 2
      2793924.81     10022580.99      2794296.31     10021983.82
#Sta/Elev= 30
  4606.4 1727.48  4637.2 1727.19  4643.1 1725.71  4664.3 1724.36  4758.7 1719.72
  4789.4 1719.57  4853.2 1715.90  4897.6 1715.06  4920.5 1712.90  4941.7 1713.40
  4984.3 1711.80  5011.9 1711.27  5014.7 1710.77  5017.9 1711.27  5050.7 1713.99
  5078.6 1714.03  5117.2 1715.77  5136.5 1717.30  5157.7 1721.76  5167.2 1726.23
  5173.1 1726.77  5180.3 1731.17  5209.7 1739.47  5215.6 1742.64  5230.9 1745.84
  5239.1 1747.06  5267.5 1748.05  5298.0 1751.41  5307.0 1754.03  5309.7 1754.03
#Mann=5,-1,0
  4606.4     0.1       0  4984.3    0.16       0  5011.9    0.07       0
  5017.9    0.16       0  5117.2     0.1       0
Bank Sta=5011.9,5017.9
Exp/Cntr=0.3,0.1

Type RM Length L Ch R = 1,18308,429,429,429
BEGIN DESCRIPTION:
UNT038 IN SNOGR 38.0
END DESCRIPTION:
XS GIS Cut Line= 3
      2794136.63     10022841.41      2794393.55     10022629.62
      2794626.06     10022178.48
#Sta/Elev= 30
  4597.9 1726.48  4618.8 1724.21  4690.5 1719.26  4760.8 1715.89  4810.3 1714.82
  4853.3 1710.03  4930.8 1705.48  4970.0 1704.40  4994.8 1702.10  4997.5 1701.60
  5000.8 1702.10  5036.5 1705.59  5070.5 1705.80  5101.7 1706.25  5152.9 1705.98
  5162.5 1706.54  5185.0 1711.53  5197.2 1715.58  5213.8 1719.05  5219.4 1721.49
  5230.0 1723.65  5241.6 1729.07  5252.5 1730.90  5258.1 1732.90  5286.2 1736.13
  5300.5 1736.96  5324.6 1739.56  5340.7 1742.63  5385.5 1749.96  5438.4 1754.79
#Mann=7,-1,0
  4597.9     0.1       0  4994.8    0.07       0  5000.8     0.1       0
  5070.5    0.05       0  5101.7     0.1       0  5300.5    0.16       0
  5340.7     0.1       0
Bank Sta=4994.8,5000.8
Exp/Cntr=0.3,0.1

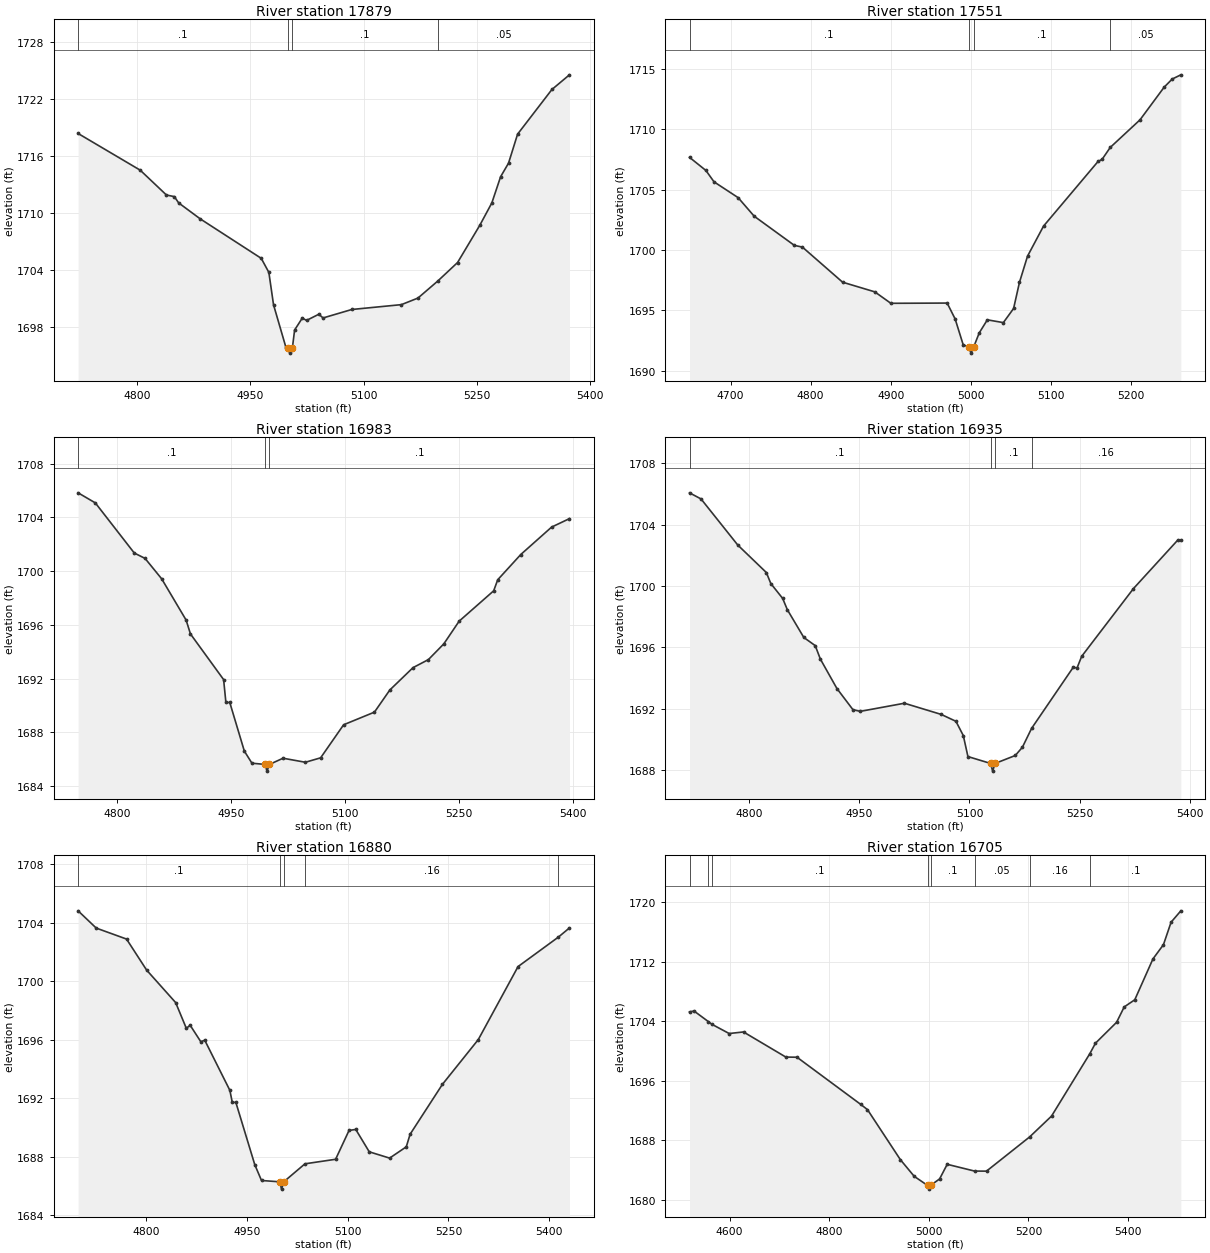
Type RM Length L Ch R = 1,17879,328,328,328
BEGIN DESCRIPTION:
UNT038 IN SNOGR 37.0
END DESCRIPTION:
XS GIS Cut Line= 2
      2794480.36     10023126.15      2794789.36     10022553.27
#Sta/Elev= 30
  4721.7 1718.36  4804.0 1714.50  4838.7 1711.89  4849.2 1711.72  4854.9 1711.06
  4883.5 1709.38  4964.3 1705.23  4974.4 1703.75  4980.6 1700.34  4996.8 1695.92
  4999.5 1695.76  5002.2 1695.26  5005.5 1695.76  5008.5 1697.69  5018.7 1698.95
  5024.3 1698.70  5040.6 1699.35  5046.2 1698.96  5084.3 1699.85  5150.0 1700.36
  5171.9 1701.05  5198.0 1702.83  5224.4 1704.79  5253.8 1708.70  5269.8 1711.06
  5281.4 1713.81  5291.9 1715.24  5303.9 1718.29  5349.4 1722.99  5372.6 1724.53
#Mann=4,-1,0
  4721.7     0.1       0  4999.5    0.07       0  5005.5     0.1       0
  5198.0    0.05       0
Bank Sta=4999.5,5005.5
Exp/Cntr=0.3,0.1

Type RM Length L Ch R = 1,17551,568,568,568
BEGIN DESCRIPTION:
UNT038 IN SNOGR 36.0
END DESCRIPTION:
XS GIS Cut Line= 2
      2794897.02     10023284.16      2794952.58     10022672.98
#Sta/Elev= 30
  4648.8 1707.68  4669.3 1706.59  4679.4 1705.65  4709.5 1704.34  4729.6 1702.80
  4779.8 1700.38  4789.8 1700.24  4840.0 1697.33  4880.2 1696.53  4900.3 1695.58
  4970.6 1695.60  4980.6 1694.28  4990.6 1692.15  4997.7 1691.95  5000.4 1691.45
  5003.7 1691.95  5010.7 1693.13  5020.8 1694.21  5040.8 1693.98  5053.6 1695.15
  5060.9 1697.31  5071.0 1699.49  5091.0 1701.98  5159.1 1707.34  5164.1 1707.51
  5174.3 1708.50  5211.5 1710.79  5241.7 1713.50  5251.7 1714.17  5262.5 1714.52
#Mann=4,-1,0
  4648.8     0.1       0  4997.7    0.07       0  5003.7     0.1       0
  5174.3    0.05       0
Bank Sta=4997.7,5003.7
Exp/Cntr=0.3,0.1

Type RM Length L Ch R = 1,16983,48,48,48
BEGIN DESCRIPTION:
Mapping XS a880db38
END DESCRIPTION:
XS GIS Cut Line= 4
      2795202.57     10023438.67      2795296.33     10023266.77
      2795310.22     10023131.36      2795256.40     10022820.61
#Sta/Elev= 30
  4748.4 1705.83  4771.1 1705.08  4822.4 1701.35  4836.6 1700.95  4858.5 1699.43
  4890.7 1696.36  4896.4 1695.33  4940.1 1691.93  4943.1 1690.23  4948.2 1690.23
  4967.4 1686.61  4977.4 1685.71  4994.5 1685.62  4997.3 1685.12  5000.5 1685.62
  5018.4 1686.08  5047.8 1685.78  5067.9 1686.11  5098.2 1688.57  5138.8 1689.51
  5159.1 1691.16  5189.6 1692.82  5209.9 1693.42  5230.2 1694.59  5250.4 1696.28
  5295.9 1698.54  5301.2 1699.36  5331.6 1701.24  5372.2 1703.28  5395.7 1703.91
#Mann=3,-1,0
  4748.4     0.1       0  4994.5    0.07       0  5000.5     0.1       0
Bank Sta=4994.5,5000.5
Exp/Cntr=0.3,0.1

Type RM Length L Ch R = 1,16935,55,55,55
BEGIN DESCRIPTION:
Mapping XS a29ea8a2
END DESCRIPTION:
XS GIS Cut Line= 4
      2795245.96     10023482.09      2795344.94     10023289.34
      2795350.15     10023126.15      2795317.16     10022839.69
#Sta/Elev= 30
  4719.2 1706.08  4734.9 1705.68  4784.9 1702.67  4823.7 1700.88  4829.8 1700.16
  4845.9 1699.19  4852.3 1698.45  4874.7 1696.64  4890.2 1696.11  4897.2 1695.23
  4919.7 1693.31  4941.5 1691.93  4951.5 1691.82  5011.5 1692.35  5061.6 1691.62
  5081.6 1691.17  5091.6 1690.24  5097.9 1688.87  5128.8 1688.42  5131.5 1687.92
  5134.8 1688.42  5162.3 1688.94  5172.0 1689.48  5184.5 1690.71  5241.2 1694.70
  5246.3 1694.65  5252.6 1695.41  5323.0 1699.83  5383.0 1702.98  5387.5 1702.98
#Mann=4,-1,0
  4719.2     0.1       0  5128.8    0.07       0  5134.8     0.1       0
  5184.5    0.16       0
Bank Sta=5128.8,5134.8
Exp/Cntr=0.3,0.1

Type RM Length L Ch R = 1,16880,175,175,175
BEGIN DESCRIPTION:
Mapping XS 7529766a
END DESCRIPTION:
XS GIS Cut Line= 4
      2795282.44     10023506.36      2795397.02     10023304.97
      2795410.91     10023091.42      2795360.57     10022810.20
#Sta/Elev= 30
  4698.7 1704.82  4725.7 1703.64  4770.8 1702.89  4800.7 1700.77  4843.9 1698.55
  4859.8 1696.79  4865.5 1697.00  4881.4 1695.87  4887.2 1695.98  4924.6 1692.55
  4928.2 1691.73  4933.5 1691.73  4961.7 1687.47  4971.7 1686.39  4998.8 1686.30
  5001.5 1685.80  5004.8 1686.30  5036.4 1687.53  5082.0 1687.84  5102.0 1689.81
  5112.0 1689.88  5132.1 1688.35  5162.4 1687.92  5187.2 1688.69  5192.9 1689.55
  5241.0 1692.96  5294.4 1696.02  5353.6 1701.01  5413.5 1703.02  5430.1 1703.65
#Mann=5,-1,0
  4698.7     0.1       0  4998.8    0.07       0  5004.8     0.1       0
  5036.4    0.16       0  5413.5     0.1       0
Bank Sta=4998.8,5004.8
Exp/Cntr=0.3,0.1

Type RM Length L Ch R = 1,16705,232,232,232
BEGIN DESCRIPTION:
UNT038 IN SNOGR 35.0
END DESCRIPTION:
XS GIS Cut Line= 3
      2795285.93     10023643.49      2795504.66     10023367.47
      2795843.19     10022831.03
#Sta/Elev= 30
  4519.4 1705.27  4528.5 1705.39  4557.3 1703.96  4564.4 1703.60  4599.0 1702.36
  4627.8 1702.57  4712.8 1699.19  4735.2 1699.17  4863.4 1692.81  4876.7 1692.12
  4942.7 1685.39  4970.6 1683.14  4997.3 1681.92  5000.1 1681.42  5003.3 1681.92
  5021.5 1682.79  5036.8 1684.76  5091.7 1683.85  5115.7 1683.84  5202.4 1688.45
  5246.3 1691.25  5323.1 1699.64  5334.5 1701.06  5376.9 1703.87  5392.2 1705.94
  5413.4 1706.90  5449.9 1712.40  5471.0 1714.32  5486.3 1717.34  5505.9 1718.87
#Mann=8,-1,0
  4519.4     0.1       0  4557.3    0.05       0  4564.4     0.1       0
  4997.3    0.07       0  5003.3     0.1       0  5091.7    0.05       0
  5202.4    0.16       0  5323.1     0.1       0
Bank Sta=4997.3,5003.3
Exp/Cntr=0.3,0.1

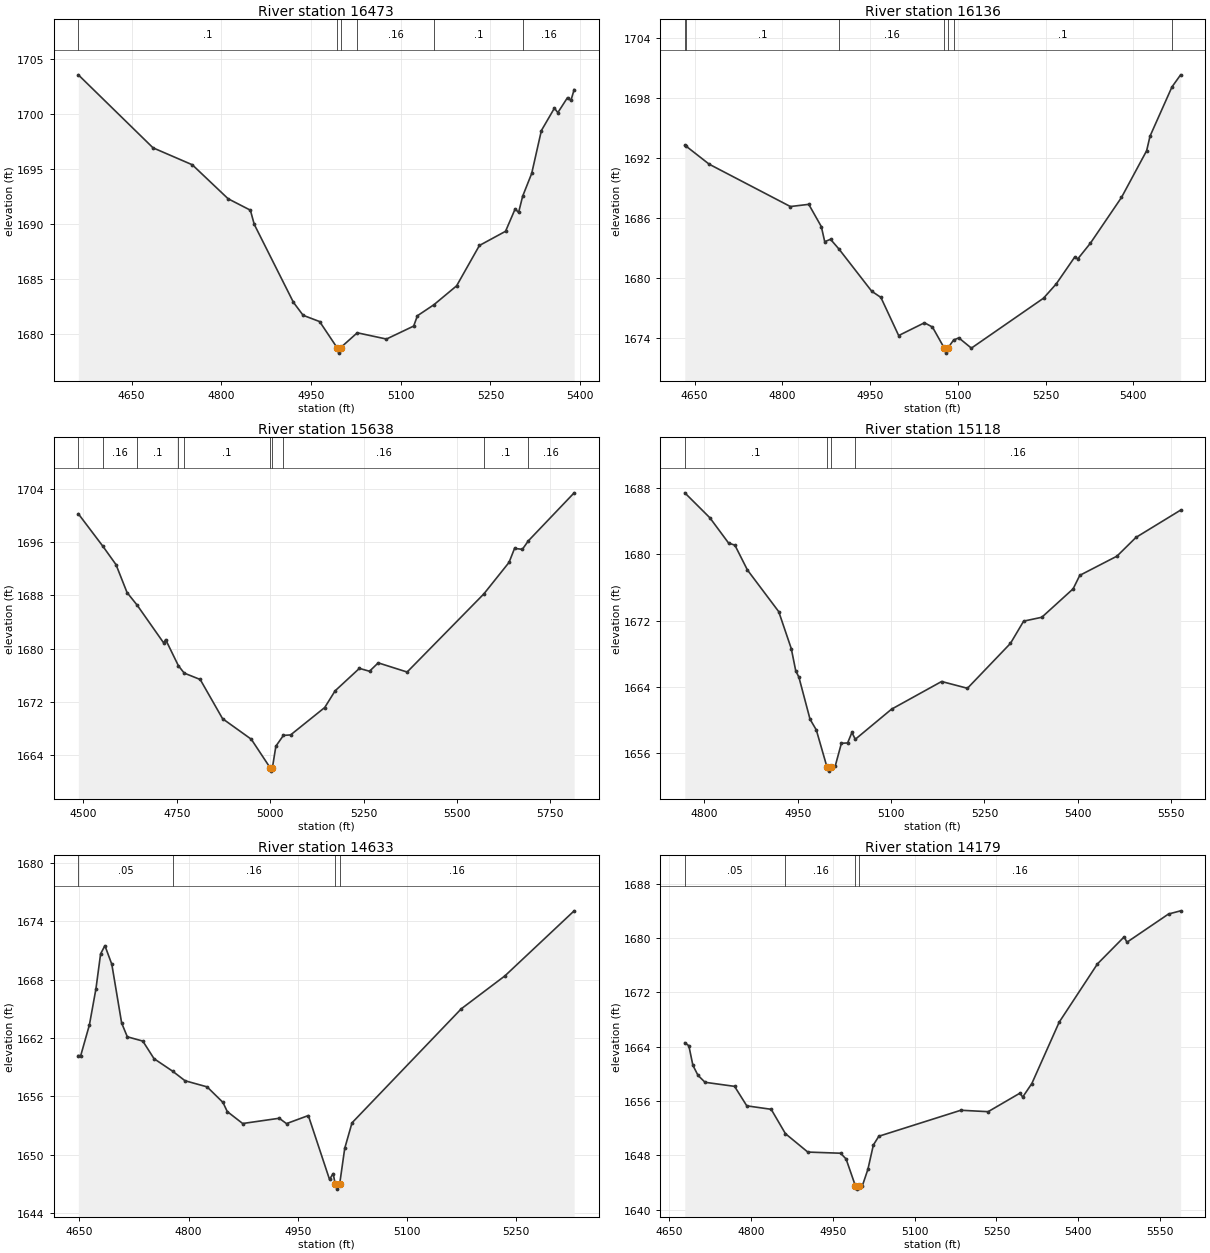
Type RM Length L Ch R = 1,16473,337,337,337
BEGIN DESCRIPTION:
UNT038 IN SNOGR 34.0
END DESCRIPTION:
XS GIS Cut Line= 2
      2795582.77     10023716.45      2795978.23     10022987.97
#Sta/Elev= 30
  4561.0 1703.56  4685.9 1696.92  4751.5 1695.38  4811.4 1692.29  4848.6 1691.25
  4855.1 1689.96  4920.6 1682.87  4936.8 1681.69  4964.4 1681.12  4993.5 1678.75
  4996.2 1678.25  4999.5 1678.75  5027.3 1680.10  5076.1 1679.53  5121.6 1680.71
  5127.9 1681.65  5155.4 1682.65  5193.4 1684.37  5231.5 1688.04  5275.2 1689.33
  5291.3 1691.37  5297.0 1691.04  5303.8 1692.52  5318.9 1694.59  5335.1 1698.49
  5356.9 1700.53  5362.6 1700.12  5378.8 1701.49  5384.5 1701.23  5389.9 1702.22
#Mann=6,-1,0
  4561.0     0.1       0  4993.5    0.07       0  4999.5     0.1       0
  5027.3    0.16       0  5155.4     0.1       0  5303.8    0.16       0
Bank Sta=4993.5,4999.5
Exp/Cntr=0.3,0.1

Type RM Length L Ch R = 1,16136,498,498,498
BEGIN DESCRIPTION:
UNT038 IN SNOGR 33.0
END DESCRIPTION:
XS GIS Cut Line= 2
      2795905.70     10023799.76      2796331.82     10023067.06
#Sta/Elev= 30
  4633.3 1693.30  4635.0 1693.23  4675.0 1691.40  4813.8 1687.16  4845.2 1687.38
  4866.7 1685.15  4872.5 1683.64  4882.4 1683.88  4896.9 1682.90  4952.8 1678.68
  4968.5 1678.06  4998.9 1674.24  5043.0 1675.52  5056.7 1675.09  5076.9 1672.98
  5079.6 1672.48  5082.9 1672.98  5092.8 1673.79  5101.7 1674.01  5123.2 1672.98
  5246.5 1677.98  5268.1 1679.40  5299.5 1682.07  5305.3 1681.93  5326.8 1683.50
  5379.8 1688.07  5422.8 1692.75  5428.6 1694.21  5466.1 1699.14  5480.9 1700.35
#Mann=7,-1,0
  4633.3    0.16       0  4635.0     0.1       0  4896.9    0.16       0
  5076.9    0.07       0  5082.9    0.16       0  5092.8     0.1       0
  5466.1    0.16       0
Bank Sta=5076.9,5082.9
Exp/Cntr=0.3,0.1

Type RM Length L Ch R = 1,15638,520,520,520
BEGIN DESCRIPTION:
UNT038 IN SNOGR 32.0
END DESCRIPTION:
XS GIS Cut Line= 3
      2795926.53     10024013.30      2796525.50     10023742.47
      2796915.01     10023197.15
#Sta/Elev= 30
  4486.2 1700.25  4551.8 1695.38  4587.1 1692.61  4616.6 1688.42  4643.7 1686.52
  4714.5 1680.86  4720.0 1681.34  4754.1 1677.42  4769.7 1676.31  4812.5 1675.35
  4872.4 1669.46  4949.3 1666.37  4999.8 1662.08  5002.6 1661.58  5005.8 1662.08
  5015.1 1665.33  5035.3 1666.95  5054.5 1667.02  5145.9 1671.14  5173.6 1673.64
  5238.7 1677.02  5265.8 1676.59  5289.1 1677.85  5366.5 1676.47  5571.9 1688.21
  5639.4 1692.95  5654.1 1695.05  5675.0 1694.91  5691.0 1696.18  5813.7 1703.40
#Mann=10,-1,0
  4486.2     0.1       0  4551.8    0.16       0  4643.7     0.1       0
  4754.1    0.05       0  4769.7     0.1       0  4999.8    0.07       0
  5005.8     0.1       0  5035.3    0.16       0  5571.9     0.1       0
  5691.0    0.16       0
Bank Sta=4999.8,5005.8
Exp/Cntr=0.3,0.1

Type RM Length L Ch R = 1,15118,485,485,485
BEGIN DESCRIPTION:
UNT038 IN SNOGR 31.0
END DESCRIPTION:
XS GIS Cut Line= 2
      2796723.41     10024273.73      2796811.95     10023482.07
#Sta/Elev= 30
  4768.5 1687.45  4808.8 1684.43  4838.9 1681.37  4849.0 1681.12  4869.1 1678.12
  4919.4 1673.08  4939.6 1668.60  4946.8 1665.90  4951.8 1665.16  4969.7 1660.07
  4979.8 1658.77  4996.9 1654.29  4999.7 1653.79  5002.9 1654.29  5010.0 1654.35
  5020.1 1657.16  5030.1 1657.20  5037.0 1658.47  5042.4 1657.64  5100.6 1661.28
  5181.1 1664.63  5222.6 1663.81  5291.7 1669.24  5312.9 1671.93  5342.1 1672.40
  5392.4 1675.84  5403.1 1677.47  5462.8 1679.79  5493.4 1682.06  5565.1 1685.36
#Mann=4,-1,0
  4768.5     0.1       0  4996.9    0.07       0  5002.9     0.1       0
  5042.4    0.16       0
Bank Sta=4996.9,5002.9
Exp/Cntr=0.3,0.1

Type RM Length L Ch R = 1,14633,454,454,454
BEGIN DESCRIPTION:
UNT038 IN SNOGR 30.0
END DESCRIPTION:
XS GIS Cut Line= 3
      2797067.14     10024414.38      2797192.16     10024211.22
      2797197.37     10023768.60
#Sta/Elev= 30
  4648.6 1660.20  4651.9 1660.20  4663.8 1663.35  4672.8 1667.07  4679.2 1670.66
  4685.1 1671.51  4694.6 1669.59  4708.1 1663.55  4715.9 1662.13  4737.2 1661.69
  4752.6 1659.88  4778.0 1658.60  4795.2 1657.61  4825.5 1656.98  4847.3 1655.38
  4853.2 1654.44  4874.4 1653.21  4924.6 1653.75  4934.6 1653.20  4964.6 1654.03
  4993.7 1647.46  4998.7 1648.06  5001.6 1646.96  5004.4 1646.46  5007.6 1646.96
  5014.6 1650.66  5024.6 1653.28  5174.7 1665.01  5234.7 1668.40  5329.8 1675.09
#Mann=4,-1,0
  4648.6    0.05       0  4778.0    0.16       0  5001.6    0.07       0
  5007.6    0.16       0
Bank Sta=5001.6,5007.6
Exp/Cntr=0.3,0.1

Type RM Length L Ch R = 1,14179,466,466,466
BEGIN DESCRIPTION:
UNT038 IN SNOGR 29.0
END DESCRIPTION:
XS GIS Cut Line= 3
      2797145.25     10024461.23      2797332.79     10024367.47
      2798030.67     10024403.92
#Sta/Elev= 30
  4678.9 1664.57  4686.3 1664.14  4693.7 1661.26  4703.1 1659.77  4716.0 1658.75
  4770.1 1658.15  4792.5 1655.28  4837.2 1654.77  4863.3 1651.18  4904.3 1648.47
  4964.3 1648.30  4974.4 1647.46  4991.4 1643.51  4994.1 1643.01  4997.4 1643.51
  5004.4 1643.54  5014.4 1645.93  5024.4 1649.51  5034.4 1650.80  5184.7 1654.63
  5234.7 1654.42  5293.0 1657.15  5298.0 1656.57  5314.8 1658.57  5364.9 1667.61
  5435.0 1676.19  5484.0 1680.18  5489.0 1679.38  5565.2 1683.54  5587.4 1684.01
#Mann=4,-1,0
  4678.9    0.05       0  4863.3    0.16       0  4991.4    0.07       0
  4997.4    0.16       0
Bank Sta=4991.4,4997.4
Exp/Cntr=0.3,0.1

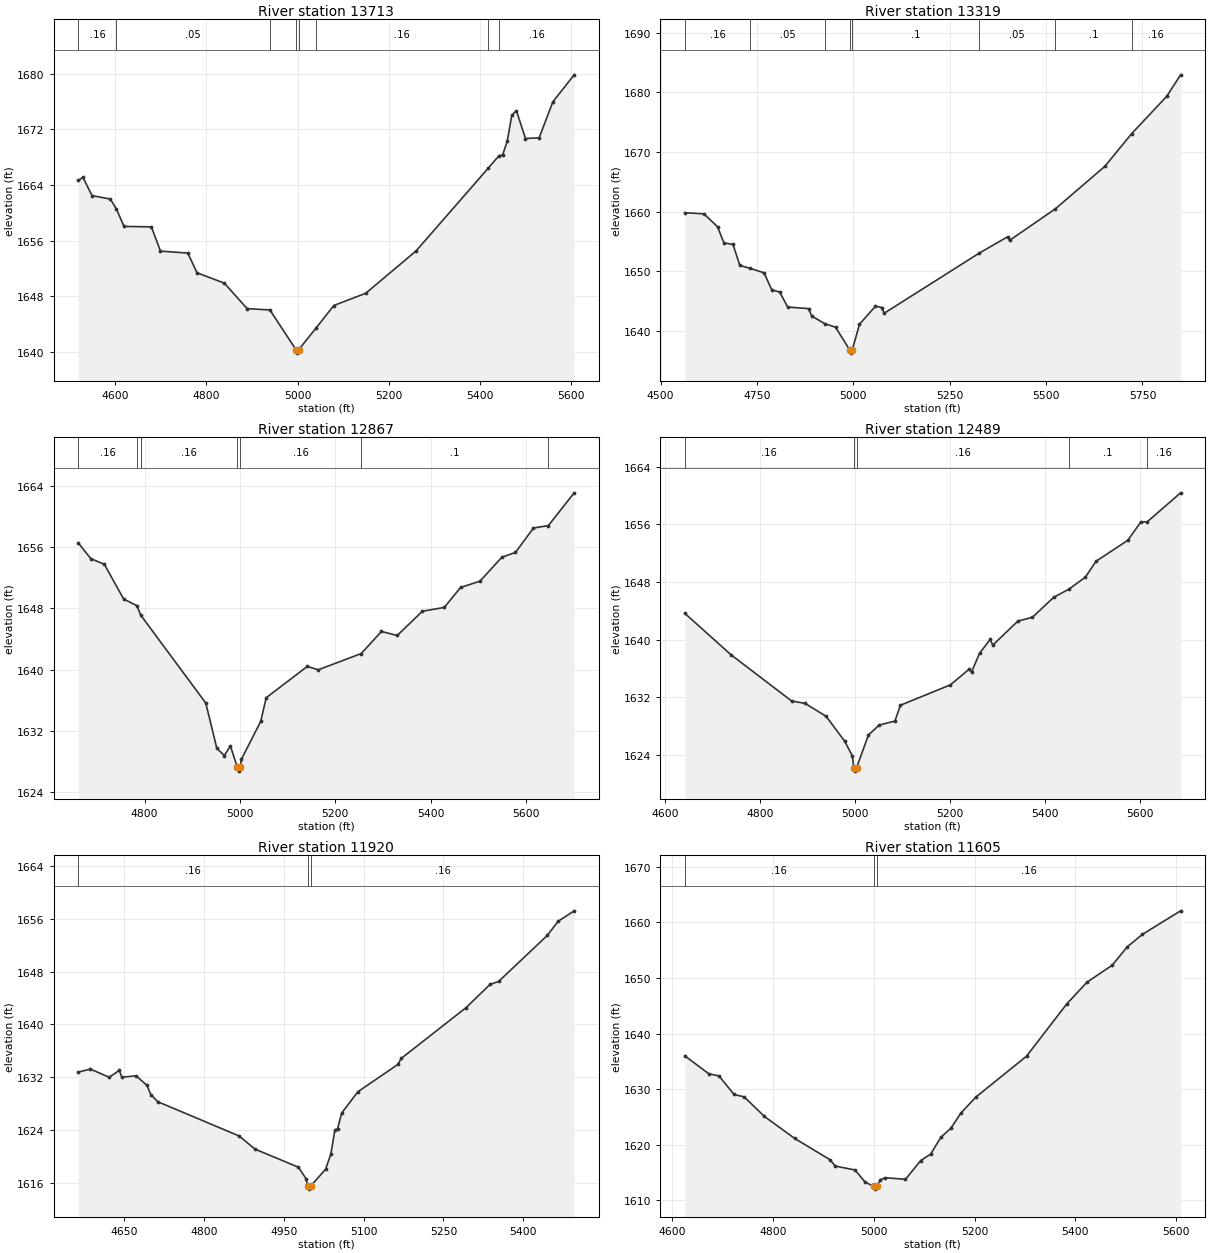
Type RM Length L Ch R = 1,13713,394,394,394
BEGIN DESCRIPTION:
UNT038 IN SNOGR 28.0
END DESCRIPTION:
XS GIS Cut Line= 2
      2797098.41     10024752.88      2798185.20     10024737.28
#Sta/Elev= 30
  4519.3 1664.65  4529.4 1665.08  4549.4 1662.46  4589.4 1661.97  4602.9 1660.52
  4619.4 1658.04  4679.4 1657.97  4699.4 1654.49  4759.4 1654.21  4779.4 1651.38
  4839.4 1649.89  4889.4 1646.23  4939.2 1646.04  4996.4 1640.34  4999.2 1639.84
  5002.4 1640.34  5041.2 1643.51  5079.4 1646.68  5149.4 1648.44  5259.4 1654.50
  5417.4 1666.37  5441.3 1668.19  5449.5 1668.32  5459.5 1670.27  5469.5 1674.00
  5479.5 1674.68  5499.5 1670.66  5529.5 1670.77  5559.5 1675.93  5606.2 1679.81
#Mann=8,-1,0
  4519.3    0.16       0  4602.9    0.05       0  4939.2     0.1       0
  4996.4    0.07       0  5002.4     0.1       0  5041.2    0.16       0
  5417.4    0.05       0  5441.3    0.16       0
Bank Sta=4996.4,5002.4
Exp/Cntr=0.3,0.1

Type RM Length L Ch R = 1,13319,452,452,452
BEGIN DESCRIPTION:
UNT038 IN SNOGR 27.0
END DESCRIPTION:
XS GIS Cut Line= 3
      2797150.48     10024987.25      2797759.87     10025148.72
      2798414.81     10025117.53
#Sta/Elev= 30
  4562.9 1659.80  4612.7 1659.60  4647.8 1657.44  4664.3 1654.73  4688.0 1654.46
  4705.6 1650.94  4732.9 1650.44  4768.4 1649.70  4788.4 1646.86  4809.1 1646.46
  4829.8 1643.95  4883.9 1643.69  4891.9 1642.45  4925.4 1641.18  4953.9 1640.56
  4991.1 1636.71  4993.9 1636.21  4997.1 1636.71  5016.0 1641.05  5057.4 1644.09
  5074.6 1643.87  5079.7 1642.89  5326.4 1653.00  5400.2 1655.75  5405.2 1655.14
  5524.3 1660.46  5652.4 1667.58  5722.3 1673.10  5812.6 1679.32  5849.0 1682.96
#Mann=8,-1,0
  4562.9    0.16       0  4732.9    0.05       0  4925.4     0.1       0
  4991.1    0.07       0  4997.1     0.1       0  5326.4    0.05       0
  5524.3     0.1       0  5722.3    0.16       0
Bank Sta=4991.1,4997.1
Exp/Cntr=0.3,0.1

Type RM Length L Ch R = 1,12867,378,378,378
BEGIN DESCRIPTION:
UNT038 IN SNOGR 26.0
END DESCRIPTION:
XS GIS Cut Line= 2
      2797259.86     10025669.56      2798206.19     10025237.99
#Sta/Elev= 30
  4661.0 1656.54  4687.0 1654.50  4715.6 1653.75  4756.1 1649.21  4783.8 1648.35
  4792.0 1647.10  4928.4 1635.62  4951.5 1629.72  4967.2 1628.76  4980.0 1630.03
  4994.5 1627.23  4997.3 1626.73  5000.5 1627.23  5003.0 1628.27  5043.6 1633.23
  5055.1 1636.32  5141.3 1640.41  5164.3 1639.97  5254.4 1642.09  5296.9 1644.98
  5329.9 1644.45  5382.7 1647.62  5428.8 1648.12  5462.8 1650.73  5503.4 1651.54
  5549.5 1654.68  5578.0 1655.30  5615.7 1658.49  5647.0 1658.81  5701.1 1663.09
#Mann=7,-1,0
  4661.0    0.16       0  4783.8     0.1       0  4792.0    0.16       0
  4994.5    0.07       0  5000.5    0.16       0  5254.4     0.1       0
  5647.0    0.05       0
Bank Sta=4994.5,5000.5
Exp/Cntr=0.3,0.1

Type RM Length L Ch R = 1,12489,569,569,569
BEGIN DESCRIPTION:
UNT038 IN SNOGR 25.0
END DESCRIPTION:
XS GIS Cut Line= 2
      2797494.23     10025961.22      2798423.54     10025488.78
#Sta/Elev= 30
  4642.1 1643.66  4739.0 1637.92  4866.9 1631.48  4894.8 1631.16  4939.3 1629.36
  4978.2 1625.91  4994.6 1623.84  4997.4 1622.25  5000.2 1621.75  5003.4 1622.25
  5028.3 1626.77  5050.7 1628.15  5083.8 1628.69  5095.6 1630.90  5200.7 1633.73
  5239.6 1635.89  5245.2 1635.53  5261.8 1638.11  5284.1 1640.03  5289.7 1639.25
  5342.4 1642.58  5373.1 1643.11  5417.6 1645.88  5449.4 1647.00  5484.4 1648.68
  5506.6 1650.88  5573.4 1653.79  5601.2 1656.37  5614.3 1656.36  5684.6 1660.39
#Mann=5,-1,0
  4642.1    0.16       0  4997.4    0.07       0  5003.4    0.16       0
  5449.4     0.1       0  5614.3    0.16       0
Bank Sta=4997.4,5003.4
Exp/Cntr=0.3,0.1

Type RM Length L Ch R = 1,11920,315,315,315
BEGIN DESCRIPTION:
UNT038 IN SNOGR 24.0
END DESCRIPTION:
XS GIS Cut Line= 2
      2797551.54     10026174.76      2798468.23     10026336.22
#Sta/Elev= 30
  4564.5 1632.79  4587.1 1633.24  4622.3 1632.00  4641.3 1633.03  4646.4 1632.00
  4673.1 1632.22  4693.4 1630.76  4700.6 1629.37  4713.7 1628.29  4866.0 1623.11
  4896.5 1621.09  4977.7 1618.36  4991.9 1616.64  4995.0 1615.54  4997.7 1615.04
  5001.0 1615.54  5028.5 1618.03  5038.6 1620.36  5046.1 1623.99  5051.2 1624.21
  5058.9 1626.58  5089.4 1629.81  5164.7 1633.96  5170.6 1634.85  5292.5 1642.56
  5337.5 1646.08  5353.4 1646.52  5444.8 1653.49  5465.1 1655.63  5495.3 1657.23
#Mann=3,-1,0
  4564.5    0.16       0  4995.0    0.07       0  5001.0    0.16       0
Bank Sta=4995,5001
Exp/Cntr=0.3,0.1

Type RM Length L Ch R = 1,11605,417,417,417
BEGIN DESCRIPTION:
UNT038 IN SNOGR 23.0
END DESCRIPTION:
XS GIS Cut Line= 2
      2797530.66     10026554.97      2798514.24     10026534.15
#Sta/Elev= 30
  4625.1 1636.00  4672.9 1632.76  4692.9 1632.39  4722.9 1629.05  4742.9 1628.62
  4782.9 1625.12  4843.0 1621.16  4913.0 1617.34  4923.9 1616.18  4963.0 1615.48
  4983.0 1613.29  5000.0 1612.54  5002.7 1612.04  5006.0 1612.54  5013.0 1613.71
  5023.0 1614.09  5063.0 1613.80  5093.0 1617.16  5113.0 1618.34  5133.0 1621.34
  5153.0 1622.98  5173.0 1625.72  5203.0 1628.61  5303.1 1635.93  5383.1 1645.34
  5423.1 1649.23  5473.1 1652.28  5503.1 1655.59  5533.1 1657.83  5608.9 1662.06
#Mann=3,-1,0
  4625.1    0.16       0  5000.0    0.07       0  5006.0    0.16       0
Bank Sta=5000,5006
Exp/Cntr=0.3,0.1

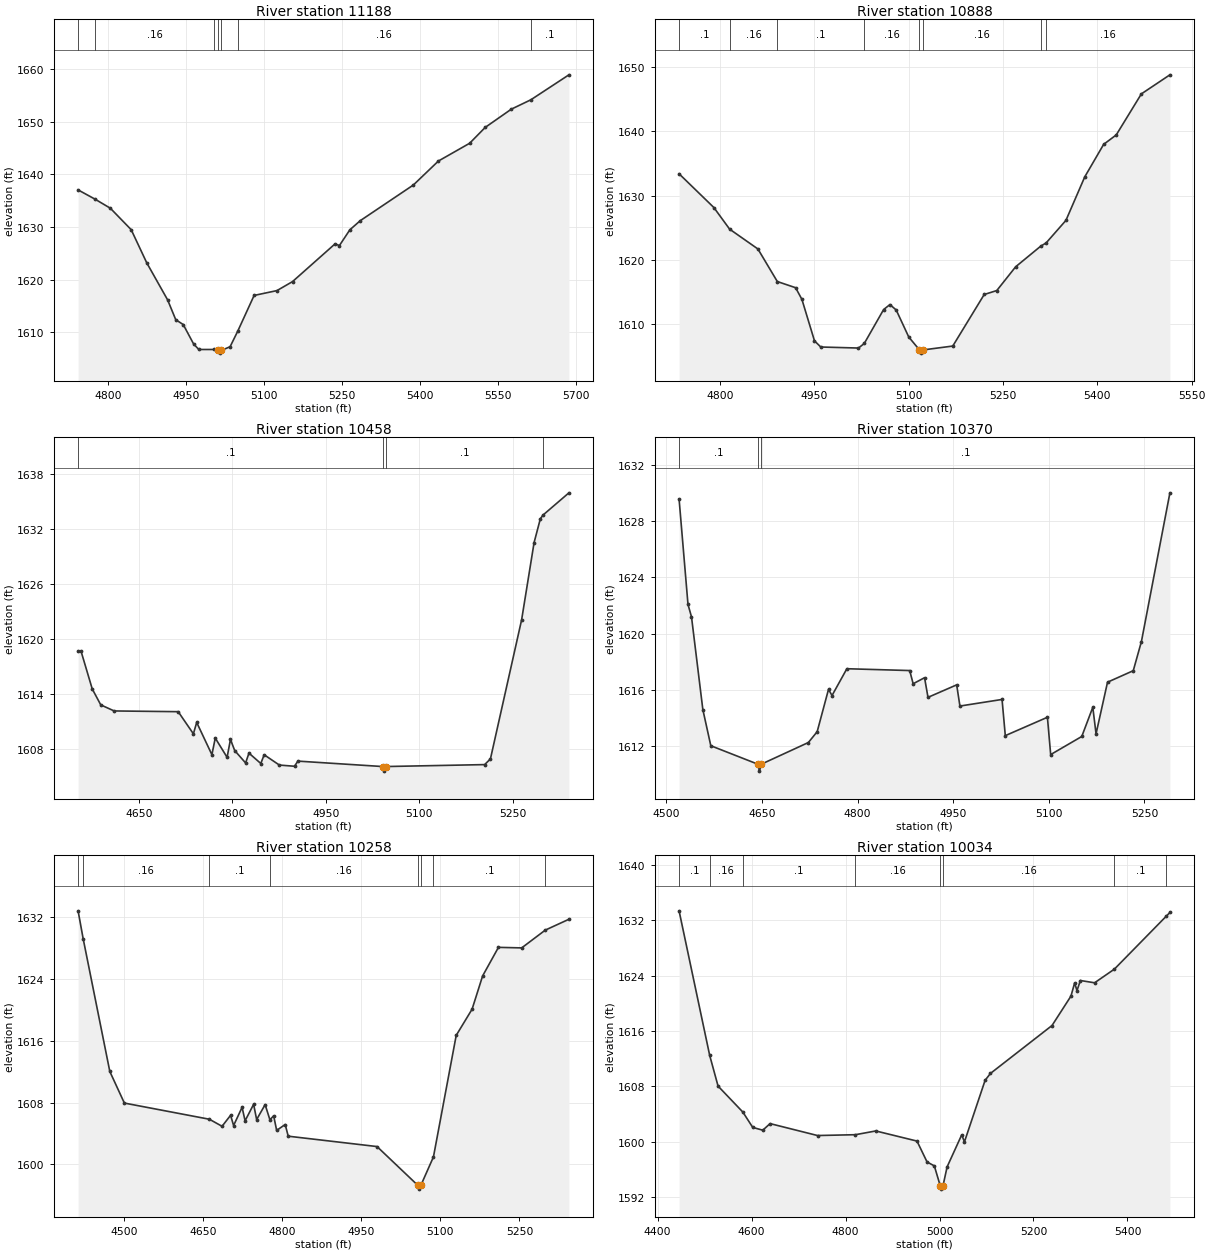
Type RM Length L Ch R = 1,11188,300,300,300
BEGIN DESCRIPTION:
UNT038 IN SNOGR 22.0
END DESCRIPTION:
XS GIS Cut Line= 2
      2797676.53     10026961.22      2798619.16     10026898.72
#Sta/Elev= 30
  4742.1 1637.05  4774.8 1635.29  4804.2 1633.57  4844.3 1629.50  4874.3 1623.20
  4914.4 1616.18  4930.1 1612.41  4944.5 1611.49  4964.5 1607.80  4974.5 1606.76
  5003.2 1606.76  5011.6 1606.57  5014.4 1606.07  5017.6 1606.57  5034.7 1607.29
  5049.5 1610.26  5080.9 1617.02  5124.9 1617.94  5154.9 1619.65  5236.6 1626.80
  5245.1 1626.49  5265.2 1629.48  5285.2 1631.21  5387.4 1637.98  5435.6 1642.53
  5495.7 1645.90  5525.8 1648.92  5575.9 1652.37  5613.5 1654.15  5686.8 1658.89
#Mann=7,-1,0
  4742.1     0.1       0  4774.8    0.16       0  5003.2     0.1       0
  5011.6    0.07       0  5017.6     0.1       0  5049.5    0.16       0
  5613.5     0.1       0
Bank Sta=5011.6,5017.6
Exp/Cntr=0.3,0.1

Type RM Length L Ch R = 1,10888,430,430,430
BEGIN DESCRIPTION:
UNT038 IN SNOGR 21.0
END DESCRIPTION:
XS GIS Cut Line= 2
      2797713.04     10027237.26      2798493.84     10027237.26
#Sta/Elev= 30
  4734.6 1633.41  4790.0 1628.16  4815.0 1624.81  4860.0 1621.73  4890.9 1616.67
  4920.0 1615.71  4930.0 1613.90  4950.0 1607.46  4960.0 1606.50  5020.0 1606.34
  5029.2 1607.05  5060.0 1612.32  5070.0 1613.09  5080.0 1612.25  5100.0 1608.05
  5117.0 1606.05  5119.8 1605.55  5123.0 1606.05  5170.0 1606.65  5220.0 1614.66
  5240.0 1615.27  5270.0 1618.96  5309.7 1622.15  5318.6 1622.68  5350.0 1626.17
  5380.0 1632.94  5410.0 1637.98  5430.0 1639.44  5470.0 1645.82  5515.4 1648.78
#Mann=8,-1,0
  4734.6     0.1       0  4815.0    0.16       0  4890.9     0.1       0
  5029.2    0.16       0  5117.0    0.07       0  5123.0    0.16       0
  5309.7    0.05       0  5318.6    0.16       0
Bank Sta=5117,5123
Exp/Cntr=0.3,0.1

Type RM Length L Ch R = 1,10458,88,88,88
BEGIN DESCRIPTION:
Mapping XS 5c398002
END DESCRIPTION:
XS GIS Cut Line= 3
      2797754.63     10027419.54      2798124.46     10027565.38
      2798514.26     10027586.17
#Sta/Elev= 30
  4552.5 1618.65  4557.3 1618.65  4575.2 1614.56  4588.9 1612.82  4610.4 1612.16
  4713.2 1612.08  4737.6 1609.67  4742.9 1610.91  4767.3 1607.40  4772.7 1609.21
  4791.7 1607.11  4797.1 1609.06  4803.9 1607.85  4821.4 1606.50  4826.8 1607.57
  4845.8 1606.44  4851.2 1607.39  4875.6 1606.27  4899.9 1606.14  4905.3 1606.70
  5041.2 1606.11  5043.9 1605.61  5047.2 1606.11  5205.1 1606.32  5214.4 1606.94
  5264.5 1622.09  5284.5 1630.49  5294.5 1633.07  5298.8 1633.48  5340.4 1635.90
#Mann=4,-1,0
  4552.5     0.1       0  5041.2    0.07       0  5047.2     0.1       0
  5298.8    0.16       0
Bank Sta=5041.2,5047.2
Exp/Cntr=0.3,0.1

Type RM Length L Ch R = 1,10370,112,112,112
BEGIN DESCRIPTION:
Mapping XS 29896d04
END DESCRIPTION:
XS GIS Cut Line= 3
      2797712.96     10027482.03      2798077.58     10027643.51
      2798445.38     10027695.31
#Sta/Elev= 30
  4519.8 1629.60  4533.8 1622.07  4539.3 1621.19  4557.1 1614.58  4569.6 1612.00
  4643.1 1610.69  4645.9 1610.19  4649.1 1610.69  4722.7 1612.23  4736.5 1613.00
  4754.3 1616.02  4759.8 1615.58  4783.1 1617.49  4881.7 1617.36  4887.1 1616.42
  4905.0 1616.85  4910.4 1615.45  4955.4 1616.34  4960.5 1614.83  5026.6 1615.30
  5031.7 1612.72  5097.8 1614.03  5102.9 1611.37  5151.7 1612.66  5169.0 1614.74
  5174.1 1612.85  5192.1 1616.53  5232.5 1617.35  5245.3 1619.43  5290.0 1630.03
#Mann=3,-1,0
  4519.8     0.1       0  4643.1    0.07       0  4649.1     0.1       0
Bank Sta=4643.1,4649.1
Exp/Cntr=0.3,0.1

Type RM Length L Ch R = 1,10258,224,224,224
BEGIN DESCRIPTION:
Mapping XS 787ec302
END DESCRIPTION:
XS GIS Cut Line= 3
      2797681.76     10027539.35      2798046.33     10027737.26
      2798561.95     10027763.30
#Sta/Elev= 30
  4412.8 1632.77  4422.4 1629.18  4473.0 1612.01  4500.6 1607.93  4661.9 1605.84
  4685.9 1604.93  4702.1 1606.35  4707.8 1605.03  4723.9 1607.38  4729.6 1605.64
  4745.8 1607.77  4751.5 1605.80  4767.6 1607.73  4776.7 1605.77  4783.8 1606.28
  4789.5 1604.40  4805.7 1605.16  4811.4 1603.65  4979.9 1602.31  5057.1 1597.31
  5059.8 1596.81  5063.1 1597.31  5086.9 1600.97  5130.1 1616.68  5160.2 1620.06
  5180.2 1624.36  5210.2 1628.05  5254.3 1627.98  5299.1 1630.28  5343.9 1631.68
#Mann=8,-1,0
  4412.8     0.1       0  4422.4    0.16       0  4661.9     0.1       0
  4776.7    0.16       0  5057.1    0.07       0  5063.1    0.16       0
  5086.9     0.1       0  5299.1    0.05       0
Bank Sta=5057.1,5063.1
Exp/Cntr=0.3,0.1

Type RM Length L Ch R = 1,10034,261,261,261
BEGIN DESCRIPTION:
UNT038 IN SNOGR 20.0
END DESCRIPTION:
XS GIS Cut Line= 3
      2797629.70     10027617.49      2798192.16     10027956.01
      2798577.55     10028002.88
#Sta/Elev= 30
  4445.7 1633.33  4510.9 1612.47  4528.7 1608.05  4581.5 1604.30  4602.5 1602.09
  4623.9 1601.69  4639.4 1602.64  4740.4 1600.92  4821.0 1601.04  4864.4 1601.58
  4952.1 1600.12  4973.5 1597.11  4989.0 1596.54  5001.5 1593.69  5004.2 1593.19
  5007.5 1593.69  5016.2 1596.40  5047.3 1601.02  5053.1 1600.01  5097.1 1608.89
  5108.5 1609.88  5239.5 1616.79  5279.8 1621.03  5287.6 1622.93  5292.6 1621.83
  5299.9 1623.28  5330.1 1622.95  5372.2 1624.92  5483.0 1632.58  5490.4 1633.09
#Mann=8,-1,0
  4445.7     0.1       0  4510.9    0.16       0  4581.5     0.1       0
  4821.0    0.16       0  5001.5    0.07       0  5007.5    0.16       0
  5372.2     0.1       0  5483.0    0.05       0
Bank Sta=5001.5,5007.5
Exp/Cntr=0.3,0.1