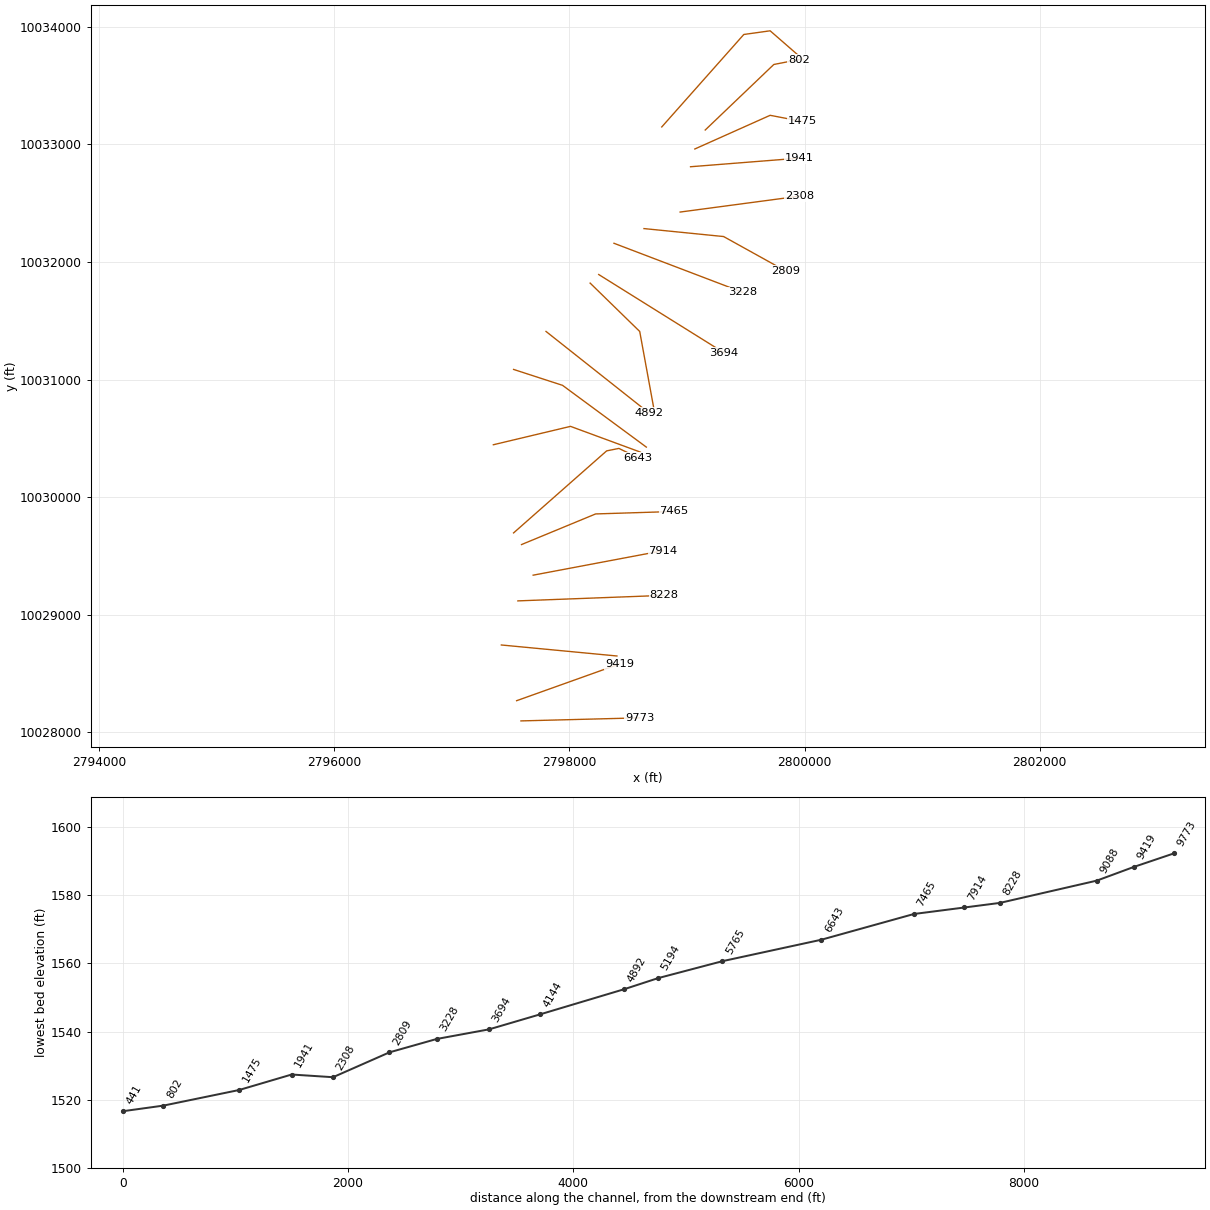
HEC-RAS study UNT038 IN SNOGR.prj: UNT038 IN SNOGR Base Level Engineering

--- UNT038 IN SNOGR.g01 (geometry) --- (continued)

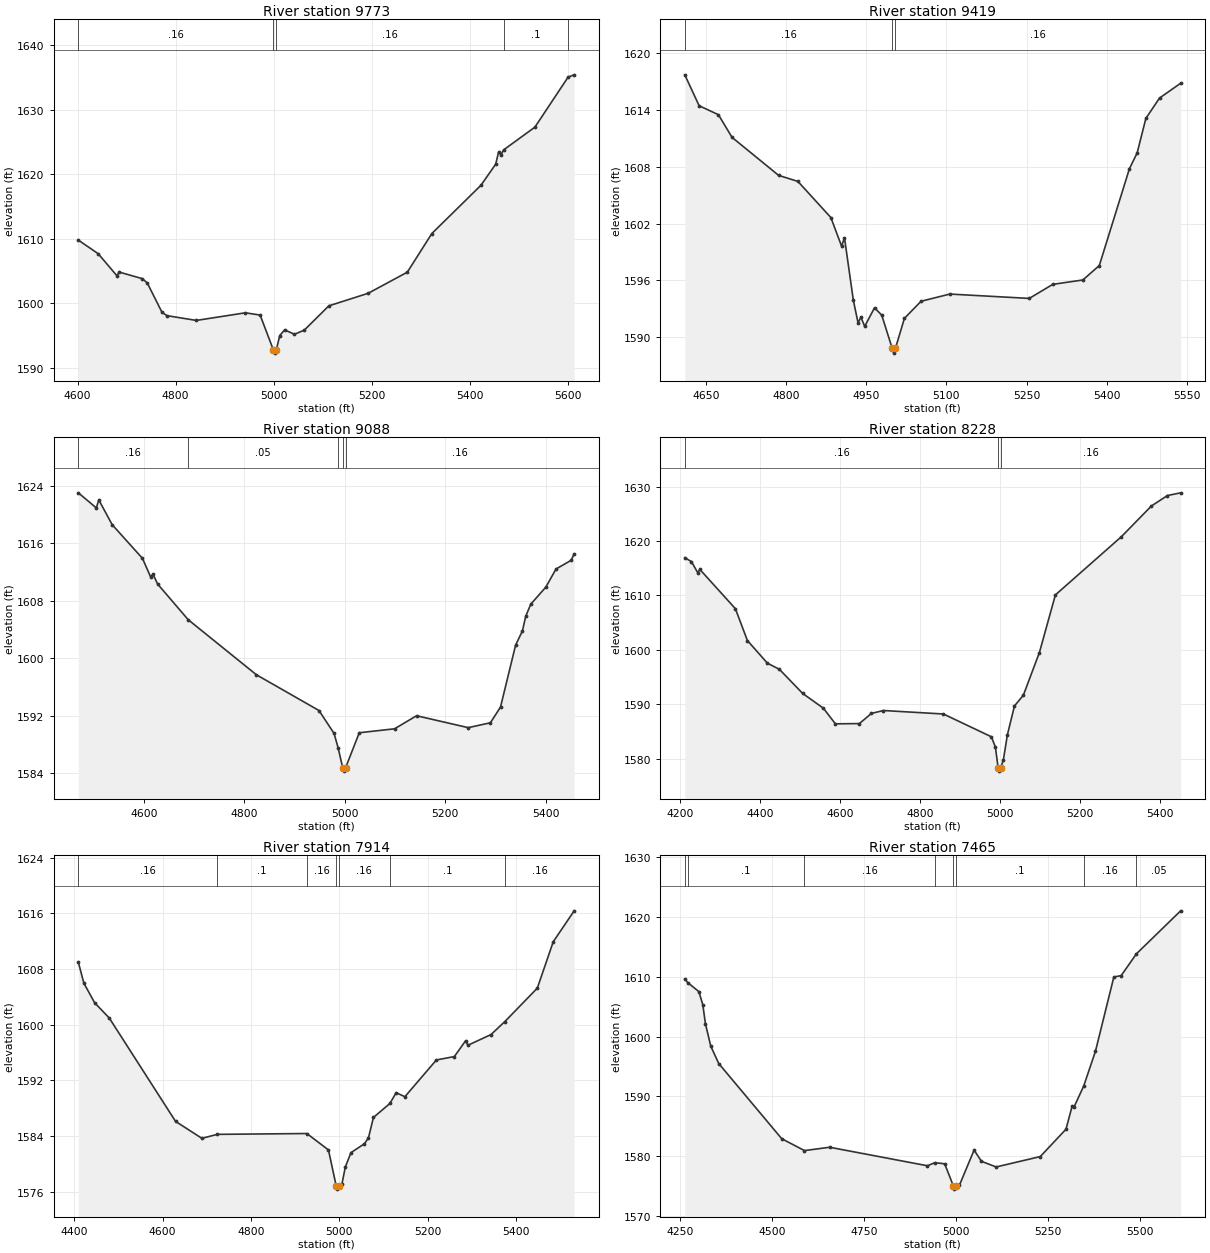
Type RM Length L Ch R = 1,9773,354,354,354
BEGIN DESCRIPTION:
UNT038 IN SNOGR 19.0
END DESCRIPTION:
XS GIS Cut Line= 2
      2797587.98     10028096.63      2798598.44     10028122.68
#Sta/Elev= 30
  4601.6 1609.76  4642.1 1607.65  4680.1 1604.25  4685.1 1604.80  4732.1 1603.78
  4742.1 1603.12  4772.1 1598.58  4782.1 1598.05  4842.2 1597.31  4942.2 1598.49
  4972.2 1598.14  4999.2 1592.74  5002.0 1592.24  5005.2 1592.74  5012.2 1594.96
  5022.2 1595.85  5042.2 1595.16  5062.2 1595.80  5112.3 1599.57  5192.3 1601.51
  5272.3 1604.79  5322.3 1610.78  5422.4 1618.26  5452.4 1621.53  5458.4 1623.41
  5463.4 1622.99  5468.5 1623.74  5532.4 1627.27  5600.1 1635.03  5612.4 1635.38
#Mann=5,-1,0
  4601.6    0.16       0  4999.2    0.07       0  5005.2    0.16       0
  5468.5     0.1       0  5600.1    0.05       0
Bank Sta=4999.2,5005.2
Exp/Cntr=0.3,0.1

Type RM Length L Ch R = 1,9419,331,331,331
BEGIN DESCRIPTION:
UNT038 IN SNOGR 18.0
END DESCRIPTION:
XS GIS Cut Line= 2
      2797551.56     10028268.52      2798425.03     10028580.47
#Sta/Elev= 30
  4610.6 1617.74  4637.4 1614.47  4673.5 1613.52  4699.0 1611.12  4786.1 1607.10
  4822.2 1606.46  4883.8 1602.64  4903.9 1599.61  4909.3 1600.50  4925.9 1593.88
  4934.7 1591.49  4940.0 1592.10  4947.1 1591.12  4965.5 1593.09  4979.0 1592.31
  4998.6 1588.79  5001.4 1588.29  5004.6 1588.79  5021.4 1591.97  5052.6 1593.78
  5106.4 1594.54  5255.0 1594.08  5299.0 1595.57  5355.2 1596.03  5386.0 1597.56
  5442.3 1607.80  5456.8 1609.48  5473.1 1613.13  5498.6 1615.28  5538.1 1616.85
#Mann=3,-1,0
  4610.6    0.16       0  4998.6    0.07       0  5004.6    0.16       0
Bank Sta=4998.6,5004.6
Exp/Cntr=0.3,0.1

Type RM Length L Ch R = 1,9088,860,860,860
BEGIN DESCRIPTION:
UNT038 IN SNOGR 17.0
END DESCRIPTION:
XS GIS Cut Line= 2
      2797421.36     10028742.46      2798404.51     10028648.83
#Sta/Elev= 30
  4469.4 1623.04  4505.2 1620.94  4510.2 1622.05  4536.8 1618.60  4597.1 1613.91
  4613.2 1611.35  4618.2 1611.70  4627.2 1610.34  4688.3 1605.35  4824.1 1597.68
  4948.7 1592.70  4978.8 1589.50  4986.8 1587.51  4995.9 1584.75  4998.6 1584.25
  5001.9 1584.75  5029.0 1589.60  5099.3 1590.15  5143.1 1591.97  5246.0 1590.31
  5290.2 1590.99  5310.3 1593.18  5340.4 1601.82  5354.0 1603.80  5360.5 1605.83
  5370.6 1607.52  5400.7 1609.91  5420.8 1612.42  5450.9 1613.63  5457.0 1614.52
#Mann=5,-1,0
  4469.4    0.16       0  4688.3    0.05       0  4986.8    0.16       0
  4995.9    0.07       0  5001.9    0.16       0
Bank Sta=4995.9,5001.9
Exp/Cntr=0.3,0.1

Type RM Length L Ch R = 1,8228,314,314,314
BEGIN DESCRIPTION:
UNT038 IN SNOGR 16.0
END DESCRIPTION:
XS GIS Cut Line= 2
      2797561.94     10029117.47      2798801.56     10029164.34
#Sta/Elev= 30
  4212.2 1616.93  4228.7 1616.24  4244.7 1614.17  4249.7 1614.81  4338.8 1607.57
  4368.8 1601.72  4418.9 1597.56  4448.9 1596.43  4507.1 1592.00  4559.0 1589.28
  4589.0 1586.41  4649.0 1586.46  4679.1 1588.33  4709.1 1588.86  4859.2 1588.22
  4979.3 1584.03  4989.3 1582.13  4996.3 1578.22  4999.0 1577.72  5002.3 1578.22
  5009.3 1579.82  5019.3 1584.40  5037.0 1589.70  5059.3 1591.68  5099.4 1599.52
  5139.4 1610.11  5304.4 1620.80  5379.6 1626.45  5419.6 1628.37  5452.7 1628.87
#Mann=3,-1,0
  4212.2    0.16       0  4996.3    0.07       0  5002.3    0.16       0
Bank Sta=4996.3,5002.3
Exp/Cntr=0.3,0.1

Type RM Length L Ch R = 1,7914,449,449,449
BEGIN DESCRIPTION:
UNT038 IN SNOGR 15.0
END DESCRIPTION:
XS GIS Cut Line= 2
      2797692.16     10029336.21      2798794.90     10029544.28
#Sta/Elev= 30
  4409.1 1608.99  4421.6 1605.98  4446.0 1603.16  4479.1 1600.97  4629.2 1586.11
  4688.8 1583.68  4723.6 1584.25  4926.3 1584.37  4975.2 1582.01  4992.6 1576.88
  4995.3 1576.38  4998.6 1576.88  5005.8 1577.15  5013.4 1579.56  5026.1 1581.62
  5056.6 1582.90  5065.8 1583.75  5077.0 1586.68  5114.3 1588.69  5128.4 1590.24
  5148.2 1589.66  5219.5 1594.94  5260.2 1595.43  5285.6 1597.70  5290.7 1597.05
  5343.1 1598.59  5374.5 1600.46  5447.9 1605.26  5484.0 1611.93  5531.3 1616.37
#Mann=7,-1,0
  4409.1    0.16       0  4723.6     0.1       0  4926.3    0.16       0
  4992.6    0.07       0  4998.6    0.16       0  5114.3     0.1       0
  5374.5    0.16       0
Bank Sta=4992.6,4998.6
Exp/Cntr=0.3,0.1

Type RM Length L Ch R = 1,7465,822,822,822
BEGIN DESCRIPTION:
UNT038 IN SNOGR 14.0
END DESCRIPTION:
XS GIS Cut Line= 3
      2797593.20     10029596.63      2798223.41     10029857.05
      2798890.09     10029877.88
#Sta/Elev= 30
  4262.7 1609.63  4271.4 1609.01  4300.9 1607.54  4311.7 1605.34  4318.8 1602.17
  4333.3 1598.41  4355.0 1595.50  4526.4 1582.91  4588.3 1580.92  4656.7 1581.48
  4922.9 1578.38  4942.8 1578.90  4969.7 1578.71  4993.6 1574.97  4996.3 1574.47
  4999.6 1574.97  5009.7 1575.11  5049.7 1581.00  5069.7 1579.13  5109.7 1578.18
  5229.8 1579.92  5299.8 1584.51  5316.7 1588.43  5321.7 1588.23  5347.9 1591.72
  5379.9 1597.55  5429.9 1609.98  5449.9 1610.22  5491.3 1613.86  5611.6 1621.06
#Mann=8,-1,0
  4262.7    0.05       0  4271.4     0.1       0  4588.3    0.16       0
  4942.8     0.1       0  4993.6    0.07       0  4999.6     0.1       0
  5347.9    0.16       0  5491.3    0.05       0
Bank Sta=4993.6,4999.6
Exp/Cntr=0.3,0.1

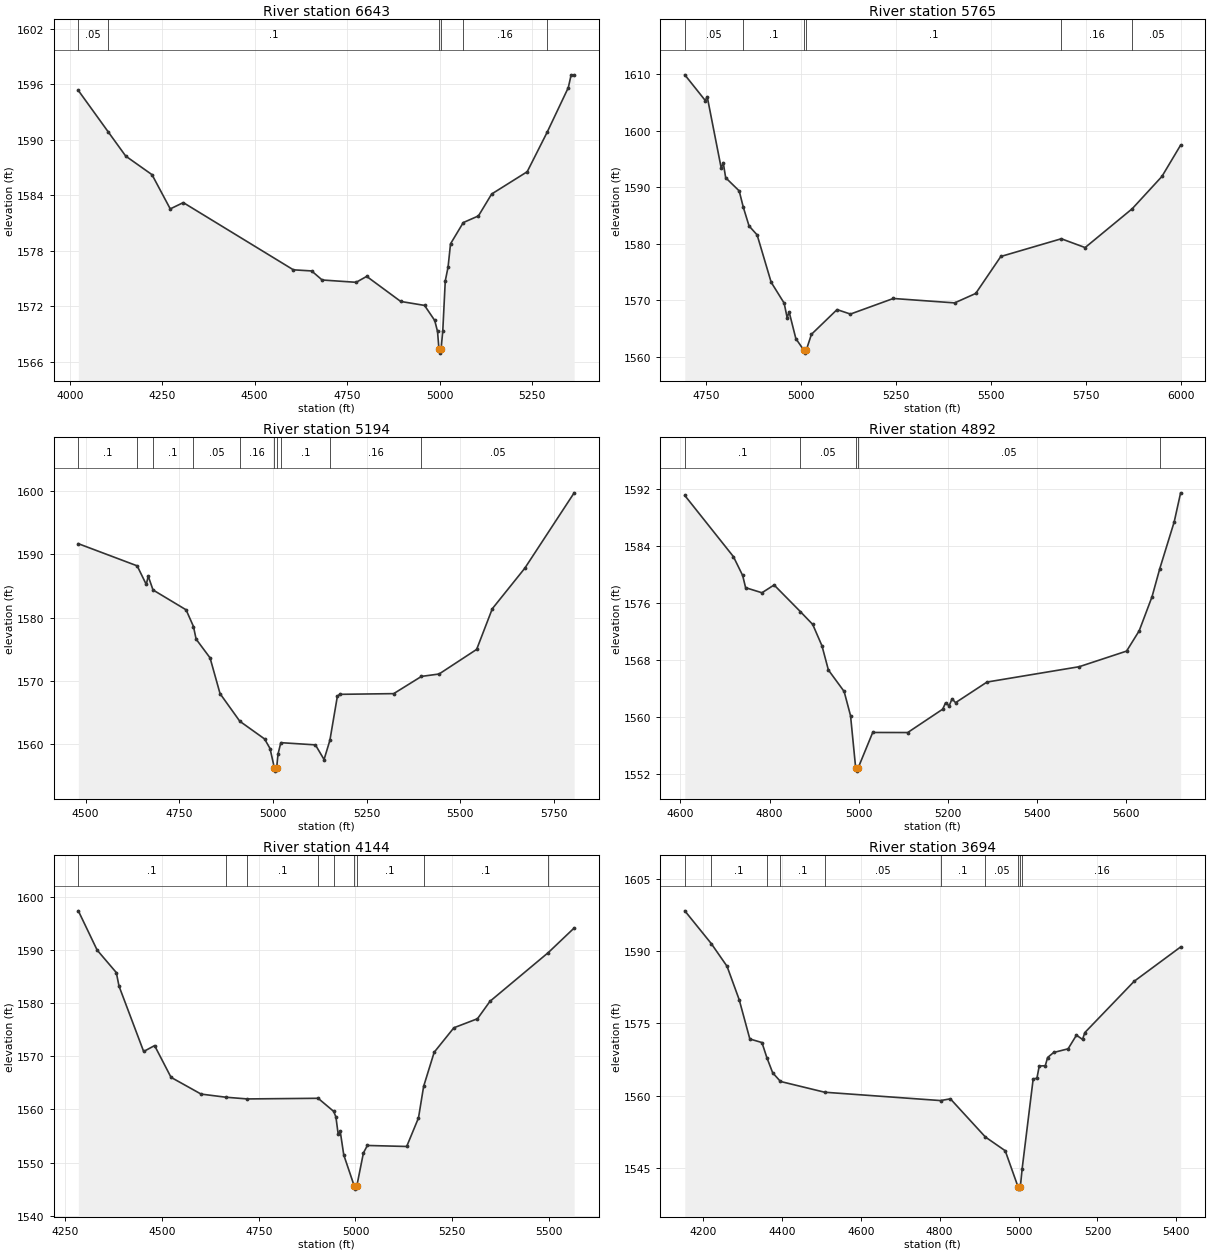
Type RM Length L Ch R = 1,6643,878,878,878
BEGIN DESCRIPTION:
UNT038 IN SNOGR 13.0
END DESCRIPTION:
XS GIS Cut Line= 4
      2797525.50     10029695.59      2798317.16     10030393.51
      2798421.33     10030414.34      2798582.82     10030336.20
#Sta/Elev= 30
  4023.1 1595.33  4104.1 1590.84  4151.3 1588.23  4222.4 1586.22  4271.7 1582.52
  4307.0 1583.20  4604.7 1575.93  4654.1 1575.81  4682.5 1574.83  4774.5 1574.58
  4803.0 1575.22  4895.0 1572.51  4959.5 1572.08  4987.0 1570.45  4994.6 1569.26
  4998.3 1567.42  5001.0 1566.92  5004.3 1567.42  5008.8 1569.34  5015.5 1574.73
  5023.1 1576.23  5029.7 1578.74  5064.2 1581.04  5105.2 1581.76  5141.0 1584.13
  5237.1 1586.54  5290.8 1590.79  5348.2 1595.63  5356.0 1597.02  5364.1 1597.02
#Mann=6,-1,0
  4023.1    0.05       0  4104.1     0.1       0  4998.3    0.07       0
  5004.3     0.1       0  5064.2    0.16       0  5290.8    0.05       0
Bank Sta=4998.3,5004.3
Exp/Cntr=0.3,0.1

Type RM Length L Ch R = 1,5765,571,571,571
BEGIN DESCRIPTION:
UNT038 IN SNOGR 12.0
END DESCRIPTION:
XS GIS Cut Line= 3
      2797353.63     10030445.59      2798009.87     10030601.84
      2798603.57     10030383.11
#Sta/Elev= 30
  4692.9 1609.93  4746.9 1605.38  4752.0 1606.06  4789.0 1593.38  4794.2 1594.37
  4800.7 1591.70  4836.3 1589.37  4847.0 1586.51  4862.3 1583.16  4883.6 1581.57
  4920.6 1573.19  4954.9 1569.48  4962.8 1566.89  4967.9 1567.95  4985.7 1563.20
  5007.0 1561.13  5009.8 1560.63  5013.0 1561.13  5026.8 1563.96  5094.3 1568.34
  5129.6 1567.55  5242.7 1570.31  5404.4 1569.53  5459.9 1571.20  5526.1 1577.75
  5685.6 1580.89  5748.4 1579.33  5872.6 1586.21  5950.9 1591.93  6000.2 1597.48
#Mann=6,-1,0
  4692.9    0.05       0  4847.0     0.1       0  5007.0    0.07       0
  5013.0     0.1       0  5685.6    0.16       0  5872.6    0.05       0
Bank Sta=5007,5013
Exp/Cntr=0.3,0.1

Type RM Length L Ch R = 1,5194,302,302,302
BEGIN DESCRIPTION:
UNT038 IN SNOGR 11.0
END DESCRIPTION:
XS GIS Cut Line= 3
      2797525.53     10031086.21      2797942.16     10030950.80
      2798654.60     10030425.57
#Sta/Elev= 30
  4480.6 1591.70  4637.6 1588.19  4661.9 1585.24  4667.1 1586.56  4679.9 1584.37
  4768.2 1581.22  4787.9 1578.57  4794.9 1576.58  4832.1 1573.61  4858.8 1567.94
  4911.6 1563.56  4977.6 1560.76  4992.2 1559.24  5003.8 1556.16  5006.6 1555.66
  5009.8 1556.16  5013.5 1558.36  5021.0 1560.17  5113.3 1559.82  5136.4 1557.50
  5151.9 1560.54  5171.9 1567.53  5178.1 1567.83  5322.2 1567.94  5396.3 1570.67
  5443.3 1571.05  5543.6 1574.95  5585.3 1581.39  5671.9 1587.80  5803.8 1599.76
#Mann=10,-1,0
  4480.6     0.1       0  4637.6    0.05       0  4679.9     0.1       0
  4787.9    0.05       0  4911.6    0.16       0  5003.8    0.07       0
  5009.8    0.16       0  5021.0     0.1       0  5151.9    0.16       0
  5396.3    0.05       0
Bank Sta=5003.8,5009.8
Exp/Cntr=0.3,0.1

Type RM Length L Ch R = 1,4892,748,748,748
BEGIN DESCRIPTION:
UNT038 IN SNOGR 10.0
END DESCRIPTION:
XS GIS Cut Line= 2
      2797801.51     10031409.16      2798673.52     10030718.81
#Sta/Elev= 30
  4609.8 1591.05  4718.8 1582.48  4739.6 1579.83  4746.2 1578.12  4782.9 1577.41
  4810.1 1578.50  4868.8 1574.78  4896.7 1572.97  4917.5 1569.97  4931.9 1566.58
  4967.2 1563.57  4981.6 1560.17  4993.0 1552.90  4995.8 1552.40  4999.0 1552.90
  5031.3 1557.82  5109.8 1557.81  5188.4 1561.09  5194.7 1561.98  5202.8 1561.55
  5209.2 1562.54  5217.2 1562.00  5287.7 1564.89  5494.5 1567.04  5600.8 1569.23
  5629.1 1572.08  5657.9 1576.86  5675.1 1580.76  5707.6 1587.35  5722.0 1591.42
#Mann=5,-1,0
  4609.8     0.1       0  4868.8    0.05       0  4993.0    0.04       0
  4999.0    0.05       0  5675.1    0.16       0
Bank Sta=4993,4999
Exp/Cntr=0.3,0.1

Type RM Length L Ch R = 1,4144,450,450,450
BEGIN DESCRIPTION:
UNT038 IN SNOGR 9.0
END DESCRIPTION:
XS GIS Cut Line= 3
      2798176.54     10031820.59      2798598.41     10031409.13
      2798723.24     10030727.78
#Sta/Elev= 30
  4283.5 1597.34  4332.1 1589.96  4381.7 1585.73  4388.7 1583.18  4452.4 1570.89
  4480.7 1572.00  4523.2 1566.03  4600.9 1562.88  4665.2 1562.29  4720.4 1561.97
  4903.5 1562.09  4943.6 1559.64  4949.5 1558.58  4955.4 1555.31  4960.5 1555.96
  4969.8 1551.44  4997.3 1545.51  5000.0 1545.01  5003.3 1545.51  5020.6 1551.81
  5030.8 1553.22  5132.5 1553.03  5163.0 1558.40  5176.3 1564.33  5203.6 1570.75
  5254.5 1575.35  5315.5 1577.05  5347.9 1580.33  5498.8 1589.50  5565.5 1594.11
#Mann=9,-1,0
  4283.5     0.1       0  4665.2    0.05       0  4720.4     0.1       0
  4903.5    0.16       0  4943.6     0.1       0  4997.3    0.07       0
  5003.3     0.1       0  5176.3     0.1       0  5498.8    0.16       0
Bank Sta=4997.3,5003.3
Exp/Cntr=0.3,0.1

Type RM Length L Ch R = 1,3694,466,466,466
BEGIN DESCRIPTION:
UNT038 IN SNOGR 8.0
END DESCRIPTION:
XS GIS Cut Line= 2
      2798249.45     10031893.51      2799315.68     10031227.77
#Sta/Elev= 30
  4153.9 1598.34  4220.9 1591.56  4261.0 1586.84  4291.7 1579.94  4318.8 1571.77
  4349.5 1571.03  4361.9 1567.91  4376.7 1564.76  4396.5 1562.96  4508.5 1560.73
  4802.2 1559.00  4827.2 1559.36  4915.9 1551.45  4966.2 1548.60  4998.6 1541.14
  5001.3 1540.64  5004.6 1541.14  5009.2 1544.91  5037.1 1563.49  5046.6 1563.63
  5052.5 1566.17  5067.8 1566.22  5073.7 1567.93  5089.0 1568.97  5125.6 1569.73
  5146.8 1572.56  5162.2 1571.68  5168.1 1573.10  5293.1 1583.73  5410.9 1590.85
#Mann=10,-1,0
  4153.9    0.16       0  4220.9     0.1       0  4361.9    0.16       0
  4396.5     0.1       0  4508.5    0.05       0  4802.2     0.1       0
  4915.9    0.05       0  4998.6   0.035       0  5004.6    0.05       0
  5009.2    0.16       0
Bank Sta=4998.6,5004.6
Exp/Cntr=0.3,0.1

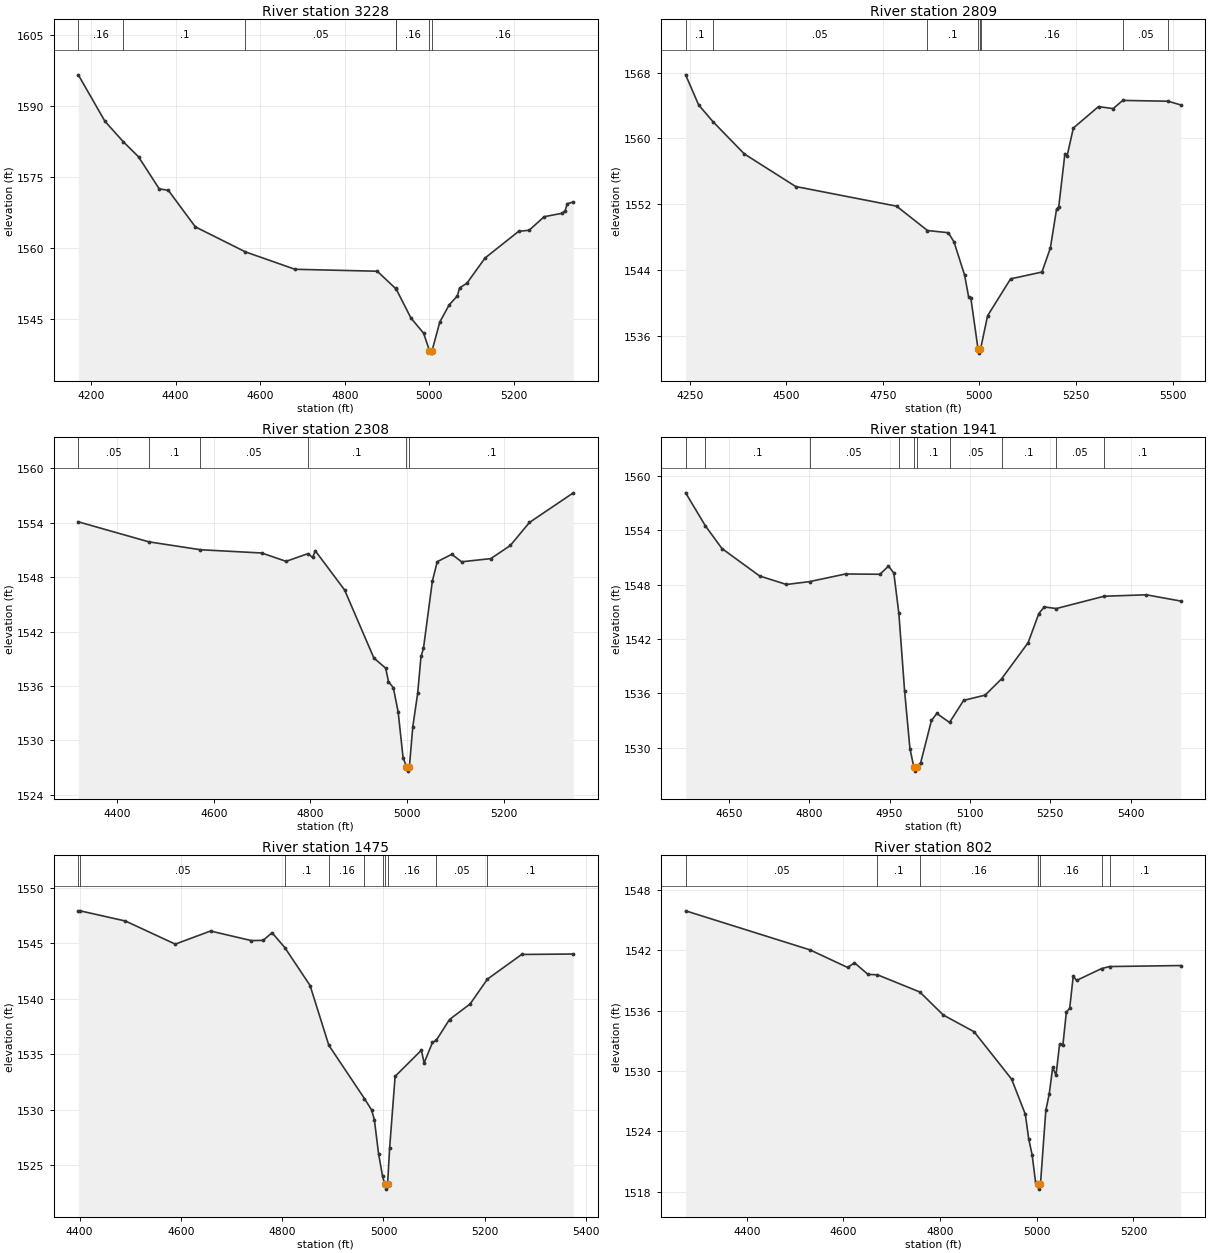
Type RM Length L Ch R = 1,3228,419,419,419
BEGIN DESCRIPTION:
UNT038 IN SNOGR 7.0
END DESCRIPTION:
XS GIS Cut Line= 2
      2798379.63     10032159.15      2799473.45     10031742.45
#Sta/Elev= 30
  4169.9 1596.66  4232.9 1586.84  4275.9 1582.55  4312.3 1579.33  4361.3 1572.54
  4382.7 1572.25  4446.7 1564.51  4565.1 1559.22  4682.3 1555.54  4876.8 1555.13
  4920.0 1551.49  4921.8 1551.32  4956.4 1545.24  4986.5 1542.01  5000.3 1538.31
  5003.1 1537.81  5006.3 1538.31  5024.7 1544.39  5046.7 1548.00  5066.1 1549.90
  5071.4 1551.59  5088.9 1552.61  5131.7 1557.93  5211.2 1563.57  5235.9 1563.79
  5271.4 1566.66  5313.7 1567.38  5320.9 1567.90  5326.2 1569.41  5340.4 1569.76
#Mann=7,-1,0
  4169.9    0.16       0  4275.9     0.1       0  4565.1    0.05       0
  4920.0     0.1       0  4921.8    0.16       0  5000.3    0.07       0
  5006.3    0.16       0
Bank Sta=5000.3,5006.3
Exp/Cntr=0.3,0.1

Type RM Length L Ch R = 1,2809,501,501,501
BEGIN DESCRIPTION:
UNT038 IN SNOGR 6.0
END DESCRIPTION:
XS GIS Cut Line= 3
      2798634.89     10032284.13      2799311.96     10032216.42
      2799837.97     10031924.77
#Sta/Elev= 30
  4239.2 1567.73  4272.9 1564.07  4309.9 1562.04  4391.2 1558.11  4524.2 1554.15
  4785.5 1551.76  4865.4 1548.80  4919.6 1548.53  4934.2 1547.41  4961.6 1543.38
  4971.9 1540.76  4977.6 1540.63  4996.4 1534.39  4999.1 1533.89  5002.4 1534.39
  5003.5 1534.52  5021.1 1538.43  5080.7 1542.92  5161.9 1543.75  5183.7 1546.67
  5199.7 1551.39  5205.4 1551.69  5221.4 1558.15  5227.2 1557.90  5243.2 1561.26
  5308.4 1563.87  5346.2 1563.62  5371.2 1564.62  5488.7 1564.52  5521.1 1564.07
#Mann=8,-1,0
  4239.2     0.1       0  4309.9    0.05       0  4865.4     0.1       0
  4996.4    0.07       0  5002.4     0.1       0  5003.5    0.16       0
  5371.2    0.05       0  5488.7     0.1       0
Bank Sta=4996.4,5002.4
Exp/Cntr=0.3,0.1

Type RM Length L Ch R = 1,2308,367,367,367
BEGIN DESCRIPTION:
UNT038 IN SNOGR 5.0
END DESCRIPTION:
XS GIS Cut Line= 2
      2798942.13     10032424.75      2799957.74     10032560.17
#Sta/Elev= 30
  4319.6 1554.11  4465.8 1551.90  4572.5 1551.03  4699.3 1550.67  4749.7 1549.75
  4795.0 1550.60  4804.4 1550.18  4810.2 1550.91  4870.8 1546.59  4931.3 1539.09
  4955.8 1537.96  4961.6 1536.49  4971.7 1535.79  4981.7 1533.11  4991.8 1528.08
  4998.9 1527.10  5001.7 1526.60  5004.9 1527.10  5012.0 1531.52  5022.1 1535.22
  5028.9 1539.25  5034.0 1540.14  5052.4 1547.55  5062.5 1549.71  5092.7 1550.53
  5112.9 1549.70  5173.4 1550.05  5213.8 1551.50  5253.4 1554.04  5344.2 1557.31
#Mann=6,-1,0
  4319.6    0.05       0  4465.8     0.1       0  4572.5    0.05       0
  4795.0     0.1       0  4998.9    0.07       0  5004.9     0.1       0
Bank Sta=4998.9,5004.9
Exp/Cntr=0.3,0.1

Type RM Length L Ch R = 1,1941,466,466,466
BEGIN DESCRIPTION:
UNT038 IN SNOGR 4.0
END DESCRIPTION:
XS GIS Cut Line= 2
      2799030.74     10032810.18      2799952.57     10032883.09
#Sta/Elev= 30
  4569.0 1558.15  4605.9 1554.50  4636.9 1551.99  4707.2 1548.96  4757.3 1548.02
  4800.8 1548.34  4867.7 1549.18  4932.0 1549.15  4947.9 1550.05  4957.9 1549.29
  4967.3 1544.83  4978.0 1536.27  4988.0 1529.88  4995.1 1527.89  4997.8 1527.39
  5001.1 1527.89  5008.1 1528.33  5028.2 1532.99  5038.2 1533.76  5062.0 1532.77
  5088.3 1535.21  5128.5 1535.79  5159.1 1537.59  5208.7 1541.58  5228.8 1544.81
  5238.8 1545.54  5261.4 1545.36  5350.7 1546.72  5429.4 1546.88  5493.7 1546.19
#Mann=10,-1,0
  4569.0    0.05       0  4605.9     0.1       0  4800.8    0.05       0
  4967.3     0.1       0  4995.1    0.07       0  5001.1     0.1       0
  5062.0    0.05       0  5159.1     0.1       0  5261.4    0.05       0
  5350.7     0.1       0
Bank Sta=4995.1,5001.1
Exp/Cntr=0.3,0.1

Type RM Length L Ch R = 1,1475,673,673,673
BEGIN DESCRIPTION:
UNT038 IN SNOGR 3.0
END DESCRIPTION:
XS GIS Cut Line= 3
      2799067.19     10032961.23      2799707.79     10033247.67
      2799978.60     10033195.59
#Sta/Elev= 30
  4397.4 1547.92  4401.0 1547.92  4490.6 1547.00  4588.9 1544.92  4658.5 1546.10
  4739.1 1545.24  4762.3 1545.26  4780.0 1545.95  4805.2 1544.61  4855.1 1541.19
  4892.1 1535.81  4962.4 1531.01  4976.6 1529.98  4982.0 1529.11  4990.3 1526.05
  4998.2 1524.01  5002.2 1523.35  5005.0 1522.85  5008.2 1523.35  5012.2 1526.57
  5023.0 1533.01  5074.8 1535.36  5080.3 1534.22  5096.8 1536.07  5104.0 1536.24
  5130.4 1538.13  5171.1 1539.53  5205.3 1541.77  5272.9 1543.99  5374.9 1544.03
#Mann=10,-1,0
  4397.4     0.1       0  4401.0    0.05       0  4805.2     0.1       0
  4892.1    0.16       0  4962.4    0.05       0  4998.2    0.16       0
  5002.2    0.07       0  5008.2    0.16       0  5104.0    0.05       0
  5205.3     0.1       0
Bank Sta=5002.2,5008.2
Exp/Cntr=0.3,0.1

Type RM Length L Ch R = 1,802,361,361,361
BEGIN DESCRIPTION:
UNT038 IN SNOGR 2.0
END DESCRIPTION:
XS GIS Cut Line= 3
      2799155.74     10033122.71      2799739.04     10033679.97
      2799952.60     10033721.64
#Sta/Elev= 30
  4273.5 1545.94  4530.7 1542.06  4608.7 1540.31  4622.9 1540.77  4650.9 1539.62
  4670.4 1539.58  4758.1 1537.87  4806.6 1535.58  4870.4 1533.92  4948.1 1529.20
  4976.4 1525.71  4983.3 1523.29  4990.5 1521.67  4997.5 1518.99  5001.7 1518.77
  5004.4 1518.27  5007.7 1518.77  5018.8 1526.11  5025.8 1527.71  5033.0 1530.37
  5039.9 1529.60  5047.2 1532.66  5054.1 1532.60  5061.3 1535.87  5068.2 1536.26
  5075.5 1539.44  5082.5 1539.02  5134.2 1540.20  5150.6 1540.40  5297.8 1540.50
#Mann=7,-1,0
  4273.5    0.05       0  4670.4     0.1       0  4758.1    0.16       0
  5001.7    0.07       0  5007.7    0.16       0  5134.2    0.05       0
  5150.6     0.1       0
Bank Sta=5001.7,5007.7
Exp/Cntr=0.3,0.1

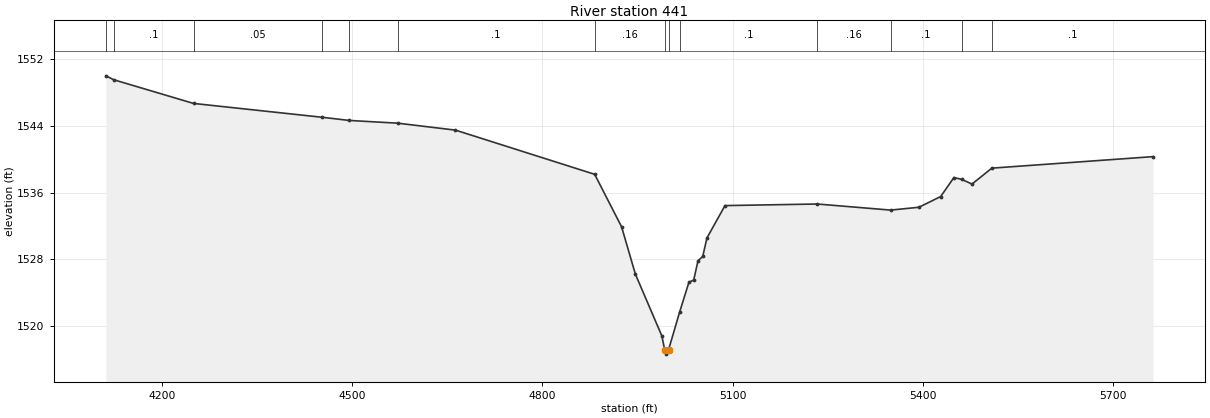
Type RM Length L Ch R = 1,441,0,0,0
BEGIN DESCRIPTION:
UNT038 IN SNOGR 1.0
END DESCRIPTION:
XS GIS Cut Line= 4
      2798785.89     10033148.69      2799483.83     10033935.17
      2799707.79     10033966.42      2799989.04     10033721.63
#Sta/Elev= 30
  4112.1 1549.99  4124.4 1549.52  4250.2 1546.68  4452.9 1545.02  4495.7 1544.64
  4572.2 1544.31  4663.1 1543.48  4882.5 1538.18  4924.9 1531.89  4946.6 1526.22
  4988.4 1518.80  4992.9 1517.12  4995.7 1516.62  4998.9 1517.12  5016.3 1521.64
  5031.1 1525.25  5038.6 1525.50  5045.3 1527.80  5052.8 1528.33  5059.5 1530.56
  5087.9 1534.43  5233.5 1534.62  5348.9 1533.89  5393.5 1534.23  5427.8 1535.51
  5448.7 1537.79  5460.9 1537.58  5477.2 1537.01  5508.5 1538.92  5762.6 1540.30
#Mann=14,-1,0
  4112.1    0.05       0  4124.4     0.1       0  4250.2    0.05       0
  4452.9     0.1       0  4495.7    0.05       0  4572.2     0.1       0
  4882.5    0.16       0  4992.9    0.07       0  4998.9    0.16       0
  5016.3     0.1       0  5233.5    0.16       0  5348.9     0.1       0
  5460.9    0.05       0  5508.5     0.1       0
Bank Sta=4992.9,4998.9
Exp/Cntr=0.3,0.1

Chan Stop Cuts=-1