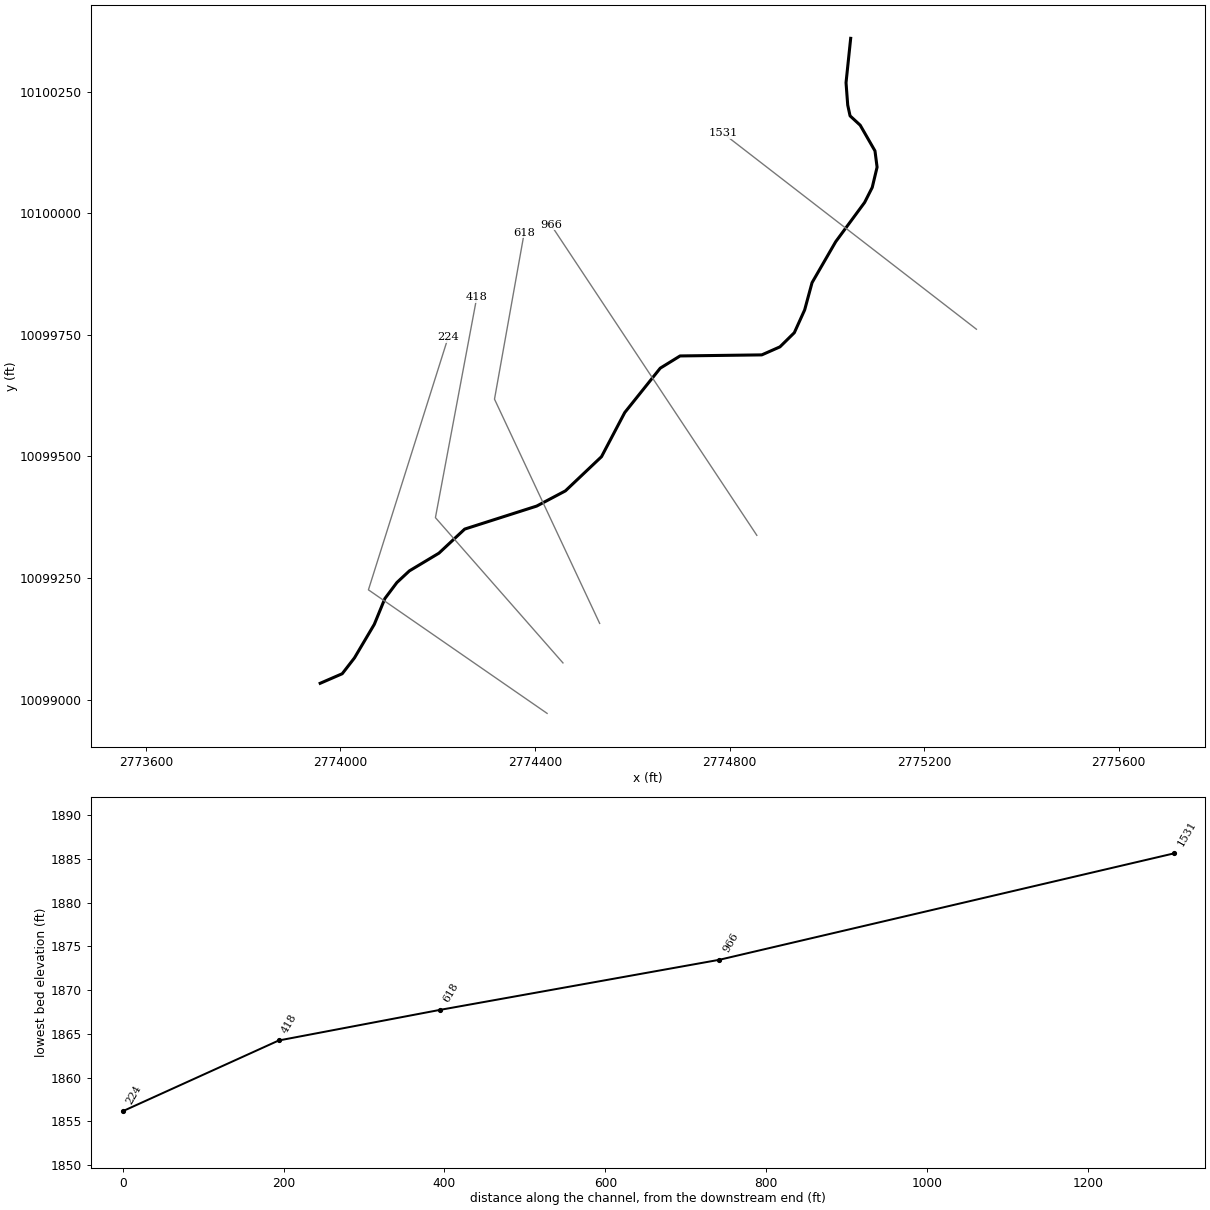
--- UNT039 IN NNOGR.prj (project) ---

Proj Title=UNT039 IN NNOGR Base Level Engineering
Current Plan=p01
Default Exp/Contr=0.3,0.1
English Units
Geom File=g01
Flow File=f01
Plan File=p01
Y Axis Title=Elevation
X Axis Title(PF)=Main Channel Distance
X Axis Title(XS)=Station
BEGIN DESCRIPTION:
UNT039 IN NNOGR
END DESCRIPTION:
DSS Export Rating Curves= 0
DSS Export Rating Curve Sorted= 0
DSS Export Volume Flow Curves= 0
DXF OffsetX= 0
DXF OffsetY= 0
DXF ScaleX= 1
DXF ScaleY= 10

--- UNT039 IN NNOGR.p01 (plan) ---

Plan Title=Multiple Run
Short Identifier=Multiple
Geom File=g01
Flow File=f01
Subcritical Flow
K Sum by GR= 0
Std Step Tol= 0.01
Critical Tol= 0.01
Num of Std Step Trials= 20
Max Error Tol= 0.3
Flow Tol Ratio= 0.001
Split Flow NTrial= 30
Split Flow Tol= 0.02
Split Flow Ratio= 0.02
Log Output Level= 0
Friction Slope Method= 1
Unsteady Friction Slope Method= 2
Unsteady Bridges Friction Slope Method= 1
Parabolic Critical Depth
Global Vel Dist=  1 , 1 , 1
Global Log Level= 0
CheckData=True
Encroach Param= -1, 0, 0, 0
BEGIN DESCRIPTION:
Multiple Run
END DESCRIPTION:

--- UNT039 IN NNOGR.f01 (steady flow) ---

Flow Title=Multiple
Program Version=4.10
Number of Profiles= 7
Profile Names=10-year,25-year,50-year,1pct_min,100-year,1pct_plu,500-year
River Rch & RM=UNT039 IN NNOGR,Reach-1         ,1531
     319     436     533     479     648     876     958
Boundary for River Rch & Prof#=UNT039 IN NNOGR,Reach-1         , 1
Up Type= 0
Dn Type= 3
Dn Slope=0.03
Boundary for River Rch & Prof#=UNT039 IN NNOGR,Reach-1         , 2
Up Type= 0
Dn Type= 3
Dn Slope=0.03
Boundary for River Rch & Prof#=UNT039 IN NNOGR,Reach-1         , 3
Up Type= 0
Dn Type= 3
Dn Slope=0.03
Boundary for River Rch & Prof#=UNT039 IN NNOGR,Reach-1         , 4
Up Type= 0
Dn Type= 3
Dn Slope=0.03
Boundary for River Rch & Prof#=UNT039 IN NNOGR,Reach-1         , 5
Up Type= 0
Dn Type= 3
Dn Slope=0.03
Boundary for River Rch & Prof#=UNT039 IN NNOGR,Reach-1         , 6
Up Type= 0
Dn Type= 3
Dn Slope=0.03
Boundary for River Rch & Prof#=UNT039 IN NNOGR,Reach-1         , 7
Up Type= 0
Dn Type= 3
Dn Slope=0.03
DSS Import GetInterval= 0
DSS Import GetPeak= 0
DSS Import FillOption= 0

--- UNT039 IN NNOGR.g01 (geometry) ---

Geom Title=Existing Conditions
Program Version=4.10

River Reach=UNT039 IN NNOGR ,Reach-1
Reach XY= 30
      2775048.89     10100359.39      2775039.34     10100268.25
      2775042.81     10100222.24      2775047.62     10100200.07
      2775068.47     10100180.84      2775098.83     10100128.02
      2775103.17      10100094.6      2775093.19     10100052.93
      2775077.57     10100022.12      2775018.11     10099941.39
      2774969.49     10099857.19       2774954.3      10099801.2
      2774933.04     10099754.32      2774903.52     10099725.24
       2774866.2     10099708.75      2774698.23     10099706.58
      2774657.43      10099681.4      2774584.51     10099590.26
      2774536.77     10099499.55      2774462.55     10099429.23
      2774403.52     10099397.98      2774255.52     10099350.68
      2774202.57      10099301.2       2774141.8     10099264.74
       2774116.2     10099240.87      2774091.46     10099207.88
      2774069.75     10099154.93      2774028.96     10099085.92
      2774003.78     10099053.37      2773958.47     10099033.73

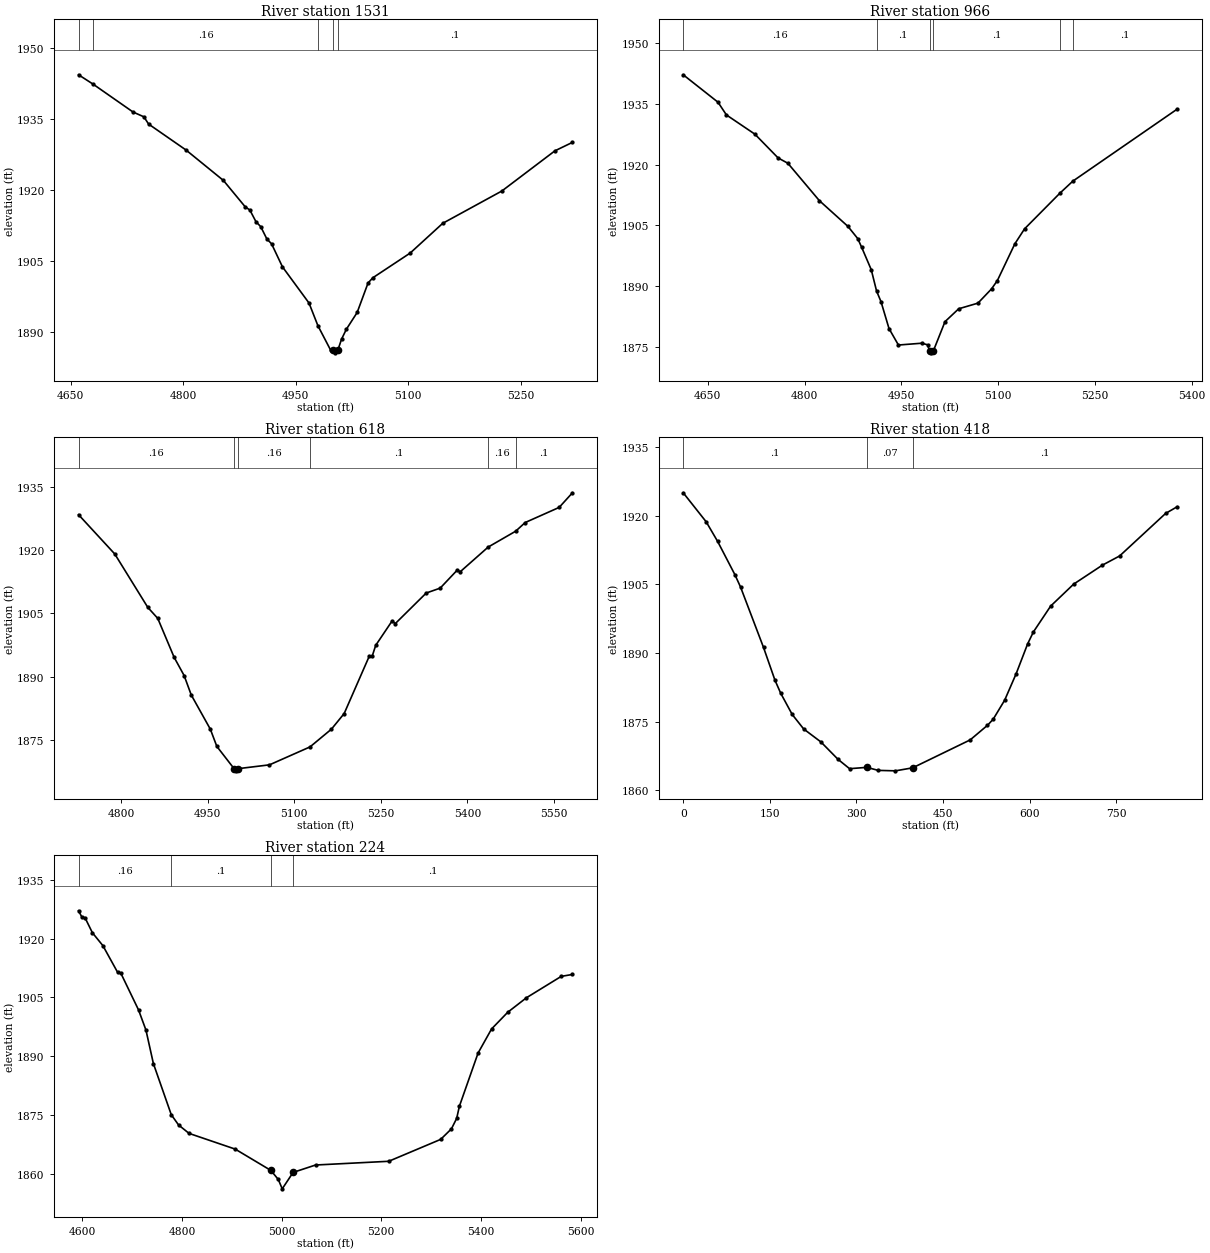
Type RM Length L Ch R = 1 ,1531    ,565,565,565
BEGIN DESCRIPTION:
UNT039 IN NNOGR 3.0
END DESCRIPTION:
XS GIS Cut Line= 2
      2775307.33     10099761.52       2774786.5      10100164.3
#Sta/Elev= 30
  4660.6 1944.35  4679.9 1942.38  4733.2 1936.49  4747.7 1935.47    4754 1933.94
  4803.8 1928.47  4853.7 1922.04  4882.6  1916.5    4889 1915.78  4897.1 1913.33
  4903.5 1912.27  4911.6 1909.69  4917.9 1908.66  4932.4  1903.8  4967.8 1896.16
  4979.7 1891.36  4996.7 1886.19  5000.1 1886.14  5002.8 1885.64  5006.1 1886.14
  5011.2 1888.53  5017.6 1890.62    5032 1894.16  5046.5 1900.38  5052.9 1901.49
  5102.7 1906.71  5146.1 1912.99  5224.9 1919.81  5295.6 1928.29    5319 1930.08
#Mann= 5 ,-1 , 0
  4660.6      .1       0  4679.9     .16       0  4979.7      .1       0
  5000.1     .07       0  5006.1      .1       0
Bank Sta=5000.1,5006.1
XS Rating Curve= 0 ,0
Exp/Cntr=0.3,0.1

Type RM Length L Ch R = 1 ,966     ,348,348,348
BEGIN DESCRIPTION:
UNT039 IN NNOGR 2.0
END DESCRIPTION:
XS GIS Cut Line= 2
      2774855.97     10099337.88      2774432.89     10099975.97
#Sta/Elev= 30
  4611.8 1942.22  4665.7 1935.44  4678.8 1932.29  4722.9 1927.54  4758.9 1921.66
    4774 1920.35  4822.8 1911.11  4867.2 1904.73  4882.3 1901.73  4888.3 1899.61
  4903.3 1894.02  4911.5 1888.77  4918.4 1886.13  4930.8 1879.48  4945.4 1875.41
  4981.5 1875.86  4990.6 1875.47  4993.6 1873.98  4996.3 1873.48  4999.6 1873.98
  5017.6 1881.19  5038.8 1884.37  5068.7 1885.77  5089.8  1889.3  5098.8 1891.36
  5125.9 1900.44  5140.9 1904.13  5195.7 1912.95  5215.7 1915.92  5377.4 1933.72
#Mann= 6 ,-1 , 0
  4611.8     .16       0  4911.5      .1       0  4993.6     .07       0
  4999.6      .1       0  5195.7     .16       0  5215.7      .1       0
Bank Sta=4993.6,4999.6
XS Rating Curve= 0 ,0
Exp/Cntr=0.3,0.1

Type RM Length L Ch R = 1 ,618     ,200,200,200
BEGIN DESCRIPTION:
Mapping XS e5f183e9
END DESCRIPTION:
XS GIS Cut Line= 3
      2774532.93     10099156.83      2774316.79     10099617.76
      2774377.85     10099959.45
#Sta/Elev= 30
    4726 1928.37  4788.8 1919.07    4846 1906.44  4863.3 1903.83  4891.7 1894.61
    4909  1890.3  4921.4 1885.69  4954.5 1877.59  4965.7 1873.53  4995.7 1868.24
  4998.5 1867.74  5001.7 1868.24    5057 1869.16  5127.2  1873.4  5164.4 1877.61
  5186.5 1881.31  5230.1 1894.92  5235.1 1894.92  5241.2 1897.46  5269.8 1903.27
  5274.9 1902.57  5328.7 1909.83  5352.9 1910.99  5382.5 1915.26  5387.6 1914.86
  5436.1 1920.71  5483.7 1924.46  5500.3 1926.52  5559.2  1930.1  5582.2 1933.56
#Mann= 6 ,-1 , 0
    4726     .16       0  4995.7     .07       0  5001.7     .16       0
  5127.2      .1       0  5436.1     .16       0  5483.7      .1       0
Bank Sta=4995.7,5001.7
XS Rating Curve= 0 ,0
Exp/Cntr=0.3,0.1

Type RM Length L Ch R = 1 ,418     ,194,194,194
XS GIS Cut Line= 3
     2774457.518     10099075.61     2774195.365    10099374.221
     2774280.434    10099827.346
#Sta/Elev= 30
       0 1925.03   39.74 1918.69    59.6  1914.4   89.41 1907.15   99.34 1904.41
  139.07 1891.22  158.94 1884.04  168.88  1881.2  188.74 1876.57  208.61  1873.4
  238.41 1870.57  268.22 1866.75  288.08 1864.72  317.89 1865.01  337.75 1864.35
  367.56 1864.25  397.36 1864.91  496.91 1871.01  526.78 1874.19  536.73 1875.52
  556.65 1879.69  576.56 1885.48  596.47 1892.01  606.42 1894.61  636.29 1900.26
  676.11 1905.06  725.89 1909.21  755.76 1911.22   835.4 1920.52  855.31 1921.97
#Mann= 3 , 0 , 0
       0      .1       0  317.89     .07       0  397.36      .1       0
Bank Sta=317.89,397.36
XS Rating Curve= 0 ,0
Exp/Cntr=0.3,0.1

Type RM Length L Ch R = 1 ,224     ,0,0,0
BEGIN DESCRIPTION:
UNT039 IN NNOGR 1.0
END DESCRIPTION:
XS GIS Cut Line= 3
       2774424.9      10098971.9      2774057.67     10099225.83
      2774221.74     10099745.37
#Sta/Elev= 30
  4592.5 1927.12  4599.4 1925.46  4605.5 1925.34  4620.3 1921.51  4641.3 1918.23
    4671 1911.39  4677.1 1911.26  4712.9 1901.82  4727.8 1896.67  4742.7 1888.13
  4778.6 1875.08  4793.3 1872.45  4814.3 1870.31  4906.9  1866.3  4978.5 1860.86
  4993.4 1858.55  5001.3 1856.16  5023.1 1860.35  5068.2 1862.24    5215 1863.19
  5319.3 1868.78  5340.9 1871.47  5351.4 1874.13  5356.9 1877.25  5394.4 1890.82
  5421.5 1896.97  5453.9 1901.22  5491.4 1904.92  5561.3 1910.38  5583.8 1910.87
#Mann= 4 ,-1 , 0
  4592.5     .16       0  4778.6      .1       0  4978.5     .07       0
  5023.1      .1       0
Bank Sta=4978.5,5023.1
XS Rating Curve= 0 ,0
Exp/Cntr=0.3,0.1

Chan Stop Cuts=-1
Use User Specified Reach Order=0
Composite Channel Slope=5