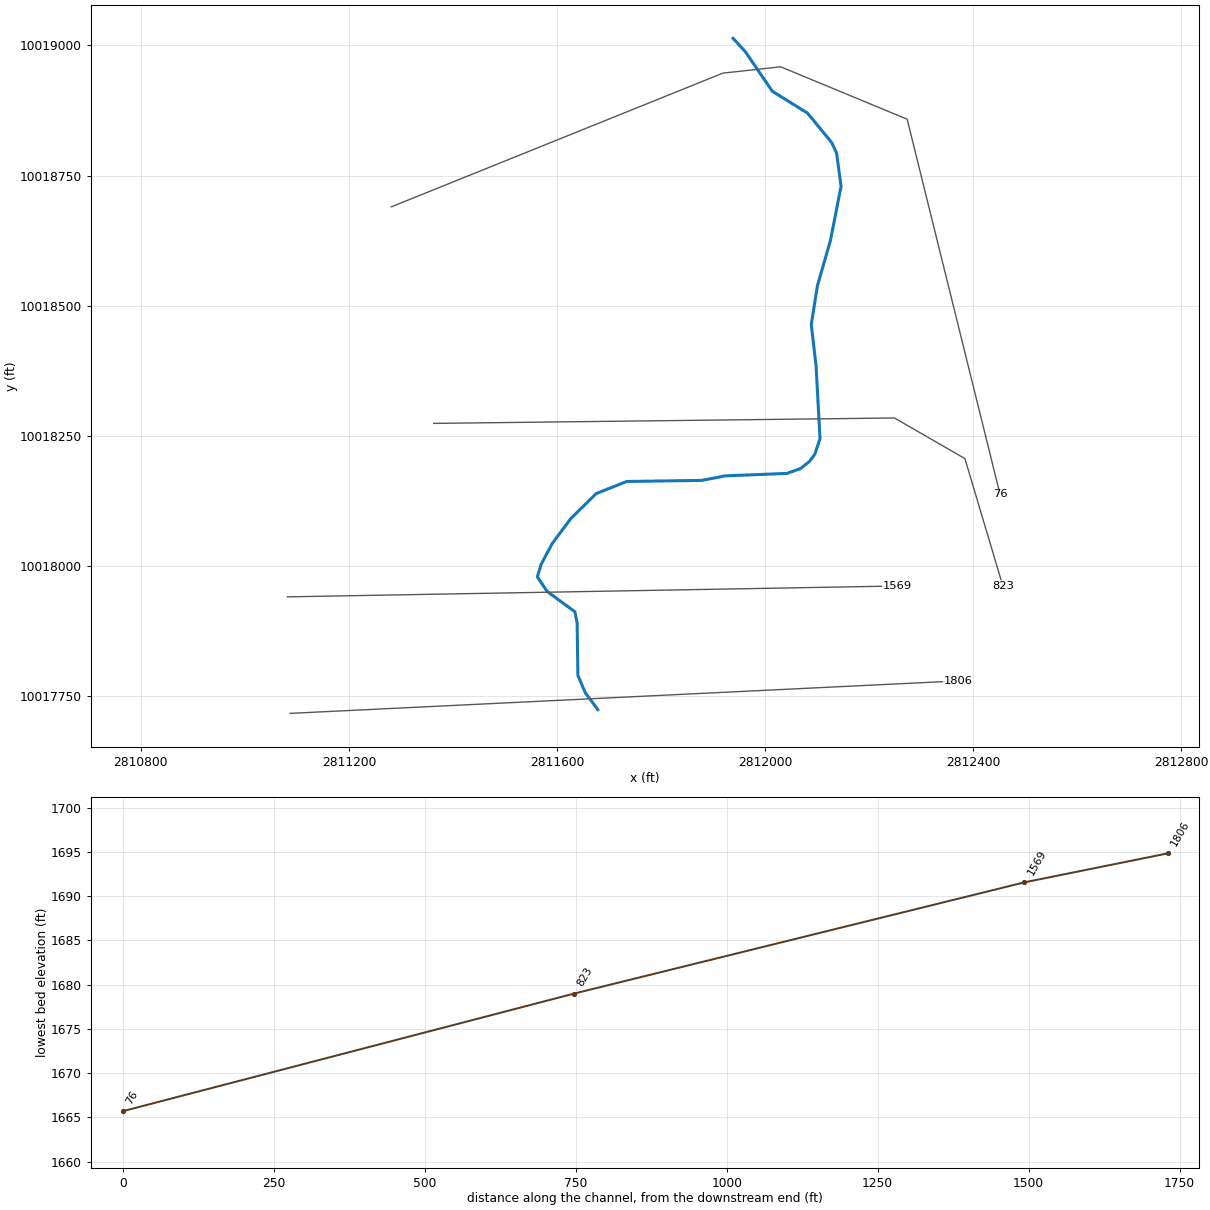
--- UNT040 IN SNOGR.prj (project) ---

Proj Title=UNT040 IN SNOGR Base Level Engineering
Current Plan=p01
Default Exp/Contr=0.3,0.1
English Units
Geom File=g01
Flow File=f01
Plan File=p01
BEGIN DESCRIPTION:
UNT040 IN SNOGR
END DESCRIPTION:

--- UNT040 IN SNOGR.p01 (plan) ---

Plan Title=Multiple Run
Short Identifier=Multiple
Geom File=g01
Flow File=f01
Subcritical Flow
K Sum by GR= 0
Std Step Tol= 0.01
Critical Tol= 0.01
Num of Std Step Trials= 20
Max Error Tol= 0.3
Flow Tol Ratio= 0.001
Split Flow NTrial= 30
Split Flow Tol= 0.02
Split Flow Ratio= 0.02
Log Output Level= 0
Friction Slope Method= 1
Unsteady Friction Slope Method= 2
Unsteady Bridges Friction Slope Method= 1
Parabolic Critical Depth
Global Vel Dist=  1 , 1 , 1
Global Log Level= 0
CheckData=True
Encroach Param= -1, 0, 0, 0
BEGIN DESCRIPTION:
Multiple Run
END DESCRIPTION:

--- UNT040 IN SNOGR.f01 (steady flow) ---

Flow Title=Multiple
Number of Profiles=7
Profile Names=10-year,25-year,50-year,1pct_min,100-year,1pct_plu,500-year
River Rch & RM= UNT040 IN SNOGR,Reach-1,1806
     893    1297    1650    1537    2079    2811    3310
Boundary for River Rch & Prof#=UNT040 IN SNOGR,Reach-1,1
Up Type=0
Dn Type=3
Dn Slope=0.005
Boundary for River Rch & Prof#=UNT040 IN SNOGR,Reach-1,2
Up Type=0
Dn Type=3
Dn Slope=0.005
Boundary for River Rch & Prof#=UNT040 IN SNOGR,Reach-1,3
Up Type=0
Dn Type=3
Dn Slope=0.005
Boundary for River Rch & Prof#=UNT040 IN SNOGR,Reach-1,4
Up Type=0
Dn Type=3
Dn Slope=0.005
Boundary for River Rch & Prof#=UNT040 IN SNOGR,Reach-1,5
Up Type=0
Dn Type=3
Dn Slope=0.005
Boundary for River Rch & Prof#=UNT040 IN SNOGR,Reach-1,6
Up Type=0
Dn Type=3
Dn Slope=0.005
Boundary for River Rch & Prof#=UNT040 IN SNOGR,Reach-1,7
Up Type=0
Dn Type=3
Dn Slope=0.005

--- UNT040 IN SNOGR.g01 (geometry) ---

Geom Title=Existing Conditions

River Reach=UNT040 IN SNOGR,Reach-1
Reach XY= 30
      2811678.47     10017723.73      2811654.50     10017755.96
      2811640.21     10017789.28      2811638.72     10017889.89
      2811634.54     10017911.56      2811581.31     10017950.58
      2811562.31     10017978.72      2811569.55     10018002.83
      2811590.76     10018042.65      2811626.38     10018090.54
      2811675.45     10018138.83      2811734.14     10018162.10
      2811878.28     10018164.18      2811923.27     10018172.86
      2812041.76     10018177.56      2812067.60     10018186.69
      2812085.15     10018200.37      2812095.66     10018214.70
      2812105.52     10018244.46      2812097.93     10018384.27
      2812088.69     10018463.53      2812100.54     10018538.32
      2812125.48     10018624.98      2812145.96     10018729.26
      2812137.35     10018793.20      2812127.86     10018813.49
      2812081.50     10018870.04      2812013.80     10018912.08
      2811962.02     10018988.01      2811938.47     10019013.73

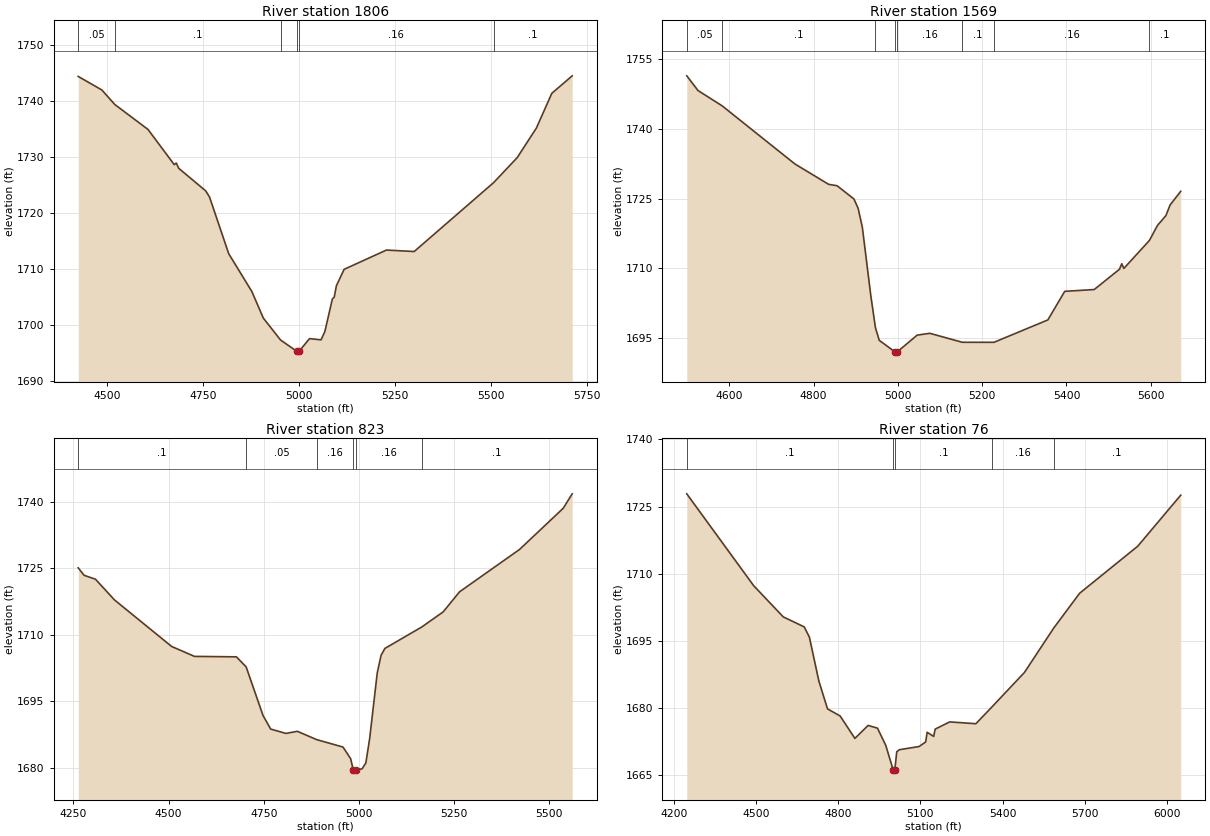
Type RM Length L Ch R = 1,1806,237,237,237
BEGIN DESCRIPTION:
UNT040 IN SNOGR 3.0
END DESCRIPTION:
XS GIS Cut Line= 2
      2811087.12     10017716.42      2812371.50     10017778.82
#Sta/Elev= 30
  4424.9 1744.42  4486.3 1742.01  4520.1 1739.41  4606.5 1734.96  4675.0 1728.66
  4680.0 1728.97  4686.6 1728.01  4756.6 1724.00  4766.7 1722.89  4816.7 1712.76
  4876.8 1706.03  4906.8 1701.27  4951.5 1697.37  4993.9 1695.34  4996.7 1694.84
  4999.9 1695.34  5027.0 1697.61  5057.0 1697.39  5067.0 1698.88  5086.4 1704.67
  5091.4 1705.03  5097.0 1707.05  5117.1 1709.98  5227.2 1713.42  5299.5 1713.16
  5506.1 1725.45  5567.6 1729.92  5617.7 1735.21  5657.7 1741.40  5710.8 1744.53
#Mann=6,-1,0
  4424.9    0.05       0  4520.1     0.1       0  4951.5    0.16       0
  4993.9    0.07       0  4999.9    0.16       0  5506.1     0.1       0
Bank Sta=4993.9,4999.9
Exp/Cntr=0.3,0.1

Type RM Length L Ch R = 1,1569,746,746,746
BEGIN DESCRIPTION:
Mapping XS 4368d090
END DESCRIPTION:
XS GIS Cut Line= 2
      2811081.92     10017940.38      2812253.63     10017961.21
#Sta/Elev= 30
  4499.1 1751.46  4525.7 1748.30  4582.9 1745.01  4755.7 1732.49  4835.7 1728.11
  4855.7 1727.81  4895.7 1724.96  4905.7 1722.95  4915.7 1718.83  4935.7 1704.17
  4946.7 1697.28  4955.7 1694.55  4992.7 1692.07  4995.5 1691.57  4998.7 1692.07
  5045.7 1695.66  5075.7 1696.05  5152.8 1694.12  5227.9 1694.11  5355.8 1698.93
  5395.8 1705.08  5465.8 1705.47  5525.8 1709.84  5531.1 1711.02  5536.1 1710.01
  5596.7 1716.03  5615.8 1719.25  5635.8 1721.37  5645.8 1723.67  5671.0 1726.61
#Mann=8,-1,0
  4499.1    0.05       0  4582.9     0.1       0  4946.7    0.16       0
  4992.7    0.07       0  4998.7    0.16       0  5152.8     0.1       0
  5227.9    0.16       0  5596.7     0.1       0
Bank Sta=4992.7,4998.7
Exp/Cntr=0.3,0.1

Type RM Length L Ch R = 1,823,747,747,747
BEGIN DESCRIPTION:
UNT040 IN SNOGR 2.0
END DESCRIPTION:
XS GIS Cut Line= 4
      2811363.13     10018273.72      2812248.59     10018284.13
      2812384.00     10018206.01      2812456.93     10017961.19
#Sta/Elev= 30
  4262.7 1725.13  4278.0 1723.45  4308.0 1722.56  4358.0 1717.88  4508.1 1707.37
  4568.1 1705.13  4678.1 1705.03  4703.7 1702.76  4748.1 1691.77  4768.1 1688.72
  4808.1 1687.73  4838.1 1688.21  4889.0 1686.33  4958.1 1684.65  4978.1 1682.03
  4985.1 1679.49  4987.8 1678.99  4991.1 1679.49  5008.1 1679.73  5018.1 1681.06
  5028.1 1686.56  5048.1 1701.46  5058.1 1705.38  5068.1 1706.93  5164.9 1711.77
  5221.1 1715.18  5264.2 1719.72  5421.7 1729.28  5536.5 1738.59  5560.0 1741.85
#Mann=6,-1,0
  4262.7     0.1       0  4703.7    0.05       0  4889.0    0.16       0
  4985.1    0.07       0  4991.1    0.16       0  5164.9     0.1       0
Bank Sta=4985.1,4991.1
Exp/Cntr=0.3,0.1

Type RM Length L Ch R = 1,76,0,0,0
BEGIN DESCRIPTION:
UNT040 IN SNOGR 1.0
END DESCRIPTION:
XS GIS Cut Line= 5
      2811281.62     10018689.89      2811918.81     10018946.85
      2812029.92     10018959.01      2812272.98     10018858.31
      2812451.47     10018137.40
#Sta/Elev= 30
  4246.4 1727.86  4491.0 1707.33  4598.8 1700.38  4675.4 1698.14  4694.2 1695.89
  4729.1 1686.02  4760.6 1679.83  4806.9 1678.23  4860.6 1673.23  4908.9 1676.13
  4943.2 1675.52  4973.3 1671.70  5000.5 1666.20  5003.3 1665.70  5006.5 1666.20
  5013.6 1670.27  5023.6 1670.71  5095.3 1671.42  5119.2 1672.44  5124.6 1674.60
  5148.5 1673.67  5153.9 1675.31  5207.1 1676.92  5302.6 1676.51  5361.6 1680.28
  5479.9 1687.95  5587.2 1697.89  5681.8 1705.66  5894.0 1716.16  6051.0 1727.56
#Mann=5,-1,0
  4246.4     0.1       0  5000.5    0.07       0  5006.5     0.1       0
  5361.6    0.16       0  5587.2     0.1       0
Bank Sta=5000.5,5006.5
Exp/Cntr=0.3,0.1

Chan Stop Cuts=-1