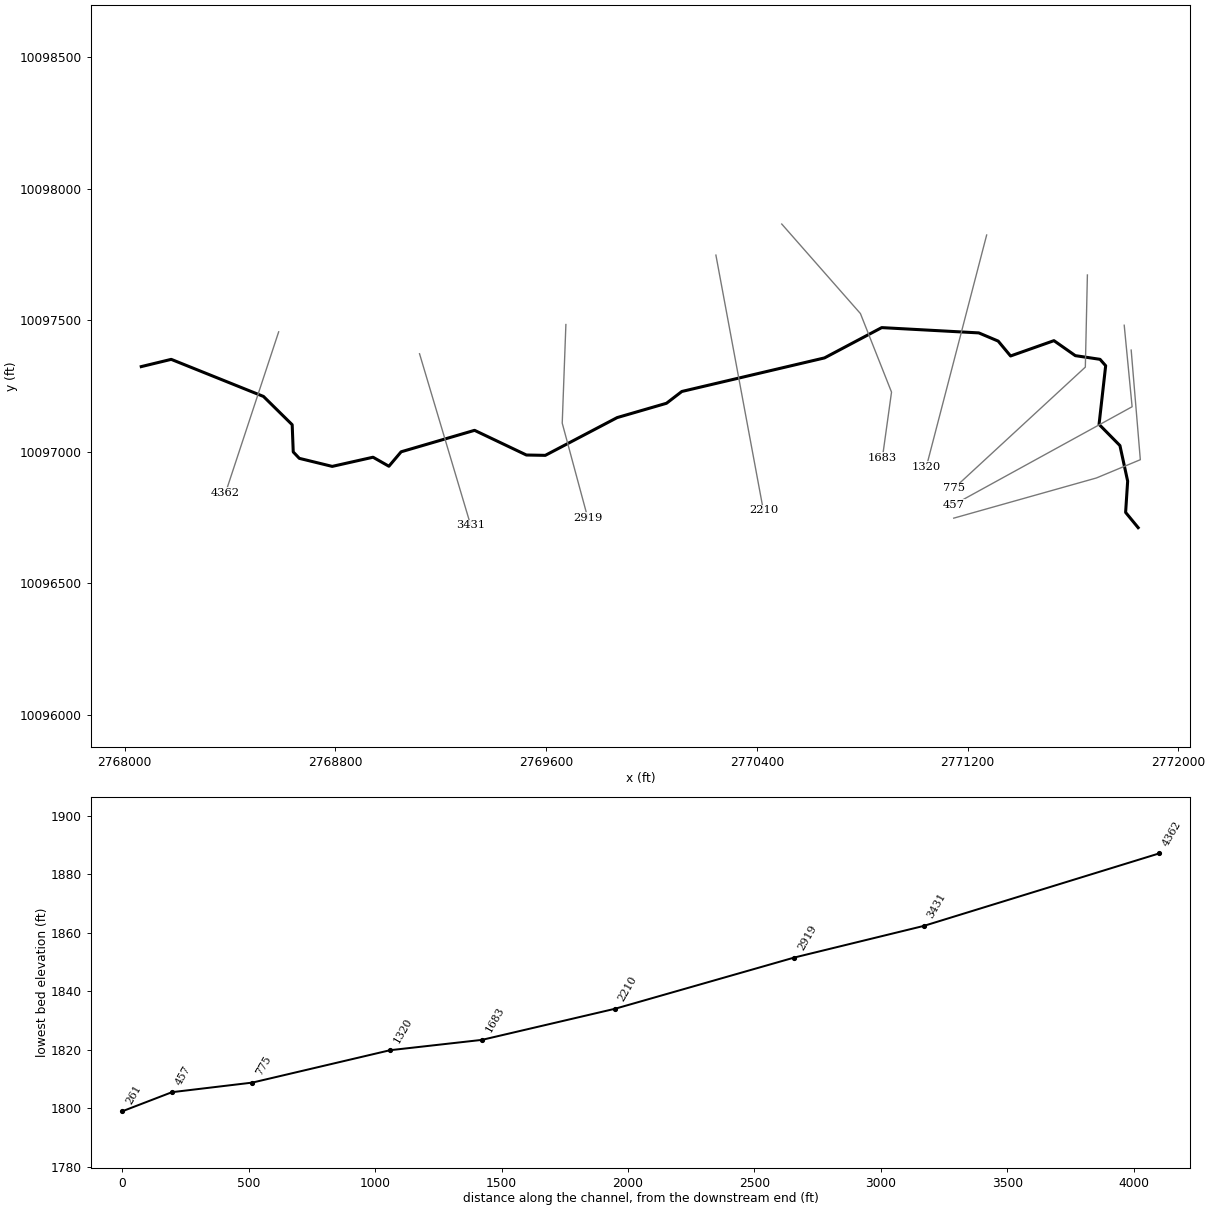
--- UNT041 IN NNOGR.prj (project) ---

Proj Title=UNT041 IN NNOGR Base Level Engineering
Current Plan=p01
Default Exp/Contr=0.3,0.1
English Units
Geom File=g01
Flow File=f01
Plan File=p01
Y Axis Title=Elevation
X Axis Title(PF)=Main Channel Distance
X Axis Title(XS)=Station
BEGIN DESCRIPTION:
UNT041 IN NNOGR
END DESCRIPTION:
DSS Export Rating Curves= 0
DSS Export Rating Curve Sorted= 0
DSS Export Volume Flow Curves= 0
DXF OffsetX= 0
DXF OffsetY= 0
DXF ScaleX= 1
DXF ScaleY= 10

--- UNT041 IN NNOGR.p01 (plan) ---

Plan Title=Multiple Run
Short Identifier=Multiple
Geom File=g01
Flow File=f01
Subcritical Flow
K Sum by GR= 0
Std Step Tol= 0.01
Critical Tol= 0.01
Num of Std Step Trials= 20
Max Error Tol= 0.3
Flow Tol Ratio= 0.001
Split Flow NTrial= 30
Split Flow Tol= 0.02
Split Flow Ratio= 0.02
Log Output Level= 0
Friction Slope Method= 1
Unsteady Friction Slope Method= 2
Unsteady Bridges Friction Slope Method= 1
Parabolic Critical Depth
Global Vel Dist=  1 , 1 , 1
Global Log Level= 0
CheckData=True
Encroach Param= -1, 0, 0, 0
BEGIN DESCRIPTION:
Multiple Run
END DESCRIPTION:

--- UNT041 IN NNOGR.f01 (steady flow) ---

Flow Title=Multiple
Program Version=4.10
Number of Profiles= 7
Profile Names=10-year,25-year,50-year,1pct_min,100-year,1pct_plu,500-year
River Rch & RM=UNT041 IN NNOGR,Reach-1         ,4362
     331     453     554     498     674     911     997
Boundary for River Rch & Prof#=UNT041 IN NNOGR,Reach-1         , 1
Up Type= 0
Dn Type= 3
Dn Slope=0.017
Boundary for River Rch & Prof#=UNT041 IN NNOGR,Reach-1         , 2
Up Type= 0
Dn Type= 3
Dn Slope=0.017
Boundary for River Rch & Prof#=UNT041 IN NNOGR,Reach-1         , 3
Up Type= 0
Dn Type= 3
Dn Slope=0.017
Boundary for River Rch & Prof#=UNT041 IN NNOGR,Reach-1         , 4
Up Type= 0
Dn Type= 3
Dn Slope=0.017
Boundary for River Rch & Prof#=UNT041 IN NNOGR,Reach-1         , 5
Up Type= 0
Dn Type= 3
Dn Slope=0.017
Boundary for River Rch & Prof#=UNT041 IN NNOGR,Reach-1         , 6
Up Type= 0
Dn Type= 3
Dn Slope=0.017
Boundary for River Rch & Prof#=UNT041 IN NNOGR,Reach-1         , 7
Up Type= 0
Dn Type= 3
Dn Slope=0.017
DSS Import GetInterval= 0
DSS Import GetPeak= 0
DSS Import FillOption= 0

--- UNT041 IN NNOGR.g01 (geometry) ---

Geom Title=Existing Conditions
Program Version=4.10

River Reach=UNT041 IN NNOGR ,Reach-1
Reach XY= 30
      2768063.47     10097323.73      2768177.23      10097351.3
       2768527.4     10097210.36      2768636.44     10097102.82
      2768640.44     10096999.33      2768663.49     10096974.97
      2768788.41      10096944.4      2768943.38     10096979.25
      2769003.54     10096944.93      2769049.98     10096999.88
      2769328.72     10097081.48      2769525.48     10096987.66
      2769597.25     10096986.35      2769870.05     10097129.92
       2770057.3     10097184.37      2770115.56     10097229.19
      2770657.18     10097356.84      2770874.28       10097472.
      2771242.75      10097451.9      2771316.44      10097420.7
      2771363.37     10097364.14      2771528.06     10097422.41
      2771609.17     10097365.42      2771702.95     10097351.43
      2771724.39     10097327.09      2771699.29     10097104.13
      2771778.52     10097023.64      2771807.85     10096888.44
      2771800.09     10096769.49      2771847.73     10096711.47

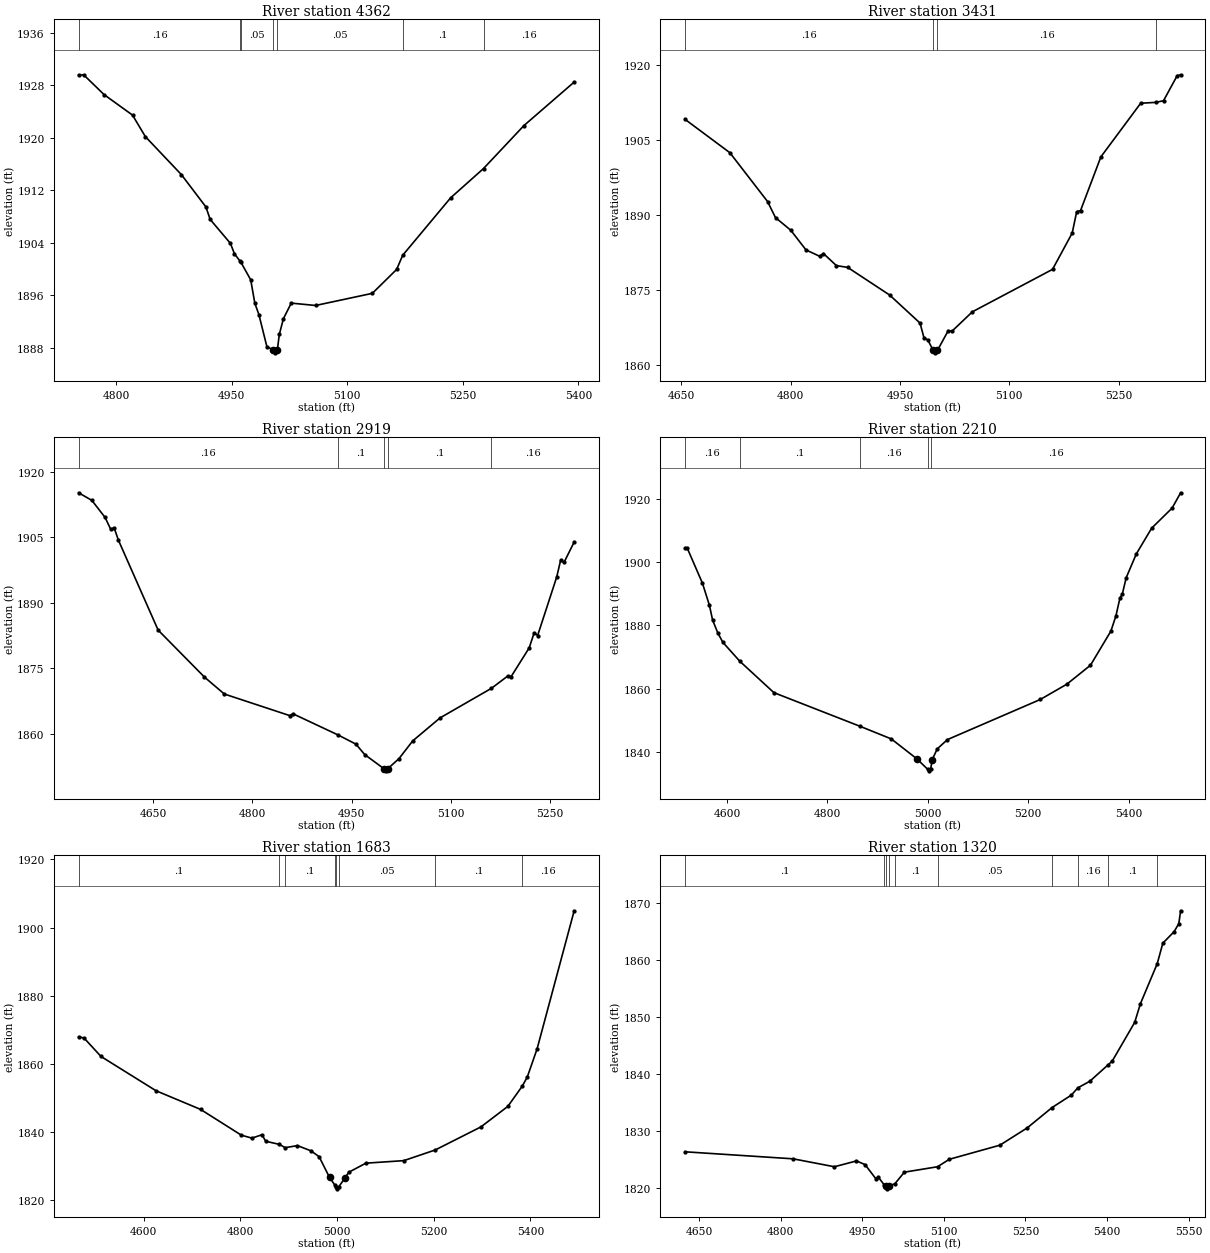
Type RM Length L Ch R = 1 ,4362    ,931,931,931
BEGIN DESCRIPTION:
UNT041 IN NNOGR 9.0
END DESCRIPTION:
XS GIS Cut Line= 2
      2768585.13     10097455.97      2768383.72      10096844.8
#Sta/Elev= 30
  4751.1 1929.53  4757.6 1929.58  4784.1 1926.56  4821.1 1923.43  4837.7 1920.16
  4884.6 1914.35  4916.4 1909.43  4921.9 1907.53  4948.2 1903.88  4953.5 1902.27
    4961 1901.13  4961.8 1901.01  4974.6 1898.31  4979.9 1894.75  4985.2 1893.02
  4995.6 1888.11  5003.2 1887.69  5005.9 1887.19  5009.2 1887.69  5011.7 1889.99
    5017 1892.39  5027.2 1894.77  5058.8 1894.41  5132.5 1896.26  5164.1 1899.91
  5171.9 1902.06  5234.1 1910.81  5276.9 1915.29  5329.4 1921.84  5394.6 1928.47
#Mann= 7 ,-1 , 0
  4751.1     .16       0    4961      .1       0  4961.8     .05       0
  5003.2    .035       0  5009.2     .05       0  5171.9      .1       0
  5276.9     .16       0
Bank Sta=5003.2,5009.2
XS Rating Curve= 0 ,0
Exp/Cntr=0.3,0.1

Type RM Length L Ch R = 1 ,3431    ,512,512,512
BEGIN DESCRIPTION:
UNT041 IN NNOGR 7.0
END DESCRIPTION:
XS GIS Cut Line= 2
      2769119.85     10097372.61      2769313.89     10096721.19
#Sta/Elev= 30
  4655.4 1909.05  4716.8 1902.39  4768.5 1892.63  4779.4 1889.41  4800.3  1886.9
  4821.2 1882.96    4840 1881.68  4845.2 1882.23  4862.9 1879.82  4878.4 1879.46
    4936 1873.93  4977.7 1868.32  4983.1 1865.34  4988.3 1864.98  4995.6 1862.88
  4998.3 1862.38  5001.6 1862.88  5016.3 1866.81  5021.5 1866.71  5049.4 1870.58
  5159.4 1879.07  5186.4 1886.34  5192.5  1890.6  5197.8 1890.82  5225.7 1901.56
  5280.3 1912.28  5300.7 1912.45  5311.6 1912.78  5330.4  1917.8  5335.1 1917.97
#Mann= 4 ,-1 , 0
  4655.4     .16       0  4995.6     .07       0  5001.6     .16       0
  5300.7      .1       0
Bank Sta=4995.6,5001.6
XS Rating Curve= 0 ,0
Exp/Cntr=0.3,0.1

Type RM Length L Ch R = 1 ,2919    ,709,709,709
BEGIN DESCRIPTION:
UNT041 IN NNOGR 6.0
END DESCRIPTION:
XS GIS Cut Line= 3
       2769675.4     10097483.71      2769661.51     10097108.73
      2769758.58      10096748.2
#Sta/Elev= 30
  4537.6 1915.16  4557.6 1913.42  4577.6 1909.51  4586.2 1906.77  4591.2 1907.17
  4597.6 1904.35  4657.7 1883.75  4727.7    1873  4757.7 1869.13  4856.4  1864.2
  4861.4 1864.61  4929.6 1859.76  4956.5 1857.67  4969.8 1855.28  4998.7 1852.06
  5001.4 1851.56  5004.7 1852.06  5021.6 1854.36  5042.3 1858.41  5083.7 1863.68
  5161.2 1870.43  5185.8 1873.24    5191 1873.12  5218.3  1879.7  5225.8 1883.16
    5231 1882.51  5259.8 1895.88  5265.7 1899.69  5270.9 1899.24  5286.2  1903.9
#Mann= 5 ,-1 , 0
  4537.6     .16       0  4929.6      .1       0  4998.7     .07       0
  5004.7      .1       0  5161.2     .16       0
Bank Sta=4998.7,5004.7
XS Rating Curve= 0 ,0
Exp/Cntr=0.3,0.1

Type RM Length L Ch R = 1 ,2210    ,527,527,527
BEGIN DESCRIPTION:
UNT041 IN NNOGR 4.0
END DESCRIPTION:
XS GIS Cut Line= 2
      2770244.85     10097747.62       2770425.1     10096777.02
#Sta/Elev= 30
  4516.5 1904.27    4521 1904.27    4551  1893.3    4565 1886.28  4571.3 1881.63
  4581.5 1877.63  4591.7 1874.62  4625.4 1868.65  4693.4 1858.72  4865.7 1848.05
  4927.3 1844.11  4978.2 1837.82  4999.7 1834.53  5002.5 1834.03  5005.7 1834.53
  5008.7 1837.53  5018.8 1840.97  5039.2  1843.9  5224.1 1856.56  5276.9 1861.38
    5324 1867.36  5364.7 1878.13  5374.8 1882.97  5382.6 1888.49  5387.6 1889.87
  5395.2    1895  5415.5 1902.56    5446 1910.66  5486.7    1917  5503.7 1921.83
#Mann= 5 ,-1 , 0
  4516.5     .16       0  4625.4      .1       0  4865.7     .16       0
  4999.7     .07       0  5005.7     .16       0
Bank Sta=4978.2,5008.7
XS Rating Curve= 0 ,0
Exp/Cntr=0.3,0.1

Type RM Length L Ch R = 1 ,1683    ,363,363,363
BEGIN DESCRIPTION:
UNT041 IN NNOGR 3.0
END DESCRIPTION:
XS GIS Cut Line= 4
      2770494.82      10097865.7      2770793.46      10097525.4
      2770911.51     10097226.79      2770876.92     10096977.73
#Sta/Elev= 30
  4465.2 1867.95  4476.4 1867.61  4511.5  1862.2  4625.4 1852.14  4717.4 1846.68
  4801.9 1839.11  4823.7 1838.25  4844.6 1839.24  4852.2 1837.33  4880.6 1836.41
  4892.6 1835.45    4918 1836.05  4945.9 1834.52  4962.8  1832.8  4984.3 1826.72
  4995.1 1824.52    4997 1823.87  4999.7 1823.37    5003 1823.87  5016.5 1826.62
  5024.3 1828.25  5059.5  1830.9  5137.9 1831.64    5203 1834.77  5297.6 1841.54
  5353.2 1847.55  5383.2 1853.52  5393.6 1856.21  5413.8 1864.44  5490.5 1904.94
#Mann= 8 ,-1 , 0
  4465.2      .1       0  4880.6     .16       0  4892.6      .1       0
  4995.1     .05       0    4997    .035       0    5003     .05       0
    5203      .1       0  5383.2     .16       0
Bank Sta=4984.3,5016.5
XS Rating Curve= 0 ,0
Exp/Cntr=0.3,0.1

Type RM Length L Ch R = 1 ,1320    ,545,545,545
BEGIN DESCRIPTION:
UNT041 IN NNOGR 2.0
END DESCRIPTION:
XS GIS Cut Line= 2
      2771272.62     10097824.01      2771043.47      10096942.1
#Sta/Elev= 30
  4624.3 1826.33  4822.9  1825.1  4898.8 1823.71  4939.4 1824.73  4955.2 1824.09
  4974.8 1821.64  4979.9 1821.85  4990.1 1820.58  4993.5 1820.34  4996.3 1819.84
  4999.5 1820.34  5010.1 1820.74  5027.5 1822.76  5088.5 1823.71  5110.2 1825.02
  5203.2 1827.49  5253.4 1830.52  5299.2 1834.09  5334.5 1836.26  5346.4 1837.53
  5368.5 1838.69  5401.9 1841.55  5409.8 1842.24    5451    1849  5461.5 1852.27
  5492.4 1859.28  5502.8 1862.89  5523.5  1864.9  5532.1  1866.3  5535.5 1868.56
#Mann= 10 ,-1 , 0
  4624.3      .1       0  4990.1     .05       0  4993.5    .035       0
  4999.5     .05       0  5010.1      .1       0  5088.5     .05       0
  5299.2      .1       0  5346.4     .16       0  5401.9      .1       0
  5492.4     .16       0
Bank Sta=4993.5,4999.5
XS Rating Curve= 0 ,0
Exp/Cntr=0.3,0.1

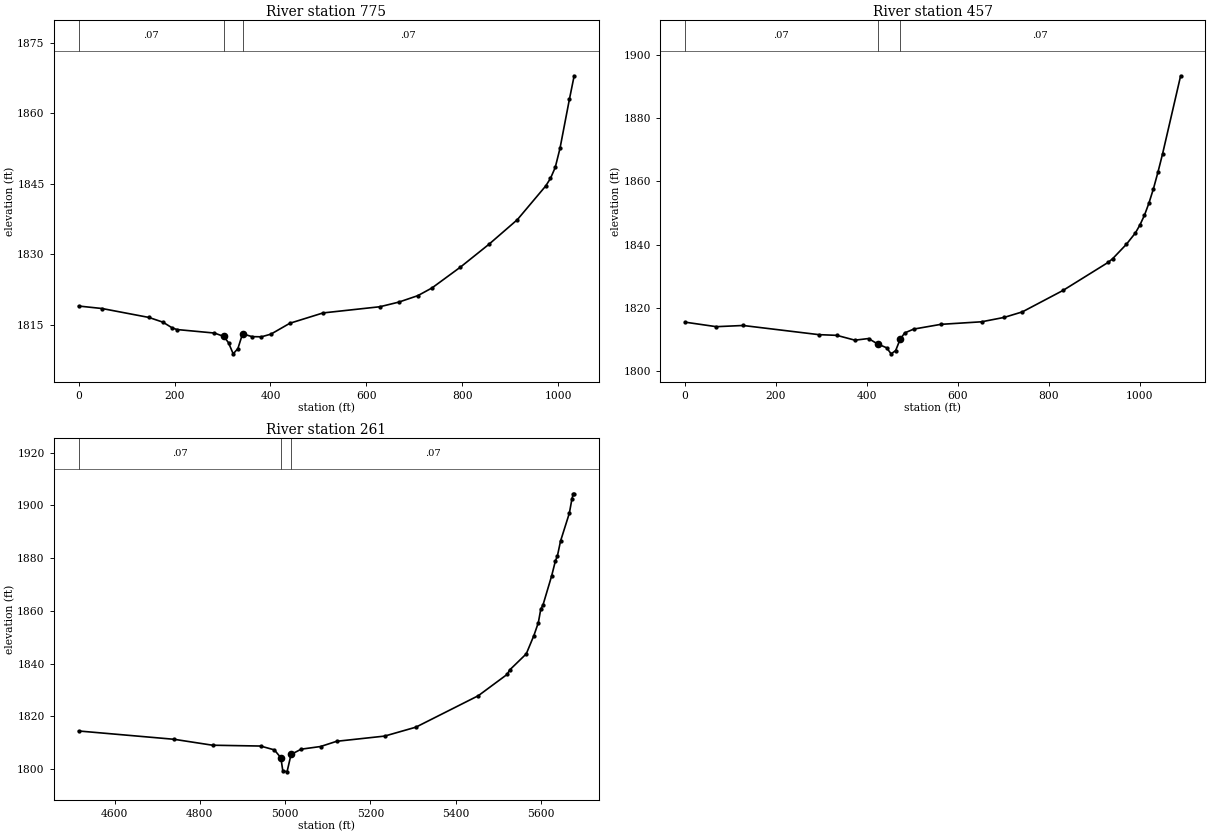
Type RM Length L Ch R = 1 ,775     ,318,318,318
XS GIS Cut Line= 3
      2771655.02    10097672.107     2771647.208    10097321.847
      2771148.51     10096860.91
#Sta/Elev= 30
       0 1818.94   48.83 1818.41   146.5 1816.51   175.8  1815.5  195.33 1814.27
   205.1 1813.93  283.23 1813.18  302.77 1812.46  312.53 1811.12   322.3 1808.75
  332.07 1809.86  341.83 1813.02  361.48 1812.42  381.24 1812.38     401 1812.95
  440.52 1815.27  509.69 1817.47  628.25 1818.79  667.77 1819.78   707.3 1821.15
  736.94  1822.8  796.22 1827.24   855.5 1832.09  914.78 1837.34  974.07 1844.54
  983.95 1846.15  993.83 1848.47 1003.71 1852.52 1023.47 1863.04 1033.35 1868.02
#Mann= 3 , 0 , 0
       0     .07       0  302.77     .03       0  341.83     .07       0
Bank Sta=302.77,341.83
XS Rating Curve= 0 ,0
Exp/Cntr=0.3,0.1

Type RM Length L Ch R = 1 ,457     ,196,196,196
XS GIS Cut Line= 3
     2771794.796    10097481.047     2771824.744    10097171.151
     2771147.661    10096798.755
#Sta/Elev= 30
       0 1815.49   68.67 1814.06  127.53 1814.44  294.31 1811.54  333.84 1811.32
  373.65 1809.79   403.5 1810.31  423.41 1808.61  443.31 1807.39  453.26 1805.47
  463.22  1806.5  473.17 1810.09  483.12 1812.09  503.02  1813.3  562.74  1814.8
  652.31 1815.61  702.07    1817  741.88 1818.74  831.45 1825.53  930.97 1834.42
  940.92 1835.61  970.78 1840.11  990.68 1843.72 1000.63 1846.23 1010.59 1849.31
 1020.54 1853.19 1030.49 1857.76 1040.44 1863.02  1050.4  1868.7  1090.2 1893.43
#Mann= 3 , 0 , 0
       0     .07       0  423.41     .03       0  473.17     .07       0
Bank Sta=423.41,473.17
XS Rating Curve= 0 ,0
Exp/Cntr=0.3,0.1

Type RM Length L Ch R = 1 ,261     ,0,0,0
BEGIN DESCRIPTION:
UNT041 IN NNOGR 1.0
END DESCRIPTION:
XS GIS Cut Line= 4
      2771821.23     10097386.56      2771855.96     10096969.84
      2771689.29      10096900.4      2771147.64     10096747.63
#Sta/Elev= 30
  4515.9 1814.44  4739.5 1811.29  4829.8 1809.04  4942.3 1808.73  4974.7 1807.27
  4989.9 1804.29 4994.44 1799.36 5004.38 1798.95  5013.8 1805.55  5037.6 1807.54
    5083 1808.55  5120.7 1810.53  5233.1  1812.5  5306.3 1815.88  5452.7 1827.81
  5520.7 1835.94  5525.9 1837.52  5565.1 1843.67    5583 1850.63  5593.4  1855.5
  5599.1 1860.61  5604.3  1862.2  5624.6 1873.22  5633.1 1878.71  5638.3 1880.95
  5645.4  1886.4  5666.1 1897.01  5672.3 1902.52  5675.4 1904.36  5677.4 1904.36
#Mann= 3 , 0 , 0
  4515.9     .07       0  4989.9     .03       0  5013.8     .07       0
Bank Sta=4989.9,5013.8
XS Rating Curve= 0 ,0
Exp/Cntr=0.3,0.1

Chan Stop Cuts=-1
Use User Specified Reach Order=0
Composite Channel Slope=5