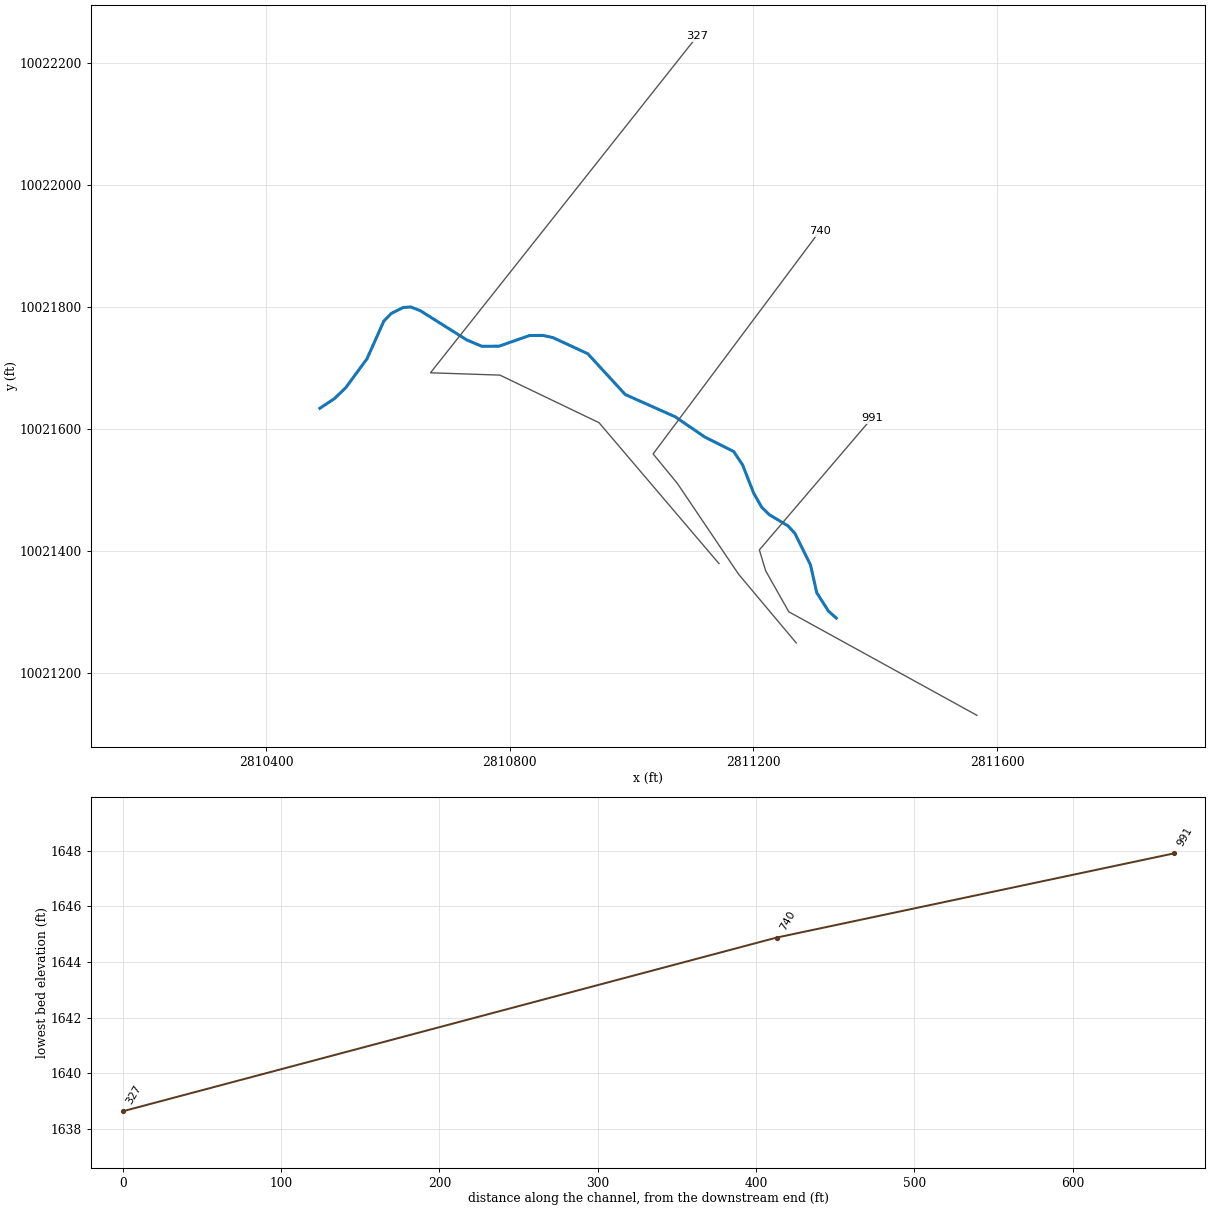
--- UNT041 IN SNOGR.prj (project) ---

Proj Title=UNT041 IN SNOGR Base Level Engineering
Current Plan=p01
Default Exp/Contr=0.3,0.1
English Units
Geom File=g01
Flow File=f01
Plan File=p01
Y Axis Title=Elevation
X Axis Title(PF)=Main Channel Distance
X Axis Title(XS)=Station
BEGIN DESCRIPTION:
UNT041 IN SNOGR
END DESCRIPTION:
DSS Export Rating Curves= 0
DSS Export Rating Curve Sorted= 0
DSS Export Volume Flow Curves= 0
DXF OffsetX= 0
DXF OffsetY= 0
DXF ScaleX= 1
DXF ScaleY= 10

--- UNT041 IN SNOGR.p01 (plan) ---

Plan Title=Multiple Run
Short Identifier=Multiple
Geom File=g01
Flow File=f01
Subcritical Flow
K Sum by GR= 0
Std Step Tol= 0.01
Critical Tol= 0.01
Num of Std Step Trials= 20
Max Error Tol= 0.3
Flow Tol Ratio= 0.001
Split Flow NTrial= 30
Split Flow Tol= 0.02
Split Flow Ratio= 0.02
Log Output Level= 0
Friction Slope Method= 1
Unsteady Friction Slope Method= 2
Unsteady Bridges Friction Slope Method= 1
Parabolic Critical Depth
Global Vel Dist=  1 , 1 , 1
Global Log Level= 0
CheckData=True
Encroach Param= -1, 0, 0, 0
BEGIN DESCRIPTION:
Multiple Run
END DESCRIPTION:

--- UNT041 IN SNOGR.f01 (steady flow) ---

Flow Title=Multiple
Program Version=4.10
Number of Profiles= 7
Profile Names=10-year,25-year,50-year,1pct_min,100-year,1pct_plu,500-year
River Rch & RM=UNT041 IN SNOGR,Reach-1         ,991
     801    1158    1468    1363    1844    2494    2918
Boundary for River Rch & Prof#=UNT041 IN SNOGR,Reach-1         , 1
Up Type= 0
Dn Type= 3
Dn Slope=0.02
Boundary for River Rch & Prof#=UNT041 IN SNOGR,Reach-1         , 2
Up Type= 0
Dn Type= 3
Dn Slope=0.02
Boundary for River Rch & Prof#=UNT041 IN SNOGR,Reach-1         , 3
Up Type= 0
Dn Type= 3
Dn Slope=0.02
Boundary for River Rch & Prof#=UNT041 IN SNOGR,Reach-1         , 4
Up Type= 0
Dn Type= 3
Dn Slope=0.02
Boundary for River Rch & Prof#=UNT041 IN SNOGR,Reach-1         , 5
Up Type= 0
Dn Type= 3
Dn Slope=0.02
Boundary for River Rch & Prof#=UNT041 IN SNOGR,Reach-1         , 6
Up Type= 0
Dn Type= 3
Dn Slope=0.02
Boundary for River Rch & Prof#=UNT041 IN SNOGR,Reach-1         , 7
Up Type= 0
Dn Type= 3
Dn Slope=0.02
DSS Import GetInterval= 0
DSS Import GetPeak= 0
DSS Import FillOption= 0

--- UNT041 IN SNOGR.g01 (geometry) ---

Geom Title=Existing Conditions
Program Version=4.10

River Reach=UNT041 IN SNOGR ,Reach-1
Reach XY= 30
      2811336.04     10021289.32      2811323.09     10021300.84
      2811303.88     10021331.03      2811293.66     10021376.48
       2811268.1     10021428.29      2811256.69     10021440.75
       2811226.1     10021458.97      2811213.57     10021471.27
      2811200.34     10021494.43       2811182.2     10021540.75
      2811167.63     10021562.69      2811119.82     10021586.73
      2811071.53     10021619.76       2810989.6     10021656.26
      2810928.27      10021723.1      2810871.28     10021749.55
      2810854.49     10021753.28      2810832.54      10021753.1
      2810782.48     10021735.59      2810754.29     10021735.38
      2810729.48     10021745.88      2810653.16     10021793.94
      2810637.39     10021799.99      2810625.11     10021799.07
      2810605.81     10021789.45      2810593.47     10021776.87
      2810565.78      10021714.9       2810530.9     10021667.42
       2810512.1     10021649.32      2810488.47     10021633.73

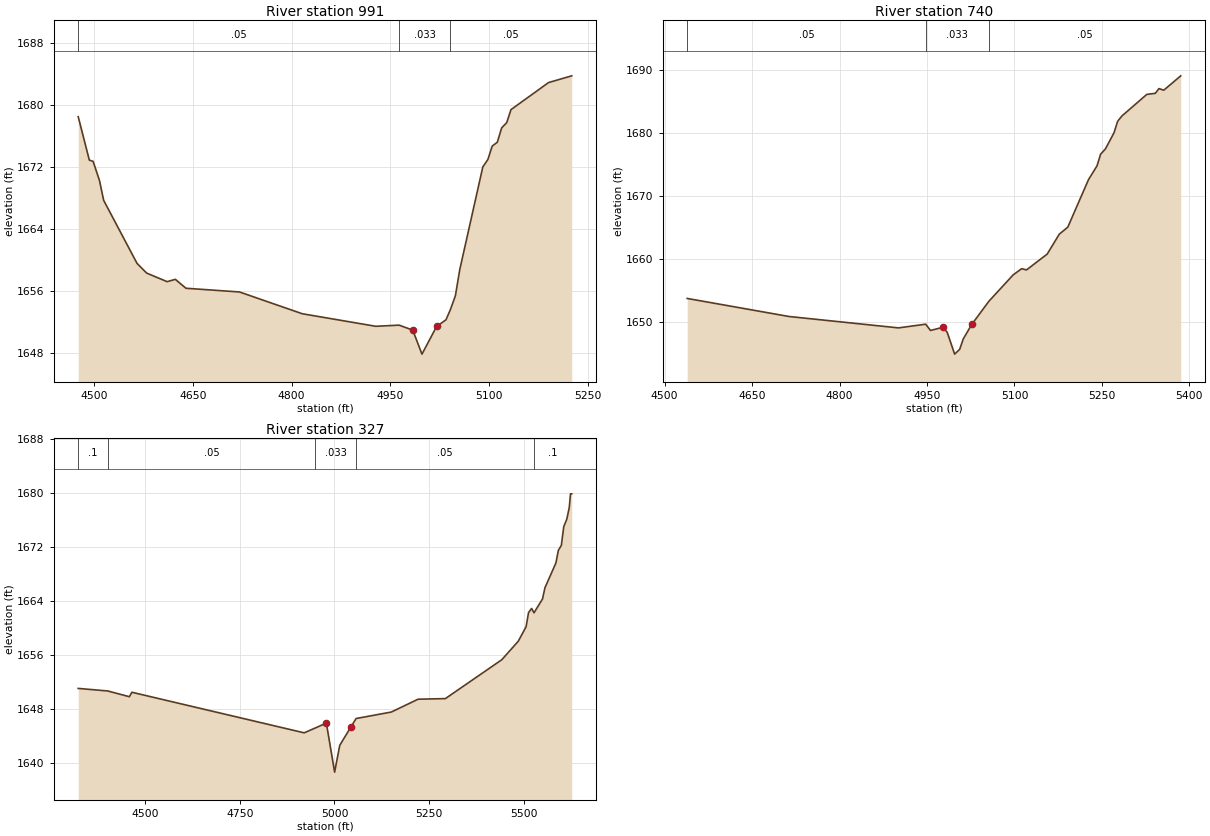
Type RM Length L Ch R = 1 ,991     ,251,251,251
BEGIN DESCRIPTION:
UNIT041 IN SNOGR 1.0
END DESCRIPTION:
XS GIS Cut Line= 5
      2811566.79     10021129.79      2811258.03     10021299.69
      2811220.05     10021366.96      2811209.71     10021401.25
      2811394.47     10021617.61
#Sta/Elev= 30
  4475.6 1678.55  4492.5 1672.94  4498.2 1672.79  4507.9 1670.32  4514.3 1667.75
    4565 1659.62  4579.6 1658.37  4610.7 1657.26  4623.2 1657.56  4639.3 1656.41
  4720.7 1655.93  4816.1 1653.12    4928  1651.5  4963.2 1651.65    4984 1651.01
    4998 1647.91  5020.3 1651.48  5034.5 1652.34  5041.1 1653.63  5048.8 1655.44
  5055.4  1658.8  5090.5 1672.07  5098.2 1673.03  5104.8 1674.76  5112.5 1675.25
  5119.1  1677.1  5126.8 1677.78  5133.3 1679.46  5190.4 1682.95  5225.6 1683.82
#Mann= 3 ,-1 , 0
  4475.6     .05       0  4963.2    .033       0  5041.1     .05       0
Bank Sta=4984,5020.3
XS Rating Curve= 0 ,0
Exp/Cntr=0.3,0.1

Type RM Length L Ch R = 1 ,740     ,413,413,413
BEGIN DESCRIPTION:
UNIT041 IN SNOGR 2.0
END DESCRIPTION:
XS GIS Cut Line= 5
      2811270.31     10021248.51      2811175.62     10021361.32
      2811075.17     10021510.32      2811035.32     10021558.79
      2811308.88     10021924.59
#Sta/Elev= 30
  4538.7 1653.73  4713.4 1650.86  4901.2 1649.05  4947.7 1649.64    4956 1648.64
  4976.9 1649.14  4984.5 1648.38  4997.4 1644.88    5006 1645.64  5012.3 1647.32
  5026.9 1649.62  5056.1 1653.28  5097.7 1657.47  5112.3 1658.46  5120.7 1658.27
  5156.1 1660.78  5176.9 1663.95  5191.5 1665.07    5227 1672.62  5241.6 1674.81
  5247.8 1676.67  5256.1 1677.51  5270.7 1680.06    5277 1681.89  5284.2 1682.73
    5327 1686.17  5341.6 1686.34  5347.8 1687.09  5356.2 1686.84  5385.2 1689.12
#Mann= 3 ,-1 , 0
  4538.7     .05       0  4947.7    .033       0  5056.1     .05       0
Bank Sta=4976.9,5026.9
XS Rating Curve= 0 ,0
Exp/Cntr=0.3,0.1

Type RM Length L Ch R = 1 ,327     ,0,0,0
BEGIN DESCRIPTION:
UNIT041 IN SNOGR 3.0
END DESCRIPTION:
XS GIS Cut Line= 5
      2811143.45     10021378.76      2810946.61     10021610.02
      2810783.85     10021688.14      2810669.96     10021691.92
      2811107.47     10022244.01
#Sta/Elev= 30
  4323.6 1651.03  4401.5 1650.65  4458.7  1649.8  4465.2 1650.46    4920 1644.45
  4949.8 1645.18  4978.6 1645.89  5000.4 1638.63  5013.9  1642.6  5042.7 1645.26
  5057.1 1646.57  5150.1 1647.53  5220.6 1649.43  5292.7 1649.52  5441.7 1655.28
    5485 1658.01  5505.8 1660.17  5512.2 1662.26  5520.3 1662.87  5526.7 1662.23
  5549.1 1664.28  5555.5 1665.94  5584.4  1669.6  5590.8 1671.46  5598.8 1672.22
  5605.2    1675  5613.1 1676.08  5619.6 1677.78    5623 1679.85  5626.2 1679.85
#Mann= 5 ,-1 , 0
  4323.6      .1       0  4401.5     .05       0  4949.8    .033       0
  5057.1     .05       0  5526.7      .1       0
Bank Sta=4978.6,5042.7
XS Rating Curve= 0 ,0
Exp/Cntr=0.3,0.1

Chan Stop Cuts=-1
Use User Specified Reach Order=0
Composite Channel Slope=5