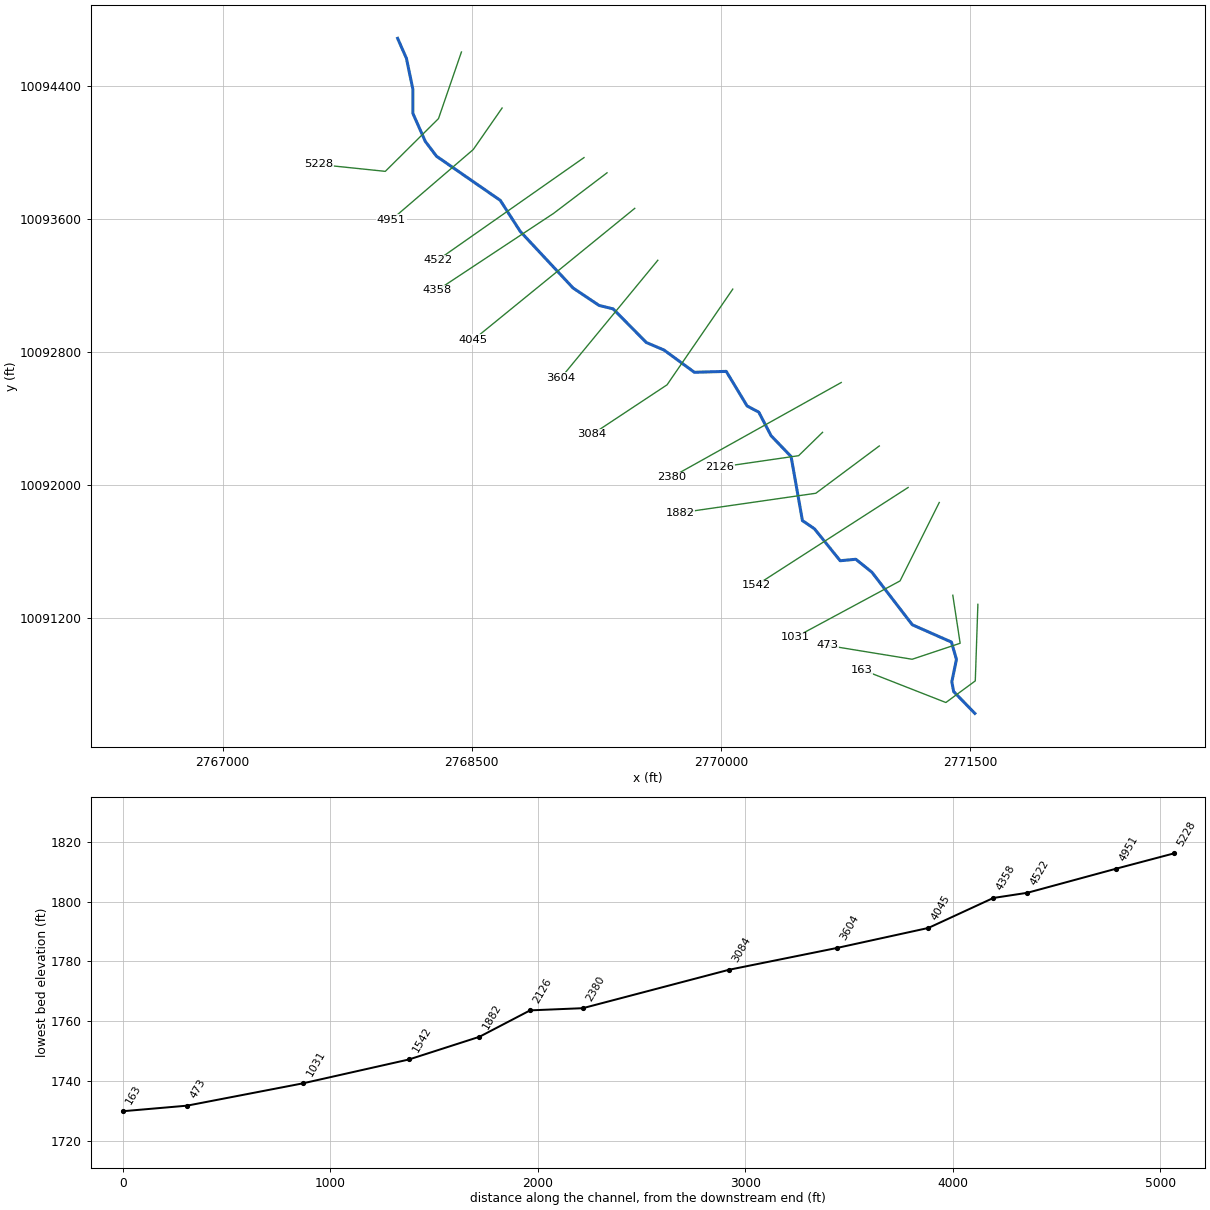
--- UNT042 IN NNOGR.prj (project) ---

Proj Title=UNT042 IN NNOGR Base Level Engineering
Current Plan=p01
Default Exp/Contr=0.3,0.1
English Units
Geom File=g01
Flow File=f01
Plan File=p01
Y Axis Title=Elevation
X Axis Title(PF)=Main Channel Distance
X Axis Title(XS)=Station
BEGIN DESCRIPTION:
UNT042 IN NNOGR
END DESCRIPTION:
DSS Export Rating Curves= 0
DSS Export Rating Curve Sorted= 0
DSS Export Volume Flow Curves= 0
DXF OffsetX= 0
DXF OffsetY= 0
DXF ScaleX= 1
DXF ScaleY= 10

--- UNT042 IN NNOGR.p01 (plan) ---

Plan Title=Multiple Run
Short Identifier=Multiple
Geom File=g01
Flow File=f01
Subcritical Flow
K Sum by GR= 0
Std Step Tol= 0.01
Critical Tol= 0.01
Num of Std Step Trials= 20
Max Error Tol= 0.3
Flow Tol Ratio= 0.001
Split Flow NTrial= 30
Split Flow Tol= 0.02
Split Flow Ratio= 0.02
Log Output Level= 0
Friction Slope Method= 1
Unsteady Friction Slope Method= 2
Unsteady Bridges Friction Slope Method= 1
Parabolic Critical Depth
Global Vel Dist=  1 , 1 , 1
Global Log Level= 0
CheckData=True
Encroach Param= -1, 0, 0, 0
BEGIN DESCRIPTION:
Multiple Run
END DESCRIPTION:

--- UNT042 IN NNOGR.f01 (steady flow) ---

Flow Title=Multiple
Program Version=4.10
Number of Profiles= 7
Profile Names=10-year,25-year,50-year,1pct_min,100-year,1pct_plu,500-year
River Rch & RM=UNT042 IN NNOGR,Reach-1         ,5228
     537     761     952     874    1182    1598    1826
Boundary for River Rch & Prof#=UNT042 IN NNOGR,Reach-1         , 1
Up Type= 0
Dn Type= 3
Dn Slope=0.0148
Boundary for River Rch & Prof#=UNT042 IN NNOGR,Reach-1         , 2
Up Type= 0
Dn Type= 3
Dn Slope=0.0148
Boundary for River Rch & Prof#=UNT042 IN NNOGR,Reach-1         , 3
Up Type= 0
Dn Type= 3
Dn Slope=0.0148
Boundary for River Rch & Prof#=UNT042 IN NNOGR,Reach-1         , 4
Up Type= 0
Dn Type= 3
Dn Slope=0.0148
Boundary for River Rch & Prof#=UNT042 IN NNOGR,Reach-1         , 5
Up Type= 0
Dn Type= 3
Dn Slope=0.0148
Boundary for River Rch & Prof#=UNT042 IN NNOGR,Reach-1         , 6
Up Type= 0
Dn Type= 3
Dn Slope=0.0148
Boundary for River Rch & Prof#=UNT042 IN NNOGR,Reach-1         , 7
Up Type= 0
Dn Type= 3
Dn Slope=0.0148
DSS Import GetInterval= 0
DSS Import GetPeak= 0
DSS Import FillOption= 0

--- UNT042 IN NNOGR.g01 (geometry) ---

Geom Title=Existing Conditions
Program Version=4.10

River Reach=UNT042 IN NNOGR ,Reach-1
Reach XY= 30
      2768053.21     10094687.91      2768106.15      10094567.8
      2768144.95     10094382.46      2768144.95     10094236.62
      2768219.95     10094067.35       2768287.3     10093978.16
      2768671.21     10093712.45      2768791.82     10093525.17
      2769109.46     10093184.85       2769266.1     10093079.82
      2769350.95     10093058.97      2769550.37     10092856.69
      2769657.36     10092811.18      2769840.03     10092677.29
      2770031.75     10092682.72       2770157.4      10092474.6
      2770227.89     10092437.11      2770301.49     10092295.76
      2770422.15     10092170.01      2770490.48     10091784.53
      2770562.91     10091734.93      2770717.73     10091542.74
      2770811.93     10091551.57      2770908.63     10091473.81
      2771151.92     10091157.24      2771387.64     10091053.02
      2771417.78     10090948.53      2771389.84     10090813.33
      2771401.17     10090754.91      2771528.47     10090623.73

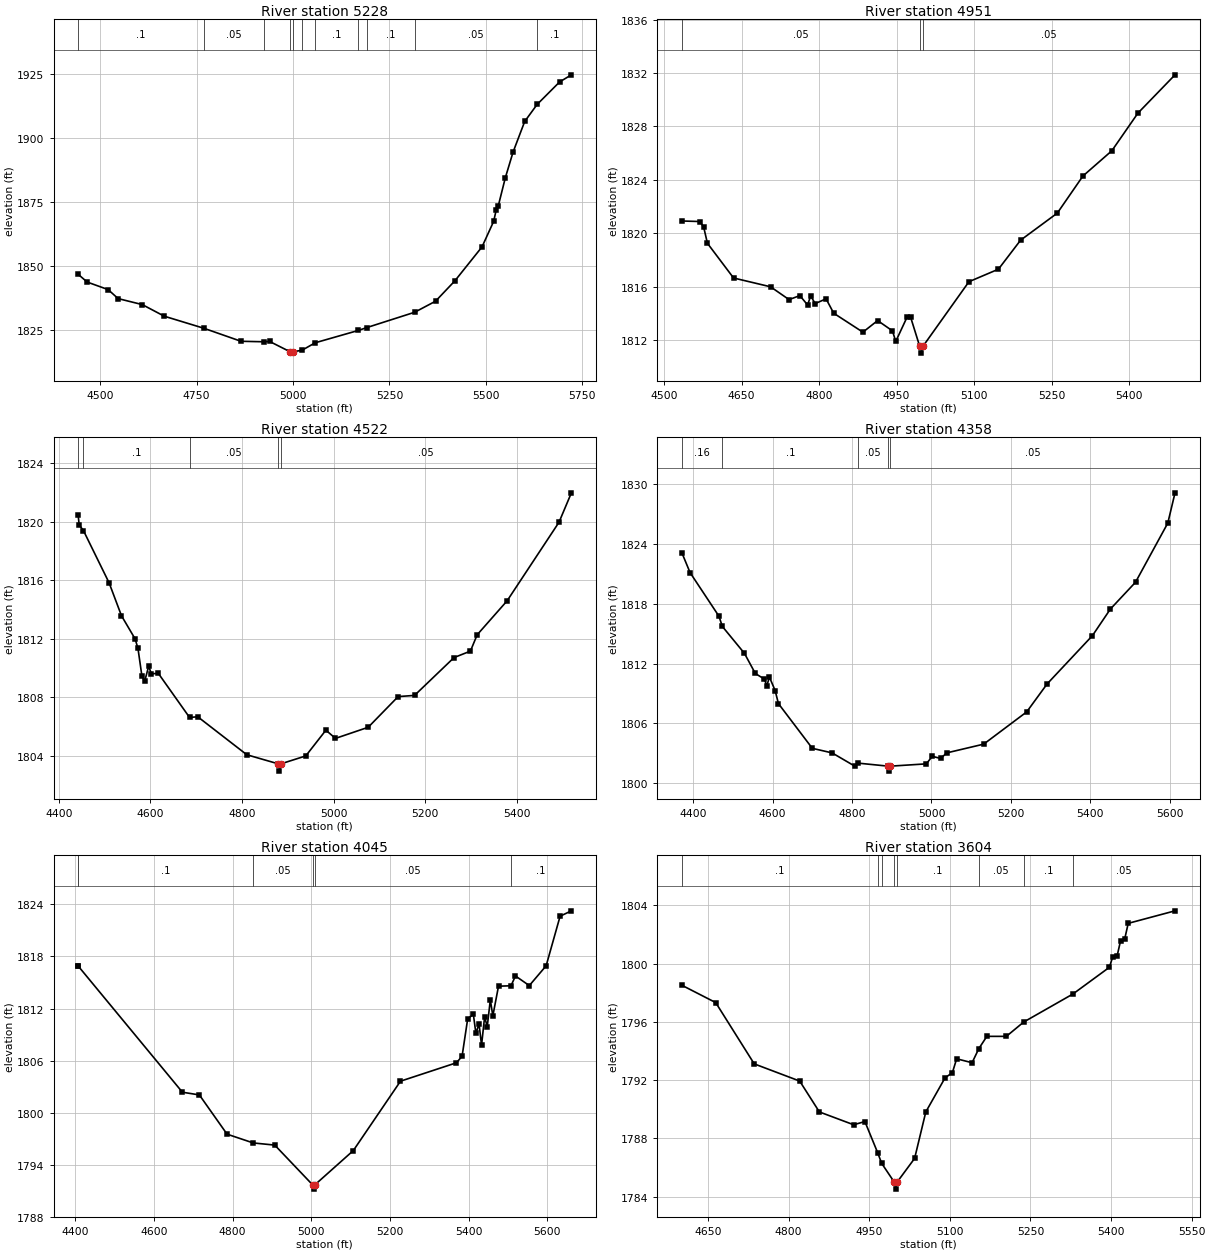
Type RM Length L Ch R = 1 ,5228    ,277,277,277
BEGIN DESCRIPTION:
UNT042 IN NNOGR 12.0
END DESCRIPTION:
XS GIS Cut Line= 4
      2768437.44     10094605.75      2768299.44     10094204.76
      2767979.13     10093887.05      2767578.12     10093928.71
#Sta/Elev= 30
  4443.3 1846.82  4466.6  1843.8  4520.9 1840.86  4546.8 1837.35  4609.3 1835.02
  4666.4 1830.49  4769.1 1825.78  4865.3 1820.71  4924.4 1820.52  4939.5 1820.64
    4993 1816.59  4995.8 1816.09    4999 1816.59  5023.4 1817.21  5057.7 1820.13
  5169.5 1824.94  5190.9 1826.03  5315.5 1832.03  5369.5 1836.33  5419.7 1844.28
  5490.1 1857.53  5520.3  1867.5  5526.8 1871.92  5531.9 1873.33  5550.4 1884.44
  5570.5 1894.48  5600.7 1906.43  5632.9 1913.07  5691.2 1921.84  5721.7 1924.61
#Mann= 11 ,-1 , 0
  4443.3      .1       0  4769.1     .05       0  4924.4      .1       0
    4993     .07       0    4999      .1       0  5023.4     .05       0
  5057.7      .1       0  5169.5     .05       0  5190.9      .1       0
  5315.5     .05       0  5632.9      .1       0
Bank Sta=4993,4999
XS Rating Curve= 0 ,0
Exp/Cntr=0.3,0.1

Type RM Length L Ch R = 1 ,4951    ,429,429,429
BEGIN DESCRIPTION:
UNT042 IN NNOGR 11.0
END DESCRIPTION:
XS GIS Cut Line= 3
      2768682.33     10094268.43      2768508.73     10094018.46
      2768015.66     10093594.83
#Sta/Elev= 30
  4534.4 1820.91    4569 1820.87  4576.6 1820.47  4583.9 1819.24  4634.5 1816.64
  4706.1 1815.98  4741.9 1815.02  4762.8 1815.32  4777.7 1814.62  4783.8 1815.29
  4792.5 1814.72  4813.5 1815.08  4828.3    1814  4884.8 1812.58  4913.3 1813.45
  4941.9 1812.68  4948.4 1811.89  4970.4 1813.72    4977 1813.72  4994.8 1811.51
  4997.6 1811.01  5000.8 1811.51    5090 1816.36  5147.1  1817.3  5189.9 1819.47
    5261  1821.5  5310.6 1824.28  5366.5 1826.17    5417 1828.99  5488.8 1831.86
#Mann= 3 ,-1 , 0
  4534.4     .05       0  4994.8    .035       0  5000.8     .05       0
Bank Sta=4994.8,5000.8
XS Rating Curve= 0 ,0
Exp/Cntr=0.3,0.1

Type RM Length L Ch R = 1 ,4522    ,164,164,164
BEGIN DESCRIPTION:
UNT042 IN NNOGR 10.0
END DESCRIPTION:
XS GIS Cut Line= 2
      2769175.37     10093969.82      2768293.46     10093351.79
#Sta/Elev= 30
  4442.5 1820.43  4444.6 1819.78  4453.9  1819.4    4510 1815.82    4537 1813.57
  4566.7 1811.99    4573 1811.34  4581.5 1809.47  4587.6 1809.08  4596.3 1810.11
  4602.4 1809.59  4617.2 1809.64  4685.7 1806.61  4703.5 1806.66  4810.7 1804.06
  4879.2 1803.44    4882 1802.94  4885.2 1803.44  4939.4 1803.98  4983.3 1805.74
  5004.3 1805.18  5075.7 1805.94  5141.1 1808.04  5176.9 1808.12  5263.2 1810.71
  5298.9 1811.15  5313.7 1812.27    5379 1814.59  5492.4 1819.97  5519.4 1821.98
#Mann= 5 ,-1 , 0
  4442.5     .16       0  4453.9      .1       0  4685.7     .05       0
  4879.2    .035       0  4885.2     .05       0
Bank Sta=4879.2,4885.2
XS Rating Curve= 0 ,0
Exp/Cntr=0.3,0.1

Type RM Length L Ch R = 1 ,4358    ,313,313,313
BEGIN DESCRIPTION:
Mapping XS 7b885810
END DESCRIPTION:
XS GIS Cut Line= 3
      2769313.97     10093878.19      2768991.42     10093633.38
      2768293.41      10093171.9
#Sta/Elev= 30
  4371.5 1823.15  4392.2 1821.15  4464.9 1816.77  4473.5 1815.74  4529.1 1813.04
  4556.5 1811.02  4579.3 1810.45  4585.6 1809.78  4591.9 1810.67  4606.4  1809.3
  4614.7 1807.99    4700  1803.5  4749.9 1803.04  4806.5 1801.72    4816 1802.01
  4890.8 1801.71  4893.5 1801.21  4896.8 1801.71    4987 1801.94  5002.1  1802.7
  5023.2 1802.48  5038.2 1803.04  5131.5 1803.92  5239.8 1807.16    5291 1809.96
  5405.3 1814.82  5450.5 1817.49  5513.7 1820.18    5595 1826.12  5613.2 1829.16
#Mann= 5 ,-1 , 0
  4371.5     .16       0  4473.5      .1       0    4816     .05       0
  4890.8    .035       0  4896.8     .05       0
Bank Sta=4890.8,4896.8
XS Rating Curve= 0 ,0
Exp/Cntr=0.3,0.1

Type RM Length L Ch R = 1 ,4045    ,441,441,441
BEGIN DESCRIPTION:
UNT042 IN NNOGR 9.0
END DESCRIPTION:
XS GIS Cut Line= 2
      2769480.96     10093664.29      2768508.72     10092872.61
#Sta/Elev= 30
  4407.7 1816.88  4407.9 1816.88  4672.6 1802.36  4715.7 1802.05  4786.1 1797.53
  4852.6 1796.52  4907.4 1796.27  5003.5  1791.7  5006.3  1791.2  5009.5  1791.7
  5107.1 1795.64    5227 1803.63  5369.2 1805.75  5383.6  1806.5  5397.9 1810.83
  5412.3 1811.32  5418.7 1809.16  5426.7 1810.22  5433.1 1807.78    5441 1811.08
  5447.5 1809.88  5455.4 1812.99  5461.8 1811.15  5476.2 1814.57    5508 1814.62
  5519.3 1815.75  5554.5 1814.64  5597.3 1816.92  5632.8 1822.63  5661.5 1823.25
#Mann= 6 ,-1 , 0
  4407.7     .16       0  4407.9      .1       0  4852.6     .05       0
  5003.5    .035       0  5009.5     .05       0    5508      .1       0
Bank Sta=5003.5,5009.5
XS Rating Curve= 0 ,0
Exp/Cntr=0.3,0.1

Type RM Length L Ch R = 1 ,3604    ,520,520,520
BEGIN DESCRIPTION:
UNT042 IN NNOGR 8.0
END DESCRIPTION:
XS GIS Cut Line= 2
      2769619.83     10093351.77      2769036.51     10092643.45
#Sta/Elev= 30
  4601.5 1798.51  4664.5 1797.32  4736.2 1793.11  4820.8 1791.93  4857.4 1789.81
  4921.2 1788.93  4942.1 1789.15  4966.3 1786.97  4973.3 1786.28  4996.4 1785.01
  4999.2 1784.51  5002.4 1785.01  5034.6 1786.62  5055.4 1789.81  5091.2 1792.15
  5104.9 1792.51  5112.8 1793.46  5141.5 1793.19  5154.1 1794.16    5169    1795
  5205.3    1795  5237.4 1795.98  5329.2 1797.91  5396.9 1799.74  5403.3 1800.47
  5411.2  1800.5  5417.7 1801.55  5425.5 1801.69    5432 1802.76  5519.1 1803.62
#Mann= 8 ,-1 , 0
  4601.5      .1       0  4966.3     .05       0  4973.3      .1       0
  4996.4     .07       0  5002.4      .1       0  5154.1     .05       0
  5237.4      .1       0  5329.2     .05       0
Bank Sta=4996.4,5002.4
XS Rating Curve= 0 ,0
Exp/Cntr=0.3,0.1

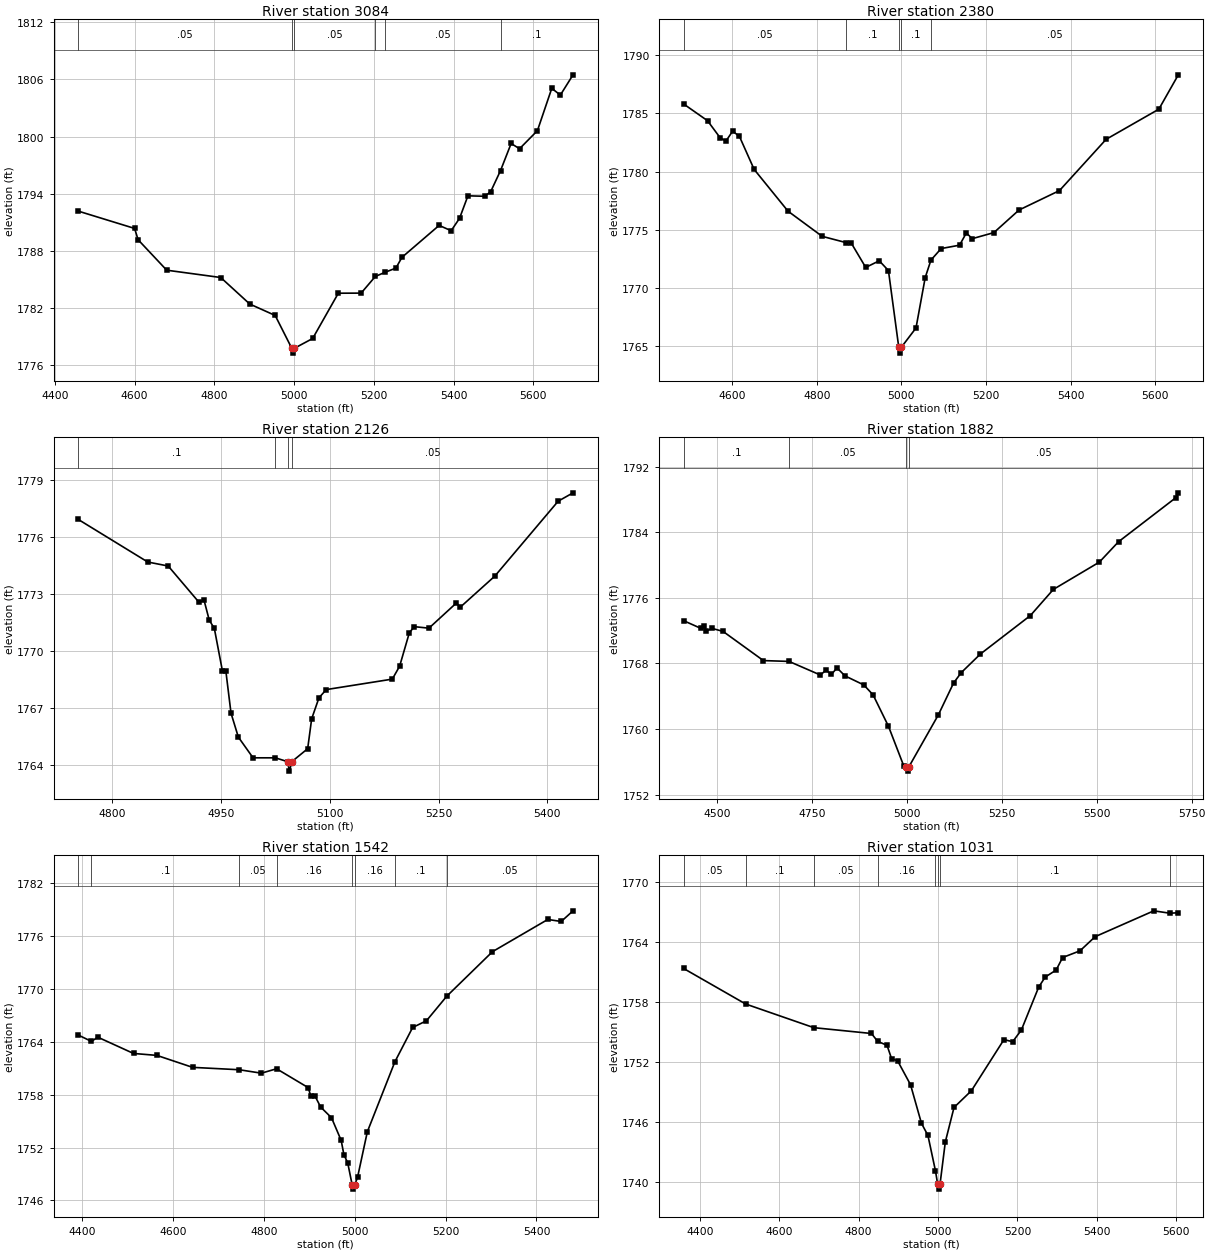
Type RM Length L Ch R = 1 ,3084    ,704,704,704
BEGIN DESCRIPTION:
UNT042 IN NNOGR 7.0
END DESCRIPTION:
XS GIS Cut Line= 3
      2770071.24     10093178.19       2769675.4     10092601.79
      2769223.98     10092303.15
#Sta/Elev= 30
    4459 1792.16  4600.2 1790.34    4609 1789.15  4680.7 1785.95  4816.2 1785.18
    4889 1782.39  4952.7 1781.19  4994.4 1777.73  4997.1 1777.23  5000.4 1777.73
  5046.7 1778.77    5111 1783.53  5168.2 1783.54  5203.8 1785.29  5228.2 1785.73
  5255.4 1786.17  5270.5  1787.3  5363.8 1790.66  5393.9  1790.1  5414.9  1791.4
    5436 1793.77  5478.3 1793.72  5493.1 1794.21  5517.8 1796.43  5544.3 1799.27
  5565.4 1798.72  5610.2 1800.62  5646.2 1805.07  5667.7 1804.36  5699.5 1806.49
#Mann= 6 ,-1 , 0
    4459     .05       0  4994.4    .035       0  5000.4     .05       0
  5203.8      .1       0  5228.2     .05       0  5517.8      .1       0
Bank Sta=4994.4,5000.4
XS Rating Curve= 0 ,0
Exp/Cntr=0.3,0.1

Type RM Length L Ch R = 1 ,2380    ,254,254,254
BEGIN DESCRIPTION:
UNT042 IN NNOGR 5.0
END DESCRIPTION:
XS GIS Cut Line= 2
      2770724.03     10092615.69       2769703.3      10092046.3
#Sta/Elev= 30
  4485.3 1785.81  4541.9 1784.37  4571.8  1782.9  4585.3 1782.62  4601.3 1783.47
  4617.3 1783.02    4652 1780.19  4732.1  1776.6  4812.7 1774.44  4869.3  1773.9
    4881 1773.89  4915.6 1771.77  4947.6 1772.34  4969.3  1771.5  4993.7 1764.91
  4996.5 1764.41  4999.7 1764.91  5034.4 1766.57  5056.1 1770.89  5069.7  1772.4
  5093.8 1773.39  5137.3 1773.68  5153.3 1774.73  5167.3 1774.24  5218.4 1774.76
  5277.8  1776.7  5373.4 1778.37  5483.5 1782.77  5608.1 1785.36  5654.1 1788.31
#Mann= 5 ,-1 , 0
  4485.3     .05       0  4869.3      .1       0  4993.7     .07       0
  4999.7      .1       0  5069.7     .05       0
Bank Sta=4993.7,4999.7
XS Rating Curve= 0 ,0
Exp/Cntr=0.3,0.1

Type RM Length L Ch R = 1 ,2126    ,244,244,244
BEGIN DESCRIPTION:
Mapping XS 062f7299
END DESCRIPTION:
XS GIS Cut Line= 3
      2770611.75     10092315.85      2770467.64      10092175.2
      2769991.82     10092105.99
#Sta/Elev= 30
  4753.3 1776.92  4849.1 1774.68  4877.3 1774.47  4919.8 1772.56  4926.8 1772.66
  4933.9 1771.62  4940.9 1771.19  4952.1 1768.94  4956.8 1768.94  4963.9 1766.73
    4974 1765.47  4994.3 1764.38    5025 1764.38  5041.8 1764.18  5044.5 1763.68
  5047.8 1764.18  5069.6 1764.86  5075.1 1766.43  5085.2 1767.54  5095.3 1767.97
  5186.3 1768.52  5196.4  1769.2  5209.8 1770.96  5216.6 1771.28  5236.8  1771.2
  5274.8 1772.53  5279.9  1772.3  5327.7 1773.94    5415 1777.88  5435.5 1778.32
#Mann= 4 ,-1 , 0
  4753.3      .1       0    5025     .05       0  5041.8     .07       0
  5047.8     .05       0
Bank Sta=5041.8,5047.8
XS Rating Curve= 0 ,0
Exp/Cntr=0.3,0.1

Type RM Length L Ch R = 1 ,1882    ,340,340,340
BEGIN DESCRIPTION:
UNT042 IN NNOGR 4.0
END DESCRIPTION:
XS GIS Cut Line= 3
      2770953.14      10092233.7      2770571.23     10091949.01
      2769752.63     10091831.08
#Sta/Elev= 30
  4411.5 1773.21  4457.1 1772.27  4465.5 1772.53  4471.7 1771.94  4486.3 1772.27
  4515.5  1771.9  4621.9 1768.34  4689.4 1768.24    4772 1766.58  4786.6 1767.17
  4801.2 1766.67  4815.8 1767.45  4836.6 1766.48  4886.4 1765.37  4910.8 1764.16
  4951.3 1760.33  4991.7 1755.48  4998.8 1755.36  5001.5 1754.86  5004.8 1755.36
  5082.6 1761.71    5123 1765.62  5143.2 1766.88  5193.7 1769.15  5325.1 1773.83
  5385.7 1777.02  5506.9 1780.35  5557.5 1782.84    5709 1788.23  5714.9  1788.8
#Mann= 4 ,-1 , 0
  4411.5      .1       0  4689.4     .05       0  4998.8    .035       0
  5004.8     .05       0
Bank Sta=4998.8,5004.8
XS Rating Curve= 0 ,0
Exp/Cntr=0.3,0.1

Type RM Length L Ch R = 1 ,1542    ,511,511,511
BEGIN DESCRIPTION:
UNT042 IN NNOGR 3.0
END DESCRIPTION:
XS GIS Cut Line= 2
      2771126.77     10091983.72      2770211.77     10091394.51
#Sta/Elev= 30
  4392.1 1764.78    4421 1764.06    4435 1764.54  4513.6 1762.69    4565 1762.47
  4643.6 1761.11  4746.1 1760.84  4794.8 1760.45  4828.3 1760.95  4897.8 1758.81
  4903.7 1757.84    4913 1757.83  4925.3  1756.6  4949.1 1755.39  4970.4 1752.81
  4976.4 1751.19  4984.8 1750.26  4994.5 1747.78  4997.2 1747.28  5000.5 1747.78
  5006.7 1748.69  5027.9 1753.79  5088.6 1761.75  5127.6 1765.64  5157.9  1766.4
  5202.8  1769.2  5303.2 1774.25  5424.9 1777.91  5454.4 1777.68  5480.4 1778.89
#Mann= 8 ,-1 , 0
  4392.1     .05       0    4421      .1       0  4746.1     .05       0
  4828.3     .16       0  4994.5     .07       0  5000.5     .16       0
  5088.6      .1       0  5202.8     .05       0
Bank Sta=4994.5,5000.5
XS Rating Curve= 0 ,0
Exp/Cntr=0.3,0.1

Type RM Length L Ch R = 1 ,1031    ,558,558,558
BEGIN DESCRIPTION:
UNT042 IN NNOGR 2.0
END DESCRIPTION:
XS GIS Cut Line= 3
      2771314.27     10091893.41      2771078.18     10091421.23
      2770446.28     10091080.98
#Sta/Elev= 30
  4359.3 1761.33  4515.7 1757.78  4687.4 1755.42  4832.4 1754.84  4847.8 1754.06
  4871.5 1753.66    4883 1752.33  4898.2 1752.11  4930.7 1749.73  4958.2 1745.88
  4974.5 1744.67  4993.5 1741.13    4999 1739.81  5001.8 1739.31    5005 1739.81
  5018.3 1744.02  5040.2 1747.46    5084 1749.13  5165.9 1754.23  5187.8 1754.02
  5209.7 1755.18  5253.5 1759.48  5269.8 1760.47  5297.3 1761.17  5313.6 1762.42
  5357.4 1763.09  5395.5  1764.5  5543.2 1767.08  5583.8 1766.84  5604.9 1766.89
#Mann= 8 ,-1 , 0
  4359.3     .05       0  4515.7      .1       0  4687.4     .05       0
  4847.8     .16       0  4993.5      .1       0    4999     .07       0
    5005      .1       0  5583.8     .05       0
Bank Sta=4999,5005
XS Rating Curve= 0 ,0
Exp/Cntr=0.3,0.1

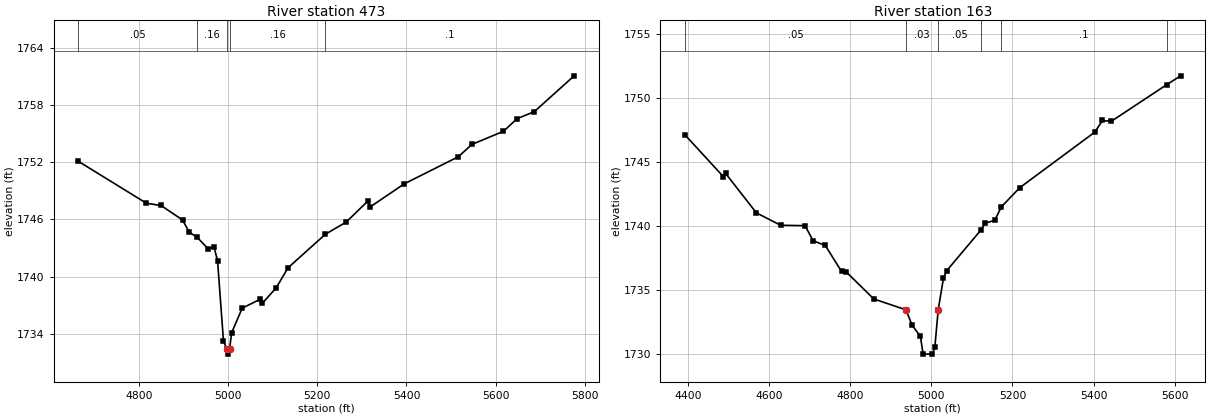
Type RM Length L Ch R = 1 ,473     ,310,310,310
BEGIN DESCRIPTION:
Mapping XS 924166c3
END DESCRIPTION:
XS GIS Cut Line= 4
      2771395.79     10091334.97      2771440.06      10091045.9
        2771151.     10090949.55      2770641.98     10091032.65
#Sta/Elev= 30
  4663.5  1752.1  4816.5 1747.69  4849.1 1747.46  4897.4 1745.94  4912.5 1744.66
  4930.5 1744.11  4954.5 1742.93  4968.2 1743.09    4976 1741.65  4989.2 1733.29
  4996.8 1732.36  4999.5 1731.86  5002.8 1732.36  5007.6 1734.11  5031.4 1736.69
  5070.9  1737.6  5076.2 1737.18  5107.8 1738.83  5134.1 1740.92  5218.2 1744.45
  5264.5 1745.71  5313.2 1747.92  5318.3  1747.3  5394.9 1749.73  5516.5 1752.58
  5546.9 1753.87  5617.8 1755.25  5648.2 1756.57  5686.9 1757.31  5776.4 1761.07
#Mann= 5 ,-1 , 0
  4663.5     .05       0  4930.5     .16       0  4996.8     .07       0
  5002.8     .16       0  5218.2      .1       0
Bank Sta=4996.8,5002.8
XS Rating Curve= 0 ,0
Exp/Cntr=0.3,0.1

Type RM Length L Ch R = 1 ,163     ,0,0,0
BEGIN DESCRIPTION:
UNT042 IN NNOGR 1.0
END DESCRIPTION:
XS GIS Cut Line= 4
      2771546.83     10091280.29      2771531.21     10090819.34
      2771354.13     10090689.13      2770848.93     10090887.04
#Sta/Elev= 30
  4391.4 1747.15  4486.9 1743.86  4491.9 1744.13  4568.1 1741.04  4628.1 1740.07
  4688.1 1740.04  4708.1 1738.86  4738.2 1738.49  4778.2 1736.46  4789.6 1736.43
  4857.9 1734.31  4937.4 1733.46    4952 1732.28  4972.9 1731.38 4979.53    1730
  5002.4 1730.01  5008.4 1730.53  5016.8 1733.47  5029.8 1735.95  5037.7 1736.52
  5123.1 1739.73  5132.2 1740.23  5156.3 1740.46  5172.6 1741.51  5218.1 1743.01
  5403.2 1747.35  5422.2 1748.26  5443.7 1748.19  5581.2 1751.07    5615 1751.75
#Mann= 6 ,-1 , 0
  4391.4     .05       0  4937.4     .03       0  5016.8     .05       0
  5123.1     .16       0  5172.6      .1       0  5581.2     .12       0
Bank Sta=4937.4,5016.8
XS Rating Curve= 0 ,0
Exp/Cntr=0.3,0.1

Chan Stop Cuts=-1
Use User Specified Reach Order=0
Composite Channel Slope=5