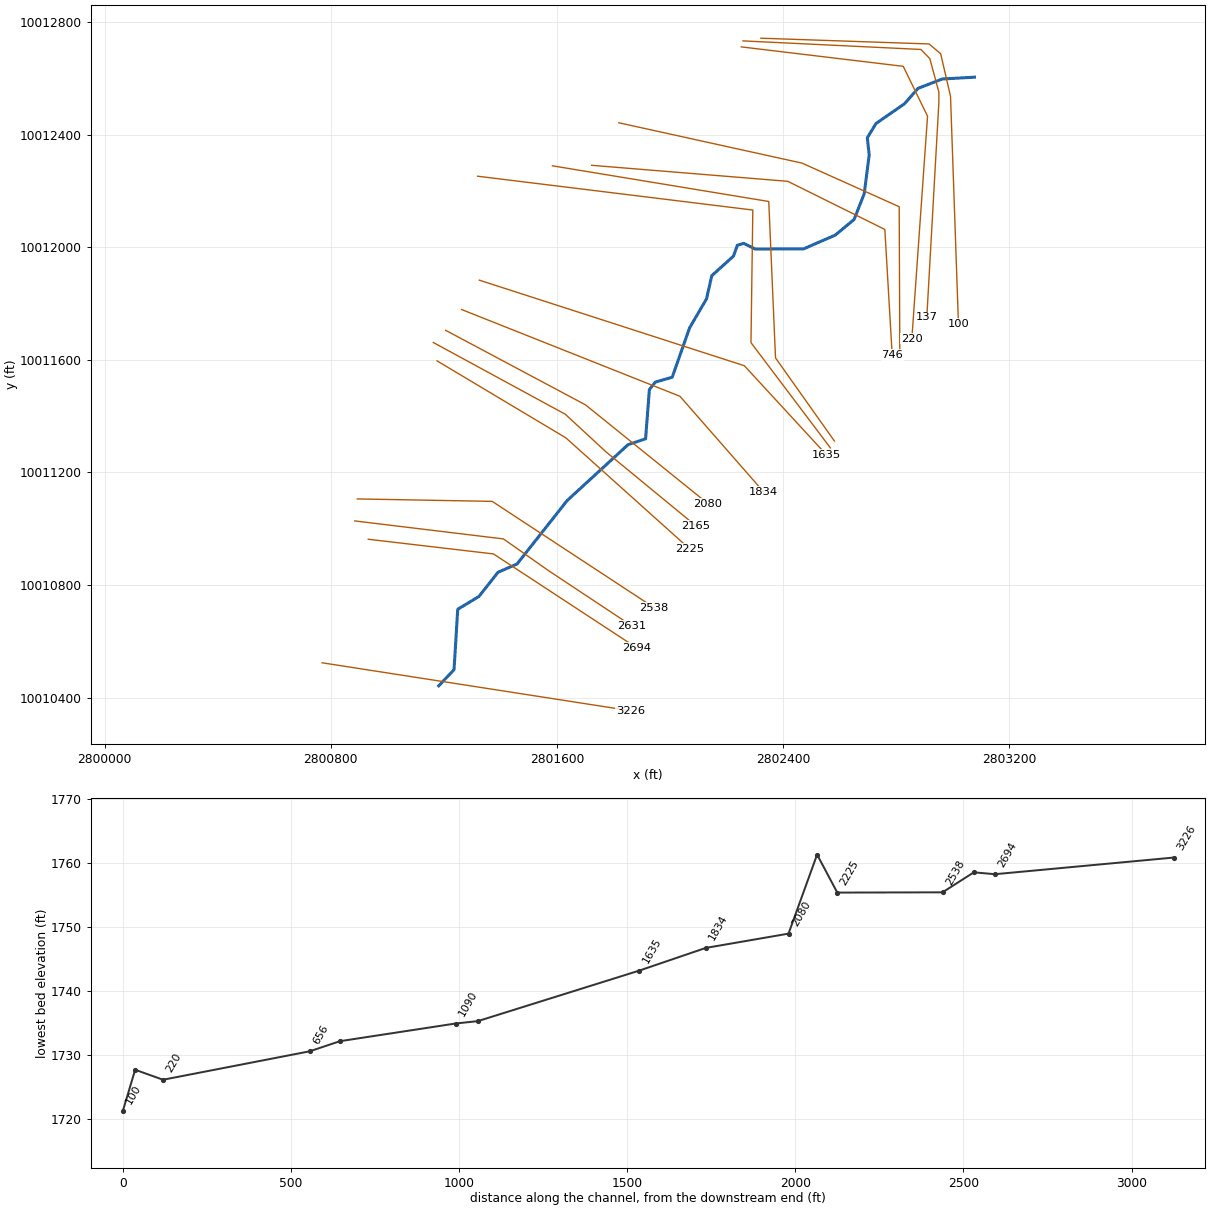
--- UNT042 IN SNOGR.prj (project) ---

Proj Title=UNT042 IN SNOGR Base Level Engineering
Current Plan=p01
Default Exp/Contr=0.3,0.1
English Units
Geom File=g01
Flow File=f01
Plan File=p01
Y Axis Title=Elevation
X Axis Title(PF)=Main Channel Distance
X Axis Title(XS)=Station
BEGIN DESCRIPTION:
UNT042 IN SNOGR
END DESCRIPTION:
DSS Export Rating Curves= 0
DSS Export Rating Curve Sorted= 0
DSS Export Volume Flow Curves= 0
DXF OffsetX= 0
DXF OffsetY= 0
DXF ScaleX= 1
DXF ScaleY= 10

--- UNT042 IN SNOGR.p01 (plan) ---

Plan Title=Multiple Run
Short Identifier=Multiple
Geom File=g01
Flow File=f01
Subcritical Flow
K Sum by GR= 0
Std Step Tol= 0.01
Critical Tol= 0.01
Num of Std Step Trials= 20
Max Error Tol= 0.3
Flow Tol Ratio= 0.001
Split Flow NTrial= 30
Split Flow Tol= 0.02
Split Flow Ratio= 0.02
Log Output Level= 0
Friction Slope Method= 1
Unsteady Friction Slope Method= 2
Unsteady Bridges Friction Slope Method= 1
Parabolic Critical Depth
Global Vel Dist=  1 , 1 , 1
Global Log Level= 0
CheckData=True
Encroach Param= -1, 0, 0, 0
BEGIN DESCRIPTION:
Multiple Run
END DESCRIPTION:

--- UNT042 IN SNOGR.f01 (steady flow) ---

Flow Title=Multiple
Number of Profiles=7
Profile Names=10-year,25-year,50-year,1pct_min,100-year,1pct_plu,500-year
River Rch & RM= UNT042 IN SNOGR,Reach-1,3226
     865    1252    1587    1473    1993    2695    3152
River Rch & RM= UNT042 IN SNOGR,Reach-1,2225
     982    1430    1821    1697    2296    3104    3660
Boundary for River Rch & Prof#=UNT042 IN SNOGR,Reach-1,1
Up Type=0
Dn Type=3
Dn Slope=0.005
Boundary for River Rch & Prof#=UNT042 IN SNOGR,Reach-1,2
Up Type=0
Dn Type=3
Dn Slope=0.005
Boundary for River Rch & Prof#=UNT042 IN SNOGR,Reach-1,3
Up Type=0
Dn Type=3
Dn Slope=0.005
Boundary for River Rch & Prof#=UNT042 IN SNOGR,Reach-1,4
Up Type=0
Dn Type=3
Dn Slope=0.005
Boundary for River Rch & Prof#=UNT042 IN SNOGR,Reach-1,5
Up Type=0
Dn Type=3
Dn Slope=0.005
Boundary for River Rch & Prof#=UNT042 IN SNOGR,Reach-1,6
Up Type=0
Dn Type=3
Dn Slope=0.005
Boundary for River Rch & Prof#=UNT042 IN SNOGR,Reach-1,7
Up Type=0
Dn Type=3
Dn Slope=0.005

--- UNT042 IN SNOGR.g01 (geometry) ---

Geom Title=Existing Conditions
Program Version=4.10

River Reach=UNT042 IN SNOGR ,Reach-1
Reach XY= 30
      2801181.97     10010441.99       2801236.3     10010499.55
      2801249.38     10010713.97      2801324.33     10010759.58
      2801391.87     10010845.48      2801459.23     10010874.94
      2801636.38     10011100.13      2801851.61     10011298.48
      2801913.86     10011319.55      2801927.37     10011494.73
       2801948.4     10011521.03      2802008.06     10011538.19
      2802069.48     10011713.31      2802129.31     10011816.27
      2802148.11      10011898.8      2802224.88     10011968.48
      2802238.48     10012006.67      2802260.79     10012013.71
      2802302.19     10011993.38      2802473.12     10011994.21
      2802585.06     10012043.09      2802651.59     10012098.59
      2802687.46      10012190.7      2802704.89     10012328.28
       2802698.2     10012388.66      2802728.98     10012439.36
      2802829.71     10012509.34      2802877.49     10012564.09
      2802963.55     10012597.43      2803077.27     10012603.79

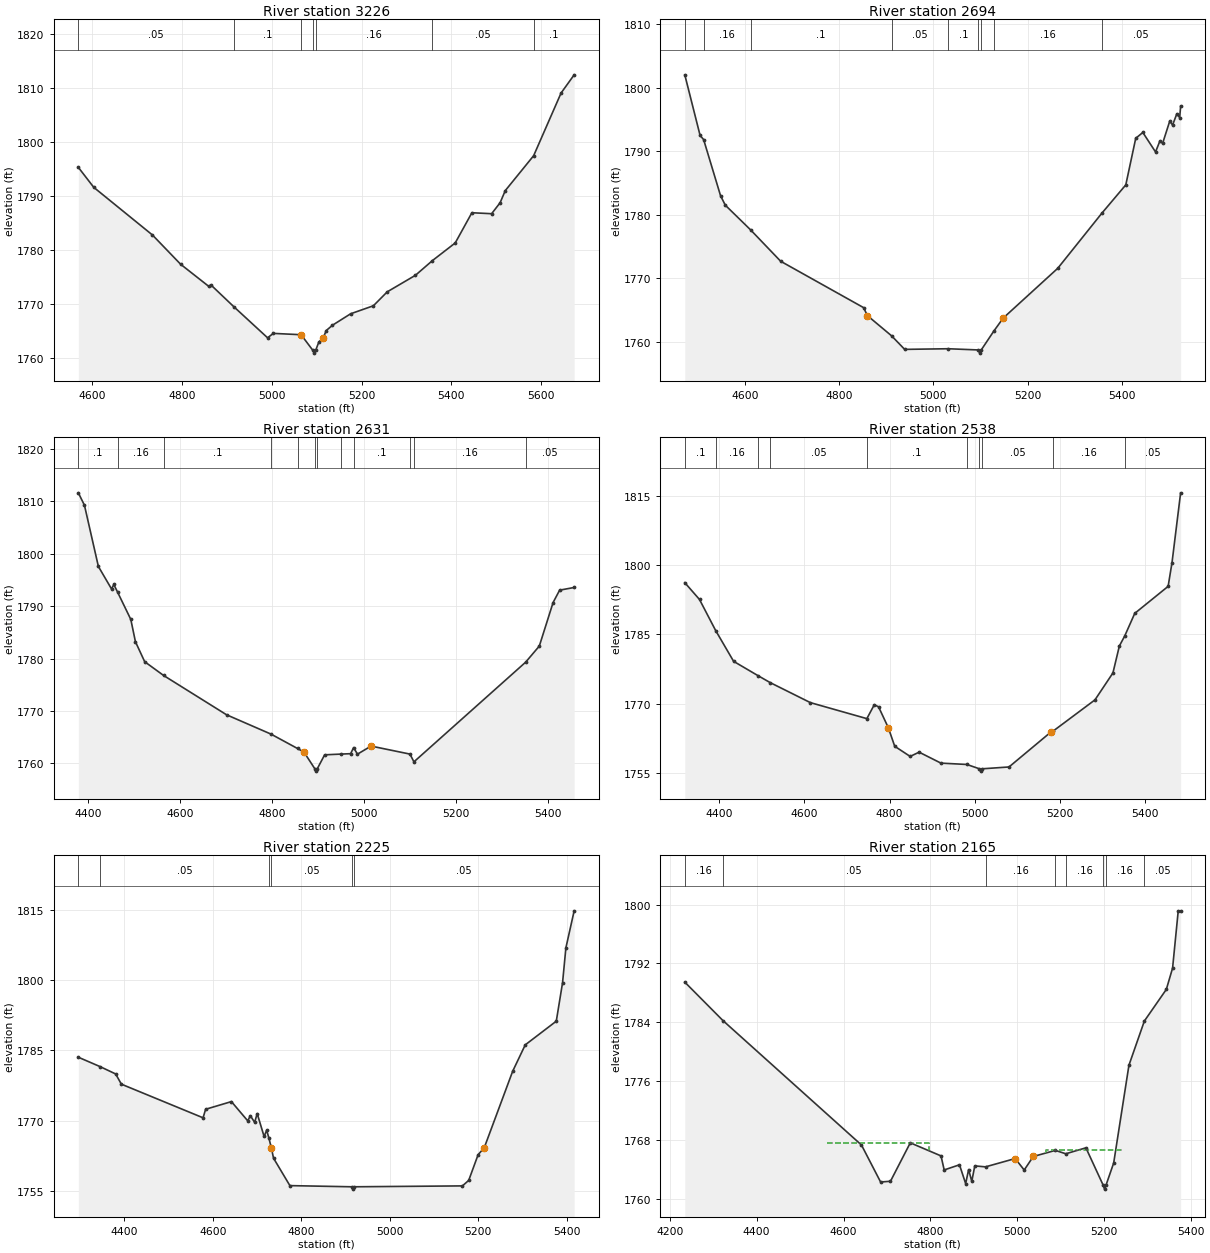
Type RM Length L Ch R = 1 ,3226    ,532,532,532
BEGIN DESCRIPTION:
UNT042 IN SNOGR 16.0
END DESCRIPTION:
XS GIS Cut Line= 2
      2800769.67     10010524.04      2801859.97      10010353.9
#Sta/Elev= 30
  4569.7 1795.27    4604 1791.57  4734.7 1782.73  4797.4 1777.31  4860.2  1773.2
  4865.3 1773.44  4915.4 1769.47  4990.9 1763.68  5003.7  1764.5  5065.5 1764.25
  5091.8 1761.34  5094.5 1760.84  5097.8 1761.34  5104.9 1762.88    5115 1763.73
  5121.5 1765.03  5135.3 1766.01  5175.7 1768.13  5226.4 1769.62  5257.2  1772.2
    5320 1775.27  5357.9    1778  5408.5 1781.26  5445.6 1786.86  5489.5 1786.68
  5508.4 1788.71  5519.9 1790.96  5583.1 1797.44  5644.1 1809.05  5673.2 1812.42
#Mann= 7 ,-1 , 0
  4569.7     .05       0  4915.4      .1       0  5065.5     .16       0
  5091.8     .07       0  5097.8     .16       0  5357.9     .05       0
  5583.1      .1       0
Bank Sta=5065.5,5115
XS Rating Curve= 0 ,0
Exp/Cntr=0.3,0.1

Type RM Length L Ch R = 1 ,2694    ,63,63,63
BEGIN DESCRIPTION:
UNT042 IN SNOGR 15.0
END DESCRIPTION:
XS GIS Cut Line= 3
      2800933.02     10010962.75      2801375.69     10010910.67
      2801883.47     10010576.49
#Sta/Elev= 30
  4471.7 1802.04  4504.2  1792.5  4511.7 1791.85  4547.7 1783.01  4557.7 1781.53
  4611.5 1777.64  4675.4  1772.7  4851.6  1765.4  4859.8 1764.14    4911 1760.97
  4938.9 1758.83  5031.2 1758.93  5095.6 1758.74  5098.3 1758.24  5101.6 1758.74
    5128 1761.67  5148.2 1763.75  5264.2 1771.59  5357.9 1780.26  5408.8 1784.72
  5429.9 1792.05    5445 1792.97    5472  1789.9  5481.1  1791.6  5487.1 1791.27
  5502.2 1794.76  5508.2 1794.13  5517.3 1795.92  5523.3  1795.3  5525.3 1797.09
#Mann= 9 ,-1 , 0
  4471.7      .1       0  4511.7     .16       0  4611.5      .1       0
    4911     .05       0  5031.2      .1       0  5095.6    .035       0
  5101.6      .1       0    5128     .16       0  5357.9     .05       0
Bank Sta=4859.8,5148.2
XS Rating Curve= 0 ,0
Exp/Cntr=0.3,0.1

Type RM Length L Ch R = 1 ,2631    ,93,93,93
BEGIN DESCRIPTION:
UNT042 IN SNOGR 14.0
END DESCRIPTION:
XS GIS Cut Line= 4
      2800885.22     10011027.86      2801411.13     10010963.92
      2801569.55     10010851.94      2801864.78      10010655.5
#Sta/Elev= 30
  4378.3 1811.63  4391.6 1809.26  4421.9 1797.58  4450.5 1793.29  4455.5 1794.14
  4463.9 1792.64  4492.4 1787.48  4502.5 1783.22  4522.6 1779.41  4563.8 1776.78
  4700.7 1769.28  4797.2  1765.6    4855 1762.85  4869.2 1762.15  4892.3 1759.03
  4895.1 1758.53  4898.3 1759.03    4914 1761.64  4949.5 1761.78  4970.6 1761.86
    4977 1763.02  4985.4 1761.77    5015 1763.31  5099.6 1761.78  5108.2  1760.3
  5351.2 1779.32  5380.9 1782.39  5410.9  1790.7  5425.1 1793.06  5456.7 1793.57
#Mann= 12 ,-1 , 0
  4378.3      .1       0  4463.9     .16       0  4563.8      .1       0
  4797.2     .05       0    4855      .1       0  4892.3     .07       0
  4898.3      .1       0  4949.5     .05       0    4977      .1       0
  5099.6     .05       0  5108.2     .16       0  5351.2     .05       0
Bank Sta=4869.2,5015
XS Rating Curve= 0 ,0
Exp/Cntr=0.3,0.1

Type RM Length L Ch R = 1 ,2538    ,313,313,313
BEGIN DESCRIPTION:
UNT042 IN SNOGR 13.0
END DESCRIPTION:
XS GIS Cut Line= 3
      2800893.94     10011105.98      2801371.35      10011097.3
      2801943.89     10010719.94
#Sta/Elev= 30
  4319.6 1796.16  4354.1 1792.52  4392.1 1785.79  4434.1 1779.15  4490.8 1776.08
  4519.9 1774.55  4614.2 1770.22  4746.7 1766.76  4764.2 1769.77  4774.2 1769.31
  4797.1 1764.78  4812.1 1760.78  4848.3 1758.59  4869.3 1759.51  4920.5 1757.14
  4981.3 1756.85  5010.9 1755.91  5013.6 1755.41  5016.9 1755.91  5080.2 1756.31
  5179.5 1763.94  5184.5 1764.12  5281.9 1770.82    5324 1776.64  5339.1 1782.47
  5351.6 1784.62  5375.2 1789.52  5453.5 1795.36  5462.6  1800.5  5482.8 1815.58
#Mann= 10 ,-1 , 0
  4319.6      .1       0  4392.1     .16       0  4490.8      .1       0
  4519.9     .05       0  4746.7      .1       0  4981.3     .05       0
  5010.9    .033       0  5016.9     .05       0  5184.5     .16       0
  5351.6     .05       0
Bank Sta=4797.1,5179.5
XS Rating Curve= 0 ,0
Exp/Cntr=0.3,0.1

Type RM Length L Ch R = 1 ,2225    ,60,60,60
BEGIN DESCRIPTION:
UNT042 IN SNOGR 12.0
END DESCRIPTION:
XS GIS Cut Line= 3
      2801176.06     10011596.42      2801631.77     10011322.99
      2802069.77     10010928.36
#Sta/Elev= 30
    4296 1783.53  4344.9 1781.54  4380.4 1779.96  4393.3 1777.78    4578  1770.6
  4583.8 1772.42  4642.1 1774.06    4679 1769.95  4684.9 1771.05  4694.6 1769.63
  4700.4  1771.5    4716 1766.61  4721.8 1767.94  4726.5 1766.39  4732.6  1764.1
  4737.3 1761.98  4774.3 1756.12    4914 1755.87  4916.7 1755.37    4920 1755.87
  5164.4 1756.06  5178.6 1757.24  5199.9 1762.73  5213.7  1764.2    5278 1780.54
  5306.4 1786.17  5376.6 1791.23  5390.8 1799.46  5398.3 1806.88    5417 1814.79
#Mann= 6 ,-1 , 0
    4296     .16       0  4344.9     .05       0  4726.5      .1       0
  4732.6     .05       0    4914    .033       0    4920     .05       0
Bank Sta=4732.6,5213.7
XS Rating Curve= 0 ,0
Exp/Cntr=0.3,0.1

Type RM Length L Ch R = 1 ,2165    ,85,85,85
BEGIN DESCRIPTION:
UNT042 IN SNOGR 11.0
END DESCRIPTION:
XS GIS Cut Line= 4
      2801163.06     10011661.51      2801629.79      10011406.8
      2801774.01     10011272.98      2802091.94      10011010.4
#Sta/Elev= 30
  4234.8 1789.46  4322.4 1784.24  4641.3  1767.3  4685.3 1762.27    4708 1762.37
  4753.6  1767.6  4824.3 1765.82  4831.6 1763.91  4866.8 1764.61    4881 1762.05
  4887.8 1763.96  4895.1 1762.36    4902 1764.46  4926.7 1764.33  4994.9 1765.46
  5015.7  1763.9  5036.6 1765.74  5087.4 1766.57  5111.4 1766.11  5157.7 1766.92
  5197.7  1761.8  5200.5  1761.3  5203.7  1761.8  5221.6 1764.86  5256.7 1778.16
  5292.2 1784.17  5342.7 1788.47  5357.1 1791.37  5370.1 1799.16  5375.6 1799.16
#Mann= 8 ,-1 , 0
  4234.8     .16       0  4322.4     .05       0  4926.7     .16       0
  5087.4     .05       0  5111.4     .16       0  5197.7     .07       0
  5203.7     .16       0  5292.2     .05       0
#XS Ineff= 2 ,-1
 4562.79 4797.38 1767.55 5065.99 5242.15 1766.66
Permanent Ineff=
       T       T
Bank Sta=4994.9,5036.6
XS Rating Curve= 0 ,0
Exp/Cntr=0.3,0.1

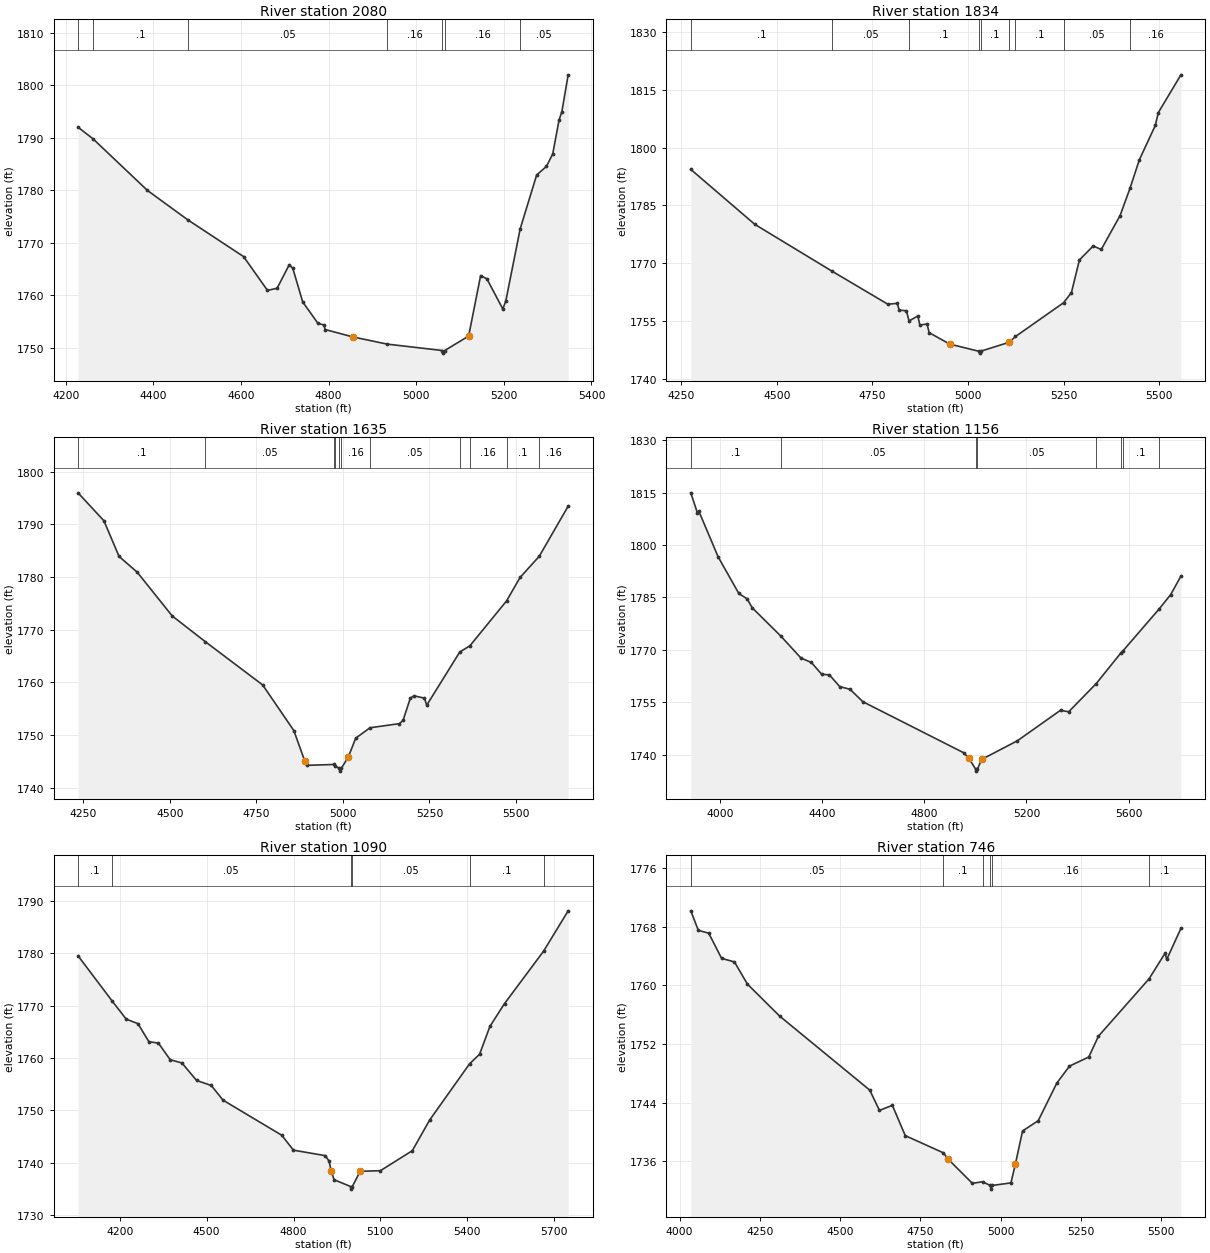
Type RM Length L Ch R = 1 ,2080    ,246,246,246
BEGIN DESCRIPTION:
UNT042 IN SNOGR 10.0
END DESCRIPTION:
XS GIS Cut Line= 3
      2801206.45     10011704.92      2801701.21     10011440.18
      2802134.32     10011089.37
#Sta/Elev= 30
  4228.3 1792.03    4263 1789.77  4386.7 1779.97  4478.9 1774.36  4606.1 1767.36
  4660.6 1760.92  4682.6 1761.33  4710.2  1765.8  4718.3 1765.15    4741 1758.72
    4776 1754.61  4789.4 1754.35    4792 1753.46    4856 1752.04  4933.6 1750.68
  5059.2 1749.46    5062 1748.96  5065.2 1749.46  5119.7 1752.22    5147 1763.72
  5161.3 1763.13  5197.7 1757.37  5204.5 1758.92  5237.3 1772.65  5274.9 1782.92
  5297.2 1784.55  5311.6 1786.94  5325.9 1793.35  5332.4 1794.99  5346.8 1802.01
#Mann= 7 ,-1 , 0
  4228.3     .16       0    4263      .1       0  4478.9     .05       0
  4933.6     .16       0  5059.2     .07       0  5065.2     .16       0
  5237.3     .05       0
Bank Sta=4856,5119.7
XS Rating Curve= 0 ,0
Exp/Cntr=0.3,0.1

Type RM Length L Ch R = 1 ,1834    ,199,199,199
BEGIN DESCRIPTION:
UNT042 IN SNOGR 9.0
END DESCRIPTION:
XS GIS Cut Line= 3
      2801262.86     10011778.72      2802035.41     10011470.56
      2802330.57       10011132.
#Sta/Elev= 30
  4275.4 1794.35  4442.9 1780.09  4644.5 1767.97  4790.5  1759.4  4814.8 1759.63
  4820.2 1757.88    4839 1757.71  4845.8 1755.06  4868.7 1756.36  4874.1 1754.01
  4892.9 1754.29  4898.3 1752.03  4952.2 1749.07  5027.4 1747.23  5030.2 1746.73
  5033.4 1747.23  5106.1  1749.5  5107.6  1749.6    5124 1751.04  5249.8  1759.8
  5270.2 1762.44  5291.1 1770.89  5327.1 1774.51    5348 1773.59  5397.4 1782.39
  5423.5 1789.53  5447.7 1796.84  5489.5 1805.77  5497.1 1809.05  5556.3 1818.86
#Mann= 9 ,-1 , 0
  4275.4      .1       0  4644.5     .05       0  4845.8      .1       0
  5027.4     .07       0  5033.4      .1       0  5107.6     .16       0
    5124      .1       0  5249.8     .05       0  5423.5     .16       0
Bank Sta=4952.2,5106.1
XS Rating Curve= 0 ,0
Exp/Cntr=0.3,0.1

Type RM Length L Ch R = 1 ,1635    ,479,479,479
BEGIN DESCRIPTION:
UNT042 IN SNOGR 8.0
END DESCRIPTION:
XS GIS Cut Line= 3
      2801325.79     10011882.89      2802263.28     10011579.07
      2802553.77     10011262.56
#Sta/Elev= 30
  4235.4 1795.97  4310.1 1790.67  4353.8  1783.9  4406.1 1780.92  4507.3 1772.61
  4602.4 1767.75  4768.5 1759.52  4858.4 1750.87    4890 1745.09  4896.4 1744.27
  4973.2 1744.43  4977.8 1744.21  4989.4 1743.67  4992.1 1743.17  4995.4 1743.67
  5016.1 1745.92  5037.1 1749.42  5078.4  1751.4  5163.3 1752.18  5173.8 1752.81
  5194.8 1757.01  5205.3 1757.46  5235.4 1757.02  5242.2 1755.68  5337.3 1765.75
  5366.9 1766.96  5472.8 1775.48  5511.7 1779.92    5567 1783.93  5650.5 1793.44
#Mann= 11 ,-1 , 0
  4235.4      .1       0  4602.4     .05       0  4973.2      .1       0
  4977.8     .16       0  4989.4     .07       0  4995.4     .16       0
  5078.4     .05       0  5337.3      .1       0  5366.9     .16       0
  5472.8      .1       0    5567     .16       0
Bank Sta=4890,5016.1
XS Rating Curve= 0 ,0
Exp/Cntr=0.3,0.1

Type RM Length L Ch R = 1 ,1156    ,66,66,66
BEGIN DESCRIPTION:
UNT042 IN SNOGR 7.0
END DESCRIPTION:
XS GIS Cut Line= 4
      2801319.61     10012252.14      2802293.22       10012132.
      2802286.71     10011661.08      2802567.64     10011287.22
#Sta/Elev= 30
  3885.6 1814.92  3911.5 1809.18  3916.6 1809.76  3992.7  1796.6  4073.8 1786.12
  4106.1 1784.59  4126.3 1782.02    4237 1774.03  4317.2 1767.65    4358 1766.38
  4398.3 1763.01  4428.5 1762.84  4468.8 1759.49  4509.1 1758.72  4559.5 1755.16
  4954.9 1740.54  4974.9 1738.94  5001.9  1735.8  5004.6  1735.3  5007.9  1735.8
  5024.9 1738.66  5164.9 1743.99  5333.7 1752.72  5365.5 1752.27  5473.7 1760.36
  5571.2 1769.22  5576.6 1769.57  5720.5 1781.74  5765.4 1785.83  5805.2 1791.08
#Mann= 8 ,-1 , 0
  3885.6      .1       0    4237     .05       0  5001.9     .04       0
  5007.9     .05       0  5473.7      .1       0  5571.2     .16       0
  5576.6      .1       0  5720.5     .16       0
Bank Sta=4974.9,5024.9
XS Rating Curve= 0 ,0
Exp/Cntr=0.3,0.1

Type RM Length L Ch R = 1 ,1090    ,344,344,344
BEGIN DESCRIPTION:
UNT042 IN SNOGR 6.0
END DESCRIPTION:
XS GIS Cut Line= 4
       2801584.4     10012289.03      2802349.64     10012162.38
      2802373.52     10011606.82      2802581.86     10011311.67
#Sta/Elev= 30
  4055.7 1779.56  4172.7 1770.97    4222 1767.45  4262.5 1766.58  4300.3 1763.14
  4333.5 1762.85    4374 1759.68  4414.6 1759.06  4465.3 1755.71  4515.9 1754.76
  4556.5 1751.95  4759.2 1745.24  4799.8 1742.38  4910.1 1741.33  4922.7 1740.29
  4930.1 1738.43  4940.1 1736.73  4997.2 1735.43  4999.9 1734.93  5003.2 1735.43
  5030.2 1738.34  5100.3 1738.46  5210.4 1742.29  5270.4 1748.16    5408 1758.89
  5442.8 1760.74  5478.5 1766.07    5529 1770.43  5664.1 1780.47  5748.7 1788.16
#Mann= 6 ,-1 , 0
  4055.7      .1       0  4172.7     .05       0  4997.2     .04       0
  5003.2     .05       0    5408      .1       0  5664.1     .16       0
Bank Sta=4930.1,5030.2
XS Rating Curve= 0 ,0
Exp/Cntr=0.3,0.1

Type RM Length L Ch R = 1 ,746     ,90,90,90
BEGIN DESCRIPTION:
UNT042 IN SNOGR 5.0
END DESCRIPTION:
XS GIS Cut Line= 4
      2801722.89     10012290.88      2802416.92     10012233.99
      2802760.24     10012063.01       2802786.2     10011617.37
#Sta/Elev= 30
    4035 1770.18  4058.5 1767.51  4090.8 1767.13  4130.9 1763.69    4171  1763.2
  4211.2 1760.18  4311.5 1755.81  4592.4 1745.69  4622.5 1742.92  4662.7 1743.62
  4702.8 1739.48  4821.5 1737.13  4836.1 1736.28  4911.8 1732.96  4943.8 1733.18
  4967.4 1732.67  4970.1 1732.17  4973.4 1732.67    5032 1733.02  5045.9 1735.61
  5068.2 1740.11    5117 1741.52  5174.8 1746.65  5214.3 1748.97  5274.5 1750.22
  5304.5 1753.06  5462.4 1760.91  5512.1  1764.4  5517.1 1763.54  5561.3 1767.78
#Mann= 6 ,-1 , 0
    4035     .05       0  4821.5      .1       0  4943.8     .16       0
  4967.4     .07       0  4973.4     .16       0  5462.4      .1       0
Bank Sta=4836.1,5045.9
XS Rating Curve= 0 ,0
Exp/Cntr=0.3,0.1

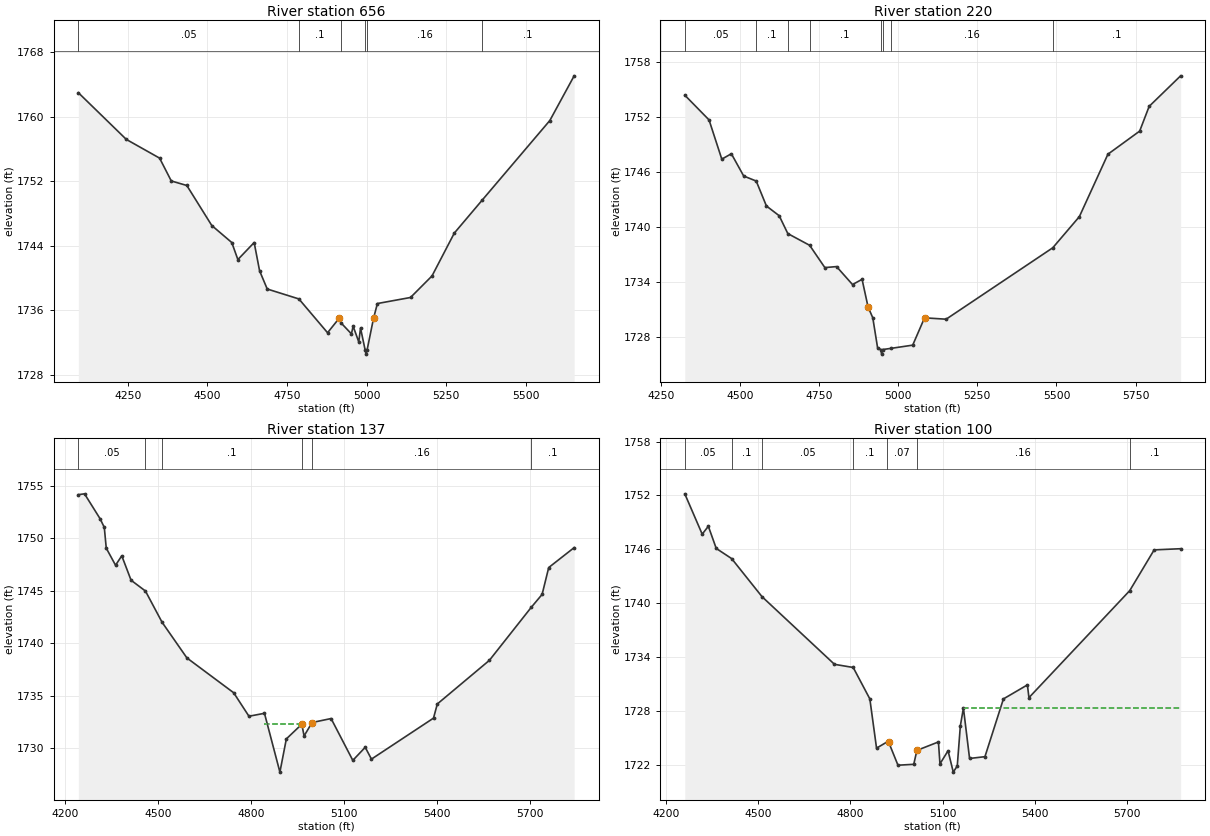
Type RM Length L Ch R = 1 ,656     ,436,436,436
BEGIN DESCRIPTION:
UNT042 IN SNOGR 4.0
END DESCRIPTION:
XS GIS Cut Line= 4
      2801819.24     10012441.92      2802467.27     10012298.66
      2802811.02     10012143.72      2802813.19     10011627.35
#Sta/Elev= 30
  4094.5 1762.99  4245.2  1757.2  4349.7 1754.88  4386.4 1752.05  4435.2 1751.49
  4513.6 1746.53  4576.4 1744.42  4595.5 1742.31  4646.7 1744.42  4663.7 1740.92
  4687.7 1738.66  4787.1 1737.43  4877.2 1733.24  4913.1 1735.01    4920 1734.44
  4952.1  1733.1  4957.5 1734.05  4975.2  1732.1  4980.7 1733.82  4995.3 1731.09
  4998.1 1730.59  5001.3 1731.09  5021.5 1735.02  5033.7 1736.86  5137.7 1737.61
  5205.2 1740.28  5275.2 1745.59  5363.1 1749.69  5575.2 1759.54  5651.6 1765.08
#Mann= 6 ,-1 , 0
  4094.5     .05       0  4787.1      .1       0    4920     .16       0
  4995.3     .07       0  5001.3     .16       0  5363.1      .1       0
Bank Sta=4913.1,5021.5
XS Rating Curve= 0 ,0
Exp/Cntr=0.3,0.1

Type RM Length L Ch R = 1 ,220     ,83,83,83
BEGIN DESCRIPTION:
UNT042 IN SNOGR 3.0
END DESCRIPTION:
XS GIS Cut Line= 4
      2802252.39     10012711.43      2802825.34     10012642.41
      2802911.28     10012465.33      2802855.73      10011674.6
#Sta/Elev= 30
  4325.6  1754.4  4402.2  1751.7  4442.5 1747.42  4472.7 1748.01  4511.7 1745.58
  4551.3 1745.03  4583.5 1742.31  4623.8 1741.25  4651.1  1739.3  4720.1 1738.02
  4768.1 1735.59  4805.1  1735.7  4855.5 1733.74  4885.7 1734.31  4904.7 1731.29
  4919.6 1730.11  4934.6 1726.87  4944.7 1726.65  4947.5 1726.15  4950.7 1726.65
  4977.5 1726.78  5045.7 1727.13  5083.1 1730.11  5151.3 1729.96  5488.2 1737.75
  5572.3 1741.15  5662.5 1747.96  5762.8 1750.48  5792.8 1753.18  5892.2 1756.51
#Mann= 8 ,-1 , 0
  4325.6     .05       0  4551.3      .1       0  4651.1     .05       0
  4720.1      .1       0  4944.7     .07       0  4950.7      .1       0
  4977.5     .16       0  5488.2      .1       0
Bank Sta=4904.7,5083.1
XS Rating Curve= 0 ,0
Exp/Cntr=0.3,0.1

Type RM Length L Ch R = 1 ,137     ,37,37,37
BEGIN DESCRIPTION:
UNT042 IN SNOGR 2.0
END DESCRIPTION:
XS GIS Cut Line= 6
      2802258.47     10012732.72      2802887.84     10012702.31
      2802919.44     10012669.58      2802951.38     10012550.83
      2802951.38     10012514.72      2802908.67     10011750.53
#Sta/Elev= 30
  4241.6 1754.17  4261.6 1754.25  4311.7 1751.88  4325.4 1751.05  4331.7 1749.07
  4361.7 1747.44  4381.8 1748.34  4411.8 1746.01  4458.2 1744.98  4511.9    1742
    4592  1738.6  4742.9 1735.28  4792.2 1733.04  4842.3 1733.32  4892.1 1727.71
  4912.9 1730.88  4962.8 1732.28  4970.1 1731.16    4996 1732.44  5057.3 1732.82
  5127.4 1728.83  5167.5 1730.08  5187.5 1728.95  5387.8 1732.86  5400.1 1734.21
  5568.1 1738.37  5703.1 1743.42  5738.3 1744.66  5759.6 1747.22  5841.7 1749.12
#Mann= 6 ,-1 , 0
  4241.6     .05       0  4458.2      .1       0  4511.9      .1       0
  4962.8     .07       0    4996     .16       0  5703.1      .1       0
#XS Ineff= 2 ,-1
 4839.68 4953.49 1732.26 5056.83 5429.65 1732.62
Permanent Ineff=
       T       T
Bank Sta=4962.8,4996
XS Rating Curve= 0 ,0
Exp/Cntr=0.3,0.1

Type RM Length L Ch R = 1 ,100     ,0,0,0
BEGIN DESCRIPTION:
UNT042 IN SNOGR 1.0
END DESCRIPTION:
XS GIS Cut Line= 5
      2802321.89     10012742.26      2802916.48     10012721.84
      2802957.69     10012687.21      2802992.62     10012535.76
      2803020.62     10011727.64
#Sta/Elev= 30
  4261.4 1752.18    4318 1747.69    4338 1748.57  4363.7  1746.1  4413.8 1744.97
  4512.6 1740.73  4748.3  1733.2  4809.2 1732.85  4863.3 1729.35  4885.1 1723.87
  4919.8 1724.57    4924 1724.58  4954.8 1721.97  5006.1 1722.07  5016.4 1723.62
  5086.4 1724.56  5091.4 1722.12  5117.7 1723.58  5134.7  1721.2  5147.7 1721.89
  5157.7 1726.35  5167.7 1728.34  5187.7 1722.72  5237.7 1722.92  5297.8 1729.35
  5375.8 1730.91  5380.8 1729.49  5708.6  1741.4  5788.1 1745.94  5874.2 1746.07
#Mann= 7 ,-1 , 0
  4261.4     .05       0  4413.8      .1       0  4512.6     .05       0
  4809.2      .1       0  4919.8     .07       0  5016.4     .16       0
  5708.6      .1       0
#XS Ineff= 2 , 0
                         5168.02         1728.34
Permanent Ineff=
       T       T
Bank Sta=4924,5016.4
XS Rating Curve= 0 ,0
Exp/Cntr=0.3,0.1

Chan Stop Cuts=-1
Use User Specified Reach Order=0
Composite Channel Slope=5