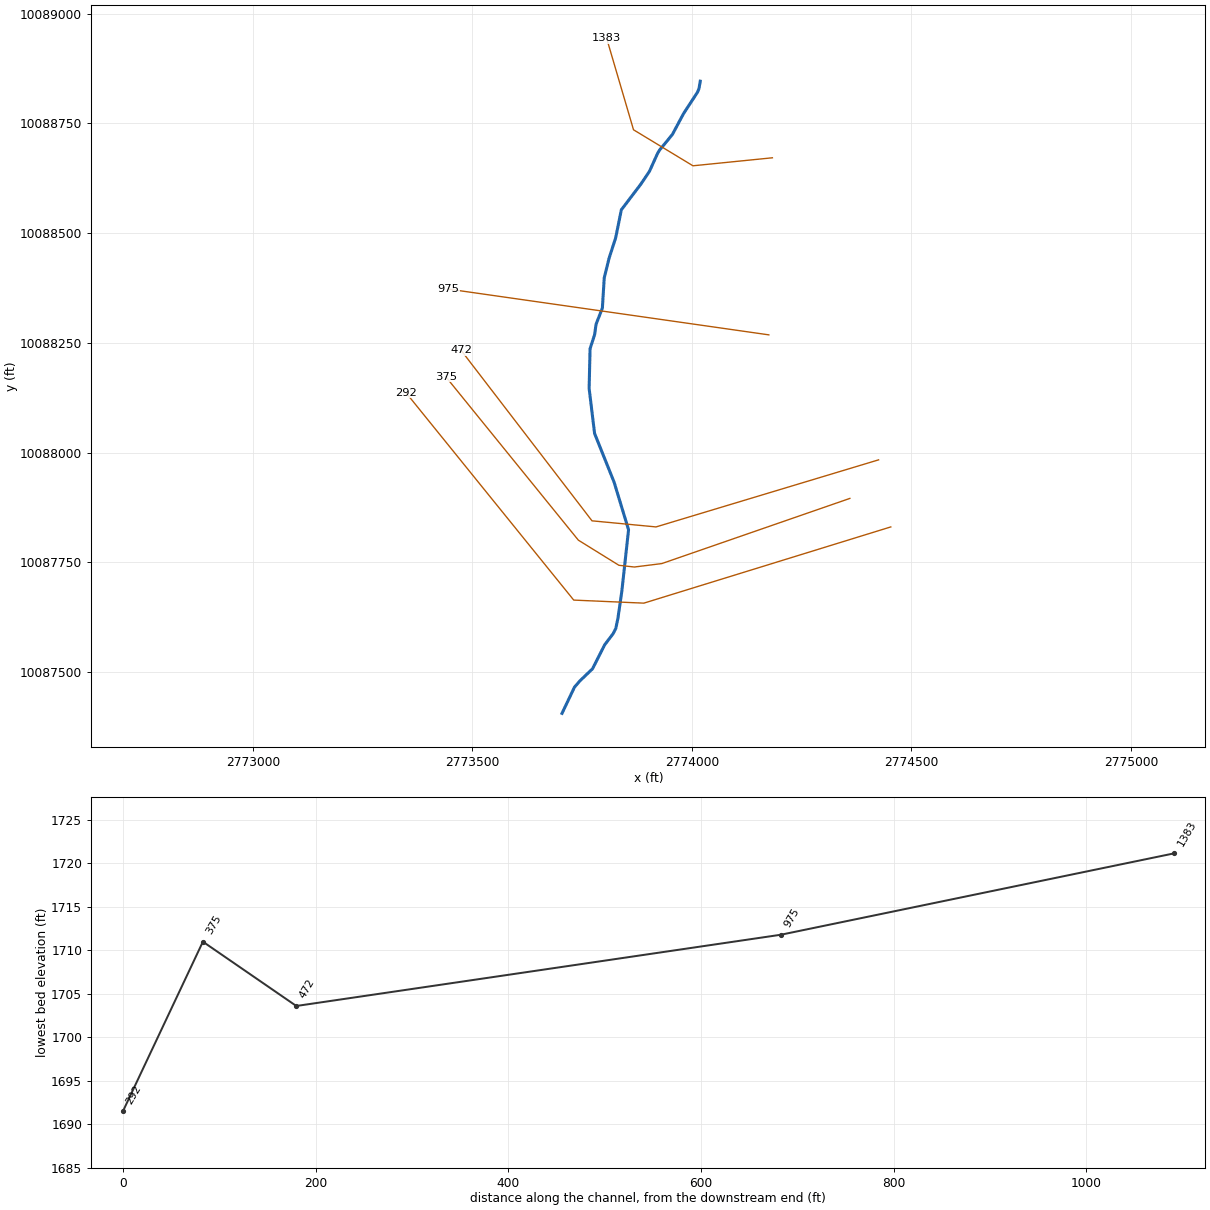
--- UNT043 IN NNOGR.prj (project) ---

Proj Title=UNT043 IN NNOGR Base Level Engineering
Current Plan=p01
Default Exp/Contr=0.3,0.1
English Units
Geom File=g01
Flow File=f01
Plan File=p01
BEGIN DESCRIPTION:
UNT043 IN NNOGR
END DESCRIPTION:

--- UNT043 IN NNOGR.p01 (plan) ---

Plan Title=Multiple Run
Short Identifier=Multiple
Geom File=g01
Flow File=f01
Subcritical Flow
K Sum by GR= 0
Std Step Tol= 0.01
Critical Tol= 0.01
Num of Std Step Trials= 20
Max Error Tol= 0.3
Flow Tol Ratio= 0.001
Split Flow NTrial= 30
Split Flow Tol= 0.02
Split Flow Ratio= 0.02
Log Output Level= 0
Friction Slope Method= 1
Unsteady Friction Slope Method= 2
Unsteady Bridges Friction Slope Method= 1
Parabolic Critical Depth
Global Vel Dist=  1 , 1 , 1
Global Log Level= 0
CheckData=True
Encroach Param= -1, 0, 0, 0
BEGIN DESCRIPTION:
Multiple Run
END DESCRIPTION:

--- UNT043 IN NNOGR.f01 (steady flow) ---

Flow Title=Multiple
Number of Profiles=7
Profile Names=10-year,25-year,50-year,1pct_min,100-year,1pct_plu,500-year
River Rch & RM= UNT043 IN NNOGR,Reach-1,1383
     251     339     411     367     496     670     721
Boundary for River Rch & Prof#=UNT043 IN NNOGR,Reach-1,1
Up Type=0
Dn Type=3
Dn Slope=0.005
Boundary for River Rch & Prof#=UNT043 IN NNOGR,Reach-1,2
Up Type=0
Dn Type=3
Dn Slope=0.005
Boundary for River Rch & Prof#=UNT043 IN NNOGR,Reach-1,3
Up Type=0
Dn Type=3
Dn Slope=0.005
Boundary for River Rch & Prof#=UNT043 IN NNOGR,Reach-1,4
Up Type=0
Dn Type=3
Dn Slope=0.005
Boundary for River Rch & Prof#=UNT043 IN NNOGR,Reach-1,5
Up Type=0
Dn Type=3
Dn Slope=0.005
Boundary for River Rch & Prof#=UNT043 IN NNOGR,Reach-1,6
Up Type=0
Dn Type=3
Dn Slope=0.005
Boundary for River Rch & Prof#=UNT043 IN NNOGR,Reach-1,7
Up Type=0
Dn Type=3
Dn Slope=0.005

--- UNT043 IN NNOGR.g01 (geometry) ---

Geom Title=Existing Conditions

River Reach=UNT043 IN NNOGR,Reach-1
Reach XY= 30
      2774019.17     10088846.28      2774016.33     10088829.62
      2774013.00     10088821.28      2773981.19     10088772.60
      2773955.69     10088724.88      2773926.76     10088689.73
      2773922.13     10088682.21      2773903.52     10088641.07
      2773883.40     10088611.11      2773839.42     10088553.26
      2773826.52     10088489.54      2773811.34     10088442.54
      2773800.46     10088398.20      2773796.19     10088329.38
      2773781.75     10088292.37      2773778.54     10088269.00
      2773768.20     10088236.86      2773766.03     10088146.58
      2773778.50     10088043.72      2773822.89     10087933.04
      2773855.87     10087824.53      2773840.59     10087684.81
      2773831.56     10087622.41      2773826.85     10087599.86
      2773820.75     10087587.83      2773801.52     10087562.51
      2773773.67     10087507.62      2773744.61     10087479.86
      2773732.66     10087465.90      2773704.26     10087406.24

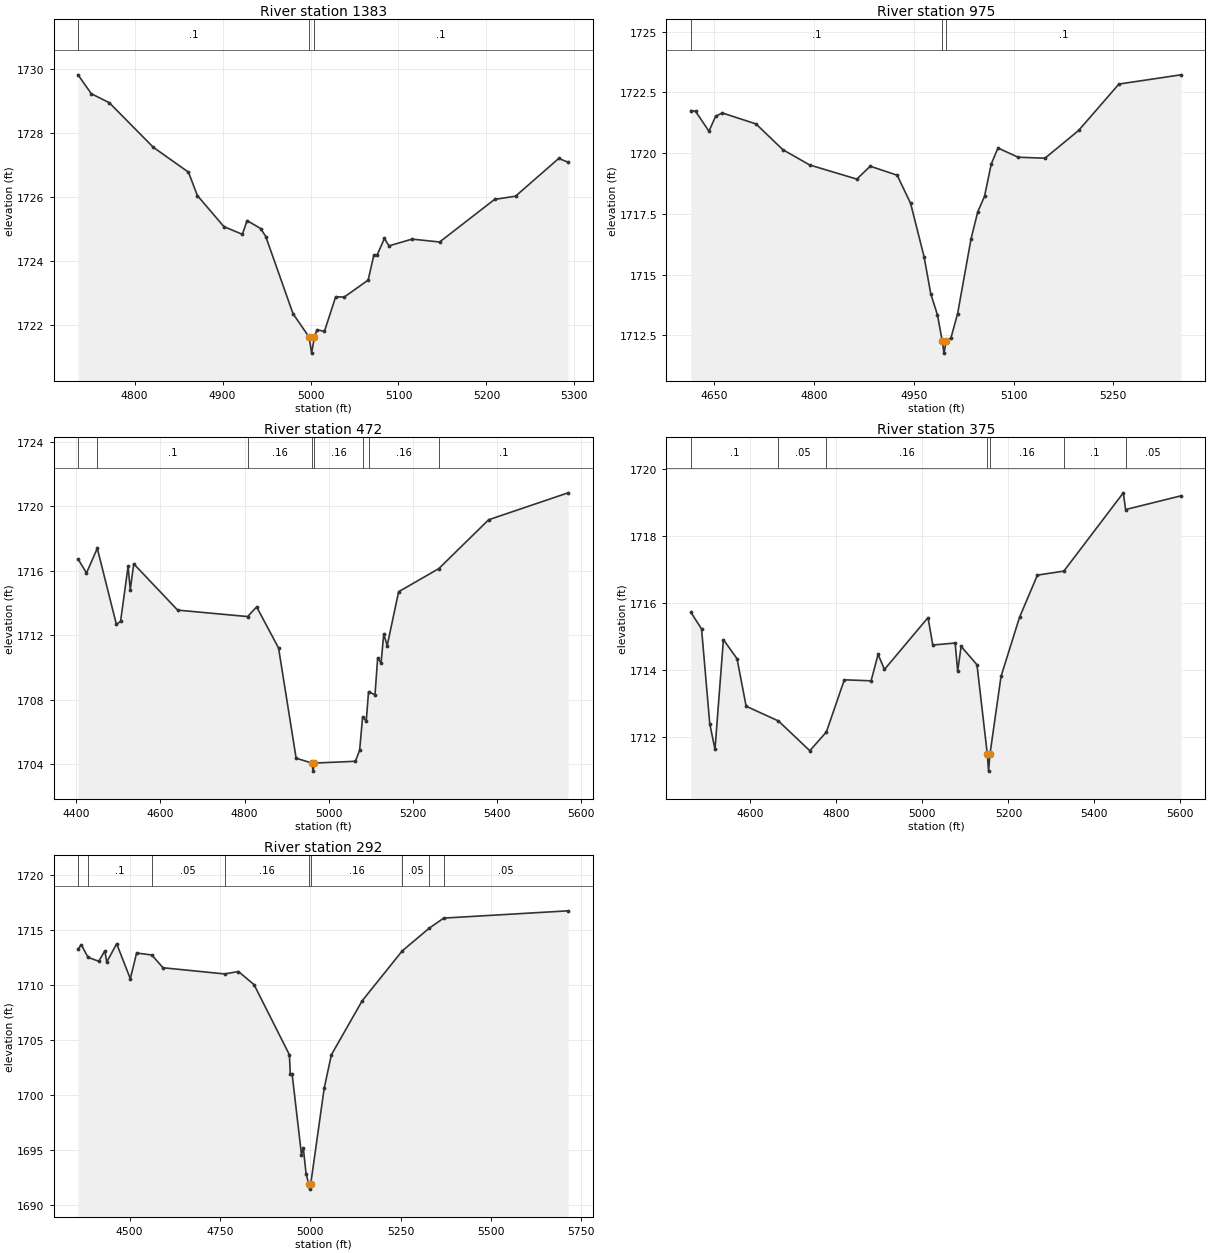
Type RM Length L Ch R = 1,1383,408,408,408
BEGIN DESCRIPTION:
UNT043 IN NNOGR 3.0
END DESCRIPTION:
XS GIS Cut Line= 4
      2774183.53     10088671.81      2774002.56     10088653.58
      2773867.15     10088735.61      2773805.96     10088943.91
#Sta/Elev= 30
  4735.6 1729.81  4750.7 1729.22  4771.1 1728.94  4821.1 1727.55  4861.2 1726.77
  4871.3 1726.04  4901.5 1725.07  4922.5 1724.83  4927.8 1725.26  4943.3 1725.01
  4949.1 1724.76  4980.1 1722.35  4998.4 1721.62  5001.2 1721.12  5004.4 1721.62
  5007.3 1721.85  5015.8 1721.80  5028.6 1722.88  5038.3 1722.87  5065.5 1723.40
  5072.1 1724.19  5075.8 1724.19  5084.0 1724.70  5089.2 1724.47  5115.5 1724.68
  5146.8 1724.59  5209.3 1725.92  5233.1 1726.02  5282.3 1727.20  5292.9 1727.08
#Mann=3,-1,0
  4735.6     0.1       0  4998.4    0.07       0  5004.4     0.1       0
Bank Sta=4998.4,5004.4
Exp/Cntr=0.3,0.1

Type RM Length L Ch R = 1,975,503,503,503
BEGIN DESCRIPTION:
UNT043 IN NNOGR 2.0
END DESCRIPTION:
XS GIS Cut Line= 2
      2774175.40     10088268.46      2773446.20     10088372.63
#Sta/Elev= 30
  4615.0 1721.75  4622.0 1721.72  4642.2 1720.90  4652.3 1721.52  4662.4 1721.65
  4712.9 1721.20  4753.3 1720.14  4793.7 1719.51  4864.4 1718.93  4884.6 1719.46
  4925.1 1719.09  4945.3 1717.93  4965.5 1715.74  4975.6 1714.21  4985.7 1713.34
  4992.8 1712.27  4995.5 1711.77  4998.8 1712.27  5005.9 1712.39  5016.0 1713.40
  5036.2 1716.48  5046.3 1717.59  5056.4 1718.22  5066.5 1719.55  5076.6 1720.21
  5106.9 1719.83  5147.3 1719.79  5197.8 1720.93  5258.4 1722.84  5351.6 1723.22
#Mann=3,-1,0
  4615.0     0.1       0  4992.8    0.07       0  4998.8     0.1       0
Bank Sta=4992.8,4998.8
Exp/Cntr=0.3,0.1

Type RM Length L Ch R = 1,472,97,97,97
BEGIN DESCRIPTION:
Mapping XS fb27ae02
END DESCRIPTION:
XS GIS Cut Line= 4
      2774425.38     10087983.73      2773918.46     10087830.96
      2773772.62     10087844.84      2773474.04     10088233.70
#Sta/Elev= 30
  4403.8 1716.73  4423.9 1715.86  4449.6 1717.39  4495.1 1712.67  4505.0 1712.87
  4522.9 1716.27  4528.1 1714.82  4536.3 1716.43  4640.8 1713.56  4807.3 1713.16
  4828.8 1713.76  4881.0 1711.21  4922.8 1704.38  4960.4 1704.08  4963.1 1703.58
  4966.4 1704.08  5063.8 1704.19  5073.9 1704.87  5081.0 1706.94  5089.7 1706.69
  5095.1 1708.50  5110.5 1708.31  5116.8 1710.59  5125.0 1710.29  5131.3 1712.08
  5139.5 1711.36  5166.7 1714.70  5262.2 1716.13  5380.9 1719.16  5570.0 1720.83
#Mann=8,-1,0
  4403.8    0.05       0  4449.6     0.1       0  4807.3    0.16       0
  4960.4    0.07       0  4966.4    0.16       0  5081.0     0.1       0
  5095.1    0.16       0  5262.2     0.1       0
Bank Sta=4960.4,4966.4
Exp/Cntr=0.3,0.1

Type RM Length L Ch R = 1,375,83,83,83
BEGIN DESCRIPTION:
Mapping XS bdcda10b
END DESCRIPTION:
XS GIS Cut Line= 6
      2774359.95     10087895.88      2773931.58     10087747.45
      2773869.08     10087739.64      2773833.92     10087743.54
      2773741.47     10087800.84      2773439.38     10088173.24
#Sta/Elev= 30
  4461.3 1715.72  4486.2 1715.22  4505.2 1712.39  4517.4 1711.62  4537.0 1714.90
  4568.7 1714.33  4589.9 1712.91  4665.0 1712.47  4738.0 1711.58  4776.5 1712.14
  4818.3 1713.70  4880.6 1713.67  4896.8 1714.46  4911.7 1714.01  5013.0 1715.56
  5024.1 1714.74  5076.1 1714.80  5082.0 1713.96  5090.0 1714.70  5126.9 1714.15
  5151.0 1711.47  5153.8 1710.97  5157.0 1711.47  5182.8 1713.80  5225.9 1715.57
  5267.5 1716.83  5329.0 1716.95  5467.3 1719.29  5472.6 1718.79  5601.3 1719.20
#Mann=7,-1,0
  4461.3     0.1       0  4665.0    0.05       0  4776.5    0.16       0
  5151.0    0.07       0  5157.0    0.16       0  5329.0     0.1       0
  5472.6    0.05       0
Bank Sta=5151,5157
Exp/Cntr=0.3,0.1

Type RM Length L Ch R = 1,292,0,0,0
BEGIN DESCRIPTION:
UNT043 IN NNOGR 1.0
END DESCRIPTION:
XS GIS Cut Line= 4
      2774453.22     10087830.97      2773890.68     10087657.34
      2773730.96     10087664.29      2773348.98     10088136.55
#Sta/Elev= 30
  4357.5 1713.26  4366.4 1713.68  4385.1 1712.53  4414.8 1712.17  4431.7 1713.12
  4436.9 1712.10  4464.4 1713.76  4502.2 1710.58  4519.5 1712.92  4561.5 1712.74
  4592.7 1711.58  4763.1 1711.02  4801.3 1711.24  4844.5 1710.05  4942.4 1703.68
  4944.8 1701.95  4949.8 1701.95  4975.8 1694.60  4980.8 1695.23  4988.5 1692.88
  4995.5 1691.98  4998.2 1691.48  5001.5 1691.98  5038.5 1700.62  5058.5 1703.68
  5143.7 1708.58  5254.5 1713.11  5329.5 1715.18  5369.4 1716.09  5713.5 1716.75
#Mann=9,-1,0
  4357.5    0.05       0  4385.1     0.1       0  4561.5    0.05       0
  4763.1    0.16       0  4995.5    0.07       0  5001.5    0.16       0
  5254.5    0.05       0  5329.5    0.16       0  5369.4    0.05       0
Bank Sta=4995.5,5001.5
Exp/Cntr=0.3,0.1

Chan Stop Cuts=-1