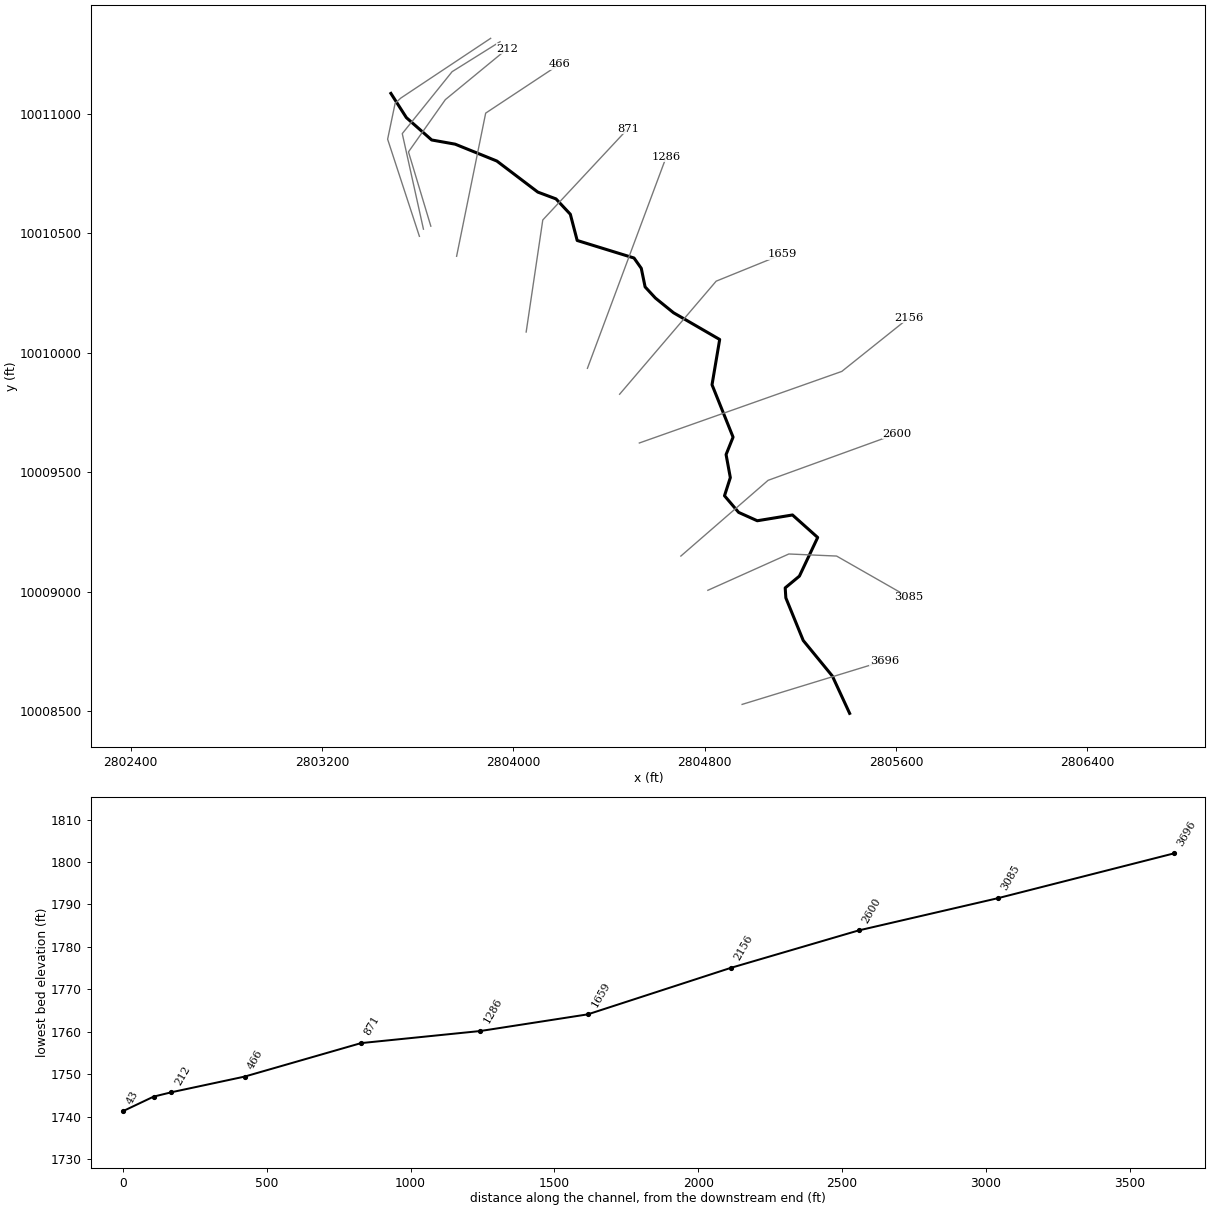
--- UNT043 IN SNOGR.prj (project) ---

Proj Title=UNT043 IN SNOGR Base Level Engineering
Current Plan=p01
Default Exp/Contr=0.3,0.1
English Units
Geom File=g01
Flow File=f01
Plan File=p01
Y Axis Title=Elevation
X Axis Title(PF)=Main Channel Distance
X Axis Title(XS)=Station
BEGIN DESCRIPTION:
UNT043 IN SNOGR
END DESCRIPTION:
DSS Export Rating Curves= 0
DSS Export Rating Curve Sorted= 0
DSS Export Volume Flow Curves= 0
DXF OffsetX= 0
DXF OffsetY= 0
DXF ScaleX= 1
DXF ScaleY= 10

--- UNT043 IN SNOGR.p01 (plan) ---

Plan Title=Multiple Run
Short Identifier=Multiple
Geom File=g01
Flow File=f01
Subcritical Flow
K Sum by GR= 0
Std Step Tol= 0.01
Critical Tol= 0.01
Num of Std Step Trials= 20
Max Error Tol= 0.3
Flow Tol Ratio= 0.001
Split Flow NTrial= 30
Split Flow Tol= 0.02
Split Flow Ratio= 0.02
Log Output Level= 0
Friction Slope Method= 1
Unsteady Friction Slope Method= 2
Unsteady Bridges Friction Slope Method= 1
Parabolic Critical Depth
Global Vel Dist=  1 , 1 , 1
Global Log Level= 0
CheckData=True
Encroach Param= -1, 0, 0, 0
BEGIN DESCRIPTION:
Multiple Run
END DESCRIPTION:

--- UNT043 IN SNOGR.f01 (steady flow) ---

Flow Title=Multiple
Number of Profiles=7
Profile Names=10-year,25-year,50-year,1pct_min,100-year,1pct_plu,500-year
River Rch & RM= UNT043 IN SNOGR,Reach-1,3696
     646     923    1160    1070    1447    1957    2256
Boundary for River Rch & Prof#=UNT043 IN SNOGR,Reach-1,1
Up Type=0
Dn Type=3
Dn Slope=0.005
Boundary for River Rch & Prof#=UNT043 IN SNOGR,Reach-1,2
Up Type=0
Dn Type=3
Dn Slope=0.005
Boundary for River Rch & Prof#=UNT043 IN SNOGR,Reach-1,3
Up Type=0
Dn Type=3
Dn Slope=0.005
Boundary for River Rch & Prof#=UNT043 IN SNOGR,Reach-1,4
Up Type=0
Dn Type=3
Dn Slope=0.005
Boundary for River Rch & Prof#=UNT043 IN SNOGR,Reach-1,5
Up Type=0
Dn Type=3
Dn Slope=0.005
Boundary for River Rch & Prof#=UNT043 IN SNOGR,Reach-1,6
Up Type=0
Dn Type=3
Dn Slope=0.005
Boundary for River Rch & Prof#=UNT043 IN SNOGR,Reach-1,7
Up Type=0
Dn Type=3
Dn Slope=0.005

--- UNT043 IN SNOGR.g01 (geometry) ---

Geom Title=Existing Conditions
Program Version=4.10

River Reach=UNT043 IN SNOGR ,Reach-1
Reach XY= 30
      2805405.87     10008490.29      2805333.68     10008646.46
      2805211.92     10008795.16      2805139.17      10008973.5
      2805136.49     10009015.36      2805195.87     10009064.61
      2805272.25     10009226.29      2805166.99     10009320.42
      2805019.71     10009296.23      2804941.93     10009331.17
      2804882.72     10009400.78      2804907.06     10009476.67
      2804889.34     10009573.14      2804918.57     10009646.13
      2804830.58     10009865.24      2804862.59     10010054.66
      2804669.63     10010166.54      2804593.81     10010228.07
      2804550.83     10010274.64      2804534.85     10010352.41
      2804504.44     10010395.59       2804266.9     10010468.96
      2804238.26     10010578.66      2804178.25     10010642.93
      2804102.28     10010671.36      2803931.09     10010801.34
      2803756.76      10010871.9      2803658.65     10010889.43
      2803552.82     10010982.95      2803488.15     10011084.26

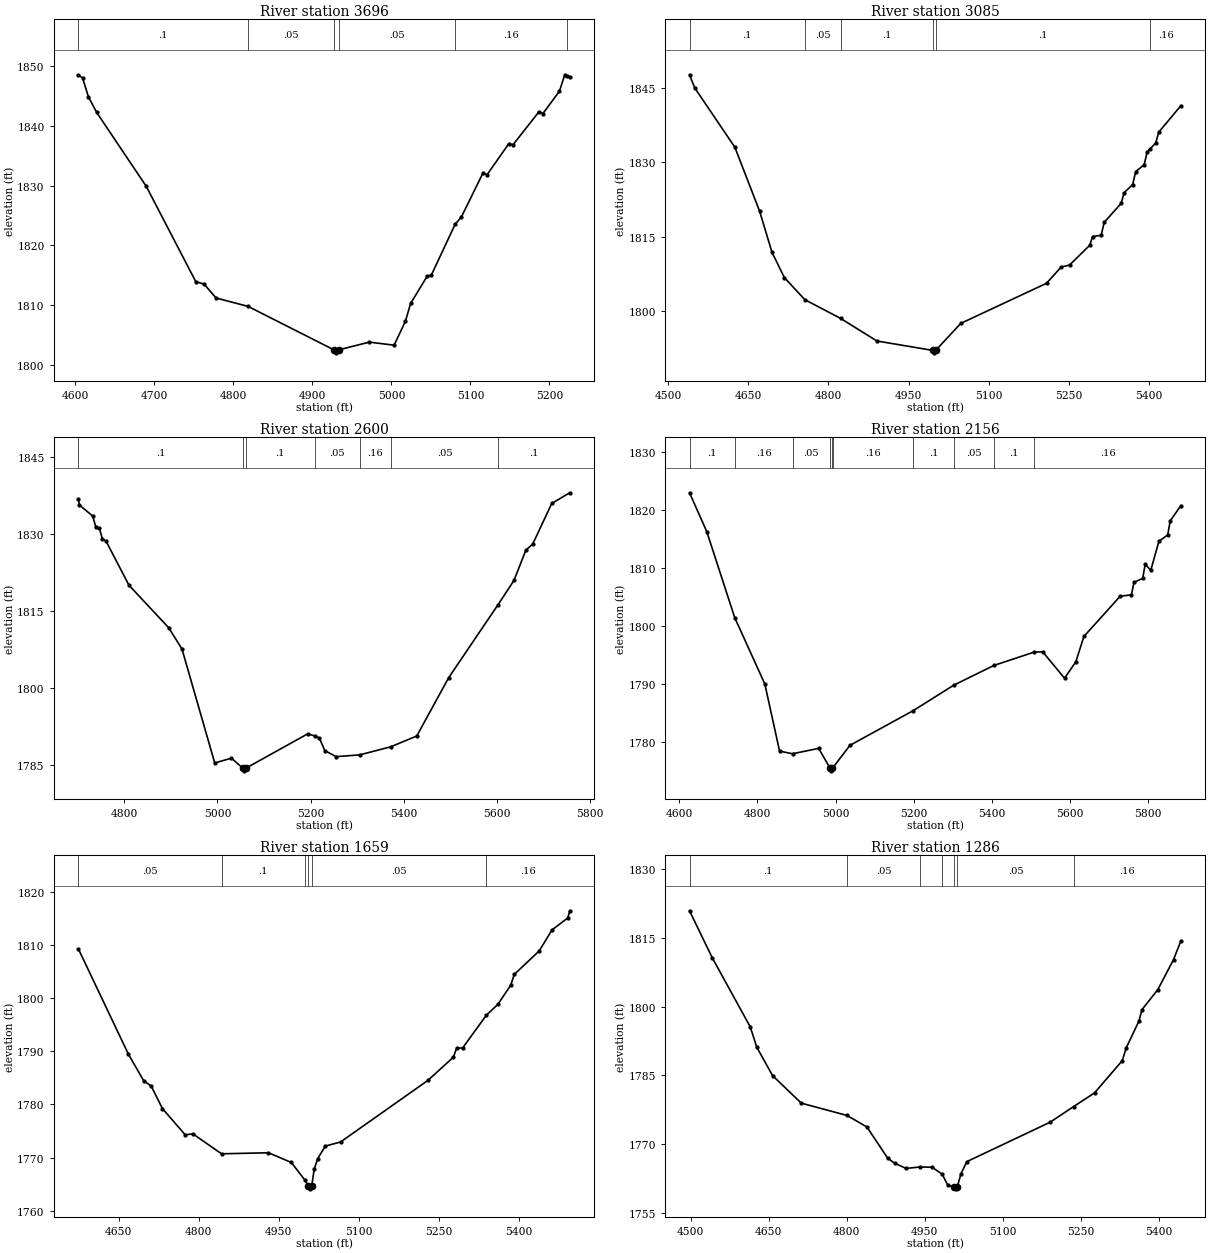
Type RM Length L Ch R = 1 ,3696    ,611,611,611
BEGIN DESCRIPTION:
UNT043 IN SNOGR 10.0
END DESCRIPTION:
XS GIS Cut Line= 2
      2804956.41     10008527.85        2805551.     10008710.13
#Sta/Elev= 30
  4603.8 1848.41    4609 1848.03  4616.4 1844.85  4626.9 1842.22  4689.6 1829.88
  4752.4 1813.91  4762.8 1813.53    4778 1811.19  4818.5 1809.79  4927.2 1802.52
  4929.9 1802.02  4933.2 1802.52    4972 1803.81  5003.4  1803.3  5017.7 1807.31
  5024.3 1810.28  5045.2 1814.83  5050.4 1814.99  5080.6 1823.51  5088.4 1824.71
  5115.9  1832.1  5121.1 1831.82  5148.6 1837.01  5153.9 1836.82  5186.6 1842.32
  5191.8 1842.04  5212.6 1845.77  5219.4 1848.52  5222.3 1848.24  5225.7 1848.15
#Mann= 6 ,-1 , 0
  4603.8      .1       0  4818.5     .05       0  4927.2    .035       0
  4933.2     .05       0  5080.6     .16       0  5222.3      .1       0
Bank Sta=4927.2,4933.2
XS Rating Curve= 0 ,0
Exp/Cntr=0.3,0.1

Type RM Length L Ch R = 1 ,3085    ,485,485,485
BEGIN DESCRIPTION:
UNT043 IN SNOGR 9.0
END DESCRIPTION:
XS GIS Cut Line= 4
       2804813.2     10009005.29      2805151.73      10009157.2
      2805351.39     10009148.51      2805654.32     10008975.41
#Sta/Elev= 30
    4540 1847.71  4549.8 1845.05  4624.8 1833.08  4671.2 1820.14  4694.4 1811.82
  4717.5 1806.71  4755.9 1802.24  4822.7 1798.46  4890.7 1793.89  4994.9 1791.99
  4997.6 1791.49  5000.9 1791.99  5047.9 1797.45  5208.3 1805.55  5235.7 1808.84
  5251.5 1809.24    5289 1813.22  5294.7 1815.01  5310.6 1815.25  5316.3 1817.87
    5348 1821.71  5353.7 1823.88  5369.6 1825.52  5375.3 1828.13  5391.2 1829.54
  5396.9 1832.18  5402.6 1832.74  5412.8 1833.94  5418.5 1836.12  5459.8 1841.45
#Mann= 6 ,-1 , 0
    4540      .1       0  4755.9     .05       0  4822.7      .1       0
  4994.9     .07       0  5000.9      .1       0  5402.6     .16       0
Bank Sta=4994.9,5000.9
XS Rating Curve= 0 ,0
Exp/Cntr=0.3,0.1

Type RM Length L Ch R = 1 ,2600    ,444,444,444
BEGIN DESCRIPTION:
UNT043 IN SNOGR 8.0
END DESCRIPTION:
XS GIS Cut Line= 3
      2804700.36     10009148.53      2805064.93     10009465.35
      2805603.09     10009660.66
#Sta/Elev= 30
  4701.4 1836.67  4703.6 1835.57  4732.1 1833.42  4738.7 1831.31  4746.3 1831.07
    4753 1828.93  4760.6 1828.57    4810 1819.97  4895.4  1811.7  4923.9 1807.56
  4994.2 1785.41  5030.1 1786.34  5054.8 1784.38  5057.5 1783.88  5060.8 1784.38
  5193.9 1791.07  5209.4 1790.67  5219.2 1790.21  5230.7 1787.81  5255.1 1786.64
  5305.4 1786.98  5372.2 1788.55  5428.2 1790.65  5496.7 1801.98  5603.1 1816.22
  5637.1 1820.91  5662.4 1826.75  5677.5 1828.01  5718.3 1835.89  5756.9 1837.95
#Mann= 7 ,-1 , 0
  4701.4      .1       0  5054.8     .07       0  5060.8      .1       0
  5209.4     .05       0  5305.4     .16       0  5372.2     .05       0
  5603.1      .1       0
Bank Sta=5054.8,5060.8
XS Rating Curve= 0 ,0
Exp/Cntr=0.3,0.1

Type RM Length L Ch R = 1 ,2156    ,497,497,497
BEGIN DESCRIPTION:
UNT043 IN SNOGR 7.0
END DESCRIPTION:
XS GIS Cut Line= 3
      2804526.71      10009621.6      2805373.09     10009921.08
      2805654.36      10010146.1
#Sta/Elev= 30
    4626 1822.95  4670.3 1816.24  4741.8 1801.44  4818.8 1790.03  4856.6 1778.47
  4889.7 1778.01  4956.7 1778.94  4985.5 1775.57  4988.3 1775.07  4991.5 1775.57
  4992.8 1775.58  5036.7 1779.46  5198.9 1785.44    5302  1789.8    5405 1793.21
  5508.1 1795.51  5530.2 1795.57  5586.2 1791.02    5615 1793.83  5635.8 1798.21
  5728.7 1805.14  5757.5 1805.37  5763.9 1807.51  5786.3 1808.22  5792.7 1810.62
  5807.1 1809.62  5827.9 1814.61  5850.3 1815.68  5856.7  1818.1    5884 1820.74
#Mann= 10 ,-1 , 0
    4626      .1       0  4741.8     .16       0  4889.7     .05       0
  4985.5     .07       0  4991.5     .05       0  4992.8     .16       0
  5198.9      .1       0    5302     .05       0    5405      .1       0
  5508.1     .16       0
Bank Sta=4985.5,4991.5
XS Rating Curve= 0 ,0
Exp/Cntr=0.3,0.1

Type RM Length L Ch R = 1 ,1659    ,373,373,373
BEGIN DESCRIPTION:
UNT043 IN SNOGR 6.0
END DESCRIPTION:
XS GIS Cut Line= 3
      2804444.29     10009825.62      2804847.91     10010298.69
      2805124.59     10010411.09
#Sta/Elev= 30
  4574.6 1809.23  4668.2 1789.46  4696.8 1784.47  4711.1 1783.44  4731.9 1779.23
  4774.7 1774.29    4789 1774.47  4842.7 1770.72  4930.7 1770.91  4973.5 1769.09
  4998.7  1765.8  5005.6 1764.63  5008.4 1764.13  5011.6 1764.63  5016.3 1767.81
  5022.9 1769.83  5037.2 1772.17  5065.7 1772.94  5229.4 1784.53  5277.1 1788.89
  5283.4 1790.66  5294.2 1790.59    5339  1796.8  5360.2  1798.8  5384.3 1802.39
  5391.3 1804.47  5437.8 1808.86  5461.9 1812.83  5491.4 1815.07  5495.1 1816.42
#Mann= 6 ,-1 , 0
  4574.6     .05       0  4842.7      .1       0  4998.7     .05       0
  5005.6    .035       0  5011.6     .05       0    5339     .16       0
Bank Sta=5005.6,5011.6
XS Rating Curve= 0 ,0
Exp/Cntr=0.3,0.1

Type RM Length L Ch R = 1 ,1286    ,415,415,415
BEGIN DESCRIPTION:
UNT043 IN SNOGR 5.0
END DESCRIPTION:
XS GIS Cut Line= 2
       2804309.7     10009934.06      2804639.44     10010819.13
#Sta/Elev= 30
  4497.8 1820.96  4541.3 1810.74  4614.8 1795.54    4627 1791.18  4657.5 1784.94
  4712.7 1778.93  4800.4 1776.25  4838.9 1773.72  4878.6 1766.93  4892.3 1765.79
  4914.3 1764.67  4940.9 1764.99  4964.3 1764.93  4983.6 1763.39  4994.6 1760.94
  5006.7 1760.71  5009.4 1760.21  5012.7 1760.71  5019.6  1763.5    5031 1766.16
  5190.9 1774.76  5236.3 1778.19  5276.5 1781.19  5329.8 1788.23  5337.2 1790.99
  5361.8 1796.88  5367.5 1799.35  5397.9 1803.72  5428.2 1810.29  5442.3 1814.36
#Mann= 7 ,-1 , 0
  4497.8      .1       0  4800.4     .05       0  4940.9      .1       0
  4983.6     .05       0  5006.7    .035       0  5012.7     .05       0
  5236.3     .16       0
Bank Sta=5006.7,5012.7
XS Rating Curve= 0 ,0
Exp/Cntr=0.3,0.1

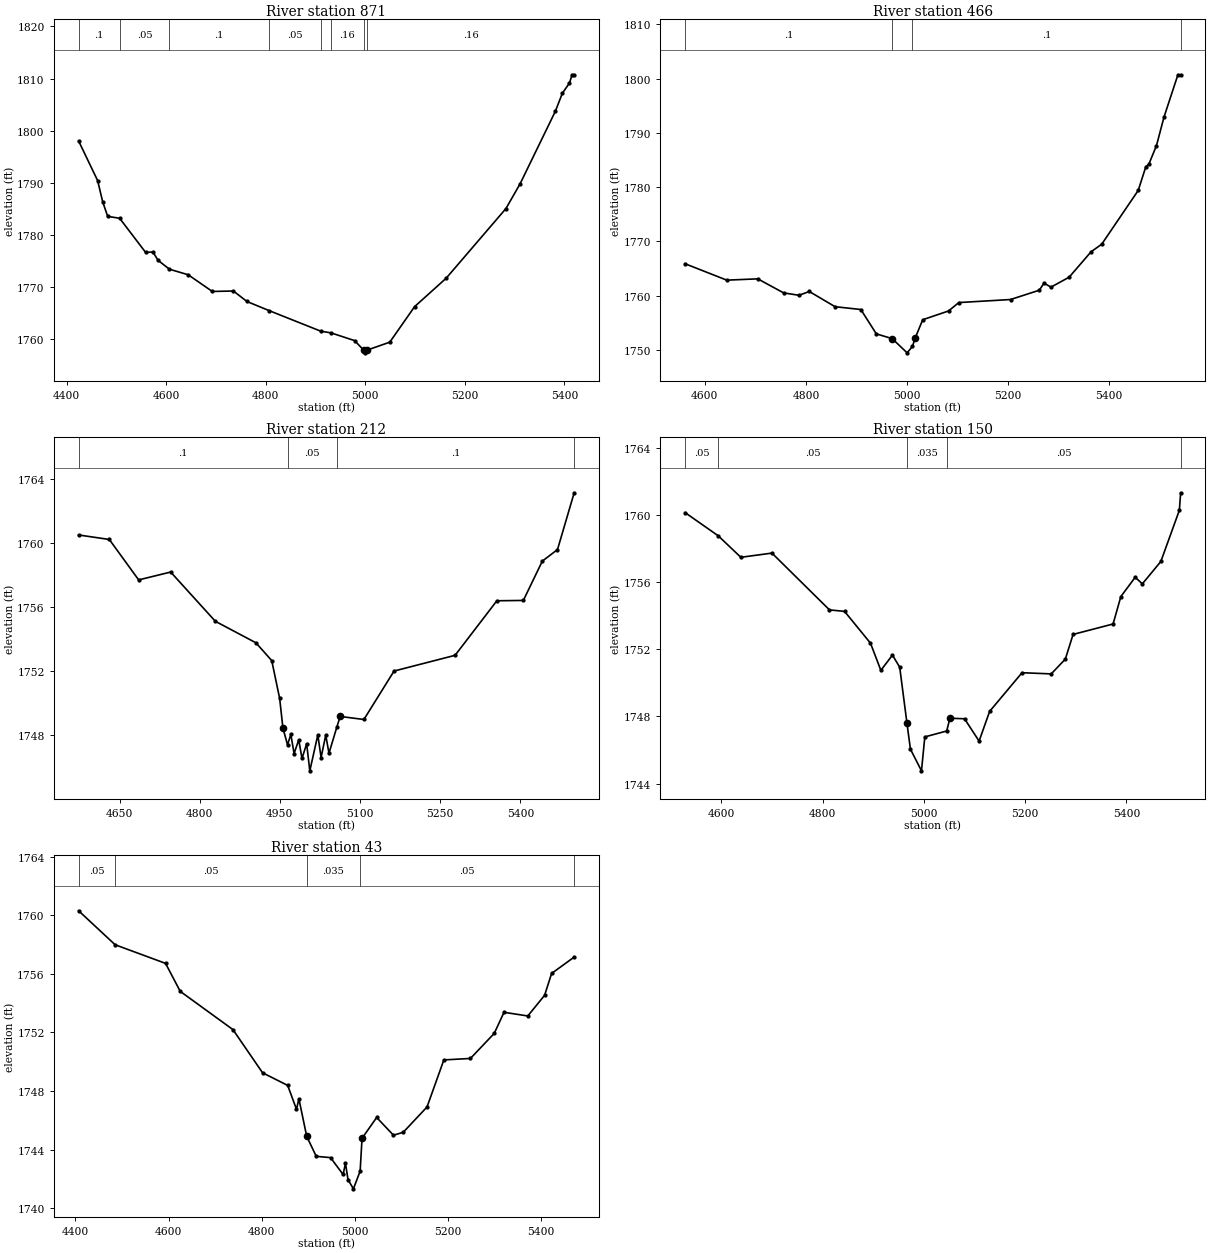
Type RM Length L Ch R = 1 ,871     ,405,405,405
BEGIN DESCRIPTION:
UNT043 IN SNOGR 4.0
END DESCRIPTION:
XS GIS Cut Line= 3
      2804053.64     10010085.98      2804123.09     10010554.76
      2804479.02     10010936.74
#Sta/Elev= 30
  4423.8 1798.02    4462 1790.42  4472.1 1786.37  4482.2 1783.55  4506.2 1783.19
  4558.5 1776.63  4573.2 1776.72  4583.3 1775.13  4606.3 1773.41  4643.9 1772.35
  4692.5 1769.14  4734.9 1769.23    4762 1767.22  4806.5 1765.47  4910.1 1761.53
  4931.1 1761.19  4978.4 1759.71  4996.9 1757.86  4999.6 1757.36  5002.9 1757.86
  5049.2 1759.41    5099 1766.22  5162.6 1771.69  5282.7 1785.06  5311.1  1789.8
  5381.9 1803.71  5396.1 1807.19  5410.3 1809.14  5415.7 1810.73  5419.8 1810.73
#Mann= 8 ,-1 , 0
  4423.8      .1       0  4506.2     .05       0  4606.3      .1       0
  4806.5     .05       0  4910.1      .1       0  4931.1     .16       0
  4996.9     .07       0  5002.9     .16       0
Bank Sta=4996.9,5002.9
XS Rating Curve= 0 ,0
Exp/Cntr=0.3,0.1

Type RM Length L Ch R = 1 ,466     ,254,254,254
BEGIN DESCRIPTION:
UNT043 IN SNOGR 3.0
END DESCRIPTION:
XS GIS Cut Line= 3
      2803762.84     10010402.83      2803884.37     10011001.81
       2804192.5     10011205.78
#Sta/Elev= 30
  4560.9 1765.88  4643.4 1762.86  4704.7  1763.1  4755.7 1760.52  4786.3 1760.07
  4806.7 1760.77  4857.7 1757.97  4908.7 1757.45  4939.4 1752.96  4970.7 1752.09
  5000.3 1749.47  5010.8 1750.65  5016.3 1752.21  5031.2 1755.57  5082.2 1757.18
  5102.6 1758.73  5204.9 1759.29    5262 1761.01  5271.1 1762.32  5284.9 1761.57
  5320.9  1763.4  5364.3 1768.08  5385.4 1769.48  5457.6 1779.38  5472.6 1783.72
  5478.6 1784.21  5493.7 1787.62  5508.7 1792.91  5536.2 1800.69  5541.6 1800.69
#Mann= 4 ,-1 , 0
  4560.9      .1       0  4970.7     .05       0  5010.8      .1       0
  5541.6     .16       0
Bank Sta=4970.7,5016.3
XS Rating Curve= 0 ,0
Exp/Cntr=0.3,0.1

Type RM Length L Ch R = 1 ,212     ,62,62,62
BEGIN DESCRIPTION:
UNT043 IN SNOGR 2.0
END DESCRIPTION:
XS GIS Cut Line= 4
      2803655.07     10010528.79      2803561.63     10010839.55
      2803715.84      10011058.3      2803974.49     10011271.13
#Sta/Elev= 30
  4573.5 1760.49  4630.9 1760.21  4685.8 1757.69  4745.7 1758.18  4829.3 1755.11
  4905.2 1753.77  4934.8 1752.66  4949.6  1750.3  4955.7 1748.46  4964.3 1747.41
  4970.5 1748.06  4976.6 1746.87  4985.3 1747.72  4991.4 1746.56  5000.1 1747.48
    5006 1745.79    5021 1748.03  5027.1 1746.62  5035.8 1748.01  5041.9 1746.89
  5056.7 1748.53  5062.8 1749.18  5107.2 1748.99  5163.6 1752.01  5277.8 1752.99
    5356 1756.39  5405.5 1756.41    5441 1758.86  5469.4 1759.58  5500.6 1763.12
#Mann= 4 ,-1 , 0
  4573.5      .1       0  4964.3     .05       0  5056.7      .1       0
  5500.6     .16       0
Bank Sta=4955.7,5062.8
XS Rating Curve= 0 ,0
Exp/Cntr=0.3,0.1

Type RM Length L Ch R = 1 ,150     ,107,107,107
BEGIN DESCRIPTION:
Mapping XS e127791b
END DESCRIPTION:
XS GIS Cut Line= 4
      2803624.21     10010516.26      2803535.66     10010916.04
      2803743.99     10011175.15       2803944.6      10011300.7
#Sta/Elev= 30
  4528.4 1760.13  4593.8 1758.75  4638.5 1757.47  4699.9 1757.72  4813.5 1754.34
  4843.3 1754.25  4894.5 1752.36    4915 1750.74  4937.9 1751.65  4952.2 1750.93
  4966.6 1747.58  4973.4 1746.05  4995.2 1744.76  5001.8 1746.78    5045 1747.13
  5051.4 1747.89  5080.2 1747.86    5109 1746.53  5129.8  1748.3  5193.8  1750.6
  5251.4 1750.53  5279.3 1751.41  5294.6 1752.88  5373.6  1753.5  5388.9 1755.13
  5417.2 1756.28  5431.4 1755.89  5467.9 1757.22  5504.5 1760.27    5507 1761.31
#Mann= 5 ,-1 , 0
  4528.4     .05       0  4593.8     .05       0  4966.6    .035       0
    5045     .05       0    5507      .1       0
Bank Sta=4966.6,5051.4
XS Rating Curve= 0 ,0
Exp/Cntr=0.3,0.1

Type RM Length L Ch R = 1 ,43      ,0,0,0
BEGIN DESCRIPTION:
UNT043 IN SNOGR 1.0
END DESCRIPTION:
XS GIS Cut Line= 5
      2803607.29     10010486.31      2803474.46      10010892.6
      2803505.71     10011042.34      2803529.15     10011064.48
      2803905.14      10011314.7
#Sta/Elev= 30
  4406.8  1760.3  4485.2 1757.98  4593.5 1756.71    4625  1754.8  4738.2 1752.19
  4801.9 1749.24  4855.8 1748.38  4874.7 1746.75  4879.9 1747.46  4896.7  1744.9
  4917.1 1743.54  4947.8 1743.45  4974.8  1742.3  4979.9 1743.06  4985.4 1741.94
    4997 1741.32  5011.4 1742.53  5015.5 1744.77  5046.9 1746.19    5083 1744.98
    5104 1745.18  5155.1 1746.91  5191.2 1750.12  5248.3 1750.22  5299.4 1751.93
  5320.4 1753.37  5371.5 1753.12  5407.6 1754.53  5422.6 1756.02  5471.1 1757.14
#Mann= 5 ,-1 , 0
  4406.8     .05       0  4485.2     .05       0  4896.7    .035       0
  5011.4     .05       0  5471.1      .1       0
Bank Sta=4896.7,5015.5
XS Rating Curve= 0 ,0
Exp/Cntr=0.3,0.1

Chan Stop Cuts=-1
Use User Specified Reach Order=0
Composite Channel Slope=5