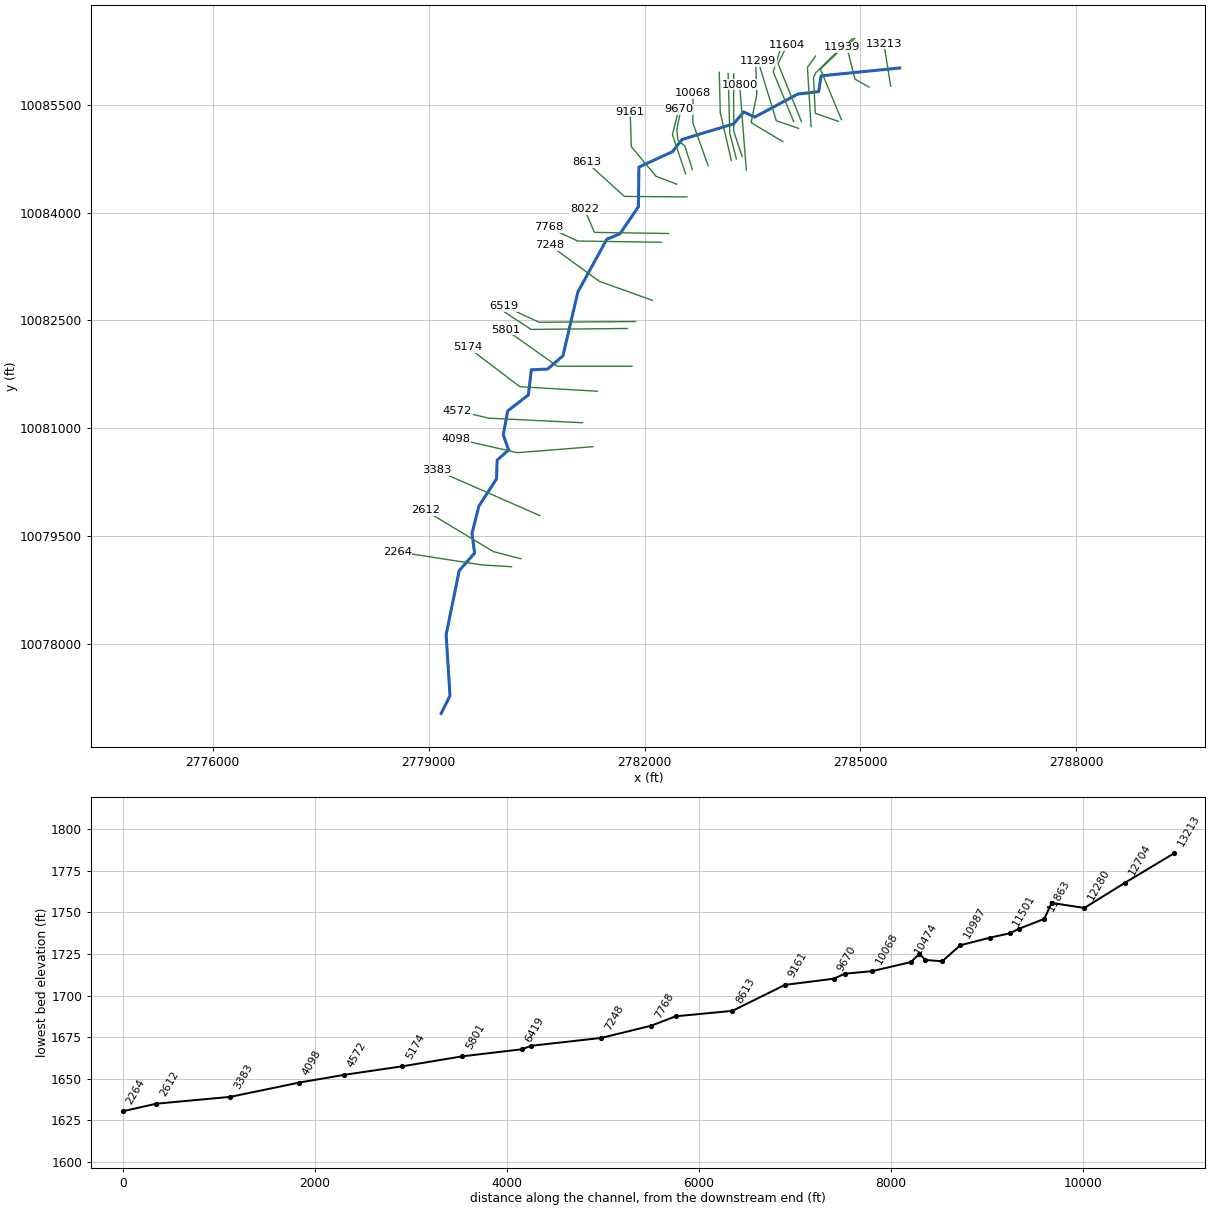
--- UNT044 IN NNOGR.prj (project) ---

Proj Title=UNT044 IN NNOGR Base Level Engineering
Current Plan=p01
Default Exp/Contr=0.3,0.1
English Units
Geom File=g01
Flow File=f01
Plan File=p01
Y Axis Title=Elevation
X Axis Title(PF)=Main Channel Distance
X Axis Title(XS)=Station
BEGIN DESCRIPTION:
UNT044 IN NNOGR
END DESCRIPTION:
DSS Export Rating Curves= 0
DSS Export Rating Curve Sorted= 0
DSS Export Volume Flow Curves= 0
DXF OffsetX= 0
DXF OffsetY= 0
DXF ScaleX= 1
DXF ScaleY= 10

--- UNT044 IN NNOGR.p01 (plan) ---

Plan Title=Multiple Run
Short Identifier=Multiple
Geom File=g01
Flow File=f01
Subcritical Flow
K Sum by GR= 0
Std Step Tol= 0.01
Critical Tol= 0.01
Num of Std Step Trials= 20
Max Error Tol= 0.3
Flow Tol Ratio= 0.001
Split Flow NTrial= 30
Split Flow Tol= 0.02
Split Flow Ratio= 0.02
Log Output Level= 0
Friction Slope Method= 1
Unsteady Friction Slope Method= 2
Unsteady Bridges Friction Slope Method= 1
Parabolic Critical Depth
Global Vel Dist=  1 , 1 , 1
Global Log Level= 0
CheckData=True
Encroach Param= -1, 0, 0, 0
BEGIN DESCRIPTION:
Multiple Run
END DESCRIPTION:

--- UNT044 IN NNOGR.f01 (steady flow) ---

Flow Title=Multiple
Number of Profiles=7
Profile Names=10-year,25-year,50-year,1pct_min,100-year,1pct_plu,500-year
River Rch & RM= UNT044 IN NNOGR,Reach-1,13213
     927    1357    1735    1623    2195    2969    3531
River Rch & RM= UNT044 IN NNOGR,Reach-1,3383
    1017    1494    1913    1793    2425    3279    3912
Boundary for River Rch & Prof#=UNT044 IN NNOGR,Reach-1,1
Up Type=0
Dn Type=3
Dn Slope=0.005
Boundary for River Rch & Prof#=UNT044 IN NNOGR,Reach-1,2
Up Type=0
Dn Type=3
Dn Slope=0.005
Boundary for River Rch & Prof#=UNT044 IN NNOGR,Reach-1,3
Up Type=0
Dn Type=3
Dn Slope=0.005
Boundary for River Rch & Prof#=UNT044 IN NNOGR,Reach-1,4
Up Type=0
Dn Type=3
Dn Slope=0.005
Boundary for River Rch & Prof#=UNT044 IN NNOGR,Reach-1,5
Up Type=0
Dn Type=3
Dn Slope=0.005
Boundary for River Rch & Prof#=UNT044 IN NNOGR,Reach-1,6
Up Type=0
Dn Type=3
Dn Slope=0.005
Boundary for River Rch & Prof#=UNT044 IN NNOGR,Reach-1,7
Up Type=0
Dn Type=3
Dn Slope=0.005

--- UNT044 IN NNOGR.g01 (geometry) ---

Geom Title=Existing Conditions
Program Version=4.10

River Reach=UNT044 IN NNOGR ,Reach-1
Reach XY= 30
      2785544.32     10086009.85      2784453.11      10085900.6
      2784419.08     10085681.16      2784126.72     10085646.44
      2783529.91      10085326.9      2783378.08     10085399.38
      2783237.96     10085233.59      2782521.55     10085016.32
      2782387.42     10084846.29      2781921.76     10084631.65
      2781915.29     10084080.74      2781657.86     10083704.21
       2781476.3     10083630.08      2781074.03     10082896.34
      2780866.63     10082009.15      2780654.16     10081824.66
      2780427.84     10081814.36      2780386.16     10081464.68
      2780099.65     10081242.82      2780037.15     10080908.45
      2780112.26     10080700.35      2779951.68     10080557.05
      2779944.38     10080299.27      2779698.73     10079919.02
      2779603.23     10079540.35      2779639.19     10079266.24
       2779425.1     10079022.66      2779244.16     10078130.92
      2779297.45     10077284.15      2779175.33     10077038.13

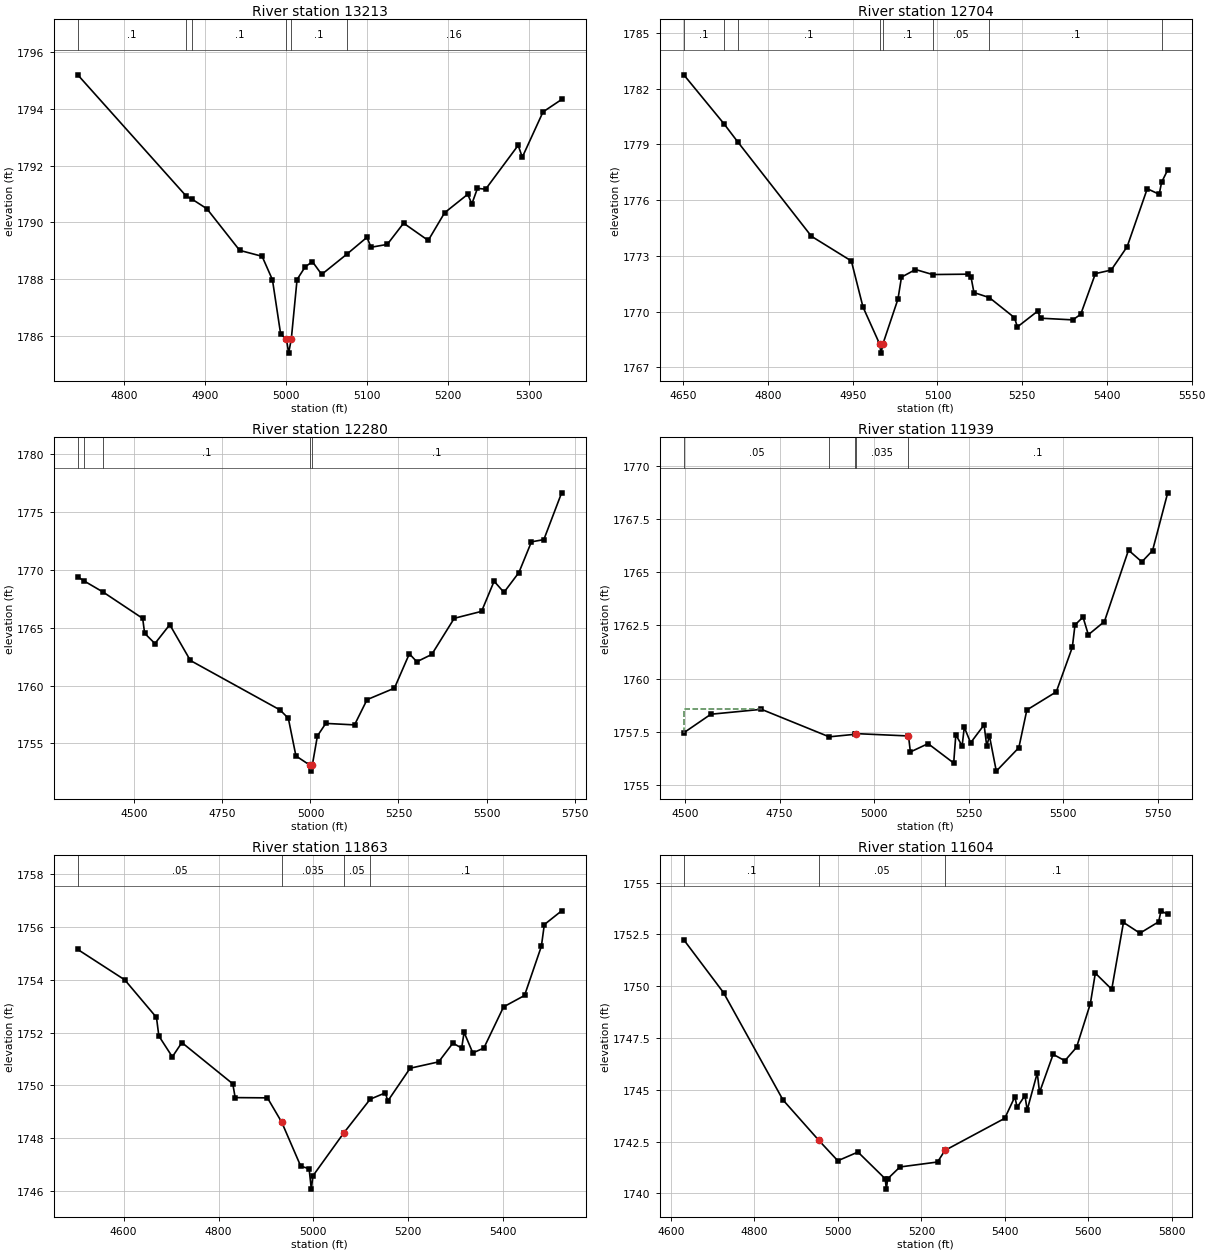
Type RM Length L Ch R = 1 ,13213   ,509,509,509
BEGIN DESCRIPTION:
UNT044 IN NNOGR 29.0
END DESCRIPTION:
XS GIS Cut Line= 2
      2785419.54     10085756.18      2785325.79     10086346.49
#Sta/Elev= 30
  4742.9 1795.21  4877.1 1790.92  4884.5 1790.81  4902.4 1790.48  4942.9 1789.01
  4970.6  1788.8  4983.4 1787.97  4993.6 1786.04  5000.7 1785.88  5003.4 1785.38
  5006.7 1785.88  5013.8 1787.98  5023.9 1788.43  5032.8 1788.61  5044.2 1788.16
  5075.5 1788.88  5100.1 1789.47  5105.2 1789.12  5125.2 1789.22  5145.4 1789.97
  5175.8 1789.36  5196.1 1790.34  5224.6 1790.99  5229.7 1790.65  5236.6  1791.2
  5246.7 1791.17  5286.9 1792.72    5292  1792.3  5317.6  1793.9  5340.6 1794.34
#Mann= 6 ,-1 , 0
  4742.9      .1       0  4877.1     .05       0  4884.5      .1       0
  5000.7     .07       0  5006.7      .1       0  5075.5     .16       0
Bank Sta=5000.7,5006.7
XS Rating Curve= 0 ,0
Exp/Cntr=0.3,0.1

Type RM Length L Ch R = 1 ,12704   ,424,424,424
BEGIN DESCRIPTION:
UNT044 IN NNOGR 28.0
END DESCRIPTION:
XS GIS Cut Line= 4
      2785119.36     10085743.57      2784922.71     10085855.57
      2784806.82     10086313.91      2784921.42     10086421.99
#Sta/Elev= 30
    4651 1782.74  4721.7 1780.12  4746.5 1779.13  4876.9 1774.05  4947.6 1772.72
  4968.2 1770.24  4997.5 1768.26  5000.2 1767.76  5003.5 1768.26  5030.1 1770.67
  5036.3 1771.85  5061.1 1772.26  5091.5 1771.99  5153.9 1772.01  5159.4 1771.86
  5164.6 1771.02  5191.8 1770.75  5236.3 1769.67  5241.5 1769.17  5277.4 1770.02
  5282.5 1769.64  5339.6 1769.55  5353.6 1769.85  5379.6 1772.04  5407.5 1772.23
  5435.8 1773.49  5471.4 1776.61  5492.5 1776.31  5496.8 1776.96  5507.6 1777.62
#Mann= 8 ,-1 , 0
    4651      .1       0  4721.7     .05       0  4746.5      .1       0
  4997.5     .07       0  5003.5      .1       0  5091.5     .05       0
  5191.8      .1       0  5496.8     .05       0
Bank Sta=4997.5,5003.5
XS Rating Curve= 0 ,0
Exp/Cntr=0.3,0.1

Type RM Length L Ch R = 1 ,12280   ,341,341,341
BEGIN DESCRIPTION:
UNT044 IN NNOGR 27.0
END DESCRIPTION:
XS GIS Cut Line= 3
      2784735.77     10085291.67      2784442.79     10085994.83
      2784887.69     10086415.86
#Sta/Elev= 30
  4339.1 1769.38  4356.2 1769.04  4411.4 1768.06  4523.6 1765.79    4529 1764.51
  4558.3 1763.62  4600.5 1765.25    4659 1762.16  4913.6 1757.89  4937.2 1757.17
  4958.8 1753.92  4999.2 1753.11  5001.9 1752.61  5005.2 1753.11  5019.8 1755.65
  5043.6 1756.73  5125.2  1756.6  5160.8 1758.78  5238.5 1759.77  5280.9 1762.74
    5302 1762.05  5344.5 1762.68  5408.4  1765.8    5486  1766.4  5521.6    1769
  5549.6 1768.04    5592 1769.75  5627.6  1772.4  5662.8 1772.59  5713.4 1776.63
#Mann= 5 ,-1 , 0
  4339.1      .1       0  4356.2     .05       0  4411.4      .1       0
  4999.2     .07       0  5005.2      .1       0
Bank Sta=4999.2,5005.2
XS Rating Curve= 0 ,0
Exp/Cntr=0.3,0.1

Type RM Length L Ch R = 1 ,11939   ,76,76,76
BEGIN DESCRIPTION:
UNT044 IN NNOGR 26.0
END DESCRIPTION:
XS GIS Cut Line= 5
     2784692.938    10085267.919     2784372.625    10085379.898
      2784347.49     10085879.47      2784379.41      10085943.3
      2784739.45     10086299.49
#Sta/Elev= 30
  4496.9 1757.46  4568.5 1758.33  4702.2 1758.56  4881.3 1757.27  4950.4 1757.39
  4952.6 1757.42  5091.1 1757.31  5096.1 1756.56  5142.9 1756.95  5210.6 1756.04
  5216.2 1757.36    5233 1756.85  5238.6 1757.72  5255.4 1756.99    5291 1757.83
    5298 1756.83  5305.1 1757.32  5323.3 1755.66  5382.9 1756.76  5404.1 1758.53
  5481.9 1759.38  5524.3 1761.47  5531.4 1762.52  5552.6 1762.89  5566.7 1762.06
  5609.2 1762.68  5672.9 1766.03  5708.2 1765.48  5736.5 1766.01  5776.6 1768.72
#Mann= 5 ,-1 , 0
  4496.9     .05       0  4881.3      .1       0  4950.4     .05       0
  4952.6    .035       0  5091.1      .1       0
#XS Ineff= 2 , 0
         4703.22 1758.58
Permanent Ineff=
       F       F
Bank Sta=4952.6,5091.1
XS Rating Curve= 0 ,0
Exp/Cntr=0.3,0.1

Type RM Length L Ch R = 1 ,11863   ,259,259,259
BEGIN DESCRIPTION:
Mapping XS 803c759c
END DESCRIPTION:
XS GIS Cut Line= 3
      2784313.86      10085194.8      2784262.66      10086018.7
      2784376.79     10086175.72
#Sta/Elev= 30
  4503.4 1755.14  4602.5 1753.99  4669.3 1752.57  4674.3 1751.87  4702.7 1751.08
  4722.8 1751.62  4830.1 1750.06  4835.1 1749.54  4903.1 1749.53  4933.2 1748.61
  4973.2 1746.95  4990.9 1746.85  4995.6 1746.08  4998.9 1746.58  5063.4 1748.19
  5119.6 1749.48  5151.6 1749.72  5156.7 1749.41  5203.7 1750.65  5263.8 1750.89
  5293.9  1751.6  5312.4 1751.41  5317.4 1752.01  5335.8 1751.23    5359 1751.41
  5400.7 1752.97  5444.8  1753.4  5480.3 1755.26  5486.5 1756.08    5523  1756.6
#Mann= 4 ,-1 , 0
  4503.4     .05       0  4933.2    .035       0  5063.4     .05       0
  5119.6      .1       0
Bank Sta=4933.2,5063.4
XS Rating Curve= 0 ,0
Exp/Cntr=0.3,0.1

Type RM Length L Ch R = 1 ,11604   ,103,103,103
BEGIN DESCRIPTION:
UNT044 IN NNOGR 25.0
END DESCRIPTION:
XS GIS Cut Line= 3
      2784180.19      10085263.5      2783854.68     10086070.78
      2783982.13     10086330.01
#Sta/Elev= 30
  4630.7 1752.24  4725.8 1749.69  4868.2 1744.51  4954.4 1742.55  4999.6 1741.57
  5047.9 1741.99  5113.2  1740.7  5115.9  1740.2  5119.2  1740.7  5148.5 1741.27
  5238.6 1741.51  5256.3 1742.07  5399.6 1743.62  5423.8 1744.66  5429.2 1744.15
    5448 1744.72  5453.3 1744.02  5477.5 1745.81  5482.9 1744.87  5515.5 1746.71
  5543.6  1746.4  5571.6 1747.05  5604.7 1749.16  5616.6 1750.63  5655.9 1749.85
    5684 1753.08  5723.4 1752.56  5768.3 1753.11  5773.9 1753.64    5790 1753.47
#Mann= 3 , 0 , 0
  4630.7      .1       0  4954.4     .05       0  5256.3      .1       0
Bank Sta=4954.4,5256.3
XS Rating Curve= 0 ,0
Exp/Cntr=0.3,0.1

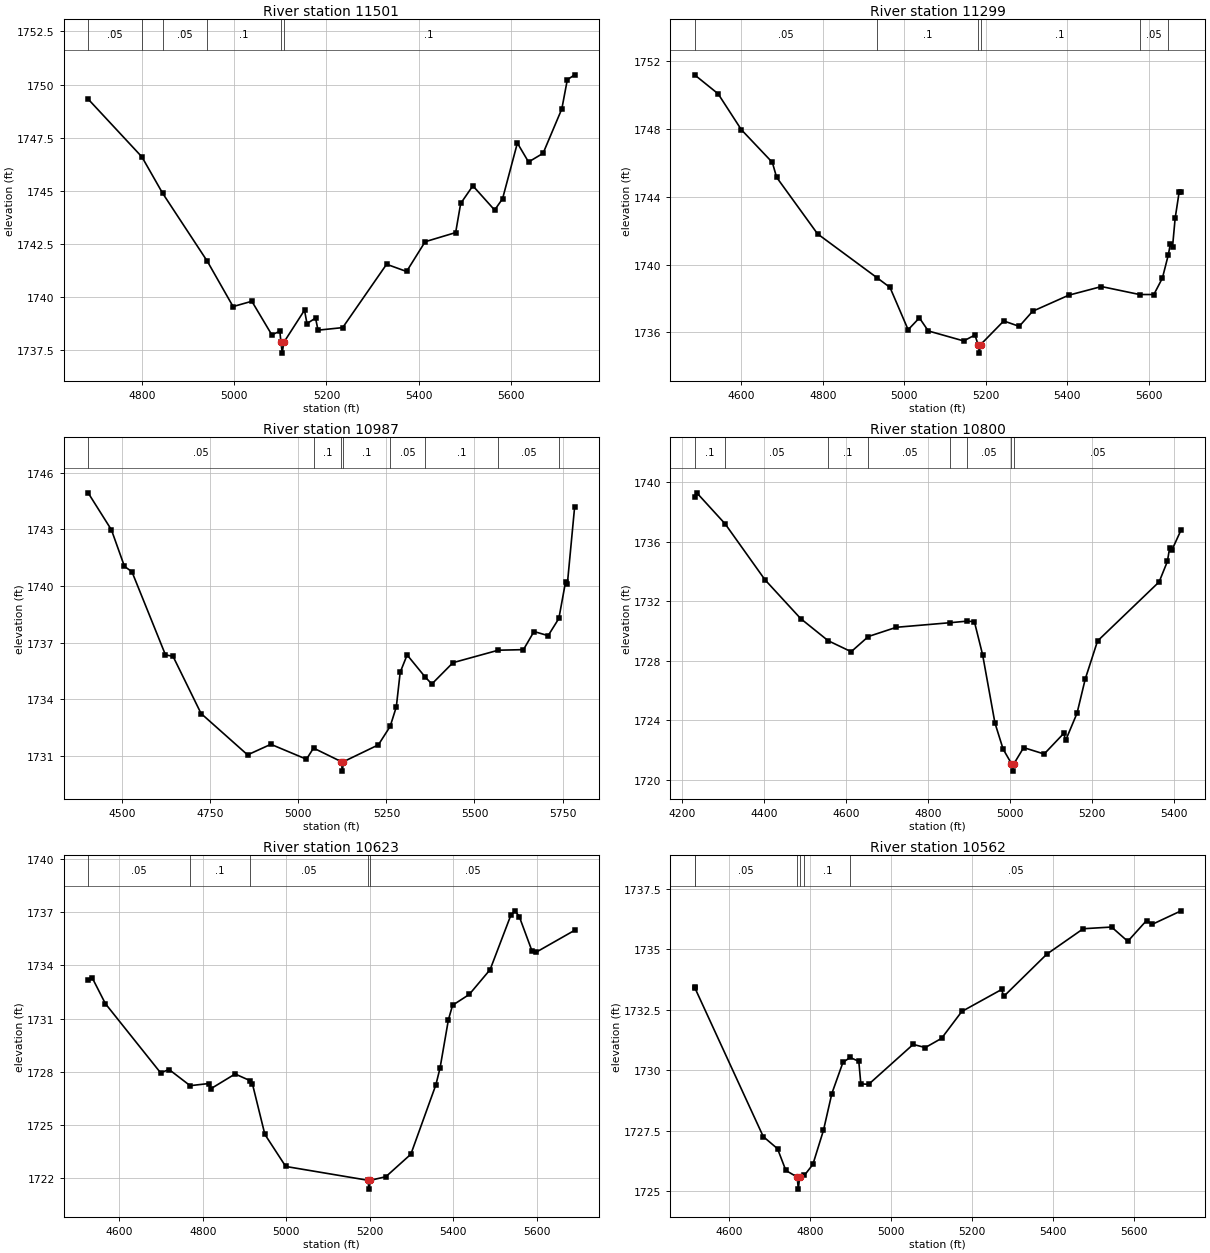
Type RM Length L Ch R = 1 ,11501   ,202,202,202
BEGIN DESCRIPTION:
Mapping XS 8e456ff8
END DESCRIPTION:
XS GIS Cut Line= 3
      2784071.69     10085265.67       2783787.4     10085957.93
      2783880.73     10086248.76
#Sta/Elev= 30
  4683.8 1749.32  4800.3  1746.6  4845.2 1744.89    4942 1741.69  4997.8 1739.56
  5038.4 1739.81  5081.7 1738.23  5099.1  1738.4  5101.5 1737.87  5104.3 1737.37
  5107.5 1737.87  5152.5 1739.39  5157.9 1738.76  5176.4 1739.02  5181.8 1738.45
  5235.2 1738.57  5330.3 1741.55  5373.6 1741.21  5413.8 1742.61  5479.9 1743.04
  5490.8 1744.41  5517.2 1745.24  5564.3  1744.1  5581.5 1744.63  5613.6 1747.25
  5637.8 1746.36  5669.3 1746.77  5709.9 1748.86  5721.8 1750.23  5737.6 1750.46
#Mann= 6 ,-1 , 0
  4683.8     .05       0  4800.3      .1       0  4845.2     .05       0
    4942      .1       0  5101.5     .07       0  5107.5      .1       0
Bank Sta=5101.5,5107.5
XS Rating Curve= 0 ,0
Exp/Cntr=0.3,0.1

Type RM Length L Ch R = 1 ,11299   ,312,312,312
BEGIN DESCRIPTION:
Mapping XS 264f7e00
END DESCRIPTION:
XS GIS Cut Line= 3
      2784138.99     10085170.16      2783830.81     10085276.51
       2783576.9     10086107.68
#Sta/Elev= 30
  4484.9 1751.21  4542.7 1750.09  4599.8 1747.97  4675.9 1746.04  4686.4 1745.16
    4787 1741.82  4932.5 1739.24  4964.9 1738.66  5009.5 1736.16  5037.1 1736.86
    5059 1736.09    5146  1735.5  5173.5 1735.85  5181.4 1735.28  5184.2 1734.78
  5187.4 1735.28  5244.4 1736.68  5282.4 1736.36  5315.2 1737.25    5404  1738.2
  5484.4 1738.71    5578 1738.24  5613.1 1738.24  5634.1 1739.21  5648.8  1740.6
  5653.6 1741.23  5658.9 1741.03  5665.4 1742.74  5675.3  1744.3    5680  1744.3
#Mann= 6 ,-1 , 0
  4484.9     .05       0  4932.5      .1       0  5181.4     .07       0
  5187.4      .1       0    5578     .05       0  5648.8      .1       0
Bank Sta=5181.4,5187.4
XS Rating Curve= 0 ,0
Exp/Cntr=0.3,0.1

Type RM Length L Ch R = 1 ,10987   ,187,187,187
BEGIN DESCRIPTION:
Mapping XS c9889922
END DESCRIPTION:
XS GIS Cut Line= 4
      2783921.61     10084985.51      2783480.32     10085250.62
      2783559.63     10085640.46      2783542.71     10086108.93
#Sta/Elev= 30
    4403 1744.93  4469.2 1742.97  4506.1 1741.04  4527.5 1740.75  4622.7 1736.35
    4644 1736.28  4723.7 1733.25  4855.8 1731.06  4921.9 1731.62    5023 1730.83
    5043 1731.42  5122.1  1730.7  5124.8  1730.2  5128.1  1730.7  5227.1 1731.59
  5260.7 1732.57  5278.1  1733.6  5289.1 1735.43  5308.8 1736.35  5359.2  1735.2
  5378.9 1734.81    5439 1735.94  5567.6  1736.6  5639.1 1736.63  5669.1 1737.59
  5709.2 1737.37  5739.6 1738.28  5758.8 1740.23  5763.8 1740.11  5784.4 1744.18
#Mann= 8 ,-1 , 0
    4403     .05       0    5043      .1       0  5122.1    .035       0
  5128.1      .1       0  5260.7     .05       0  5359.2      .1       0
  5567.6     .05       0  5739.6      .1       0
Bank Sta=5122.1,5128.1
XS Rating Curve= 0 ,0
Exp/Cntr=0.3,0.1

Type RM Length L Ch R = 1 ,10800   ,177,177,177
BEGIN DESCRIPTION:
Mapping XS 966827a9
END DESCRIPTION:
XS GIS Cut Line= 2
      2783413.79     10084592.27      2783321.35     10085777.17
#Sta/Elev= 30
  4229.7 1739.02  4235.1 1739.27  4304.5 1737.18  4401.7 1733.43    4489 1730.82
  4555.9 1729.34  4612.3  1728.6  4654.2 1729.62  4722.7 1730.24  4854.7 1730.55
  4894.2 1730.65  4913.2 1730.62  4933.3  1728.4  4963.4 1723.82  4983.4 1722.06
  5003.9 1721.08  5006.6 1720.58  5009.9 1721.08  5033.6 1722.16  5083.7 1721.73
  5131.4 1723.11  5136.4 1722.66    5164 1724.47  5184.1 1726.77  5214.1 1729.32
  5364.6 1733.29  5384.7 1734.66  5390.3 1735.59  5395.3  1735.4  5418.2 1736.78
#Mann= 8 ,-1 , 0
  4229.7      .1       0  4304.5     .05       0  4555.9      .1       0
  4654.2     .05       0  4854.7      .1       0  4894.2     .05       0
  5003.9    .035       0  5009.9     .05       0
Bank Sta=5003.9,5009.9
XS Rating Curve= 0 ,0
Exp/Cntr=0.3,0.1

Type RM Length L Ch R = 1 ,10623   ,61,61,61
BEGIN DESCRIPTION:
Mapping XS de217723
END DESCRIPTION:
XS GIS Cut Line= 3
      2783356.43     10084779.08      2783239.23     10085130.68
      2783238.12     10085926.36
#Sta/Elev= 30
  4524.8 1733.15  4534.6  1733.3  4566.2 1731.84  4698.4 1727.94    4719 1728.12
  4769.4 1727.21  4813.9 1727.33  4819.2 1727.04  4877.2 1727.87  4913.4 1727.49
  4918.5 1727.33  4948.5 1724.46  4998.5 1722.65  5195.5 1721.87  5198.2 1721.37
  5201.5 1721.87  5238.5 1722.07  5298.5 1723.34  5358.5 1727.26  5368.5 1728.21
  5388.5 1730.93  5398.5 1731.75  5438.5 1732.36  5488.5 1733.76  5538.5 1736.85
  5548.5 1737.08  5558.5 1736.75  5588.5 1734.84  5598.5 1734.74  5691.1 1735.98
#Mann= 5 ,-1 , 0
  4524.8     .05       0  4769.4      .1       0  4913.4     .05       0
  5195.5    .035       0  5201.5     .05       0
Bank Sta=5195.5,5201.5
XS Rating Curve= 0 ,0
Exp/Cntr=0.3,0.1

Type RM Length L Ch R = 1 ,10562   ,88,88,88
BEGIN DESCRIPTION:
Mapping XS 86266430
END DESCRIPTION:
XS GIS Cut Line= 3
      2783275.69     10084745.22      2783184.54     10085102.03
       2783161.1     10085935.34
#Sta/Elev= 30
  4515.2 1733.45  4516.1  1733.4  4684.9 1727.26  4720.1 1726.76  4740.7 1725.86
  4768.7 1725.59  4771.5 1725.09  4774.7 1725.59  4786.5 1725.66  4807.4 1726.11
  4833.6 1727.52  4854.3 1729.04  4881.8 1730.33  4899.6 1730.53  4920.9 1730.37
  4925.9 1729.44  4945.2 1729.42  5055.2 1731.07  5085.2 1730.94  5125.3 1731.32
  5175.3 1732.43  5273.8 1733.34  5278.8 1733.05  5385.4  1734.8  5475.4 1735.85
  5545.4 1735.92  5585.4 1735.33  5631.8 1736.19  5645.5 1736.03  5717.1 1736.59
#Mann= 6 ,-1 , 0
  4515.2      .1       0  4516.1     .05       0  4768.7    .035       0
  4774.7     .05       0  4786.5      .1       0  4899.6     .05       0
Bank Sta=4768.7,4774.7
XS Rating Curve= 0 ,0
Exp/Cntr=0.3,0.1

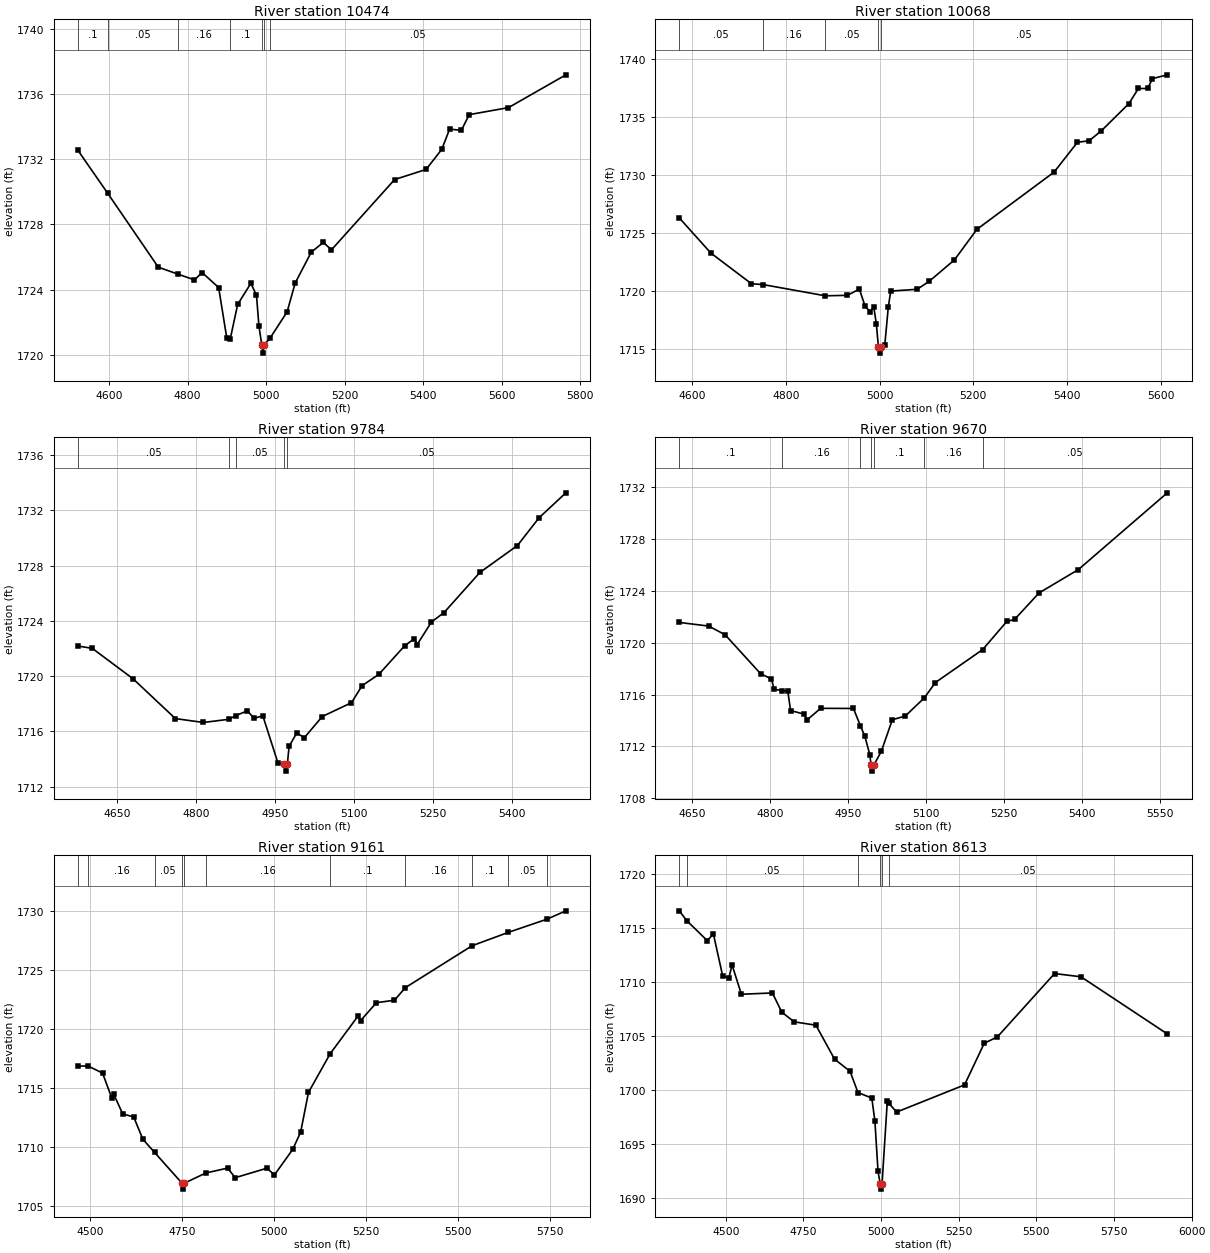
Type RM Length L Ch R = 1 ,10474   ,406,406,406
BEGIN DESCRIPTION:
UNT044 IN NNOGR 24.0
END DESCRIPTION:
XS GIS Cut Line= 3
      2783205.38      10084724.4      2783051.73     10085391.09
      2783038.73     10085949.87
#Sta/Elev= 30
  4520.6 1732.54  4596.4 1729.91  4725.2 1725.38  4775.5 1724.95  4817.5  1724.6
  4836.9 1725.05  4879.1 1724.13  4899.6 1721.06  4908.6 1720.98  4927.6  1723.1
  4961.2 1724.39  4975.5 1723.65  4981.7 1721.77    4989 1720.61  4991.7 1720.11
    4995 1720.61  5010.4 1721.04  5053.5 1722.64  5074.1 1724.41  5115.1  1726.3
  5145.9  1726.9  5166.4 1726.44  5327.4 1730.75  5407.5 1731.37  5447.5  1732.6
  5467.5 1733.84  5497.5 1733.77  5517.5 1734.73  5617.5 1735.16  5763.7 1737.17
#Mann= 7 ,-1 , 0
  4520.6      .1       0  4596.4     .05       0  4775.5     .16       0
  4908.6      .1       0    4989     .07       0    4995      .1       0
  5010.4     .05       0
Bank Sta=4989,4995
XS Rating Curve= 0 ,0
Exp/Cntr=0.3,0.1

Type RM Length L Ch R = 1 ,10068   ,284,284,284
BEGIN DESCRIPTION:
UNT044 IN NNOGR 22.0
END DESCRIPTION:
XS GIS Cut Line= 3
      2782883.95      10084650.3      2782670.41     10085249.26
      2782675.62     10085655.53
#Sta/Elev= 30
    4572  1726.3  4639.3 1723.27    4726 1720.62  4750.7 1720.55  4883.9 1719.58
    4931 1719.62  4956.5 1720.16  4968.5 1718.71  4979.1 1718.21  4987.4 1718.58
  4992.7 1717.17  4997.3 1715.13  5000.1 1714.63  5003.3 1715.13  5010.9 1715.37
  5018.2 1718.57  5023.5 1719.99  5079.8 1720.14  5105.3 1720.82  5159.6 1722.68
  5207.6 1725.32  5372.4 1730.26  5422.4 1732.84  5446.9 1732.96  5472.4 1733.79
  5532.4 1736.18  5552.4 1737.48  5572.4 1737.48  5582.4 1738.33  5614.2 1738.66
#Mann= 5 ,-1 , 0
    4572     .05       0  4750.7     .16       0  4883.9     .05       0
  4997.3    .035       0  5003.3     .05       0
Bank Sta=4997.3,5003.3
XS Rating Curve= 0 ,0
Exp/Cntr=0.3,0.1

Type RM Length L Ch R = 1 ,9784    ,114,114,114
BEGIN DESCRIPTION:
Mapping XS affb4f46
END DESCRIPTION:
XS GIS Cut Line= 5
       2782665.1     10084597.84      2782559.19     10084925.99
      2782465.44     10084998.91      2782448.08     10085148.21
      2782508.84     10085453.73
#Sta/Elev= 30
  4576.1 1722.18  4603.3 1722.01  4680.6 1719.81  4760.9 1716.93    4814 1716.65
  4862.7 1716.88    4875 1717.14  4897.5 1717.49  4910.1 1716.95  4926.8 1717.13
  4955.7 1713.69  4967.2 1713.63    4970 1713.13  4973.2 1713.63  4976.6 1714.92
    4991 1715.89  5005.5 1715.55  5039.5 1717.08  5094.9 1718.08    5115 1719.31
  5146.8 1720.13  5195.6 1722.19  5214.3 1722.72  5219.4 1722.28  5246.6 1723.92
  5270.5  1724.6  5338.4  1727.5  5409.7 1729.45  5450.5 1731.45  5501.5 1733.26
#Mann= 5 ,-1 , 0
  4576.1     .05       0  4862.7     .16       0    4875     .05       0
  4967.2     .04       0  4973.2     .05       0
Bank Sta=4967.2,4973.2
XS Rating Curve= 0 ,0
Exp/Cntr=0.3,0.1

Type RM Length L Ch R = 1 ,9670    ,509,509,509
BEGIN DESCRIPTION:
UNT044 IN NNOGR 21.0
END DESCRIPTION:
XS GIS Cut Line= 3
      2782571.35     10084535.35      2782387.32     10085083.98
      2782475.86     10085432.95
#Sta/Elev= 30
  4625.9 1721.56  4682.2 1721.28  4713.7 1720.62  4782.4  1717.6  4803.1 1717.21
  4808.3 1716.41  4824.2  1716.3  4834.6 1716.24  4839.9 1714.77  4866.2 1714.49
  4871.4 1714.04  4897.7 1714.94  4960.8 1714.93  4974.2  1713.6  4982.8 1712.78
  4992.3 1711.37  4994.6  1710.6  4997.4  1710.1  5000.6  1710.6  5014.5 1711.63
  5035.6 1714.06  5060.7 1714.35  5097.3 1715.75  5118.5 1716.93  5209.5 1719.47
  5255.9 1721.64  5270.8 1721.79  5317.8 1723.83  5393.7 1725.64  5564.6 1731.55
#Mann= 7 ,-1 , 0
  4625.9      .1       0  4824.2     .16       0  4974.2      .1       0
  4994.6     .07       0  5000.6      .1       0  5097.3     .16       0
  5209.5     .05       0
Bank Sta=4994.6,5000.6
XS Rating Curve= 0 ,0
Exp/Cntr=0.3,0.1

Type RM Length L Ch R = 1 ,9161    ,548,548,548
BEGIN DESCRIPTION:
Mapping XS 61b62274
END DESCRIPTION:
XS GIS Cut Line= 4
      2782446.46     10084395.09      2782159.99     10084504.47
      2781816.24     10084915.92      2781800.64     10085399.48
#Sta/Elev= 30
  4467.1 1716.84  4495.1 1716.83    4534 1716.24  4558.7 1714.16    4564 1714.48
  4588.8 1712.78  4618.8 1712.52  4643.5 1710.64  4675.4 1709.52  4750.1 1706.91
  4752.9 1706.41  4756.1 1706.91  4815.2 1707.78    4874 1708.19  4894.8 1707.38
  4980.7 1708.18  5001.5 1707.62    5051 1709.77  5072.5 1711.23  5093.9  1714.6
  5152.7 1717.87  5228.9 1721.08  5235.8 1720.69  5278.7  1722.2  5327.7 1722.41
  5357.6 1723.48  5538.5 1727.02  5636.7 1728.15  5742.1 1729.27  5793.7 1729.98
#Mann= 11 ,-1 , 0
  4467.1      .1       0  4495.1     .16       0  4675.4     .05       0
  4750.1     .07       0  4756.1     .05       0  4815.2     .16       0
  5152.7      .1       0  5357.6     .16       0  5538.5      .1       0
  5636.7     .05       0  5742.1      .1       0
Bank Sta=4750.1,4756.1
XS Rating Curve= 0 ,0
Exp/Cntr=0.3,0.1

Type RM Length L Ch R = 1 ,8613    ,591,591,591
BEGIN DESCRIPTION:
UNT044 IN NNOGR 19.0
END DESCRIPTION:
XS GIS Cut Line= 3
      2782588.16     10084217.67      2781720.11     10084224.62
      2781199.29     10084696.83
#Sta/Elev= 30
  4350.4 1716.62  4373.8 1715.72  4440.1 1713.86  4460.1 1714.46  4490.1 1710.55
  4510.1 1710.42  4520.1 1711.61  4550.1 1708.88  4650.1    1709  4680.1 1707.22
  4720.1 1706.32  4790.1 1706.01  4850.1 1702.86  4900.1 1701.73  4925.5 1699.76
  4970.1 1699.25  4980.1  1697.1  4990.1 1692.45  4997.1  1691.3  4999.9  1690.8
  5003.1  1691.3  5020.1    1699  5024.2 1698.78  5050.1 1697.95  5268.6 1700.47
  5332.1 1704.33  5374.7 1704.93  5558.5  1710.8  5643.7  1710.5  5921.5  1705.2
#Mann= 6 ,-1 , 0
  4350.4      .1       0  4373.8     .05       0  4925.5      .1       0
  4997.1     .07       0  5003.1      .1       0  5024.2     .05       0
Bank Sta=4997.1,5003.1
XS Rating Curve= 0 ,0
Exp/Cntr=0.3,0.1

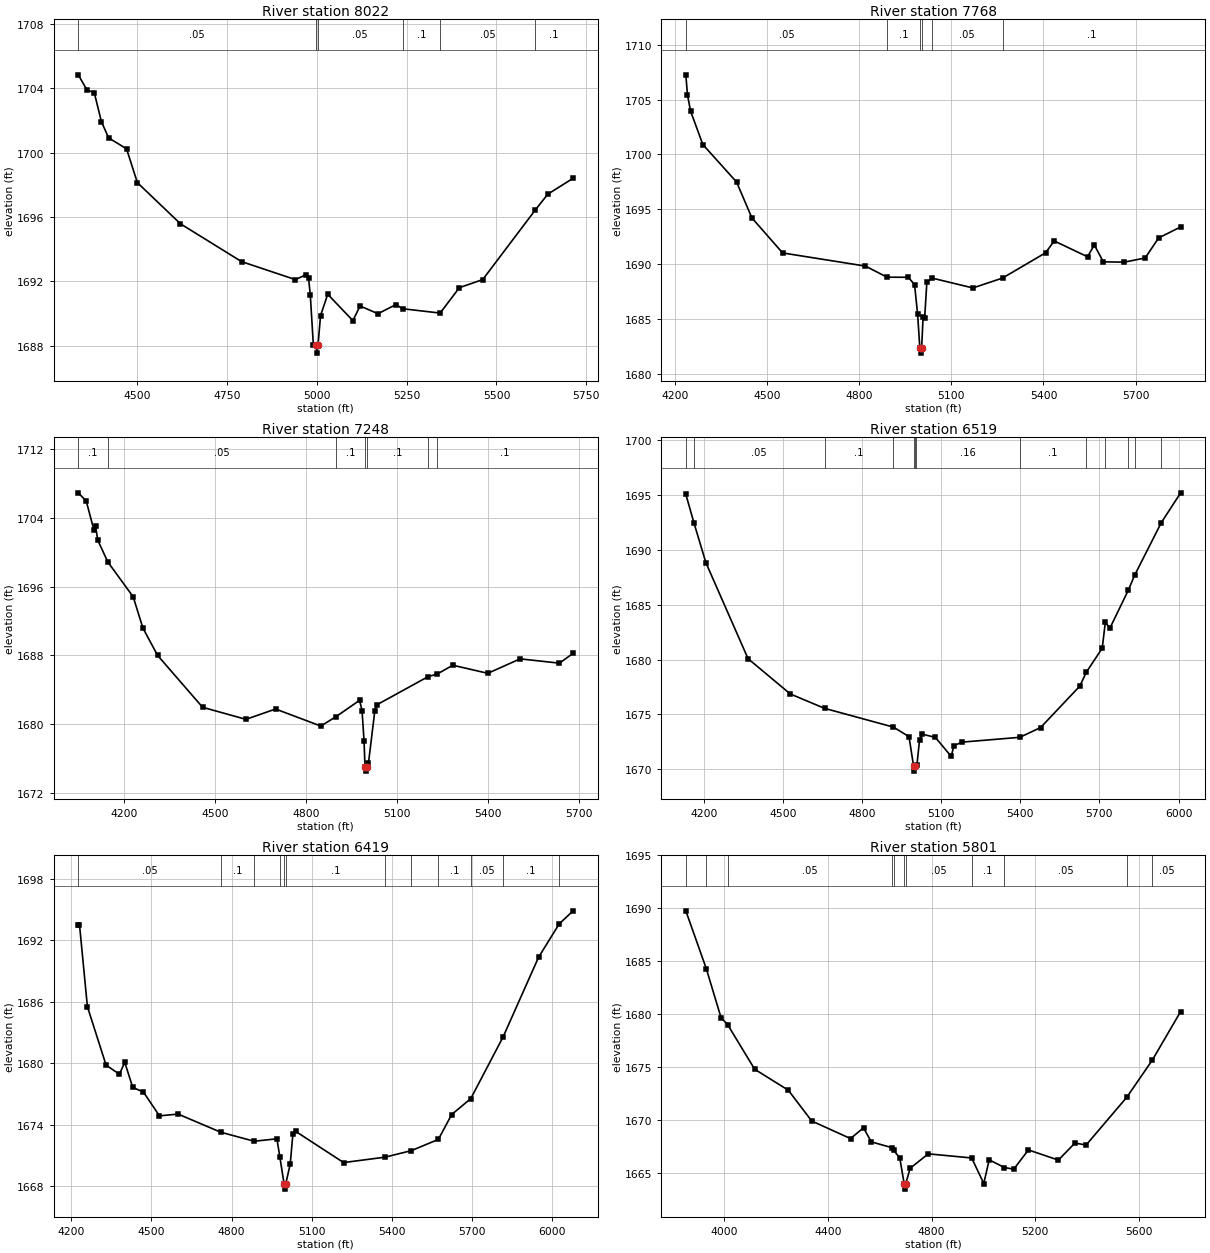
Type RM Length L Ch R = 1 ,8022    ,254,254,254
BEGIN DESCRIPTION:
UNT044 IN NNOGR 17.0
END DESCRIPTION:
XS GIS Cut Line= 3
      2782332.81     10083708.97      2781304.16      10083724.6
      2781166.12     10084044.95
#Sta/Elev= 30
  4335.9 1704.83  4360.2 1703.88  4380.3 1703.73  4400.3 1701.92  4420.3 1700.91
  4470.3 1700.23  4500.3 1698.13  4620.3 1695.57  4790.3 1693.22  4940.3  1692.1
  4970.3 1692.41  4976.8 1692.22  4981.8 1691.15  4990.3 1688.04  4997.3 1688.03
  5000.1 1687.53  5003.3 1688.03  5010.3 1689.86  5030.3 1691.19  5100.3 1689.55
  5120.3 1690.46  5170.3 1689.98  5220.3 1690.55  5238.5 1690.29  5343.3 1690.02
  5396.8  1691.6  5461.7  1692.1  5607.9 1696.42  5642.9 1697.41  5713.5  1698.4
#Mann= 6 ,-1 , 0
  4335.9     .05       0  4997.3    .035       0  5003.3     .05       0
  5238.5      .1       0  5343.3     .05       0  5607.9      .1       0
Bank Sta=4997.3,5003.3
XS Rating Curve= 0 ,0
Exp/Cntr=0.3,0.1

Type RM Length L Ch R = 1 ,7768    ,520,520,520
BEGIN DESCRIPTION:
Mapping XS e34fbcc5
END DESCRIPTION:
XS GIS Cut Line= 3
      2782233.85     10083586.58      2781069.78     10083604.81
      2780663.57      10083794.9
#Sta/Elev= 30
  4234.5 1707.25  4239.9 1705.42  4249.9 1703.95  4289.9  1700.9  4399.9 1697.48
  4449.9 1694.21  4549.9 1691.02    4820 1689.82  4890.3 1688.81    4960  1688.8
    4980 1688.12    4990 1685.41    4997 1682.39  4999.7 1681.89    5003 1682.39
  5007.8 1685.19  5012.8 1685.09    5020 1688.33  5036.7 1688.73    5170 1687.83
  5266.6 1688.73  5406.8 1691.03  5435.2 1692.11  5543.7 1690.67  5565.8 1691.75
    5595 1690.21  5663.6 1690.18  5731.4 1690.56  5775.5 1692.39  5847.2 1693.39
#Mann= 6 ,-1 , 0
  4234.5     .05       0  4890.3      .1       0    4997     .07       0
    5003      .1       0  5036.7     .05       0  5266.6      .1       0
Bank Sta=4997,5003
XS Rating Curve= 0 ,0
Exp/Cntr=0.3,0.1

Type RM Length L Ch R = 1 ,7248    ,729,729,729
BEGIN DESCRIPTION:
UNT044 IN NNOGR 16.0
END DESCRIPTION:
XS GIS Cut Line= 3
      2782108.95     10082780.19      2781372.88     10083044.06
       2780685.4     10083544.05
#Sta/Elev= 30
  4048.9  1706.9  4075.1 1705.94  4100.5 1702.58  4105.8 1703.03  4113.2 1701.39
  4146.2 1698.87    4230 1694.81  4261.9 1691.19  4310.5    1688  4458.9 1681.97
  4601.8 1680.57  4699.6 1681.77  4848.7 1679.79  4898.9 1680.88  4976.6 1682.78
  4984.7 1681.59  4991.3 1678.08  4994.5 1675.05  4997.3 1674.55  5000.5 1675.05
    5006  1675.5  5026.9 1681.58  5034.1 1682.27  5202.4 1685.53  5231.6 1685.82
  5284.2 1686.86  5399.4 1685.92    5506  1687.6  5635.8  1687.1  5680.9 1688.25
#Mann= 7 ,-1 , 0
  4048.9      .1       0  4146.2     .05       0  4898.9      .1       0
  4994.5     .07       0  5000.5      .1       0  5202.4     .05       0
  5231.6      .1       0
Bank Sta=4994.5,5000.5
XS Rating Curve= 0 ,0
Exp/Cntr=0.3,0.1

Type RM Length L Ch R = 1 ,6519    ,100,100,100
BEGIN DESCRIPTION:
UNT044 IN NNOGR 14.0
END DESCRIPTION:
XS GIS Cut Line= 3
      2781874.48     10082485.02      2780535.93      10082474.6
      2780048.94     10082701.16
#Sta/Elev= 30
  4132.4 1695.06  4162.9 1692.48  4208.4 1688.83  4368.4 1680.08  4528.4 1676.87
  4658.1 1675.56  4919.2 1673.85  4978.4 1672.98  4995.4 1670.34  4998.2 1669.84
  5001.4 1670.34  5003.7 1670.35  5008.4 1670.38  5018.4 1672.71  5028.4 1673.21
  5078.4 1672.91  5138.4 1671.18  5148.4 1672.15  5178.4 1672.48  5398.3 1672.92
  5477.2 1673.81  5625.6 1677.58  5650.5 1678.85  5710.8 1681.04  5722.4 1683.38
    5740 1682.87    5810 1686.34  5833.5 1687.68  5934.5 1692.47  6008.1 1695.19
#Mann= 13 ,-1 , 0
  4132.4      .1       0  4162.9     .05       0  4658.1      .1       0
  4919.2     .05       0  4995.4    .035       0  5001.4     .05       0
  5003.7     .16       0  5398.3      .1       0  5650.5     .05       0
  5722.4      .1       0    5810     .05       0  5833.5      .1       0
  5934.5     .05       0
Bank Sta=4995.4,5001.4
XS Rating Curve= 0 ,0
Exp/Cntr=0.3,0.1

Type RM Length L Ch R = 1 ,6419    ,618,618,618
BEGIN DESCRIPTION:
Mapping XS 362c0f13
END DESCRIPTION:
XS GIS Cut Line= 3
      2781762.53     10082388.66      2780423.95     10082375.64
      2779993.16     10082658.51
#Sta/Elev= 30
  4225.9 1693.53  4230.4 1693.53    4260 1685.53    4330 1679.82    4380 1678.93
    4400 1680.09    4430 1677.64    4470 1677.19    4530 1674.87    4600 1675.04
  4759.9 1673.27    4885 1672.39    4970 1672.63    4981 1670.88    4997 1668.22
  4999.7 1667.72    5003 1668.22    5020 1670.17    5030 1673.12    5040 1673.36
    5220 1670.31  5375.6 1670.84  5474.3 1671.48  5574.9 1672.57  5624.9    1675
  5696.4 1676.55  5817.9 1682.59  5950.4 1690.34  6027.8  1693.6  6079.9 1694.87
#Mann= 12 ,-1 , 0
  4225.9     .05       0  4759.9      .1       0    4885     .05       0
    4981      .1       0    4997     .07       0    5003      .1       0
  5375.6     .16       0  5474.3     .05       0  5574.9      .1       0
  5696.4     .05       0  5817.9      .1       0  6027.8     .05       0
Bank Sta=4997,5003
XS Rating Curve= 0 ,0
Exp/Cntr=0.3,0.1

Type RM Length L Ch R = 1 ,5801    ,627,627,627
BEGIN DESCRIPTION:
UNT044 IN NNOGR 13.0
END DESCRIPTION:
XS GIS Cut Line= 3
      2781824.29     10081863.51      2780789.55     10081863.51
      2780075.45     10082369.61
#Sta/Elev= 30
  3851.4 1689.76  3930.3 1684.31  3987.2 1679.69  4012.8 1679.02  4117.2 1674.81
  4247.2 1672.83  4337.2 1669.93  4487.2 1668.27  4537.2 1669.29  4567.2 1667.96
  4645.8 1667.42  4653.4 1667.17  4677.2 1666.44  4694.2    1664    4697  1663.5
  4700.2    1664  4717.2 1665.47  4787.2 1666.83  4954.7 1666.44  5001.4 1664.03
  5022.3 1666.26  5081.4 1665.54  5117.1 1665.38  5173.7  1667.2  5289.4 1666.24
  5353.2 1667.85  5396.4 1667.66  5553.1 1672.16  5651.6 1675.66  5761.4 1680.26
#Mann= 11 ,-1 , 0
  3851.4     .05       0  3930.3      .1       0  4012.8     .05       0
  4645.8      .1       0  4653.4     .05       0  4694.2     .07       0
  4700.2     .05       0  4954.7      .1       0  5081.4     .05       0
  5553.1      .1       0  5651.6     .05       0
Bank Sta=4694.2,4700.2
XS Rating Curve= 0 ,0
Exp/Cntr=0.3,0.1

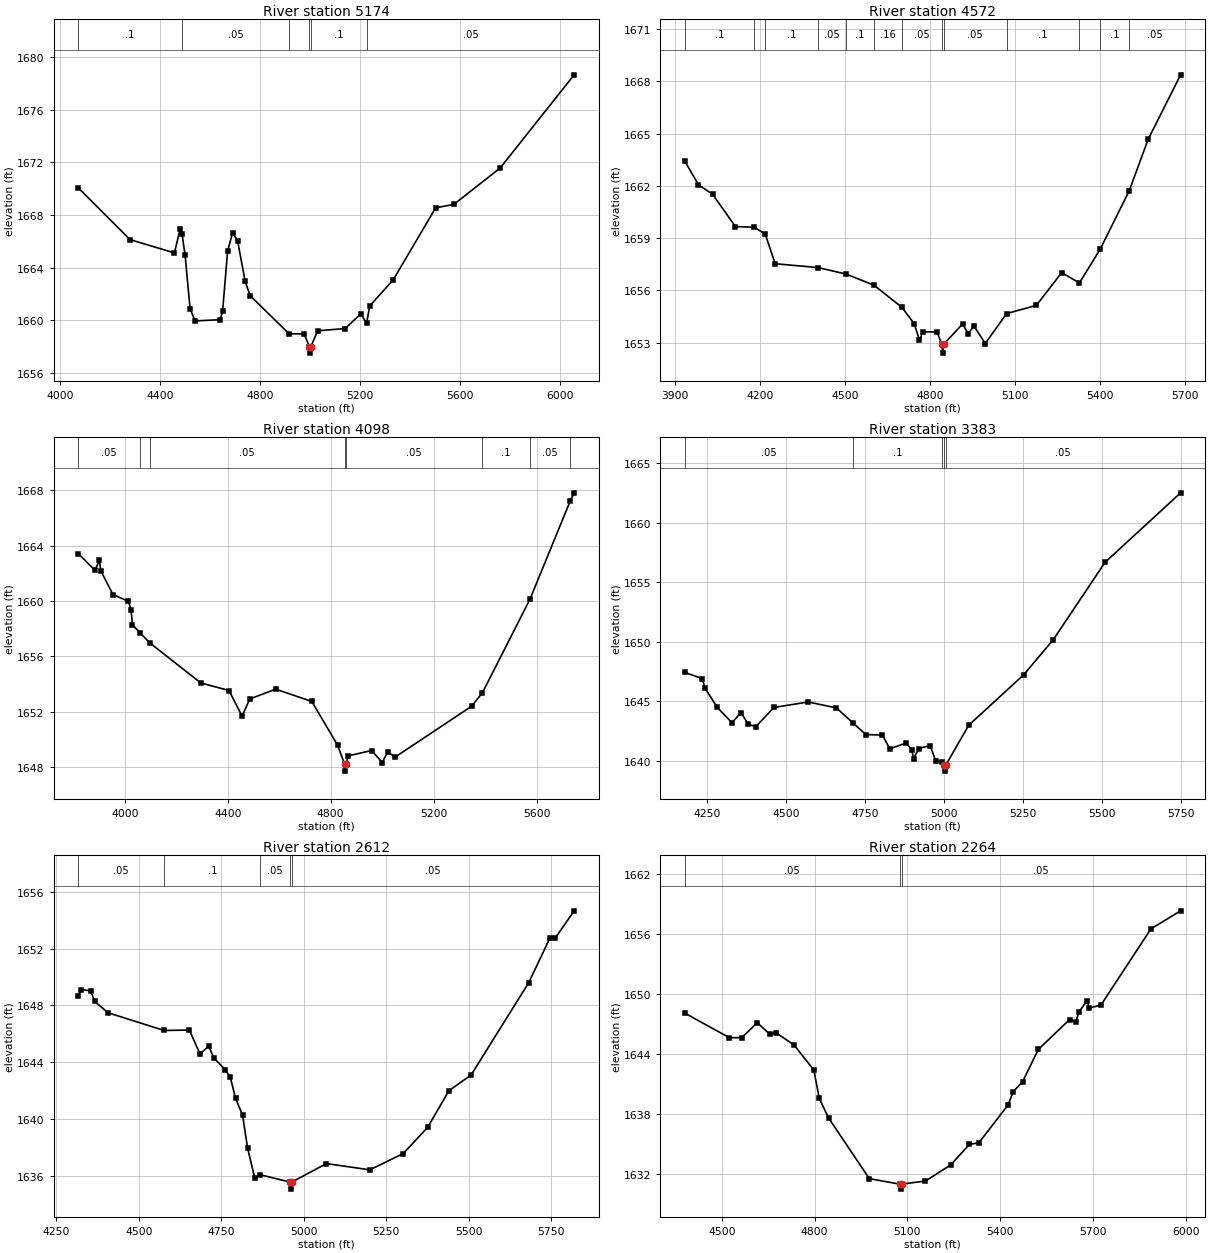
Type RM Length L Ch R = 1 ,5174    ,602,602,602
BEGIN DESCRIPTION:
UNT044 IN NNOGR 12.0
END DESCRIPTION:
XS GIS Cut Line= 3
      2781345.11     10081516.29      2780268.72     10081578.79
      2779546.47     10082127.41
#Sta/Elev= 30
  4072.7 1670.05  4279.7 1666.12  4457.5 1665.11    4480  1666.9  4487.9 1666.54
  4500.1 1664.95  4520.1 1660.86  4540.1 1659.94  4640.3 1660.03  4650.3 1660.68
  4670.4 1665.25  4690.4 1666.65  4710.4 1666.03  4740.5 1662.96  4760.5 1661.86
  4916.4 1658.96  4976.7 1658.95  4997.9 1657.99  5000.7 1657.49  5003.9 1657.99
    5031 1659.19  5141.1 1659.36  5204.1 1660.48  5226.8 1659.75  5239.4 1661.08
    5333 1663.05  5503.6 1668.54  5576.3  1668.8  5761.4 1671.56  6057.9 1678.65
#Mann= 6 ,-1 , 0
  4072.7      .1       0  4487.9     .05       0  4916.4      .1       0
  4997.9     .07       0  5003.9      .1       0  5226.8     .05       0
Bank Sta=4997.9,5003.9
XS Rating Curve= 0 ,0
Exp/Cntr=0.3,0.1

Type RM Length L Ch R = 1 ,4572    ,474,474,474
BEGIN DESCRIPTION:
UNT044 IN NNOGR 10.0
END DESCRIPTION:
XS GIS Cut Line= 3
      2781136.76     10081078.79      2779838.16     10081141.29
      2779402.05     10081245.12
#Sta/Elev= 30
  3934.8 1663.42  3983.1 1662.06  4033.2 1661.51  4113.3 1659.66  4180.1 1659.62
  4218.3 1659.24  4253.5 1657.53  4404.2 1657.31  4502.9 1656.94  4601.9  1656.3
  4700.9 1655.02    4744 1654.08  4762.4 1653.14  4774.1 1653.62  4824.1 1653.62
  4841.1  1652.9  4843.9  1652.4  4847.1  1652.9  4914.2 1654.07  4934.2 1653.52
  4954.3 1653.96  4994.3 1652.95  5069.7 1654.67  5174.5 1655.14  5263.7 1657.02
  5326.3 1656.43  5399.5 1658.36    5502 1661.72    5569 1664.68  5683.2 1668.37
#Mann= 13 ,-1 , 0
  3934.8      .1       0  4180.1     .05       0  4218.3      .1       0
  4404.2     .05       0  4502.9      .1       0  4601.9     .16       0
  4700.9     .05       0  4841.1    .035       0  4847.1     .05       0
  5069.7      .1       0  5326.3     .05       0  5399.5      .1       0
    5502     .05       0
Bank Sta=4841.1,4847.1
XS Rating Curve= 0 ,0
Exp/Cntr=0.3,0.1

Type RM Length L Ch R = 1 ,4098    ,715,715,715
BEGIN DESCRIPTION:
UNT044 IN NNOGR 9.0
END DESCRIPTION:
XS GIS Cut Line= 3
       2781282.6     10080745.45      2780233.99     10080662.12
      2779381.61     10080856.16
#Sta/Elev= 30
  3819.7 1663.43    3884 1662.22  3901.8 1662.93  3906.8 1662.19  3954.3 1660.46
  4014.4 1659.97  4024.5 1659.35  4030.1 1658.27  4059.6 1657.69  4096.4 1656.98
  4295.3 1654.07  4405.1 1653.52  4455.8 1651.67  4485.9 1652.91  4586.2 1653.62
  4726.7 1652.73    4827 1649.56  4854.1 1648.19  4856.8 1647.69  4860.1 1648.19
  4866.9 1648.79  4959.3 1649.18  5000.4 1648.31  5020.9 1649.07  5051.6 1648.72
  5347.9 1652.39  5389.4 1653.36  5574.3 1660.13  5730.9 1667.25  5745.8 1667.82
#Mann= 8 ,-1 , 0
  3819.7     .05       0  4059.6      .1       0  4096.4     .05       0
  4854.1    .035       0  4860.1     .05       0  5389.4      .1       0
  5574.3     .05       0  5730.9      .1       0
Bank Sta=4854.1,4860.1
XS Rating Curve= 0 ,0
Exp/Cntr=0.3,0.1

Type RM Length L Ch R = 1 ,3383    ,771,771,771
BEGIN DESCRIPTION:
UNT044 IN NNOGR 7.0
END DESCRIPTION:
XS GIS Cut Line= 2
       2780546.5     10079787.12      2779109.35     10080418.91
#Sta/Elev= 30
  4180.2 1647.44    4236 1646.92  4243.6 1646.15  4282.7 1644.51  4329.4 1643.22
  4358.2 1644.06  4381.6 1643.08  4404.9 1642.88  4462.5  1644.5  4571.3 1644.96
  4660.2 1644.46  4711.9 1643.22  4753.6 1642.22  4805.8 1642.18  4829.1 1641.03
  4881.3 1641.51    4899 1640.94  4904.6  1640.2  4920.9 1641.05  4956.8  1641.3
  4974.7 1640.02  4995.3 1639.91  5000.5 1639.65  5003.3 1639.15  5006.5 1639.65
    5079    1643  5253.4 1647.25  5346.8 1650.19  5510.7 1656.69  5750.1 1662.53
#Mann= 5 ,-1 , 0
  4180.2     .05       0  4711.9      .1       0  4995.3     .05       0
  5000.5    .035       0  5006.5     .05       0
Bank Sta=5000.5,5006.5
XS Rating Curve= 0 ,0
Exp/Cntr=0.3,0.1

Type RM Length L Ch R = 1 ,2612    ,348,348,348
BEGIN DESCRIPTION:
UNT044 IN NNOGR 6.0
END DESCRIPTION:
XS GIS Cut Line= 3
      2780284.25     10079186.99      2779900.12     10079286.82
      2778953.45     10079858.72
#Sta/Elev= 30
    4317 1648.67    4326 1649.11    4354 1649.03  4366.6 1648.28  4407.1 1647.48
    4577 1646.23  4653.6 1646.26  4685.8 1644.57  4712.2 1645.13  4727.5  1644.3
  4762.6 1643.46  4777.8 1642.92  4793.4 1641.45  4814.7 1640.27  4830.2 1637.92
  4851.6 1635.84  4869.1 1636.05  4958.2 1635.54  4960.9 1635.04  4964.2 1635.54
  5068.9 1636.84  5200.9  1636.4  5301.8 1637.55  5375.5 1639.39  5440.2 1641.98
  5507.5 1643.09  5682.1  1649.6  5746.2 1652.74  5761.7 1652.72  5819.9 1654.67
#Mann= 5 ,-1 , 0
    4317     .05       0    4577      .1       0  4869.1     .05       0
  4958.2    .035       0  4964.2     .05       0
Bank Sta=4958.2,4964.2
XS Rating Curve= 0 ,0
Exp/Cntr=0.3,0.1

Type RM Length L Ch R = 1 ,2264    ,138,138,138
BEGIN DESCRIPTION:
Mapping XS c15a9d75
END DESCRIPTION:
XS GIS Cut Line= 3
      2780152.21     10079076.51      2779735.51     10079102.56
      2778563.61     10079284.85
#Sta/Elev= 30
  4380.5  1648.1  4524.5 1645.65  4564.6 1645.65  4614.7 1647.14  4654.8 1646.02
  4674.8 1646.15  4733.3 1644.94    4798 1642.41  4815.3 1639.58  4845.6 1637.62
  4977.2 1631.56  5075.4 1631.01  5078.1 1630.51  5081.4 1631.01  5158.9 1631.32
  5240.3 1632.93    5301 1634.98  5331.4 1635.14  5425.6 1638.91  5442.7 1640.25
  5473.1 1641.26  5523.7 1644.47  5624.9 1647.46  5645.1 1647.24  5655.2 1648.24
  5682.2 1649.36  5687.3 1648.61  5726.1  1648.9    5888 1656.53    5984 1658.33
#Mann= 3 ,-1 , 0
  4380.5     .05       0  5075.4    .035       0  5081.4     .05       0
Bank Sta=5075.4,5081.4
XS Rating Curve= 0 ,0
Exp/Cntr=0.3,0.1