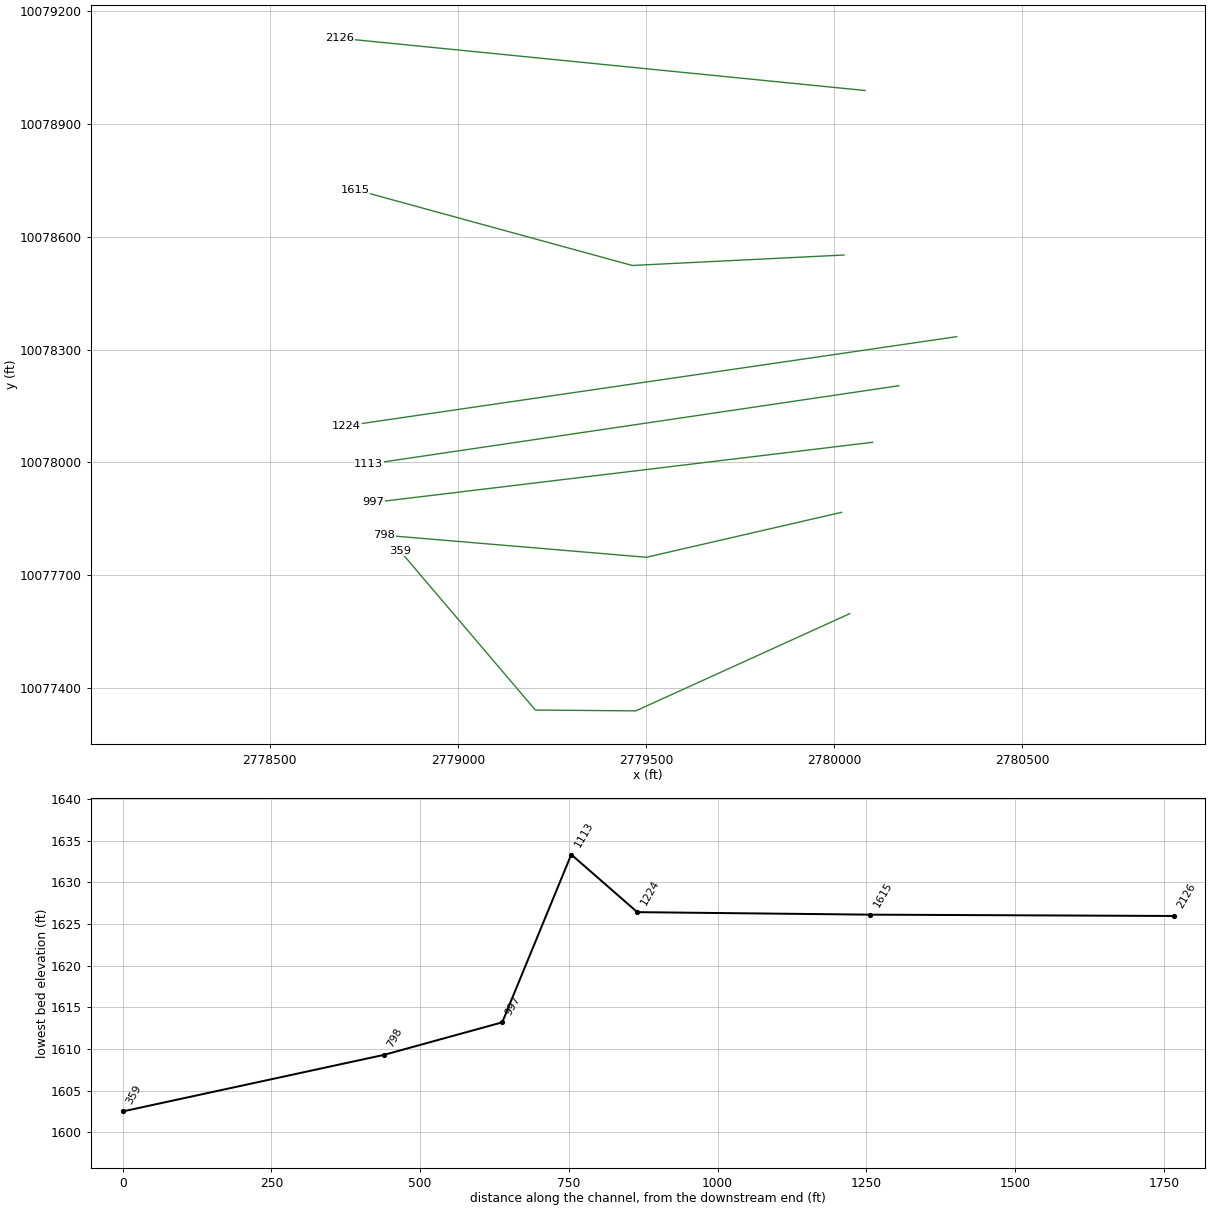
HEC-RAS study UNT044 IN NNOGR.prj: UNT044 IN NNOGR Base Level Engineering

--- UNT044 IN NNOGR.g01 (geometry) --- (continued)

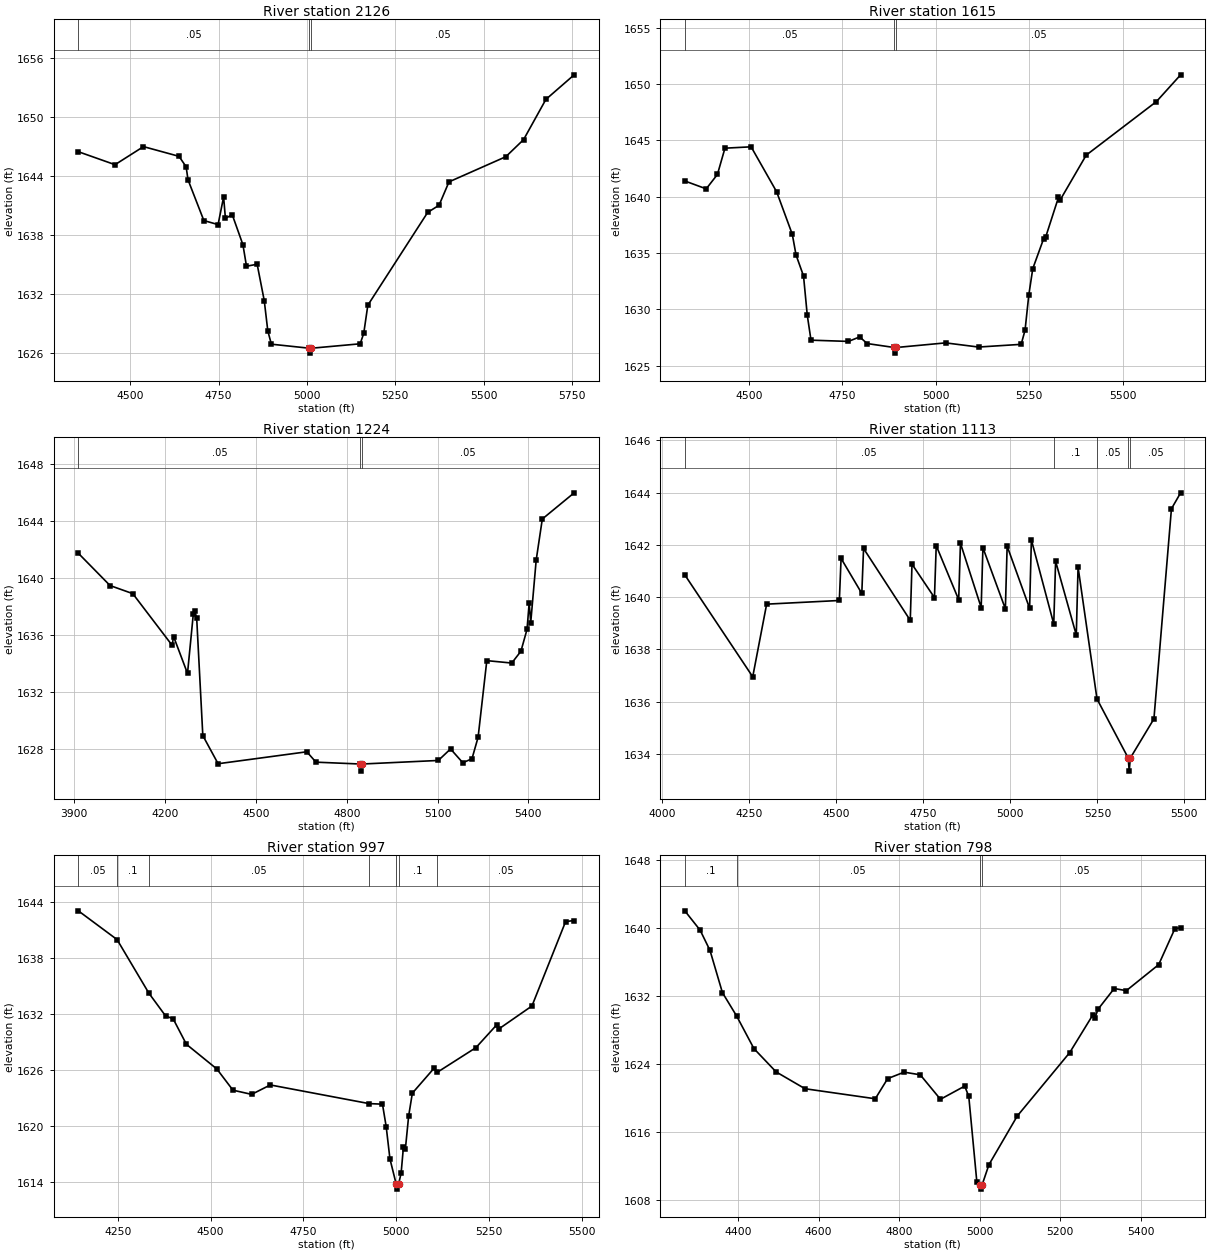
Type RM Length L Ch R = 1 ,2126    ,511,511,511
BEGIN DESCRIPTION:
UNT044 IN NNOGR 5.0
END DESCRIPTION:
XS GIS Cut Line= 2
      2780081.86     10078987.97      2778686.06     10079126.86
#Sta/Elev= 30
  4353.2 1646.47    4457 1645.15  4537.5 1646.99    4638    1646  4658.1 1644.94
  4663.5 1643.61  4708.3 1639.46  4748.5 1639.05  4764.2 1641.86  4769.3 1639.69
  4788.7 1640.05  4818.9 1636.99  4828.9 1634.81  4859.1 1635.01  4879.2  1631.3
  4889.2 1628.23  4899.3 1626.87  5006.8 1626.46  5009.6 1625.96  5012.8 1626.46
  5150.5 1626.91  5160.6 1627.97  5172.2 1630.84  5341.5 1640.29  5373.7 1641.02
  5401.8  1643.4  5562.5 1645.96  5612.8  1647.7    5676  1651.8  5755.9  1654.3
#Mann= 3 ,-1 , 0
  4353.2     .05       0  5006.8    .033       0  5012.8     .05       0
Bank Sta=5006.8,5012.8
XS Rating Curve= 0 ,0
Exp/Cntr=0.3,0.1

Type RM Length L Ch R = 1 ,1615    ,391,391,391
BEGIN DESCRIPTION:
UNT044 IN NNOGR 4.0
END DESCRIPTION:
XS GIS Cut Line= 3
      2780025.69     10078551.01      2779463.16     10078523.23
      2778727.03     10078724.63
#Sta/Elev= 30
  4328.7  1641.4    4386  1640.7    4416 1641.98  4436.1 1644.31  4506.1 1644.43
  4574.4 1640.44  4616.3 1636.66  4626.3 1634.83  4646.3 1632.97  4656.3 1629.49
  4666.3 1627.27  4766.5 1627.16  4796.5 1627.56  4816.5 1626.97  4888.8 1626.62
  4891.5 1626.12  4894.8 1626.62  5026.4 1627.03  5114.5 1626.66  5228.5  1626.9
  5238.9 1628.15    5249 1631.29  5259.6 1633.62  5288.6 1636.27  5293.8 1636.39
  5328.3 1639.94  5333.5 1639.75  5402.5 1643.69  5590.5 1648.45  5655.1 1650.82
#Mann= 3 ,-1 , 0
  4328.7     .05       0  4888.8    .033       0  4894.8     .05       0
Bank Sta=4888.8,4894.8
XS Rating Curve= 0 ,0
Exp/Cntr=0.3,0.1

Type RM Length L Ch R = 1 ,1224    ,111,111,111
BEGIN DESCRIPTION:
UNT044 IN NNOGR 3.0
END DESCRIPTION:
XS GIS Cut Line= 2
      2780325.43     10078334.12      2778704.39     10078097.58
#Sta/Elev= 30
  3913.3 1641.74  4018.1 1639.47  4093.2  1638.9  4223.1 1635.27  4228.1 1635.88
    4274 1633.29  4293.1 1637.45  4298.1  1637.7  4304.4 1637.16  4324.6 1628.92
  4375.1 1626.94  4668.2 1627.78  4698.5 1627.05    4845 1626.92  4847.8 1626.42
    4851 1626.92  5102.7 1627.17  5143.1 1627.98  5183.6 1627.01  5213.9 1627.29
  5234.1  1628.8  5262.9 1634.19  5345.3 1634.02  5375.6 1634.85  5395.8 1636.39
  5402.9 1638.25    5408 1636.87  5426.1 1641.27  5446.3 1644.15  5551.5 1645.99
#Mann= 3 ,-1 , 0
  3913.3     .05       0    4845    .033       0    4851     .05       0
Bank Sta=4845,4851
XS Rating Curve= 0 ,0
Exp/Cntr=0.3,0.1

Type RM Length L Ch R = 1 ,1113    ,116,116,116
BEGIN DESCRIPTION:
Mapping XS 89889911
END DESCRIPTION:
XS GIS Cut Line= 2
      2780171.49     10078203.79      2778762.59     10077995.57
#Sta/Elev= 30
  4064.9 1640.85    4260 1636.95    4300 1639.73  4508.8 1639.87  4513.8 1641.48
  4573.3 1640.14  4578.4 1641.86  4712.5 1639.11  4717.5 1641.26    4782 1639.98
  4787.1 1641.97  4851.6  1639.9  4856.7 1642.06  4916.2  1639.6  4921.2 1641.89
  4985.7 1639.55  4990.8 1641.95  5055.3 1639.57  5060.4 1642.19  5124.7 1638.97
    5130 1641.37  5189.4 1638.55  5194.5 1641.15  5248.9  1636.1  5338.6 1633.84
  5341.4 1633.34  5344.6 1633.84  5412.4 1635.34  5462.7 1643.38  5489.1 1643.99
#Mann= 5 ,-1 , 0
  4064.9     .05       0  5124.7      .1       0  5248.9     .05       0
  5338.6    .033       0  5344.6     .05       0
Bank Sta=5338.6,5344.6
XS Rating Curve= 0 ,0
Exp/Cntr=0.3,0.1

Type RM Length L Ch R = 1 ,997     ,199,199,199
BEGIN DESCRIPTION:
UNT044 IN NNOGR 2.0
END DESCRIPTION:
XS GIS Cut Line= 2
      2780102.04     10078053.61      2778775.62     10077893.89
#Sta/Elev= 30
  4143.6 1643.03  4247.9 1639.95  4333.7  1634.2  4378.9 1631.75    4399 1631.46
  4434.8 1628.72  4516.9 1626.07  4560.2  1623.8  4610.5 1623.35  4660.9 1624.36
    4927 1622.36  4963.1  1622.3  4973.1  1619.9  4983.2 1616.44  5000.3 1613.69
  5003.1 1613.19  5006.3 1613.69  5013.4 1614.92  5019.6 1617.72  5024.7 1617.44
  5033.6 1621.02  5043.6 1623.48  5101.8 1626.14  5110.1  1625.7  5214.9 1628.36
    5271 1630.81  5276.1 1630.35  5365.9 1632.83  5456.6 1641.88  5479.6 1641.99
#Mann= 7 ,-1 , 0
  4143.6     .05       0  4247.9      .1       0  4333.7     .05       0
    4927      .1       0  5000.3     .07       0  5006.3      .1       0
  5110.1     .05       0
Bank Sta=5000.3,5006.3
XS Rating Curve= 0 ,0
Exp/Cntr=0.3,0.1

Type RM Length L Ch R = 1 ,798     ,439,439,439
BEGIN DESCRIPTION:
Mapping XS 0fe45c83
END DESCRIPTION:
XS GIS Cut Line= 3
      2780019.46     10077867.54      2779500.82     10077748.19
      2778804.18     10077806.78
#Sta/Elev= 30
  4267.8 1642.02  4305.9 1639.74  4330.4 1637.36  4361.2  1632.4  4396.6 1629.64
  4439.5 1625.81  4494.6 1623.07  4566.4 1621.09  4740.8 1619.91  4771.6 1622.28
  4812.4 1623.04  4852.5 1622.73  4902.7 1619.85  4962.9  1621.4    4973 1620.19
    4993 1610.15  5000.1 1609.78  5002.8 1609.28  5006.1 1609.78  5023.1 1612.16
  5093.4 1617.88  5223.8 1625.35  5281.4  1629.8  5286.4 1629.45  5294.1 1630.45
  5334.2 1632.88  5364.3 1632.63  5444.6 1635.69  5484.8 1639.92  5499.1 1640.03
#Mann= 4 ,-1 , 0
  4267.8      .1       0  4396.6     .05       0  5000.1    .035       0
  5006.1     .05       0
Bank Sta=5000.1,5006.1
XS Rating Curve= 0 ,0
Exp/Cntr=0.3,0.1

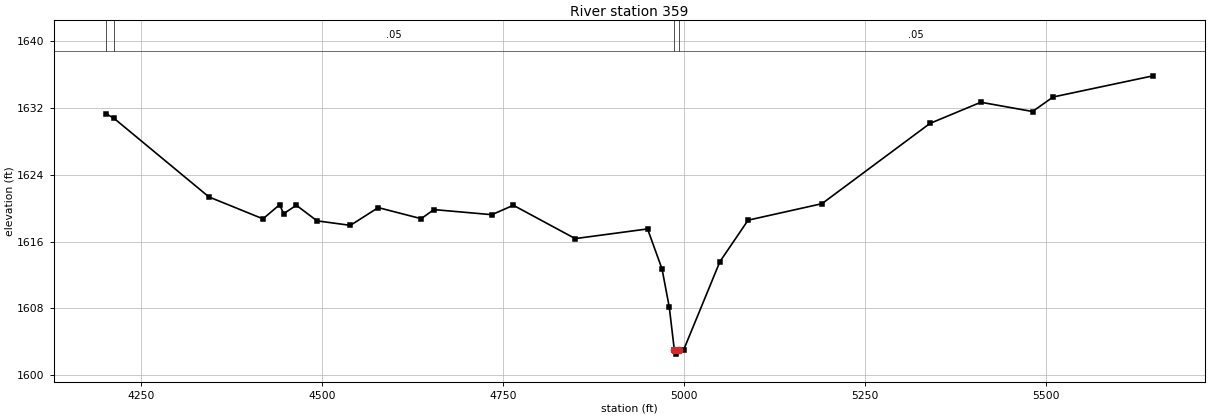
Type RM Length L Ch R = 1 ,359     ,0,0,0
BEGIN DESCRIPTION:
UNT044 IN NNOGR 1.0
END DESCRIPTION:
XS GIS Cut Line= 4
       2780041.2     10077598.46       2779472.6      10077340.2
      2779205.68     10077342.37      2778845.42     10077765.57
#Sta/Elev= 30
  4201.4 1631.34  4212.6 1630.78  4343.8 1621.35  4418.5 1618.72  4441.5 1620.42
    4447 1619.34  4464.6 1620.35  4493.2 1618.48  4539.3 1617.94  4577.8 1620.07
  4637.1 1618.74  4654.7 1619.83  4734.9 1619.22  4764.5 1620.35    4850 1616.35
    4950 1617.51    4970  1612.7    4980 1608.13    4987 1602.99  4989.8 1602.49
    4993 1602.99    5000 1603.03    5050 1613.59  5088.9 1618.56    5191 1620.54
  5340.3 1630.17  5410.6 1632.71    5482  1631.6  5510.5 1633.34  5648.6 1635.88
#Mann= 4 ,-1 , 0
  4201.4      .1       0  4212.6     .05       0    4987    .035       0
    4993     .05       0
Bank Sta=4987,4993
XS Rating Curve= 0 ,0
Exp/Cntr=0.3,0.1

Chan Stop Cuts=-1
Use User Specified Reach Order=0
Composite Channel Slope=5