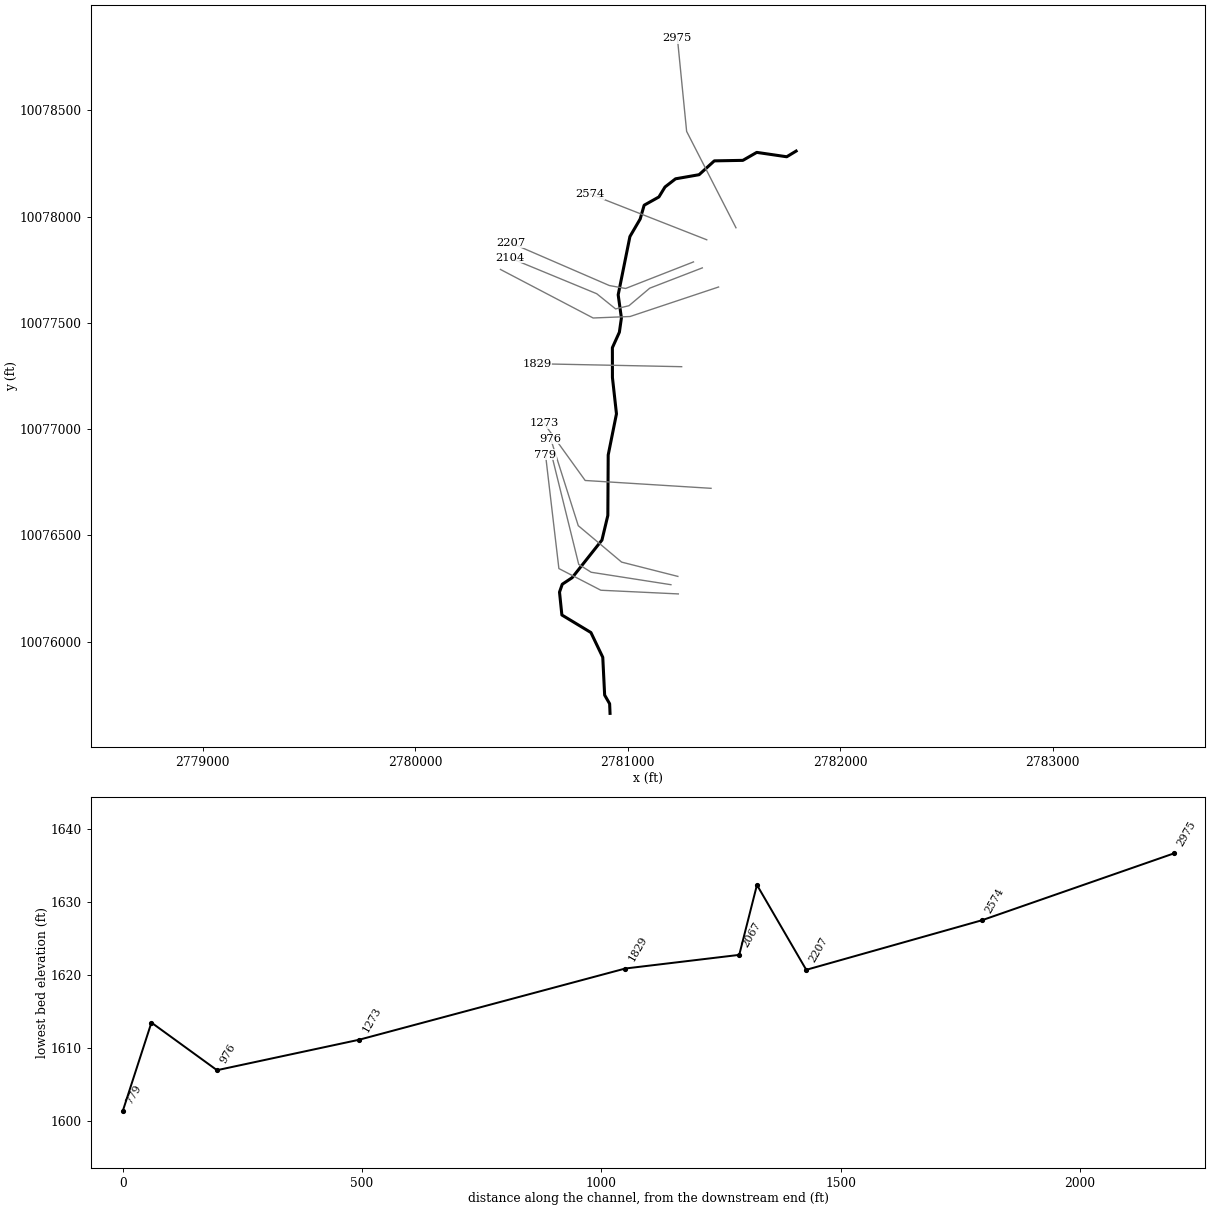
--- UNT045 IN NNOGR.prj (project) ---

Proj Title=UNT045 IN NNOGR Base Level Engineering
Current Plan=p01
Default Exp/Contr=0.3,0.1
English Units
Geom File=g01
Flow File=f01
Plan File=p01
BEGIN DESCRIPTION:
UNT045 IN NNOGR
END DESCRIPTION:

--- UNT045 IN NNOGR.p01 (plan) ---

Plan Title=Multiple Run
Short Identifier=Multiple
Geom File=g01
Flow File=f01
Subcritical Flow
K Sum by GR= 0
Std Step Tol= 0.01
Critical Tol= 0.01
Num of Std Step Trials= 20
Max Error Tol= 0.3
Flow Tol Ratio= 0.001
Split Flow NTrial= 30
Split Flow Tol= 0.02
Split Flow Ratio= 0.02
Log Output Level= 0
Friction Slope Method= 1
Unsteady Friction Slope Method= 2
Unsteady Bridges Friction Slope Method= 1
Parabolic Critical Depth
Global Vel Dist=  1 , 1 , 1
Global Log Level= 0
CheckData=True
Encroach Param= -1, 0, 0, 0
BEGIN DESCRIPTION:
Multiple Run
END DESCRIPTION:

--- UNT045 IN NNOGR.f01 (steady flow) ---

Flow Title=Multiple
Number of Profiles=7
Profile Names=10-year,25-year,50-year,1pct_min,100-year,1pct_plu,500-year
River Rch & RM= UNT045 IN NNOGR,Reach-1,2975
     301     407     493     438     593     802     859
Boundary for River Rch & Prof#=UNT045 IN NNOGR,Reach-1,1
Up Type=0
Dn Type=3
Dn Slope=0.005
Boundary for River Rch & Prof#=UNT045 IN NNOGR,Reach-1,2
Up Type=0
Dn Type=3
Dn Slope=0.005
Boundary for River Rch & Prof#=UNT045 IN NNOGR,Reach-1,3
Up Type=0
Dn Type=3
Dn Slope=0.005
Boundary for River Rch & Prof#=UNT045 IN NNOGR,Reach-1,4
Up Type=0
Dn Type=3
Dn Slope=0.005
Boundary for River Rch & Prof#=UNT045 IN NNOGR,Reach-1,5
Up Type=0
Dn Type=3
Dn Slope=0.005
Boundary for River Rch & Prof#=UNT045 IN NNOGR,Reach-1,6
Up Type=0
Dn Type=3
Dn Slope=0.005
Boundary for River Rch & Prof#=UNT045 IN NNOGR,Reach-1,7
Up Type=0
Dn Type=3
Dn Slope=0.005

--- UNT045 IN NNOGR.g01 (geometry) ---

Geom Title=Existing Conditions

River Reach=UNT045 IN NNOGR,Reach-1
Reach XY= 30
      2781793.47     10078308.73      2781749.20     10078281.95
      2781608.15     10078302.55      2781542.87     10078265.05
      2781408.49     10078262.65      2781336.80     10078197.55
      2781226.00     10078178.18      2781176.37     10078139.69
      2781147.73     10078092.83      2781078.29     10078053.94
      2781059.54     10077989.01      2781011.28     10077906.43
      2780956.07     10077632.24      2780971.26     10077523.30
      2780961.65     10077456.21      2780928.78     10077383.55
      2780929.02     10077243.04      2780948.00     10077072.21
      2780909.11     10076878.71      2780907.39     10076594.02
      2780879.68     10076478.16      2780739.56     10076301.27
      2780692.85     10076270.27      2780679.97     10076233.19
      2780691.10     10076125.64      2780827.80     10076043.02
      2780883.53     10075926.58      2780892.38     10075748.66
      2780915.82     10075707.92      2780917.76     10075662.64

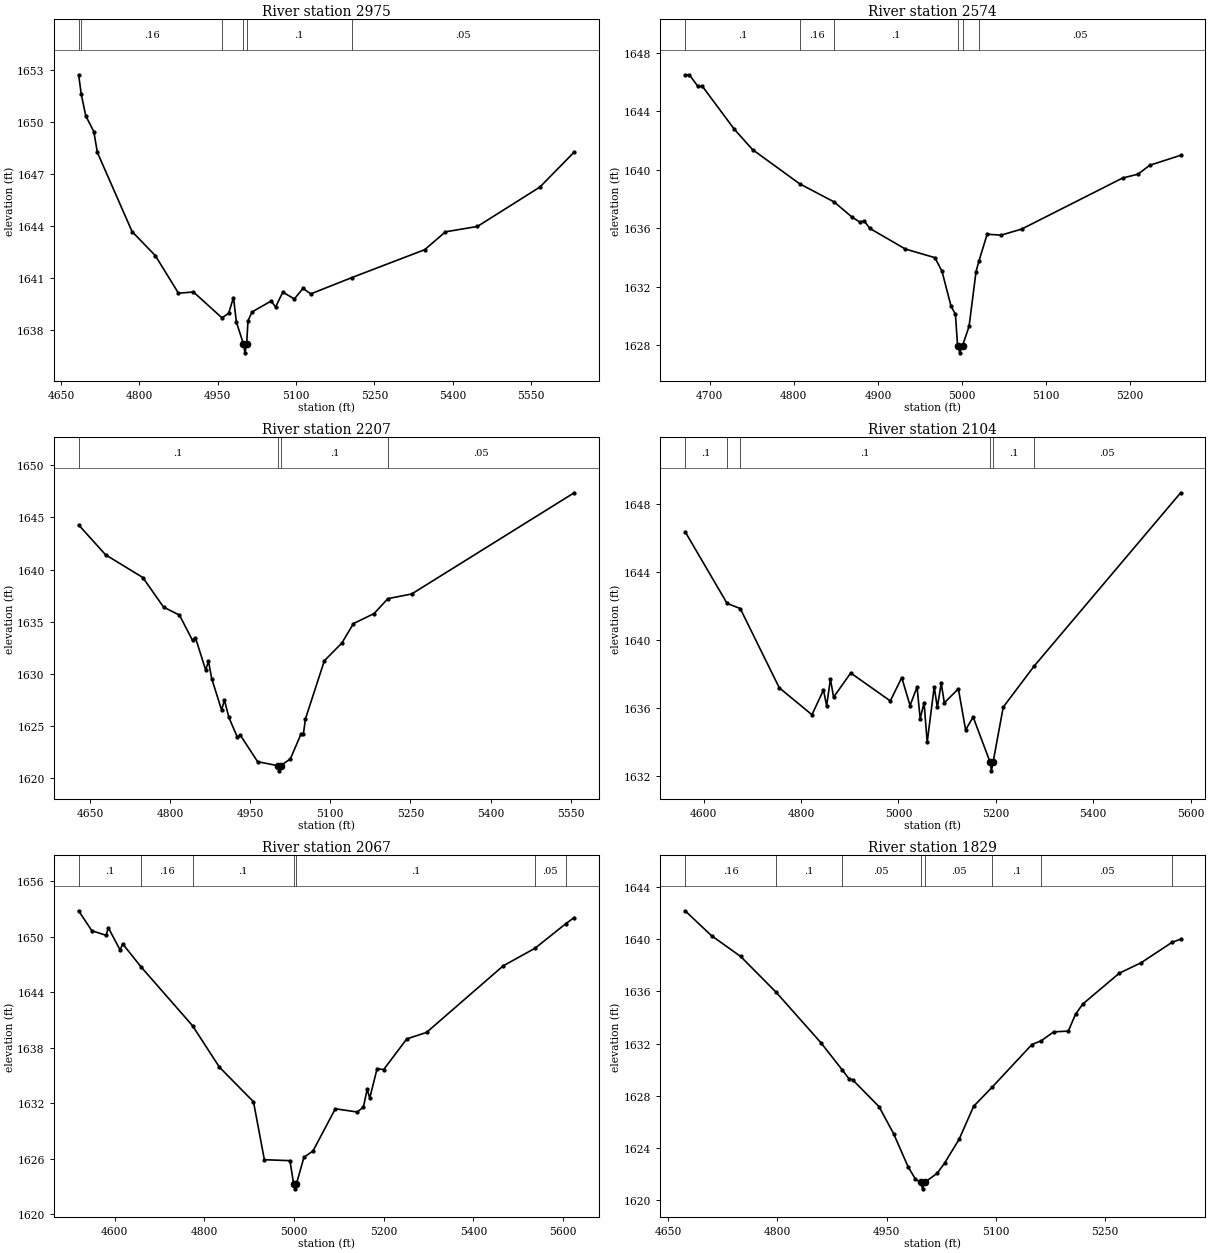
Type RM Length L Ch R = 1,2975,401,401,401
BEGIN DESCRIPTION:
UNT045 IN NNOGR 7.0
END DESCRIPTION:
XS GIS Cut Line= 3
      2781510.35     10077947.87      2781278.16     10078401.40
      2781234.81     10078839.25
#Sta/Elev= 30
  4683.4 1652.70  4688.4 1651.58  4697.1 1650.33  4712.5 1649.42  4719.3 1648.22
  4785.9 1643.65  4830.3 1642.27  4874.7 1640.10  4903.4 1640.17  4958.0 1638.68
  4970.8 1638.94  4980.1 1639.85  4985.7 1638.43  4999.3 1637.16  5002.1 1636.66
  5005.3 1637.16  5007.9 1638.51  5015.8 1639.02  5052.4 1639.65  5060.7 1639.30
  5074.6 1640.16  5096.8 1639.77  5113.4 1640.38  5128.1 1640.06  5206.8 1641.00
  5346.5 1642.61  5386.2 1643.64  5447.5 1643.95  5567.1 1646.22  5632.9 1648.24
#Mann=6,-1,0
  4683.4     0.1       0  4688.4    0.16       0  4958.0     0.1       0
  4999.3    0.07       0  5005.3     0.1       0  5206.8    0.05       0
Bank Sta=4999.3,5005.3
Exp/Cntr=0.3,0.1

Type RM Length L Ch R = 1,2574,367,367,367
BEGIN DESCRIPTION:
UNT045 IN NNOGR 5.0
END DESCRIPTION:
XS GIS Cut Line= 2
      2781372.85     10077891.30      2780824.27     10078106.56
#Sta/Elev= 30
  4670.7 1646.48  4675.7 1646.48  4685.9 1645.69  4691.3 1645.69  4729.1 1642.77
  4750.9 1641.37  4806.8 1639.04  4848.1 1637.79  4868.8 1636.78  4878.4 1636.42
  4883.8 1636.50  4890.3 1635.99  4932.6 1634.58  4967.8 1633.99  4976.2 1633.06
  4986.9 1630.69  4992.2 1630.12  4994.7 1627.99  4997.4 1627.49  5000.7 1627.99
  5008.4 1629.30  5016.7 1633.04  5020.2 1633.77  5029.9 1635.59  5046.5 1635.53
  5070.9 1635.94  5191.0 1639.43  5209.2 1639.69  5223.3 1640.30  5260.0 1640.98
#Mann=6,-1,0
  4670.7     0.1       0  4806.8    0.16       0  4848.1     0.1       0
  4994.7    0.07       0  5000.7     0.1       0  5020.2    0.05       0
Bank Sta=4994.7,5000.7
Exp/Cntr=0.3,0.1

Type RM Length L Ch R = 1,2207,103,103,103
BEGIN DESCRIPTION:
Mapping XS cec2e011
END DESCRIPTION:
XS GIS Cut Line= 4
      2781310.40     10077787.13      2780990.94     10077662.12
      2780914.55     10077676.01      2780449.26     10077877.40
#Sta/Elev= 30
  4628.8 1644.29  4679.2 1641.42  4749.0 1639.24  4787.8 1636.40  4817.6 1635.63
  4842.1 1633.20  4847.5 1633.47  4866.6 1630.37  4871.9 1631.21  4877.9 1629.55
  4896.4 1626.53  4901.8 1627.47  4910.1 1625.81  4926.2 1623.89  4931.6 1624.11
  4963.8 1621.57  5001.3 1621.19  5004.0 1620.69  5007.3 1621.19  5025.2 1621.84
  5045.0 1624.21  5049.5 1624.21  5053.5 1625.69  5088.8 1631.25  5121.5 1632.95
  5143.3 1634.82  5181.8 1635.78  5207.7 1637.21  5252.3 1637.66  5556.5 1647.37
#Mann=4,-1,0
  4628.8     0.1       0  5001.3    0.07       0  5007.3     0.1       0
  5207.7    0.05       0
Bank Sta=5001.3,5007.3
Exp/Cntr=0.3,0.1

Type RM Length L Ch R = 1,2104,37,37,37
BEGIN DESCRIPTION:
Mapping XS 98257e31
END DESCRIPTION:
XS GIS Cut Line= 6
      2781351.99     10077759.06      2781104.55     10077663.55
      2781006.89     10077581.09      2780943.96     10077565.90
      2780854.98     10077637.51      2780444.81     10077806.79
#Sta/Elev= 30
  4562.2 1646.36  4648.4 1642.15  4675.4 1641.85  4755.5 1637.20  4822.6 1635.62
  4846.2 1637.07  4852.7 1636.15  4860.5 1637.71  4867.0 1636.65  4902.1 1638.07
  4983.4 1636.43  5006.9 1637.80  5023.9 1636.16  5038.3 1637.25  5044.7 1635.39
  5052.7 1636.33  5059.1 1634.00  5073.5 1637.26  5079.9 1636.05  5087.9 1637.47
  5094.3 1636.32  5123.1 1637.14  5138.0 1634.73  5153.4 1635.49  5188.3 1632.83
  5191.0 1632.33  5194.3 1632.83  5215.2 1636.07  5278.5 1638.47  5579.3 1648.64
#Mann=6,-1,0
  4562.2     0.1       0  4648.4    0.16       0  4675.4     0.1       0
  5188.3    0.07       0  5194.3     0.1       0  5278.5    0.05       0
Bank Sta=5188.3,5194.3
Exp/Cntr=0.3,0.1

Type RM Length L Ch R = 1,2067,238,238,238
BEGIN DESCRIPTION:
UNT045 IN NNOGR 4.0
END DESCRIPTION:
XS GIS Cut Line= 4
      2781428.46     10077669.07      2781011.77     10077530.17
      2780838.16     10077523.23      2780402.04     10077751.67
#Sta/Elev= 30
  4519.5 1652.82  4549.0 1650.66  4580.6 1650.17  4585.9 1650.97  4612.3 1648.55
  4617.5 1649.26  4658.0 1646.79  4773.5 1640.39  4833.6 1635.90  4909.5 1632.16
  4933.8 1625.89  4990.9 1625.79  4999.1 1623.24  5001.8 1622.74  5005.1 1623.24
  5022.1 1626.16  5042.1 1626.83  5092.1 1631.40  5141.1 1631.05  5154.7 1631.59
  5163.1 1633.51  5168.8 1632.56  5185.2 1635.74  5199.9 1635.64  5251.4 1638.96
  5295.5 1639.66  5466.4 1646.86  5537.6 1648.77  5605.5 1651.40  5624.8 1652.09
#Mann=7,-1,0
  4519.5     0.1       0  4658.0    0.16       0  4773.5     0.1       0
  4999.1    0.07       0  5005.1     0.1       0  5537.6    0.05       0
  5605.5     0.1       0
Bank Sta=4999.1,5005.1
Exp/Cntr=0.3,0.1

Type RM Length L Ch R = 1,1829,556,556,556
BEGIN DESCRIPTION:
UNT045 IN NNOGR 3.0
END DESCRIPTION:
XS GIS Cut Line= 2
      2781254.80     10077294.06      2780574.24     10077307.95
#Sta/Elev= 30
  4673.1 1642.18  4709.4 1640.27  4749.4 1638.68  4798.4 1635.92  4859.5 1632.08
  4888.6 1630.01  4898.2 1629.31  4903.2 1629.23  4939.5 1627.17  4959.5 1625.10
  4979.5 1622.55  4989.5 1621.62  4996.5 1621.37  4999.3 1620.87  5002.5 1621.37
  5019.5 1622.07  5029.5 1622.84  5049.5 1624.67  5069.5 1627.20  5095.0 1628.67
  5149.5 1631.93  5162.3 1632.22  5179.5 1632.90  5199.5 1632.96  5209.5 1634.26
  5219.5 1635.04  5269.6 1637.40  5299.6 1638.20  5342.2 1639.77  5353.8 1640.00
#Mann=8,-1,0
  4673.1    0.16       0  4798.4     0.1       0  4888.6    0.05       0
  4996.5   0.035       0  5002.5    0.05       0  5095.0     0.1       0
  5162.3    0.05       0  5342.2     0.1       0
Bank Sta=4996.5,5002.5
Exp/Cntr=0.3,0.1

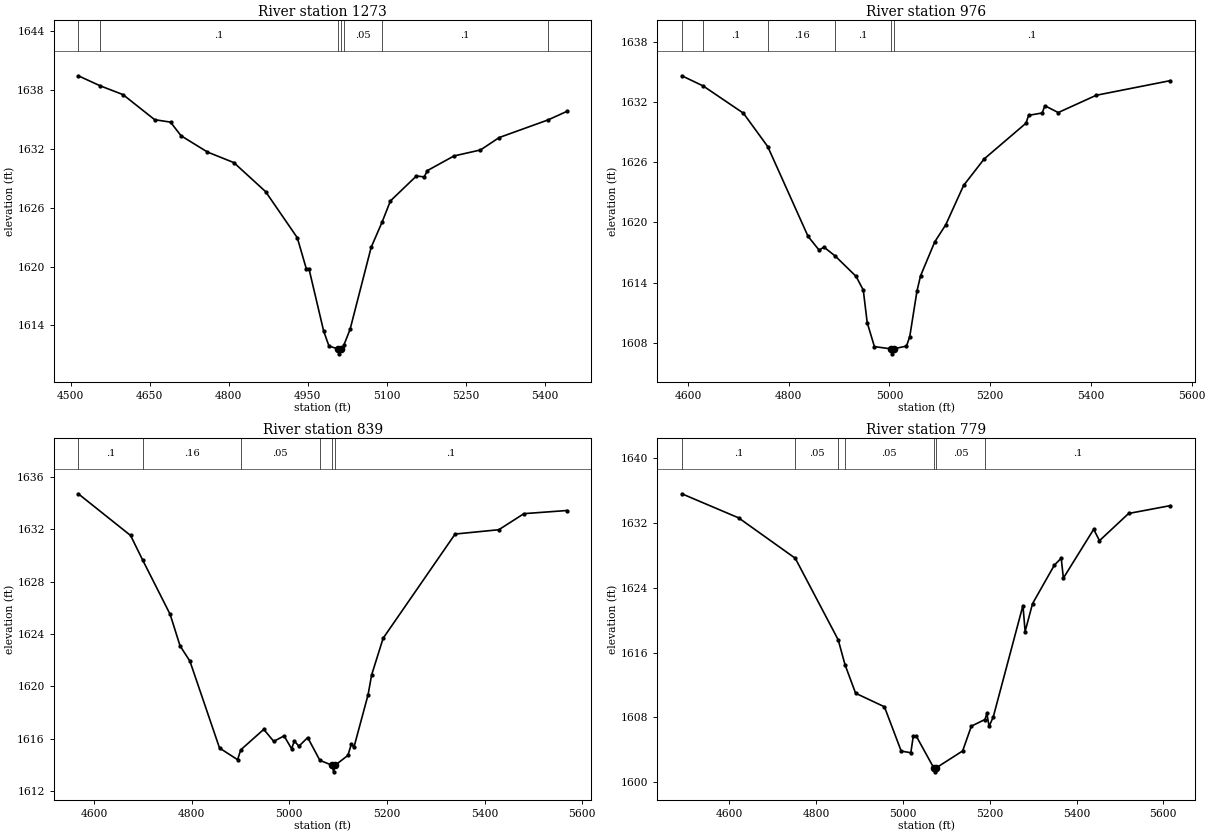
Type RM Length L Ch R = 1,1273,297,297,297
BEGIN DESCRIPTION:
UNT045 IN NNOGR 2.0
END DESCRIPTION:
XS GIS Cut Line= 3
      2781393.13     10076721.72      2780800.73     10076758.61
      2780605.83     10077029.29
#Sta/Elev= 30
  4514.4 1639.47  4556.2 1638.44  4599.2 1637.55  4659.3 1634.99  4689.4 1634.74
  4709.4 1633.35  4759.5 1631.69  4809.6 1630.61  4869.8 1627.65  4929.9 1622.95
  4947.0 1619.79  4952.0 1619.80  4980.0 1613.41  4990.0 1611.90  5007.0 1611.60
  5009.8 1611.10  5013.0 1611.60  5018.3 1611.99  5030.1 1613.60  5070.1 1621.97
  5090.9 1624.55  5106.6 1626.70  5156.0 1629.25  5170.7 1629.15  5176.9 1629.80
  5227.2 1631.29  5277.5 1631.90  5313.1 1633.17  5405.9 1634.97  5441.5 1635.84
#Mann=7,-1,0
  4514.4    0.05       0  4556.2     0.1       0  5007.0    0.07       0
  5013.0     0.1       0  5018.3    0.05       0  5090.9     0.1       0
  5405.9    0.05       0
Bank Sta=5007,5013
Exp/Cntr=0.3,0.1

Type RM Length L Ch R = 1,976,137,137,137
BEGIN DESCRIPTION:
Mapping XS a2e235dd
END DESCRIPTION:
XS GIS Cut Line= 4
      2781236.92     10076307.22      2780972.17     10076374.49
      2780768.18     10076545.93      2780637.96     10076956.13
#Sta/Elev= 30
  4587.9 1634.59  4630.2 1633.58  4710.1 1630.87  4758.4 1627.55  4838.4 1618.62
  4860.4 1617.24  4870.0 1617.54  4892.5 1616.65  4933.8 1614.63  4948.1 1613.27
  4955.9 1610.03  4970.2 1607.64  5002.3 1607.42  5005.1 1606.92  5008.3 1607.42
  5033.9 1607.69  5040.4 1608.64  5054.7 1613.17  5061.8 1614.68  5089.9 1618.05
  5112.0 1619.78  5147.3 1623.68  5188.2 1626.32  5271.1 1629.87  5276.3 1630.65
  5303.3 1630.89  5308.6 1631.61  5335.1 1630.93  5410.6 1632.65  5557.9 1634.11
#Mann=6,-1,0
  4587.9    0.05       0  4630.2     0.1       0  4758.4    0.16       0
  4892.5     0.1       0  5002.3    0.07       0  5008.3     0.1       0
Bank Sta=5002.3,5008.3
Exp/Cntr=0.3,0.1

Type RM Length L Ch R = 1,839,60,60,60
BEGIN DESCRIPTION:
Mapping XS e1662d4d
END DESCRIPTION:
XS GIS Cut Line= 4
      2781204.33     10076268.16      2780828.94     10076326.75
      2780770.35     10076363.64      2780638.09     10076899.18
#Sta/Elev= 30
  4567.8 1634.72  4674.9 1631.53  4699.4 1629.67  4755.9 1625.50  4776.2 1623.09
  4796.4 1621.92  4857.1 1615.27  4894.1 1614.38  4900.5 1615.13  4947.7 1616.70
  4968.1 1615.78  4989.3 1616.20  5004.6 1615.22  5010.5 1615.81  5019.6 1615.41
  5037.7 1616.07  5062.6 1614.33  5087.8 1613.95  5090.6 1613.45  5093.8 1613.95
  5120.1 1614.71  5127.2 1615.60  5132.3 1615.32  5161.3 1619.34  5168.6 1620.86
  5192.2 1623.67  5339.6 1631.64  5429.1 1631.97  5480.6 1633.20  5568.6 1633.44
#Mann=6,-1,0
  4567.8     0.1       0  4699.4    0.16       0  4900.5    0.05       0
  5062.6     0.1       0  5087.8   0.035       0  5093.8     0.1       0
Bank Sta=5087.8,5093.8
Exp/Cntr=0.3,0.1

Type RM Length L Ch R = 1,779,0,0,0
BEGIN DESCRIPTION:
UNT045 IN NNOGR 1.0
END DESCRIPTION:
XS GIS Cut Line= 4
      2781239.10     10076224.75      2780874.51     10076242.11
      2780677.03     10076344.11      2780614.18     10076879.46
#Sta/Elev= 30
  4490.1 1635.61  4620.9 1632.64  4751.6 1627.65  4850.6 1617.58  4866.2 1614.52
  4890.7 1610.99  4957.1 1609.32  4995.8 1603.85  5018.0 1603.65  5023.6 1605.70
  5030.7 1605.68  5070.7 1601.79  5073.5 1601.29  5076.7 1601.79  5137.4 1603.87
  5157.5 1606.93  5188.9 1607.75  5193.2 1608.50  5198.3 1606.90  5207.9 1608.05
  5276.4 1621.82  5281.4 1618.61  5298.5 1622.05  5348.8 1626.80  5364.6 1627.66
  5369.6 1625.20  5439.5 1631.23  5452.8 1629.82  5520.0 1633.18  5616.4 1634.15
#Mann=7,-1,0
  4490.1     0.1       0  4751.6    0.05       0  4850.6    0.16       0
  4866.2    0.05       0  5070.7   0.035       0  5076.7    0.05       0
  5188.9     0.1       0
Bank Sta=5070.7,5076.7
Exp/Cntr=0.3,0.1

Chan Stop Cuts=-1