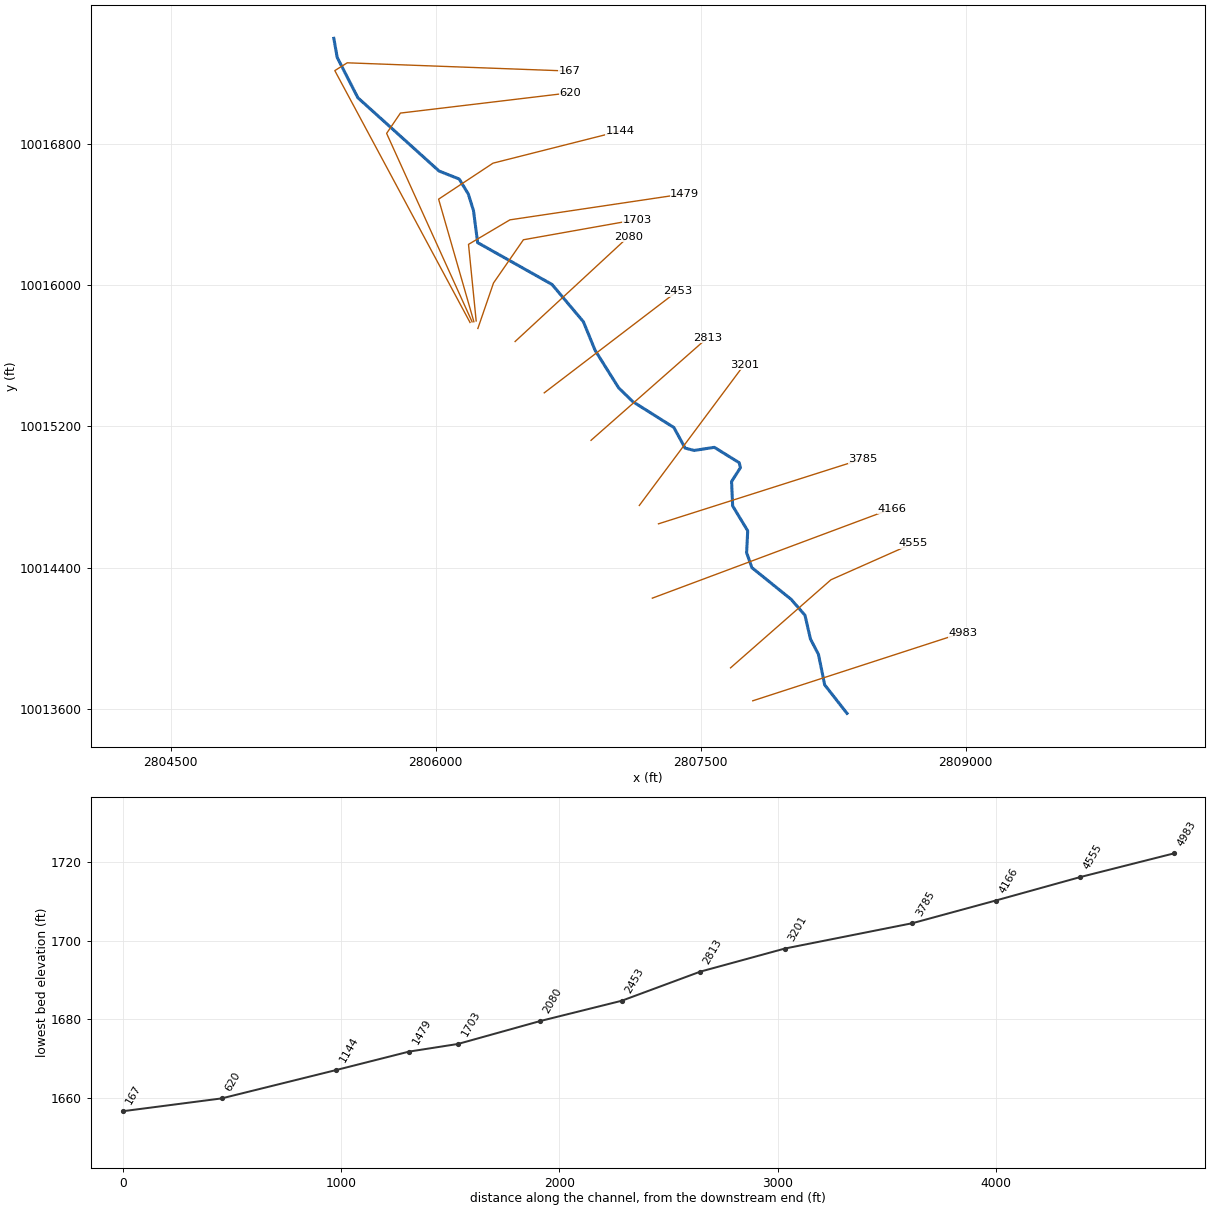
--- UNT045 IN SNOGR.prj (project) ---

Proj Title=UNT045 IN SNOGR Base Level Engineering
Current Plan=p01
Default Exp/Contr=0.3,0.1
English Units
Geom File=g01
Flow File=f01
Plan File=p01
Y Axis Title=Elevation
X Axis Title(PF)=Main Channel Distance
X Axis Title(XS)=Station
BEGIN DESCRIPTION:
UNT045 IN SNOGR
END DESCRIPTION:
DSS Export Rating Curves= 0
DSS Export Rating Curve Sorted= 0
DSS Export Volume Flow Curves= 0
DXF OffsetX= 0
DXF OffsetY= 0
DXF ScaleX= 1
DXF ScaleY= 10

--- UNT045 IN SNOGR.p01 (plan) ---

Plan Title=Multiple Run
Short Identifier=Multiple
Geom File=g01
Flow File=f01
Subcritical Flow
K Sum by GR= 0
Std Step Tol= 0.01
Critical Tol= 0.01
Num of Std Step Trials= 20
Max Error Tol= 0.3
Flow Tol Ratio= 0.001
Split Flow NTrial= 30
Split Flow Tol= 0.02
Split Flow Ratio= 0.02
Log Output Level= 0
Friction Slope Method= 1
Unsteady Friction Slope Method= 2
Unsteady Bridges Friction Slope Method= 1
Parabolic Critical Depth
Global Vel Dist=  1 , 1 , 1
Global Log Level= 0
CheckData=True
Encroach Param= -1, 0, 0, 0
BEGIN DESCRIPTION:
Multiple Run
END DESCRIPTION:

--- UNT045 IN SNOGR.f01 (steady flow) ---

Flow Title=Multiple
Program Version=4.10
Number of Profiles= 7
Profile Names=10-year,25-year,50-year,1pct_min,100-year,1pct_plu,500-year
River Rch & RM=UNT045 IN SNOGR,Reach-1         ,4983
     960    1410    1807    1697    2295    3103    3713
River Rch & RM=UNT045 IN SNOGR,Reach-1         ,3785
    1141    1685    2167    2040    2759    3731    4488
Boundary for River Rch & Prof#=UNT045 IN SNOGR,Reach-1         , 1
Up Type= 0
Dn Type= 3
Dn Slope=0.007
Boundary for River Rch & Prof#=UNT045 IN SNOGR,Reach-1         , 2
Up Type= 0
Dn Type= 3
Dn Slope=0.007
Boundary for River Rch & Prof#=UNT045 IN SNOGR,Reach-1         , 3
Up Type= 0
Dn Type= 3
Dn Slope=0.007
Boundary for River Rch & Prof#=UNT045 IN SNOGR,Reach-1         , 4
Up Type= 0
Dn Type= 3
Dn Slope=0.007
Boundary for River Rch & Prof#=UNT045 IN SNOGR,Reach-1         , 5
Up Type= 0
Dn Type= 3
Dn Slope=0.007
Boundary for River Rch & Prof#=UNT045 IN SNOGR,Reach-1         , 6
Up Type= 0
Dn Type= 3
Dn Slope=0.007
Boundary for River Rch & Prof#=UNT045 IN SNOGR,Reach-1         , 7
Up Type= 0
Dn Type= 3
Dn Slope=0.007
DSS Import GetInterval= 0
DSS Import GetPeak= 0
DSS Import FillOption= 0

--- UNT045 IN SNOGR.g01 (geometry) ---

Geom Title=Existing Conditions
Program Version=4.10

River Reach=UNT045 IN SNOGR ,Reach-1
Reach XY= 30
      2808328.47     10013573.73      2808202.03     10013735.21
      2808166.73     10013908.01      2808121.52       10013995.
      2808090.43     10014129.84      2808011.76      10014220.1
      2807789.93     10014399.34      2807760.02       10014484.
      2807766.28     10014608.03      2807681.03     10014749.14
      2807674.88     10014887.46      2807724.76     10014965.37
      2807718.49     10014993.59      2807577.35     10015081.06
      2807463.11     10015063.42      2807411.65     10015076.81
      2807348.37     10015193.22       2807116.3     10015339.59
      2807036.06     10015417.38      2806902.29      10015630.6
      2806835.93     10015792.68      2806658.44     10016003.76
      2806237.22     10016240.87      2806213.66      10016422.9
      2806184.27     10016516.71      2806132.85     10016601.11
      2806018.74      10016646.6      2805558.98     10017061.92
      2805442.14     10017290.21      2805422.97     10017398.31

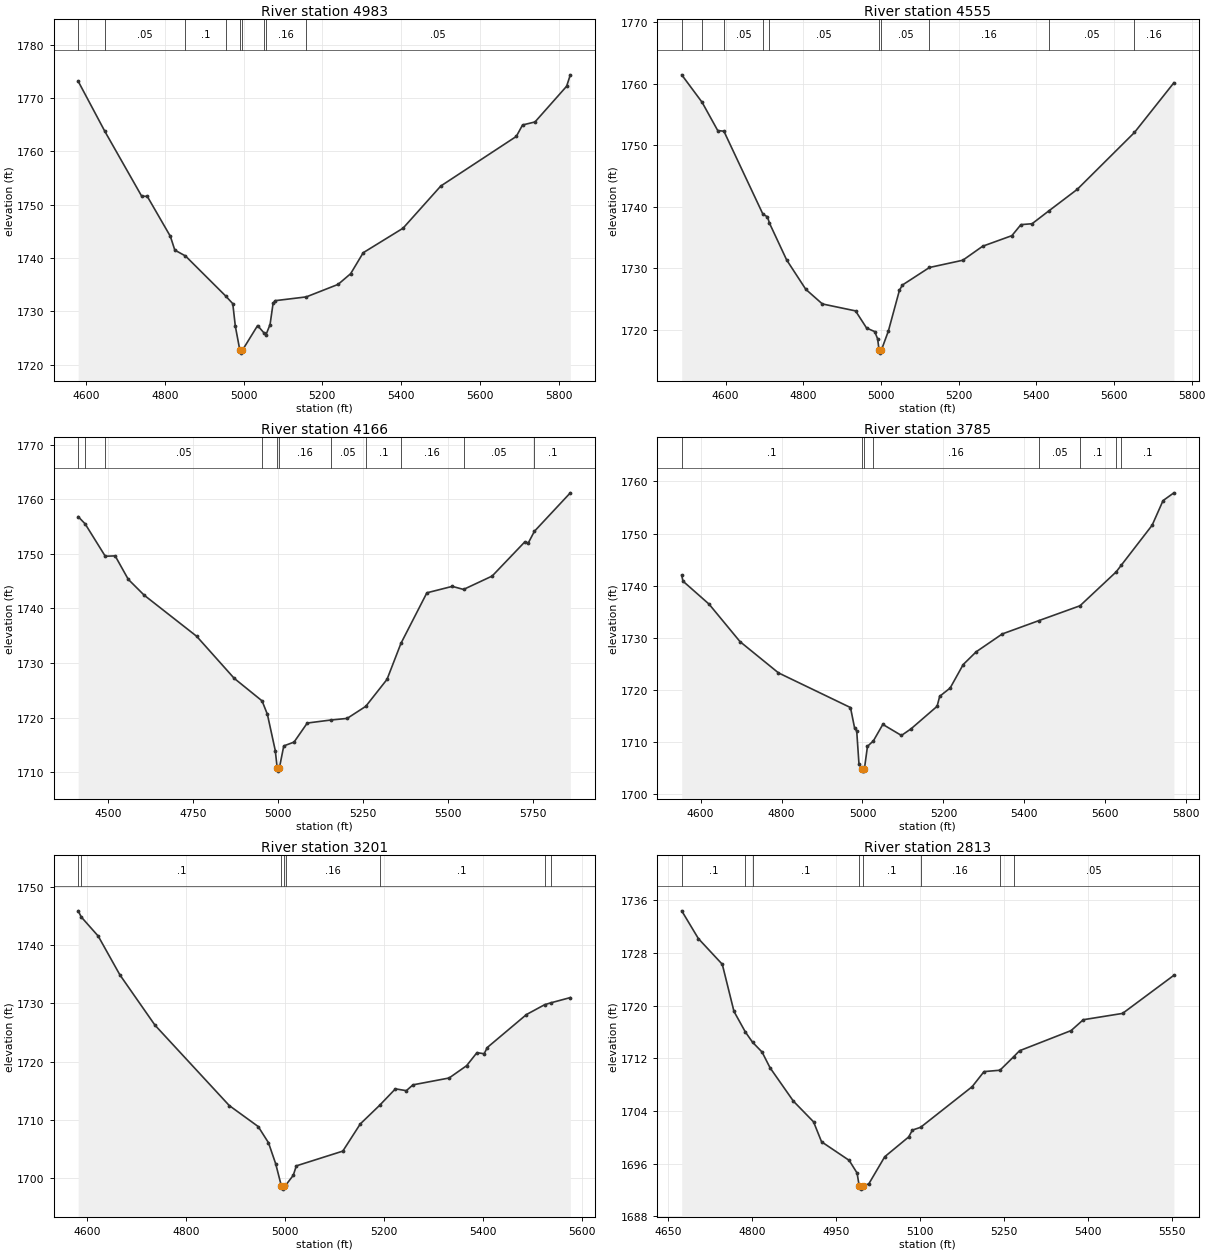
Type RM Length L Ch R = 1 ,4983    ,428,428,428
BEGIN DESCRIPTION:
UNT045 IN SNOGR 10.0
END DESCRIPTION:
XS GIS Cut Line= 2
      2807794.95     10013645.04       2808983.8      10014031.2
#Sta/Elev= 30
    4580 1773.16    4648 1763.73  4741.4  1751.6  4755.5 1751.58  4814.2 1744.08
  4825.5  1741.5  4852.6  1740.4  4954.9 1732.88  4972.7 1731.46  4979.2 1727.23
  4990.8 1722.69  4993.5 1722.19  4996.8 1722.69  5035.8 1727.36  5052.4 1725.94
  5057.2 1725.66  5067.4 1727.55  5075.1 1731.53  5080.3 1732.02  5159.4 1732.73
  5240.1 1735.07  5272.1 1737.08    5304 1741.01  5405.1  1745.6    5501 1753.51
  5692.7  1762.8  5708.7 1764.95  5740.3 1765.52  5820.6 1772.21    5830 1774.35
#Mann= 9 ,-1 , 0
    4580      .1       0    4648     .05       0  4852.6      .1       0
  4954.9     .05       0  4990.8    .035       0  4996.8     .05       0
  5052.4      .1       0  5057.2     .16       0  5159.4     .05       0
Bank Sta=4990.8,4996.8
XS Rating Curve= 0 ,0
Exp/Cntr=0.3,0.1

Type RM Length L Ch R = 1 ,4555    ,389,389,389
BEGIN DESCRIPTION:
UNT045 IN SNOGR 9.0
END DESCRIPTION:
XS GIS Cut Line= 3
      2807669.09     10013831.67      2808237.67     10014330.81
      2808704.46     10014538.27
#Sta/Elev= 30
  4486.9 1761.46  4539.4 1756.99  4579.6  1752.4  4595.5 1752.29  4696.2 1738.77
  4707.7 1738.37  4712.8 1737.34  4757.1 1731.35  4806.4 1726.57  4849.1 1724.19
  4934.5 1723.06    4963 1720.27  4983.9 1719.69  4991.4 1718.51  4995.1 1716.69
  4997.8 1716.19  5001.1 1716.69    5019 1719.77  5047.4 1726.38    5055 1727.26
  5124.8 1730.12  5210.7  1731.3  5261.9 1733.58  5337.1  1735.3  5360.4 1737.09
  5389.1 1737.24  5432.1 1739.32  5505.4 1742.83  5652.7 1752.08  5754.3 1760.17
#Mann= 10 ,-1 , 0
  4486.9     .16       0  4539.4      .1       0  4595.5     .05       0
  4696.2      .1       0  4712.8     .05       0  4995.1    .035       0
  5001.1     .05       0  5124.8     .16       0  5432.1     .05       0
  5652.7     .16       0
Bank Sta=4995.1,5001.1
XS Rating Curve= 0 ,0
Exp/Cntr=0.3,0.1

Type RM Length L Ch R = 1 ,4166    ,381,381,381
BEGIN DESCRIPTION:
UNT045 IN SNOGR 8.0
END DESCRIPTION:
XS GIS Cut Line= 2
      2807226.36     10014226.63       2808584.2     10014734.19
#Sta/Elev= 30
    4411 1756.83  4431.5 1755.51  4490.9 1749.57    4520 1749.64  4558.6 1745.34
  4605.4 1742.44    4760 1734.91  4870.5 1727.21  4952.7 1723.07  4968.4  1720.6
  4991.6 1713.97  4997.4  1710.7  5000.2  1710.2  5003.4  1710.7  5016.6 1714.82
  5046.9 1715.52  5085.8 1719.01  5154.5 1719.56  5203.3 1719.86  5258.1 1722.07
  5320.7 1727.01  5361.8 1733.62  5438.1 1742.87  5512.9 1744.05  5546.1 1743.49
  5630.3 1745.94  5725.9 1752.16    5737 1752.03  5754.8 1754.14  5860.6 1761.19
#Mann= 11 ,-1 , 0
    4411     .05       0  4431.5      .1       0  4490.9     .05       0
  4952.7     .16       0  4997.4     .07       0  5003.4     .16       0
  5154.5     .05       0  5258.1      .1       0  5361.8     .16       0
  5546.1     .05       0  5754.8      .1       0
Bank Sta=4997.4,5003.4
XS Rating Curve= 0 ,0
Exp/Cntr=0.3,0.1

Type RM Length L Ch R = 1 ,3785    ,584,584,584
BEGIN DESCRIPTION:
UNT045 IN SNOGR 7.0
END DESCRIPTION:
XS GIS Cut Line= 2
      2807261.13     10014647.65      2808419.93     10015016.56
#Sta/Elev= 30
  4553.4 1742.02  4556.4 1740.89  4620.9 1736.48  4697.5 1729.28  4792.5 1723.29
  4970.4 1716.64  4980.6 1712.71  4985.8 1712.15  4991.4  1705.8  4998.9 1704.95
  5001.6 1704.45  5004.9 1704.95  5012.4 1709.21  5026.9 1710.24  5050.3 1713.41
  5096.3 1711.29    5120 1712.56  5184.4 1716.88  5190.8  1718.8  5216.6 1720.38
  5248.9 1724.89  5281.1 1727.34  5345.5 1730.76  5435.4  1733.3  5537.5 1736.16
  5626.9 1742.66  5639.7 1743.96  5715.7  1751.6  5742.7 1756.33  5769.5 1757.82
#Mann= 8 ,-1 , 0
  4553.4      .1       0  4998.9     .07       0  5004.9      .1       0
  5026.9     .16       0  5435.4     .05       0  5537.5      .1       0
  5626.9     .05       0  5639.7      .1       0
Bank Sta=4998.9,5004.9
XS Rating Curve= 0 ,0
Exp/Cntr=0.3,0.1

Type RM Length L Ch R = 1 ,3201    ,388,388,388
BEGIN DESCRIPTION:
UNT045 IN SNOGR 6.0
END DESCRIPTION:
XS GIS Cut Line= 2
      2807152.59      10014751.8      2807746.57     10015549.56
#Sta/Elev= 30
  4581.3 1745.97  4587.6 1744.91  4621.8 1741.62  4665.6 1734.94  4736.5 1726.27
  4886.7 1712.41  4945.1  1708.8  4965.9 1706.01  4980.5 1702.38  4992.1 1698.51
  4994.9 1698.01  4998.1 1698.51  5001.5 1698.77    5016 1700.39  5022.2 1702.02
  5116.1 1704.56  5151.5 1709.25  5190.6 1712.46  5222.4 1715.29  5244.5 1714.98
  5257.9 1715.98  5330.9 1717.16  5366.3 1719.28  5387.2 1721.53  5401.8 1721.34
    5408 1722.41  5487.3  1728.1  5523.9 1729.79  5536.3 1730.11  5575.9 1731.02
#Mann= 8 ,-1 , 0
  4581.3     .05       0  4587.6      .1       0  4992.1     .07       0
  4998.1      .1       0  5001.5     .16       0  5190.6      .1       0
  5523.9     .16       0  5536.3      .1       0
Bank Sta=4992.1,4998.1
XS Rating Curve= 0 ,0
Exp/Cntr=0.3,0.1

Type RM Length L Ch R = 1 ,2813    ,360,360,360
BEGIN DESCRIPTION:
UNT045 IN SNOGR 5.0
END DESCRIPTION:
XS GIS Cut Line= 2
      2806879.16     10015120.73       2807538.9     10015702.34
#Sta/Elev= 30
  4674.6  1734.4  4704.4 1730.18  4747.1 1726.28    4768 1719.12  4788.4 1715.99
  4801.2 1714.44  4818.2 1712.95  4832.4 1710.57  4874.2 1705.49  4910.2 1702.35
  4924.5 1699.32  4973.8  1696.5    4988 1694.57  4991.7 1692.63  4994.5 1692.13
  4997.7 1692.63  5008.9 1692.93  5037.4 1697.05  5080.1 1700.05  5086.9  1701.1
  5101.5 1701.52  5193.6 1707.69  5214.8 1709.98  5243.3 1710.19  5267.8 1712.24
  5278.3 1713.15  5370.4 1716.21  5392.2 1717.86  5462.4 1718.82  5554.1 1724.61
#Mann= 8 ,-1 , 0
  4674.6      .1       0  4788.4     .16       0  4801.2      .1       0
  4991.7     .07       0  4997.7      .1       0  5101.5     .16       0
  5243.3      .1       0  5267.8     .05       0
Bank Sta=4991.7,4997.7
XS Rating Curve= 0 ,0
Exp/Cntr=0.3,0.1

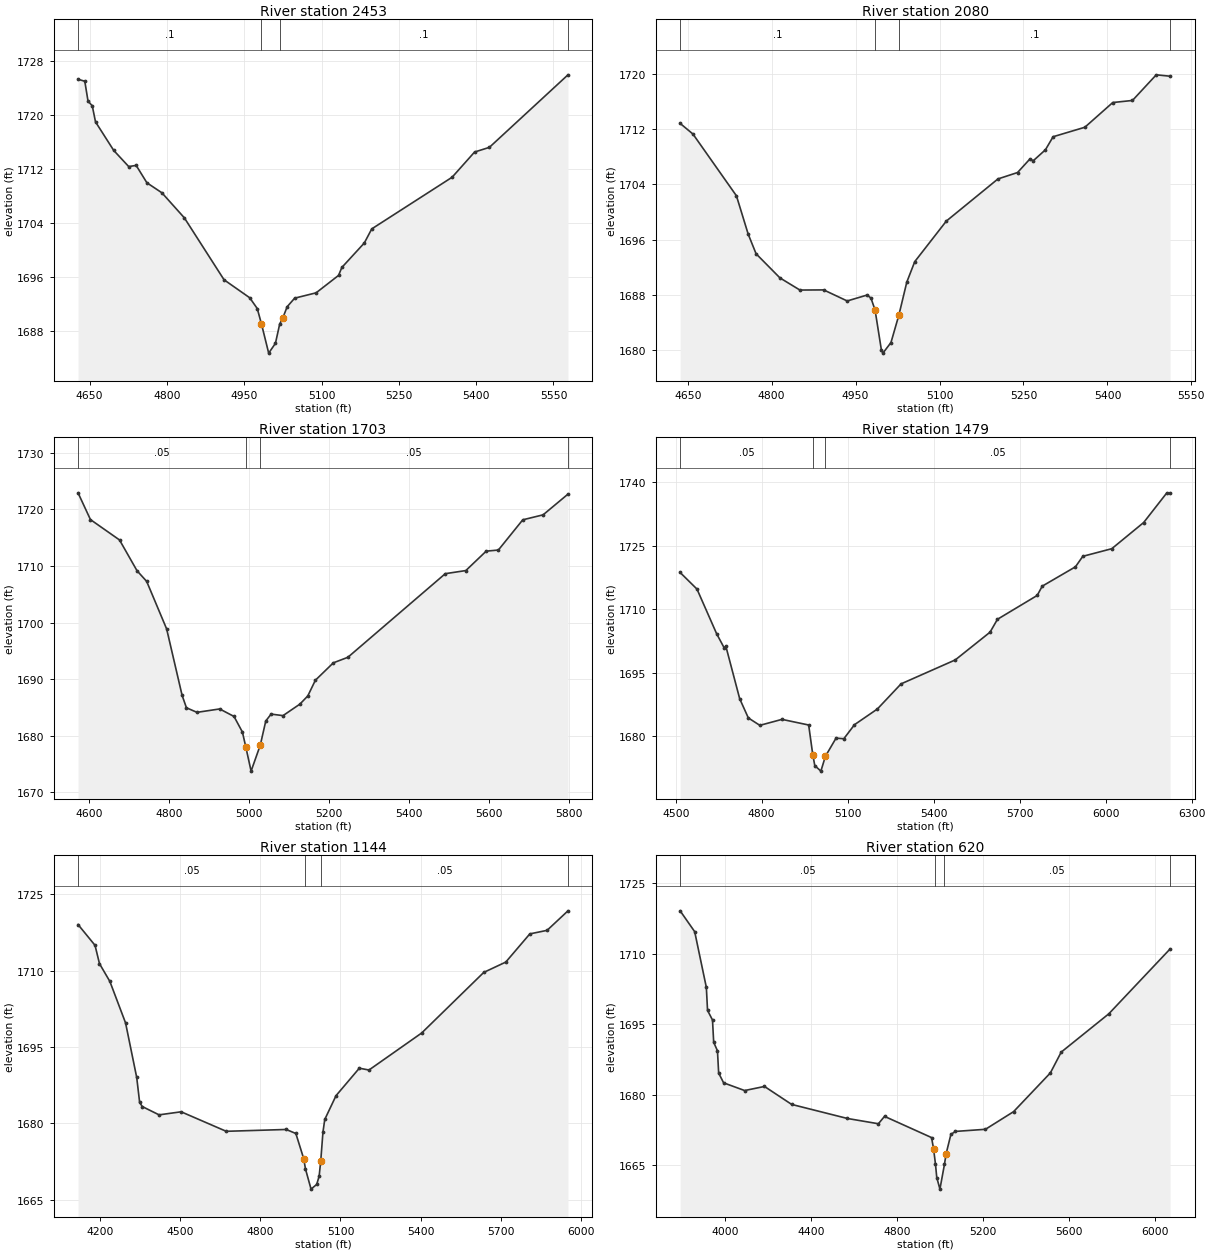
Type RM Length L Ch R = 1 ,2453    ,373,373,373
BEGIN DESCRIPTION:
UNT045 IN SNOGR 4.0
END DESCRIPTION:
XS GIS Cut Line= 2
      2806614.38     10015389.81      2807369.62     10015967.09
#Sta/Elev= 30
  4627.5 1725.24  4640.6 1724.95  4646.9    1722  4655.1 1721.32  4661.4 1718.94
  4696.7 1714.72  4725.8 1712.33  4740.3  1712.5  4761.1 1709.93  4790.2 1708.45
  4833.8 1704.74  4910.8 1695.58  4960.6 1692.92  4975.2 1691.33  4983.4 1689.05
  4997.4 1684.73  5010.5 1686.18  5018.7 1689.01    5025 1689.98  5033.3  1691.6
  5047.8 1692.86  5089.4 1693.65    5133 1696.23  5139.3  1697.4  5182.9 1701.02
  5197.4 1703.11  5353.3 1710.75  5396.9 1714.48  5425.6 1715.17  5578.1  1725.9
#Mann= 4 ,-1 , 0
  4627.5      .1       0  4983.4     .05       0  5018.7      .1       0
  5578.1      .1       0
Bank Sta=4983.4,5025
XS Rating Curve= 0 ,0
Exp/Cntr=0.3,0.1

Type RM Length L Ch R = 1 ,2080    ,377,377,377
BEGIN DESCRIPTION:
UNT045 IN SNOGR 3.0
END DESCRIPTION:
XS GIS Cut Line= 2
      2806449.45     10015680.61      2807091.86     10016275.27
#Sta/Elev= 30
  4636.5 1712.83  4659.4 1711.29  4737.1 1702.35  4758.1  1696.8  4772.2 1693.96
  4814.8 1690.47  4850.5 1688.71    4893 1688.73    4935 1687.13  4970.7 1687.99
  4977.5 1687.54  4984.8 1685.82    4996 1680.08  4998.8 1679.58  5013.2 1681.11
  5027.4  1685.1  5041.5 1689.86  5055.7 1692.82  5112.1 1698.69  5204.3 1704.79
  5239.4 1705.72    5261 1707.64  5267.8 1707.45  5289.2 1709.01  5302.9  1710.9
  5359.6 1712.27  5409.5 1715.85  5444.7 1716.15  5487.2 1719.86  5511.9 1719.66
#Mann= 4 ,-1 , 0
  4636.5      .1       0  4984.8     .05       0  5027.4      .1       0
  5511.9     .05       0
Bank Sta=4984.8,5027.4
XS Rating Curve= 0 ,0
Exp/Cntr=0.3,0.1

Type RM Length L Ch R = 1 ,1703    ,224,224,224
BEGIN DESCRIPTION:
Mapping XS c1309c4a
END DESCRIPTION:
XS GIS Cut Line= 4
      2806238.54     10015754.45      2806327.08     10016012.27
      2806496.35     10016257.06      2807139.61     10016371.65
#Sta/Elev= 30
  4573.3 1722.94  4604.3 1718.21  4676.9 1714.61  4720.6 1709.17  4744.7 1707.29
  4794.6 1698.88  4833.2 1687.14    4844 1684.95  4870.3 1684.14  4927.1 1684.74
  4962.9 1683.41  4983.8 1680.66  4992.6 1677.93  5005.5 1673.75  5028.5 1678.36
  5042.2 1682.62  5055.5 1683.83  5085.2 1683.56  5127.3 1685.59  5147.1 1687.04
    5166 1689.81  5210.9 1692.89  5247.2 1693.87  5490.5 1708.65  5541.8  1709.2
  5592.6 1712.63  5623.1 1712.83    5684 1718.17  5734.8 1719.05  5796.9 1722.71
#Mann= 4 ,-1 , 0
  4573.3     .05       0  4992.6    .035       0  5028.5     .05       0
  5796.9     .05       0
Bank Sta=4992.6,5028.5
XS Rating Curve= 0 ,0
Exp/Cntr=0.3,0.1

Type RM Length L Ch R = 1 ,1479    ,335,335,335
BEGIN DESCRIPTION:
Mapping XS dffa731b
END DESCRIPTION:
XS GIS Cut Line= 4
      2806228.99     10015796.96      2806185.59     10016231.02
      2806419.96     10016369.91      2807409.56     10016517.48
#Sta/Elev= 30
  4515.5 1718.71  4574.3 1714.79  4642.9 1704.24  4669.8 1700.83  4674.8 1701.35
  4723.3  1688.9  4753.4 1684.37  4793.6 1682.62  4870.8 1684.03  4963.9  1682.7
  4978.3 1675.66  4985.3 1673.11  5006.5 1671.81  5022.3 1675.31  5059.4  1679.6
  5086.6 1679.46  5123.7 1682.77  5203.6 1686.48  5286.2 1692.41  5475.4 1698.07
  5596.7 1704.62  5622.5 1707.66  5761.1 1713.29  5778.7 1715.48  5894.6 1720.05
  5920.3 1722.53  6021.4 1724.33  6132.6 1730.51  6213.5 1737.52  6224.7 1737.38
#Mann= 4 ,-1 , 0
  4515.5     .05       0  4978.3    .035       0  5022.3     .05       0
  6224.7      .1       0
Bank Sta=4978.3,5022.3
XS Rating Curve= 0 ,0
Exp/Cntr=0.3,0.1

Type RM Length L Ch R = 1 ,1144    ,524,524,524
BEGIN DESCRIPTION:
Mapping XS 7e0dca40
END DESCRIPTION:
XS GIS Cut Line= 4
      2806215.98     10015792.63      2806016.32      10016487.1
      2806324.48     10016691.09      2807044.23      10016873.2
#Sta/Elev= 30
  4117.4 1719.05    4181 1714.97  4197.7 1711.37  4236.6 1707.88  4295.4 1699.73
  4337.1 1689.03  4348.1 1684.12  4357.9 1683.32  4420.8 1681.69  4503.5 1682.29
  4672.3 1678.46  4896.9 1678.82    4933 1678.03  4962.5 1673.08  4969.1 1671.06
  4989.9 1667.11  5011.2 1668.04  5020.3 1669.67  5026.3 1672.69  5034.5  1678.3
  5041.3 1680.79  5083.5 1685.46  5170.7 1690.85  5206.8 1690.49  5404.2 1697.76
  5636.6 1709.65  5719.1 1711.68  5809.1 1717.21  5873.8 1717.91    5952 1721.74
#Mann= 4 ,-1 , 0
  4117.4     .05       0  4969.1    .035       0  5026.3     .05       0
    5952      .1       0
Bank Sta=4962.5,5026.3
XS Rating Curve= 0 ,0
Exp/Cntr=0.3,0.1

Type RM Length L Ch R = 1 ,620     ,453,453,453
BEGIN DESCRIPTION:
Mapping XS b748fe9e
END DESCRIPTION:
XS GIS Cut Line= 4
      2806205.86     10015792.09      2805721.92      10016859.8
      2805800.04     10016974.82      2806761.38     10017089.83
#Sta/Elev= 30
    3790 1719.08  3857.7 1714.65    3912 1702.79  3917.5 1697.91  3940.6 1695.87
  3946.1 1691.13  3963.7 1689.32  3969.2 1684.59  3992.3 1682.51  4090.1 1680.87
  4182.5 1681.74  4308.9 1677.92  4568.4 1674.93  4712.4 1673.81    4741 1675.38
  4959.8 1670.87    4969 1668.52  4977.9 1665.28    4984 1662.38  4998.7 1659.91
  5019.9  1665.2  5027.5 1667.43  5049.8 1671.55  5070.8 1672.18  5210.5 1672.63
  5341.4 1676.38  5512.6 1684.62    5563 1689.04  5784.6 1697.19  6069.5 1710.97
#Mann= 4 ,-1 , 0
    3790     .05       0  4977.9    .035       0  5019.9     .05       0
  6069.5      .1       0
Bank Sta=4969,5027.5
XS Rating Curve= 0 ,0
Exp/Cntr=0.3,0.1

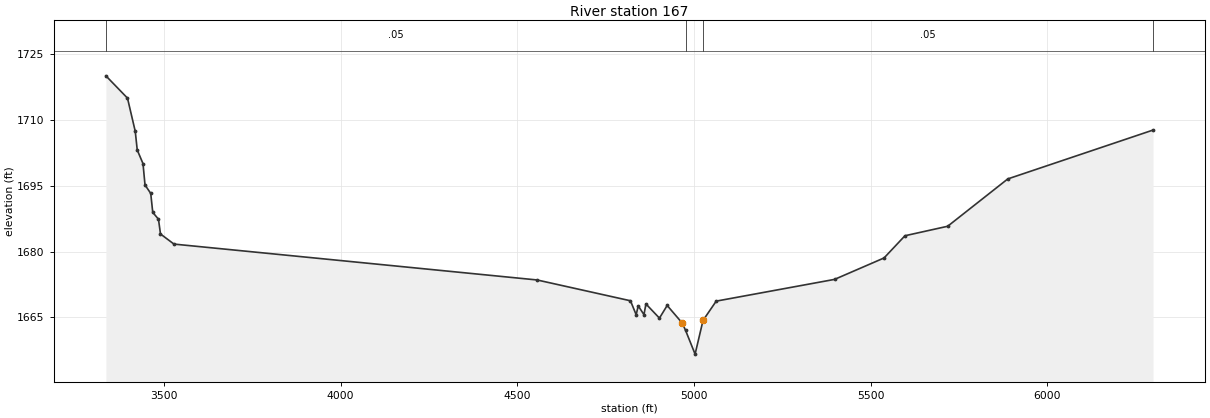
Type RM Length L Ch R = 1 ,167     ,0,0,0
BEGIN DESCRIPTION:
UNT045 IN SNOGR 2.0
END DESCRIPTION:
XS GIS Cut Line= 4
      2806194.25     10015788.35      2805428.64     10017215.39
      2805498.95     10017259.67      2806759.34     10017212.79
#Sta/Elev= 30
  3335.7 1720.03  3396.8 1714.95  3418.8 1707.38  3424.4 1703.14  3440.7 1700.04
  3446.4 1695.18  3462.6 1693.25  3468.3 1688.93  3484.5 1687.38  3490.2 1684.01
  3528.4 1681.71  4556.1 1673.54  4820.4  1668.8  4836.6 1665.61  4842.3 1667.65
  4858.6 1665.64  4864.2 1668.08  4902.4 1664.85  4924.3 1667.73    4967 1663.72
  4976.4 1662.05  5003.3 1656.65  5025.8 1664.33  5063.1 1668.72    5398 1673.67
  5538.1 1678.55  5597.3 1683.61  5718.2 1685.77  5888.3 1696.55  6299.5 1707.68
#Mann= 4 ,-1 , 0
  3335.7     .05       0  4976.4    .035       0  5025.8     .05       0
  6299.5      .1       0
Bank Sta=4967,5025.8
XS Rating Curve= 0 ,0
Exp/Cntr=0.3,0.1

Chan Stop Cuts=-1
Use User Specified Reach Order=0
Composite Channel Slope=5