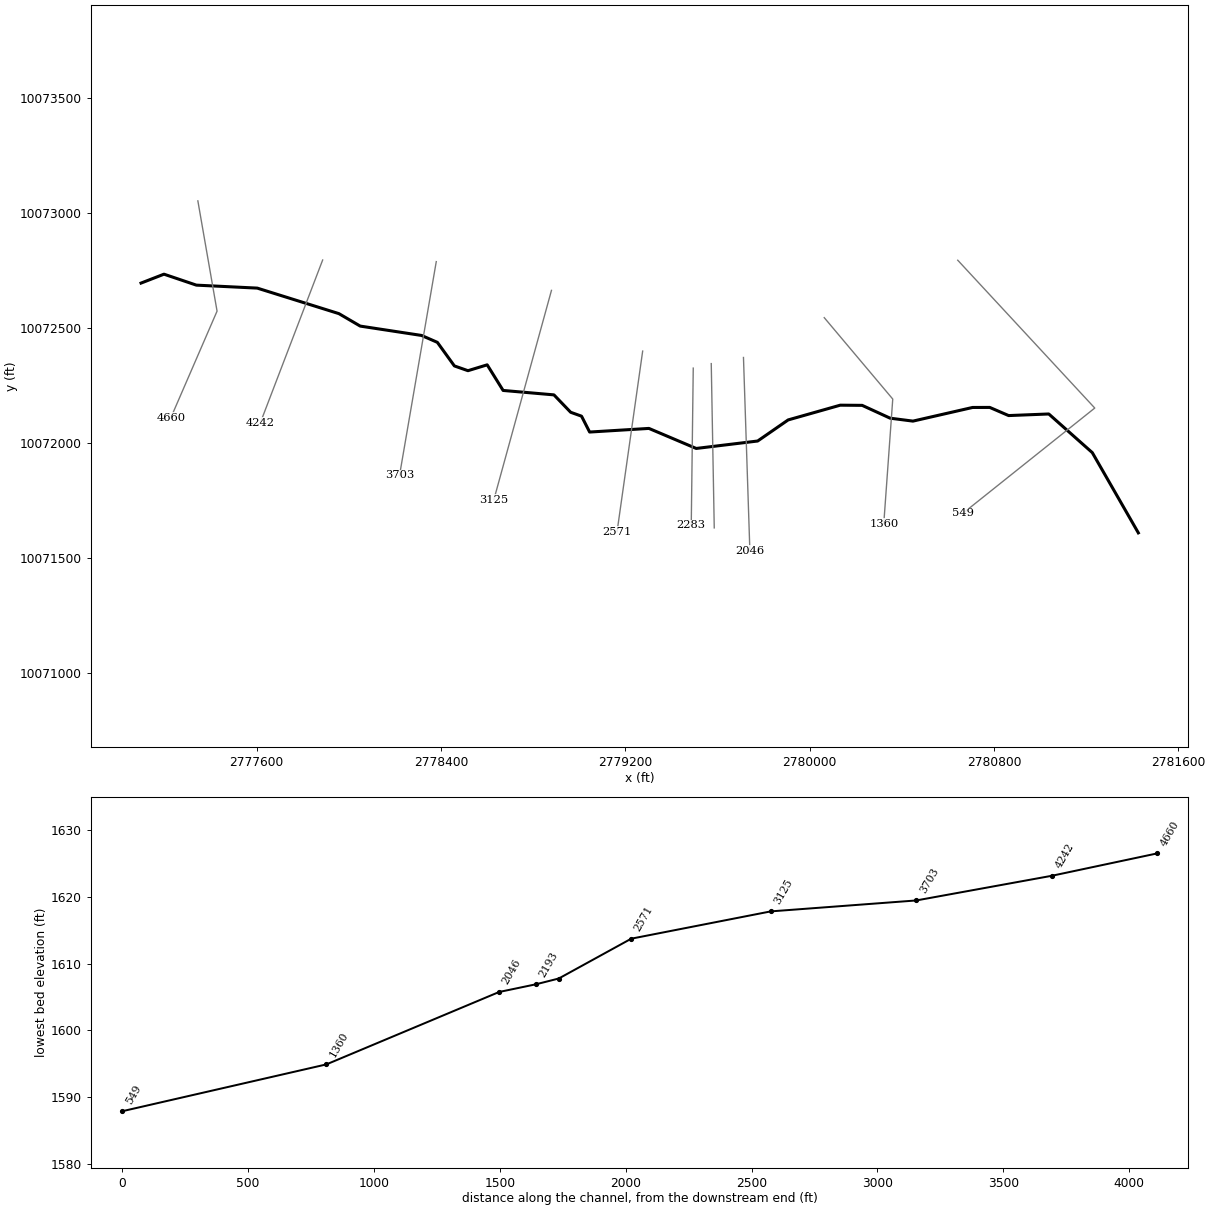
--- UNT046 IN NNOGR.prj (project) ---

Proj Title=UNT046 IN NNOGR Base Level Engineering
Current Plan=p01
Default Exp/Contr=0.3,0.1
English Units
Geom File=g01
Flow File=f01
Plan File=p01
Y Axis Title=Elevation
X Axis Title(PF)=Main Channel Distance
X Axis Title(XS)=Station
BEGIN DESCRIPTION:
UNT046 IN NNOGR
END DESCRIPTION:
DSS Export Rating Curves= 0
DSS Export Rating Curve Sorted= 0
DSS Export Volume Flow Curves= 0
DXF OffsetX= 0
DXF OffsetY= 0
DXF ScaleX= 1
DXF ScaleY= 10

--- UNT046 IN NNOGR.p01 (plan) ---

Plan Title=Multiple Run
Short Identifier=Multiple
Geom File=g01
Flow File=f01
Subcritical Flow
K Sum by GR= 0
Std Step Tol= 0.01
Critical Tol= 0.01
Num of Std Step Trials= 20
Max Error Tol= 0.3
Flow Tol Ratio= 0.001
Split Flow NTrial= 30
Split Flow Tol= 0.02
Split Flow Ratio= 0.02
Log Output Level= 0
Friction Slope Method= 1
Unsteady Friction Slope Method= 2
Unsteady Bridges Friction Slope Method= 1
Parabolic Critical Depth
Global Vel Dist=  1 , 1 , 1
Global Log Level= 0
CheckData=True
Encroach Param= -1, 0, 0, 0
BEGIN DESCRIPTION:
Multiple Run
END DESCRIPTION:

--- UNT046 IN NNOGR.f01 (steady flow) ---

Flow Title=Multiple
Program Version=4.10
Number of Profiles= 7
Profile Names=10-year,25-year,50-year,1pct_min,100-year,1pct_plu,500-year
River Rch & RM=UNT046 IN NNOGR,Reach-1         ,4660
     615     873    1093    1002    1355    1833    2092
Boundary for River Rch & Prof#=UNT046 IN NNOGR,Reach-1         , 1
Up Type= 0
Dn Type= 3
Dn Slope=0.0138
Boundary for River Rch & Prof#=UNT046 IN NNOGR,Reach-1         , 2
Up Type= 0
Dn Type= 3
Dn Slope=0.0138
Boundary for River Rch & Prof#=UNT046 IN NNOGR,Reach-1         , 3
Up Type= 0
Dn Type= 3
Dn Slope=0.0138
Boundary for River Rch & Prof#=UNT046 IN NNOGR,Reach-1         , 4
Up Type= 0
Dn Type= 3
Dn Slope=0.0138
Boundary for River Rch & Prof#=UNT046 IN NNOGR,Reach-1         , 5
Up Type= 0
Dn Type= 3
Dn Slope=0.0138
Boundary for River Rch & Prof#=UNT046 IN NNOGR,Reach-1         , 6
Up Type= 0
Dn Type= 3
Dn Slope=0.0138
Boundary for River Rch & Prof#=UNT046 IN NNOGR,Reach-1         , 7
Up Type= 0
Dn Type= 3
Dn Slope=0.0138
DSS Import GetInterval= 0
DSS Import GetPeak= 0
DSS Import FillOption= 0

--- UNT046 IN NNOGR.g01 (geometry) ---

Geom Title=Existing Conditions
Program Version=4.10

River Reach=UNT046 IN NNOGR ,Reach-1
Reach XY= 30
      2777098.47     10072693.73      2777198.08     10072732.47
      2777338.59     10072684.86       2777602.9     10072671.92
      2777957.33     10072560.98      2778049.75     10072506.84
      2778315.95     10072466.19      2778384.58     10072436.18
      2778458.47     10072333.73      2778517.35     10072313.02
      2778600.82      10072338.5      2778669.94     10072227.18
      2778890.61     10072207.94       2778963.2      10072132.3
      2779010.31      10072115.4      2779045.46     10072046.42
      2779302.77     10072062.18      2779508.05      10071975.1
      2779774.72      10072007.4      2779907.01     10072099.06
      2780133.15     10072163.15      2780228.28     10072162.37
      2780349.67     10072106.63      2780448.73     10072093.91
      2780707.53     10072153.23      2780782.01      10072153.4
      2780863.95     10072117.99      2781038.26     10072124.93
      2781227.15     10071956.88      2781426.95     10071608.22

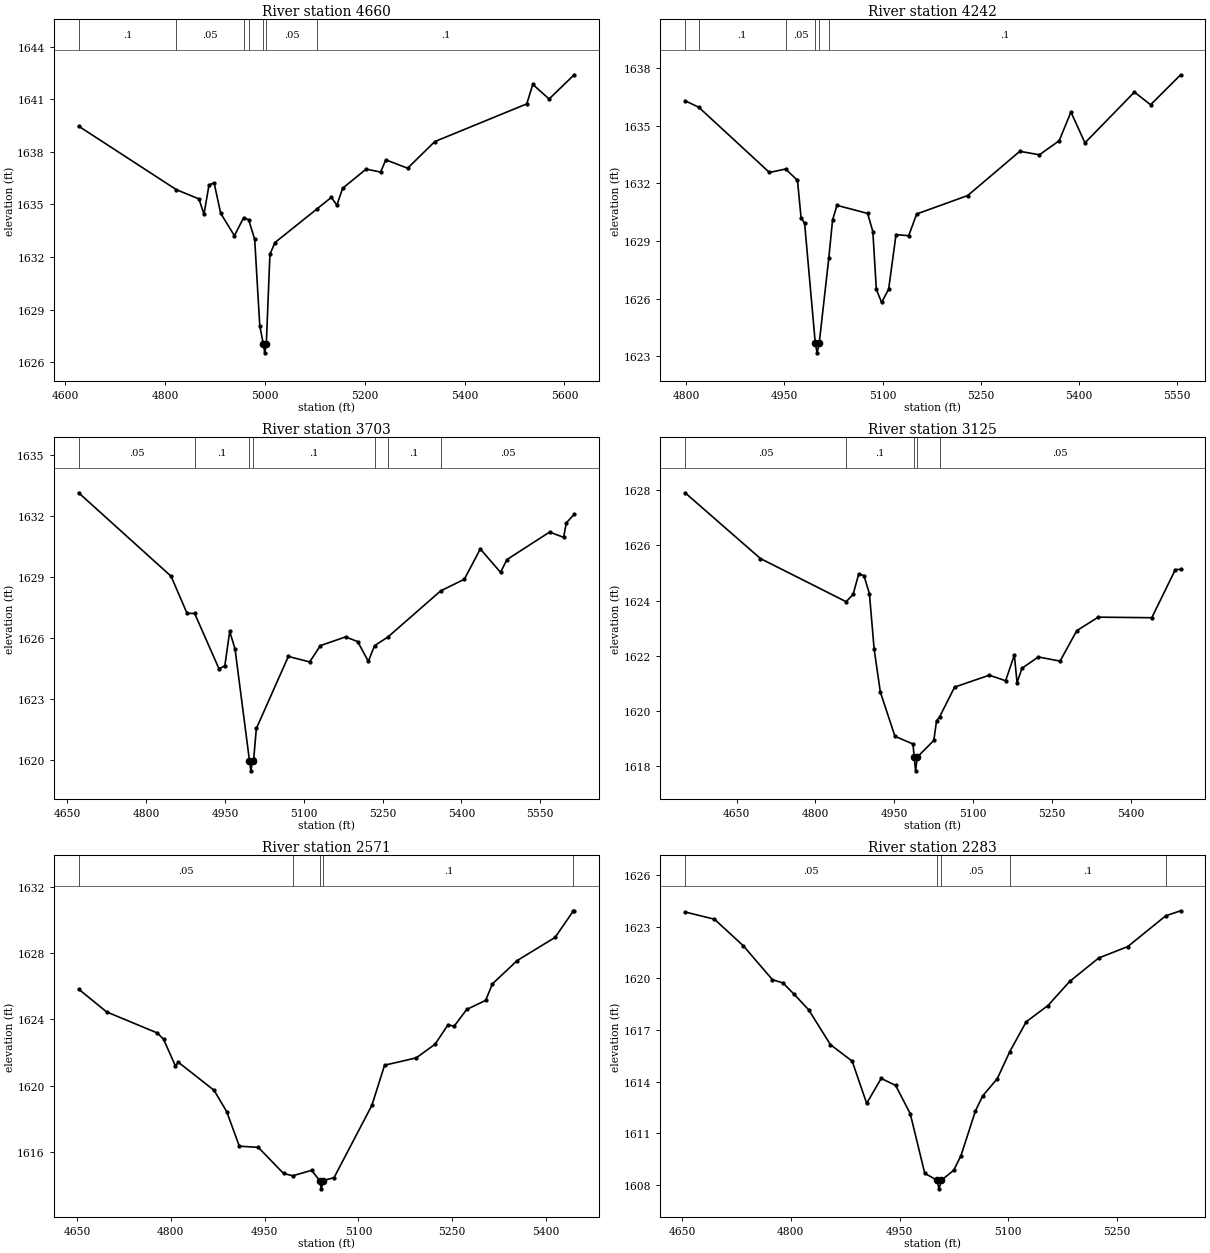
Type RM Length L Ch R = 1 ,4660    ,418,418,418
BEGIN DESCRIPTION:
UNT046 IN NNOGR 11.0
END DESCRIPTION:
XS GIS Cut Line= 3
       2777345.1     10073051.02      2777428.44     10072571.84
      2777227.51     10072107.63
#Sta/Elev= 30
  4627.2 1639.46  4822.7 1635.84    4868 1635.31  4878.2 1634.44  4888.3 1636.11
  4898.5 1636.22  4911.6 1634.49  4939.1 1633.21  4957.5 1634.24  4967.6 1634.12
  4979.7 1633.01  4989.9 1628.07    4997 1627.03  4999.8 1626.53    5003 1627.03
  5010.2 1632.15  5020.3 1632.82    5104 1634.73  5133.3  1635.4  5144.2 1634.95
  5155.9 1635.92  5202.9 1637.01  5231.8 1636.84  5242.3 1637.54  5285.9 1637.06
  5340.3 1638.58  5524.5 1640.73  5536.5 1641.84  5569.2 1641.01  5619.4 1642.39
#Mann= 7 ,-1 , 0
  4627.2      .1       0  4822.7     .05       0  4957.5      .1       0
  4967.6     .05       0    4997     .04       0    5003     .05       0
    5104      .1       0
Bank Sta=4997,5003
XS Rating Curve= 0 ,0
Exp/Cntr=0.3,0.1

Type RM Length L Ch R = 1 ,4242    ,539,539,539
BEGIN DESCRIPTION:
UNT046 IN NNOGR 10.0
END DESCRIPTION:
XS GIS Cut Line= 2
      2777886.77     10072794.06      2777616.52     10072087.26
#Sta/Elev= 30
  4798.4 1636.29  4819.3 1635.95  4927.2 1632.56  4951.9 1632.74    4970 1632.15
  4975.5  1630.2  4980.9 1629.92  4997.2 1623.68    5000 1623.18  5003.2 1623.68
  5017.8  1628.1  5023.6 1630.09  5030.3 1630.85  5077.1 1630.43  5085.1 1629.49
  5090.4 1626.48  5098.5  1625.8  5109.2 1626.49  5120.5 1629.33  5139.8 1629.27
    5152  1630.4    5230 1631.36  5309.5 1633.66  5339.5 1633.48  5369.6 1634.21
  5387.6  1635.7    5409  1634.1  5484.5 1636.74  5509.2 1636.08  5555.1 1637.64
#Mann= 6 ,-1 , 0
  4798.4     .05       0  4819.3      .1       0  4951.9     .05       0
  4997.2    .035       0  5003.2     .05       0  5017.8      .1       0
Bank Sta=4997.2,5003.2
XS Rating Curve= 0 ,0
Exp/Cntr=0.3,0.1

Type RM Length L Ch R = 1 ,3703    ,578,578,578
BEGIN DESCRIPTION:
UNT046 IN NNOGR 9.0
END DESCRIPTION:
XS GIS Cut Line= 2
      2778379.82     10072787.07      2778220.29     10071857.66
#Sta/Elev= 30
  4671.7 1633.14  4847.6 1629.04    4878 1627.22  4892.5 1627.21  4938.9 1624.49
  4949.9 1624.64  4959.2 1626.33  4969.3 1625.47  4996.8 1619.98  4999.5 1619.48
  5002.8 1619.98  5004.8 1620.05  5009.9 1621.56  5070.8  1625.1  5111.4 1624.83
  5131.7 1625.63  5179.7 1626.06  5202.7 1625.83    5223 1624.86  5234.8 1625.63
  5260.1 1626.05  5360.6 1628.32  5405.6 1628.89  5436.1 1630.38  5474.6 1629.23
  5486.8 1629.86    5568 1631.21  5594.6 1630.95  5599.7 1631.66  5614.7 1632.08
#Mann= 7 ,-1 , 0
  4671.7     .05       0  4892.5      .1       0  4996.8     .07       0
  5002.8      .1       0  5234.8     .05       0  5260.1      .1       0
  5360.6     .05       0
Bank Sta=4996.8,5002.8
XS Rating Curve= 0 ,0
Exp/Cntr=0.3,0.1

Type RM Length L Ch R = 1 ,3125    ,554,554,554
BEGIN DESCRIPTION:
UNT046 IN NNOGR 8.0
END DESCRIPTION:
XS GIS Cut Line= 2
      2778879.82      10072662.1      2778629.84     10071752.42
#Sta/Elev= 30
    4552  1627.9  4695.5 1625.52  4858.5 1623.96  4871.8 1624.22  4882.6 1624.97
  4892.5  1624.9  4902.9 1624.25  4911.9 1622.24  4923.7 1620.69  4951.5 1619.09
  4985.9 1618.81  4988.1 1618.34  4990.8 1617.84  4994.1 1618.34  5025.5 1618.94
  5030.7 1619.65  5036.7  1619.8  5065.1 1620.87  5131.1  1621.3  5162.2  1621.1
  5178.8 1622.03    5184 1621.03  5193.3 1621.55  5224.4 1621.96  5265.9 1621.81
  5297.6 1622.91  5338.5  1623.4  5440.5 1623.38  5485.3 1625.12  5495.4 1625.13
#Mann= 5 ,-1 , 0
    4552     .05       0  4858.5      .1       0  4988.1     .07       0
  4994.1      .1       0  5036.7     .05       0
Bank Sta=4988.1,4994.1
XS Rating Curve= 0 ,0
Exp/Cntr=0.3,0.1

Type RM Length L Ch R = 1 ,2571    ,288,288,288
BEGIN DESCRIPTION:
UNT046 IN NNOGR 6.0
END DESCRIPTION:
XS GIS Cut Line= 2
      2779275.66     10072398.21      2779164.56     10071613.54
#Sta/Elev= 30
  4652.5 1625.83  4697.4 1624.45  4778.2 1623.18  4788.3  1622.8  4807.1  1621.2
  4812.2  1621.4  4869.1 1619.71  4889.3 1618.42  4909.5 1616.33  4939.8 1616.26
  4980.2 1614.68  4994.8 1614.54  5025.2 1614.87  5037.8 1614.25  5040.6 1613.75
  5043.8 1614.25    5061 1614.43  5121.6 1618.81  5141.8 1621.23  5192.3 1621.67
  5222.6  1622.5  5243.3 1623.68  5252.9 1623.58  5273.1  1624.6  5303.4 1625.15
  5314.3 1626.15  5353.9 1627.56  5414.5 1628.96  5443.8 1630.57    5445 1630.57
#Mann= 5 ,-1 , 0
  4652.5     .05       0  4994.8      .1       0  5037.8     .07       0
  5043.8      .1       0  5443.8     .05       0
Bank Sta=5037.8,5043.8
XS Rating Curve= 0 ,0
Exp/Cntr=0.3,0.1

Type RM Length L Ch R = 1 ,2283    ,90,90,90
BEGIN DESCRIPTION:
Mapping XS 0048ad92
END DESCRIPTION:
XS GIS Cut Line= 2
      2779495.17     10072324.26      2779486.49     10071640.71
#Sta/Elev= 30
  4654.1 1623.85  4694.6 1623.43  4734.6 1621.88  4774.6 1619.92  4789.1 1619.73
  4804.6 1619.07  4824.6 1618.17  4854.6 1616.15  4884.6 1615.19  4904.6 1612.74
  4924.6 1614.19  4944.6 1613.78  4964.7 1612.14  4984.7 1608.68  5001.7 1608.28
  5004.4 1607.78  5007.7 1608.28  5024.7 1608.86  5034.7 1609.71  5054.7 1612.31
  5064.7 1613.18  5084.7 1614.17  5102.1 1615.75  5124.7 1617.48  5154.7 1618.42
  5184.7 1619.82  5224.7 1621.18  5264.7 1621.84  5317.2 1623.63  5337.7 1623.92
#Mann= 5 ,-1 , 0
  4654.1     .05       0  5001.7     .04       0  5007.7     .05       0
  5102.1      .1       0  5317.2     .05       0
Bank Sta=5001.7,5007.7
XS Rating Curve= 0 ,0
Exp/Cntr=0.3,0.1

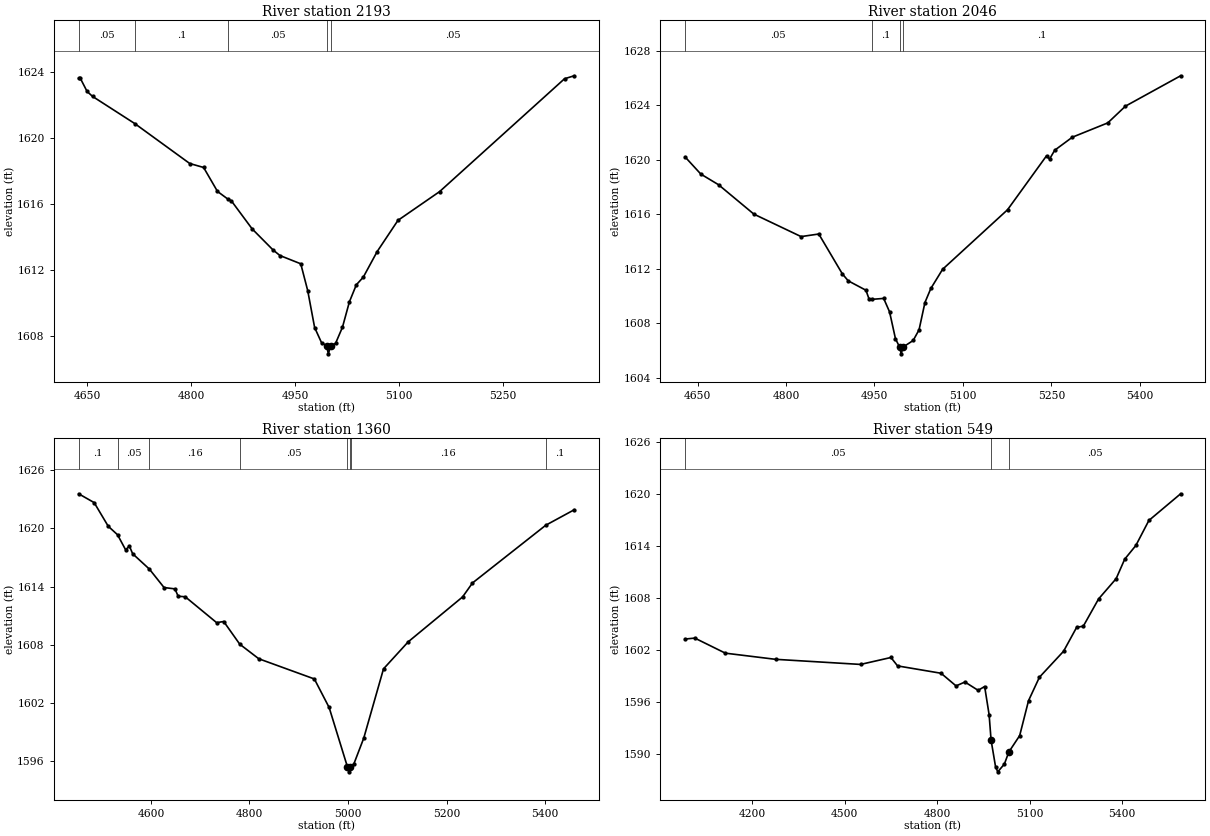
Type RM Length L Ch R = 1 ,2193    ,147,147,147
BEGIN DESCRIPTION:
Mapping XS c1de0d04
END DESCRIPTION:
XS GIS Cut Line= 2
       2779573.3     10072343.82      2779586.32     10071629.84
#Sta/Elev= 30
  4638.1 1623.59  4640.6 1623.59  4650.3  1622.8  4658.2  1622.5  4718.9 1620.86
  4798.2 1618.44  4818.2  1618.2  4838.2 1616.75  4853.7 1616.27  4858.2 1616.18
  4888.2 1614.48  4918.2 1613.21  4928.2 1612.87  4958.2 1612.37  4968.2 1610.75
  4978.2 1608.51  4988.3 1607.58  4995.3 1607.42    4998 1606.92  5001.3 1607.42
  5008.3 1607.55  5018.3 1608.53  5028.3 1610.07  5038.3  1611.1  5048.3 1611.56
  5068.3 1613.11  5098.3    1615  5158.3 1616.74  5338.3 1623.57  5352.2 1623.75
#Mann= 5 ,-1 , 0
  4638.1     .05       0  4718.9      .1       0  4853.7     .05       0
  4995.3     .04       0  5001.3     .05       0
Bank Sta=4995.3,5001.3
XS Rating Curve= 0 ,0
Exp/Cntr=0.3,0.1

Type RM Length L Ch R = 1 ,2046    ,686,686,686
BEGIN DESCRIPTION:
UNT046 IN NNOGR 4.0
END DESCRIPTION:
XS GIS Cut Line= 2
      2779713.16     10072370.41      2779740.94     10071530.16
#Sta/Elev= 30
  4628.7 1620.22  4655.4 1618.96  4685.4 1618.18  4745.4 1616.02  4825.5 1614.37
  4855.5 1614.56  4895.5 1611.63  4905.5 1611.12  4935.5 1610.43  4940.5 1609.82
  4945.1 1609.76  4965.6 1609.83  4975.6 1608.84  4985.6 1606.87  4992.6 1606.26
  4995.3 1605.76  4998.6 1606.26  5015.6 1606.74  5025.6 1607.52  5035.6 1609.53
  5045.6 1610.56  5065.6 1611.97  5175.7 1616.34    5242 1620.31    5247 1620.06
  5255.7 1620.71  5285.7 1621.67  5345.8 1622.72  5375.8 1623.95  5469.4 1626.18
#Mann= 4 ,-1 , 0
  4628.7     .05       0  4945.1      .1       0  4992.6     .07       0
  4998.6      .1       0
Bank Sta=4992.6,4998.6
XS Rating Curve= 0 ,0
Exp/Cntr=0.3,0.1

Type RM Length L Ch R = 1 ,1360    ,811,811,811
BEGIN DESCRIPTION:
UNT046 IN NNOGR 2.0
END DESCRIPTION:
XS GIS Cut Line= 3
      2780063.72      10072543.5      2780361.06     10072189.74
      2780322.05     10071647.97
#Sta/Elev= 30
  4453.4 1623.56  4484.9 1622.65  4513.5 1620.21  4532.3 1619.34  4548.7 1617.79
  4556.4 1618.17    4563 1617.38  4596.9  1615.8  4626.7  1613.9  4648.8 1613.76
  4655.3    1613  4669.6 1612.95  4733.4 1610.28  4747.7  1610.4  4780.3 1608.06
  4818.9 1606.56  4931.6 1604.48  4961.6 1601.54  4998.8 1595.41  5001.5 1594.91
  5004.8 1595.41  5005.4 1595.44  5011.8 1595.73  5031.8 1598.38  5071.9 1605.52
  5122.1 1608.31  5232.3 1612.93  5252.4 1614.37  5401.1 1620.32  5458.7 1621.91
#Mann= 8 ,-1 , 0
  4453.4      .1       0  4532.3     .05       0  4596.9     .16       0
  4780.3     .05       0  4998.8    .035       0  5004.8     .05       0
  5005.4     .16       0  5401.1      .1       0
Bank Sta=4998.8,5004.8
XS Rating Curve= 0 ,0
Exp/Cntr=0.3,0.1

Type RM Length L Ch R = 1 ,549     ,0,0,0
BEGIN DESCRIPTION:
UNT046 IN NNOGR 1.0
END DESCRIPTION:
XS GIS Cut Line= 3
      2780643.15     10072793.06      2781237.79     10072150.68
      2780664.86     10071692.77
#Sta/Elev= 30
  3981.5 1603.22    4013 1603.33  4112.2 1601.59    4275 1600.88  4551.1 1600.29
  4649.8 1601.09  4671.3 1600.12  4812.5 1599.27  4861.2 1597.81    4890 1598.26
  4932.8  1597.3    4954 1597.74  4968.5 1594.49  4974.9 1591.55  4989.3  1588.5
  4996.6 1587.89  5018.1 1588.79  5032.5 1590.18  5067.7 1592.07  5096.5 1596.11
  5131.8 1598.81  5210.2 1601.81  5252.8 1604.58  5274.2  1604.7  5323.9 1607.85
  5380.9 1610.19  5408.7 1612.44  5444.9 1614.02  5487.2 1616.91  5590.3 1619.99
#Mann= 3 , 0 , 0
  3981.5     .05       0  4974.9     .03       0  5032.5     .05       0
Bank Sta=4974.9,5032.5
XS Rating Curve= 0 ,0
Exp/Cntr=0.3,0.1

Chan Stop Cuts=-1
Use User Specified Reach Order=0
Composite Channel Slope=5