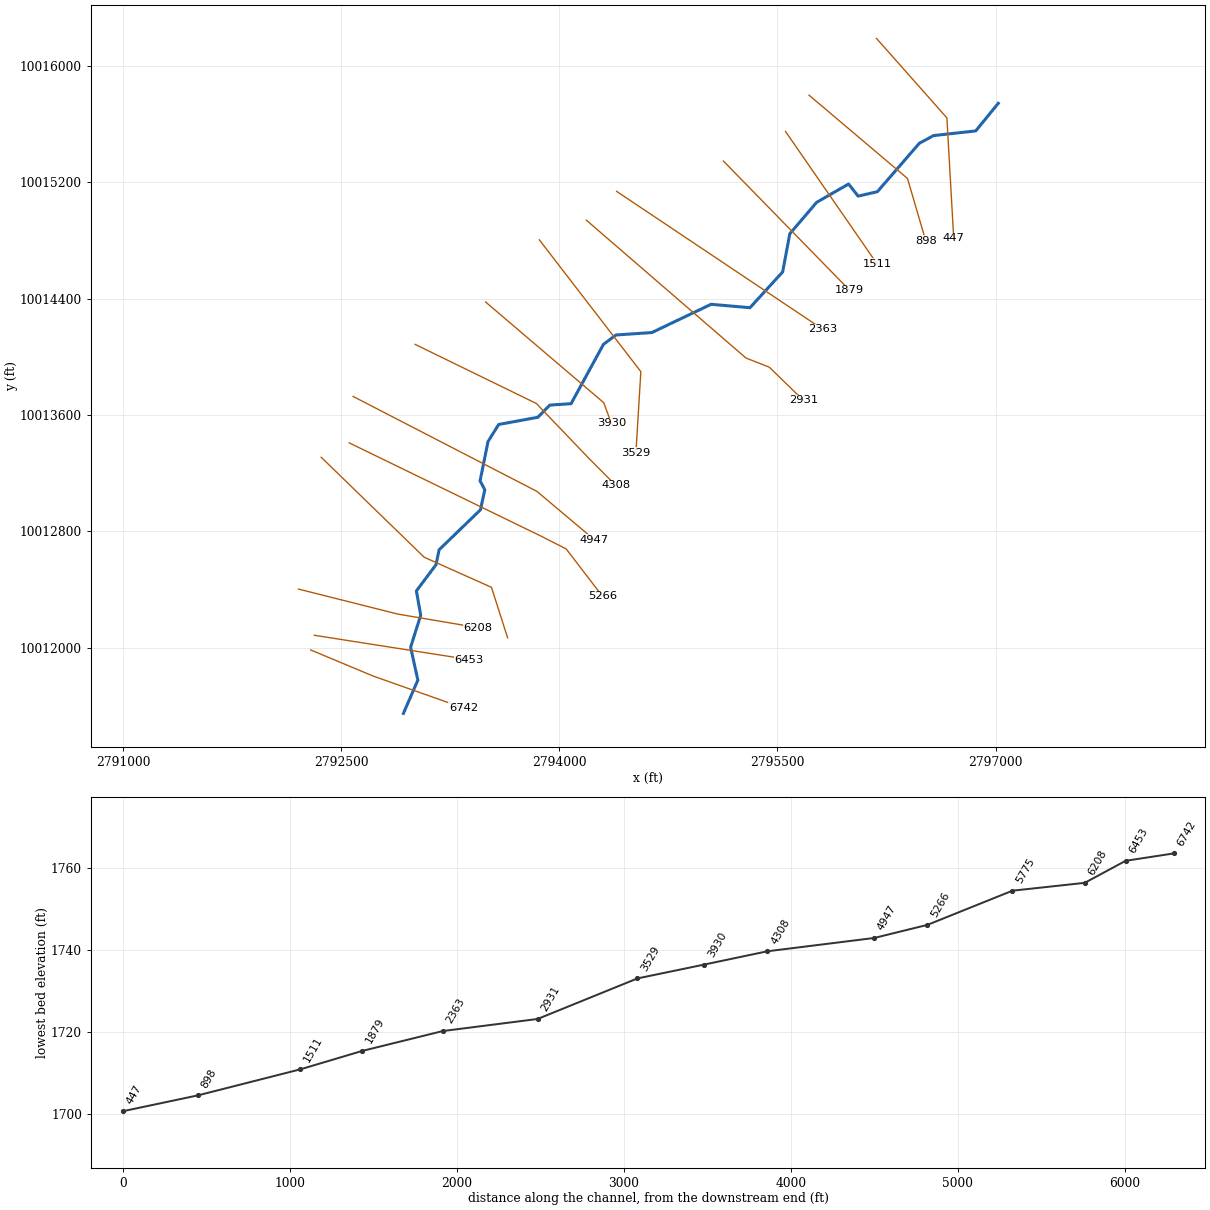
--- UNT046 IN SNOGR.prj (project) ---

Proj Title=UNT046 IN SNOGR Base Level Engineering
Current Plan=p01
Default Exp/Contr=0.3,0.1
English Units
Geom File=g01
Flow File=f01
Plan File=p01
Y Axis Title=Elevation
X Axis Title(PF)=Main Channel Distance
X Axis Title(XS)=Station
BEGIN DESCRIPTION:
UNT046 IN SNOGR
END DESCRIPTION:
DSS Export Rating Curves= 0
DSS Export Rating Curve Sorted= 0
DSS Export Volume Flow Curves= 0
DXF OffsetX= 0
DXF OffsetY= 0
DXF ScaleX= 1
DXF ScaleY= 10

--- UNT046 IN SNOGR.p01 (plan) ---

Plan Title=Multiple Run
Short Identifier=Multiple
Geom File=g01
Flow File=f01
Subcritical Flow
K Sum by GR= 0
Std Step Tol= 0.01
Critical Tol= 0.01
Num of Std Step Trials= 20
Max Error Tol= 0.3
Flow Tol Ratio= 0.001
Split Flow NTrial= 30
Split Flow Tol= 0.02
Split Flow Ratio= 0.02
Log Output Level= 0
Friction Slope Method= 1
Unsteady Friction Slope Method= 2
Unsteady Bridges Friction Slope Method= 1
Parabolic Critical Depth
Global Vel Dist=  1 , 1 , 1
Global Log Level= 0
CheckData=True
Encroach Param= -1, 0, 0, 0
BEGIN DESCRIPTION:
Multiple Run
END DESCRIPTION:

--- UNT046 IN SNOGR.f01 (steady flow) ---

Flow Title=Multiple
Number of Profiles=7
Profile Names=10-year,25-year,50-year,1pct_min,100-year,1pct_plu,500-year
River Rch & RM= UNT046 IN SNOGR,Reach-1,6742
    1311    1944    2505    2361    3193    4318    5210
Boundary for River Rch & Prof#=UNT046 IN SNOGR,Reach-1,1
Up Type=0
Dn Type=3
Dn Slope=0.005
Boundary for River Rch & Prof#=UNT046 IN SNOGR,Reach-1,2
Up Type=0
Dn Type=3
Dn Slope=0.005
Boundary for River Rch & Prof#=UNT046 IN SNOGR,Reach-1,3
Up Type=0
Dn Type=3
Dn Slope=0.005
Boundary for River Rch & Prof#=UNT046 IN SNOGR,Reach-1,4
Up Type=0
Dn Type=3
Dn Slope=0.005
Boundary for River Rch & Prof#=UNT046 IN SNOGR,Reach-1,5
Up Type=0
Dn Type=3
Dn Slope=0.005
Boundary for River Rch & Prof#=UNT046 IN SNOGR,Reach-1,6
Up Type=0
Dn Type=3
Dn Slope=0.005
Boundary for River Rch & Prof#=UNT046 IN SNOGR,Reach-1,7
Up Type=0
Dn Type=3
Dn Slope=0.005

--- UNT046 IN SNOGR.g01 (geometry) ---

Geom Title=Existing Conditions
Program Version=4.10

River Reach=UNT046 IN SNOGR ,Reach-1
Reach XY= 30
       2792928.6     10011549.18      2793027.92     10011777.97
      2792978.06     10012003.75      2793047.63     10012224.24
      2793017.76     10012391.08       2793152.8     10012571.13
      2793173.83     10012673.76      2793458.26     10012948.82
       2793488.4     10013086.73      2793455.62     10013147.66
      2793510.28     10013417.98      2793583.74     10013535.55
      2793853.03     10013585.06       2793935.1     10013668.78
      2794081.23      10013678.3      2794303.92      10014086.3
      2794389.75     10014150.75      2794636.89     10014167.52
      2795044.09     10014361.87      2795311.37     10014338.28
      2795536.16      10014584.6      2795585.17     10014846.57
      2795769.48     10015062.58      2795989.54     10015188.87
      2796054.57     10015105.57      2796187.52     10015136.13
      2796475.74     10015468.86      2796573.85     10015521.88
      2796863.38     10015553.73      2797018.47     10015743.73

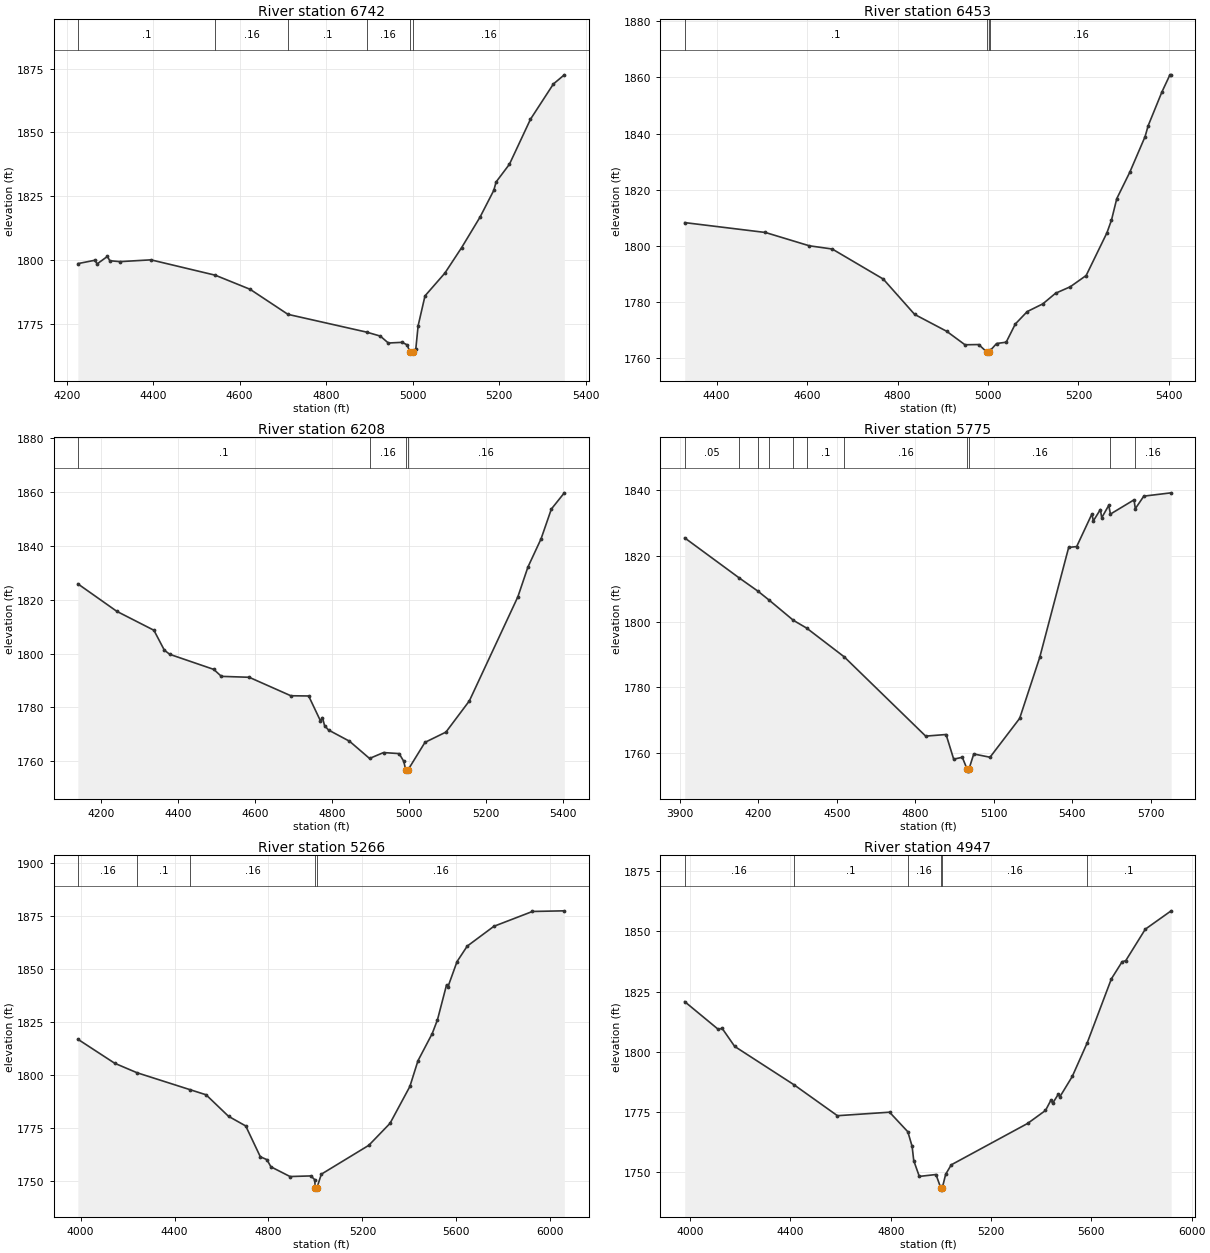
Type RM Length L Ch R = 1 ,6742    ,289,289,289
BEGIN DESCRIPTION:
UNT046 IN SNOGR 15.0
END DESCRIPTION:
XS GIS Cut Line= 3
      2792290.92     10011985.31      2792722.55     10011804.97
      2793342.29     10011586.23
#Sta/Elev= 30
  4225.9 1798.56    4265 1799.87  4270.5 1798.45  4294.3 1801.39  4299.7 1799.69
  4323.5 1799.34  4394.9 1800.04  4543.7 1794.02  4624.2  1788.5  4711.8 1778.68
  4893.7 1771.72  4925.3 1770.17  4943.9 1767.45  4975.7 1767.72  4987.2 1766.75
  4993.9 1763.99  4996.6 1763.49  4999.9 1763.99  5007.5 1765.23  5012.8 1774.21
  5028.7 1785.92  5074.7 1794.85  5113.5 1804.86    5156 1816.79  5187.8 1827.27
  5193.1 1830.55    5224 1837.51  5272.6 1855.12  5325.6 1868.94  5350.9 1872.53
#Mann= 6 ,-1 , 0
  4225.9      .1       0  4543.7     .16       0  4711.8      .1       0
  4893.7     .16       0  4993.9     .07       0  4999.9     .16       0
Bank Sta=4993.9,4999.9
XS Rating Curve= 0 ,0
Exp/Cntr=0.3,0.1

Type RM Length L Ch R = 1 ,6453    ,245,245,245
BEGIN DESCRIPTION:
UNT046 IN SNOGR 14.0
END DESCRIPTION:
XS GIS Cut Line= 2
      2792316.25     10012086.22      2793378.76     10011919.56
#Sta/Elev= 30
  4329.4 1808.24  4507.8 1804.72  4604.9 1799.97  4655.6 1798.82  4768.4 1788.11
  4837.8  1775.5  4908.6 1769.48  4949.1 1764.67  4979.5 1764.75  4996.7 1762.19
  4999.5 1761.69  5002.7 1762.19    5005 1762.63    5019 1765.12  5040.2 1765.59
  5060.4 1772.08  5086.7 1776.51  5121.2 1779.26  5149.3 1783.04  5181.9 1785.36
    5217 1789.37  5262.9 1804.59    5273 1809.14  5284.7 1816.79  5313.5 1826.22
  5347.3 1838.92    5354 1842.76  5384.4  1854.8  5402.2 1860.94  5404.9 1860.94
#Mann= 4 ,-1 , 0
  4329.4      .1       0  4996.7     .07       0  5002.7      .1       0
    5005     .16       0
Bank Sta=4996.7,5002.7
XS Rating Curve= 0 ,0
Exp/Cntr=0.3,0.1

Type RM Length L Ch R = 1 ,6208    ,433,433,433
BEGIN DESCRIPTION:
UNT046 IN SNOGR 13.0
END DESCRIPTION:
XS GIS Cut Line= 3
      2792206.89     10012403.93      2792889.21     10012232.05
       2793441.7     10012138.42
#Sta/Elev= 30
  4140.4 1825.95  4241.8 1815.72    4338  1808.7  4365.1  1801.3  4379.2 1799.75
  4493.5 1794.15  4513.3 1791.56  4585.5 1791.22  4693.8 1784.35  4740.1 1784.27
  4770.8    1775    4776 1776.22  4781.4 1773.26  4791.7 1771.61  4846.2 1767.45
  4898.3 1761.04  4934.6 1763.23  4975.1 1762.85    4987 1760.04  4992.4 1756.83
  4995.2 1756.33  4998.4 1756.83  5042.3 1767.02  5096.8 1770.84  5157.7 1782.46
  5283.7 1821.14  5309.8 1832.19    5344  1842.7  5370.7 1853.76  5404.4 1859.79
#Mann= 4 ,-1 , 0
  4140.4      .1       0  4898.3     .16       0  4992.4     .07       0
  4998.4     .16       0
Bank Sta=4992.4,4998.4
XS Rating Curve= 0 ,0
Exp/Cntr=0.3,0.1

Type RM Length L Ch R = 1 ,5775    ,509,509,509
BEGIN DESCRIPTION:
UNT046 IN SNOGR 12.0
END DESCRIPTION:
XS GIS Cut Line= 4
      2792363.15     10013310.19       2793071.5     10012622.67
        2793534.     10012415.86       2793645.1     10012068.67
#Sta/Elev= 30
  3918.9 1825.51  4127.2  1813.3    4199 1809.25  4240.9 1806.58  4334.3 1800.37
  4384.5 1798.03    4528 1789.27  4839.5 1765.09  4917.4 1765.58  4946.5 1758.07
  4979.4 1758.64  4998.3 1754.92  5001.1 1754.42  5004.3 1754.92  5023.2 1759.65
  5085.3 1758.65  5198.5  1770.5  5275.2  1789.1  5385.7 1822.59  5416.4 1822.87
  5474.6 1832.81  5479.9 1830.67  5506.8 1834.15    5512 1831.64  5538.9 1835.44
  5545.2 1832.76  5635.4  1837.1  5640.3 1834.41  5672.8 1838.23  5777.2 1839.24
#Mann= 11 ,-1 , 0
  3918.9     .05       0  4127.2      .1       0    4199     .16       0
  4240.9      .1       0  4334.3     .05       0  4384.5      .1       0
    4528     .16       0  4998.3     .07       0  5004.3     .16       0
  5545.2      .1       0  5640.3     .16       0
Bank Sta=4998.3,5004.3
XS Rating Curve= 0 ,0
Exp/Cntr=0.3,0.1

Type RM Length L Ch R = 1 ,5266    ,319,319,319
BEGIN DESCRIPTION:
UNT046 IN SNOGR 11.0
END DESCRIPTION:
XS GIS Cut Line= 4
      2792555.86     10013409.14        2793884.      10012763.3
      2794047.89     10012679.74      2794297.86     10012353.38
#Sta/Elev= 30
  3988.1  1816.8  4145.1 1805.47  4239.9 1801.01    4464 1793.08  4534.1 1790.61
  4629.8 1780.46  4703.1  1775.9  4765.2 1761.38  4793.3 1760.01  4810.3 1756.64
  4891.7 1752.05  4980.6 1752.34  4996.3 1750.62  4999.9 1746.61  5002.6 1746.11
  5005.9 1746.61  5025.1 1753.16  5227.3 1766.78  5317.6 1777.13  5402.2 1794.53
  5436.6 1806.65  5497.5 1819.51  5519.8 1826.02  5558.6 1842.54  5564.2 1841.47
  5603.1 1853.43  5646.4 1860.72  5760.1 1870.07  5924.3 1877.07    6060 1877.37
#Mann= 5 ,-1 , 0
  3988.1     .16       0  4239.9      .1       0    4464     .16       0
  4999.9     .07       0  5005.9     .16       0
Bank Sta=4999.9,5005.9
XS Rating Curve= 0 ,0
Exp/Cntr=0.3,0.1

Type RM Length L Ch R = 1 ,4947    ,639,639,639
BEGIN DESCRIPTION:
UNT046 IN SNOGR 10.0
END DESCRIPTION:
XS GIS Cut Line= 3
      2792582.59     10013728.36       2793846.5     10013075.58
      2794242.32     10012742.25
#Sta/Elev= 30
  3978.2 1820.81  4111.2 1809.37  4127.7 1809.69  4177.6  1802.2  4413.9 1786.29
  4587.3 1773.42  4795.2 1774.88  4868.1 1766.75  4885.2 1760.68  4891.7 1754.74
  4913.9  1748.2  4980.3 1748.99  4999.5 1743.42  5002.2 1742.92  5005.5 1743.42
    5019  1749.1  5041.2 1753.01  5345.7  1770.2  5417.1  1775.6  5439.2 1779.96
  5445.7 1778.58  5467.8  1782.3  5474.3 1781.25  5523.8 1789.71  5583.8 1803.78
  5679.8 1830.27  5722.7 1837.38    5737 1837.81  5815.1  1850.9  5918.2 1858.53
#Mann= 6 ,-1 , 0
  3978.2     .16       0  4413.9      .1       0  4868.1     .16       0
  4999.5     .07       0  5005.5     .16       0  5583.8      .1       0
Bank Sta=4999.5,5005.5
XS Rating Curve= 0 ,0
Exp/Cntr=0.3,0.1

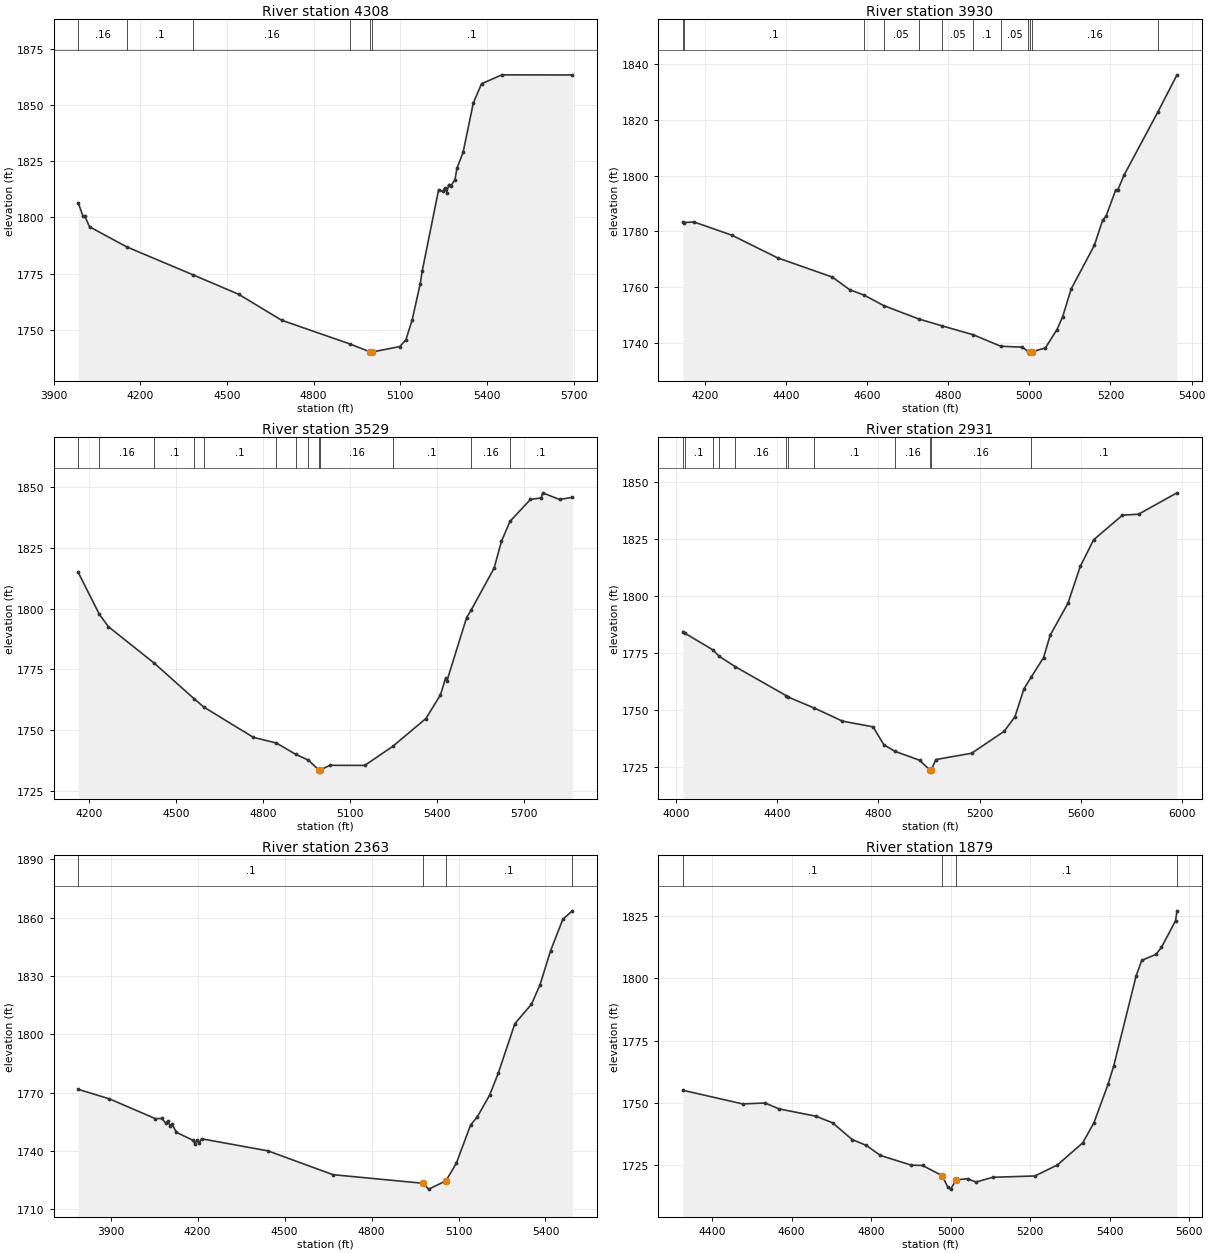
Type RM Length L Ch R = 1 ,4308    ,378,378,378
BEGIN DESCRIPTION:
UNT046 IN SNOGR 9.0
END DESCRIPTION:
XS GIS Cut Line= 4
      2793009.02     10014086.21      2793842.34     10013679.97
       2794196.5     10013310.17      2794387.42     10013117.99
#Sta/Elev= 30
  3985.3 1806.54  4001.9 1800.52  4007.4 1800.74  4024.4 1795.86  4153.8 1786.89
  4383.1 1774.48  4540.9 1765.82  4689.1 1754.32  4925.4 1743.77    4996 1740.19
  4998.7 1739.69    5002 1740.19    5098 1742.61  5119.1 1745.59  5140.5 1754.33
  5168.8 1770.51  5175.7 1776.28  5232.3 1812.32  5246.5 1811.61  5253.4  1813.1
  5260.6 1811.11  5267.5 1814.67  5274.8  1814.1  5288.9 1816.81  5295.8 1821.88
  5317.2 1829.03  5352.4 1850.89  5380.8 1859.46  5451.6 1863.44  5695.3 1863.37
#Mann= 6 ,-1 , 0
  3985.3     .16       0  4153.8      .1       0  4383.1     .16       0
  4925.4      .1       0    4996     .07       0    5002      .1       0
Bank Sta=4996,5002
XS Rating Curve= 0 ,0
Exp/Cntr=0.3,0.1

Type RM Length L Ch R = 1 ,3930    ,401,401,401
BEGIN DESCRIPTION:
UNT046 IN SNOGR 8.0
END DESCRIPTION:
XS GIS Cut Line= 3
       2793493.4     10014377.87      2794305.88     10013685.17
      2794357.95     10013544.59
#Sta/Elev= 30
  4146.3 1783.34  4149.2  1783.2  4174.2 1783.36  4266.5 1778.69  4379.6 1770.56
  4514.6 1763.67  4557.4 1759.15    4593 1757.21  4641.1 1753.48  4727.6 1748.68
  4785.4  1746.2  4862.2 1743.02  4929.7 1738.92  4982.4  1738.6  4996.8 1737.12
  5001.3 1736.96  5004.1 1736.46  5007.3 1736.96  5039.5 1738.32    5068 1744.85
  5082.3 1749.55  5103.1  1759.4  5160.3 1775.04  5181.1 1784.21  5188.8 1785.35
  5212.4 1794.66  5217.4 1794.66  5233.7 1800.22  5316.8 1822.75  5363.9 1836.04
#Mann= 12 ,-1 , 0
  4146.3     .16       0  4149.2      .1       0    4593     .16       0
  4641.1     .05       0  4727.6      .1       0  4785.4     .05       0
  4862.2      .1       0  4929.7     .05       0  4996.8     .16       0
  5001.3     .07       0  5007.3     .16       0  5316.8      .1       0
Bank Sta=5001.3,5007.3
XS Rating Curve= 0 ,0
Exp/Cntr=0.3,0.1

Type RM Length L Ch R = 1 ,3529    ,598,598,598
BEGIN DESCRIPTION:
UNT046 IN SNOGR 7.0
END DESCRIPTION:
XS GIS Cut Line= 3
      2793863.19     10014804.94      2794561.09     10013898.72
      2794527.05     10013339.46
#Sta/Elev= 30
  4162.2 1814.92  4235.1 1797.63    4266  1792.6  4425.1 1777.47  4561.8 1762.89
  4595.6 1759.44  4766.2 1746.99  4845.5 1744.66  4912.9 1739.96  4956.2  1737.6
  4991.5 1733.58  4994.2 1733.08  4997.5 1733.58  5029.8 1735.48  5150.3 1735.44
  5246.3 1743.23  5361.1 1754.74  5411.2 1764.44  5428.8 1771.32  5433.9 1770.33
  5501.4 1796.28  5517.1  1799.4  5596.3 1816.68  5621.6 1827.69  5651.3 1835.99
  5721.8 1844.99  5758.8  1845.6  5763.8  1847.7  5821.9 1844.96  5866.3 1845.85
#Mann= 13 ,-1 , 0
  4162.2     .05       0  4235.1     .16       0  4425.1      .1       0
  4561.8     .16       0  4595.6      .1       0  4845.5     .05       0
  4912.9      .1       0  4956.2     .16       0  4991.5     .07       0
  4997.5     .16       0  5246.3      .1       0  5517.1     .16       0
  5651.3      .1       0
Bank Sta=4991.5,4997.5
XS Rating Curve= 0 ,0
Exp/Cntr=0.3,0.1

Type RM Length L Ch R = 1 ,2931    ,568,568,568
BEGIN DESCRIPTION:
UNT046 IN SNOGR 6.0
END DESCRIPTION:
XS GIS Cut Line= 4
      2794186.05     10014940.41        2795284.     10013992.24
      2795443.72     10013929.74       2795679.8     10013700.61
#Sta/Elev= 30
  4027.7 1784.35  4034.5 1783.69  4148.4 1776.18  4169.9 1773.59  4234.7 1768.96
  4435.1 1756.31  4442.7 1755.71  4546.7 1750.85    4658 1745.11  4778.7 1742.61
  4821.5 1734.76  4865.2  1731.9    4963 1727.96  5002.8 1723.72  5005.5 1723.22
  5008.8 1723.72  5026.6 1728.29  5168.1 1731.06  5296.4 1740.65    5339 1747.02
  5374.3 1759.19    5403 1764.36  5452.2 1772.97    5478 1782.72    5548 1796.66
  5596.9 1812.85  5649.8 1824.53  5763.6  1835.3  5827.2 1835.72  5978.9 1845.08
#Mann= 12 ,-1 , 0
  4027.7     .16       0  4034.5      .1       0  4148.4     .16       0
  4169.9      .1       0  4234.7     .16       0  4435.1      .1       0
  4442.7     .16       0  4546.7      .1       0  4865.2     .16       0
  5002.8     .07       0  5008.8     .16       0    5403      .1       0
Bank Sta=5002.8,5008.8
XS Rating Curve= 0 ,0
Exp/Cntr=0.3,0.1

Type RM Length L Ch R = 1 ,2363    ,484,484,484
BEGIN DESCRIPTION:
UNT046 IN SNOGR 5.0
END DESCRIPTION:
XS GIS Cut Line= 2
      2794394.39     10015138.32       2795811.1     10014190.37
#Sta/Elev= 30
  3788.2 1771.62  3895.4 1766.76  4054.5 1756.55  4075.5 1756.64  4090.5 1754.26
  4096.5 1755.15  4105.5 1752.88  4111.5 1753.81  4126.6 1749.52  4183.6 1745.45
  4190.2 1743.74  4198.6 1745.47  4204.6 1743.86  4213.6 1746.19  4442.8 1739.97
    4667 1727.71  4976.3 1723.31    4997 1720.28  5056.5 1724.51  5092.6 1733.65
  5141.4 1753.22  5164.8 1757.49  5207.5 1768.72    5237 1779.93  5294.5 1805.48
  5351.6 1815.44  5381.3 1825.51  5417.4 1842.92  5459.7 1859.14  5492.8 1863.51
#Mann= 4 ,-1 , 0
  3788.2      .1       0  4976.3     .07       0  5056.5      .1       0
  5492.8     .16       0
Bank Sta=4976.3,5056.5
XS Rating Curve= 0 ,0
Exp/Cntr=0.3,0.1

Type RM Length L Ch R = 1 ,1879    ,368,368,368
BEGIN DESCRIPTION:
UNT046 IN SNOGR 4.0
END DESCRIPTION:
XS GIS Cut Line= 2
      2795128.82     10015346.61      2795997.29     10014457.34
#Sta/Elev= 30
  4326.6 1755.07  4476.9  1749.6  4533.5 1749.96  4568.7  1747.6  4660.8 1744.69
  4703.2 1742.02  4752.6  1735.3  4788.1 1732.96  4823.4 1728.94  4901.2 1725.05
  4929.5 1724.93    4979 1720.82  4993.1 1716.25    5000 1715.43  5014.4 1719.14
  5042.7  1719.6  5063.8 1718.27  5106.3 1720.18  5212.3 1720.71  5268.8 1725.12
  5332.6 1734.01  5360.9 1742.12  5396.1 1757.46  5410.3 1764.74  5466.9    1801
    5481 1807.16  5516.5 1809.52  5530.6 1812.39  5565.9 1823.04  5569.6 1827.01
#Mann= 4 ,-1 , 0
  4326.6      .1       0    4979     .07       0  5014.4      .1       0
  5569.6     .16       0
Bank Sta=4979,5014.4
XS Rating Curve= 0 ,0
Exp/Cntr=0.3,0.1

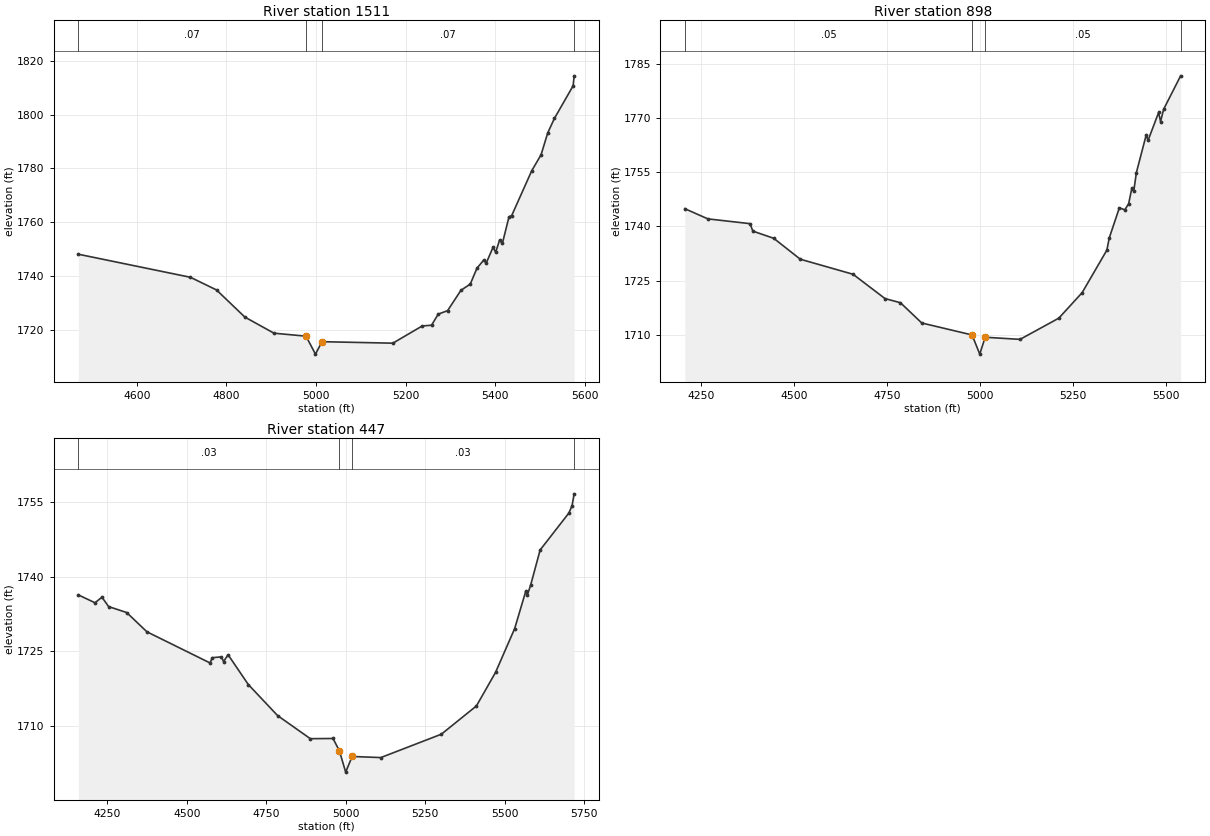
Type RM Length L Ch R = 1 ,1511    ,613,613,613
BEGIN DESCRIPTION:
UNT046 IN SNOGR 3.0
END DESCRIPTION:
XS GIS Cut Line= 2
      2795555.91     10015549.72      2796185.94     10014638.52
#Sta/Elev= 30
    4469  1748.1  4719.4 1739.53  4777.7 1734.83    4841 1724.75  4906.1 1718.76
  4977.7 1717.65  4998.8 1710.98  5013.5  1715.6  5171.7 1715.05  5237.3 1721.44
  5258.2 1721.73  5273.1 1725.84    5294 1727.13  5323.8 1734.69  5344.7    1737
  5359.6 1742.91  5374.5 1745.86  5380.5 1744.86  5395.4 1750.63  5401.5 1748.87
  5410.3 1753.41  5416.4 1752.09  5431.2 1761.98  5437.3 1762.48  5481.9 1779.08
  5502.9 1785.06  5517.7 1793.15  5532.6 1798.54  5574.5 1810.69  5576.8 1814.38
#Mann= 4 ,-1 , 0
    4469     .07       0  4977.7     .05       0  5013.5     .07       0
  5576.8     .16       0
Bank Sta=4977.7,5013.5
XS Rating Curve= 0 ,0
Exp/Cntr=0.3,0.1

Type RM Length L Ch R = 1 ,898     ,451,451,451
BEGIN DESCRIPTION:
UNT046 IN SNOGR 2.0
END DESCRIPTION:
XS GIS Cut Line= 3
       2795717.3     10015799.79      2796394.42     10015226.84
      2796519.42     10014799.75
#Sta/Elev= 30
  4207.3 1744.88  4269.3 1742.06  4382.4 1740.74  4390.2 1738.67  4446.2 1736.69
  4517.6  1730.9  4659.3 1726.74  4745.1 1720.02  4786.7 1718.86  4843.9 1713.26
  4979.1 1709.95  4999.7 1704.65  5014.2 1709.32  5107.9 1708.73  5212.1  1714.6
  5274.7 1721.65  5341.2 1733.42  5347.6  1736.8  5374.7 1745.12  5389.3 1744.56
  5399.7 1746.26  5408.1 1750.49  5413.3 1749.67  5420.5 1754.88  5446.7 1765.22
  5451.9 1763.78  5480.2 1771.49  5485.4 1768.97  5493.5 1772.35  5539.3 1781.63
#Mann= 4 ,-1 , 0
  4207.3     .05       0  4979.1     .03       0  5014.2     .05       0
  5539.3      .1       0
Bank Sta=4979.1,5014.2
XS Rating Curve= 0 ,0
Exp/Cntr=0.3,0.1

Type RM Length L Ch R = 1 ,447     ,0,0,0
BEGIN DESCRIPTION:
UNT046 IN SNOGR 1.0
END DESCRIPTION:
XS GIS Cut Line= 3
      2796180.85     10016190.41      2796665.25     10015643.51
      2796712.04     10014817.01
#Sta/Elev= 30
  4159.3 1736.34  4211.7 1734.76  4233.5 1735.88  4254.4    1734  4311.3  1732.8
  4374.8 1728.94  4573.1 1722.69  4580.6 1723.74    4609 1723.91  4615.7 1722.96
  4629.9 1724.34  4693.5 1718.36  4785.5 1712.13  4888.5 1707.49  4959.8 1707.53
  4979.8 1705.06  4999.6 1700.78  5019.9 1703.92    5110  1703.7  5300.3 1708.39
  5410.5 1714.06  5470.6 1720.79  5530.7 1729.58  5565.9 1737.14  5570.9 1736.38
  5580.8 1738.27  5610.8 1745.36    5701 1752.76    5711 1754.22  5717.7 1756.62
#Mann= 4 ,-1 , 0
  4159.3     .03       0  4979.8    .025       0  5019.9     .03       0
  5717.7      .1       0
Bank Sta=4979.8,5019.9
XS Rating Curve= 0 ,0
Exp/Cntr=0.3,0.1

Chan Stop Cuts=-1
Use User Specified Reach Order=0
Composite Channel Slope=5