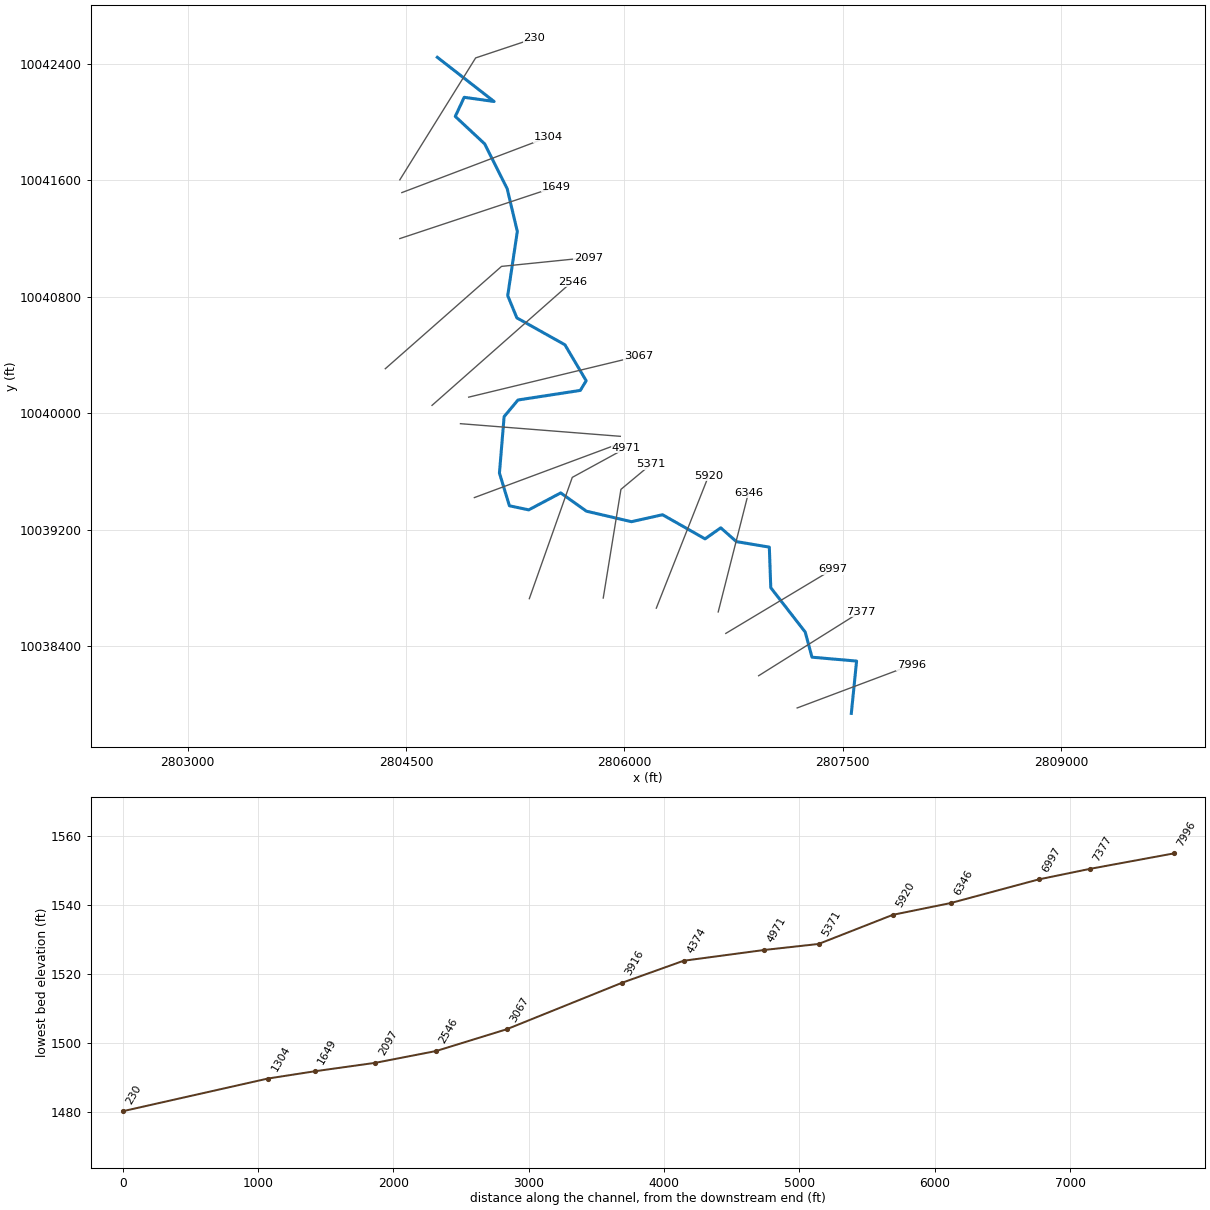
--- UNT048 IN SNOGR.prj (project) ---

Proj Title=UNT048 IN SNOGR Base Level Engineering
Current Plan=p01
Default Exp/Contr=0.3,0.1
English Units
Geom File=g01
Flow File=f01
Plan File=p01
BEGIN DESCRIPTION:
UNT048 IN SNOGR
END DESCRIPTION:

--- UNT048 IN SNOGR.p01 (plan) ---

Plan Title=Multiple Run
Short Identifier=Multiple
Geom File=g01
Flow File=f01
Subcritical Flow
K Sum by GR= 0
Std Step Tol= 0.01
Critical Tol= 0.01
Num of Std Step Trials= 20
Max Error Tol= 0.3
Flow Tol Ratio= 0.001
Split Flow NTrial= 30
Split Flow Tol= 0.02
Split Flow Ratio= 0.02
Log Output Level= 0
Friction Slope Method= 1
Unsteady Friction Slope Method= 2
Unsteady Bridges Friction Slope Method= 1
Parabolic Critical Depth
Global Vel Dist=  1 , 1 , 1
Global Log Level= 0
CheckData=True
Encroach Param= -1, 0, 0, 0
BEGIN DESCRIPTION:
Multiple Run
END DESCRIPTION:

--- UNT048 IN SNOGR.f01 (steady flow) ---

Flow Title=Multiple
Number of Profiles=7
Profile Names=10-year,25-year,50-year,1pct_min,100-year,1pct_plu,500-year
River Rch & RM= UNT048 IN SNOGR,Reach-1,7996
     774    1112    1403    1296    1753    2370    2746
River Rch & RM= UNT048 IN SNOGR,Reach-1,6997
    1127    1647    2102    1962    2653    3588    4243
Boundary for River Rch & Prof#=UNT048 IN SNOGR,Reach-1,1
Up Type=0
Dn Type=3
Dn Slope=0.005
Boundary for River Rch & Prof#=UNT048 IN SNOGR,Reach-1,2
Up Type=0
Dn Type=3
Dn Slope=0.005
Boundary for River Rch & Prof#=UNT048 IN SNOGR,Reach-1,3
Up Type=0
Dn Type=3
Dn Slope=0.005
Boundary for River Rch & Prof#=UNT048 IN SNOGR,Reach-1,4
Up Type=0
Dn Type=3
Dn Slope=0.005
Boundary for River Rch & Prof#=UNT048 IN SNOGR,Reach-1,5
Up Type=0
Dn Type=3
Dn Slope=0.005
Boundary for River Rch & Prof#=UNT048 IN SNOGR,Reach-1,6
Up Type=0
Dn Type=3
Dn Slope=0.005
Boundary for River Rch & Prof#=UNT048 IN SNOGR,Reach-1,7
Up Type=0
Dn Type=3
Dn Slope=0.005

--- UNT048 IN SNOGR.g01 (geometry) ---

Geom Title=Existing Conditions

River Reach=UNT048 IN SNOGR,Reach-1
Reach XY= 30
      2807559.66     10037937.53      2807595.79     10038296.86
      2807289.36     10038323.57      2807242.86     10038496.24
      2807006.23     10038800.81      2806996.29     10039079.79
      2806769.83     10039117.73      2806662.70     10039212.43
      2806554.74     10039136.49      2806262.67     10039302.34
      2806048.88     10039254.58      2805739.75     10039326.67
      2805562.90     10039452.16      2805343.02     10039335.72
      2805210.43     10039363.91      2805141.97     10039588.76
      2805174.08     10039976.28      2805269.48     10040090.66
      2805697.74     10040156.54      2805737.97     10040222.98
      2805591.80     10040470.08      2805261.59     10040654.96
      2805198.84     10040807.65      2805264.81     10041248.76
      2805195.07     10041542.59      2805040.30     10041850.54
      2804838.48     10042039.01      2804899.82     10042170.36
      2805105.06     10042141.63      2804715.21     10042445.14

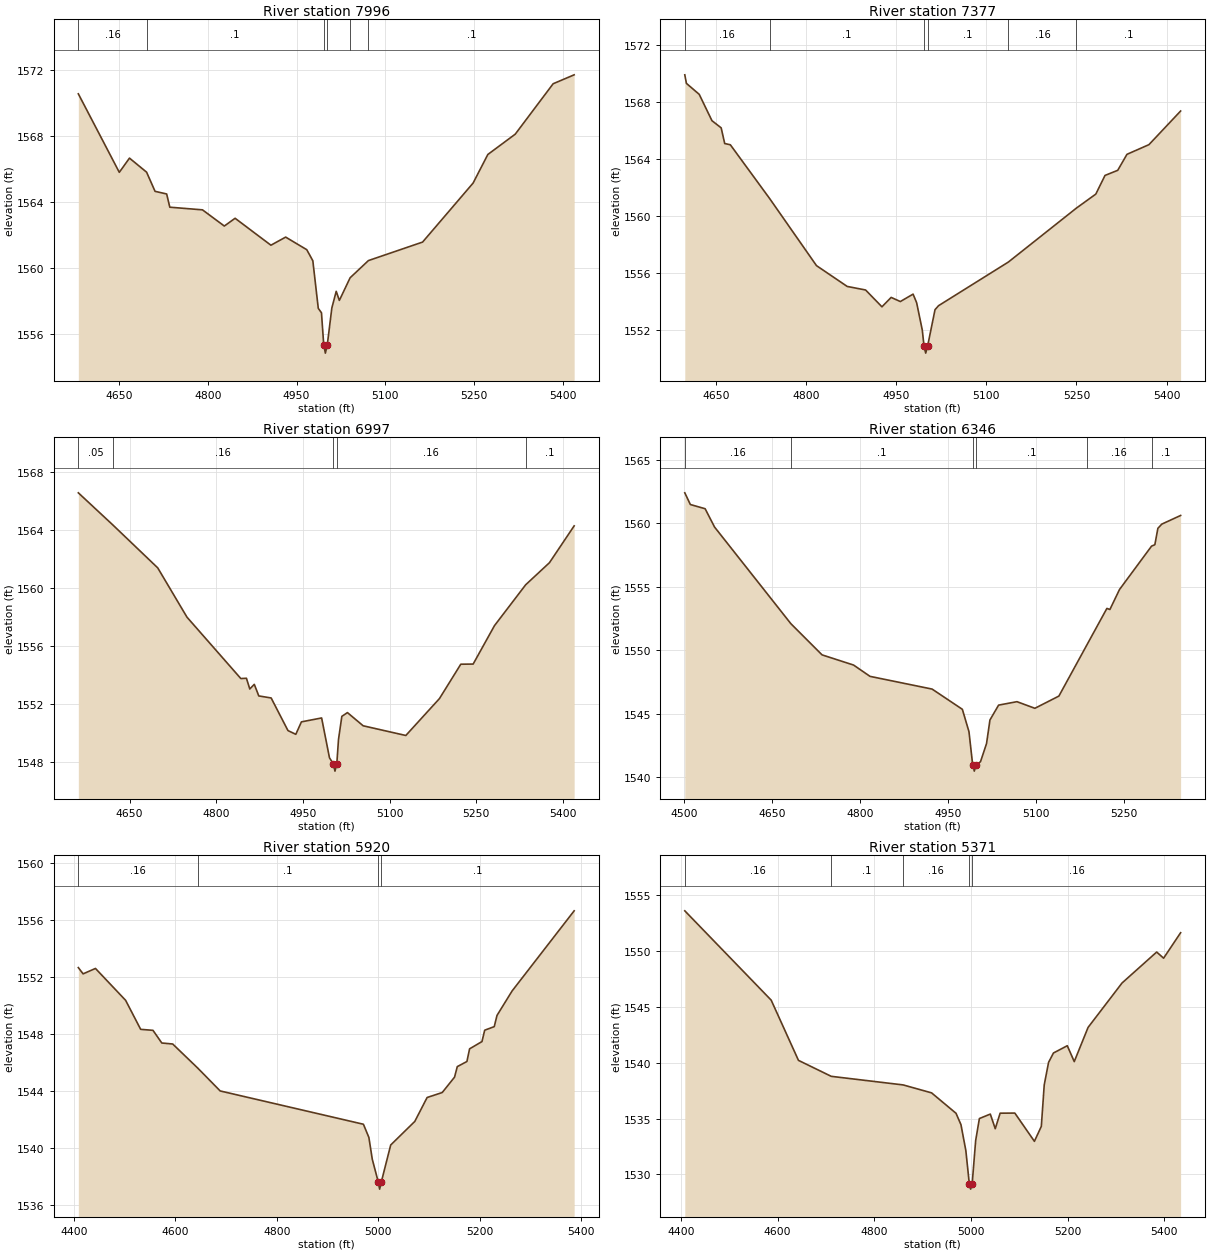
Type RM Length L Ch R = 1,7996,619,619,619
BEGIN DESCRIPTION:
UNT048 IN SNOGR 15.0
END DESCRIPTION:
XS GIS Cut Line= 2
      2807187.63     10037974.81      2807971.63     10038269.36
#Sta/Elev= 30
  4581.4 1570.55  4650.6 1565.80  4667.8 1566.66  4696.7 1565.81  4711.0 1564.65
  4730.6 1564.49  4735.9 1563.69  4791.1 1563.53  4828.0 1562.55  4846.2 1563.02
  4906.7 1561.39  4931.6 1561.88  4967.2 1561.12  4977.5 1560.45  4986.7 1557.57
  4992.1 1557.30  4995.9 1555.36  4998.7 1554.86  5001.9 1555.36  5009.6 1557.59
  5017.0 1558.60  5022.3 1558.05  5040.5 1559.42  5071.4 1560.46  5162.9 1561.58
  5248.2 1565.15  5273.1 1566.88  5319.4 1568.11  5383.4 1571.16  5418.9 1571.70
#Mann=6,-1,0
  4581.4    0.16       0  4696.7     0.1       0  4995.9    0.07       0
  5001.9     0.1       0  5040.5    0.16       0  5071.4     0.1       0
Bank Sta=4995.9,5001.9
Exp/Cntr=0.3,0.1

Type RM Length L Ch R = 1,7377,380,380,380
BEGIN DESCRIPTION:
UNT048 IN SNOGR 14.0
END DESCRIPTION:
XS GIS Cut Line= 2
      2806922.89     10038196.18      2807621.67     10038634.55
#Sta/Elev= 30
  4598.4 1569.93  4601.1 1569.33  4622.4 1568.56  4643.6 1566.71  4658.9 1566.21
  4664.8 1565.11  4674.2 1565.02  4739.7 1561.24  4817.5 1556.54  4868.6 1555.08
  4899.2 1554.83  4926.4 1553.65  4941.7 1554.31  4957.0 1554.02  4978.2 1554.54
  4984.1 1553.94  4993.5 1552.02  4996.4 1550.90  4999.2 1550.40  5002.4 1550.90
  5014.7 1553.45  5020.6 1553.73  5136.7 1556.79  5250.0 1560.58  5282.2 1561.56
  5297.5 1562.87  5318.7 1563.23  5334.0 1564.35  5370.6 1565.03  5423.3 1567.39
#Mann=6,-1,0
  4598.4    0.16       0  4739.7     0.1       0  4996.4    0.07       0
  5002.4     0.1       0  5136.7    0.16       0  5250.0     0.1       0
Bank Sta=4996.4,5002.4
Exp/Cntr=0.3,0.1

Type RM Length L Ch R = 1,6997,651,651,651
BEGIN DESCRIPTION:
UNT048 IN SNOGR 13.0
END DESCRIPTION:
XS GIS Cut Line= 2
      2806697.18     10038486.97      2807433.42     10038928.72
#Sta/Elev= 30
  4561.1 1566.55  4620.4 1564.35  4698.6 1561.37  4749.2 1557.97  4842.5 1553.73
  4852.2 1553.75  4858.0 1553.01  4865.8 1553.33  4873.6 1552.53  4895.0 1552.39
  4924.1 1550.14  4937.7 1549.88  4947.4 1550.74  4982.4 1551.01  4996.0 1548.26
  5002.7 1547.84  5005.5 1547.34  5008.7 1547.84  5011.6 1549.52  5017.4 1551.12
  5027.1 1551.38  5054.3 1550.47  5128.2 1549.80  5186.5 1552.35  5223.4 1554.72
  5244.8 1554.73  5281.7 1557.38  5335.7 1560.20  5377.0 1561.73  5419.7 1564.27
#Mann=5,-1,0
  4561.1    0.05       0  4620.4    0.16       0  5002.7    0.07       0
  5008.7    0.16       0  5335.7     0.1       0
Bank Sta=5002.7,5008.7
Exp/Cntr=0.3,0.1

Type RM Length L Ch R = 1,6346,426,426,426
BEGIN DESCRIPTION:
UNT048 IN SNOGR 12.0
END DESCRIPTION:
XS GIS Cut Line= 2
      2806645.06     10038634.50      2806853.41     10039454.86
#Sta/Elev= 30
  4500.6 1562.38  4510.1 1561.46  4535.3 1561.13  4551.4 1559.69  4681.7 1552.09
  4734.9 1549.64  4788.7 1548.84  4816.8 1547.95  4922.8 1546.95  4974.4 1545.36
  4985.7 1543.60  4992.0 1541.00  4994.8 1540.50  4998.0 1541.00  5005.4 1541.24
  5015.7 1542.67  5021.5 1544.52  5036.3 1545.69  5067.6 1545.96  5098.2 1545.44
  5139.2 1546.40  5187.2 1550.44  5221.1 1553.29  5226.3 1553.21  5242.7 1554.78
  5297.4 1558.19  5303.0 1558.30  5308.2 1559.59  5314.9 1559.92  5347.0 1560.60
#Mann=6,-1,0
  4500.6    0.16       0  4681.7     0.1       0  4992.0    0.07       0
  4998.0     0.1       0  5187.2    0.16       0  5297.4     0.1       0
Bank Sta=4992,4998
Exp/Cntr=0.3,0.1

Type RM Length L Ch R = 1,5920,549,549,549
BEGIN DESCRIPTION:
UNT048 IN SNOGR 11.0
END DESCRIPTION:
XS GIS Cut Line= 2
      2806219.74     10038660.61      2806579.33     10039570.42
#Sta/Elev= 30
  4408.3 1552.68  4417.7 1552.24  4442.1 1552.62  4501.6 1550.38  4531.3 1548.34
  4555.6 1548.27  4573.0 1547.38  4594.5 1547.31  4644.4 1545.60  4688.2 1544.01
  4970.8 1541.67  4981.6 1540.74  4988.3 1539.21  5000.1 1537.61  5002.8 1537.11
  5006.1 1537.61  5024.6 1540.21  5072.2 1541.87  5096.5 1543.55  5126.3 1543.90
  5150.6 1544.98  5156.0 1545.72  5175.0 1546.08  5180.3 1546.97  5204.7 1547.48
  5210.1 1548.28  5228.9 1548.53  5234.4 1549.32  5264.2 1551.04  5386.6 1556.67
#Mann=4,-1,0
  4408.3    0.16       0  4644.4     0.1       0  5000.1    0.07       0
  5006.1     0.1       0
Bank Sta=5000.1,5006.1
Exp/Cntr=0.3,0.1

Type RM Length L Ch R = 1,5371,400,400,400
BEGIN DESCRIPTION:
UNT048 IN SNOGR 10.0
END DESCRIPTION:
XS GIS Cut Line= 3
      2805855.14     10038729.99      2805976.67     10039476.54
      2806183.42     10039648.83
#Sta/Elev= 30
  4408.2 1553.60  4586.9 1545.60  4643.3 1540.21  4711.1 1538.78  4859.9 1538.01
  4918.6 1537.30  4969.2 1535.47  4979.4 1534.45  4989.5 1532.13  4996.6 1529.18
  4999.4 1528.68  5002.6 1529.18  5009.8 1533.03  5017.5 1535.00  5040.1 1535.40
  5050.3 1534.09  5060.4 1535.48  5090.8 1535.49  5131.3 1532.96  5145.6 1534.30
  5151.6 1538.01  5160.6 1540.03  5170.7 1540.87  5199.3 1541.52  5213.7 1540.10
  5242.3 1543.16  5312.6 1547.14  5384.2 1549.91  5398.5 1549.36  5433.7 1551.64
#Mann=5,-1,0
  4408.2    0.16       0  4711.1     0.1       0  4859.9    0.16       0
  4996.6    0.07       0  5002.6    0.16       0
Bank Sta=4996.6,5002.6
Exp/Cntr=0.3,0.1

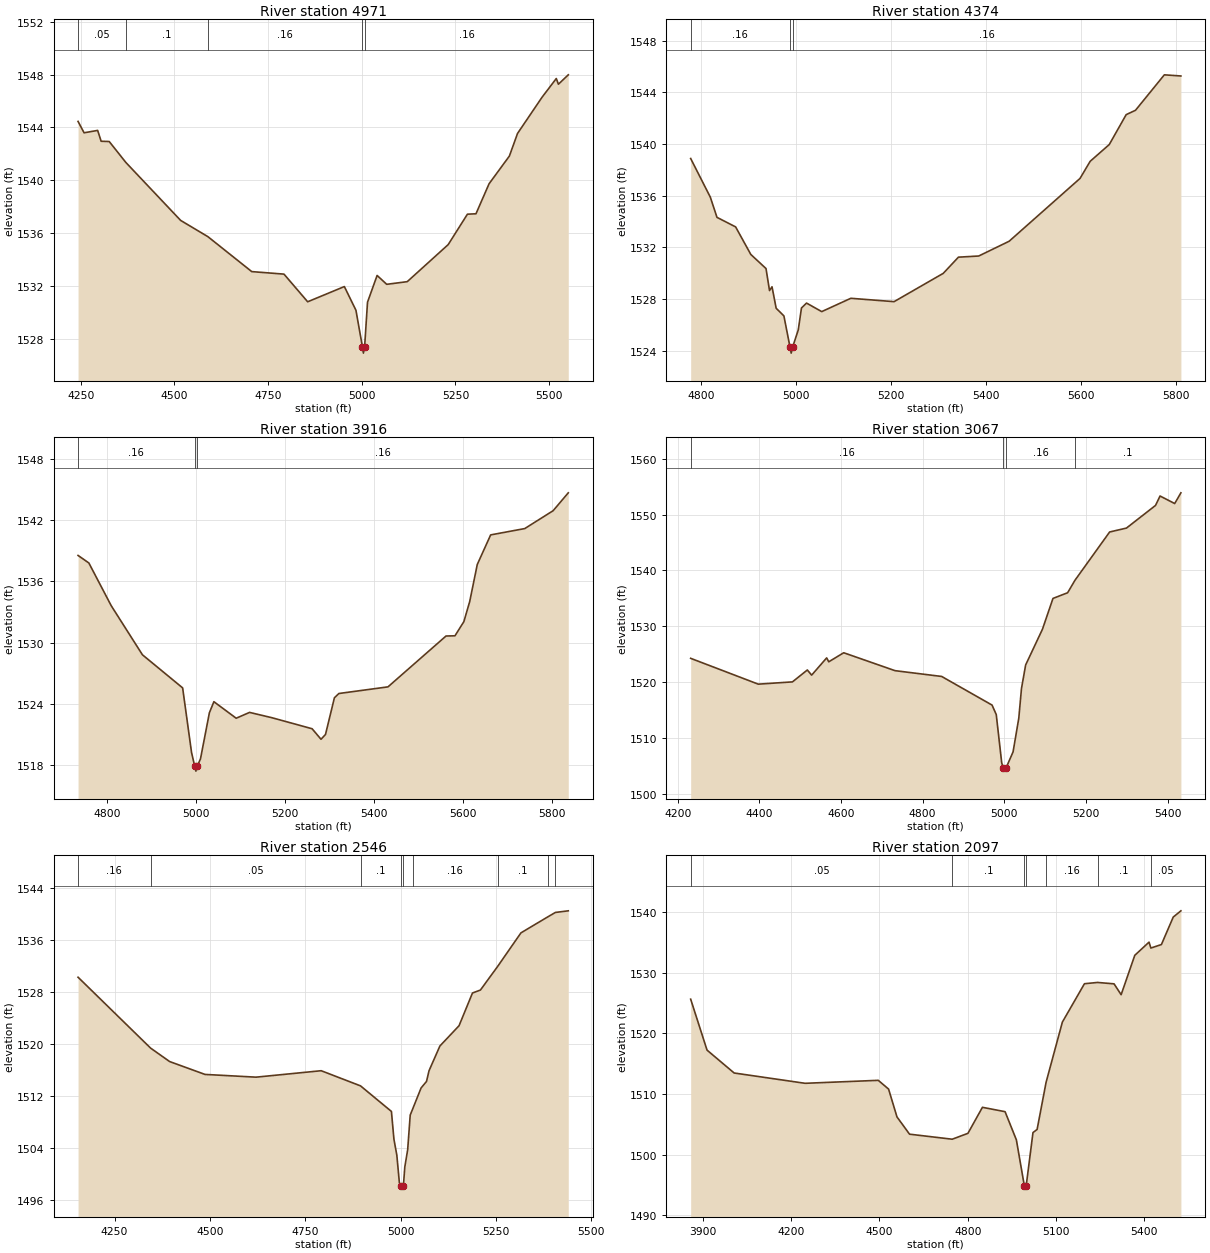
Type RM Length L Ch R = 1,4971,597,597,597
BEGIN DESCRIPTION:
UNT048 IN SNOGR 9.0
END DESCRIPTION:
XS GIS Cut Line= 3
      2805347.34     10038725.71      2805642.47     10039559.01
      2806014.61     10039762.39
#Sta/Elev= 30
  4243.0 1544.46  4259.1 1543.60  4295.3 1543.78  4304.6 1542.96  4326.2 1542.94
  4370.5 1541.36  4516.7 1536.98  4589.5 1535.75  4706.5 1533.11  4792.5 1532.92
  4855.7 1530.83  4953.6 1531.98  4984.5 1530.19  5001.7 1527.45  5004.5 1526.95
  5007.7 1527.45  5015.4 1530.80  5041.0 1532.82  5066.6 1532.15  5121.4 1532.35
  5230.7 1535.15  5282.0 1537.45  5304.8 1537.48  5339.8 1539.75  5393.9 1541.84
  5415.7 1543.55  5481.2 1546.29  5519.1 1547.70  5524.8 1547.27  5551.1 1547.98
#Mann=5,-1,0
  4243.0    0.05       0  4370.5     0.1       0  4589.5    0.16       0
  5001.7    0.07       0  5007.7    0.16       0
Bank Sta=5001.7,5007.7
Exp/Cntr=0.3,0.1

Type RM Length L Ch R = 1,4374,458,458,458
BEGIN DESCRIPTION:
UNT048 IN SNOGR 8.0
END DESCRIPTION:
XS GIS Cut Line= 2
      2804969.70     10039420.11      2805937.63     10039780.37
#Sta/Elev= 30
  4777.6 1538.88  4819.0 1535.89  4833.0 1534.33  4872.3 1533.59  4904.3 1531.46
  4936.3 1530.37  4943.7 1528.67  4949.0 1528.96  4957.7 1527.30  4974.0 1526.71
  4986.7 1524.33  4989.4 1523.83  4992.7 1524.33  5004.3 1525.63  5011.0 1527.32
  5021.7 1527.70  5053.7 1527.04  5115.0 1528.07  5206.1 1527.81  5309.8 1530.00
  5341.7 1531.25  5384.5 1531.34  5448.5 1532.48  5597.9 1537.34  5619.2 1538.66
  5659.5 1539.96  5695.1 1542.27  5714.8 1542.61  5775.5 1545.35  5810.4 1545.26
#Mann=3,-1,0
  4777.6    0.16       0  4986.7    0.07       0  4992.7    0.16       0
Bank Sta=4986.7,4992.7
Exp/Cntr=0.3,0.1

Type RM Length L Ch R = 1,3916,849,849,849
BEGIN DESCRIPTION:
UNT048 IN SNOGR 7.0
END DESCRIPTION:
XS GIS Cut Line= 2
      2804874.24     10039927.93      2805972.32     10039841.13
#Sta/Elev= 30
  4735.6 1538.54  4759.9 1537.80  4810.1 1533.62  4880.3 1528.81  4970.6 1525.57
  4990.6 1519.25  4997.6 1517.92  5000.4 1517.42  5003.6 1517.92  5010.7 1518.62
  5030.7 1523.13  5040.8 1524.22  5090.9 1522.60  5121.0 1523.17  5171.2 1522.65
  5261.5 1521.57  5281.5 1520.54  5291.6 1521.01  5311.6 1524.60  5321.6 1525.02
  5432.0 1525.67  5562.4 1530.65  5582.5 1530.67  5602.5 1532.06  5615.6 1534.02
  5632.6 1537.65  5662.7 1540.55  5739.3 1541.17  5803.1 1542.92  5837.1 1544.67
#Mann=3,-1,0
  4735.6    0.16       0  4997.6    0.07       0  5003.6    0.16       0
Bank Sta=4997.6,5003.6
Exp/Cntr=0.3,0.1

Type RM Length L Ch R = 1,3067,521,521,521
BEGIN DESCRIPTION:
UNT048 IN SNOGR 6.0
END DESCRIPTION:
XS GIS Cut Line= 2
      2804930.68     10040110.23      2806098.18     10040392.34
#Sta/Elev= 30
  4231.6 1524.25  4397.3 1519.62  4481.0 1520.03  4517.4 1522.16  4528.0 1521.24
  4564.8 1524.33  4569.9 1523.63  4606.6 1525.25  4732.2 1522.04  4846.6 1521.00
  4970.0 1515.87  4980.3 1514.17  4993.7 1505.51  4997.9 1504.53  5000.7 1504.03
  5003.9 1504.53  5021.5 1507.48  5035.5 1513.51  5042.1 1518.84  5052.3 1523.06
  5093.5 1529.47  5119.3 1534.99  5155.2 1536.01  5173.2 1538.25  5258.1 1546.90
  5299.3 1547.60  5370.5 1551.66  5381.6 1553.35  5417.5 1552.00  5432.7 1553.92
#Mann=4,-1,0
  4231.6    0.16       0  4997.9    0.07       0  5003.9    0.16       0
  5173.2     0.1       0
Bank Sta=4997.9,5003.9
Exp/Cntr=0.3,0.1

Type RM Length L Ch R = 1,2546,449,449,449
BEGIN DESCRIPTION:
UNT048 IN SNOGR 5.0
END DESCRIPTION:
XS GIS Cut Line= 2
      2804678.92     10040053.79      2805642.43     10040904.46
#Sta/Elev= 30
  4154.2 1530.33  4344.4 1519.43  4394.3 1517.36  4487.1 1515.38  4621.0 1514.96
  4791.7 1515.95  4894.8 1513.62  4975.8 1509.69  4982.4 1505.41  4990.0 1502.96
  4996.7 1498.71  5001.2 1498.24  5004.0 1497.74  5007.2 1498.24  5010.9 1501.14
  5018.4 1503.79  5025.1 1509.13  5031.3 1510.03  5053.6 1513.30  5067.8 1514.30
  5074.5 1515.96  5102.9 1519.75  5153.1 1522.87  5188.3 1527.90  5209.2 1528.36
  5254.2 1531.98  5315.4 1537.15  5385.5 1539.60  5405.7 1540.29  5439.5 1540.54
#Mann=9,-1,0
  4154.2    0.16       0  4344.4    0.05       0  4894.8     0.1       0
  5001.2    0.07       0  5007.2     0.1       0  5031.3    0.16       0
  5254.2     0.1       0  5385.5    0.16       0  5405.7     0.1       0
Bank Sta=5001.2,5007.2
Exp/Cntr=0.3,0.1

Type RM Length L Ch R = 1,2097,448,448,448
BEGIN DESCRIPTION:
UNT048 IN SNOGR 4.0
END DESCRIPTION:
XS GIS Cut Line= 3
      2804357.76     10040305.55      2805156.36     10041008.66
      2805754.38     10041069.33
#Sta/Elev= 30
  3859.1 1525.65  3914.7 1517.25  4006.7 1513.48  4247.7 1511.78  4496.2 1512.27
  4531.3 1510.83  4559.8 1506.24  4602.5 1503.39  4747.5 1502.56  4800.8 1503.53
  4850.1 1507.82  4927.0 1507.10  4965.4 1502.45  4992.6 1494.83  4995.3 1494.33
  4998.6 1494.83  5021.8 1503.66  5035.8 1504.17  5066.3 1511.95  5121.6 1521.87
  5196.6 1528.20  5241.1 1528.41  5297.1 1528.18  5321.2 1526.39  5367.5 1532.88
  5416.0 1535.06  5422.2 1534.08  5458.0 1534.66  5498.2 1539.19  5524.2 1540.22
#Mann=7,-1,0
  3859.1    0.05       0  4747.5     0.1       0  4992.6    0.07       0
  4998.6     0.1       0  5066.3    0.16       0  5241.1     0.1       0
  5422.2    0.05       0
Bank Sta=4992.6,4998.6
Exp/Cntr=0.3,0.1

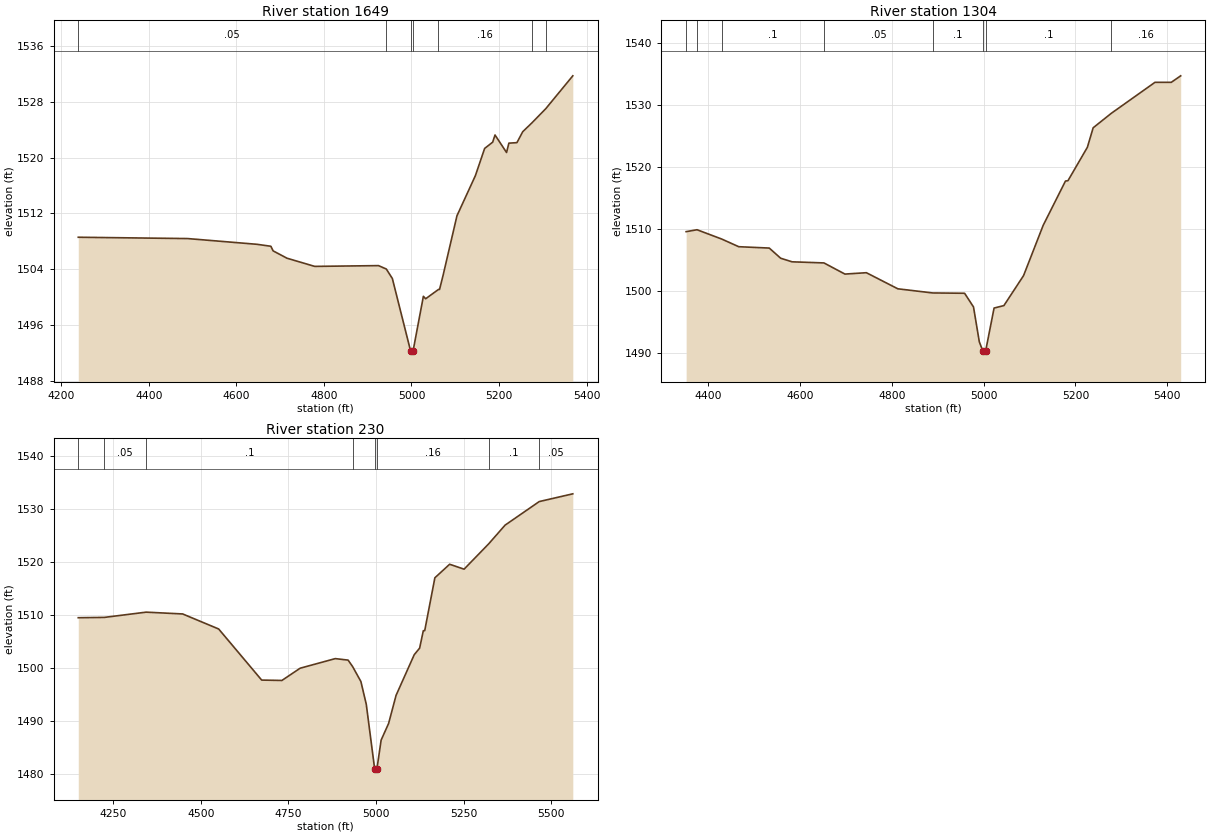
Type RM Length L Ch R = 1,1649,345,345,345
BEGIN DESCRIPTION:
UNT048 IN SNOGR 3.0
END DESCRIPTION:
XS GIS Cut Line= 2
      2804457.56     10041199.63      2805529.63     10041555.54
#Sta/Elev= 30
  4238.9 1508.60  4488.7 1508.41  4647.1 1507.59  4678.8 1507.31  4684.0 1506.65
  4715.7 1505.60  4779.0 1504.43  4924.7 1504.54  4942.6 1504.05  4956.3 1502.70
  4997.8 1492.38  5000.5 1491.88  5003.8 1492.38  5027.2 1500.15  5032.4 1499.80
  5061.7 1501.13  5064.1 1501.13  5072.2 1503.15  5103.9 1511.67  5146.0 1517.41
  5167.1 1521.30  5185.5 1522.20  5190.8 1523.23  5217.2 1520.72  5222.5 1522.06
  5240.8 1522.13  5254.2 1523.70  5274.8 1524.94  5306.6 1526.98  5368.5 1531.69
#Mann=7,-1,0
  4238.9    0.05       0  4942.6     0.1       0  4997.8    0.07       0
  5003.8     0.1       0  5061.7    0.16       0  5274.8    0.05       0
  5306.6     0.1       0
Bank Sta=4997.8,5003.8
Exp/Cntr=0.3,0.1

Type RM Length L Ch R = 1,1304,1074,1074,1074
BEGIN DESCRIPTION:
UNT048 IN SNOGR 2.0
END DESCRIPTION:
XS GIS Cut Line= 2
      2804471.45     10041515.60      2805478.45     10041897.56
#Sta/Elev= 30
  4352.3 1509.57  4376.0 1509.88  4430.0 1508.37  4466.8 1507.14  4533.3 1506.92
  4558.1 1505.28  4582.9 1504.70  4652.4 1504.52  4698.1 1502.72  4744.8 1502.94
  4813.3 1500.34  4889.3 1499.67  4958.7 1499.62  4978.1 1497.41  4990.8 1491.76
  4998.5 1490.29  5001.3 1489.79  5004.5 1490.29  5022.9 1497.23  5044.3 1497.63
  5087.1 1502.47  5129.9 1510.60  5178.4 1517.75  5183.8 1517.80  5226.1 1523.20
  5238.7 1526.35  5278.3 1528.69  5373.3 1533.69  5408.8 1533.69  5429.3 1534.74
#Mann=8,-1,0
  4352.3     0.1       0  4376.0    0.05       0  4430.0     0.1       0
  4652.4    0.05       0  4889.3     0.1       0  4998.5    0.07       0
  5004.5     0.1       0  5278.3    0.16       0
Bank Sta=4998.5,5004.5
Exp/Cntr=0.3,0.1

Type RM Length L Ch R = 1,230,0,0,0
BEGIN DESCRIPTION:
UNT048 IN SNOGR 1.0
END DESCRIPTION:
XS GIS Cut Line= 3
      2804457.55     10041603.25      2804978.40     10042440.95
      2805382.05     10042575.50
#Sta/Elev= 30
  4150.0 1509.47  4224.7 1509.53  4343.7 1510.52  4448.1 1510.18  4550.9 1507.34
  4673.6 1497.70  4731.4 1497.63  4783.4 1499.94  4883.7 1501.75  4920.3 1501.47
  4933.1 1500.27  4956.9 1497.43  4972.3 1493.12  4996.4 1480.83  4999.1 1480.33
  5002.4 1480.83  5014.7 1486.38  5036.0 1489.51  5057.3 1494.81  5109.2 1502.49
  5124.6 1503.73  5135.1 1507.02  5139.1 1507.02  5168.1 1517.00  5210.3 1519.56
  5251.5 1518.63  5321.6 1523.40  5368.4 1526.93  5466.1 1531.39  5561.9 1532.85
#Mann=8,-1,0
  4150.0     0.1       0  4224.7    0.05       0  4343.7     0.1       0
  4933.1    0.16       0  4996.4    0.07       0  5002.4    0.16       0
  5321.6     0.1       0  5466.1    0.05       0
Bank Sta=4996.4,5002.4
Exp/Cntr=0.3,0.1

Chan Stop Cuts=-1