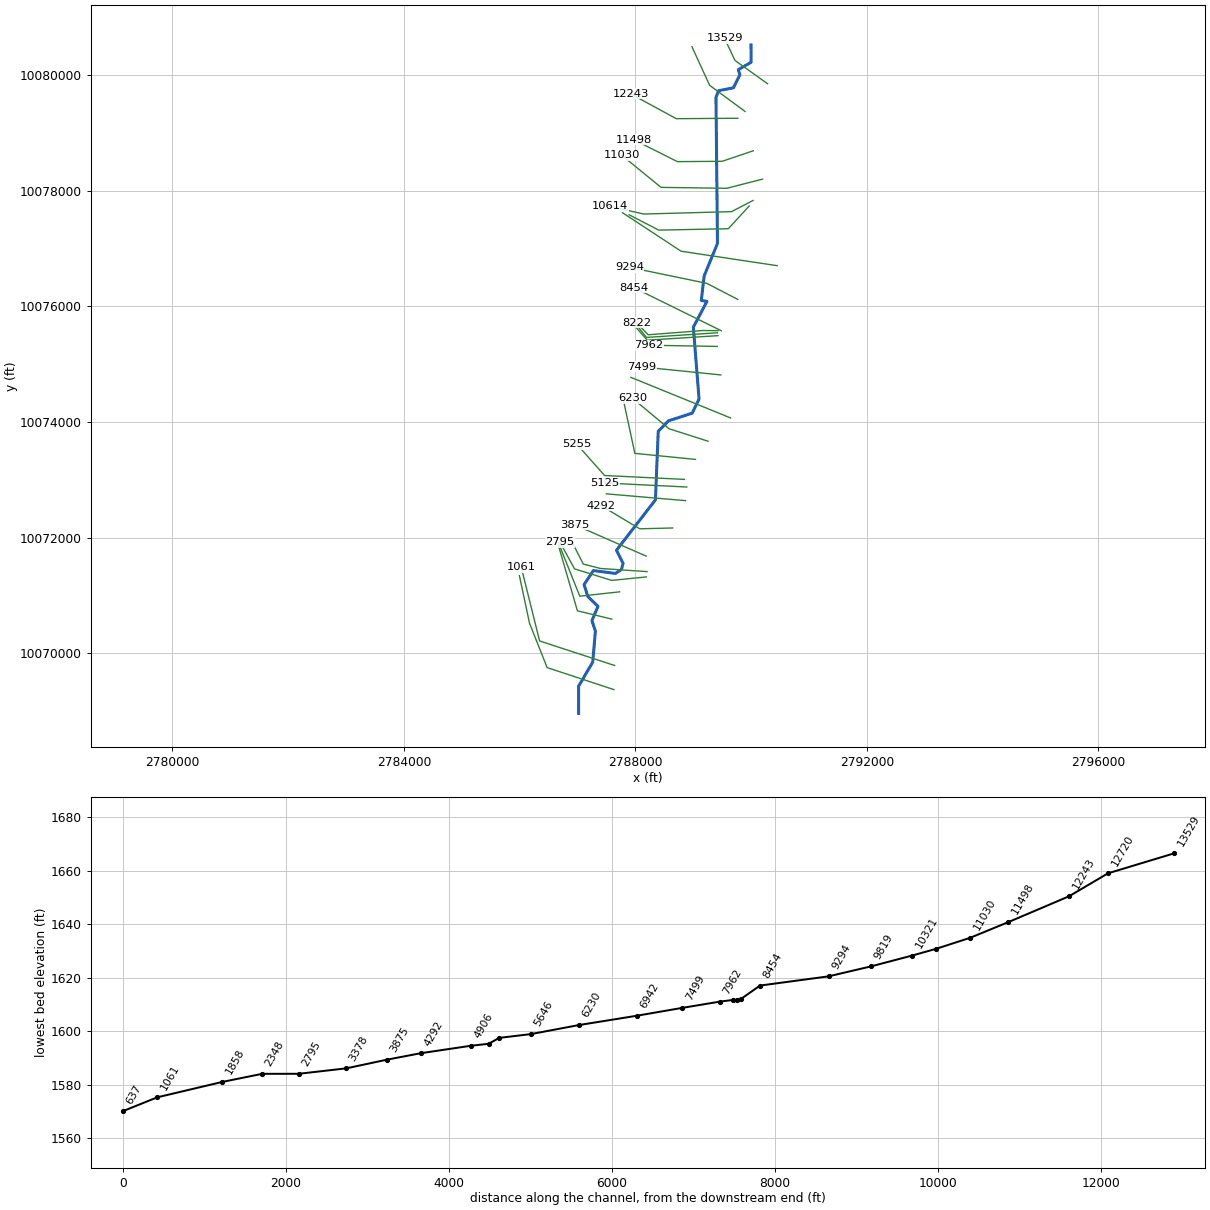
--- UNT049 IN NNOGR.prj (project) ---

Proj Title=UNT049 IN NNOGR Base Level Engineering
Current Plan=p01
Default Exp/Contr=0.3,0.1
English Units
Geom File=g01
Flow File=f01
Plan File=p01
Y Axis Title=Elevation
X Axis Title(PF)=Main Channel Distance
X Axis Title(XS)=Station
BEGIN DESCRIPTION:
UNT049 IN NNOGR
END DESCRIPTION:
DSS Export Rating Curves= 0
DSS Export Rating Curve Sorted= 0
DSS Export Volume Flow Curves= 0
DXF OffsetX= 0
DXF OffsetY= 0
DXF ScaleX= 1
DXF ScaleY= 10

--- UNT049 IN NNOGR.p01 (plan) ---

Plan Title=Multiple Run
Short Identifier=Multiple
Geom File=g01
Flow File=f01
Subcritical Flow
K Sum by GR= 0
Std Step Tol= 0.01
Critical Tol= 0.01
Num of Std Step Trials= 20
Max Error Tol= 0.3
Flow Tol Ratio= 0.001
Split Flow NTrial= 30
Split Flow Tol= 0.02
Split Flow Ratio= 0.02
Log Output Level= 0
Friction Slope Method= 1
Unsteady Friction Slope Method= 2
Unsteady Bridges Friction Slope Method= 1
Parabolic Critical Depth
Global Vel Dist=  1 , 1 , 1
Global Log Level= 0
CheckData=True
Encroach Param= -1, 0, 0, 0
BEGIN DESCRIPTION:
Multiple Run
END DESCRIPTION:

--- UNT049 IN NNOGR.f01 (steady flow) ---

Flow Title=Multiple
Number of Profiles=7
Profile Names=10-year,25-year,50-year,1pct_min,100-year,1pct_plu,500-year
River Rch & RM= UNT049 IN NNOGR,Reach-1,13529
    1049    1552    1997    1882    2545    3441    4149
River Rch & RM= UNT049 IN NNOGR,Reach-1,8168
    1388    2067    2672    2523    3412    4615    5593
Boundary for River Rch & Prof#=UNT049 IN NNOGR,Reach-1,1
Up Type=0
Dn Type=3
Dn Slope=0.005
Boundary for River Rch & Prof#=UNT049 IN NNOGR,Reach-1,2
Up Type=0
Dn Type=3
Dn Slope=0.005
Boundary for River Rch & Prof#=UNT049 IN NNOGR,Reach-1,3
Up Type=0
Dn Type=3
Dn Slope=0.005
Boundary for River Rch & Prof#=UNT049 IN NNOGR,Reach-1,4
Up Type=0
Dn Type=3
Dn Slope=0.005
Boundary for River Rch & Prof#=UNT049 IN NNOGR,Reach-1,5
Up Type=0
Dn Type=3
Dn Slope=0.005
Boundary for River Rch & Prof#=UNT049 IN NNOGR,Reach-1,6
Up Type=0
Dn Type=3
Dn Slope=0.005
Boundary for River Rch & Prof#=UNT049 IN NNOGR,Reach-1,7
Up Type=0
Dn Type=3
Dn Slope=0.005

--- UNT049 IN NNOGR.g01 (geometry) ---

Geom Title=Existing Conditions
Program Version=4.10

River Reach=UNT049 IN NNOGR ,Reach-1
Reach XY= 30
      2789997.06     10080520.36      2789999.38      10080221.7
      2789777.98     10080092.84      2789805.29     10080004.96
      2789692.97     10079779.44      2789435.74     10079728.65
      2789391.83     10079612.71      2789417.84     10077088.84
      2789187.73     10076526.63      2789137.87     10076102.15
      2789235.56     10076086.18       2789001.1       10075641.
      2789099.54     10074398.29       2788981.9     10074154.63
      2788569.82     10074020.58      2788394.45     10073840.59
      2788345.69     10072654.82      2787673.26     10071784.72
      2787786.61     10071557.74      2787758.29      10071449.1
       2787653.5     10071383.34      2787272.74     10071432.29
      2787112.89     10071190.77       2787178.2     10070983.32
      2787353.24     10070813.95      2787248.89     10070569.09
      2787308.59     10070385.65      2787262.68     10069849.97
      2787018.47     10069433.73      2787018.47     10068963.73

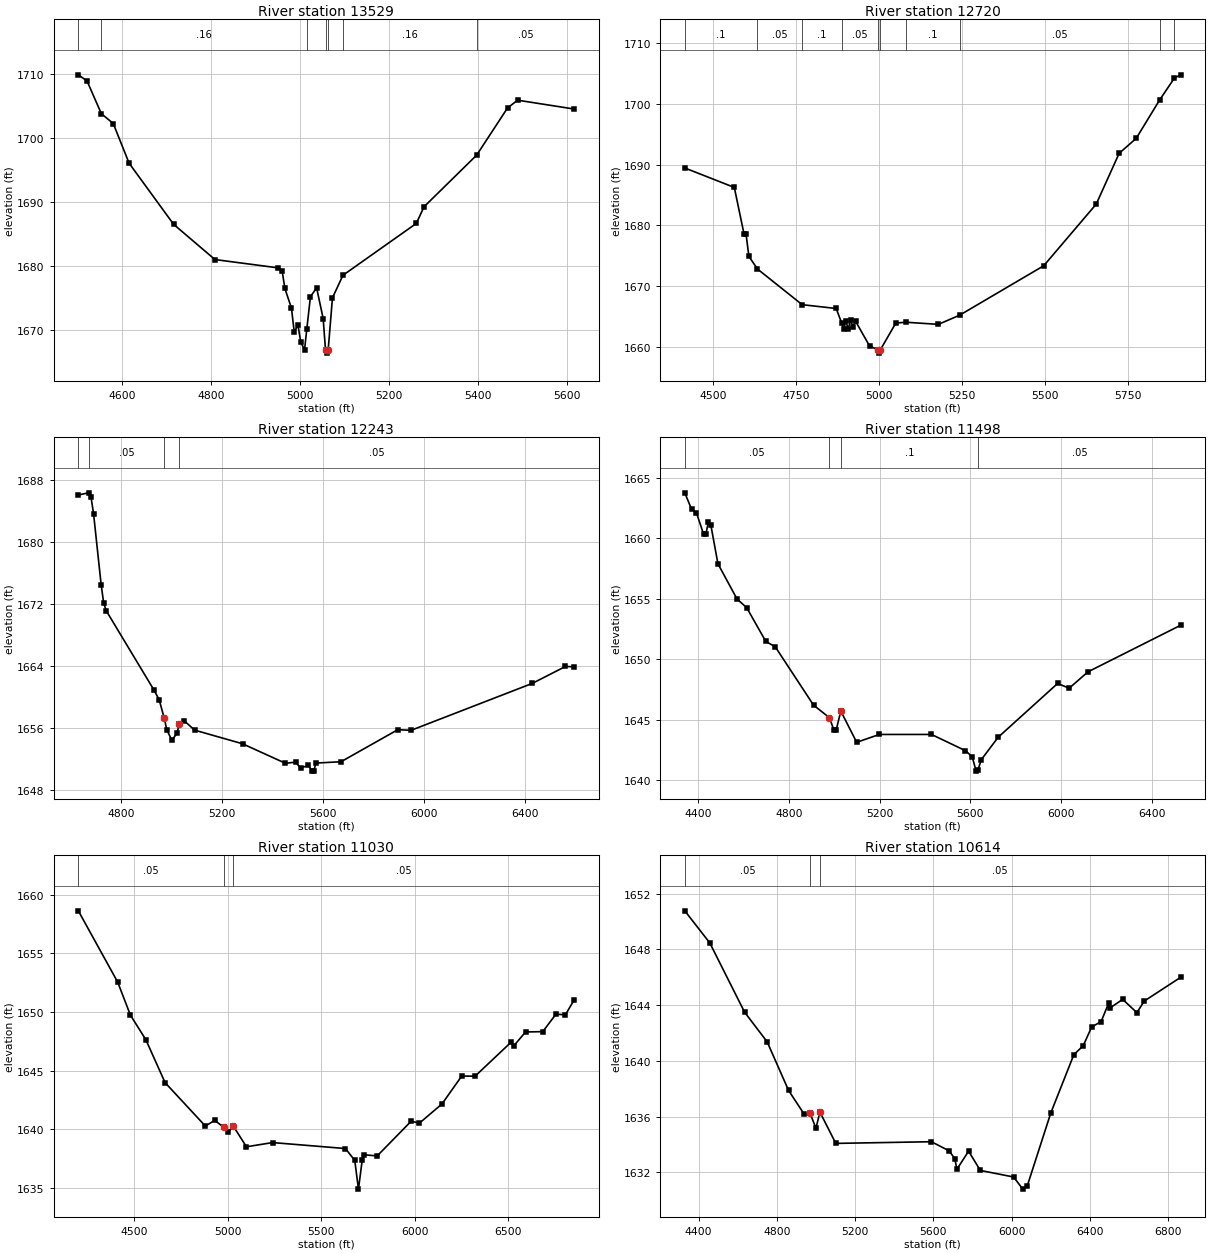
Type RM Length L Ch R = 1 ,13529   ,809,809,809
BEGIN DESCRIPTION:
UNT049 IN NNOGR 23.0
END DESCRIPTION:
XS GIS Cut Line= 3
      2790282.57     10079849.65      2789720.11      10080252.4
      2789539.53     10080634.38
#Sta/Elev= 30
  4502.2  1709.8  4521.8 1708.84  4553.9 1703.75  4580.7 1702.21  4616.3 1696.03
  4716.3 1686.51  4809.2 1681.02  4951.7 1679.72  4960.3 1679.22  4966.4 1676.51
  4981.2 1673.45  4987.3 1669.77  4995.9 1670.78  5002.1 1668.16  5010.6 1666.96
  5015.7 1670.22  5023.8 1675.23  5037.7 1676.62  5052.4 1671.83  5057.7 1666.94
  5060.5 1666.44  5063.7 1666.94  5073.3 1675.05  5096.9 1678.57  5261.8 1686.65
  5279.1 1689.24  5397.4 1697.29  5466.7 1704.63  5489.4 1705.85  5616.5 1704.47
#Mann= 7 ,-1 , 0
  4502.2      .1       0  4553.9     .16       0  5015.7      .1       0
  5057.7     .07       0  5063.7      .1       0  5096.9     .16       0
  5397.4     .05       0
Bank Sta=5057.7,5063.7
XS Rating Curve= 0 ,0
Exp/Cntr=0.3,0.1

Type RM Length L Ch R = 1 ,12720   ,477,477,477
BEGIN DESCRIPTION:
UNT049 IN NNOGR 21.0
END DESCRIPTION:
XS GIS Cut Line= 3
      2789893.73     10079370.44      2789282.61     10079821.84
      2788977.06     10080488.49
#Sta/Elev= 30
  4414.6 1689.44  4563.7 1686.24  4592.9  1678.6  4599.1 1678.54  4607.6  1674.9
  4633.5 1672.82    4768 1666.96  4870.5 1666.33    4887 1663.94  4893.6 1662.93
  4899.8 1664.35    4906 1662.99  4914.4 1664.37  4920.7 1663.36  4929.1 1664.21
  4970.8 1660.18    4997 1659.49  4999.8 1658.99    5003 1659.49  5050.1 1663.94
  5080.8 1664.07  5178.2 1663.72  5242.3 1665.23  5495.5 1673.36  5653.6  1683.5
  5722.6 1691.85  5774.1 1694.32  5844.2  1700.6  5889.2 1704.25  5907.7 1704.76
#Mann= 10 ,-1 , 0
  4414.6      .1       0  4633.5     .05       0    4768      .1       0
    4887     .05       0    4997    .035       0    5003     .05       0
  5080.8      .1       0  5242.3     .05       0  5844.2      .1       0
  5889.2     .05       0
Bank Sta=4997,5003
XS Rating Curve= 0 ,0
Exp/Cntr=0.3,0.1

Type RM Length L Ch R = 1 ,12243   ,745,745,745
BEGIN DESCRIPTION:
UNT049 IN NNOGR 20.0
END DESCRIPTION:
XS GIS Cut Line= 3
      2789768.76      10079252.4      2788706.22     10079245.45
      2787914.59     10079675.99
#Sta/Elev= 30
  4629.7 1686.03  4670.1 1686.31    4680 1685.75    4690 1683.62    4720 1674.48
    4730 1672.12    4740 1671.11    4930 1660.83    4950  1659.6    4970 1657.23
    4980 1655.75    5000 1654.39    5020 1655.27    5030  1656.5    5050 1656.88
    5090  1655.7    5280 1653.94    5450 1651.42    5490 1651.57    5510 1650.81
    5540 1651.14    5557 1650.41    5563 1650.41    5570 1651.45    5670 1651.62
  5894.6 1655.75  5948.1 1655.68  6427.8 1661.73  6558.9 1663.91  6593.4 1663.87
#Mann= 4 ,-1 , 0
  4629.7      .1       0  4670.1     .05       0    4970    .035       0
    5030     .05       0
#Block Obstruct= 2 , 0
                         5046.21         1654.39
Bank Sta=4970,5030
XS Rating Curve= 0 ,0
Exp/Cntr=0.3,0.1

Type RM Length L Ch R = 1 ,11498   ,468,468,468
BEGIN DESCRIPTION:
UNT049 IN NNOGR 18.0
END DESCRIPTION:
XS GIS Cut Line= 4
      2790036.98     10078690.47      2789497.88     10078508.16
      2788724.44     10078502.95       2787969.2     10078883.18
#Sta/Elev= 30
  4339.6 1663.75  4369.7 1662.38  4390.8 1662.12  4422.5 1660.33    4433 1660.36
  4443.8 1661.36  4454.2 1661.12  4485.8 1657.89  4570.3 1654.97  4612.5 1654.27
  4696.9 1651.48  4739.2 1651.02  4907.8 1646.21  4978.1 1645.17  4998.1 1644.12
  5008.1 1644.19  5028.1 1645.72  5098.1 1643.14  5198.1 1643.79  5428.1 1643.79
  5578.1 1642.45  5608.1 1641.94  5625.1 1640.76  5633.7 1640.88  5648.1 1641.71
  5722.6 1643.56  5984.8    1648  6035.9 1647.61  6118.7 1648.96  6527.7 1652.81
#Mann= 4 ,-1 , 0
  4339.6     .05       0  4978.1    .035       0  5028.1      .1       0
  5633.7     .05       0
#Block Obstruct= 2 , 0
                         5037.48         1644.08
Bank Sta=4978.1,5028.1
XS Rating Curve= 0 ,0
Exp/Cntr=0.3,0.1

Type RM Length L Ch R = 1 ,11030   ,416,416,416
BEGIN DESCRIPTION:
UNT049 IN NNOGR 17.0
END DESCRIPTION:
XS GIS Cut Line= 4
       2790198.4     10078200.87      2789578.61     10078042.02
      2788443.19     10078057.64      2787762.15     10078613.91
#Sta/Elev= 30
  4199.5 1658.63  4410.3 1652.55  4478.2 1649.74  4560.7 1647.65    4664 1643.98
  4879.5 1640.28  4929.5 1640.76  4979.5 1640.16  4999.5 1639.75  5029.5 1640.27
  5099.5 1638.51  5239.5 1638.87  5629.5 1638.36  5679.5 1637.35  5699.3  1634.9
  5719.5 1637.38  5729.5 1637.83  5799.6 1637.73    5982  1640.7  6025.1 1640.52
  6146.4 1642.16  6252.1 1644.54  6323.7 1644.53  6515.4 1647.41  6529.8 1647.09
  6593.7  1648.3  6686.3 1648.33  6756.6 1649.82  6807.3 1649.76  6854.2 1651.04
#Mann= 3 , 0 , 0
  4199.5     .05       0  4979.5    .035       0  5029.5     .05       0
#Block Obstruct= 2 , 0
                         5035.67         1639.63
Bank Sta=4979.5,5029.5
XS Rating Curve= 0 ,0
Exp/Cntr=0.3,0.1

Type RM Length L Ch R = 1 ,10614   ,293,293,293
BEGIN DESCRIPTION:
UNT049 IN NNOGR 16.0
END DESCRIPTION:
XS GIS Cut Line= 4
      2790031.73     10077831.07      2789661.94     10077638.37
      2788143.71      10077596.7      2787559.52     10077729.12
#Sta/Elev= 30
  4329.3 1650.76    4457 1648.46  4634.6  1643.5  4750.5 1641.36  4859.8 1637.88
  4939.8 1636.17  4969.8 1636.24  4999.9 1635.16  5019.9 1636.33  5101.2 1634.08
  5590.1  1634.2  5680.1 1633.55  5710.1 1632.98  5720.1 1632.22  5780.1 1633.52
  5840.2 1632.14  6010.2 1631.67  6057.3  1630.8  6080.3 1631.04  6200.3 1636.26
  6318.1 1640.44  6366.3 1641.09  6409.4 1642.43  6457.7 1642.82  6495.7 1644.12
  6500.8 1643.77  6567.8 1644.41  6640.4 1643.46  6678.4 1644.29  6864.1 1645.99
#Mann= 3 , 0 , 0
  4329.3     .05       0  4969.8    .035       0  5019.9     .05       0
#Block Obstruct= 2 , 0
                          5026.6         1635.14
Bank Sta=4969.8,5019.9
XS Rating Curve= 0 ,0
Exp/Cntr=0.3,0.1

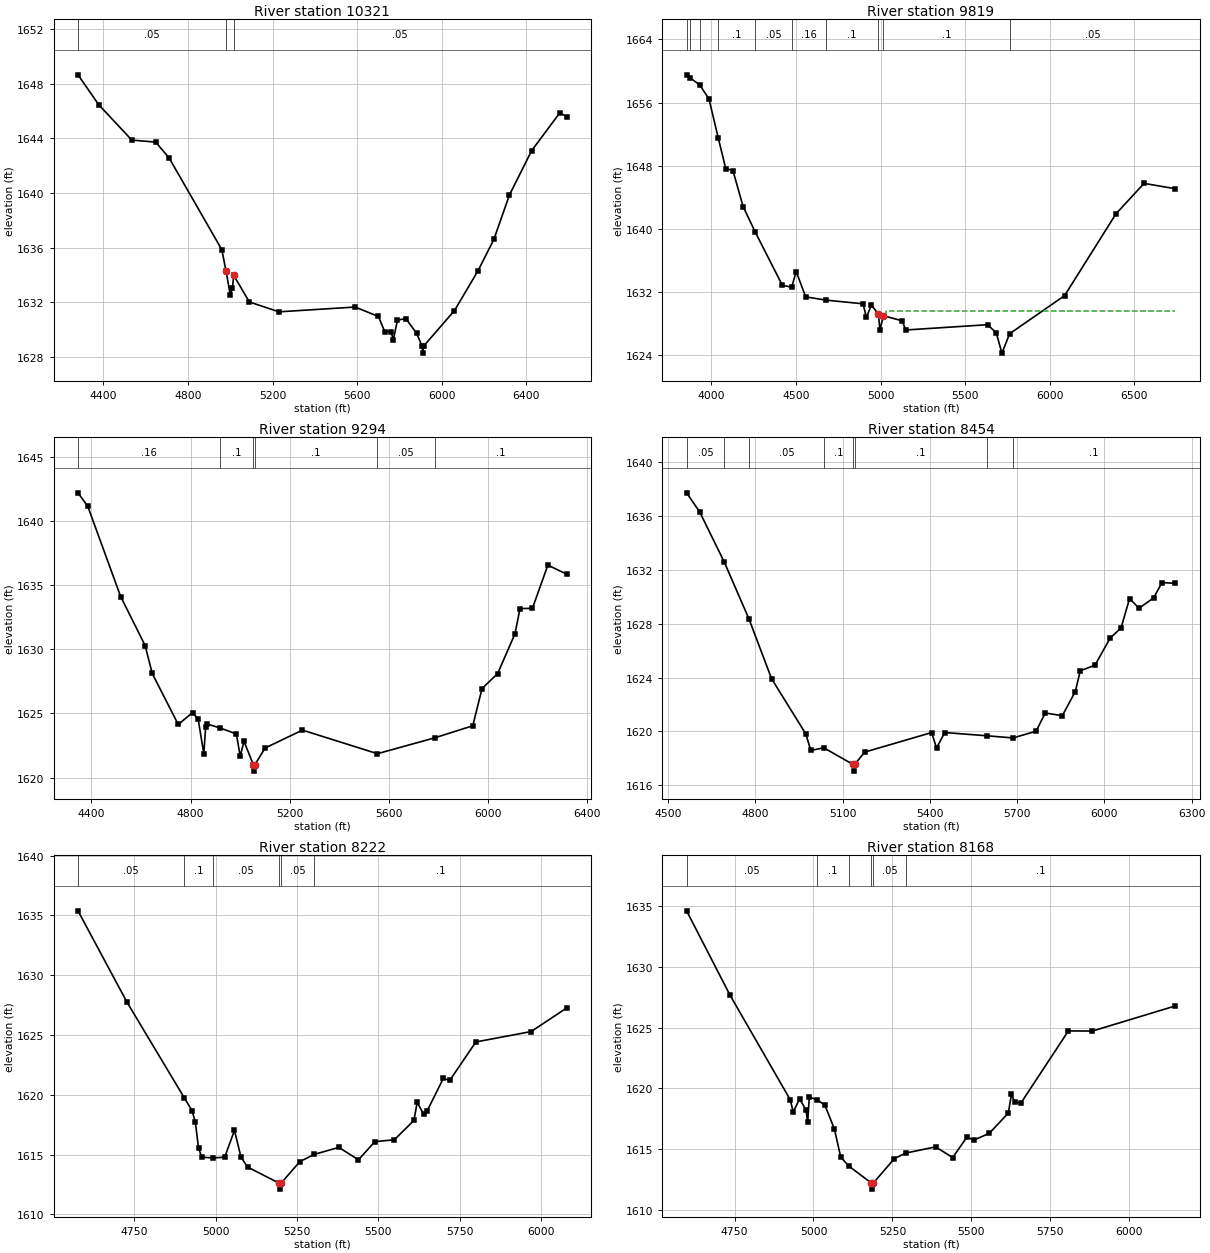
Type RM Length L Ch R = 1 ,10321   ,502,502,502
BEGIN DESCRIPTION:
Mapping XS 17e0480d
END DESCRIPTION:
XS GIS Cut Line= 4
      2789965.79     10077735.62      2789605.52      10077342.8
      2788403.26     10077318.93      2787892.31     10077583.06
#Sta/Elev= 30
  4279.9 1648.64  4378.2 1646.45  4534.2 1643.87  4647.6 1643.72  4711.1 1642.55
    4960 1635.85    4980 1634.27    5000 1632.52    5010 1633.06  5016.3 1633.97
    5090 1632.03  5230.1 1631.31  5590.1 1631.66  5700.1 1630.97  5730.1 1629.86
  5760.2 1629.87  5770.2 1629.24  5790.2 1630.71  5830.2 1630.81  5880.2 1629.74
  5907.2 1628.79  5909.9 1628.29  5913.2 1628.79  6059.4  1631.4  6170.1 1634.29
    6246 1636.61  6319.5 1639.86  6424.6  1643.1  6557.5 1645.86  6590.6 1645.58
#Mann= 3 , 0 , 0
  4279.9     .05       0    4980    .035       0  5016.3     .05       0
#Block Obstruct= 2 , 0
                         5025.96         1632.51
Bank Sta=4980,5016.3
XS Rating Curve= 0 ,0
Exp/Cntr=0.3,0.1

Type RM Length L Ch R = 1 ,9819    ,525,525,525
BEGIN DESCRIPTION:
UNT049 IN NNOGR 15.0
END DESCRIPTION:
XS GIS Cut Line= 3
      2790449.32     10076703.78      2788789.55     10076953.79
      2787776.94     10077619.61
#Sta/Elev= 30
    3853 1659.51  3871.8 1659.15  3930.9 1658.23  3985.3 1656.45    4041 1651.45
  4084.5 1647.63  4126.9 1647.39  4187.6  1642.8  4258.8  1639.6  4419.2 1632.85
  4474.5 1632.62  4501.1 1634.59  4557.2 1631.39  4678.1 1630.97  4896.9 1630.51
  4915.7 1628.78    4946 1630.34  4986.5 1629.23  4996.6 1627.22  5016.8    1629
  5128.1 1628.35  5148.3 1627.19    5633 1627.86  5684.3 1626.82  5717.4 1624.26
  5763.2 1626.72  6087.9 1631.54  6392.2 1641.91  6557.9 1645.76  6743.4 1645.08
#Mann= 10 ,-1 , 0
    3853     .05       0  3871.8      .1       0  3930.9     .05       0
    4041      .1       0  4258.8     .05       0  4474.5     .16       0
  4678.1      .1       0  4986.5     .07       0  5016.8      .1       0
  5763.2     .05       0
#XS Ineff= 2 , 0
       0                 5029.98       0 1629.55
Permanent Ineff=
       F       T
Bank Sta=4986.5,5016.8
XS Rating Curve= 0 ,0
Exp/Cntr=0.3,0.1

Type RM Length L Ch R = 1 ,9294    ,840,840,840
BEGIN DESCRIPTION:
UNT049 IN NNOGR 14.0
END DESCRIPTION:
XS GIS Cut Line= 3
      2789768.68     10076120.47      2789233.99     10076398.23
       2787893.7     10076676.01
#Sta/Elev= 30
  4345.9 1642.21  4385.5 1641.15  4518.2 1634.11  4616.6  1630.3  4645.3 1628.12
  4750.2 1624.14  4808.2 1625.07  4830.7 1624.54  4853.2 1621.87  4860.8 1623.91
  4866.4 1624.18  4918.5 1623.87  4984.7  1623.4  5000.1 1621.66  5015.3 1622.83
  5053.2    1621  5055.9  1620.5  5059.2    1621  5100.4  1622.3  5250.9  1623.7
  5553.5 1621.86    5785  1623.1    5938 1624.04  5975.3 1626.94  6038.3 1628.11
  6108.1 1631.21  6128.5 1633.18  6178.6  1633.2  6240.8 1636.57  6317.2 1635.86
#Mann= 6 ,-1 , 0
  4345.9     .16       0  4918.5      .1       0  5053.2     .07       0
  5059.2      .1       0  5553.5     .05       0    5785      .1       0
Bank Sta=5053.2,5059.2
XS Rating Curve= 0 ,0
Exp/Cntr=0.3,0.1

Type RM Length L Ch R = 1 ,8454    ,232,232,232
BEGIN DESCRIPTION:
UNT049 IN NNOGR 12.0
END DESCRIPTION:
XS GIS Cut Line= 2
      2789483.99     10075578.79      2787977.03     10076321.85
#Sta/Elev= 30
    4564 1637.69  4609.1 1636.27  4693.7 1632.55  4778.8 1628.32  4856.1 1623.91
    4974 1619.81  4990.9 1618.59  5035.4 1618.79  5135.8 1617.56  5138.5 1617.06
  5141.8 1617.56  5176.1 1618.47  5406.4 1619.92  5423.1 1618.77  5451.1 1619.92
  5596.4 1619.68  5686.2 1619.52  5765.5 1620.02  5796.6 1621.37  5855.3 1621.17
  5900.2 1622.96  5917.1  1624.5  5967.6 1624.91  6019.6 1626.91  6057.4 1627.68
  6086.5 1629.85  6119.2 1629.13  6169.7 1629.91    6198 1631.04  6244.2 1630.98
#Mann= 8 ,-1 , 0
    4564     .05       0  4693.7      .1       0  4778.8     .05       0
  5035.4      .1       0  5135.8    .035       0  5141.8      .1       0
  5596.4     .05       0  5686.2      .1       0
Bank Sta=5135.8,5141.8
XS Rating Curve= 0 ,0
Exp/Cntr=0.3,0.1

Type RM Length L Ch R = 1 ,8222    ,54,54,54
BEGIN DESCRIPTION:
Mapping XS c4913e97
END DESCRIPTION:
XS GIS Cut Line= 4
      2789428.82     10075580.79      2789166.28     10075582.96
       2788220.1     10075509.17      2788018.71     10075719.23
#Sta/Elev= 30
    4577 1635.39  4727.4 1627.76  4904.2 1619.73  4927.6 1618.68  4937.7 1617.71
  4947.7 1615.53  4957.7 1614.78  4992.9 1614.72  5027.9 1614.78    5058 1617.02
  5078.1 1614.79  5098.1 1613.96  5195.4 1612.61  5198.2 1612.11  5201.4 1612.61
  5258.6  1614.4  5302.1 1615.01    5379  1615.6  5439.2 1614.56  5489.3 1616.08
  5549.5 1616.24  5609.7 1617.86  5619.7 1619.37  5639.8 1618.37  5649.8 1618.63
    5700 1621.37    5720 1621.21    5800 1624.42  5969.8 1625.29  6079.6 1627.27
#Mann= 6 ,-1 , 0
    4577     .05       0  4904.2      .1       0  4992.9     .05       0
  5195.4    .035       0  5201.4     .05       0  5302.1      .1       0
Bank Sta=5195.4,5201.4
XS Rating Curve= 0 ,0
Exp/Cntr=0.3,0.1

Type RM Length L Ch R = 1 ,8168    ,50,50,50
BEGIN DESCRIPTION:
Mapping XS 466c6ae1
END DESCRIPTION:
XS GIS Cut Line= 3
      2789415.84      10075543.9      2788191.89      10075463.6
      2787990.09     10075715.31
#Sta/Elev= 30
  4597.8 1634.62  4735.5 1627.67  4925.9 1619.08  4935.9 1618.06  4955.9 1619.13
    4976 1618.24  4981.6 1617.22  4986.6 1619.28  5012.4 1619.05  5036.1 1618.61
  5066.2 1616.66  5086.2 1614.34    5111 1613.62  5183.4  1612.2  5186.2  1611.7
  5189.4  1612.2  5256.6 1614.22  5292.5 1614.67  5386.9 1615.18  5441.2  1614.3
  5487.1 1616.02  5507.1 1615.72  5557.2  1616.3  5617.4 1617.96  5627.4 1619.51
  5637.4 1618.87  5657.4 1618.79  5807.8 1624.73    5884 1624.72    6147 1626.79
#Mann= 6 ,-1 , 0
  4597.8     .05       0  5012.4      .1       0    5111     .05       0
  5183.4    .035       0  5189.4     .05       0  5292.5      .1       0
Bank Sta=5183.4,5189.4
XS Rating Curve= 0 ,0
Exp/Cntr=0.3,0.1

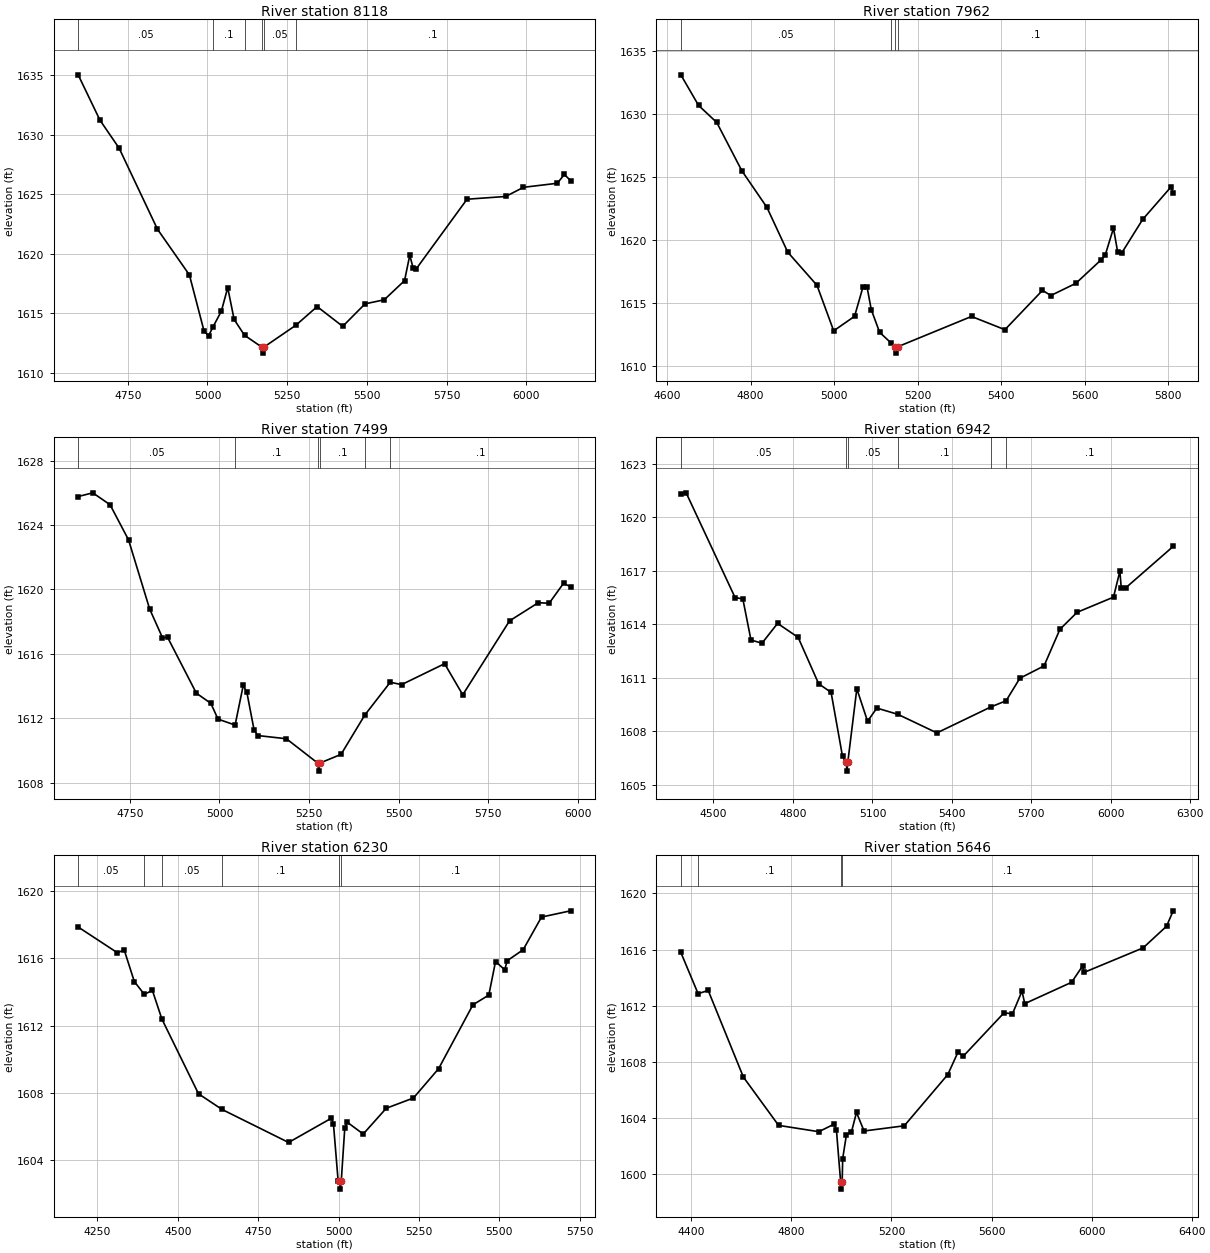
Type RM Length L Ch R = 1 ,8118    ,156,156,156
BEGIN DESCRIPTION:
Mapping XS 998d6bd4
END DESCRIPTION:
XS GIS Cut Line= 3
      2789426.74     10075493.99      2788204.91     10075415.86
      2787992.87     10075656.02
#Sta/Elev= 30
  4594.3 1635.05  4662.7 1631.24  4722.8 1628.89  4843.1 1622.08  4943.3 1618.24
  4989.2 1613.53  5003.4 1613.12  5017.6 1613.89  5043.5 1615.19  5063.5 1617.17
  5083.6  1614.5  5116.2 1613.17  5170.8 1612.17  5173.5 1611.67  5176.8 1612.17
  5277.2 1614.01  5344.1 1615.58  5424.3 1613.92  5494.4 1615.81  5554.5 1616.15
  5618.3 1617.76  5634.7  1619.9  5644.7 1618.86  5654.7 1618.74  5814.3  1624.6
  5935.4 1624.83  5991.4  1625.6  6097.7 1625.94  6119.5 1626.68    6139 1626.17
#Mann= 6 ,-1 , 0
  4594.3     .05       0  5017.6      .1       0  5116.2     .05       0
  5170.8    .035       0  5176.8     .05       0  5277.2      .1       0
Bank Sta=5170.8,5176.8
XS Rating Curve= 0 ,0
Exp/Cntr=0.3,0.1

Type RM Length L Ch R = 1 ,7962    ,463,463,463
BEGIN DESCRIPTION:
UNT049 IN NNOGR 11.0
END DESCRIPTION:
XS GIS Cut Line= 2
      2789414.51     10075307.95       2788235.5     10075328.76
#Sta/Elev= 30
  4632.9 1633.14  4675.5 1630.71    4719 1629.36    4779 1625.53    4839 1622.63
    4889 1619.07    4959 1616.44    4999 1612.83    5049 1613.98    5069 1616.29
    5079 1616.29    5089 1614.51    5109 1612.71  5135.4  1611.9    5146 1611.56
  5148.8 1611.06    5152 1611.56  5329.1 1613.97  5409.1 1612.92  5499.1 1616.04
  5519.1 1615.63  5579.1  1616.6  5639.1 1618.45  5649.1 1618.82  5669.1 1620.97
  5679.1 1619.09  5689.1 1619.02  5739.1 1621.67  5807.3 1624.26  5812.1 1623.73
#Mann= 4 ,-1 , 0
  4632.9     .05       0  5135.4      .1       0    5146    .035       0
    5152      .1       0
Bank Sta=5146,5152
XS Rating Curve= 0 ,0
Exp/Cntr=0.3,0.1

Type RM Length L Ch R = 1 ,7499    ,557,557,557
BEGIN DESCRIPTION:
UNT049 IN NNOGR 10.0
END DESCRIPTION:
XS GIS Cut Line= 2
      2789477.08     10074814.89      2788109.01     10074953.78
#Sta/Elev= 30
  4605.3 1625.77  4646.2    1626  4694.4 1625.26    4746 1623.08  4804.9 1618.79
  4840.7 1617.01  4855.2 1617.02  4935.4 1613.56  4975.8 1612.93  4995.9 1611.95
  5043.6 1611.58  5066.3 1614.04  5076.3 1613.63  5096.4  1611.3  5106.5 1610.93
  5186.9 1610.73  5274.3 1609.22  5277.1 1608.72  5280.3 1609.22  5339.5 1609.76
  5406.1 1612.21    5477 1614.24  5508.5 1614.09  5628.7 1615.39  5679.4 1613.46
  5810.1 1618.05  5890.5 1619.18  5920.6 1619.14  5960.8 1620.38  5980.4 1620.17
#Mann= 6 ,-1 , 0
  4605.3     .05       0  5043.6      .1       0  5274.3    .035       0
  5280.3      .1       0  5406.1     .05       0    5477      .1       0
Bank Sta=5274.3,5280.3
XS Rating Curve= 0 ,0
Exp/Cntr=0.3,0.1

Type RM Length L Ch R = 1 ,6942    ,712,712,712
BEGIN DESCRIPTION:
UNT049 IN NNOGR 9.0
END DESCRIPTION:
XS GIS Cut Line= 2
      2789643.75     10074071.83      2787922.52     10074772.81
#Sta/Elev= 30
  4376.7 1621.31  4396.8 1621.36  4581.4  1615.5  4610.8 1615.42  4641.5 1613.12
    4683 1612.94  4741.9 1614.05  4819.5 1613.27    4897 1610.67  4943.9 1610.19
  4987.1  1606.6    5001 1606.28  5003.8 1605.78    5007 1606.28  5041.1 1610.39
  5081.6 1608.57  5116.6 1609.31  5195.9 1608.96  5343.4 1607.92  5546.5 1609.37
  5604.5 1609.72  5656.5 1610.98  5747.7 1611.67  5807.7 1613.72  5872.5 1614.67
  6009.9 1615.52  6033.9 1616.97  6039.3 1616.02    6056 1616.04  6235.2 1618.36
#Mann= 6 ,-1 , 0
  4376.7     .05       0    5001    .035       0    5007     .05       0
  5195.9      .1       0  5546.5     .05       0  5604.5      .1       0
Bank Sta=5001,5007
XS Rating Curve= 0 ,0
Exp/Cntr=0.3,0.1

Type RM Length L Ch R = 1 ,6230    ,584,584,584
BEGIN DESCRIPTION:
UNT049 IN NNOGR 8.0
END DESCRIPTION:
XS GIS Cut Line= 3
      2789254.79     10073669.08      2788581.22     10073884.34
      2787949.26     10074412.13
#Sta/Elev= 30
  4190.5 1617.85  4312.6 1616.32  4333.6 1616.49  4365.1 1614.61  4396.3 1613.85
  4421.1 1614.09  4450.9 1612.38  4564.6 1607.95  4637.7 1607.02  4844.6 1605.06
  4977.7  1606.5  4984.2 1606.13  4998.5  1602.8  5002.4 1602.79  5005.2 1602.29
  5008.4 1602.79  5019.3 1605.93  5027.1 1606.26  5076.6 1605.56  5148.2 1607.09
  5232.8  1607.7  5310.9 1609.44  5417.6 1613.23    5467 1613.81  5487.9  1615.8
  5516.5 1615.31  5524.3 1615.85  5573.7  1616.5  5630.8 1618.44    5721 1618.81
#Mann= 6 ,-1 , 0
  4190.5     .05       0  4396.3      .1       0  4450.9     .05       0
  4637.7      .1       0  5002.4     .07       0  5008.4      .1       0
Bank Sta=5002.4,5008.4
XS Rating Curve= 0 ,0
Exp/Cntr=0.3,0.1

Type RM Length L Ch R = 1 ,5646    ,391,391,391
BEGIN DESCRIPTION:
UNT049 IN NNOGR 7.0
END DESCRIPTION:
XS GIS Cut Line= 3
      2789037.34     10073354.66       2787990.5     10073458.83
       2787797.8     10074354.62
#Sta/Elev= 30
  4357.9  1615.8    4427 1612.86  4467.3 1613.09    4608 1606.92  4748.7 1603.48
  4909.5 1603.03  4969.8 1603.56  4979.8 1603.18  4996.9 1599.44  4999.7 1598.94
  5002.9 1599.44    5005 1601.12    5020 1602.82  5040.1 1603.02  5060.2  1604.4
  5090.4 1603.08  5251.2 1603.45  5425.2  1607.1  5466.1  1608.7  5486.2 1608.39
  5650.2  1611.5  5683.5 1611.42  5721.8 1613.04  5732.9 1612.15  5920.1 1613.67
  5964.3 1614.84  5969.4 1614.37  6205.9 1616.12  6299.5 1617.66  6326.2 1618.76
#Mann= 4 ,-1 , 0
  4357.9     .05       0    4427      .1       0  4996.9     .07       0
  5002.9      .1       0
Bank Sta=4996.9,5002.9
XS Rating Curve= 0 ,0
Exp/Cntr=0.3,0.1

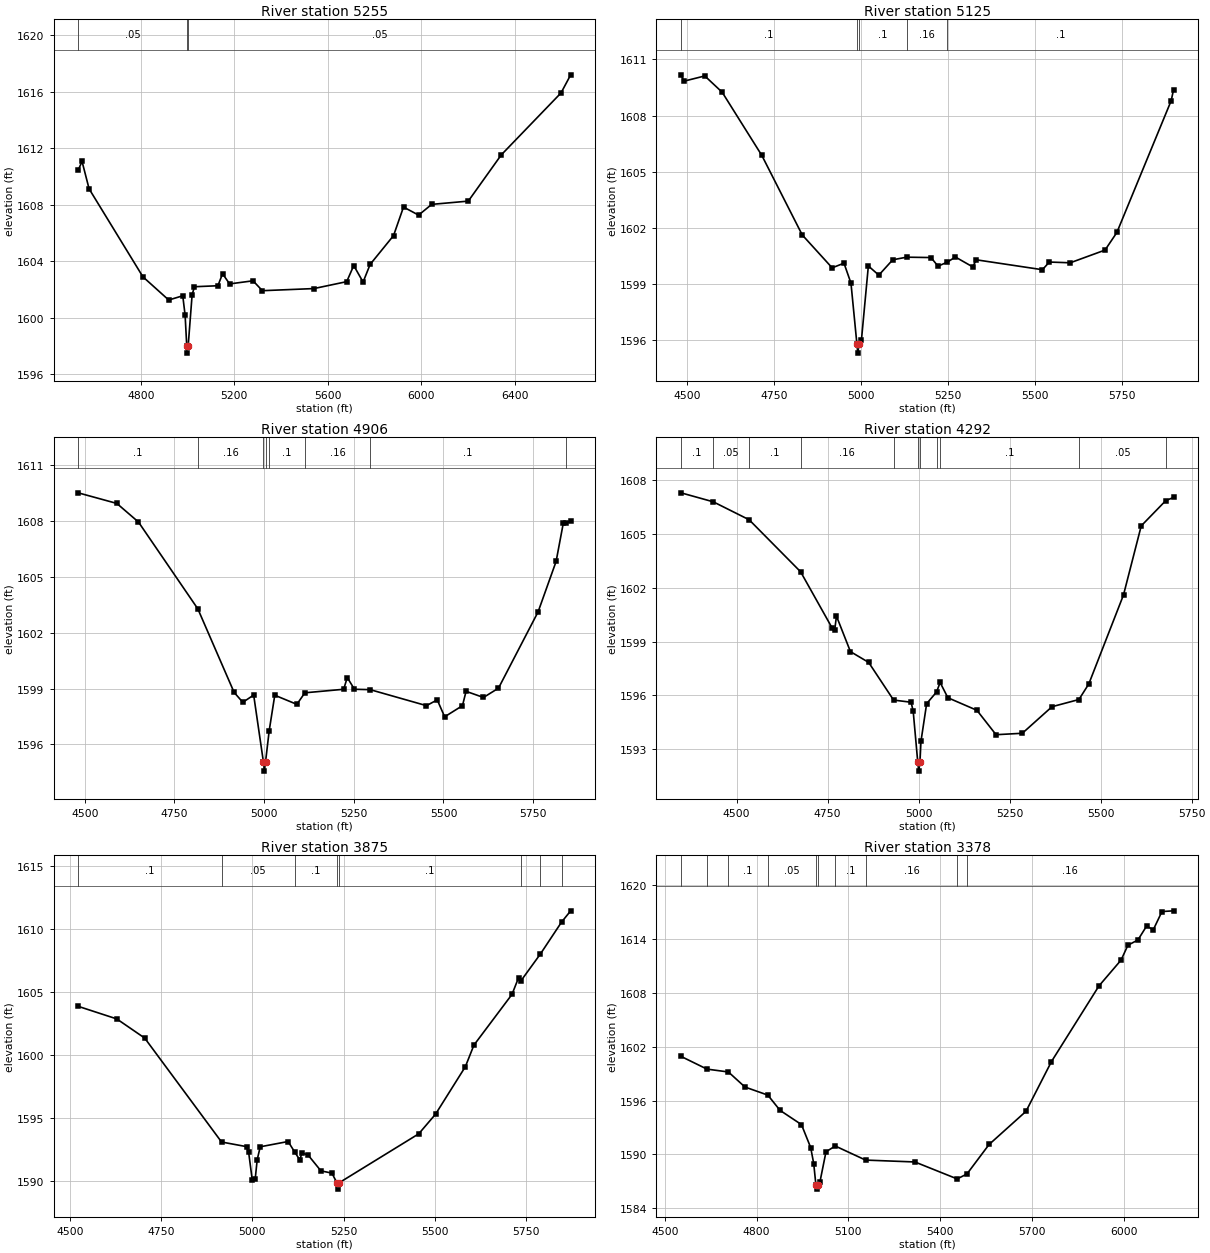
Type RM Length L Ch R = 1 ,5255    ,130,130,130
BEGIN DESCRIPTION:
Mapping XS 6830c6be
END DESCRIPTION:
XS GIS Cut Line= 3
      2788845.09     10073009.34      2787467.06     10073076.01
      2786985.96     10073619.53
#Sta/Elev= 30
  4532.7 1610.46  4549.3 1611.08  4579.4 1609.14  4809.6 1602.91  4919.8 1601.27
  4979.8 1601.57  4989.9 1600.19  4996.9 1598.01  4999.6 1597.51  5002.9 1598.01
  5019.9 1601.65  5029.9 1602.21    5130 1602.28    5150 1603.13  5180.1 1602.41
  5280.2 1602.63  5320.2 1601.93  5540.5 1602.08  5680.7 1602.57  5710.7 1603.71
  5750.7 1602.54  5780.8 1603.79  5880.9 1605.83  5923.5 1607.85    5988 1607.28
    6044 1608.04  6200.4 1608.27  6341.8 1611.55  6596.9 1615.93  6638.2 1617.21
#Mann= 3 ,-1 , 0
  4532.7     .05       0  4996.9     .04       0  5002.9     .05       0
Bank Sta=4996.9,5002.9
XS Rating Curve= 0 ,0
Exp/Cntr=0.3,0.1

Type RM Length L Ch R = 1 ,5125    ,219,219,219
BEGIN DESCRIPTION:
Mapping XS ea182e56
END DESCRIPTION:
XS GIS Cut Line= 2
      2788886.74      10072877.4      2787471.74     10072946.76
#Sta/Elev= 30
  4482.5 1610.18  4490.8 1609.84  4550.9 1610.12  4600.9 1609.25    4715 1605.87
  4831.2 1601.62  4917.3 1599.86  4951.3 1600.11  4971.4 1599.04  4988.4  1595.8
  4991.1  1595.3  4994.4  1595.8  5001.4 1595.98  5021.4 1599.96  5051.5 1599.47
  5091.5 1600.29  5131.5 1600.43  5201.6 1600.41  5221.7 1599.95  5248.1 1600.16
  5271.7 1600.44  5321.7 1599.91  5331.8 1600.29    5522 1599.76    5542 1600.17
  5602.1 1600.13  5702.2 1600.81  5736.2 1601.75  5892.5  1608.8  5899.2 1609.38
#Mann= 5 ,-1 , 0
  4482.5      .1       0  4988.4     .07       0  4994.4      .1       0
  5131.5     .16       0  5248.1      .1       0
Bank Sta=4988.4,4994.4
XS Rating Curve= 0 ,0
Exp/Cntr=0.3,0.1

Type RM Length L Ch R = 1 ,4906    ,614,614,614
BEGIN DESCRIPTION:
UNT049 IN NNOGR 6.0
END DESCRIPTION:
XS GIS Cut Line= 2
      2788865.91     10072641.29      2787497.89     10072759.34
#Sta/Elev= 30
  4481.5 1609.52  4589.3 1608.95  4649.6 1607.95  4815.2 1603.28  4916.3 1598.79
  4940.6 1598.26  4970.8 1598.65  4997.9 1595.06  5000.6 1594.56  5003.9 1595.06
  5014.1 1596.74  5029.6 1598.64  5091.2 1598.15  5113.5 1598.77  5221.7 1598.96
  5231.7 1599.59  5251.8 1598.96  5295.5 1598.94  5452.5 1598.08  5482.6 1598.39
  5503.2 1597.48  5552.9 1598.08  5562.9 1598.85  5611.5 1598.52  5653.3 1599.02
  5763.7 1603.12  5813.9 1605.83  5833.9 1607.88  5841.8 1607.91  5854.6    1608
#Mann= 8 ,-1 , 0
  4481.5      .1       0  4815.2     .16       0  4997.9     .07       0
  5003.9     .16       0  5014.1      .1       0  5113.5     .16       0
  5295.5      .1       0  5841.8     .05       0
Bank Sta=4997.9,5003.9
XS Rating Curve= 0 ,0
Exp/Cntr=0.3,0.1

Type RM Length L Ch R = 1 ,4292    ,417,417,417
BEGIN DESCRIPTION:
UNT049 IN NNOGR 4.0
END DESCRIPTION:
XS GIS Cut Line= 3
      2788643.68     10072169.06      2788074.27     10072155.17
      2787402.05     10072557.12
#Sta/Elev= 30
  4347.4 1607.29  4435.9 1606.79  4534.5 1605.79  4675.9 1602.89  4762.7 1599.75
  4769.4 1599.62  4774.4 1600.42  4812.8 1598.44  4862.8 1597.84  4931.3 1595.74
  4979.3 1595.62  4985.1 1595.13  4997.7 1592.28  5000.4 1591.78  5003.7 1592.28
  5006.5 1593.44  5022.1 1595.54  5049.3 1596.19  5059.1 1596.72  5080.4 1595.87
  5160.2 1595.17  5212.7 1593.81  5284.9 1593.89  5366.4 1595.37  5440.3 1595.77
  5467.5 1596.64  5562.8  1601.6  5611.5 1605.45  5679.1 1606.86  5700.2 1607.03
#Mann= 11 ,-1 , 0
  4347.4      .1       0  4435.9     .05       0  4534.5      .1       0
  4675.9     .16       0  4931.3      .1       0  4997.7     .07       0
  5003.7      .1       0  5049.3     .16       0  5059.1      .1       0
  5440.3     .05       0  5679.1      .1       0
Bank Sta=4997.7,5003.7
XS Rating Curve= 0 ,0
Exp/Cntr=0.3,0.1

Type RM Length L Ch R = 1 ,3875    ,497,497,497
BEGIN DESCRIPTION:
UNT049 IN NNOGR 3.0
END DESCRIPTION:
XS GIS Cut Line= 2
       2788185.4     10071682.95      2786949.27     10072224.62
#Sta/Elev= 30
  4522.5 1603.86  4628.3 1602.86  4704.8 1601.34  4915.4 1593.09  4984.3 1592.72
  4989.7 1592.26  4999.5 1590.08  5007.7 1590.18  5013.1 1591.69  5021.4 1592.71
  5097.8 1593.13  5115.5 1592.31    5130 1591.66  5135.4 1592.22  5152.4 1592.06
  5187.7  1590.8  5217.9 1590.62  5231.4 1589.85  5234.2 1589.35  5237.4 1589.85
  5455.7 1593.74  5501.8  1595.3  5583.5 1599.07  5606.9 1600.78  5711.3 1604.81
  5729.2 1606.13  5734.9 1605.85    5789 1608.01  5847.4 1610.56  5872.1 1611.44
#Mann= 8 ,-1 , 0
  4522.5      .1       0  4915.4     .05       0  5115.5      .1       0
  5231.4     .04       0  5237.4      .1       0  5734.9     .16       0
    5789      .1       0  5847.4     .16       0
Bank Sta=5231.4,5237.4
XS Rating Curve= 0 ,0
Exp/Cntr=0.3,0.1

Type RM Length L Ch R = 1 ,3378    ,583,583,583
BEGIN DESCRIPTION:
Mapping XS 10f15cab
END DESCRIPTION:
XS GIS Cut Line= 4
      2788201.39     10071414.56      2787394.14     10071469.24
      2787099.87     10071544.76      2786873.37     10071987.37
#Sta/Elev= 30
    4553 1600.93  4637.9 1599.51    4708 1599.19  4762.1 1597.51  4836.9 1596.61
  4876.7 1594.91  4946.8 1593.32  4976.9 1590.76  4986.9 1588.97  4993.9 1586.62
  4996.7 1586.12  4999.9 1586.62    5007 1586.89    5027 1590.29  5057.3 1590.93
  5156.5 1589.36  5317.7 1589.15  5455.8 1587.26  5487.8 1587.81  5560.1  1591.1
  5680.8  1594.8    5764 1600.35  5919.5  1608.8  5991.7 1611.68  6013.9 1613.33
  6046.7 1613.92  6074.9 1615.46  6097.1 1615.07  6125.3 1617.09  6163.1 1617.17
#Mann= 10 ,-1 , 0
    4553      .1       0  4637.9     .05       0    4708      .1       0
  4836.9     .05       0  4993.9     .04       0  4999.9     .05       0
  5057.3      .1       0  5156.5     .16       0  5455.8      .1       0
  5487.8     .16       0
Bank Sta=4993.9,4999.9
XS Rating Curve= 0 ,0
Exp/Cntr=0.3,0.1

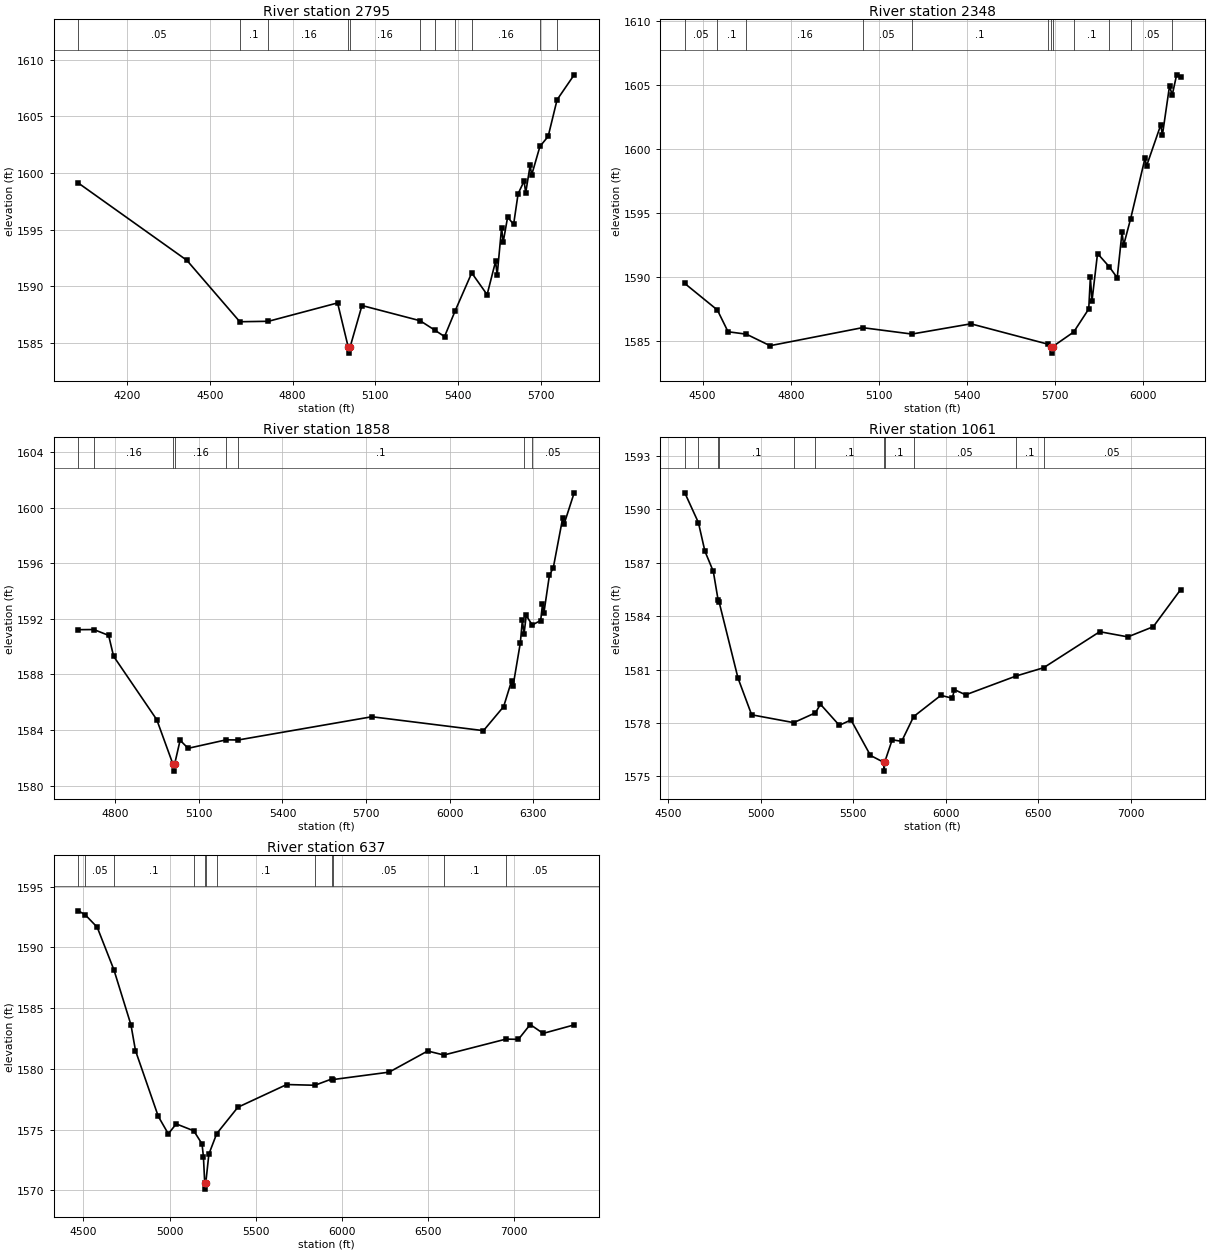
Type RM Length L Ch R = 1 ,2795    ,447,447,447
BEGIN DESCRIPTION:
UNT049 IN NNOGR 2.0
END DESCRIPTION:
XS GIS Cut Line= 4
      2788189.89     10071323.19      2787590.98     10071262.43
      2786948.62     10071462.08      2786697.79     10071920.48
#Sta/Elev= 30
  4023.3  1599.1  4416.7 1592.28  4608.6 1586.86  4712.4  1586.9    4963 1588.52
  5001.9 1584.59  5004.7 1584.09  5007.9 1584.59  5051.4 1588.29  5262.1 1586.95
  5315.3 1586.12  5350.7 1585.55  5389.3 1587.83  5449.2 1591.17    5505 1589.25
  5535.7 1592.19  5541.4 1590.97  5557.5 1595.16  5563.2 1593.88  5579.3 1596.09
  5601.1 1595.46  5617.3 1598.15  5639.1 1599.28  5644.8 1598.23  5660.9 1600.65
  5666.6 1599.82  5696.4 1602.33  5726.3 1603.22  5758.6 1606.45  5820.5 1608.65
#Mann= 11 ,-1 , 0
  4023.3     .05       0  4608.6      .1       0  4712.4     .16       0
  5001.9     .07       0  5007.9     .16       0  5262.1     .05       0
  5315.3     .16       0  5389.3     .05       0  5449.2     .16       0
  5696.4     .05       0  5758.6     .16       0
Bank Sta=5001.9,5007.9
XS Rating Curve= 0 ,0
Exp/Cntr=0.3,0.1

Type RM Length L Ch R = 1 ,2348    ,490,490,490
BEGIN DESCRIPTION:
Mapping XS 86503c25
END DESCRIPTION:
XS GIS Cut Line= 3
      2787726.79     10071065.14      2787039.29     10070989.62
      2786669.51     10071914.07
#Sta/Elev= 30
  4439.6 1589.52  4550.4 1587.45  4586.8 1585.75  4649.2 1585.56  4729.7 1584.66
  5044.4 1586.07  5212.3 1585.57  5413.2 1586.37  5675.2 1584.78  5684.9 1584.58
  5687.6 1584.08  5690.9 1584.58  5763.1 1585.73  5814.2 1587.53  5819.8 1590.02
  5825.2 1588.14  5844.1 1591.86  5883.5 1590.84  5911.1 1589.97  5927.5 1593.53
  5932.9 1592.51  5956.8 1594.58  6005.6 1599.29    6011  1598.7  6059.5 1601.92
  6064.8 1601.09  6089.1 1604.95  6098.3 1604.24  6113.3 1605.82  6126.9 1605.68
#Mann= 12 ,-1 , 0
  4439.6     .05       0  4550.4      .1       0  4649.2     .16       0
  5044.4     .05       0  5212.3      .1       0  5675.2     .05       0
  5684.9     .07       0  5690.9     .05       0  5763.1      .1       0
  5883.5     .16       0  5956.8     .05       0  6098.3     .16       0
Bank Sta=5684.9,5690.9
XS Rating Curve= 0 ,0
Exp/Cntr=0.3,0.1

Type RM Length L Ch R = 1 ,1858    ,797,797,797
BEGIN DESCRIPTION:
Mapping XS aa2b081d
END DESCRIPTION:
XS GIS Cut Line= 3
      2787591.41     10070593.78      2786997.62     10070737.02
       2786672.2     10071859.06
#Sta/Elev= 30
  4667.5 1591.22  4723.1 1591.23  4776.2 1590.81    4794 1589.31  4948.9 1584.75
    5007 1581.55  5009.7 1581.05    5013 1581.55  5032.7 1583.27  5061.4 1582.69
  5198.1  1583.3  5241.2 1583.29  5720.7 1584.96  6121.2 1583.96  6193.6 1585.69
  6221.9 1587.53  6227.1 1587.14  6253.6 1590.29  6260.7 1591.89  6266.9 1590.92
  6274.5 1592.24  6296.1 1591.56  6326.5 1591.88    6333 1593.06  6338.2 1592.45
  6357.8 1595.13  6371.8 1595.68  6405.4 1599.24  6410.6 1598.82  6446.6 1601.06
#Mann= 8 ,-1 , 0
  4667.5     .05       0  4723.1     .16       0    5007     .07       0
    5013     .16       0  5198.1     .05       0  5241.2      .1       0
  6266.9     .16       0  6296.1     .05       0
Bank Sta=5007,5013
XS Rating Curve= 0 ,0
Exp/Cntr=0.3,0.1

Type RM Length L Ch R = 1 ,1061    ,424,424,424
BEGIN DESCRIPTION:
Mapping XS 33780a3f
END DESCRIPTION:
XS GIS Cut Line= 3
      2787641.56     10069791.38      2786344.65     10070215.87
      2786027.33     10071490.36
#Sta/Elev= 30
  4591.1 1590.91  4664.6 1589.24  4699.6 1587.64  4745.1  1586.5  4771.3 1584.88
  4776.6 1584.78  4878.4 1580.52  4952.1 1578.46  5179.4 1578.02  5296.5 1578.57
  5323.8 1579.05  5425.6 1577.87  5488.7 1578.17  5593.9 1576.18  5664.6  1575.8
  5667.3  1575.3  5670.6  1575.8  5711.3 1577.06  5762.3 1576.97  5827.2 1578.36
  5974.1 1579.55  6035.9 1579.39  6047.4 1579.87  6108.1 1579.58  6381.7 1580.64
  6529.2  1581.1  6832.2 1583.12    6984 1582.83  7121.3  1583.4  7269.1 1585.48
#Mann= 11 ,-1 , 0
  4591.1     .05       0  4664.6     .16       0  4771.3     .05       0
  4776.6      .1       0  5179.4     .16       0  5296.5      .1       0
  5664.6     .07       0  5670.6      .1       0  5827.2     .05       0
  6381.7      .1       0  6529.2     .05       0
Bank Sta=5664.6,5670.6
XS Rating Curve= 0 ,0
Exp/Cntr=0.3,0.1

Type RM Length L Ch R = 1 ,637     ,0,0,0
BEGIN DESCRIPTION:
Mapping XS 33780a3f.1
END DESCRIPTION:
XS GIS Cut Line= 4
      2787628.53     10069374.72      2786474.86     10069754.94
      2786170.17     10070523.16       2785995.7     10071343.46
#Sta/Elev= 30
  4470.1 1593.01  4510.4 1592.68  4579.7 1591.66  4676.6 1588.16  4775.6 1583.63
  4802.1  1581.5  4934.4 1576.09  4992.7 1574.65  5038.7 1575.47  5140.6  1574.9
  5188.6 1573.82  5196.7 1572.75  5204.2  1570.6    5207  1570.1  5210.2  1570.6
  5228.3 1572.98  5273.9 1574.67  5396.7 1576.84  5680.3 1578.71    5844 1578.65
  5942.7 1579.17  5949.2 1579.12  6275.2 1579.73    6499 1581.47  6593.4 1581.14
  6953.9 1582.45  7026.1 1582.43  7094.6 1583.65  7169.8 1582.92  7349.9 1583.62
#Mann= 12 ,-1 , 0
  4470.1      .1       0  4510.4     .05       0  4676.6      .1       0
  5140.6     .16       0  5204.2     .07       0  5210.2     .16       0
  5273.9      .1       0    5844     .05       0  5942.7      .1       0
  5949.2     .05       0  6593.4      .1       0  6953.9     .05       0
Bank Sta=5204.2,5210.2
XS Rating Curve= 0 ,0
Exp/Cntr=0.3,0.1

Chan Stop Cuts=-1
Use User Specified Reach Order=0
Composite Channel Slope=5