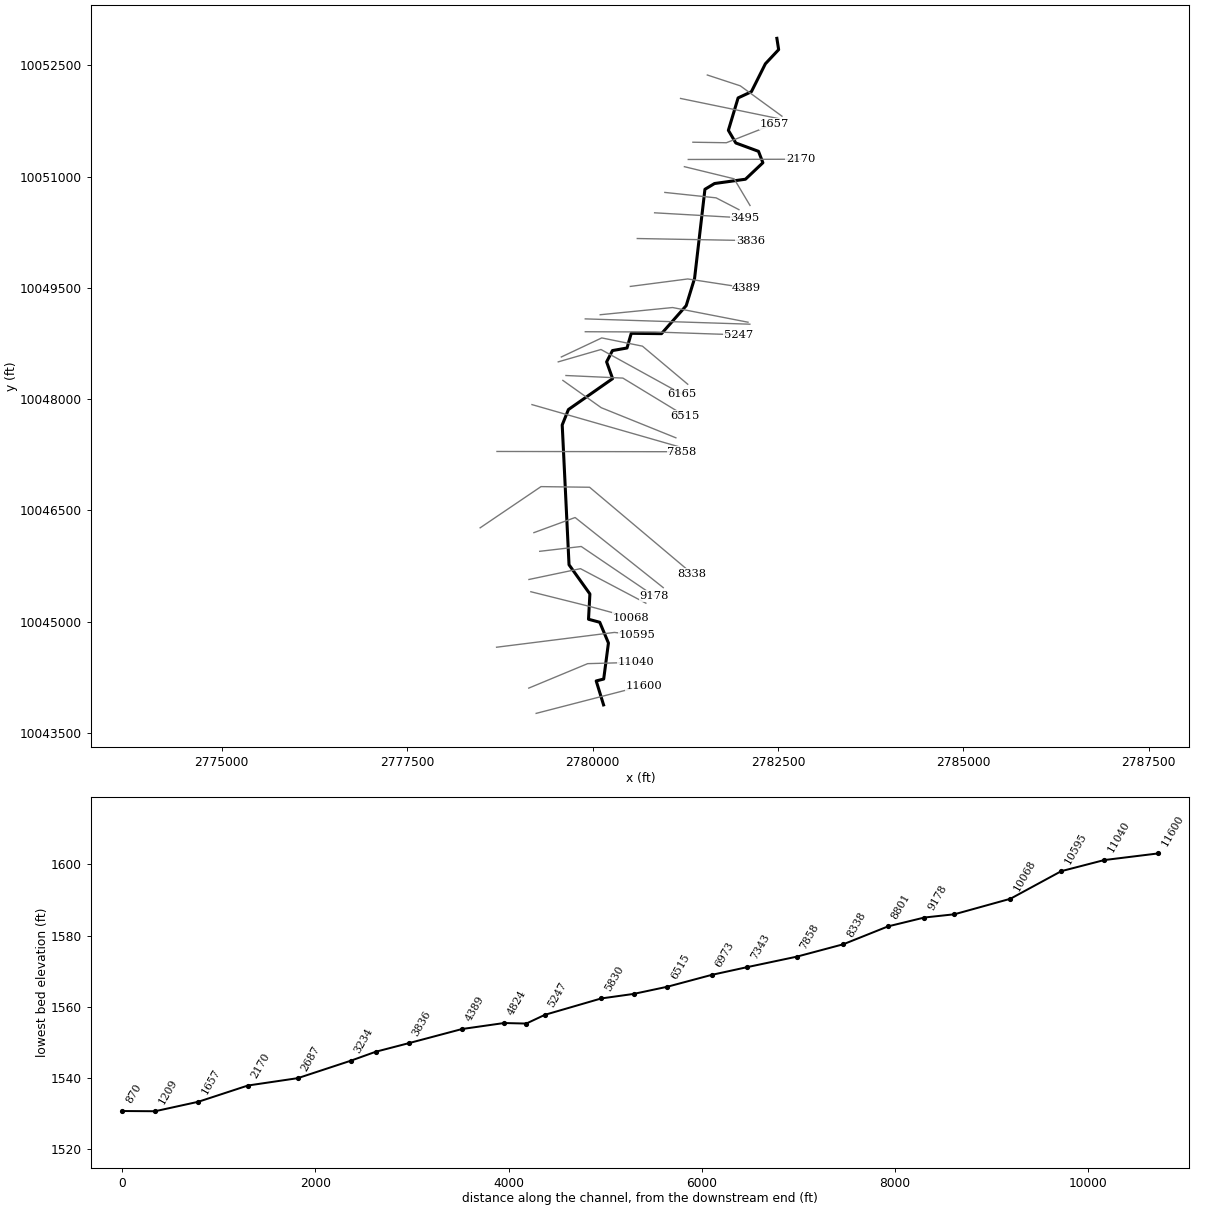
--- UNT049 IN SNOGR.prj (project) ---

Proj Title=UNT049 IN SNOGR Base Level Engineering
Current Plan=p01
Default Exp/Contr=0.3,0.1
English Units
Geom File=g01
Flow File=f01
Plan File=p01
BEGIN DESCRIPTION:
UNT049 IN SNOGR
END DESCRIPTION:

--- UNT049 IN SNOGR.p01 (plan) ---

Plan Title=Multiple Run
Short Identifier=Multiple
Geom File=g01
Flow File=f01
Subcritical Flow
K Sum by GR= 0
Std Step Tol= 0.01
Critical Tol= 0.01
Num of Std Step Trials= 20
Max Error Tol= 0.3
Flow Tol Ratio= 0.001
Split Flow NTrial= 30
Split Flow Tol= 0.02
Split Flow Ratio= 0.02
Log Output Level= 0
Friction Slope Method= 1
Unsteady Friction Slope Method= 2
Unsteady Bridges Friction Slope Method= 1
Parabolic Critical Depth
Global Vel Dist=  1 , 1 , 1
Global Log Level= 0
CheckData=True
Encroach Param= -1, 0, 0, 0
BEGIN DESCRIPTION:
Multiple Run
END DESCRIPTION:

--- UNT049 IN SNOGR.f01 (steady flow) ---

Flow Title=Multiple
Number of Profiles=7
Profile Names=10-year,25-year,50-year,1pct_min,100-year,1pct_plu,500-year
River Rch & RM= UNT049 IN SNOGR,Reach-1,11600
    1197    1763    2262    2120    2867    3877    4630
River Rch & RM= UNT049 IN SNOGR,Reach-1,5054
    1299    1915    2457    2302    3114    4211    5027
Boundary for River Rch & Prof#=UNT049 IN SNOGR,Reach-1,1
Up Type=0
Dn Type=3
Dn Slope=0.005
Boundary for River Rch & Prof#=UNT049 IN SNOGR,Reach-1,2
Up Type=0
Dn Type=3
Dn Slope=0.005
Boundary for River Rch & Prof#=UNT049 IN SNOGR,Reach-1,3
Up Type=0
Dn Type=3
Dn Slope=0.005
Boundary for River Rch & Prof#=UNT049 IN SNOGR,Reach-1,4
Up Type=0
Dn Type=3
Dn Slope=0.005
Boundary for River Rch & Prof#=UNT049 IN SNOGR,Reach-1,5
Up Type=0
Dn Type=3
Dn Slope=0.005
Boundary for River Rch & Prof#=UNT049 IN SNOGR,Reach-1,6
Up Type=0
Dn Type=3
Dn Slope=0.005
Boundary for River Rch & Prof#=UNT049 IN SNOGR,Reach-1,7
Up Type=0
Dn Type=3
Dn Slope=0.005

--- UNT049 IN SNOGR.g01 (geometry) ---

Geom Title=Existing Conditions

River Reach=UNT049 IN SNOGR,Reach-1
Reach XY= 30
      2780149.06     10043877.69      2780049.82     10044200.78
      2780150.83     10044226.63      2780214.68     10044712.46
      2780097.36     10044992.09      2779946.04     10045032.59
      2779964.71     10045373.55      2779683.25     10045767.31
      2779591.36     10047652.53      2779674.95     10047860.18
      2780270.92     10048277.32      2780190.17     10048503.24
      2780269.07     10048655.77      2780465.01     10048690.43
      2780522.52     10048888.42      2780930.57     10048884.00
      2781263.13     10049261.23      2781376.23     10049629.48
      2781515.86     10050830.29      2781645.30     10050908.32
      2782062.26     10050966.16      2782297.43     10051188.63
      2782238.28     10051342.44      2781932.21     10051455.07
      2781832.05     10051625.75      2781963.25     10052062.62
      2782142.37     10052146.16      2782330.97     10052522.81
      2782509.88     10052713.79      2782486.07     10052866.11

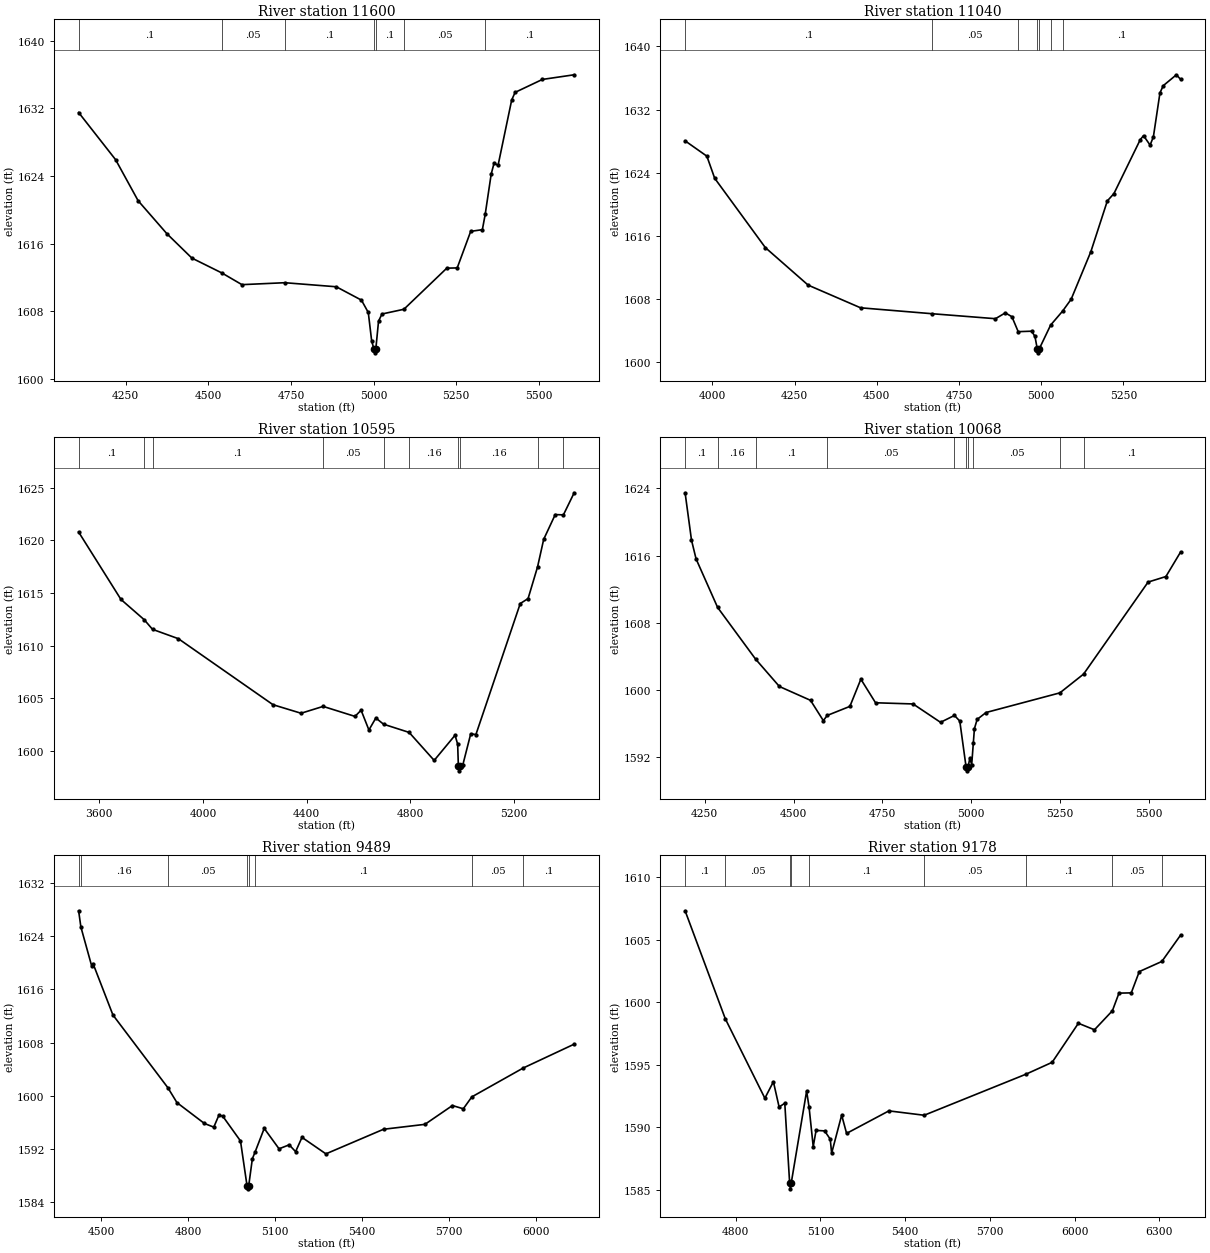
Type RM Length L Ch R = 1,11600,560,560,560
BEGIN DESCRIPTION:
UNT049 IN SNOGR 23.0
END DESCRIPTION:
XS GIS Cut Line= 2
      2779240.15     10043763.44      2780691.49     10044138.43
#Sta/Elev= 30
  4107.7 1631.50  4219.6 1625.92  4287.7 1621.07  4374.5 1617.18  4450.3 1614.29
  4541.1 1612.53  4601.7 1611.15  4731.4 1611.38  4887.1 1610.90  4963.2 1609.32
  4983.9 1607.86  4994.2 1604.47  5000.8 1603.59  5003.6 1603.09  5006.8 1603.59
  5014.9 1606.83  5025.2 1607.68  5091.6 1608.24  5221.4 1613.10  5252.9 1613.13
  5293.7 1617.45  5329.0 1617.65  5337.6 1619.47  5355.7 1624.22  5364.5 1625.53
  5376.4 1625.24  5417.7 1632.98  5428.0 1633.88  5510.6 1635.41  5606.7 1635.96
#Mann=7,-1,0
  4107.7     0.1       0  4541.1    0.05       0  4731.4     0.1       0
  5000.8    0.07       0  5006.8     0.1       0  5091.6    0.05       0
  5337.6     0.1       0
Bank Sta=5000.8,5006.8
Exp/Cntr=0.3,0.1

Type RM Length L Ch R = 1,11040,445,445,445
BEGIN DESCRIPTION:
UNT049 IN SNOGR 22.0
END DESCRIPTION:
XS GIS Cut Line= 3
      2779140.34     10044104.20      2779934.63     10044434.07
      2780581.33     10044451.44
#Sta/Elev= 30
  3917.2 1628.05  3983.4 1626.11  4007.2 1623.31  4161.2 1614.54  4291.4 1609.79
  4450.8 1606.92  4668.4 1606.17  4861.1 1605.54  4891.1 1606.28  4911.1 1605.79
  4930.2 1603.90  4971.2 1603.96  4981.2 1603.29  4988.2 1601.72  4990.9 1601.22
  4994.2 1601.72  5028.8 1604.73  5065.2 1606.50  5091.2 1608.00  5151.2 1614.03
  5201.3 1620.45  5221.3 1621.37  5301.3 1628.19  5311.3 1628.71  5331.3 1627.51
  5341.3 1628.55  5361.3 1634.12  5371.3 1635.03  5411.3 1636.41  5424.2 1635.82
#Mann=7,-1,0
  3917.2     0.1       0  4668.4    0.05       0  4930.2     0.1       0
  4988.2    0.07       0  4994.2     0.1       0  5028.8    0.16       0
  5065.2     0.1       0
Bank Sta=4988.2,4994.2
Exp/Cntr=0.3,0.1

Type RM Length L Ch R = 1,10595,527,527,527
BEGIN DESCRIPTION:
UNT049 IN SNOGR 21.0
END DESCRIPTION:
XS GIS Cut Line= 3
      2778706.31     10044655.42      2780294.88     10044855.08
      2780605.40     10044820.58
#Sta/Elev= 30
  3520.0 1620.78  3683.4 1614.38  3773.4 1612.45  3805.3 1611.54  3905.2 1610.65
  4270.6 1604.38  4378.9 1603.57  4464.1 1604.22  4587.2 1603.27  4610.7 1603.86
  4640.9 1601.98  4667.7 1603.12  4697.3 1602.53  4796.2 1601.75  4892.9 1599.09
  4973.5 1601.48  4983.6 1600.63  4986.3 1598.60  4989.0 1598.10  4992.3 1598.60
  5003.7 1598.68  5034.0 1601.61  5054.1 1601.55  5225.3 1613.99  5255.5 1614.46
  5292.2 1617.48  5315.8 1620.09  5360.4 1622.44  5391.9 1622.41  5433.5 1624.51
#Mann=10,-1,0
  3520.0     0.1       0  3773.4    0.05       0  3805.3     0.1       0
  4464.1    0.05       0  4697.3     0.1       0  4796.2    0.16       0
  4986.3    0.07       0  4992.3    0.16       0  5292.2    0.05       0
  5391.9     0.1       0
Bank Sta=4986.3,4992.3
Exp/Cntr=0.3,0.1

Type RM Length L Ch R = 1,10068,579,579,579
BEGIN DESCRIPTION:
UNT049 IN SNOGR 20.0
END DESCRIPTION:
XS GIS Cut Line= 3
      2779168.50     10045403.72      2779968.47     10045203.73
      2780518.49     10045053.73
#Sta/Elev= 30
  4194.9 1623.48  4212.9 1617.84  4225.8 1615.60  4286.4 1609.82  4393.1 1603.67
  4460.3 1600.40  4547.9 1598.75  4584.0 1596.33  4594.9 1596.95  4658.7 1598.03
  4689.6 1601.27  4730.9 1598.46  4836.5 1598.32  4913.8 1596.13  4953.0 1596.95
  4968.0 1596.28  4985.6 1590.85  4988.3 1590.35  4991.6 1590.85  4996.3 1591.86
  5001.5 1591.08  5006.1 1593.65  5009.2 1595.38  5016.9 1596.48  5041.9 1597.30
  5249.7 1599.64  5316.5 1601.88  5498.0 1612.84  5548.1 1613.50  5589.6 1616.43
#Mann=10,-1,0
  4194.9     0.1       0  4286.4    0.16       0  4393.1     0.1       0
  4594.9    0.05       0  4953.0     0.1       0  4985.6    0.07       0
  4991.6     0.1       0  5006.1    0.05       0  5249.7    0.16       0
  5316.5     0.1       0
Bank Sta=4985.6,4991.6
Exp/Cntr=0.3,0.1

Type RM Length L Ch R = 1,9489,311,311,311
BEGIN DESCRIPTION:
UNT049 IN SNOGR 19.0
END DESCRIPTION:
XS GIS Cut Line= 3
      2779142.86     10045568.98      2779837.35     10045714.82
      2780719.31     10045249.54
#Sta/Elev= 30
  4423.1 1627.82  4430.8 1625.39  4467.6 1619.59  4472.7 1619.88  4541.2 1612.15
  4730.6 1601.20  4761.7 1598.97  4856.3 1595.83  4888.6 1595.28  4906.2 1597.07
  4919.3 1596.94  4980.6 1593.20  5003.0 1586.50  5005.7 1586.00  5009.0 1586.50
  5021.5 1590.53  5030.3 1591.47  5062.3 1595.09  5113.4 1592.02  5148.4 1592.62
  5170.4 1591.59  5192.4 1593.74  5274.8 1591.26  5473.2 1594.96  5615.9 1595.70
  5710.6 1598.53  5748.0 1598.04  5777.4 1599.83  5954.3 1604.17  6129.9 1607.76
#Mann=8,-1,0
  4423.1    0.05       0  4430.8    0.16       0  4730.6    0.05       0
  5003.0    0.04       0  5009.0    0.05       0  5030.3     0.1       0
  5777.4    0.05       0  5954.3     0.1       0
Bank Sta=5003,5009
Exp/Cntr=0.3,0.1

Type RM Length L Ch R = 1,9178,377,377,377
BEGIN DESCRIPTION:
UNT049 IN SNOGR 18.0
END DESCRIPTION:
XS GIS Cut Line= 3
      2779287.92     10045948.83      2779847.83     10046013.94
      2780833.11     10045345.51
#Sta/Elev= 30
  4620.7 1607.31  4763.0 1598.68  4903.1 1592.33  4933.3 1593.65  4953.5 1591.63
  4973.6 1591.93  4990.7 1585.59  4993.5 1585.09  4996.7 1585.59  5050.9 1592.90
  5059.5 1591.63  5074.3 1588.47  5084.4 1589.76  5114.6 1589.72  5134.5 1589.06
  5139.5 1587.94  5175.0 1590.98  5192.4 1589.52  5342.2 1591.32  5467.1 1590.97
  5827.3 1594.25  5920.1 1595.20  6013.0 1598.32  6069.9 1597.80  6133.4 1599.32
  6156.7 1600.73  6200.2 1600.75  6228.6 1602.45  6308.5 1603.26  6375.0 1605.37
#Mann=9,-1,0
  4620.7     0.1       0  4763.0    0.05       0  4990.7    0.04       0
  4996.7    0.05       0  5059.5     0.1       0  5467.1    0.05       0
  5827.3     0.1       0  6133.4    0.05       0  6308.5     0.1       0
Bank Sta=4990.7,4996.7
Exp/Cntr=0.3,0.1

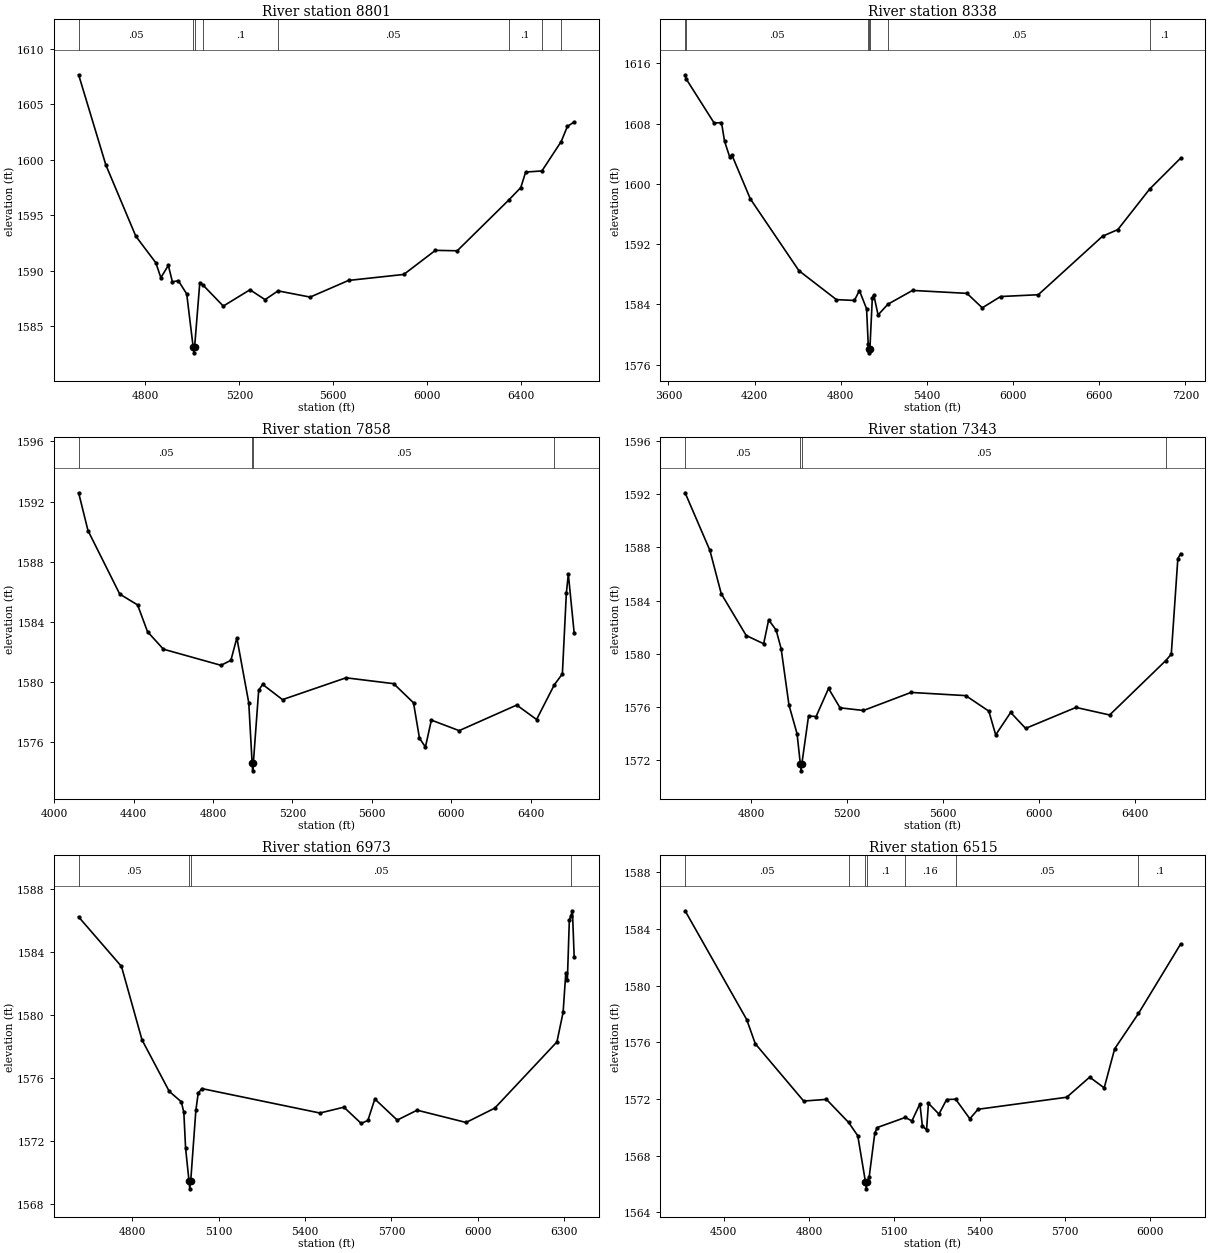
Type RM Length L Ch R = 1,8801,463,463,463
BEGIN DESCRIPTION:
UNT049 IN SNOGR 17.0
END DESCRIPTION:
XS GIS Cut Line= 3
      2779209.82     10046200.57      2779765.36     10046404.56
      2780953.79     10045459.02
#Sta/Elev= 30
  4515.5 1607.64  4631.4 1599.52  4759.1 1593.10  4844.3 1590.71  4865.6 1589.37
  4897.6 1590.47  4914.9 1588.99  4940.1 1589.10  4975.9 1587.90  5003.4 1583.10
  5006.1 1582.60  5009.4 1583.10  5031.5 1588.92  5045.3 1588.70  5131.6 1586.81
  5245.3 1588.28  5309.4 1587.39  5364.8 1588.18  5501.6 1587.62  5665.0 1589.12
  5900.4 1589.66  6035.0 1591.83  6127.9 1591.79  6346.4 1596.34  6398.6 1597.48
  6419.4 1598.88  6488.6 1598.98  6570.8 1601.63  6597.2 1602.99  6626.0 1603.39
#Mann=8,-1,0
  4515.5    0.05       0  5003.4    0.04       0  5009.4    0.05       0
  5045.3     0.1       0  5364.8    0.05       0  6346.4     0.1       0
  6488.6    0.05       0  6570.8     0.1       0
Bank Sta=5003.4,5009.4
Exp/Cntr=0.3,0.1

Type RM Length L Ch R = 1,8338,480,480,480
BEGIN DESCRIPTION:
UNT049 IN SNOGR 16.0
END DESCRIPTION:
XS GIS Cut Line= 4
      2778484.95     10046265.65      2779305.29     10046821.23
      2779960.67     10046812.55      2781340.88     10045649.35
#Sta/Elev= 30
  3716.0 1614.47  3722.5 1613.95  3918.6 1608.06  3969.5 1608.13  3990.5 1605.67
  4026.4 1603.58  4041.4 1603.85  4170.2 1598.01  4508.7 1588.48  4769.9 1584.64
  4895.0 1584.53  4930.0 1585.84  4980.0 1583.42  4991.2 1578.78  4997.0 1578.08
  4999.7 1577.58  5003.0 1578.08  5020.0 1584.91  5030.0 1585.27  5060.0 1582.61
  5128.4 1584.03  5300.0 1585.86  5679.1 1585.47  5785.7 1583.55  5913.2 1585.05
  6175.9 1585.29  6623.2 1593.05  6729.8 1593.93  6951.0 1599.30  7167.2 1603.41
#Mann=7,-1,0
  3716.0     0.1       0  3722.5    0.05       0  4991.2     0.1       0
  4997.0    0.07       0  5003.0     0.1       0  5128.4    0.05       0
  6951.0     0.1       0
Bank Sta=4997,5003
Exp/Cntr=0.3,0.1

Type RM Length L Ch R = 1,7858,515,515,515
BEGIN DESCRIPTION:
UNT049 IN SNOGR 15.0
END DESCRIPTION:
XS GIS Cut Line= 2
      2778711.38     10047295.13      2781207.88     10047291.66
#Sta/Elev= 30
  4122.9 1592.58  4170.0 1590.07  4330.0 1585.85  4420.0 1585.13  4470.0 1583.35
  4550.0 1582.19  4840.0 1581.12  4890.0 1581.45  4920.0 1582.94  4980.0 1578.63
  4997.0 1574.61  4999.7 1574.11  5003.0 1574.61  5030.0 1579.47  5050.0 1579.85
  5150.0 1578.84  5470.0 1580.29  5710.0 1579.90  5810.0 1578.63  5840.0 1576.28
  5870.0 1575.69  5900.0 1577.48  6040.0 1576.78  6330.0 1578.48  6430.0 1577.52
  6519.2 1579.82  6560.0 1580.55  6580.0 1585.92  6590.0 1587.18  6619.4 1583.26
#Mann=4,-1,0
  4122.9    0.05       0  4997.0    0.04       0  5003.0    0.05       0
  6519.2     0.1       0
Bank Sta=4997,5003
Exp/Cntr=0.3,0.1

Type RM Length L Ch R = 1,7343,370,370,370
BEGIN DESCRIPTION:
UNT049 IN SNOGR 14.0
END DESCRIPTION:
XS GIS Cut Line= 2
      2779183.56     10047927.08      2781169.74     10047357.62
#Sta/Elev= 30
  4525.2 1592.12  4628.6 1587.78  4675.9 1584.51  4780.0 1581.36  4852.8 1580.74
  4873.6 1582.54  4904.8 1581.77  4925.6 1580.37  4958.3 1576.12  4992.1 1573.95
  5005.8 1571.66  5008.6 1571.16  5011.8 1571.66  5040.0 1575.30  5071.3 1575.25
  5123.3 1577.37  5171.2 1575.91  5268.9 1575.71  5467.2 1577.07  5695.4 1576.83
  5791.7 1575.66  5820.2 1573.87  5882.7 1575.56  5945.1 1574.36  6155.2 1575.94
  6295.3 1575.37  6529.4 1579.47  6552.4 1579.95  6579.7 1587.15  6591.4 1587.53
#Mann=4,-1,0
  4525.2    0.05       0  5005.8    0.04       0  5011.8    0.05       0
  6529.4     0.1       0
Bank Sta=5005.8,5011.8
Exp/Cntr=0.3,0.1

Type RM Length L Ch R = 1,6973,458,458,458
BEGIN DESCRIPTION:
UNT049 IN SNOGR 13.0
END DESCRIPTION:
XS GIS Cut Line= 3
      2779600.24     10048253.48      2780117.62     10047885.41
      2781124.05     10047479.36
#Sta/Elev= 30
  4614.1 1586.22  4762.8 1583.08  4834.1 1578.42  4928.8 1575.15  4970.6 1574.49
  4979.3 1573.82  4985.4 1571.55  4997.2 1569.47  4999.9 1568.97  5003.2 1569.47
  5021.1 1573.96  5029.2 1575.04  5041.9 1575.33  5451.7 1573.78  5534.9 1574.15
  5595.0 1573.12  5618.2 1573.31  5642.3 1574.67  5720.1 1573.33  5789.1 1573.96
  5959.0 1573.18  6058.7 1574.09  6274.4 1578.29  6295.9 1580.17  6305.3 1582.69
  6310.7 1582.22  6317.5 1586.00  6322.8 1586.30  6328.3 1586.61  6334.3 1583.68
#Mann=4,-1,0
  4614.1    0.05       0  4997.2   0.035       0  5003.2    0.05       0
  6322.8     0.1       0
Bank Sta=4997.2,5003.2
Exp/Cntr=0.3,0.1

Type RM Length L Ch R = 1,6515,350,350,350
BEGIN DESCRIPTION:
UNT049 IN SNOGR 12.0
END DESCRIPTION:
XS GIS Cut Line= 3
      2779641.93     10048319.43      2780409.29     10048284.71
      2781241.80     10047778.26
#Sta/Elev= 30
  4364.4 1585.29  4581.2 1577.60  4611.2 1575.90  4781.4 1571.85  4861.4 1571.97
  4939.4 1570.34  4971.6 1569.40  4998.6 1566.15  5001.3 1565.65  5004.6 1566.15
  5011.6 1566.47  5031.6 1569.60  5040.1 1569.98  5138.3 1570.69  5162.1 1570.45
  5190.1 1571.65  5198.9 1570.08  5213.5 1569.82  5220.2 1571.69  5257.0 1570.93
  5284.2 1571.96  5315.9 1571.98  5365.7 1570.60  5394.6 1571.27  5706.5 1572.12
  5787.1 1573.54  5838.2 1572.78  5875.0 1575.54  5958.8 1578.04  6107.0 1582.94
#Mann=7,-1,0
  4364.4    0.05       0  4939.4     0.1       0  4998.6    0.07       0
  5004.6     0.1       0  5138.3    0.16       0  5315.9    0.05       0
  5958.8     0.1       0
Bank Sta=4998.6,5004.6
Exp/Cntr=0.3,0.1

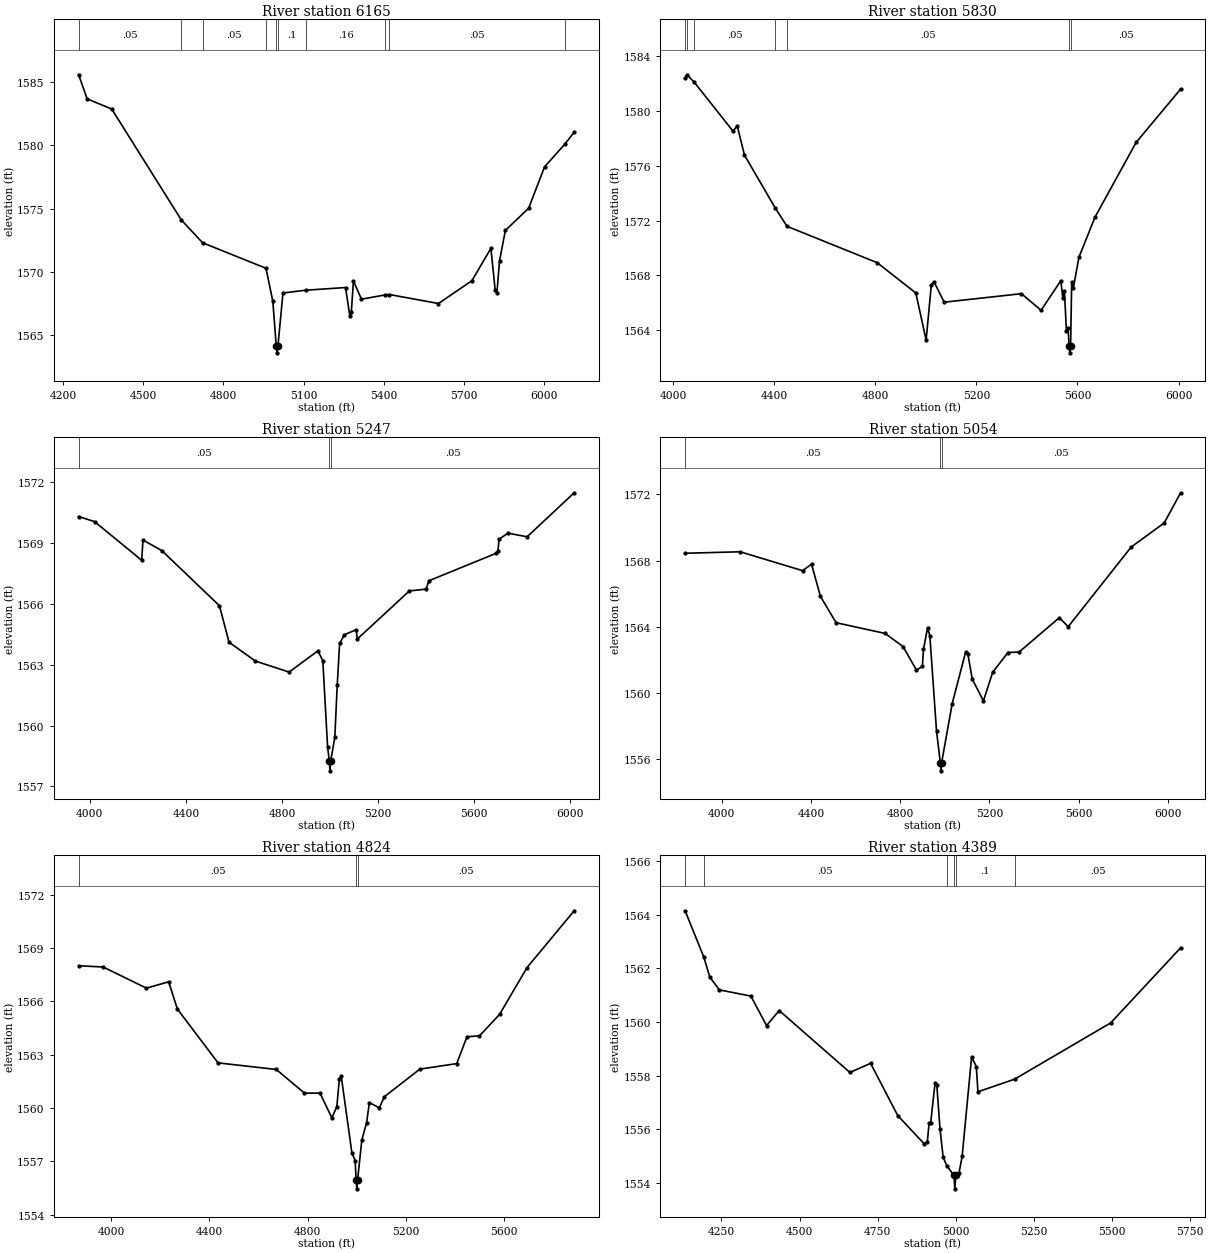
Type RM Length L Ch R = 1,6165,335,335,335
BEGIN DESCRIPTION:
UNT049 IN SNOGR 11.0
END DESCRIPTION:
XS GIS Cut Line= 3
      2779537.80     10048503.47      2780114.15     10048670.13
      2781211.35     10048065.97
#Sta/Elev= 30
  4258.8 1585.56  4290.7 1583.66  4382.5 1582.86  4642.7 1574.11  4722.2 1572.31
  4959.2 1570.30  4984.8 1567.69  4997.7 1564.13  5000.4 1563.63  5003.7 1564.13
  5022.7 1568.35  5107.8 1568.57  5256.6 1568.78  5272.6 1566.55  5278.3 1566.87
  5286.1 1569.29  5316.2 1567.86  5405.2 1568.20  5420.7 1568.23  5604.0 1567.52
  5729.0 1569.32  5800.0 1571.87  5816.1 1568.56  5822.6 1568.37  5832.2 1570.88
  5854.0 1573.28  5941.1 1575.04  6000.7 1578.30  6076.4 1580.09  6111.3 1581.03
#Mann=10,-1,0
  4258.8    0.05       0  4642.7    0.08       0  4722.2    0.05       0
  4959.2     0.1       0  4997.7    0.07       0  5003.7     0.1       0
  5107.8    0.16       0  5405.2     0.1       0  5420.7    0.05       0
  6076.4     0.1       0
Bank Sta=4997.7,5003.7
Exp/Cntr=0.3,0.1

Type RM Length L Ch R = 1,5830,583,583,583
BEGIN DESCRIPTION:
UNT049 IN SNOGR 10.0
END DESCRIPTION:
XS GIS Cut Line= 4
      2779579.43     10048569.44      2780124.56     10048826.38
      2780673.17     10048715.27      2781283.85     10048201.74
#Sta/Elev= 30
  4047.9 1582.39  4055.6 1582.62  4083.6 1582.09  4237.1 1578.52  4254.3 1578.89
  4282.7 1576.77  4404.3 1572.92  4450.9 1571.58  4807.6 1568.93  4960.6 1566.72
  5001.4 1563.29  5021.8 1567.29  5032.0 1567.55  5072.9 1566.05  5378.2 1566.67
  5456.2 1565.46  5534.3 1567.62  5542.0 1566.39  5548.6 1566.83  5556.3 1563.97
  5562.9 1564.17  5567.0 1562.86  5569.7 1562.36  5573.0 1562.86  5577.2 1567.52
  5583.7 1567.08  5605.8 1569.32  5669.5 1572.25  5832.1 1577.69  6008.2 1581.58
#Mann=7,-1,0
  4047.9    0.05       0  4055.6     0.1       0  4083.6    0.05       0
  4404.3    0.08       0  4450.9    0.05       0  5567.0    0.04       0
  5573.0    0.05       0
Bank Sta=5567,5573
Exp/Cntr=0.3,0.1

Type RM Length L Ch R = 1,5247,193,193,193
BEGIN DESCRIPTION:
Mapping XS 502c096d
END DESCRIPTION:
XS GIS Cut Line= 3
      2779902.36     10048909.71      2780839.84     10048906.24
      2781964.11     10048868.07
#Sta/Elev= 30
  3953.4 1570.31  4019.5 1570.06  4216.1 1568.15  4221.1 1569.15  4299.5 1568.63
  4539.5 1565.91  4579.5 1564.11  4689.5 1563.18  4829.5 1562.64  4949.5 1563.69
  4969.6 1563.20  4989.6 1558.95  4996.6 1558.27  4999.3 1557.77  5002.6 1558.27
  5019.6 1559.42  5029.6 1561.98  5039.6 1564.05  5059.6 1564.48  5108.4 1564.73
  5113.4 1564.27  5329.8 1566.64  5399.8 1566.73  5410.8 1567.14  5690.0 1568.49
  5698.3 1568.59  5703.3 1569.19  5740.0 1569.49  5820.0 1569.31  6015.8 1571.48
#Mann=3,-1,0
  3953.4    0.05       0  4996.6    0.04       0  5002.6    0.05       0
Bank Sta=4996.6,5002.6
Exp/Cntr=0.3,0.1

Type RM Length L Ch R = 1,5054,230,230,230
BEGIN DESCRIPTION:
Mapping XS 58e90356
END DESCRIPTION:
XS GIS Cut Line= 2
      2779902.03     10049083.08      2782122.08     10049011.46
#Sta/Elev= 30
  3835.6 1568.44  4082.2 1568.53  4362.3 1567.39  4402.3 1567.78  4442.3 1565.84
  4512.4 1564.25  4732.5 1563.60  4812.5 1562.81  4872.6 1561.39  4899.2 1561.61
  4904.2 1562.64  4922.6 1563.95  4932.6 1563.47  4962.6 1557.71  4979.6 1555.81
  4982.4 1555.31  4985.6 1555.81  5032.7 1559.36  5092.7 1562.46  5102.7 1562.38
  5122.7 1560.85  5172.7 1559.53  5214.4 1561.26  5282.8 1562.45  5332.8 1562.48
  5512.9 1564.55  5552.9 1564.01  5834.7 1568.81  5983.2 1570.27  6056.8 1572.09
#Mann=3,-1,0
  3835.6    0.05       0  4979.6    0.04       0  4985.6    0.05       0
Bank Sta=4979.6,4985.6
Exp/Cntr=0.3,0.1

Type RM Length L Ch R = 1,4824,435,435,435
BEGIN DESCRIPTION:
Mapping XS abee7c1f
END DESCRIPTION:
XS GIS Cut Line= 3
      2780103.74     10049138.88      2781079.42     10049236.10
      2782096.74     10049038.19
#Sta/Elev= 30
  3868.4 1568.00  3968.2 1567.93  4144.5 1566.74  4234.9 1567.10  4270.2 1565.57
  4435.9 1562.54  4672.9 1562.17  4787.7 1560.84  4851.0 1560.84  4898.9 1559.45
  4919.3 1560.08  4929.4 1561.61  4937.2 1561.79  4980.4 1557.50  4993.9 1557.05
  4997.8 1555.96  5000.5 1555.46  5003.8 1555.96  5021.1 1558.21  5040.5 1559.18
  5051.7 1560.31  5092.2 1560.01  5112.8 1560.64  5257.3 1562.19  5407.2 1562.50
  5449.0 1564.01  5499.9 1564.06  5581.4 1565.26  5693.5 1567.90  5885.3 1571.09
#Mann=3,-1,0
  3868.4    0.05       0  4997.8   0.035       0  5003.8    0.05       0
Bank Sta=4997.8,5003.8
Exp/Cntr=0.3,0.1

Type RM Length L Ch R = 1,4389,553,553,553
BEGIN DESCRIPTION:
Mapping XS dd9489b7
END DESCRIPTION:
XS GIS Cut Line= 3
      2780510.02     10049520.83      2781284.29     10049621.52
      2782079.47     10049499.98
#Sta/Elev= 30
  4134.0 1564.15  4193.3 1562.44  4213.1 1561.68  4243.4 1561.20  4344.2 1560.97
  4394.6 1559.87  4435.0 1560.43  4661.2 1558.12  4727.4 1558.46  4814.4 1556.51
  4898.8 1555.46  4908.9 1555.53  4914.4 1556.22  4919.4 1556.22  4933.7 1557.74
  4939.2 1557.65  4949.4 1556.02  4959.5 1554.96  4971.2 1554.64  4994.1 1554.28
  4996.9 1553.78  5000.1 1554.28  5010.1 1554.36  5020.2 1554.99  5050.5 1558.70
  5065.6 1558.34  5070.8 1557.40  5188.1 1557.87  5495.6 1559.97  5719.2 1562.77
#Mann=6,-1,0
  4134.0     0.1       0  4193.3    0.05       0  4971.2     0.1       0
  4994.1    0.07       0  5000.1     0.1       0  5188.1    0.05       0
Bank Sta=4994.1,5000.1
Exp/Cntr=0.3,0.1

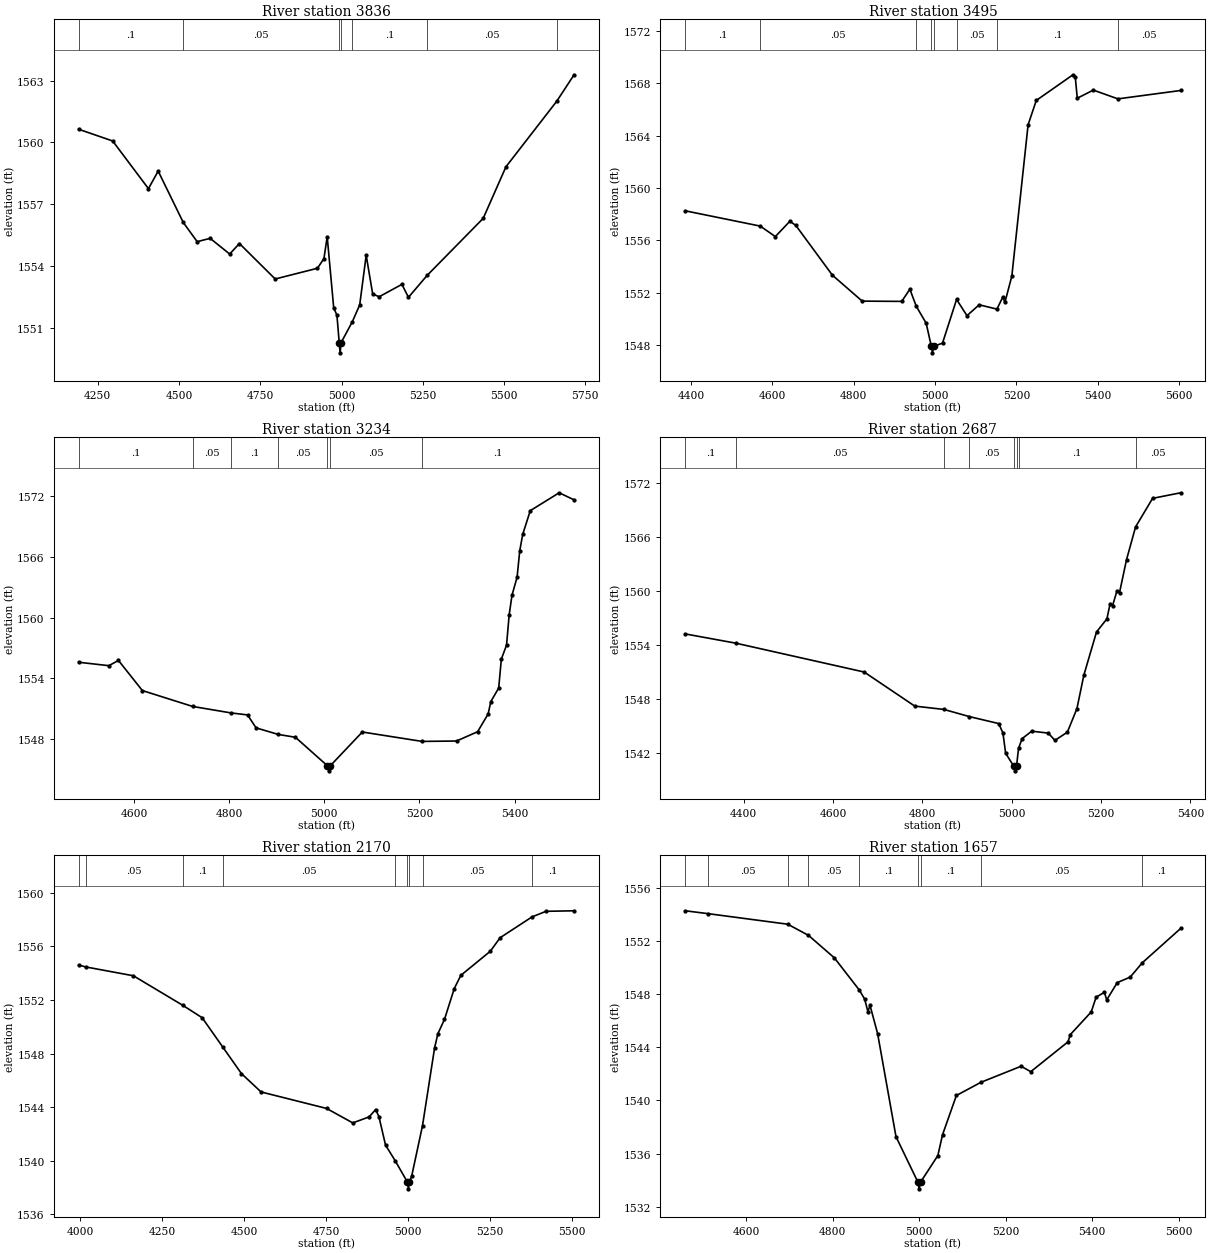
Type RM Length L Ch R = 1,3836,341,341,341
BEGIN DESCRIPTION:
UNT049 IN SNOGR 8.0
END DESCRIPTION:
XS GIS Cut Line= 2
      2780603.70     10050166.66      2782128.05     10050138.88
#Sta/Elev= 30
  4191.0 1560.64  4295.8 1560.07  4405.8 1557.76  4435.8 1558.61  4513.0 1556.12
  4555.8 1555.19  4595.8 1555.35  4655.8 1554.59  4685.8 1555.10  4795.9 1553.38
  4925.9 1553.90  4945.9 1554.37  4955.9 1555.43  4975.9 1551.99  4985.9 1551.62
  4992.9 1550.30  4995.6 1549.80  4998.9 1550.30  5033.0 1551.30  5055.9 1552.12
  5075.9 1554.53  5095.9 1552.65  5115.9 1552.52  5185.9 1553.12  5205.9 1552.49
  5263.2 1553.55  5436.0 1556.32  5506.0 1558.82  5662.4 1562.00  5715.6 1563.28
#Mann=7,-1,0
  4191.0     0.1       0  4513.0    0.05       0  4992.9   0.035       0
  4998.9    0.05       0  5033.0     0.1       0  5263.2    0.05       0
  5662.4     0.1       0
Bank Sta=4992.9,4998.9
Exp/Cntr=0.3,0.1

Type RM Length L Ch R = 1,3495,261,261,261
BEGIN DESCRIPTION:
UNT049 IN SNOGR 9.0
END DESCRIPTION:
XS GIS Cut Line= 2
      2780837.32     10050513.44      2782052.64     10050443.99
#Sta/Elev= 30
  4386.1 1558.25  4570.6 1557.08  4607.6 1556.28  4643.2 1557.45  4657.7 1557.14
  4747.8 1553.33  4821.0 1551.35  4918.1 1551.33  4938.1 1552.26  4953.8 1550.96
  4978.2 1549.66  4990.8 1547.90  4993.6 1547.40  4996.8 1547.90  5018.3 1548.14
  5052.9 1551.48  5078.4 1550.24  5108.4 1551.07  5152.0 1550.74  5166.6 1551.67
  5171.6 1551.25  5188.6 1553.26  5228.6 1564.82  5248.7 1566.68  5338.8 1568.64
  5344.4 1568.50  5349.4 1566.85  5388.9 1567.47  5449.2 1566.80  5603.4 1567.44
#Mann=8,-1,0
  4386.1     0.1       0  4570.6    0.05       0  4953.8     0.1       0
  4990.8    0.07       0  4996.8     0.1       0  5052.9    0.05       0
  5152.0     0.1       0  5449.2    0.05       0
Bank Sta=4990.8,4996.8
Exp/Cntr=0.3,0.1

Type RM Length L Ch R = 1,3234,547,547,547
BEGIN DESCRIPTION:
UNT049 IN SNOGR 7.0
END DESCRIPTION:
XS GIS Cut Line= 3
      2780975.23     10050788.19      2781666.23     10050715.27
      2781974.37     10050556.00
#Sta/Elev= 30
  4483.5 1555.60  4547.1 1555.26  4567.2 1555.78  4617.5 1552.80  4723.1 1551.23
  4803.6 1550.59  4838.7 1550.39  4856.6 1549.11  4903.3 1548.46  4939.3 1548.18
  5006.6 1545.36  5009.4 1544.86  5012.6 1545.36  5080.0 1548.70  5205.7 1547.77
  5278.1 1547.81  5322.4 1548.73  5344.5 1550.48  5350.2 1551.71  5366.7 1553.05
  5372.3 1555.91  5383.2 1557.29  5388.8 1560.30  5394.7 1562.23  5405.4 1564.01
  5411.0 1566.63  5417.2 1568.24  5433.1 1570.59  5493.9 1572.36  5525.2 1571.66
#Mann=7,-1,0
  4483.5     0.1       0  4723.1    0.05       0  4803.6     0.1       0
  4903.3    0.05       0  5006.6   0.035       0  5012.6    0.05       0
  5205.7     0.1       0
Bank Sta=5006.6,5012.6
Exp/Cntr=0.3,0.1

Type RM Length L Ch R = 1,2687,517,517,517
BEGIN DESCRIPTION:
UNT049 IN SNOGR 6.0
END DESCRIPTION:
XS GIS Cut Line= 3
      2781239.11     10051135.41      2781909.29     10050972.21
      2782124.02     10050612.02
#Sta/Elev= 30
  4268.9 1555.21  4382.3 1554.18  4669.6 1550.97  4782.8 1547.18  4848.0 1546.81
  4905.3 1546.01  4970.6 1545.24  4980.2 1544.19  4986.2 1541.94  5004.6 1540.48
  5007.3 1539.98  5010.6 1540.48  5015.1 1542.48  5023.2 1543.57  5044.6 1544.39
  5081.6 1544.18  5096.6 1543.37  5124.4 1544.28  5145.8 1546.90  5161.4 1550.64
  5189.7 1555.43  5213.0 1556.89  5219.8 1558.51  5225.6 1558.35  5235.4 1559.99
  5241.2 1559.81  5256.8 1563.46  5277.1 1567.11  5315.2 1570.29  5378.0 1570.91
#Mann=8,-1,0
  4268.9     0.1       0  4382.3    0.05       0  4848.0     0.1       0
  4905.3    0.05       0  5004.6   0.035       0  5010.6    0.05       0
  5015.1     0.1       0  5277.1    0.05       0
Bank Sta=5004.6,5010.6
Exp/Cntr=0.3,0.1

Type RM Length L Ch R = 1,2170,513,513,513
BEGIN DESCRIPTION:
UNT049 IN SNOGR 5.0
END DESCRIPTION:
XS GIS Cut Line= 2
      2781291.27     10051232.63      2782804.26     10051236.10
#Sta/Elev= 30
  3994.6 1554.61  4016.3 1554.47  4161.8 1553.81  4313.0 1551.60  4371.8 1550.68
  4434.5 1548.50  4491.8 1546.51  4551.8 1545.14  4751.8 1543.91  4831.8 1542.83
  4881.8 1543.28  4901.8 1543.83  4911.8 1543.28  4931.8 1541.18  4961.2 1540.01
  4998.8 1538.41  5001.6 1537.91  5004.8 1538.41  5011.8 1538.87  5044.8 1542.63
  5081.8 1548.45  5091.8 1549.49  5111.8 1550.55  5141.8 1552.86  5161.8 1553.84
  5251.8 1555.64  5281.8 1556.65  5379.0 1558.20  5421.8 1558.62  5507.6 1558.66
#Mann=9,-1,0
  3994.6     0.1       0  4016.3    0.05       0  4313.0     0.1       0
  4434.5    0.05       0  4961.2     0.1       0  4998.8    0.07       0
  5004.8     0.1       0  5044.8    0.05       0  5379.0     0.1       0
Bank Sta=4998.8,5004.8
Exp/Cntr=0.3,0.1

Type RM Length L Ch R = 1,1657,448,448,448
BEGIN DESCRIPTION:
UNT049 IN SNOGR 4.0
END DESCRIPTION:
XS GIS Cut Line= 3
      2781353.70     10051465.27      2781805.12     10051458.32
      2782450.99     10051711.81
#Sta/Elev= 30
  4459.3 1554.26  4513.1 1554.04  4696.3 1553.25  4744.3 1552.41  4804.1 1550.72
  4862.0 1548.29  4874.1 1547.62  4881.6 1546.68  4886.6 1547.14  4904.1 1545.02
  4946.6 1537.27  4997.3 1533.85  5000.1 1533.35  5003.3 1533.85  5043.3 1535.85
  5054.1 1537.41  5086.2 1540.37  5142.9 1541.36  5235.8 1542.57  5258.1 1542.16
  5344.1 1544.40  5349.6 1544.95  5397.8 1546.65  5409.2 1547.76  5428.3 1548.13
  5433.7 1547.56  5458.1 1548.86  5487.9 1549.27  5516.3 1550.36  5604.6 1552.93
#Mann=9,-1,0
  4459.3     0.1       0  4513.1    0.05       0  4696.3     0.1       0
  4744.3    0.05       0  4862.0     0.1       0  4997.3    0.07       0
  5003.3     0.1       0  5142.9    0.05       0  5516.3     0.1       0
Bank Sta=4997.3,5003.3
Exp/Cntr=0.3,0.1

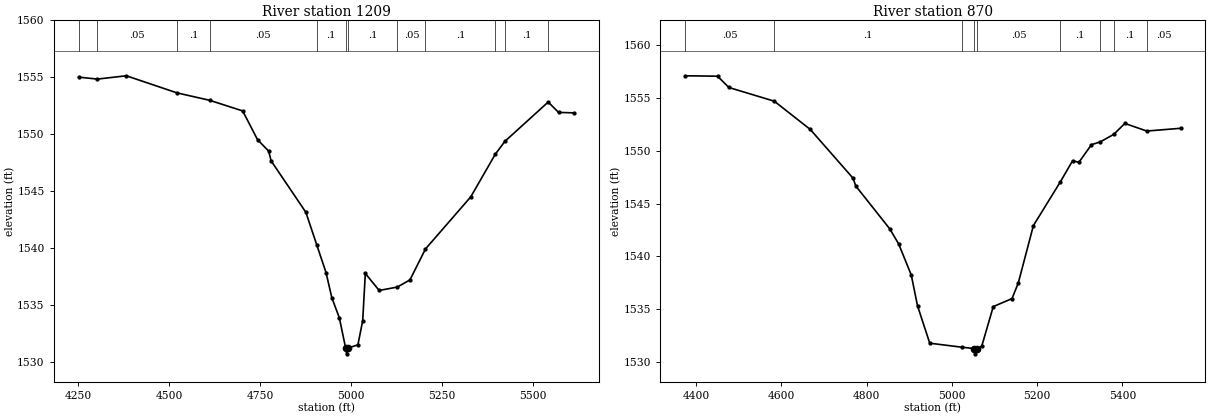
Type RM Length L Ch R = 1,1209,339,339,339
BEGIN DESCRIPTION:
UNT049 IN SNOGR 3.0
END DESCRIPTION:
XS GIS Cut Line= 2
      2781187.07     10052055.54      2782520.35     10051781.25
#Sta/Elev= 30
  4251.9 1555.01  4303.5 1554.84  4382.9 1555.13  4521.7 1553.63  4612.3 1552.97
  4702.5 1552.04  4743.4 1549.51  4774.0 1548.51  4780.5 1547.66  4876.1 1543.13
  4906.2 1540.25  4931.5 1537.83  4947.6 1535.60  4968.0 1533.86  4985.4 1531.19
  4988.2 1530.69  4991.4 1531.19  5019.0 1531.48  5032.2 1533.60  5039.4 1537.76
  5077.4 1536.26  5127.3 1536.56  5162.0 1537.19  5204.7 1539.91  5329.1 1544.49
  5396.3 1548.23  5422.9 1549.37  5541.7 1552.82  5570.3 1551.91  5613.1 1551.87
#Mann=12,-1,0
  4251.9     0.1       0  4303.5    0.05       0  4521.7     0.1       0
  4612.3    0.05       0  4906.2     0.1       0  4985.4    0.07       0
  4991.4     0.1       0  5127.3    0.05       0  5204.7     0.1       0
  5396.3    0.05       0  5422.9     0.1       0  5541.7    0.05       0
Bank Sta=4985.4,4991.4
Exp/Cntr=0.3,0.1

Type RM Length L Ch R = 1,870,0,0,0
BEGIN DESCRIPTION:
UNT049 IN SNOGR 2.0
END DESCRIPTION:
XS GIS Cut Line= 3
      2781548.18     10052371.51      2781992.62     10052225.68
      2782554.27     10051816.58
#Sta/Elev= 30
  4373.9 1557.12  4450.0 1557.08  4476.6 1556.01  4583.1 1554.71  4667.6 1552.03
  4768.3 1547.39  4774.1 1546.68  4854.3 1542.59  4875.1 1541.16  4904.5 1538.23
  4919.2 1535.30  4947.9 1531.76  5023.0 1531.38  5052.1 1531.25  5054.9 1530.75
  5058.1 1531.25  5069.8 1531.47  5096.9 1535.23  5140.9 1535.99  5155.6 1537.47
  5191.1 1542.92  5253.7 1547.02  5283.1 1549.07  5297.8 1548.91  5327.1 1550.58
  5348.4 1550.86  5379.7 1551.57  5405.6 1552.60  5457.1 1551.88  5536.5 1552.14
#Mann=9,-1,0
  4373.9    0.05       0  4583.1     0.1       0  5023.0    0.05       0
  5052.1    0.07       0  5058.1    0.05       0  5253.7     0.1       0
  5348.4    0.05       0  5379.7     0.1       0  5457.1    0.05       0
Bank Sta=5052.1,5058.1
Exp/Cntr=0.3,0.1

Chan Stop Cuts=-1