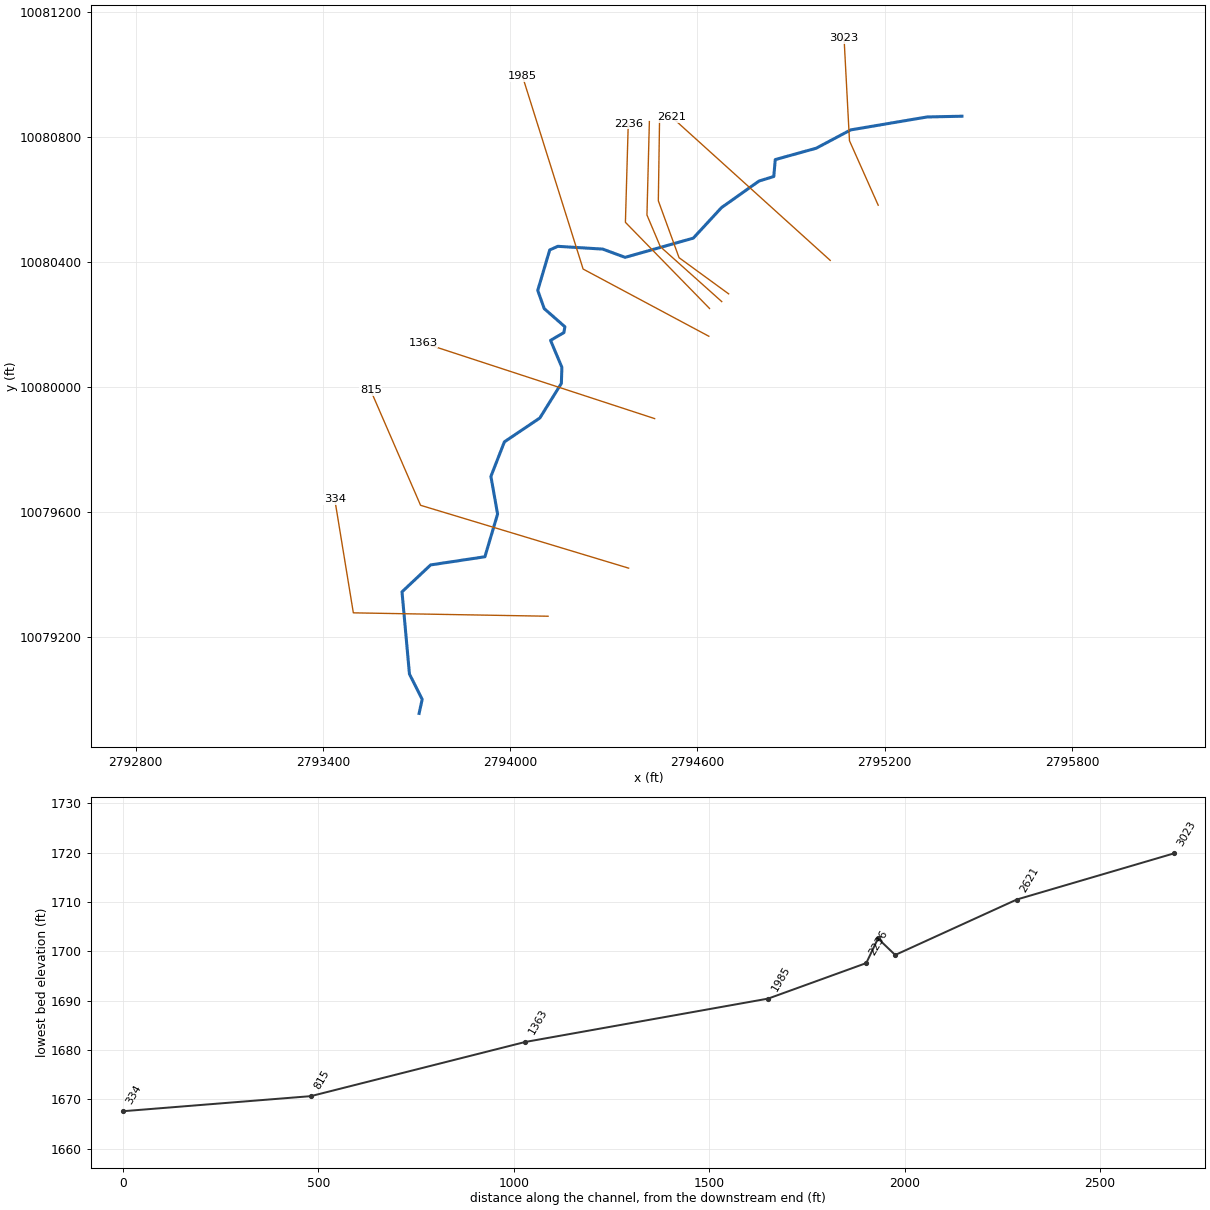
--- UNT050 IN NNOGR.prj (project) ---

Proj Title=UNT050 IN NNOGR Base Level Engineering
Current Plan=p01
Default Exp/Contr=0.3,0.1
English Units
Geom File=g01
Flow File=f01
Plan File=p01
Y Axis Title=Elevation
X Axis Title(PF)=Main Channel Distance
X Axis Title(XS)=Station
BEGIN DESCRIPTION:
UNT050 IN NNOGR
END DESCRIPTION:
DSS Export Rating Curves= 0
DSS Export Rating Curve Sorted= 0
DSS Export Volume Flow Curves= 0
DXF OffsetX= 0
DXF OffsetY= 0
DXF ScaleX= 1
DXF ScaleY= 10

--- UNT050 IN NNOGR.p01 (plan) ---

Plan Title=Multiple Run
Short Identifier=Multiple
Geom File=g01
Flow File=f01
Subcritical Flow
K Sum by GR= 0
Std Step Tol= 0.01
Critical Tol= 0.01
Num of Std Step Trials= 20
Max Error Tol= 0.3
Flow Tol Ratio= 0.001
Split Flow NTrial= 30
Split Flow Tol= 0.02
Split Flow Ratio= 0.02
Log Output Level= 0
Friction Slope Method= 1
Unsteady Friction Slope Method= 2
Unsteady Bridges Friction Slope Method= 1
Parabolic Critical Depth
Global Vel Dist=  1 , 1 , 1
Global Log Level= 0
CheckData=True
Encroach Param= -1, 0, 0, 0
BEGIN DESCRIPTION:
Multiple Run
END DESCRIPTION:

--- UNT050 IN NNOGR.f01 (steady flow) ---

Flow Title=Multiple
Program Version=4.10
Number of Profiles= 7
Profile Names=10-year,25-year,50-year,1pct_min,100-year,1pct_plu,500-year
River Rch & RM=UNT050 IN NNOGR,Reach-1         ,3023
     560     798    1003     925    1251    1692    1952
Boundary for River Rch & Prof#=UNT050 IN NNOGR,Reach-1         , 1
Up Type= 0
Dn Type= 3
Dn Slope=0.013
Boundary for River Rch & Prof#=UNT050 IN NNOGR,Reach-1         , 2
Up Type= 0
Dn Type= 3
Dn Slope=0.013
Boundary for River Rch & Prof#=UNT050 IN NNOGR,Reach-1         , 3
Up Type= 0
Dn Type= 3
Dn Slope=0.013
Boundary for River Rch & Prof#=UNT050 IN NNOGR,Reach-1         , 4
Up Type= 0
Dn Type= 3
Dn Slope=0.013
Boundary for River Rch & Prof#=UNT050 IN NNOGR,Reach-1         , 5
Up Type= 0
Dn Type= 3
Dn Slope=0.013
Boundary for River Rch & Prof#=UNT050 IN NNOGR,Reach-1         , 6
Up Type= 0
Dn Type= 3
Dn Slope=0.013
Boundary for River Rch & Prof#=UNT050 IN NNOGR,Reach-1         , 7
Up Type= 0
Dn Type= 3
Dn Slope=0.013
DSS Import GetInterval= 0
DSS Import GetPeak= 0
DSS Import FillOption= 0

--- UNT050 IN NNOGR.g01 (geometry) ---

Geom Title=Existing Conditions

River Reach=UNT050 IN NNOGR,Reach-1
Reach XY= 30
      2795447.77     10080867.07      2795336.08     10080864.69
      2795091.36     10080823.28      2794980.83     10080764.55
      2794849.58     10080728.10      2794844.89     10080673.93
      2794797.50     10080659.35      2794677.39     10080574.27
      2794587.06     10080476.45      2794368.53     10080414.91
      2794296.79     10080441.33      2794152.88     10080450.22
      2794127.02     10080438.61      2794088.54     10080309.01
      2794109.39     10080250.55      2794175.60     10080192.47
      2794172.33     10080173.71      2794129.62     10080148.93
      2794165.92     10080062.49      2794164.26     10080010.95
      2794095.30     10079900.15      2793981.73     10079823.69
      2793938.50     10079713.01      2793959.93     10079592.35
      2793919.28     10079455.57      2793745.48     10079429.41
      2793653.66     10079343.15      2793677.53     10079079.70
      2793718.30     10078998.64      2793708.47     10078953.73

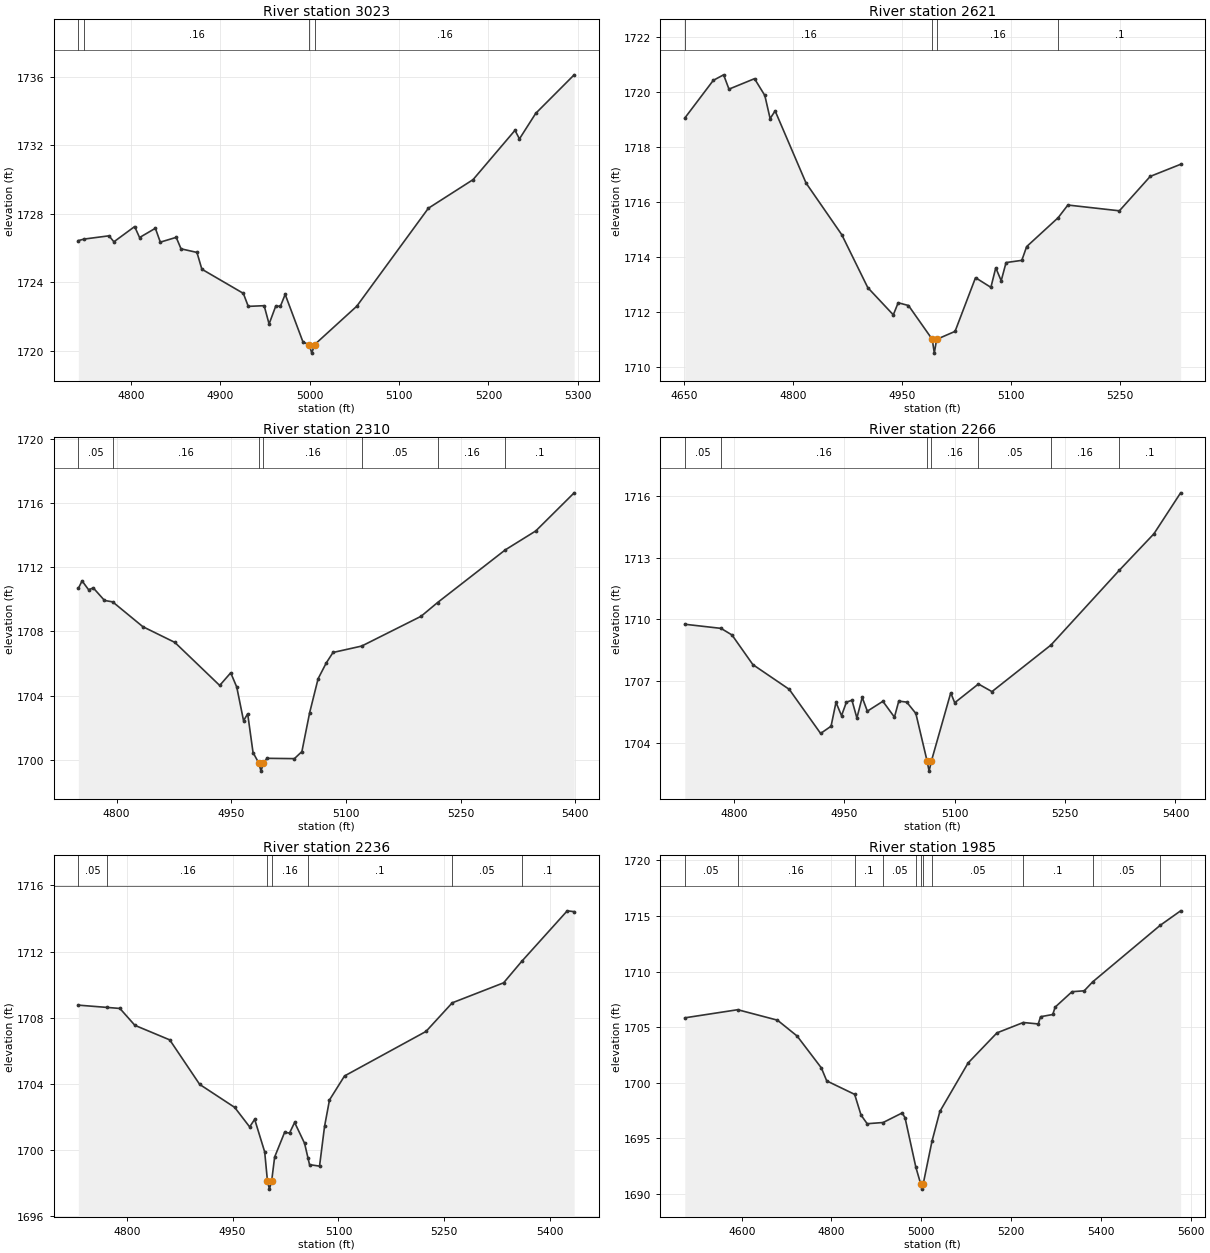
Type RM Length L Ch R = 1,3023,402,402,402
BEGIN DESCRIPTION:
KUHLMAN CREEK 35.0
END DESCRIPTION:
XS GIS Cut Line= 3
      2795179.43     10080581.95      2795087.42     10080788.53
      2795070.06     10081116.63
#Sta/Elev= 30
  4741.2 1726.44  4747.7 1726.53  4775.5 1726.72  4781.0 1726.37  4804.2 1727.26
  4809.7 1726.62  4827.4 1727.16  4832.9 1726.35  4850.7 1726.63  4856.1 1725.96
  4873.9 1725.75  4879.4 1724.77  4925.8 1723.36  4931.3 1722.60  4949.1 1722.64
  4954.6 1721.57  4962.0 1722.61  4967.3 1722.61  4972.6 1723.30  4992.6 1720.51
  4999.6 1720.37  5002.3 1719.87  5005.6 1720.37  5052.7 1722.61  5132.8 1728.33
  5182.8 1730.00  5229.7 1732.88  5234.7 1732.38  5252.9 1733.87  5295.9 1736.12
#Mann=4,-1,0
  4741.2     0.1       0  4747.7    0.16       0  4999.6    0.07       0
  5005.6    0.16       0
Bank Sta=4999.6,5005.6
Exp/Cntr=0.3,0.1

Type RM Length L Ch R = 1,2621,311,311,311
BEGIN DESCRIPTION:
KUHLMAN CREEK 34.0
END DESCRIPTION:
XS GIS Cut Line= 2
      2795025.68     10080405.16      2794518.75     10080863.48
#Sta/Elev= 30
  4650.8 1719.06  4690.1 1720.43  4704.3 1720.63  4711.7 1720.11  4746.9 1720.49
  4761.1 1719.88  4768.4 1719.04  4775.3 1719.32  4817.9 1716.70  4867.2 1714.82
  4903.0 1712.90  4938.2 1711.91  4944.9 1712.35  4959.1 1712.25  4991.9 1711.02
  4994.7 1710.52  4997.9 1711.02  5023.3 1711.31  5051.5 1713.26  5072.7 1712.91
  5079.4 1713.62  5086.9 1713.15  5093.6 1713.81  5115.3 1713.89  5122.0 1714.39
  5165.4 1715.44  5178.8 1715.90  5249.8 1715.69  5292.3 1716.94  5334.2 1717.38
#Mann=4,-1,0
  4650.8    0.16       0  4991.9    0.07       0  4997.9    0.16       0
  5165.4     0.1       0
Bank Sta=4991.9,4997.9
Exp/Cntr=0.3,0.1

Type RM Length L Ch R = 1,2310,44,44,44
BEGIN DESCRIPTION:
Mapping XS 9147b17a
END DESCRIPTION:
XS GIS Cut Line= 4
      2794700.24     10080297.91      2794541.36     10080413.82
      2794474.95     10080596.11      2794478.86     10080853.90
#Sta/Elev= 30
  4749.9 1710.69  4754.8 1711.16  4763.3 1710.61  4769.5 1710.72  4784.1 1709.94
  4794.8 1709.85  4834.3 1708.30  4876.1 1707.32  4934.8 1704.63  4949.2 1705.42
  4957.1 1704.53  4966.0 1702.43  4971.4 1702.86  4978.4 1700.44  4986.0 1699.78
  4988.8 1699.28  4992.0 1699.78  4996.6 1700.08  5032.5 1700.06  5042.3 1700.50
  5052.4 1702.92  5063.5 1705.05  5074.2 1706.04  5083.0 1706.69  5120.5 1707.09
  5198.2 1708.95  5219.8 1709.81  5308.4 1713.10  5348.2 1714.28  5398.4 1716.66
#Mann=7,-1,0
  4749.9    0.05       0  4794.8    0.16       0  4986.0    0.07       0
  4992.0    0.16       0  5120.5    0.05       0  5219.8    0.16       0
  5308.4     0.1       0
Bank Sta=4986,4992
Exp/Cntr=0.3,0.1

Type RM Length L Ch R = 1,2266,30,30,30
BEGIN DESCRIPTION:
Mapping XS dc970bfb
END DESCRIPTION:
XS GIS Cut Line= 4
      2794678.10     10080273.17      2794481.46     10080448.98
      2794438.49     10080550.54      2794446.27     10080849.99
#Sta/Elev= 30
  4733.4 1709.76  4782.6 1709.56  4797.5 1709.24  4825.9 1707.80  4875.3 1706.60
  4917.9 1704.46  4932.1 1704.81  4938.8 1705.97  4946.3 1705.32  4953.0 1705.98
  4960.5 1706.07  4967.2 1705.21  4974.4 1706.21  4981.4 1705.54  5002.5 1706.02
  5018.2 1705.25  5024.1 1706.03  5034.9 1705.98  5047.3 1705.43  5062.5 1703.13
  5065.3 1702.63  5068.5 1703.13  5094.7 1706.43  5100.1 1705.95  5132.3 1706.86
  5150.7 1706.49  5230.8 1708.75  5323.7 1712.38  5370.7 1714.15  5407.0 1716.14
#Mann=7,-1,0
  4733.4    0.05       0  4782.6    0.16       0  5062.5    0.07       0
  5068.5    0.16       0  5132.3    0.05       0  5230.8    0.16       0
  5323.7     0.1       0
Bank Sta=5062.5,5068.5
Exp/Cntr=0.3,0.1

Type RM Length L Ch R = 1,2236,251,251,251
BEGIN DESCRIPTION:
Mapping XS 78d0e7e0
END DESCRIPTION:
XS GIS Cut Line= 3
      2794639.02     10080251.05      2794369.48     10080527.10
      2794378.60     10080843.55
#Sta/Elev= 30
  4731.5 1708.76  4772.8 1708.62  4790.4 1708.56  4811.6 1707.54  4861.0 1706.66
  4903.4 1703.97  4953.0 1702.58  4974.2 1701.40  4981.3 1701.86  4995.5 1699.89
  4999.4 1698.14  5002.2 1697.64  5005.4 1698.14  5009.6 1699.58  5023.7 1701.07
  5030.7 1701.03  5037.9 1701.67  5052.0 1700.41  5056.9 1699.51  5059.0 1699.12
  5073.2 1699.03  5080.3 1701.43  5087.3 1703.03  5108.6 1704.48  5224.0 1707.17
  5261.2 1708.90  5334.0 1710.11  5359.7 1711.41  5424.1 1714.46  5433.9 1714.41
#Mann=7,-1,0
  4731.5    0.05       0  4772.8    0.16       0  4999.4    0.07       0
  5005.4    0.16       0  5056.9     0.1       0  5261.2    0.05       0
  5359.7     0.1       0
Bank Sta=4999.4,5005.4
Exp/Cntr=0.3,0.1

Type RM Length L Ch R = 1,1985,622,622,622
BEGIN DESCRIPTION:
KUHLMAN CREEK 33.0
END DESCRIPTION:
XS GIS Cut Line= 3
      2794636.79     10080162.11      2794233.99     10080377.40
      2794039.56     10080995.42
#Sta/Elev= 30
  4473.2 1705.84  4591.1 1706.57  4679.6 1705.63  4723.5 1704.20  4777.4 1701.34
  4789.4 1700.17  4851.6 1698.96  4865.8 1697.10  4879.5 1696.32  4915.1 1696.43
  4957.5 1697.29  4963.9 1696.85  4988.0 1692.40  4998.5 1690.94  5001.3 1690.44
  5004.5 1690.94  5023.8 1694.73  5041.4 1697.42  5104.3 1701.78  5168.7 1704.49
  5227.3 1705.42  5260.6 1705.29  5265.8 1705.94  5293.0 1706.14  5298.2 1706.80
  5335.9 1708.19  5363.0 1708.27  5381.8 1709.07  5532.4 1714.16  5577.8 1715.46
#Mann=11,-1,0
  4473.2    0.05       0  4591.1    0.16       0  4851.6     0.1       0
  4915.1    0.05       0  4988.0     0.1       0  4998.5    0.07       0
  5004.5     0.1       0  5023.8    0.05       0  5227.3     0.1       0
  5381.8    0.05       0  5532.4     0.1       0
Bank Sta=4998.5,5004.5
Exp/Cntr=0.3,0.1

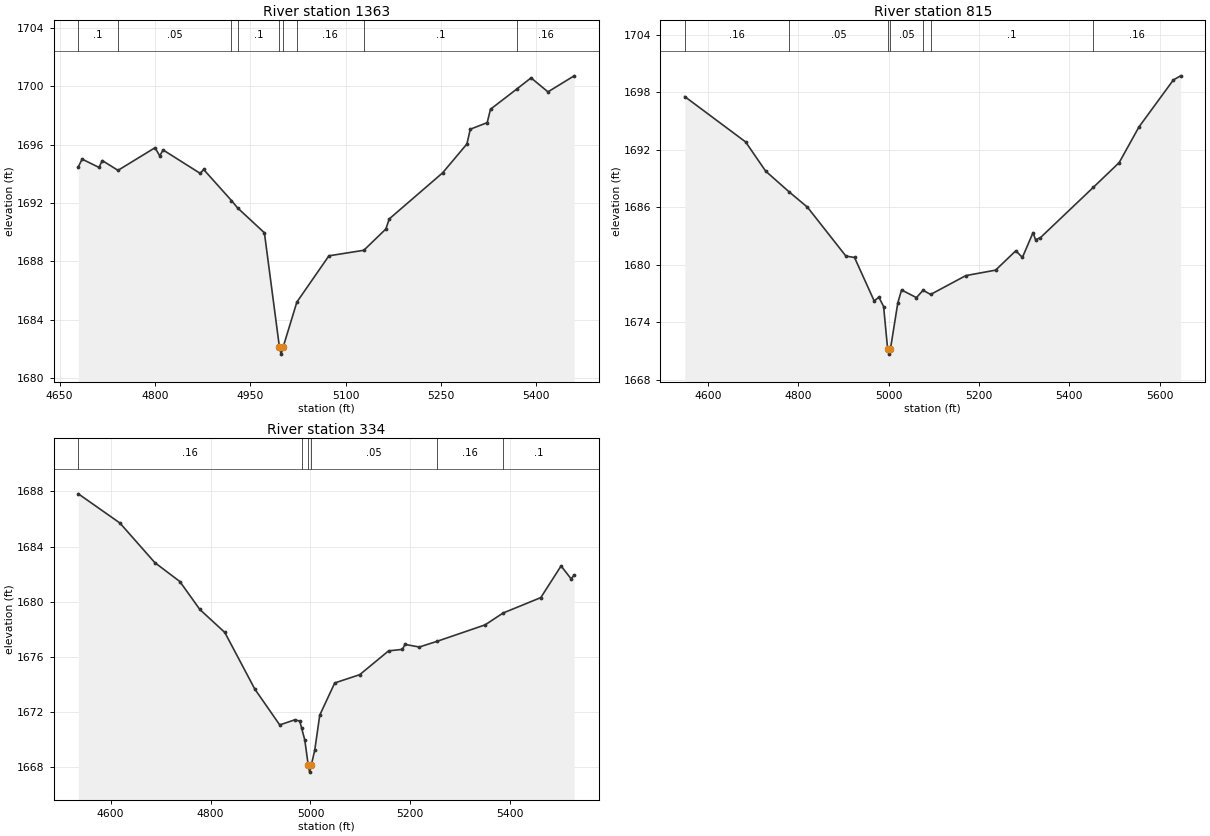
Type RM Length L Ch R = 1,1363,548,548,548
BEGIN DESCRIPTION:
KUHLMAN CREEK 31.0
END DESCRIPTION:
XS GIS Cut Line= 2
      2794463.13     10079898.24      2793721.78     10080140.74
#Sta/Elev= 30
  4679.5 1694.48  4685.4 1695.01  4712.0 1694.44  4717.2 1694.91  4741.9 1694.24
  4800.1 1695.79  4807.6 1695.23  4812.8 1695.64  4871.3 1694.03  4876.6 1694.30
  4920.4 1692.17  4929.9 1691.67  4972.2 1689.96  4995.8 1682.14  4998.5 1681.64
  5001.8 1682.14  5023.3 1685.21  5073.7 1688.38  5128.6 1688.76  5163.3 1690.22
  5168.6 1690.91  5252.6 1694.07  5290.8 1696.05  5296.1 1697.06  5322.7 1697.51
  5327.9 1698.43  5369.1 1699.81  5391.7 1700.58  5418.3 1699.62  5459.5 1700.72
#Mann=9,-1,0
  4679.5     0.1       0  4741.9    0.05       0  4920.4    0.16       0
  4929.9     0.1       0  4995.8    0.07       0  5001.8     0.1       0
  5023.3    0.16       0  5128.6     0.1       0  5369.1    0.16       0
Bank Sta=4995.8,5001.8
Exp/Cntr=0.3,0.1

Type RM Length L Ch R = 1,815,481,481,481
BEGIN DESCRIPTION:
KUHLMAN CREEK 30.0
END DESCRIPTION:
XS GIS Cut Line= 3
      2794379.80     10079419.07      2793713.16     10079620.45
      2793553.44     10079988.50
#Sta/Elev= 30
  4548.8 1697.56  4683.4 1692.83  4727.8 1689.78  4779.6 1687.62  4820.4 1686.01
  4905.4 1680.91  4924.5 1680.76  4968.0 1676.23  4978.5 1676.61  4988.9 1675.64
  4997.9 1671.17  5000.6 1670.67  5003.9 1671.17  5020.3 1676.01  5028.6 1677.37
  5061.6 1676.57  5076.3 1677.34  5092.9 1676.90  5170.9 1678.87  5236.8 1679.44
  5281.5 1681.46  5296.2 1680.77  5319.7 1683.36  5325.2 1682.62  5336.0 1682.83
  5452.8 1688.07  5510.4 1690.67  5554.0 1694.38  5630.3 1699.30  5646.4 1699.73
#Mann=7,-1,0
  4548.8    0.16       0  4779.6    0.05       0  4997.9    0.04       0
  5003.9    0.05       0  5076.3    0.16       0  5092.9     0.1       0
  5452.8    0.16       0
Bank Sta=4997.9,5003.9
Exp/Cntr=0.3,0.1

Type RM Length L Ch R = 1,334,0,0,0
BEGIN DESCRIPTION:
KUHLMAN CREEK 30.1
END DESCRIPTION:
XS GIS Cut Line= 3
      2794121.65     10079265.00      2793497.76     10079275.85
      2793438.21     10079639.62
#Sta/Elev= 30
  4535.3 1687.83  4618.5 1685.71  4688.5 1682.83  4738.5 1681.46  4778.5 1679.43
  4828.5 1677.76  4888.5 1673.65  4938.5 1671.04  4968.6 1671.41  4978.6 1671.32
  4982.3 1670.81  4988.6 1669.95  4995.6 1668.11  4998.3 1667.61  5001.6 1668.11
  5008.6 1669.21  5018.6 1671.75  5048.6 1674.09  5098.6 1674.69  5156.4 1676.42
  5184.2 1676.53  5189.2 1676.89  5217.9 1676.70  5253.1 1677.11  5349.7 1678.31
  5385.6 1679.17  5461.1 1680.29  5501.7 1682.59  5521.9 1681.65  5527.9 1681.93
#Mann=6,-1,0
  4535.3    0.16       0  4982.3    0.05       0  4995.6    0.04       0
  5001.6    0.05       0  5253.1    0.16       0  5385.6     0.1       0
Bank Sta=4995.6,5001.6
Exp/Cntr=0.3,0.1

Chan Stop Cuts=-1