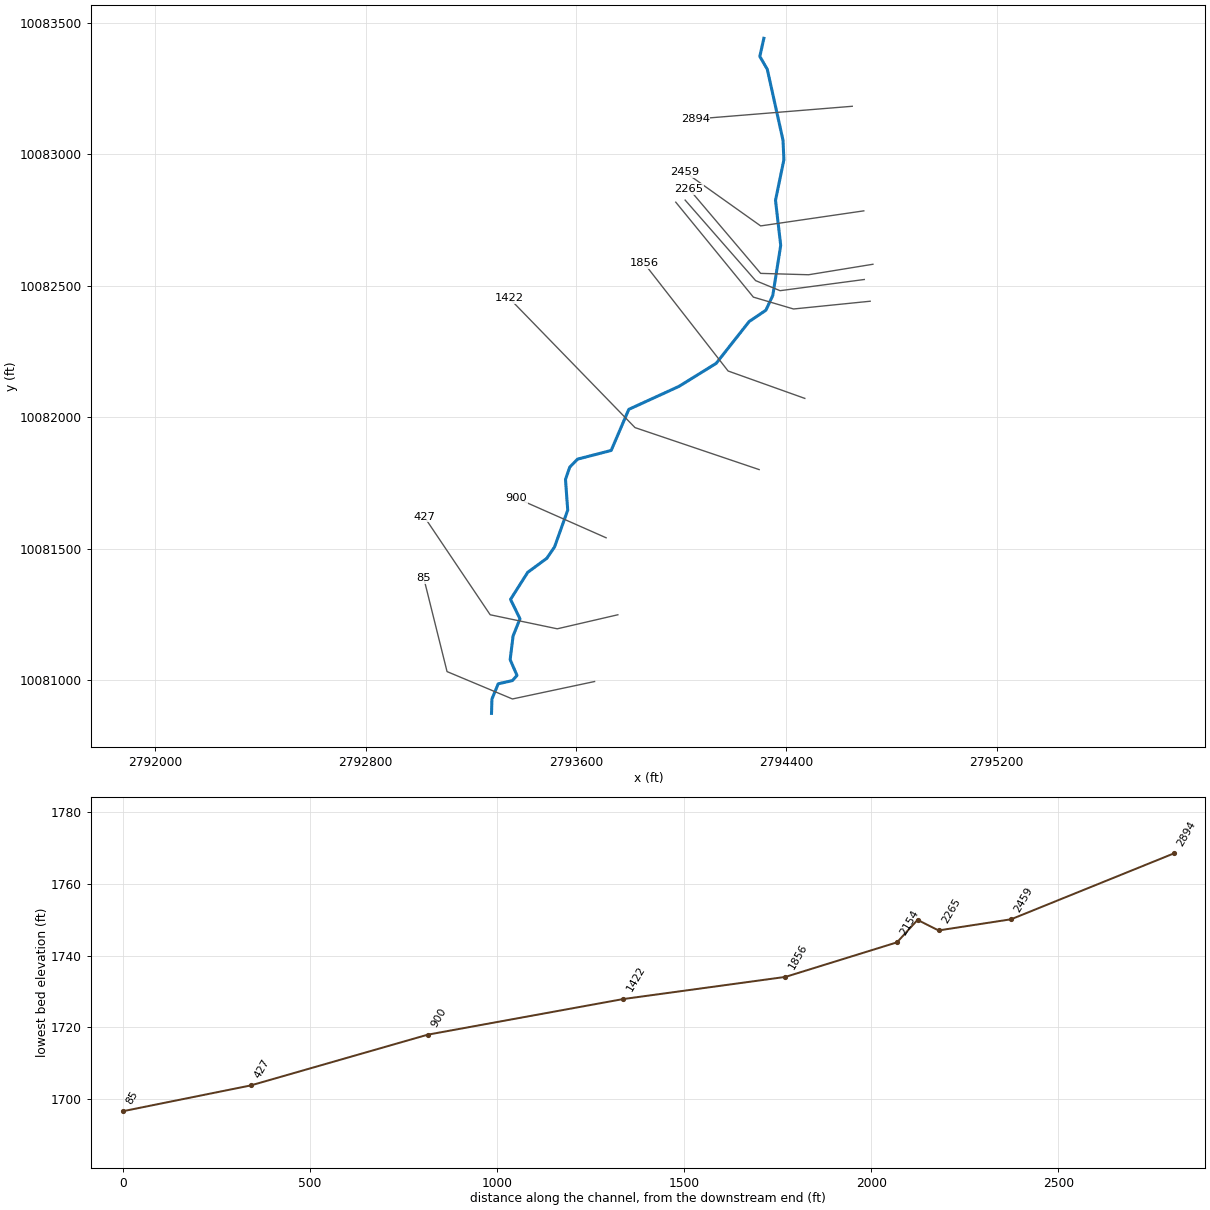
--- UNT051 IN NNOGR.prj (project) ---

Proj Title=UNT051 IN NNOGR Base Level Engineering
Current Plan=p01
Default Exp/Contr=0.3,0.1
English Units
Geom File=g01
Flow File=f01
Plan File=p01
Y Axis Title=Elevation
X Axis Title(PF)=Main Channel Distance
X Axis Title(XS)=Station
BEGIN DESCRIPTION:
UNT051 IN NNOGR
END DESCRIPTION:
DSS File=dss
DSS Export Rating Curves= 0
DSS Export Rating Curve Sorted= 0
DSS Export Volume Flow Curves= 0
DXF OffsetX= 0
DXF OffsetY= 0
DXF ScaleX= 1
DXF ScaleY= 10

--- UNT051 IN NNOGR.p01 (plan) ---

Plan Title=Multiple Run
Program Version=4.10
Short Identifier=Multiple Run
Geom File=g01
Flow File=f01
Subcritical Flow
K Sum by GR= 0
Std Step Tol= 0.01
Critical Tol= 0.01
Num of Std Step Trials= 20
Max Error Tol= 0.3
Flow Tol Ratio= 0.001
Split Flow NTrial= 30
Split Flow Tol= 0.02
Split Flow Ratio= 0.02
Log Output Level= 0
Friction Slope Method= 1
Unsteady Friction Slope Method= 2
Unsteady Bridges Friction Slope Method= 1
Parabolic Critical Depth
Global Vel Dist= 1 , 1 , 1
Global Log Level= 0
CheckData=True
Encroach Param=-1 ,0,0, 0
BEGIN DESCRIPTION:
Multiple Run
END DESCRIPTION:
Computation Interval=1HOUR
Output Interval=1HOUR
Run HTab= 0
Run UNet= 0
Run PostProcess= 0
Run WQNet= 0
UNET Theta= 1
UNET Theta Warmup= 1
UNET ZTol= 0.02
UNET ZSATol= 0.05
UNET MxIter= 20
UNET MaxInSteps= 0
UNET DtIC= 0
UNET DtMin= 0
UNET MaxCRTS= 20
UNET WFStab= 2
UNET SFStab= 1
UNET WFX= 1
UNET SFX= 1
UNET DSS MLevel= 4
UNET DZMax Abort= 100
UNET Convert EG Bridges= 0
UNET Use Existing IB Tables=-1
UNET Froude Reduction=False
UNET Froude Limit= 1
UNET Froude Power= 10
UNET Time Slicing=0,0, 5
UNET Junction Losses=0
Instantaneous Interval=1HOUR
DSS File=dss
Write IC File= 0
Write IC File at Sim End=0
Echo Input=False
Echo Parameters=False
Echo Output=False
Write Detailed= 0
WQ AD Non Conservative
WQ ULTIMATE=-1
WQ Max Comp Step=1HOUR
WQ Output Interval=15MIN
WQ Output Selected Increments= 0
WQ Output face flow=0
WQ Output face velocity=0
WQ Output face area=0
WQ Output face dispersion=0
WQ Output cell volume=0
WQ Output cell surface area=0
WQ Output cell continuity=0
WQ Output cumulative cell continuity=0
WQ Output face conc=0
WQ Output face dconc_dx=0
WQ Output face courant=0
WQ Output face peclet=0
WQ Output face adv mass=0
WQ Output face disp mass=0
WQ Output cell mass=0
WQ Output cell source sink temp=0
WQ Output cell source sink nsm=0
WQ Output MaxMinRange=-1
WQ Daily Max Min Mean=-1
WQ Daily Range=0
WQ Daily Time=0
WQ Create Restart=0
WQ Fixed Restart=0
WQ System Summary=0
WQ Use Fixed Temperature=0
Sorting and Armoring Iterations= 10
XS Update Threshold= 0.02
Hydraulics Update Threshold= 0.02
Energy Slope Method= 1
Volume Change Method= 0
XS Weighting Method= 0
Number of US Weighted Cross Sections= 1
Number of DS Weighted Cross Sections= 1
Upstream XS Weight=0.25
Main XS Weight=0.5
Downstream XS Weight=0.25
Number of DS XS's Weighted with US Boundary= 1
Upstream Boundary Weight= 1
Weight of XSs Associated with US Boundary= 0
Number of US XS's Weighted with DS Boundary= 1
Downstream Boundary Weight= 0.5
Weight of XSs Associated with DS Boundary= 0.5
Sediment Output Level= 4
Mass or Volume Output= 0
Output Increment Type= 1
Profile and TS Output Increment= 10
XS Output Flag= 0
XS Output Increment= 10
Disregard all LS=0
Disregard all Conn=0
Disregard all Breaches=0
Disregard all Pumps=0

--- UNT051 IN NNOGR.f01 (steady flow) ---

Flow Title=Multiple
Program Version=4.10
Number of Profiles= 7
Profile Names=10-year,25-year,50-year,1pct_min,100-year,1pct_plu,500-year
River Rch & RM=UNT051 IN NNOGR,Reach-1         ,2894
     362     501     617     559     756    1023    1137
Boundary for River Rch & Prof#=UNT051 IN NNOGR,Reach-1         , 1
Up Type= 0
Dn Type= 3
Dn Slope=0.025
Boundary for River Rch & Prof#=UNT051 IN NNOGR,Reach-1         , 2
Up Type= 0
Dn Type= 3
Dn Slope=0.025
Boundary for River Rch & Prof#=UNT051 IN NNOGR,Reach-1         , 3
Up Type= 0
Dn Type= 3
Dn Slope=0.025
Boundary for River Rch & Prof#=UNT051 IN NNOGR,Reach-1         , 4
Up Type= 0
Dn Type= 3
Dn Slope=0.025
Boundary for River Rch & Prof#=UNT051 IN NNOGR,Reach-1         , 5
Up Type= 0
Dn Type= 3
Dn Slope=0.025
Boundary for River Rch & Prof#=UNT051 IN NNOGR,Reach-1         , 6
Up Type= 0
Dn Type= 3
Dn Slope=0.025
Boundary for River Rch & Prof#=UNT051 IN NNOGR,Reach-1         , 7
Up Type= 0
Dn Type= 3
Dn Slope=0.025
DSS Import GetInterval= 0
DSS Import GetPeak= 0
DSS Import FillOption= 0

--- UNT051 IN NNOGR.g01 (geometry) ---

Geom Title=Existing Conditions
Program Version=4.10

River Reach=UNT051 IN NNOGR ,Reach-1
Reach XY= 30
      2794314.39     10083441.38      2794299.04     10083372.57
      2794327.32     10083323.86      2794387.25     10083053.71
      2794390.58     10082979.69      2794358.67     10082825.19
       2794378.5     10082653.82       2794348.3     10082463.28
      2794322.15     10082407.28      2794258.34     10082364.02
      2794133.02     10082205.06      2793991.63     10082117.58
      2793800.57     10082030.05      2793733.62     10081873.77
      2793605.82     10081840.82      2793575.99     10081810.27
      2793559.87     10081763.57      2793568.35     10081646.88
      2793518.24     10081506.63      2793488.79     10081463.61
      2793416.07     10081410.05      2793350.84     10081307.28
      2793386.72     10081233.37      2793360.47     10081167.99
      2793349.37     10081078.27      2793375.42     10081017.98
      2793357.58     10080998.31      2793303.97     10080986.28
      2793280.06     10080928.25      2793278.47     10080873.73

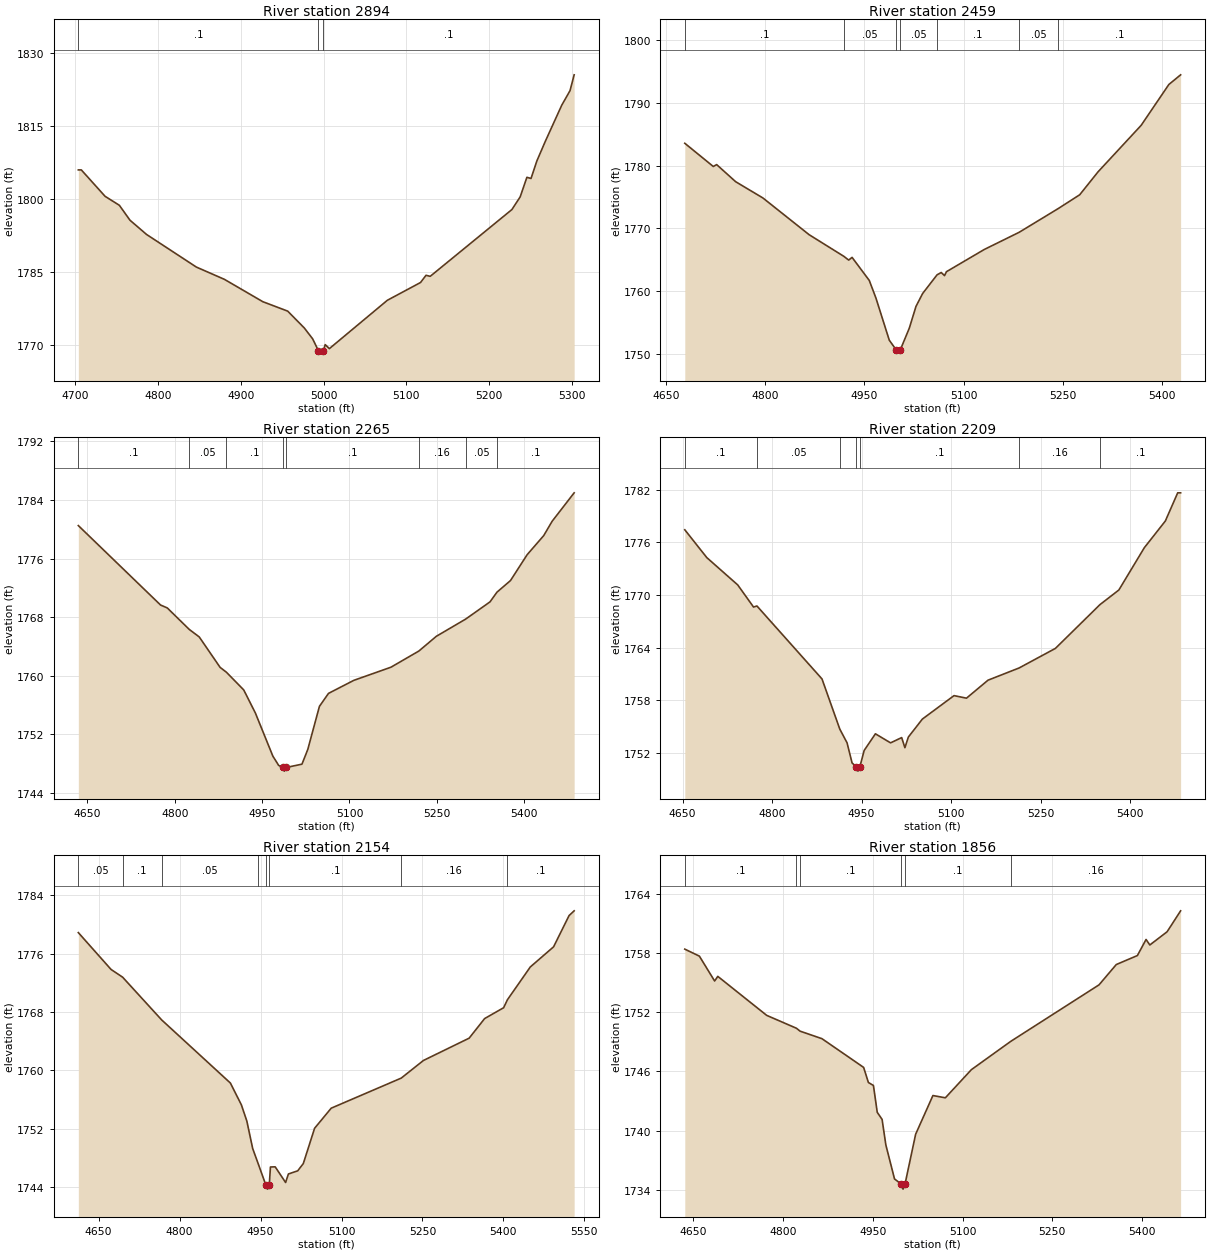
Type RM Length L Ch R = 1 ,2894    ,435,435,435
BEGIN DESCRIPTION:
UNT051 IN NNOGR 6.0
END DESCRIPTION:
XS GIS Cut Line= 2
      2794650.61     10083182.95      2794053.49     10083134.35
#Sta/Elev= 30
  4703.6 1806.04  4707.2 1806.04  4735.9 1800.62  4753.2 1798.77    4766 1795.71
    4786 1792.79  4846.2 1786.09  4880.1 1783.57  4926.5 1778.98  4956.6 1777.04
  4976.6 1773.59  4986.7 1771.36  4993.7 1768.92  4996.5 1768.42  4999.7 1768.92
  5001.9 1770.17  5006.9 1769.34    5077 1779.27  5117.1 1782.92  5123.7  1784.4
  5128.8 1784.19  5227.5  1797.9  5237.5 1800.51  5245.6 1804.52  5250.6 1804.28
  5257.6 1807.86  5267.6 1811.81  5287.7 1819.32  5297.7 1822.31  5302.7 1825.56
#Mann= 3 ,-1 , 0
  4703.6      .1       0  4993.7     .07       0  4999.7      .1       0
Bank Sta=4993.7,4999.7
XS Rating Curve= 0 ,0
Exp/Cntr=0.3,0.1

Type RM Length L Ch R = 1 ,2459    ,194,194,194
BEGIN DESCRIPTION:
UNT051 IN NNOGR 5.0
END DESCRIPTION:
XS GIS Cut Line= 3
      2794694.63     10082785.19      2794302.22     10082727.89
      2794013.99     10082932.77
#Sta/Elev= 30
  4678.3 1783.55  4721.4 1779.85  4726.5 1780.15  4755.3 1777.42  4796.5 1774.83
  4866.4 1768.98  4918.9 1765.53  4926.3 1764.93  4931.4 1765.36  4957.4 1761.69
  4967.5 1758.88  4987.7 1752.16  4998.3  1750.6  5001.1  1750.1  5004.3  1750.6
    5018 1754.08  5028.1 1757.55  5038.2 1759.61    5060 1762.58  5066.3 1762.95
  5071.3 1762.45  5074.2 1763.08  5131.4 1766.62  5184.2 1769.36  5243.3 1773.14
  5275.8 1775.34  5303.6    1779  5368.8 1786.41  5410.7 1792.92  5428.5 1794.46
#Mann= 7 ,-1 , 0
  4678.3      .1       0  4918.9     .05       0  4998.3    .035       0
  5004.3     .05       0    5060      .1       0  5184.2     .05       0
  5243.3      .1       0
Bank Sta=4998.3,5004.3
XS Rating Curve= 0 ,0
Exp/Cntr=0.3,0.1

Type RM Length L Ch R = 1 ,2265    ,56,56,56
BEGIN DESCRIPTION:
Mapping XS 0ca43a11
END DESCRIPTION:
XS GIS Cut Line= 4
      2794729.28     10082582.05      2794484.52     10082542.12
      2794302.22     10082547.33      2794029.66      10082868.5
#Sta/Elev= 30
  4634.3  1780.5  4775.5 1769.66  4787.1 1769.26  4824.8 1766.33    4842  1765.3
  4877.8 1761.15  4888.6 1760.49  4918.4 1758.07  4938.4 1754.92  4968.4 1749.04
  4978.4 1747.77  4985.4 1747.49  4988.1 1746.99  4991.4 1747.49  5018.4 1747.94
  5028.4 1749.95  5048.4 1755.83    5064  1757.6  5107.5 1759.38  5171.2 1761.17
  5219.2 1763.38  5249.2 1765.39  5299.6 1767.74  5341.4 1770.09  5353.3 1771.41
  5376.6    1773  5405.1 1776.52  5433.7 1779.14    5448 1781.08  5485.9 1784.97
#Mann= 8 ,-1 , 0
  4634.3      .1       0  4824.8     .05       0  4888.6      .1       0
  4985.4     .07       0  4991.4      .1       0  5219.2     .16       0
  5299.6     .05       0  5353.3      .1       0
Bank Sta=4985.4,4991.4
XS Rating Curve= 0 ,0
Exp/Cntr=0.3,0.1

Type RM Length L Ch R = 1 ,2209    ,55,55,55
BEGIN DESCRIPTION:
Mapping XS c2448f66
END DESCRIPTION:
XS GIS Cut Line= 4
      2794696.36     10082524.07      2794376.01     10082481.53
      2794283.13     10082519.73      2794014.92     10082826.13
#Sta/Elev= 30
  4653.8 1777.42  4690.7 1774.25  4742.5 1771.14    4769 1768.62  4774.7 1768.74
  4883.7 1760.43  4913.5 1754.72  4925.7 1753.15  4934.1 1750.86  4941.2 1750.43
    4944 1749.93  4947.2 1750.43  4954.3 1752.28  4973.2 1754.18  4998.6 1753.15
  5017.2 1753.75  5022.6  1752.6  5028.4 1753.81  5051.9 1755.86  5104.9 1758.53
  5125.8 1758.24  5161.9 1760.29    5214 1761.68  5274.8 1763.91  5349.5  1768.9
  5381.1 1770.56  5423.8 1775.38    5459 1778.42  5479.7 1781.63  5484.6 1781.63
#Mann= 7 ,-1 , 0
  4653.8      .1       0  4774.7     .05       0  4913.5      .1       0
  4941.2     .07       0  4947.2      .1       0    5214     .16       0
  5349.5      .1       0
Bank Sta=4941.2,4947.2
XS Rating Curve= 0 ,0
Exp/Cntr=0.3,0.1

Type RM Length L Ch R = 1 ,2154    ,298,298,298
BEGIN DESCRIPTION:
Mapping XS 6fd4fdf0
END DESCRIPTION:
XS GIS Cut Line= 4
      2794718.85     10082441.43      2794427.22     10082411.92
      2794274.45     10082457.05      2793979.31     10082818.17
#Sta/Elev= 30
  4612.3 1778.89    4673 1773.83  4694.4 1772.77  4766.8  1766.9  4894.1 1758.24
  4914.5 1755.24  4924.6 1753.01  4935.4 1749.25  4945.3 1747.23  4960.1 1744.18
  4962.9 1743.68  4966.1 1744.18  4968.3 1746.72  4977.1 1746.74  4996.4 1744.59
  5001.6 1745.76  5018.8 1746.19  5029.2 1747.19  5050.1 1752.03  5080.9 1754.79
  5210.7 1758.92  5251.8 1761.34  5336.5  1764.4  5365.2 1767.09  5400.4 1768.58
  5407.5 1769.68  5449.9 1774.18    5493 1776.94  5521.7 1781.23  5531.1 1781.88
#Mann= 8 ,-1 , 0
  4612.3     .05       0  4694.4      .1       0  4766.8     .05       0
  4945.3      .1       0  4960.1     .07       0  4966.1      .1       0
  5210.7     .16       0  5407.5      .1       0
Bank Sta=4960.1,4966.1
XS Rating Curve= 0 ,0
Exp/Cntr=0.3,0.1

Type RM Length L Ch R = 1 ,1856    ,434,434,434
BEGIN DESCRIPTION:
UNT051 IN NNOGR 4.0
END DESCRIPTION:
XS GIS Cut Line= 3
      2794470.15     10082071.83      2794178.44     10082176.01
      2793858.99     10082585.74
#Sta/Elev= 30
  4635.5 1758.38  4659.9 1757.67  4685.4 1755.15  4690.7 1755.62  4772.5 1751.67
  4822.1 1750.37  4828.4 1750.07  4864.9 1749.31  4934.6  1746.4  4942.6 1744.87
    4951 1744.57  4957.4 1741.85  4965.5 1741.13  4971.8 1738.54  4986.3  1735.1
  4997.8 1734.57  5000.5 1734.07  5003.8 1734.57  5021.6 1739.63  5050.5 1743.55
  5071.3 1743.32  5114.8 1746.17  5180.5 1749.03  5328.3 1754.76  5357.2 1756.82
  5392.5 1757.73    5407 1759.36  5413.3  1758.8  5442.2 1760.14  5464.8 1762.26
#Mann= 6 ,-1 , 0
  4635.5      .1       0  4822.1     .16       0  4828.4      .1       0
  4997.8     .07       0  5003.8      .1       0  5180.5     .16       0
Bank Sta=4997.8,5003.8
XS Rating Curve= 0 ,0
Exp/Cntr=0.3,0.1

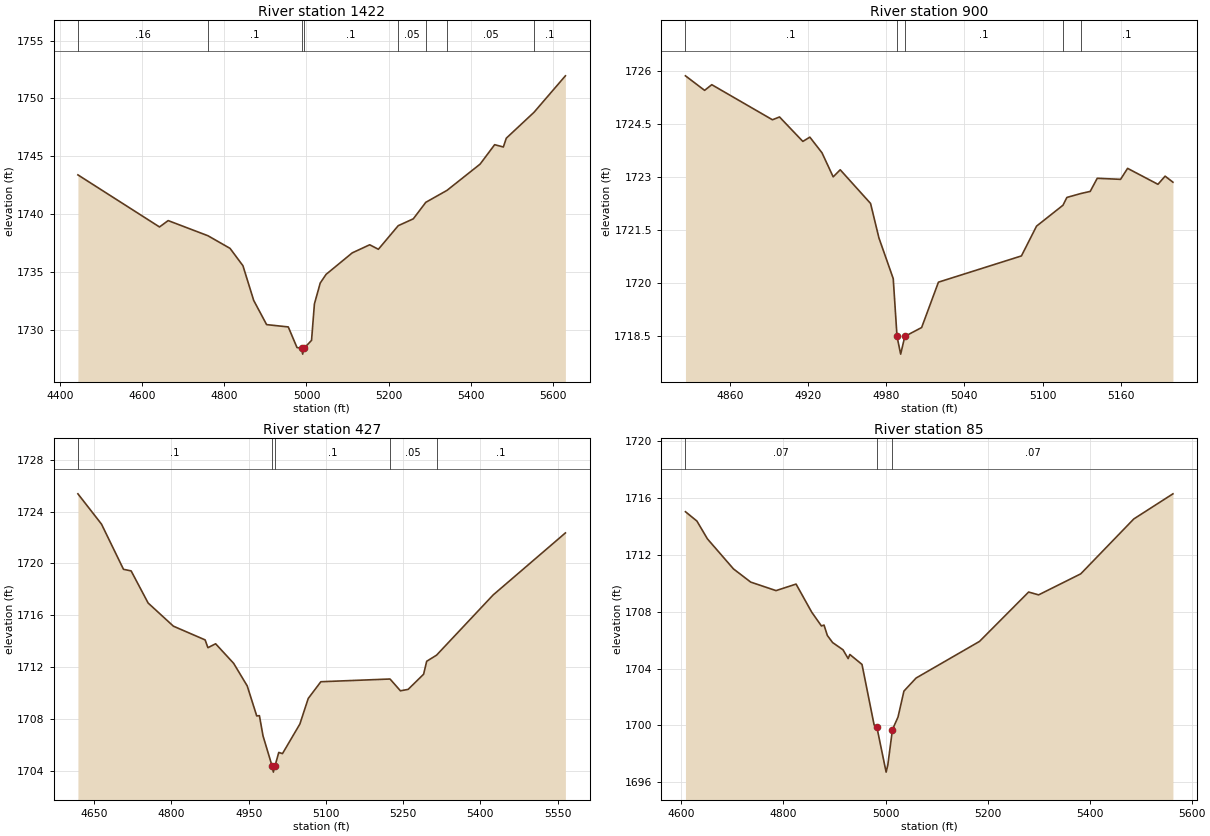
Type RM Length L Ch R = 1 ,1422    ,522,522,522
BEGIN DESCRIPTION:
UNT051 IN NNOGR 3.0
END DESCRIPTION:
XS GIS Cut Line= 3
      2794296.49     10081801.01      2793824.27     10081960.73
      2793345.13     10082453.76
#Sta/Elev= 30
    4444 1743.39  4642.5 1738.89  4663.6 1739.44  4760.4 1738.13  4814.1 1737.04
  4845.5 1735.54  4871.7 1732.54  4903.1 1730.45  4955.8 1730.25    4977 1728.47
  4988.1  1728.4  4990.8  1727.9  4994.1  1728.4  5012.4 1729.09  5019.4 1732.24
  5033.5 1734.04  5047.7 1734.79  5111.4 1736.65  5153.9 1737.35    5175 1736.96
  5223.3    1739  5259.9 1739.59  5290.4 1741.02  5341.9 1742.05  5422.5 1744.32
  5457.9    1746  5479.1  1745.8  5486.2 1746.56  5553.7  1748.8    5630 1751.95
#Mann= 8 ,-1 , 0
    4444     .16       0  4760.4      .1       0  4988.1     .07       0
  4994.1      .1       0  5223.3     .05       0  5290.4     .16       0
  5341.9     .05       0  5553.7      .1       0
Bank Sta=4988.1,4994.1
XS Rating Curve= 0 ,0
Exp/Cntr=0.3,0.1

Type RM Length L Ch R = 1 ,900     ,473,473,473
BEGIN DESCRIPTION:
UNT051 IN NNOGR 2.0
END DESCRIPTION:
XS GIS Cut Line= 2
      2793714.32     10081541.65      2793372.07     10081692.96
#Sta/Elev= 30
  4825.9 1725.85  4840.6 1725.44  4846.1  1725.6  4892.7 1724.61  4898.1 1724.69
    4916    1724  4921.4 1724.12  4930.7 1723.68  4939.3    1723  4944.7  1723.2
    4968 1722.25  4974.4 1721.28  4985.4 1720.13  4988.3  1718.5  4991.1    1718
  4994.3  1718.5  5007.2 1718.75  5020.1 1720.03  5083.8 1720.77  5095.4 1721.61
  5115.7  1722.2  5118.7 1722.42  5129.4 1722.53  5136.6 1722.59    5142 1722.96
  5159.9 1722.93  5165.3 1723.24  5188.6 1722.79  5194.1 1723.02  5200.1 1722.85
#Mann= 5 ,-1 , 0
  4825.9      .1       0  4988.3     .07       0  4994.3      .1       0
  5115.7     .05       0  5129.4      .1       0
Bank Sta=4988.3,4994.3
XS Rating Curve= 0 ,0
Exp/Cntr=0.3,0.1

Type RM Length L Ch R = 1 ,427     ,342,342,342
BEGIN DESCRIPTION:
Mapping XS 58b12c39
END DESCRIPTION:
XS GIS Cut Line= 4
      2793759.12     10081248.82      2793528.61     10081195.42
      2793273.41     10081248.81      2793022.76     10081621.53
#Sta/Elev= 30
  4618.5 1725.37  4664.3 1723.03    4707 1719.54  4721.8 1719.42  4754.8 1716.94
  4803.9 1715.15  4865.5 1714.09  4870.9 1713.49  4885.9 1713.79  4920.9 1712.28
  4947.2 1710.54  4965.7 1708.22  4970.9 1708.24  4977.9 1706.68  4995.3 1704.38
    4998 1703.88  5001.3 1704.38  5008.5  1705.4  5015.7 1705.31  5049.4 1707.59
  5065.7 1709.57  5090.2 1710.86  5224.5 1711.07  5244.7 1710.16  5259.7 1710.27
  5289.7 1711.44  5295.7 1712.44  5314.8 1712.91  5424.7 1717.56    5565 1722.35
#Mann= 5 ,-1 , 0
  4618.5      .1       0  4995.3     .07       0  5001.3      .1       0
  5224.5     .05       0  5314.8      .1       0
Bank Sta=4995.3,5001.3
XS Rating Curve= 0 ,0
Exp/Cntr=0.3,0.1

Type RM Length L Ch R = 1 ,85      ,0,0,0
BEGIN DESCRIPTION:
UNT051 IN NNOGR 1.0
END DESCRIPTION:
XS GIS Cut Line= 4
      2793670.52      10080994.9      2793358.04      10080928.5
      2793109.34     10081032.66      2793020.81     10081388.11
#Sta/Elev= 30
  4607.9 1715.05  4630.4 1714.39  4650.9 1713.14    4702 1711.02  4735.8 1710.09
  4785.4 1709.49  4824.7 1709.95  4855.4 1707.97  4874.4    1707  4879.5 1707.06
    4886 1706.33  4896.3 1705.83  4916.7 1705.32  4926.8  1704.7  4930.1 1704.99
  4953.9 1704.29  4977.7 1700.02  4983.1 1699.86  5001.2  1696.7  5004.5  1697.2
  5013.6  1699.7  5024.5 1700.58  5036.1 1702.41  5059.9 1703.33  5184.2 1705.91
  5280.5 1709.39    5300 1709.19  5382.6 1710.67  5486.6 1714.54  5563.3 1716.31
#Mann= 3 , 0 , 0
  4607.9     .07       0  4983.1     .03       0  5013.6     .07       0
Bank Sta=4983.1,5013.6
XS Rating Curve= 0 ,0
Exp/Cntr=0.3,0.1

Chan Stop Cuts=-1
Use User Specified Reach Order=0
Composite Channel Slope=5