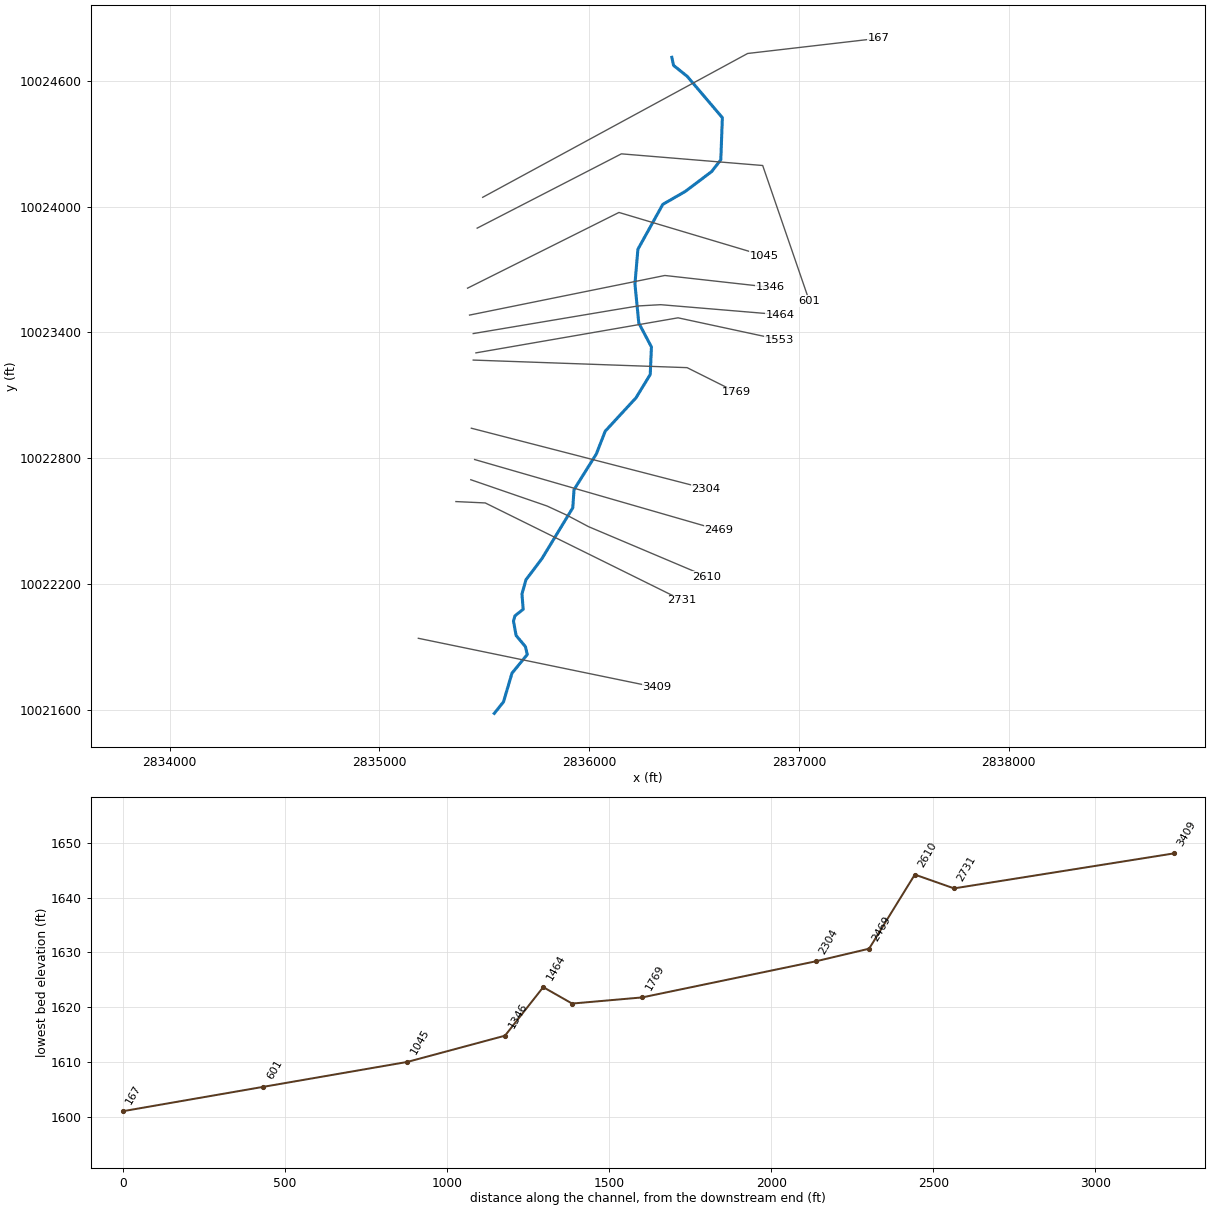
--- UNT051 IN SNOGR.prj (project) ---

Proj Title=UNT051 IN SNOGR Base Level Engineering
Current Plan=p01
Default Exp/Contr=0.3,0.1
English Units
Geom File=g01
Flow File=f01
Plan File=p01
BEGIN DESCRIPTION:
UNT051 IN SNOGR
END DESCRIPTION:

--- UNT051 IN SNOGR.p01 (plan) ---

Plan Title=Multiple Run
Short Identifier=Multiple
Geom File=g01
Flow File=f01
Subcritical Flow
K Sum by GR= 0
Std Step Tol= 0.01
Critical Tol= 0.01
Num of Std Step Trials= 20
Max Error Tol= 0.3
Flow Tol Ratio= 0.001
Split Flow NTrial= 30
Split Flow Tol= 0.02
Split Flow Ratio= 0.02
Log Output Level= 0
Friction Slope Method= 1
Unsteady Friction Slope Method= 2
Unsteady Bridges Friction Slope Method= 1
Parabolic Critical Depth
Global Vel Dist=  1 , 1 , 1
Global Log Level= 0
CheckData=True
Encroach Param= -1, 0, 0, 0
BEGIN DESCRIPTION:
Multiple Run
END DESCRIPTION:

--- UNT051 IN SNOGR.f01 (steady flow) ---

Flow Title=Multiple
Number of Profiles=7
Profile Names=10-year,25-year,50-year,1pct_min,100-year,1pct_plu,500-year
River Rch & RM= UNT051 IN SNOGR,Reach-1,3409
    1305    1932    2488    2345    3172    4289    5171
Boundary for River Rch & Prof#=UNT051 IN SNOGR,Reach-1,1
Up Type=0
Dn Type=3
Dn Slope=0.005
Boundary for River Rch & Prof#=UNT051 IN SNOGR,Reach-1,2
Up Type=0
Dn Type=3
Dn Slope=0.005
Boundary for River Rch & Prof#=UNT051 IN SNOGR,Reach-1,3
Up Type=0
Dn Type=3
Dn Slope=0.005
Boundary for River Rch & Prof#=UNT051 IN SNOGR,Reach-1,4
Up Type=0
Dn Type=3
Dn Slope=0.005
Boundary for River Rch & Prof#=UNT051 IN SNOGR,Reach-1,5
Up Type=0
Dn Type=3
Dn Slope=0.005
Boundary for River Rch & Prof#=UNT051 IN SNOGR,Reach-1,6
Up Type=0
Dn Type=3
Dn Slope=0.005
Boundary for River Rch & Prof#=UNT051 IN SNOGR,Reach-1,7
Up Type=0
Dn Type=3
Dn Slope=0.005

--- UNT051 IN SNOGR.g01 (geometry) ---

Geom Title=Existing Conditions

River Reach=UNT051 IN SNOGR,Reach-1
Reach XY= 30
      2835548.19     10021584.13      2835592.13     10021639.08
      2835632.55     10021775.75      2835705.58     10021864.90
      2835696.38     10021902.56      2835652.24     10021955.37
      2835639.61     10022024.33      2835646.77     10022049.17
      2835685.88     10022080.30      2835680.12     10022153.37
      2835699.05     10022220.93      2835774.93     10022321.16
      2835922.40     10022564.17      2835928.30     10022650.62
      2836034.61     10022820.62      2836077.00     10022929.34
      2836223.72     10023088.38      2836291.65     10023199.63
      2836297.35     10023330.97      2836237.10     10023444.83
      2836218.69     10023631.08      2836232.83     10023796.55
      2836351.42     10024010.51      2836458.50     10024072.23
      2836584.95     10024167.53      2836628.03     10024223.27
      2836635.49     10024423.90      2836467.98     10024620.84
      2836402.75     10024673.18      2836394.56     10024711.50

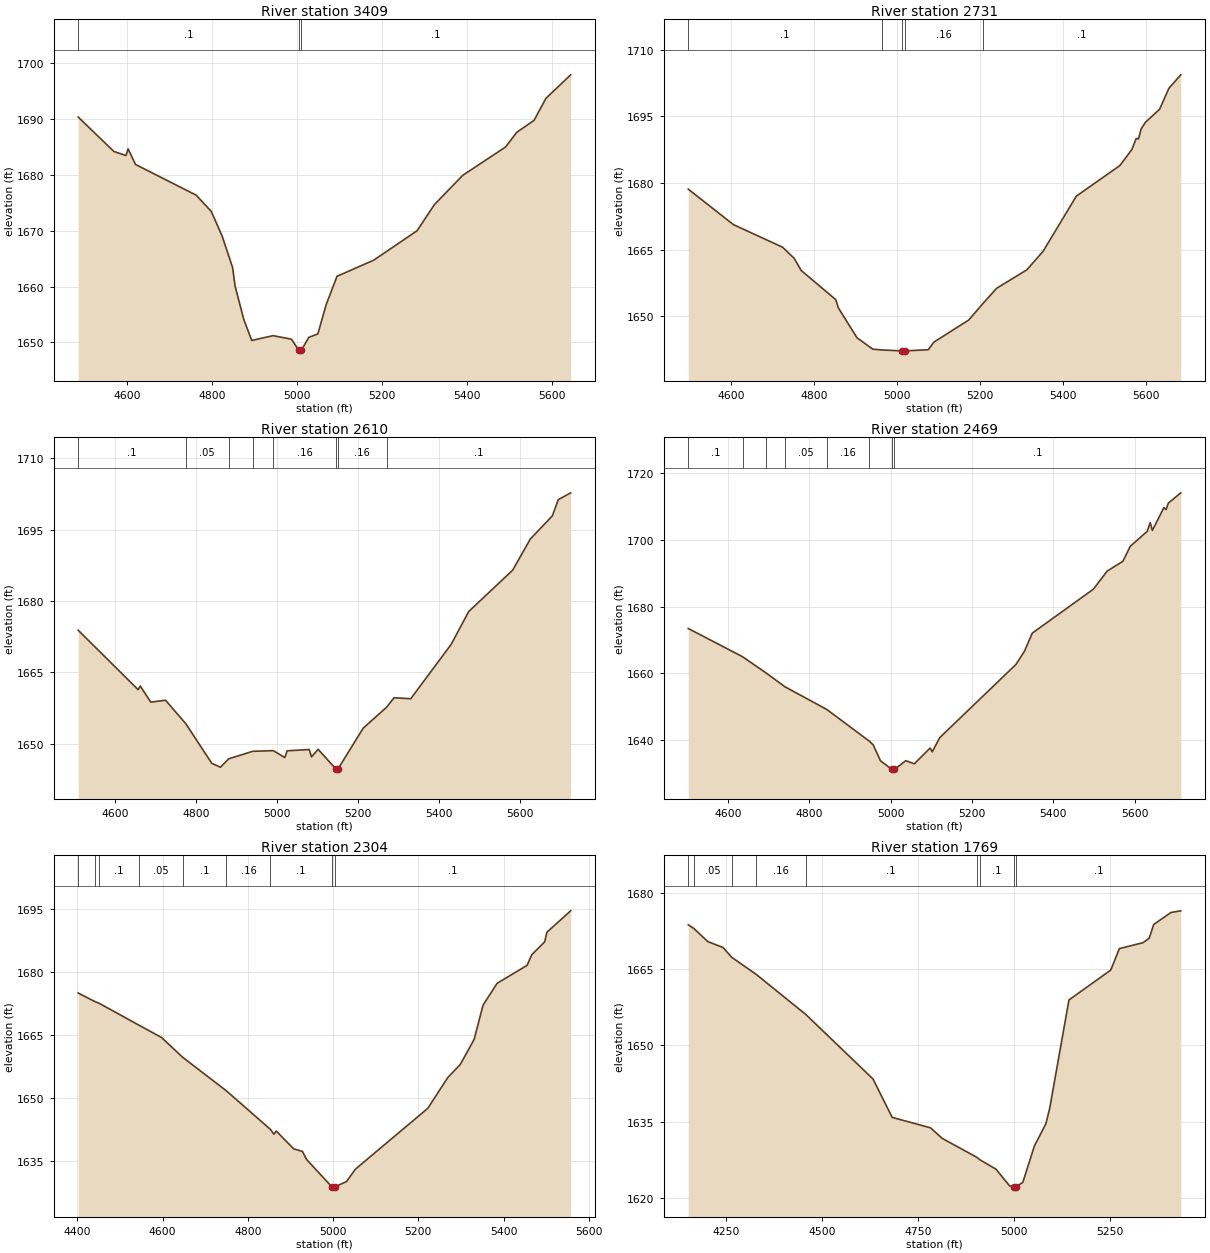
Type RM Length L Ch R = 1,3409,678,678,678
BEGIN DESCRIPTION:
UNT051 IN SNOGR 7.0
END DESCRIPTION:
XS GIS Cut Line= 2
      2835186.14     10021942.08      2836322.99     10021707.50
#Sta/Elev= 30
  4483.8 1690.38  4567.9 1684.21  4596.4 1683.48  4601.5 1684.67  4618.9 1681.88
  4761.9 1676.38  4797.4 1673.48  4823.1 1669.06  4847.7 1663.43  4853.8 1660.02
  4874.2 1654.10  4892.9 1650.34  4943.1 1651.20  4986.5 1650.57  5003.9 1648.57
  5006.7 1648.07  5009.9 1648.57  5027.3 1650.89  5048.8 1651.52  5068.2 1656.73
  5093.9 1661.84  5180.5 1664.73  5282.6 1670.00  5323.4 1674.68  5390.4 1679.94
  5491.0 1685.00  5517.5 1687.64  5558.3 1689.78  5586.4 1693.74  5644.6 1697.94
#Mann=3,-1,0
  4483.8     0.1       0  5003.9    0.07       0  5009.9     0.1       0
Bank Sta=5003.9,5009.9
Exp/Cntr=0.3,0.1

Type RM Length L Ch R = 1,2731,121,121,121
BEGIN DESCRIPTION:
UNT051 IN SNOGR 6.0
END DESCRIPTION:
XS GIS Cut Line= 3
      2835365.26     10022593.82      2835505.18     10022587.31
      2836444.19     10022123.23
#Sta/Elev= 30
  4495.9 1678.61  4604.8 1670.62  4723.2 1665.54  4751.2 1663.04  4768.1 1660.30
  4851.6 1653.72  4857.8 1651.86  4902.7 1645.14  4940.8 1642.57  4963.5 1642.39
  5011.9 1642.18  5014.6 1641.68  5017.9 1642.18  5074.7 1642.45  5087.8 1644.14
  5172.0 1649.13  5206.7 1652.88  5239.3 1656.28  5312.2 1660.44  5351.5 1664.63
  5431.6 1677.04  5536.6 1683.93  5565.5 1687.55  5575.9 1690.04  5581.5 1689.93
  5587.8 1692.19  5598.3 1693.68  5632.4 1696.62  5654.7 1701.32  5683.4 1704.36
#Mann=5,-1,0
  4495.9     0.1       0  4963.5    0.16       0  5011.9    0.07       0
  5017.9    0.16       0  5206.7     0.1       0
Bank Sta=5011.9,5017.9
Exp/Cntr=0.3,0.1

Type RM Length L Ch R = 1,2610,141,141,141
BEGIN DESCRIPTION:
Mapping XS c4363183
END DESCRIPTION:
XS GIS Cut Line= 5
      2835436.25     10022697.93      2835799.40     10022572.79
      2835896.41     10022527.90      2835997.31     10022474.35
      2836560.32     10022236.28
#Sta/Elev= 30
  4509.0 1673.84  4657.1 1661.33  4662.4 1662.10  4688.3 1658.71  4724.8 1659.11
  4774.8 1654.18  4839.1 1645.84  4860.4 1645.02  4880.7 1646.78  4940.1 1648.37
  4991.0 1648.51  5019.4 1647.05  5025.1 1648.47  5079.7 1648.75  5085.4 1647.19
  5101.7 1648.80  5145.1 1644.70  5147.8 1644.20  5151.1 1644.70  5213.2 1653.25
  5270.7 1657.63  5289.2 1659.63  5330.6 1659.43  5430.3 1670.86  5473.8 1677.78
  5582.3 1686.47  5625.8 1693.02  5680.1 1697.87  5694.9 1701.29  5725.5 1702.73
#Mann=8,-1,0
  4509.0     0.1       0  4774.8    0.05       0  4880.7     0.1       0
  4940.1    0.05       0  4991.0    0.16       0  5145.1    0.07       0
  5151.1    0.16       0  5270.7     0.1       0
Bank Sta=5145.1,5151.1
Exp/Cntr=0.3,0.1

Type RM Length L Ch R = 1,2469,165,165,165
BEGIN DESCRIPTION:
Mapping XS 6035bc92
END DESCRIPTION:
XS GIS Cut Line= 2
      2835454.51     10022794.27      2836617.84     10022458.54
#Sta/Elev= 30
  4502.4 1673.42  4635.7 1664.97  4694.2 1660.05  4739.7 1655.98  4843.6 1649.10
  4947.6 1639.63  4957.2 1638.50  4974.9 1633.77  5003.1 1631.16  5005.9 1630.66
  5009.1 1631.16  5037.3 1633.79  5058.1 1632.85  5097.0 1637.59  5102.2 1636.44
  5120.6 1640.70  5307.9 1662.64  5328.8 1666.59  5348.1 1672.03  5498.3 1685.21
  5532.0 1690.61  5570.8 1693.58  5589.0 1698.07  5630.6 1702.55  5638.1 1705.16
  5643.3 1702.82  5671.7 1709.69  5676.9 1709.04  5682.6 1711.02  5713.2 1714.10
#Mann=8,-1,0
  4502.4     0.1       0  4635.7    0.05       0  4694.2     0.1       0
  4739.7    0.05       0  4843.6    0.16       0  4947.6     0.1       0
  5003.1    0.07       0  5009.1     0.1       0
Bank Sta=5003.1,5009.1
Exp/Cntr=0.3,0.1

Type RM Length L Ch R = 1,2304,535,535,535
BEGIN DESCRIPTION:
UNT051 IN SNOGR 5.0
END DESCRIPTION:
XS GIS Cut Line= 2
      2835438.81     10022943.55      2836557.56     10022654.84
#Sta/Elev= 30
  4402.0 1675.03  4440.7 1673.02  4451.1 1672.59  4543.8 1667.42  4597.9 1664.42
  4646.8 1659.76  4749.8 1651.74  4852.8 1642.59  4861.4 1641.41  4866.5 1642.19
  4907.7 1637.93  4928.3 1637.33  4937.5 1635.45  4997.6 1628.85  5000.4 1628.35
  5003.6 1628.85  5031.6 1630.16  5052.3 1633.09  5222.2 1647.58  5269.2 1654.92
  5298.3 1658.01  5320.8 1662.12  5331.1 1664.05  5351.8 1672.13  5384.8 1677.33
  5455.1 1681.61  5466.2 1684.14  5496.4 1687.20  5501.7 1689.50  5557.4 1694.59
#Mann=9,-1,0
  4402.0     0.1       0  4440.7    0.05       0  4451.1     0.1       0
  4543.8    0.05       0  4646.8     0.1       0  4749.8    0.16       0
  4852.8     0.1       0  4997.6    0.07       0  5003.6     0.1       0
Bank Sta=4997.6,5003.6
Exp/Cntr=0.3,0.1

Type RM Length L Ch R = 1,1769,216,216,216
BEGIN DESCRIPTION:
UNT051 IN SNOGR 4.0
END DESCRIPTION:
XS GIS Cut Line= 3
      2835447.80     10023268.36      2836467.36     10023232.26
      2836701.97     10023114.96
#Sta/Elev= 30
  4151.7 1673.67  4165.8 1672.97  4202.4 1670.38  4242.4 1669.20  4264.7 1667.29
  4328.6 1663.93  4457.7 1656.06  4632.7 1643.39  4682.7 1635.85  4782.8 1633.79
  4812.8 1631.73  4902.4 1628.04  4911.9 1627.49  4952.9 1625.68  4988.5 1622.39
  4999.9 1622.26  5002.6 1621.76  5005.9 1622.26  5022.9 1623.09  5052.9 1630.22
  5082.9 1634.60  5093.0 1637.68  5143.0 1658.91  5251.9 1664.78  5274.3 1668.99
  5335.8 1670.15  5352.0 1671.04  5363.7 1673.73  5408.5 1676.08  5434.2 1676.41
#Mann=9,-1,0
  4151.7     0.1       0  4165.8    0.05       0  4264.7     0.1       0
  4328.6    0.16       0  4457.7     0.1       0  4902.4    0.16       0
  4911.9     0.1       0  4999.9    0.07       0  5005.9     0.1       0
Bank Sta=4999.9,5005.9
Exp/Cntr=0.3,0.1

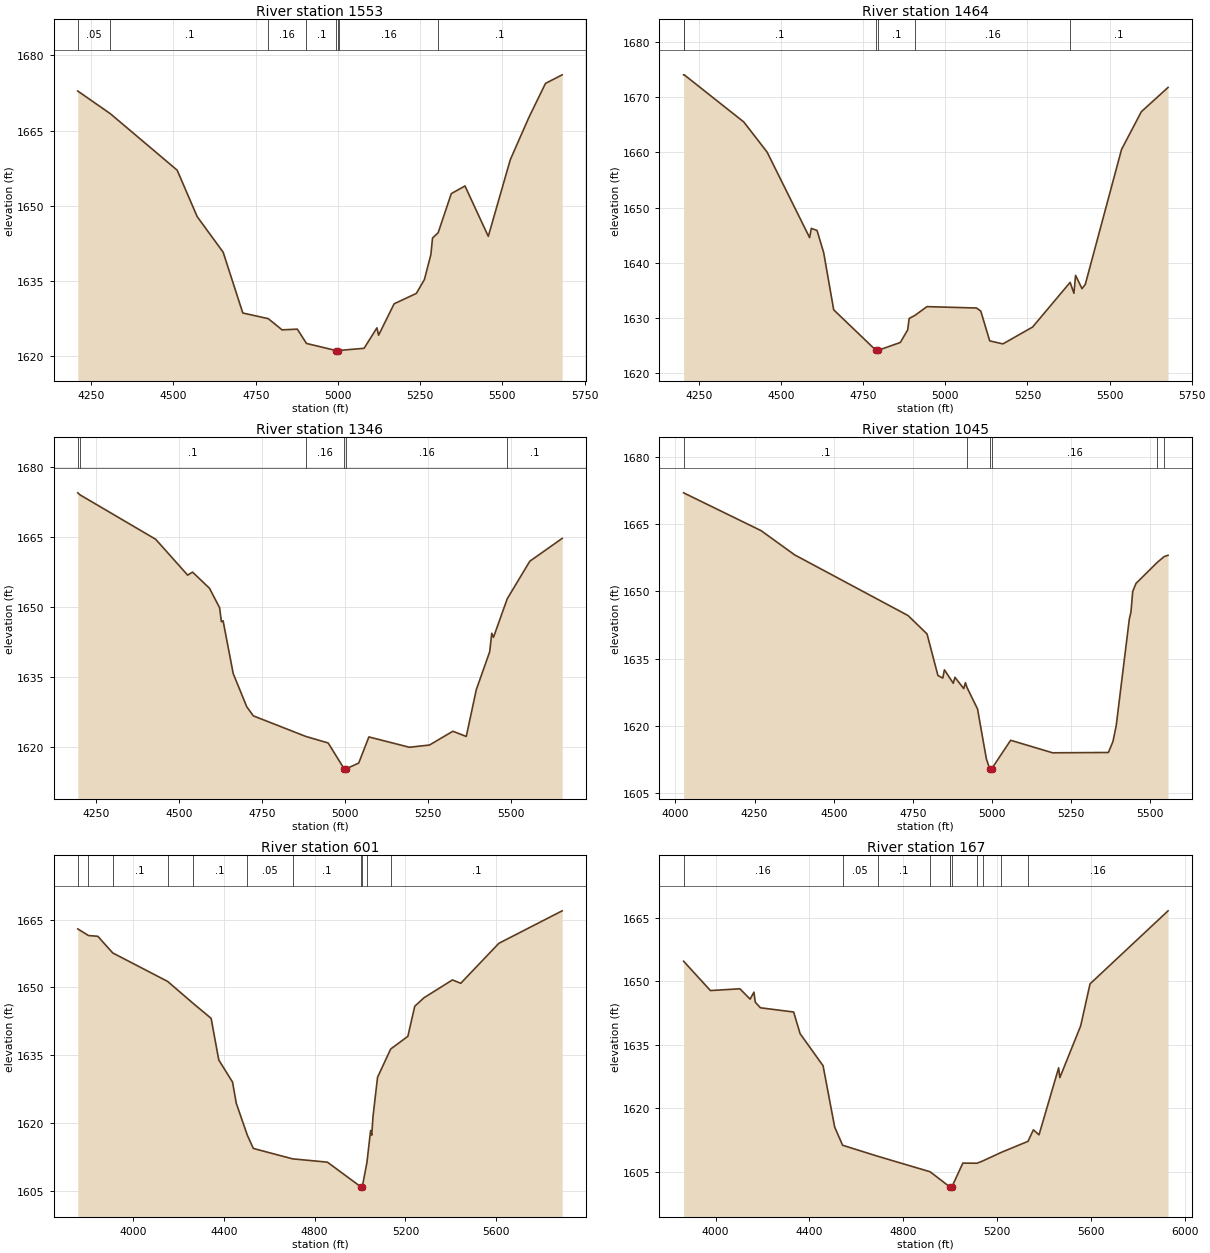
Type RM Length L Ch R = 1,1553,89,89,89
BEGIN DESCRIPTION:
UNT051 IN SNOGR 3.0
END DESCRIPTION:
XS GIS Cut Line= 3
      2835460.67     10023302.71      2836424.18     10023469.81
      2836908.11     10023365.64
#Sta/Elev= 30
  4209.0 1672.88  4308.1 1668.36  4511.2 1657.11  4572.1 1647.85  4651.1 1640.75
  4710.8 1628.64  4788.2 1627.51  4830.2 1625.28  4876.6 1625.42  4904.4 1622.57
  4995.4 1621.14  4998.2 1620.64  5001.4 1621.14  5003.8 1621.18  5079.6 1621.60
  5118.6 1625.68  5123.7 1624.22  5170.9 1630.47  5238.4 1632.54  5262.9 1635.30
  5282.6 1640.27  5287.7 1643.59  5304.8 1644.64  5344.7 1652.43  5386.4 1653.96
  5457.2 1643.92  5524.2 1659.21  5580.0 1667.53  5631.1 1674.40  5681.9 1676.11
#Mann=8,-1,0
  4209.0    0.05       0  4308.1     0.1       0  4788.2    0.16       0
  4904.4     0.1       0  4995.4    0.07       0  5001.4     0.1       0
  5003.8    0.16       0  5304.8     0.1       0
Bank Sta=4995.4,5001.4
Exp/Cntr=0.3,0.1

Type RM Length L Ch R = 1,1464,118,118,118
BEGIN DESCRIPTION:
Mapping XS 50f152ae
END DESCRIPTION:
XS GIS Cut Line= 5
      2835447.87     10023394.67      2836117.63     10023507.29
      2836233.51     10023526.36      2836341.33     10023532.42
      2836909.45     10023484.89
#Sta/Elev= 30
  4203.4 1674.03  4205.3 1674.03  4386.5 1665.50  4457.5 1660.05  4587.0 1644.55
  4592.1 1646.23  4609.6 1645.85  4629.9 1641.80  4660.3 1631.48  4789.1 1624.14
  4791.9 1623.64  4795.1 1624.14  4863.1 1625.57  4885.5 1627.85  4890.0 1629.92
  4907.3 1630.46  4944.2 1632.06  5095.1 1631.81  5108.0 1631.26  5135.2 1625.86
  5175.4 1625.31  5265.7 1628.36  5380.0 1636.45  5391.6 1634.48  5396.6 1637.73
  5416.2 1635.31  5426.2 1636.09  5536.6 1660.53  5596.8 1667.35  5678.1 1671.75
#Mann=6,-1,0
  4203.4    0.05       0  4205.3     0.1       0  4789.1    0.07       0
  4795.1     0.1       0  4907.3    0.16       0  5380.0     0.1       0
Bank Sta=4789.1,4795.1
Exp/Cntr=0.3,0.1

Type RM Length L Ch R = 1,1346,301,301,301
BEGIN DESCRIPTION:
Mapping XS f12794d1
END DESCRIPTION:
XS GIS Cut Line= 3
      2835430.30     10023482.84      2836361.24     10023671.63
      2836865.22     10023615.39
#Sta/Elev= 30
  4195.7 1674.50  4203.1 1674.04  4430.1 1664.53  4526.3 1656.83  4540.8 1657.49
  4591.8 1654.03  4622.4 1649.83  4627.7 1646.83  4632.8 1647.05  4663.2 1635.72
  4704.0 1628.58  4723.9 1626.63  4881.0 1622.23  4948.9 1620.81  4996.9 1615.27
  4999.7 1614.77  5002.9 1615.27  5040.7 1616.50  5071.3 1622.11  5193.1 1619.89
  5253.5 1620.37  5323.9 1623.33  5364.2 1622.21  5394.4 1632.26  5434.6 1640.38
  5440.9 1644.36  5446.0 1643.48  5487.4 1651.76  5555.3 1659.82  5652.7 1664.72
#Mann=6,-1,0
  4195.7    0.05       0  4203.1     0.1       0  4881.0    0.16       0
  4996.9    0.07       0  5002.9    0.16       0  5487.4     0.1       0
Bank Sta=4996.9,5002.9
Exp/Cntr=0.3,0.1

Type RM Length L Ch R = 1,1045,444,444,444
BEGIN DESCRIPTION:
UNT051 IN SNOGR 2.0
END DESCRIPTION:
XS GIS Cut Line= 3
      2835420.79     10023611.22      2836142.55     10023972.09
      2836835.36     10023765.15
#Sta/Elev= 30
  4025.9 1671.93  4270.6 1663.51  4376.8 1658.11  4734.6 1644.62  4794.7 1640.52
  4829.1 1631.27  4844.4 1630.69  4849.6 1632.53  4877.5 1629.54  4882.8 1630.87
  4910.7 1628.35  4915.9 1629.67  4921.0 1628.59  4954.2 1623.82  4982.1 1612.72
  4992.6 1610.48  4995.3 1609.98  4998.6 1610.48  5058.8 1616.85  5191.3 1614.06
  5367.4 1614.13  5381.7 1616.53  5392.2 1620.10  5433.6 1643.84  5438.8 1645.42
  5444.3 1649.98  5454.8 1651.77  5522.1 1656.46  5543.5 1657.73  5555.9 1658.03
#Mann=6,-1,0
  4025.9     0.1       0  4921.0    0.16       0  4992.6    0.07       0
  4998.6    0.16       0  5522.1     0.1       0  5543.5    0.16       0
Bank Sta=4992.6,4998.6
Exp/Cntr=0.3,0.1

Type RM Length L Ch R = 1,601,434,434,434
BEGIN DESCRIPTION:
Mapping XS a12bba50
END DESCRIPTION:
XS GIS Cut Line= 4
      2835466.64     10023897.32      2836154.11     10024251.48
      2836827.72     10024195.92      2837049.94     10023550.12
#Sta/Elev= 30
  3757.5 1662.94  3804.7 1661.47  3845.9 1661.30  3911.3 1657.63  4153.1 1651.33
  4264.9 1646.50  4344.5 1643.17  4378.2 1633.97  4438.8 1629.08  4455.3 1624.39
  4504.0 1617.33  4530.5 1614.42  4703.0 1612.12  4856.3 1611.39  5003.8 1605.93
  5006.6 1605.43  5009.8 1605.93  5030.3 1611.32  5046.4 1618.38  5051.4 1617.35
  5057.0 1621.47  5077.0 1630.14  5134.8 1636.39  5210.5 1639.20  5240.8 1645.85
  5281.8 1647.73  5406.7 1651.66  5443.3 1650.92  5610.9 1659.75  5889.7 1666.93
#Mann=11,-1,0
  3757.5     0.1       0  3804.7    0.16       0  3911.3     0.1       0
  4153.1    0.16       0  4264.9     0.1       0  4504.0    0.05       0
  4703.0     0.1       0  5003.8    0.07       0  5009.8     0.1       0
  5030.3    0.16       0  5134.8     0.1       0
Bank Sta=5003.8,5009.8
Exp/Cntr=0.3,0.1

Type RM Length L Ch R = 1,167,0,0,0
BEGIN DESCRIPTION:
UNT051 IN SNOGR 1.0
END DESCRIPTION:
XS GIS Cut Line= 3
      2835492.97     10024044.29      2836756.07     10024729.97
      2837378.59     10024802.14
#Sta/Elev= 30
  3863.7 1654.73  3977.9 1647.81  4103.4 1648.23  4147.1 1645.79  4163.3 1647.44
  4169.0 1645.08  4190.8 1643.75  4332.5 1642.75  4360.0 1637.64  4457.9 1630.07
  4507.3 1615.61  4541.1 1611.32  4689.8 1608.74  4913.7 1605.07  4998.5 1601.47
  5000.5 1601.47  5003.2 1600.97  5006.5 1601.47  5053.3 1607.11  5113.5 1607.08
  5137.6 1607.60  5217.9 1609.66  5331.2 1612.25  5353.7 1614.96  5377.9 1613.78
  5461.6 1629.59  5466.6 1627.26  5555.3 1639.48  5595.3 1649.39  5927.6 1666.62
#Mann=11,-1,0
  3863.7    0.16       0  4541.1    0.05       0  4689.8     0.1       0
  4913.7    0.05       0  4998.5    0.16       0  5000.5    0.07       0
  5006.5    0.16       0  5113.5     0.1       0  5137.6    0.16       0
  5217.9     0.1       0  5331.2    0.16       0
Bank Sta=5000.5,5006.5
Exp/Cntr=0.3,0.1

Chan Stop Cuts=-1