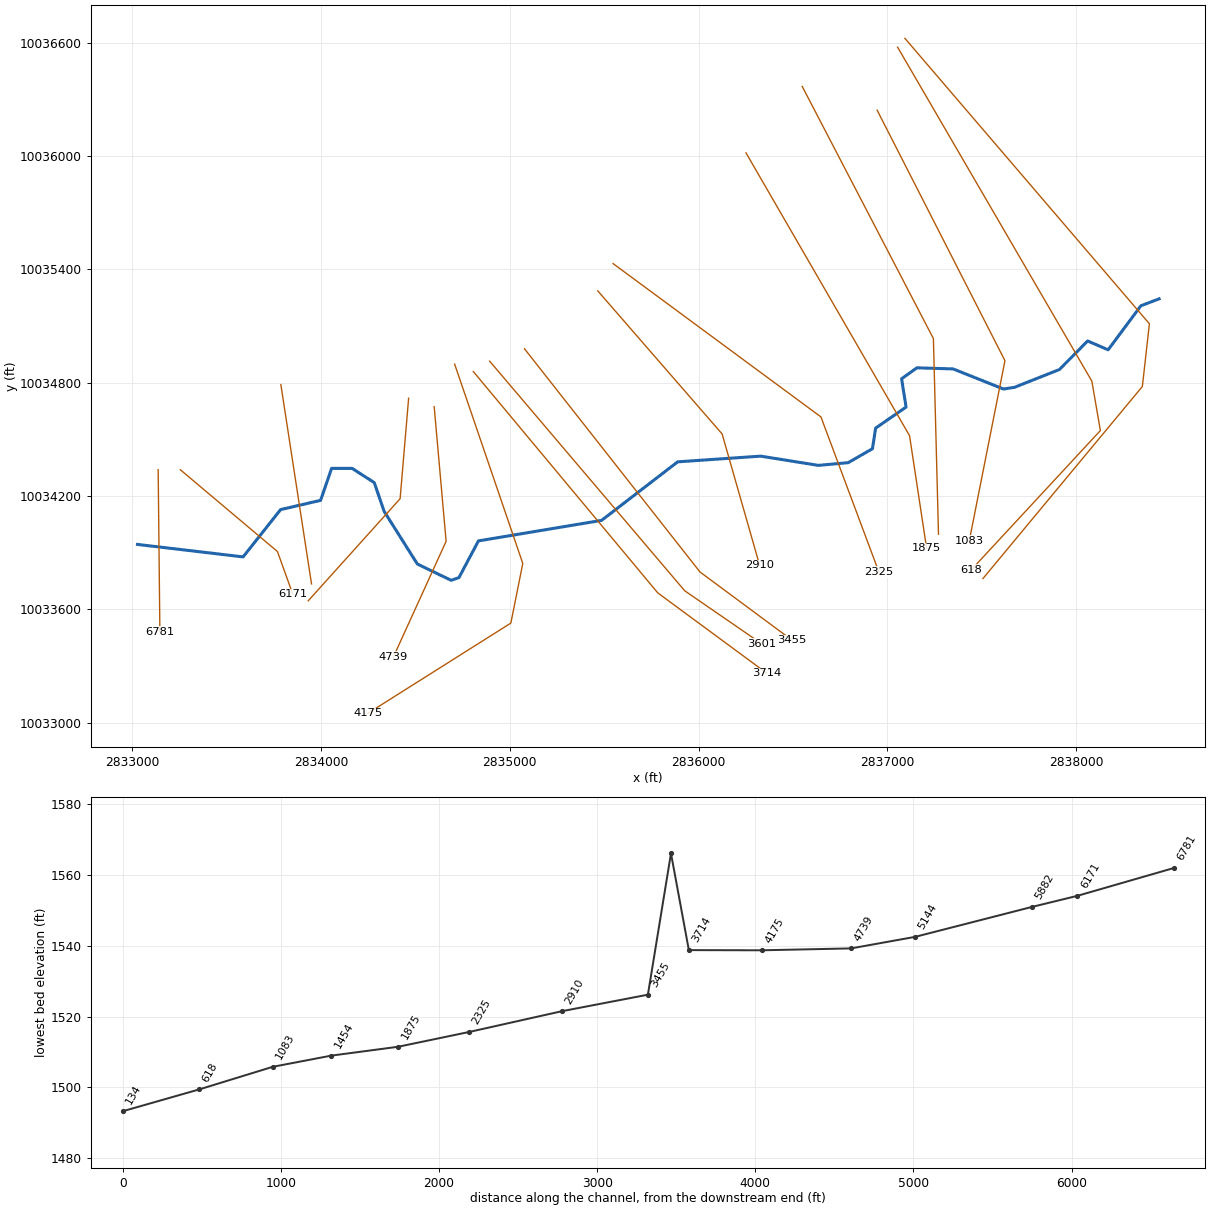
--- UNT052 IN SNOGR.prj (project) ---

Proj Title=UNT052 IN SNOGR Base Level Engineering
Current Plan=p01
Default Exp/Contr=0.3,0.1
English Units
Geom File=g01
Flow File=f01
Plan File=p01
BEGIN DESCRIPTION:
UNT052 IN SNOGR
END DESCRIPTION:

--- UNT052 IN SNOGR.p01 (plan) ---

Plan Title=Multiple Run
Short Identifier=Multiple
Geom File=g01
Flow File=f01
Subcritical Flow
K Sum by GR= 0
Std Step Tol= 0.01
Critical Tol= 0.01
Num of Std Step Trials= 20
Max Error Tol= 0.3
Flow Tol Ratio= 0.001
Split Flow NTrial= 30
Split Flow Tol= 0.02
Split Flow Ratio= 0.02
Log Output Level= 0
Friction Slope Method= 1
Unsteady Friction Slope Method= 2
Unsteady Bridges Friction Slope Method= 1
Parabolic Critical Depth
Global Vel Dist=  1 , 1 , 1
Global Log Level= 0
CheckData=True
Encroach Param= -1, 0, 0, 0
BEGIN DESCRIPTION:
Multiple Run
END DESCRIPTION:

--- UNT052 IN SNOGR.f01 (steady flow) ---

Flow Title=Multiple
Number of Profiles=7
Profile Names=10-year,25-year,50-year,1pct_min,100-year,1pct_plu,500-year
River Rch & RM= UNT052 IN SNOGR,Reach-1,6781
     547     712     839     573     970    1368    1288
River Rch & RM= UNT052 IN SNOGR,Reach-1,3714
    1002    1302    1533    1046    1773    2500    2351
Boundary for River Rch & Prof#=UNT052 IN SNOGR,Reach-1,1
Up Type=0
Dn Type=3
Dn Slope=0.005
Boundary for River Rch & Prof#=UNT052 IN SNOGR,Reach-1,2
Up Type=0
Dn Type=3
Dn Slope=0.005
Boundary for River Rch & Prof#=UNT052 IN SNOGR,Reach-1,3
Up Type=0
Dn Type=3
Dn Slope=0.005
Boundary for River Rch & Prof#=UNT052 IN SNOGR,Reach-1,4
Up Type=0
Dn Type=3
Dn Slope=0.005
Boundary for River Rch & Prof#=UNT052 IN SNOGR,Reach-1,5
Up Type=0
Dn Type=3
Dn Slope=0.005
Boundary for River Rch & Prof#=UNT052 IN SNOGR,Reach-1,6
Up Type=0
Dn Type=3
Dn Slope=0.005
Boundary for River Rch & Prof#=UNT052 IN SNOGR,Reach-1,7
Up Type=0
Dn Type=3
Dn Slope=0.005

--- UNT052 IN SNOGR.g01 (geometry) ---

Geom Title=Existing Conditions

River Reach=UNT052 IN SNOGR,Reach-1
Reach XY= 30
      2833028.54     10033943.30      2833587.93     10033877.27
      2833786.30     10034127.62      2833998.22     10034176.72
      2834056.58     10034346.20      2834164.92     10034346.12
      2834282.52     10034270.46      2834334.36     10034119.00
      2834510.40     10033839.68      2834689.42     10033753.30
      2834730.91     10033767.70      2834834.23     10033962.03
      2835486.24     10034070.65      2835889.22     10034380.64
      2836328.53     10034410.77      2836634.19     10034361.88
      2836792.36     10034376.30      2836920.64     10034450.09
      2836937.37     10034559.33      2837098.53     10034670.32
      2837074.92     10034820.62      2837156.04     10034878.45
      2837347.90     10034872.62      2837614.48     10034766.25
      2837672.69     10034775.19      2837910.60     10034869.48
      2838060.15     10035020.64      2838168.47     10034973.73
      2838342.01     10035207.00      2838438.47     10035243.73

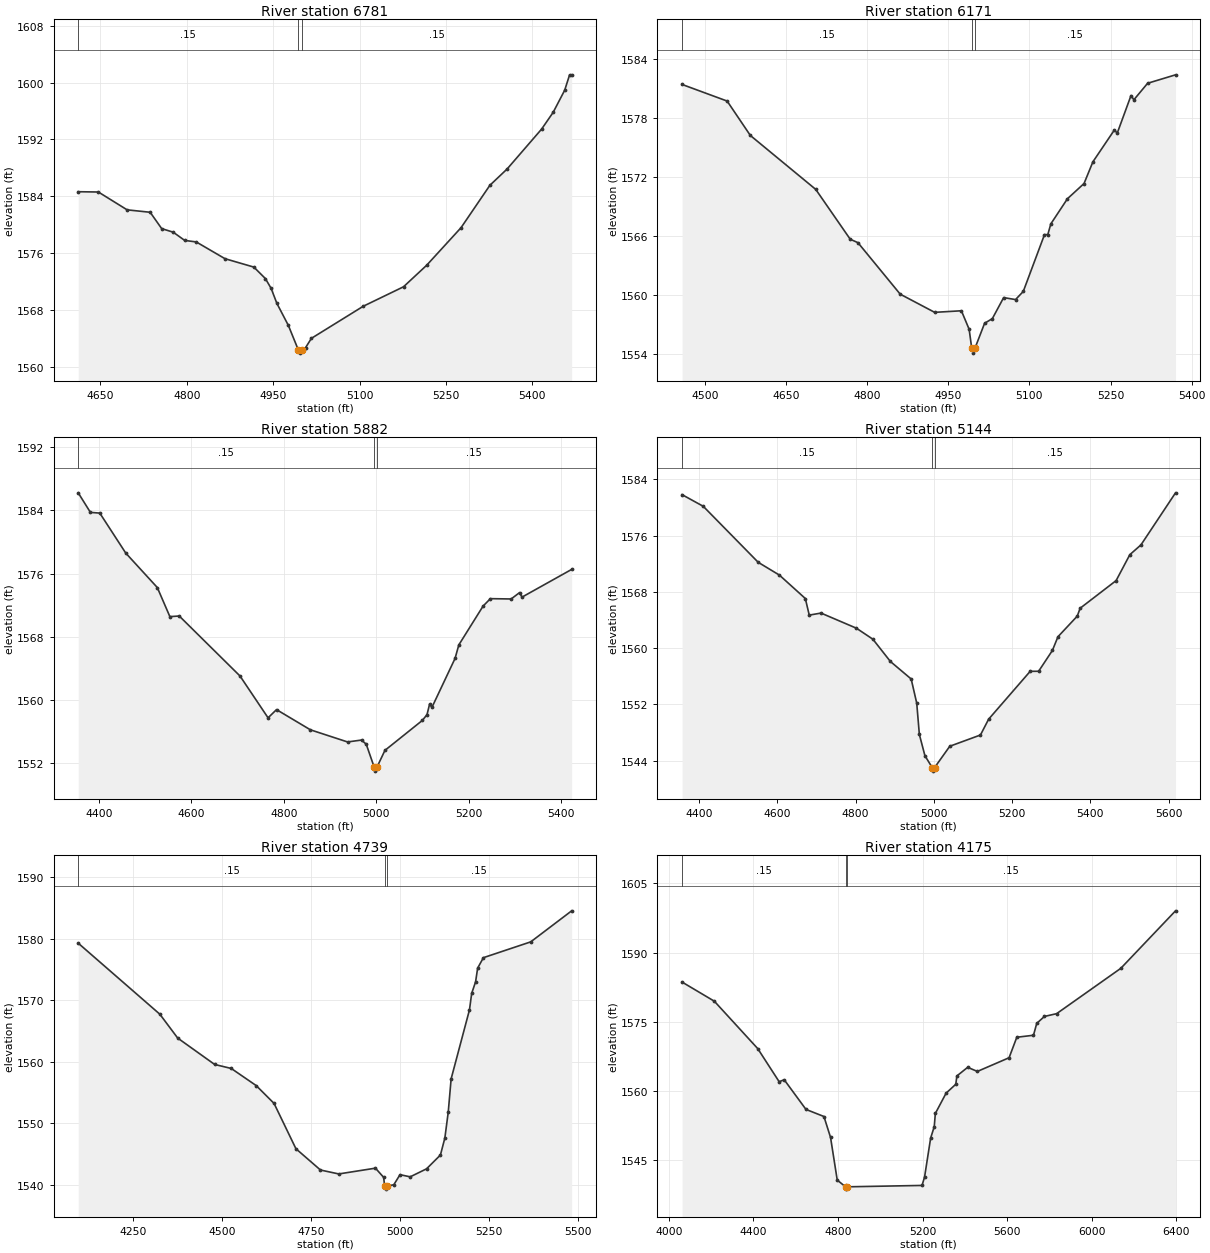
Type RM Length L Ch R = 1,6781,610,610,610
BEGIN DESCRIPTION:
UNT052 IN SNOGR 14.0
END DESCRIPTION:
XS GIS Cut Line= 2
      2833138.12     10034338.77      2833147.15     10033481.61
#Sta/Elev= 30
  4611.3 1584.64  4646.3 1584.60  4696.3 1582.09  4736.3 1581.75  4756.3 1579.45
  4776.3 1578.95  4796.3 1577.79  4816.3 1577.58  4866.3 1575.22  4916.4 1574.04
  4936.4 1572.43  4946.4 1571.05  4956.4 1568.94  4976.4 1565.83  4993.4 1562.44
  4996.1 1561.94  4999.4 1562.44  5006.4 1562.73  5016.4 1564.02  5106.4 1568.53
  5176.4 1571.27  5216.4 1574.28  5276.4 1579.59  5326.4 1585.54  5356.4 1587.84
  5416.4 1593.46  5436.4 1595.81  5456.4 1598.92  5464.9 1601.08  5468.5 1601.08
#Mann=3,-1,0
  4611.3    0.15       0  4993.4    0.05       0  4999.4    0.15       0
Bank Sta=4993.4,4999.4
Exp/Cntr=0.3,0.1

Type RM Length L Ch R = 1,6171,289,289,289
BEGIN DESCRIPTION:
UNT052 IN SNOGR 13.0
END DESCRIPTION:
XS GIS Cut Line= 3
      2833255.42     10034338.73      2833769.69     10033905.66
      2833850.90     10033680.06
#Sta/Elev= 30
  4458.1 1581.43  4541.4 1579.74  4584.3 1576.24  4705.2 1570.75  4768.9 1565.68
  4783.2 1565.33  4861.3 1560.09  4925.0 1558.24  4974.4 1558.40  4988.7 1556.52
  4993.5 1554.59  4996.3 1554.09  4999.5 1554.59  5017.3 1557.13  5031.6 1557.60
  5052.5 1559.74  5074.5 1559.54  5088.8 1560.37  5128.0 1566.15  5134.1 1566.15
  5139.7 1567.24  5170.4 1569.80  5201.1 1571.35  5217.5 1573.56  5257.2 1576.80
  5262.5 1576.48  5287.9 1580.30  5293.2 1579.87  5318.6 1581.55  5370.2 1582.41
#Mann=3,-1,0
  4458.1    0.15       0  4993.5    0.05       0  4999.5    0.15       0
Bank Sta=4993.5,4999.5
Exp/Cntr=0.3,0.1

Type RM Length L Ch R = 1,5882,738,738,738
BEGIN DESCRIPTION:
UNT052 IN SNOGR 12.0
END DESCRIPTION:
XS GIS Cut Line= 2
      2833787.73     10034789.84      2833950.13     10033734.26
#Sta/Elev= 30
  4355.2 1586.23  4381.6 1583.75  4401.9 1583.66  4458.1 1578.59  4526.4 1574.22
  4553.6 1570.53  4573.9 1570.61  4705.4 1563.00  4766.1 1557.70  4784.4 1558.74
  4857.7 1556.18  4938.1 1554.64  4968.4 1554.88  4978.6 1554.35  4995.8 1551.44
  4998.5 1550.94  5001.8 1551.44  5019.0 1553.57  5100.0 1557.37  5110.1 1558.10
  5115.7 1559.44  5120.8 1559.03  5170.8 1565.23  5179.0 1566.95  5231.5 1571.87
  5247.3 1572.81  5292.2 1572.77  5310.5 1573.58  5315.6 1573.00  5423.2 1576.52
#Mann=3,-1,0
  4355.2    0.15       0  4995.8    0.05       0  5001.8    0.15       0
Bank Sta=4995.8,5001.8
Exp/Cntr=0.3,0.1

Type RM Length L Ch R = 1,5144,405,405,405
BEGIN DESCRIPTION:
UNT052 IN SNOGR 11.0
END DESCRIPTION:
XS GIS Cut Line= 3
      2834464.41     10034717.70      2834419.29     10034185.35
      2833932.79     10033644.79
#Sta/Elev= 30
  4356.3 1581.84  4410.5 1580.18  4551.0 1572.21  4605.2 1570.39  4671.4 1567.06
  4681.4 1564.70  4711.5 1564.99  4801.9 1562.84  4844.1 1561.27  4888.9 1558.10
  4942.0 1555.61  4956.2 1552.17  4962.9 1547.72  4977.1 1544.70  4995.8 1543.00
  4998.5 1542.50  5001.8 1543.00  5040.7 1546.04  5119.1 1547.64  5140.0 1549.89
  5246.2 1556.70  5267.8 1556.71  5303.0 1559.67  5317.2 1561.62  5366.5 1564.55
  5374.0 1565.68  5465.9 1569.61  5501.0 1573.30  5529.4 1574.69  5617.8 1582.10
#Mann=3,-1,0
  4356.3    0.15       0  4995.8    0.05       0  5001.8    0.15       0
Bank Sta=4995.8,5001.8
Exp/Cntr=0.3,0.1

Type RM Length L Ch R = 1,4739,564,564,564
BEGIN DESCRIPTION:
UNT052 IN SNOGR 10.0
END DESCRIPTION:
XS GIS Cut Line= 3
      2834599.74     10034672.58      2834662.89     10033959.79
      2834383.88     10033347.77
#Sta/Elev= 30
  4095.0 1579.26  4324.7 1567.70  4374.9 1563.82  4478.8 1559.53  4525.5 1558.88
  4595.8 1556.09  4646.0 1553.19  4707.5 1545.82  4776.5 1542.36  4828.0 1541.72
  4931.2 1542.66  4954.2 1541.17  4957.1 1539.75  4959.9 1539.25  4963.1 1539.75
  4982.8 1539.96  5000.3 1541.60  5028.9 1541.25  5074.9 1542.55  5114.0 1544.80
  5126.5 1547.58  5136.0 1551.79  5144.1 1557.19  5195.7 1568.41  5201.9 1571.09
  5212.9 1572.97  5218.7 1575.20  5234.9 1576.90  5368.0 1579.47  5483.2 1584.52
#Mann=3,-1,0
  4095.0    0.15       0  4957.1    0.05       0  4963.1    0.15       0
Bank Sta=4957.1,4963.1
Exp/Cntr=0.3,0.1

Type RM Length L Ch R = 1,4175,461,461,461
BEGIN DESCRIPTION:
UNT052 IN SNOGR 9.0
END DESCRIPTION:
XS GIS Cut Line= 4
      2834708.00     10034898.12      2835068.90     10033842.50
      2835005.74     10033526.72      2834248.00     10033048.62
#Sta/Elev= 30
  4062.3 1583.60  4214.9 1579.45  4420.1 1569.18  4521.4 1562.00  4545.3 1562.43
  4648.2 1556.00  4733.2 1554.46  4764.5 1549.92  4796.1 1540.68  4835.4 1539.22
  4838.2 1538.72  4841.4 1539.22  5197.0 1539.52  5209.0 1541.32  5237.8 1549.78
  5254.9 1552.27  5260.0 1555.12  5311.0 1559.53  5356.8 1561.45  5361.9 1563.25
  5412.9 1565.12  5458.8 1564.23  5608.8 1567.20  5645.3 1571.64  5724.2 1572.07
  5739.5 1574.64  5775.9 1576.15  5833.6 1576.75  6137.2 1586.58  6395.9 1599.04
#Mann=3,-1,0
  4062.3    0.15       0  4835.4    0.05       0  4841.4    0.15       0
Bank Sta=4835.4,4841.4
Exp/Cntr=0.3,0.1

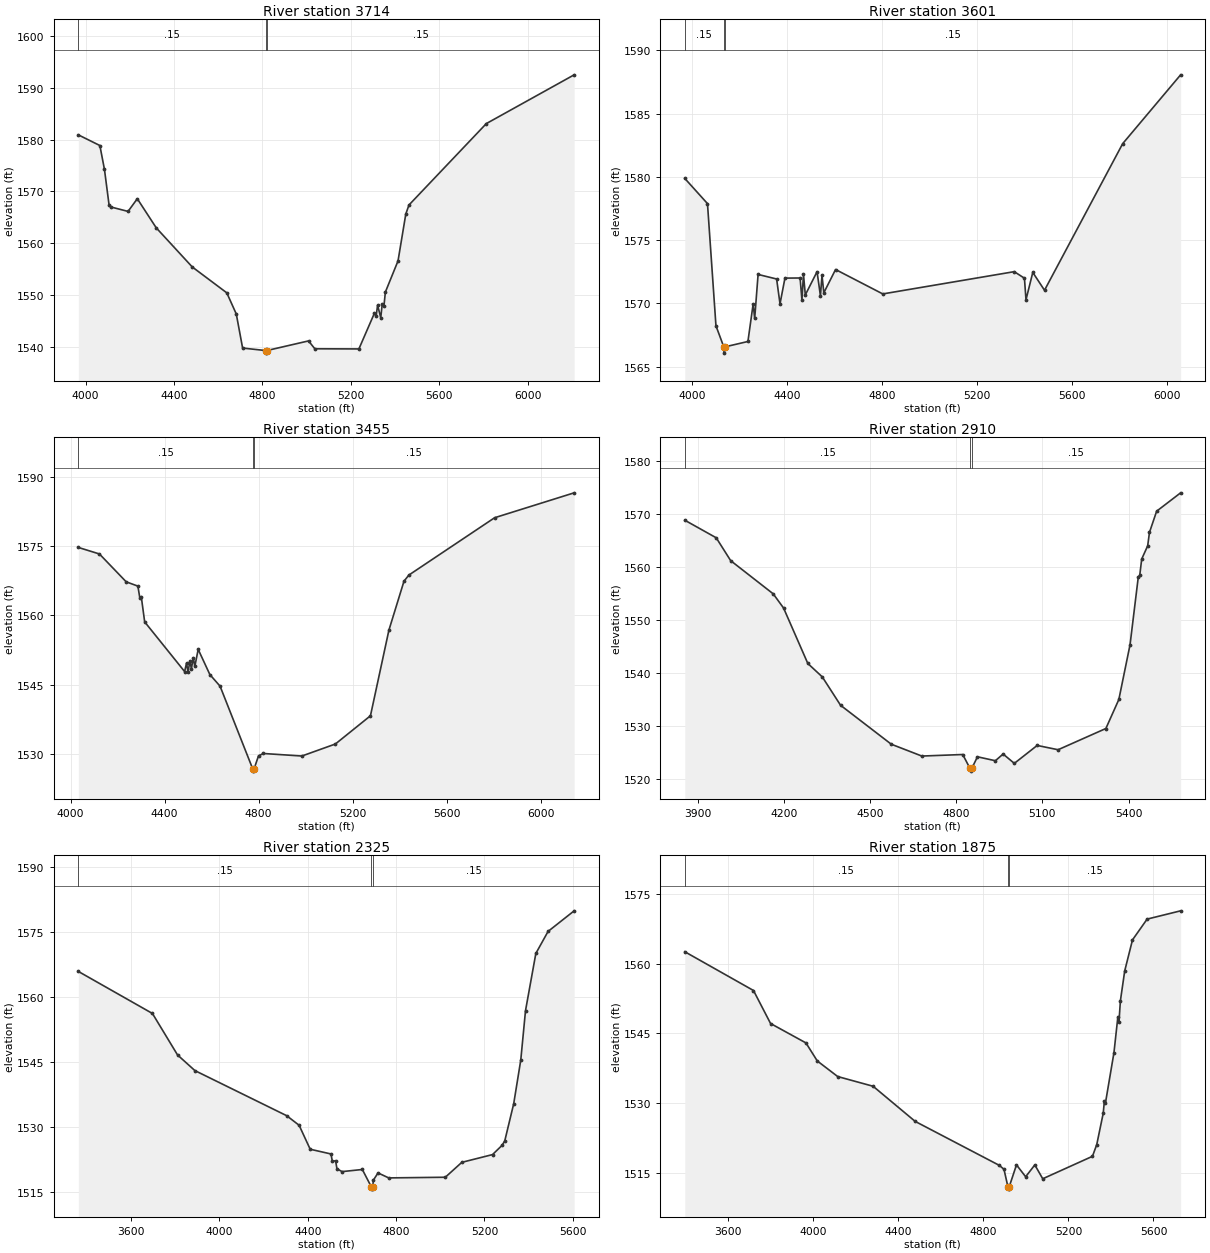
Type RM Length L Ch R = 1,3714,113,113,113
BEGIN DESCRIPTION:
UNT052 IN SNOGR 8.0
END DESCRIPTION:
XS GIS Cut Line= 3
      2834807.05     10034858.62      2835783.63     10033686.72
      2836360.88     10033261.38
#Sta/Elev= 30
  3967.5 1580.94  4064.9 1578.88  4085.7 1574.26  4106.5 1567.40  4114.3 1567.01
  4192.4 1566.15  4234.2 1568.60  4320.0 1562.97  4482.7 1555.42  4638.9 1550.42
  4681.9 1546.33  4710.5 1539.75  4814.2 1539.27  4817.0 1538.77  4820.2 1539.27
  5008.6 1541.13  5037.2 1539.61  5236.4 1539.58  5306.7 1546.49  5314.5 1545.95
  5321.0 1548.03  5335.3 1545.62  5341.8 1548.20  5349.6 1547.84  5356.2 1550.57
  5413.4 1556.59  5448.6 1565.65  5462.9 1567.39  5812.8 1583.12  6210.0 1592.54
#Mann=3,-1,0
  3967.5    0.15       0  4814.2    0.05       0  4820.2    0.15       0
Bank Sta=4814.2,4820.2
Exp/Cntr=0.3,0.1

Type RM Length L Ch R = 1,3601,146,146,146
BEGIN DESCRIPTION:
Mapping XS 4f91378a
END DESCRIPTION:
XS GIS Cut Line= 3
      2834893.48     10034913.74      2835926.02     10033698.14
      2836331.81     10033418.60
#Sta/Elev= 30
  3969.5 1579.87  4065.0 1577.88  4100.7 1568.22  4133.5 1566.56  4136.2 1566.06
  4139.5 1566.56  4235.3 1566.98  4257.3 1569.95  4263.8 1568.80  4278.1 1572.28
  4356.1 1571.92  4370.4 1569.96  4391.2 1571.99  4455.0 1572.00  4462.7 1570.24
  4469.2 1572.28  4476.9 1570.66  4526.4 1572.50  4540.6 1570.59  4547.2 1572.20
  4554.9 1570.83  4604.3 1572.67  4803.1 1570.74  5356.7 1572.50  5399.6 1571.98
  5406.1 1570.28  5434.7 1572.44  5484.1 1571.03  5813.3 1582.62  6057.2 1588.06
#Mann=3,-1,0
  3969.5    0.15       0  4133.5    0.05       0  4139.5    0.15       0
Bank Sta=4133.5,4139.5
Exp/Cntr=0.3,0.1

Type RM Length L Ch R = 1,3455,545,545,545
BEGIN DESCRIPTION:
UNT052 IN SNOGR 7.0
END DESCRIPTION:
XS GIS Cut Line= 3
      2835077.93     10034979.30      2836007.22     10033797.39
      2836494.42     10033436.50
#Sta/Elev= 30
  4032.7 1574.77  4122.5 1573.35  4236.4 1567.30  4286.1 1566.37  4294.2 1563.85
  4300.5 1564.09  4315.0 1558.60  4485.0 1547.81  4493.0 1549.65  4499.4 1547.74
  4507.5 1550.07  4513.8 1548.43  4521.9 1550.82  4528.3 1548.92  4542.7 1552.63
  4592.4 1547.16  4635.8 1544.64  4774.6 1526.69  4777.3 1526.19  4780.6 1526.69
  4799.4 1529.51  4820.2 1530.02  4983.8 1529.47  5126.5 1532.08  5275.7 1538.21
  5354.3 1556.82  5418.4 1567.44  5439.2 1568.77  5804.0 1581.22  6142.5 1586.63
#Mann=3,-1,0
  4032.7    0.15       0  4774.6    0.05       0  4780.6    0.15       0
Bank Sta=4774.6,4780.6
Exp/Cntr=0.3,0.1

Type RM Length L Ch R = 1,2910,585,585,585
BEGIN DESCRIPTION:
UNT052 IN SNOGR 6.0
END DESCRIPTION:
XS GIS Cut Line= 3
      2835465.86     10035286.09      2836124.51     10034528.20
      2836323.00     10033833.49
#Sta/Elev= 30
  3854.7 1568.79  3964.1 1565.48  4014.5 1561.17  4162.6 1554.92  4198.7 1552.24
  4283.1 1541.80  4333.5 1539.27  4397.1 1533.93  4573.7 1526.59  4680.1 1524.36
  4822.5 1524.65  4848.0 1522.02  4850.8 1521.52  4854.0 1522.02  4873.8 1524.22
  4936.2 1523.48  4963.2 1524.74  5002.2 1522.98  5081.8 1526.36  5154.6 1525.55
  5321.0 1529.55  5366.2 1535.02  5405.2 1545.34  5433.8 1558.06  5439.0 1558.42
  5445.8 1561.48  5466.6 1563.97  5472.8 1566.50  5497.8 1570.49  5581.3 1573.95
#Mann=3,-1,0
  3854.7    0.15       0  4848.0    0.05       0  4854.0    0.15       0
Bank Sta=4848,4854
Exp/Cntr=0.3,0.1

Type RM Length L Ch R = 1,2325,450,450,450
BEGIN DESCRIPTION:
UNT052 IN SNOGR 5.0
END DESCRIPTION:
XS GIS Cut Line= 3
      2835547.05     10035430.45      2836647.80     10034618.42
      2836954.55     10033797.42
#Sta/Elev= 30
  3361.8 1565.89  3697.2 1556.19  3810.9 1546.62  3889.3 1543.02  4304.9 1532.61
  4361.2 1530.40  4411.3 1524.87  4505.4 1523.78  4511.6 1522.07  4526.2 1522.23
  4532.4 1520.37  4555.5 1519.71  4647.3 1520.20  4688.2 1516.17  4691.0 1515.67
  4694.2 1516.17  4697.4 1517.75  4718.3 1519.41  4766.7 1518.26  5022.9 1518.41
  5097.6 1521.85  5236.7 1523.64  5279.1 1525.74  5291.9 1526.78  5332.5 1535.38
  5364.5 1545.46  5385.9 1556.84  5432.7 1570.04  5488.0 1575.12  5606.1 1579.87
#Mann=3,-1,0
  3361.8    0.15       0  4688.2    0.05       0  4694.2    0.15       0
Bank Sta=4688.2,4694.2
Exp/Cntr=0.3,0.1

Type RM Length L Ch R = 1,1875,421,421,421
BEGIN DESCRIPTION:
UNT052 IN SNOGR 4.0
END DESCRIPTION:
XS GIS Cut Line= 3
      2836250.82     10036016.88      2837116.96     10034519.17
      2837207.19     10033923.69
#Sta/Elev= 30
  3395.4 1562.56  3718.5 1554.22  3798.9 1547.12  3965.4 1542.94  4018.5 1539.07
  4114.6 1535.71  4281.2 1533.62  4479.2 1526.06  4875.4 1516.59  4896.9 1515.75
  4915.4 1511.99  4918.2 1511.49  4921.4 1511.99  4955.7 1516.71  4998.8 1514.15
  5041.9 1516.70  5079.2 1513.72  5313.1 1518.55  5333.3 1521.08  5363.7 1527.81
  5369.0 1530.38  5374.0 1529.97  5414.2 1540.85  5432.7 1548.59  5437.7 1547.41
  5444.6 1552.04  5464.8 1558.44  5501.4 1565.11  5570.2 1569.58  5727.8 1571.36
#Mann=3,-1,0
  3395.4    0.15       0  4915.4    0.05       0  4921.4    0.15       0
Bank Sta=4915.4,4921.4
Exp/Cntr=0.3,0.1

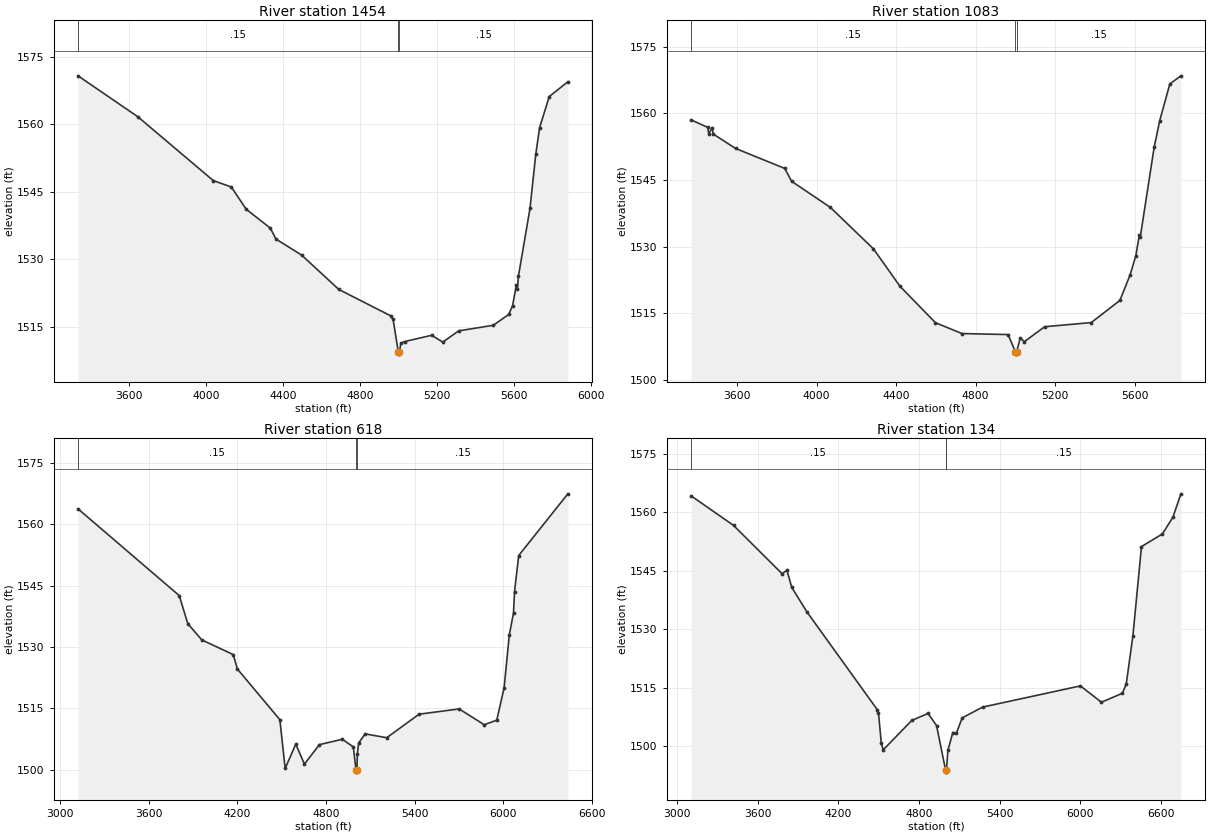
Type RM Length L Ch R = 1,1454,371,371,371
BEGIN DESCRIPTION:
UNT052 IN SNOGR 3.0
END DESCRIPTION:
XS GIS Cut Line= 3
      2836548.54     10036368.79      2837243.27     10035033.45
      2837270.30     10033997.36
#Sta/Elev= 30
  3335.6 1570.72  3644.8 1561.68  4037.1 1547.50  4131.1 1546.06  4208.3 1541.13
  4333.3 1536.95  4363.0 1534.51  4495.7 1530.97  4689.0 1523.34  4960.6 1517.44
  4970.6 1516.68  4997.6 1509.50  5000.4 1509.00  5003.6 1509.50  5010.6 1511.40
  5030.6 1511.79  5170.7 1513.18  5228.7 1511.67  5310.7 1514.16  5490.8 1515.40
  5570.8 1517.82  5590.8 1519.78  5610.5 1524.41  5615.5 1523.46  5620.8 1526.24
  5680.9 1541.32  5710.9 1553.34  5730.9 1559.23  5780.9 1566.13  5877.3 1569.39
#Mann=3,-1,0
  3335.6    0.15       0  4997.6    0.05       0  5003.6    0.15       0
Bank Sta=4997.6,5003.6
Exp/Cntr=0.3,0.1

Type RM Length L Ch R = 1,1083,465,465,465
BEGIN DESCRIPTION:
UNT052 IN SNOGR 2.0
END DESCRIPTION:
XS GIS Cut Line= 3
      2836945.53     10036242.46      2837622.21     10034916.16
      2837433.11     10033961.66
#Sta/Elev= 30
  3369.7 1558.54  3452.8 1556.86  3458.4 1555.40  3475.1 1556.82  3480.7 1555.36
  3592.8 1552.12  3839.8 1547.63  3875.2 1544.71  4069.6 1538.85  4286.3 1529.52
  4419.6 1521.10  4597.5 1512.92  4730.8 1510.47  4963.1 1510.24  4999.7 1506.34
  5002.4 1505.84  5005.7 1506.34  5024.2 1509.49  5044.6 1508.64  5146.6 1512.00
  5381.0 1512.94  5525.0 1517.92  5576.2 1523.66  5605.3 1528.02  5622.3 1532.56
  5627.4 1532.19  5697.1 1552.36  5724.8 1558.31  5776.0 1566.63  5831.7 1568.45
#Mann=3,-1,0
  3369.7    0.15       0  4999.7    0.05       0  5005.7    0.15       0
Bank Sta=4999.7,5005.7
Exp/Cntr=0.3,0.1

Type RM Length L Ch R = 1,618,484,484,484
BEGIN DESCRIPTION:
UNT052 IN SNOGR 1.5
END DESCRIPTION:
XS GIS Cut Line= 4
      2837053.83     10036576.22      2838082.35     10034807.89
      2838127.46     10034546.24      2837443.68     10033808.48
#Sta/Elev= 30
  3120.5 1563.74  3805.9 1542.56  3863.8 1535.72  3958.6 1531.74  4172.1 1528.15
  4199.4 1524.65  4487.4 1512.26  4523.2 1500.35  4595.0 1506.30  4653.7 1501.43
  4755.5 1506.17  4910.3 1507.49  4984.8 1505.61  5003.3 1499.96  5006.0 1499.46
  5009.3 1499.96  5012.1 1503.92  5020.6 1506.55  5065.0 1508.80  5211.0 1507.86
  5430.4 1513.61  5701.7 1514.89  5871.4 1511.03  5956.3 1512.15  6006.1 1520.05
  6041.3 1532.99  6069.6 1538.31  6076.5 1543.50  6104.8 1552.34  6437.6 1567.41
#Mann=3,-1,0
  3120.5    0.15       0  5003.3    0.05       0  5009.3    0.15       0
Bank Sta=5003.3,5009.3
Exp/Cntr=0.3,0.1

Type RM Length L Ch R = 1,134,0,0,0
BEGIN DESCRIPTION:
UNT052 IN SNOGR 1.0
END DESCRIPTION:
XS GIS Cut Line= 4
      2837092.43     10036623.24      2838387.08     10035111.69
      2838349.80     10034779.56      2837505.88     10033762.78
#Sta/Elev= 30
  3104.3 1564.17  3419.8 1556.60  3782.0 1544.17  3817.1 1545.13  3853.4 1540.69
  3966.4 1534.39  4491.1 1509.27  4498.8 1508.57  4519.6 1500.80  4533.9 1499.00
  4746.8 1506.56  4867.6 1508.35  4931.2 1505.26  4998.5 1493.80  5001.2 1493.30
  5004.5 1493.80  5015.7 1498.87  5052.0 1503.45  5079.4 1503.37  5122.3 1507.22
  5273.6 1509.98  6002.0 1515.42  6158.2 1511.23  6314.5 1513.53  6343.1 1515.90
  6392.6 1528.23  6456.4 1551.16  6612.7 1554.41  6690.8 1558.72  6750.1 1564.69
#Mann=3,-1,0
  3104.3    0.15       0  4998.5    0.05       0  5004.5    0.15       0
Bank Sta=4998.5,5004.5
Exp/Cntr=0.3,0.1

Chan Stop Cuts=-1