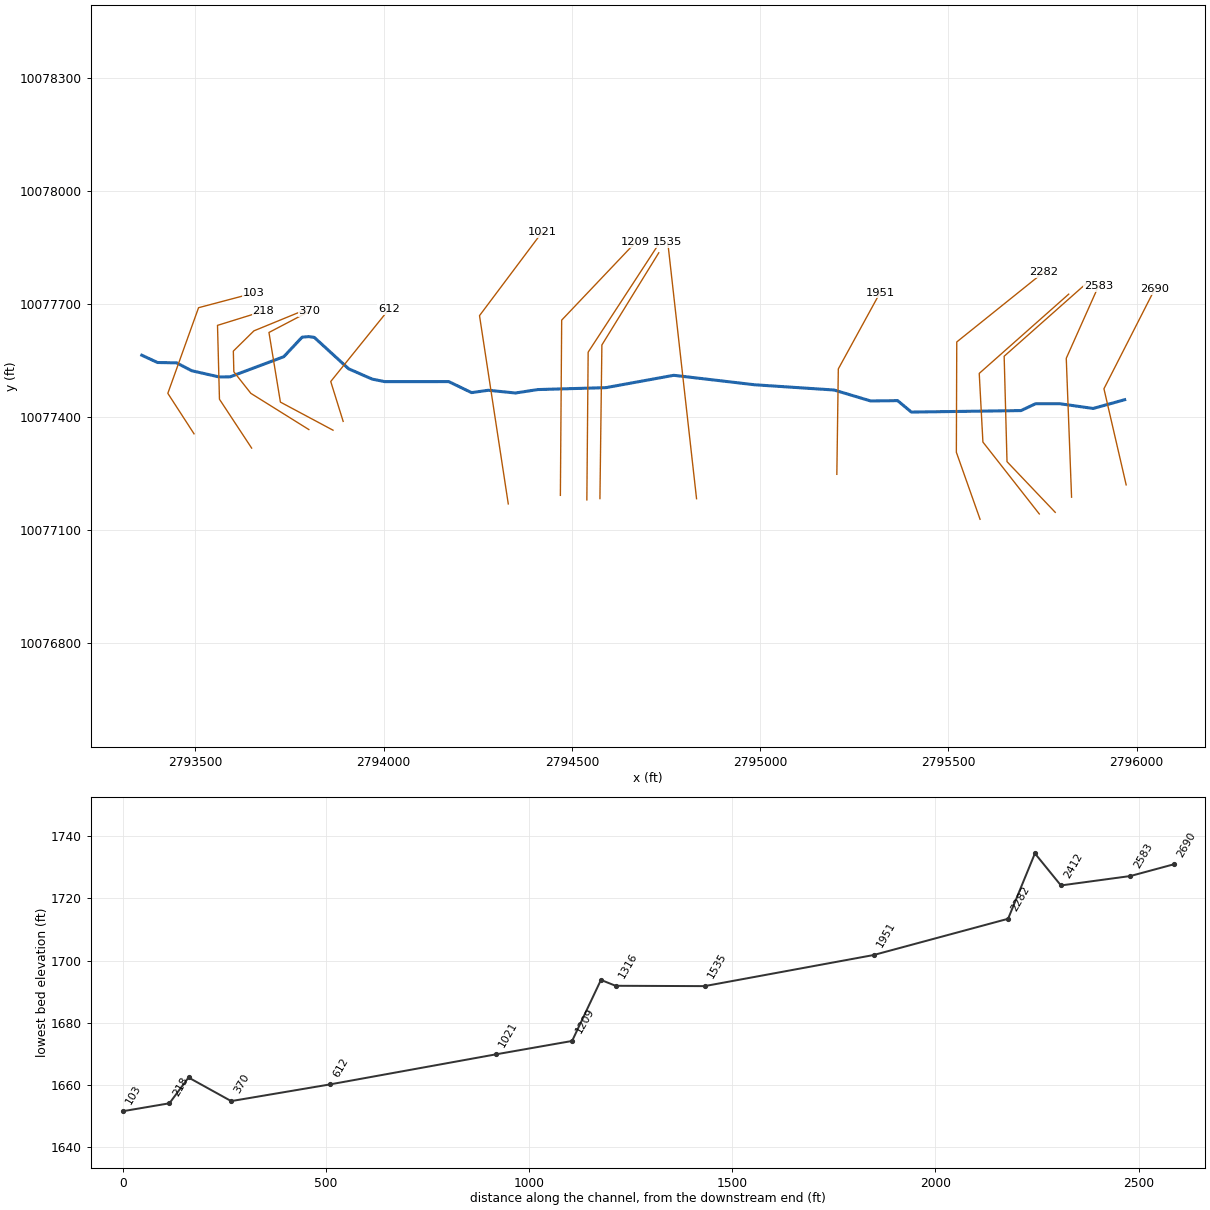
--- UNT053 IN NNOGR.prj (project) ---

Proj Title=UNT053 IN NNOGR Base Level Engineering
Current Plan=p01
Default Exp/Contr=0.3,0.1
English Units
Geom File=g01
Flow File=f01
Plan File=p01
Y Axis Title=Elevation
X Axis Title(PF)=Main Channel Distance
X Axis Title(XS)=Station
BEGIN DESCRIPTION:
UNT053 IN NNOGR
END DESCRIPTION:
DSS Export Rating Curves= 0
DSS Export Rating Curve Sorted= 0
DSS Export Volume Flow Curves= 0
DXF OffsetX= 0
DXF OffsetY= 0
DXF ScaleX= 1
DXF ScaleY= 10

--- UNT053 IN NNOGR.p01 (plan) ---

Plan Title=Multiple Run
Short Identifier=Multiple
Geom File=g01
Flow File=f01
Subcritical Flow
K Sum by GR= 0
Std Step Tol= 0.01
Critical Tol= 0.01
Num of Std Step Trials= 20
Max Error Tol= 0.3
Flow Tol Ratio= 0.001
Split Flow NTrial= 30
Split Flow Tol= 0.02
Split Flow Ratio= 0.02
Log Output Level= 0
Friction Slope Method= 1
Unsteady Friction Slope Method= 2
Unsteady Bridges Friction Slope Method= 1
Parabolic Critical Depth
Global Vel Dist=  1 , 1 , 1
Global Log Level= 0
CheckData=True
Encroach Param= -1, 0, 0, 0
BEGIN DESCRIPTION:
Multiple Run
END DESCRIPTION:

--- UNT053 IN NNOGR.f01 (steady flow) ---

Flow Title=Multiple
Program Version=4.10
Number of Profiles= 7
Profile Names=10-year,25-year,50-year,1pct_min,100-year,1pct_plu,500-year
River Rch & RM=UNT053 IN NNOGR,Reach-1         ,2690
     191     252     300     263     356     481     500
Boundary for River Rch & Prof#=UNT053 IN NNOGR,Reach-1         , 1
Up Type= 0
Dn Type= 3
Dn Slope=0.022
Boundary for River Rch & Prof#=UNT053 IN NNOGR,Reach-1         , 2
Up Type= 0
Dn Type= 3
Dn Slope=0.022
Boundary for River Rch & Prof#=UNT053 IN NNOGR,Reach-1         , 3
Up Type= 0
Dn Type= 3
Dn Slope=0.022
Boundary for River Rch & Prof#=UNT053 IN NNOGR,Reach-1         , 4
Up Type= 0
Dn Type= 3
Dn Slope=0.022
Boundary for River Rch & Prof#=UNT053 IN NNOGR,Reach-1         , 5
Up Type= 0
Dn Type= 3
Dn Slope=0.022
Boundary for River Rch & Prof#=UNT053 IN NNOGR,Reach-1         , 6
Up Type= 0
Dn Type= 3
Dn Slope=0.022
Boundary for River Rch & Prof#=UNT053 IN NNOGR,Reach-1         , 7
Up Type= 0
Dn Type= 3
Dn Slope=0.022
DSS Import GetInterval= 0
DSS Import GetPeak= 0
DSS Import FillOption= 0

--- UNT053 IN NNOGR.g01 (geometry) ---

Geom Title=Existing Conditions
Program Version=4.10

River Reach=UNT053 IN NNOGR ,Reach-1
Reach XY= 30
      2795968.22     10077445.74      2795884.34     10077422.55
       2795795.8     10077435.14      2795731.57     10077435.14
      2795692.94     10077416.91      2795401.75     10077412.95
       2795365.3     10077443.33      2795293.59     10077442.47
      2795196.46     10077471.55      2794985.52     10077485.44
      2794770.68     10077510.61      2794590.48     10077477.81
      2794409.81     10077472.73       2794350.2     10077463.62
      2794278.39     10077470.87      2794233.65     10077464.62
      2794173.21     10077493.83       2794003.5     10077493.77
      2793969.65     10077500.55      2793907.15      10077527.9
      2793816.07     10077611.27      2793801.25      10077613.4
      2793783.67     10077611.88      2793735.06     10077560.02
      2793592.31     10077506.54      2793563.66      10077506.2
      2793490.57     10077522.69      2793450.29      10077543.7
      2793399.77     10077544.56      2793357.98     10077563.93

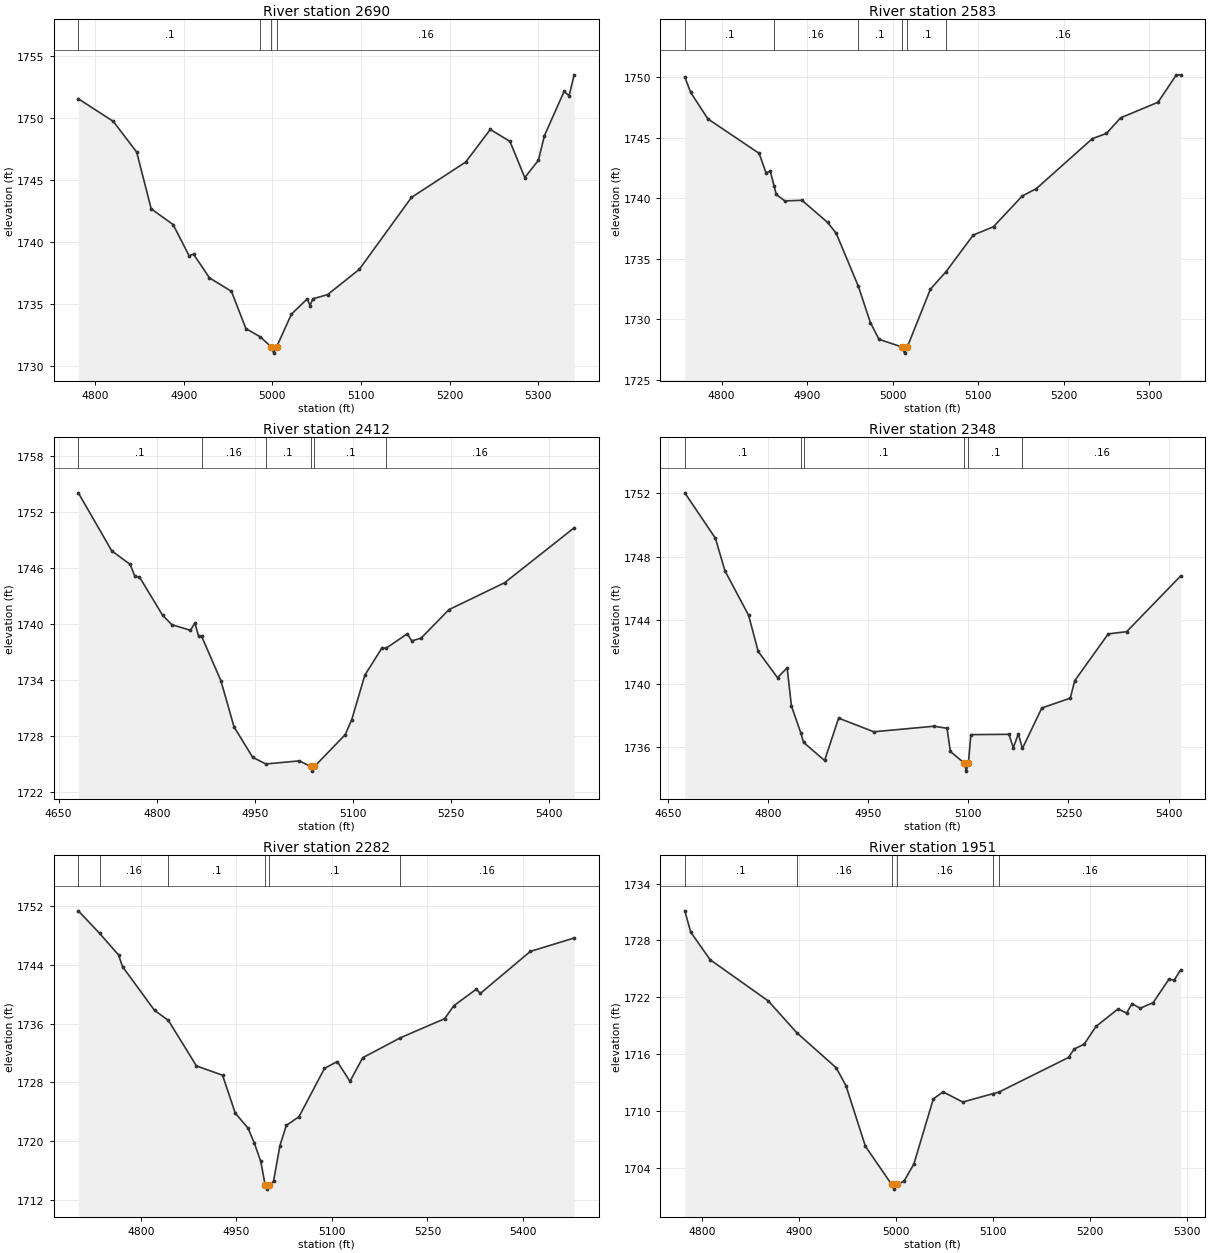
Type RM Length L Ch R = 1 ,2690    ,107,107,107
BEGIN DESCRIPTION:
UNT053 IN NNOGR 6.0
END DESCRIPTION:
XS GIS Cut Line= 3
       2795972.2     10077219.59      2795913.16     10077474.83
      2796048.16     10077739.63
#Sta/Elev= 30
  4781.1 1751.52  4820.6 1749.69  4846.9 1747.22  4863.3 1742.64    4888 1741.37
    4906 1738.86  4911.1 1738.98    4929 1737.07  4953.8 1735.98  4970.1 1732.98
  4986.4 1732.31  4998.7  1731.5  5001.4    1731  5004.7  1731.5  5021.4 1734.14
  5039.3 1735.38  5042.4 1734.84  5045.6 1735.38  5062.2 1735.72    5098 1737.76
  5156.8 1743.56  5217.9 1746.41  5245.7 1749.04  5267.9 1748.08  5284.6 1745.16
    5300 1746.56  5306.8 1748.55    5329 1752.12  5334.6 1751.76  5340.3 1753.45
#Mann= 4 ,-1 , 0
  4781.1      .1       0  4986.4     .16       0  4998.7     .07       0
  5004.7     .16       0
Bank Sta=4998.7,5004.7
XS Rating Curve= 0 ,0
Exp/Cntr=0.3,0.1

Type RM Length L Ch R = 1 ,2583    ,171,171,171
BEGIN DESCRIPTION:
Mapping XS 2473ee9a
END DESCRIPTION:
XS GIS Cut Line= 3
       2795827.2     10077186.89       2795813.1     10077555.79
      2795898.82     10077747.86
#Sta/Elev= 30
  4757.1    1750  4763.9 1748.74    4784 1746.55    4844  1743.7    4852  1742.1
    4857 1742.24  4861.6 1740.97    4864 1740.31    4874 1739.78    4894 1739.83
  4924.1    1738  4934.1  1737.1  4959.9 1732.74  4974.1 1729.72  4984.1 1728.36
  5011.1 1727.72  5013.9 1727.22  5017.1 1727.72  5044.2  1732.5  5062.4 1733.94
  5094.2 1736.96  5117.9 1737.65  5151.6 1740.19  5167.8 1740.78  5233.5 1744.92
  5249.9 1745.34  5266.4 1746.63  5310.2 1747.92  5331.6 1750.18  5336.6 1750.18
#Mann= 6 ,-1 , 0
  4757.1      .1       0  4861.6     .16       0  4959.9      .1       0
  5011.1     .07       0  5017.1      .1       0  5062.4     .16       0
Bank Sta=5011.1,5017.1
XS Rating Curve= 0 ,0
Exp/Cntr=0.3,0.1

Type RM Length L Ch R = 1 ,2412    ,64,64,64
BEGIN DESCRIPTION:
Mapping XS 5d444a75
END DESCRIPTION:
XS GIS Cut Line= 4
       2795783.8     10077146.72      2795655.76     10077281.27
      2795648.17     10077561.21      2795867.32     10077755.41
#Sta/Elev= 30
  4680.1 1754.04  4731.2 1747.82  4759.4 1746.36  4766.7 1745.07  4773.6 1745.02
  4809.1  1740.9  4823.3 1739.89  4851.6  1739.3  4858.5 1740.08  4864.1 1738.66
  4868.7 1738.66  4898.3 1733.87  4918.3 1728.94  4946.9 1725.67  4966.9 1724.96
  5018.4 1725.29  5035.4 1724.69  5038.1 1724.19  5041.4 1724.69  5088.4  1728.1
  5098.4 1729.71  5118.4 1734.47  5144.6  1737.4    5151 1737.38  5183.5 1738.92
  5190.2 1738.16  5204.4 1738.45  5247.1 1741.51  5332.4  1744.4  5438.7 1750.29
#Mann= 6 ,-1 , 0
  4680.1      .1       0  4868.7     .16       0  4966.9      .1       0
  5035.4     .07       0  5041.4      .1       0    5151     .16       0
Bank Sta=5035.4,5041.4
XS Rating Curve= 0 ,0
Exp/Cntr=0.3,0.1

Type RM Length L Ch R = 1 ,2348    ,66,66,66
BEGIN DESCRIPTION:
Mapping XS c719b8df
END DESCRIPTION:
XS GIS Cut Line= 4
      2795741.48     10077142.39      2795591.74     10077333.35
      2795581.98     10077515.64      2795819.63     10077726.16
#Sta/Elev= 30
  4675.3 1752.04  4721.1 1749.18  4735.5 1747.12  4770.8 1744.33  4785.3 1742.04
  4814.2 1740.39  4828.6 1741.01    4835 1738.61  4849.1 1736.91  4853.2 1736.31
  4884.7 1735.17  4905.7 1737.84  4958.4 1736.98  5048.5 1737.33  5068.1  1737.2
  5073.1 1735.74  5094.1    1735  5096.8  1734.5  5100.1    1735  5103.8  1736.8
  5160.7 1736.82  5167.4 1735.98  5174.9 1736.85    5181 1735.93  5210.1 1738.48
  5252.7  1739.1  5259.4  1740.2  5309.6 1743.15  5337.2 1743.29    5418  1746.8
#Mann= 6 ,-1 , 0
  4675.3      .1       0  4849.1     .16       0  4853.2      .1       0
  5094.1     .07       0  5100.1      .1       0    5181     .16       0
Bank Sta=5094.1,5100.1
XS Rating Curve= 0 ,0
Exp/Cntr=0.3,0.1

Type RM Length L Ch R = 1 ,2282    ,331,331,331
BEGIN DESCRIPTION:
UNT053 IN NNOGR 5.0
END DESCRIPTION:
XS GIS Cut Line= 4
      2795584.15     10077128.28      2795521.22     10077306.22
       2795522.3     10077599.19      2795753.42     10077784.74
#Sta/Elev= 30
  4702.1 1751.37  4735.4 1748.31  4765.2 1745.36  4771.5 1743.76  4821.7 1737.81
  4843.4 1736.44  4887.5 1730.24  4928.4 1728.98  4948.4 1723.81  4968.4 1721.77
  4978.4 1719.71  4988.4 1717.23  4995.4 1713.96  4998.1 1713.46  5001.4 1713.96
  5008.4 1714.53  5018.4 1719.36  5028.4 1722.13  5048.4 1723.33  5088.4 1729.91
  5108.4 1730.84  5128.4 1728.14  5148.4 1731.36  5207.6 1734.08    5277 1736.68
  5291.4 1738.45  5326.6 1740.69    5333 1740.12  5411.4 1745.84  5480.2 1747.67
#Mann= 6 ,-1 , 0
  4702.1      .1       0  4735.4     .16       0  4843.4      .1       0
  4995.4     .07       0  5001.4      .1       0  5207.6     .16       0
Bank Sta=4995.4,5001.4
XS Rating Curve= 0 ,0
Exp/Cntr=0.3,0.1

Type RM Length L Ch R = 1 ,1951    ,416,416,416
BEGIN DESCRIPTION:
UNT053 IN NNOGR 4.0
END DESCRIPTION:
XS GIS Cut Line= 3
      2795203.82     10077247.59      2795207.73     10077527.56
       2795318.8     10077730.34
#Sta/Elev= 30
  4782.2 1731.12  4788.3 1728.88  4808.3 1725.97  4868.3 1721.62  4897.7 1718.27
  4938.4 1714.57  4948.4 1712.68  4968.4 1706.31  4995.4 1702.29  4998.1 1701.79
  5001.4 1702.29  5008.4 1702.66  5018.4 1704.44  5038.4 1711.29  5048.4 1712.04
  5068.8 1710.97  5099.9 1711.85  5106.1 1712.02  5177.9 1715.67  5183.6 1716.55
    5194 1717.07  5206.1 1718.93  5228.9 1720.78  5237.6 1720.34  5243.3 1721.33
  5251.7 1720.85  5265.1 1721.45  5281.2 1723.89  5286.9 1723.84  5293.4 1724.89
#Mann= 6 ,-1 , 0
  4782.2      .1       0  4897.7     .16       0  4995.4     .07       0
  5001.4     .16       0  5099.9      .1       0  5106.1     .16       0
Bank Sta=4995.4,5001.4
XS Rating Curve= 0 ,0
Exp/Cntr=0.3,0.1

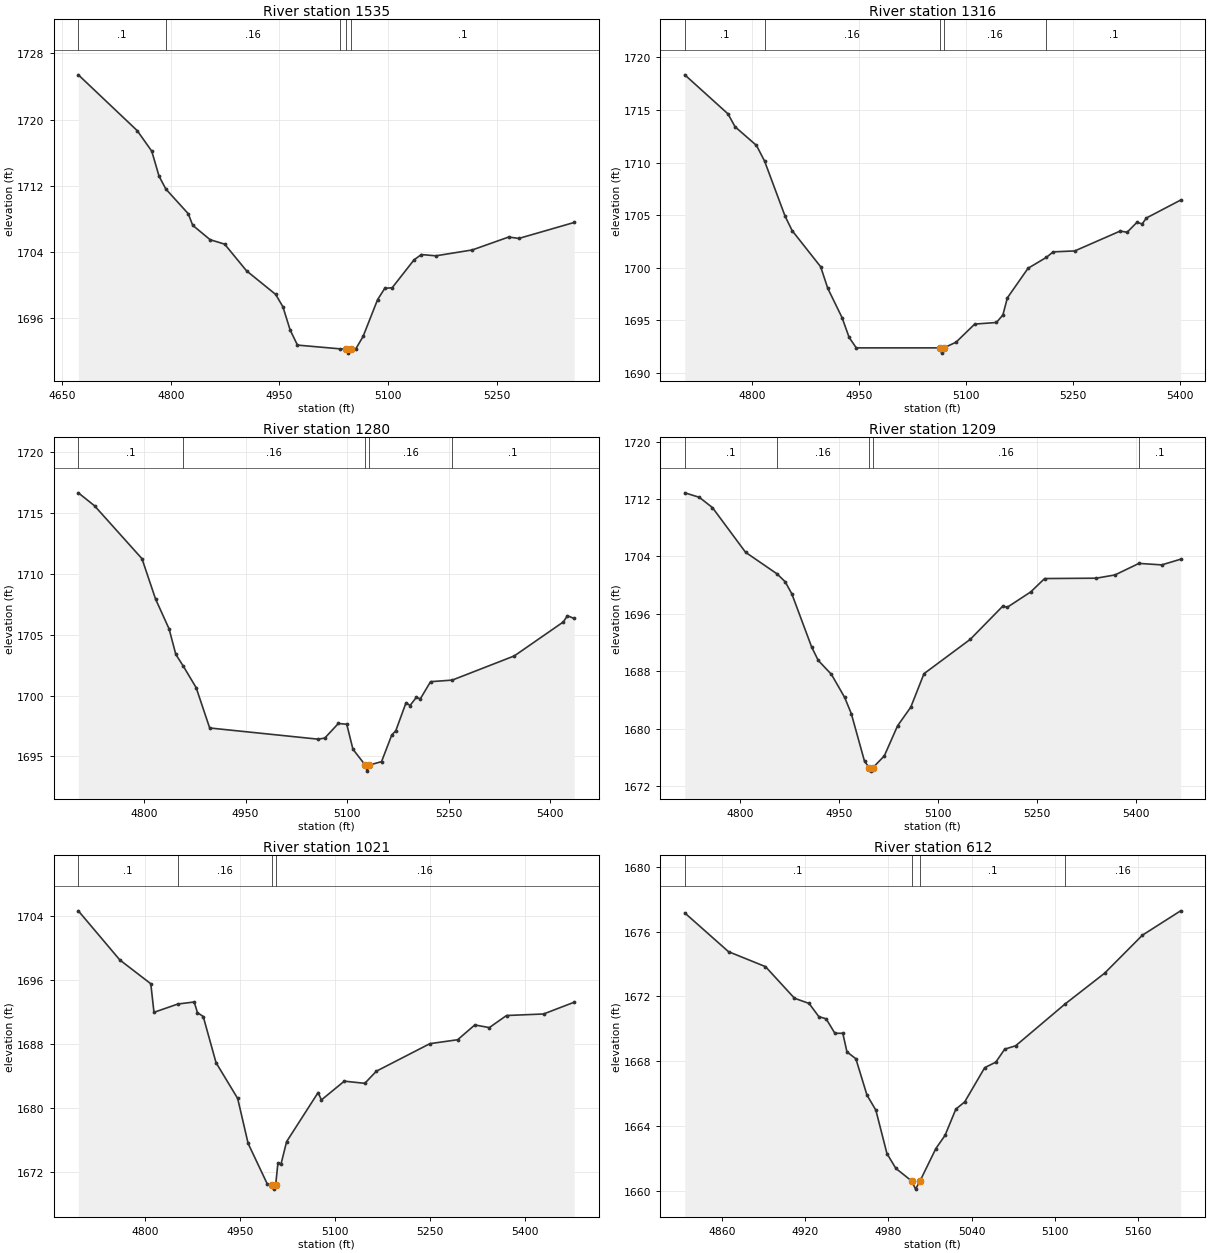
Type RM Length L Ch R = 1 ,1535    ,219,219,219
BEGIN DESCRIPTION:
UNT053 IN NNOGR 3.0
END DESCRIPTION:
XS GIS Cut Line= 2
      2794831.22     10077182.92      2794754.82     10077863.54
#Sta/Elev= 30
  4672.2 1725.41  4753.5 1718.67  4773.6 1716.19  4783.7 1713.16  4793.1 1711.61
    4824 1708.63  4830.2 1707.23  4854.2 1705.49  4874.3 1704.95  4904.5 1701.73
  4944.7 1698.88  4954.8 1697.38  4964.8 1694.57  4974.9 1692.75  5033.4  1692.3
  5042.3 1692.28  5045.1 1691.78  5048.3 1692.28  5055.4 1692.28  5065.5 1693.79
  5085.6 1698.25  5095.5 1699.61  5105.7 1699.68  5135.9 1703.05    5146 1703.69
  5166.1 1703.54  5216.4 1704.25  5266.7 1705.81  5280.7 1705.64  5357.1 1707.57
#Mann= 5 ,-1 , 0
  4672.2      .1       0  4793.1     .16       0  5033.4      .1       0
  5042.3     .07       0  5048.3      .1       0
Bank Sta=5042.3,5048.3
XS Rating Curve= 0 ,0
Exp/Cntr=0.3,0.1

Type RM Length L Ch R = 1 ,1316    ,36,36,36
BEGIN DESCRIPTION:
Mapping XS cd67514f
END DESCRIPTION:
XS GIS Cut Line= 3
      2794574.62     10077183.17      2794579.83     10077591.15
      2794730.89     10077835.98
#Sta/Elev= 30
  4705.3 1718.33  4765.9 1714.62  4775.9 1713.39  4805.9 1711.62  4817.2 1710.14
  4845.9 1704.92  4855.9 1703.53  4895.9  1700.1  4905.9 1698.05  4925.9 1695.27
  4935.9 1693.38  4945.9 1692.39  5062.9 1692.39  5065.6 1691.89  5068.9 1692.39
  5085.9 1692.93  5112.1 1694.65  5142.5  1694.8  5151.6 1695.51  5157.9 1697.14
  5186.9 1699.95  5212.7 1700.99  5222.1 1701.51  5252.5  1701.6  5316.3 1703.49
  5325.9 1703.37  5339.6 1704.31  5347.1 1704.17    5353 1704.73    5401 1706.43
#Mann= 5 ,-1 , 0
  4705.3      .1       0  4817.2     .16       0  5062.9     .07       0
  5068.9     .16       0  5212.7      .1       0
Bank Sta=5062.9,5068.9
XS Rating Curve= 0 ,0
Exp/Cntr=0.3,0.1

Type RM Length L Ch R = 1 ,1280    ,71,71,71
BEGIN DESCRIPTION:
Mapping XS 3d3477d6
END DESCRIPTION:
XS GIS Cut Line= 3
       2794539.9     10077179.71      2794543.37     10077572.05
      2794729.13     10077856.76
#Sta/Elev= 30
  4703.1 1716.68  4727.1 1715.61  4797.1 1711.26  4817.1 1707.95  4837.1 1705.49
  4847.1 1703.38  4857.8 1702.45  4877.1 1700.65  4897.1 1697.33  5057.1 1696.41
  5067.1  1696.5  5087.1  1697.7  5099.5 1697.64  5108.7 1695.58  5126.8 1694.28
  5129.5 1693.78  5132.8 1694.28  5150.9 1694.56    5166 1696.75    5172 1697.11
  5187.1 1699.41    5193 1699.18  5202.2 1699.84  5208.2 1699.73  5223.3 1701.14
  5255.3 1701.27    5347 1703.26  5419.5 1706.06  5425.4 1706.57  5435.4 1706.34
#Mann= 5 ,-1 , 0
  4703.1      .1       0  4857.8     .16       0  5126.8     .07       0
  5132.8     .16       0  5255.3      .1       0
Bank Sta=5126.8,5132.8
XS Rating Curve= 0 ,0
Exp/Cntr=0.3,0.1

Type RM Length L Ch R = 1 ,1209    ,188,188,188
BEGIN DESCRIPTION:
Mapping XS bf116af6
END DESCRIPTION:
XS GIS Cut Line= 3
      2794469.59      10077191.8      2794473.06     10077657.12
      2794669.21     10077863.69
#Sta/Elev= 30
  4716.8 1712.86  4738.7 1712.24  4758.7  1710.8  4808.7 1704.59  4856.4 1701.58
  4868.7 1700.48  4878.7 1698.81  4908.7 1691.41  4918.7 1689.54  4938.7 1687.59
  4958.7 1684.38  4968.7 1682.14  4988.7 1675.51  4995.7 1674.63  4998.5 1674.13
  5001.7 1674.63  5018.7 1676.26  5038.7 1680.43  5058.7 1683.03  5078.7 1687.69
  5148.7 1692.47  5197.7 1697.07    5205 1696.95  5240.2 1699.07  5261.2 1700.93
  5339.3 1700.98  5367.6 1701.43    5404 1703.04  5438.4 1702.83    5467 1703.62
#Mann= 5 ,-1 , 0
  4716.8      .1       0  4856.4     .16       0  4995.7     .07       0
  5001.7     .16       0    5404      .1       0
Bank Sta=4995.7,5001.7
XS Rating Curve= 0 ,0
Exp/Cntr=0.3,0.1

Type RM Length L Ch R = 1 ,1021    ,409,409,409
BEGIN DESCRIPTION:
UNT053 IN NNOGR 2.0
END DESCRIPTION:
XS GIS Cut Line= 3
      2794331.22     10077169.04      2794254.83     10077669.06
      2794420.53       10077890.
#Sta/Elev= 30
  4695.2 1704.61  4760.6 1698.47  4809.5 1695.49  4814.5 1691.92  4852.3 1692.96
    4878 1693.21    4883 1691.89  4892.2 1691.39  4912.4 1685.62  4946.5 1681.15
    4963 1675.52  4993.3 1670.44  5000.4 1670.31  5003.2 1669.81  5006.4 1670.31
  5009.9 1673.02    5015 1672.99  5023.7 1675.75  5073.4 1681.89  5078.5 1680.96
  5114.7 1683.31    5147 1683.04  5165.3 1684.56  5249.7    1688  5293.4 1688.49
  5320.5 1690.34  5343.4 1690.01  5370.5 1691.52  5428.9 1691.71  5477.2 1693.18
#Mann= 4 ,-1 , 0
  4695.2      .1       0  4852.3     .16       0  5000.4     .07       0
  5006.4     .16       0
Bank Sta=5000.4,5006.4
XS Rating Curve= 0 ,0
Exp/Cntr=0.3,0.1

Type RM Length L Ch R = 1 ,612     ,242,242,242
BEGIN DESCRIPTION:
Mapping XS cd002aa5
END DESCRIPTION:
XS GIS Cut Line= 3
       2793892.7     10077388.27      2793859.72     10077494.14
      2794014.27     10077685.81
#Sta/Elev= 30
  4833.4 1677.15  4864.9 1674.76  4891.5 1673.84  4912.4 1671.89  4922.9 1671.57
  4929.9 1670.76  4935.2 1670.62  4941.5 1669.73  4947.2 1669.73  4950.2 1668.58
  4956.6 1668.16  4964.6 1665.92    4971 1664.99    4979 1662.31  4985.4  1661.4
  4996.8 1660.62  4999.6 1660.12  5002.8 1660.62  5014.2 1662.62  5020.8 1663.43
  5028.6 1665.05    5035  1665.5  5049.4 1667.61  5057.4 1667.95  5063.8 1668.75
  5071.7 1668.96  5107.2 1671.53  5135.7 1673.43    5163 1675.78  5190.5 1677.28
#Mann= 4 ,-1 , 0
  4833.4      .1       0  4996.8     .07       0  5002.8      .1       0
  5107.2     .16       0
Bank Sta=4996.8,5002.8
XS Rating Curve= 0 ,0
Exp/Cntr=0.3,0.1

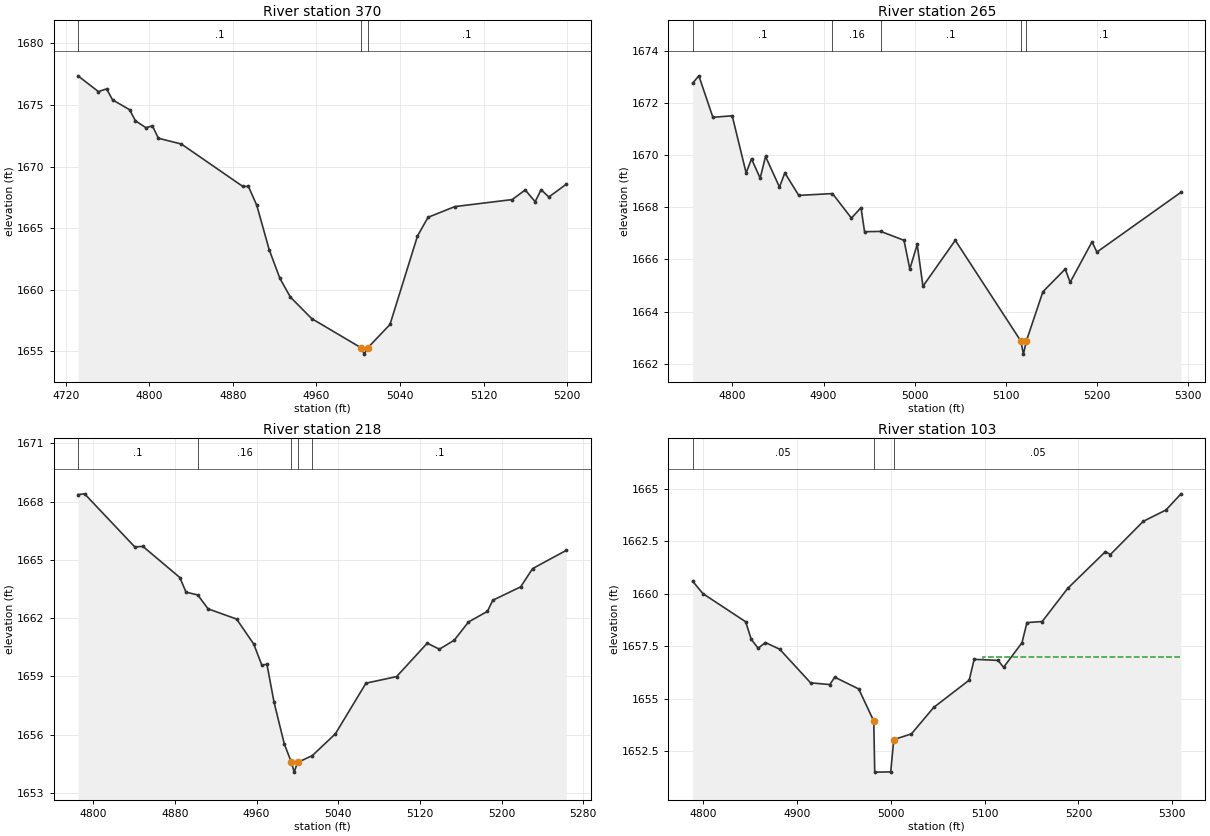
Type RM Length L Ch R = 1 ,370     ,105,105,105
BEGIN DESCRIPTION:
Mapping XS bd0ed0b8
END DESCRIPTION:
XS GIS Cut Line= 4
      2793865.78      10077364.8      2793726.04     10077439.45
      2793695.66     10077624.35      2793803.27     10077680.75
#Sta/Elev= 30
  4731.8 1677.37  4751.4 1676.09  4759.2 1676.31  4764.9 1675.42  4781.2 1674.62
  4786.8 1673.72  4796.8 1673.16  4803.1  1673.3  4808.8  1672.3  4830.8 1671.83
  4889.5 1668.39  4894.9 1668.39  4902.9 1666.86  4914.8 1663.25    4925 1660.93
  4935.1  1659.4  4955.4 1657.66    5003 1655.27  5005.8 1654.77    5009 1655.27
  5030.4 1657.18  5056.7 1664.36  5066.8 1665.88  5092.4 1666.75  5147.3 1667.32
  5159.8  1668.1  5169.3 1667.15    5175 1668.12  5182.4 1667.53  5199.1 1668.57
#Mann= 3 ,-1 , 0
  4731.8      .1       0    5003     .07       0    5009      .1       0
Bank Sta=5003,5009
XS Rating Curve= 0 ,0
Exp/Cntr=0.3,0.1

Type RM Length L Ch R = 1 ,265     ,47,47,47
BEGIN DESCRIPTION:
Mapping XS c1520343
END DESCRIPTION:
XS GIS Cut Line= 6
      2793801.55     10077366.54      2793647.54     10077462.68
       2793602.4     10077519.97      2793601.04     10077574.87
      2793655.73     10077628.69      2793794.49     10077685.57
#Sta/Elev= 30
  4756.3 1672.75  4763.1 1673.03  4778.5 1671.44  4799.7  1671.5    4815 1669.31
  4820.9 1669.85  4830.4 1669.11  4836.3 1669.94  4851.6 1668.77  4857.5 1669.31
  4872.8 1668.45  4909.8 1668.52  4930.6 1667.58  4941.1 1667.98    4945 1667.06
  4962.8 1667.07  4988.3 1666.73  4994.7 1665.63  5002.8 1666.57  5009.1 1664.97
  5044.6 1666.73  5116.6 1662.87  5119.4 1662.37  5122.6 1662.87  5140.8 1664.76
  5165.3 1665.63  5170.7 1665.12  5194.7 1666.67  5200.1 1666.28  5292.4 1668.57
#Mann= 5 ,-1 , 0
  4756.3      .1       0  4909.8     .16       0  4962.8      .1       0
  5116.6     .07       0  5122.6      .1       0
Bank Sta=5116.6,5122.6
XS Rating Curve= 0 ,0
Exp/Cntr=0.3,0.1

Type RM Length L Ch R = 1 ,218     ,115,115,115
BEGIN DESCRIPTION:
Mapping XS c76ad8cf
END DESCRIPTION:
XS GIS Cut Line= 4
      2793649.64     10077317.28       2793564.2     10077447.05
        2793559.     10077643.23      2793679.99     10077680.76
#Sta/Elev= 30
  4785.1 1668.36  4791.6  1668.4  4840.7 1665.67  4848.8 1665.69  4884.9 1664.09
  4890.9 1663.34  4902.5 1663.19  4912.5 1662.48  4940.5 1661.95  4957.2 1660.67
  4965.2 1659.58  4970.2 1659.62  4977.2 1657.66  4987.2 1655.52  4994.2 1654.57
  4996.9 1654.07  5000.2 1654.57  5014.6 1654.92  5037.2 1656.04  5067.2 1658.65
  5097.2 1658.99  5127.2 1660.71  5139.1  1660.4  5153.6 1660.86  5167.6  1661.8
  5186.2 1662.35  5191.4 1662.92  5218.7 1663.61  5230.4 1664.55  5263.4 1665.49
#Mann= 5 ,-1 , 0
  4785.1      .1       0  4902.5     .16       0  4994.2     .07       0
  5000.2     .16       0  5014.6      .1       0
Bank Sta=4994.2,5000.2
XS Rating Curve= 0 ,0
Exp/Cntr=0.3,0.1

Type RM Length L Ch R = 1 ,103     ,0,0,0
BEGIN DESCRIPTION:
UNT053 IN NNOGR 1.0
END DESCRIPTION:
XS GIS Cut Line= 4
      2793496.64     10077355.27      2793427.05     10077462.68
      2793508.65     10077690.11      2793653.93     10077728.59
#Sta/Elev= 30
  4789.3  1660.6  4800.2 1660.01  4845.7 1658.67  4851.7 1657.83    4859 1657.41
  4866.8 1657.68    4882 1657.36  4914.9 1655.76  4935.3 1655.68  4940.6 1656.03
  4966.1 1655.47  4982.1 1653.94 4983.14 1651.51 5000.17 1651.52  5003.4 1653.06
  5022.2 1653.33  5045.9 1654.59  5083.7 1655.89    5089 1656.88  5114.5 1656.83
  5120.3  1656.5  5139.9 1657.67  5145.2 1658.63  5161.4 1658.68  5188.6 1660.26
  5228.8 1662.01    5234 1661.87    5269 1663.45  5293.2 1663.99  5309.2 1664.76
#Mann= 3 , 0 , 0
  4789.3     .05       0  4982.1     .03       0  5003.4     .05       0
#XS Ineff= 2 , 0
                         5098.65         1656.97
Permanent Ineff=
       F       F
Bank Sta=4982.1,5003.4
XS Rating Curve= 0 ,0
Exp/Cntr=0.3,0.1

Chan Stop Cuts=-1
Use User Specified Reach Order=0
Composite Channel Slope=5