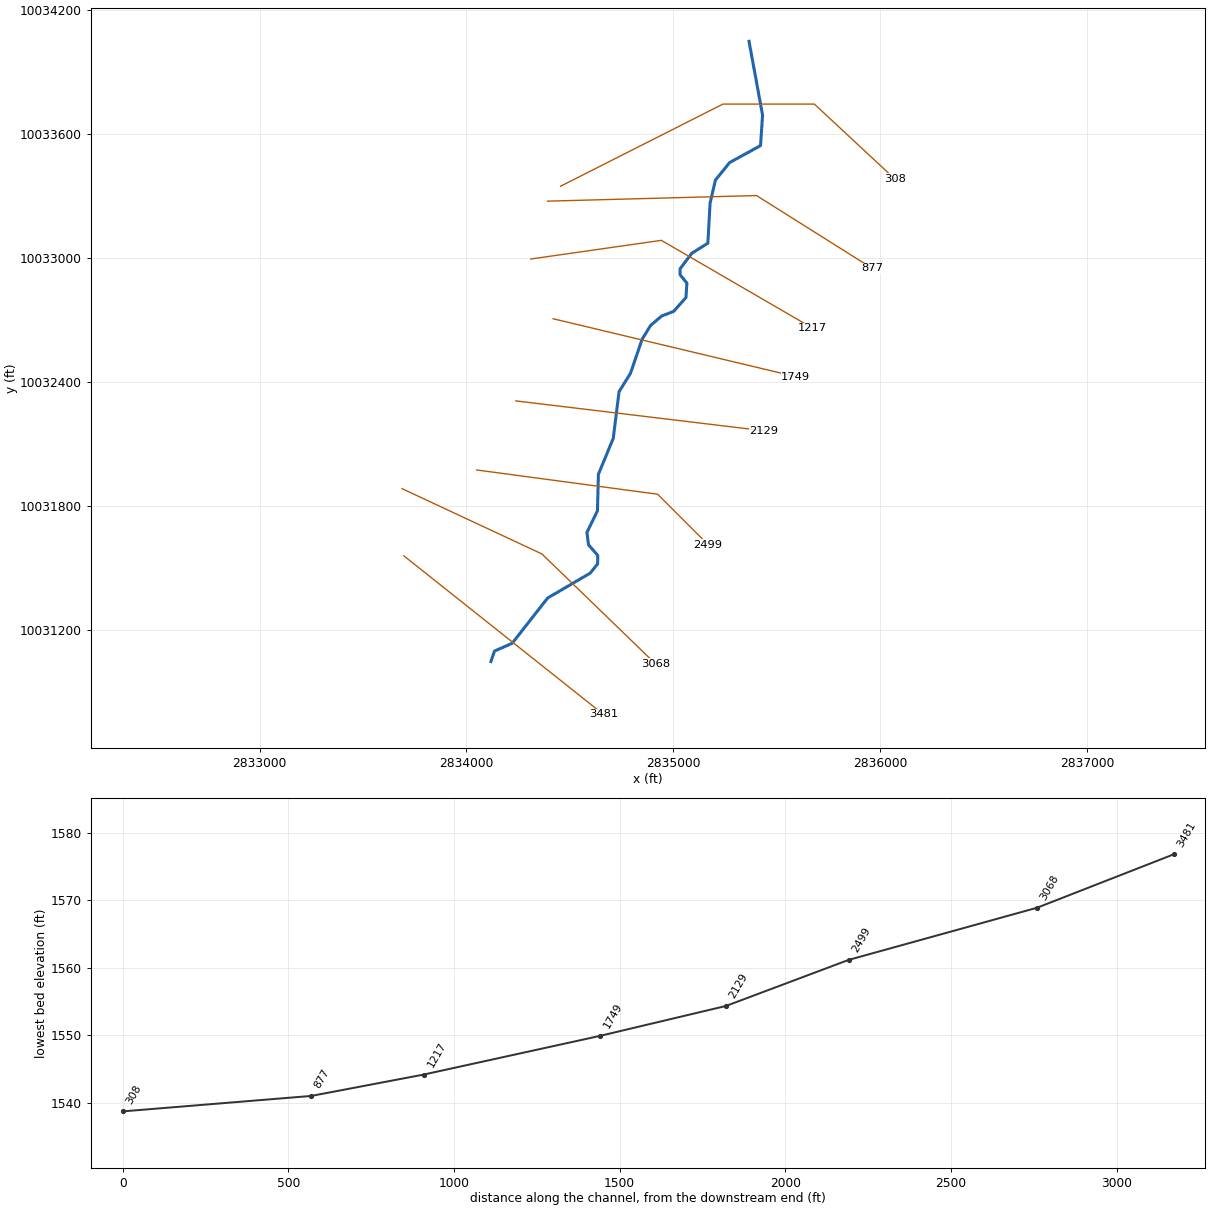
--- UNT053 IN SNOGR.prj (project) ---

Proj Title=UNT053 IN SNOGR Base Level Engineering
Current Plan=p01
Default Exp/Contr=0.3,0.1
English Units
Geom File=g01
Flow File=f01
Plan File=p01
BEGIN DESCRIPTION:
UNT053 IN SNOGR
END DESCRIPTION:

--- UNT053 IN SNOGR.p01 (plan) ---

Plan Title=Multiple Run
Short Identifier=Multiple
Geom File=g01
Flow File=f01
Subcritical Flow
K Sum by GR= 0
Std Step Tol= 0.01
Critical Tol= 0.01
Num of Std Step Trials= 20
Max Error Tol= 0.3
Flow Tol Ratio= 0.001
Split Flow NTrial= 30
Split Flow Tol= 0.02
Split Flow Ratio= 0.02
Log Output Level= 0
Friction Slope Method= 1
Unsteady Friction Slope Method= 2
Unsteady Bridges Friction Slope Method= 1
Parabolic Critical Depth
Global Vel Dist=  1 , 1 , 1
Global Log Level= 0
CheckData=True
Encroach Param= -1, 0, 0, 0
BEGIN DESCRIPTION:
Multiple Run
END DESCRIPTION:

--- UNT053 IN SNOGR.f01 (steady flow) ---

Flow Title=Multiple
Number of Profiles=7
Profile Names=10-year,25-year,50-year,1pct_min,100-year,1pct_plu,500-year
River Rch & RM= UNT053 IN SNOGR,Reach-1,3481
     912    1326    1686    1571    2124    2873    3382
Boundary for River Rch & Prof#=UNT053 IN SNOGR,Reach-1,1
Up Type=0
Dn Type=3
Dn Slope=0.005
Boundary for River Rch & Prof#=UNT053 IN SNOGR,Reach-1,2
Up Type=0
Dn Type=3
Dn Slope=0.005
Boundary for River Rch & Prof#=UNT053 IN SNOGR,Reach-1,3
Up Type=0
Dn Type=3
Dn Slope=0.005
Boundary for River Rch & Prof#=UNT053 IN SNOGR,Reach-1,4
Up Type=0
Dn Type=3
Dn Slope=0.005
Boundary for River Rch & Prof#=UNT053 IN SNOGR,Reach-1,5
Up Type=0
Dn Type=3
Dn Slope=0.005
Boundary for River Rch & Prof#=UNT053 IN SNOGR,Reach-1,6
Up Type=0
Dn Type=3
Dn Slope=0.005
Boundary for River Rch & Prof#=UNT053 IN SNOGR,Reach-1,7
Up Type=0
Dn Type=3
Dn Slope=0.005

--- UNT053 IN SNOGR.g01 (geometry) ---

Geom Title=Existing Conditions

River Reach=UNT053 IN SNOGR,Reach-1
Reach XY= 30
      2834118.44     10031048.87      2834135.77     10031099.67
      2834221.48     10031137.23      2834392.61     10031355.86
      2834597.96     10031475.83      2834634.60     10031520.83
      2834635.02     10031561.94      2834590.23     10031613.23
      2834582.74     10031673.04      2834633.56     10031777.31
      2834638.18     10031953.95      2834710.04     10032127.75
      2834738.03     10032353.11      2834793.21     10032441.81
      2834849.54     10032606.57      2834890.92     10032673.75
      2834944.54     10032719.19      2835002.09     10032741.25
      2835061.69     10032808.65      2835066.06     10032877.98
      2835033.27     10032918.21      2835033.44     10032947.38
      2835089.48     10033022.02      2835167.37     10033070.89
      2835178.21     10033264.79      2835203.95     10033375.53
      2835272.37     10033460.39      2835422.08     10033542.57
      2835432.01     10033689.83      2835366.41     10034046.56

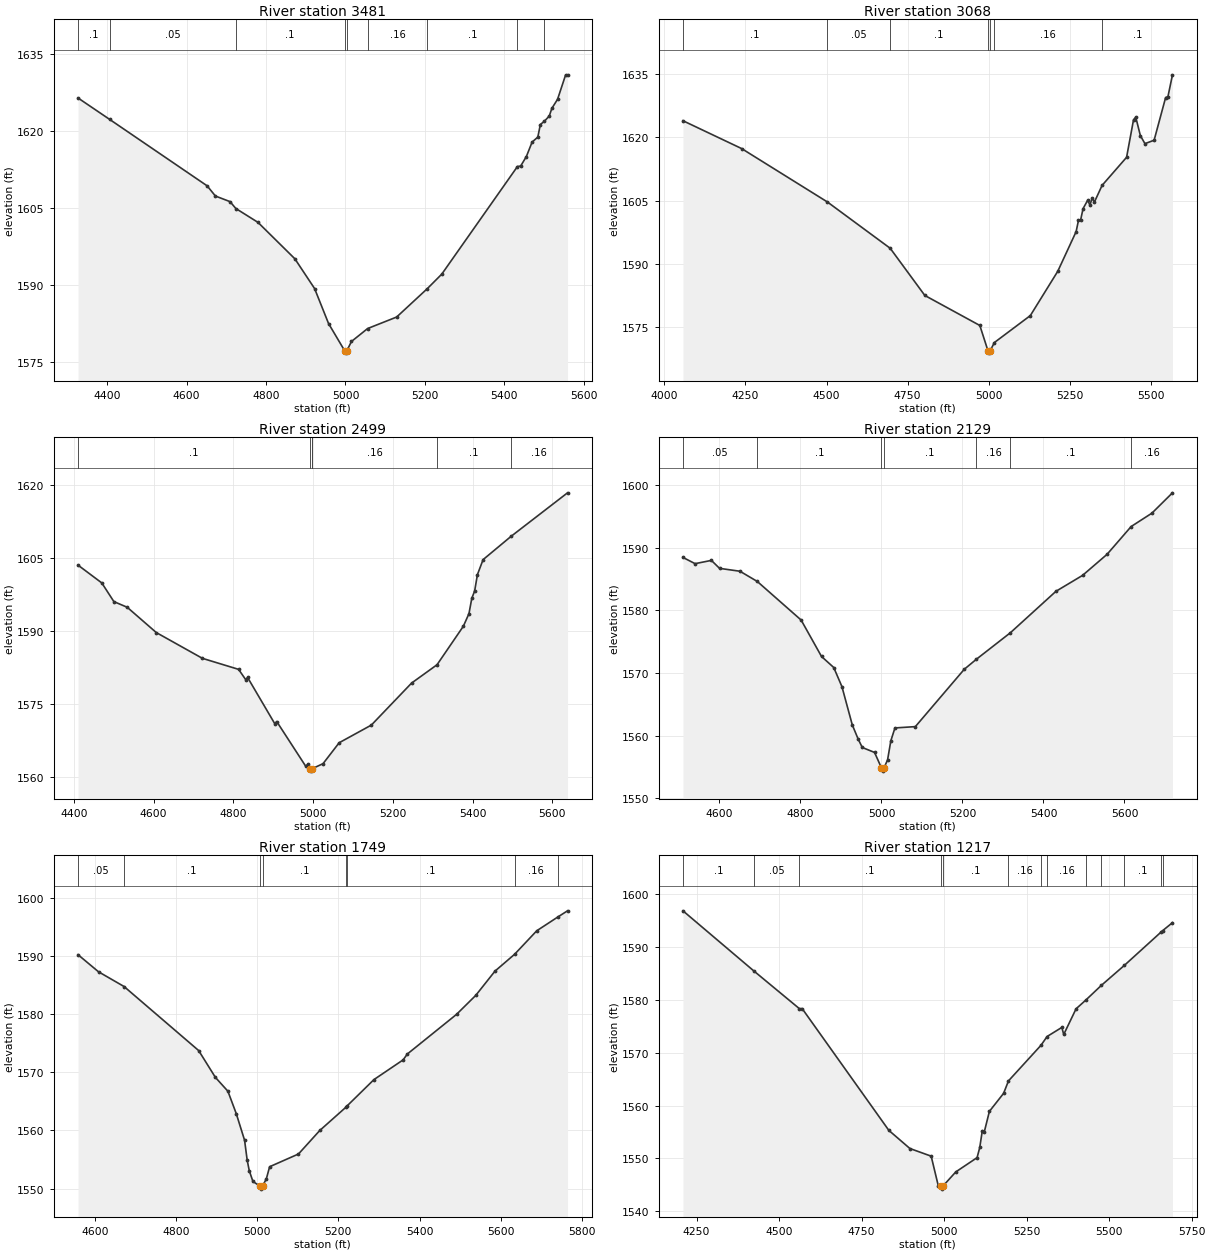
Type RM Length L Ch R = 1,3481,413,413,413
BEGIN DESCRIPTION:
UNT053 IN SNOGR 8.0
END DESCRIPTION:
XS GIS Cut Line= 2
      2833697.47     10031559.88      2834662.92     10030792.94
#Sta/Elev= 30
  4326.3 1626.52  4406.3 1622.33  4651.5 1609.41  4672.4 1607.42  4709.2 1606.33
  4723.9 1604.99  4779.6 1602.29  4872.6 1595.19  4922.2 1589.40  4957.4 1582.58
  4997.7 1577.32  5000.5 1576.82  5003.7 1577.32  5015.1 1579.09  5055.8 1581.61
  5128.9 1583.85  5206.4 1589.40  5242.6 1592.21  5433.2 1613.17  5441.3 1613.26
  5455.7 1615.12  5470.1 1617.93  5484.5 1618.90  5490.9 1621.35  5500.9 1621.98
  5513.4 1623.01  5519.8 1624.49  5534.2 1626.26  5554.6 1631.03  5559.3 1631.03
#Mann=9,-1,0
  4326.3     0.1       0  4406.3    0.05       0  4723.9     0.1       0
  4997.7    0.07       0  5003.7     0.1       0  5055.8    0.16       0
  5206.4     0.1       0  5433.2    0.16       0  5500.9     0.1       0
Bank Sta=4997.7,5003.7
Exp/Cntr=0.3,0.1

Type RM Length L Ch R = 1,3068,569,569,569
BEGIN DESCRIPTION:
UNT053 IN SNOGR 7.0
END DESCRIPTION:
XS GIS Cut Line= 3
      2833688.48     10031884.66      2834365.16     10031568.88
      2834913.36     10031038.65
#Sta/Elev= 30
  4057.3 1623.87  4238.1 1617.29  4502.7 1604.65  4696.3 1593.70  4803.1 1582.54
  4972.7 1575.44  4998.0 1569.40  5000.8 1568.90  5004.0 1569.40  5017.6 1571.41
  5128.4 1577.78  5213.0 1588.26  5269.6 1597.64  5276.8 1600.28  5283.8 1600.50
  5291.0 1603.08  5305.1 1605.05  5312.1 1603.96  5319.2 1605.56  5326.2 1604.67
  5349.6 1608.57  5425.2 1615.22  5446.6 1624.09  5453.5 1624.71  5467.7 1620.35
  5481.8 1618.45  5510.1 1619.26  5545.6 1629.36  5552.6 1629.52  5566.7 1634.73
#Mann=7,-1,0
  4057.3     0.1       0  4502.7    0.05       0  4696.3     0.1       0
  4998.0    0.07       0  5004.0     0.1       0  5017.6    0.16       0
  5349.6     0.1       0
Bank Sta=4998,5004
Exp/Cntr=0.3,0.1

Type RM Length L Ch R = 1,2499,370,370,370
BEGIN DESCRIPTION:
UNT053 IN SNOGR 6.0
END DESCRIPTION:
XS GIS Cut Line= 3
      2834049.38     10031974.88      2834924.54     10031857.59
      2835168.15     10031613.99
#Sta/Elev= 30
  4410.7 1603.54  4470.3 1599.88  4500.6 1596.04  4534.1 1594.87  4607.0 1589.67
  4722.6 1584.37  4813.4 1582.10  4831.0 1580.01  4836.0 1580.43  4903.9 1570.95
  4909.0 1571.37  4981.9 1562.15  4987.0 1562.58  4992.0 1561.67  4994.7 1561.17
  4998.0 1561.67  4998.1 1561.68  5025.2 1562.71  5065.6 1567.01  5146.3 1570.64
  5247.2 1579.28  5311.0 1583.05  5377.0 1590.97  5391.1 1593.57  5398.2 1596.72
  5405.3 1598.21  5412.3 1601.59  5426.5 1604.67  5497.0 1609.48  5638.2 1618.41
#Mann=6,-1,0
  4410.7     0.1       0  4992.0    0.07       0  4998.0     0.1       0
  4998.1    0.16       0  5311.0     0.1       0  5497.0    0.16       0
Bank Sta=4992,4998
Exp/Cntr=0.3,0.1

Type RM Length L Ch R = 1,2129,380,380,380
BEGIN DESCRIPTION:
UNT053 IN SNOGR 5.0
END DESCRIPTION:
XS GIS Cut Line= 2
      2834238.80     10032308.71      2835438.85     10032164.35
#Sta/Elev= 30
  4509.9 1588.44  4539.8 1587.45  4580.1 1587.97  4600.2 1586.70  4650.6 1586.24
  4693.4 1584.61  4801.7 1578.45  4852.0 1572.64  4882.2 1570.88  4902.4 1567.83
  4928.0 1561.72  4942.7 1559.43  4952.7 1558.12  4983.0 1557.33  5000.1 1554.85
  5002.8 1554.35  5006.1 1554.85  5015.1 1556.14  5023.2 1559.20  5033.3 1561.24
  5083.7 1561.45  5204.5 1570.60  5234.6 1572.21  5318.4 1576.43  5430.9 1583.04
  5496.6 1585.58  5557.1 1588.94  5616.5 1593.37  5667.9 1595.51  5718.6 1598.75
#Mann=7,-1,0
  4509.9    0.05       0  4693.4     0.1       0  5000.1    0.07       0
  5006.1     0.1       0  5234.6    0.16       0  5318.4     0.1       0
  5616.5    0.16       0
Bank Sta=5000.1,5006.1
Exp/Cntr=0.3,0.1

Type RM Length L Ch R = 1,1749,532,532,532
BEGIN DESCRIPTION:
UNT053 IN SNOGR 4.0
END DESCRIPTION:
XS GIS Cut Line= 2
      2834419.33     10032705.68      2835592.24     10032425.99
#Sta/Elev= 30
  4558.8 1590.22  4609.3 1587.28  4672.2 1584.75  4856.0 1573.74  4897.2 1569.13
  4928.0 1566.75  4948.6 1562.90  4969.1 1558.32  4975.5 1554.91  4980.7 1553.07
  4989.7 1551.24  5007.3 1550.42  5010.0 1549.92  5013.3 1550.42  5022.8 1551.71
  5030.8 1553.77  5101.9 1555.96  5154.3 1560.00  5218.9 1564.01  5221.7 1564.23
  5287.8 1568.75  5359.7 1572.14  5370.1 1573.15  5491.2 1579.96  5538.5 1583.22
  5586.0 1587.40  5634.1 1590.28  5688.8 1594.33  5741.4 1596.73  5764.6 1597.76
#Mann=8,-1,0
  4558.8    0.05       0  4672.2     0.1       0  5007.3    0.07       0
  5013.3     0.1       0  5218.9    0.16       0  5221.7     0.1       0
  5634.1    0.16       0  5741.4     0.1       0
Bank Sta=5007.3,5013.3
Exp/Cntr=0.3,0.1

Type RM Length L Ch R = 1,1217,340,340,340
BEGIN DESCRIPTION:
UNT053 IN SNOGR 3.0
END DESCRIPTION:
XS GIS Cut Line= 3
      2834311.06     10032994.41      2834942.59     10033084.63
      2835673.42     10032660.56
#Sta/Elev= 30
  4209.0 1596.87  4423.5 1585.50  4561.7 1578.35  4570.0 1578.37  4832.7 1555.31
  4896.4 1551.88  4960.9 1550.43  4982.5 1544.81  4989.4 1544.69  4992.2 1544.19
  4995.4 1544.69  5035.5 1547.45  5100.0 1550.15  5108.1 1552.08  5115.8 1555.25
  5121.6 1554.97  5137.3 1558.91  5180.4 1562.33  5195.1 1564.68  5293.6 1571.42
  5312.1 1573.08  5356.7 1574.80  5362.5 1573.47  5399.8 1578.32  5429.1 1579.96
  5476.1 1582.74  5546.1 1586.54  5658.6 1592.92  5662.2 1593.12  5691.9 1594.63
#Mann=13,-1,0
  4209.0     0.1       0  4423.5    0.05       0  4561.7     0.1       0
  4989.4    0.07       0  4995.4     0.1       0  5195.1    0.16       0
  5293.6     0.1       0  5312.1    0.16       0  5429.1     0.1       0
  5476.1    0.16       0  5546.1     0.1       0  5658.6    0.16       0
  5662.2     0.1       0
Bank Sta=4989.4,4995.4
Exp/Cntr=0.3,0.1

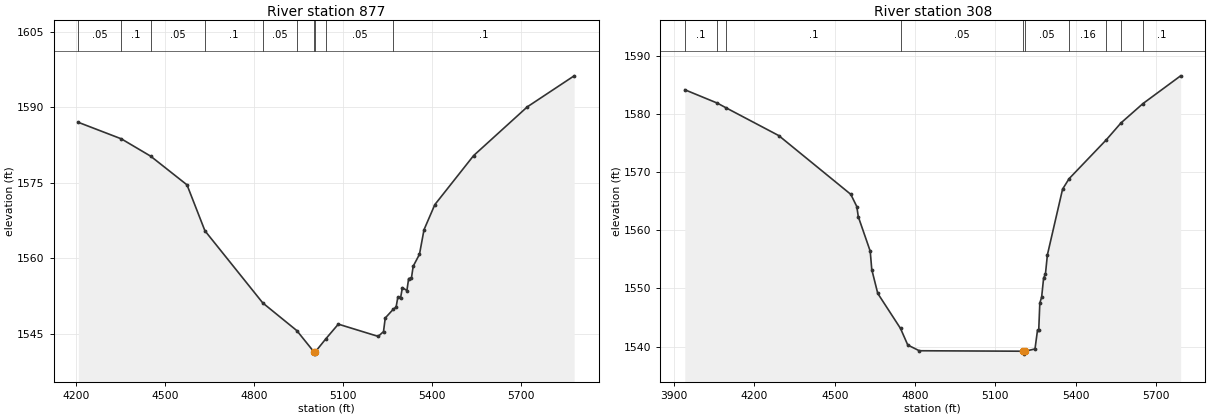
Type RM Length L Ch R = 1,877,569,569,569
BEGIN DESCRIPTION:
UNT053 IN SNOGR 2.0
END DESCRIPTION:
XS GIS Cut Line= 3
      2834392.20     10033274.09      2835402.72     10033301.16
      2835962.08     10032949.31
#Sta/Elev= 30
  4207.1 1587.02  4352.2 1583.74  4450.8 1580.31  4573.5 1574.61  4633.9 1565.50
  4829.1 1551.17  4943.7 1545.69  5000.7 1541.52  5003.4 1541.02  5006.7 1541.52
  5042.3 1544.11  5083.7 1546.97  5218.0 1544.54  5236.0 1545.49  5241.9 1548.19
  5269.1 1549.94  5278.4 1550.34  5284.3 1552.30  5293.7 1552.21  5299.6 1554.22
  5314.9 1553.64  5320.8 1556.02  5330.2 1556.13  5336.1 1558.46  5357.3 1560.84
  5372.6 1565.71  5409.1 1570.69  5539.8 1580.42  5721.0 1590.10  5878.8 1596.25
#Mann=10,-1,0
  4207.1    0.05       0  4352.2     0.1       0  4450.8    0.05       0
  4633.9     0.1       0  4829.1    0.05       0  4943.7    0.16       0
  5000.7    0.07       0  5006.7    0.16       0  5042.3    0.05       0
  5269.1     0.1       0
Bank Sta=5000.7,5006.7
Exp/Cntr=0.3,0.1

Type RM Length L Ch R = 1,308,0,0,0
BEGIN DESCRIPTION:
UNT053 IN SNOGR 1.0
END DESCRIPTION:
XS GIS Cut Line= 4
      2834455.42     10033346.29      2835240.32     10033743.26
      2835682.41     10033743.26      2836070.35     10033382.39
#Sta/Elev= 30
  3940.1 1584.13  4061.8 1581.83  4094.0 1581.03  4290.9 1576.26  4559.9 1566.17
  4582.3 1564.08  4588.0 1562.32  4632.5 1556.41  4638.3 1553.25  4660.7 1549.15
  4745.6 1543.14  4772.8 1540.29  4815.8 1539.31  5204.8 1539.23  5207.6 1538.73
  5210.8 1539.23  5247.8 1539.62  5257.3 1542.88  5261.8 1542.88  5265.8 1547.50
  5272.6 1548.51  5280.0 1551.81  5286.8 1552.47  5294.1 1555.78  5350.8 1567.06
  5375.0 1568.85  5513.0 1575.48  5569.1 1578.44  5651.1 1581.76  5791.6 1586.52
#Mann=10,-1,0
  3940.1     0.1       0  4061.8    0.05       0  4094.0     0.1       0
  4745.6    0.05       0  5204.8   0.033       0  5210.8    0.05       0
  5375.0    0.16       0  5513.0     0.1       0  5569.1    0.16       0
  5651.1     0.1       0
Bank Sta=5204.8,5210.8
Exp/Cntr=0.3,0.1

Chan Stop Cuts=-1