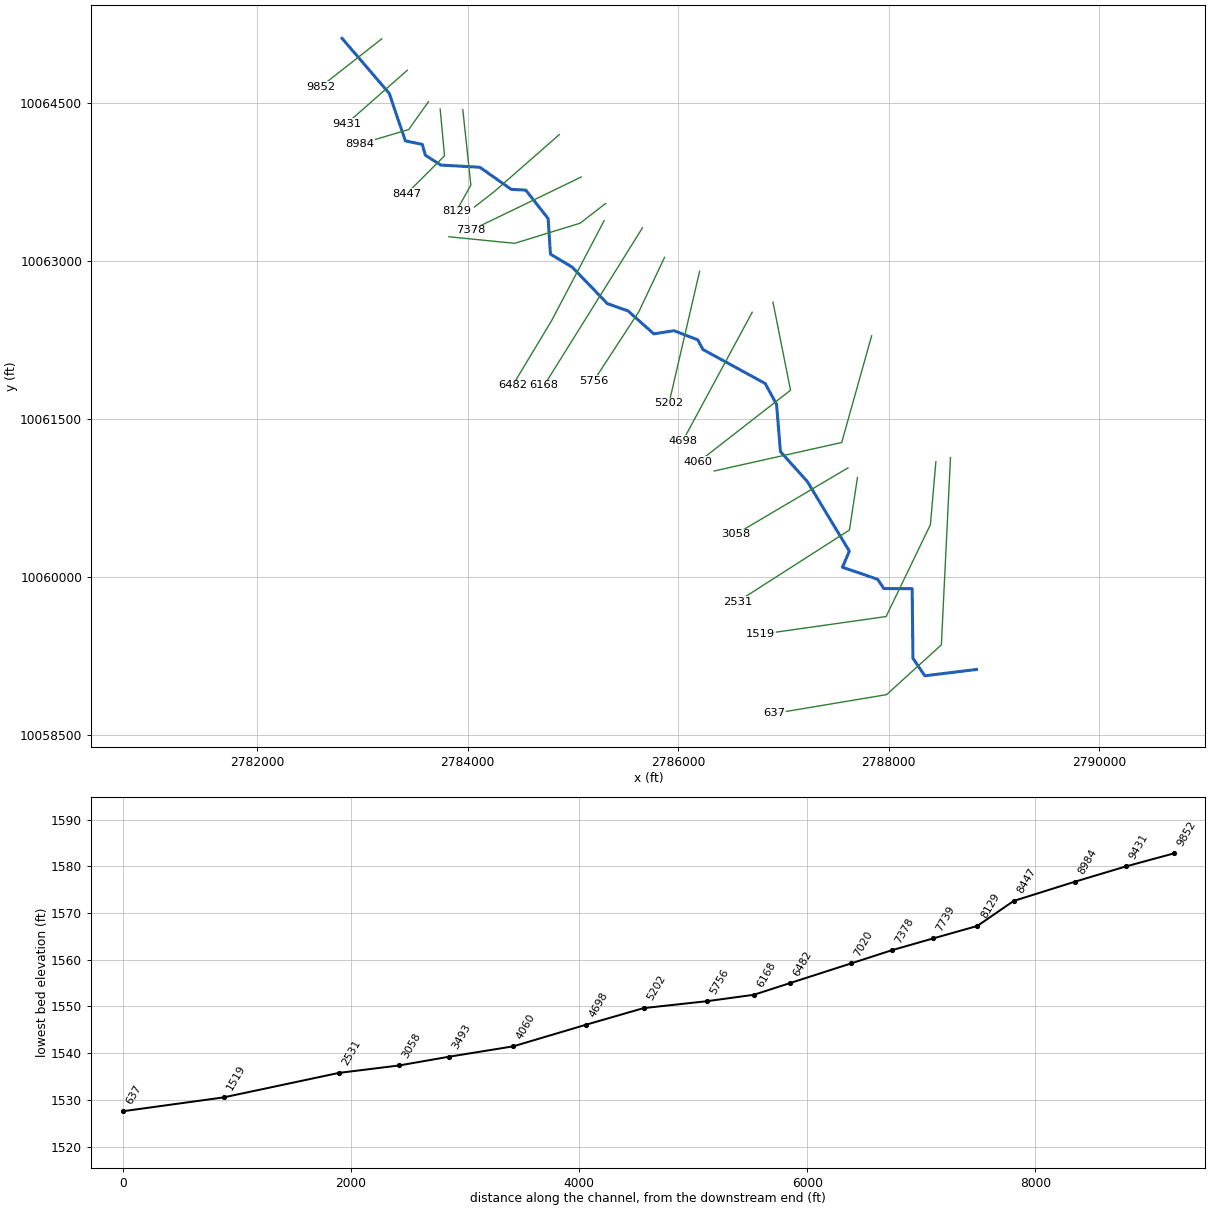
--- UNT054 IN NNOGR.prj (project) ---

Proj Title=UNT054 IN NNOGR Base Level Engineering
Current Plan=p01
Default Exp/Contr=0.3,0.1
English Units
Geom File=g01
Flow File=f01
Plan File=p01
BEGIN DESCRIPTION:
UNT054 IN NNOGR
END DESCRIPTION:

--- UNT054 IN NNOGR.p01 (plan) ---

Plan Title=Multiple Run
Short Identifier=Multiple
Geom File=g01
Flow File=f01
Subcritical Flow
K Sum by GR= 0
Std Step Tol= 0.01
Critical Tol= 0.01
Num of Std Step Trials= 20
Max Error Tol= 0.3
Flow Tol Ratio= 0.001
Split Flow NTrial= 30
Split Flow Tol= 0.02
Split Flow Ratio= 0.02
Log Output Level= 0
Friction Slope Method= 1
Unsteady Friction Slope Method= 2
Unsteady Bridges Friction Slope Method= 1
Parabolic Critical Depth
Global Vel Dist=  1 , 1 , 1
Global Log Level= 0
CheckData=True
Encroach Param= -1, 0, 0, 0
BEGIN DESCRIPTION:
Multiple Run
END DESCRIPTION:

--- UNT054 IN NNOGR.f01 (steady flow) ---

Flow Title=Multiple
Number of Profiles=7
Profile Names=10-year,25-year,50-year,1pct_min,100-year,1pct_plu,500-year
River Rch & RM= UNT054 IN NNOGR,Reach-1,9852
     258     343     410     360     487     659     688
River Rch & RM= UNT054 IN NNOGR,Reach-1,6168
     621     869    1077     975    1318    1783    1986
Boundary for River Rch & Prof#=UNT054 IN NNOGR,Reach-1,1
Up Type=0
Dn Type=3
Dn Slope=0.005
Boundary for River Rch & Prof#=UNT054 IN NNOGR,Reach-1,2
Up Type=0
Dn Type=3
Dn Slope=0.005
Boundary for River Rch & Prof#=UNT054 IN NNOGR,Reach-1,3
Up Type=0
Dn Type=3
Dn Slope=0.005
Boundary for River Rch & Prof#=UNT054 IN NNOGR,Reach-1,4
Up Type=0
Dn Type=3
Dn Slope=0.005
Boundary for River Rch & Prof#=UNT054 IN NNOGR,Reach-1,5
Up Type=0
Dn Type=3
Dn Slope=0.005
Boundary for River Rch & Prof#=UNT054 IN NNOGR,Reach-1,6
Up Type=0
Dn Type=3
Dn Slope=0.005
Boundary for River Rch & Prof#=UNT054 IN NNOGR,Reach-1,7
Up Type=0
Dn Type=3
Dn Slope=0.005

--- UNT054 IN NNOGR.g01 (geometry) ---

Geom Title=Existing Conditions

River Reach=UNT054 IN NNOGR,Reach-1
Reach XY= 30
      2782807.74     10065115.34      2783256.09     10064592.75
      2783409.30     10064140.97      2783570.45     10064107.89
      2783599.02     10064004.82      2783746.59     10063911.07
      2784117.09     10063890.40      2784415.61     10063680.11
      2784553.58     10063673.31      2784765.80     10063402.63
      2784787.81     10063064.90      2784995.04     10062941.05
      2785328.42     10062594.79      2785524.60     10062525.82
      2785770.03     10062307.40      2785962.22     10062337.68
      2786187.46     10062250.52      2786236.15     10062159.25
      2786828.08     10061835.69      2786936.48     10061637.87
      2786973.01     10061189.15      2787229.29     10060903.23
      2787627.94     10060242.46      2787561.96     10060090.11
      2787895.82     10059975.79      2787955.91     10059886.90
      2788224.64     10059886.45      2788232.32     10059224.24
      2788345.42     10059058.56      2788835.19     10059118.61

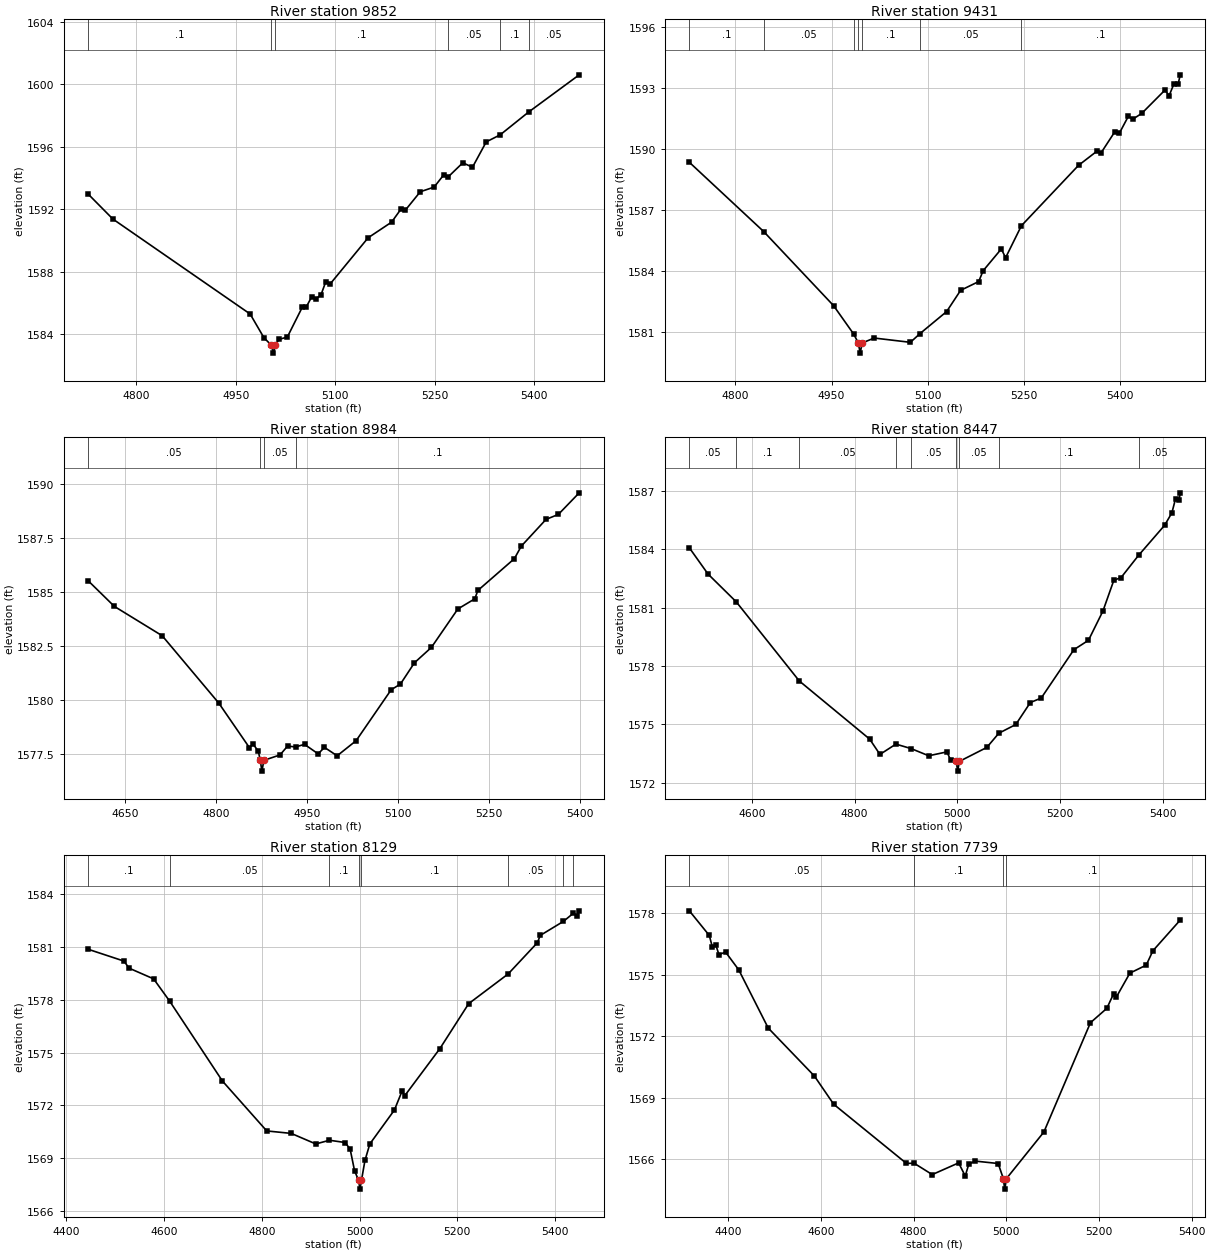
Type RM Length L Ch R = 1,9852,421,421,421
BEGIN DESCRIPTION:
UNT054 IN NNOGR 19.0
END DESCRIPTION:
XS GIS Cut Line= 2
      2783184.37     10065110.21      2782602.26     10064652.84
#Sta/Elev= 30
  4727.8 1592.96  4764.8 1591.37  4971.8 1585.28  4992.6 1583.76  5004.0 1583.27
  5006.8 1582.77  5010.0 1583.27  5015.1 1583.65  5027.9 1583.80  5050.4 1585.71
  5056.8 1585.76  5064.9 1586.40  5071.2 1586.25  5078.7 1586.51  5085.7 1587.33
  5092.0 1587.18  5149.8 1590.17  5185.1 1591.17  5199.5 1592.02  5205.9 1591.94
  5228.4 1593.12  5249.3 1593.42  5263.7 1594.20  5270.4 1594.07  5292.6 1594.98
  5307.1 1594.69  5327.9 1596.32  5348.9 1596.77  5391.7 1598.23  5468.1 1600.62
#Mann=6,-1,0
  4727.8     0.1       0  5004.0    0.07       0  5010.0     0.1       0
  5270.4    0.05       0  5348.9     0.1       0  5391.7    0.05       0
Bank Sta=5004,5010
Exp/Cntr=0.3,0.1

Type RM Length L Ch R = 1,9431,447,447,447
BEGIN DESCRIPTION:
UNT054 IN NNOGR 18.0
END DESCRIPTION:
XS GIS Cut Line= 2
      2783427.46     10064811.63      2782852.28     10064305.74
#Sta/Elev= 30
  4728.0 1589.34  4844.1 1585.94  4953.0 1582.31  4984.3 1580.92  4991.7 1580.48
  4994.5 1579.98  4997.7 1580.48  5016.5 1580.72  5072.9 1580.51  5088.0 1580.94
  5129.5 1582.02  5151.3 1583.06  5179.5 1583.49  5186.4 1584.02  5214.8 1585.09
  5221.5 1584.66  5246.2 1586.23  5335.3 1589.19  5363.8 1589.88  5370.4 1589.80
  5392.2 1590.85  5398.9 1590.76  5413.1 1591.60  5419.8 1591.45  5434.0 1591.74
  5470.1 1592.88  5476.7 1592.61  5484.3 1593.20  5490.9 1593.20  5494.0 1593.63
#Mann=7,-1,0
  4728.0     0.1       0  4844.1    0.05       0  4984.3     0.1       0
  4991.7    0.07       0  4997.7     0.1       0  5088.0    0.05       0
  5246.2     0.1       0
Bank Sta=4991.7,4997.7
Exp/Cntr=0.3,0.1

Type RM Length L Ch R = 1,8984,537,537,537
BEGIN DESCRIPTION:
UNT054 IN NNOGR 17.0
END DESCRIPTION:
XS GIS Cut Line= 3
      2783628.82     10064512.98      2783441.32     10064249.10
      2782976.02     10064110.20
#Sta/Elev= 30
  4589.9 1585.52  4632.8 1584.34  4711.7 1582.98  4805.0 1579.86  4855.4 1577.80
  4861.6 1577.96  4870.2 1577.63  4873.3 1577.21  4876.1 1576.71  4879.3 1577.21
  4905.9 1577.46  4918.4 1577.87  4931.5 1577.83  4946.3 1577.95  4968.8 1577.51
  4979.2 1577.81  5000.1 1577.42  5031.4 1578.12  5089.2 1580.48  5104.4 1580.74
  5127.6 1581.73  5155.5 1582.44  5199.1 1584.22  5227.0 1584.69  5232.2 1585.08
  5292.3 1586.55  5303.7 1587.13  5344.5 1588.37  5364.8 1588.60  5399.2 1589.60
#Mann=4,-1,0
  4589.9    0.05       0  4873.3    0.07       0  4879.3    0.05       0
  4931.5     0.1       0
Bank Sta=4873.3,4879.3
Exp/Cntr=0.3,0.1

Type RM Length L Ch R = 1,8447,318,318,318
BEGIN DESCRIPTION:
UNT054 IN NNOGR 16.0
END DESCRIPTION:
XS GIS Cut Line= 3
      2783739.93     10064443.54      2783781.60     10063999.10
      2783420.82     10063638.33
#Sta/Elev= 30
  4477.9 1584.08  4514.3 1582.73  4569.3 1581.30  4692.1 1577.23  4829.2 1574.24
  4849.3 1573.45  4880.4 1573.98  4910.0 1573.75  4944.4 1573.38  4979.8 1573.58
  4986.9 1573.17  4998.0 1573.09  5000.8 1572.59  5004.0 1573.09  5057.6 1573.81
  5081.0 1574.54  5114.1 1574.99  5142.4 1576.12  5163.6 1576.35  5227.3 1578.84
  5255.6 1579.32  5283.9 1580.83  5305.1 1582.41  5319.2 1582.55  5353.2 1583.69
  5404.1 1585.24  5418.2 1585.88  5425.3 1586.60  5432.3 1586.54  5434.5 1586.91
#Mann=9,-1,0
  4477.9    0.05       0  4569.3     0.1       0  4692.1    0.05       0
  4880.4     0.1       0  4910.0    0.05       0  4998.0   0.035       0
  5004.0    0.05       0  5081.0     0.1       0  5353.2    0.05       0
Bank Sta=4998,5004
Exp/Cntr=0.3,0.1

Type RM Length L Ch R = 1,8129,390,390,390
BEGIN DESCRIPTION:
UNT054 IN NNOGR 15.0
END DESCRIPTION:
XS GIS Cut Line= 3
      2783955.21     10064436.61      2784031.60     10063721.32
      2783893.07     10063471.97
#Sta/Elev= 30
  4444.9 1580.88  4517.9 1580.21  4528.2 1579.81  4578.5 1579.20  4611.4 1577.93
  4719.3 1573.39  4810.0 1570.55  4860.1 1570.41  4910.4 1569.81  4938.4 1570.02
  4970.8 1569.89  4980.8 1569.50  4989.7 1568.29  4997.9 1567.74  5000.7 1567.24
  5003.9 1567.74  5011.0 1568.87  5021.0 1569.81  5071.3 1571.74  5087.0 1572.82
  5092.1 1572.54  5164.3 1575.23  5223.3 1577.79  5304.1 1579.48  5364.0 1581.26
  5369.7 1581.67  5417.2 1582.47  5437.0 1582.92  5445.2 1582.80  5449.5 1583.07
#Mann=8,-1,0
  4444.9     0.1       0  4611.4    0.05       0  4938.4     0.1       0
  4997.9    0.07       0  5003.9     0.1       0  5304.1    0.05       0
  5417.2     0.1       0  5437.0    0.05       0
Bank Sta=4997.9,5003.9
Exp/Cntr=0.3,0.1

Type RM Length L Ch R = 1,7739,361,361,361
BEGIN DESCRIPTION:
UNT054 IN NNOGR 14.0
END DESCRIPTION:
XS GIS Cut Line= 3
      2784871.91     10064200.52      2784253.82     10063658.82
      2784066.32     10063512.99
#Sta/Elev= 30
  4316.0 1578.13  4359.0 1576.93  4365.7 1576.36  4373.3 1576.45  4379.9 1575.99
  4394.1 1576.12  4422.6 1575.25  4486.2 1572.41  4585.8 1570.07  4627.6 1568.69
  4784.2 1565.81  4801.3 1565.81  4840.2 1565.26  4897.1 1565.83  4911.4 1565.19
  4918.9 1565.76  4932.2 1565.92  4982.5 1565.80  4993.8 1565.05  4996.5 1564.55
  4999.8 1565.05  5081.2 1567.34  5181.6 1572.67  5216.9 1573.37  5231.4 1574.07
  5237.7 1573.93  5266.7 1575.09  5302.0 1575.48  5316.4 1576.18  5375.4 1577.68
#Mann=4,-1,0
  4316.0    0.05       0  4801.3     0.1       0  4993.8    0.07       0
  4999.8     0.1       0
Bank Sta=4993.8,4999.8
Exp/Cntr=0.3,0.1

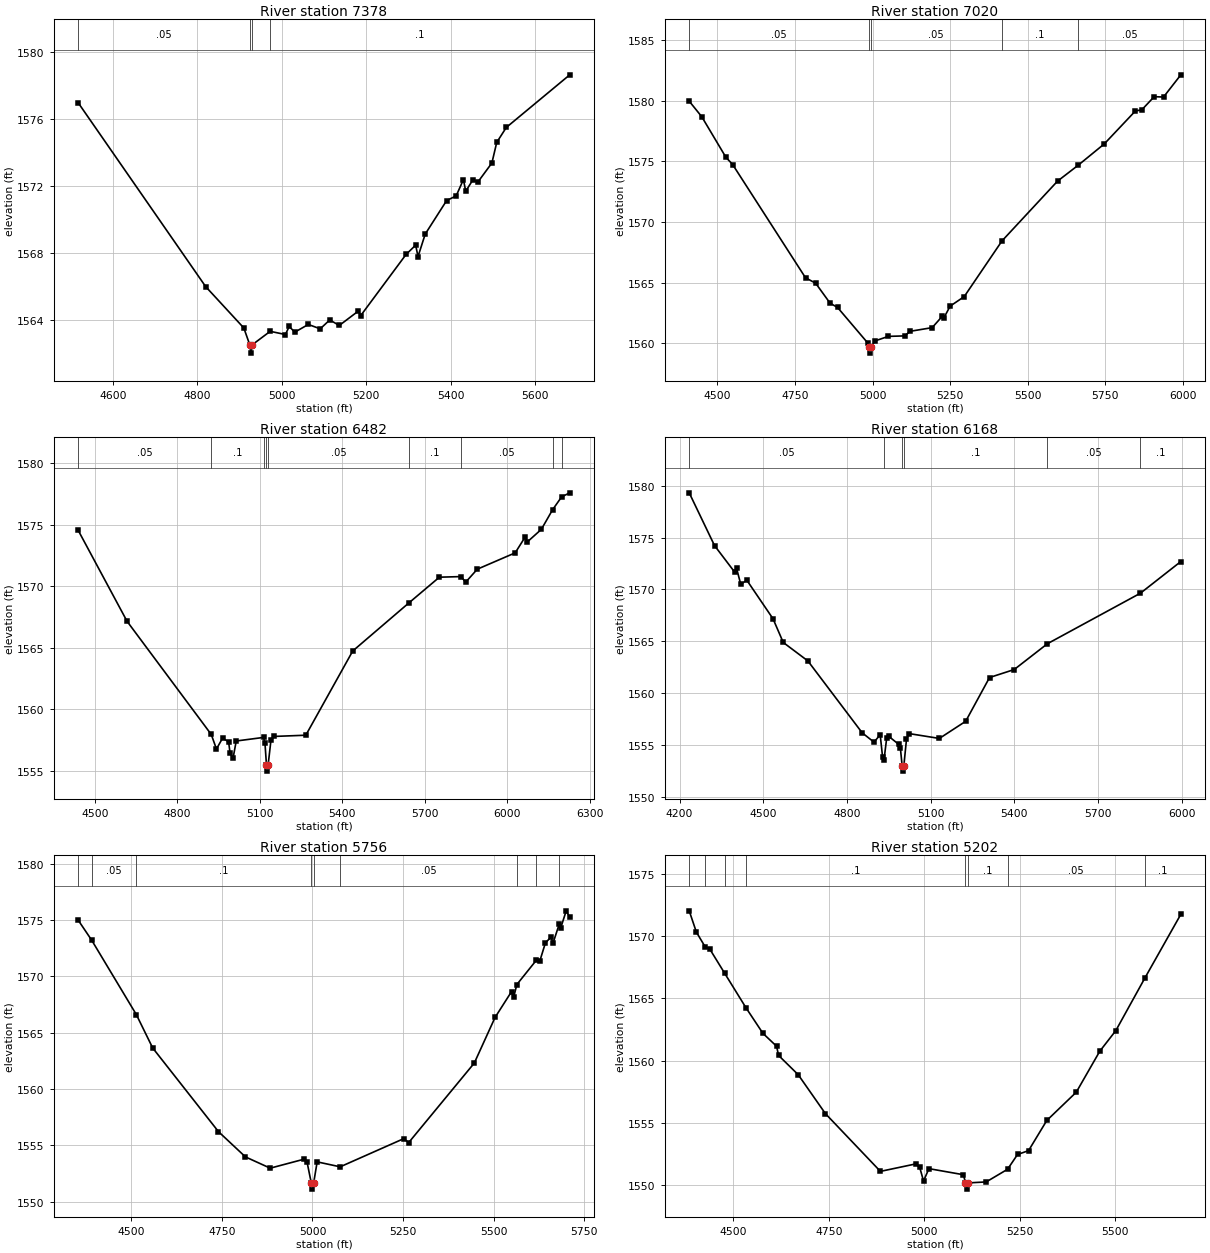
Type RM Length L Ch R = 1,7378,358,358,358
BEGIN DESCRIPTION:
UNT054 IN NNOGR 13.0
END DESCRIPTION:
XS GIS Cut Line= 2
      2785080.17     10063797.69      2784032.57     10063291.24
#Sta/Elev= 30
  4517.9 1576.97  4819.7 1566.00  4910.1 1563.53  4924.1 1562.53  4926.9 1562.03
  4930.1 1562.53  4972.5 1563.33  5008.5 1563.14  5017.5 1563.62  5030.7 1563.28
  5062.7 1563.74  5090.9 1563.48  5113.5 1564.01  5136.0 1563.68  5181.2 1564.54
  5186.8 1564.27  5294.2 1567.92  5316.8 1568.47  5322.4 1567.79  5339.4 1569.13
  5390.1 1571.13  5412.7 1571.41  5429.8 1572.38  5435.3 1571.69  5452.4 1572.37
  5463.9 1572.23  5497.2 1573.37  5508.7 1574.60  5531.3 1575.49  5681.5 1578.63
#Mann=4,-1,0
  4517.9    0.05       0  4924.1    0.07       0  4930.1    0.05       0
  4972.5     0.1       0
Bank Sta=4924.1,4930.1
Exp/Cntr=0.3,0.1

Type RM Length L Ch R = 1,7020,538,538,538
BEGIN DESCRIPTION:
Mapping XS 283afc78
END DESCRIPTION:
XS GIS Cut Line= 4
      2785312.05     10063545.99      2785069.02     10063358.51
      2784447.49     10063167.53      2783822.96     10063229.99
#Sta/Elev= 30
  4408.9 1579.96  4449.3 1578.68  4527.1 1575.34  4548.9 1574.74  4783.8 1565.41
  4816.5 1564.96  4862.9 1563.32  4887.2 1562.96  4985.3 1560.01  4987.6 1559.70
  4990.3 1559.20  4993.6 1559.70  5009.3 1560.22  5050.8 1560.58  5103.5 1560.62
  5121.4 1561.00  5192.1 1561.30  5224.8 1562.24  5230.0 1562.11  5250.0 1563.07
  5295.5 1563.86  5417.3 1568.45  5596.2 1573.37  5662.7 1574.68  5747.0 1576.44
  5847.5 1579.16  5867.6 1579.24  5907.8 1580.33  5937.9 1580.30  5993.7 1582.13
#Mann=5,-1,0
  4408.9    0.05       0  4987.6   0.035       0  4993.6    0.05       0
  5417.3     0.1       0  5662.7    0.05       0
Bank Sta=4987.6,4993.6
Exp/Cntr=0.3,0.1

Type RM Length L Ch R = 1,6482,314,314,314
BEGIN DESCRIPTION:
UNT054 IN NNOGR 12.0
END DESCRIPTION:
XS GIS Cut Line= 3
      2785298.20     10063382.85      2784798.18     10062431.42
      2784430.13     10061820.31
#Sta/Elev= 30
  4438.8 1574.56  4616.9 1567.15  4923.1 1557.95  4941.9 1556.77  4964.0 1557.64
  4986.0 1557.37  4991.7 1556.41  5002.4 1556.03  5013.9 1557.42  5113.1 1557.71
  5118.3 1557.28  5123.9 1555.47  5126.7 1554.97  5129.9 1555.47  5140.3 1557.50
  5149.5 1557.79  5267.0 1557.89  5437.7 1564.74  5642.0 1568.65  5752.8 1570.74
  5832.7 1570.79  5847.9 1570.32  5890.7 1571.39  6028.6 1572.72  6065.4 1574.03
  6071.3 1573.58  6123.7 1574.63  6164.7 1576.23  6197.4 1577.27  6227.0 1577.60
#Mann=9,-1,0
  4438.8    0.05       0  4923.1     0.1       0  5113.1    0.05       0
  5123.9    0.07       0  5129.9    0.05       0  5642.0     0.1       0
  5832.7    0.05       0  6164.7     0.1       0  6197.4    0.05       0
Bank Sta=5123.9,5129.9
Exp/Cntr=0.3,0.1

Type RM Length L Ch R = 1,6168,412,412,412
BEGIN DESCRIPTION:
UNT054 IN NNOGR 11.0
END DESCRIPTION:
XS GIS Cut Line= 2
      2785662.01     10063314.76      2784728.84     10061819.09
#Sta/Elev= 30
  4234.5 1579.31  4325.2 1574.23  4398.3 1571.64  4404.2 1572.04  4419.5 1570.48
  4440.8 1570.90  4535.1 1567.17  4571.7 1564.89  4660.0 1563.11  4854.8 1556.18
  4897.3 1555.28  4919.3 1556.00  4928.0 1553.83  4933.0 1553.58  4942.9 1555.73
  4949.2 1555.86  4985.8 1555.07  4991.7 1554.72  4998.1 1552.99  5000.9 1552.49
  5004.1 1552.99  5013.6 1555.55  5022.4 1556.11  5131.5 1555.64  5225.8 1557.29
  5311.4 1561.51  5399.9 1562.28  5519.1 1564.77  5852.7 1569.64  5997.4 1572.69
#Mann=6,-1,0
  4234.5    0.05       0  4933.0     0.1       0  4998.1    0.07       0
  5004.1     0.1       0  5519.1    0.05       0  5852.7     0.1       0
Bank Sta=4998.1,5004.1
Exp/Cntr=0.3,0.1

Type RM Length L Ch R = 1,5756,554,554,554
BEGIN DESCRIPTION:
UNT054 IN NNOGR 10.0
END DESCRIPTION:
XS GIS Cut Line= 3
      2785871.86     10063033.80      2785628.82     10062519.93
      2785198.28     10061860.24
#Sta/Elev= 30
  4353.5 1575.00  4390.8 1573.22  4514.1 1566.61  4559.2 1563.65  4740.7 1556.22
  4815.1 1553.98  4883.4 1552.98  4977.1 1553.78  4984.9 1553.54  4997.0 1551.62
  4999.7 1551.12  5003.0 1551.62  5012.9 1553.54  5076.4 1553.10  5251.8 1555.60
  5265.4 1555.25  5446.4 1562.31  5503.7 1566.36  5549.1 1568.65  5555.1 1568.18
  5563.8 1569.28  5617.1 1571.42  5627.5 1571.40  5642.6 1572.98  5657.7 1573.48
  5663.7 1572.96  5680.7 1574.64  5684.8 1574.30  5699.9 1575.82  5709.7 1575.24
#Mann=9,-1,0
  4353.5     0.1       0  4390.8    0.05       0  4514.1     0.1       0
  4997.0    0.07       0  5003.0     0.1       0  5076.4    0.05       0
  5563.8     0.1       0  5617.1    0.05       0  5680.7     0.1       0
Bank Sta=4997,5003
Exp/Cntr=0.3,0.1

Type RM Length L Ch R = 1,5202,504,504,504
BEGIN DESCRIPTION:
UNT054 IN NNOGR 9.0
END DESCRIPTION:
XS GIS Cut Line= 2
      2786205.21     10062901.90      2785913.99     10061646.85
#Sta/Elev= 30
  4384.0 1572.06  4402.7 1570.35  4426.5 1569.12  4437.3 1569.01  4476.7 1567.04
  4533.0 1564.24  4577.2 1562.19  4613.0 1561.15  4618.2 1560.41  4669.6 1558.86
  4741.0 1555.72  4885.1 1551.07  4977.5 1551.67  4987.8 1551.42  4998.1 1550.30
  5012.3 1551.29  5102.7 1550.80  5108.0 1550.14  5110.7 1549.64  5114.0 1550.14
  5162.3 1550.22  5218.3 1551.24  5244.4 1552.43  5273.3 1552.74  5321.1 1555.17
  5398.4 1557.45  5460.0 1560.75  5502.0 1562.41  5578.6 1566.67  5672.4 1571.78
#Mann=8,-1,0
  4384.0    0.05       0  4426.5     0.1       0  4476.7    0.05       0
  4533.0     0.1       0  5108.0    0.07       0  5114.0     0.1       0
  5218.3    0.05       0  5578.6     0.1       0
Bank Sta=5108,5114
Exp/Cntr=0.3,0.1

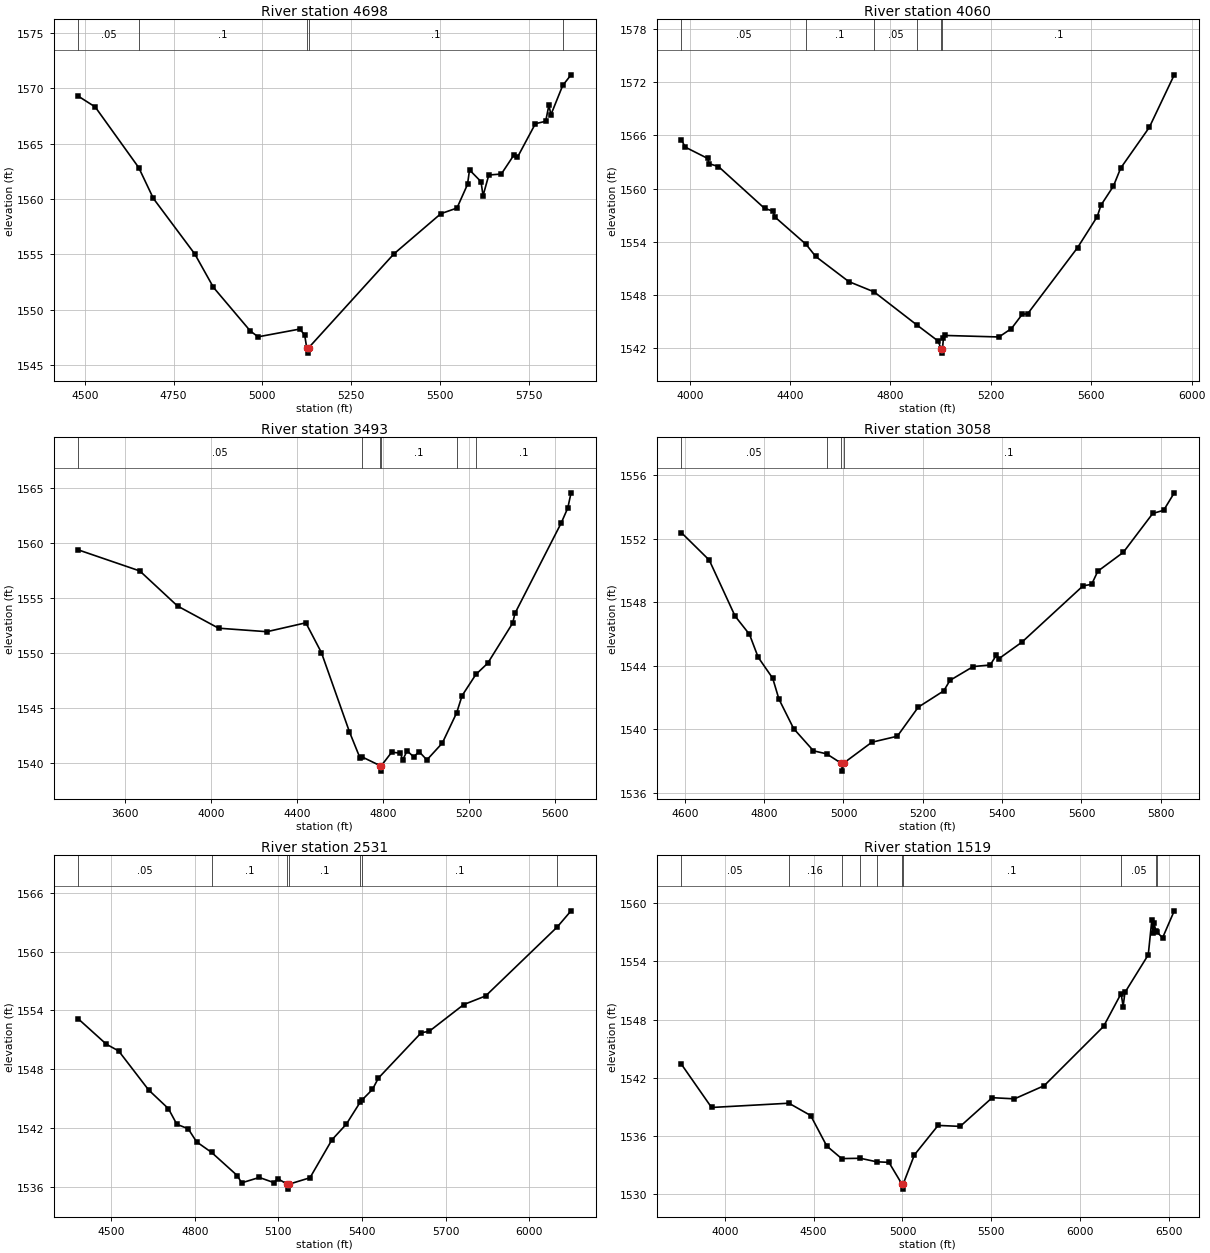
Type RM Length L Ch R = 1,4698,638,638,638
BEGIN DESCRIPTION:
UNT054 IN NNOGR 7.0
END DESCRIPTION:
XS GIS Cut Line= 2
      2786705.21     10062512.99      2786045.49     10061290.78
#Sta/Elev= 30
  4480.9 1569.28  4528.9 1568.30  4651.5 1562.83  4692.7 1560.05  4809.6 1555.03
  4862.1 1552.02  4965.9 1548.09  4987.8 1547.56  5105.1 1548.26  5119.1 1547.74
  5124.8 1546.59  5127.5 1546.09  5130.8 1546.59  5370.5 1555.04  5502.8 1558.67
  5548.3 1559.18  5578.0 1561.31  5583.7 1562.62  5616.1 1561.56  5621.8 1560.29
  5638.0 1562.16  5673.3 1562.25  5709.3 1563.99  5718.7 1563.76  5769.3 1566.79
  5798.3 1567.01  5807.4 1568.46  5813.1 1567.60  5846.3 1570.24  5869.8 1571.20
#Mann=5,-1,0
  4480.9    0.05       0  4651.5     0.1       0  5124.8    0.07       0
  5130.8     0.1       0  5846.3    0.05       0
Bank Sta=5124.8,5130.8
Exp/Cntr=0.3,0.1

Type RM Length L Ch R = 1,4060,567,567,567
BEGIN DESCRIPTION:
UNT054 IN NNOGR 6.0
END DESCRIPTION:
XS GIS Cut Line= 3
      2786902.35     10062608.52      2787069.02     10061771.70
      2786192.70     10061089.35
#Sta/Elev= 30
  3966.8 1565.49  3981.9 1564.67  4071.7 1563.39  4076.8 1562.80  4114.4 1562.48
  4298.0 1557.77  4332.3 1557.45  4338.8 1556.81  4463.7 1553.71  4501.9 1552.35
  4633.7 1549.52  4734.6 1548.36  4904.2 1544.65  4989.8 1542.82  5001.2 1541.96
  5004.0 1541.46  5007.2 1541.96  5010.9 1543.17  5018.7 1543.45  5232.2 1543.28
  5282.0 1544.23  5325.4 1545.85  5346.2 1545.88  5545.3 1553.34  5624.0 1556.85
  5638.5 1558.12  5688.2 1560.27  5717.2 1562.30  5831.2 1566.89  5930.7 1572.81
#Mann=6,-1,0
  3966.8    0.05       0  4463.7     0.1       0  4734.6    0.05       0
  4904.2     0.1       0  5001.2    0.07       0  5007.2     0.1       0
Bank Sta=5001.2,5007.2
Exp/Cntr=0.3,0.1

Type RM Length L Ch R = 1,3493,435,435,435
BEGIN DESCRIPTION:
UNT054 IN NNOGR 5.0
END DESCRIPTION:
XS GIS Cut Line= 3
      2787839.84     10062289.03      2787555.13     10061275.17
      2786343.40     10061004.36
#Sta/Elev= 30
  3381.0 1559.36  3667.8 1557.44  3843.4 1554.25  4034.5 1552.23  4259.7 1551.91
  4440.9 1552.72  4513.6 1550.00  4643.9 1542.80  4692.4 1540.45  4704.1 1540.50
  4786.5 1539.72  4789.2 1539.22  4792.5 1539.72  4840.5 1540.94  4881.5 1540.86
  4891.8 1540.22  4912.2 1541.07  4943.0 1540.52  4968.3 1540.99  5004.5 1540.24
  5076.2 1541.77  5143.2 1544.53  5168.4 1546.09  5232.6 1548.02  5287.6 1549.04
  5404.1 1552.70  5414.3 1553.57  5629.5 1561.79  5660.5 1563.17  5675.7 1564.55
#Mann=6,-1,0
  3381.0    0.05       0  4704.1     0.1       0  4786.5    0.07       0
  4792.5     0.1       0  5143.2    0.16       0  5232.6     0.1       0
Bank Sta=4786.5,4792.5
Exp/Cntr=0.3,0.1

Type RM Length L Ch R = 1,3058,527,527,527
BEGIN DESCRIPTION:
UNT054 IN NNOGR 4.0
END DESCRIPTION:
XS GIS Cut Line= 2
      2787614.96     10061033.84      2786545.52     10060401.90
#Sta/Elev= 30
  4591.6 1552.39  4661.8 1550.66  4726.9 1547.13  4763.2 1545.98  4785.0 1544.54
  4821.8 1543.21  4837.4 1541.90  4874.5 1540.04  4924.4 1538.64  4957.5 1538.45
  4994.3 1537.86  4997.1 1537.36  5000.3 1537.86  5071.5 1539.18  5135.8 1539.56
  5188.5 1541.39  5252.9 1542.42  5268.5 1543.08  5327.0 1543.95  5369.9 1544.05
  5385.5 1544.67  5391.4 1544.44  5449.9 1545.49  5604.0 1549.04  5625.5 1549.13
  5641.1 1549.96  5705.4 1551.15  5779.6 1553.60  5807.1 1553.80  5833.8 1554.90
#Mann=4,-1,0
  4591.6    0.05       0  4957.5     0.1       0  4994.3    0.07       0
  5000.3     0.1       0
Bank Sta=4994.3,5000.3
Exp/Cntr=0.3,0.1

Type RM Length L Ch R = 1,2531,1012,1012,1012
BEGIN DESCRIPTION:
UNT054 IN NNOGR 3.0
END DESCRIPTION:
XS GIS Cut Line= 3
      2787705.21     10060943.52      2787628.82     10060443.54
      2786566.36     10059763.01
#Sta/Elev= 30
  4382.0 1553.14  4482.9 1550.55  4527.2 1549.86  4634.7 1545.88  4705.5 1543.98
  4735.8 1542.38  4776.3 1541.93  4806.7 1540.59  4860.6 1539.51  4952.9 1537.14
  4968.1 1536.41  5031.6 1536.96  5083.1 1536.44  5098.3 1536.83  5131.7 1536.27
  5134.4 1535.77  5137.7 1536.27  5213.3 1536.93  5292.0 1540.80  5343.5 1542.39
  5393.6 1544.65  5398.5 1544.82  5437.4 1545.94  5458.5 1547.09  5612.6 1551.73
  5640.3 1551.85  5764.6 1554.59  5843.2 1555.47  6100.2 1562.51  6149.5 1564.15
#Mann=7,-1,0
  4382.0    0.05       0  4860.6     0.1       0  5131.7    0.07       0
  5137.7     0.1       0  5393.6    0.16       0  5398.5     0.1       0
  6100.2    0.05       0
Bank Sta=5131.7,5137.7
Exp/Cntr=0.3,0.1

Type RM Length L Ch R = 1,1519,882,882,882
BEGIN DESCRIPTION:
UNT054 IN NNOGR 2.0
END DESCRIPTION:
XS GIS Cut Line= 4
      2788450.09     10061092.89      2788398.01     10060493.92
      2787977.00     10059621.53      2786783.45     10059452.26
#Sta/Elev= 30
  3755.1 1543.40  3924.9 1538.94  4360.5 1539.38  4483.0 1538.11  4573.5 1534.97
  4657.4 1533.67  4762.6 1533.70  4854.3 1533.34  4923.7 1533.28  4997.5 1531.02
  5000.3 1530.52  5003.5 1531.02  5067.2 1534.05  5200.5 1537.09  5325.0 1536.99
  5505.3 1539.95  5630.7 1539.83  5798.2 1541.19  6132.4 1547.30  6231.2 1550.69
  6242.6 1549.35  6252.7 1550.80  6384.0 1554.68  6404.2 1558.27  6411.2 1556.89
  6416.3 1557.93  6427.3 1557.14  6433.4 1557.02  6464.8 1556.44  6530.5 1559.22
#Mann=10,-1,0
  3755.1    0.05       0  4360.5    0.16       0  4657.4     0.1       0
  4762.6    0.16       0  4854.3     0.1       0  4997.5    0.07       0
  5003.5     0.1       0  6231.2    0.05       0  6427.3     0.1       0
  6433.4    0.05       0
Bank Sta=4997.5,5003.5
Exp/Cntr=0.3,0.1

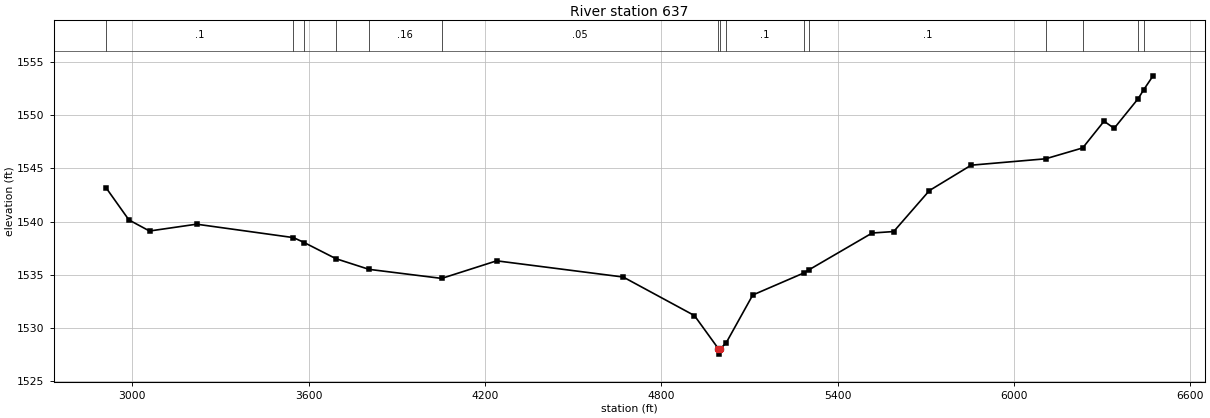
Type RM Length L Ch R = 1,637,0,0,0
BEGIN DESCRIPTION:
UNT054 IN NNOGR 1.0
END DESCRIPTION:
XS GIS Cut Line= 4
      2788588.98     10061131.99      2788502.18     10059352.43
      2787981.34     10058879.34      2786917.93     10058701.38
#Sta/Elev= 30
  2909.8 1543.20  2988.1 1540.16  3058.2 1539.12  3218.4 1539.76  3548.0 1538.50
  3584.3 1538.04  3692.7 1536.52  3805.1 1535.52  4052.4 1534.67  4239.6 1536.32
  4670.1 1534.80  4912.6 1531.18  4994.4 1528.06  4997.2 1527.56  5000.4 1528.06
  5020.2 1528.60  5111.0 1533.11  5284.9 1535.18  5303.2 1535.49  5517.3 1538.93
  5590.7 1539.07  5712.3 1542.92  5854.3 1545.30  6107.7 1545.90  6233.8 1546.92
  6306.5 1549.43  6340.9 1548.76  6423.0 1551.56  6441.1 1552.37  6473.3 1553.69
#Mann=15,-1,0
  2909.8     0.1       0  3548.0    0.05       0  3584.3    0.16       0
  3692.7     0.1       0  3805.1    0.16       0  4052.4    0.05       0
  4994.4   0.035       0  5000.4    0.05       0  5020.2     0.1       0
  5284.9    0.05       0  5303.2     0.1       0  6107.7    0.05       0
  6233.8     0.1       0  6423.0    0.05       0  6441.1     0.1       0
Bank Sta=4994.4,5000.4
Exp/Cntr=0.3,0.1

Chan Stop Cuts=-1