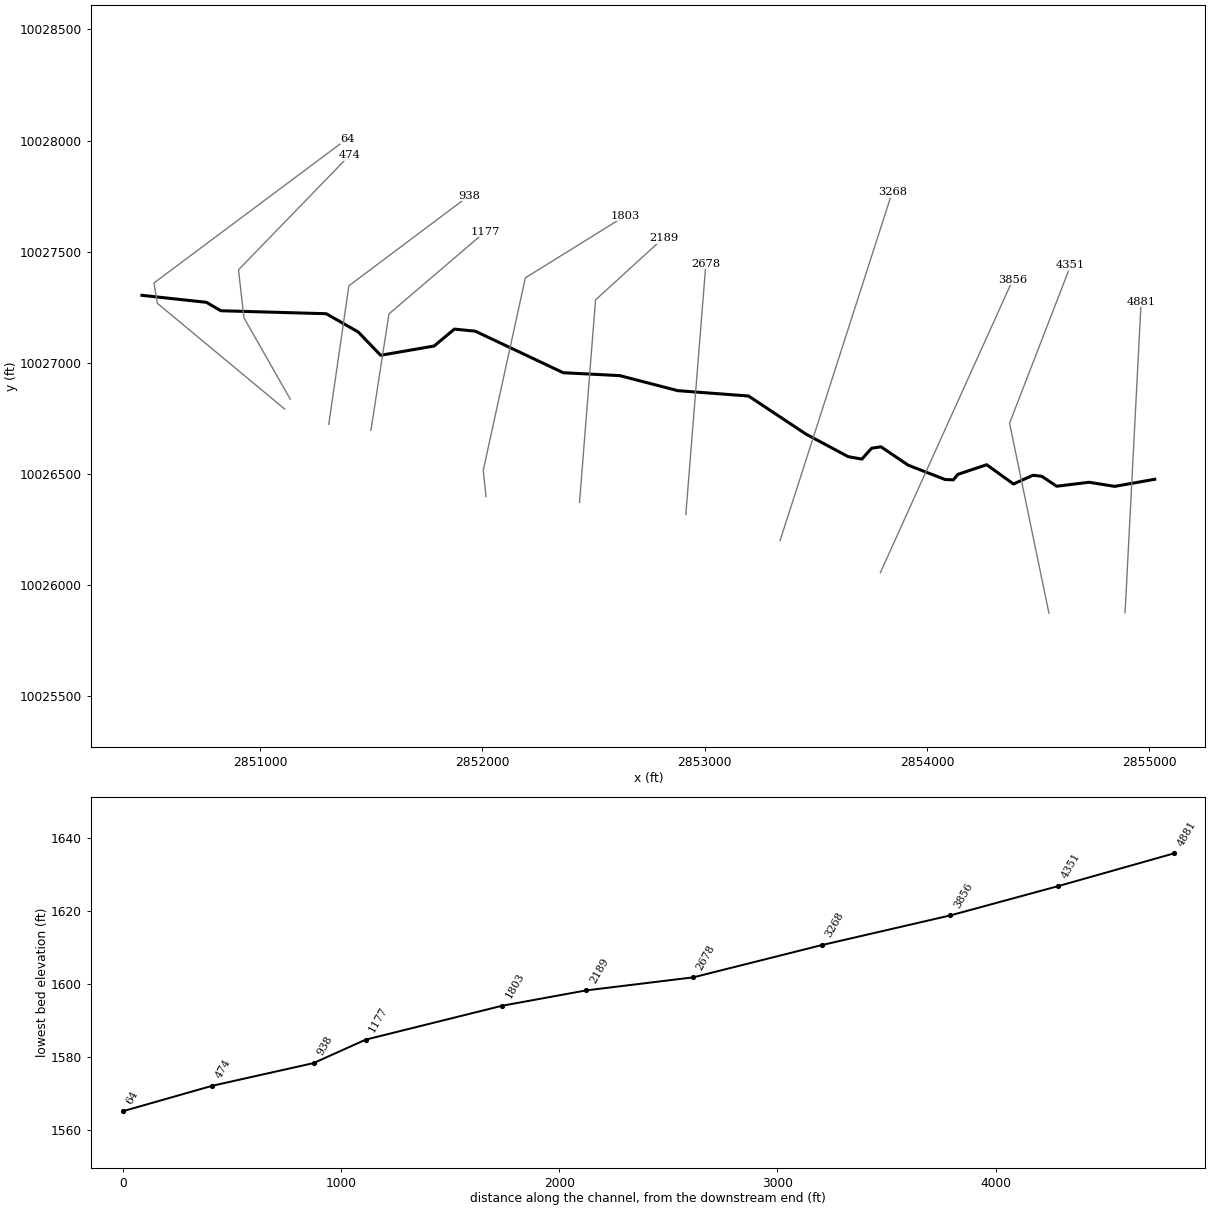
--- UNT054 IN SNOGR.prj (project) ---

Proj Title=UNT054 IN SNOGR Base Level Engineering
Current Plan=p01
Default Exp/Contr=0.3,0.1
English Units
Geom File=g01
Flow File=f01
Plan File=p01
BEGIN DESCRIPTION:
UNT054 IN SNOGR
END DESCRIPTION:

--- UNT054 IN SNOGR.p01 (plan) ---

Plan Title=Multiple Run
Short Identifier=Multiple
Geom File=g01
Flow File=f01
Subcritical Flow
K Sum by GR= 0
Std Step Tol= 0.01
Critical Tol= 0.01
Num of Std Step Trials= 20
Max Error Tol= 0.3
Flow Tol Ratio= 0.001
Split Flow NTrial= 30
Split Flow Tol= 0.02
Split Flow Ratio= 0.02
Log Output Level= 0
Friction Slope Method= 1
Unsteady Friction Slope Method= 2
Unsteady Bridges Friction Slope Method= 1
Parabolic Critical Depth
Global Vel Dist=  1 , 1 , 1
Global Log Level= 0
CheckData=True
Encroach Param= -1, 0, 0, 0
BEGIN DESCRIPTION:
Multiple Run
END DESCRIPTION:

--- UNT054 IN SNOGR.f01 (steady flow) ---

Flow Title=Multiple
Number of Profiles=7
Profile Names=10-year,25-year,50-year,1pct_min,100-year,1pct_plu,500-year
River Rch & RM= UNT054 IN SNOGR,Reach-1,4881
     964    1404    1789    1671    2260    3056    3613
River Rch & RM= UNT054 IN SNOGR,Reach-1,3856
    1087    1591    2033    1901    2571    3477    4128
River Rch & RM= UNT054 IN SNOGR,Reach-1,938
    1249    1841    2364    2221    3003    4062    4866
Boundary for River Rch & Prof#=UNT054 IN SNOGR,Reach-1,1
Up Type=0
Dn Type=3
Dn Slope=0.005
Boundary for River Rch & Prof#=UNT054 IN SNOGR,Reach-1,2
Up Type=0
Dn Type=3
Dn Slope=0.005
Boundary for River Rch & Prof#=UNT054 IN SNOGR,Reach-1,3
Up Type=0
Dn Type=3
Dn Slope=0.005
Boundary for River Rch & Prof#=UNT054 IN SNOGR,Reach-1,4
Up Type=0
Dn Type=3
Dn Slope=0.005
Boundary for River Rch & Prof#=UNT054 IN SNOGR,Reach-1,5
Up Type=0
Dn Type=3
Dn Slope=0.005
Boundary for River Rch & Prof#=UNT054 IN SNOGR,Reach-1,6
Up Type=0
Dn Type=3
Dn Slope=0.005
Boundary for River Rch & Prof#=UNT054 IN SNOGR,Reach-1,7
Up Type=0
Dn Type=3
Dn Slope=0.005

--- UNT054 IN SNOGR.g01 (geometry) ---

Geom Title=Existing Conditions

River Reach=UNT054 IN SNOGR,Reach-1
Reach XY= 30
      2855024.54     10026476.30      2854844.47     10026444.38
      2854728.44     10026462.84      2854583.26     10026444.93
      2854516.06     10026489.79      2854476.62     10026494.39
      2854388.88     10026455.06      2854268.41     10026541.70
      2854138.87     10026498.55      2854118.47     10026473.73
      2854081.58     10026475.22      2853916.05     10026539.28
      2853792.85     10026622.31      2853750.82     10026615.89
      2853707.21     10026567.05      2853645.69     10026577.97
      2853455.68     10026679.35      2853197.26     10026850.83
      2852878.95     10026874.89      2852617.93     10026942.53
      2852363.68     10026955.59      2851967.90     10027142.50
      2851873.97     10027151.78      2851782.72     10027075.66
      2851542.23     10027034.06      2851441.33     10027138.95
      2851297.33     10027221.04      2850823.72     10027234.35
      2850758.25     10027272.31      2850468.47     10027303.73

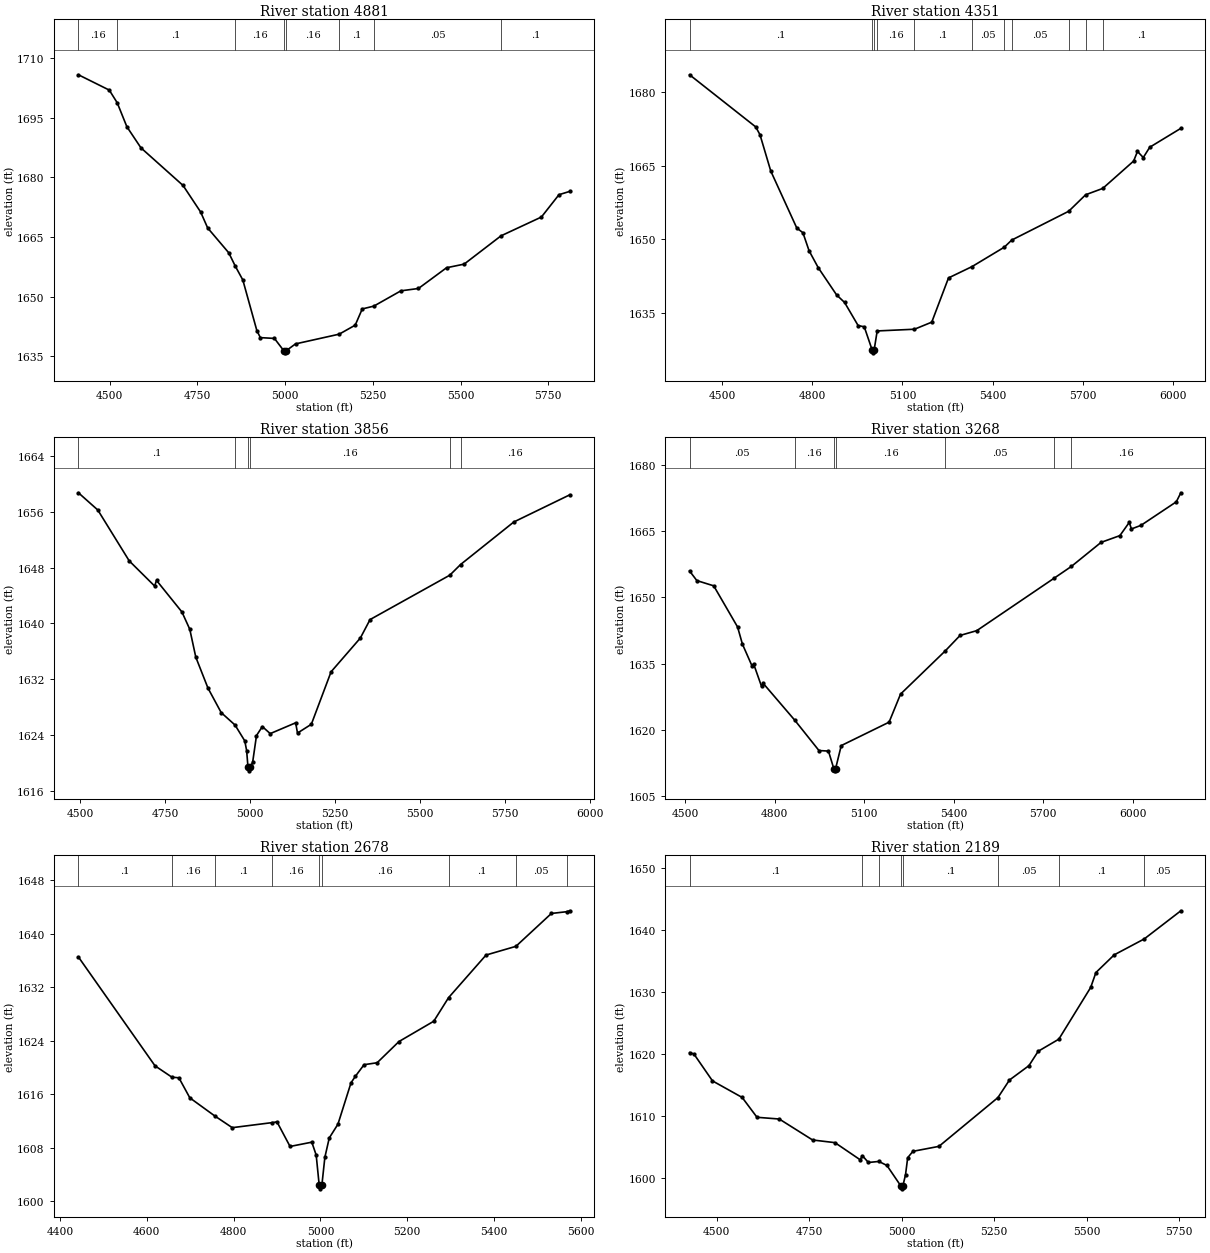
Type RM Length L Ch R = 1,4881,530,530,530
BEGIN DESCRIPTION:
UNT054 IN SNOGR 10.0
END DESCRIPTION:
XS GIS Cut Line= 2
      2854890.91     10025875.80      2854963.09     10027274.24
#Sta/Elev= 30
  4410.8 1705.83  4498.8 1701.97  4521.4 1698.78  4548.9 1692.75  4589.0 1687.44
  4709.1 1677.96  4759.2 1671.28  4779.2 1667.27  4839.3 1661.02  4857.9 1657.66
  4879.4 1654.18  4919.4 1641.44  4929.4 1639.66  4969.5 1639.46  4996.5 1636.33
  4999.3 1635.83  5002.5 1636.33  5029.6 1638.08  5154.1 1640.53  5199.8 1642.80
  5219.8 1646.88  5252.8 1647.59  5330.0 1651.44  5380.0 1652.03  5460.1 1657.25
  5510.2 1658.16  5615.3 1665.28  5730.5 1670.02  5780.6 1675.64  5811.1 1676.47
#Mann=8,-1,0
  4410.8    0.16       0  4521.4     0.1       0  4857.9    0.16       0
  4996.5    0.07       0  5002.5    0.16       0  5154.1     0.1       0
  5252.8    0.05       0  5615.3     0.1       0
Bank Sta=4996.5,5002.5
Exp/Cntr=0.3,0.1

Type RM Length L Ch R = 1,4351,495,495,495
BEGIN DESCRIPTION:
UNT054 IN SNOGR 9.0
END DESCRIPTION:
XS GIS Cut Line= 3
      2854548.38     10025874.22      2854371.30     10026728.39
      2854646.73     10027440.34
#Sta/Elev= 30
  4391.3 1683.51  4611.5 1672.89  4625.7 1671.30  4661.6 1663.90  4748.2 1652.30
  4768.7 1651.33  4789.1 1647.67  4819.7 1644.21  4881.0 1638.65  4907.3 1637.14
  4952.4 1632.43  4972.9 1632.17  4999.6 1627.37  5002.3 1626.87  5005.6 1627.37
  5015.9 1631.33  5140.1 1631.68  5197.6 1633.12  5253.4 1642.13  5331.8 1644.44
  5439.1 1648.39  5463.9 1649.84  5653.6 1655.71  5710.0 1659.07  5766.9 1660.36
  5869.8 1665.94  5882.6 1667.90  5901.9 1666.65  5923.4 1668.75  6027.0 1672.60
#Mann=11,-1,0
  4391.3     0.1       0  4999.6    0.07       0  5005.6     0.1       0
  5015.9    0.16       0  5140.1     0.1       0  5331.8    0.05       0
  5439.1     0.1       0  5463.9    0.05       0  5653.6    0.16       0
  5710.0    0.05       0  5766.9     0.1       0
Bank Sta=4999.6,5005.6
Exp/Cntr=0.3,0.1

Type RM Length L Ch R = 1,3856,588,588,588
BEGIN DESCRIPTION:
UNT054 IN SNOGR 8.0
END DESCRIPTION:
XS GIS Cut Line= 2
      2853790.20     10026056.26      2854385.67     10027373.52
#Sta/Elev= 30
  4494.9 1658.72  4551.9 1656.25  4644.4 1648.95  4719.2 1645.34  4724.7 1646.15
  4799.5 1641.62  4822.6 1639.14  4840.3 1635.14  4876.2 1630.69  4915.1 1627.18
  4955.8 1625.40  4984.4 1623.13  4989.9 1621.74  4993.9 1619.33  4996.7 1618.83
  4999.9 1619.33  5007.5 1620.03  5018.9 1623.89  5036.1 1625.18  5059.3 1624.17
  5134.1 1625.72  5139.6 1624.25  5180.3 1625.51  5238.4 1633.04  5324.5 1637.88
  5353.1 1640.53  5587.8 1646.90  5619.5 1648.43  5776.1 1654.53  5940.5 1658.42
#Mann=6,-1,0
  4494.9     0.1       0  4955.8    0.16       0  4993.9    0.07       0
  4999.9    0.16       0  5587.8     0.1       0  5619.5    0.16       0
Bank Sta=4993.9,4999.9
Exp/Cntr=0.3,0.1

Type RM Length L Ch R = 1,3268,590,590,590
BEGIN DESCRIPTION:
UNT054 IN SNOGR 7.0
END DESCRIPTION:
XS GIS Cut Line= 2
      2853339.07     10026200.58      2853843.62     10027768.29
#Sta/Elev= 30
  4515.0 1656.00  4539.3 1653.83  4595.9 1652.64  4675.9 1643.31  4692.1 1639.43
  4724.2 1634.50  4729.4 1634.99  4756.3 1629.83  4761.5 1630.56  4867.4 1622.20
  4948.7 1615.31  4980.5 1615.19  4998.5 1611.21  5001.3 1610.71  5004.5 1611.21
  5023.4 1616.43  5183.8 1621.74  5222.2 1628.10  5372.2 1637.90  5421.8 1641.40
  5477.7 1642.48  5736.4 1654.34  5795.3 1657.06  5894.5 1662.49  5957.5 1664.02
  5989.0 1667.02  5996.2 1665.53  6028.3 1666.35  6146.6 1671.68  6161.9 1673.73
#Mann=7,-1,0
  4515.0    0.05       0  4867.4    0.16       0  4998.5    0.07       0
  5004.5    0.16       0  5372.2    0.05       0  5736.4     0.1       0
  5795.3    0.16       0
Bank Sta=4998.5,5004.5
Exp/Cntr=0.3,0.1

Type RM Length L Ch R = 1,2678,489,489,489
BEGIN DESCRIPTION:
UNT054 IN SNOGR 5.0
END DESCRIPTION:
XS GIS Cut Line= 2
      2852915.03     10026317.91      2853005.25     10027445.71
#Sta/Elev= 30
  4442.6 1636.54  4619.0 1620.26  4657.9 1618.56  4674.0 1618.47  4699.2 1615.47
  4756.9 1612.75  4796.9 1611.01  4889.4 1611.77  4899.9 1611.88  4930.0 1608.20
  4980.1 1608.84  4990.2 1606.91  4997.2 1602.36  4999.9 1601.86  5003.2 1602.36
  5010.2 1606.58  5020.3 1609.47  5040.3 1611.53  5070.4 1617.72  5080.5 1618.70
  5100.5 1620.43  5130.6 1620.72  5180.8 1623.89  5261.0 1626.93  5295.0 1630.45
  5381.4 1636.83  5450.1 1638.13  5531.9 1643.05  5567.0 1643.31  5574.0 1643.45
#Mann=9,-1,0
  4442.6     0.1       0  4657.9    0.16       0  4756.9     0.1       0
  4889.4    0.16       0  4997.2    0.07       0  5003.2    0.16       0
  5295.0     0.1       0  5450.1    0.05       0  5567.0     0.1       0
Bank Sta=4997.2,5003.2
Exp/Cntr=0.3,0.1

Type RM Length L Ch R = 1,2189,386,386,386
BEGIN DESCRIPTION:
UNT054 IN SNOGR 4.0
END DESCRIPTION:
XS GIS Cut Line= 3
      2852436.85     10026372.07      2852509.02     10027283.28
      2852814.61     10027561.90
#Sta/Elev= 30
  4426.6 1620.27  4438.3 1620.05  4488.5 1615.71  4568.7 1613.04  4608.8 1609.84
  4669.0 1609.56  4759.0 1606.18  4819.5 1605.75  4887.5 1602.99  4893.6 1603.65
  4909.8 1602.55  4938.1 1602.72  4959.9 1602.07  4997.1 1598.80  4999.8 1598.30
  5003.1 1598.80  5010.1 1600.56  5016.0 1603.32  5030.1 1604.35  5100.4 1605.15
  5259.9 1613.02  5291.0 1615.85  5343.7 1618.17  5368.7 1620.49  5424.4 1622.44
  5510.5 1630.78  5524.7 1633.19  5574.1 1636.04  5655.3 1638.61  5754.2 1643.15
#Mann=8,-1,0
  4426.6     0.1       0  4893.6    0.16       0  4938.1     0.1       0
  4997.1    0.07       0  5003.1     0.1       0  5259.9    0.05       0
  5424.4     0.1       0  5655.3    0.05       0
Bank Sta=4997.1,5003.1
Exp/Cntr=0.3,0.1

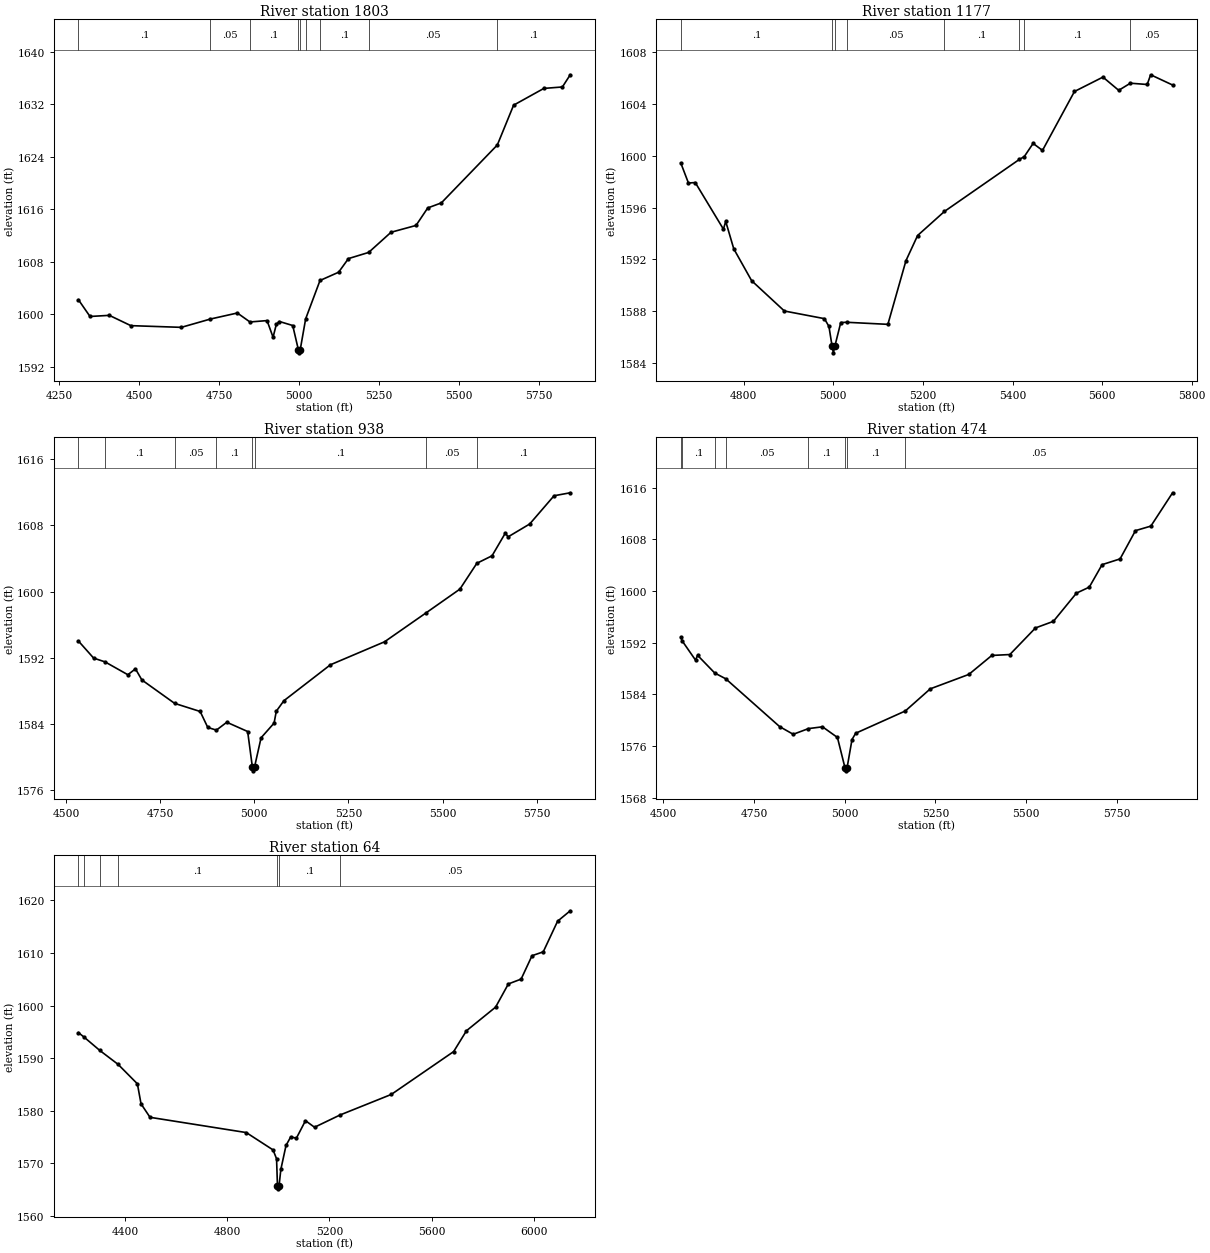
Type RM Length L Ch R = 1,1803,626,626,626
BEGIN DESCRIPTION:
UNT054 IN SNOGR 3.0
END DESCRIPTION:
XS GIS Cut Line= 4
      2852016.43     10026397.81      2852003.77     10026516.39
      2852193.24     10027382.53      2852643.89     10027661.93
#Sta/Elev= 30
  4311.1 1602.19  4347.2 1599.64  4407.6 1599.81  4474.7 1598.24  4632.4 1597.98
  4723.5 1599.25  4807.4 1600.17  4846.8 1598.80  4900.2 1599.01  4919.0 1596.47
  4929.2 1598.44  4939.0 1598.87  4980.4 1598.26  4997.9 1594.59  5000.6 1594.09
  5003.9 1594.59  5020.8 1599.28  5065.6 1605.13  5123.7 1606.39  5154.4 1608.47
  5217.5 1609.41  5287.5 1612.49  5365.5 1613.53  5402.1 1616.20  5444.6 1616.97
  5619.5 1625.81  5670.3 1631.88  5764.8 1634.44  5822.7 1634.66  5847.2 1636.52
#Mann=9,-1,0
  4311.1     0.1       0  4723.5    0.05       0  4846.8     0.1       0
  4997.9    0.07       0  5003.9     0.1       0  5020.8    0.05       0
  5065.6     0.1       0  5217.5    0.05       0  5619.5     0.1       0
Bank Sta=4997.9,5003.9
Exp/Cntr=0.3,0.1

Type RM Length L Ch R = 1,1177,239,239,239
BEGIN DESCRIPTION:
Mapping XS cba8c82f
END DESCRIPTION:
XS GIS Cut Line= 3
      2851498.52     10026696.84      2851579.72     10027220.13
      2852012.03     10027589.39
#Sta/Elev= 30
  4659.3 1599.45  4676.4 1597.90  4691.6 1597.94  4754.5 1594.34  4759.6 1594.94
  4777.6 1592.82  4817.5 1590.36  4890.6 1588.02  4980.0 1587.43  4990.1 1586.83
  4997.2 1585.29  5000.0 1584.79  5003.2 1585.29  5016.5 1587.13  5029.6 1587.15
  5121.7 1586.99  5162.1 1591.91  5188.1 1593.85  5248.1 1595.71  5415.5 1599.73
  5426.2 1599.94  5446.0 1600.96  5466.9 1600.42  5538.3 1604.97  5601.9 1606.08
  5637.1 1605.06  5663.2 1605.61  5700.7 1605.51  5708.4 1606.26  5757.4 1605.47
#Mann=8,-1,0
  4659.3     0.1       0  4997.2    0.07       0  5003.2     0.1       0
  5029.6    0.05       0  5248.1     0.1       0  5415.5    0.05       0
  5426.2     0.1       0  5663.2    0.05       0
Bank Sta=4997.2,5003.2
Exp/Cntr=0.3,0.1

Type RM Length L Ch R = 1,938,464,464,464
BEGIN DESCRIPTION:
UNT054 IN SNOGR 2.0
END DESCRIPTION:
XS GIS Cut Line= 3
      2851309.05     10026723.86      2851399.28     10027346.44
      2851940.65     10027752.47
#Sta/Elev= 30
  4533.2 1594.04  4573.5 1591.98  4603.9 1591.52  4664.4 1589.97  4684.6 1590.68
  4701.6 1589.34  4788.6 1586.51  4856.4 1585.53  4876.6 1583.60  4899.5 1583.28
  4927.1 1584.23  4982.5 1583.11  4994.9 1578.86  4997.6 1578.36  5000.9 1578.86
  5018.1 1582.35  5052.7 1584.13  5058.5 1585.56  5078.7 1586.83  5202.2 1591.17
  5346.0 1593.95  5456.7 1597.46  5546.0 1600.31  5591.0 1603.43  5631.4 1604.34
  5666.8 1607.09  5673.8 1606.62  5731.4 1608.18  5796.0 1611.59  5839.0 1611.95
#Mann=8,-1,0
  4533.2    0.16       0  4603.9     0.1       0  4788.6    0.05       0
  4899.5     0.1       0  4994.9    0.07       0  5000.9     0.1       0
  5456.7    0.05       0  5591.0     0.1       0
Bank Sta=4994.9,5000.9
Exp/Cntr=0.3,0.1

Type RM Length L Ch R = 1,474,410,410,410
BEGIN DESCRIPTION:
Mapping XS af2c6212
END DESCRIPTION:
XS GIS Cut Line= 4
      2851135.50     10026836.91      2850927.15     10027203.24
      2850902.85     10027418.52      2851402.83     10027934.13
#Sta/Elev= 30
  4547.9 1592.82  4552.3 1592.23  4588.5 1589.30  4594.2 1590.04  4641.5 1587.30
  4672.0 1586.40  4820.5 1579.00  4858.0 1577.81  4899.9 1578.69  4938.7 1578.97
  4979.9 1577.32  5000.6 1572.65  5003.4 1572.15  5006.6 1572.65  5020.1 1577.00
  5030.2 1577.97  5167.1 1581.42  5236.0 1584.85  5342.2 1587.08  5405.7 1590.02
  5455.4 1590.16  5526.1 1594.28  5575.5 1595.30  5639.1 1599.67  5674.5 1600.60
  5709.8 1604.08  5759.4 1604.97  5801.9 1609.35  5844.3 1610.05  5904.2 1615.21
#Mann=8,-1,0
  4547.9    0.16       0  4552.3     0.1       0  4641.5    0.16       0
  4672.0    0.05       0  4899.9     0.1       0  5000.6    0.07       0
  5006.6     0.1       0  5167.1    0.05       0
Bank Sta=5000.6,5006.6
Exp/Cntr=0.3,0.1

Type RM Length L Ch R = 1,64,0,0,0
BEGIN DESCRIPTION:
UNT054 IN SNOGR 1.0
END DESCRIPTION:
XS GIS Cut Line= 4
      2851111.15     10026791.81      2850538.27     10027267.48
      2850522.64     10027359.49      2851392.38     10028008.76
#Sta/Elev= 30
  4218.3 1594.87  4240.5 1594.01  4301.9 1591.48  4373.5 1588.83  4448.8 1585.14
  4463.1 1581.33  4498.2 1578.77  4874.6 1575.87  4979.4 1572.57  4993.1 1570.88
  4996.7 1565.67  4999.4 1565.17  5002.7 1565.67  5009.8 1568.85  5030.1 1573.42
  5048.3 1575.03  5070.7 1574.81  5106.2 1578.13  5141.6 1576.88  5241.3 1579.21
  5441.8 1583.12  5685.7 1591.27  5735.8 1595.23  5849.7 1599.72  5899.6 1604.13
  5949.5 1605.05  5992.2 1609.50  6036.0 1610.23  6092.2 1616.06  6141.6 1618.04
#Mann=7,-1,0
  4218.3    0.16       0  4240.5     0.1       0  4301.9    0.16       0
  4373.5     0.1       0  4996.7    0.07       0  5002.7     0.1       0
  5241.3    0.05       0
Bank Sta=4996.7,5002.7
Exp/Cntr=0.3,0.1

Chan Stop Cuts=-1