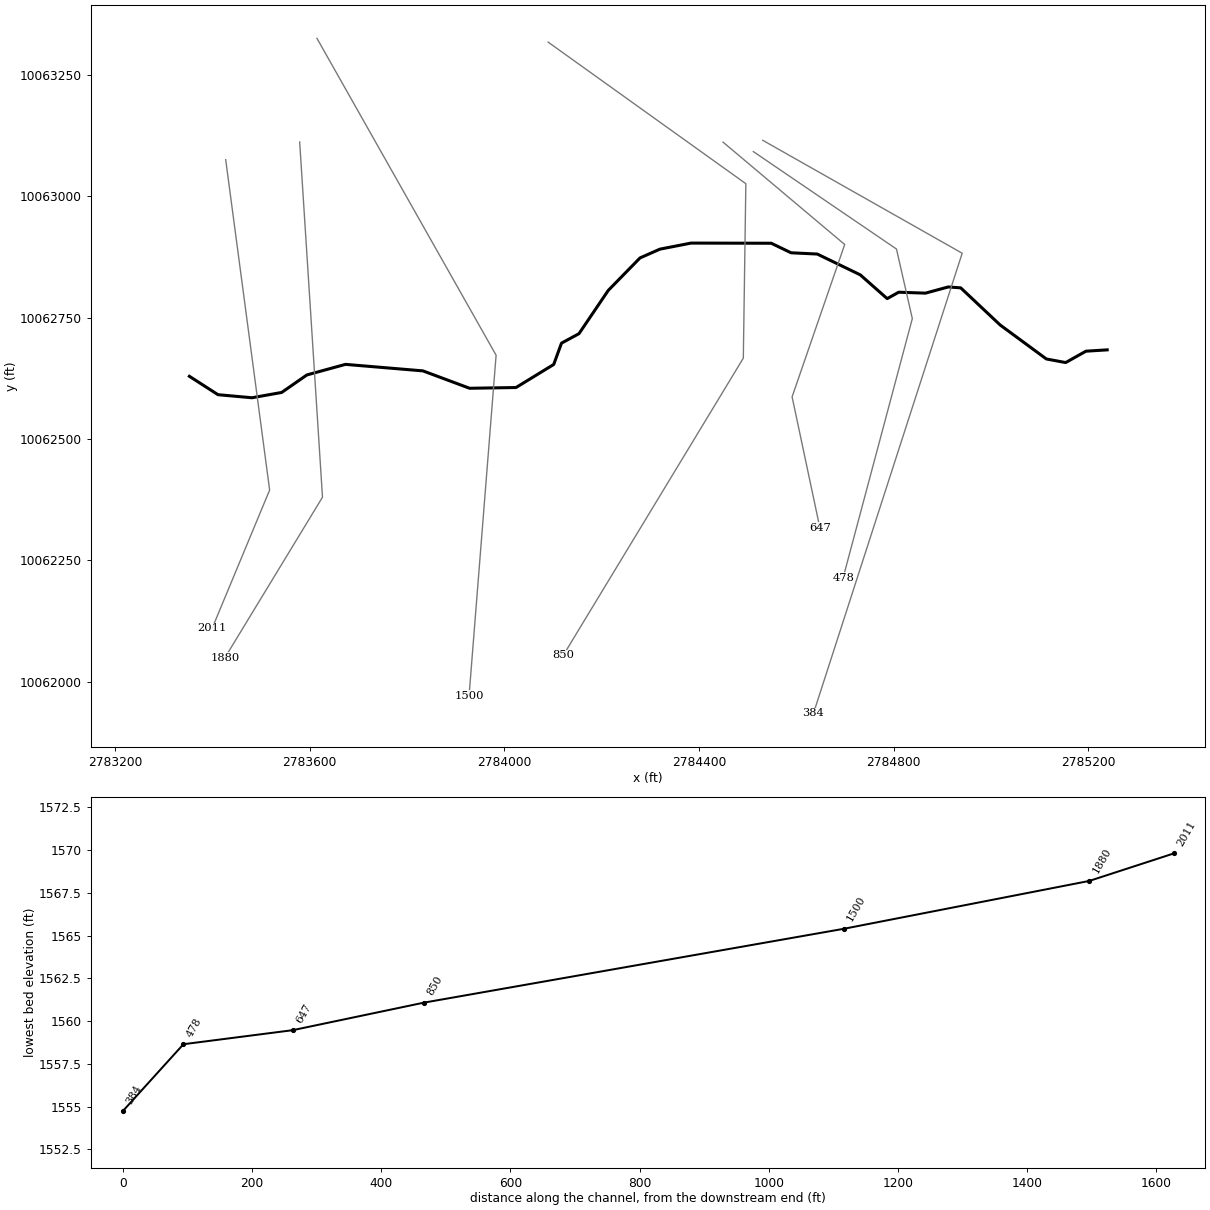
--- UNT055 IN NNOGR.prj (project) ---

Proj Title=UNT055 IN NNOGR Base Level Engineering
Current Plan=p01
Default Exp/Contr=0.3,0.1
English Units
Geom File=g01
Flow File=f01
Plan File=p01
Y Axis Title=Elevation
X Axis Title(PF)=Main Channel Distance
X Axis Title(XS)=Station
BEGIN DESCRIPTION:
UNT055 IN NNOGR
END DESCRIPTION:
DSS Export Rating Curves= 0
DSS Export Rating Curve Sorted= 0
DSS Export Volume Flow Curves= 0
DXF OffsetX= 0
DXF OffsetY= 0
DXF ScaleX= 1
DXF ScaleY= 10

--- UNT055 IN NNOGR.p01 (plan) ---

Plan Title=Multiple Run
Short Identifier=Multiple
Geom File=g01
Flow File=f01
Subcritical Flow
K Sum by GR= 0
Std Step Tol= 0.01
Critical Tol= 0.01
Num of Std Step Trials= 20
Max Error Tol= 0.3
Flow Tol Ratio= 0.001
Split Flow NTrial= 30
Split Flow Tol= 0.02
Split Flow Ratio= 0.02
Log Output Level= 0
Friction Slope Method= 1
Unsteady Friction Slope Method= 2
Unsteady Bridges Friction Slope Method= 1
Parabolic Critical Depth
Global Vel Dist=  1 , 1 , 1
Global Log Level= 0
CheckData=True
Encroach Param= -1, 0, 0, 0
BEGIN DESCRIPTION:
Multiple Run
END DESCRIPTION:

--- UNT055 IN NNOGR.f01 (steady flow) ---

Flow Title=Multiple
Program Version=4.10
Number of Profiles= 7
Profile Names=10-year,25-year,50-year,1pct_min,100-year,1pct_plu,500-year
River Rch & RM=UNT055 IN NNOGR,Reach-1         ,2011
     188     244     288     250     338     457     464
Boundary for River Rch & Prof#=UNT055 IN NNOGR,Reach-1         , 1
Up Type= 0
Dn Type= 3
Dn Slope=0.05
Boundary for River Rch & Prof#=UNT055 IN NNOGR,Reach-1         , 2
Up Type= 0
Dn Type= 3
Dn Slope=0.05
Boundary for River Rch & Prof#=UNT055 IN NNOGR,Reach-1         , 3
Up Type= 0
Dn Type= 3
Dn Slope=0.05
Boundary for River Rch & Prof#=UNT055 IN NNOGR,Reach-1         , 4
Up Type= 0
Dn Type= 3
Dn Slope=0.05
Boundary for River Rch & Prof#=UNT055 IN NNOGR,Reach-1         , 5
Up Type= 0
Dn Type= 3
Dn Slope=0.05
Boundary for River Rch & Prof#=UNT055 IN NNOGR,Reach-1         , 6
Up Type= 0
Dn Type= 3
Dn Slope=0.05
Boundary for River Rch & Prof#=UNT055 IN NNOGR,Reach-1         , 7
Up Type= 0
Dn Type= 3
Dn Slope=0.05
DSS Import GetInterval= 0
DSS Import GetPeak= 0
DSS Import FillOption= 0

--- UNT055 IN NNOGR.g01 (geometry) ---

Geom Title=Existing Conditions
Program Version=4.10

River Reach=UNT055 IN NNOGR ,Reach-1
Reach XY= 30
      2783352.84      10062629.3      2783411.59      10062591.4
      2783481.42     10062585.08      2783542.45       10062596.
      2783594.16     10062632.04       2783673.5     10062653.85
      2783832.75     10062640.42      2783928.47     10062604.62
      2784023.89     10062606.15      2784101.36     10062653.68
      2784117.33     10062697.56      2784153.26      10062717.1
      2784213.41     10062806.21      2784278.62     10062873.11
      2784319.49      10062891.2      2784383.48      10062903.7
      2784548.31     10062903.37      2784588.99     10062883.71
      2784642.78     10062881.13      2784731.19     10062838.25
      2784786.47     10062789.31      2784810.12     10062802.49
      2784865.05     10062800.57      2784911.92     10062813.33
      2784937.52     10062811.49      2785018.51     10062735.01
      2785113.48     10062664.98      2785153.16     10062657.56
      2785194.79     10062681.01      2785238.47     10062683.73

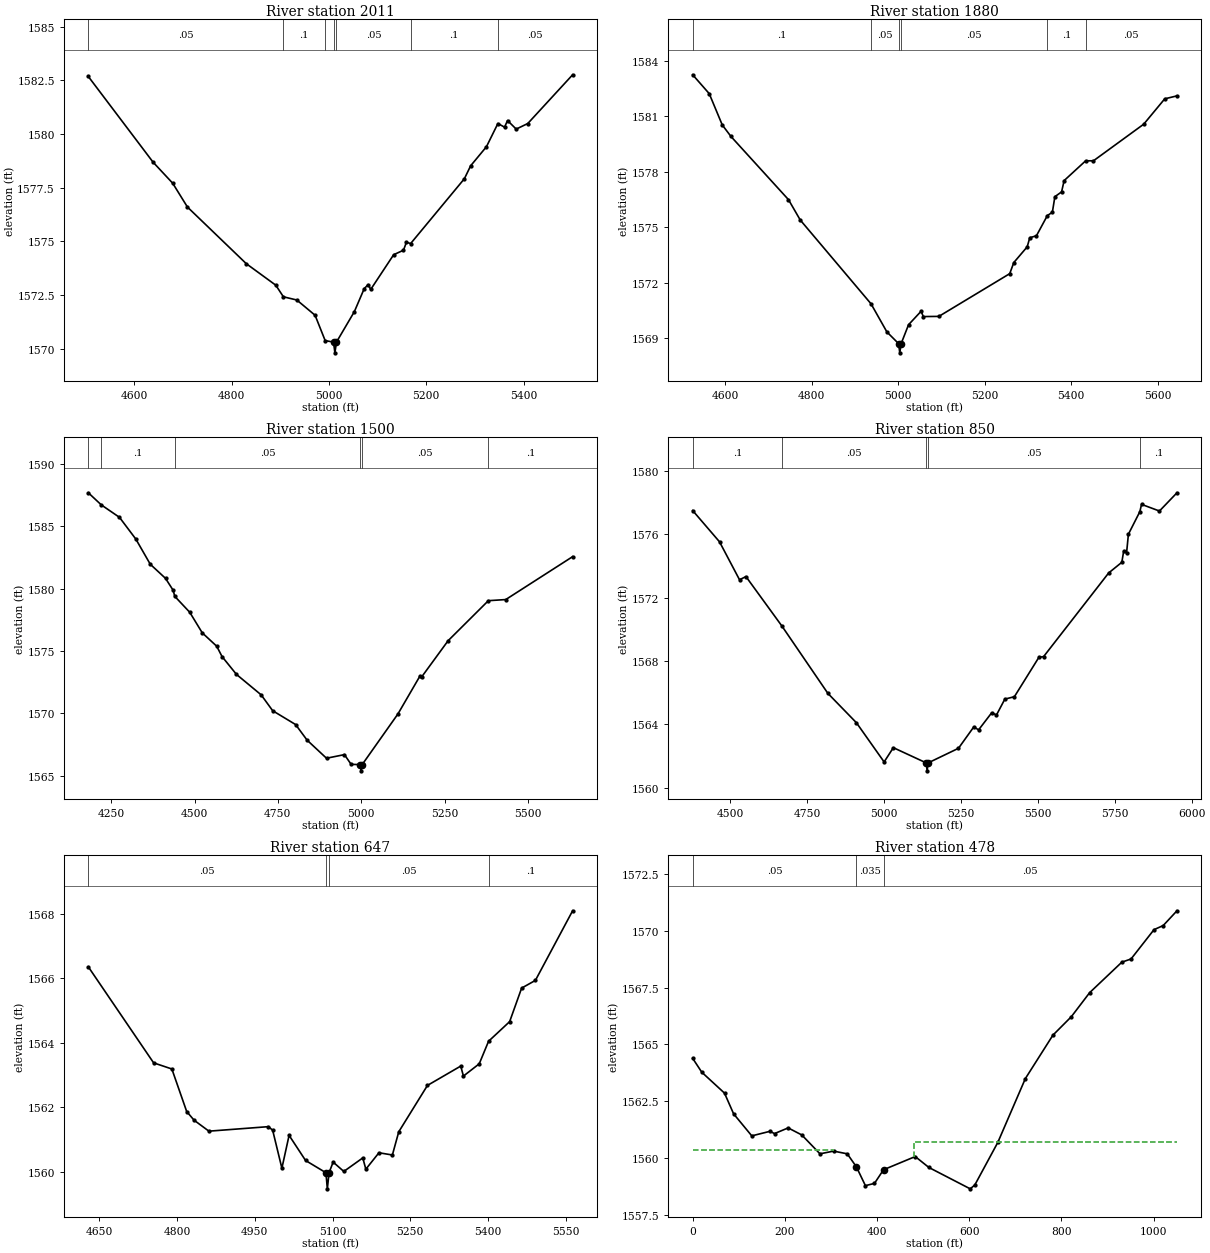
Type RM Length L Ch R = 1 ,2011    ,131,131,131
BEGIN DESCRIPTION:
UNT055 IN NNOGR 3.0
END DESCRIPTION:
XS GIS Cut Line= 3
      2783427.43     10063075.53      2783517.71     10062394.93
      2783399.65      10062110.2
#Sta/Elev= 30
  4505.8 1582.68  4638.8 1578.69  4679.1 1577.71  4709.4  1576.6  4830.4 1573.96
  4890.9 1572.96  4906.5 1572.42  4934.1 1572.27  4971.6 1571.56  4992.3 1570.38
  5009.5 1570.31  5012.3 1569.81  5015.5 1570.31  5052.3 1571.73  5072.5  1572.8
  5080.8 1572.99  5085.8 1572.76    5133 1574.38  5153.2 1574.59  5159.2 1574.96
  5167.9  1574.9  5278.3 1577.92  5291.1 1578.52  5323.6 1579.41  5347.1 1580.49
  5360.8 1580.32  5366.9 1580.63  5384.7 1580.23  5408.5 1580.49  5500.6 1582.76
#Mann= 7 ,-1 , 0
  4505.8     .05       0  4906.5      .1       0  4992.3     .05       0
  5009.5    .035       0  5015.5     .05       0  5167.9      .1       0
  5347.1     .05       0
Bank Sta=5009.5,5015.5
XS Rating Curve= 0 ,0
Exp/Cntr=0.3,0.1

Type RM Length L Ch R = 1 ,1880    ,380,380,380
BEGIN DESCRIPTION:
Mapping XS 1096a527
END DESCRIPTION:
XS GIS Cut Line= 3
      2783579.43       10063112.      2783626.31     10062380.21
      2783425.77     10062049.44
#Sta/Elev= 30
  4524.7 1583.23    4563 1582.21  4593.1 1580.52  4613.1  1579.9  4746.3 1576.48
  4773.5 1575.38  4937.2 1570.85  4973.9 1569.33  5000.9  1568.7  5003.7  1568.2
  5006.9  1568.7    5024 1569.72  5053.1 1570.45  5058.1 1570.16  5094.1 1570.17
    5258 1572.48  5267.4 1573.08  5298.4 1573.93  5304.3 1574.42  5319.8 1574.53
    5345 1575.62  5356.6  1575.8  5362.4 1576.64  5377.9  1576.9  5383.8 1577.51
  5433.6 1578.58  5451.6 1578.58  5567.9 1580.56  5616.5 1581.93  5644.8 1582.09
#Mann= 6 ,-1 , 0
  4524.7      .1       0  4937.2     .05       0  5000.9    .035       0
  5006.9     .05       0    5345      .1       0  5433.6     .05       0
Bank Sta=5000.9,5006.9
XS Rating Curve= 0 ,0
Exp/Cntr=0.3,0.1

Type RM Length L Ch R = 1 ,1500    ,650,650,650
BEGIN DESCRIPTION:
UNT055 IN NNOGR 2.0
END DESCRIPTION:
XS GIS Cut Line= 3
      2783614.93      10063325.5      2783982.99     10062672.71
      2783927.43     10061971.31
#Sta/Elev= 30
  4181.3 1587.69  4220.2 1586.72  4274.8 1585.72  4323.8 1583.98  4367.2 1581.96
  4412.9 1580.83  4435.9 1579.87  4440.6 1579.39  4485.6 1578.11  4523.2 1576.46
  4566.5 1575.39  4582.5 1574.56  4625.8 1573.13  4699.9 1571.49  4734.4 1570.22
  4803.2 1569.11  4837.7 1567.86  4895.9 1566.41  4949.7  1566.7  4969.8 1565.92
  4996.9  1565.9  4999.6  1565.4  5002.9  1565.9  5110.2 1569.96  5176.7 1573.02
  5181.7 1572.94  5260.7 1575.83  5381.5 1579.04  5433.7 1579.13  5634.3 1582.57
#Mann= 6 ,-1 , 0
  4181.3     .05       0  4220.2      .1       0  4440.6     .05       0
  4996.9    .035       0  5002.9     .05       0  5381.5      .1       0
Bank Sta=4996.9,5002.9
XS Rating Curve= 0 ,0
Exp/Cntr=0.3,0.1

Type RM Length L Ch R = 1 ,850     ,203,203,203
BEGIN DESCRIPTION:
Mapping XS cbac2e71
END DESCRIPTION:
XS GIS Cut Line= 4
      2784089.88     10063317.69       2784496.1     10063026.04
      2784490.89     10062666.67      2784121.11      10062054.7
#Sta/Elev= 30
  4377.8 1577.48  4465.1 1575.51  4530.1 1573.12    4551 1573.32  4668.4 1570.19
  4817.4 1565.96  4910.2 1564.11  5000.2 1561.64  5030.2 1562.54  5137.2 1561.58
    5140 1561.08  5143.2 1561.58  5241.9  1562.5  5291.8 1563.85  5307.3 1563.66
    5350 1564.74  5365.5  1564.6  5392.7  1565.6  5423.7 1565.75  5503.3 1568.23
  5518.8 1568.28  5730.3 1573.55    5773 1574.22  5778.9 1574.91  5788.5 1574.82
  5794.4 1575.99  5831.6 1577.41  5837.1 1577.87  5895.3 1577.45  5952.3  1578.6
#Mann= 5 ,-1 , 0
  4377.8      .1       0  4668.4     .05       0  5137.2    .035       0
  5143.2     .05       0  5831.6      .1       0
Bank Sta=5137.2,5143.2
XS Rating Curve= 0 ,0
Exp/Cntr=0.3,0.1

Type RM Length L Ch R = 1 ,647     ,169,169,169
BEGIN DESCRIPTION:
Mapping XS 234777c6
END DESCRIPTION:
XS GIS Cut Line= 4
      2784449.17     10063111.73      2784699.17     10062900.79
       2784591.1     10062586.99      2784648.12     10062317.45
#Sta/Elev= 30
  4628.7 1566.36  4754.7 1563.38  4789.9 1563.19  4818.5 1561.87  4832.8  1561.6
  4861.4 1561.26  4976.2  1561.4  4984.4 1561.29  5002.2 1560.11  5016.1 1561.13
  5047.9 1560.35  5087.2 1559.97  5089.9 1559.47  5093.2 1559.97  5101.1  1560.3
  5121.7 1560.01  5158.3 1560.43  5164.2 1560.08  5189.5 1560.59  5215.4 1560.52
  5227.7 1561.24  5283.1 1562.68  5347.3 1563.28  5352.5 1562.97    5383 1563.35
    5401 1564.05  5441.7 1564.66  5464.8  1565.7  5491.4 1565.94  5563.2  1568.1
#Mann= 4 ,-1 , 0
  4628.7     .05       0  5087.2    .035       0  5093.2     .05       0
    5401      .1       0
Bank Sta=5087.2,5093.2
XS Rating Curve= 0 ,0
Exp/Cntr=0.3,0.1

Type RM Length L Ch R = 1 ,478     ,94,94,94
XS GIS Cut Line= 4
     2784511.496    10063092.195      2784805.55    10062891.457
     2784838.102    10062748.228     2784695.958    10062214.374
#Sta/Elev= 30
       0 1564.39   19.73 1563.78   69.06 1562.86   88.79 1561.95  128.25 1560.98
  167.71 1561.18  177.57 1561.08  207.17 1561.33  236.76 1561.02  276.22 1560.19
  305.82 1560.31  335.41 1560.19  355.14 1559.62  374.79 1558.79  394.44 1558.89
  414.09 1559.49  482.87 1560.07  512.49 1559.59   602.2 1558.65  612.17 1558.82
  662.01 1560.69  721.82  1563.5  781.64 1565.41  821.51 1566.22  861.38 1567.28
  931.16 1568.62   951.1 1568.76 1000.94 1570.05 1020.88 1570.23 1050.78 1570.88
#Mann= 3 , 0 , 0
       0     .05       0  355.14    .035       0  414.09     .05       0
#XS Ineff= 2 , 0
             304 1560.36  479.24         1560.72
Permanent Ineff=
       F       F
Bank Sta=355.14,414.09
XS Rating Curve= 0 ,0
Exp/Cntr=0.3,0.1

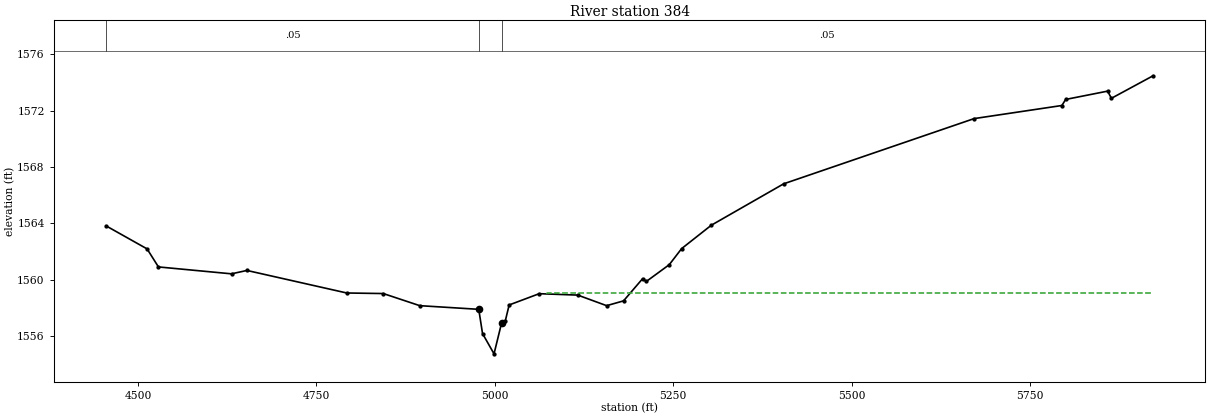
Type RM Length L Ch R = 1 ,384     ,0,0,0
BEGIN DESCRIPTION:
UNT055 IN NNOGR 1.0
END DESCRIPTION:
XS GIS Cut Line= 3
      2784530.84     10063115.44      2784940.54     10062882.81
      2784634.98     10061934.88
#Sta/Elev= 30
  4455.4 1563.81  4512.7 1562.18  4528.6  1560.9    4631 1560.41  4652.6 1560.65
  4792.5 1559.05  4843.7 1559.01  4894.8 1558.15  4977.5 1557.89  4982.8 1556.17
  4998.9 1554.73  5009.6 1556.94  5014.8 1557.09  5020.1  1558.2  5062.2    1559
  5116.3  1558.9  5156.7 1558.15  5180.4 1558.49  5207.2 1560.07  5212.4 1559.87
  5244.5 1561.06  5261.8  1562.2  5303.4 1563.86  5404.8  1566.8  5671.7 1571.43
  5794.7 1572.36    5800 1572.79  5858.8 1573.38  5864.1 1572.87  5922.5 1574.47
#Mann= 3 , 0 , 0
  4455.4     .05       0  4977.5    .035       0  5009.6     .05       0
#XS Ineff= 2 , 0
                         5072.51         1559.06
Permanent Ineff=
       F       F
Bank Sta=4977.5,5009.6
XS Rating Curve= 0 ,0
Exp/Cntr=0.3,0.1

Chan Stop Cuts=-1
Use User Specified Reach Order=0
Composite Channel Slope=5