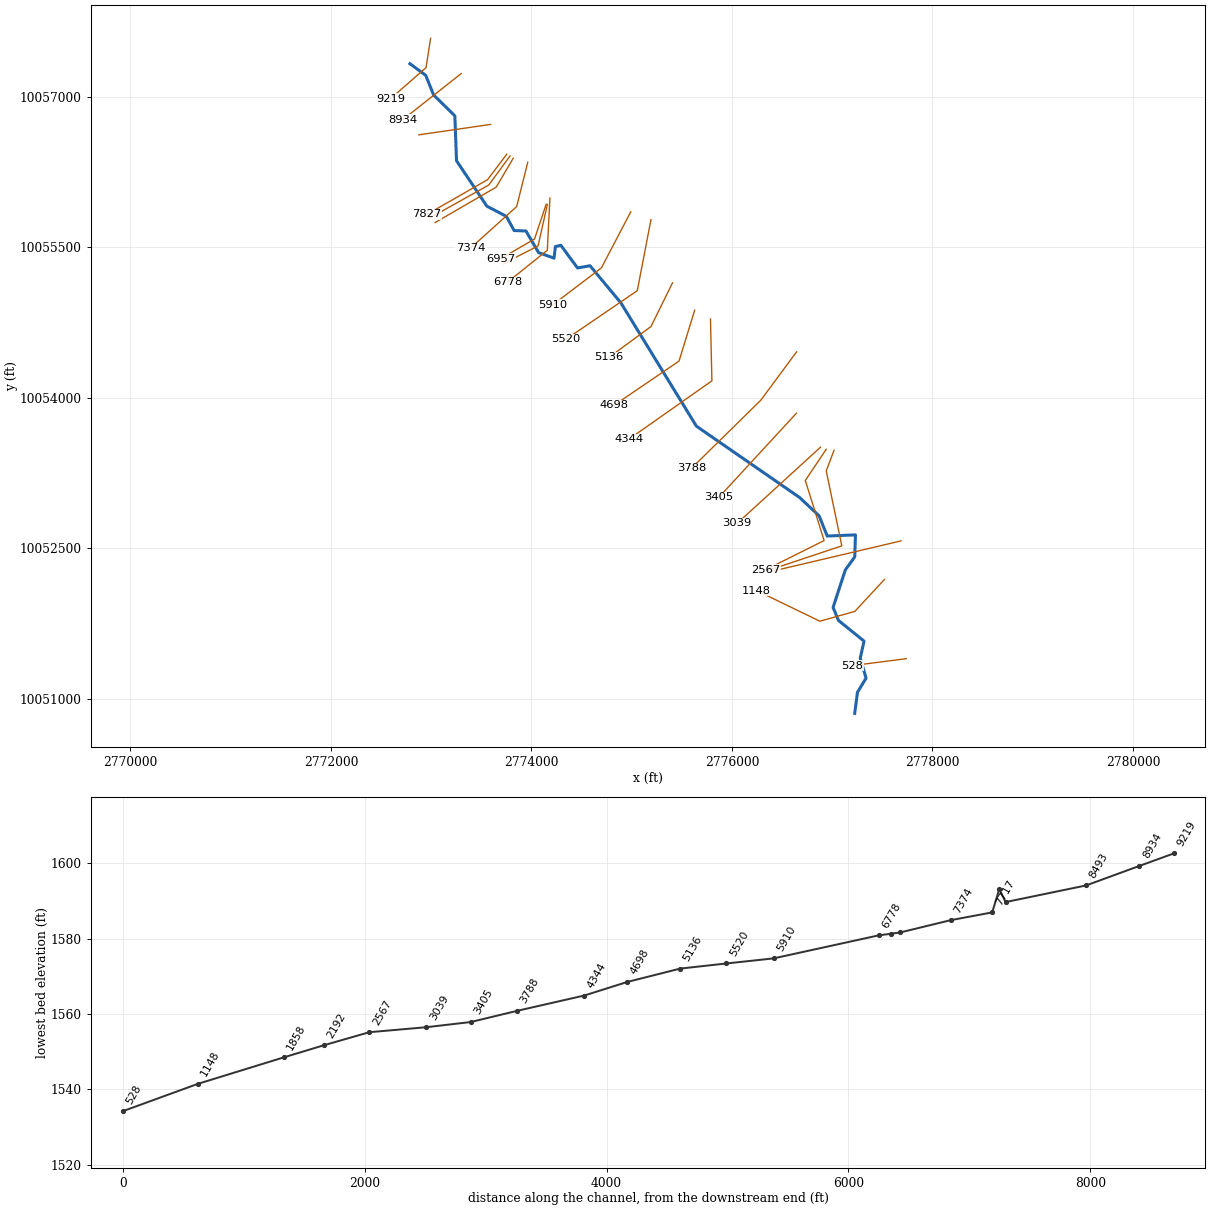
--- UNT056 IN NNOGR.prj (project) ---

Proj Title=UNT056 IN NNOGR Base Level Engineering
Current Plan=p01
Default Exp/Contr=0.3,0.1
English Units
Geom File=g01
Flow File=f01
Plan File=p01
Y Axis Title=Elevation
X Axis Title(PF)=Main Channel Distance
X Axis Title(XS)=Station
BEGIN DESCRIPTION:
UNT056 IN NNOGR
END DESCRIPTION:
DSS Export Rating Curves= 0
DSS Export Rating Curve Sorted= 0
DSS Export Volume Flow Curves= 0
DXF OffsetX= 0
DXF OffsetY= 0
DXF ScaleX= 1
DXF ScaleY= 10

--- UNT056 IN NNOGR.p01 (plan) ---

Plan Title=Multiple Run
Short Identifier=Multiple
Geom File=g01
Flow File=f01
Subcritical Flow
K Sum by GR= 0
Std Step Tol= 0.01
Critical Tol= 0.01
Num of Std Step Trials= 20
Max Error Tol= 0.3
Flow Tol Ratio= 0.001
Split Flow NTrial= 30
Split Flow Tol= 0.02
Split Flow Ratio= 0.02
Log Output Level= 0
Friction Slope Method= 1
Unsteady Friction Slope Method= 2
Unsteady Bridges Friction Slope Method= 1
Parabolic Critical Depth
Global Vel Dist=  1 , 1 , 1
Global Log Level= 0
CheckData=True
Encroach Param= -1, 0, 0, 0
BEGIN DESCRIPTION:
Multiple Run
END DESCRIPTION:

--- UNT056 IN NNOGR.f01 (steady flow) ---

Flow Title=Multiple
Number of Profiles=7
Profile Names=10-year,25-year,50-year,1pct_min,100-year,1pct_plu,500-year
River Rch & RM= UNT056 IN NNOGR,Reach-1,9219
     446     614     753     676     915    1237    1353
River Rch & RM= UNT056 IN NNOGR,Reach-1,2567
     770    1097    1375    1261    1705    2306    2633
Boundary for River Rch & Prof#=UNT056 IN NNOGR,Reach-1,1
Up Type=0
Dn Type=3
Dn Slope=0.005
Boundary for River Rch & Prof#=UNT056 IN NNOGR,Reach-1,2
Up Type=0
Dn Type=3
Dn Slope=0.005
Boundary for River Rch & Prof#=UNT056 IN NNOGR,Reach-1,3
Up Type=0
Dn Type=3
Dn Slope=0.005
Boundary for River Rch & Prof#=UNT056 IN NNOGR,Reach-1,4
Up Type=0
Dn Type=3
Dn Slope=0.005
Boundary for River Rch & Prof#=UNT056 IN NNOGR,Reach-1,5
Up Type=0
Dn Type=3
Dn Slope=0.005
Boundary for River Rch & Prof#=UNT056 IN NNOGR,Reach-1,6
Up Type=0
Dn Type=3
Dn Slope=0.005
Boundary for River Rch & Prof#=UNT056 IN NNOGR,Reach-1,7
Up Type=0
Dn Type=3
Dn Slope=0.005

--- UNT056 IN NNOGR.g01 (geometry) ---

Geom Title=Existing Conditions
Program Version=4.10

River Reach=UNT056 IN NNOGR ,Reach-1
Reach XY= 30
      2772787.93      10057332.9       2772945.1     10057217.06
      2773023.97     10057021.31      2773236.09     10056812.75
      2773252.42     10056365.14      2773555.63     10055911.59
      2773749.38     10055810.55      2773826.98     10055668.89
      2773945.21      10055664.2      2774071.26     10055448.57
      2774225.42     10055393.37      2774238.44     10055508.47
      2774293.61     10055521.35      2774459.44     10055295.43
      2774584.47      10055317.7      2774892.94     10054946.16
      2775645.22      10053717.5      2776674.92     10053005.82
      2776869.19     10052823.18      2776950.14     10052621.57
       2777231.9      10052633.1      2777224.83     10052413.89
      2777130.43     10052283.04      2777008.48     10051908.67
      2777062.64     10051779.56      2777317.63     10051573.27
      2777279.71     10051404.07      2777337.86     10051204.18
      2777251.54     10051062.45      2777224.53     10050852.69

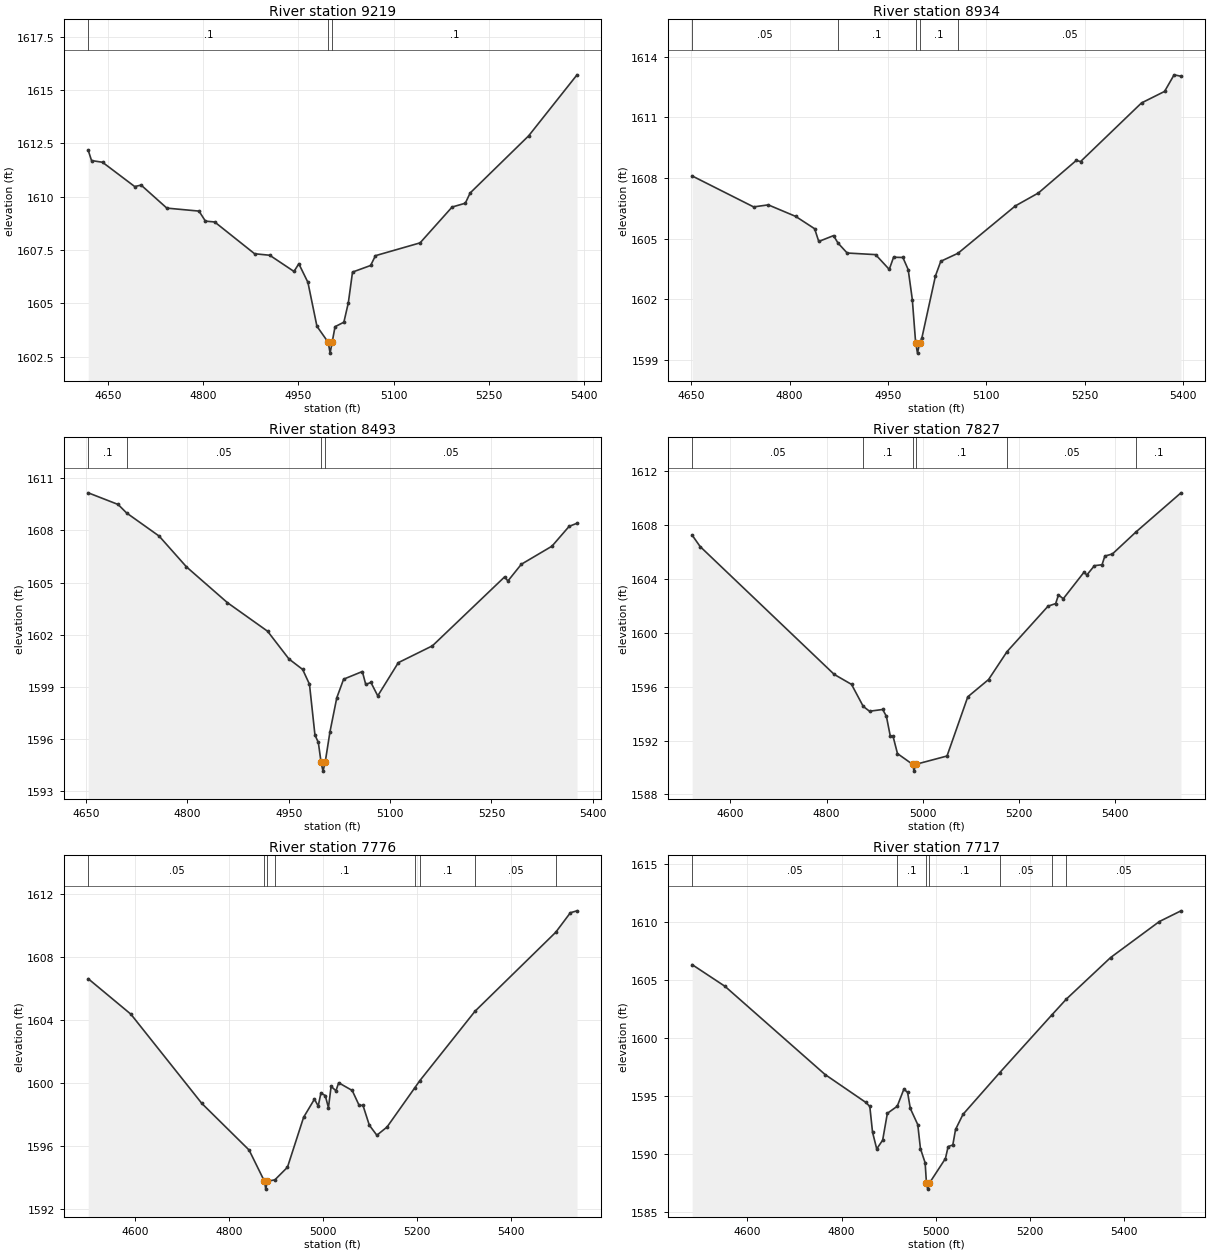
Type RM Length L Ch R = 1 ,9219    ,285,285,285
BEGIN DESCRIPTION:
UNT056 IN NNOGR 20.0
END DESCRIPTION:
XS GIS Cut Line= 3
      2772993.95     10057585.98      2772948.41     10057293.27
      2772592.06     10056982.28
#Sta/Elev= 30
  4619.2 1612.17  4624.4 1611.69  4641.7 1611.61  4692.4 1610.47  4702.4 1610.54
  4742.9 1609.46  4793.5 1609.32  4803.6 1608.85  4818.2 1608.81    4881 1607.32
  4904.8 1607.25    4943 1606.49  4950.6 1606.85  4964.9 1605.98  4979.1 1603.92
    4997 1603.16  4999.8 1602.66    5003 1603.16  5007.6  1603.9  5021.5 1604.11
  5028.5 1605.02  5035.1 1606.46  5063.6 1606.77  5071.2 1607.23  5141.4 1607.83
  5191.8 1609.51  5212.6 1609.69  5220.2 1610.17  5312.3 1612.85  5388.4 1615.71
#Mann= 3 ,-1 , 0
  4619.2      .1       0    4997     .07       0    5003      .1       0
Bank Sta=4997,5003
XS Rating Curve= 0 ,0
Exp/Cntr=0.3,0.1

Type RM Length L Ch R = 1 ,8934    ,441,441,441
BEGIN DESCRIPTION:
UNT056 IN NNOGR 19.0
END DESCRIPTION:
XS GIS Cut Line= 2
      2773299.64     10057234.75      2772714.27     10056772.95
#Sta/Elev= 30
  4651.3  1608.1    4745 1606.57  4767.4 1606.67  4809.2  1606.1  4838.1 1605.49
  4844.4 1604.86  4866.9 1605.15  4873.8 1604.78  4887.7 1604.29  4931.1 1604.21
  4951.9 1603.48  4958.5 1604.08  4972.7 1604.07  4980.8 1603.47  4987.1 1601.99
  4992.2 1599.84    4995 1599.34  4998.2 1599.84  5001.6 1600.08  5022.4 1603.16
  5030.5 1603.88  5056.9 1604.28  5144.3 1606.62  5179.5 1607.26  5237.3 1608.87
  5243.7 1608.81  5336.7 1611.71  5371.9 1612.28  5386.4  1613.1  5396.9 1613.03
#Mann= 5 ,-1 , 0
  4651.3     .05       0  4873.8      .1       0  4992.2     .07       0
  4998.2      .1       0  5056.9     .05       0
Bank Sta=4992.2,4998.2
XS Rating Curve= 0 ,0
Exp/Cntr=0.3,0.1

Type RM Length L Ch R = 1 ,8493    ,666,666,666
BEGIN DESCRIPTION:
UNT056 IN NNOGR 18.0
END DESCRIPTION:
XS GIS Cut Line= 2
      2773592.25     10056727.43      2772876.88     10056623.37
#Sta/Elev= 30
  4653.6 1610.16  4697.8 1609.49  4710.4    1609  4758.5 1607.67  4798.9  1605.9
  4859.5 1603.84  4918.8  1602.2  4950.5  1600.6  4970.7    1600  4980.8 1599.15
  4988.9 1596.23  4993.9  1595.8    4998 1594.65  5000.8 1594.15    5004 1594.65
  5011.1 1596.41  5021.2 1598.37  5031.3 1599.44    5059 1599.88    5064 1599.14
  5071.7 1599.25  5081.8 1598.48  5112.2 1600.39  5162.7 1601.36  5269.3 1605.32
  5274.3 1605.09  5294.1 1606.05  5339.4 1607.09  5364.8 1608.23  5376.5 1608.41
#Mann= 4 ,-1 , 0
  4653.6      .1       0  4710.4     .05       0    4998    .035       0
    5004     .05       0
Bank Sta=4998,5004
XS Rating Curve= 0 ,0
Exp/Cntr=0.3,0.1

Type RM Length L Ch R = 1 ,7827    ,51,51,51
BEGIN DESCRIPTION:
UNT056 IN NNOGR 17.0
END DESCRIPTION:
XS GIS Cut Line= 3
      2773754.48     10056430.52      2773561.78     10056175.94
      2772957.12     10055829.41
#Sta/Elev= 30
  4520.6 1607.22  4537.1 1606.38  4815.9  1596.9  4851.9 1596.16  4876.2 1594.53
  4889.3 1594.17  4916.7  1594.3  4924.4 1593.79  4932.5 1592.32  4938.2 1592.31
  4947.4 1591.03    4979 1590.23  4981.8 1589.73    4985 1590.23  5050.4 1590.85
  5093.6 1595.24  5136.8 1596.52  5175.2 1598.59  5260.5 1601.96  5276.3 1602.15
  5282.1 1602.79  5292.1 1602.51  5335.3 1604.48  5341.1 1604.27  5356.9 1604.96
  5372.7 1605.03  5378.5 1605.67  5394.3 1605.83  5443.9 1607.48  5536.8 1610.36
#Mann= 6 ,-1 , 0
  4520.6     .05       0  4876.2      .1       0    4979     .07       0
    4985      .1       0  5175.2     .05       0  5443.9      .1       0
Bank Sta=4979,4985
XS Rating Curve= 0 ,0
Exp/Cntr=0.3,0.1

Type RM Length L Ch R = 1 ,7776    ,59,59,59
BEGIN DESCRIPTION:
Mapping XS efb40c2a
END DESCRIPTION:
XS GIS Cut Line= 3
       2773786.3     10056412.84      2773574.15      10056122.9
      2772981.83     10055791.48
#Sta/Elev= 30
  4501.3  1606.6  4591.9 1604.35  4742.5 1598.69  4842.9 1595.73  4875.5 1593.75
  4878.3 1593.25  4881.5 1593.75  4897.7 1593.84  4924.4 1594.64  4958.7 1597.81
  4981.7 1598.96  4989.7 1598.52  4995.4 1599.34  5004.6 1599.19  5011.4 1598.42
  5017.1 1599.77  5027.4 1599.49  5033.1    1600  5061.9 1599.51  5076.5 1598.57
  5084.8 1598.56  5098.2 1597.31  5114.2 1596.67  5135.8 1597.19    5195 1599.69
  5205.4 1600.13  5322.7 1604.54  5494.1 1609.55  5525.2 1610.79  5539.3 1610.91
#Mann= 8 ,-1 , 0
  4501.3     .05       0  4875.5     .07       0  4881.5     .05       0
  4897.7      .1       0    5195     .05       0  5205.4      .1       0
  5322.7     .05       0  5494.1      .1       0
Bank Sta=4875.5,4881.5
XS Rating Curve= 0 ,0
Exp/Cntr=0.3,0.1

Type RM Length L Ch R = 1 ,7717    ,343,343,343
BEGIN DESCRIPTION:
Mapping XS 47fbda96
END DESCRIPTION:
XS GIS Cut Line= 3
      2773818.12     10056389.85       2773648.4     10056101.69
      2773039.02     10055748.42
#Sta/Elev= 30
  4482.5  1606.3  4552.1 1604.44  4764.9 1596.85  4851.5 1594.45    4860  1594.1
  4865.8 1591.89  4874.7 1590.45  4887.3  1591.2  4897.3 1593.51  4918.3 1594.12
  4932.4 1595.59  4940.3 1595.31  4946.1 1593.93  4961.9 1592.54  4967.6 1590.48
  4977.6 1589.25  4980.4 1587.49  4983.1 1586.99  4986.4 1587.49  5020.7 1589.62
  5026.5 1590.65  5036.4 1590.79  5042.2 1592.12    5058 1593.42  5135.9    1597
  5247.2 1601.99    5278 1603.35  5371.7 1606.91  5475.4 1610.01  5521.3 1610.93
#Mann= 7 ,-1 , 0
  4482.5     .05       0  4918.3      .1       0  4980.4     .07       0
  4986.4      .1       0  5135.9     .05       0  5247.2      .1       0
    5278     .05       0
Bank Sta=4980.4,4986.4
XS Rating Curve= 0 ,0
Exp/Cntr=0.3,0.1

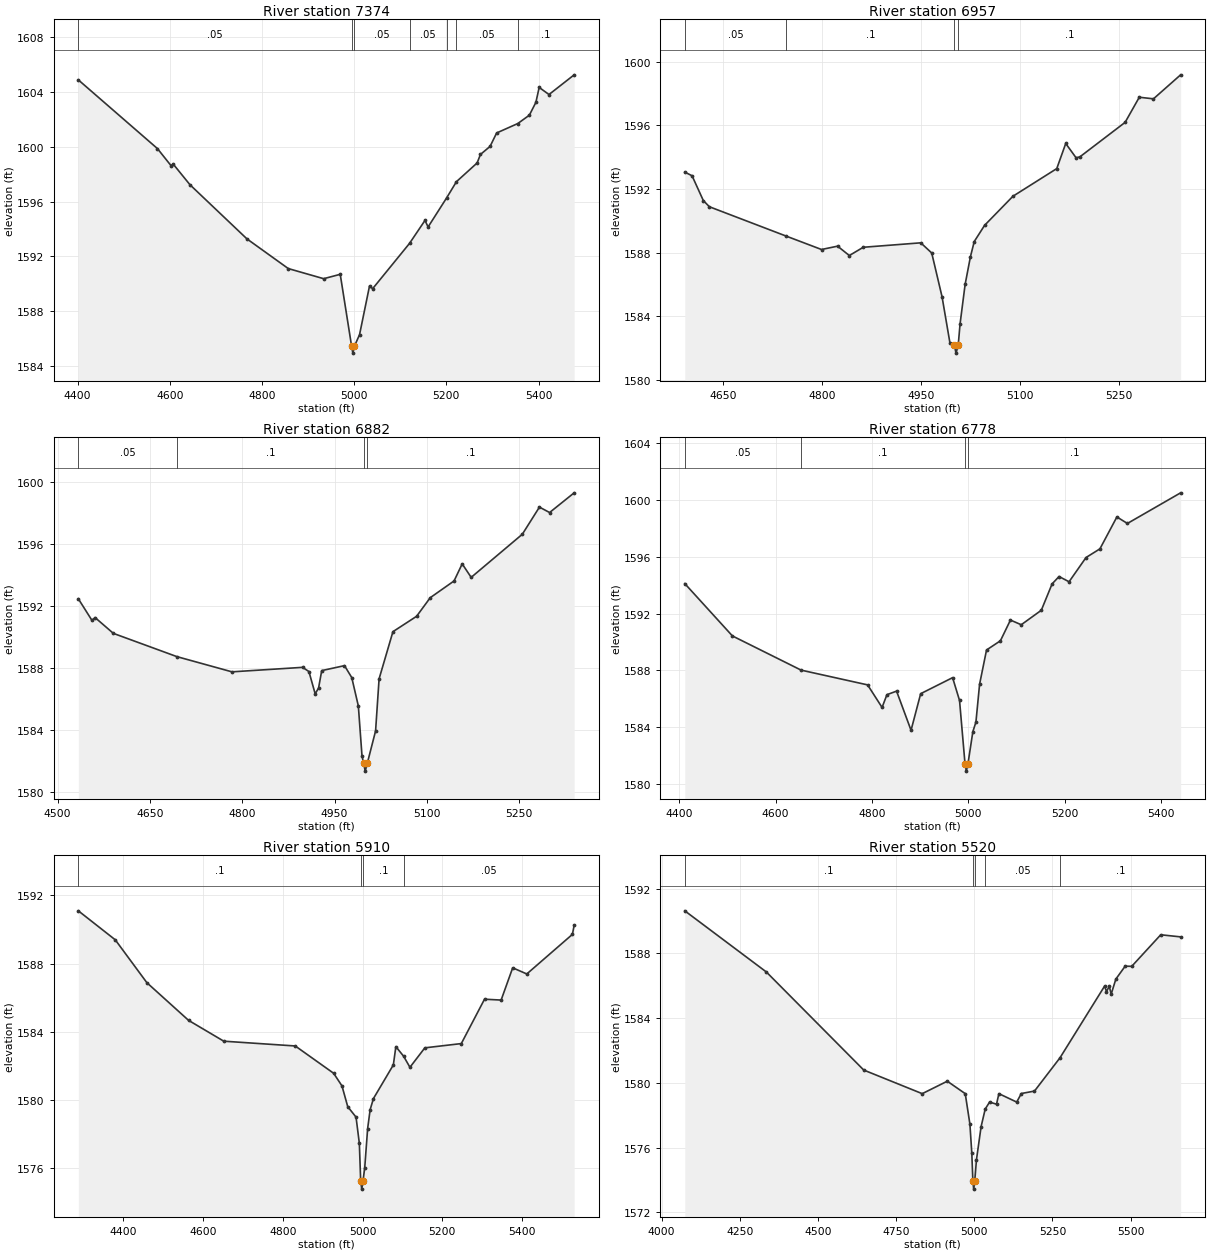
Type RM Length L Ch R = 1 ,7374    ,417,417,417
BEGIN DESCRIPTION:
UNT056 IN NNOGR 16.0
END DESCRIPTION:
XS GIS Cut Line= 3
      2773963.03     10056350.22      2773852.46     10055907.94
      2773392.08     10055492.95
#Sta/Elev= 30
  4401.6  1604.9  4573.2 1599.88  4602.5 1598.64  4607.6 1598.74  4643.7 1597.24
  4767.4 1593.28  4857.1 1591.11  4933.9 1590.37  4969.8 1590.69  4994.5 1585.43
  4997.2 1584.93  5000.5 1585.43  5011.7 1586.28  5033.3 1589.83  5040.1 1589.64
  5120.1 1592.95  5153.7 1594.63  5160.4 1594.15  5200.7 1596.28  5221.9 1597.46
  5266.8 1598.83    5274 1599.45  5294.9 1600.04  5309.1 1601.02    5355 1601.71
  5380.1 1602.32  5394.3 1603.26  5401.4 1604.35  5422.7 1603.83  5477.3 1605.27
#Mann= 7 ,-1 , 0
  4401.6     .05       0  4994.5     .07       0  5000.5     .05       0
  5120.1     .05       0  5200.7      .1       0  5221.9     .05       0
    5355      .1       0
Bank Sta=4994.5,5000.5
XS Rating Curve= 0 ,0
Exp/Cntr=0.3,0.1

Type RM Length L Ch R = 1 ,6957    ,75,75,75
BEGIN DESCRIPTION:
Mapping XS 6faaa3e8
END DESCRIPTION:
XS GIS Cut Line= 3
      2774146.58     10055930.38      2774030.47     10055584.21
      2773696.27      10055388.9
#Sta/Elev= 30
    4592 1593.06    4603 1592.83  4620.1 1591.27  4629.3 1590.88    4746 1589.03
  4799.4 1588.19  4823.8  1588.4  4841.6 1587.81  4862.7 1588.33    4950 1588.61
  4966.6 1587.97  4982.3 1585.21  4994.2 1582.32  5000.8 1582.17  5003.5 1581.67
  5006.8 1582.17  5009.6 1583.51  5017.3    1586  5025.3 1587.73  5031.1 1588.69
  5046.8 1589.71  5089.8 1591.54  5156.3 1593.28  5169.9 1594.86  5185.6 1593.96
  5191.4 1594.02    5260 1596.19  5281.5 1597.77    5303 1597.67  5344.2 1599.18
#Mann= 4 ,-1 , 0
    4592     .05       0    4746      .1       0  5000.8     .07       0
  5006.8      .1       0
Bank Sta=5000.8,5006.8
XS Rating Curve= 0 ,0
Exp/Cntr=0.3,0.1

Type RM Length L Ch R = 1 ,6882    ,104,104,104
BEGIN DESCRIPTION:
Mapping XS b95dc8f9
END DESCRIPTION:
XS GIS Cut Line= 3
      2774158.51      10055929.3      2774066.28     10055515.86
      2773726.67     10055341.17
#Sta/Elev= 30
  4533.8 1592.44  4555.9 1591.05    4561 1591.23  4590.7 1590.21    4694 1588.71
  4783.4 1587.73  4898.1 1588.02  4908.4 1587.75  4918.6 1586.31  4924.1 1586.69
  4929.2 1587.81  4966.2 1588.13    4978 1587.36  4988.7 1585.53  4994.6 1582.33
  4997.2 1581.83  4999.9 1581.33  5003.2 1581.83  5016.7 1583.92  5022.4 1587.28
  5044.9 1590.32  5083.3 1591.31  5105.5 1592.51  5144.2 1593.59  5157.4 1594.69
    5172 1593.82  5255.1  1596.6  5282.9 1598.35  5299.4    1598  5339.3 1599.27
#Mann= 4 ,-1 , 0
  4533.8     .05       0    4694      .1       0  4997.2     .07       0
  5003.2      .1       0
Bank Sta=4997.2,5003.2
XS Rating Curve= 0 ,0
Exp/Cntr=0.3,0.1

Type RM Length L Ch R = 1 ,6778    ,868,868,868
BEGIN DESCRIPTION:
UNT056 IN NNOGR 14.0
END DESCRIPTION:
XS GIS Cut Line= 3
      2774184.15     10055992.45      2774158.14     10055472.18
      2773762.42     10055154.31
#Sta/Elev= 30
  4411.8 1594.11  4510.6 1590.42  4653.1 1588.01    4791 1586.97    4821 1585.38
  4831.1 1586.28  4851.1 1586.53  4881.1 1583.77  4901.1 1586.35  4967.3 1587.48
  4981.7 1585.87  4993.1 1581.39  4995.8 1580.89  4999.1 1581.39  5009.3 1583.67
  5015.7 1584.35  5023.3 1587.02  5037.7 1589.43  5066.5 1590.08  5087.3 1591.54
  5109.7 1591.21  5151.3 1592.23  5173.7 1594.09  5188.1 1594.61  5208.9 1594.24
  5244.1 1595.95  5272.9 1596.56  5308.1 1598.81  5329.9 1598.35  5440.3 1600.51
#Mann= 4 ,-1 , 0
  4411.8     .05       0  4653.1      .1       0  4993.1     .07       0
  4999.1      .1       0
Bank Sta=4993.1,4999.1
XS Rating Curve= 0 ,0
Exp/Cntr=0.3,0.1

Type RM Length L Ch R = 1 ,5910    ,390,390,390
BEGIN DESCRIPTION:
UNT056 IN NNOGR 13.0
END DESCRIPTION:
XS GIS Cut Line= 3
      2774990.62     10055855.87      2774697.96     10055296.57
      2774210.19     10054925.86
#Sta/Elev= 30
  4286.9 1591.09  4379.6 1589.39  4458.8 1586.88  4563.5 1584.67  4651.8 1583.45
  4831.1 1583.17  4927.4 1581.57  4948.3 1580.83  4962.8 1579.61  4983.6    1579
  4991.9 1577.46  4995.2 1575.28  4997.9 1574.78  5001.2 1575.28  5005.4 1576.03
  5012.7 1578.33    5019 1579.44  5027.3 1580.09  5077.2 1582.06  5083.5 1583.13
  5102.9 1582.57  5118.8 1581.92  5156.2 1583.06  5247.7 1583.31  5305.9 1585.91
  5347.6 1585.86  5376.6 1587.75    5412 1587.39  5526.4 1589.71  5530.8 1590.24
#Mann= 4 ,-1 , 0
  4286.9      .1       0  4995.2     .07       0  5001.2      .1       0
  5102.9     .05       0
Bank Sta=4995.2,5001.2
XS Rating Curve= 0 ,0
Exp/Cntr=0.3,0.1

Type RM Length L Ch R = 1 ,5520    ,384,384,384
BEGIN DESCRIPTION:
UNT056 IN NNOGR 12.0
END DESCRIPTION:
XS GIS Cut Line= 3
      2775192.27     10055777.88      2775055.68     10055068.94
      2774341.89     10054582.26
#Sta/Elev= 30
  4074.1 1590.63    4335 1586.85  4646.4 1580.79  4833.5 1579.33  4913.7  1580.1
  4971.1 1579.33    4986 1577.45  4992.1 1575.65  4995.5 1573.93  4998.2 1573.43
  5001.5 1573.93    5007 1575.25  5021.9  1577.3    5035 1578.38  5048.9 1578.81
  5071.1 1578.68  5078.8 1579.33  5135.7 1578.81  5150.6 1579.34  5192.6 1579.49
  5274.3 1581.55  5416.9 1585.98  5422.9 1585.64  5431.8 1585.97  5437.9 1585.48
  5452.8 1586.41  5482.6 1587.21  5503.6  1587.2  5596.4 1589.15    5660 1589.02
#Mann= 5 ,-1 , 0
  4074.1      .1       0  4995.5     .07       0  5001.5      .1       0
    5035     .05       0  5274.3      .1       0
Bank Sta=4995.5,5001.5
XS Rating Curve= 0 ,0
Exp/Cntr=0.3,0.1

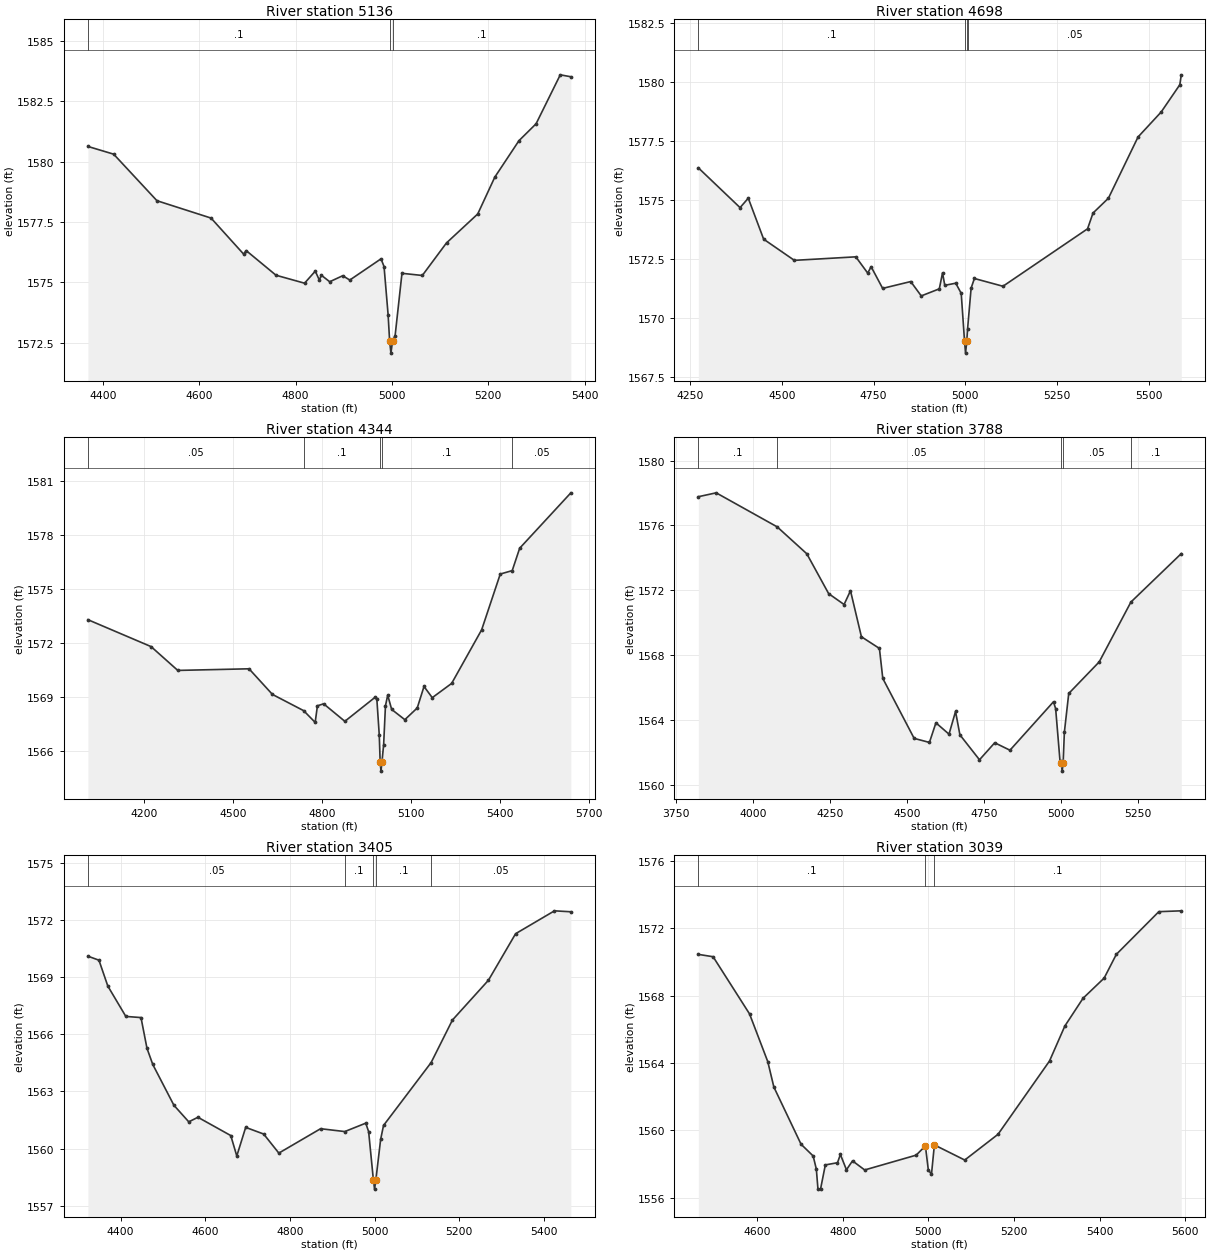
Type RM Length L Ch R = 1 ,5136    ,438,438,438
BEGIN DESCRIPTION:
UNT056 IN NNOGR 11.0
END DESCRIPTION:
XS GIS Cut Line= 3
      2775406.88     10055146.96      2775192.26     10054711.22
      2774775.98     10054405.52
#Sta/Elev= 30
  4369.1 1580.63  4422.5 1580.31  4512.3 1578.38  4624.6 1577.66    4692 1576.17
  4697.6 1576.31  4759.4 1575.29  4818.6 1574.96  4840.9 1575.46  4849.3 1575.09
  4853.5 1575.29  4870.8 1575.02  4897.9 1575.27  4912.5 1575.09  4977.3 1575.97
  4983.6 1575.65    4992 1573.66  4995.2 1572.56  4997.9 1572.06  5001.2 1572.56
  5006.6 1572.79  5020.8 1575.37    5063 1575.28  5113.2 1576.63    5178 1577.83
  5213.5 1579.36  5263.6 1580.87  5299.1 1581.57  5349.3  1583.6  5371.3 1583.52
#Mann= 3 ,-1 , 0
  4369.1      .1       0  4995.2     .07       0  5001.2      .1       0
Bank Sta=4995.2,5001.2
XS Rating Curve= 0 ,0
Exp/Cntr=0.3,0.1

Type RM Length L Ch R = 1 ,4698    ,354,354,354
BEGIN DESCRIPTION:
UNT056 IN NNOGR 10.0
END DESCRIPTION:
XS GIS Cut Line= 3
      2775628.03     10054873.84      2775471.93     10054366.52
      2774822.54     10053924.93
#Sta/Elev= 30
  4272.6 1576.37  4386.3 1574.68  4408.7 1575.08  4450.6 1573.34  4534.3 1572.44
  4701.7 1572.59  4734.2  1571.9  4743.5 1572.17  4774.9 1571.25  4851.4 1571.54
  4880.1 1570.93  4929.3 1571.23  4938.1 1571.91  4944.2 1571.38  4974.1 1571.47
    4989 1571.04  4998.1    1569  5000.8  1568.5  5004.1    1569  5006.4 1569.54
    5016 1571.26  5024.9 1571.67  5102.8 1571.34  5333.3 1573.78  5348.2 1574.45
  5390.2 1575.08  5470.9 1577.68  5533.9 1578.74  5584.8  1579.9  5588.7 1580.32
#Mann= 4 ,-1 , 0
  4272.6      .1       0  4998.1     .07       0  5004.1      .1       0
  5006.4     .05       0
Bank Sta=4998.1,5004.1
XS Rating Curve= 0 ,0
Exp/Cntr=0.3,0.1

Type RM Length L Ch R = 1 ,4344    ,556,556,556
BEGIN DESCRIPTION:
UNT056 IN NNOGR 9.0
END DESCRIPTION:
XS GIS Cut Line= 3
      2775785.77     10054786.35      2775799.91     10054169.39
      2774973.67     10053588.55
#Sta/Elev= 30
  4011.4  1573.3  4224.1 1571.81  4314.1 1570.49  4554.2 1570.58    4633 1569.16
  4738.2 1568.26    4777 1567.61  4784.6 1568.53  4805.5 1568.64    4877 1567.67
    4978 1568.99  4984.8  1568.9  4992.9 1566.92    4996 1565.41  4998.7 1564.91
    5002 1565.41  5007.7 1566.38  5013.8 1568.53  5021.4 1569.12  5034.7 1568.33
  5079.1 1567.76  5120.9 1568.41  5143.7  1569.6  5171.5 1568.98  5236.8 1569.77
  5337.9 1572.74  5400.6 1575.83  5440.9 1576.02    5466 1577.26  5638.5 1580.33
#Mann= 5 ,-1 , 0
  4011.4     .05       0  4738.2      .1       0    4996     .07       0
    5002      .1       0  5440.9     .05       0
Bank Sta=4996,5002
XS Rating Curve= 0 ,0
Exp/Cntr=0.3,0.1

Type RM Length L Ch R = 1 ,3788    ,383,383,383
BEGIN DESCRIPTION:
UNT056 IN NNOGR 8.0
END DESCRIPTION:
XS GIS Cut Line= 3
      2776644.96     10054459.33      2776287.85     10053976.69
      2775597.07     10053298.28
#Sta/Elev= 30
    3822 1577.77  3879.9 1578.01  4078.1 1575.91  4174.3 1574.25  4245.3 1571.79
  4295.4 1571.12  4316.2 1571.97  4351.7 1569.13  4410.2 1568.41  4421.1 1566.56
    4523 1562.86  4572.6 1562.61  4593.7 1563.82  4636.2 1563.12  4657.4 1564.52
  4671.6 1563.08  4735.2 1561.54  4784.7 1562.59  4834.2 1562.13  4975.6 1565.12
  4982.6 1564.69  4996.8 1561.45  5000.9 1561.34  5003.7 1560.84  5006.9 1561.34
  5010.9 1563.24  5025.1 1565.63  5124.1 1567.58    5227 1571.27  5390.6 1574.26
#Mann= 5 ,-1 , 0
    3822      .1       0  4078.1     .05       0  5000.9    .035       0
  5006.9     .05       0    5227      .1       0
Bank Sta=5000.9,5006.9
XS Rating Curve= 0 ,0
Exp/Cntr=0.3,0.1

Type RM Length L Ch R = 1 ,3405    ,366,366,366
BEGIN DESCRIPTION:
UNT056 IN NNOGR 7.0
END DESCRIPTION:
XS GIS Cut Line= 2
      2776642.64     10053846.21       2775869.4       10053008.
#Sta/Elev= 30
  4322.9 1570.09  4348.9 1569.88  4369.9 1568.52  4412.4 1566.93  4448.2 1566.87
  4462.3 1565.26    4476 1564.41  4525.9 1562.27    4561  1561.4  4582.6 1561.64
  4660.2 1560.68  4674.4 1559.61  4695.4 1561.11  4737.9 1560.76  4773.7 1559.76
  4872.3 1561.04  4929.4 1560.89  4978.9 1561.33  4985.7 1560.89  4996.9 1558.37
  4999.7 1557.87  5002.9 1558.37  5014.1 1560.48  5020.9 1561.21  5133.3 1564.51
  5183.6 1566.74  5268.7 1568.83  5332.8 1571.27  5424.6 1572.47  5463.3 1572.42
#Mann= 5 ,-1 , 0
  4322.9     .05       0  4929.4      .1       0  4996.9     .07       0
  5002.9      .1       0  5133.3     .05       0
Bank Sta=4996.9,5002.9
XS Rating Curve= 0 ,0
Exp/Cntr=0.3,0.1

Type RM Length L Ch R = 1 ,3039    ,472,472,472
BEGIN DESCRIPTION:
UNT056 IN NNOGR 6.0
END DESCRIPTION:
XS GIS Cut Line= 2
       2776883.3     10053508.02      2776050.78     10052747.05
#Sta/Elev= 30
  4462.6 1570.46  4497.1 1570.32  4582.2 1566.92  4624.8 1564.08    4639 1562.57
  4702.5 1559.17  4730.8 1558.47  4738.2 1557.69    4742  1556.5    4748  1556.5
  4759.2 1557.94  4787.6 1558.07  4794.4 1558.56  4808.5 1557.65  4822.7 1558.18
  4851.1 1557.64  4971.3 1558.52  4992.9 1559.07  4999.7 1557.65  5007.1 1557.38
  5013.9 1559.13  5084.8 1558.23  5162.5 1559.76  5282.8 1564.12  5318.6  1566.2
  5361.1 1567.85  5410.4 1569.05  5438.8 1570.46  5538.1    1573  5590.5 1573.05
#Mann= 3 , 0 , 0
  4462.6      .1       0  4992.9     .07       0  5013.9      .1       0
Bank Sta=4992.9,5013.9
XS Rating Curve= 0 ,0
Exp/Cntr=0.3,0.1

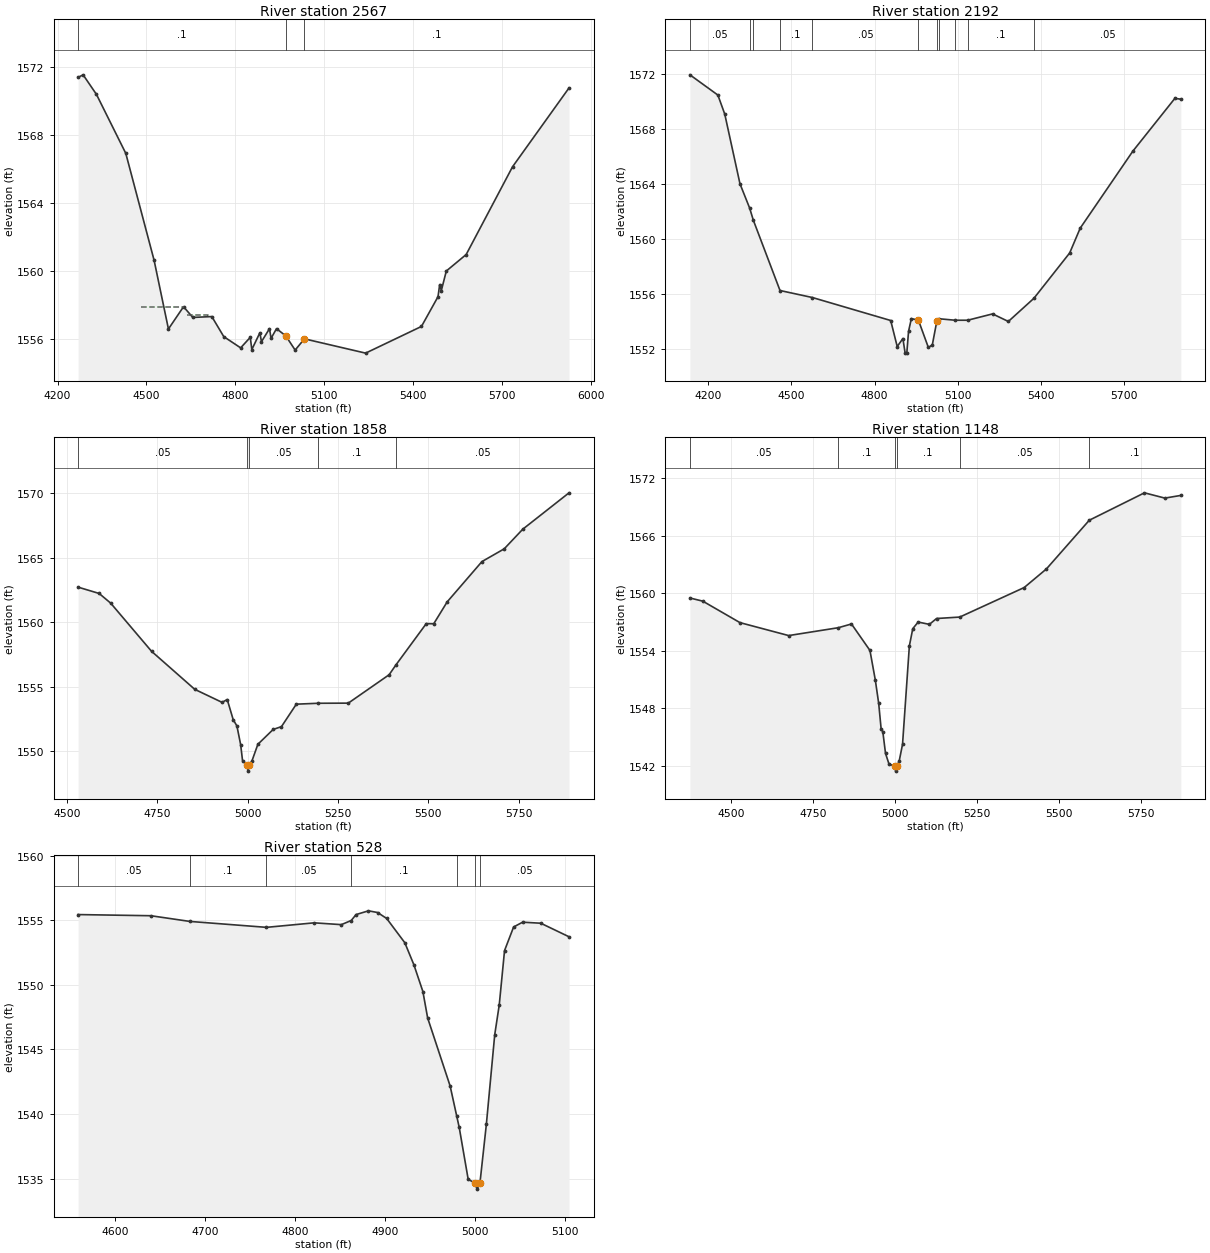
Type RM Length L Ch R = 1 ,2567    ,375,375,375
BEGIN DESCRIPTION:
UNT056 IN NNOGR 5.0
END DESCRIPTION:
XS GIS Cut Line= 4
      2776940.17     10053486.95      2776731.59     10053175.84
      2776918.98     10052576.53      2776332.77     10052283.42
#Sta/Elev= 30
  4269.3 1571.39  4286.3 1571.54  4331.3 1570.39  4430.4 1566.92    4526 1560.63
  4574.4 1556.59  4625.4  1557.9  4656.6 1557.27  4720.9 1557.32  4761.3 1556.14
  4818.3 1555.48  4850.8  1556.1    4856 1555.38  4883.3 1556.37  4888.5 1555.84
  4915.7 1556.61    4921 1556.04  4939.4 1556.61  4970.9 1556.18  5002.3 1555.35
  5033.7 1556.01  5240.3 1555.17  5428.9 1556.74  5484.8 1558.49  5490.4  1559.2
    5496 1558.85  5512.8    1560  5579.9 1560.97  5736.4 1566.13  5927.2 1570.77
#Mann= 3 , 0 , 0
  4269.3      .1       0  4970.9     .07       0  5033.7      .1       0
#XS Ineff= 2 ,-1
 4480.62 4626.55 1557.89 4636.86 4708.24 1557.39
Permanent Ineff=
       F       F
Bank Sta=4970.9,5033.7
XS Rating Curve= 0 ,0
Exp/Cntr=0.3,0.1

Type RM Length L Ch R = 1 ,2192    ,334,334,334
BEGIN DESCRIPTION:
Mapping XS 7bde8c21
END DESCRIPTION:
XS GIS Cut Line= 4
      2777017.97     10053476.34       2776940.2     10053271.31
      2777095.77     10052523.49      2776347.93     10052274.22
#Sta/Elev= 30
  4133.9 1571.93  4234.7 1570.46  4259.5 1569.08  4314.5 1564.01  4349.3 1562.25
  4362.6 1561.37  4458.9 1556.26  4575.7 1555.75  4858.3 1554.08  4881.8 1552.19
  4902.3 1552.77  4910.4 1551.71  4916.4 1551.71  4922.7 1553.29  4932.9 1554.22
  4958.4  1554.1  4994.2 1552.12  5008.5 1552.31  5024.8 1554.04  5031.5 1554.21
  5090.7  1554.1    5136  1554.1  5225.9 1554.56  5282.8 1554.01  5374.9 1555.69
  5504.2 1558.99  5542.1 1560.79  5731.9 1566.38  5883.7 1570.22  5905.3 1570.16
#Mann= 11 ,-1 , 0
  4133.9     .05       0  4349.3      .1       0  4362.6     .05       0
  4458.9      .1       0  4575.7     .05       0  4958.4    .035       0
  5024.8     .05       0  5031.5      .1       0  5090.7     .05       0
    5136      .1       0  5374.9     .05       0
Bank Sta=4958.4,5024.8
XS Rating Curve= 0 ,0
Exp/Cntr=0.3,0.1

Type RM Length L Ch R = 1 ,1858    ,710,710,710
BEGIN DESCRIPTION:
UNT056 IN NNOGR 4.0
END DESCRIPTION:
XS GIS Cut Line= 2
      2777686.28       10052573.      2776363.89     10052261.85
#Sta/Elev= 30
  4531.2 1562.73  4589.5 1562.24  4621.4 1561.49  4734.4 1557.76    4854 1554.81
  4929.6  1553.8  4943.9 1554.02  4960.4 1552.46  4970.7 1551.97    4981 1550.53
  4986.3 1549.28  4998.5 1548.97  5001.3 1548.47  5004.5 1548.97  5011.8 1549.22
  5028.7 1550.55    5071  1551.7    5094 1551.92  5135.1 1553.66  5195.9 1553.73
  5278.9 1553.74  5391.9 1555.94  5410.4 1556.69  5494.6  1559.9  5515.3 1559.89
  5552.6 1561.59  5648.7 1564.71  5710.4  1565.7  5761.7 1567.22  5889.7 1570.04
#Mann= 5 ,-1 , 0
  4531.2     .05       0  4998.5    .035       0  5004.5     .05       0
  5195.9      .1       0  5410.4     .05       0
Bank Sta=4998.5,5004.5
XS Rating Curve= 0 ,0
Exp/Cntr=0.3,0.1

Type RM Length L Ch R = 1 ,1148    ,620,620,620
BEGIN DESCRIPTION:
UNT056 IN NNOGR 2.0
END DESCRIPTION:
XS GIS Cut Line= 4
      2777520.05     10052187.58      2777224.83     10051869.38
      2776876.55     10051772.14      2776245.41       10052078.
#Sta/Elev= 30
    4374  1559.5  4413.2 1559.17  4526.6 1556.93  4675.1 1555.58  4826.4  1556.4
  4866.6 1556.79  4922.9 1554.03  4939.3 1550.94  4949.6  1548.5    4957 1545.85
  4962.2 1545.54  4970.4 1543.29  4980.8  1542.2  4998.6 1541.94  5001.3 1541.44
  5004.6 1541.94  5011.9 1542.46  5022.3 1544.24  5043.1  1554.5  5053.5  1556.3
  5069.9 1556.99  5104.1 1556.75  5126.1 1557.36  5196.7 1557.51  5393.2 1560.59
    5461 1562.53  5591.7 1567.61    5760 1570.47  5822.2 1569.92    5871  1570.2
#Mann= 6 ,-1 , 0
    4374     .05       0  4826.4      .1       0  4998.6     .07       0
  5004.6      .1       0  5196.7     .05       0  5591.7      .1       0
Bank Sta=4998.6,5004.6
XS Rating Curve= 0 ,0
Exp/Cntr=0.3,0.1

Type RM Length L Ch R = 1 ,528     ,0,0,0
BEGIN DESCRIPTION:
UNT056 IN NNOGR 1.0
END DESCRIPTION:
XS GIS Cut Line= 2
      2777738.78     10051398.21      2777197.32     10051328.77
#Sta/Elev= 30
  4558.8 1555.45  4639.8 1555.36  4682.9 1554.92  4768.3 1554.46  4821.3 1554.81
  4851.5 1554.67  4862.5 1554.99  4867.9 1555.45  4881.7 1555.74  4891.8 1555.61
  4901.9 1555.15  4922.1 1553.27  4932.2 1551.56  4942.2 1549.49  4947.5 1547.44
  4972.5 1542.17  4979.7 1539.88  4982.6 1538.96  4992.6 1534.93  4999.7 1534.68
  5002.5 1534.18  5005.7 1534.68  5012.8 1539.21  5022.1 1546.15  5027.1 1548.44
    5033 1552.66  5043.1 1554.49  5053.1 1554.86  5073.3 1554.78  5104.7 1553.73
#Mann= 7 ,-1 , 0
  4558.8     .05       0  4682.9      .1       0  4768.3     .05       0
  4862.5      .1       0  4979.7     .05       0  4999.7    .035       0
  5005.7     .05       0
Bank Sta=4999.7,5005.7
XS Rating Curve= 0 ,0
Exp/Cntr=0.3,0.1

Chan Stop Cuts=-1
Use User Specified Reach Order=0
Composite Channel Slope=5