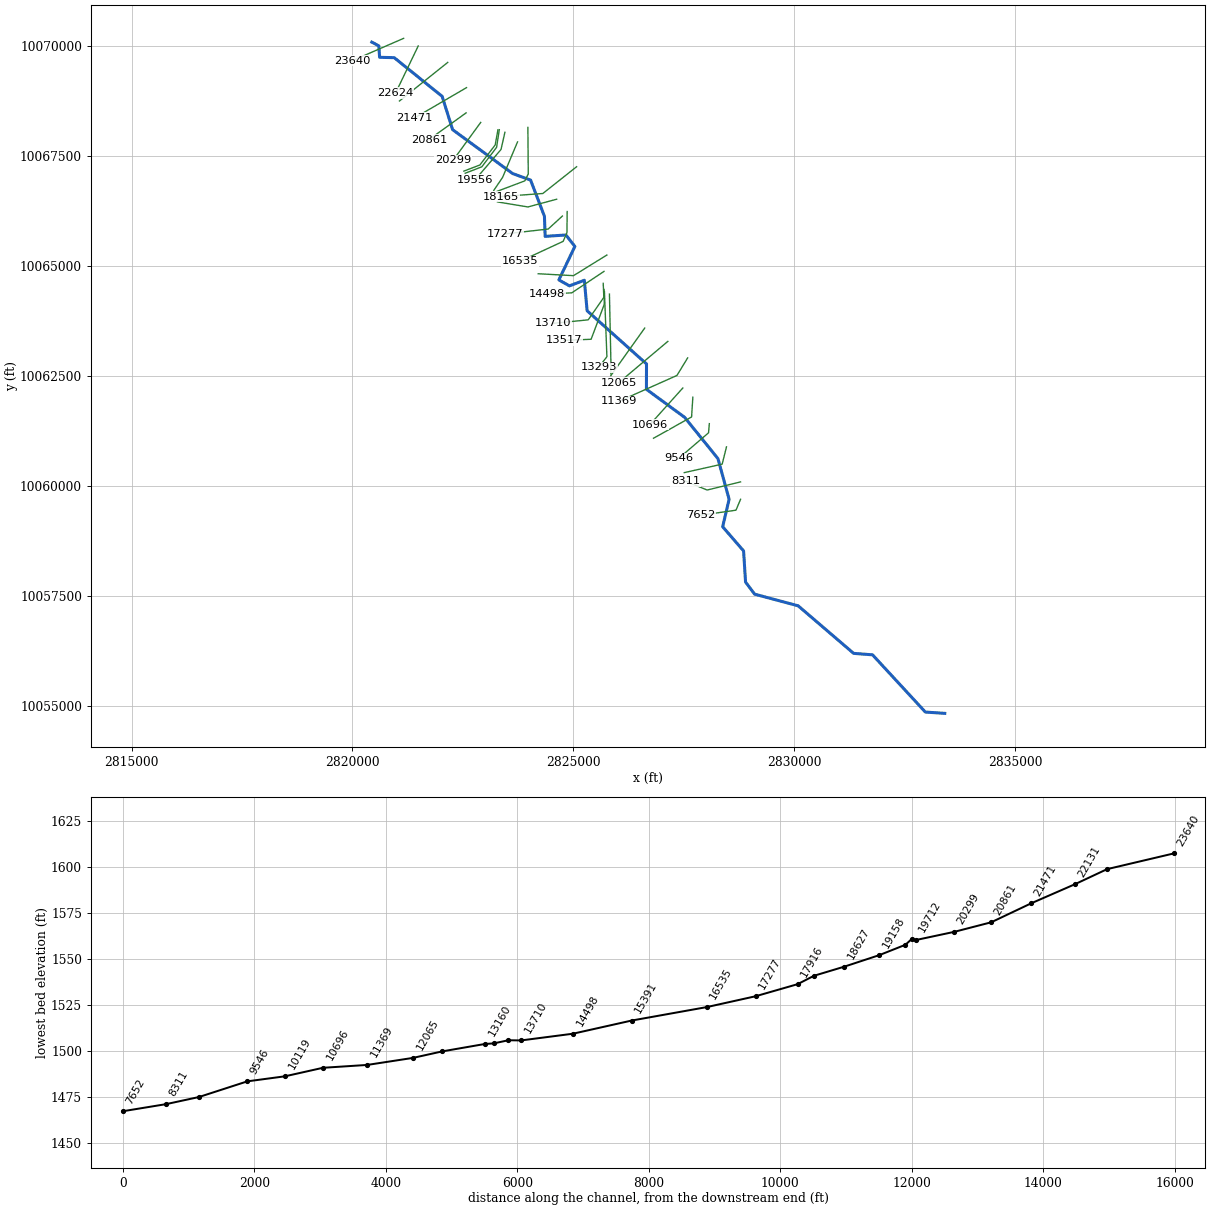
--- UNT057 IN NNOGR.prj (project) ---

Proj Title=UNT057 IN NNOGR Base Level Engineering
Current Plan=p01
Default Exp/Contr=0.3,0.1
English Units
Geom File=g01
Flow File=f01
Plan File=p01
BEGIN DESCRIPTION:
UNT057 IN NNOGR
END DESCRIPTION:

--- UNT057 IN NNOGR.p01 (plan) ---

Plan Title=Multiple Run
Short Identifier=Multiple
Geom File=g01
Flow File=f01
Subcritical Flow
K Sum by GR= 0
Std Step Tol= 0.01
Critical Tol= 0.01
Num of Std Step Trials= 20
Max Error Tol= 0.3
Flow Tol Ratio= 0.001
Split Flow NTrial= 30
Split Flow Tol= 0.02
Split Flow Ratio= 0.02
Log Output Level= 0
Friction Slope Method= 1
Unsteady Friction Slope Method= 2
Unsteady Bridges Friction Slope Method= 1
Parabolic Critical Depth
Global Vel Dist=  1 , 1 , 1
Global Log Level= 0
CheckData=True
Encroach Param= -1, 0, 0, 0
BEGIN DESCRIPTION:
Multiple Run
END DESCRIPTION:

--- UNT057 IN NNOGR.f01 (steady flow) ---

Flow Title=Multiple
Number of Profiles=7
Profile Names=10-year,25-year,50-year,1pct_min,100-year,1pct_plu,500-year
River Rch & RM= UNT057 IN NNOGR,Reach-1,23640
    1285    1911    2467    2332    3153    4264    5170
River Rch & RM= UNT057 IN NNOGR,Reach-1,18165
    2351    3588    4714    4521    6114    8269   10335
River Rch & RM= UNT057 IN NNOGR,Reach-1,12511
    2467    3748    4909    4690    6343    8577   10638
River Rch & RM= UNT057 IN NNOGR,Reach-1,1041
    3340    5142    6794    6543    8849   11968   15084
Boundary for River Rch & Prof#=UNT057 IN NNOGR,Reach-1,1
Up Type=0
Dn Type=3
Dn Slope=0.005
Boundary for River Rch & Prof#=UNT057 IN NNOGR,Reach-1,2
Up Type=0
Dn Type=3
Dn Slope=0.005
Boundary for River Rch & Prof#=UNT057 IN NNOGR,Reach-1,3
Up Type=0
Dn Type=3
Dn Slope=0.005
Boundary for River Rch & Prof#=UNT057 IN NNOGR,Reach-1,4
Up Type=0
Dn Type=3
Dn Slope=0.005
Boundary for River Rch & Prof#=UNT057 IN NNOGR,Reach-1,5
Up Type=0
Dn Type=3
Dn Slope=0.005
Boundary for River Rch & Prof#=UNT057 IN NNOGR,Reach-1,6
Up Type=0
Dn Type=3
Dn Slope=0.005
Boundary for River Rch & Prof#=UNT057 IN NNOGR,Reach-1,7
Up Type=0
Dn Type=3
Dn Slope=0.005

--- UNT057 IN NNOGR.g01 (geometry) ---

Geom Title=Existing Conditions

River Reach=UNT057 IN NNOGR,Reach-1
Reach XY= 30
      2820438.47     10070083.73      2820597.96     10069998.56
      2820615.25     10069738.43      2820946.21     10069730.18
      2822031.22     10068851.40      2822268.26     10068094.74
      2823625.55     10067098.41      2824033.17     10066949.89
      2824346.88     10066128.07      2824363.19     10065670.77
      2824832.91     10065702.46      2825035.90     10065442.41
      2824673.67     10064681.59      2824913.29     10064547.14
      2825250.69     10064673.99      2825313.05     10063981.19
      2826657.78     10062773.87      2826655.72     10062197.01
      2827521.79     10061560.17      2828275.06     10060621.71
      2828527.80     10059700.12      2828381.49     10059074.99
      2828855.43     10058526.01      2828899.81     10057819.43
      2829105.35     10057544.10      2830091.27     10057279.05
      2831347.02     10056199.46      2831774.84     10056166.17
      2832970.02     10054866.03      2833409.27     10054836.30

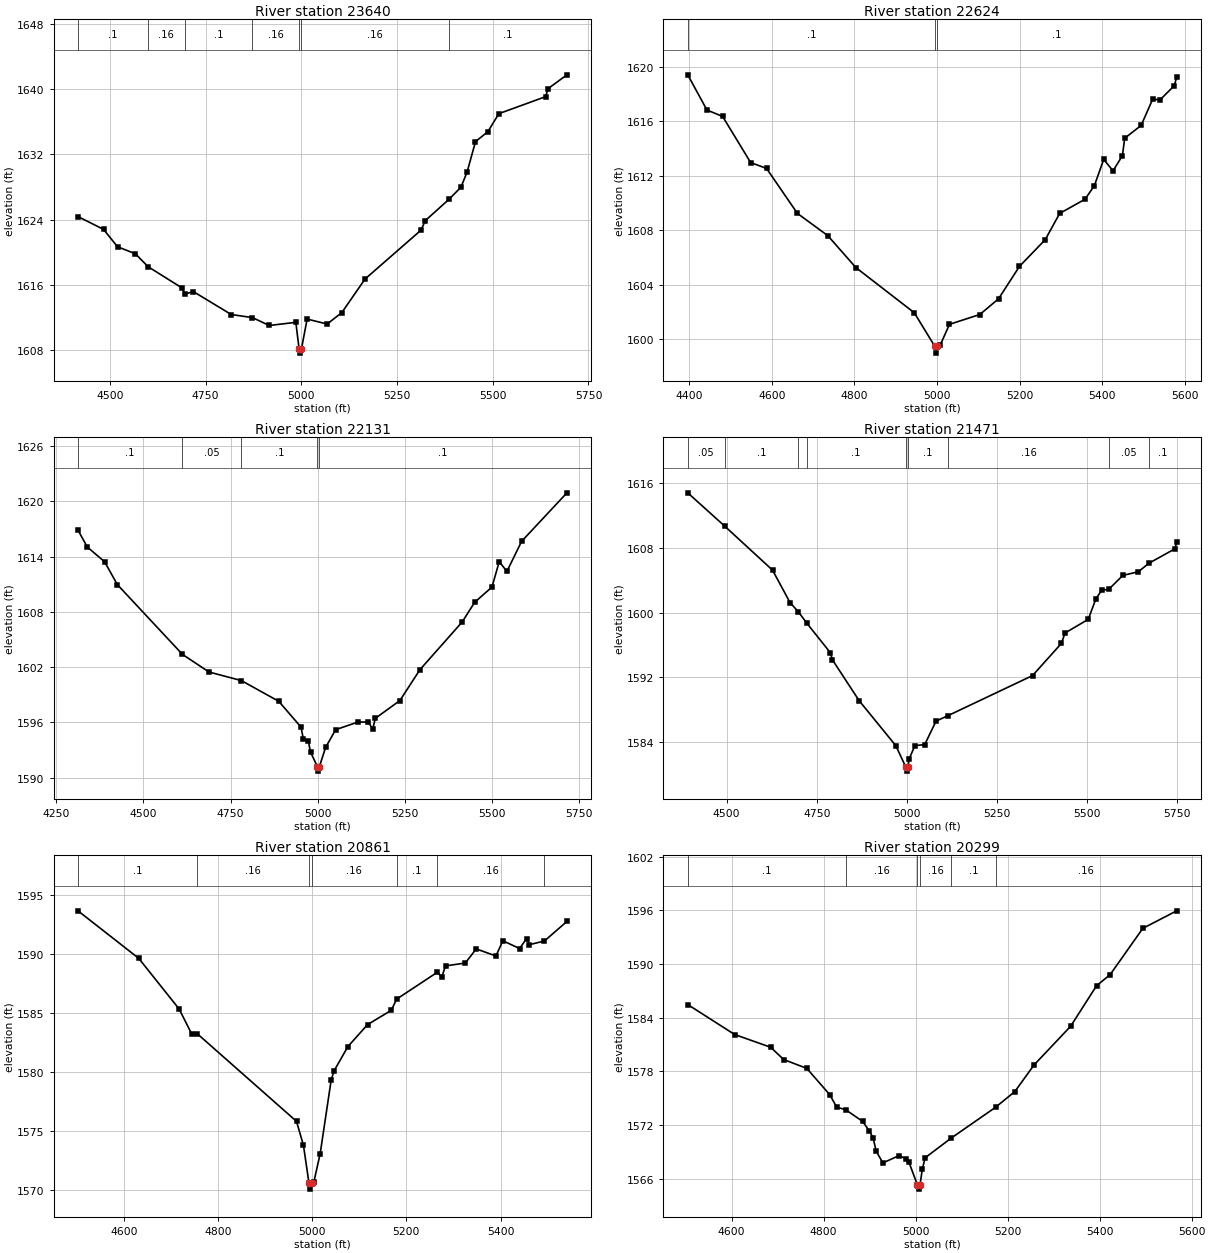
Type RM Length L Ch R = 1,23640,1016,1016,1016
BEGIN DESCRIPTION:
UNT057 IN NNOGR 48.0
END DESCRIPTION:
XS GIS Cut Line= 2
      2821159.71     10070169.30      2819989.67     10069657.95
#Sta/Elev= 30
  4416.8 1624.36  4483.6 1622.78  4520.0 1620.65  4566.8 1619.78  4599.7 1618.20
  4689.2 1615.56  4695.5 1614.82  4718.1 1615.13  4817.1 1612.31  4872.5 1611.93
  4916.2 1610.96  4985.7 1611.35  4994.3 1608.06  4997.0 1607.56  5000.3 1608.06
  5015.2 1611.75  5067.5 1611.14  5105.7 1612.54  5166.5 1616.68  5312.4 1622.68
  5324.0 1623.87  5385.6 1626.48  5416.9 1627.97  5433.1 1629.86  5454.9 1633.58
  5487.1 1634.80  5515.9 1637.02  5638.4 1639.12  5643.9 1640.08  5693.7 1641.80
#Mann=7,-1,0
  4416.8     0.1       0  4599.7    0.16       0  4695.5     0.1       0
  4872.5    0.16       0  4994.3    0.07       0  5000.3    0.16       0
  5385.6     0.1       0
Bank Sta=4994.3,5000.3
Exp/Cntr=0.3,0.1

Type RM Length L Ch R = 1,22624,493,493,493
BEGIN DESCRIPTION:
UNT057 IN NNOGR 46.0
END DESCRIPTION:
XS GIS Cut Line= 2
      2821489.54     10069995.68      2820977.56     10068928.32
#Sta/Elev= 30
  4396.5 1619.39  4443.0 1616.81  4480.9 1616.34  4548.8 1612.96  4587.2 1612.53
  4662.1 1609.23  4735.6 1607.60  4803.6 1605.26  4945.0 1601.95  4994.6 1599.49
  4997.3 1598.99  5000.6 1599.49  5007.4 1599.55  5030.1 1601.10  5103.6 1601.82
  5148.9 1602.97  5199.7 1605.35  5262.1 1607.31  5297.0 1609.23  5358.3 1610.27
  5380.9 1611.26  5403.6 1613.19  5426.2 1612.35  5448.9 1613.47  5454.4 1614.74
  5494.2 1615.68  5522.4 1617.62  5539.5 1617.54  5574.3 1618.59  5580.3 1619.21
#Mann=3,-1,0
  4396.5     0.1       0  4994.6    0.07       0  5000.6     0.1       0
Bank Sta=4994.6,5000.6
Exp/Cntr=0.3,0.1

Type RM Length L Ch R = 1,22131,660,660,660
BEGIN DESCRIPTION:
UNT057 IN NNOGR 45.0
END DESCRIPTION:
XS GIS Cut Line= 2
      2822157.94     10069622.41      2821064.17     10068745.65
#Sta/Elev= 30
  4312.5 1616.87  4339.1 1615.04  4388.7 1613.44  4425.5 1610.95  4612.1 1603.38
  4688.0 1601.47  4780.9 1600.54  4888.1 1598.29  4952.1 1595.48  4958.5 1594.20
  4972.9 1593.96  4979.3 1592.77  4998.7 1591.21  5001.4 1590.71  5004.7 1591.21
  5022.5 1593.29  5051.3 1595.21  5115.3 1596.04  5144.1 1596.04  5157.7 1595.30
  5164.9 1596.44  5235.4 1598.37  5293.0 1601.73  5414.0 1606.90  5449.8 1609.04
  5499.4 1610.69  5520.2 1613.45  5542.2 1612.39  5584.3 1615.65  5714.3 1620.92
#Mann=5,-1,0
  4312.5     0.1       0  4612.1    0.05       0  4780.9     0.1       0
  4998.7    0.07       0  5004.7     0.1       0
Bank Sta=4998.7,5004.7
Exp/Cntr=0.3,0.1

Type RM Length L Ch R = 1,21471,610,610,610
BEGIN DESCRIPTION:
UNT057 IN NNOGR 44.0
END DESCRIPTION:
XS GIS Cut Line= 2
      2822583.26     10069049.48      2821412.40     10068364.31
#Sta/Elev= 30
  4392.1 1614.80  4494.2 1610.70  4627.4 1605.24  4676.1 1601.22  4699.1 1600.09
  4721.9 1598.72  4787.7 1595.04  4793.5 1594.16  4867.8 1589.10  4969.5 1583.54
  4997.1 1580.90  4999.9 1580.40  5003.1 1580.90  5006.6 1581.93  5022.3 1583.55
  5049.6 1583.68  5081.0 1586.58  5114.7 1587.27  5348.7 1592.21  5428.9 1596.19
  5438.8 1597.47  5503.2 1599.16  5524.7 1601.71  5540.4 1602.74  5560.7 1602.89
  5599.1 1604.59  5642.1 1605.04  5672.2 1606.11  5743.7 1607.88  5748.7 1608.69
#Mann=9,-1,0
  4392.1    0.05       0  4494.2     0.1       0  4699.1    0.05       0
  4721.9     0.1       0  4997.1    0.07       0  5003.1     0.1       0
  5114.7    0.16       0  5560.7    0.05       0  5672.2     0.1       0
Bank Sta=4997.1,5003.1
Exp/Cntr=0.3,0.1

Type RM Length L Ch R = 1,20861,562,562,562
BEGIN DESCRIPTION:
UNT057 IN NNOGR 42.0
END DESCRIPTION:
XS GIS Cut Line= 2
      2822574.59     10068476.57      2821733.04     10067869.26
#Sta/Elev= 30
  4503.0 1593.65  4631.9 1589.62  4717.7 1585.32  4744.9 1583.16  4755.7 1583.24
  4966.8 1575.79  4981.6 1573.75  4993.3 1570.54  4996.0 1570.04  4999.3 1570.54
  5003.8 1570.68  5017.1 1573.06  5040.4 1579.30  5046.6 1580.08  5076.0 1582.14
  5117.7 1584.00  5168.0 1585.21  5179.4 1586.16  5265.8 1588.44  5275.1 1588.04
  5283.3 1588.98  5325.1 1589.22  5348.3 1590.42  5390.1 1589.82  5404.8 1591.11
  5440.4 1590.45  5455.1 1591.30  5461.3 1590.78  5493.0 1591.09  5540.8 1592.75
#Mann=7,-1,0
  4503.0     0.1       0  4755.7    0.16       0  4993.3    0.07       0
  4999.3    0.16       0  5179.4     0.1       0  5265.8    0.16       0
  5493.0    0.05       0
Bank Sta=4993.3,4999.3
Exp/Cntr=0.3,0.1

Type RM Length L Ch R = 1,20299,587,587,587
BEGIN DESCRIPTION:
UNT057 IN NNOGR 41.0
END DESCRIPTION:
XS GIS Cut Line= 2
      2822904.50     10068259.60      2822279.45     10067400.16
#Sta/Elev= 30
  4504.8 1585.47  4606.7 1582.12  4685.2 1580.69  4713.3 1579.32  4763.6 1578.33
  4813.8 1575.37  4828.5 1573.99  4847.8 1573.72  4884.9 1572.40  4899.6 1571.33
  4907.7 1570.55  4914.3 1569.08  4928.9 1567.76  4964.5 1568.59  4979.2 1568.21
  4985.4 1567.87  5003.7 1565.33  5006.4 1564.83  5009.7 1565.33  5014.7 1567.10
  5020.9 1568.34  5077.2 1570.53  5173.8 1573.98  5215.7 1575.74  5257.4 1578.71
  5337.0 1583.04  5393.4 1587.58  5422.8 1588.81  5493.9 1593.99  5567.5 1595.95
#Mann=6,-1,0
  4504.8     0.1       0  4847.8    0.16       0  5003.7    0.07       0
  5009.7    0.16       0  5077.2     0.1       0  5173.8    0.16       0
Bank Sta=5003.7,5009.7
Exp/Cntr=0.3,0.1

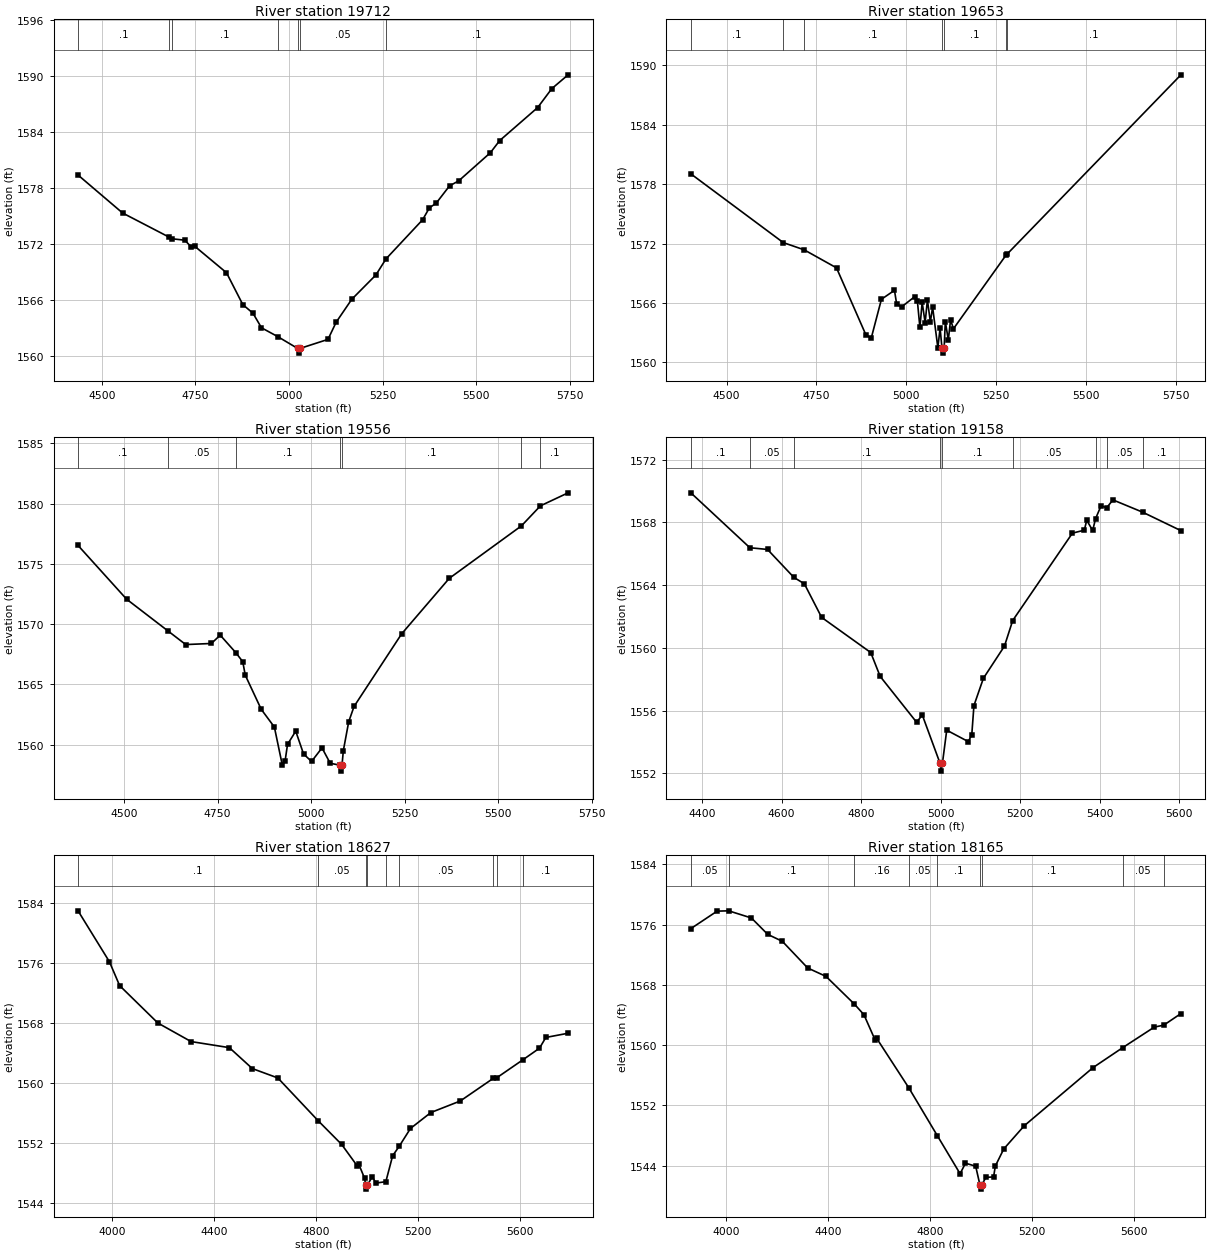
Type RM Length L Ch R = 1,19712,59,59,59
BEGIN DESCRIPTION:
Mapping XS 94986432
END DESCRIPTION:
XS GIS Cut Line= 4
      2823293.62     10068090.64      2823232.09     10067747.57
      2822885.29     10067292.63      2822522.59     10067153.13
#Sta/Elev= 30
  4436.4 1579.40  4555.4 1575.34  4678.1 1572.79  4688.1 1572.58  4721.7 1572.43
  4738.0 1571.74  4748.2 1571.78  4833.0 1568.95  4876.6 1565.54  4903.7 1564.62
  4926.5 1563.06  4970.2 1562.11  5023.2 1560.85  5026.0 1560.35  5029.2 1560.85
  5104.1 1561.82  5126.0 1563.66  5167.7 1566.11  5232.1 1568.71  5259.1 1570.43
  5357.0 1574.62  5375.0 1575.89  5393.4 1576.40  5428.8 1578.24  5453.4 1578.78
  5538.0 1581.79  5562.7 1583.08  5664.3 1586.62  5702.0 1588.64  5745.6 1590.12
#Mann=7,-1,0
  4436.4     0.1       0  4678.1    0.05       0  4688.1     0.1       0
  4970.2    0.05       0  5023.2   0.035       0  5029.2    0.05       0
  5259.1     0.1       0
Bank Sta=5023.2,5029.2
Exp/Cntr=0.3,0.1

Type RM Length L Ch R = 1,19653,97,97,97
BEGIN DESCRIPTION:
UNT057 IN NNOGR 39.0
END DESCRIPTION:
XS GIS Cut Line= 4
      2823325.31     10068094.35      2823263.79     10067693.50
      2822930.04     10067251.62      2822552.52     10067104.70
#Sta/Elev= 30
  4400.6 1579.04  4657.9 1572.10  4716.1 1571.37  4806.1 1569.55  4888.5 1562.74
  4903.0 1562.48  4931.2 1566.38  4967.5 1567.28  4973.8 1565.85  4988.4 1565.64
  5023.8 1566.64  5031.4 1566.16  5038.3 1563.53  5044.6 1566.08  5052.9 1564.01
  5059.2 1566.31  5067.4 1564.10  5073.7 1565.58  5088.3 1561.48  5094.5 1563.47
  5099.8 1561.44  5102.6 1560.94  5105.8 1561.44  5109.1 1564.12  5117.4 1562.26
  5123.7 1564.30  5131.7 1563.40  5277.4 1570.80  5280.1 1570.90  5765.0 1589.04
#Mann=7,-1,0
  4400.6     0.1       0  4657.9    0.05       0  4716.1     0.1       0
  5099.8    0.07       0  5105.8     0.1       0  5277.4    0.05       0
  5280.1     0.1       0
Bank Sta=5099.8,5105.8
Exp/Cntr=0.3,0.1

Type RM Length L Ch R = 1,19556,398,398,398
BEGIN DESCRIPTION:
Mapping XS 2e53c299
END DESCRIPTION:
XS GIS Cut Line= 3
      2823452.10     10068034.73      2823364.47     10067645.02
      2822773.42     10066951.43
#Sta/Elev= 30
  4376.6 1576.53  4506.4 1572.07  4618.0 1569.41  4664.6 1568.30  4733.1 1568.39
  4756.9 1569.08  4798.5 1567.63  4817.1 1566.88  4823.8 1565.76  4866.6 1562.92
  4901.7 1561.45  4922.6 1558.34  4930.3 1558.62  4936.9 1560.01  4958.8 1561.11
  4979.7 1559.22  5001.1 1558.59  5029.1 1559.72  5051.1 1558.44  5076.6 1558.29
  5079.4 1557.79  5082.6 1558.29  5086.2 1559.50  5100.5 1561.89  5114.8 1563.16
  5242.1 1569.19  5369.5 1573.80  5562.6 1578.16  5613.3 1579.82  5687.3 1580.90
#Mann=7,-1,0
  4376.6     0.1       0  4618.0    0.05       0  4798.5     0.1       0
  5076.6    0.07       0  5082.6     0.1       0  5562.6    0.05       0
  5613.3     0.1       0
Bank Sta=5076.6,5082.6
Exp/Cntr=0.3,0.1

Type RM Length L Ch R = 1,19158,531,531,531
BEGIN DESCRIPTION:
UNT057 IN NNOGR 38.0
END DESCRIPTION:
XS GIS Cut Line= 3
      2823737.79     10067816.83      2823399.26     10067009.56
      2823199.61     10066714.42
#Sta/Elev= 30
  4372.1 1569.88  4520.4 1566.38  4564.8 1566.27  4631.0 1564.49  4657.4 1564.08
  4700.8 1561.94  4824.2 1559.70  4847.9 1558.18  4939.3 1555.26  4953.9 1555.71
  4998.4 1552.64  5001.2 1552.14  5004.4 1552.64  5015.2 1554.75  5069.5 1554.02
  5078.2 1554.47  5083.6 1556.32  5107.4 1558.06  5160.3 1560.11  5181.0 1561.74
  5331.1 1567.31  5361.0 1567.50  5367.1 1568.13  5382.0 1567.48  5389.3 1568.23
  5403.0 1569.05  5417.3 1568.93  5432.9 1569.43  5507.3 1568.65  5603.8 1567.47
#Mann=9,-1,0
  4372.1     0.1       0  4520.4    0.05       0  4631.0     0.1       0
  4998.4    0.07       0  5004.4     0.1       0  5181.0    0.05       0
  5389.3     0.1       0  5417.3    0.05       0  5507.3     0.1       0
Bank Sta=4998.4,5004.4
Exp/Cntr=0.3,0.1

Type RM Length L Ch R = 1,18627,462,462,462
BEGIN DESCRIPTION:
UNT057 IN NNOGR 37.0
END DESCRIPTION:
XS GIS Cut Line= 4
      2823972.18     10068146.69      2823980.86     10067087.69
      2823902.73     10066931.44      2823260.41     10066688.40
#Sta/Elev= 30
  3867.6 1582.98  3990.6 1576.19  4030.6 1573.01  4180.6 1568.02  4310.6 1565.55
  4460.6 1564.74  4550.6 1561.95  4650.6 1560.70  4807.9 1555.02  4900.6 1551.84
  4962.3 1548.95  4967.9 1549.19  4990.2 1547.35  4995.1 1546.38  4997.9 1545.88
  5001.1 1546.38  5020.5 1547.54  5034.9 1546.69  5073.8 1546.87  5100.5 1550.33
  5126.0 1551.58  5170.4 1553.97  5250.3 1556.09  5365.6 1557.63  5494.1 1560.63
  5508.8 1560.73  5612.6 1563.16  5676.0 1564.67  5700.8 1566.10  5788.1 1566.66
#Mann=9,-1,0
  3867.6     0.1       0  4807.9    0.05       0  4995.1    0.04       0
  5001.1    0.05       0  5073.8     0.1       0  5126.0    0.05       0
  5494.1     0.1       0  5508.8    0.05       0  5612.6     0.1       0
Bank Sta=4995.1,5001.1
Exp/Cntr=0.3,0.1

Type RM Length L Ch R = 1,18165,249,249,249
BEGIN DESCRIPTION:
UNT057 IN NNOGR 36.0
END DESCRIPTION:
XS GIS Cut Line= 3
      2825074.62     10067252.63      2824310.72     10066644.98
      2823364.57     10066575.54
#Sta/Elev= 30
  3860.2 1575.46  3963.4 1577.78  4008.8 1577.82  4098.1 1576.87  4162.0 1574.70
  4219.7 1573.77  4319.0 1570.24  4391.1 1569.12  4502.7 1565.44  4540.0 1564.04
  4583.3 1560.73  4589.7 1560.92  4716.6 1554.32  4828.3 1547.99  4917.7 1542.94
  4938.8 1544.34  4978.9 1543.94  4996.0 1541.40  4998.7 1540.90  5002.0 1541.40
  5019.1 1542.47  5049.1 1542.51  5056.2 1543.97  5089.2 1546.23  5169.5 1549.30
  5440.2 1557.03  5556.4 1559.67  5680.8 1562.40  5717.5 1562.65  5785.0 1564.19
#Mann=9,-1,0
  3860.2    0.05       0  4008.8     0.1       0  4502.7    0.16       0
  4716.6    0.05       0  4828.3     0.1       0  4996.0    0.07       0
  5002.0     0.1       0  5556.4    0.05       0  5717.5     0.1       0
Bank Sta=4996,5002
Exp/Cntr=0.3,0.1

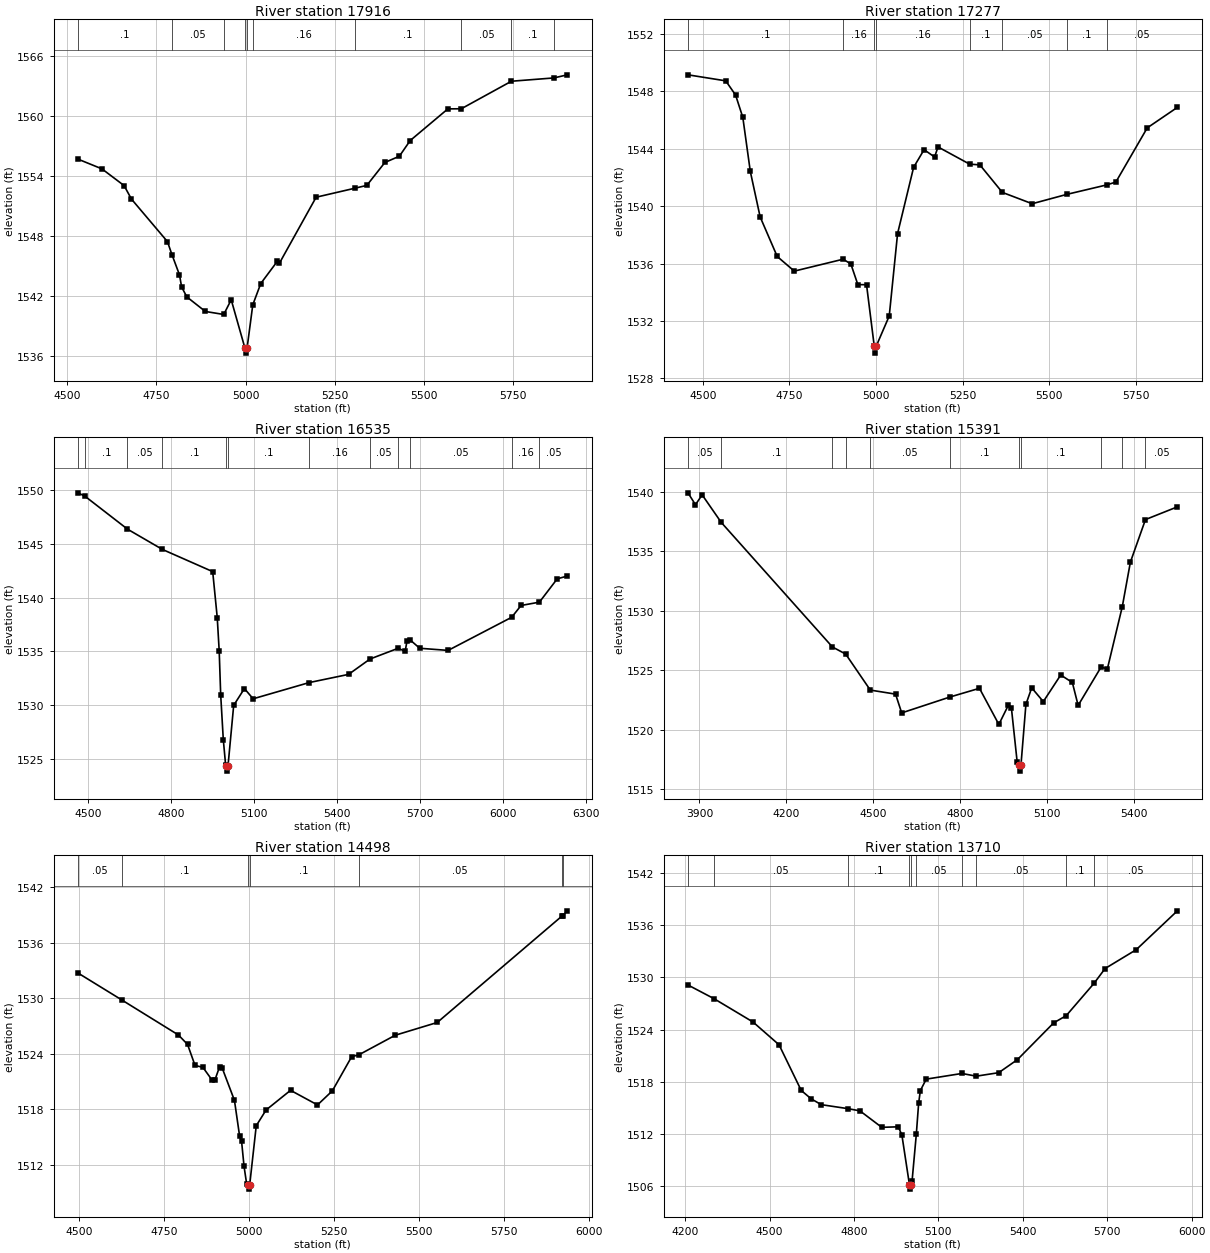
Type RM Length L Ch R = 1,17916,639,639,639
BEGIN DESCRIPTION:
UNT057 IN NNOGR 35.0
END DESCRIPTION:
XS GIS Cut Line= 3
      2824623.22     10066514.77      2823973.70     10066339.18
      2823283.58     10066453.77
#Sta/Elev= 30
  4530.2 1555.70  4597.3 1554.73  4659.4 1553.06  4680.1 1551.71  4780.9 1547.47
  4794.0 1546.13  4814.8 1544.14  4820.8 1542.93  4835.5 1541.94  4887.3 1540.49
  4938.9 1540.19  4959.8 1541.66  4998.3 1536.83  5001.0 1536.33  5004.3 1536.83
  5020.3 1541.15  5042.7 1543.28  5089.6 1545.52  5094.7 1545.29  5198.0 1551.90
  5307.0 1552.80  5340.1 1553.08  5390.8 1555.37  5431.3 1555.99  5461.8 1557.56
  5567.4 1560.72  5605.0 1560.73  5745.6 1563.48  5864.6 1563.81  5902.6 1564.12
#Mann=10,-1,0
  4530.2     0.1       0  4794.0    0.05       0  4938.9     0.1       0
  4998.3    0.07       0  5004.3     0.1       0  5020.3    0.16       0
  5307.0     0.1       0  5605.0    0.05       0  5745.6     0.1       0
  5864.6    0.05       0
Bank Sta=4998.3,5004.3
Exp/Cntr=0.3,0.1

Type RM Length L Ch R = 1,17277,742,742,742
BEGIN DESCRIPTION:
UNT057 IN NNOGR 34.0
END DESCRIPTION:
XS GIS Cut Line= 3
      2824753.39     10066132.80      2824432.25     10065837.69
      2823462.05     10065727.36
#Sta/Elev= 30
  4457.5 1549.16  4566.5 1548.74  4594.9 1547.75  4615.8 1546.19  4637.4 1542.42
  4665.8 1539.25  4715.1 1536.49  4764.4 1535.47  4905.3 1536.30  4927.6 1535.97
  4947.8 1534.53  4972.9 1534.52  4995.1 1530.25  4997.8 1529.75  5001.1 1530.25
  5038.4 1532.34  5062.5 1538.09  5108.8 1542.71  5139.0 1543.94  5169.2 1543.43
  5179.3 1544.13  5270.5 1542.93  5300.0 1542.88  5364.9 1540.96  5451.0 1540.17
  5552.2 1540.83  5665.8 1541.48  5692.5 1541.68  5783.1 1545.46  5870.1 1546.89
#Mann=8,-1,0
  4457.5     0.1       0  4905.3    0.16       0  4995.1    0.07       0
  5001.1    0.16       0  5270.5     0.1       0  5364.9    0.05       0
  5552.2     0.1       0  5665.8    0.05       0
Bank Sta=4995.1,5001.1
Exp/Cntr=0.3,0.1

Type RM Length L Ch R = 1,16535,1144,1144,1144
BEGIN DESCRIPTION:
UNT057 IN NNOGR 33.0
END DESCRIPTION:
XS GIS Cut Line= 4
      2824861.72     10066235.06      2824856.51     10065755.85
      2824770.57     10065557.93      2823796.62     10065104.81
#Sta/Elev= 30
  4462.4 1549.74  4487.7 1549.42  4641.3 1546.36  4767.8 1544.47  4949.3 1542.41
  4965.7 1538.14  4972.8 1535.03  4978.2 1530.95  4987.6 1526.79  4996.2 1524.38
  4998.7 1524.35  5001.4 1523.85  5004.7 1524.35  5025.2 1529.97  5063.9 1531.53
  5095.5 1530.58  5298.4 1532.09  5440.5 1532.85  5518.0 1534.28  5620.0 1535.28
  5645.0 1534.99  5651.9 1535.97  5663.3 1536.05  5697.7 1535.28  5800.3 1535.08
  6030.0 1538.16  6064.1 1539.26  6130.4 1539.57  6194.8 1541.74  6231.6 1542.00
#Mann=12,-1,0
  4462.4    0.05       0  4487.7     0.1       0  4641.3    0.05       0
  4767.8     0.1       0  4998.7    0.07       0  5004.7     0.1       0
  5298.4    0.16       0  5518.0    0.05       0  5620.0    0.16       0
  5663.3    0.05       0  6030.0    0.16       0  6130.4    0.05       0
Bank Sta=4998.7,5004.7
Exp/Cntr=0.3,0.1

Type RM Length L Ch R = 1,15391,893,893,893
BEGIN DESCRIPTION:
UNT057 IN NNOGR 32.0
END DESCRIPTION:
XS GIS Cut Line= 3
      2825760.37     10065247.41      2825005.16     10064778.66
      2824206.59     10064822.06
#Sta/Elev= 30
  3860.3 1539.93  3886.1 1538.93  3909.2 1539.76  3975.1 1537.44  4358.6 1526.96
  4404.5 1526.36  4489.4 1523.33  4576.5 1522.99  4597.7 1521.41  4764.5 1522.75
  4866.0 1523.48  4932.9 1520.44  4966.2 1522.08  4976.2 1521.83  4996.2 1517.26
  5003.2 1517.01  5006.0 1516.51  5009.2 1517.01  5026.3 1522.13  5046.3 1523.52
  5086.3 1522.36  5146.4 1524.60  5186.5 1523.97  5206.5 1522.04  5285.2 1525.25
  5307.5 1525.13  5358.9 1530.36  5386.8 1534.10  5438.8 1537.68  5548.9 1538.75
#Mann=11,-1,0
  3860.3    0.05       0  3975.1     0.1       0  4358.6    0.05       0
  4404.5     0.1       0  4489.4    0.05       0  4764.5     0.1       0
  5003.2    0.07       0  5009.2     0.1       0  5285.2    0.16       0
  5358.9     0.1       0  5438.8    0.05       0
Bank Sta=5003.2,5009.2
Exp/Cntr=0.3,0.1

Type RM Length L Ch R = 1,14498,788,788,788
BEGIN DESCRIPTION:
UNT057 IN NNOGR 30.0
END DESCRIPTION:
XS GIS Cut Line= 3
      2825695.09     10064875.67      2824965.88     10064388.66
      2824402.13     10064357.48
#Sta/Elev= 30
  4495.8 1532.72  4625.1 1529.80  4791.4 1526.02  4818.4 1525.00  4840.5 1522.72
  4863.5 1522.52  4890.5 1521.15  4899.5 1521.20  4912.6 1522.56  4920.5 1522.44
  4956.6 1518.94  4971.6 1515.13  4977.6 1514.51  4984.8 1511.82  4992.6 1509.88
  4995.6 1509.84  4998.4 1509.34  5001.6 1509.84  5020.8 1516.20  5049.7 1517.90
  5121.8 1520.03  5201.2 1518.45  5244.9 1519.97  5302.0 1523.68  5322.0 1523.85
  5430.2 1525.99  5553.9 1527.37  5921.5 1538.89  5923.4 1538.93  5937.3 1539.45
#Mann=7,-1,0
  4495.8    0.05       0  4625.1     0.1       0  4995.6    0.07       0
  5001.6     0.1       0  5322.0    0.05       0  5921.5     0.1       0
  5923.4    0.05       0
Bank Sta=4995.6,5001.6
Exp/Cntr=0.3,0.1

Type RM Length L Ch R = 1,13710,193,193,193
BEGIN DESCRIPTION:
UNT057 IN NNOGR 29.0
END DESCRIPTION:
XS GIS Cut Line= 4
      2825677.69     10064604.77      2825691.58     10064285.36
      2825337.41     10063774.94      2824542.87     10063695.14
#Sta/Elev= 30
  4209.8 1529.11  4302.4 1527.54  4441.1 1524.86  4533.5 1522.25  4612.3 1517.01
  4648.1 1516.04  4683.8 1515.38  4777.0 1514.93  4821.0 1514.67  4898.6 1512.78
  4957.5 1512.84  4970.2 1511.88  4997.0 1506.19  4999.7 1505.69  5003.0 1506.19
  5006.2 1506.58  5021.4 1511.99  5029.7 1515.57  5035.8 1517.00  5056.7 1518.31
  5183.6 1518.96  5234.5 1518.65  5314.3 1519.05  5380.9 1520.55  5509.8 1524.77
  5554.1 1525.59  5652.8 1529.29  5692.4 1531.00  5803.0 1533.16  5949.3 1537.62
#Mann=10,-1,0
  4209.8     0.1       0  4302.4    0.05       0  4777.0     0.1       0
  4997.0    0.07       0  5003.0     0.1       0  5021.4    0.05       0
  5183.6     0.1       0  5234.5    0.05       0  5554.1     0.1       0
  5652.8    0.05       0
Bank Sta=4997,5003
Exp/Cntr=0.3,0.1

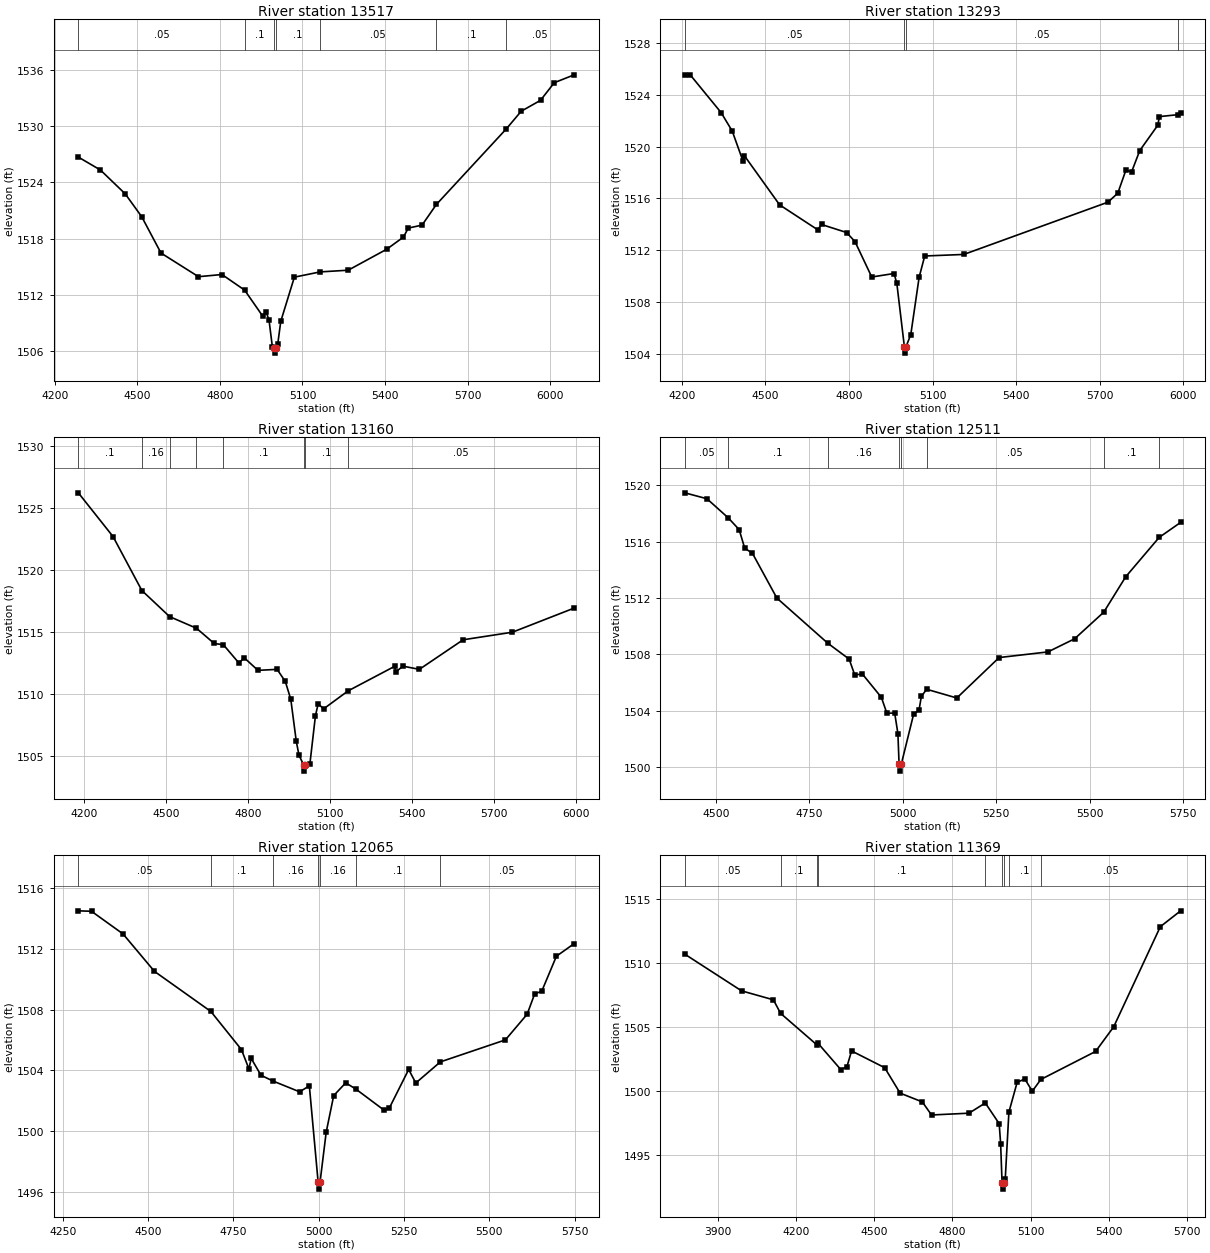
Type RM Length L Ch R = 1,13517,224,224,224
BEGIN DESCRIPTION:
Mapping XS f9f56a63
END DESCRIPTION:
XS GIS Cut Line= 4
      2825697.65     10064464.17      2825700.26     10064123.03
      2825403.38     10063333.97      2824786.24     10063307.93
#Sta/Elev= 30
  4285.4 1526.69  4365.8 1525.31  4455.8 1522.77  4515.8 1520.33  4585.8 1516.46
  4722.0 1513.94  4807.4 1514.17  4889.6 1512.51  4954.9 1509.76  4967.7 1510.18
  4978.4 1509.31  4990.5 1506.47  4996.8 1506.29  4999.5 1505.79  5002.8 1506.29
  5010.0 1506.74  5021.1 1509.18  5070.5 1513.89  5164.2 1514.45  5266.1 1514.63
  5405.8 1516.86  5466.9 1518.16  5484.5 1519.12  5534.6 1519.44  5586.6 1521.64
  5841.1 1529.71  5894.9 1531.58  5965.0 1532.74  6015.0 1534.62  6087.3 1535.46
#Mann=7,-1,0
  4285.4    0.05       0  4889.6     0.1       0  4996.8    0.07       0
  5002.8     0.1       0  5164.2    0.05       0  5586.6     0.1       0
  5841.1    0.05       0
Bank Sta=4996.8,5002.8
Exp/Cntr=0.3,0.1

Type RM Length L Ch R = 1,13293,133,133,133
BEGIN DESCRIPTION:
Mapping XS 624b4ee0
END DESCRIPTION:
XS GIS Cut Line= 3
      2825705.47     10064413.82      2825761.02     10062938.14
      2825577.08     10062698.66
#Sta/Elev= 30
  4211.2 1525.53  4231.3 1525.51  4341.4 1522.62  4381.4 1521.19  4420.1 1518.87
  4425.1 1519.29  4551.5 1515.50  4688.1 1513.58  4701.6 1513.99  4791.7 1513.37
  4821.7 1512.67  4881.8 1509.94  4961.8 1510.21  4971.8 1509.45  4998.9 1504.57
  5001.6 1504.07  5004.9 1504.57  5021.9 1505.50  5051.9 1509.93  5071.9 1511.56
  5212.0 1511.68  5729.1 1515.71  5764.4 1516.40  5793.4 1518.17  5814.3 1518.06
  5843.3 1519.69  5907.6 1521.63  5914.0 1522.31  5981.7 1522.46  5989.9 1522.57
#Mann=4,-1,0
  4211.2    0.05       0  4998.9    0.04       0  5004.9    0.05       0
  5981.7     0.1       0
Bank Sta=4998.9,5004.9
Exp/Cntr=0.3,0.1

Type RM Length L Ch R = 1,13160,649,649,649
BEGIN DESCRIPTION:
UNT057 IN NNOGR 27.0
END DESCRIPTION:
XS GIS Cut Line= 3
      2825818.46     10064360.48      2825851.01     10062850.03
      2825850.70     10062547.74
#Sta/Elev= 30
  4179.6 1526.24  4306.4 1522.71  4411.9 1518.35  4513.4 1516.24  4611.7 1515.30
  4676.5 1514.07  4710.0 1513.97  4766.5 1512.50  4786.5 1512.91  4836.5 1511.90
  4906.5 1511.98  4936.5 1511.00  4956.5 1509.56  4976.5 1506.18  4986.5 1505.04
  5003.5 1504.26  5006.3 1503.76  5009.5 1504.26  5026.5 1504.37  5046.6 1508.23
  5056.6 1509.20  5076.6 1508.79  5165.9 1510.24  5335.9 1512.22  5340.9 1511.78
  5366.6 1512.24  5426.6 1511.98  5586.7 1514.37  5766.7 1514.98  5992.7 1516.93
#Mann=8,-1,0
  4179.6     0.1       0  4411.9    0.16       0  4513.4     0.1       0
  4611.7    0.16       0  4710.0     0.1       0  5003.5    0.07       0
  5009.5     0.1       0  5165.9    0.05       0
Bank Sta=5003.5,5009.5
Exp/Cntr=0.3,0.1

Type RM Length L Ch R = 1,12511,446,446,446
BEGIN DESCRIPTION:
UNT057 IN NNOGR 25.0
END DESCRIPTION:
XS GIS Cut Line= 2
      2826616.74     10063588.44      2825849.68     10062507.19
#Sta/Elev= 30
  4417.1 1519.47  4476.3 1519.05  4533.4 1517.69  4562.4 1516.86  4577.2 1515.55
  4598.1 1515.17  4663.3 1512.00  4799.3 1508.80  4856.5 1507.67  4871.3 1506.56
  4892.2 1506.60  4942.6 1504.96  4957.4 1503.83  4978.3 1503.84  4986.9 1502.38
  4990.0 1500.22  4992.8 1499.72  4996.0 1500.22  5028.7 1503.74  5043.5 1504.08
  5049.6 1505.02  5063.7 1505.53  5144.4 1504.91  5257.5 1507.78  5388.0 1508.18
  5459.3 1509.11  5537.3 1511.00  5595.9 1513.51  5685.6 1516.31  5742.8 1517.37
#Mann=8,-1,0
  4417.1    0.05       0  4533.4     0.1       0  4799.3    0.16       0
  4990.0    0.07       0  4996.0    0.16       0  5063.7    0.05       0
  5537.3     0.1       0  5685.6    0.05       0
Bank Sta=4990,4996
Exp/Cntr=0.3,0.1

Type RM Length L Ch R = 1,12065,696,696,696
BEGIN DESCRIPTION:
UNT057 IN NNOGR 24.0
END DESCRIPTION:
XS GIS Cut Line= 2
      2827140.61     10063285.63      2826029.86     10062348.44
#Sta/Elev= 30
  4295.2 1514.50  4333.8 1514.47  4426.1 1512.98  4518.4 1510.51  4683.7 1507.87
  4773.3 1505.36  4795.2 1504.09  4801.9 1504.78  4830.5 1503.67  4865.7 1503.29
  4943.7 1502.58  4972.3 1502.97  4997.9 1496.67  5000.6 1496.17  5003.9 1496.67
  5021.7 1499.92  5043.7 1502.33  5078.9 1503.17  5108.0 1502.77  5192.0 1501.36
  5206.3 1501.49  5263.5 1504.05  5284.3 1503.16  5356.3 1504.55  5547.0 1506.00
  5610.7 1507.69  5632.6 1509.02  5653.6 1509.21  5696.5 1511.51  5748.5 1512.34
#Mann=7,-1,0
  4295.2    0.05       0  4683.7     0.1       0  4865.7    0.16       0
  4997.9    0.07       0  5003.9    0.16       0  5108.0     0.1       0
  5356.3    0.05       0
Bank Sta=4997.9,5003.9
Exp/Cntr=0.3,0.1

Type RM Length L Ch R = 1,11369,673,673,673
BEGIN DESCRIPTION:
UNT057 IN NNOGR 23.0
END DESCRIPTION:
XS GIS Cut Line= 3
      2827589.28     10062910.77      2827346.24     10062511.49
      2826035.47     10061925.55
#Sta/Elev= 30
  3772.7 1510.72  3990.6 1507.85  4112.7 1507.15  4140.4 1506.09  4278.9 1503.64
  4283.5 1503.76  4372.0 1501.68  4395.2 1501.93  4412.9 1503.15  4539.9 1501.84
  4599.2 1499.85  4684.6 1499.16  4719.7 1498.14  4863.5 1498.28  4926.1 1499.08
  4979.5 1497.46  4985.0 1495.90  4990.5 1492.84  4993.2 1492.34  4996.5 1492.84
  5002.7 1493.12  5016.7 1498.36  5048.3 1500.69  5077.8 1500.96  5106.5 1500.00
  5139.4 1500.92  5349.5 1503.11  5419.1 1505.04  5598.0 1512.87  5675.9 1514.11
#Mann=9,-1,0
  3772.7    0.05       0  4140.4     0.1       0  4278.9    0.05       0
  4283.5     0.1       0  4926.1    0.16       0  4990.5    0.07       0
  4996.5    0.16       0  5016.7     0.1       0  5139.4    0.05       0
Bank Sta=4990.5,4996.5
Exp/Cntr=0.3,0.1

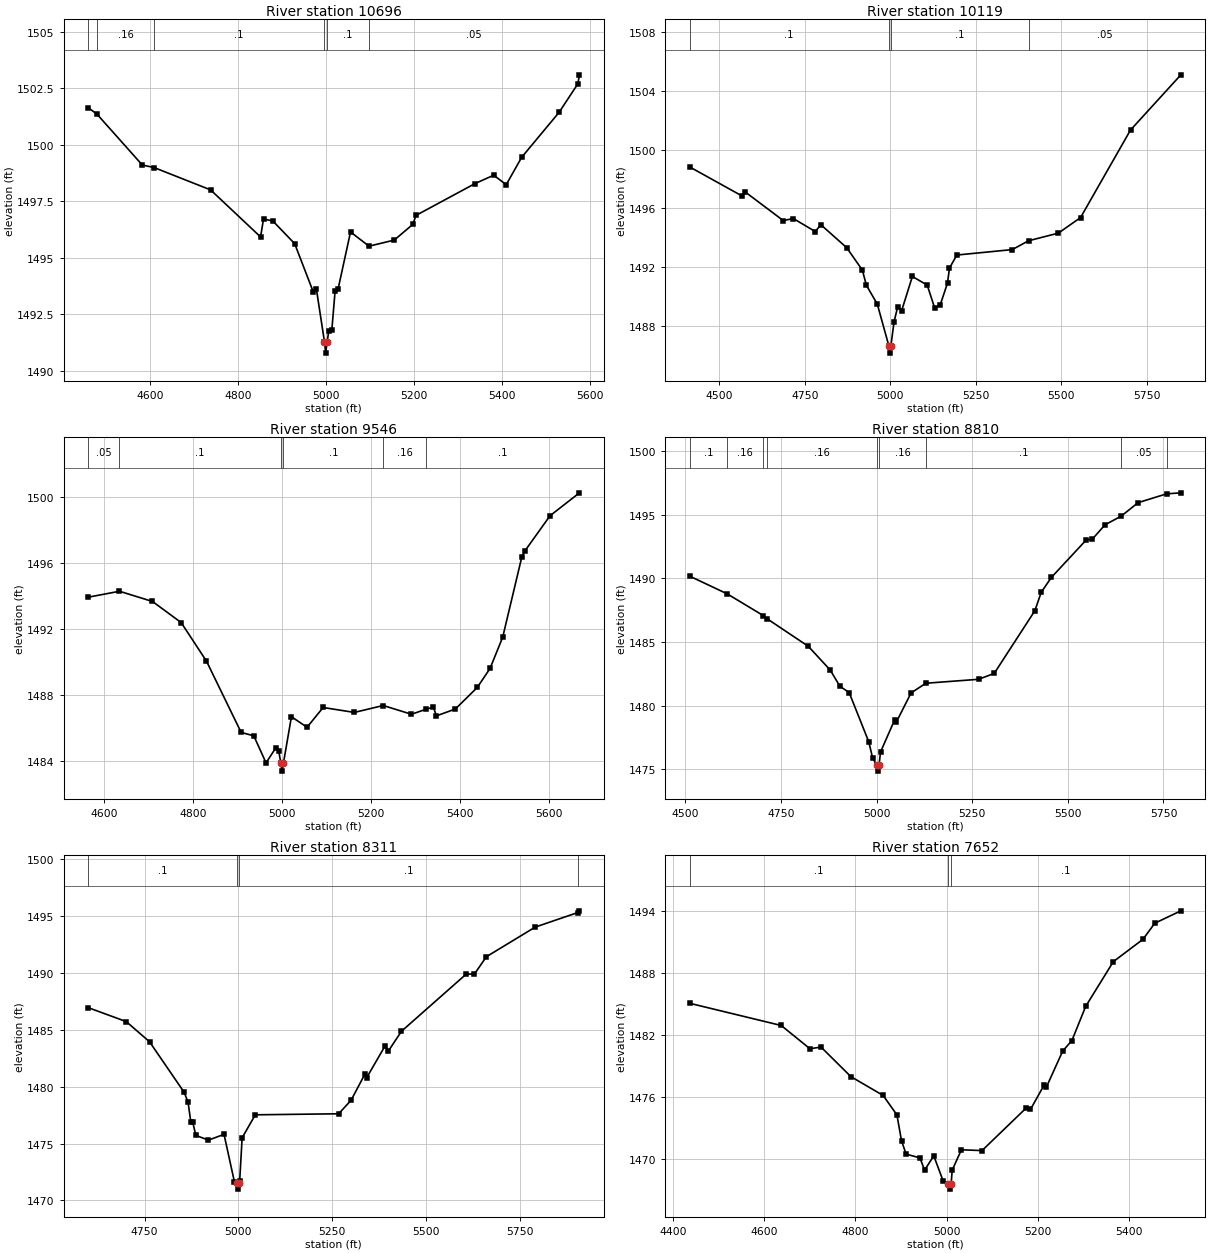
Type RM Length L Ch R = 1,10696,577,577,577
BEGIN DESCRIPTION:
UNT057 IN NNOGR 22.0
END DESCRIPTION:
XS GIS Cut Line= 2
      2827479.12     10062226.57      2826733.00     10061393.70
#Sta/Elev= 30
  4458.3 1501.64  4478.7 1501.34  4581.4 1499.10  4608.0 1498.99  4736.9 1498.00
  4850.6 1495.92  4857.3 1496.71  4878.3 1496.63  4928.3 1495.62  4970.9 1493.47
  4977.7 1493.61  4996.1 1491.28  4998.9 1490.78  5002.1 1491.28  5006.1 1491.78
  5012.8 1491.79  5020.3 1493.54  5027.0 1493.61  5055.4 1496.14  5097.4 1495.51
  5154.9 1495.78  5197.5 1496.48  5204.2 1496.87  5338.8 1498.28  5381.4 1498.65
  5409.8 1498.23  5444.9 1499.44  5530.1 1501.43  5572.8 1502.69  5576.5 1503.09
#Mann=6,-1,0
  4458.3     0.1       0  4478.7    0.16       0  4608.0     0.1       0
  4996.1    0.07       0  5002.1     0.1       0  5097.4    0.05       0
Bank Sta=4996.1,5002.1
Exp/Cntr=0.3,0.1

Type RM Length L Ch R = 1,10119,573,573,573
BEGIN DESCRIPTION:
UNT057 IN NNOGR 21.0
END DESCRIPTION:
XS GIS Cut Line= 3
      2827706.48     10062016.73      2827678.27     10061569.65
      2826816.75     10061085.72
#Sta/Elev= 30
  4413.5 1498.83  4566.8 1496.85  4576.8 1497.11  4687.0 1495.18  4717.1 1495.31
  4780.6 1494.43  4797.3 1494.89  4872.7 1493.33  4918.6 1491.80  4930.2 1490.77
  4962.1 1489.49  4995.9 1486.65  4998.6 1486.15  5001.9 1486.65  5011.2 1488.29
  5021.4 1489.27  5033.3 1489.04  5064.7 1491.37  5108.1 1490.78  5129.8 1489.23
  5145.7 1489.41  5167.4 1490.92  5173.1 1491.94  5194.8 1492.83  5356.8 1493.20
  5404.2 1493.80  5491.3 1494.32  5556.4 1495.38  5702.4 1501.34  5849.6 1505.10
#Mann=4,-1,0
  4413.5     0.1       0  4995.9    0.07       0  5001.9     0.1       0
  5404.2    0.05       0
Bank Sta=4995.9,5001.9
Exp/Cntr=0.3,0.1

Type RM Length L Ch R = 1,9546,736,736,736
BEGIN DESCRIPTION:
UNT057 IN NNOGR 20.0
END DESCRIPTION:
XS GIS Cut Line= 3
      2828079.74     10061417.73      2828062.38     10061209.41
      2827383.27     10060625.76
#Sta/Elev= 30
  4564.1 1493.95  4634.4 1494.31  4708.6 1493.69  4773.1 1492.41  4830.0 1490.07
  4907.9 1485.75  4936.4 1485.54  4963.9 1483.90  4985.8 1484.81  4992.4 1484.63
  4997.1 1483.90  4999.8 1483.40  5003.1 1483.90  5021.0 1486.70  5056.1 1486.06
  5092.3 1487.26  5162.5 1486.96  5227.3 1487.38  5290.9 1486.85  5324.4 1487.16
  5340.3 1487.28  5346.9 1486.75  5389.7 1487.17  5439.0 1488.48  5467.6 1489.63
  5496.1 1491.53  5538.9 1496.38  5545.5 1496.74  5602.5 1498.89  5668.6 1500.28
#Mann=6,-1,0
  4564.1    0.05       0  4634.4     0.1       0  4997.1    0.07       0
  5003.1     0.1       0  5227.3    0.16       0  5324.4     0.1       0
Bank Sta=4997.1,5003.1
Exp/Cntr=0.3,0.1

Type RM Length L Ch R = 1,8810,499,499,499
BEGIN DESCRIPTION:
UNT057 IN NNOGR 18.0
END DESCRIPTION:
XS GIS Cut Line= 3
      2828468.20     10060890.39      2828370.54     10060497.60
      2827512.30     10060304.71
#Sta/Elev= 30
  4511.0 1490.17  4609.1 1488.78  4703.7 1487.07  4712.7 1486.84  4821.3 1484.66
  4878.5 1482.80  4904.0 1481.52  4928.1 1481.03  4979.4 1477.16  4989.6 1475.87
  5000.4 1475.36  5003.1 1474.86  5006.4 1475.36  5010.1 1476.36  5046.7 1478.86
  5051.8 1478.73  5090.0 1481.00  5128.6 1481.76  5266.4 1482.07  5307.4 1482.53
  5413.6 1487.45  5430.3 1488.90  5456.9 1490.07  5548.6 1493.03  5563.6 1493.06
  5597.1 1494.20  5639.4 1494.88  5683.7 1495.94  5758.1 1496.63  5795.4 1496.71
#Mann=9,-1,0
  4511.0     0.1       0  4609.1    0.16       0  4703.7     0.1       0
  4712.7    0.16       0  5000.4    0.07       0  5006.4    0.16       0
  5128.6     0.1       0  5639.4    0.05       0  5758.1     0.1       0
Bank Sta=5000.4,5006.4
Exp/Cntr=0.3,0.1

Type RM Length L Ch R = 1,8311,659,659,659
BEGIN DESCRIPTION:
UNT057 IN NNOGR 17.0
END DESCRIPTION:
XS GIS Cut Line= 3
      2828787.18     10060093.95      2828029.83     10059909.49
      2827539.42     10060111.30
#Sta/Elev= 30
  4599.7 1486.96  4701.2 1485.73  4763.1 1483.96  4855.7 1479.50  4866.0 1478.62
  4873.2 1476.91  4878.4 1476.88  4886.6 1475.72  4920.1 1475.30  4961.8 1475.81
  4989.5 1471.63  4995.4 1471.49  4998.1 1470.99  5001.4 1471.49  5003.5 1471.71
  5010.1 1475.51  5045.2 1477.53  5267.4 1477.62  5300.6 1478.81  5337.2 1481.10
  5342.4 1480.81  5391.5 1483.61  5400.2 1483.15  5434.9 1484.88  5607.8 1489.92
  5629.4 1489.91  5661.3 1491.44  5791.6 1494.05  5905.3 1495.33  5909.5 1495.48
#Mann=4,-1,0
  4599.7     0.1       0  4995.4    0.07       0  5001.4     0.1       0
  5905.3    0.05       0
Bank Sta=4995.4,5001.4
Exp/Cntr=0.3,0.1

Type RM Length L Ch R = 1,7652,415,415,415
BEGIN DESCRIPTION:
UNT057 IN NNOGR 16.0
END DESCRIPTION:
XS GIS Cut Line= 3
      2828787.19     10059698.94      2828683.04     10059451.59
      2827881.80     10059336.82
#Sta/Elev= 30
  4436.1 1485.11  4637.1 1482.96  4700.1 1480.71  4724.5 1480.87  4789.9 1478.01
  4860.6 1476.19  4890.9 1474.31  4901.0 1471.80  4911.1 1470.51  4941.5 1470.14
  4951.6 1468.96  4971.8 1470.34  4992.0 1467.95  5003.9 1467.62  5006.7 1467.12
  5009.9 1467.62  5012.2 1468.96  5032.4 1470.93  5077.6 1470.85  5173.8 1474.94
  5183.9 1474.83  5213.7 1477.18  5218.8 1476.99  5254.6 1480.48  5274.8 1481.50
  5305.1 1484.81  5365.7 1489.14  5430.7 1491.30  5456.7 1492.86  5513.9 1494.06
#Mann=3,-1,0
  4436.1     0.1       0  5003.9    0.07       0  5009.9     0.1       0
Bank Sta=5003.9,5009.9
Exp/Cntr=0.3,0.1