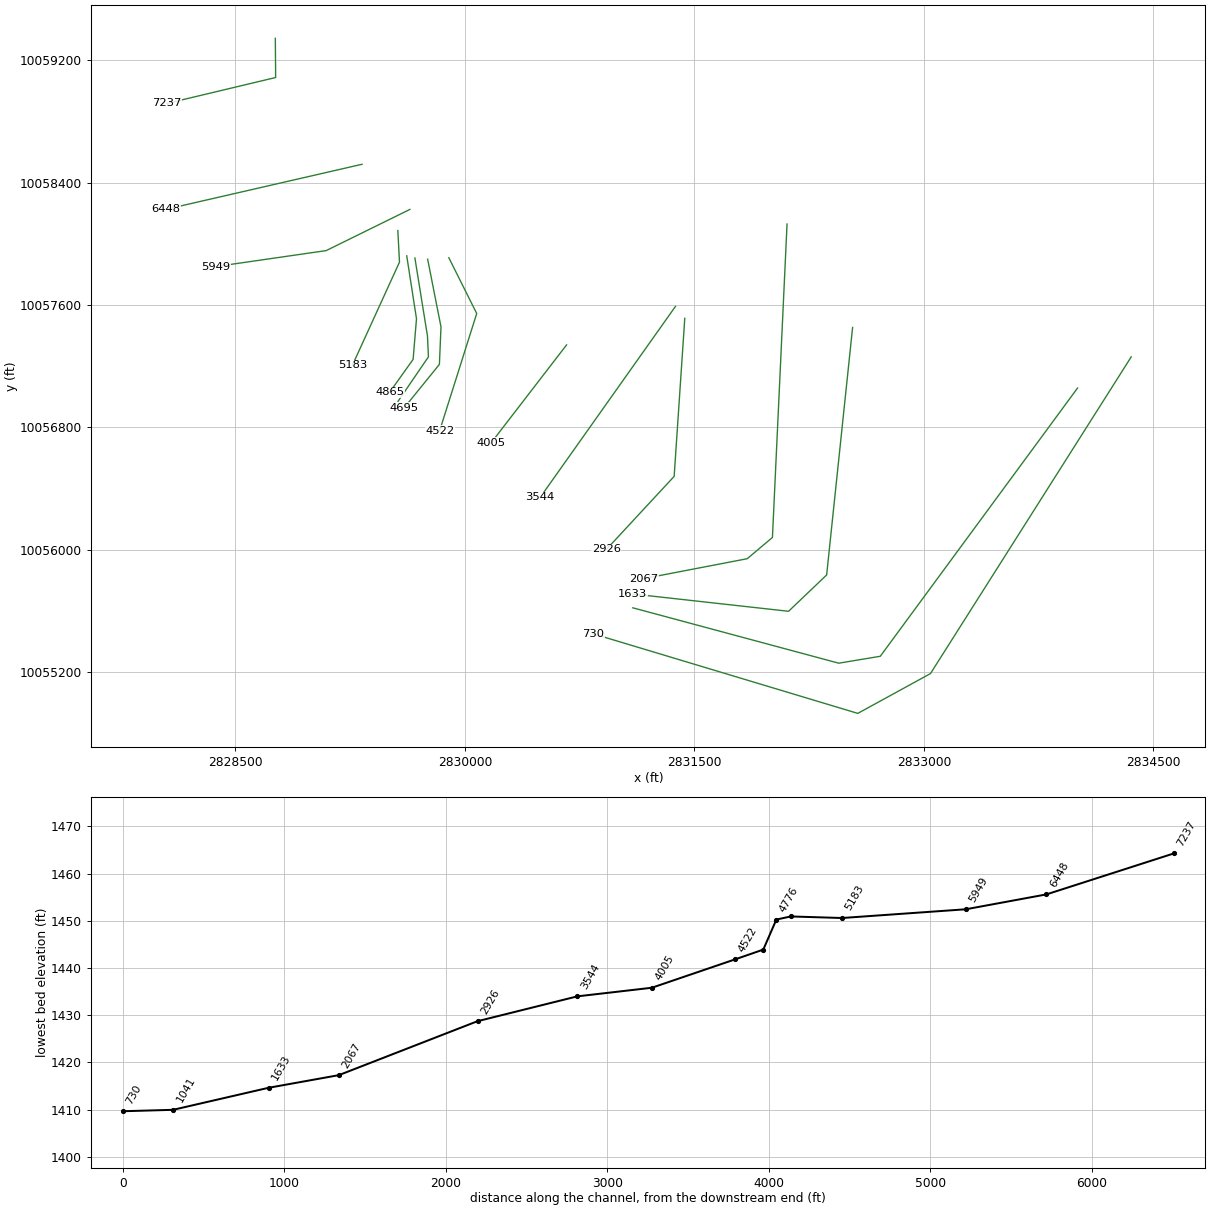
HEC-RAS study UNT057 IN NNOGR.prj: UNT057 IN NNOGR Base Level Engineering

--- UNT057 IN NNOGR.g01 (geometry) --- (continued)

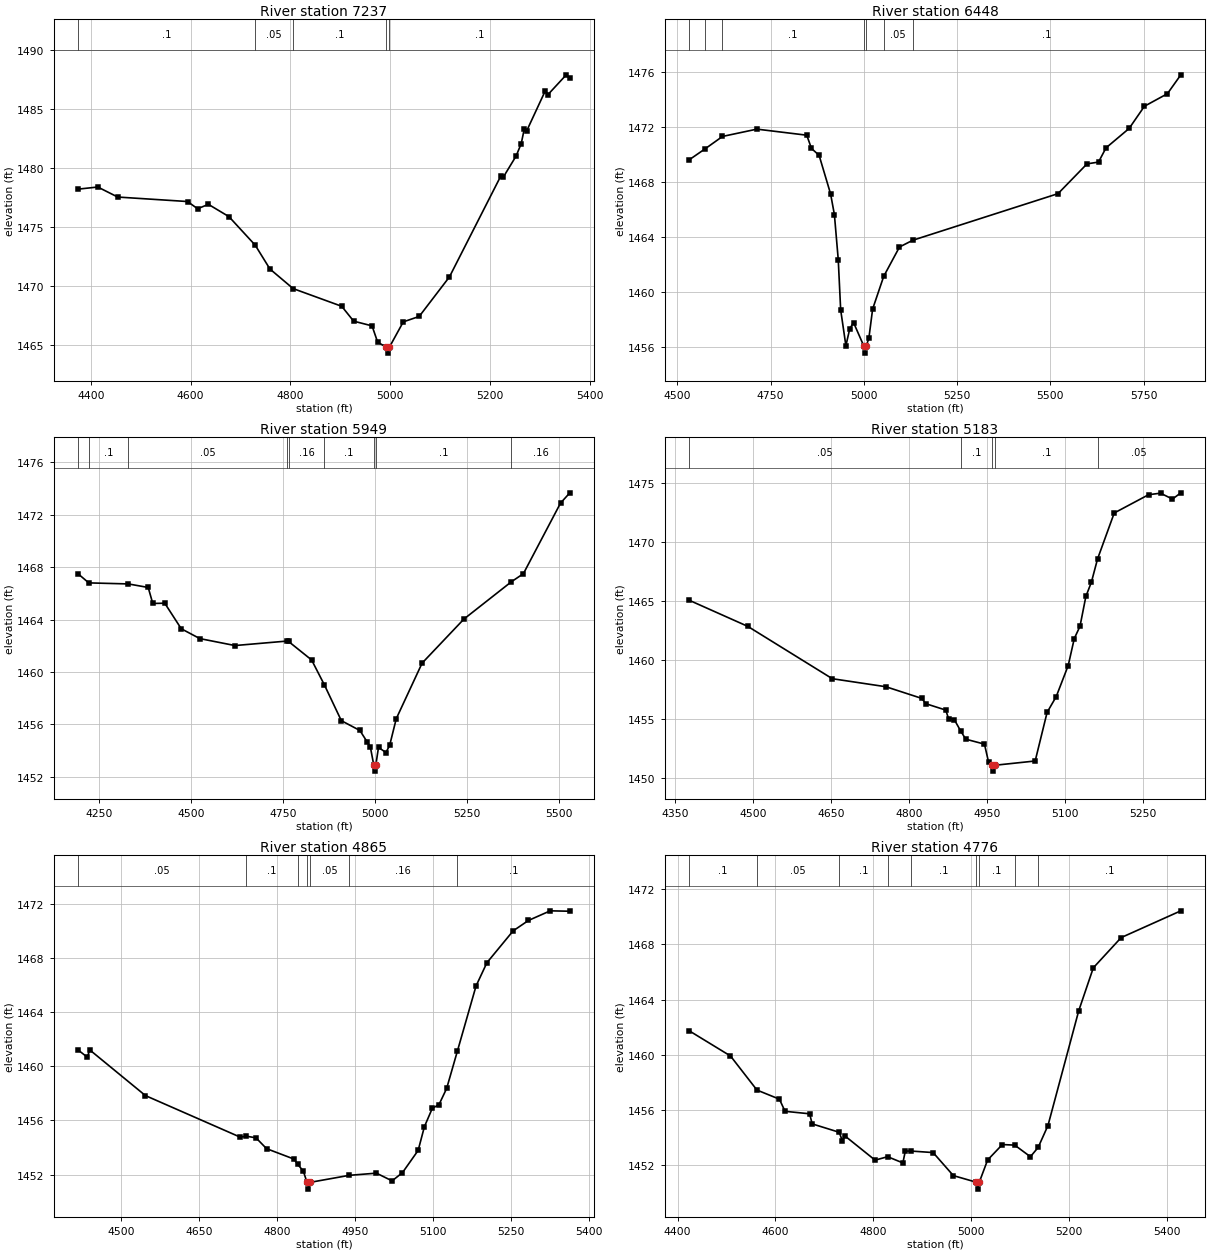
Type RM Length L Ch R = 1,7237,789,789,789
BEGIN DESCRIPTION:
UNT057 IN NNOGR 15.0
END DESCRIPTION:
XS GIS Cut Line= 3
      2828761.17     10059343.12      2828763.34     10059087.01
      2828053.67     10058917.73
#Sta/Elev= 30
  4374.5 1478.17  4413.9 1478.35  4453.9 1477.50  4593.9 1477.12  4613.9 1476.51
  4635.7 1476.88  4676.8 1475.84  4729.5 1473.42  4759.0 1471.40  4805.5 1469.74
  4902.9 1468.24  4926.8 1466.98  4963.7 1466.58  4974.9 1465.20  4992.4 1464.77
  4995.2 1464.27  4998.4 1464.77  5026.3 1466.92  5058.2 1467.38  5118.8 1470.73
  5221.5 1479.26  5226.7 1479.18  5252.5 1480.98  5262.7 1482.03  5268.8 1483.26
  5273.9 1483.13  5310.9 1486.50  5316.0 1486.17  5353.0 1487.86  5360.2 1487.57
#Mann=5,-1,0
  4374.5     0.1       0  4729.5    0.05       0  4805.5     0.1       0
  4992.4    0.07       0  4998.4     0.1       0
Bank Sta=4992.4,4998.4
Exp/Cntr=0.3,0.1

Type RM Length L Ch R = 1,6448,499,499,499
BEGIN DESCRIPTION:
UNT057 IN NNOGR 14.0
END DESCRIPTION:
XS GIS Cut Line= 2
      2829328.12     10058519.99      2828043.38     10058224.85
#Sta/Elev= 30
  4531.6 1469.61  4575.5 1470.43  4621.1 1471.31  4713.3 1471.84  4847.0 1471.40
  4859.6 1470.44  4880.1 1469.94  4910.9 1467.14  4921.1 1465.64  4931.4 1462.38
  4937.9 1458.73  4951.9 1456.13  4962.2 1457.35  4972.4 1457.81  5000.2 1456.09
  5003.0 1455.59  5006.2 1456.09  5013.5 1456.67  5023.6 1458.79  5053.3 1461.16
  5095.6 1463.29  5131.3 1463.78  5520.6 1467.16  5598.3 1469.32  5629.1 1469.45
  5649.2 1470.48  5711.2 1471.89  5752.2 1473.50  5813.8 1474.41  5849.8 1475.78
#Mann=7,-1,0
  4531.6     0.1       0  4575.5    0.16       0  4621.1     0.1       0
  5000.2    0.07       0  5006.2     0.1       0  5053.3    0.05       0
  5131.3     0.1       0
Bank Sta=5000.2,5006.2
Exp/Cntr=0.3,0.1

Type RM Length L Ch R = 1,5949,766,766,766
BEGIN DESCRIPTION:
UNT057 IN NNOGR 13.0
END DESCRIPTION:
XS GIS Cut Line= 3
      2829640.57     10058224.84      2829093.71     10057955.74
      2828373.38     10057851.60
#Sta/Elev= 30
  4193.4 1467.49  4222.4 1466.80  4330.1 1466.72  4384.0 1466.45  4396.4 1465.23
  4429.0 1465.25  4473.9 1463.30  4524.4 1462.55  4619.9 1462.02  4760.8 1462.36
  4765.7 1462.33  4828.4 1460.92  4863.3 1459.01  4909.2 1456.29  4959.7 1455.54
  4979.9 1454.65  4988.3 1454.26  4997.2 1452.94  4999.9 1452.44  5003.2 1452.94
  5010.3 1454.25  5030.5 1453.86  5040.6 1454.40  5058.6 1456.44  5128.9 1460.68
  5242.6 1464.04  5371.9 1466.89  5404.3 1467.50  5505.4 1472.89  5530.7 1473.67
#Mann=9,-1,0
  4193.4    0.05       0  4222.4     0.1       0  4330.1    0.05       0
  4760.8     0.1       0  4765.7    0.16       0  4863.3     0.1       0
  4997.2    0.07       0  5003.2     0.1       0  5371.9    0.16       0
Bank Sta=4997.2,5003.2
Exp/Cntr=0.3,0.1

Type RM Length L Ch R = 1,5183,318,318,318
BEGIN DESCRIPTION:
UNT057 IN NNOGR 11.0
END DESCRIPTION:
XS GIS Cut Line= 3
      2829561.95     10058086.61      2829572.80     10057880.41
      2829265.39     10057207.15
#Sta/Elev= 30
  4376.6 1465.09  4489.6 1462.87  4652.3 1458.43  4755.4 1457.75  4824.5 1456.76
  4832.3 1456.31  4870.6 1455.77  4876.2 1455.03  4887.2 1454.95  4899.9 1453.96
  4909.2 1453.30  4945.2 1452.88  4953.2 1451.33  4959.7 1451.09  4962.4 1450.59
  4965.7 1451.09  5042.8 1451.45  5065.8 1455.58  5083.3 1456.91  5106.4 1459.55
  5118.1 1461.84  5129.1 1462.88  5140.4 1465.41  5151.1 1466.63  5162.8 1468.58
  5195.0 1472.49  5261.1 1474.04  5284.1 1474.17  5307.1 1473.67  5323.2 1474.20
#Mann=5,-1,0
  4376.6    0.05       0  4899.9     0.1       0  4959.7    0.07       0
  4965.7     0.1       0  5162.8    0.05       0
Bank Sta=4959.7,4965.7
Exp/Cntr=0.3,0.1

Type RM Length L Ch R = 1,4865,89,89,89
BEGIN DESCRIPTION:
Mapping XS c6c05273
END DESCRIPTION:
XS GIS Cut Line= 4
      2829620.11     10057921.63      2829683.91     10057510.19
      2829661.77     10057244.56      2829509.44     10057031.03
#Sta/Elev= 30
  4417.9 1461.20  4435.4 1460.67  4440.4 1461.20  4547.3 1457.83  4729.5 1454.76
  4741.3 1454.83  4759.8 1454.71  4780.1 1453.91  4832.8 1453.14  4840.2 1452.74
  4850.8 1452.25  4857.8 1451.42  4860.6 1450.92  4863.8 1451.42  4939.2 1451.94
  4991.3 1452.10  5021.4 1451.53  5041.4 1452.14  5071.5 1453.78  5083.5 1455.53
  5098.7 1456.89  5111.5 1457.16  5126.3 1458.36  5146.8 1461.10  5182.8 1465.93
  5203.7 1467.65  5254.1 1470.00  5283.6 1470.77  5325.4 1471.48  5363.1 1471.45
#Mann=7,-1,0
  4417.9    0.05       0  4741.3     0.1       0  4840.2    0.05       0
  4857.8    0.07       0  4863.8    0.05       0  4939.2    0.16       0
  5146.8     0.1       0
Bank Sta=4857.8,4863.8
Exp/Cntr=0.3,0.1

Type RM Length L Ch R = 1,4776,81,81,81
BEGIN DESCRIPTION:
Mapping XS 733566da
END DESCRIPTION:
XS GIS Cut Line= 4
      2829673.50     10057907.29      2829755.52     10057398.21
      2829762.04     10057261.49      2829563.12     10056970.26
#Sta/Elev= 30
  4423.7 1461.74  4508.3 1459.91  4562.4 1457.44  4608.3 1456.78  4619.8 1455.90
  4670.1 1455.72  4675.2 1454.99  4730.6 1454.38  4737.0 1453.75  4742.1 1454.12
  4803.9 1452.36  4829.5 1452.61  4860.7 1452.16  4865.7 1453.02  4877.3 1453.02
  4922.5 1452.91  4963.9 1451.24  5010.9 1450.76  5013.7 1450.26  5016.9 1450.76
  5033.9 1452.37  5064.0 1453.49  5089.3 1453.45  5121.4 1452.61  5137.2 1453.28
  5157.3 1454.87  5220.2 1463.19  5250.0 1466.30  5306.9 1468.49  5428.9 1470.43
#Mann=9,-1,0
  4423.7     0.1       0  4562.4    0.05       0  4730.6     0.1       0
  4829.5    0.05       0  4877.3     0.1       0  5010.9    0.07       0
  5016.9     0.1       0  5089.3    0.16       0  5137.2     0.1       0
Bank Sta=5010.9,5016.9
Exp/Cntr=0.3,0.1

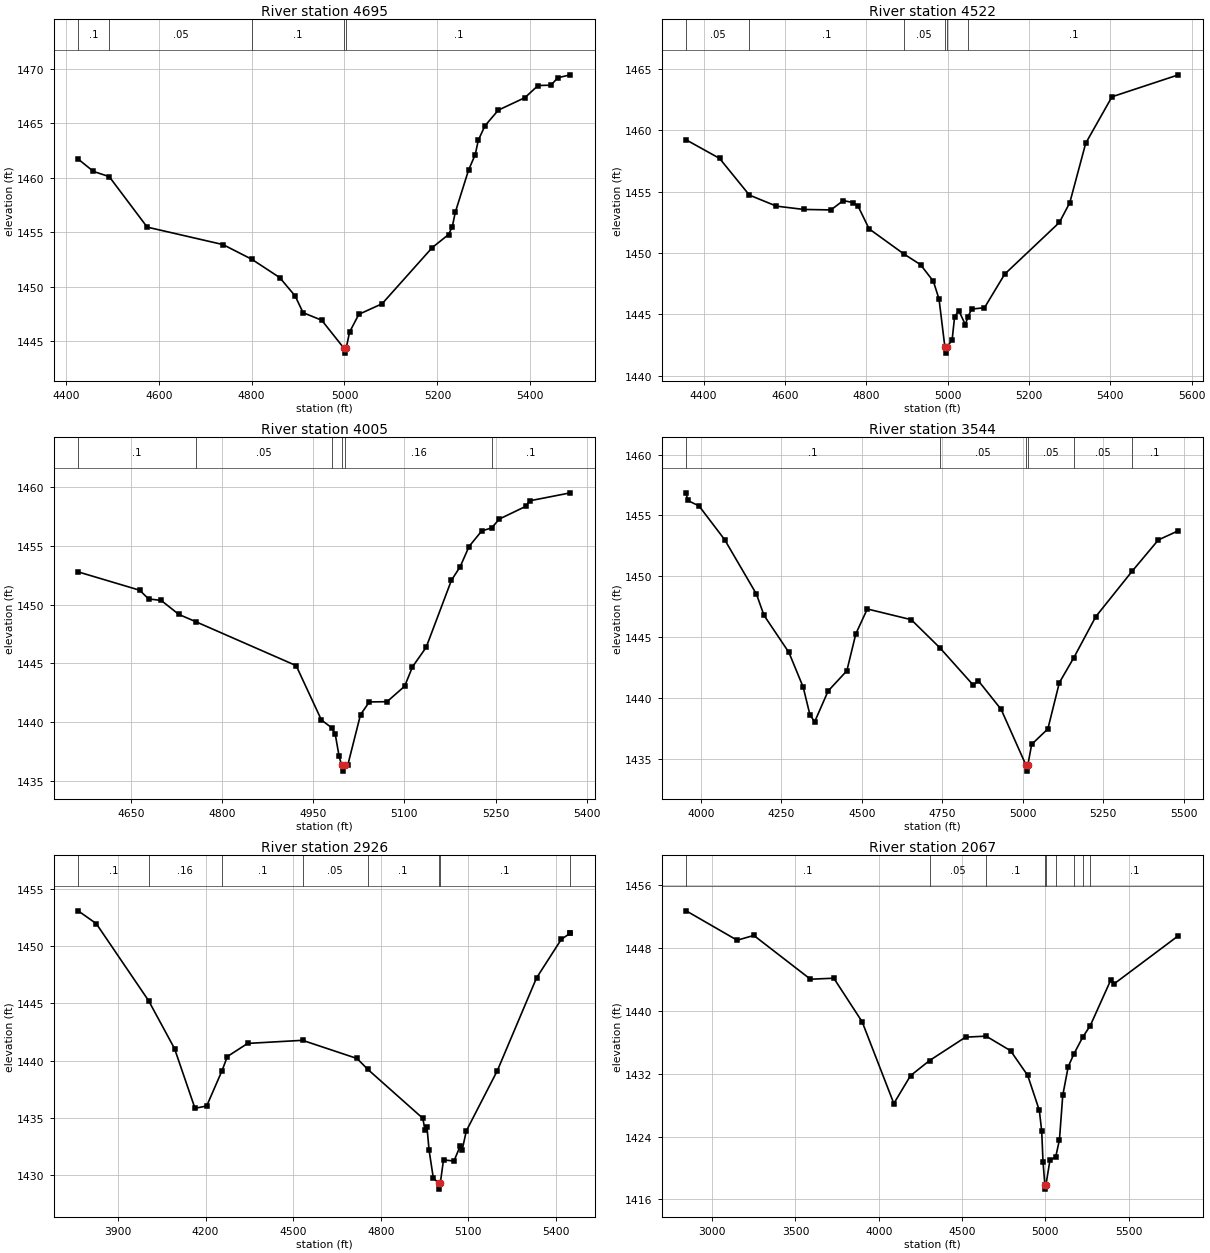
Type RM Length L Ch R = 1,4695,173,173,173
BEGIN DESCRIPTION:
Mapping XS 124ba4d7
END DESCRIPTION:
XS GIS Cut Line= 4
      2829756.83     10057899.51      2829844.07     10057456.80
      2829833.65     10057212.01      2829604.51     10056929.49
#Sta/Elev= 30
  4426.5 1461.70  4459.4 1460.57  4493.4 1460.09  4575.1 1455.46  4738.2 1453.86
  4800.4 1452.51  4860.5 1450.83  4893.8 1449.14  4910.8 1447.61  4950.9 1446.92
  4997.9 1444.40  5000.7 1443.90  5003.9 1444.40  5010.9 1445.83  5030.9 1447.46
  5081.0 1448.43  5188.9 1453.58  5224.1 1454.78  5232.1 1455.49  5238.5 1456.81
  5267.2 1460.70  5281.6 1462.12  5288.1 1463.43  5302.4 1464.75  5331.2 1466.19
  5388.7 1467.34  5416.7 1468.45  5444.7 1468.48  5459.1 1469.16  5486.5 1469.43
#Mann=5,-1,0
  4426.5     0.1       0  4493.4    0.05       0  4800.4     0.1       0
  4997.9    0.07       0  5003.9     0.1       0
Bank Sta=4997.9,5003.9
Exp/Cntr=0.3,0.1

Type RM Length L Ch R = 1,4522,517,517,517
BEGIN DESCRIPTION:
UNT057 IN NNOGR 10.0
END DESCRIPTION:
XS GIS Cut Line= 3
      2829895.26     10057909.14      2830077.55     10057544.55
      2829835.38     10056778.96
#Sta/Elev= 30
  4357.0 1459.23  4439.1 1457.72  4512.4 1454.73  4578.8 1453.83  4645.9 1453.56
  4713.0 1453.52  4743.2 1454.28  4767.7 1454.12  4779.7 1453.83  4806.8 1451.98
  4892.0 1449.94  4933.3 1449.06  4964.8 1447.71  4978.8 1446.26  4993.2 1442.35
  4996.0 1441.85  4999.2 1442.35  5011.1 1442.95  5017.2 1444.83  5027.7 1445.30
  5043.4 1444.18  5050.3 1444.83  5059.2 1445.44  5090.6 1445.55  5140.4 1448.29
  5274.8 1452.50  5300.4 1454.11  5339.5 1458.95  5404.1 1462.74  5567.6 1464.53
#Mann=6,-1,0
  4357.0    0.05       0  4512.4     0.1       0  4892.0    0.05       0
  4993.2   0.035       0  4999.2    0.05       0  5050.3     0.1       0
Bank Sta=4993.2,4999.2
Exp/Cntr=0.3,0.1

Type RM Length L Ch R = 1,4005,461,461,461
BEGIN DESCRIPTION:
UNT057 IN NNOGR 8.0
END DESCRIPTION:
XS GIS Cut Line= 2
      2830664.88     10057339.42      2830170.72     10056697.88
#Sta/Elev= 30
  4563.4 1452.78  4664.6 1451.22  4679.2 1450.48  4700.0 1450.35  4729.0 1449.16
  4756.9 1448.54  4922.0 1444.80  4963.6 1440.17  4980.8 1439.50  4986.3 1438.96
  4992.6 1437.11  4996.8 1436.32  4999.5 1435.82  5002.8 1436.32  5007.1 1436.37
  5027.9 1440.63  5042.4 1441.71  5071.5 1441.73  5100.5 1443.05  5113.4 1444.70
  5135.8 1446.35  5177.4 1452.06  5191.9 1453.23  5206.4 1454.94  5227.2 1456.26
  5243.7 1456.53  5256.3 1457.28  5299.8 1458.36  5306.1 1458.83  5373.2 1459.51
#Mann=6,-1,0
  4563.4     0.1       0  4756.9    0.05       0  4980.8    0.16       0
  4996.8    0.07       0  5002.8    0.16       0  5243.7     0.1       0
Bank Sta=4996.8,5002.8
Exp/Cntr=0.3,0.1

Type RM Length L Ch R = 1,3544,618,618,618
BEGIN DESCRIPTION:
UNT057 IN NNOGR 7.0
END DESCRIPTION:
XS GIS Cut Line= 2
      2831376.69     10057591.16      2830492.38     10056342.72
#Sta/Elev= 30
  3954.3 1456.86  3958.6 1456.24  3994.3 1455.78  4073.7 1453.02  4172.7 1448.54
  4196.1 1446.80  4273.6 1443.75  4317.9 1440.90  4338.8 1438.64  4353.6 1438.05
  4395.4 1440.58  4453.6 1442.24  4481.6 1445.28  4517.2 1447.32  4653.8 1446.44
  4742.4 1444.14  4847.0 1441.05  4861.8 1441.44  4933.2 1439.07  5010.2 1434.50
  5012.9 1434.00  5016.2 1434.50  5028.0 1436.20  5078.4 1437.47  5114.1 1441.27
  5159.3 1443.33  5227.3 1446.69  5339.6 1450.40  5421.7 1452.99  5484.2 1453.75
#Mann=6,-1,0
  3954.3     0.1       0  4742.4    0.05       0  5010.2    0.04       0
  5016.2    0.05       0  5159.3    0.05       0  5339.6     0.1       0
Bank Sta=5010.2,5016.2
Exp/Cntr=0.3,0.1

Type RM Length L Ch R = 1,2926,859,859,859
BEGIN DESCRIPTION:
UNT057 IN NNOGR 6.0
END DESCRIPTION:
XS GIS Cut Line= 3
      2831437.46     10057513.06      2831368.01     10056480.05
      2830925.33     10056002.65
#Sta/Elev= 30
  3763.5 1453.11  3825.5 1451.99  4004.6 1445.25  4093.6 1441.05  4163.7 1435.82
  4203.8 1436.02  4256.5 1439.12  4274.6 1440.35  4344.1 1441.50  4532.2 1441.77
  4718.8 1440.18  4756.0 1439.22  4944.3 1434.94  4951.6 1433.90  4958.4 1434.17
  4965.8 1432.13  4980.0 1429.74  4998.0 1429.24  5000.7 1428.74  5004.0 1429.24
  5015.1 1431.30  5050.8 1431.20  5071.8 1432.48  5079.2 1432.19  5093.3 1433.84
  5199.4 1439.11  5333.7 1447.23  5418.8 1450.62  5448.8 1451.14  5449.9 1451.14
#Mann=8,-1,0
  3763.5     0.1       0  4004.6    0.16       0  4256.5     0.1       0
  4532.2    0.05       0  4756.0     0.1       0  4998.0    0.07       0
  5004.0     0.1       0  5448.8    0.05       0
Bank Sta=4998,5004
Exp/Cntr=0.3,0.1

Type RM Length L Ch R = 1,2067,434,434,434
BEGIN DESCRIPTION:
UNT057 IN NNOGR 4.0
END DESCRIPTION:
XS GIS Cut Line= 4
      2832105.86     10058129.37      2832010.37     10056080.74
      2831845.44     10055941.86      2831168.32     10055811.64
#Sta/Elev= 30
  2843.7 1452.71  3149.7 1448.97  3249.8 1449.58  3590.1 1444.01  3730.3 1444.14
  3900.5 1438.59  4090.7 1428.20  4190.8 1431.74  4305.5 1433.67  4521.2 1436.64
  4644.8 1436.77  4791.4 1434.92  4894.5 1431.77  4964.4 1427.32  4978.7 1424.67
  4986.4 1420.80  4997.7 1417.81  5000.5 1417.31  5003.7 1417.81  5028.1 1420.98
  5062.6 1421.40  5085.3 1423.61  5104.9 1429.23  5137.6 1432.87  5171.7 1434.50
  5224.7 1436.63  5270.5 1438.12  5394.4 1443.96  5412.6 1443.41  5799.7 1449.55
#Mann=9,-1,0
  2843.7     0.1       0  4305.5    0.05       0  4644.8     0.1       0
  4997.7    0.07       0  5003.7     0.1       0  5062.6    0.05       0
  5171.7     0.1       0  5224.7    0.05       0  5270.5     0.1       0
Bank Sta=4997.7,5003.7
Exp/Cntr=0.3,0.1

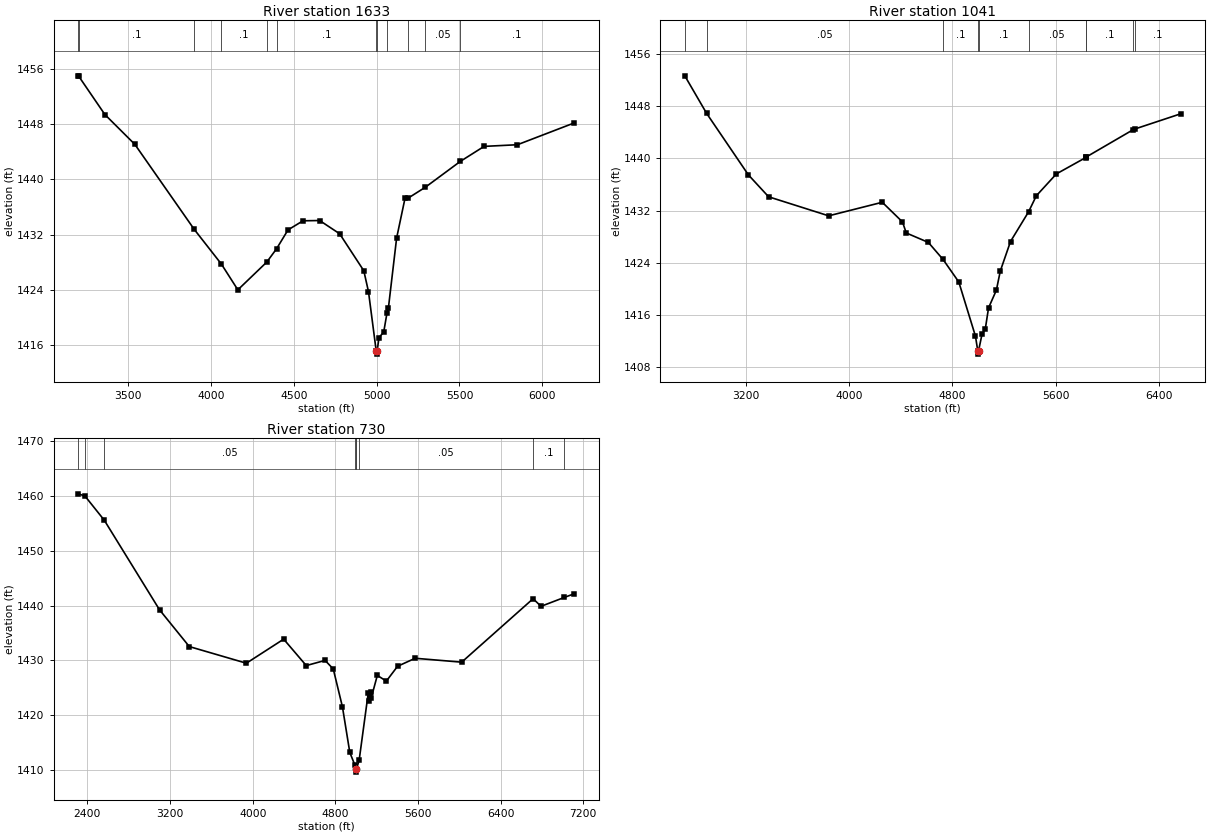
Type RM Length L Ch R = 1,1633,592,592,592
BEGIN DESCRIPTION:
UNT057 IN NNOGR 3.0
END DESCRIPTION:
XS GIS Cut Line= 4
      2832534.36     10057453.26      2832364.69     10055835.83
      2832115.86     10055598.31      2831097.93     10055711.41
#Sta/Elev= 30
  3198.2 1455.03  3201.4 1454.94  3358.6 1449.41  3539.6 1445.08  3898.3 1432.74
  4061.9 1427.72  4161.6 1423.97  4336.3 1428.00  4395.4 1429.93  4464.6 1432.67
  4555.1 1433.99  4655.7 1434.03  4776.3 1432.11  4922.3 1426.74  4950.6 1423.70
  4997.0 1415.14  4999.8 1414.64  5003.0 1415.14  5014.2 1417.05  5042.5 1417.84
  5062.5 1420.64  5070.8 1421.32  5120.5 1431.49  5171.6 1437.31  5189.3 1437.27
  5294.6 1438.87  5505.1 1442.61  5648.8 1444.79  5850.1 1445.03  6192.7 1448.19
#Mann=12,-1,0
  3198.2    0.16       0  3201.4     0.1       0  3898.3    0.05       0
  4061.9     0.1       0  4336.3    0.05       0  4395.4     0.1       0
  4997.0    0.07       0  5003.0     0.1       0  5062.5    0.05       0
  5189.3     0.1       0  5294.6    0.05       0  5505.1     0.1       0
Bank Sta=4997,5003
Exp/Cntr=0.3,0.1

Type RM Length L Ch R = 1,1041,311,311,311
BEGIN DESCRIPTION:
UNT057 IN NNOGR 2.0
END DESCRIPTION:
XS GIS Cut Line= 4
      2834004.72     10057057.37      2832715.32     10055304.23
      2832443.87     10055258.99      2831097.92     10055620.93
#Sta/Elev= 30
  2724.8 1452.67  2894.3 1446.90  3218.0 1437.47  3374.8 1434.11  3840.6 1431.19
  4256.2 1433.27  4413.0 1430.25  4442.3 1428.56  4613.6 1427.11  4727.4 1424.50
  4849.7 1421.04  4979.0 1412.72  4996.8 1410.47  4999.6 1409.97  5002.8 1410.47
  5029.6 1413.01  5055.6 1413.88  5080.3 1417.06  5141.2 1419.79  5171.4 1422.71
  5250.7 1427.25  5390.7 1431.80  5451.1 1434.27  5606.4 1437.62  5833.5 1440.12
  5836.7 1440.20  5838.5 1440.22  6203.2 1444.42  6216.3 1444.52  6570.0 1446.84
#Mann=11,-1,0
  2724.8     0.1       0  2894.3    0.05       0  4727.4     0.1       0
  4996.8    0.07       0  5002.8     0.1       0  5390.7    0.05       0
  5833.5     0.1       0  5836.7    0.05       0  5838.5     0.1       0
  6203.2    0.05       0  6216.3     0.1       0
Bank Sta=4996.8,5002.8
Exp/Cntr=0.3,0.1

Type RM Length L Ch R = 1,730,0,0,0
BEGIN DESCRIPTION:
UNT057 IN NNOGR 1.0
END DESCRIPTION:
XS GIS Cut Line= 4
      2834355.37     10057260.99      2833043.33     10055191.13
      2832568.29     10054930.99      2830837.78     10055451.27
#Sta/Elev= 30
  2312.2 1460.34  2376.7 1459.93  2563.5 1455.53  3098.3 1439.22  3386.4 1432.53
  3938.8 1429.50  4299.8 1433.88  4518.4 1429.07  4700.6 1430.01  4779.8 1428.45
  4868.6 1421.55  4939.8 1413.26  4988.5 1410.97  4996.5 1410.17  4999.3 1409.67
  5002.5 1410.17  5030.0 1411.79  5119.0 1424.16  5124.7 1422.54  5140.8 1424.32
  5146.5 1423.13  5206.2 1427.28  5293.5 1426.24  5402.2 1428.94  5572.5 1430.40
  6022.8 1429.69  6713.9 1441.24  6791.2 1439.86  7016.2 1441.48  7111.5 1442.14
#Mann=9,-1,0
  2312.2    0.05       0  2376.7     0.1       0  2563.5    0.05       0
  4988.5     0.1       0  4996.5    0.07       0  5002.5     0.1       0
  5030.0    0.05       0  6713.9     0.1       0  7016.2    0.05       0
Bank Sta=4996.5,5002.5
Exp/Cntr=0.3,0.1

Chan Stop Cuts=-1