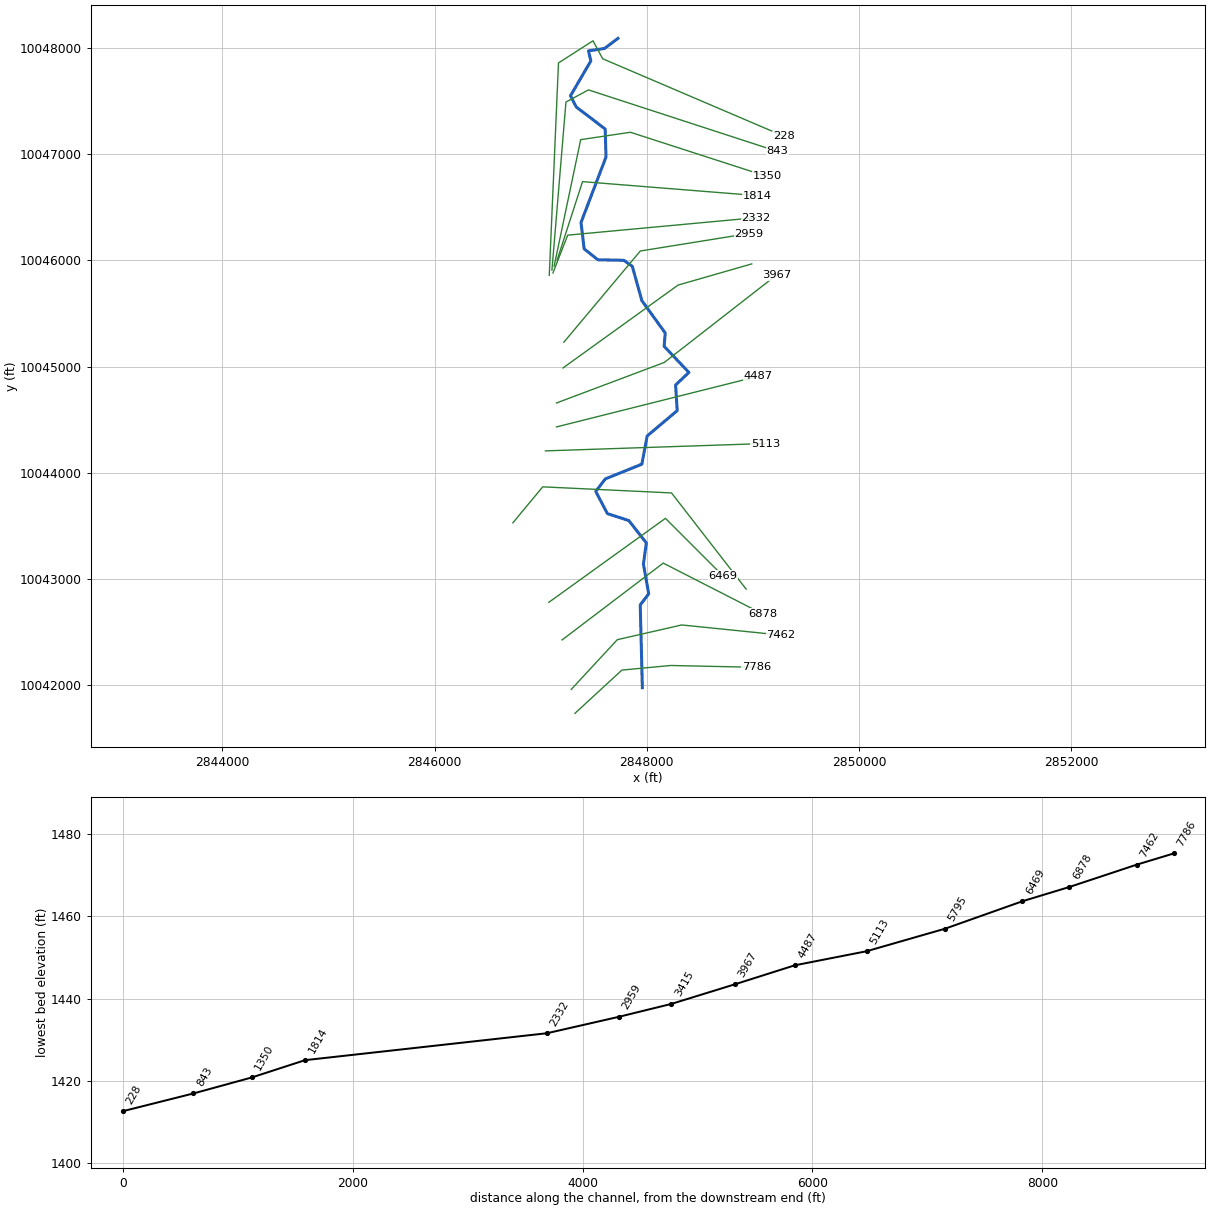
--- UNT057 IN SNOGR.prj (project) ---

Proj Title=UNT057 IN SNOGR Base Level Engineering
Current Plan=p01
Default Exp/Contr=0.3,0.1
English Units
Geom File=g01
Flow File=f01
Plan File=p01
Y Axis Title=Elevation
X Axis Title(PF)=Main Channel Distance
X Axis Title(XS)=Station
BEGIN DESCRIPTION:
UNT057 IN SNOGR
END DESCRIPTION:
DSS Export Rating Curves= 0
DSS Export Rating Curve Sorted= 0
DSS Export Volume Flow Curves= 0
DXF OffsetX= 0
DXF OffsetY= 0
DXF ScaleX= 1
DXF ScaleY= 10

--- UNT057 IN SNOGR.p01 (plan) ---

Plan Title=Multiple Run
Short Identifier=Multiple
Geom File=g01
Flow File=f01
Subcritical Flow
K Sum by GR= 0
Std Step Tol= 0.01
Critical Tol= 0.01
Num of Std Step Trials= 20
Max Error Tol= 0.3
Flow Tol Ratio= 0.001
Split Flow NTrial= 30
Split Flow Tol= 0.02
Split Flow Ratio= 0.02
Log Output Level= 0
Friction Slope Method= 1
Unsteady Friction Slope Method= 2
Unsteady Bridges Friction Slope Method= 1
Parabolic Critical Depth
Global Vel Dist=  1 , 1 , 1
Global Log Level= 0
CheckData=True
Encroach Param= -1, 0, 0, 0
BEGIN DESCRIPTION:
Multiple Run
END DESCRIPTION:

--- UNT057 IN SNOGR.f01 (steady flow) ---

Flow Title=Multiple
Number of Profiles=7
Profile Names=10-year,25-year,50-year,1pct_min,100-year,1pct_plu,500-year
River Rch & RM= UNT057 IN SNOGR,Reach-1,7786
    1509    2247    2904    2742    3708    5015    6076
Boundary for River Rch & Prof#=UNT057 IN SNOGR,Reach-1,1
Up Type=0
Dn Type=3
Dn Slope=0.005
Boundary for River Rch & Prof#=UNT057 IN SNOGR,Reach-1,2
Up Type=0
Dn Type=3
Dn Slope=0.005
Boundary for River Rch & Prof#=UNT057 IN SNOGR,Reach-1,3
Up Type=0
Dn Type=3
Dn Slope=0.005
Boundary for River Rch & Prof#=UNT057 IN SNOGR,Reach-1,4
Up Type=0
Dn Type=3
Dn Slope=0.005
Boundary for River Rch & Prof#=UNT057 IN SNOGR,Reach-1,5
Up Type=0
Dn Type=3
Dn Slope=0.005
Boundary for River Rch & Prof#=UNT057 IN SNOGR,Reach-1,6
Up Type=0
Dn Type=3
Dn Slope=0.005
Boundary for River Rch & Prof#=UNT057 IN SNOGR,Reach-1,7
Up Type=0
Dn Type=3
Dn Slope=0.005

--- UNT057 IN SNOGR.g01 (geometry) ---

Geom Title=Existing Conditions
Program Version=4.10

River Reach=UNT057 IN SNOGR ,Reach-1
Reach XY= 30
      2847958.47     10041973.73      2847938.54      10042753.5
      2848018.37     10042858.77      2847968.63     10043137.84
      2847996.14     10043337.83      2847831.15     10043548.89
      2847629.09     10043614.33      2847519.09     10043823.87
      2847609.33     10043941.36      2847953.89     10044080.57
      2848003.72     10044346.33      2848286.82     10044584.58
      2848271.77     10044826.72      2848397.21     10044944.95
      2848163.86     10045191.12      2848174.16     10045316.53
      2847953.97      10045621.3      2847863.66     10045945.53
      2847783.05     10046001.89      2847539.81     10046006.49
      2847410.18     10046109.33      2847380.36      10046358.1
      2847615.85     10046974.92      2847608.19     10047239.05
      2847335.23     10047447.26      2847281.43     10047552.65
      2847473.18     10047881.15      2847450.59     10047975.53
      2847601.36     10047998.13      2847728.47     10048093.73

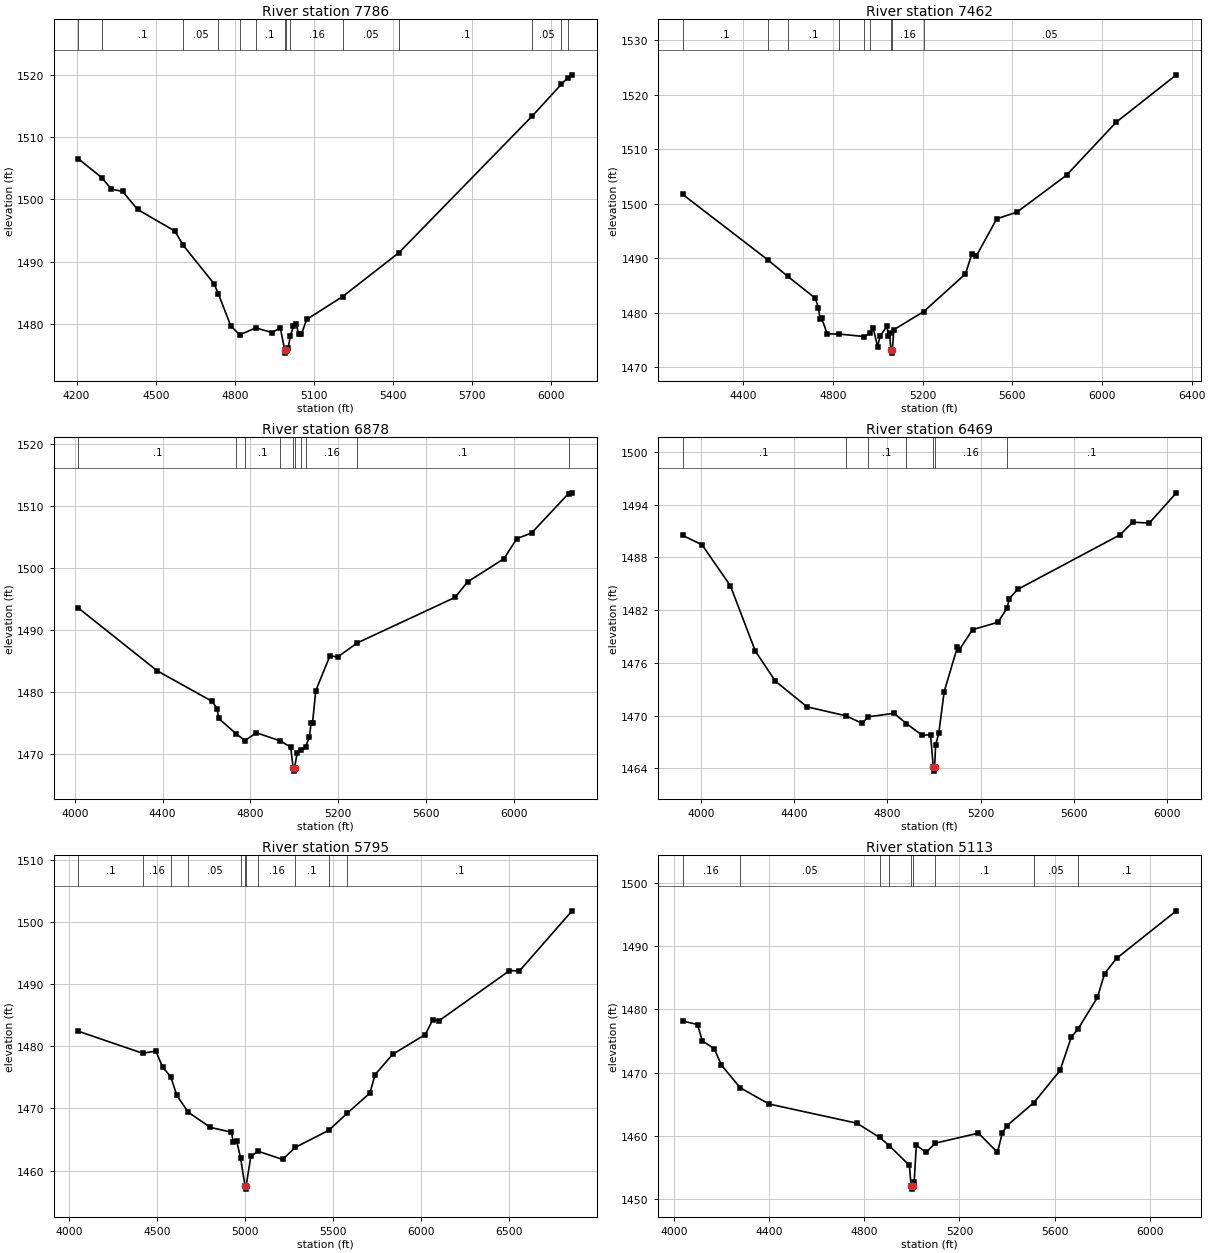
Type RM Length L Ch R = 1 ,7786    ,324,324,324
BEGIN DESCRIPTION:
UNT057 IN SNOGR 12.0
END DESCRIPTION:
XS GIS Cut Line= 4
      2847322.96     10041731.75      2847765.68     10042139.75
      2848225.75     10042183.15        2849033.     10042165.79
#Sta/Elev= 30
  4206.4 1506.55  4295.7  1503.5  4332.1 1501.66  4374.7 1501.29  4431.4 1498.39
  4572.6 1494.93  4604.5 1492.63  4721.1 1486.47  4737.1 1484.87    4785 1479.66
  4818.8 1478.26  4878.9 1479.37  4941.8 1478.62    4972 1479.42  4989.1 1475.82
  4991.8 1475.32  4995.1 1475.82  5002.1 1476.17  5010.6 1478.14  5022.2 1479.63
  5032.2 1479.94  5042.3 1478.34  5052.3 1478.39  5072.4 1480.73  5208.2  1484.4
  5421.4 1491.43  5927.7 1513.43  6036.9 1518.48  6061.4 1519.53    6078 1520.02
#Mann= 14 ,-1 , 0
  4206.4     .16       0  4295.7      .1       0  4604.5     .05       0
  4737.1      .1       0  4818.8     .16       0  4878.9      .1       0
  4989.1     .07       0  4995.1      .1       0  5010.6     .16       0
  5208.2     .05       0  5421.4      .1       0  5927.7     .05       0
  6036.9      .1       0  6061.4     .05       0
Bank Sta=4989.1,4995.1
XS Rating Curve= 0 ,0
Exp/Cntr=0.3,0.1

Type RM Length L Ch R = 1 ,7462    ,584,584,584
BEGIN DESCRIPTION:
UNT057 IN SNOGR 11.0
END DESCRIPTION:
XS GIS Cut Line= 4
      2847288.22     10041957.42      2847722.28      10042426.2
      2848329.92     10042565.09      2849265.48      10042469.8
#Sta/Elev= 30
  4129.1 1501.74  4509.8  1489.7  4597.6  1486.7  4721.2 1482.67  4735.4 1480.93
  4742.2 1478.86  4749.6 1479.03  4774.3 1476.11  4828.1 1476.08  4940.7 1475.62
  4964.9 1476.22  4979.5  1477.2  4999.3 1473.78  5010.3 1475.72    5041 1477.49
  5047.4 1475.76  5052.5 1476.25  5058.6 1473.08  5061.3 1472.58  5064.6 1473.08
  5071.8 1476.88  5205.5 1480.22  5391.3 1487.13    5420 1490.84  5440.1 1490.46
  5530.6 1497.23    5621 1498.47  5842.2 1505.25  6063.3 1514.97  6331.7 1523.67
#Mann= 9 ,-1 , 0
  4129.1      .1       0  4509.8     .05       0  4597.6      .1       0
  4828.1     .16       0  4940.7      .1       0  4964.9     .16       0
  5058.6     .07       0  5064.6     .16       0  5205.5     .05       0
Bank Sta=5058.6,5064.6
XS Rating Curve= 0 ,0
Exp/Cntr=0.3,0.1

Type RM Length L Ch R = 1 ,6878    ,409,409,409
BEGIN DESCRIPTION:
UNT057 IN SNOGR 10.0
END DESCRIPTION:
XS GIS Cut Line= 3
      2847201.95     10042423.97       2848155.1     10043147.95
      2849092.61     10042668.78
#Sta/Elev= 30
  4015.3 1493.55  4375.9 1483.37  4626.3 1478.43  4648.2 1477.24  4654.5 1475.71
  4735.3 1473.18    4775 1472.12  4827.1 1473.37  4935.2 1472.07  4983.1 1471.05
  4994.6 1467.67  4997.4 1467.17  5000.6 1467.67  5012.2 1470.02  5029.5 1470.64
  5051.9 1471.12  5068.4 1472.73  5076.7    1475  5082.9 1475.03  5097.5 1480.18
  5161.9 1485.81  5197.3 1485.63  5287.4 1487.91  5732.4 1495.26  5788.8 1497.76
  5954.6  1501.5  6013.4 1504.75  6080.8 1505.67  6249.2 1512.05  6265.1 1512.16
#Mann= 10 ,-1 , 0
  4015.3      .1       0  4735.3     .05       0    4775      .1       0
  4935.2     .16       0  4994.6     .07       0  5000.6     .16       0
  5029.5      .1       0  5051.9     .16       0  5287.4      .1       0
  6249.2     .05       0
Bank Sta=4994.6,5000.6
XS Rating Curve= 0 ,0
Exp/Cntr=0.3,0.1

Type RM Length L Ch R = 1 ,6469    ,674,674,674
BEGIN DESCRIPTION:
UNT057 IN SNOGR 9.0
END DESCRIPTION:
XS GIS Cut Line= 3
      2847076.98     10042778.16      2848175.94     10043569.83
      2848717.28     10043028.48
#Sta/Elev= 30
  3920.7 1490.52  4004.9 1489.43  4126.4 1484.77  4233.2 1477.36  4319.1 1473.94
  4455.3 1471.01  4622.4 1469.99  4692.2 1469.13  4717.1 1469.87  4828.4 1470.28
  4881.8 1469.11  4949.9 1467.77  4985.5 1467.85  4997.2  1464.2    5000  1463.7
  5003.2  1464.2  5007.1 1466.63  5021.1 1468.05  5044.1 1472.74  5100.8  1477.8
    5107 1477.42  5165.9 1479.79  5275.1 1480.63  5314.2 1482.25  5323.6 1483.32
    5359 1484.36  5797.4 1490.55    5854 1492.01  5924.7 1491.91  6040.7 1495.35
#Mann= 7 ,-1 , 0
  3920.7      .1       0  4622.4     .05       0  4717.1      .1       0
  4881.8     .16       0  4997.2     .07       0  5003.2     .16       0
  5314.2      .1       0
Bank Sta=4997.2,5003.2
XS Rating Curve= 0 ,0
Exp/Cntr=0.3,0.1

Type RM Length L Ch R = 1 ,5795    ,682,682,682
BEGIN DESCRIPTION:
UNT057 IN SNOGR 8.0
END DESCRIPTION:
XS GIS Cut Line= 4
      2846738.42     10043528.14      2847019.69      10043866.7
      2848233.23     10043809.41      2848936.37     10042903.14
#Sta/Elev= 30
  4053.4 1482.41  4418.7 1478.87  4493.6 1479.22  4532.4 1476.64  4578.5 1475.09
  4612.5  1472.1  4677.5  1469.4  4802.7 1466.95  4922.8 1466.17  4932.8  1464.6
  4952.8  1464.7  4974.4 1462.05  4999.9 1457.52  5002.6 1457.02  5005.9 1457.52
  5032.9 1462.28  5073.3 1463.11  5213.1 1461.79  5284.4 1463.72  5474.7 1466.47
  5581.1 1469.26  5708.4 1472.47    5738 1475.44  5837.6  1478.7  6022.3 1481.87
  6065.7 1484.27    6101  1484.1  6500.4 1492.15  6557.2 1492.11  6855.5 1501.77
#Mann= 11 ,-1 , 0
  4053.4      .1       0  4418.7     .16       0  4578.5      .1       0
  4677.5     .05       0  4974.4      .1       0  4999.9     .07       0
  5005.9      .1       0  5073.3     .16       0  5284.4      .1       0
  5474.7     .16       0  5581.1      .1       0
Bank Sta=4999.9,5005.9
XS Rating Curve= 0 ,0
Exp/Cntr=0.3,0.1

Type RM Length L Ch R = 1 ,5113    ,626,626,626
BEGIN DESCRIPTION:
UNT057 IN SNOGR 7.0
END DESCRIPTION:
XS GIS Cut Line= 2
      2847045.23     10044205.72      2849119.87     10044275.16
#Sta/Elev= 30
    4036 1478.17  4099.3 1477.59  4119.3    1475  4169.3 1473.78  4199.3  1471.2
  4277.6 1467.62  4399.4 1465.02  4769.6 1461.98  4865.1 1459.72  4904.6 1458.45
  4989.8 1455.31  4996.8 1452.05  4999.5 1451.55  5002.8 1452.05  5009.8 1452.65
  5018.8 1458.49  5059.8 1457.38  5099.2 1458.83  5279.9 1460.41    5360 1457.37
    5380 1460.42    5400  1461.6  5513.3 1465.25  5622.9 1470.33  5670.1 1475.58
  5697.8 1476.85  5780.2 1481.89  5810.2 1485.67  5860.3 1488.06  6111.8 1495.59
#Mann= 9 ,-1 , 0
    4036     .16       0  4277.6     .05       0  4865.1      .1       0
  4904.6     .16       0  4996.8     .07       0  5002.8     .16       0
  5099.2      .1       0  5513.3     .05       0  5697.8      .1       0
Bank Sta=4996.8,5002.8
XS Rating Curve= 0 ,0
Exp/Cntr=0.3,0.1

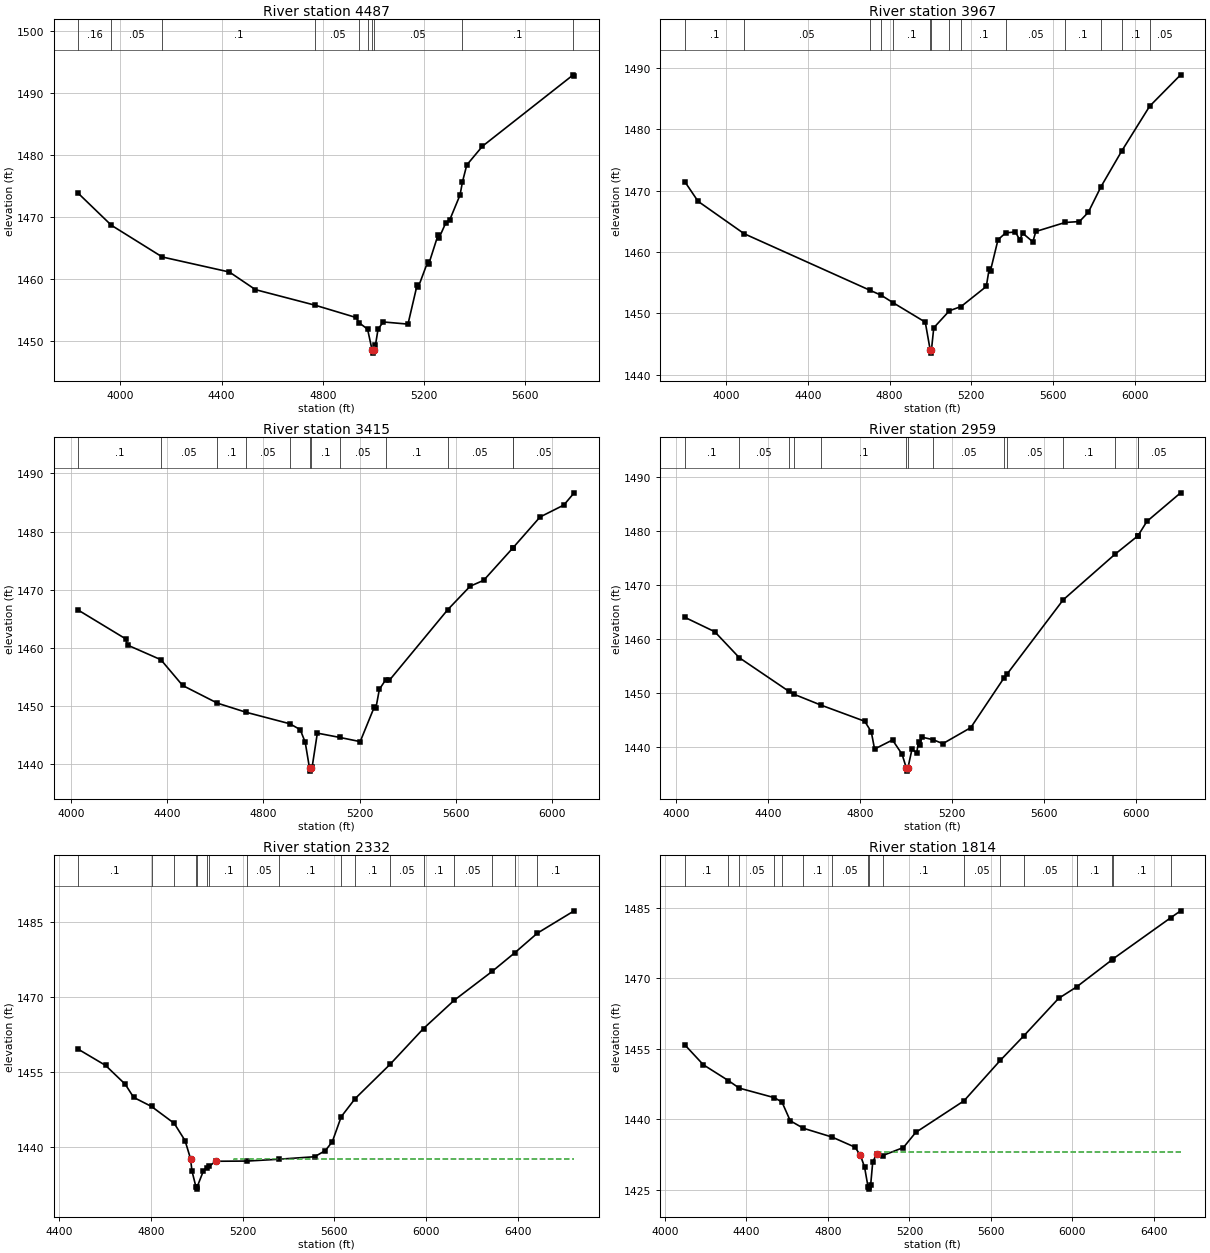
Type RM Length L Ch R = 1 ,4487    ,520,520,520
BEGIN DESCRIPTION:
UNT057 IN SNOGR 6.0
END DESCRIPTION:
XS GIS Cut Line= 2
       2847149.4     10044431.42      2849050.18     10044908.79
#Sta/Elev= 30
  3833.5 1473.84    3964 1468.71  4165.3  1463.6  4430.5 1461.18  4533.6 1458.34
  4770.7 1455.82  4930.8 1453.86  4944.7 1452.97  4976.8 1451.97  4994.6 1448.62
  4997.4 1448.12  5000.6 1448.62  5007.9 1449.39  5018.2 1451.99  5038.9 1453.14
  5136.5 1452.79  5172.5 1459.08  5177.7  1458.8  5213.7 1462.73  5218.8 1462.49
  5254.8 1467.08    5260 1466.73  5286.3 1469.13  5301.1 1469.53  5342.3 1473.59
  5351.8 1475.69  5368.8 1478.41  5430.7 1481.43  5789.8 1492.93  5793.3 1492.78
#Mann= 10 ,-1 , 0
  3833.5     .16       0    3964     .05       0  4165.3      .1       0
  4770.7     .05       0  4944.7      .1       0  4976.8     .05       0
  4994.6    .035       0  5000.6     .05       0  5351.8      .1       0
  5789.8     .05       0
Bank Sta=4994.6,5000.6
XS Rating Curve= 0 ,0
Exp/Cntr=0.3,0.1

Type RM Length L Ch R = 1 ,3967    ,552,552,552
BEGIN DESCRIPTION:
UNT057 IN SNOGR 4.0
END DESCRIPTION:
XS GIS Cut Line= 3
      2847149.39     10044657.12      2848164.99     10045039.05
      2849223.72     10045863.48
#Sta/Elev= 30
    3798 1471.45  3862.9 1468.25  4088.4 1462.97  4703.8 1453.76  4759.6 1452.94
  4817.3 1451.73    4975 1448.56  4999.2 1444.01  5001.9 1443.51  5005.2 1444.01
  5016.6 1447.64  5093.4 1450.42  5150.2  1451.1  5273.6 1454.37  5288.1 1457.27
  5294.4 1456.97    5331 1461.99  5369.2 1463.12  5416.5 1463.25  5437.3 1461.97
  5451.8 1463.05  5501.6 1461.65  5516.1 1463.33  5659.5  1464.8  5729.6 1464.95
    5773 1466.46  5835.3 1470.64  5936.7 1476.45  6073.4 1483.75  6224.9 1488.86
#Mann= 14 ,-1 , 0
    3798      .1       0  4088.4     .05       0  4703.8      .1       0
  4759.6     .05       0  4817.3      .1       0  4999.2     .07       0
  5005.2      .1       0  5093.4     .05       0  5150.2      .1       0
  5369.2     .05       0  5659.5      .1       0  5835.3     .05       0
  5936.7      .1       0  6073.4     .05       0
Bank Sta=4999.2,5005.2
XS Rating Curve= 0 ,0
Exp/Cntr=0.3,0.1

Type RM Length L Ch R = 1 ,3415    ,456,456,456
BEGIN DESCRIPTION:
UNT057 IN SNOGR 3.0
END DESCRIPTION:
XS GIS Cut Line= 3
      2847210.13     10044986.97      2848295.19     10045768.22
      2848989.61     10045967.86
#Sta/Elev= 30
  4031.7 1466.46    4228 1461.53  4236.5 1460.44  4374.6 1457.93  4464.8  1453.5
  4609.4 1450.45  4728.8 1448.88  4909.7 1446.91  4953.3  1445.9  4974.2 1443.71
    4992 1439.25  4994.8 1438.75    4998 1439.25  5003.1  1439.5  5024.5 1445.29
  5117.8 1444.55  5202.5 1443.83  5261.3 1449.81  5267.5 1449.54  5282.2 1452.84
  5308.1 1454.45    5324  1454.4  5566.1 1466.54  5659.2 1470.58  5715.5  1471.6
  5835.2  1477.1  5835.4 1477.11  5949.7  1482.5  6048.5 1484.56  6091.3 1486.66
#Mann= 12 ,-1 , 0
  4031.7      .1       0  4374.6     .05       0  4609.4      .1       0
  4728.8     .05       0  4909.7      .1       0    4992     .07       0
    4998      .1       0  5117.8     .05       0  5308.1      .1       0
  5566.1     .05       0  5835.2      .1       0  5835.4     .05       0
Bank Sta=4992,4998
XS Rating Curve= 0 ,0
Exp/Cntr=0.3,0.1

Type RM Length L Ch R = 1 ,2959    ,627,627,627
BEGIN DESCRIPTION:
UNT057 IN SNOGR 2.0
END DESCRIPTION:
XS GIS Cut Line= 3
      2847218.81     10045230.03      2847939.29      10046089.4
      2848963.57     10046254.32
#Sta/Elev= 30
  4037.2 1464.06  4167.5  1461.4  4274.8 1456.58  4490.6 1450.37  4511.2 1449.86
  4628.1 1447.86  4820.6 1444.84  4849.2 1442.88  4863.5  1439.7  4941.6 1441.38
  4983.2 1438.75  5002.3 1436.12  5005.1 1435.62  5008.3 1436.12  5026.2 1439.64
    5047 1439.02  5054.8 1441.04  5061.3 1440.54  5069.1 1441.91  5118.5 1441.43
  5160.7  1440.7  5282.3 1443.66  5427.3 1452.87  5439.9 1453.54  5684.7 1467.29
  5909.7  1475.7    6009 1479.09  6010.3 1479.13  6049.1 1481.79  6196.1 1487.08
#Mann= 14 ,-1 , 0
  4037.2      .1       0  4274.8     .05       0  4490.6      .1       0
  4511.2     .05       0  4628.1      .1       0  5002.3     .07       0
  5008.3      .1       0  5118.5     .05       0  5427.3      .1       0
  5439.9     .05       0  5684.7      .1       0  5909.7     .05       0
    6009      .1       0  6010.3     .05       0
Bank Sta=5002.3,5008.3
XS Rating Curve= 0 ,0
Exp/Cntr=0.3,0.1

Type RM Length L Ch R = 1 ,2332    ,2104,2104,2104
BEGIN DESCRIPTION:
Mapping XS 1fb7ee0b
END DESCRIPTION:
XS GIS Cut Line= 3
        2847116.     10045882.91       2847254.9     10046238.84
      2849030.07     10046403.77
#Sta/Elev= 30
  4482.4 1459.52  4601.4  1456.3  4687.2 1452.54  4723.9 1449.92  4801.9 1448.11
  4900.9 1444.75  4948.4  1441.3  4972.4 1437.67  4978.5 1435.25  4995.6 1432.12
  4998.4 1431.62  5001.6 1432.12  5028.8 1435.29  5043.2 1435.89  5054.9  1436.2
  5081.7 1437.18  5220.3 1437.22  5360.1 1437.59  5513.8 1438.08    5561 1439.31
  5591.2 1441.07  5630.4 1446.08  5691.3 1449.69  5843.2  1456.5  5989.5 1463.66
  6123.2 1469.28  6289.6 1475.07  6388.2 1478.78  6486.9 1482.69  6647.3 1487.14
#Mann= 17 ,-1 , 0
  4482.4      .1       0  4801.9     .16       0  4900.9      .1       0
  4995.6     .07       0  5001.6      .1       0  5043.2     .05       0
  5054.9      .1       0  5220.3     .05       0  5360.1      .1       0
  5630.4     .05       0  5691.3      .1       0  5843.2     .05       0
  5989.5      .1       0  6123.2     .05       0  6289.6      .1       0
  6388.2     .05       0  6486.9      .1       0
#XS Ineff= 2 , 0
                          5160.8         1437.73
Permanent Ineff=
       T       T
Bank Sta=4972.4,5081.7
XS Rating Curve= 0 ,0
Exp/Cntr=0.3,0.1

Type RM Length L Ch R = 1 ,1814    ,464,464,464
BEGIN DESCRIPTION:
Mapping XS e4be6319
END DESCRIPTION:
XS GIS Cut Line= 3
      2847155.08     10046003.62      2847394.66     10046743.18
      2849043.69     10046611.26
#Sta/Elev= 30
  4098.6 1455.85  4189.4  1451.6  4311.7 1448.24  4365.5 1446.62  4537.7 1444.58
  4575.2 1443.64  4615.8 1439.65    4680 1438.06  4820.3 1436.19  4933.4 1434.02
  4960.1 1432.26  4980.1  1429.8  4997.2 1425.58    5000 1425.08  5003.2 1425.58
  5010.2 1425.98  5020.3 1430.87  5040.3 1432.64  5069.2 1432.24  5170.7 1433.95
  5230.9 1437.16  5467.9 1443.91    5646 1452.54  5759.9  1457.7  5931.6 1465.74
  6020.2  1468.2  6195.2 1474.02  6199.5 1474.19  6482.5 1482.97  6530.3 1484.42
#Mann= 17 ,-1 , 0
  4098.6      .1       0  4311.7     .16       0  4365.5     .05       0
  4537.7      .1       0  4575.2     .05       0    4680      .1       0
  4820.3     .05       0  4997.2    .035       0  5003.2     .05       0
  5069.2      .1       0  5467.9     .05       0    5646      .1       0
  5759.9     .05       0  6020.2      .1       0  6195.2     .05       0
  6199.5      .1       0  6482.5     .05       0
#XS Ineff= 2 , 0
                         5047.89         1433.05
Permanent Ineff=
       T       T
Bank Sta=4960.1,5040.3
XS Rating Curve= 0 ,0
Exp/Cntr=0.3,0.1

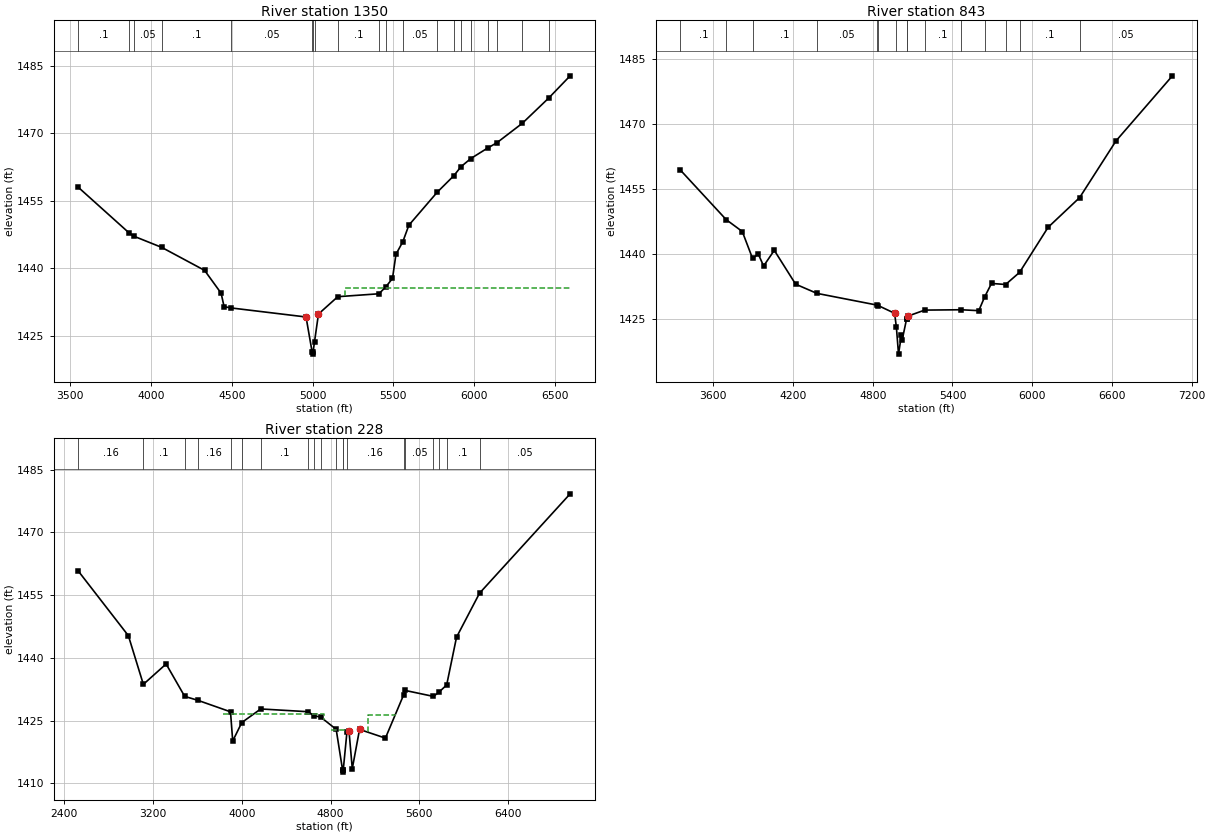
Type RM Length L Ch R = 1 ,1350    ,507,507,507
BEGIN DESCRIPTION:
Mapping XS 16ffebdb
END DESCRIPTION:
XS GIS Cut Line= 4
      2847127.29     10045948.01      2847377.29     10047139.02
      2847846.04     10047208.46      2849133.83     10046791.93
#Sta/Elev= 30
  3549.2 1458.05  3863.5 1447.89  3891.8 1447.16  4066.3 1444.64  4331.6 1439.52
  4433.8 1434.44  4452.3 1431.44  4496.5 1431.15  4959.4 1429.14  4996.9 1421.37
  4999.6 1420.87  5002.9 1421.37    5012 1423.68  5036.2  1429.8  5155.7 1433.66
  5410.5 1434.31    5453 1435.85  5494.3 1437.73  5515.8 1443.11  5558.1 1445.89
  5595.6 1449.58  5771.7 1456.95  5873.6 1460.59    5918  1462.6  5978.8 1464.42
  6083.9 1466.78  6140.7 1467.95  6297.6 1472.27    6460 1477.86  6593.5 1482.84
#Mann= 20 ,-1 , 0
  3549.2      .1       0  3863.5     .16       0  3891.8     .05       0
  4066.3      .1       0  4496.5     .05       0  4996.9    .035       0
  5002.9     .05       0    5012     .05       0  5155.7      .1       0
  5410.5     .05       0    5453      .1       0  5558.1     .05       0
  5771.7      .1       0  5873.6     .05       0    5918      .1       0
  5978.8     .05       0  6083.9      .1       0  6140.7     .05       0
  6297.6      .1       0    6460     .05       0
#XS Ineff= 2 , 0
                         5199.72         1435.51
Permanent Ineff=
       T       T
Bank Sta=4959.4,5036.2
XS Rating Curve= 0 ,0
Exp/Cntr=0.3,0.1

Type RM Length L Ch R = 1 ,843     ,615,615,615
BEGIN DESCRIPTION:
Mapping XS 542d0191
END DESCRIPTION:
XS GIS Cut Line= 4
      2847106.46     10045909.88      2847238.41     10047493.18
      2847450.21     10047607.77      2849230.17     10047028.33
#Sta/Elev= 30
  3353.1 1459.42  3697.5    1448  3818.6 1445.26  3895.7 1439.07    3939 1440.06
  3979.1 1437.31  4059.4 1440.92  4219.9 1433.12  4379.9    1431  4833.5 1428.29
  4840.3  1428.2  4964.7 1426.41  4978.2 1423.15  4994.1 1416.99  5016.2 1421.38
  5021.9  1420.3  5054.3 1425.01    5058 1425.17    5067 1425.78    5191 1427.14
  5464.5 1427.22  5597.9 1427.01  5641.5 1430.14  5693.7 1433.29  5799.7 1433.04
  5904.9 1435.84  6119.3 1446.22  6356.8 1453.08  6630.1 1466.14  7054.6 1481.15
#Mann= 15 ,-1 , 0
  3353.1      .1       0  3697.5     .16       0  3895.7      .1       0
  4379.9     .05       0  4833.5      .1       0  4840.3     .05       0
  4978.2    .035       0  5054.3     .05       0    5058     .16       0
    5191      .1       0  5464.5     .05       0  5641.5      .1       0
  5799.7     .05       0  5904.9      .1       0  6356.8     .05       0
Bank Sta=4964.7,5067
XS Rating Curve= 0 ,0
Exp/Cntr=0.3,0.1

Type RM Length L Ch R = 1 ,228     ,0,0,0
BEGIN DESCRIPTION:
UNT057 IN SNOGR 1.0
END DESCRIPTION:
XS GIS Cut Line= 5
      2847081.29      10045861.2      2847168.09     10047862.11
      2847493.61     10048070.44      2847584.76     10047901.17
      2849290.52     10047171.99
#Sta/Elev= 30
  2523.8 1460.78  2976.8 1445.28  3111.8 1433.65  3317.1 1438.52  3484.5 1430.78
    3605 1429.82  3897.7 1427.09  3917.6 1420.11  3999.6 1424.52  4170.1 1427.77
  4596.3 1427.11  4655.1 1426.11  4710.3 1425.84  4850.6  1422.9  4908.4 1413.17
  4911.1 1412.67  4914.4 1413.17  4947.9  1422.3  4966.1 1422.55  4995.8 1413.51
  5061.5 1422.88  5294.6  1420.8  5459.8 1431.19  5473.8 1432.19  5727.5 1430.77
  5775.7 1431.74  5847.1 1433.51  5935.9 1444.92  6143.4 1455.44  6960.4 1479.19
#Mann= 20 ,-1 , 0
  2523.8     .16       0  3111.8      .1       0  3484.5     .05       0
    3605     .16       0  3897.7      .1       0  3999.6     .05       0
  4170.1      .1       0  4596.3     .16       0  4655.1      .1       0
  4710.3     .16       0  4850.6     .05       0  4908.4     .07       0
  4914.4     .05       0  4947.9     .16       0  5459.8      .1       0
  5473.8     .05       0  5727.5      .1       0  5775.7     .05       0
  5847.1      .1       0  6143.4     .05       0
#XS Ineff= 3 ,-1
 3829.55 4741.48 1426.47 4803.98 4948.86 1422.79 5136.36 5392.05 1426.21
Permanent Ineff=
       T       T       T
Bank Sta=4966.1,5061.5
XS Rating Curve= 0 ,0
Exp/Cntr=0.3,0.1

Chan Stop Cuts=-1
Use User Specified Reach Order=0
Composite Channel Slope=5