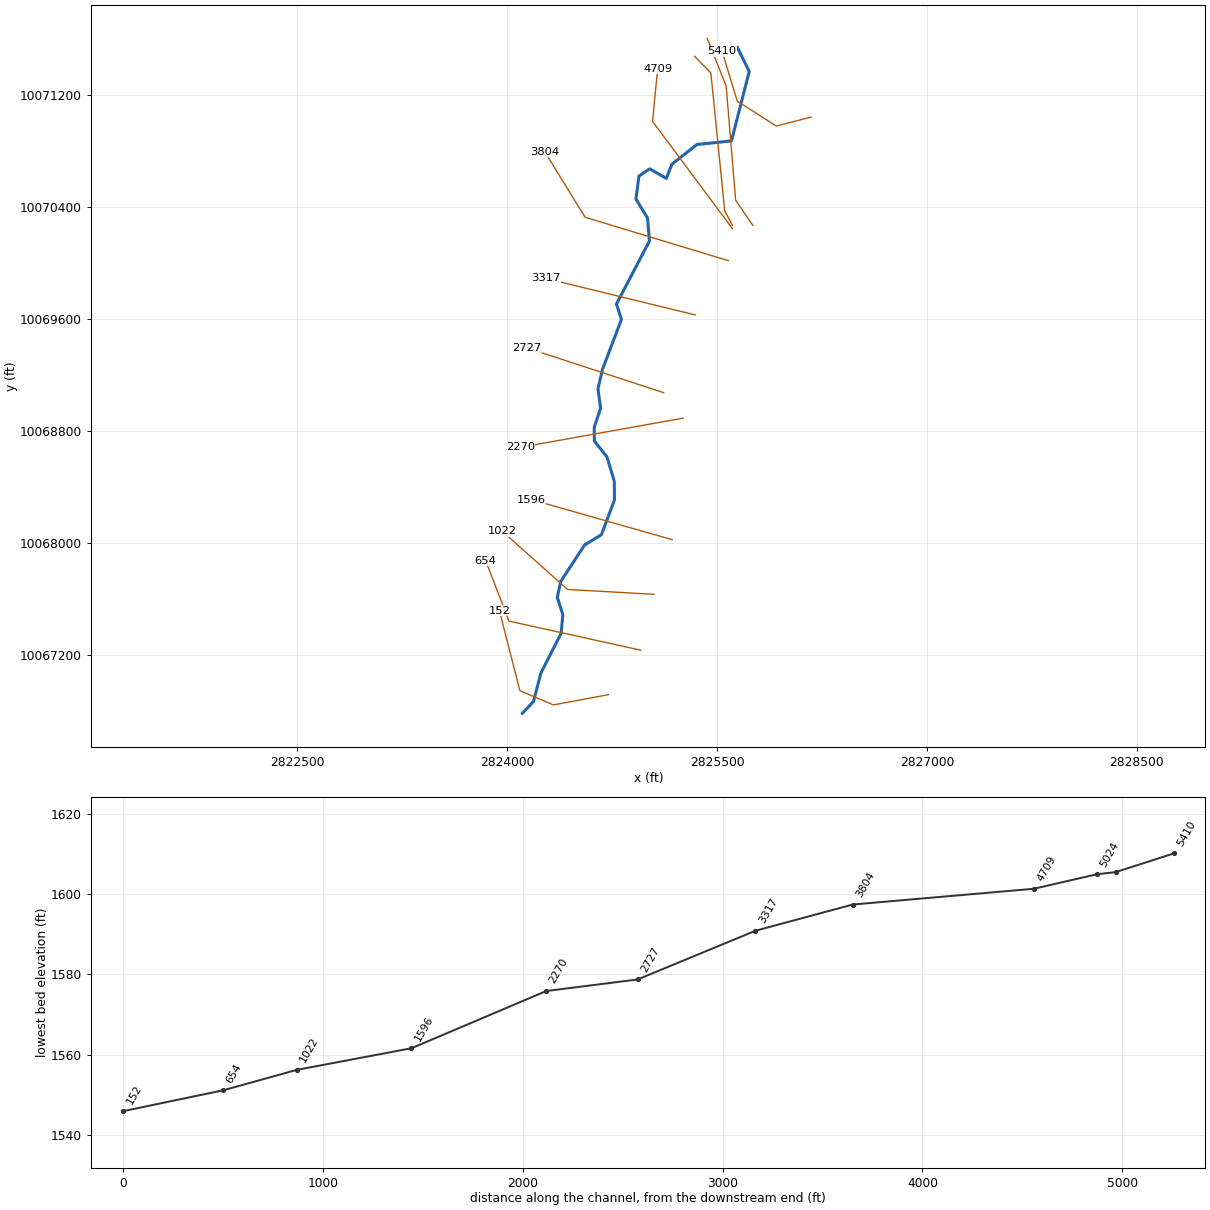
--- UNT058 IN NNOGR.prj (project) ---

Proj Title=UNT058 IN NNOGR Base Level Engineering
Current Plan=p01
Default Exp/Contr=0.3,0.1
English Units
Geom File=g01
Flow File=f01
Plan File=p01
Y Axis Title=Elevation
X Axis Title(PF)=Main Channel Distance
X Axis Title(XS)=Station
BEGIN DESCRIPTION:
UNT058 IN NNOGR
END DESCRIPTION:
DSS Export Rating Curves= 0
DSS Export Rating Curve Sorted= 0
DSS Export Volume Flow Curves= 0
DXF OffsetX= 0
DXF OffsetY= 0
DXF ScaleX= 1
DXF ScaleY= 10

--- UNT058 IN NNOGR.p01 (plan) ---

Plan Title=Multiple Run
Short Identifier=Multiple
Geom File=g01
Flow File=f01
Subcritical Flow
K Sum by GR= 0
Std Step Tol= 0.01
Critical Tol= 0.01
Num of Std Step Trials= 20
Max Error Tol= 0.3
Flow Tol Ratio= 0.001
Split Flow NTrial= 30
Split Flow Tol= 0.02
Split Flow Ratio= 0.02
Log Output Level= 0
Friction Slope Method= 1
Unsteady Friction Slope Method= 2
Unsteady Bridges Friction Slope Method= 1
Parabolic Critical Depth
Global Vel Dist=  1 , 1 , 1
Global Log Level= 0
CheckData=True
Encroach Param= -1, 0, 0, 0
BEGIN DESCRIPTION:
Multiple Run
END DESCRIPTION:

--- UNT058 IN NNOGR.f01 (steady flow) ---

Flow Title=Multiple
Program Version=4.10
Number of Profiles= 7
Profile Names=10-year,25-year,50-year,1pct_min,100-year,1pct_plu,500-year
River Rch & RM=UNT058 IN NNOGR,Reach-1         ,5410
    1115    1650    2124    2003    2709    3663    4421
River Rch & RM=UNT058 IN NNOGR,Reach-1         ,3804
    1237    1833    2363    2228    3013    4075    4919
Boundary for River Rch & Prof#=UNT058 IN NNOGR,Reach-1         , 1
Up Type= 0
Dn Type= 3
Dn Slope=0.011
Boundary for River Rch & Prof#=UNT058 IN NNOGR,Reach-1         , 2
Up Type= 0
Dn Type= 3
Dn Slope=0.011
Boundary for River Rch & Prof#=UNT058 IN NNOGR,Reach-1         , 3
Up Type= 0
Dn Type= 3
Dn Slope=0.011
Boundary for River Rch & Prof#=UNT058 IN NNOGR,Reach-1         , 4
Up Type= 0
Dn Type= 3
Dn Slope=0.011
Boundary for River Rch & Prof#=UNT058 IN NNOGR,Reach-1         , 5
Up Type= 0
Dn Type= 3
Dn Slope=0.011
Boundary for River Rch & Prof#=UNT058 IN NNOGR,Reach-1         , 6
Up Type= 0
Dn Type= 3
Dn Slope=0.011
Boundary for River Rch & Prof#=UNT058 IN NNOGR,Reach-1         , 7
Up Type= 0
Dn Type= 3
Dn Slope=0.011
DSS Import GetInterval= 0
DSS Import GetPeak= 0
DSS Import FillOption= 0

--- UNT058 IN NNOGR.g01 (geometry) ---

Geom Title=Existing Conditions
Program Version=4.10

River Reach=UNT058 IN NNOGR ,Reach-1
Reach XY= 30
      2825644.94     10071542.39      2825729.68     10071370.81
      2825602.77     10070874.45      2825355.97      10070848.7
      2825177.16     10070708.28      2825137.39     10070606.55
      2825017.66     10070675.02       2824941.8     10070622.61
      2824919.91     10070459.35      2825003.27     10070322.69
      2825016.57     10070159.02       2824780.9     10069708.35
       2824816.7     10069599.52       2824681.3     10069242.56
      2824648.58     10069103.53      2824667.55     10068964.25
      2824622.29     10068828.79      2824622.66     10068730.82
      2824712.98     10068616.23      2824765.55     10068442.52
       2824766.6     10068309.34      2824673.72     10068060.72
       2824553.3     10067987.03      2824382.85     10067726.63
      2824357.99     10067613.72      2824397.59     10067488.53
      2824385.43     10067354.99       2824241.1     10067072.64
      2824188.22     10066868.83      2824108.47     10066783.73

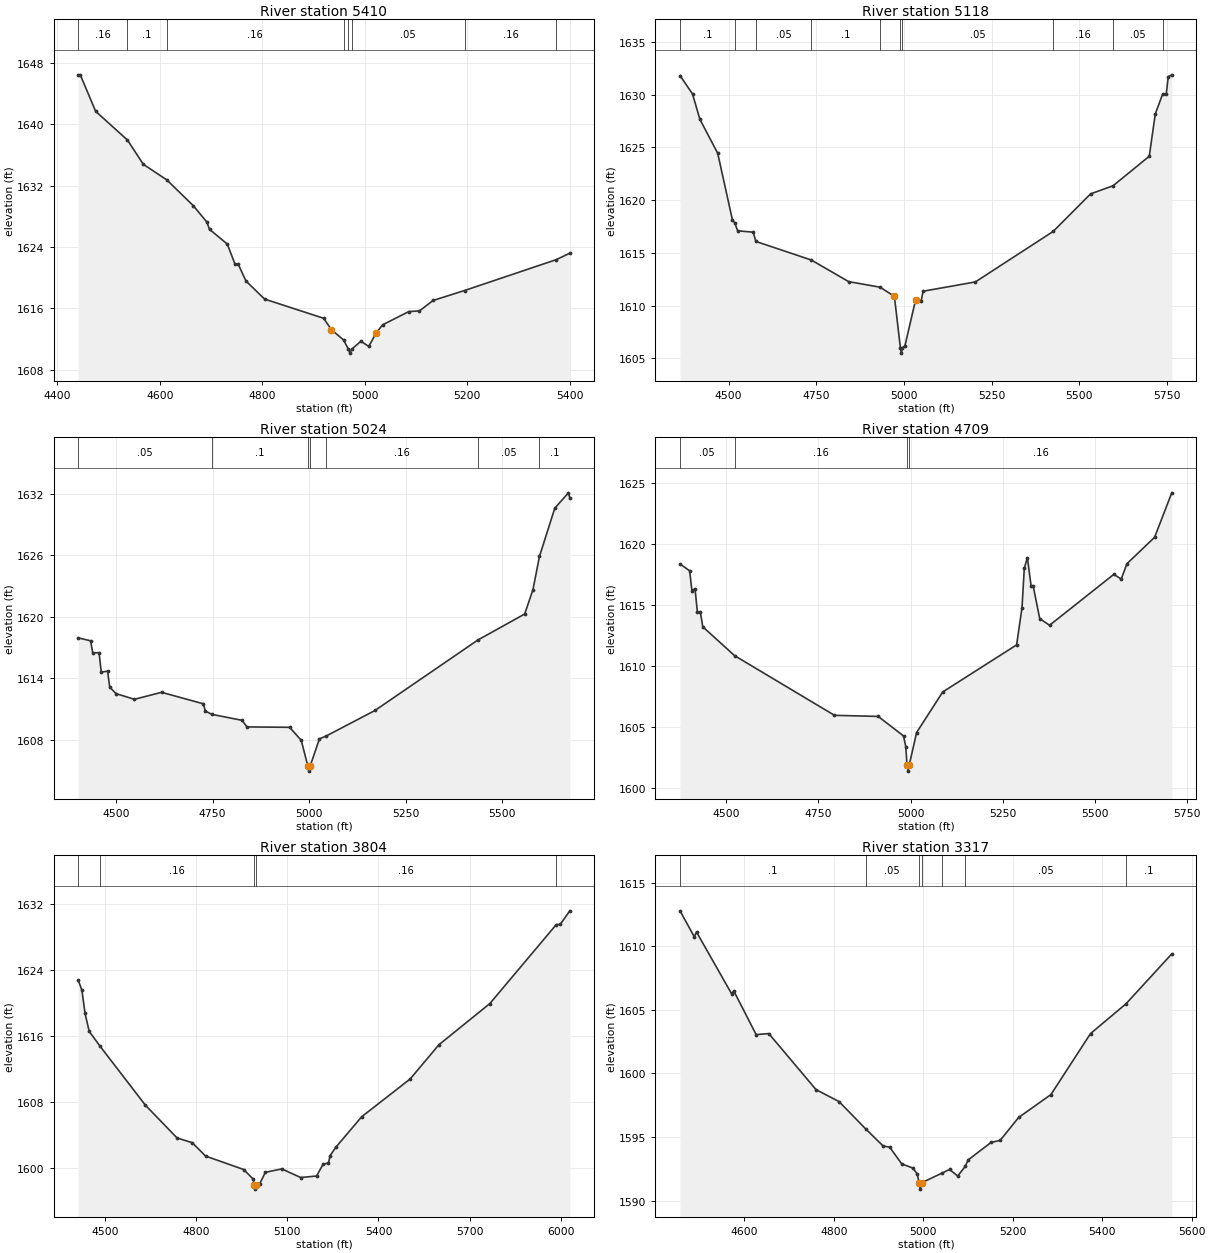
Type RM Length L Ch R = 1 ,5410    ,292,292,292
BEGIN DESCRIPTION:
UNT058 IN NNOGR 12.0
END DESCRIPTION:
XS GIS Cut Line= 4
      2826171.59     10071044.52      2825923.13     10070980.51
      2825644.27     10071158.46      2825535.75      10071514.4
#Sta/Elev= 30
  4440.7 1646.47  4444.9 1646.47  4474.9 1641.71    4537 1637.96  4567.8  1634.8
  4613.8 1632.76  4665.1 1629.42  4691.8 1627.27  4697.1 1626.31  4731.8 1624.39
    4747 1621.74    4753 1621.78  4768.2 1619.57  4804.6 1617.21  4919.7 1614.71
  4934.9 1613.22  4958.6 1611.88  4968.3 1610.66    4971 1610.16  4974.3 1610.66
  4992.4 1611.71  5007.7 1611.04  5022.6 1612.81  5034.8 1613.85  5085.9 1615.58
  5106.8 1615.67  5133.3 1617.03  5194.8 1618.33  5373.9 1622.36  5400.2  1623.2
#Mann= 8 ,-1 , 0
  4440.7     .16       0    4537      .1       0  4613.8     .16       0
  4958.6     .05       0  4968.3     .04       0  4974.3     .05       0
  5194.8     .16       0  5373.9     .05       0
Bank Sta=4934.9,5022.6
XS Rating Curve= 0 ,0
Exp/Cntr=0.3,0.1

Type RM Length L Ch R = 1 ,5118    ,94,94,94
BEGIN DESCRIPTION:
Mapping XS eaacff26
END DESCRIPTION:
XS GIS Cut Line= 4
      2825754.93     10070271.49      2825632.55     10070451.16
      2825564.84     10071266.26      2825429.44     10071607.37
#Sta/Elev= 30
  4361.5 1631.81    4397 1630.07    4418 1627.67  4468.9 1624.44  4510.8 1618.13
  4517.3 1617.86  4525.8 1617.09  4569.9 1616.96  4577.9 1616.08  4735.7 1614.32
  4842.4 1612.27  4932.3 1611.74  4972.8 1610.87  4989.9 1605.99  4992.6 1605.49
  4995.9 1605.99  5002.9 1606.19    5033  1610.5  5049.5 1610.48  5054.6 1611.36
  5203.6 1612.24  5425.6 1617.03  5532.3 1620.59  5596.4 1621.36  5699.7 1624.16
  5716.8 1628.17  5737.7 1630.04  5748.3  1630.1  5753.7 1631.69  5763.8 1631.88
#Mann= 10 ,-1 , 0
  4361.5      .1       0  4517.3     .16       0  4577.9     .05       0
  4735.7      .1       0  4932.3     .05       0  4989.9    .035       0
  4995.9     .05       0  5425.6     .16       0  5596.4     .05       0
  5737.7      .1       0
Bank Sta=4972.8,5033
XS Rating Curve= 0 ,0
Exp/Cntr=0.3,0.1

Type RM Length L Ch R = 1 ,5024    ,315,315,315
BEGIN DESCRIPTION:
Mapping XS 38f58311
END DESCRIPTION:
XS GIS Cut Line= 4
       2825609.1     10070271.49      2825554.43     10070375.64
      2825455.47     10071360.01       2825338.8     10071479.28
#Sta/Elev= 30
  4401.8 1617.95    4434 1617.66  4439.6 1616.49  4456.1  1616.5  4461.7 1614.61
  4478.1  1614.7  4483.7 1613.14  4500.2 1612.51  4547.7 1611.96    4618 1612.64
  4726.3 1611.52  4731.3 1610.81  4748.5 1610.49  4826.5 1609.91  4839.1 1609.27
  4949.7 1609.23  4979.8 1607.96  4996.9 1605.46  4999.7 1604.96  5002.9 1605.46
    5027 1608.11  5043.8 1608.37  5170.8 1610.87  5437.5 1617.74  5558.7 1620.27
    5580 1622.63    5597 1625.89  5636.6 1630.58  5671.9 1632.08  5675.6 1631.59
#Mann= 7 ,-1 , 0
  4401.8     .05       0  4748.5      .1       0  4996.9     .07       0
  5002.9      .1       0  5043.8     .16       0  5437.5     .05       0
    5597      .1       0
Bank Sta=4996.9,5002.9
XS Rating Curve= 0 ,0
Exp/Cntr=0.3,0.1

Type RM Length L Ch R = 1 ,4709    ,905,905,905
BEGIN DESCRIPTION:
UNT058 IN NNOGR 11.0
END DESCRIPTION:
XS GIS Cut Line= 3
      2825609.12     10070248.02       2825038.8     10071013.66
      2825075.14       10071390.
#Sta/Elev= 30
  4375.3 1618.35  4401.3 1617.79  4407.5 1616.16  4415.9 1616.33  4422.2 1614.42
  4430.5 1614.38  4436.8  1613.2    4523 1610.83  4793.9 1605.93  4912.4 1605.84
    4981 1604.24  4987.3 1603.34  4990.5 1601.85  4993.3 1601.35  4996.5 1601.85
  5016.5 1604.52  5087.4 1607.85  5287.6 1611.71  5302.2 1614.76  5308.4    1618
  5316.8 1618.87  5326.9 1616.53  5332.6 1616.53  5350.2 1613.87  5376.9 1613.32
  5551.1  1617.5  5571.2 1617.11  5586.5 1618.37  5661.6 1620.54  5708.1 1624.19
#Mann= 4 ,-1 , 0
  4375.3     .05       0    4523     .16       0  4990.5     .07       0
  4996.5     .16       0
Bank Sta=4990.5,4996.5
XS Rating Curve= 0 ,0
Exp/Cntr=0.3,0.1

Type RM Length L Ch R = 1 ,3804    ,487,487,487
BEGIN DESCRIPTION:
UNT058 IN NNOGR 9.0
END DESCRIPTION:
XS GIS Cut Line= 3
      2825580.42     10070018.88      2824557.03     10070328.76
      2824267.96     10070797.52
#Sta/Elev= 30
  4410.4 1622.81  4422.9 1621.55  4433.3 1618.74  4446.7 1616.58  4482.6 1614.77
  4631.9 1607.62  4736.3 1603.64  4786.4 1603.06  4830.4 1601.44  4955.8 1599.81
  4987.1 1598.65  4991.4 1597.93  4994.2 1597.43  4997.4 1597.93    5008 1598.03
  5027.3 1599.47  5081.1 1599.88  5143.8 1598.84  5196.1 1599.02    5217 1600.43
  5235.3 1600.62  5240.6 1601.49  5258.8 1602.48  5344.6 1606.21  5504.3 1610.79
    5599 1614.94  5766.9 1619.94  5985.5 1629.51  5998.7 1629.54  6030.4 1631.19
#Mann= 5 ,-1 , 0
  4410.4     .05       0  4482.6     .16       0  4991.4     .07       0
  4997.4     .16       0  5985.5      .1       0
Bank Sta=4991.4,4997.4
XS Rating Curve= 0 ,0
Exp/Cntr=0.3,0.1

Type RM Length L Ch R = 1 ,3317    ,590,590,590
BEGIN DESCRIPTION:
UNT058 IN NNOGR 7.0
END DESCRIPTION:
XS GIS Cut Line= 2
      2825343.71     10069631.09      2824276.01      10069891.5
#Sta/Elev= 30
  4456.5  1612.8  4488.2 1610.76  4493.3 1611.13  4571.6 1606.28  4576.7 1606.49
  4626.6 1603.06  4654.9 1603.14  4760.4 1598.73  4811.9 1597.79  4871.1 1595.65
  4910.2  1594.3  4925.1  1594.2  4951.9 1592.89  4976.6 1592.56  4986.8 1592.09
  4990.6  1591.4  4993.3  1590.9  4996.6  1591.4  5042.5 1592.17  5058.9 1592.45
    5077 1591.93  5093.9 1592.69  5100.1 1593.19  5151.5 1594.57  5172.1 1594.74
  5213.3 1596.54  5285.4 1598.34  5373.9 1603.14  5453.1 1605.48  5555.5 1609.41
#Mann= 7 ,-1 , 0
  4456.5      .1       0  4871.1     .05       0  4990.6    .035       0
  4996.6     .05       0  5042.5      .1       0  5093.9     .05       0
  5453.1      .1       0
Bank Sta=4990.6,4996.6
XS Rating Curve= 0 ,0
Exp/Cntr=0.3,0.1

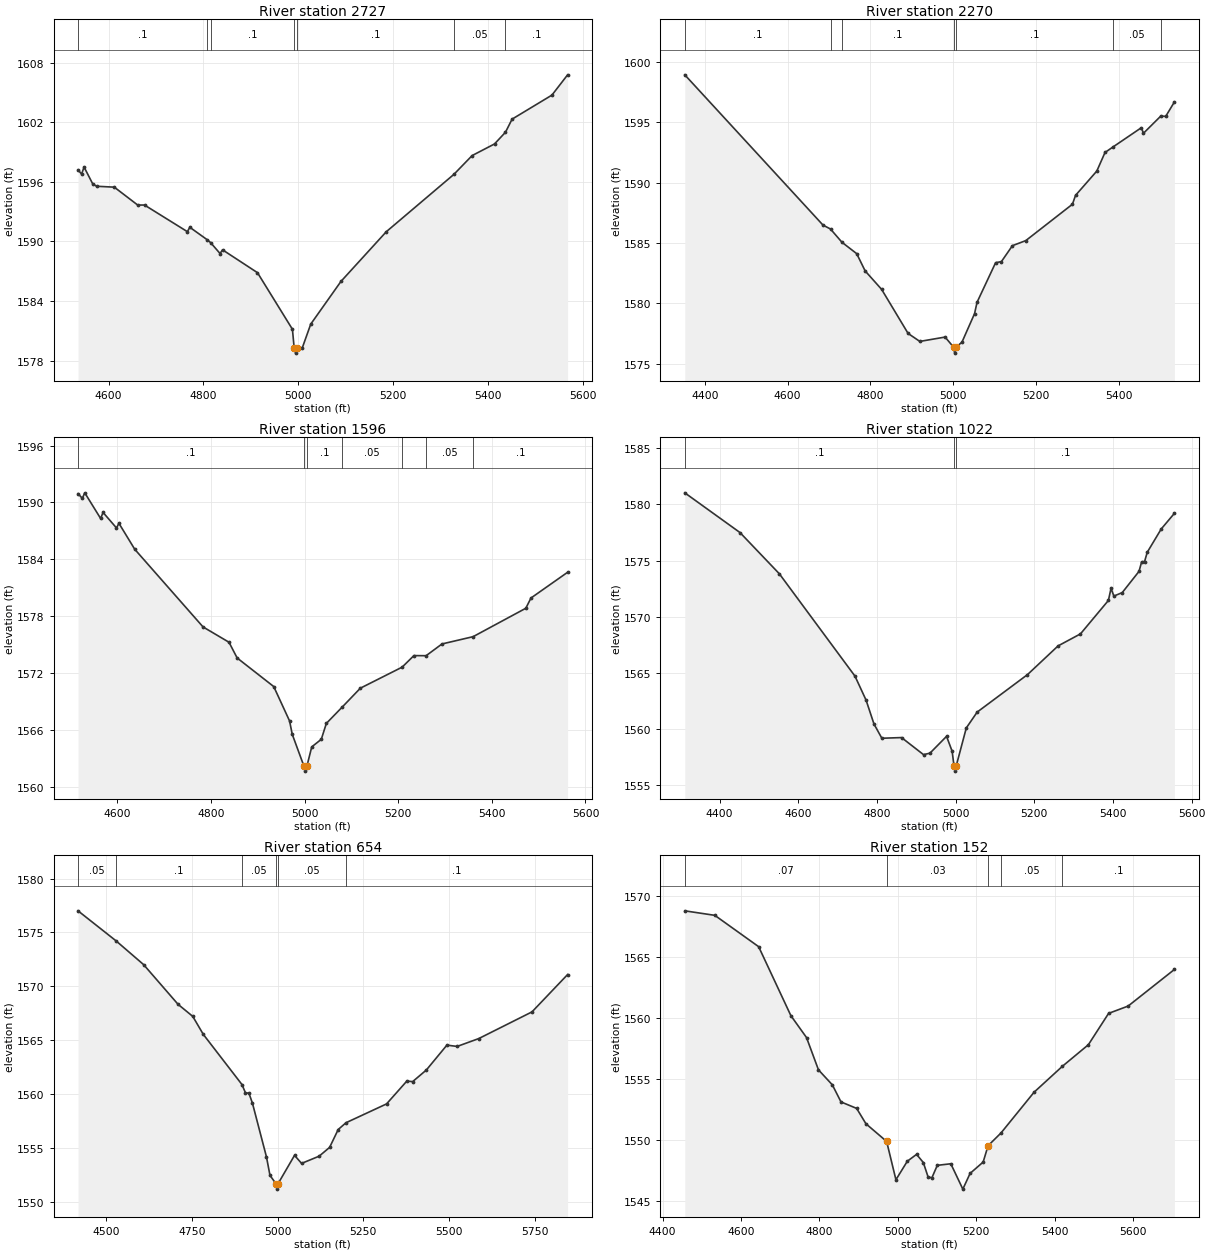
Type RM Length L Ch R = 1 ,2727    ,457,457,457
BEGIN DESCRIPTION:
UNT058 IN NNOGR 6.0
END DESCRIPTION:
XS GIS Cut Line= 2
        2825118.     10069075.54      2824137.14      10069396.7
#Sta/Elev= 30
  4535.7 1597.21  4543.2 1596.79  4548.5 1597.49  4566.8 1595.79  4575.1 1595.56
  4612.2 1595.47  4661.5 1593.67  4675.9 1593.67  4766.2 1590.99  4771.4 1591.43
  4808.5 1590.16  4815.1 1589.89  4835.1 1588.79  4840.4 1589.16    4914 1586.86
  4987.7 1581.16  4991.4 1579.26  4994.2 1578.76  4997.4 1579.26  5008.7 1579.32
  5026.3 1581.68    5090 1585.98  5185.5 1590.98  5327.9 1596.75  5366.5 1598.65
  5413.7 1599.82  5436.8    1601  5450.8 1602.32  5534.8 1604.74  5567.8 1606.78
#Mann= 7 ,-1 , 0
  4535.7      .1       0  4808.5     .05       0  4815.1      .1       0
  4991.4     .07       0  4997.4      .1       0  5327.9     .05       0
  5436.8      .1       0
Bank Sta=4991.4,4997.4
XS Rating Curve= 0 ,0
Exp/Cntr=0.3,0.1

Type RM Length L Ch R = 1 ,2270    ,674,674,674
BEGIN DESCRIPTION:
UNT058 IN NNOGR 5.0
END DESCRIPTION:
XS GIS Cut Line= 2
      2825256.91     10068893.25      2824093.72     10068684.91
#Sta/Elev= 30
  4351.8 1598.93  4685.5 1586.48  4703.5 1586.16  4731.2 1585.06  4766.7 1584.12
  4787.1 1582.69  4826.9 1581.16  4890.8 1577.51  4919.1 1576.85  4980.1 1577.21
  5000.4 1576.38  5003.2 1575.88  5006.4 1576.38  5020.7 1576.78  5051.2 1579.15
  5057.2 1580.09    5102 1583.37    5116 1583.46  5142.6 1584.78  5174.9  1585.2
  5287.4 1588.21    5295 1588.95  5346.3 1590.96  5366.1  1592.5  5384.7 1592.94
  5453.8 1594.55  5458.9 1594.09  5500.6 1595.51  5512.6 1595.49  5533.5 1596.68
#Mann= 7 ,-1 , 0
  4351.8      .1       0  4703.5     .05       0  4731.2      .1       0
  5000.4     .07       0  5006.4      .1       0  5384.7     .05       0
  5500.6      .1       0
Bank Sta=5000.4,5006.4
XS Rating Curve= 0 ,0
Exp/Cntr=0.3,0.1

Type RM Length L Ch R = 1 ,1596    ,574,574,574
BEGIN DESCRIPTION:
UNT058 IN NNOGR 3.0
END DESCRIPTION:
XS GIS Cut Line= 2
      2825178.78     10068025.19       2824172.6     10068311.43
#Sta/Elev= 30
  4515.7 1590.93  4524.9 1590.44  4530.1 1591.02    4564 1588.31  4569.2 1588.95
  4597.9 1587.31  4603.1  1587.8  4636.9 1585.06  4782.8 1576.86  4838.3 1575.24
  4855.7 1573.58  4933.9 1570.56  4967.7 1566.93  4973.5 1565.51  4998.6 1562.13
  5001.4 1561.63  5004.6 1562.13  5015.1 1564.19  5035.5 1564.99  5046.3 1566.67
  5080.7 1568.42    5119 1570.39  5208.2 1572.61  5233.4 1573.83  5259.5 1573.82
  5293.4 1575.06  5359.9 1575.83  5472.5 1578.83  5483.5 1579.91  5561.8 1582.63
#Mann= 7 ,-1 , 0
  4515.7      .1       0  4998.6     .07       0  5004.6      .1       0
  5080.7     .05       0  5208.2      .1       0  5259.5     .05       0
  5359.9      .1       0
Bank Sta=4998.6,5004.6
XS Rating Curve= 0 ,0
Exp/Cntr=0.3,0.1

Type RM Length L Ch R = 1 ,1022    ,368,368,368
BEGIN DESCRIPTION:
UNT058 IN NNOGR 2.0
END DESCRIPTION:
XS GIS Cut Line= 3
      2825048.59     10067634.56      2824432.25     10067669.29
      2823963.49     10068085.96
#Sta/Elev= 30
  4311.6 1581.04  4451.9  1577.5  4552.1 1573.82  4744.3  1564.7  4772.5 1562.56
  4792.5 1560.44  4812.5 1559.17  4862.6 1559.23  4918.4 1557.71  4934.8 1557.84
    4977 1559.34  4991.2 1558.01  4995.8 1556.74  4998.5 1556.24  5001.8 1556.74
  5027.2 1560.09  5054.8  1561.5  5182.7 1564.84  5260.5  1567.4  5317.4 1568.47
  5388.4 1571.45  5395.1 1572.53  5402.3 1571.84  5423.6 1572.15  5466.2 1574.04
  5472.9 1574.89  5480.4 1574.92  5487.1 1575.74  5522.7 1577.82  5556.1 1579.21
#Mann= 3 ,-1 , 0
  4311.6      .1       0  4995.8     .07       0  5001.8      .1       0
Bank Sta=4995.8,5001.8
XS Rating Curve= 0 ,0
Exp/Cntr=0.3,0.1

Type RM Length L Ch R = 1 ,654     ,502,502,502
BEGIN DESCRIPTION:
Mapping XS fb00ef3c
END DESCRIPTION:
XS GIS Cut Line= 3
      2824955.47     10067235.01      2824012.76     10067443.35
      2823846.08     10067875.68
#Sta/Elev= 30
  4417.6 1577.01  4528.2 1574.23  4609.1 1572.01  4709.6 1568.32  4752.5  1567.2
  4783.2 1565.53    4896 1560.87  4906.1 1560.11  4916.4 1560.06  4926.6 1559.14
  4967.6 1554.14  4977.8 1552.43  4995.3 1551.65    4998 1551.15  5001.3 1551.65
  5049.5 1554.29    5070 1553.54  5121.2 1554.21  5151.9 1555.03  5176.9 1556.69
  5199.7 1557.32  5318.1 1559.07  5377.2 1561.19  5394.2 1561.14  5434.2 1562.22
  5494.1 1564.53  5524.1 1564.41  5587.1 1565.14  5742.5 1567.62  5846.4 1571.09
#Mann= 6 ,-1 , 0
  4417.6     .05       0  4528.2      .1       0    4896     .05       0
  4995.3     .04       0  5001.3     .05       0  5199.7      .1       0
Bank Sta=4995.3,5001.3
XS Rating Curve= 0 ,0
Exp/Cntr=0.3,0.1

Type RM Length L Ch R = 1 ,152     ,0,0,0
BEGIN DESCRIPTION:
UNT058 IN NNOGR 1.0
END DESCRIPTION:
XS GIS Cut Line= 4
      2824723.74     10066917.31      2824330.47     10066844.39
      2824090.88     10066945.95      2823945.04      10067516.3
#Sta/Elev= 30
  4456.5 1568.76  4533.1 1568.39  4644.9 1565.82  4727.2 1560.16    4767 1558.37
  4797.5 1555.72  4832.9 1554.49    4855 1553.09  4894.9 1552.56  4918.6  1551.3
  4971.4 1549.85  4995.1 1546.71  5024.2 1548.23  5047.8 1548.79    5065 1548.12
  5076.9 1546.96  5086.7 1546.86  5100.6 1547.89  5135.1 1548.02  5165.8 1545.94
  5184.3 1547.23  5217.6 1548.16  5230.2  1549.5    5263 1550.54  5347.6 1553.89
    5420 1556.02    5486 1557.78  5537.6 1560.35  5587.4 1560.95  5705.4 1563.95
#Mann= 5 ,-1 , 0
  4456.5     .07       0  4971.4     .03       0  5230.2     .07       0
    5263     .05       0    5420      .1       0
Bank Sta=4971.4,5230.2
XS Rating Curve= 0 ,0
Exp/Cntr=0.3,0.1

Chan Stop Cuts=-1
Use User Specified Reach Order=0
Composite Channel Slope=5