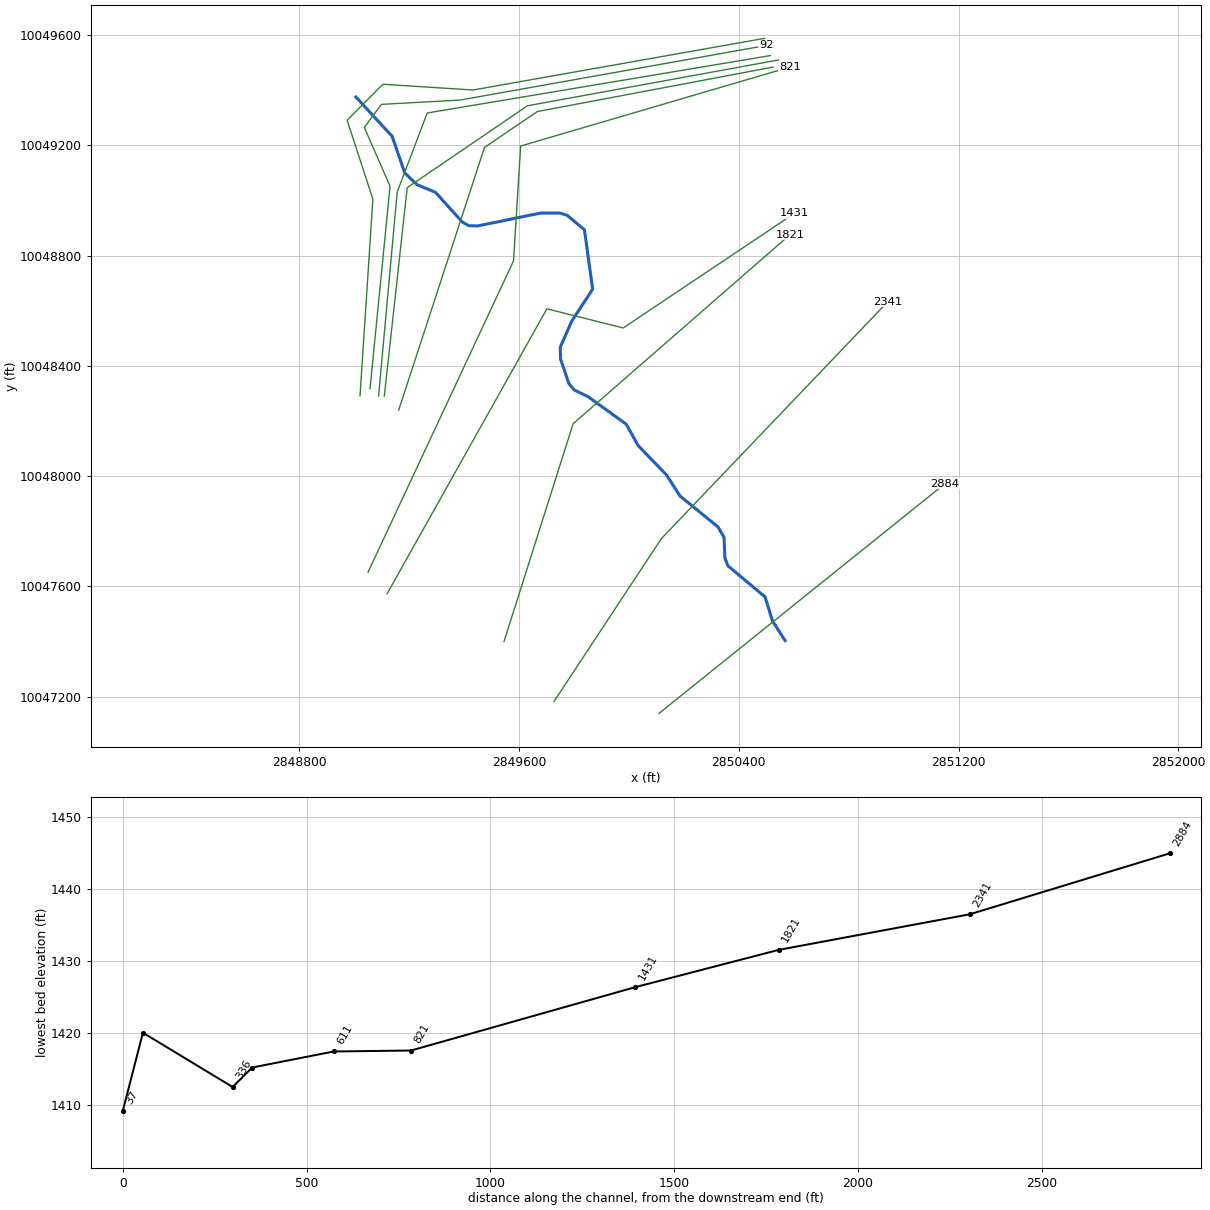
--- UNT058 IN SNOGR.prj (project) ---

Proj Title=UNT058 IN SNOGR Base Level Engineering
Current Plan=p01
Default Exp/Contr=0.3,0.1
English Units
Geom File=g01
Flow File=f01
Plan File=p01
Y Axis Title=Elevation
X Axis Title(PF)=Main Channel Distance
X Axis Title(XS)=Station
BEGIN DESCRIPTION:
UNT058 IN SNOGR
END DESCRIPTION:
DSS Export Rating Curves= 0
DSS Export Rating Curve Sorted= 0
DSS Export Volume Flow Curves= 0
DXF OffsetX= 0
DXF OffsetY= 0
DXF ScaleX= 1
DXF ScaleY= 10

--- UNT058 IN SNOGR.p01 (plan) ---

Plan Title=Multiple Run
Short Identifier=Multiple
Geom File=g01
Flow File=f01
Subcritical Flow
K Sum by GR= 0
Std Step Tol= 0.01
Critical Tol= 0.01
Num of Std Step Trials= 20
Max Error Tol= 0.3
Flow Tol Ratio= 0.001
Split Flow NTrial= 30
Split Flow Tol= 0.02
Split Flow Ratio= 0.02
Log Output Level= 0
Friction Slope Method= 1
Unsteady Friction Slope Method= 2
Unsteady Bridges Friction Slope Method= 1
Parabolic Critical Depth
Global Vel Dist=  1 , 1 , 1
Global Log Level= 0
CheckData=True
Encroach Param= -1, 0, 0, 0
BEGIN DESCRIPTION:
Multiple Run
END DESCRIPTION:

--- UNT058 IN SNOGR.f01 (steady flow) ---

Flow Title=Multiple
Program Version=4.10
Number of Profiles= 7
Profile Names=10-year,25-year,50-year,1pct_min,100-year,1pct_plu,500-year
River Rch & RM=UNT058 IN SNOGR,Reach-1         ,2884
     873    1262    1598    1481    2003    2709    3160
River Rch & RM=UNT058 IN SNOGR,Reach-1         ,37
    7056   11011   14684   14239   19256   26042   33253
Boundary for River Rch & Prof#=UNT058 IN SNOGR,Reach-1         , 1
Up Type= 0
Dn Type= 3
Dn Slope=0.27581
Boundary for River Rch & Prof#=UNT058 IN SNOGR,Reach-1         , 2
Up Type= 0
Dn Type= 3
Dn Slope=0.27581
Boundary for River Rch & Prof#=UNT058 IN SNOGR,Reach-1         , 3
Up Type= 0
Dn Type= 3
Dn Slope=0.27581
Boundary for River Rch & Prof#=UNT058 IN SNOGR,Reach-1         , 4
Up Type= 0
Dn Type= 3
Dn Slope=0.27581
Boundary for River Rch & Prof#=UNT058 IN SNOGR,Reach-1         , 5
Up Type= 0
Dn Type= 3
Dn Slope=0.27581
Boundary for River Rch & Prof#=UNT058 IN SNOGR,Reach-1         , 6
Up Type= 0
Dn Type= 3
Dn Slope=0.27581
Boundary for River Rch & Prof#=UNT058 IN SNOGR,Reach-1         , 7
Up Type= 0
Dn Type= 3
Dn Slope=0.27581
DSS Import GetInterval= 0
DSS Import GetPeak= 0
DSS Import FillOption= 0

--- UNT058 IN SNOGR.g01 (geometry) ---

Geom Title=Existing Conditions
Program Version=4.10

River Reach=UNT058 IN SNOGR ,Reach-1
Reach XY= 30
      2850568.47     10047403.73      2850522.39     10047475.43
      2850495.88     10047561.95      2850360.67     10047674.51
      2850349.48     10047703.55      2850346.27     10047778.15
       2850323.8     10047816.32      2850186.26     10047927.82
      2850137.05     10048003.96      2850033.61      10048110.9
      2849990.16     10048188.45      2849850.94     10048288.49
      2849802.14     10048311.76      2849781.65     10048334.86
      2849751.03     10048425.02      2849750.08     10048467.87
      2849791.98     10048562.27      2849868.02     10048678.07
      2849837.95     10048893.63      2849774.75     10048945.96
      2849749.09     10048953.66      2849678.68     10048953.99
      2849449.54      10048907.3      2849417.23     10048907.95
      2849393.11     10048921.72      2849295.96     10049028.88
      2849228.43     10049057.23      2849184.17     10049098.88
      2849137.74      10049232.7      2849005.95     10049374.77

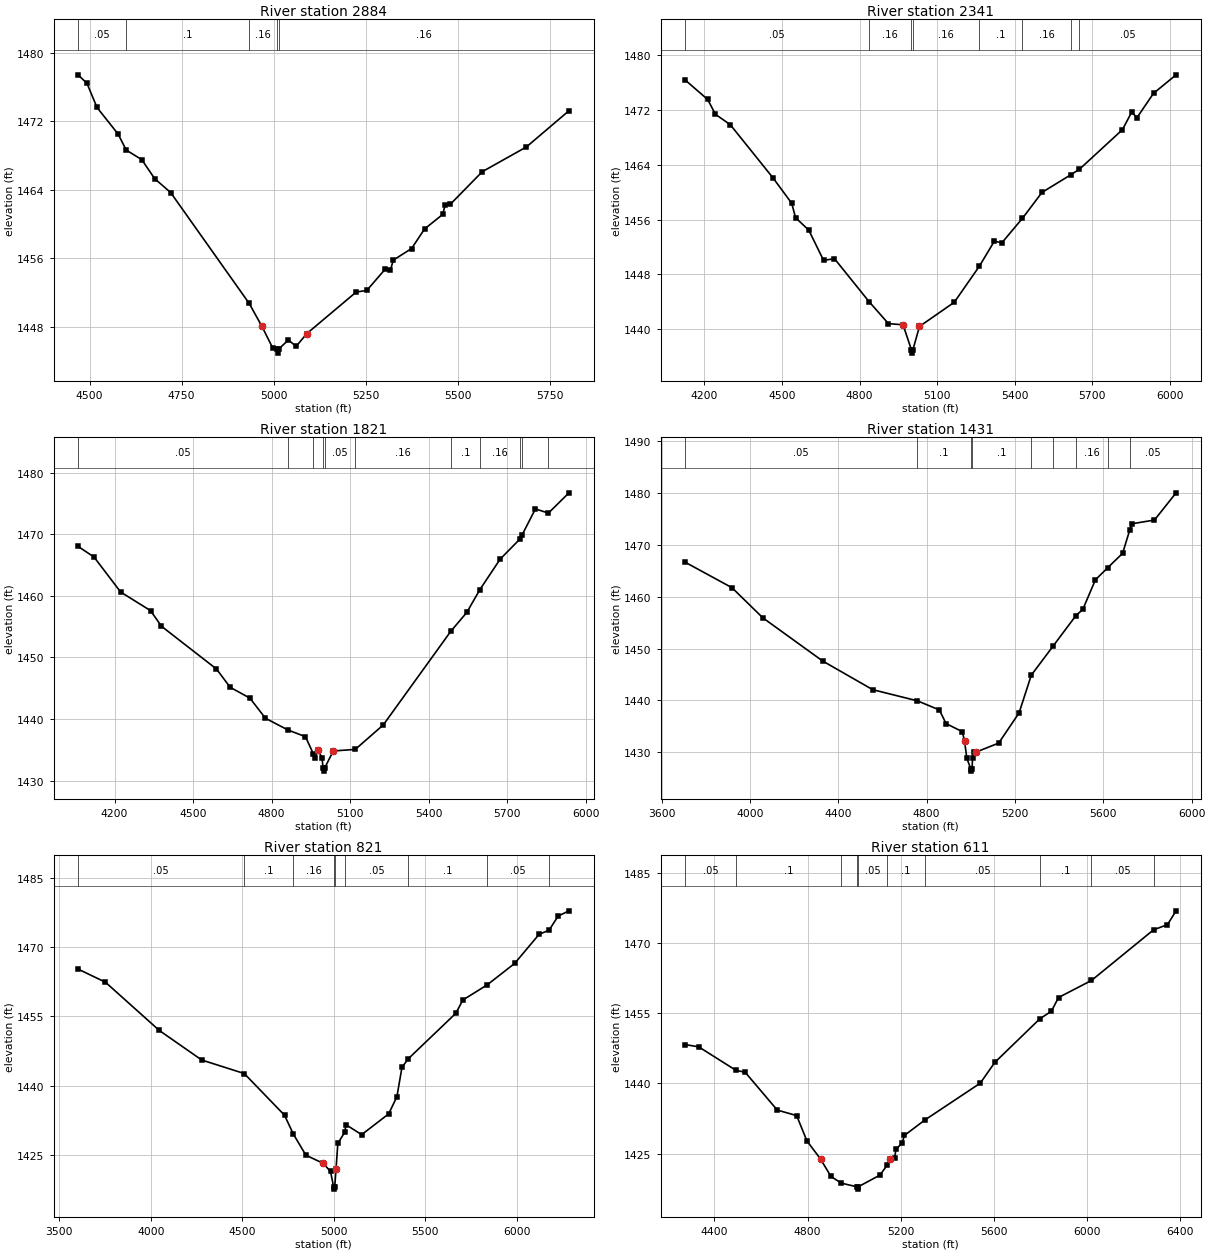
Type RM Length L Ch R = 1 ,2884    ,543,543,543
BEGIN DESCRIPTION:
UNT058 IN SNOGR 6.0
END DESCRIPTION:
XS GIS Cut Line= 2
      2850109.44     10047139.76      2851151.12      10047973.1
#Sta/Elev= 30
  4468.7 1477.41  4492.9 1476.41  4520.1  1473.6  4577.7 1470.48  4599.4 1468.63
  4641.7 1467.51    4677 1465.28  4720.2 1463.67  4933.7 1450.72  4968.3 1448.04
  4997.1 1445.56  5008.5 1445.42  5011.3 1444.92  5014.5 1445.42  5040.3 1446.46
  5061.1  1445.7    5090 1447.19  5224.4 1452.05  5253.2 1452.24  5302.9  1454.7
  5317.3 1454.59  5325.3 1455.78  5374.9 1457.13  5410.1 1459.41  5459.7 1461.12
  5466.3 1462.26  5480.5 1462.31    5567  1466.1    5687 1468.99  5802.7 1473.22
#Mann= 5 ,-1 , 0
  4468.7     .05       0  4599.4      .1       0  4933.7     .16       0
  5008.5     .07       0  5014.5     .16       0
Bank Sta=4968.3,5090
XS Rating Curve= 0 ,0
Exp/Cntr=0.3,0.1

Type RM Length L Ch R = 1 ,2341    ,520,520,520
BEGIN DESCRIPTION:
UNT058 IN SNOGR 5.0
END DESCRIPTION:
XS GIS Cut Line= 3
      2849727.47     10047183.12      2850118.11     10047773.43
      2850942.77      10048632.8
#Sta/Elev= 30
  4125.6 1476.38  4212.6 1473.54  4242.7 1471.37  4299.9 1469.86  4465.4 1462.08
  4537.6 1458.38  4552.6 1456.27  4603.8 1454.44    4661 1450.03  4703.1 1450.28
  4836.9    1444  4911.8 1440.79  4968.4 1440.62  5000.6 1436.98  5003.3 1436.48
  5006.6 1436.98  5031.9 1440.38  5166.5 1443.91  5262.9 1449.14  5321.8 1452.85
  5350.2 1452.58  5430.1 1456.17  5505.8 1459.96  5617.7 1462.55  5650.8 1463.35
  5817.1 1469.13  5852.4 1471.67  5873.5  1470.9  5937.3 1474.44  6024.5 1477.14
#Mann= 8 ,-1 , 0
  4125.6     .05       0  4836.9     .16       0  5000.6     .07       0
  5006.6     .16       0  5262.9      .1       0  5430.1     .16       0
  5617.7      .1       0  5650.8     .05       0
Bank Sta=4968.4,5031.9
XS Rating Curve= 0 ,0
Exp/Cntr=0.3,0.1

Type RM Length L Ch R = 1 ,1821    ,390,390,390
BEGIN DESCRIPTION:
UNT058 IN SNOGR 4.0
END DESCRIPTION:
XS GIS Cut Line= 3
       2849545.2     10047400.19      2849796.93     10048190.09
      2850586.85     10048875.85
#Sta/Elev= 30
  4060.7 1468.02  4121.5  1466.3  4223.4 1460.61  4337.3  1457.6  4379.2 1455.06
  4589.2 1448.12  4641.7 1445.15    4717 1443.39  4776.2 1440.13  4861.2 1438.24
  4929.2 1437.13  4959.1 1434.37  4964.3 1433.67  4978.5 1434.94  4992.8  1433.6
  4996.4 1432.04  4999.1 1431.54  5002.4 1432.04  5035.5 1434.81  5119.5 1435.07
  5226.4 1439.04  5484.5 1454.25  5545.4  1457.3    5595 1460.98  5673.1 1465.97
  5749.2 1469.25  5757.3 1469.93  5807.5 1474.11  5857.1 1473.43  5935.8 1476.72
#Mann= 11 ,-1 , 0
  4060.7     .05       0  4861.2      .1       0  4959.1     .05       0
  4996.4    .035       0  5002.4     .05       0  5119.5     .16       0
  5484.5      .1       0    5595     .16       0  5749.2     .05       0
  5757.3      .1       0  5857.1     .05       0
Bank Sta=4978.5,5035.5
XS Rating Curve= 0 ,0
Exp/Cntr=0.3,0.1

Type RM Length L Ch R = 1 ,1431    ,610,610,610
BEGIN DESCRIPTION:
UNT058 IN SNOGR 3.0
END DESCRIPTION:
XS GIS Cut Line= 4
      2849119.83     10047573.74      2849701.44     10048606.76
      2849979.22     10048537.31      2850603.83     10048953.72
#Sta/Elev= 30
  3707.1 1466.67  3918.9 1461.76  4059.1 1455.93  4329.3 1447.62  4556.3 1442.08
  4758.6 1439.93  4858.2 1438.17    4888 1435.54  4961.7 1433.99    4972 1432.15
  4982.3 1428.82  4999.9 1426.87  5002.7 1426.37  5005.9 1426.87  5008.1 1428.82
  5013.3 1430.03  5023.5 1430.04  5126.6 1431.78  5218.8 1437.61    5274 1444.88
  5371.7 1450.43  5476.1 1456.38  5507.2 1457.56  5564.3 1463.28  5619.8  1465.6
  5687.5 1468.39  5720.5 1472.98  5730.9  1474.1  5831.7 1474.81  5929.6 1480.06
#Mann= 9 ,-1 , 0
  3707.1     .05       0  4758.6      .1       0  4999.9     .07       0
  5005.9      .1       0    5274     .16       0  5371.7      .1       0
  5476.1     .16       0  5619.8      .1       0  5720.5     .05       0
Bank Sta=4972,5023.5
XS Rating Curve= 0 ,0
Exp/Cntr=0.3,0.1

Type RM Length L Ch R = 1 ,821     ,210,210,210
BEGIN DESCRIPTION:
UNT058 IN SNOGR 2.0
END DESCRIPTION:
XS GIS Cut Line= 4
      2849050.39     10047651.88      2849579.92     10048780.37
      2849605.96     10049197.04      2850585.13     10049482.99
#Sta/Elev= 30
  3602.2 1465.21    3752 1462.36  4046.1 1451.93  4278.1 1445.53  4510.8  1442.6
    4731 1433.57  4779.2 1429.49  4847.8 1424.92  4942.3 1423.17  4982.4  1421.4
  4999.4 1418.08  5002.2 1417.58  5005.4 1418.08  5012.4 1421.87  5022.4 1427.47
  5060.6 1429.93  5066.8 1431.53  5152.7 1429.37  5300.1 1433.86  5345.3 1437.57
    5373 1443.93  5408.1 1445.82  5667.3 1455.63  5706.4 1458.53  5839.1 1461.79
  5989.3 1466.44  6123.1 1472.74  6177.3 1473.63  6227.3 1476.69  6286.3 1477.82
#Mann= 9 ,-1 , 0
  3602.2     .05       0  4510.8      .1       0  4779.2     .16       0
  4999.4     .07       0  5005.4     .16       0  5060.6     .05       0
  5408.1      .1       0  5839.1     .05       0  6177.3      .1       0
Bank Sta=4942.3,5012.4
XS Rating Curve= 0 ,0
Exp/Cntr=0.3,0.1

Type RM Length L Ch R = 1 ,611     ,222,222,222
BEGIN DESCRIPTION:
Mapping XS 623fe4bb
END DESCRIPTION:
XS GIS Cut Line= 4
      2849161.62     10048238.68      2849474.11     10049191.79
      2849666.82       10049322.       2850524.8      10049483.2
#Sta/Elev= 30
  4274.4 1448.29  4332.3 1447.82  4492.2 1442.81  4532.1 1442.39  4669.9 1434.32
  4753.3 1433.14  4797.3 1427.74  4855.7 1423.88  4900.6 1420.15  4945.4 1418.72
  5011.8 1417.95  5014.6 1417.45  5017.8 1417.95  5110.4 1420.43    5143 1422.61
  5153.2 1423.88    5174 1424.02  5179.3 1425.91  5205.8 1427.27  5216.4 1428.92
  5304.4 1432.22  5541.8 1440.06  5604.5  1444.5  5797.9  1453.8  5847.5 1455.42
    5878 1458.34  6019.6 1461.98  6286.3 1472.79    6346 1473.89    6383 1476.84
#Mann= 10 ,-1 , 0
  4274.4     .05       0  4492.2      .1       0  4945.4     .05       0
  5011.8    .033       0  5017.8     .05       0    5143      .1       0
  5304.4     .05       0  5797.9      .1       0  6019.6     .05       0
  6286.3      .1       0
Bank Sta=4855.7,5153.2
XS Rating Curve= 0 ,0
Exp/Cntr=0.3,0.1

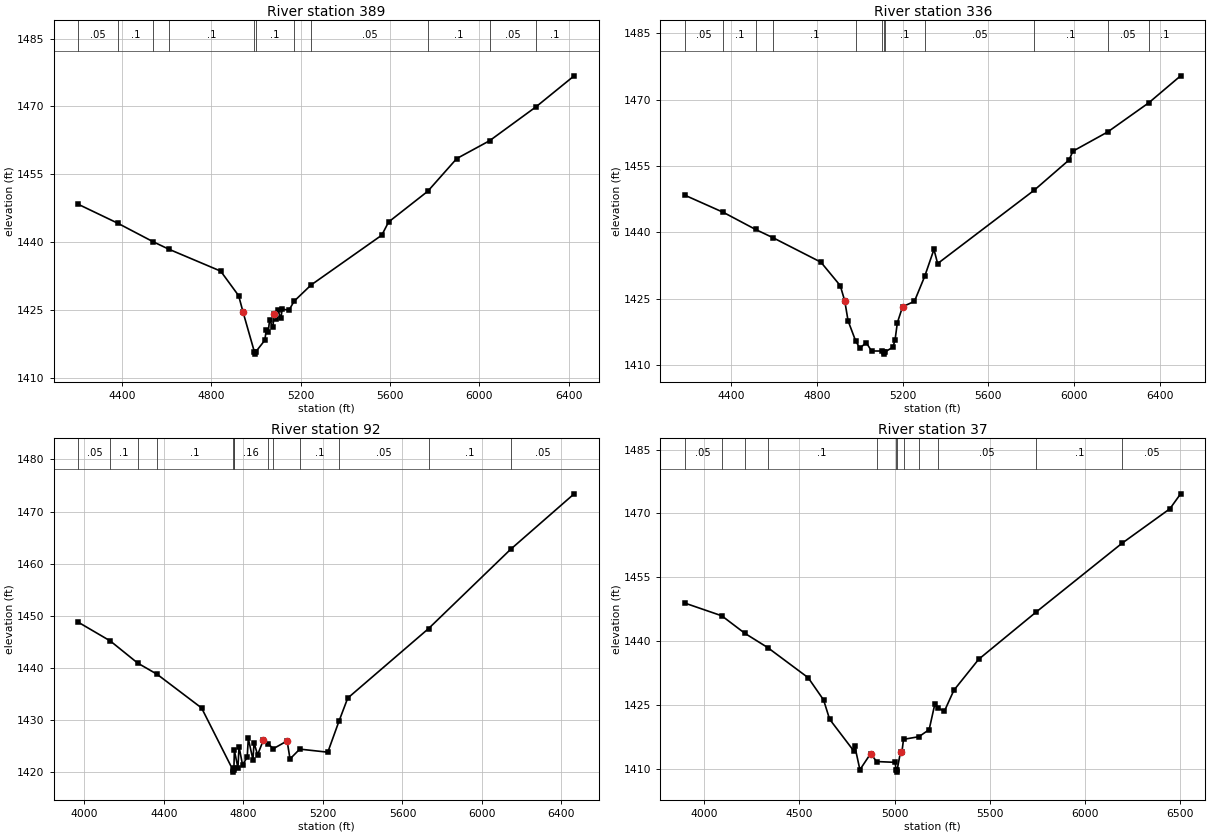
Type RM Length L Ch R = 1 ,389     ,53,53,53
BEGIN DESCRIPTION:
Mapping XS 2599f902
END DESCRIPTION:
XS GIS Cut Line= 4
      2849109.53     10048290.75      2849192.86     10049045.96
      2849630.36     10049342.83      2850545.26     10049509.18
#Sta/Elev= 30
  4205.3 1448.35  4381.4 1444.18  4540.9 1440.05  4610.5 1438.42  4842.1 1433.58
  4922.6 1428.14  4942.7 1424.44    4993 1415.72  4995.8 1415.22    4999 1415.72
  5039.8  1418.3  5045.8 1420.53  5054.7 1420.01  5060.8 1422.71  5075.7 1421.21
  5081.8 1424.06  5090.7  1422.9  5096.7  1424.9  5111.7 1423.29  5117.7 1425.18
  5147.6 1424.92  5170.9 1426.93  5246.3  1430.5    5563 1441.53  5593.5 1444.45
  5768.5 1451.23  5898.4 1458.47  6045.1 1462.41  6253.2 1469.92  6423.7 1476.77
#Mann= 11 ,-1 , 0
  4205.3     .05       0  4381.4      .1       0  4540.9     .05       0
  4610.5      .1       0    4993    .033       0    4999      .1       0
  5170.9      .1       0  5246.3     .05       0  5768.5      .1       0
  6045.1     .05       0  6253.2      .1       0
Bank Sta=4942.7,5081.8
XS Rating Curve= 0 ,0
Exp/Cntr=0.3,0.1

Type RM Length L Ch R = 1 ,336     ,244,244,244
BEGIN DESCRIPTION:
Mapping XS 807661e1
END DESCRIPTION:
XS GIS Cut Line= 4
       2849088.7     10048290.77       2849156.4     10049030.33
      2849265.78     10049316.79      2850514.67     10049524.94
#Sta/Elev= 30
  4182.3 1448.42  4362.8 1444.53  4512.5 1440.69  4595.2 1438.79  4817.9 1433.29
  4908.3 1427.99  4929.4 1424.51  4944.7 1420.05  4979.5 1415.58  4999.5 1413.86
  5029.6 1415.12  5054.3 1413.23  5101.2 1413.22  5111.4 1413.02  5114.2 1412.52
  5117.4 1413.02  5153.4 1414.07  5163.9 1415.62  5174.8  1419.6  5199.3 1423.23
  5254.6 1424.44  5302.7  1430.1  5345.8 1436.17    5363 1432.97  5814.1 1449.55
  5976.4 1456.36  5994.7 1458.36  6156.7 1462.69  6349.3  1469.3  6497.7 1475.38
#Mann= 12 ,-1 , 0
  4182.3     .05       0  4362.8      .1       0  4512.5     .05       0
  4595.2      .1       0  4979.5     .05       0  5101.2      .1       0
  5111.4    .033       0  5117.4      .1       0  5302.7     .05       0
  5814.1      .1       0  6156.7     .05       0  6349.3      .1       0
Bank Sta=4929.4,5199.3
XS Rating Curve= 0 ,0
Exp/Cntr=0.3,0.1

Type RM Length L Ch R = 1 ,92      ,55,55,55
BEGIN DESCRIPTION:
Mapping XS dea8e8d0
END DESCRIPTION:
XS GIS Cut Line= 6
      2849057.44     10048316.77      2849130.36     10049051.17
      2849036.61     10049264.71      2849099.11     10049348.04
      2849385.57     10049363.67      2850500.16     10049561.58
#Sta/Elev= 30
  3969.5 1448.78  4130.4 1445.19  4268.2 1440.95  4365.7 1438.81  4589.5 1432.35
    4746 1420.55  4748.8 1420.05    4752 1420.55  4752.2 1420.84  4754.5 1424.23
  4772.4 1420.82  4777.9 1424.95  4795.8  1421.4  4819.1 1422.95  4824.6 1426.51
  4847.9 1422.42  4853.4 1425.68  4871.3 1423.36  4900.1 1426.17  4924.1 1425.48
  4950.3 1424.54  5019.8 1426.03  5034.4 1422.58  5083.5 1424.46  5224.5 1423.87
  5280.6  1429.8  5324.7 1434.24  5731.4 1447.57  6144.4 1462.77  6463.8  1473.4
#Mann= 13 ,-1 , 0
  3969.5     .05       0  4130.4      .1       0  4268.2     .05       0
  4365.7      .1       0    4746     .07       0    4752      .1       0
  4752.2     .16       0  4924.1      .1       0  4950.3     .16       0
  5083.5      .1       0  5280.6     .05       0  5731.4      .1       0
  6144.4     .05       0
Bank Sta=4900.1,5019.8
XS Rating Curve= 0 ,0
Exp/Cntr=0.3,0.1

Type RM Length L Ch R = 1 ,37      ,0,0,0
BEGIN DESCRIPTION:
UNT058 IN SNOGR 1.0
END DESCRIPTION:
XS GIS Cut Line= 6
      2849020.99     10048290.74      2849067.86     10049004.29
      2848974.11     10049290.75      2849104.32     10049420.96
      2849432.45     10049400.12      2850494.21     10049587.49
#Sta/Elev= 30
  3896.8 1448.91  4091.2 1445.92  4212.9 1441.79  4332.4 1438.46  4545.5 1431.37
  4626.6 1426.14  4658.4  1421.6  4785.8 1414.12  4791.1 1415.21  4817.7 1409.72
  4874.4 1413.53  4905.1 1411.65  5003.3 1411.46  5007.4 1409.66  5010.2 1409.16
  5013.4 1409.66  5031.6 1413.99  5038.7 1413.89    5047 1416.87  5127.9 1417.49
  5181.8 1419.15  5211.8 1425.17    5227 1424.28  5261.9 1423.47    5312 1428.42
  5442.5  1435.7  5746.2 1446.86  6196.9    1463  6447.8 1471.08  6504.4  1474.6
#Mann= 12 ,-1 , 0
  3896.8     .05       0  4091.2      .1       0  4212.9     .05       0
  4332.4      .1       0  4905.1     .16       0  5007.4     .07       0
  5013.4     .16       0    5047      .1       0  5127.9     .16       0
    5227     .05       0  5746.2      .1       0  6196.9     .05       0
Bank Sta=4874.4,5031.6
XS Rating Curve= 0 ,0
Exp/Cntr=0.3,0.1

Chan Stop Cuts=-1
Use User Specified Reach Order=0
Composite Channel Slope=5