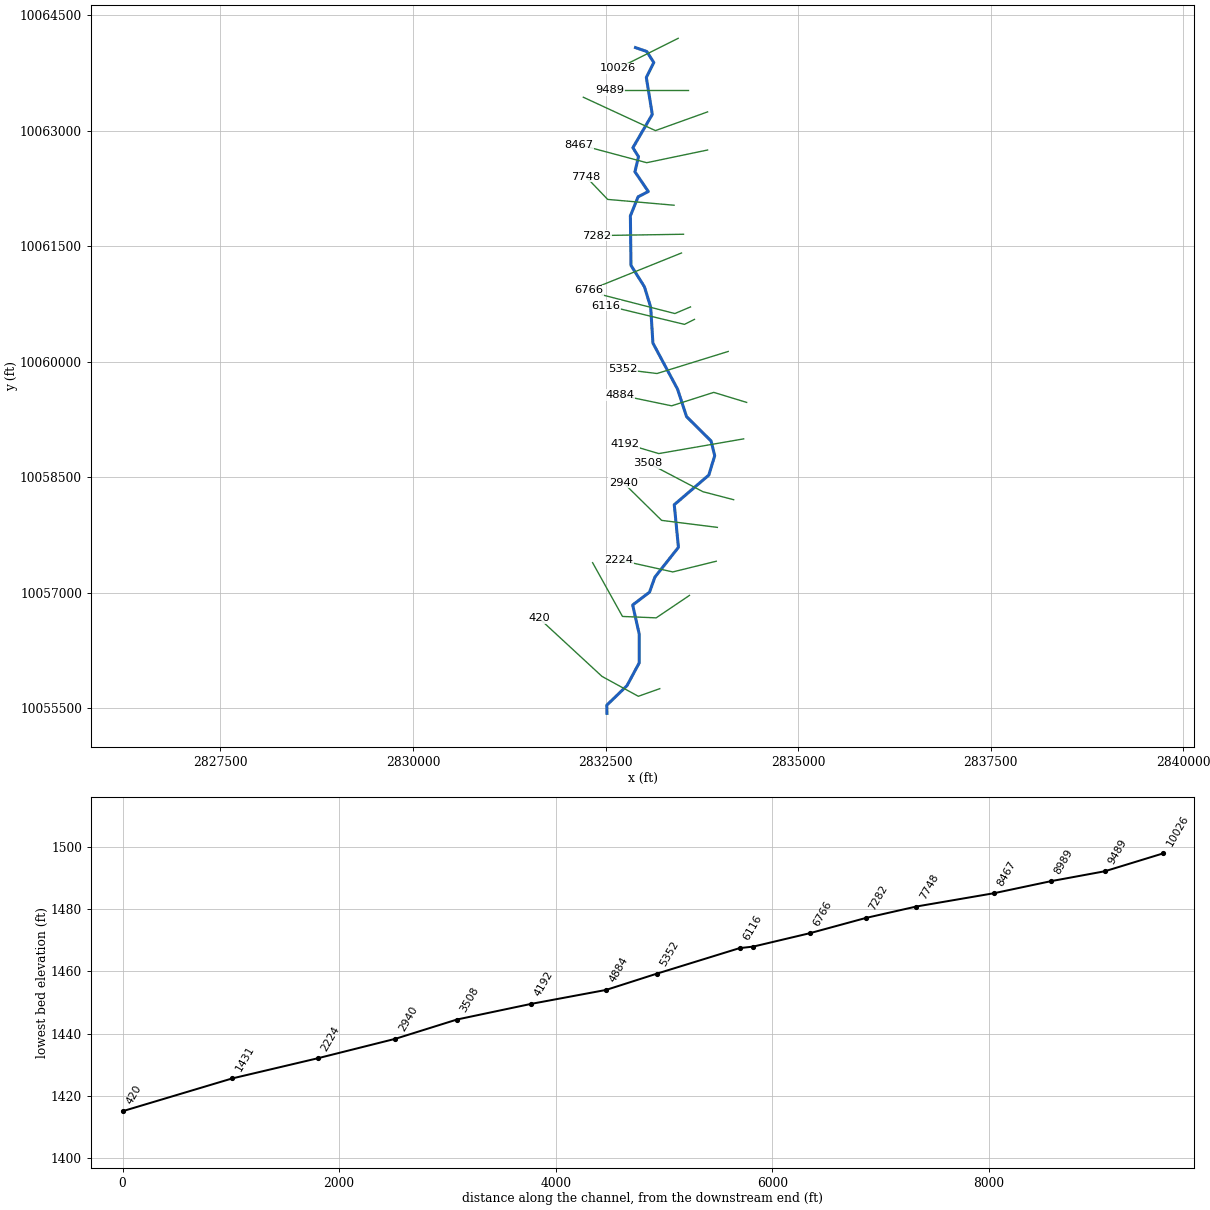
--- UNT059 IN NNOGR.prj (project) ---

Proj Title=UNT059 IN NNOGR Base Level Engineering
Current Plan=p01
Default Exp/Contr=0.3,0.1
English Units
Geom File=g01
Flow File=f01
Plan File=p01
Y Axis Title=Elevation
X Axis Title(PF)=Main Channel Distance
X Axis Title(XS)=Station
BEGIN DESCRIPTION:
UNT059 IN NNOGR
END DESCRIPTION:
DSS Export Rating Curves= 0
DSS Export Rating Curve Sorted= 0
DSS Export Volume Flow Curves= 0
DXF OffsetX= 0
DXF OffsetY= 0
DXF ScaleX= 1
DXF ScaleY= 10

--- UNT059 IN NNOGR.p01 (plan) ---

Plan Title=Multiple Run
Short Identifier=Multiple
Geom File=g01
Flow File=f01
Subcritical Flow
K Sum by GR= 0
Std Step Tol= 0.01
Critical Tol= 0.01
Num of Std Step Trials= 20
Max Error Tol= 0.3
Flow Tol Ratio= 0.001
Split Flow NTrial= 30
Split Flow Tol= 0.02
Split Flow Ratio= 0.02
Log Output Level= 0
Friction Slope Method= 1
Unsteady Friction Slope Method= 2
Unsteady Bridges Friction Slope Method= 1
Parabolic Critical Depth
Global Vel Dist=  1 , 1 , 1
Global Log Level= 0
CheckData=True
Encroach Param= -1, 0, 0, 0
BEGIN DESCRIPTION:
Multiple Run
END DESCRIPTION:

--- UNT059 IN NNOGR.f01 (steady flow) ---

Flow Title=Multiple
Program Version=4.10
Number of Profiles= 7
Profile Names=10-year,25-year,50-year,1pct_min,100-year,1pct_plu,500-year
River Rch & RM=UNT059 IN NNOGR,Reach-1         ,10026
     767    1100    1387    1281    1732    2342    2709
River Rch & RM=UNT059 IN NNOGR,Reach-1         ,8989
    1074    1563    1987    1848    2499    3380    3969
River Rch & RM=UNT059 IN NNOGR,Reach-1         ,1431
    1418    2091    2684    2517    3404    4604    5499
Boundary for River Rch & Prof#=UNT059 IN NNOGR,Reach-1         , 1
Up Type= 0
Dn Type= 3
Dn Slope=0.0095
Boundary for River Rch & Prof#=UNT059 IN NNOGR,Reach-1         , 2
Up Type= 0
Dn Type= 3
Dn Slope=0.0095
Boundary for River Rch & Prof#=UNT059 IN NNOGR,Reach-1         , 3
Up Type= 0
Dn Type= 3
Dn Slope=0.0095
Boundary for River Rch & Prof#=UNT059 IN NNOGR,Reach-1         , 4
Up Type= 0
Dn Type= 3
Dn Slope=0.0095
Boundary for River Rch & Prof#=UNT059 IN NNOGR,Reach-1         , 5
Up Type= 0
Dn Type= 3
Dn Slope=0.0095
Boundary for River Rch & Prof#=UNT059 IN NNOGR,Reach-1         , 6
Up Type= 0
Dn Type= 3
Dn Slope=0.0095
Boundary for River Rch & Prof#=UNT059 IN NNOGR,Reach-1         , 7
Up Type= 0
Dn Type= 3
Dn Slope=0.0095
DSS Import GetInterval= 0
DSS Import GetPeak= 0
DSS Import FillOption= 0

--- UNT059 IN NNOGR.g01 (geometry) ---

Geom Title=Existing Conditions
Program Version=4.10

River Reach=UNT059 IN NNOGR ,Reach-1
Reach XY= 30
      2832888.72     10064076.94      2833034.82     10064026.26
      2833126.52     10063883.71      2833029.45     10063688.83
      2833106.87     10063209.31      2832855.16     10062777.43
      2832927.91     10062660.15      2832881.59     10062465.04
      2833055.24     10062208.44       2832922.9     10062139.65
      2832822.44     10061893.09      2832830.27     10061249.26
      2833004.67     10060972.16      2833085.85      10060708.1
      2833114.88       10060241.      2833435.09     10059642.33
      2833551.87     10059285.13      2833870.15     10058970.27
      2833917.12     10058778.76      2833840.96     10058527.41
      2833391.97     10058142.26      2833446.46     10057589.71
      2833140.82     10057202.76      2833070.83     10057007.43
      2832851.96     10056840.26      2832937.21     10056463.65
      2832937.05     10056089.37      2832778.57     10055793.79
      2832516.18     10055539.89      2832518.47     10055433.73

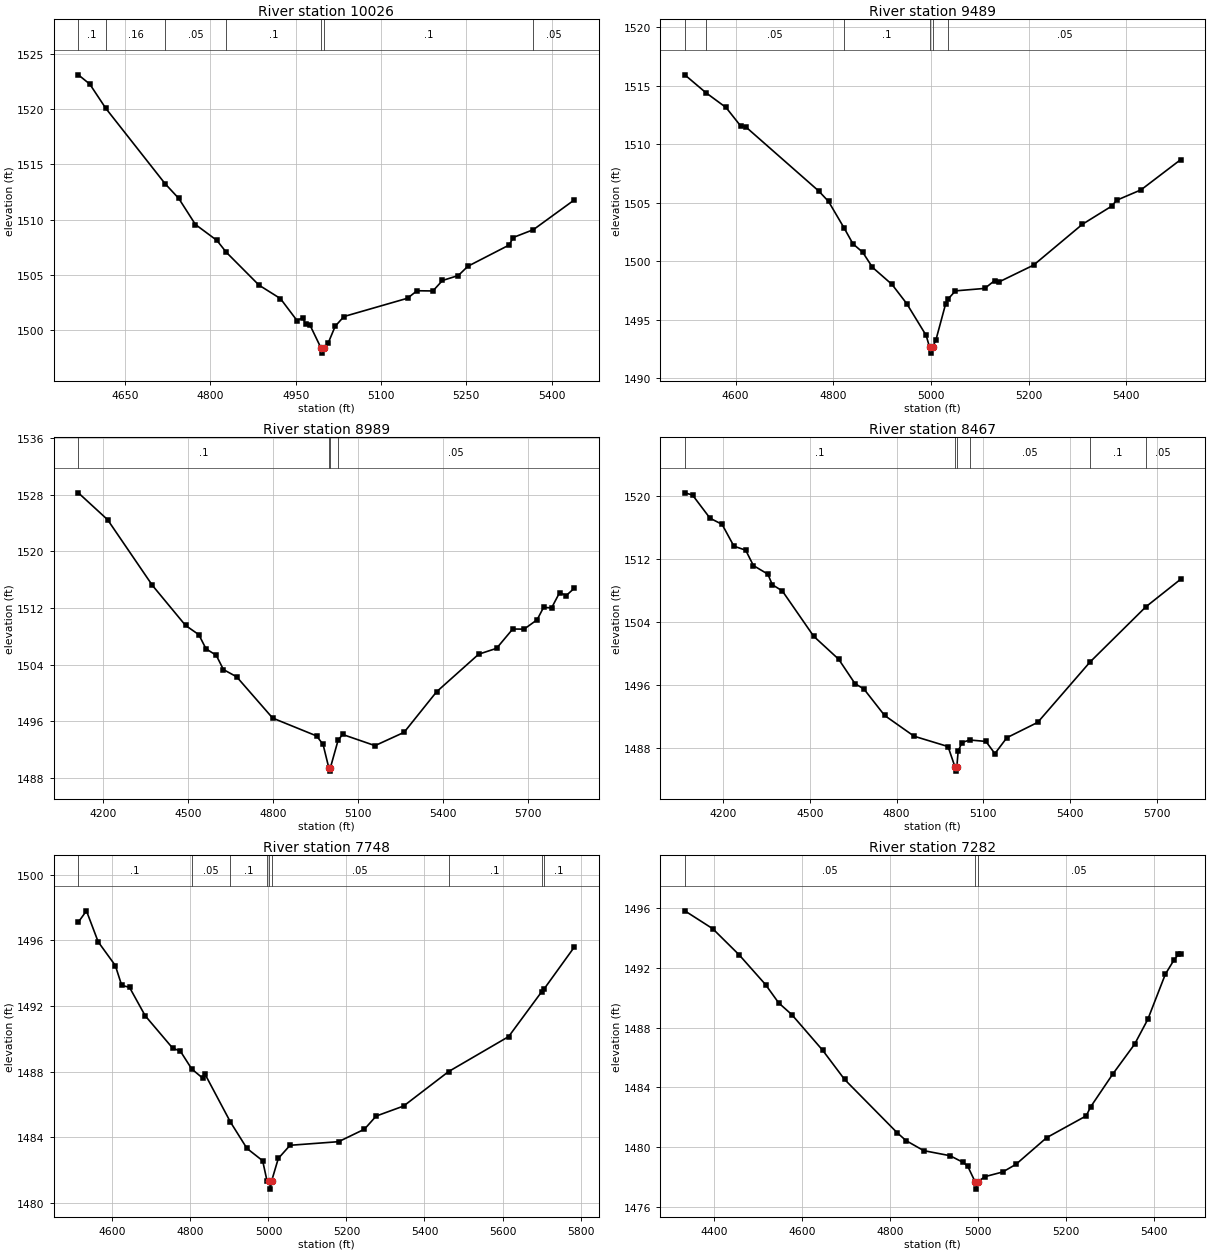
Type RM Length L Ch R = 1 ,10026   ,537,537,537
BEGIN DESCRIPTION:
UNT059 IN NNOGR 20.0
END DESCRIPTION:
XS GIS Cut Line= 2
      2833442.69     10064197.07      2832662.48     10063806.97
#Sta/Elev= 30
  4567.5 1523.13  4587.6 1522.29  4615.8 1520.09    4720 1513.26  4744.1 1511.92
  4773.5 1509.55  4811.2 1508.11    4828 1507.02  4885.3 1504.05    4923 1502.83
  4952.3 1500.83  4962.1 1501.09  4967.7 1500.49  4974.7 1500.46  4994.1 1498.38
  4996.8 1497.88  5000.1 1498.38  5006.8 1498.76  5019.4 1500.32  5034.8  1501.2
  5146.6 1502.86  5163.4 1503.54  5191.3 1503.52  5208.1 1504.47    5236 1504.92
  5252.8 1505.76  5325.5 1507.69  5332.5 1508.37    5368 1509.08  5439.8 1511.77
#Mann= 7 ,-1 , 0
  4567.5      .1       0  4615.8     .16       0    4720     .05       0
    4828      .1       0  4994.1     .07       0  5000.1      .1       0
    5368     .05       0
Bank Sta=4994.1,5000.1
XS Rating Curve= 0 ,0
Exp/Cntr=0.3,0.1

Type RM Length L Ch R = 1 ,9489    ,500,500,500
BEGIN DESCRIPTION:
UNT059 IN NNOGR 19.0
END DESCRIPTION:
XS GIS Cut Line= 2
      2833572.83     10063519.98      2832557.23     10063519.98
#Sta/Elev= 30
  4495.8 1515.94  4538.8 1514.42  4580.2 1513.15  4610.2 1511.57  4620.2 1511.51
  4770.2 1506.01  4790.2 1505.12  4822.7 1502.81  4840.2  1501.5  4860.2 1500.78
  4880.2 1499.49  4920.2 1498.03  4950.2  1496.4  4990.2 1493.67  4997.2 1492.66
  4999.9 1492.16  5003.2 1492.66  5010.2 1493.29  5030.2 1496.39  5035.5  1496.8
  5050.2 1497.48  5110.2 1497.69  5130.2 1498.35  5140.2 1498.26  5210.2 1499.68
  5310.2 1503.17  5370.2 1504.72  5380.2 1505.22  5430.2 1506.11  5511.4 1508.69
#Mann= 6 ,-1 , 0
  4495.8      .1       0  4538.8     .05       0  4822.7      .1       0
  4997.2     .07       0  5003.2      .1       0  5035.5     .05       0
Bank Sta=4997.2,5003.2
XS Rating Curve= 0 ,0
Exp/Cntr=0.3,0.1

Type RM Length L Ch R = 1 ,8989    ,522,522,522
BEGIN DESCRIPTION:
UNT059 IN NNOGR 18.0
END DESCRIPTION:
XS GIS Cut Line= 3
      2833824.59      10063242.2      2833147.53     10062999.15
      2832211.72     10063432.39
#Sta/Elev= 30
  4111.8 1528.26    4215 1524.47  4373.3 1515.19  4490.2 1509.54  4537.2 1508.23
  4562.6 1506.23  4598.7 1505.32  4624.1  1503.3  4670.8 1502.28  4797.9 1496.45
    4953 1493.93  4975.9 1492.73  4995.9 1489.46  4998.6 1488.96  5001.9 1489.46
  5028.8  1493.3  5044.7 1494.14  5159.3 1492.56    5262 1494.44  5376.6 1500.16
  5525.2 1505.47  5588.4  1506.3  5645.6 1509.03  5685.6 1509.01  5731.5 1510.33
  5754.4 1512.08  5782.8 1512.02  5811.2 1514.18  5834.2 1513.75  5862.4 1514.77
#Mann= 4 ,-1 , 0
  4111.8      .1       0  4995.9     .07       0  5001.9      .1       0
  5028.8     .05       0
Bank Sta=4995.9,5001.9
XS Rating Curve= 0 ,0
Exp/Cntr=0.3,0.1

Type RM Length L Ch R = 1 ,8467    ,719,719,719
BEGIN DESCRIPTION:
UNT059 IN NNOGR 17.0
END DESCRIPTION:
XS GIS Cut Line= 3
      2833824.64     10062747.42      2833034.68     10062582.48
      2832157.96     10062816.85
#Sta/Elev= 30
  4067.6 1520.44  4094.3 1520.16  4154.8 1517.22  4196.5 1516.44  4237.4 1513.67
  4278.2 1513.16  4304.8 1511.21  4354.8 1510.12  4370.2 1508.78  4404.8 1507.99
  4513.2 1502.24  4599.7 1499.32  4656.2 1496.22  4686.8 1495.55  4758.4 1492.19
  4860.5 1489.55  4977.8 1488.24  5002.2 1485.62    5005 1485.12  5008.2 1485.62
  5012.7 1487.62  5025.9 1488.75    5053 1489.07  5108.8 1488.89  5139.8 1487.34
  5181.2 1489.36    5288 1491.31  5468.9 1498.97  5661.8 1505.97  5782.1 1509.47
#Mann= 6 ,-1 , 0
  4067.6      .1       0  5002.2     .07       0  5008.2      .1       0
    5053     .05       0  5468.9      .1       0  5661.8     .05       0
Bank Sta=5002.2,5008.2
XS Rating Curve= 0 ,0
Exp/Cntr=0.3,0.1

Type RM Length L Ch R = 1 ,7748    ,466,466,466
BEGIN DESCRIPTION:
UNT059 IN NNOGR 15.0
END DESCRIPTION:
XS GIS Cut Line= 3
       2833389.2     10062030.58      2832527.24      10062106.1
      2832246.76     10062399.56
#Sta/Elev= 30
  4512.5  1497.1  4533.3 1497.79  4563.4  1495.9  4607.3 1494.46  4623.7 1493.25
  4643.7 1493.13  4683.9  1491.4  4754.2 1489.43  4774.2 1489.24  4803.2 1488.16
  4832.3 1487.58  4837.3 1487.84  4902.6 1484.92  4944.8 1483.32    4985 1482.57
  4996.3 1481.34  5002.1 1481.34  5004.9 1480.84  5008.1 1481.34  5025.2 1482.71
  5055.3 1483.51  5179.8 1483.73    5246 1484.49  5276.1 1485.29  5346.4  1485.9
  5461.8    1488  5615.7 1490.13  5700.7 1492.87  5707.2 1493.05  5783.7 1495.57
#Mann= 9 ,-1 , 0
  4512.5      .1       0  4803.2     .05       0  4902.6      .1       0
  4996.3     .05       0  5002.1     .03       0  5008.1     .05       0
  5461.8      .1       0  5700.7     .05       0  5707.2      .1       0
Bank Sta=5002.1,5008.1
XS Rating Curve= 0 ,0
Exp/Cntr=0.3,0.1

Type RM Length L Ch R = 1 ,7282    ,516,516,516
BEGIN DESCRIPTION:
UNT059 IN NNOGR 14.0
END DESCRIPTION:
XS GIS Cut Line= 2
       2833512.1     10061653.66      2832383.64      10061636.3
#Sta/Elev= 30
  4332.8 1495.82  4396.4 1494.62  4456.5 1492.87  4516.5 1490.88  4546.5 1489.65
  4576.5 1488.86  4646.5 1486.48  4696.5 1484.52  4816.5 1480.94  4836.5 1480.42
  4876.5 1479.75  4936.5 1479.41  4966.5 1478.96  4976.5 1478.72  4993.5 1477.67
  4996.3 1477.17  4999.5 1477.67  5016.5 1478.01  5056.5 1478.32  5086.5 1478.83
  5156.5 1480.62  5246.5 1482.08  5256.5 1482.68  5307.4  1484.9  5356.6 1486.88
  5386.6 1488.54  5426.6 1491.57  5446.6 1492.54  5456.5  1492.9  5461.4  1492.9
#Mann= 3 ,-1 , 0
  4332.8     .05       0  4993.5     .03       0  4999.5     .05       0
Bank Sta=4993.5,4999.5
XS Rating Curve= 0 ,0
Exp/Cntr=0.3,0.1

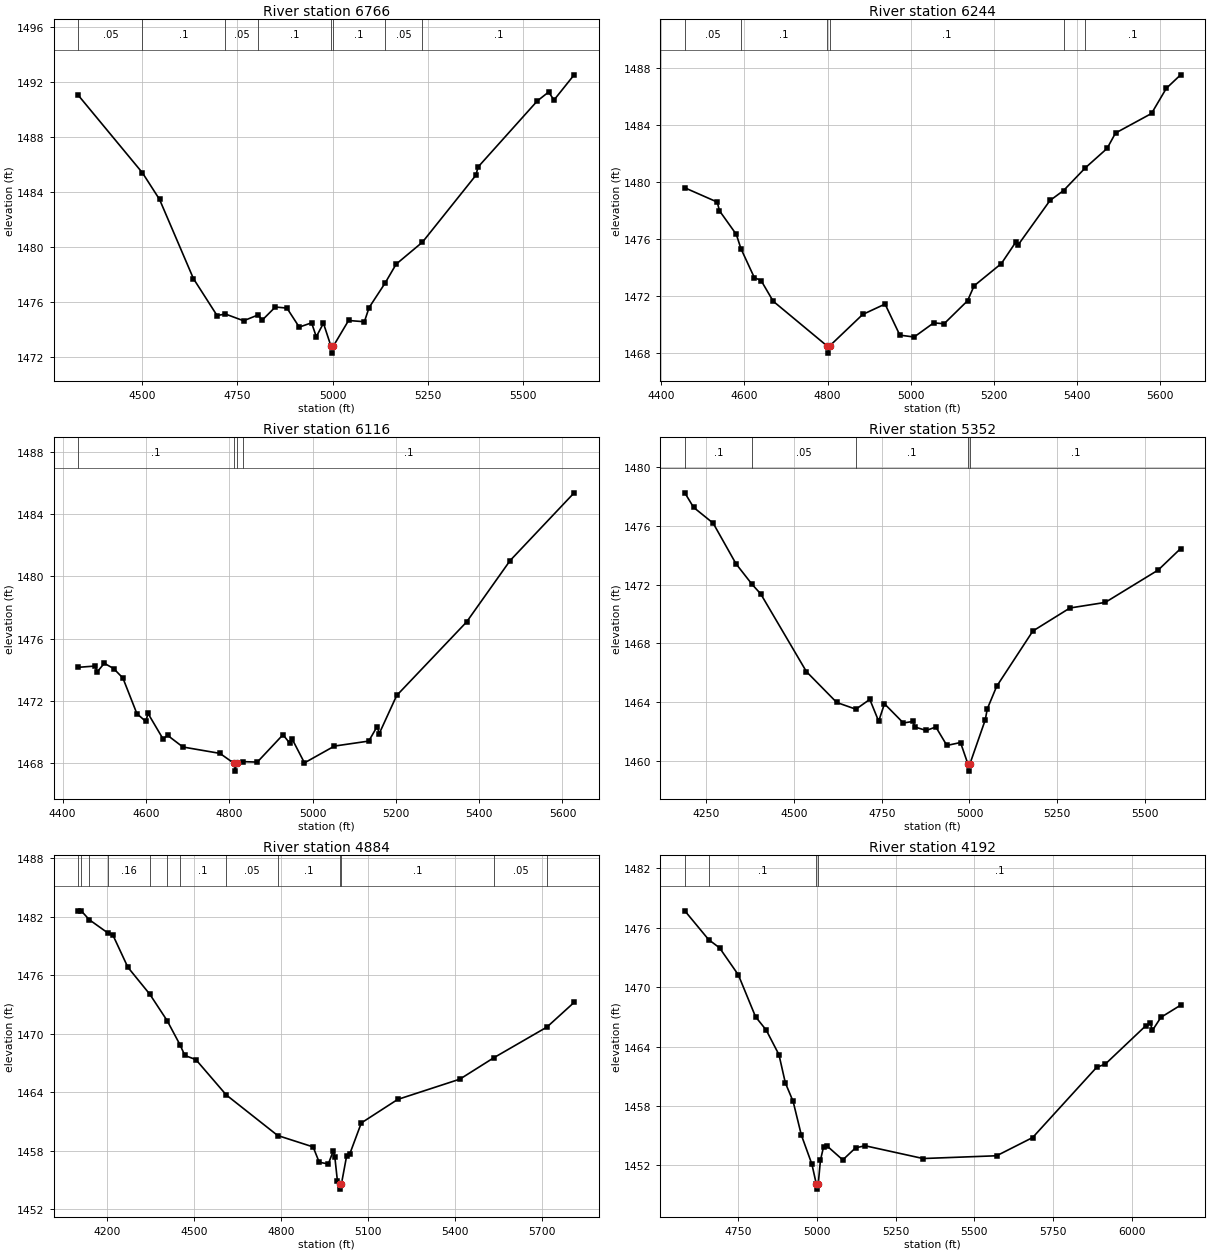
Type RM Length L Ch R = 1 ,6766    ,522,522,522
BEGIN DESCRIPTION:
UNT059 IN NNOGR 13.0
END DESCRIPTION:
XS GIS Cut Line= 2
      2833486.08     10061410.61      2832279.43     10060924.48
#Sta/Elev= 30
  4332.7 1491.01    4501 1485.38  4545.8 1483.45  4634.7  1477.7  4696.7 1475.02
  4718.5 1475.13  4766.3 1474.64    4805 1475.07  4814.6 1474.67  4849.6 1475.64
    4880 1475.56  4912.3 1474.18  4944.7 1474.49    4957 1473.48  4975.8 1474.46
  4995.6 1472.79  4998.3 1472.29  5001.6 1472.79  5041.7 1474.66  5083.2 1474.57
  5095.6  1475.6  5137.2 1477.36  5166.5 1478.75  5235.6 1480.35  5375.9 1485.21
  5381.3  1485.8  5537.1 1490.61  5566.6 1491.25  5580.7 1490.67  5633.6  1492.5
#Mann= 8 ,-1 , 0
  4332.7     .05       0    4501      .1       0  4718.5     .05       0
    4805      .1       0  4995.6     .07       0  5001.6      .1       0
  5137.2     .05       0  5235.6      .1       0
Bank Sta=4995.6,5001.6
XS Rating Curve= 0 ,0
Exp/Cntr=0.3,0.1

Type RM Length L Ch R = 1 ,6244    ,128,128,128
BEGIN DESCRIPTION:
UNT059 IN NNOGR 11.0
END DESCRIPTION:
XS GIS Cut Line= 3
      2833602.77     10060710.27      2833399.64     10060624.33
      2832456.92     10060866.52
#Sta/Elev= 30
  4456.3 1479.58  4534.4 1478.58  4539.8 1477.97  4580.4 1476.31  4591.4 1475.32
  4623.8 1473.28    4640 1473.08  4669.1 1471.63    4799 1468.49  4801.7 1467.99
    4805 1468.49  4884.6  1470.7  4938.5 1471.43  4974.1 1469.25  5008.5 1469.12
  5055.6 1470.11  5080.7 1470.05  5137.1 1471.66    5153 1472.71  5218.6 1474.27
  5254.2 1475.81  5259.3 1475.59  5335.6 1478.69  5368.4 1479.39  5420.4 1480.97
  5473.1 1482.34  5493.5 1483.42  5580.1 1484.79  5615.7 1486.55  5650.2  1487.5
#Mann= 6 ,-1 , 0
  4456.3     .05       0  4591.4      .1       0    4799     .07       0
    4805      .1       0  5368.4     .05       0  5420.4      .1       0
Bank Sta=4799,4805
XS Rating Curve= 0 ,0
Exp/Cntr=0.3,0.1

Type RM Length L Ch R = 1 ,6116    ,764,764,764
BEGIN DESCRIPTION:
Mapping XS 4a384215
END DESCRIPTION:
XS GIS Cut Line= 3
      2833654.81     10060548.79      2833524.64      10060483.7
      2832509.06     10060728.48
#Sta/Elev= 30
  4437.8 1474.16  4477.7 1474.24  4483.3 1473.87  4500.1 1474.42  4522.5 1474.08
  4544.8 1473.47  4578.4 1471.18  4599.8 1470.68    4605  1471.2  4641.1 1469.56
    4652 1469.79  4688.8 1469.04  4777.7 1468.63  4811.5 1467.99  4814.3 1467.49
  4817.5 1467.99  4833.9  1468.1  4867.4 1468.07  4929.1 1469.83  4945.4 1469.28
  4950.5 1469.58  4980.6 1468.02  5052.6  1469.1  5134.9 1469.42    5155 1470.35
  5160.1  1469.9    5202 1472.35  5369.7 1477.07  5474.3 1481.02    5628 1485.37
#Mann= 4 ,-1 , 0
  4437.8      .1       0  4811.5     .07       0  4817.5      .1       0
  4833.9      .1       0
Bank Sta=4811.5,4817.5
XS Rating Curve= 0 ,0
Exp/Cntr=0.3,0.1

Type RM Length L Ch R = 1 ,5352    ,468,468,468
BEGIN DESCRIPTION:
UNT059 IN NNOGR 10.0
END DESCRIPTION:
XS GIS Cut Line= 3
      2834092.39     10060132.15      2833167.87     10059845.68
      2832725.12     10059900.37
#Sta/Elev= 30
  4188.2 1478.26  4213.2 1477.27  4269.1 1476.19  4334.3 1473.42  4380.1 1472.02
  4404.7 1471.37  4535.1 1466.07  4621.5 1463.97  4676.2 1463.51  4715.8 1464.18
  4741.1 1462.69  4757.6 1463.88  4811.6 1462.57  4838.9 1462.68  4844.2  1462.3
  4876.8 1462.06  4904.1  1462.3  4935.6 1461.04  4974.5 1461.24  4995.4 1459.79
  4998.2 1459.29  5001.4 1459.79    5045 1462.78  5050.8 1463.53  5077.6 1465.07
  5180.8 1468.84  5286.5 1470.41  5387.2 1470.79  5538.4    1473  5602.2 1474.46
#Mann= 5 ,-1 , 0
  4188.2      .1       0  4380.1     .05       0  4676.2      .1       0
  4995.4     .07       0  5001.4      .1       0
Bank Sta=4995.4,5001.4
XS Rating Curve= 0 ,0
Exp/Cntr=0.3,0.1

Type RM Length L Ch R = 1 ,4884    ,692,692,692
BEGIN DESCRIPTION:
UNT059 IN NNOGR 9.0
END DESCRIPTION:
XS GIS Cut Line= 4
      2834331.98     10059470.67      2833904.85     10059600.89
      2833357.97     10059426.41      2832682.17     10059566.77
#Sta/Elev= 30
  4100.1 1482.63    4111  1482.6  4137.8 1481.72  4202.4 1480.35  4218.8 1480.18
    4271 1476.84  4346.8 1474.07  4406.6 1471.36  4451.4 1468.86  4467.6 1467.79
  4505.6 1467.37  4610.6 1463.74  4787.9 1459.58  4910.2 1458.41  4931.2 1456.84
  4962.7 1456.66  4979.9 1458.02  4985.2 1457.36  4994.2 1454.87  5001.7 1454.58
  5004.4 1454.08  5007.7 1454.58  5025.7 1457.46  5036.2 1457.65  5076.5 1460.87
  5201.9 1463.28  5416.4 1465.36  5533.8 1467.56  5717.2 1470.71  5810.9 1473.24
#Mann= 13 ,-1 , 0
  4100.1      .1       0    4111     .05       0  4137.8      .1       0
  4202.4     .16       0  4346.8      .1       0  4406.6     .16       0
  4451.4      .1       0  4610.6     .05       0  4787.9      .1       0
  5001.7     .07       0  5007.7      .1       0  5533.8     .05       0
  5717.2      .1       0
Bank Sta=5001.7,5007.7
XS Rating Curve= 0 ,0
Exp/Cntr=0.3,0.1

Type RM Length L Ch R = 1 ,4192    ,684,684,684
BEGIN DESCRIPTION:
UNT059 IN NNOGR 7.0
END DESCRIPTION:
XS GIS Cut Line= 3
      2834293.34     10058997.41      2833190.93     10058806.44
      2832752.49     10058936.31
#Sta/Elev= 30
  4579.6 1477.71  4655.4  1474.8  4690.1 1473.97  4749.8 1471.24  4804.5 1467.01
  4838.3 1465.67  4878.9 1463.18  4899.2 1460.33  4923.9 1458.46  4949.9 1455.08
  4983.7 1452.11  4997.7  1450.1  5000.4  1449.6  5003.7  1450.1  5010.8 1452.52
  5020.9  1453.9  5031.1 1453.98  5081.8 1452.55  5122.4 1453.77  5152.8 1453.98
  5337.1 1452.69  5570.9 1452.97  5685.3 1454.81  5888.7  1461.9  5916.3 1462.23
  6045.2 1466.11  6059.7 1466.34    6066 1465.63    6093 1466.95  6155.7 1468.18
#Mann= 4 ,-1 , 0
  4579.6     .16       0  4655.4      .1       0  4997.7     .07       0
  5003.7      .1       0
Bank Sta=4997.7,5003.7
XS Rating Curve= 0 ,0
Exp/Cntr=0.3,0.1

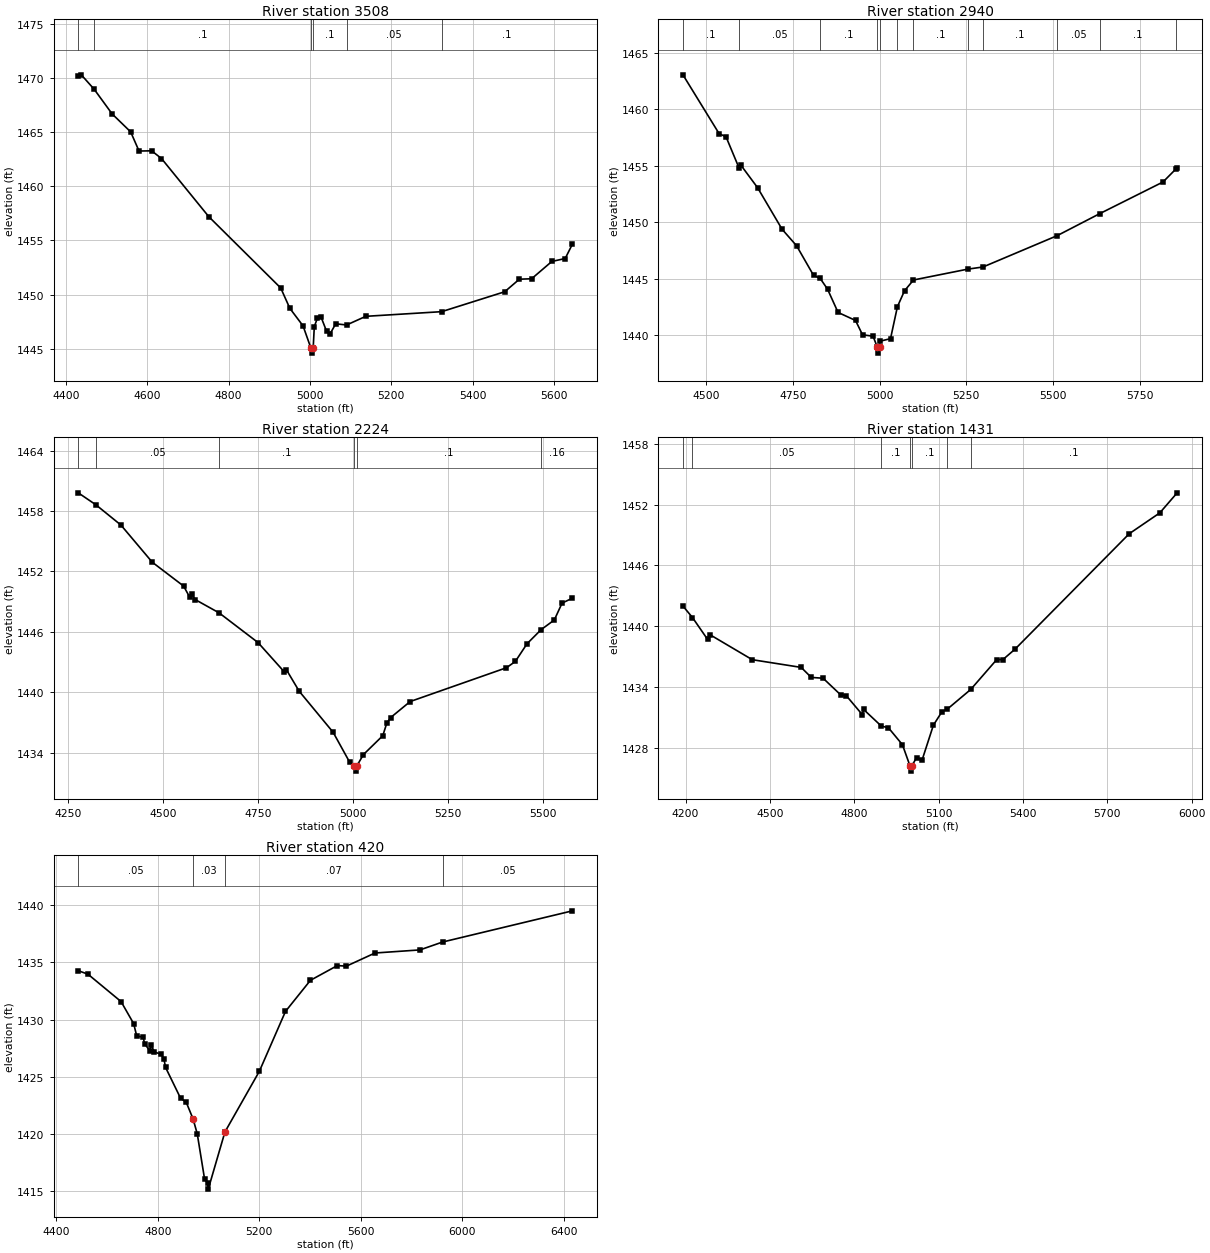
Type RM Length L Ch R = 1 ,3508    ,568,568,568
BEGIN DESCRIPTION:
UNT059 IN NNOGR 6.0
END DESCRIPTION:
XS GIS Cut Line= 3
      2834163.17     10058207.48      2833763.85     10058311.65
      2833052.77     10058684.53
#Sta/Elev= 30
  4430.2 1470.21  4437.7  1470.3  4469.5 1468.96  4513.5 1466.69  4559.1 1465.03
  4579.7 1463.26  4610.7 1463.28  4634.9 1462.57  4751.2  1457.2  4928.2 1450.61
  4950.6 1448.73  4983.1 1447.11  5002.1 1445.09  5004.9 1444.59  5008.1 1445.09
  5010.8 1447.04  5018.3 1447.81  5027.2 1447.94  5040.9 1446.62  5049.3 1446.35
  5063.5  1447.3  5090.2 1447.19  5137.5 1447.99    5324 1448.42  5479.1 1450.26
  5515.2 1451.42  5545.3 1451.46  5595.1 1453.06  5627.9 1453.33  5645.8 1454.67
#Mann= 6 ,-1 , 0
  4430.2     .05       0  4469.5      .1       0  5002.1     .07       0
  5008.1      .1       0  5090.2     .05       0    5324      .1       0
Bank Sta=5002.1,5008.1
XS Rating Curve= 0 ,0
Exp/Cntr=0.3,0.1

Type RM Length L Ch R = 1 ,2940    ,716,716,716
BEGIN DESCRIPTION:
UNT059 IN NNOGR 4.0
END DESCRIPTION:
XS GIS Cut Line= 3
      2833951.72     10057848.29      2833227.76     10057939.43
      2832733.19     10058426.19
#Sta/Elev= 30
  4433.8 1463.03  4537.9 1457.83    4558 1457.54  4595.8 1454.76  4600.4 1455.05
  4648.7 1453.05  4719.3 1449.37  4761.1 1447.91    4810 1445.29  4829.1 1445.02
  4850.3 1444.07  4880.6 1442.01  4930.9  1441.3  4951.1 1440.03  4981.3 1439.91
  4994.1 1438.91  4996.9 1438.41  5000.1 1438.91  5002.2 1439.47  5031.7 1439.69
  5051.6 1442.52  5072.1 1443.93  5097.9 1444.88  5254.1 1445.84  5298.1 1446.03
  5511.6  1448.8  5634.4 1450.75  5816.6 1453.55  5854.1 1454.71  5857.4 1454.81
#Mann= 12 ,-1 , 0
  4433.8      .1       0  4595.8     .05       0  4829.1      .1       0
  4994.1     .07       0  5000.1      .1       0  5051.6     .05       0
  5097.9      .1       0  5254.1     .05       0  5298.1      .1       0
  5511.6     .05       0  5634.4      .1       0  5854.1     .05       0
Bank Sta=4994.1,5000.1
XS Rating Curve= 0 ,0
Exp/Cntr=0.3,0.1

Type RM Length L Ch R = 1 ,2224    ,793,793,793
BEGIN DESCRIPTION:
UNT059 IN NNOGR 3.0
END DESCRIPTION:
XS GIS Cut Line= 3
      2833937.42     10057408.86      2833373.22     10057269.98
      2832671.78     10057425.86
#Sta/Elev= 30
  4277.7 1459.81  4324.1 1458.62  4389.9 1456.61  4472.3 1452.92  4554.7 1450.55
  4570.6 1449.46  4575.8  1449.8  4585.6  1449.2    4648 1447.89  4750.4 1444.94
  4819.7 1442.02  4824.9 1442.25  4858.6 1440.11  4947.9 1436.03  4991.5 1433.05
    5004 1432.67  5006.8 1432.17    5010 1432.67  5027.5 1433.81  5078.5 1435.69
    5089 1436.93  5099.2 1437.49  5150.4 1439.08  5403.8 1442.44    5427 1443.06
  5457.8 1444.82  5494.8 1446.22  5529.5 1447.18    5550 1448.86  5577.3 1449.35
#Mann= 6 ,-1 , 0
  4277.7      .1       0  4324.1     .05       0    4648      .1       0
    5004     .07       0    5010      .1       0  5494.8     .16       0
Bank Sta=5004,5010
XS Rating Curve= 0 ,0
Exp/Cntr=0.3,0.1

Type RM Length L Ch R = 1 ,1431    ,1011,1011,1011
BEGIN DESCRIPTION:
UNT059 IN NNOGR 2.0
END DESCRIPTION:
XS GIS Cut Line= 4
      2833589.77     10056965.49      2833157.45     10056673.81
      2832719.95     10056692.03      2832331.94     10057389.93
#Sta/Elev= 30
  4190.6 1441.98  4224.4 1440.85  4278.4 1438.68  4287.4 1439.14  4437.3 1436.68
  4611.1 1435.92  4647.1 1434.93  4689.1 1434.85  4751.1 1433.22  4771.2 1433.14
  4828.3 1431.26  4833.3 1431.76  4896.3 1430.12  4921.3 1429.96  4971.3 1428.28
  4998.4 1426.17  5001.1 1425.67  5004.4 1426.17  5021.4    1427  5041.4 1426.78
  5081.4 1430.21  5111.4 1431.52  5131.1  1431.8  5214.2 1433.74  5306.9  1436.7
  5328.6 1436.69  5372.1 1437.73  5778.1 1449.13  5886.8 1451.19  5948.5 1453.17
#Mann= 7 ,-1 , 0
  4190.6      .1       0  4224.4     .05       0  4896.3      .1       0
  4998.4     .07       0  5004.4      .1       0  5131.1     .05       0
  5214.2      .1       0
Bank Sta=4998.4,5004.4
XS Rating Curve= 0 ,0
Exp/Cntr=0.3,0.1

Type RM Length L Ch R = 1 ,420     ,0,0,0
BEGIN DESCRIPTION:
UNT059 IN NNOGR 1.0
END DESCRIPTION:
XS GIS Cut Line= 4
       2833204.3     10055754.53      2832925.68     10055655.58
      2832454.33     10055913.39      2831635.34     10056669.98
#Sta/Elev= 30
  4486.7 1434.27  4524.7 1433.97  4655.4 1431.57  4705.1 1429.64  4717.1 1428.56
  4742.7 1428.45    4748 1427.89  4768.2 1427.28  4773.5 1427.77  4786.9 1427.17
  4814.4 1426.94  4824.8 1426.51  4830.6 1425.82  4890.3  1423.1  4912.1 1422.77
  4939.6 1421.28  4955.8 1419.99  4984.4 1416.07  4996.4 1415.66  4999.1 1415.16
  5064.8 1420.16  5200.5 1425.47  5303.5 1430.71  5401.8 1433.43  5507.9 1434.72
  5543.6 1434.67  5656.4 1435.82  5833.3 1436.09  5922.6 1436.78  6434.6 1439.51
#Mann= 4 ,-1 , 0
  4486.7     .05       0  4939.6     .03       0  5064.8     .07       0
  5922.6     .05       0
Bank Sta=4939.6,5064.8
XS Rating Curve= 0 ,0
Exp/Cntr=0.3,0.1

Chan Stop Cuts=-1
Use User Specified Reach Order=0
Composite Channel Slope=5