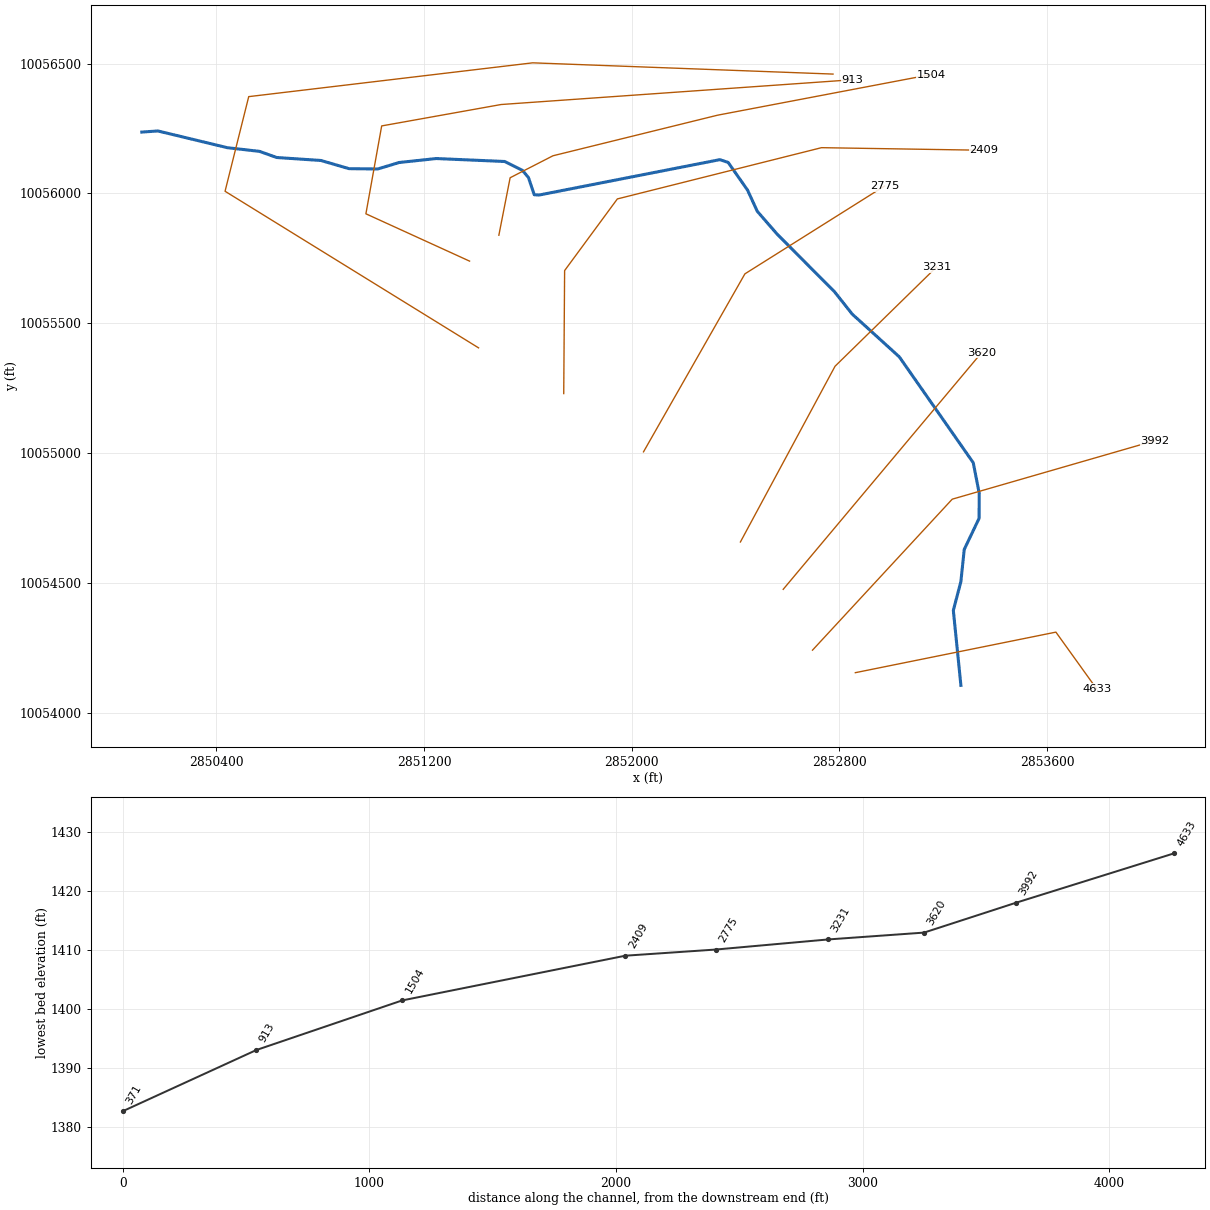
--- UNT059 IN SNOGR.prj (project) ---

Proj Title=UNT059 IN SNOGR Base Level Engineering
Current Plan=p01
Default Exp/Contr=0.3,0.1
English Units
Geom File=g01
Flow File=f01
Plan File=p01
Y Axis Title=Elevation
X Axis Title(PF)=Main Channel Distance
X Axis Title(XS)=Station
BEGIN DESCRIPTION:
UNT059 IN SNOGR
END DESCRIPTION:
DSS Export Rating Curves= 0
DSS Export Rating Curve Sorted= 0
DSS Export Volume Flow Curves= 0
DXF OffsetX= 0
DXF OffsetY= 0
DXF ScaleX= 1
DXF ScaleY= 10

--- UNT059 IN SNOGR.p01 (plan) ---

Plan Title=Multiple Run
Short Identifier=Multiple
Geom File=g01
Flow File=f01
Subcritical Flow
K Sum by GR= 0
Std Step Tol= 0.01
Critical Tol= 0.01
Num of Std Step Trials= 20
Max Error Tol= 0.3
Flow Tol Ratio= 0.001
Split Flow NTrial= 30
Split Flow Tol= 0.02
Split Flow Ratio= 0.02
Log Output Level= 0
Friction Slope Method= 1
Unsteady Friction Slope Method= 2
Unsteady Bridges Friction Slope Method= 1
Parabolic Critical Depth
Global Vel Dist=  1 , 1 , 1
Global Log Level= 0
CheckData=True
Encroach Param= -1, 0, 0, 0
BEGIN DESCRIPTION:
Multiple Run
END DESCRIPTION:

--- UNT059 IN SNOGR.f01 (steady flow) ---

Flow Title=Multiple
Program Version=4.10
Number of Profiles= 7
Profile Names=10-year,25-year,50-year,1pct_min,100-year,1pct_plu,500-year
River Rch & RM=UNT059 IN SNOGR,Reach-1         ,4633
     800    1153    1460    1353    1830    2475    2886
River Rch & RM=UNT059 IN SNOGR,Reach-1         ,3992
     984    1431    1821    1695    2293    3101    3649
Boundary for River Rch & Prof#=UNT059 IN SNOGR,Reach-1         , 1
Up Type= 0
Dn Type= 3
Dn Slope=0.019
Boundary for River Rch & Prof#=UNT059 IN SNOGR,Reach-1         , 2
Up Type= 0
Dn Type= 3
Dn Slope=0.019
Boundary for River Rch & Prof#=UNT059 IN SNOGR,Reach-1         , 3
Up Type= 0
Dn Type= 3
Dn Slope=0.019
Boundary for River Rch & Prof#=UNT059 IN SNOGR,Reach-1         , 4
Up Type= 0
Dn Type= 3
Dn Slope=0.019
Boundary for River Rch & Prof#=UNT059 IN SNOGR,Reach-1         , 5
Up Type= 0
Dn Type= 3
Dn Slope=0.019
Boundary for River Rch & Prof#=UNT059 IN SNOGR,Reach-1         , 6
Up Type= 0
Dn Type= 3
Dn Slope=0.019
Boundary for River Rch & Prof#=UNT059 IN SNOGR,Reach-1         , 7
Up Type= 0
Dn Type= 3
Dn Slope=0.019
DSS Import GetInterval= 0
DSS Import GetPeak= 0
DSS Import FillOption= 0

--- UNT059 IN SNOGR.g01 (geometry) ---

Geom Title=Existing Conditions
Program Version=4.10

River Reach=UNT059 IN SNOGR ,Reach-1
Reach XY= 30
      2853267.81     10054104.79      2853238.67     10054393.56
      2853267.67     10054504.09      2853280.72     10054628.47
      2853337.95     10054748.29      2853338.39     10054844.65
      2853315.39     10054962.46       2853030.5     10055370.37
      2852849.45     10055534.75      2852780.89     10055621.08
      2852559.58     10055843.58      2852483.57      10055930.9
      2852445.98     10056012.71      2852371.37     10056119.31
      2852339.42     10056130.06      2851643.09     10055993.75
      2851624.41     10055994.83       2851601.9      10056061.4
      2851578.73     10056088.89      2851510.61     10056122.96
      2851246.91     10056134.34      2851103.86     10056119.05
      2851021.35     10056094.09      2850910.91     10056095.35
      2850802.71     10056126.85      2850632.25     10056138.31
      2850565.81     10056161.99      2850442.19     10056176.11
      2850174.73     10056240.56       2850112.7     10056236.32

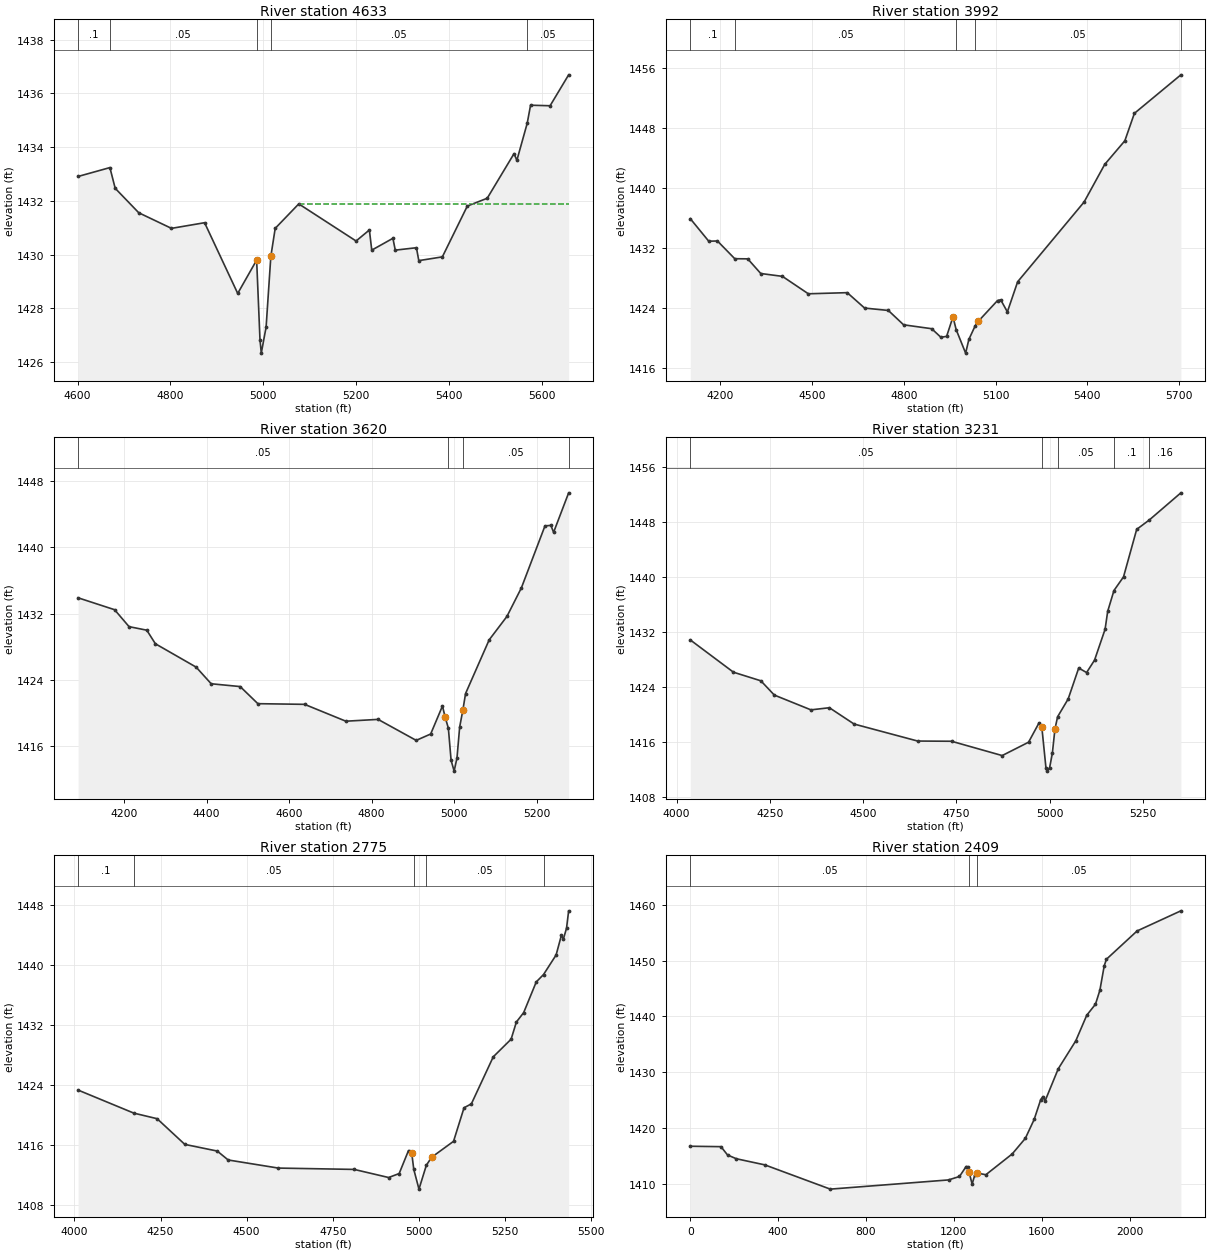
Type RM Length L Ch R = 1 ,4633    ,641,641,641
BEGIN DESCRIPTION:
UNT059 IN SNOGR 9.0
END DESCRIPTION:
XS GIS Cut Line= 3
      2852861.18     10054153.64      2853633.74     10054309.88
      2853790.77     10054091.23
#Sta/Elev= 30
    4601 1432.91  4669.6 1433.24    4681 1432.47  4731.8 1431.56  4802.3 1430.98
  4873.7 1431.19  4945.1 1428.56  4985.9  1429.8  4993.1 1426.84  4995.9 1426.34
  5006.3 1427.31  5016.5 1429.94  5025.9 1430.98  5076.7 1431.89  5200.2 1430.51
  5228.9 1430.92    5234 1430.17  5279.6 1430.61  5284.7 1430.17  5330.3 1430.26
  5335.4 1429.78  5386.2 1429.92    5440 1431.81  5482.9  1432.1  5540.7 1433.76
  5546.8 1433.51  5569.1 1434.89  5576.3 1435.56  5618.4 1435.54  5658.4 1436.69
#Mann= 5 ,-1 , 0
    4601      .1       0  4669.6     .05       0  4985.9     .04       0
  5016.5     .05       0  5569.1     .05       0
#XS Ineff= 2 , 0
                         5076.16         1431.89
Permanent Ineff=
       T       T
Bank Sta=4985.9,5016.5
XS Rating Curve= 0 ,0
Exp/Cntr=0.3,0.1

Type RM Length L Ch R = 1 ,3992    ,372,372,372
BEGIN DESCRIPTION:
UNT059 IN SNOGR 8.0
END DESCRIPTION:
XS GIS Cut Line= 3
      2852696.22     10054240.43      2853234.43     10054822.04
       2854014.6     10055047.42
#Sta/Elev= 30
  4101.8 1435.88  4162.1 1432.88  4190.5 1432.91  4247.2 1430.55  4289.7 1430.53
  4332.2 1428.58  4403.1  1428.2  4487.8 1425.88  4615.1 1426.03  4671.8 1423.98
  4749.5 1423.66  4799.4 1421.75  4891.3 1421.23  4921.4 1420.09  4940.1 1420.21
  4960.9 1422.81  4971.3 1421.11  5002.3 1417.98  5012.9 1419.81  5033.7 1421.63
  5044.2 1422.24  5106.6 1424.98    5117 1425.08  5138.8 1423.47  5172.4 1427.48
  5389.8  1438.1  5457.1  1443.1    5523 1446.25  5554.2  1449.9  5706.3 1455.03
#Mann= 5 ,-1 , 0
  4101.8      .1       0  4247.2     .05       0  4971.3     .04       0
  5033.7     .05       0  5706.3      .1       0
#XS Ineff= 2 , 0
                         5117.15         1424.96
Permanent Ineff=
       T       T
Bank Sta=4960.9,5044.2
XS Rating Curve= 0 ,0
Exp/Cntr=0.3,0.1

Type RM Length L Ch R = 1 ,3620    ,389,389,389
BEGIN DESCRIPTION:
UNT059 IN SNOGR 7.0
END DESCRIPTION:
XS GIS Cut Line= 2
      2852583.37     10054474.79       2853347.3      10055386.3
#Sta/Elev= 30
  4088.6 1433.91  4177.1 1432.47  4212.2 1430.42  4255.2 1429.99    4276 1428.35
  4374.9 1425.52  4411.3 1423.51  4481.6 1423.17  4524.5  1421.1  4637.7 1421.02
  4737.8 1418.98  4815.9  1419.2  4908.3 1416.66  4943.4 1417.43    4972 1420.82
  4978.6 1419.45  4986.3 1418.13  4992.9 1414.25  5000.3 1412.94  5007.2 1414.54
  5013.7 1418.28  5021.5 1420.34    5028 1422.33  5085.2 1428.82  5128.2 1431.65
  5163.3 1435.11  5220.5 1442.61  5234.8 1442.67  5241.4 1441.83  5277.9 1446.61
#Mann= 4 ,-1 , 0
  4088.6     .05       0  4986.3    .035       0  5021.5     .05       0
  5277.9     .05       0
Bank Sta=4978.6,5021.5
XS Rating Curve= 0 ,0
Exp/Cntr=0.3,0.1

Type RM Length L Ch R = 1 ,3231    ,456,456,456
BEGIN DESCRIPTION:
UNT059 IN SNOGR 6.0
END DESCRIPTION:
XS GIS Cut Line= 3
      2852418.46     10054657.11      2852783.04     10055334.19
      2853173.58     10055716.05
#Sta/Elev= 30
  4036.6 1430.84  4152.3 1426.15  4225.8  1424.9  4261.8 1422.83    4360 1420.68
  4409.5 1420.99  4475.7 1418.62  4646.1 1416.15  4736.9 1416.12  4872.7 1414.04
  4943.4 1415.98  4971.7 1418.81  4978.9 1418.23    4990 1412.28  4992.8 1411.78
    5000  1412.3  5007.2 1414.37  5014.2  1417.9  5021.3 1419.68  5049.6 1422.26
  5077.9 1426.76    5099  1426.1  5120.3  1427.9  5148.6 1432.39  5155.6    1435
  5172.4 1438.02    5198    1440  5233.3  1446.9  5267.2 1448.27  5351.8 1452.21
#Mann= 5 ,-1 , 0
  4036.6     .05       0  4978.9    .035       0  5021.3     .05       0
  5172.4      .1       0  5267.2     .16       0
Bank Sta=4978.9,5014.2
XS Rating Curve= 0 ,0
Exp/Cntr=0.3,0.1

Type RM Length L Ch R = 1 ,2775    ,366,366,366
BEGIN DESCRIPTION:
UNT059 IN SNOGR 5.0
END DESCRIPTION:
XS GIS Cut Line= 3
      2852045.21     10055004.35      2852435.82     10055690.09
      2852973.75     10056028.47
#Sta/Elev= 30
  4010.5 1423.29  4172.6 1420.21    4240 1419.47  4320.5 1416.04  4414.7 1415.15
  4446.4 1413.96  4591.9 1412.88  4812.3  1412.7  4912.4 1411.62    4943 1412.15
  4970.1 1415.22  4979.5 1414.89  4985.4 1412.71  5000.5 1410.07  5021.9 1413.25
  5037.2 1414.32  5100.9 1416.45  5131.4 1420.93  5152.7 1421.45  5216.3 1427.73
  5268.1 1430.08  5283.4 1432.37  5304.6 1433.63  5341.1 1437.72  5362.3 1438.71
  5398.8 1441.32  5414.1 1443.94    5420 1443.46    5429 1444.88  5435.2 1447.21
#Mann= 5 ,-1 , 0
  4010.5      .1       0  4172.6     .05       0  4985.4    .035       0
  5021.9     .05       0  5362.3      .1       0
#XS Ineff= 2 , 0
         4970.93 1415.15
Permanent Ineff=
       T       T
Bank Sta=4979.5,5037.2
XS Rating Curve= 0 ,0
Exp/Cntr=0.3,0.1

Type RM Length L Ch R = 1 ,2409    ,905,905,905
BEGIN DESCRIPTION:
UNT059 IN SNOGR 4.0
END DESCRIPTION:
XS GIS Cut Line= 5
     2851737.946    10055228.891     2851741.343    10055702.691
     2851944.468    10055978.733     2852730.958    10056176.204
     2853355.926    10056166.233
#Sta/Elev= 30
       01416.718139.67781416.641169.6087 1415.15209.51661414.477339.21741413.379
637.4509 1409.031175.7771410.679 1225.77  1411.31255.7661413.0681265.765 1413.03
 1269.77 1412.02 1283.31 1409.931295.7611411.612 1305.76 1411.921345.7541411.608
1465.7381415.3351525.7291418.1371565.7241421.513 1595.721425.0841605.7191425.616
1615.7171424.8571675.5421430.6041755.3081435.6111805.1611440.1931845.0441442.179
1864.9861444.6721884.9271449.0791894.8981450.2392034.4881455.3062233.9031458.915
#Mann= 3 , 0 , 0
       0     .05       0 1269.77    .035       0 1305.76     .05       0
Bank Sta=1269.77,1305.76
XS Rating Curve= 0 ,0
Exp/Cntr=0.3,0.1

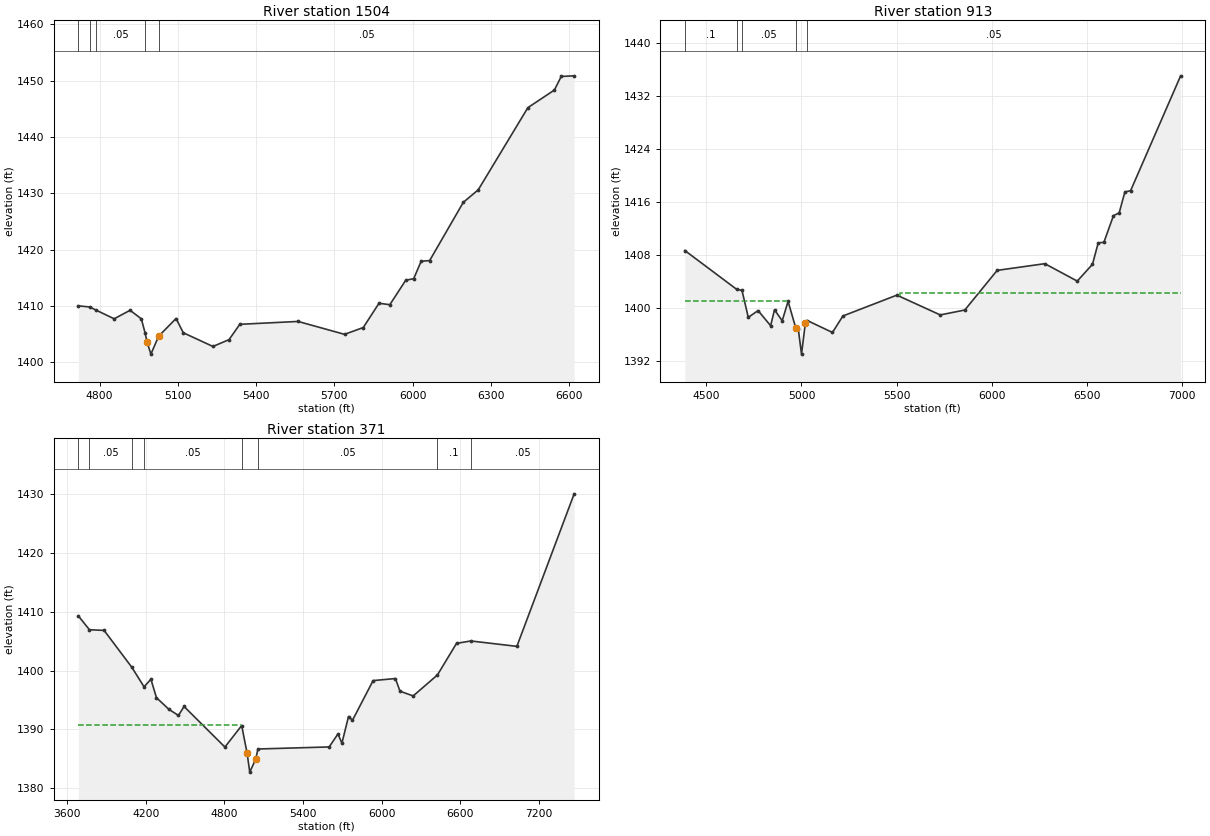
Type RM Length L Ch R = 1 ,1504    ,591,591,591
BEGIN DESCRIPTION:
UNT059 IN SNOGR 3.0
END DESCRIPTION:
XS GIS Cut Line= 5
      2851488.04     10055838.94      2851531.45     10056060.33
      2851696.38     10056144.97      2852329.92      10056301.2
      2853152.82      10056457.9
#Sta/Elev= 30
  4718.4 1410.03    4763 1409.82  4784.4 1409.31  4855.8 1407.73  4916.9 1409.24
    4960 1407.72  4974.4 1405.22  4982.2 1403.58  4996.6 1401.46  5026.5 1404.65
  5093.1 1407.78  5120.9 1405.25  5234.5 1402.82  5296.3 1404.03  5337.5 1406.75
  5560.9 1407.26  5739.2 1404.97    5811 1406.18  5871.3 1410.49  5912.8 1410.23
  5973.8 1414.57  6004.4 1414.85  6032.9 1417.94  6065.5 1418.06  6194.5 1428.39
  6251.8 1430.61  6442.1 1445.19  6543.9 1448.32    6570 1450.73  6619.6 1450.84
#Mann= 5 ,-1 , 0
  4718.4      .1       0    4763     .08       0  4784.4     .05       0
  4974.4    .035       0  5026.5     .05       0
Bank Sta=4982.2,5026.5
XS Rating Curve= 0 ,0
Exp/Cntr=0.3,0.1

Type RM Length L Ch R = 1 ,913     ,542,542,542
BEGIN DESCRIPTION:
UNT059 IN SNOGR 2.0
END DESCRIPTION:
XS GIS Cut Line= 5
      2851375.21     10055739.14      2850975.89     10055921.44
      2851036.66     10056259.98      2851496.72     10056342.45
      2852850.85     10056437.93
#Sta/Elev= 30
  4386.3 1408.72  4658.9 1402.86    4687  1402.7  4720.2 1398.62  4771.8 1399.65
  4837.7 1397.36  4858.1 1399.76  4898.7 1398.11  4929.5 1401.04  4969.8 1397.03
  4983.2 1396.87  5000.1 1393.07  5020.6 1397.79  5030.8 1398.14  5162.9 1396.34
  5217.8 1398.83  5501.7 1401.98  5729.8 1398.99  5858.9 1399.73  6029.3 1405.72
  6279.9 1406.73  6450.4  1404.1  6530.6 1406.64  6560.6 1409.86  6590.7 1409.97
  6640.8 1413.98  6670.9  1414.4    6701 1417.56  6731.1 1417.76  6994.1  1435.1
#Mann= 5 ,-1 , 0
  4386.3      .1       0  4658.9     .08       0    4687     .05       0
  4969.8    .035       0  5030.8     .05       0
#XS Ineff= 2 , 0
         4928.78 1401.06 5517.44         1402.26
Permanent Ineff=
       T       T
Bank Sta=4969.8,5020.6
XS Rating Curve= 0 ,0
Exp/Cntr=0.3,0.1

Type RM Length L Ch R = 1 ,371     ,0,0,0
BEGIN DESCRIPTION:
UNT059 IN SNOGR 1.0
END DESCRIPTION:
XS GIS Cut Line= 5
       2851409.9     10055404.96      2850433.36     10056008.25
       2850524.5     10056372.83      2851618.25     10056503.04
       2852775.3      10056459.7
#Sta/Elev= 30
  3685.4 1409.32  3770.1 1406.96  3881.9 1406.85  4092.5  1400.6    4187 1397.24
    4239 1398.54  4281.5 1395.39  4376.1 1393.41  4449.4 1392.36    4492 1393.89
  4803.8 1386.98  4931.7 1390.64  4972.9 1385.96  4993.3 1382.71  5039.9 1384.98
  5055.4 1386.65  5599.1    1387  5666.2 1389.21  5696.5 1387.64  5746.8 1392.18
    5777 1391.54  5934.4  1398.3  6104.6 1398.65  6139.6 1396.49  6240.3 1395.69
  6425.2 1399.26  6570.9 1404.64  6680.4 1405.05  7031.3 1404.13  7468.4 1430.11
#Mann= 8 ,-1 , 0
  3685.4      .1       0  3770.1     .05       0  4092.5      .1       0
    4187     .05       0  4931.7    .035       0  5055.4     .05       0
  6425.2      .1       0  6680.4     .05       0
#XS Ineff= 2 , 0
         4929.51 1390.81
Permanent Ineff=
       T       T
Bank Sta=4972.9,5039.9
XS Rating Curve= 0 ,0
Exp/Cntr=0.3,0.1

Chan Stop Cuts=-1
Use User Specified Reach Order=0
Composite Channel Slope=5