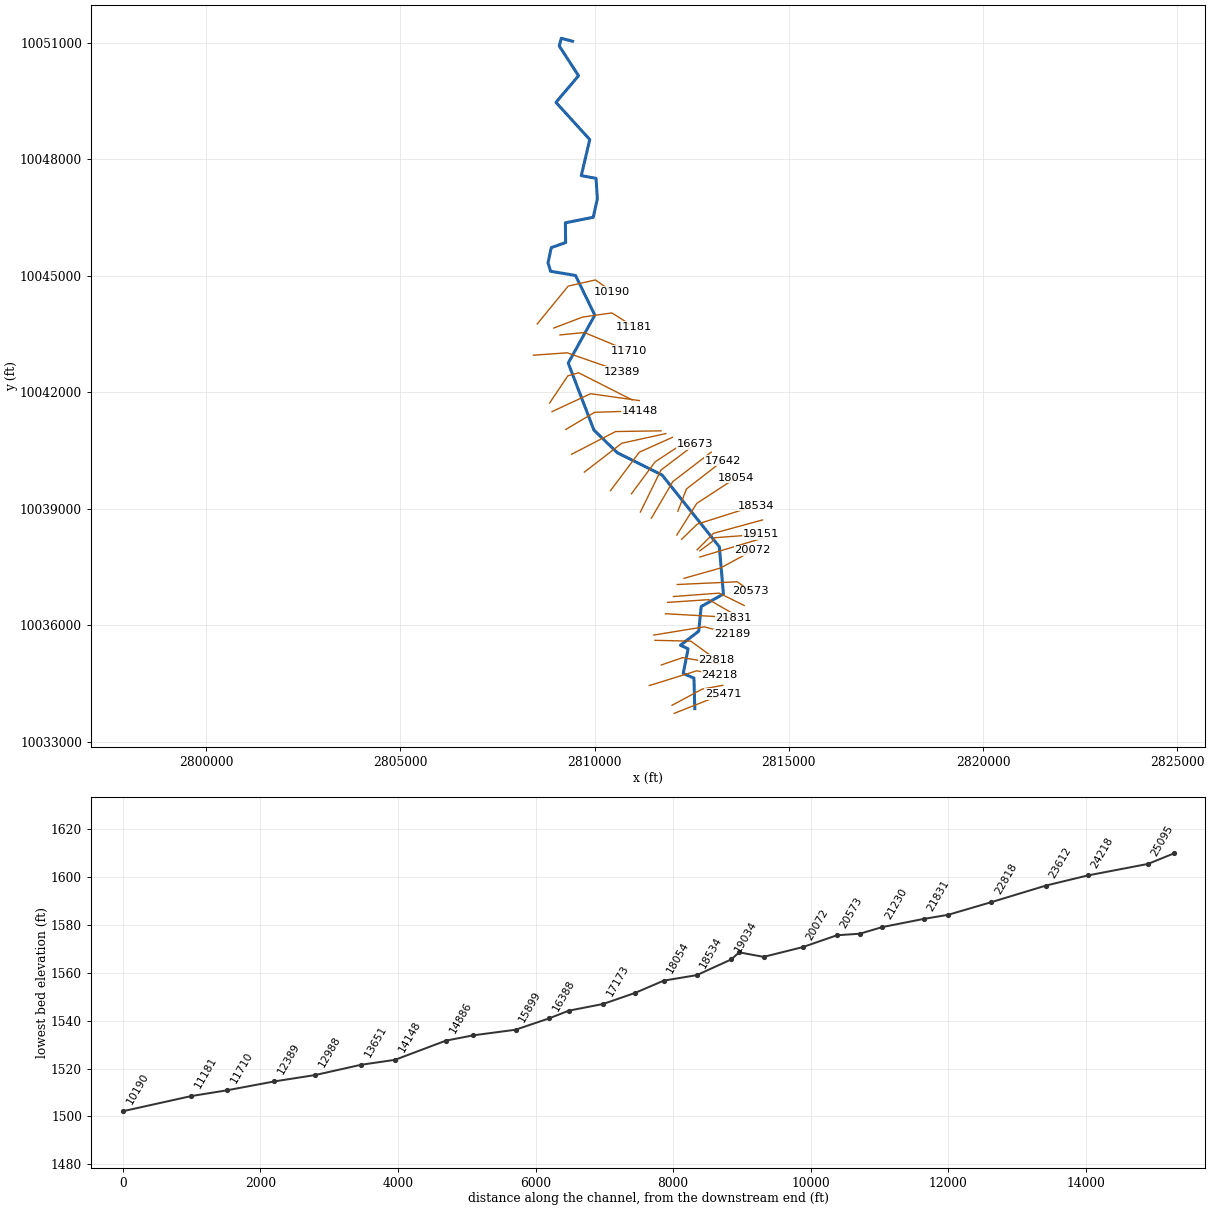
--- UNT060 IN SNOGR.prj (project) ---

Proj Title=UNT060 IN SNOGR Base Level Engineering
Current Plan=p01
Default Exp/Contr=0.3,0.1
English Units
Geom File=g01
Flow File=f01
Plan File=p01
BEGIN DESCRIPTION:
UNT060 IN SNOGR
END DESCRIPTION:

--- UNT060 IN SNOGR.p01 (plan) ---

Plan Title=Multiple Run
Short Identifier=Multiple
Geom File=g01
Flow File=f01
Subcritical Flow
K Sum by GR= 0
Std Step Tol= 0.01
Critical Tol= 0.01
Num of Std Step Trials= 20
Max Error Tol= 0.3
Flow Tol Ratio= 0.001
Split Flow NTrial= 30
Split Flow Tol= 0.02
Split Flow Ratio= 0.02
Log Output Level= 0
Friction Slope Method= 1
Unsteady Friction Slope Method= 2
Unsteady Bridges Friction Slope Method= 1
Parabolic Critical Depth
Global Vel Dist=  1 , 1 , 1
Global Log Level= 0
CheckData=True
Encroach Param= -1, 0, 0, 0
BEGIN DESCRIPTION:
Multiple Run
END DESCRIPTION:

--- UNT060 IN SNOGR.f01 (steady flow) ---

Flow Title=Multiple
Number of Profiles=7
Profile Names=10-year,25-year,50-year,1pct_min,100-year,1pct_plu,500-year
River Rch & RM= UNT060 IN SNOGR,Reach-1,25471
     913    1329    1691    1576    2131    2882    3398
River Rch & RM= UNT060 IN SNOGR,Reach-1,23612
    1277    1882    2414    2265    3063    4142    4949
River Rch & RM= UNT060 IN SNOGR,Reach-1,16388
    1575    2333    3004    2824    3819    5164    6200
River Rch & RM= UNT060 IN SNOGR,Reach-1,7803
    1775    2641    3410    3213    4346    5877    7089
River Rch & RM= UNT060 IN SNOGR,Reach-1,4726
    1883    2806    3627    3421    4626    6256    7559
Boundary for River Rch & Prof#=UNT060 IN SNOGR,Reach-1,1
Up Type=0
Dn Type=3
Dn Slope=0.005
Boundary for River Rch & Prof#=UNT060 IN SNOGR,Reach-1,2
Up Type=0
Dn Type=3
Dn Slope=0.005
Boundary for River Rch & Prof#=UNT060 IN SNOGR,Reach-1,3
Up Type=0
Dn Type=3
Dn Slope=0.005
Boundary for River Rch & Prof#=UNT060 IN SNOGR,Reach-1,4
Up Type=0
Dn Type=3
Dn Slope=0.005
Boundary for River Rch & Prof#=UNT060 IN SNOGR,Reach-1,5
Up Type=0
Dn Type=3
Dn Slope=0.005
Boundary for River Rch & Prof#=UNT060 IN SNOGR,Reach-1,6
Up Type=0
Dn Type=3
Dn Slope=0.005
Boundary for River Rch & Prof#=UNT060 IN SNOGR,Reach-1,7
Up Type=0
Dn Type=3
Dn Slope=0.005

--- UNT060 IN SNOGR.g01 (geometry) ---

Geom Title=Existing Conditions

River Reach=UNT060 IN SNOGR,Reach-1
Reach XY= 30
      2812578.48     10033852.97      2812556.66     10034638.39
      2812280.72     10034758.56      2812406.10     10035393.29
      2812210.02     10035483.43      2812679.92     10035847.12
      2812742.73     10036480.07      2813316.15     10036804.79
      2813210.31     10038019.34      2811735.60     10039867.35
      2810585.84     10040439.17      2809980.92     10041024.75
      2809320.48     10042748.12      2810005.59     10043982.51
      2809507.76     10045003.22      2808867.01     10045111.46
      2808799.94     10045329.52      2808884.55     10045721.09
      2809254.21     10045850.77      2809246.54     10046359.61
      2809964.92     10046501.67      2810070.49     10046980.32
      2810036.37     10047503.55      2809657.02     10047574.40
      2809874.69     10048502.13      2809004.26     10049459.94
      2809586.16     10050145.29      2809090.26     10050909.51
      2809141.36     10051107.85      2809431.73     10051032.90

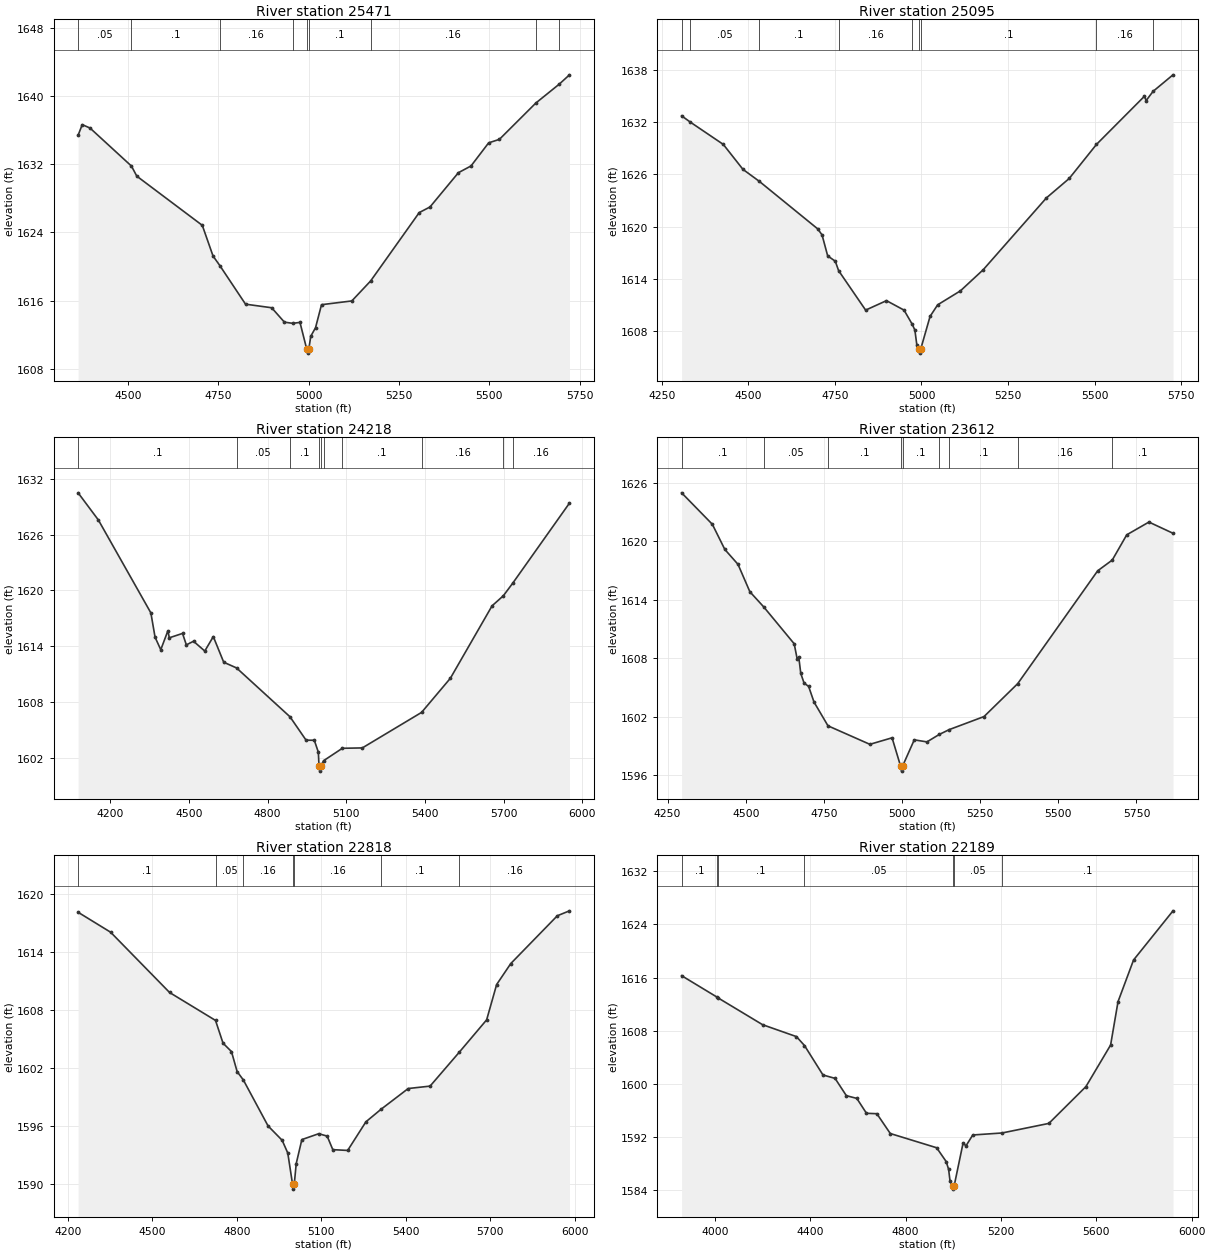
Type RM Length L Ch R = 1,25471,376,376,376
BEGIN DESCRIPTION:
UNT060 IN SNOGR 41.0
END DESCRIPTION:
XS GIS Cut Line= 2
      2812047.84     10033730.88      2813311.73     10034230.88
#Sta/Elev= 30
  4362.4 1635.42  4373.8 1636.67  4395.3 1636.27  4510.0 1631.80  4524.7 1630.62
  4705.9 1624.84  4735.6 1621.24  4754.3 1620.12  4825.5 1615.58  4897.8 1615.16
  4933.0 1613.47  4956.0 1613.33  4976.1 1613.44  4994.6 1610.33  4997.3 1609.83
  5000.6 1610.33  5006.0 1611.82  5019.1 1612.81  5035.7 1615.52  5119.5 1615.96
  5171.6 1618.31  5306.0 1626.34  5335.8 1627.00  5414.2 1631.02  5449.3 1631.82
  5498.0 1634.53  5527.7 1634.94  5628.6 1639.21  5693.1 1641.42  5721.6 1642.52
#Mann=9,-1,0
  4362.4    0.05       0  4510.0     0.1       0  4754.3    0.16       0
  4956.0     0.1       0  4994.6    0.07       0  5000.6     0.1       0
  5171.6    0.16       0  5628.6     0.1       0  5693.1    0.16       0
Bank Sta=4994.6,5000.6
Exp/Cntr=0.3,0.1

Type RM Length L Ch R = 1,25095,877,877,877
BEGIN DESCRIPTION:
UNT060 IN SNOGR 40.0
END DESCRIPTION:
XS GIS Cut Line= 3
      2811992.31     10033939.23      2812770.07     10034355.88
      2813297.86     10034453.11
#Sta/Elev= 30
  4307.4 1632.75  4332.4 1632.03  4427.8 1629.46  4484.5 1626.59  4531.8 1625.21
  4700.1 1619.75  4712.9 1619.05  4729.2 1616.63  4751.1 1616.02  4760.8 1614.93
  4838.8 1610.39  4899.0 1611.48  4949.7 1610.39  4973.5 1608.75  4981.0 1608.09
  4986.7 1606.37  4992.1 1605.94  4994.8 1605.44  4998.1 1605.94  5024.9 1609.67
  5046.8 1611.00  5112.6 1612.61  5178.4 1615.04  5361.0 1623.31  5426.7 1625.54
  5505.4 1629.46  5643.8 1635.00  5648.9 1634.51  5668.7 1635.56  5726.4 1637.47
#Mann=9,-1,0
  4307.4     0.1       0  4332.4    0.05       0  4531.8     0.1       0
  4760.8    0.16       0  4973.5     0.1       0  4992.1    0.07       0
  4998.1     0.1       0  5505.4    0.16       0  5668.7     0.1       0
Bank Sta=4992.1,4998.1
Exp/Cntr=0.3,0.1

Type RM Length L Ch R = 1,24218,606,606,606
BEGIN DESCRIPTION:
UNT060 IN SNOGR 39.0
END DESCRIPTION:
XS GIS Cut Line= 3
      2811408.23     10034446.23      2812629.49     10034826.77
      2813213.49     10034711.74
#Sta/Elev= 30
  4077.1 1630.47  4154.3 1627.56  4354.7 1617.59  4370.6 1614.99  4392.4 1613.64
  4419.7 1615.68  4424.9 1614.92  4475.4 1615.39  4490.0 1614.16  4517.3 1614.55
  4560.3 1613.50  4592.8 1615.05  4632.5 1612.30  4681.4 1611.69  4885.3 1606.45
  4946.7 1603.94  4978.1 1603.93  4993.5 1602.65  4996.1 1601.12  4998.8 1600.62
  5002.1 1601.12  5013.6 1601.74  5085.0 1603.07  5161.3 1603.11  5387.3 1606.92
  5497.1 1610.58  5656.2 1618.35  5699.2 1619.43  5735.3 1620.79  5951.5 1629.37
#Mann=10,-1,0
  4077.1     0.1       0  4681.4    0.05       0  4885.3     0.1       0
  4996.1    0.07       0  5002.1     0.1       0  5013.6    0.05       0
  5085.0     0.1       0  5387.3    0.16       0  5699.2     0.1       0
  5735.3    0.16       0
Bank Sta=4996.1,5002.1
Exp/Cntr=0.3,0.1

Type RM Length L Ch R = 1,23612,794,794,794
BEGIN DESCRIPTION:
UNT060 IN SNOGR 38.0
END DESCRIPTION:
XS GIS Cut Line= 3
      2811717.74     10034977.85      2812266.37     10035165.36
      2813244.41     10034998.89
#Sta/Elev= 30
  4295.0 1624.97  4393.3 1621.74  4433.2 1619.16  4475.4 1617.63  4513.3 1614.82
  4557.7 1613.26  4655.1 1609.48  4664.6 1607.93  4669.8 1608.10  4676.2 1606.43
  4686.8 1605.44  4701.2 1605.11  4718.5 1603.50  4763.2 1601.06  4897.2 1599.16
  4968.2 1599.83  4995.6 1596.91  4998.4 1596.41  5001.6 1596.91  5039.2 1599.62
  5079.8 1599.41  5119.5 1600.18  5151.0 1600.67  5262.4 1602.01  5370.2 1605.39
  5626.0 1616.97  5672.6 1618.07  5718.9 1620.66  5789.9 1621.97  5866.9 1620.82
#Mann=9,-1,0
  4295.0     0.1       0  4557.7    0.05       0  4763.2     0.1       0
  4995.6    0.07       0  5001.6     0.1       0  5119.5    0.16       0
  5151.0     0.1       0  5370.2    0.16       0  5672.6     0.1       0
Bank Sta=4995.6,5001.6
Exp/Cntr=0.3,0.1

Type RM Length L Ch R = 1,22818,629,629,629
BEGIN DESCRIPTION:
UNT060 IN SNOGR 37.0
END DESCRIPTION:
XS GIS Cut Line= 3
      2811553.56     10035611.24      2812475.47     10035590.41
      2813142.13     10035106.03
#Sta/Elev= 30
  4235.9 1618.11  4351.4 1616.05  4560.9 1609.82  4724.2 1606.93  4750.9 1604.58
  4780.9 1603.71  4801.0 1601.64  4823.0 1600.78  4911.0 1596.02  4961.0 1594.54
  4981.0 1593.22  4998.0 1589.99  5000.8 1589.49  5004.0 1589.99  5011.0 1592.13
  5031.0 1594.61  5091.0 1595.22  5121.0 1594.97  5141.0 1593.57  5193.8 1593.49
  5258.7 1596.45  5312.2 1597.74  5409.0 1599.89  5486.7 1600.14  5590.6 1603.65
  5687.7 1606.99  5723.2 1610.64  5773.5 1612.81  5938.9 1617.75  5982.1 1618.26
#Mann=7,-1,0
  4235.9     0.1       0  4724.2    0.05       0  4823.0    0.16       0
  4998.0    0.07       0  5004.0    0.16       0  5312.2     0.1       0
  5590.6    0.16       0
Bank Sta=4998,5004
Exp/Cntr=0.3,0.1

Type RM Length L Ch R = 1,22189,358,358,358
BEGIN DESCRIPTION:
UNT060 IN SNOGR 36.0
END DESCRIPTION:
XS GIS Cut Line= 3
      2811523.29     10035747.13      2812824.18     10035959.52
      2813540.99     10035764.83
#Sta/Elev= 30
  3860.9 1616.28  4008.8 1613.07  4013.3 1612.95  4200.5 1608.91  4342.4 1607.12
  4376.2 1605.78  4453.8 1601.35  4504.5 1600.84  4551.8 1598.24  4595.7 1597.83
  4636.2 1595.59  4679.7 1595.53  4736.1 1592.55  4930.5 1590.41  4970.6 1588.33
  4980.7 1587.16  4986.9 1585.34  4998.0 1584.69  5000.7 1584.19  5004.0 1584.69
  5041.5 1591.14  5053.4 1590.69  5082.0 1592.33  5204.6 1592.63  5401.1 1594.07
  5556.5 1599.60  5660.1 1605.85  5691.2 1612.37  5756.4 1618.64  5921.8 1626.03
#Mann=7,-1,0
  3860.9     0.1       0  4008.8    0.05       0  4013.3     0.1       0
  4376.2    0.05       0  4998.0    0.04       0  5004.0    0.05       0
  5204.6     0.1       0
Bank Sta=4998,5004
Exp/Cntr=0.3,0.1

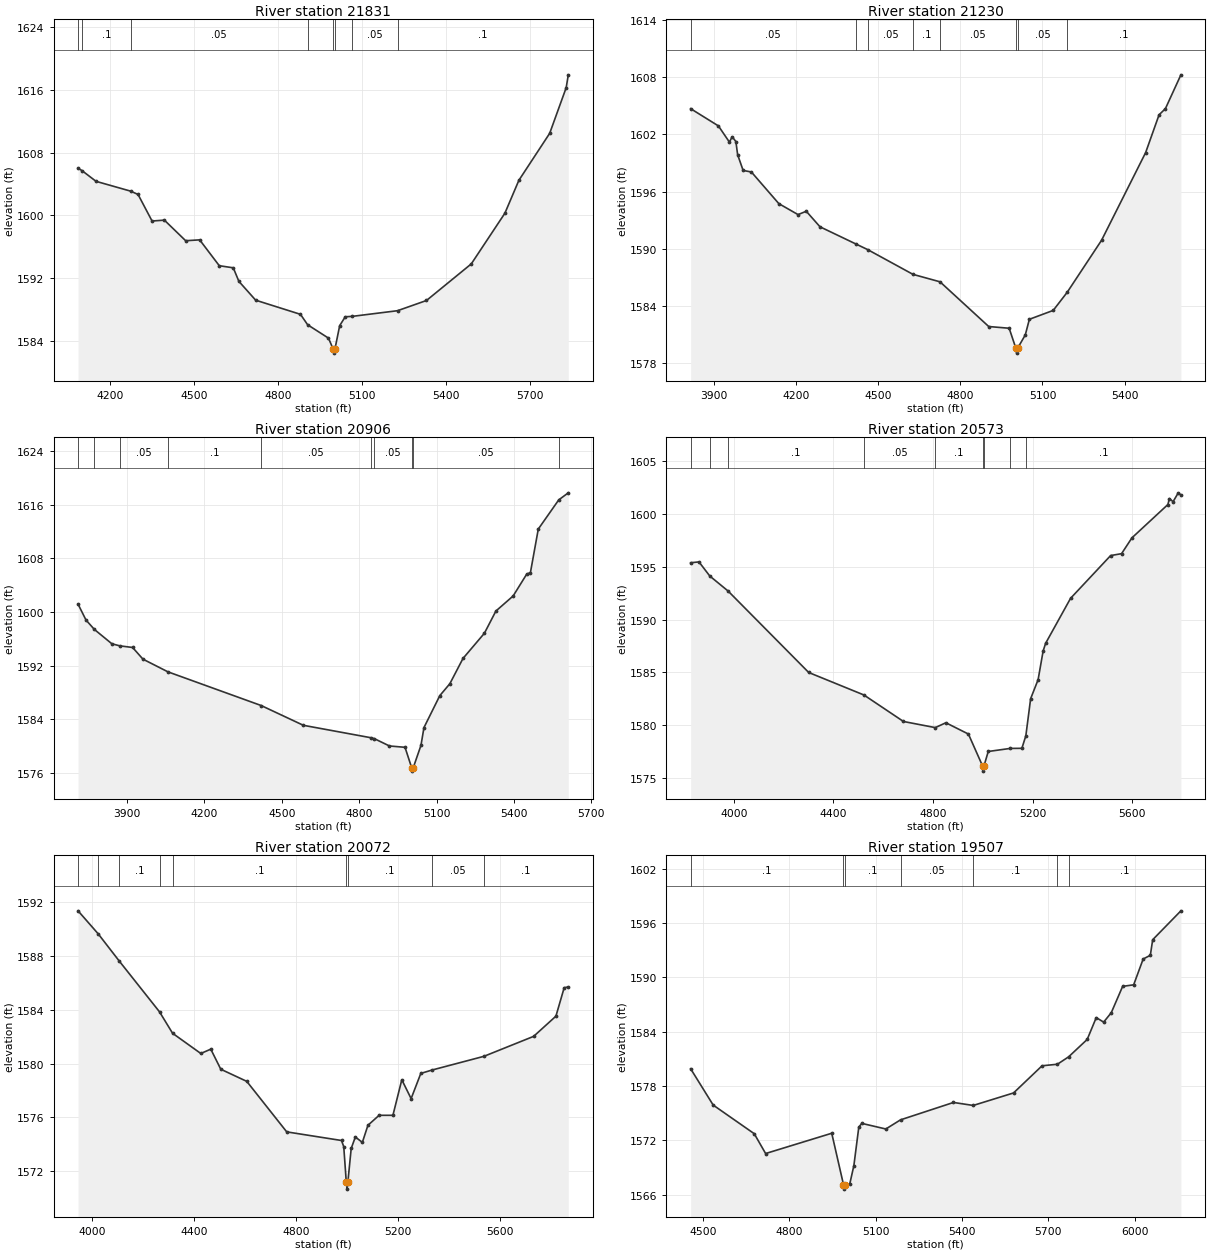
Type RM Length L Ch R = 1,21831,601,601,601
BEGIN DESCRIPTION:
UNT060 IN SNOGR 35.0
END DESCRIPTION:
XS GIS Cut Line= 2
      2811824.15     10036295.80      2813574.95     10036198.54
#Sta/Elev= 30
  4084.3 1606.00  4098.2 1605.70  4148.7 1604.33  4272.6 1603.08  4298.9 1602.66
  4349.0 1599.28  4393.1 1599.39  4469.2 1596.77  4519.3 1596.88  4589.4 1593.59
  4639.5 1593.32  4659.5 1591.60  4719.6 1589.20  4879.8 1587.40  4905.5 1586.07
  4980.0 1584.37  4997.0 1582.96  4999.8 1582.46  5003.0 1582.96  5020.1 1585.96
  5040.1 1587.09  5065.0 1587.14  5226.9 1587.86  5330.5 1589.16  5490.8 1593.82
  5611.0 1600.27  5661.0 1604.46  5771.2 1610.44  5830.3 1616.26  5837.8 1617.89
#Mann=8,-1,0
  4084.3    0.05       0  4098.2     0.1       0  4272.6    0.05       0
  4905.5     0.1       0  4997.0    0.07       0  5003.0     0.1       0
  5065.0    0.05       0  5226.9     0.1       0
Bank Sta=4997,5003
Exp/Cntr=0.3,0.1

Type RM Length L Ch R = 1,21230,324,324,324
BEGIN DESCRIPTION:
UNT060 IN SNOGR 34.0
END DESCRIPTION:
XS GIS Cut Line= 3
      2811877.30     10036587.84      2812939.22     10036658.63
      2813567.51     10036295.82
#Sta/Elev= 30
  3815.7 1604.70  3917.1 1602.89  3957.2 1601.19  3967.2 1601.76  3980.8 1601.25
  3987.2 1599.87  4007.3 1598.22  4037.4 1598.06  4137.6 1594.74  4207.7 1593.59
  4237.8 1593.94  4287.9 1592.31  4418.1 1590.52  4461.8 1589.92  4627.5 1587.32
  4726.1 1586.54  4903.9 1581.85  4978.5 1581.67  5003.1 1579.56  5005.9 1579.06
  5009.1 1579.56  5037.4 1580.97  5052.3 1582.61  5139.3 1583.54  5190.6 1585.45
  5315.9 1590.90  5476.7 1600.09  5525.8 1604.06  5548.9 1604.70  5605.5 1608.25
#Mann=8,-1,0
  3815.7    0.05       0  4418.1     0.1       0  4461.8    0.05       0
  4627.5     0.1       0  4726.1    0.05       0  5003.1    0.04       0
  5009.1    0.05       0  5190.6     0.1       0
Bank Sta=5003.1,5009.1
Exp/Cntr=0.3,0.1

Type RM Length L Ch R = 1,20906,333,333,333
BEGIN DESCRIPTION:
UNT060 IN SNOGR 33.0
END DESCRIPTION:
XS GIS Cut Line= 3
      2812027.70     10036738.28      2813204.71     10036826.78
      2813850.16     10036508.47
#Sta/Elev= 30
  3710.7 1601.19  3741.5 1598.82  3774.2 1597.41  3841.8 1595.28  3872.8 1594.97
  3922.1 1594.73  3962.2 1592.99  4058.9 1591.10  4420.2 1586.08  4583.9 1583.13
  4845.4 1581.28  4859.0 1581.14  4917.5 1580.05  4977.9 1579.85  5003.7 1576.80
  5006.5 1576.30  5009.7 1576.80  5039.7 1580.14  5051.3 1582.79  5112.7 1587.55
  5151.7 1589.33  5202.5 1593.09  5285.5 1596.85  5330.1 1600.16  5397.0 1602.41
  5449.5 1605.66  5463.9 1605.89  5494.4 1612.38  5573.7 1616.73  5610.7 1617.78
#Mann=10,-1,0
  3710.7    0.05       0  3774.2     0.1       0  3872.8    0.05       0
  4058.9     0.1       0  4420.2    0.05       0  4845.4     0.1       0
  4859.0    0.05       0  5003.7   0.035       0  5009.7    0.05       0
  5573.7     0.1       0
Bank Sta=5003.7,5009.7
Exp/Cntr=0.3,0.1

Type RM Length L Ch R = 1,20573,501,501,501
BEGIN DESCRIPTION:
UNT060 IN SNOGR 32.0
END DESCRIPTION:
XS GIS Cut Line= 3
      2812125.08     10037048.02      2813673.74     10037118.81
      2814010.03     10036871.02
#Sta/Elev= 30
  3826.9 1595.38  3860.3 1595.46  3903.8 1594.12  3976.8 1592.71  4300.8 1584.99
  4522.4 1582.86  4681.2 1580.35  4808.8 1579.77  4851.4 1580.23  4941.9 1579.16
  4998.5 1576.15  5001.3 1575.65  5004.5 1576.15  5021.5 1577.51  5109.7 1577.80
  5156.5 1577.81  5172.4 1578.99  5191.7 1582.51  5221.7 1584.31  5241.8 1587.02
  5251.8 1587.75  5351.9 1592.01  5512.8 1596.06  5556.7 1596.24  5598.4 1597.74
  5742.6 1600.89  5748.8 1601.46  5763.5 1601.16  5784.3 1602.00  5794.9 1601.80
#Mann=9,-1,0
  3826.9     0.1       0  3903.8    0.05       0  3976.8     0.1       0
  4522.4    0.05       0  4808.8     0.1       0  4998.5    0.07       0
  5004.5     0.1       0  5109.7    0.05       0  5172.4     0.1       0
Bank Sta=4998.5,5004.5
Exp/Cntr=0.3,0.1

Type RM Length L Ch R = 1,20072,565,565,565
BEGIN DESCRIPTION:
UNT060 IN SNOGR 31.0
END DESCRIPTION:
XS GIS Cut Line= 3
      2812302.04     10037207.31      2813240.11     10037472.80
      2814071.95     10037924.11
#Sta/Elev= 30
  3944.9 1591.34  4023.9 1589.63  4106.0 1587.62  4264.2 1583.84  4315.4 1582.25
  4426.0 1580.75  4465.1 1581.07  4504.3 1579.58  4606.1 1578.68  4762.7 1574.93
  4977.4 1574.29  4986.2 1573.83  4996.2 1571.18  4999.0 1570.68  5002.2 1571.18
  5015.4 1573.70  5031.6 1574.55  5059.1 1574.15  5081.0 1575.42  5124.7 1576.16
  5178.9 1576.16  5213.7 1578.80  5250.2 1577.40  5288.2 1579.27  5331.9 1579.52
  5535.8 1580.54  5730.3 1582.02  5817.7 1583.52  5850.0 1585.63  5866.2 1585.69
#Mann=9,-1,0
  3944.9     0.1       0  4023.9    0.05       0  4106.0     0.1       0
  4264.2    0.05       0  4315.4     0.1       0  4996.2    0.07       0
  5002.2     0.1       0  5331.9    0.05       0  5535.8     0.1       0
Bank Sta=4996.2,5002.2
Exp/Cntr=0.3,0.1

Type RM Length L Ch R = 1,19507,356,356,356
BEGIN DESCRIPTION:
UNT060 IN SNOGR 30.0
END DESCRIPTION:
XS GIS Cut Line= 2
      2812709.12     10037755.98      2814340.17     10038246.10
#Sta/Elev= 30
  4457.3 1579.92  4535.6 1575.91  4678.2 1572.75  4717.7 1570.56  4947.4 1572.80
  4988.2 1567.13  4991.0 1566.63  4994.2 1567.13  5010.0 1567.20  5024.3 1569.23
  5041.4 1573.47  5051.8 1573.89  5135.3 1573.27  5186.4 1574.28  5370.3 1576.20
  5438.9 1575.87  5579.0 1577.25  5678.1 1580.25  5731.4 1580.42  5770.4 1581.24
  5834.9 1583.16  5866.3 1585.57  5892.0 1585.07  5918.5 1586.11  5958.0 1589.02
  5996.3 1589.19  6029.3 1592.04  6054.2 1592.45  6062.4 1594.17  6160.4 1597.36
#Mann=7,-1,0
  4457.3     0.1       0  4988.2    0.07       0  4994.2     0.1       0
  5186.4    0.05       0  5438.9     0.1       0  5731.4    0.05       0
  5770.4     0.1       0
Bank Sta=4988.2,4994.2
Exp/Cntr=0.3,0.1

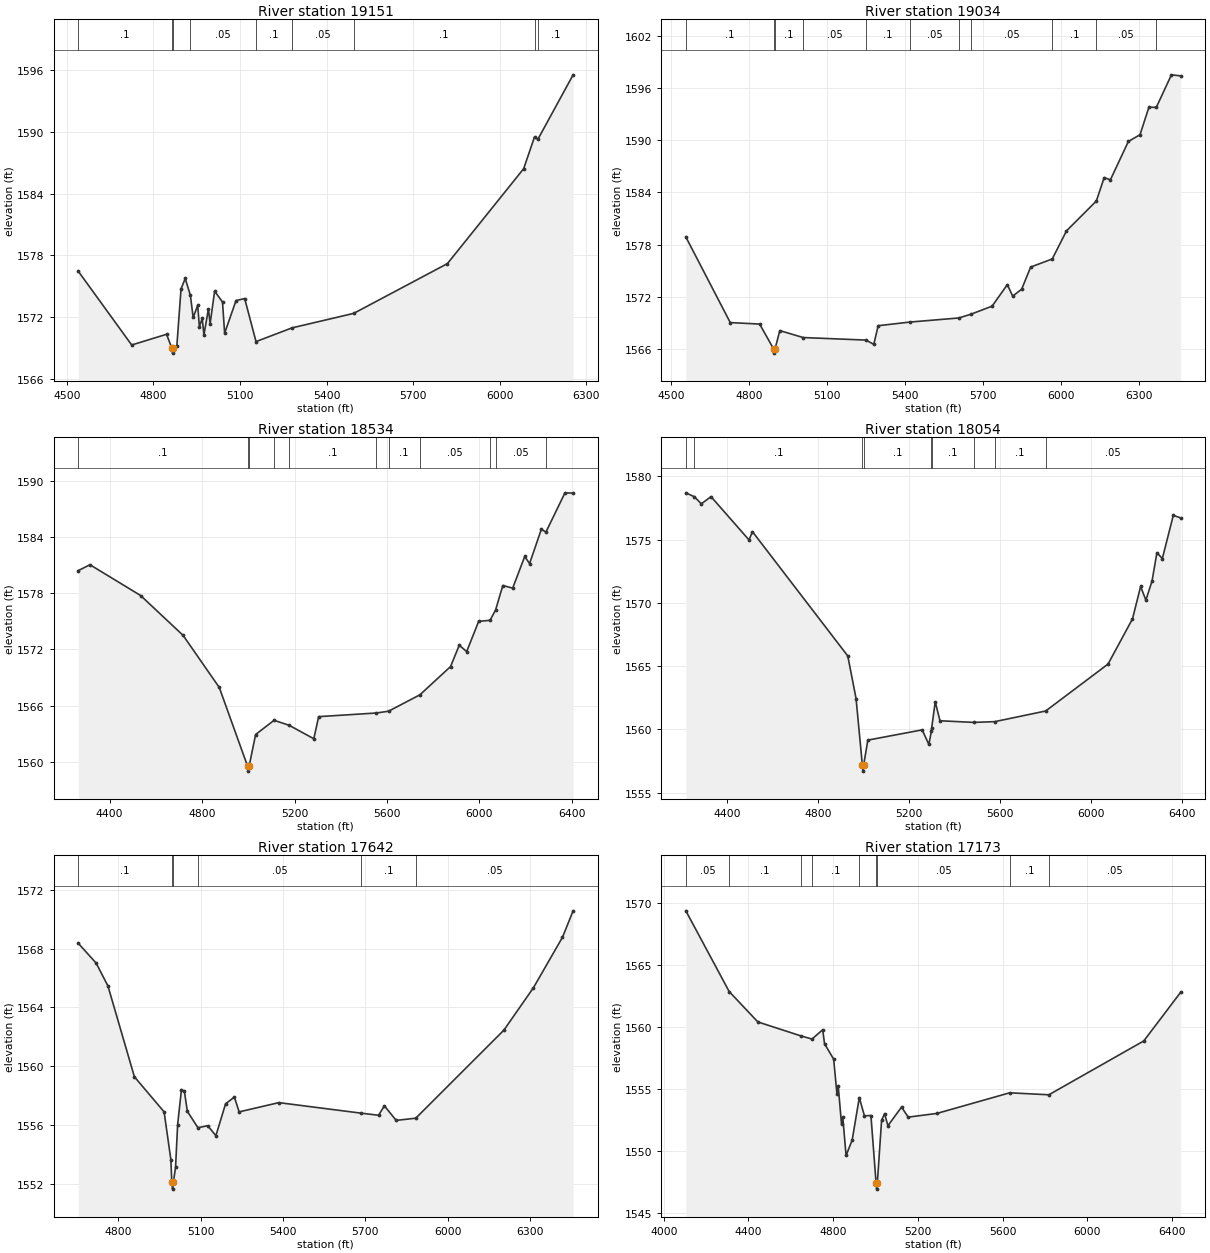
Type RM Length L Ch R = 1,19151,117,117,117
BEGIN DESCRIPTION:
Mapping XS 50db292d
END DESCRIPTION:
XS GIS Cut Line= 4
      2812709.11     10037915.26      2813018.87     10038145.37
      2813080.82     10038251.56      2814283.63     10038341.57
#Sta/Elev= 30
  4539.4 1576.46  4724.5 1569.30  4845.4 1570.34  4863.3 1569.01  4866.0 1568.51
  4869.3 1569.01  4880.9 1569.16  4895.5 1574.74  4910.1 1575.76  4927.9 1574.12
  4937.6 1571.97  4953.3 1573.15  4959.1 1571.07  4969.0 1571.89  4974.8 1570.27
  4990.5 1572.81  4996.3 1571.36  5012.0 1574.53  5039.3 1573.47  5046.6 1570.44
  5086.0 1573.61  5116.1 1573.81  5155.4 1569.63  5279.9 1570.96  5494.0 1572.37
  5818.7 1577.20  6083.1 1586.42  6120.6 1589.50  6132.1 1589.26  6254.4 1595.53
#Mann=9,-1,0
  4539.4     0.1       0  4863.3   0.035       0  4869.3     0.1       0
  4927.9    0.05       0  5155.4     0.1       0  5279.9    0.05       0
  5494.0     0.1       0  6120.6    0.05       0  6132.1     0.1       0
Bank Sta=4863.3,4869.3
Exp/Cntr=0.3,0.1

Type RM Length L Ch R = 1,19034,500,500,500
BEGIN DESCRIPTION:
UNT060 IN SNOGR 29.0
END DESCRIPTION:
XS GIS Cut Line= 3
      2812638.35     10037941.84      2813063.12     10038366.61
      2814322.81     10038710.51
#Sta/Elev= 30
  4555.3 1578.89  4726.4 1569.05  4839.6 1568.88  4893.1 1566.04  4895.9 1565.54
  4899.1 1566.04  4917.3 1568.13  5007.4 1567.33  5249.3 1567.04  5279.4 1566.55
  5296.3 1568.69  5418.5 1569.11  5607.0 1569.58  5653.7 1570.01  5735.3 1570.94
  5793.9 1573.41  5814.7 1572.09  5849.2 1572.89  5883.8 1575.43  5967.0 1576.36
  6021.9 1579.59  6136.9 1583.02  6167.1 1585.71  6191.1 1585.46  6260.2 1589.86
  6305.1 1590.64  6339.6 1593.81  6367.7 1593.77  6426.2 1597.52  6461.8 1597.40
#Mann=11,-1,0
  4555.3     0.1       0  4893.1    0.07       0  4899.1     0.1       0
  5007.4    0.05       0  5249.3     0.1       0  5418.5    0.05       0
  5607.0     0.1       0  5653.7    0.05       0  5967.0     0.1       0
  6136.9    0.05       0  6367.7     0.1       0
Bank Sta=4893.1,4899.1
Exp/Cntr=0.3,0.1

Type RM Length L Ch R = 1,18534,480,480,480
BEGIN DESCRIPTION:
UNT060 IN SNOGR 28.0
END DESCRIPTION:
XS GIS Cut Line= 3
      2812239.47     10038211.38      2812640.93     10038601.99
      2814148.09     10039079.08
#Sta/Elev= 30
  4264.4 1580.41  4314.9 1581.04  4534.1 1577.75  4718.0 1573.49  4874.4 1567.93
  4997.3 1559.49  5000.0 1558.99  5003.3 1559.49  5031.7 1562.90  5111.5 1564.42
  5176.5 1563.89  5283.5 1562.45  5304.4 1564.81  5554.2 1565.20  5606.7 1565.39
  5742.4 1567.14  5875.1 1570.16  5912.8 1572.44  5944.9 1571.76  5996.7 1574.99
  6045.7 1575.10  6069.8 1576.19  6101.2 1578.82  6144.0 1578.54  6196.0 1581.92
  6217.0 1581.16  6268.0 1584.83  6287.9 1584.53  6370.1 1588.72  6405.4 1588.69
#Mann=11,-1,0
  4264.4     0.1       0  4997.3    0.07       0  5003.3     0.1       0
  5111.5    0.05       0  5176.5     0.1       0  5554.2    0.05       0
  5606.7     0.1       0  5742.4    0.05       0  6045.7     0.1       0
  6069.8    0.05       0  6287.9     0.1       0
Bank Sta=4997.3,5003.3
Exp/Cntr=0.3,0.1

Type RM Length L Ch R = 1,18054,412,412,412
BEGIN DESCRIPTION:
UNT060 IN SNOGR 27.0
END DESCRIPTION:
XS GIS Cut Line= 3
      2812116.23     10038322.38      2812629.49     10039136.52
      2813646.00     10039799.46
#Sta/Elev= 30
  4217.4 1578.70  4255.0 1578.39  4285.6 1577.83  4328.0 1578.40  4495.1 1574.98
  4510.4 1575.63  4929.5 1565.81  4966.0 1562.44  4993.5 1557.21  4996.3 1556.71
  4999.5 1557.21  5017.7 1559.16  5256.6 1559.97  5286.0 1558.82  5297.2 1559.86
  5298.3 1560.09  5314.0 1562.19  5335.0 1560.69  5484.4 1560.56  5575.8 1560.62
  5799.6 1561.46  6074.0 1565.17  6181.5 1568.74  6217.3 1571.30  6240.4 1570.22
  6267.5 1571.73  6288.9 1573.97  6312.8 1573.51  6361.0 1576.92  6393.4 1576.72
#Mann=9,-1,0
  4217.4    0.05       0  4255.0     0.1       0  4993.5    0.07       0
  4999.5     0.1       0  5297.2    0.05       0  5298.3     0.1       0
  5484.4    0.05       0  5575.8     0.1       0  5799.6    0.05       0
Bank Sta=4993.5,4999.5
Exp/Cntr=0.3,0.1

Type RM Length L Ch R = 1,17642,469,469,469
BEGIN DESCRIPTION:
UNT060 IN SNOGR 26.0
END DESCRIPTION:
XS GIS Cut Line= 3
      2812142.77     10038933.00      2812364.00     10039508.20
      2813302.09     10040233.90
#Sta/Elev= 30
  4654.6 1568.36  4719.7 1567.01  4762.5 1565.46  4859.0 1559.27  4967.2 1556.88
  4991.8 1553.63  4995.2 1552.12  4998.0 1551.62  5001.2 1552.12  5008.9 1553.11
  5016.5 1556.02  5030.4 1558.40  5041.1 1558.28  5051.8 1556.92  5090.4 1555.80
  5125.8 1555.94  5155.8 1555.26  5191.1 1557.43  5223.2 1557.89  5240.4 1556.88
  5385.1 1557.51  5685.8 1556.79  5748.2 1556.65  5769.6 1557.29  5812.5 1556.30
  5883.7 1556.45  6204.5 1562.44  6312.3 1565.33  6418.2 1568.77  6456.9 1570.57
#Mann=6,-1,0
  4654.6     0.1       0  4995.2    0.07       0  5001.2     0.1       0
  5090.4    0.05       0  5685.8     0.1       0  5883.7    0.05       0
Bank Sta=4995.2,5001.2
Exp/Cntr=0.3,0.1

Type RM Length L Ch R = 1,17173,500,500,500
BEGIN DESCRIPTION:
UNT060 IN SNOGR 25.0
END DESCRIPTION:
XS GIS Cut Line= 3
      2811461.33     10038755.97      2812010.02     10039694.05
      2813001.17     10040455.11
#Sta/Elev= 30
  4104.5 1569.38  4309.0 1562.88  4444.5 1560.43  4646.7 1559.31  4700.2 1559.05
  4750.7 1559.80  4759.4 1558.67  4802.4 1557.43  4818.1 1554.60  4823.9 1555.27
  4839.6 1552.19  4845.4 1552.78  4861.0 1549.67  4889.7 1550.90  4923.5 1554.33
  4947.6 1552.87  4978.4 1552.89  5002.7 1547.46  5005.4 1546.96  5008.7 1547.46
  5028.7 1552.50  5042.9 1553.04  5058.6 1552.07  5123.0 1553.57  5154.4 1552.76
  5290.2 1553.06  5633.7 1554.72  5818.5 1554.56  6266.8 1558.90  6440.9 1562.82
#Mann=9,-1,0
  4104.5    0.05       0  4309.0     0.1       0  4646.7    0.05       0
  4700.2     0.1       0  4923.5    0.05       0  5002.7    0.04       0
  5008.7    0.05       0  5633.7     0.1       0  5818.5    0.05       0
Bank Sta=5002.7,5008.7
Exp/Cntr=0.3,0.1

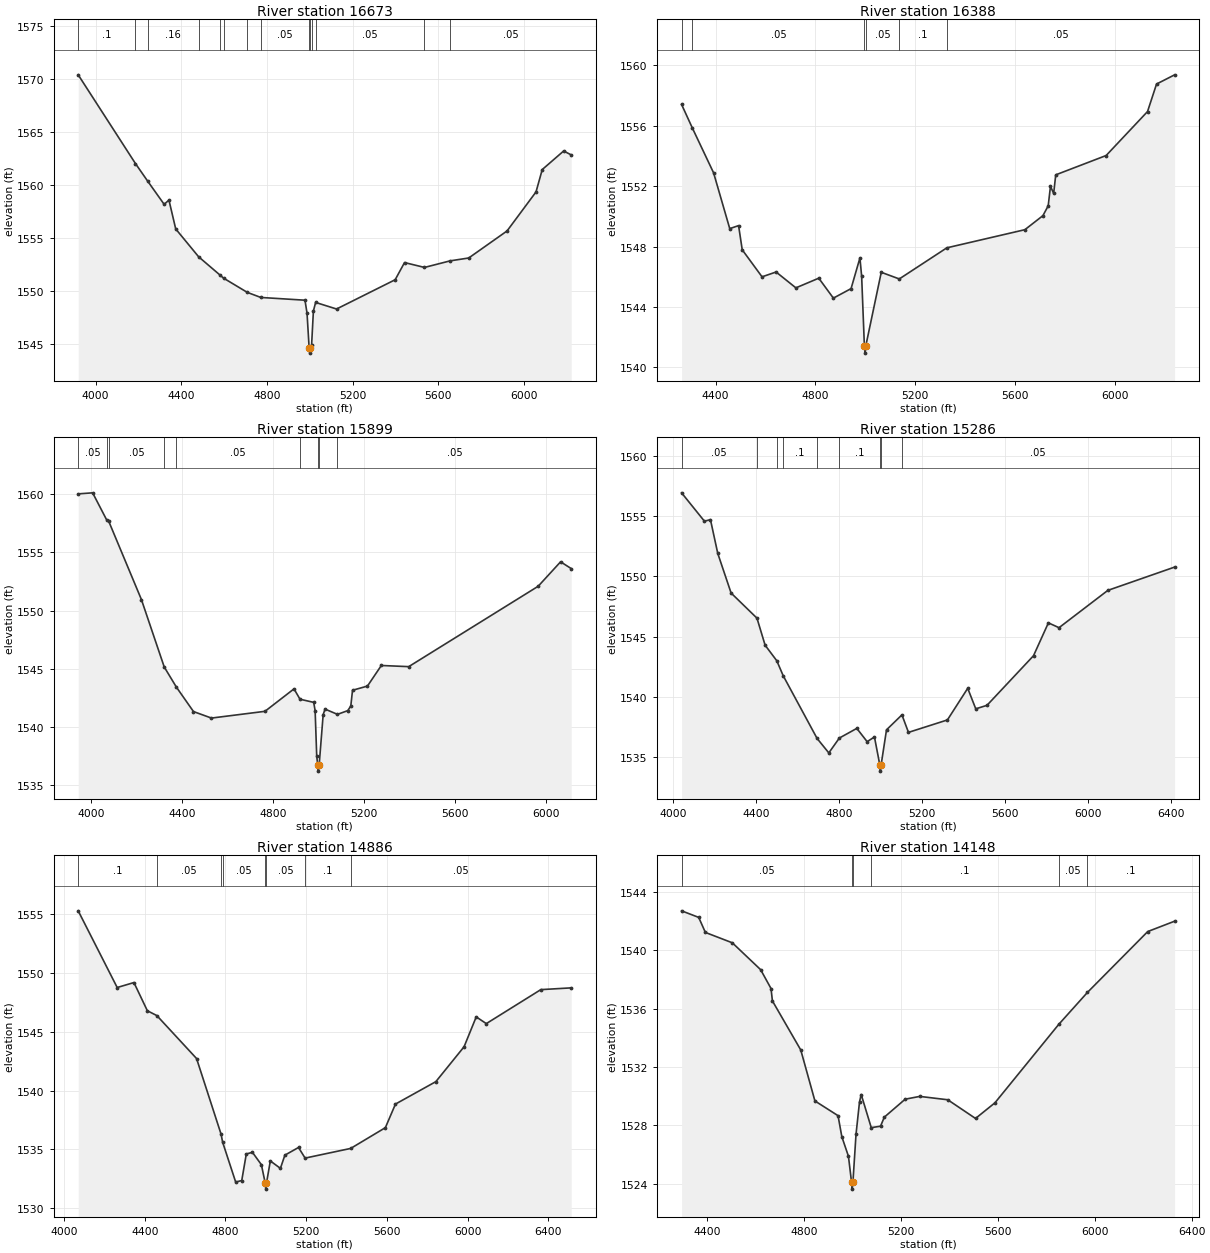
Type RM Length L Ch R = 1,16673,285,285,285
BEGIN DESCRIPTION:
UNT060 IN SNOGR 24.0
END DESCRIPTION:
XS GIS Cut Line= 3
      2811178.15     10038915.26      2811709.13     10039994.93
      2812584.36     10040657.98
#Sta/Elev= 30
  3918.6 1570.40  4186.0 1562.03  4242.8 1560.38  4319.8 1558.19  4342.2 1558.59
  4373.8 1555.87  4480.9 1553.24  4578.8 1551.55  4597.1 1551.23  4707.7 1549.89
  4770.9 1549.41  4977.1 1549.15  4986.7 1547.93  4996.5 1544.66  4999.3 1544.16
  5002.5 1544.66  5008.1 1544.94  5016.4 1548.13  5026.8 1548.94  5124.5 1548.32
  5398.1 1551.08  5441.8 1552.70  5534.9 1552.24  5654.7 1552.86  5741.4 1553.13
  5920.3 1555.68  6055.5 1559.36  6084.6 1561.47  6184.5 1563.22  6219.8 1562.85
#Mann=14,-1,0
  3918.6     0.1       0  4186.0    0.05       0  4242.8    0.16       0
  4480.9    0.05       0  4578.8     0.1       0  4597.1    0.05       0
  4707.7     0.1       0  4770.9    0.05       0  4996.5   0.035       0
  5002.5    0.05       0  5008.1     0.1       0  5026.8    0.05       0
  5534.9     0.1       0  5654.7    0.05       0
Bank Sta=4996.5,5002.5
Exp/Cntr=0.3,0.1

Type RM Length L Ch R = 1,16388,489,489,489
BEGIN DESCRIPTION:
UNT060 IN SNOGR 23.0
END DESCRIPTION:
XS GIS Cut Line= 3
      2810948.07     10039384.32      2811558.69     10040207.32
      2812353.78     10040728.55
#Sta/Elev= 30
  4263.6 1557.41  4306.5 1555.86  4391.9 1552.88  4456.6 1549.19  4492.0 1549.39
  4506.6 1547.79  4586.0 1546.00  4642.3 1546.32  4721.6 1545.27  4813.3 1545.91
  4871.8 1544.59  4942.7 1545.22  4978.2 1547.25  4985.1 1546.04  4996.0 1541.45
  4998.8 1540.95  5002.0 1541.45  5063.7 1546.30  5135.9 1545.86  5326.5 1547.92
  5639.2 1549.12  5711.5 1550.05  5732.6 1550.70  5741.7 1551.99  5754.5 1551.52
  5762.8 1552.75  5964.8 1554.03  6130.6 1556.94  6166.7 1558.76  6239.1 1559.37
#Mann=6,-1,0
  4263.6     0.1       0  4306.5    0.05       0  4996.0    0.04       0
  5002.0    0.05       0  5135.9     0.1       0  5326.5    0.05       0
Bank Sta=4996,5002
Exp/Cntr=0.3,0.1

Type RM Length L Ch R = 1,15899,613,613,613
BEGIN DESCRIPTION:
UNT060 IN SNOGR 22.0
END DESCRIPTION:
XS GIS Cut Line= 3
      2810408.22     10039463.92      2811151.61     10040455.11
      2812001.19     10040835.65
#Sta/Elev= 30
  3943.0 1560.03  4006.6 1560.12  4067.6 1557.82  4077.5 1557.67  4221.2 1550.95
  4321.7 1545.15  4375.2 1543.42  4450.4 1541.32  4529.5 1540.76  4765.0 1541.34
  4892.8 1543.27  4919.2 1542.38  4979.5 1542.11  4985.8 1541.40  4992.8 1537.49
  4997.4 1536.70  5000.1 1536.20  5003.4 1536.70  5021.2 1541.06  5029.5 1541.53
  5084.1 1541.08  5129.5 1541.40  5142.8 1541.80  5150.4 1543.15  5216.1 1543.51
  5277.2 1545.28  5397.7 1545.18  5967.5 1552.09  6066.1 1554.19  6112.9 1553.61
#Mann=9,-1,0
  3943.0    0.05       0  4067.6     0.1       0  4077.5    0.05       0
  4321.7    0.16       0  4375.2    0.05       0  4919.2     0.1       0
  4997.4    0.07       0  5003.4     0.1       0  5084.1    0.05       0
Bank Sta=4997.4,5003.4
Exp/Cntr=0.3,0.1

Type RM Length L Ch R = 1,15286,400,400,400
BEGIN DESCRIPTION:
UNT060 IN SNOGR 21.0
END DESCRIPTION:
XS GIS Cut Line= 3
      2809735.71     10039941.86      2810700.28     10040685.20
      2811833.03     10040932.99
#Sta/Elev= 30
  4040.1 1556.92  4150.3 1554.57  4179.3 1554.70  4214.6 1551.90  4278.9 1548.62
  4403.6 1546.54  4442.9 1544.30  4499.2 1543.01  4530.1 1541.77  4693.4 1536.58
  4750.0 1535.38  4800.8 1536.61  4885.0 1537.41  4934.8 1536.31  4970.1 1536.70
  4996.1 1534.37  4998.9 1533.87  5002.1 1534.37  5028.2 1537.29  5102.6 1538.53
  5134.1 1537.08  5321.9 1538.11  5419.8 1540.73  5458.6 1539.03  5512.7 1539.32
  5737.1 1543.43  5808.8 1546.15  5860.0 1545.75  6095.4 1548.84  6417.4 1550.77
#Mann=9,-1,0
  4040.1    0.05       0  4403.6     0.1       0  4499.2    0.05       0
  4530.1     0.1       0  4693.4    0.16       0  4800.8     0.1       0
  4996.1    0.07       0  5002.1     0.1       0  5102.6    0.05       0
Bank Sta=4996.1,5002.1
Exp/Cntr=0.3,0.1

Type RM Length L Ch R = 1,14886,738,738,738
BEGIN DESCRIPTION:
UNT060 IN SNOGR 20.0
END DESCRIPTION:
XS GIS Cut Line= 3
      2809408.21     10040402.00      2810540.98     10040986.09
      2811709.16     10041003.79
#Sta/Elev= 30
  4070.4 1555.23  4263.6 1548.73  4346.6 1549.15  4413.1 1546.76  4460.2 1546.35
  4656.9 1542.71  4778.5 1536.29  4786.0 1535.62  4850.7 1532.24  4880.8 1532.37
  4903.3 1534.62  4933.7 1534.76  4978.1 1533.71  4997.2 1532.14  5000.0 1531.64
  5003.2 1532.14  5022.4 1534.03  5072.3 1533.40  5094.5 1534.52  5162.0 1535.17
  5194.7 1534.27  5420.6 1535.09  5592.4 1536.85  5642.4 1538.85  5842.4 1540.75
  5982.4 1543.71  6042.5 1546.24  6092.5 1545.67  6362.5 1548.55  6513.2 1548.70
#Mann=8,-1,0
  4070.4     0.1       0  4460.2    0.05       0  4778.5     0.1       0
  4786.0    0.05       0  4997.2    0.04       0  5003.2    0.05       0
  5194.7     0.1       0  5420.6    0.05       0
Bank Sta=4997.2,5003.2
Exp/Cntr=0.3,0.1

Type RM Length L Ch R = 1,14148,497,497,497
BEGIN DESCRIPTION:
UNT060 IN SNOGR 19.0
END DESCRIPTION:
XS GIS Cut Line= 3
      2809257.83     10041039.21      2810001.16     10041481.66
      2811169.28     10041517.06
#Sta/Elev= 30
  4296.0 1542.70  4366.6 1542.25  4394.2 1541.22  4505.3 1540.51  4622.1 1538.67
  4664.9 1537.38  4670.7 1536.53  4787.6 1533.17  4846.0 1529.68  4941.4 1528.67
  4957.0 1527.23  4984.3 1525.89  4996.9 1524.14  4999.6 1523.64  5002.9 1524.14
  5015.5 1527.39  5029.9 1529.61  5036.9 1530.12  5078.4 1527.85  5116.7 1527.95
  5132.3 1528.57  5218.4 1529.80  5278.4 1529.99  5393.9 1529.76  5508.5 1528.48
  5588.5 1529.55  5851.6 1534.92  5970.0 1537.11  6218.8 1541.28  6329.7 1541.99
#Mann=6,-1,0
  4296.0    0.05       0  4996.9    0.04       0  5002.9    0.05       0
  5078.4     0.1       0  5851.6    0.05       0  5970.0     0.1       0
Bank Sta=4996.9,5002.9
Exp/Cntr=0.3,0.1

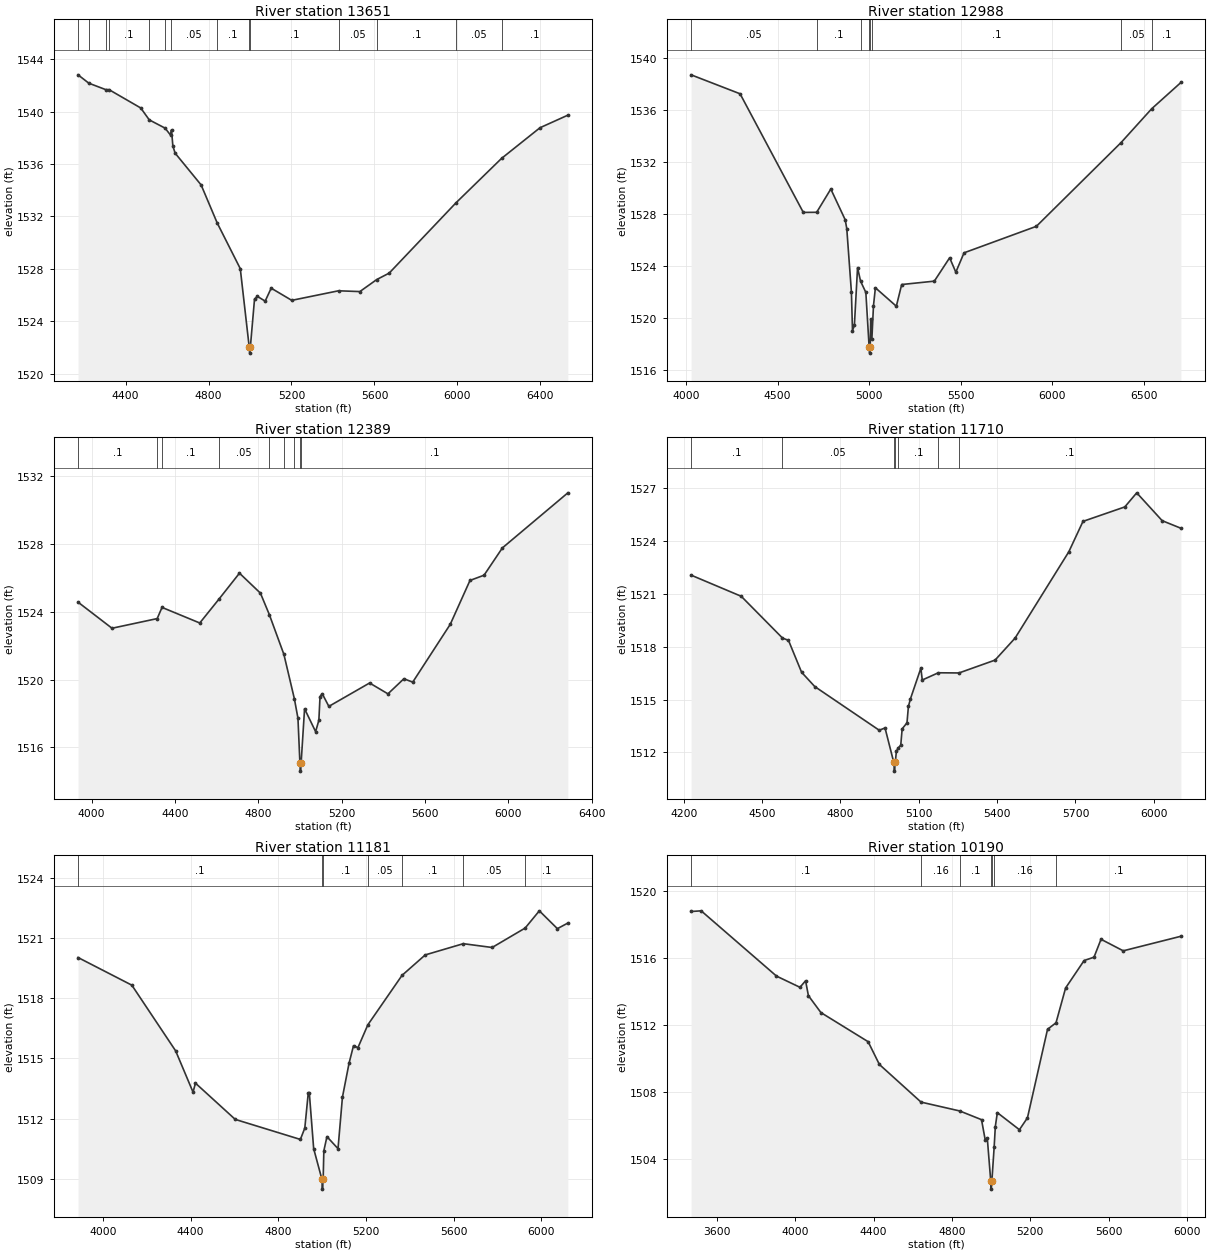
Type RM Length L Ch R = 1,13651,663,663,663
BEGIN DESCRIPTION:
UNT060 IN SNOGR 18.0
END DESCRIPTION:
XS GIS Cut Line= 3
      2808903.80     10041499.36      2809894.96     10041959.54
      2811151.58     10041782.55
#Sta/Elev= 30
  4170.8 1542.81  4223.0 1542.17  4304.4 1541.68  4320.1 1541.68  4473.1 1540.28
  4514.3 1539.37  4590.5 1538.74  4616.7 1538.21  4621.5 1538.61  4628.0 1537.38
  4638.9 1536.83  4764.4 1534.40  4841.8 1531.50  4953.1 1528.01  4995.9 1522.06
  4998.6 1521.56  5001.9 1522.06  5021.8 1525.69  5035.9 1525.89  5073.1 1525.53
  5102.1 1526.52  5201.3 1525.59  5426.8 1526.32  5529.7 1526.26  5611.3 1527.18
  5671.1 1527.67  5992.7 1533.03  6213.0 1536.43  6398.2 1538.77  6532.6 1539.73
#Mann=14,-1,0
  4170.8    0.05       0  4223.0     0.1       0  4304.4    0.05       0
  4320.1     0.1       0  4514.3    0.05       0  4590.5     0.1       0
  4616.7    0.05       0  4841.8     0.1       0  4995.9    0.07       0
  5001.9     0.1       0  5426.8    0.05       0  5611.3     0.1       0
  5992.7    0.05       0  6213.0     0.1       0
Bank Sta=4995.9,5001.9
Exp/Cntr=0.3,0.1

Type RM Length L Ch R = 1,12988,599,599,599
BEGIN DESCRIPTION:
UNT060 IN SNOGR 17.0
END DESCRIPTION:
XS GIS Cut Line= 4
      2808841.86     10041720.59      2809310.89     10042419.72
      2809585.23     10042499.37      2810964.59     10041800.84
#Sta/Elev= 30
  4028.2 1538.71  4295.6 1537.25  4640.7 1528.12  4713.7 1528.13  4790.8 1529.92
  4869.5 1527.55  4878.0 1526.87  4903.2 1522.01  4909.2 1519.01  4919.6 1519.44
  4936.8 1523.87  4953.2 1522.83  4982.1 1521.96  4999.9 1517.79  5002.7 1517.29
  5005.9 1517.79  5009.1 1519.92  5014.9 1518.36  5023.8 1520.95  5034.2 1522.32
  5148.5 1520.90  5177.7 1522.57  5355.9 1522.83  5439.5 1524.63  5473.2 1523.52
  5518.1 1525.01  5912.9 1527.05  6375.5 1533.50  6542.4 1536.10  6701.9 1538.12
#Mann=8,-1,0
  4028.2    0.05       0  4713.7     0.1       0  4953.2    0.05       0
  4999.9   0.035       0  5005.9    0.05       0  5014.9     0.1       0
  6375.5    0.05       0  6542.4     0.1       0
Bank Sta=4999.9,5005.9
Exp/Cntr=0.3,0.1

Type RM Length L Ch R = 1,12389,679,679,679
BEGIN DESCRIPTION:
UNT060 IN SNOGR 16.0
END DESCRIPTION:
XS GIS Cut Line= 3
      2808425.93     10042950.70      2809293.19     10043012.64
      2810691.42     10042525.92
#Sta/Elev= 30
  3935.2 1524.57  4098.2 1523.03  4315.0 1523.60  4338.1 1524.26  4519.2 1523.34
  4610.8 1524.74  4709.7 1526.28  4810.3 1525.10  4852.8 1523.84  4922.8 1521.49
  4973.1 1518.87  4990.3 1517.72  4999.6 1515.10  5002.4 1514.60  5005.6 1515.10
  5022.0 1518.28  5075.0 1516.93  5090.6 1517.60  5096.2 1519.00  5106.7 1519.17
  5138.5 1518.42  5334.0 1519.80  5422.0 1519.16  5498.5 1520.05  5540.9 1519.85
  5720.9 1523.26  5815.6 1525.85  5883.1 1526.16  5971.1 1527.77  6285.2 1531.02
#Mann=9,-1,0
  3935.2     0.1       0  4315.0    0.05       0  4338.1     0.1       0
  4610.8    0.05       0  4852.8     0.1       0  4922.8    0.05       0
  4973.1     0.1       0  4999.6    0.07       0  5005.6     0.1       0
Bank Sta=4999.6,5005.6
Exp/Cntr=0.3,0.1

Type RM Length L Ch R = 1,11710,529,529,529
BEGIN DESCRIPTION:
UNT060 IN SNOGR 15.0
END DESCRIPTION:
XS GIS Cut Line= 3
      2809107.39     10043472.83      2809735.67     10043534.77
      2810884.75     10043057.46
#Sta/Elev= 30
  4228.2 1522.06  4420.2 1520.86  4578.2 1518.49  4601.1 1518.36  4651.3 1516.55
  4701.6 1515.74  4948.6 1513.26  4970.8 1513.39  5004.2 1511.44  5006.9 1510.94
  5010.2 1511.44  5014.2 1512.06  5021.7 1512.26  5031.0 1512.41  5036.4 1513.34
  5054.9 1513.68  5060.3 1514.61  5068.3 1515.05  5108.0 1516.78  5113.4 1516.11
  5174.8 1516.52  5254.0 1516.51  5392.2 1517.24  5468.9 1518.49  5674.7 1523.39
  5728.8 1525.11  5888.9 1525.93  5934.6 1526.73  6032.0 1525.15  6103.8 1524.72
#Mann=7,-1,0
  4228.2     0.1       0  4578.2    0.05       0  5004.2    0.04       0
  5010.2    0.05       0  5021.7     0.1       0  5174.8    0.05       0
  5254.0     0.1       0
Bank Sta=5004.2,5010.2
Exp/Cntr=0.3,0.1

Type RM Length L Ch R = 1,11181,991,991,991
BEGIN DESCRIPTION:
UNT060 IN SNOGR 14.0
END DESCRIPTION:
XS GIS Cut Line= 4
      2808948.04     10043649.81      2809691.42     10043933.00
      2810443.64     10044039.20      2811018.89     10043676.34
#Sta/Elev= 30
  3886.1 1520.04  4131.6 1518.66  4331.6 1515.38  4410.9 1513.32  4421.9 1513.77
  4603.5 1511.96  4900.8 1510.96  4921.0 1511.53  4936.7 1513.28  4941.7 1513.26
  4961.4 1510.50  4998.8 1508.98  5001.5 1508.48  5004.8 1508.98  5007.8 1510.39
  5022.0 1511.10  5072.5 1510.50  5092.7 1513.07  5123.0 1514.77  5143.2 1515.64
  5163.4 1515.54  5208.6 1516.68  5364.7 1519.15  5470.6 1520.17  5644.3 1520.73
  5775.8 1520.54  5926.5 1521.51  5991.2 1522.37  6073.6 1521.48  6121.4 1521.76
#Mann=7,-1,0
  3886.1     0.1       0  4998.8    0.07       0  5004.8     0.1       0
  5208.6    0.05       0  5364.7     0.1       0  5644.3    0.05       0
  5926.5     0.1       0
Bank Sta=4998.8,5004.8
Exp/Cntr=0.3,0.1

Type RM Length L Ch R = 1,10190,1246,1246,1246
BEGIN DESCRIPTION:
UNT060 IN SNOGR 13.0
END DESCRIPTION:
XS GIS Cut Line= 4
      2808523.25     10043755.98      2809319.74     10044729.46
      2810018.86     10044888.76      2810451.88     10044588.29
#Sta/Elev= 30
  3467.5 1518.76  3519.0 1518.80  3903.7 1514.90  4023.6 1514.23  4052.3 1514.62
  4066.7 1513.73  4130.6 1512.72  4371.7 1510.98  4429.2 1509.62  4642.0 1507.37
  4839.9 1506.84  4950.9 1506.32  4970.1 1505.09  4980.4 1505.22  4997.9 1502.67
  5000.7 1502.17  5003.9 1502.67  5015.6 1504.71  5021.4 1505.91  5031.7 1506.74
  5144.5 1505.72  5185.5 1506.43  5288.1 1511.72  5331.4 1512.11  5380.4 1514.19
  5474.9 1515.83  5525.5 1516.03  5561.3 1517.10  5674.8 1516.41  5969.4 1517.28
#Mann=7,-1,0
  3467.5     0.1       0  4642.0    0.16       0  4839.9     0.1       0
  4997.9    0.07       0  5003.9     0.1       0  5015.6    0.16       0
  5331.4     0.1       0
Bank Sta=4997.9,5003.9
Exp/Cntr=0.3,0.1