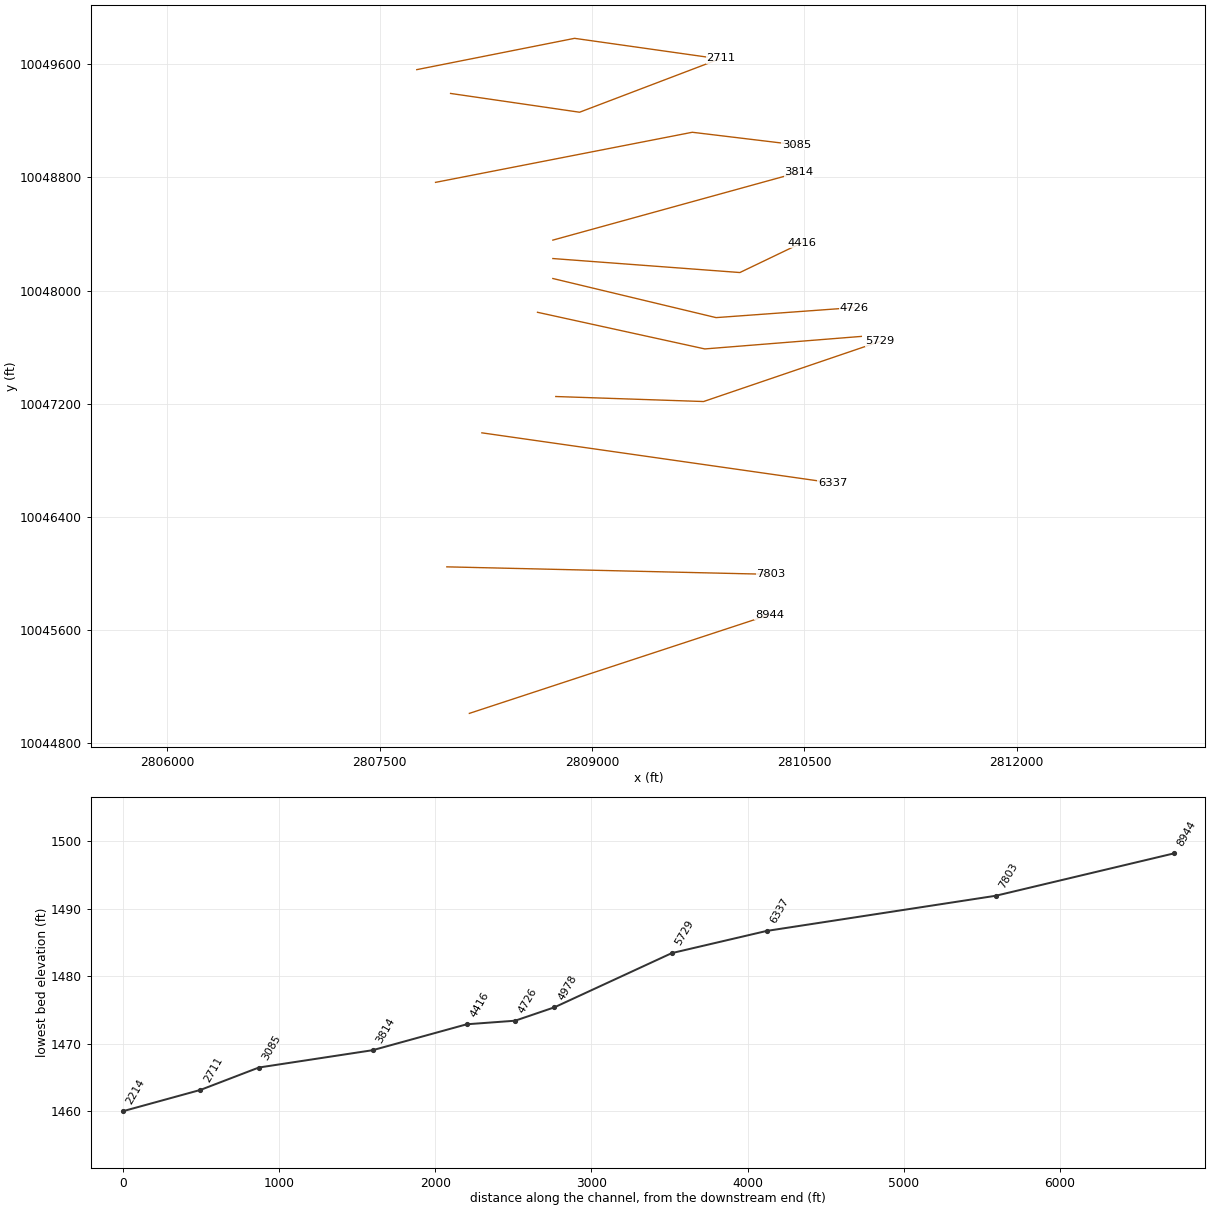
HEC-RAS study UNT060 IN SNOGR.prj: UNT060 IN SNOGR Base Level Engineering

--- UNT060 IN SNOGR.g01 (geometry) --- (continued)

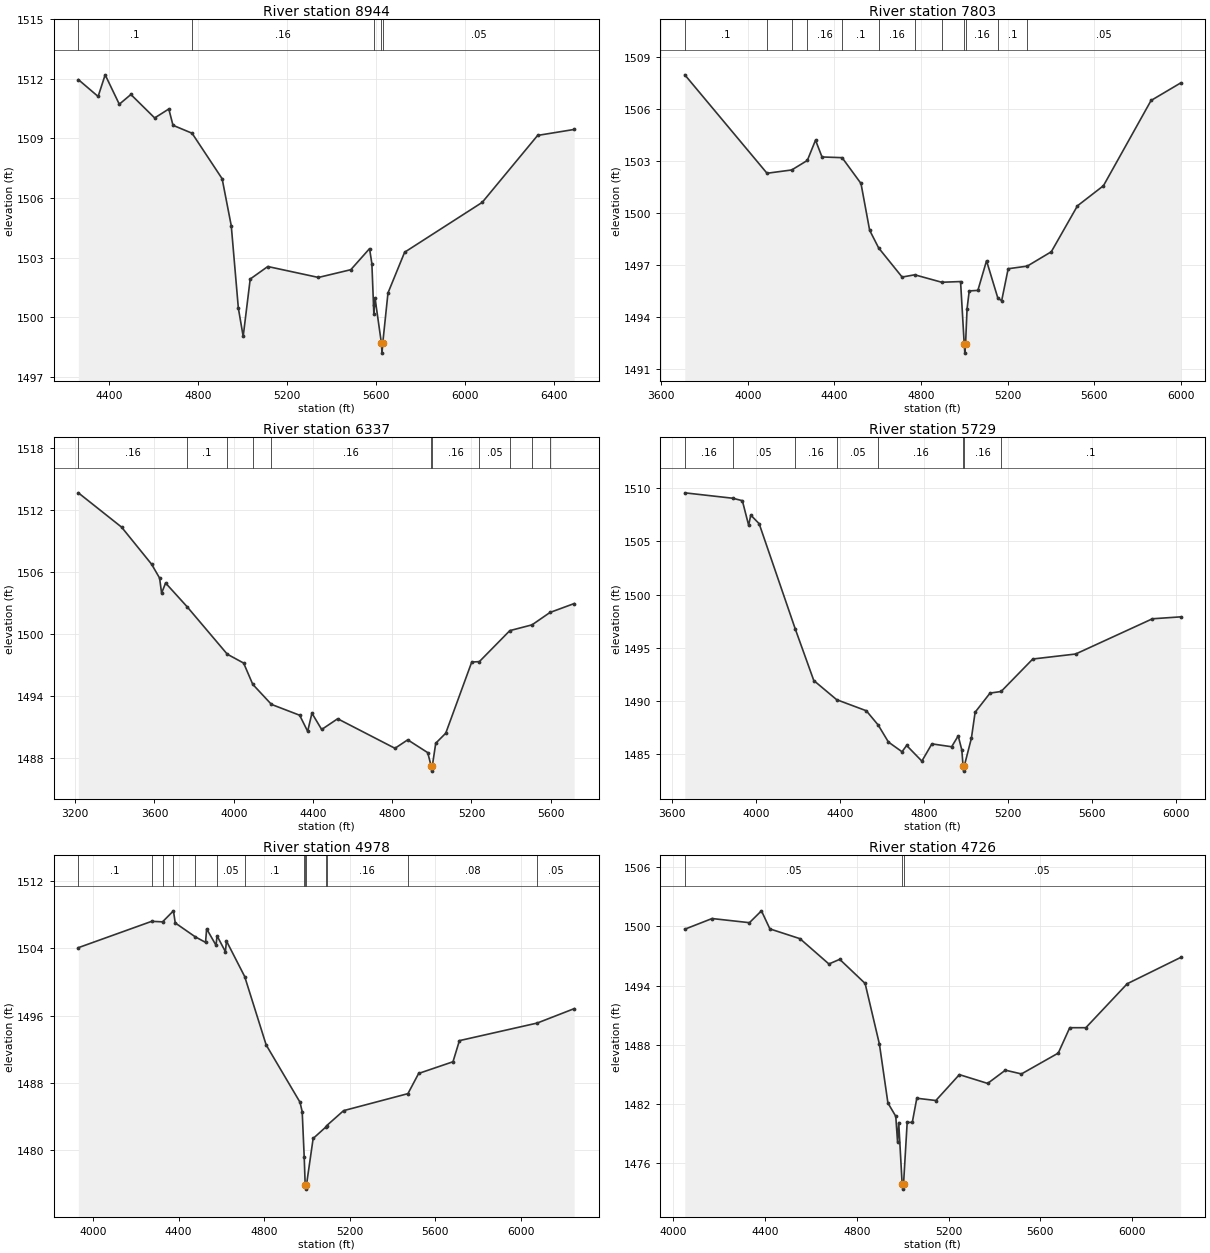
Type RM Length L Ch R = 1,8944,1141,1141,1141
BEGIN DESCRIPTION:
UNT060 IN SNOGR 12.0
END DESCRIPTION:
XS GIS Cut Line= 2
      2808133.91     10045012.66      2810252.95     10045708.93
#Sta/Elev= 30
  4260.3 1511.96  4349.3 1511.11  4381.0 1512.20  4444.6 1510.72  4496.7 1511.21
  4603.7 1510.03  4667.3 1510.48  4686.1 1509.66  4771.9 1509.26  4907.2 1506.97
  4948.3 1504.60  4980.1 1500.46  5001.9 1499.03  5033.5 1501.92  5112.6 1502.55
  5340.5 1502.00  5486.1 1502.39  5570.3 1503.45  5580.8 1502.70  5589.7 1500.17
  5592.4 1500.59  5594.9 1500.97  5623.7 1498.69  5626.5 1498.19  5629.7 1498.69
  5653.3 1501.22  5728.2 1503.27  6077.3 1505.78  6326.5 1509.15  6490.8 1509.45
#Mann=5,-1,0
  4260.3     0.1       0  4771.9    0.16       0  5592.4    0.05       0
  5623.7    0.07       0  5629.7    0.05       0
Bank Sta=5623.7,5629.7
Exp/Cntr=0.3,0.1

Type RM Length L Ch R = 1,7803,1466,1466,1466
BEGIN DESCRIPTION:
Mapping XS d2628794
END DESCRIPTION:
XS GIS Cut Line= 2
      2807974.63     10046048.05      2810265.01     10045994.99
#Sta/Elev= 30
  3708.4 1507.97  4088.3 1502.29  4202.5 1502.48  4274.6 1503.03  4312.4 1504.20
  4342.4 1503.23  4435.2 1503.19  4522.5 1501.70  4562.5 1499.00  4604.1 1497.98
  4712.5 1496.30  4770.8 1496.43  4895.7 1496.00  4982.6 1496.04  4999.6 1492.41
  5002.3 1491.91  5005.6 1492.41  5012.6 1494.46  5022.6 1495.50  5062.6 1495.53
  5102.6 1497.24  5155.3 1495.07  5172.6 1494.94  5202.6 1496.78  5290.6 1496.93
  5401.9 1497.76  5522.7 1500.41  5642.8 1501.57  5862.8 1506.49  5999.4 1507.50
#Mann=12,-1,0
  3708.4     0.1       0  4088.3    0.16       0  4202.5     0.1       0
  4274.6    0.16       0  4435.2     0.1       0  4604.1    0.16       0
  4770.8     0.1       0  4895.7    0.16       0  4999.6    0.07       0
  5005.6    0.16       0  5155.3     0.1       0  5290.6    0.05       0
Bank Sta=4999.6,5005.6
Exp/Cntr=0.3,0.1

Type RM Length L Ch R = 1,6337,608,608,608
BEGIN DESCRIPTION:
Mapping XS 0eefd719
END DESCRIPTION:
XS GIS Cut Line= 2
      2808222.38     10046994.96      2810700.23     10046640.98
#Sta/Elev= 30
  3215.7 1513.64  3434.0 1510.32  3585.5 1506.73  3625.9 1505.39  3636.0 1503.93
  3656.2 1504.91  3764.5 1502.62  3967.6 1498.02  4050.2 1497.16  4096.3 1495.10
  4190.5 1493.16  4333.0 1492.11  4373.4 1490.55  4394.9 1492.31  4444.1 1490.73
  4524.9 1491.77  4814.1 1488.91  4878.5 1489.73  4979.5 1488.49  4996.7 1487.20
  4999.5 1486.70  5002.7 1487.20  5019.9 1489.40  5070.4 1490.37  5201.7 1497.26
  5240.1 1497.30  5393.9 1500.30  5506.0 1500.86  5596.9 1502.06  5718.7 1502.92
#Mann=11,-1,0
  3215.7    0.16       0  3764.5     0.1       0  3967.6    0.05       0
  4096.3     0.1       0  4190.5    0.16       0  4996.7    0.07       0
  5002.7    0.16       0  5240.1    0.05       0  5393.9     0.1       0
  5506.0    0.05       0  5596.9     0.1       0
Bank Sta=4996.7,5002.7
Exp/Cntr=0.3,0.1

Type RM Length L Ch R = 1,5729,751,751,751
BEGIN DESCRIPTION:
UNT060 IN SNOGR 11.0
END DESCRIPTION:
XS GIS Cut Line= 3
      2808744.53     10047251.60      2809788.77     10047216.20
      2811034.99     10047640.45
#Sta/Elev= 30
  3661.1 1509.55  3890.1 1509.04  3935.2 1508.81  3965.2 1506.50  3975.2 1507.46
  4015.2 1506.65  4186.7 1496.79  4275.4 1491.92  4384.4 1490.12  4525.5 1489.08
  4582.1 1487.74  4630.9 1486.14  4695.6 1485.23  4717.6 1485.82  4790.1 1484.35
  4837.8 1485.97  4931.9 1485.70  4963.2 1486.72  4980.3 1485.40  4986.3 1483.91
  4989.1 1483.41  4992.3 1483.91  5026.0 1486.50  5043.7 1488.94  5114.8 1490.74
  5167.5 1490.89  5318.3 1493.94  5522.4 1494.41  5888.2 1497.72  6022.4 1497.90
#Mann=8,-1,0
  3661.1    0.16       0  3890.1    0.05       0  4186.7    0.16       0
  4384.4    0.05       0  4582.1    0.16       0  4986.3    0.07       0
  4992.3    0.16       0  5167.5     0.1       0
Bank Sta=4986.3,4992.3
Exp/Cntr=0.3,0.1

Type RM Length L Ch R = 1,4978,252,252,252
BEGIN DESCRIPTION:
UNT060 IN SNOGR 10.0
END DESCRIPTION:
XS GIS Cut Line= 3
      2808615.34     10047846.78      2809797.62     10047587.88
      2810903.59     10047676.36
#Sta/Elev= 30
  3930.7 1504.08  4273.8 1507.21  4324.7 1507.15  4375.7 1508.46  4384.1 1507.02
  4477.7 1505.37  4525.9 1504.71  4531.0 1506.32  4574.9 1504.36  4579.7 1505.49
  4618.7 1503.61  4623.8 1504.87  4709.0 1500.65  4809.5 1492.52  4967.8 1485.71
  4978.1 1484.59  4987.5 1479.18  4992.1 1475.88  4994.8 1475.38  4998.1 1475.88
  5029.3 1481.40  5089.5 1482.78  5093.2 1482.94  5171.9 1484.71  5472.8 1486.73
  5522.9 1489.13  5683.6 1490.52  5713.7 1493.03  6077.6 1495.12  6250.5 1496.83
#Mann=14,-1,0
  3930.7     0.1       0  4273.8    0.08       0  4324.7     0.1       0
  4375.7    0.05       0  4477.7     0.1       0  4579.7    0.05       0
  4709.0     0.1       0  4987.5    0.05       0  4992.1    0.04       0
  4998.1    0.05       0  5089.5    0.08       0  5093.2    0.16       0
  5472.8    0.08       0  6077.6    0.05       0
Bank Sta=4992.1,4998.1
Exp/Cntr=0.3,0.1

Type RM Length L Ch R = 1,4726,310,310,310
BEGIN DESCRIPTION:
UNT060 IN SNOGR 9.0
END DESCRIPTION:
XS GIS Cut Line= 3
      2808723.81     10048085.50      2809877.27     10047809.12
      2810850.69     10047879.92
#Sta/Elev= 30
  4049.6 1499.70  4168.6 1500.78  4331.5 1500.36  4383.8 1501.56  4420.7 1499.73
  4551.9 1498.74  4678.0 1496.18  4725.2 1496.65  4835.9 1494.21  4898.4 1488.05
  4935.3 1482.11  4969.6 1480.76  4977.3 1478.17  4982.4 1480.13  4997.4 1473.89
  5000.2 1473.39  5003.4 1473.89  5019.3 1480.14  5041.6 1480.15  5061.3 1482.59
  5144.4 1482.36  5246.9 1484.98  5370.2 1484.09  5447.5 1485.43  5517.6 1485.05
  5678.1 1487.16  5728.2 1489.73  5798.4 1489.73  5978.9 1494.18  6211.7 1496.84
#Mann=3,-1,0
  4049.6    0.05       0  4997.4    0.04       0  5003.4    0.05       0
Bank Sta=4997.4,5003.4
Exp/Cntr=0.3,0.1

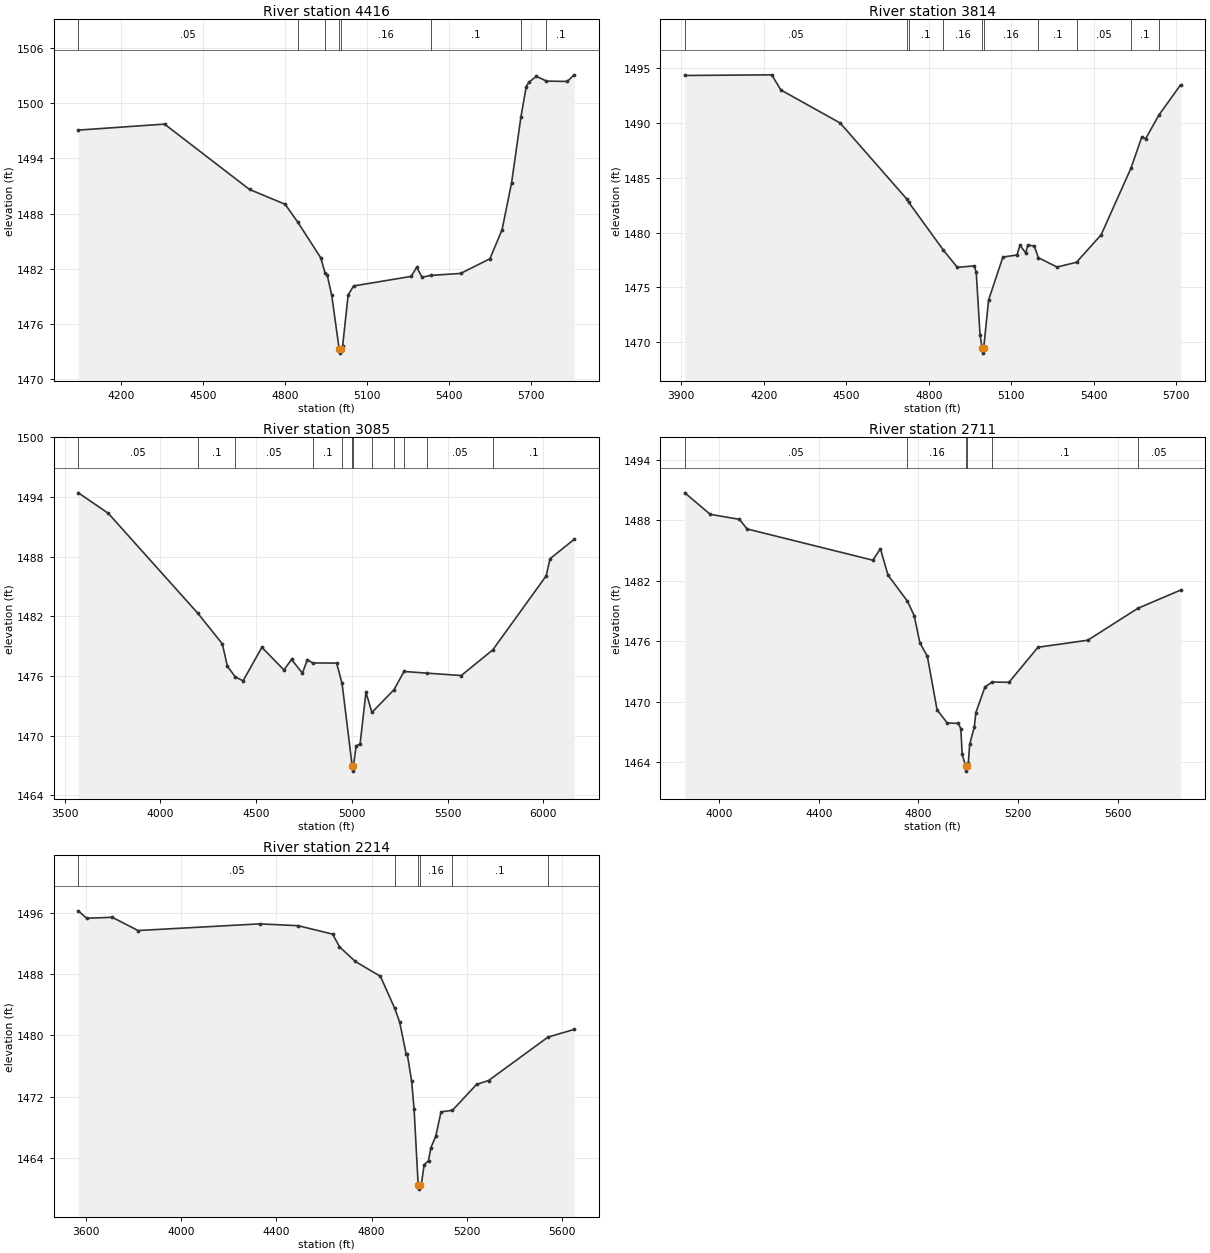
Type RM Length L Ch R = 1,4416,602,602,602
BEGIN DESCRIPTION:
UNT060 IN SNOGR 8.0
END DESCRIPTION:
XS GIS Cut Line= 3
      2808723.84     10048226.56      2810045.41     10048127.71
      2810486.47     10048339.42
#Sta/Elev= 30
  4042.5 1497.07  4358.0 1497.72  4668.9 1490.63  4799.2 1489.02  4846.4 1487.04
  4929.6 1483.21  4945.6 1481.55  4953.2 1481.34  4969.7 1479.17  4996.8 1473.36
  4999.5 1472.86  5002.8 1473.36  5009.8 1473.65  5029.9 1479.18  5049.9 1480.15
  5260.5 1481.19  5280.6 1482.17  5300.6 1481.10  5332.0 1481.30  5441.4 1481.51
  5548.6 1483.10  5593.0 1486.24  5628.1 1491.36  5662.3 1498.52  5681.7 1501.80
  5690.5 1502.24  5718.7 1502.91  5755.7 1502.39  5831.9 1502.35  5857.0 1503.07
#Mann=8,-1,0
  4042.5    0.05       0  4846.4     0.1       0  4945.6    0.16       0
  4996.8    0.07       0  5002.8    0.16       0  5332.0     0.1       0
  5662.3    0.05       0  5755.7     0.1       0
Bank Sta=4996.8,5002.8
Exp/Cntr=0.3,0.1

Type RM Length L Ch R = 1,3814,729,729,729
BEGIN DESCRIPTION:
UNT060 IN SNOGR 7.0
END DESCRIPTION:
XS GIS Cut Line= 2
      2808723.84     10048356.77      2810461.35     10048835.68
#Sta/Elev= 30
  3913.3 1494.31  4229.3 1494.37  4262.5 1492.99  4478.2 1489.98  4719.4 1483.08
  4726.6 1482.78  4853.3 1478.40  4903.9 1476.83  4965.8 1476.97  4972.7 1476.37
  4986.5 1470.68  4993.9 1469.52  4996.6 1469.02  4999.9 1469.52  5017.6 1473.86
  5069.5 1477.77  5120.6 1477.96  5131.7 1478.85  5152.5 1478.14  5160.1 1478.87
  5183.6 1478.77  5198.6 1477.71  5266.6 1476.86  5337.2 1477.30  5426.7 1479.80
  5535.7 1485.90  5574.6 1488.73  5588.1 1488.54  5636.8 1490.71  5715.6 1493.46
#Mann=10,-1,0
  3913.3    0.05       0  4719.4    0.16       0  4726.6     0.1       0
  4853.3    0.16       0  4993.9    0.07       0  4999.9    0.16       0
  5198.6     0.1       0  5337.2    0.05       0  5535.7     0.1       0
  5636.8    0.05       0
Bank Sta=4993.9,4999.9
Exp/Cntr=0.3,0.1

Type RM Length L Ch R = 1,3085,374,374,374
BEGIN DESCRIPTION:
UNT060 IN SNOGR 6.0
END DESCRIPTION:
XS GIS Cut Line= 3
      2807894.98     10048764.88      2809709.12     10049118.86
      2810443.56     10049030.38
#Sta/Elev= 30
  3572.1 1494.43  3728.5 1492.37  4196.4 1482.31  4323.9 1479.24  4350.0 1477.00
  4391.4 1475.92  4432.1 1475.53  4530.2 1478.90  4645.4 1476.62  4684.9 1477.68
  4741.6 1476.30  4767.7 1477.66  4794.6 1477.33  4920.5 1477.31  4948.8 1475.26
  5001.6 1466.95  5004.3 1466.45  5007.6 1466.95  5022.4 1469.00  5042.8 1469.17
  5073.4 1474.39  5104.4 1472.35  5219.6 1474.63  5272.1 1476.47  5392.7 1476.30
  5570.9 1476.06  5735.4 1478.64  6014.1 1486.08  6034.2 1487.80  6160.2 1489.75
#Mann=12,-1,0
  3572.1    0.05       0  4196.4     0.1       0  4391.4    0.05       0
  4794.6     0.1       0  4948.8    0.16       0  5001.6    0.07       0
  5007.6    0.16       0  5104.4     0.1       0  5219.6    0.05       0
  5272.1     0.1       0  5392.7    0.05       0  5735.4     0.1       0
Bank Sta=5001.6,5007.6
Exp/Cntr=0.3,0.1

Type RM Length L Ch R = 1,2711,497,497,497
BEGIN DESCRIPTION:
UNT060 IN SNOGR 5.0
END DESCRIPTION:
XS GIS Cut Line= 3
      2808001.12     10049393.20      2808912.66     10049260.46
      2809912.65     10049640.98
#Sta/Elev= 30
  3862.2 1490.72  3964.1 1488.59  4081.8 1488.09  4112.2 1487.14  4617.4 1484.04
  4647.7 1485.18  4678.1 1482.57  4756.4 1479.97  4783.4 1478.55  4806.1 1475.85
  4836.2 1474.52  4875.2 1469.21  4915.9 1467.91  4960.8 1467.86  4970.7 1467.34
  4976.1 1464.79  4989.9 1463.63  4992.6 1463.13  4995.9 1463.63  5000.8 1463.95
  5006.2 1465.79  5025.0 1467.52  5030.9 1468.92  5067.8 1471.49  5096.7 1471.96
  5164.1 1471.94  5280.5 1475.41  5480.6 1476.11  5681.5 1479.27  5853.3 1481.08
#Mann=6,-1,0
  3862.2    0.05       0  4756.4    0.16       0  4989.9    0.07       0
  4995.9    0.16       0  5096.7     0.1       0  5681.5    0.05       0
Bank Sta=4989.9,4995.9
Exp/Cntr=0.3,0.1

Type RM Length L Ch R = 1,2214,0,0,0
BEGIN DESCRIPTION:
UNT060 IN SNOGR 4.0
END DESCRIPTION:
XS GIS Cut Line= 3
      2807762.25     10049561.35      2808877.26     10049782.58
      2809814.38     10049649.97
#Sta/Elev= 30
  3567.6 1496.25  3602.5 1495.28  3709.9 1495.41  3818.6 1493.68  4329.2 1494.55
  4491.5 1494.31  4636.2 1493.21  4664.8 1491.56  4731.3 1489.65  4836.9 1487.71
  4896.7 1483.55  4917.7 1481.75  4944.4 1477.65  4949.5 1477.58  4968.2 1474.01
  4978.3 1470.40  4995.5 1460.47  4998.2 1459.97  5001.5 1460.47  5008.6 1460.55
  5020.5 1463.15  5038.9 1463.68  5049.0 1465.39  5069.2 1466.86  5091.5 1470.04
  5139.6 1470.25  5240.8 1473.62  5291.3 1474.13  5540.9 1479.79  5650.8 1480.79
#Mann=6,-1,0
  3567.6    0.05       0  4896.7    0.16       0  4995.5    0.07       0
  5001.5    0.16       0  5139.6     0.1       0  5540.9    0.05       0
Bank Sta=4995.5,5001.5
Exp/Cntr=0.3,0.1

Chan Stop Cuts=-1