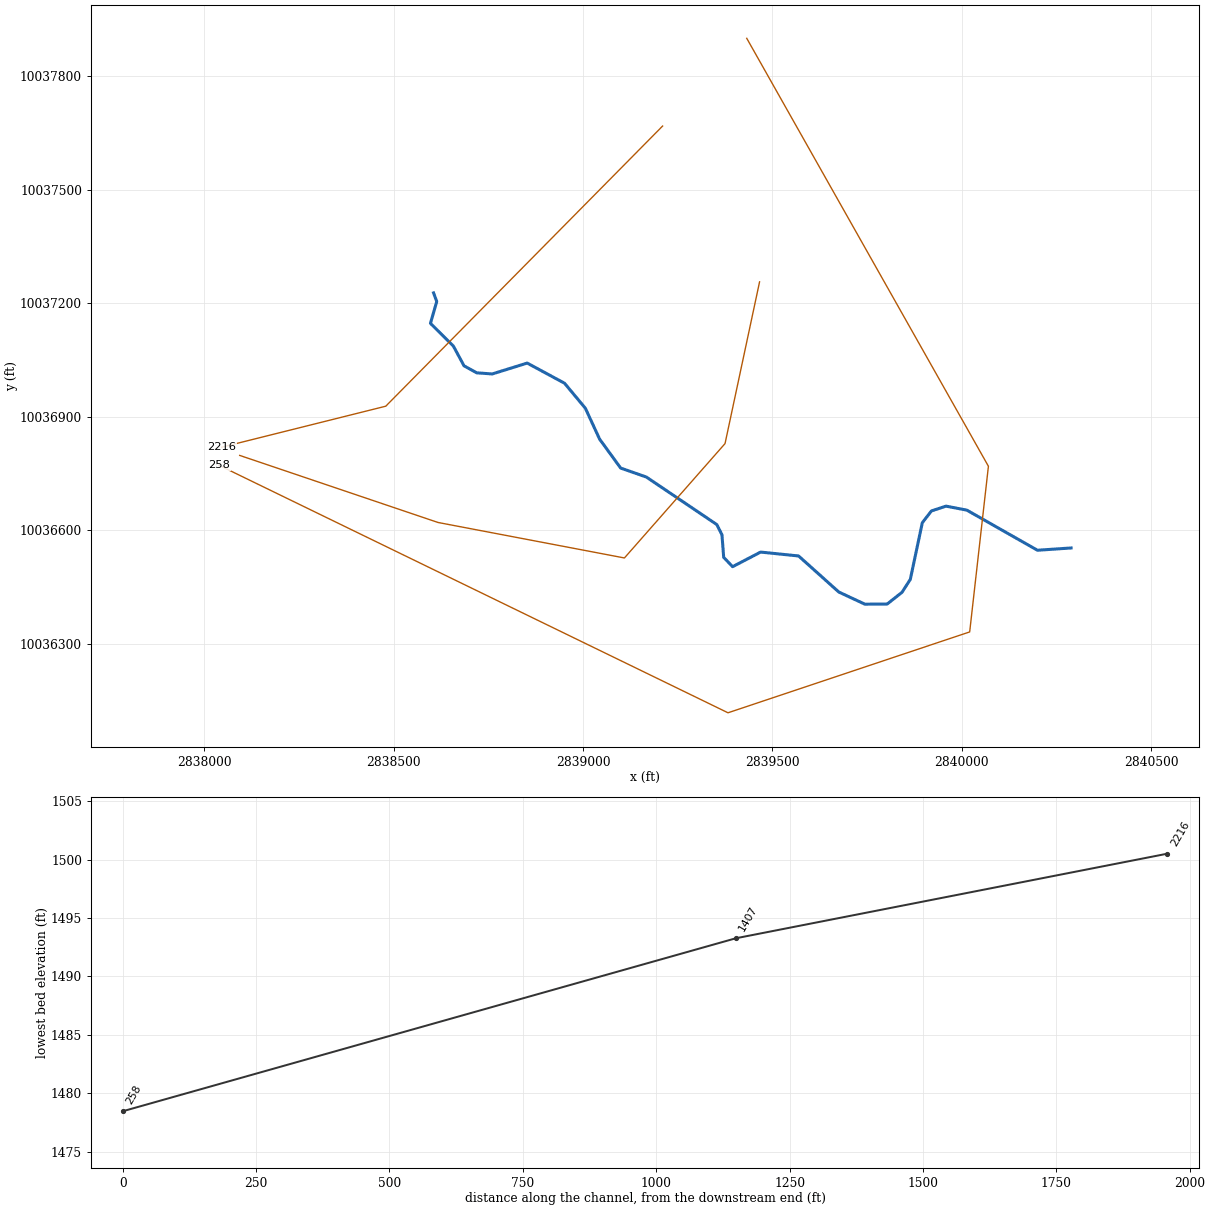
--- UNT061 IN SNOGR.prj (project) ---

Proj Title=UNT061 IN SNOGR Base Level Engineering
Current Plan=p01
Default Exp/Contr=0.3,0.1
English Units
Geom File=g01
Flow File=f01
Plan File=p01
Y Axis Title=Elevation
X Axis Title(PF)=Main Channel Distance
X Axis Title(XS)=Station
BEGIN DESCRIPTION:
UNT061 IN SNOGR
END DESCRIPTION:
DSS Export Rating Curves= 0
DSS Export Rating Curve Sorted= 0
DSS Export Volume Flow Curves= 0
DXF OffsetX= 0
DXF OffsetY= 0
DXF ScaleX= 1
DXF ScaleY= 10

--- UNT061 IN SNOGR.p01 (plan) ---

Plan Title=Multiple Run
Short Identifier=Multiple
Geom File=g01
Flow File=f01
Subcritical Flow
K Sum by GR= 0
Std Step Tol= 0.01
Critical Tol= 0.01
Num of Std Step Trials= 20
Max Error Tol= 0.3
Flow Tol Ratio= 0.001
Split Flow NTrial= 30
Split Flow Tol= 0.02
Split Flow Ratio= 0.02
Log Output Level= 0
Friction Slope Method= 1
Unsteady Friction Slope Method= 2
Unsteady Bridges Friction Slope Method= 1
Parabolic Critical Depth
Global Vel Dist=  1 , 1 , 1
Global Log Level= 0
CheckData=True
Encroach Param= -1, 0, 0, 0
BEGIN DESCRIPTION:
Multiple Run
END DESCRIPTION:

--- UNT061 IN SNOGR.f01 (steady flow) ---

Flow Title=Multiple
Program Version=4.10
Number of Profiles= 7
Profile Names=10-year,25-year,50-year,1pct_min,100-year,1pct_plu,500-year
River Rch & RM=UNT061 IN SNOGR,Reach-1         ,2216
     710    1015    1276    1176    1590    2151    2478
Boundary for River Rch & Prof#=UNT061 IN SNOGR,Reach-1         , 1
Up Type= 0
Dn Type= 3
Dn Slope=0.014
Boundary for River Rch & Prof#=UNT061 IN SNOGR,Reach-1         , 2
Up Type= 0
Dn Type= 3
Dn Slope=0.014
Boundary for River Rch & Prof#=UNT061 IN SNOGR,Reach-1         , 3
Up Type= 0
Dn Type= 3
Dn Slope=0.014
Boundary for River Rch & Prof#=UNT061 IN SNOGR,Reach-1         , 4
Up Type= 0
Dn Type= 3
Dn Slope=0.014
Boundary for River Rch & Prof#=UNT061 IN SNOGR,Reach-1         , 5
Up Type= 0
Dn Type= 3
Dn Slope=0.014
Boundary for River Rch & Prof#=UNT061 IN SNOGR,Reach-1         , 6
Up Type= 0
Dn Type= 3
Dn Slope=0.014
Boundary for River Rch & Prof#=UNT061 IN SNOGR,Reach-1         , 7
Up Type= 0
Dn Type= 3
Dn Slope=0.014
DSS Import GetInterval= 0
DSS Import GetPeak= 0
DSS Import FillOption= 0

--- UNT061 IN SNOGR.g01 (geometry) ---

Geom Title=Existing Conditions
Program Version=4.10

River Reach=UNT061 IN SNOGR ,Reach-1
Reach XY= 30
      2838605.47     10037227.43      2838613.91     10037204.58
      2838597.28     10037146.97      2838657.72       10037087.
      2838685.94     10037034.73      2838719.44     10037016.29
       2838760.3     10037013.27      2838852.71       10037042.
      2838951.21      10036988.8       2839006.2     10036922.83
      2839043.82     10036841.21       2839099.4     10036764.77
      2839167.31     10036741.02      2839353.36     10036615.45
      2839366.85     10036588.57      2839371.42     10036528.93
      2839394.97      10036504.3        2839469.     10036542.88
      2839569.16     10036532.59      2839675.25     10036437.42
      2839744.04     10036405.32      2839802.96     10036405.62
       2839842.1     10036436.53      2839864.08     10036470.73
      2839895.82     10036620.43      2839919.78     10036651.47
       2839958.4     10036664.18      2840013.29     10036653.66
      2840199.82     10036547.68      2840288.47     10036553.73

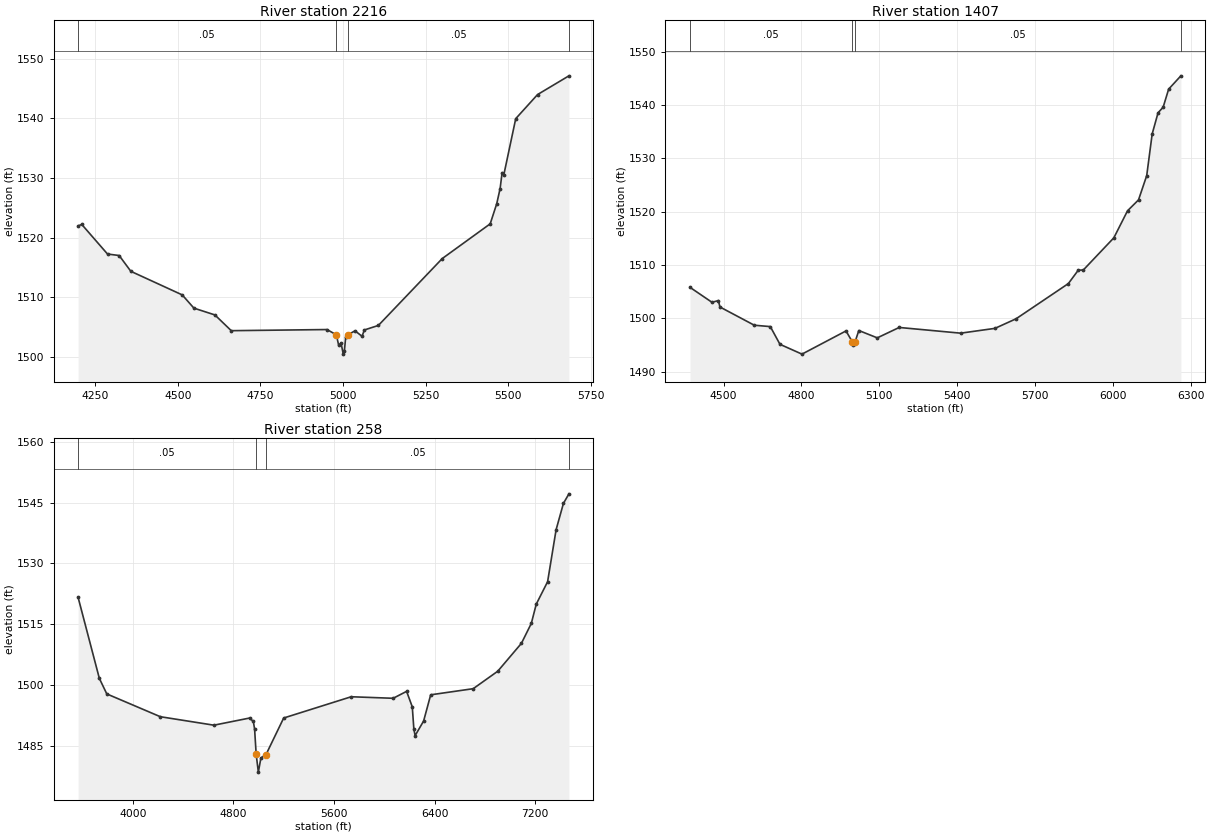
Type RM Length L Ch R = 1 ,2216    ,809,809,809
BEGIN DESCRIPTION:
UNT061 IN SNOGR 2.0
END DESCRIPTION:
XS GIS Cut Line= 3
      2839210.16     10037667.98      2838479.33     10036928.13
      2838046.31     10036819.88
#Sta/Elev= 30
  4197.9    1522  4209.2 1522.23    4287 1517.28  4322.3 1517.03  4357.7 1514.38
  4513.2 1510.43  4548.6 1508.21  4612.2 1507.07  4661.7 1504.43  4951.6 1504.62
  4979.9 1503.74    4987 1501.98  4994.1 1502.37  5000.9  1500.5  5004.2    1501
  5008.2 1503.33  5015.3 1503.75  5036.5 1504.41  5057.7 1503.49  5064.8 1504.55
  5107.2 1505.31  5300.6 1516.52  5445.8 1522.34  5465.5  1525.7  5475.8 1528.25
  5481.9 1530.93    5487 1530.55  5523.1 1539.97  5589.2 1544.01  5684.2 1547.15
#Mann= 4 ,-1 , 0
  4197.9     .05       0  4979.9    .035       0  5015.3     .05       0
  5684.2     .16       0
Bank Sta=4979.9,5015.3
XS Rating Curve= 0 ,0
Exp/Cntr=0.3,0.1

Type RM Length L Ch R = 1 ,1407    ,1149,1149,1149
BEGIN DESCRIPTION:
Mapping XS 8e34b986
END DESCRIPTION:
XS GIS Cut Line= 5
      2839466.15     10037256.49        2839375.      10036829.4
      2839109.38     10036527.32      2838617.19     10036621.07
      2838093.73     10036798.16
#Sta/Elev= 30
  4370.2 1505.78  4454.8 1502.98  4479.6  1503.3  4485.5  1502.1    4618 1498.68
  4679.8 1498.42    4717  1495.1  4801.9 1493.26  4971.7 1497.61 4995.92 1495.56
  5000.2  1494.9  5006.8 1495.59    5021 1497.69  5092.2 1496.31  5176.7 1498.26
  5413.7 1497.19    5546 1498.09  5627.5 1499.89    5829 1506.49  5867.2    1509
  5886.6 1509.03  6004.4 1515.07  6057.2 1520.14  6099.5 1522.18  6131.1 1526.73
  6152.2 1534.55  6174.8 1538.51  6194.5 1539.56  6215.6 1542.94  6262.8 1545.44
#Mann= 4 ,-1 , 0
  4370.2     .05       0 4995.92    .035       0  5006.8     .05       0
  6262.8     .16       0
Bank Sta=4995.92,5006.8
XS Rating Curve= 0 ,0
Exp/Cntr=0.3,0.1

Type RM Length L Ch R = 1 ,258     ,0,0,0
BEGIN DESCRIPTION:
UNT061 IN SNOGR 1.0
END DESCRIPTION:
XS GIS Cut Line= 5
       2839432.3     10037899.69      2840070.31     10036769.51
      2840020.83     10036332.01      2839382.81     10036118.46
      2838039.09      10036772.1
#Sta/Elev= 30
  3563.8 1521.63    3733  1501.6  3792.2 1497.77  4218.3 1492.14  4644.3 1490.05
  4927.8 1491.81    4958 1490.98  4968.1 1489.12 4980.68 1482.86    4998 1478.46
  5018.4 1481.96  5058.7 1482.78  5199.5 1491.82  5736.8 1497.07  6070.4 1496.69
  6177.6  1498.4  6222.7 1494.57  6235.3 1489.05  6245.3 1487.48  6312.9 1491.08
  6369.2 1497.55  6707.4 1499.06  6902.6 1503.37  7090.8 1510.25  7169.6 1515.17
  7209.1 1519.94  7299.3 1525.47    7367 1538.32  7425.2 1544.81    7469 1547.17
#Mann= 4 ,-1 , 0
  3563.8     .05       0 4980.68    .035       0  5058.7     .05       0
    7469     .16       0
Bank Sta=4980.68,5058.7
XS Rating Curve= 0 ,0
Exp/Cntr=0.3,0.1

Chan Stop Cuts=-1
Use User Specified Reach Order=0
Composite Channel Slope=5