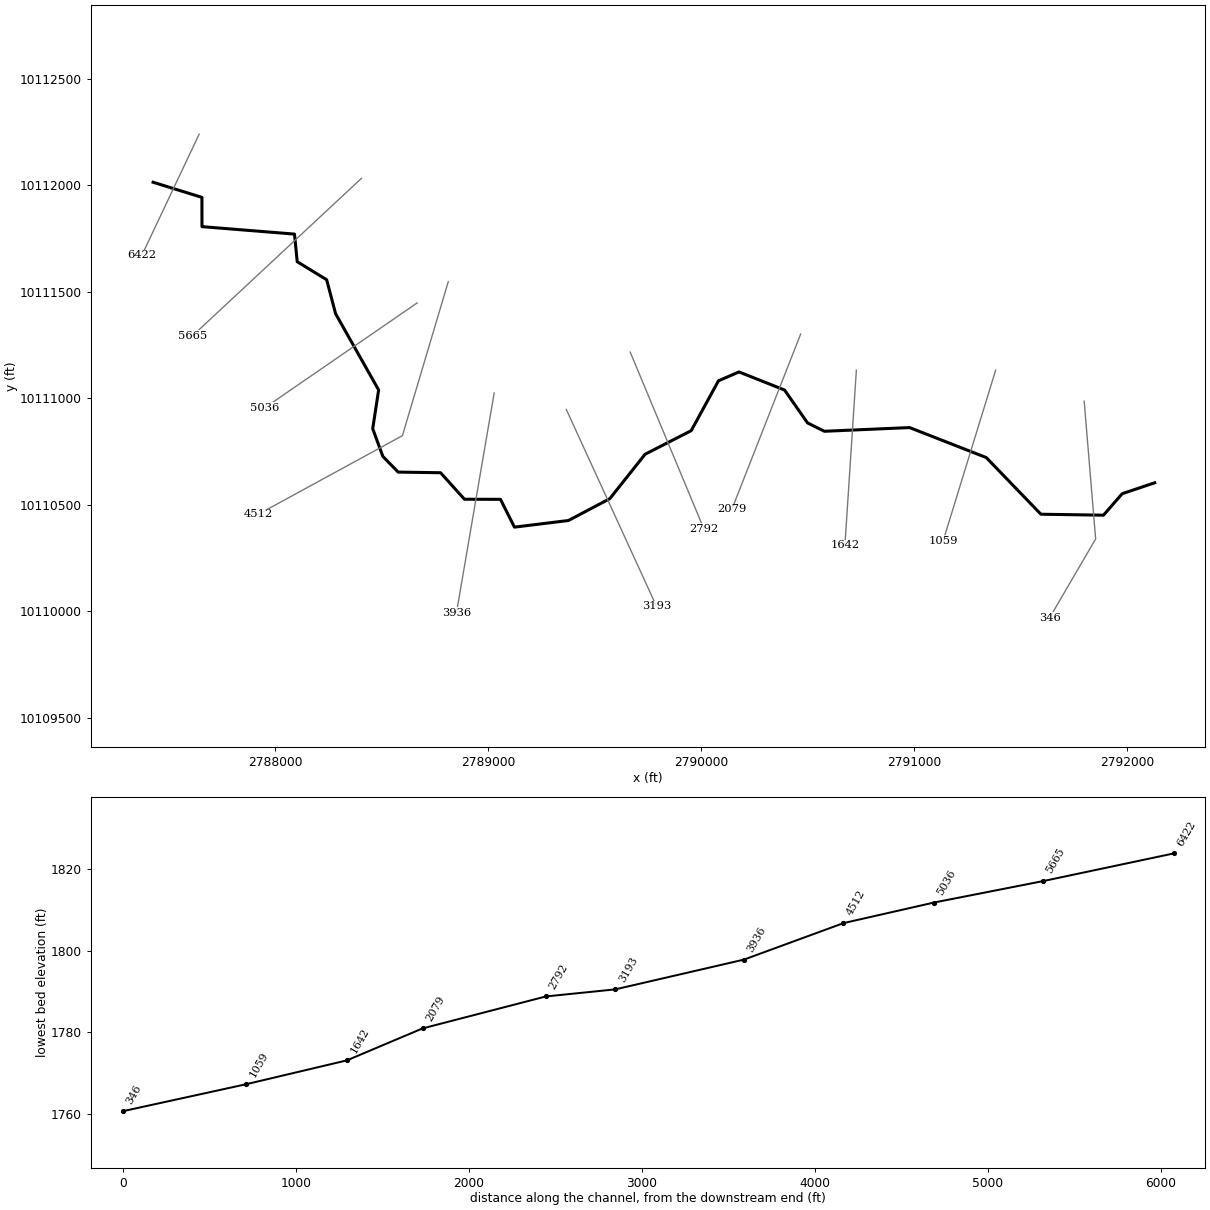
--- UNT062 IN NNOGR.prj (project) ---

Proj Title=UNT062 IN NNOGR Base Level Engineering
Current Plan=p01
Default Exp/Contr=0.3,0.1
English Units
Geom File=g01
Flow File=f01
Plan File=p01
BEGIN DESCRIPTION:
UNT062 IN NNOGR
END DESCRIPTION:

--- UNT062 IN NNOGR.p01 (plan) ---

Plan Title=Multiple Run
Short Identifier=Multiple
Geom File=g01
Flow File=f01
Subcritical Flow
K Sum by GR= 0
Std Step Tol= 0.01
Critical Tol= 0.01
Num of Std Step Trials= 20
Max Error Tol= 0.3
Flow Tol Ratio= 0.001
Split Flow NTrial= 30
Split Flow Tol= 0.02
Split Flow Ratio= 0.02
Log Output Level= 0
Friction Slope Method= 1
Unsteady Friction Slope Method= 2
Unsteady Bridges Friction Slope Method= 1
Parabolic Critical Depth
Global Vel Dist=  1 , 1 , 1
Global Log Level= 0
CheckData=True
Encroach Param= -1, 0, 0, 0
BEGIN DESCRIPTION:
Multiple Run
END DESCRIPTION:

--- UNT062 IN NNOGR.f01 (steady flow) ---

Flow Title=Multiple
Number of Profiles=7
Profile Names=10-year,25-year,50-year,1pct_min,100-year,1pct_plu,500-year
River Rch & RM= UNT062 IN NNOGR,Reach-1,6422
     726    1041    1312    1211    1637    2214    2560
River Rch & RM= UNT062 IN NNOGR,Reach-1,4512
    1021    1489    1896    1767    2389    3231    3810
Boundary for River Rch & Prof#=UNT062 IN NNOGR,Reach-1,1
Up Type=0
Dn Type=3
Dn Slope=0.005
Boundary for River Rch & Prof#=UNT062 IN NNOGR,Reach-1,2
Up Type=0
Dn Type=3
Dn Slope=0.005
Boundary for River Rch & Prof#=UNT062 IN NNOGR,Reach-1,3
Up Type=0
Dn Type=3
Dn Slope=0.005
Boundary for River Rch & Prof#=UNT062 IN NNOGR,Reach-1,4
Up Type=0
Dn Type=3
Dn Slope=0.005
Boundary for River Rch & Prof#=UNT062 IN NNOGR,Reach-1,5
Up Type=0
Dn Type=3
Dn Slope=0.005
Boundary for River Rch & Prof#=UNT062 IN NNOGR,Reach-1,6
Up Type=0
Dn Type=3
Dn Slope=0.005
Boundary for River Rch & Prof#=UNT062 IN NNOGR,Reach-1,7
Up Type=0
Dn Type=3
Dn Slope=0.005

--- UNT062 IN NNOGR.g01 (geometry) ---

Geom Title=Existing Conditions

River Reach=UNT062 IN NNOGR,Reach-1
Reach XY= 30
      2787428.47     10112013.73      2787657.75     10111942.69
      2787657.94     10111805.39      2788092.03     10111770.43
      2788104.85     10111640.83      2788242.95     10111556.33
      2788284.85     10111396.95      2788486.80     10111038.95
      2788459.10     10110857.41      2788506.47     10110727.59
      2788578.47     10110653.73      2788777.38     10110650.71
      2788889.53     10110526.38      2789058.54     10110525.88
      2789124.14     10110395.48      2789377.20     10110426.57
      2789571.25     10110528.79      2789737.14     10110737.56
      2789953.45     10110848.15      2790081.29     10111081.98
      2790177.63     10111123.71      2790391.35     10111038.83
      2790499.27     10110884.48      2790578.56     10110845.24
      2790977.99     10110862.63      2791337.75     10110721.94
      2791594.21     10110456.06      2791887.88     10110451.54
      2791975.64     10110552.36      2792128.47     10110603.73

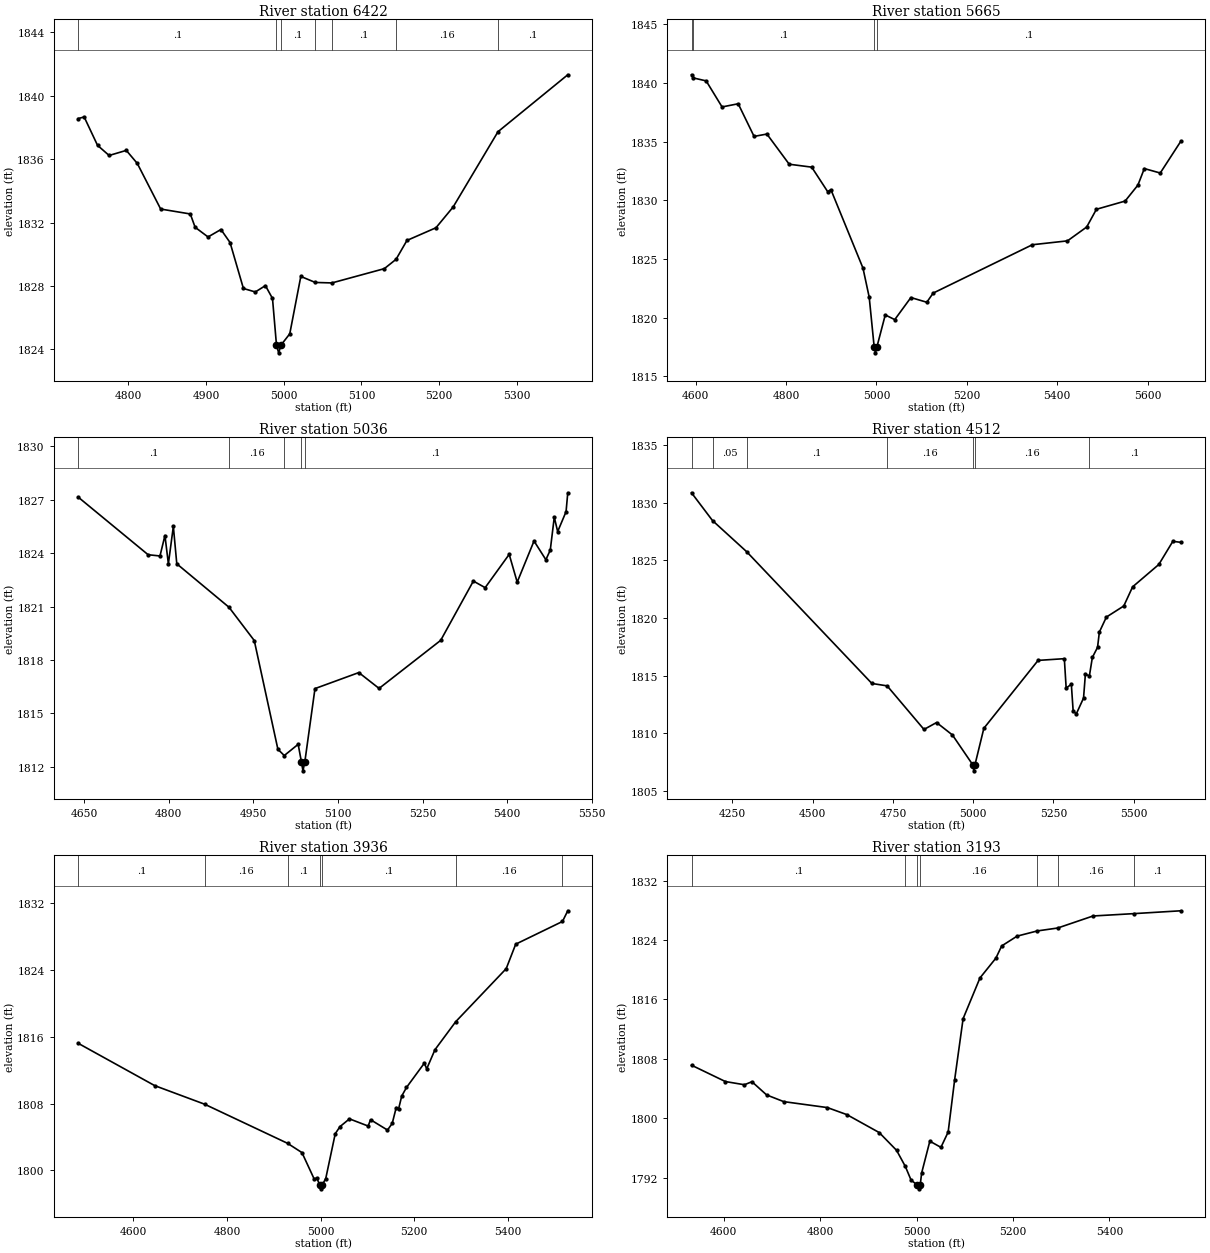
Type RM Length L Ch R = 1,6422,757,757,757
BEGIN DESCRIPTION:
UNT062 IN NNOGR 13.0
END DESCRIPTION:
XS GIS Cut Line= 2
      2787644.78     10112239.49      2787375.67     10111670.53
#Sta/Elev= 30
  4735.9 1838.56  4743.4 1838.66  4760.6 1836.87  4775.5 1836.23  4797.6 1836.55
  4811.7 1835.73  4841.8 1832.85  4879.9 1832.54  4886.1 1831.70  4902.7 1831.09
  4919.3 1831.56  4931.0 1830.74  4948.2 1827.84  4963.5 1827.62  4976.5 1828.02
  4985.6 1827.21  4990.7 1824.28  4993.5 1823.78  4996.7 1824.28  5007.8 1824.98
  5022.0 1828.60  5040.6 1828.22  5062.0 1828.19  5129.4 1829.09  5144.5 1829.68
  5158.5 1830.87  5195.8 1831.67  5217.9 1832.98  5275.6 1837.73  5365.3 1841.32
#Mann=7,-1,0
  4735.9     0.1       0  4990.7    0.07       0  4996.7     0.1       0
  5040.6    0.16       0  5062.0     0.1       0  5144.5    0.16       0
  5275.6     0.1       0
Bank Sta=4990.7,4996.7
Exp/Cntr=0.3,0.1

Type RM Length L Ch R = 1,5665,629,629,629
BEGIN DESCRIPTION:
UNT062 IN NNOGR 12.0
END DESCRIPTION:
XS GIS Cut Line= 2
      2788406.05     10112031.88      2787614.03     10111293.68
#Sta/Elev= 30
  4590.8 1840.69  4594.9 1840.42  4623.2 1840.17  4658.4 1837.95  4694.1 1838.22
  4729.2 1835.44  4757.6 1835.64  4806.9 1833.07  4856.7 1832.82  4891.9 1830.74
  4899.2 1830.90  4970.1 1824.22  4983.9 1821.74  4994.9 1817.50  4997.7 1817.00
  5000.9 1817.50  5019.4 1820.23  5040.4 1819.83  5076.1 1821.71  5111.3 1821.31
  5125.4 1822.09  5344.8 1826.21  5422.5 1826.54  5465.0 1827.72  5486.5 1829.23
  5550.0 1829.93  5578.3 1831.29  5592.5 1832.70  5627.7 1832.32  5673.5 1835.04
#Mann=4,-1,0
  4590.8    0.05       0  4594.9     0.1       0  4994.9    0.07       0
  5000.9     0.1       0
Bank Sta=4994.9,5000.9
Exp/Cntr=0.3,0.1

Type RM Length L Ch R = 1,5036,524,524,524
BEGIN DESCRIPTION:
UNT062 IN NNOGR 11.0
END DESCRIPTION:
XS GIS Cut Line= 2
      2788667.49     10111447.45      2787952.94     10110955.72
#Sta/Elev= 30
  4639.8 1827.14  4763.5 1823.91  4784.5 1823.84  4793.3 1824.99  4799.4 1823.40
  4808.2 1825.50  4814.3 1823.40  4906.8 1820.96  4951.6 1819.09  4993.5 1812.98
  5004.8 1812.63  5029.4 1813.26  5035.2 1812.27  5037.9 1811.77  5041.2 1812.27
  5059.2 1816.39  5136.9 1817.29  5172.8 1816.40  5282.0 1819.10  5339.9 1822.43
  5360.8 1822.06  5403.4 1823.93  5417.6 1822.37  5447.4 1824.68  5468.4 1823.63
  5476.2 1824.17  5483.3 1826.02  5489.3 1825.21  5504.2 1826.33  5507.2 1827.39
#Mann=5,-1,0
  4639.8     0.1       0  4906.8    0.16       0  5004.8     0.1       0
  5035.2    0.07       0  5041.2     0.1       0
Bank Sta=5035.2,5041.2
Exp/Cntr=0.3,0.1

Type RM Length L Ch R = 1,4512,576,576,576
BEGIN DESCRIPTION:
UNT062 IN NNOGR 10.0
END DESCRIPTION:
XS GIS Cut Line= 3
      2788813.64     10111547.47      2788598.32     10110824.61
      2787922.56     10110456.01
#Sta/Elev= 30
  4122.9 1830.85  4188.3 1828.44  4294.6 1825.74  4684.5 1814.31  4732.1 1814.10
  4846.8 1810.32  4886.0 1810.92  4935.4 1809.84  4999.3 1807.23  5002.0 1806.73
  5005.3 1807.23  5033.2 1810.42  5202.1 1816.31  5283.8 1816.46  5289.5 1813.91
  5305.6 1814.24  5311.3 1811.90  5321.2 1811.68  5343.6 1813.04  5349.3 1815.09
  5361.9 1814.98  5371.1 1816.57  5387.2 1817.44  5392.9 1818.77  5414.8 1820.07
  5468.9 1821.03  5496.4 1822.69  5578.0 1824.63  5621.7 1826.64  5646.9 1826.55
#Mann=7,-1,0
  4122.9     0.1       0  4188.3    0.05       0  4294.6     0.1       0
  4732.1    0.16       0  4999.3    0.07       0  5005.3    0.16       0
  5361.9     0.1       0
Bank Sta=4999.3,5005.3
Exp/Cntr=0.3,0.1

Type RM Length L Ch R = 1,3936,743,743,743
BEGIN DESCRIPTION:
UNT062 IN NNOGR 8.0
END DESCRIPTION:
XS GIS Cut Line= 2
      2789028.95     10111024.59      2788852.09     10109994.15
#Sta/Elev= 30
  4482.3 1815.22  4645.5 1810.16  4751.9 1807.94  4929.3 1803.25  4960.0 1802.14
  4986.5 1798.93  4991.6 1799.12  4997.6 1798.30  5000.4 1797.80  5003.6 1798.30
  5010.8 1799.03  5031.1 1804.40  5041.2 1805.25  5061.5 1806.18  5101.4 1805.32
  5106.5 1806.08  5142.7 1804.84  5152.8 1805.63  5161.4 1807.54  5166.5 1807.39
  5173.1 1808.91  5183.3 1809.94  5221.4 1812.85  5226.5 1812.17  5244.1 1814.46
  5288.5 1817.82  5396.3 1824.17  5416.6 1827.10  5516.5 1829.82  5527.8 1831.10
#Mann=7,-1,0
  4482.3     0.1       0  4751.9    0.16       0  4929.3     0.1       0
  4997.6    0.07       0  5003.6     0.1       0  5288.5    0.16       0
  5516.5     0.1       0
Bank Sta=4997.6,5003.6
Exp/Cntr=0.3,0.1

Type RM Length L Ch R = 1,3193,401,401,401
BEGIN DESCRIPTION:
UNT062 IN NNOGR 7.0
END DESCRIPTION:
XS GIS Cut Line= 2
      2789367.31     10110947.62      2789790.25     10110024.83
#Sta/Elev= 30
  4533.1 1807.16  4603.4 1804.96  4642.9 1804.53  4658.4 1804.94  4688.9 1803.16
  4724.4 1802.26  4814.9 1801.46  4855.4 1800.51  4922.4 1798.10  4958.4 1795.71
  4976.6 1793.54  4988.4 1791.72  5001.4 1791.03  5004.1 1790.53  5007.4 1791.03
  5010.4 1792.66  5027.4 1796.94  5050.4 1796.11  5065.4 1798.17  5078.9 1805.22
  5096.4 1813.42  5131.4 1818.90  5164.4 1821.56  5176.4 1823.20  5208.4 1824.52
  5250.3 1825.22  5292.5 1825.61  5365.9 1827.23  5451.5 1827.55  5548.2 1827.93
#Mann=7,-1,0
  4533.1     0.1       0  4976.6    0.16       0  5001.4    0.07       0
  5007.4    0.16       0  5250.3     0.1       0  5292.5    0.16       0
  5451.5     0.1       0
Bank Sta=5001.4,5007.4
Exp/Cntr=0.3,0.1

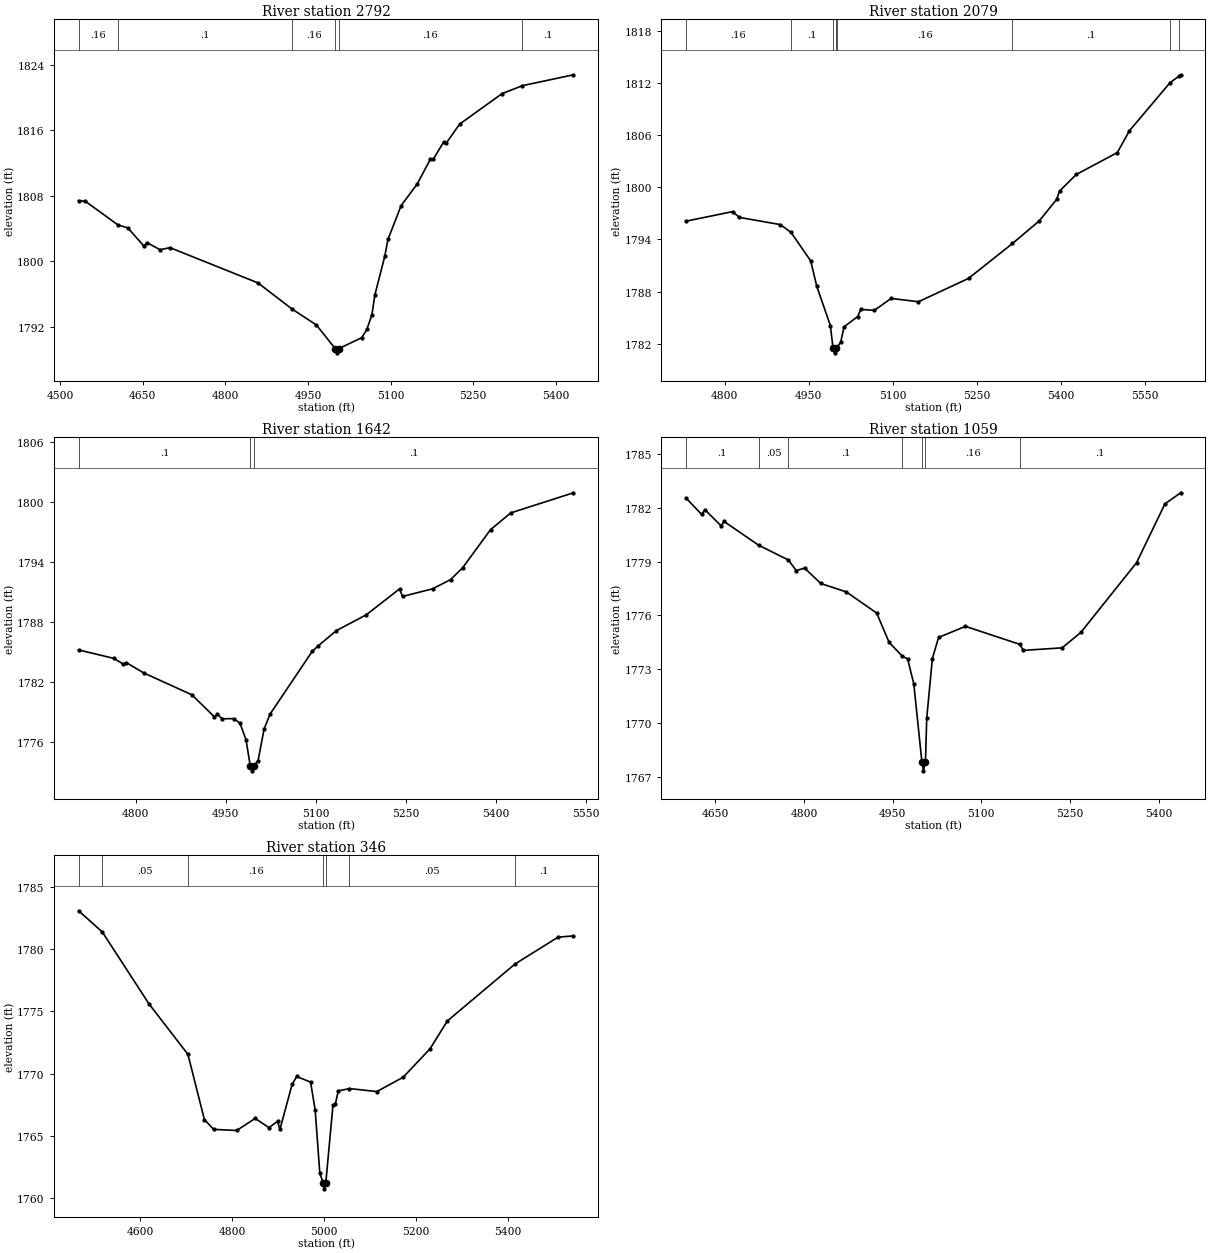
Type RM Length L Ch R = 1,2792,713,713,713
BEGIN DESCRIPTION:
UNT062 IN NNOGR 6.0
END DESCRIPTION:
XS GIS Cut Line= 2
      2789667.20     10111216.78      2790012.74     10110387.49
#Sta/Elev= 30
  4533.6 1807.40  4546.1 1807.32  4604.7 1804.45  4623.0 1804.07  4652.3 1801.84
  4657.7 1802.28  4681.5 1801.40  4699.4 1801.66  4859.2 1797.35  4920.4 1794.19
  4965.4 1792.20  4999.7 1789.30  5002.5 1788.80  5005.7 1789.30  5047.7 1790.66
  5056.9 1791.66  5066.1 1793.45  5071.5 1795.88  5089.4 1800.59  5095.4 1802.69
  5119.2 1806.80  5148.4 1809.45  5172.3 1812.47  5177.7 1812.49  5196.1 1814.54
  5201.5 1814.48  5225.4 1816.76  5302.3 1820.48  5338.9 1821.45  5432.0 1822.79
#Mann=6,-1,0
  4533.6    0.16       0  4604.7     0.1       0  4920.4    0.16       0
  4999.7    0.07       0  5005.7    0.16       0  5338.9     0.1       0
Bank Sta=4999.7,5005.7
Exp/Cntr=0.3,0.1

Type RM Length L Ch R = 1,2079,437,437,437
BEGIN DESCRIPTION:
UNT062 IN NNOGR 4.0
END DESCRIPTION:
XS GIS Cut Line= 2
      2790466.92     10111301.34      2790143.99     10110478.65
#Sta/Elev= 30
  4730.6 1796.10  4814.0 1797.20  4826.1 1796.54  4899.4 1795.71  4918.3 1794.83
  4953.6 1791.55  4964.4 1788.64  4988.8 1784.10  4993.6 1781.48  4996.3 1780.98
  4999.6 1781.48  5001.3 1781.65  5007.3 1782.24  5013.2 1783.97  5037.6 1785.15
  5043.0 1785.97  5067.4 1785.86  5097.2 1787.23  5146.1 1786.85  5235.5 1789.53
  5314.0 1793.54  5361.9 1796.14  5392.8 1798.60  5398.2 1799.57  5428.0 1801.47
  5501.2 1803.98  5523.0 1806.50  5595.5 1812.02  5612.3 1812.80  5614.4 1812.92
#Mann=8,-1,0
  4730.6    0.16       0  4918.3     0.1       0  4993.6    0.07       0
  4999.6     0.1       0  5001.3    0.16       0  5314.0     0.1       0
  5595.5    0.16       0  5612.3     0.1       0
Bank Sta=4993.6,4999.6
Exp/Cntr=0.3,0.1

Type RM Length L Ch R = 1,1642,583,583,583
BEGIN DESCRIPTION:
UNT062 IN NNOGR 3.0
END DESCRIPTION:
XS GIS Cut Line= 2
      2790728.38     10111132.15      2790674.55     10110309.41
#Sta/Elev= 30
  4704.7 1785.24  4763.2 1784.40  4779.1 1783.83  4784.1 1783.98  4813.4 1782.94
  4893.5 1780.76  4930.9 1778.56  4935.9 1778.82  4943.6 1778.37  4963.7 1778.38
  4973.7 1777.91  4983.7 1776.26  4990.7 1773.67  4993.5 1773.17  4996.7 1773.67
  5003.8 1774.20  5013.8 1777.35  5023.8 1778.84  5094.0 1785.10  5104.0 1785.65
  5134.0 1787.16  5184.1 1788.75  5239.4 1791.33  5244.4 1790.58  5294.4 1791.34
  5324.4 1792.26  5344.5 1793.44  5391.1 1797.25  5424.7 1798.92  5529.2 1800.93
#Mann=3,-1,0
  4704.7     0.1       0  4990.7    0.07       0  4996.7     0.1       0
Bank Sta=4990.7,4996.7
Exp/Cntr=0.3,0.1

Type RM Length L Ch R = 1,1059,713,713,713
BEGIN DESCRIPTION:
UNT062 IN NNOGR 2.0
END DESCRIPTION:
XS GIS Cut Line= 2
      2791382.01     10111132.22      2791135.92     10110332.42
#Sta/Elev= 30
  4600.3 1782.56  4627.1 1781.63  4632.4 1781.90  4659.8 1781.00  4665.0 1781.24
  4723.2 1779.92  4773.8 1779.09  4787.0 1778.50  4801.1 1778.64  4828.5 1777.78
  4871.7 1777.31  4923.1 1776.13  4944.0 1774.50  4966.3 1773.73  4975.4 1773.57
  4985.8 1772.18  4999.5 1767.83  5002.2 1767.33  5005.5 1767.83  5007.7 1770.27
  5017.2 1773.59  5027.7 1774.77  5073.1 1775.39  5164.6 1774.39  5171.2 1774.05
  5236.6 1774.19  5268.3 1775.05  5362.5 1778.94  5410.5 1782.22  5437.1 1782.84
#Mann=7,-1,0
  4600.3     0.1       0  4723.2    0.05       0  4773.8     0.1       0
  4966.3    0.16       0  4999.5    0.07       0  5005.5    0.16       0
  5164.6     0.1       0
Bank Sta=4999.5,5005.5
Exp/Cntr=0.3,0.1

Type RM Length L Ch R = 1,346,0,0,0
BEGIN DESCRIPTION:
UNT062 IN NNOGR 1.0
END DESCRIPTION:
XS GIS Cut Line= 3
      2791797.25     10110986.14      2791851.08     10110340.16
      2791635.79     10109971.08
#Sta/Elev= 30
  4466.2 1783.08  4517.7 1781.38  4619.1 1775.60  4703.8 1771.54  4739.6 1766.30
  4759.6 1765.51  4809.8 1765.42  4849.9 1766.39  4880.0 1765.65  4898.7 1766.16
  4903.7 1765.50  4930.2 1769.12  4940.2 1769.76  4970.4 1769.31  4980.4 1767.06
  4990.4 1762.01  4997.5 1761.23  5000.2 1760.73  5003.5 1761.23  5019.1 1767.48
  5024.1 1767.53  5030.6 1768.60  5054.7 1768.79  5114.4 1768.55  5171.6 1769.70
  5230.3 1772.00  5267.5 1774.22  5414.3 1778.79  5508.2 1780.96  5541.7 1781.06
#Mann=7,-1,0
  4466.2     0.1       0  4517.7    0.05       0  4703.8    0.16       0
  4997.5    0.07       0  5003.5    0.16       0  5054.7    0.05       0
  5414.3     0.1       0
Bank Sta=4997.5,5003.5
Exp/Cntr=0.3,0.1

Chan Stop Cuts=-1