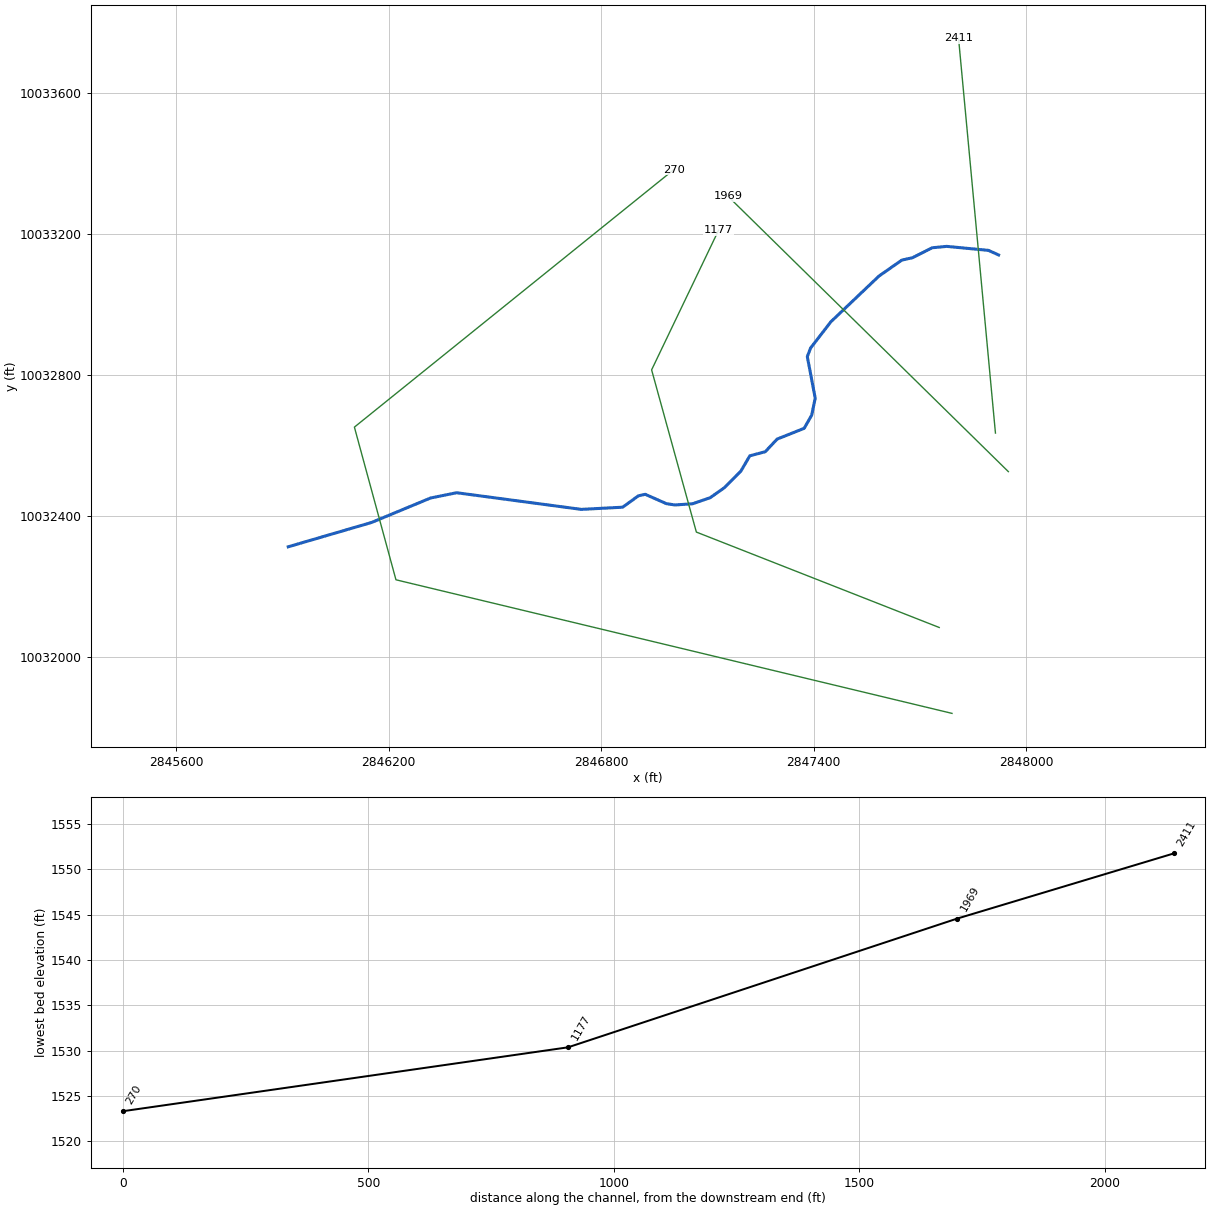
--- UNT062 IN SNOGR.prj (project) ---

Proj Title=UNT062 IN SNOGR Base Level Engineering
Current Plan=p01
Default Exp/Contr=0.3,0.1
English Units
Geom File=g01
Flow File=f01
Plan File=p01
BEGIN DESCRIPTION:
UNT062 IN SNOGR
END DESCRIPTION:

--- UNT062 IN SNOGR.p01 (plan) ---

Plan Title=Multiple Run
Short Identifier=Multiple
Geom File=g01
Flow File=f01
Subcritical Flow
K Sum by GR= 0
Std Step Tol= 0.01
Critical Tol= 0.01
Num of Std Step Trials= 20
Max Error Tol= 0.3
Flow Tol Ratio= 0.001
Split Flow NTrial= 30
Split Flow Tol= 0.02
Split Flow Ratio= 0.02
Log Output Level= 0
Friction Slope Method= 1
Unsteady Friction Slope Method= 2
Unsteady Bridges Friction Slope Method= 1
Parabolic Critical Depth
Global Vel Dist=  1 , 1 , 1
Global Log Level= 0
CheckData=True
Encroach Param= -1, 0, 0, 0
BEGIN DESCRIPTION:
Multiple Run
END DESCRIPTION:

--- UNT062 IN SNOGR.f01 (steady flow) ---

Flow Title=Multiple
Number of Profiles=7
Profile Names=10-year,25-year,50-year,1pct_min,100-year,1pct_plu,500-year
River Rch & RM= UNT062 IN SNOGR,Reach-1,2411
     500     699     865     787    1065    1440    1614
Boundary for River Rch & Prof#=UNT062 IN SNOGR,Reach-1,1
Up Type=0
Dn Type=3
Dn Slope=0.005
Boundary for River Rch & Prof#=UNT062 IN SNOGR,Reach-1,2
Up Type=0
Dn Type=3
Dn Slope=0.005
Boundary for River Rch & Prof#=UNT062 IN SNOGR,Reach-1,3
Up Type=0
Dn Type=3
Dn Slope=0.005
Boundary for River Rch & Prof#=UNT062 IN SNOGR,Reach-1,4
Up Type=0
Dn Type=3
Dn Slope=0.005
Boundary for River Rch & Prof#=UNT062 IN SNOGR,Reach-1,5
Up Type=0
Dn Type=3
Dn Slope=0.005
Boundary for River Rch & Prof#=UNT062 IN SNOGR,Reach-1,6
Up Type=0
Dn Type=3
Dn Slope=0.005
Boundary for River Rch & Prof#=UNT062 IN SNOGR,Reach-1,7
Up Type=0
Dn Type=3
Dn Slope=0.005

--- UNT062 IN SNOGR.g01 (geometry) ---

Geom Title=Existing Conditions

River Reach=UNT062 IN SNOGR,Reach-1
Reach XY= 30
      2847921.85     10033139.91      2847893.10     10033152.93
      2847775.29     10033164.26      2847734.36     10033160.29
      2847678.82     10033132.11      2847648.55     10033125.24
      2847583.92     10033079.88      2847448.35     10032950.37
      2847391.09     10032875.88      2847381.84     10032851.46
      2847404.11     10032733.67      2847394.27     10032685.80
      2847373.03     10032648.21      2847296.66     10032617.59
      2847263.06     10032581.76      2847219.45     10032570.12
      2847194.28     10032526.76      2847147.63     10032479.66
      2847107.69     10032451.39      2847057.89     10032434.12
      2847007.93     10032430.73      2846983.58     10032434.60
      2846924.22     10032460.97      2846904.83     10032456.56
      2846860.54     10032424.39      2846743.85     10032418.20
      2846391.70     10032465.43      2846318.09     10032450.43
      2846151.82     10032381.12      2845916.35     10032312.09

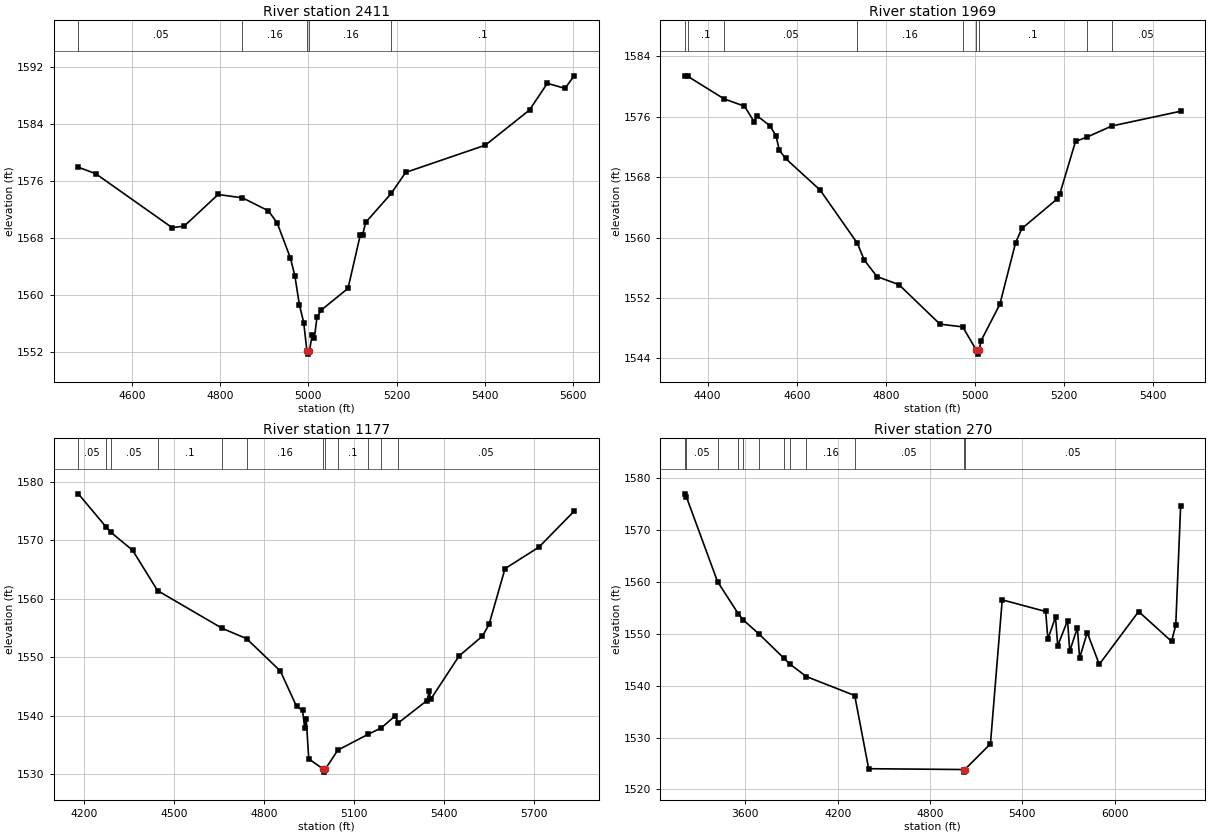
Type RM Length L Ch R = 1,2411,442,442,442
BEGIN DESCRIPTION:
UNT062 IN SNOGR 4.0
END DESCRIPTION:
XS GIS Cut Line= 2
      2847912.97     10032634.63      2847808.80     10033754.40
#Sta/Elev= 30
  4478.3 1577.96  4517.6 1577.06  4691.1 1569.49  4718.4 1569.71  4795.3 1574.14
  4850.6 1573.67  4909.5 1571.85  4929.3 1570.15  4959.5 1565.21  4969.5 1562.71
  4979.6 1558.71  4989.6 1556.16  4996.6 1552.27  4999.4 1551.77  5002.6 1552.27
  5008.7 1554.47  5013.7 1554.08  5019.7 1556.96  5029.8 1557.97  5090.0 1560.99
  5117.9 1568.49  5122.9 1568.47  5130.2 1570.24  5188.3 1574.31  5220.6 1577.23
  5401.4 1581.05  5501.8 1585.99  5542.0 1589.72  5582.1 1589.01  5602.9 1590.77
#Mann=5,-1,0
  4478.3    0.05       0  4850.6    0.16       0  4996.6    0.07       0
  5002.6    0.16       0  5188.3     0.1       0
Bank Sta=4996.6,5002.6
Exp/Cntr=0.3,0.1

Type RM Length L Ch R = 1,1969,792,792,792
BEGIN DESCRIPTION:
UNT062 IN SNOGR 3.0
END DESCRIPTION:
XS GIS Cut Line= 2
      2847949.41     10032525.28      2847157.78     10033306.49
#Sta/Elev= 30
  4348.8 1581.43  4355.9 1581.35  4437.1 1578.37  4482.7 1577.41  4504.0 1575.38
  4511.0 1576.13  4539.3 1574.84  4553.4 1573.49  4560.6 1571.62  4574.7 1570.49
  4652.4 1566.30  4735.8 1559.26  4751.4 1557.03  4779.7 1554.85  4829.2 1553.77
  4921.2 1548.54  4972.2 1548.18  5003.0 1545.07  5005.8 1544.57  5009.0 1545.07
  5013.0 1546.30  5055.5 1551.17  5090.9 1559.34  5105.0 1561.21  5182.8 1565.06
  5189.9 1565.76  5225.2 1572.74  5250.3 1573.30  5306.9 1574.79  5461.0 1576.74
#Mann=9,-1,0
  4348.8    0.05       0  4355.9     0.1       0  4437.1    0.05       0
  4735.8    0.16       0  4972.2     0.1       0  5003.0    0.07       0
  5009.0     0.1       0  5250.3    0.16       0  5306.9    0.05       0
Bank Sta=5003,5009
Exp/Cntr=0.3,0.1

Type RM Length L Ch R = 1,1177,907,907,907
BEGIN DESCRIPTION:
UNT062 IN SNOGR 2.0
END DESCRIPTION:
XS GIS Cut Line= 4
      2847754.28     10032083.15      2847068.57     10032353.82
      2846942.26     10032813.96      2847131.19     10033209.82
#Sta/Elev= 30
  4181.6 1577.91  4274.8 1572.21  4290.3 1571.33  4362.7 1568.26  4445.7 1561.38
  4661.5 1554.93  4742.4 1553.18  4855.1 1547.65  4909.2 1541.59  4929.1 1540.91
  4936.2 1537.98  4941.4 1539.40  4949.8 1532.64  4998.7 1530.88  5001.4 1530.38
  5004.7 1530.88  5046.8 1534.14  5147.7 1536.84  5190.9 1537.91  5237.6 1539.97
  5248.5 1538.79  5343.9 1542.61  5351.3 1544.18  5356.5 1542.83  5451.1 1550.23
  5528.7 1553.60  5550.8 1555.60  5604.2 1565.14  5717.0 1568.80  5834.6 1574.95
#Mann=12,-1,0
  4181.6    0.05       0  4274.8     0.1       0  4290.3    0.05       0
  4445.7     0.1       0  4661.5    0.05       0  4742.4    0.16       0
  4998.7    0.07       0  5004.7    0.16       0  5046.8     0.1       0
  5147.7    0.16       0  5190.9     0.1       0  5248.5    0.05       0
Bank Sta=4998.7,5004.7
Exp/Cntr=0.3,0.1

Type RM Length L Ch R = 1,270,0,0,0
BEGIN DESCRIPTION:
UNT062 IN SNOGR 1.0
END DESCRIPTION:
XS GIS Cut Line= 4
      2847790.37     10031839.55      2846220.47     10032218.49
      2846103.18     10032651.56      2847004.46     10033381.59
#Sta/Elev= 30
  3206.3 1577.00  3216.3 1576.44  3418.9 1560.08  3553.3 1553.90  3586.5 1552.67
  3689.1 1549.96  3851.5 1545.27  3888.8 1544.18  3996.8 1541.76  4311.1 1538.10
  4401.6 1523.99  5020.6 1523.83  5023.3 1523.33  5026.6 1523.83  5193.4 1528.78
  5270.0 1556.55  5552.4 1554.31  5566.8 1549.01  5616.4 1553.22  5630.8 1547.70
  5694.7 1552.56  5709.1 1546.68  5758.7 1551.17  5773.0 1545.30  5822.6 1550.24
  5900.9 1544.11  6156.7 1554.30  6370.6 1548.55  6398.1 1551.65  6429.8 1574.63
#Mann=12,-1,0
  3206.3    0.16       0  3216.3    0.05       0  3418.9     0.1       0
  3553.3    0.05       0  3586.5     0.1       0  3689.1    0.05       0
  3851.5     0.1       0  3888.8    0.05       0  3996.8    0.16       0
  4311.1    0.05       0  5020.6   0.033       0  5026.6    0.05       0
Bank Sta=5020.6,5026.6
Exp/Cntr=0.3,0.1

Chan Stop Cuts=-1