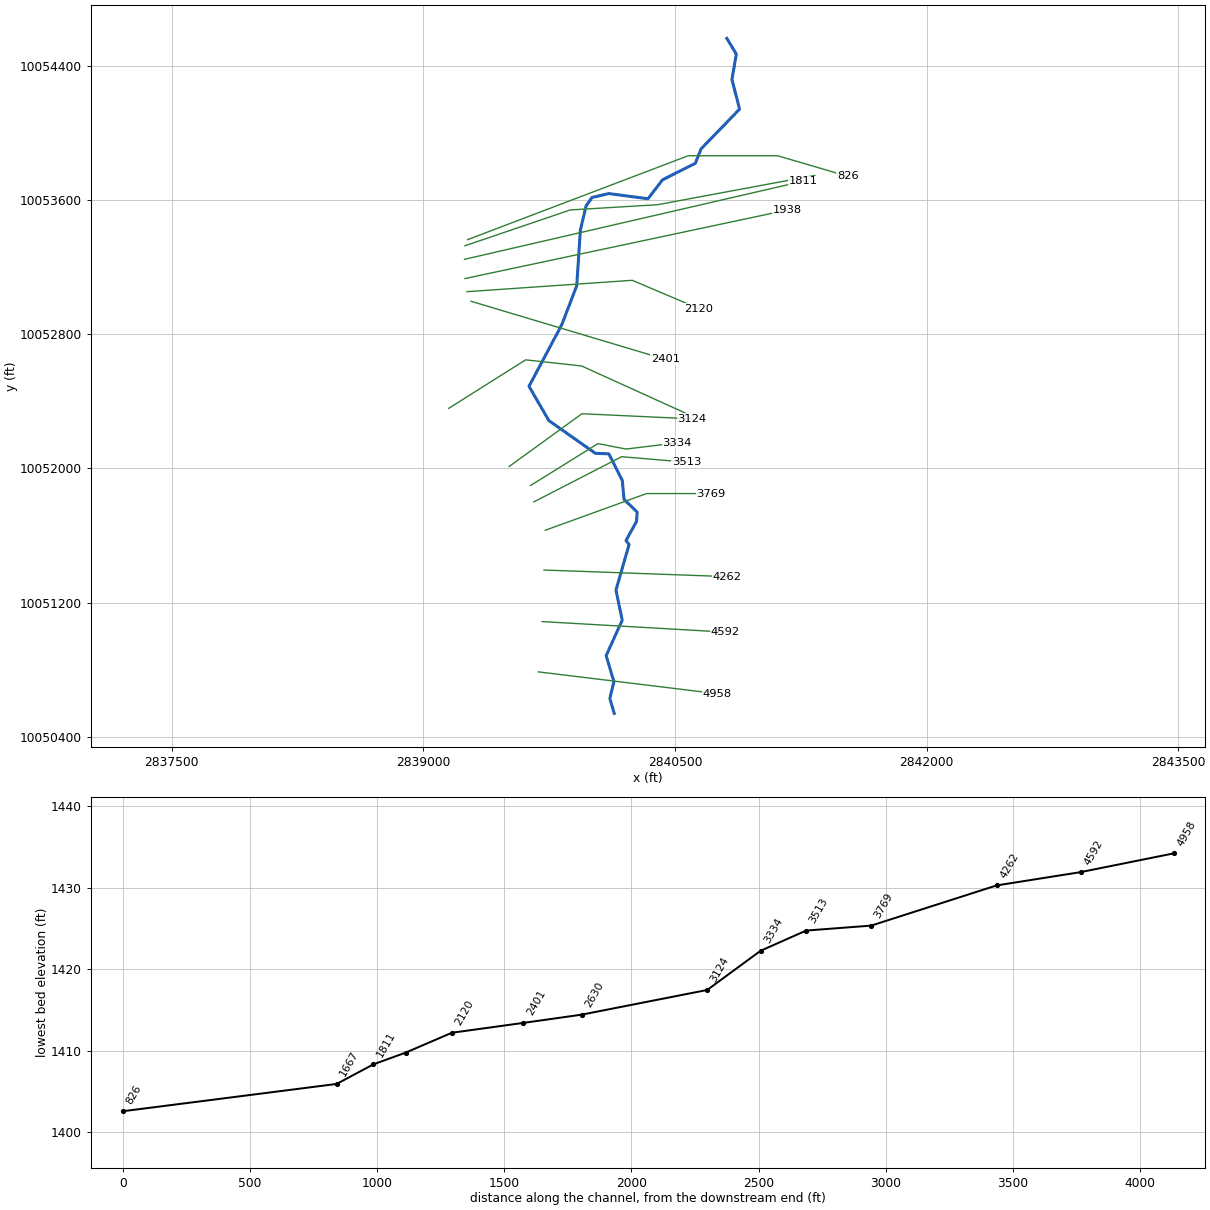
--- UNT063 IN SNOGR.prj (project) ---

Proj Title=UNT063 IN SNOGR Base Level Engineering
Current Plan=p01
Default Exp/Contr=0.3,0.1
English Units
Geom File=g01
Flow File=f01
Plan File=p01
BEGIN DESCRIPTION:
UNT063 IN SNOGR
END DESCRIPTION:

--- UNT063 IN SNOGR.p01 (plan) ---

Plan Title=Multiple Run
Short Identifier=Multiple
Geom File=g01
Flow File=f01
Subcritical Flow
K Sum by GR= 0
Std Step Tol= 0.01
Critical Tol= 0.01
Num of Std Step Trials= 20
Max Error Tol= 0.3
Flow Tol Ratio= 0.001
Split Flow NTrial= 30
Split Flow Tol= 0.02
Split Flow Ratio= 0.02
Log Output Level= 0
Friction Slope Method= 1
Unsteady Friction Slope Method= 2
Unsteady Bridges Friction Slope Method= 1
Parabolic Critical Depth
Global Vel Dist=  1 , 1 , 1
Global Log Level= 0
CheckData=True
Encroach Param= -1, 0, 0, 0
BEGIN DESCRIPTION:
Multiple Run
END DESCRIPTION:

--- UNT063 IN SNOGR.f01 (steady flow) ---

Flow Title=Multiple
Number of Profiles=7
Profile Names=10-year,25-year,50-year,1pct_min,100-year,1pct_plu,500-year
River Rch & RM= UNT063 IN SNOGR,Reach-1,4958
     819    1177    1485    1372    1855    2509    2904
Boundary for River Rch & Prof#=UNT063 IN SNOGR,Reach-1,1
Up Type=0
Dn Type=3
Dn Slope=0.005
Boundary for River Rch & Prof#=UNT063 IN SNOGR,Reach-1,2
Up Type=0
Dn Type=3
Dn Slope=0.005
Boundary for River Rch & Prof#=UNT063 IN SNOGR,Reach-1,3
Up Type=0
Dn Type=3
Dn Slope=0.005
Boundary for River Rch & Prof#=UNT063 IN SNOGR,Reach-1,4
Up Type=0
Dn Type=3
Dn Slope=0.005
Boundary for River Rch & Prof#=UNT063 IN SNOGR,Reach-1,5
Up Type=0
Dn Type=3
Dn Slope=0.005
Boundary for River Rch & Prof#=UNT063 IN SNOGR,Reach-1,6
Up Type=0
Dn Type=3
Dn Slope=0.005
Boundary for River Rch & Prof#=UNT063 IN SNOGR,Reach-1,7
Up Type=0
Dn Type=3
Dn Slope=0.005

--- UNT063 IN SNOGR.g01 (geometry) ---

Geom Title=Existing Conditions

River Reach=UNT063 IN SNOGR,Reach-1
Reach XY= 30
      2840138.12     10050539.42      2840112.15     10050628.72
      2840136.47     10050727.93      2840090.09     10050883.33
      2840185.96     10051094.93      2840148.59     10051274.02
      2840227.06     10051546.24      2840208.31     10051569.16
      2840271.51     10051683.74      2840274.98     10051739.30
      2840196.63     10051814.99      2840186.42     10051927.86
      2840106.07     10052086.00      2840026.11     10052089.09
      2839748.55     10052284.29      2839630.24     10052488.52
      2839825.03     10052854.31      2839914.90     10053088.23
      2839936.41     10053418.72      2839970.50     10053563.58
      2840005.48     10053613.49      2840105.03     10053637.27
      2840339.52     10053606.16      2840425.99     10053718.72
      2840621.78     10053817.39      2840656.54     10053904.01
      2840885.46     10054140.14      2840839.88     10054317.74
      2840866.11     10054468.25      2840809.62     10054562.21

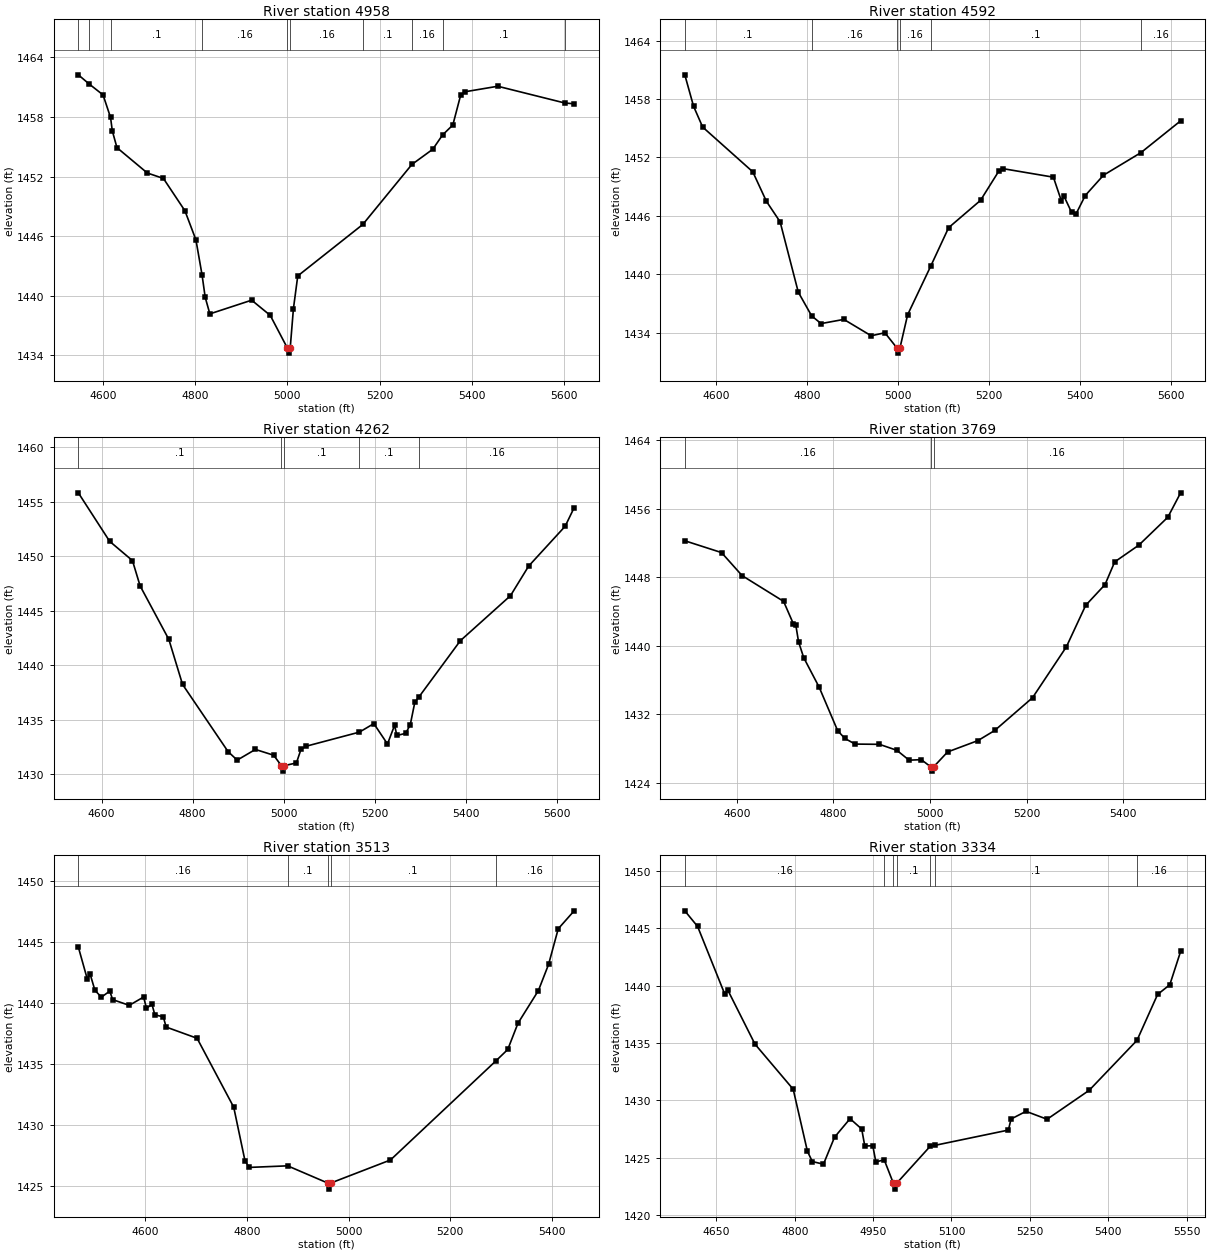
Type RM Length L Ch R = 1,4958,366,366,366
BEGIN DESCRIPTION:
UNT063 IN SNOGR 9.0
END DESCRIPTION:
XS GIS Cut Line= 2
      2839685.26     10050786.87      2840752.95     10050656.66
#Sta/Elev= 30
  4546.4 1462.24  4569.3 1461.34  4600.0 1460.22  4616.3 1457.95  4620.1 1456.60
  4630.2 1454.91  4696.0 1452.36  4731.0 1451.81  4777.6 1448.56  4801.5 1445.63
  4814.8 1442.10  4821.6 1439.85  4831.7 1438.18  4922.4 1439.56  4962.7 1438.03
  5000.0 1434.73  5002.7 1434.23  5006.0 1434.73  5013.0 1438.71  5022.4 1442.00
  5163.5 1447.18  5270.0 1453.22  5315.3 1454.75  5336.4 1456.18  5358.8 1457.19
  5375.7 1460.18  5385.8 1460.54  5456.3 1461.09  5601.2 1459.41  5622.0 1459.32
#Mann=10,-1,0
  4546.4     0.1       0  4569.3    0.16       0  4616.3     0.1       0
  4814.8    0.16       0  5000.0    0.07       0  5006.0    0.16       0
  5163.5     0.1       0  5270.0    0.16       0  5336.4     0.1       0
  5601.2    0.05       0
Bank Sta=5000,5006
Exp/Cntr=0.3,0.1

Type RM Length L Ch R = 1,4592,330,330,330
BEGIN DESCRIPTION:
UNT063 IN SNOGR 8.0
END DESCRIPTION:
XS GIS Cut Line= 2
      2839709.24     10051086.38      2840797.85     10051023.87
#Sta/Elev= 30
  4531.3 1460.48  4550.6 1457.25  4570.6 1455.12  4680.8 1450.53  4710.8 1447.50
  4740.9 1445.40  4780.9 1438.18  4810.3 1435.75  4831.0 1434.96  4881.1 1435.39
  4941.2 1433.71  4971.3 1434.02  4998.3 1432.43  5001.0 1431.93  5004.3 1432.43
  5021.3 1435.86  5071.8 1440.82  5111.5 1444.80  5181.6 1447.60  5221.7 1450.59
  5231.7 1450.85  5341.9 1449.98  5359.7 1447.52  5364.7 1448.08  5381.9 1446.37
  5391.9 1446.23  5412.0 1448.10  5452.0 1450.18  5534.5 1452.50  5621.7 1455.76
#Mann=6,-1,0
  4531.3     0.1       0  4810.3    0.16       0  4998.3    0.07       0
  5004.3    0.16       0  5071.8     0.1       0  5534.5    0.16       0
Bank Sta=4998.3,5004.3
Exp/Cntr=0.3,0.1

Type RM Length L Ch R = 1,4262,493,493,493
BEGIN DESCRIPTION:
Mapping XS 46d13e30
END DESCRIPTION:
XS GIS Cut Line= 2
      2839719.67     10051393.67      2840808.27     10051354.60
#Sta/Elev= 30
  4548.8 1455.84  4617.6 1451.39  4667.7 1449.62  4684.5 1447.30  4747.7 1442.38
  4777.7 1438.26  4877.8 1432.09  4897.8 1431.31  4937.8 1432.29  4977.9 1431.76
  4994.9 1430.80  4997.6 1430.30  5000.9 1430.80  5027.9 1431.05  5037.9 1432.29
  5047.9 1432.57  5166.3 1433.88  5198.0 1434.66  5228.0 1432.79  5243.6 1434.51
  5248.6 1433.57  5268.1 1433.77  5278.1 1434.57  5288.1 1436.63  5296.6 1437.08
  5388.1 1442.27  5498.2 1446.40  5538.2 1449.12  5618.3 1452.77  5638.1 1454.48
#Mann=5,-1,0
  4548.8     0.1       0  4994.9    0.07       0  5000.9     0.1       0
  5166.3     0.1       0  5296.6    0.16       0
Bank Sta=4994.9,5000.9
Exp/Cntr=0.3,0.1

Type RM Length L Ch R = 1,3769,256,256,256
BEGIN DESCRIPTION:
UNT063 IN SNOGR 7.0
END DESCRIPTION:
XS GIS Cut Line= 3
      2839726.99     10051630.63      2840331.12     10051849.36
      2840715.01     10051849.36
#Sta/Elev= 30
  4492.5 1452.28  4568.5 1450.90  4611.1 1448.21  4697.0 1445.20  4717.0 1442.61
  4722.3 1442.43  4728.0 1440.47  4738.7 1438.62  4770.6 1435.18  4808.9 1430.10
  4823.8 1429.19  4845.0 1428.53  4895.5 1428.50  4931.5 1427.80  4956.8 1426.65
  4982.1 1426.71  5001.6 1425.87  5004.3 1425.37  5007.6 1425.87  5036.5 1427.61
  5099.4 1428.94  5134.1 1430.12  5212.4 1433.95  5282.4 1439.89  5322.4 1444.74
  5362.4 1447.16  5382.4 1449.81  5432.4 1451.77  5492.4 1455.03  5518.9 1457.88
#Mann=3,-1,0
  4492.5    0.16       0  5001.6    0.07       0  5007.6    0.16       0
Bank Sta=5001.6,5007.6
Exp/Cntr=0.3,0.1

Type RM Length L Ch R = 1,3513,179,179,179
BEGIN DESCRIPTION:
UNT063 IN SNOGR 6.0
END DESCRIPTION:
XS GIS Cut Line= 3
      2839659.39     10051799.89      2840182.40     10052068.99
      2840568.66     10052036.44
#Sta/Elev= 30
  4468.2 1444.61  4485.8 1441.99  4491.4 1442.39  4500.9 1441.06  4513.6 1440.50
  4530.1 1441.00  4535.7 1440.30  4568.4 1439.83  4596.6 1440.51  4602.3 1439.60
  4613.2 1439.90  4618.8 1439.05  4635.4 1438.89  4641.0 1438.05  4701.9 1437.13
  4774.0 1431.48  4796.2 1427.08  4804.5 1426.54  4880.1 1426.67  4959.0 1425.26
  4961.7 1424.76  4965.0 1425.26  5082.5 1427.15  5289.6 1435.26  5313.3 1436.21
  5333.4 1438.36  5373.6 1441.04  5393.6 1443.18  5412.7 1446.11  5444.0 1447.58
#Mann=5,-1,0
  4468.2    0.16       0  4880.1     0.1       0  4959.0    0.07       0
  4965.0     0.1       0  5289.6    0.16       0
Bank Sta=4959,4965
Exp/Cntr=0.3,0.1

Type RM Length L Ch R = 1,3334,210,210,210
BEGIN DESCRIPTION:
Mapping XS 9a90fe36
END DESCRIPTION:
XS GIS Cut Line= 4
      2839639.85     10051897.54      2840041.34     10052147.11
      2840208.44     10052114.56      2840512.23     10052151.45
#Sta/Elev= 30
  4589.6 1446.50  4614.1 1445.14  4666.1 1439.25  4671.9 1439.60  4723.9 1434.90
  4797.1 1430.97  4824.3 1425.57  4833.7 1424.68  4855.0 1424.45  4876.2 1426.80
  4905.9 1428.41  4928.2 1427.51  4934.1 1426.03  4949.4 1426.06  4955.3 1424.64
  4971.2 1424.84  4988.9 1422.78  4991.7 1422.28  4994.9 1422.78  5059.5 1426.02
  5068.3 1426.09  5209.0 1427.42  5214.0 1428.38  5242.7 1429.05  5283.0 1428.36
  5363.6 1430.88  5455.1 1435.23  5494.5 1439.22  5517.9 1440.07  5538.6 1442.97
#Mann=7,-1,0
  4589.6    0.16       0  4971.2     0.1       0  4988.9    0.07       0
  4994.9     0.1       0  5059.5    0.05       0  5068.3     0.1       0
  5455.1    0.16       0
Bank Sta=4988.9,4994.9
Exp/Cntr=0.3,0.1

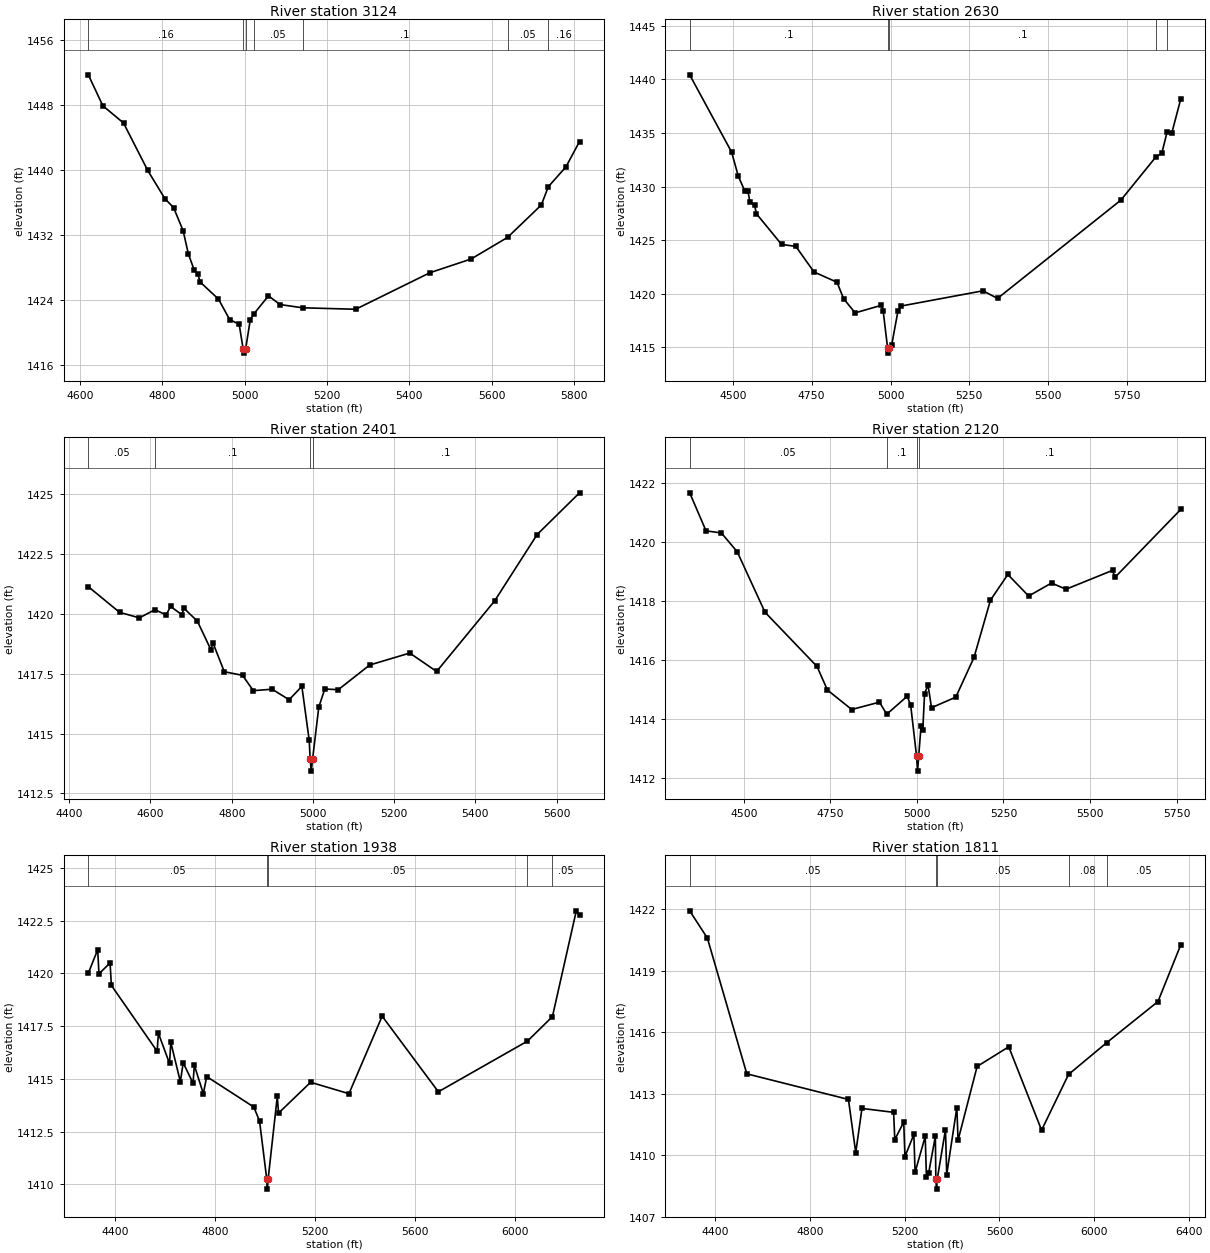
Type RM Length L Ch R = 1,3124,494,494,494
BEGIN DESCRIPTION:
UNT063 IN SNOGR 5.0
END DESCRIPTION:
XS GIS Cut Line= 3
      2839511.85     10052010.42      2839945.85     10052325.07
      2840601.19     10052294.69
#Sta/Elev= 30
  4620.7 1451.67  4655.8 1447.87  4706.1 1445.75  4764.7 1439.93  4806.6 1436.44
  4827.5 1435.36  4850.7 1432.52  4863.5 1429.65  4877.7 1427.67  4886.2 1427.19
  4892.4 1426.19  4936.5 1424.11  4963.6 1421.60  4986.8 1421.01  4996.4 1417.97
  4999.2 1417.47  5002.4 1417.97  5013.8 1421.60  5022.4 1422.29  5057.9 1424.51
  5085.9 1423.44  5140.6 1423.04  5269.5 1422.86  5449.7 1427.35  5549.8 1429.04
  5638.1 1431.69  5720.0 1435.67  5737.1 1437.92  5780.0 1440.37  5812.8 1443.47
#Mann=7,-1,0
  4620.7    0.16       0  4996.4    0.07       0  5002.4    0.16       0
  5022.4    0.05       0  5140.6     0.1       0  5638.1    0.05       0
  5737.1    0.16       0
Bank Sta=4996.4,5002.4
Exp/Cntr=0.3,0.1

Type RM Length L Ch R = 1,2630,229,229,229
BEGIN DESCRIPTION:
UNT063 IN SNOGR 4.0
END DESCRIPTION:
XS GIS Cut Line= 4
      2839151.96     10052357.18      2839610.33     10052646.27
      2839943.66     10052609.81      2840563.31     10052328.63
#Sta/Elev= 30
  4363.1 1440.43  4496.1 1433.21  4517.3 1430.96  4538.5 1429.54  4547.8 1429.59
  4553.8 1428.59  4569.0 1428.23  4574.9 1427.45  4654.5 1424.59  4699.7 1424.41
  4757.3 1422.02  4830.3 1421.06  4851.5 1419.51  4888.0 1418.20  4971.4 1418.91
  4976.5 1418.42  4990.7 1414.94  4993.4 1414.44  4996.7 1414.94  5003.7 1415.20
  5023.9 1418.41  5033.9 1418.84  5293.2 1420.26  5339.4 1419.55  5730.6 1428.73
  5840.7 1432.73  5860.6 1433.13  5877.0 1435.07  5892.2 1435.01  5920.8 1438.21
#Mann=5,-1,0
  4363.1     0.1       0  4990.7    0.07       0  4996.7     0.1       0
  5840.7    0.05       0  5877.0    0.16       0
Bank Sta=4990.7,4996.7
Exp/Cntr=0.3,0.1

Type RM Length L Ch R = 1,2401,281,281,281
BEGIN DESCRIPTION:
UNT063 IN SNOGR 3.0
END DESCRIPTION:
XS GIS Cut Line= 2
      2839284.81     10052995.23      2840443.56     10052648.90
#Sta/Elev= 30
  4447.0 1421.13  4523.9 1420.06  4572.6 1419.83  4611.0 1420.17  4638.7 1419.95
  4649.3 1420.31  4677.2 1419.96  4682.4 1420.23  4715.5 1419.69  4748.7 1418.50
  4753.9 1418.78  4781.8 1417.58  4826.6 1417.43  4853.2 1416.79  4899.6 1416.85
  4941.4 1416.41  4972.7 1416.97  4990.9 1414.71  4993.1 1413.93  4995.9 1413.43
  4999.1 1413.93  5014.4 1416.10  5029.2 1416.86  5062.4 1416.83  5139.7 1417.86
  5238.4 1418.36  5304.6 1417.59  5447.5 1420.54  5552.1 1423.31  5656.4 1425.05
#Mann=4,-1,0
  4447.0    0.05       0  4611.0     0.1       0  4993.1    0.07       0
  4999.1     0.1       0
Bank Sta=4993.1,4999.1
Exp/Cntr=0.3,0.1

Type RM Length L Ch R = 1,2120,182,182,182
BEGIN DESCRIPTION:
Mapping XS 64ba03fb
END DESCRIPTION:
XS GIS Cut Line= 3
      2839261.41     10053052.52      2840245.75     10053120.23
      2840643.85     10052951.10
#Sta/Elev= 30
  4343.3 1421.66  4390.5 1420.37  4434.7 1420.30  4480.7 1419.66  4560.9 1417.61
  4711.2 1415.77  4741.3 1414.97  4811.5 1414.31  4891.6 1414.56  4912.7 1414.15
  4971.8 1414.76  4981.9 1414.45  4998.9 1412.72  5001.7 1412.22  5004.9 1412.72
  5011.8 1413.75  5016.8 1413.62  5022.0 1414.85  5032.0 1415.14  5042.0 1414.37
  5112.2 1414.73  5164.9 1416.08  5212.4 1418.02  5262.5 1418.89  5322.7 1418.16
  5388.8 1418.60  5430.7 1418.39  5565.2 1419.03  5571.9 1418.79  5762.5 1421.10
#Mann=4,-1,0
  4343.3    0.05       0  4912.7     0.1       0  4998.9    0.07       0
  5004.9     0.1       0
Bank Sta=4998.9,5004.9
Exp/Cntr=0.3,0.1

Type RM Length L Ch R = 1,1938,127,127,127
BEGIN DESCRIPTION:
Mapping XS 952b4ac4
END DESCRIPTION:
XS GIS Cut Line= 2
      2839248.38     10053130.65      2841171.06     10053539.12
#Sta/Elev= 30
  4293.0 1420.01  4330.4 1421.12  4335.5 1419.98  4380.0 1420.49  4385.1 1419.43
  4568.2 1416.31  4573.4 1417.16  4617.9 1415.73  4623.0 1416.73  4661.1 1414.87
  4672.6 1415.76  4712.0 1414.80  4717.1 1415.65  4753.1 1414.30  4766.7 1415.11
  4955.0 1413.67  4978.0 1413.01  5006.7 1410.28  5009.5 1409.78  5012.7 1410.28
  5049.1 1414.17  5054.2 1413.38  5182.5 1414.84  5335.9 1414.30  5468.8 1417.97
  5693.7 1414.39  6050.3 1416.79  6150.2 1417.95  6245.7 1422.96  6258.6 1422.76
#Mann=5,-1,0
  4293.0    0.05       0  5006.7    0.04       0  5012.7    0.05       0
  6050.3    0.08       0  6150.2    0.05       0
Bank Sta=5006.7,5012.7
Exp/Cntr=0.3,0.1

Type RM Length L Ch R = 1,1811,144,144,144
BEGIN DESCRIPTION:
Mapping XS b26d99df
END DESCRIPTION:
XS GIS Cut Line= 2
      2839245.79     10053245.24      2841265.07     10053711.02
#Sta/Elev= 30
  4293.1 1421.93  4367.7 1420.60  4534.1 1413.97  4962.9 1412.72  4993.7 1410.12
  5019.9 1412.28  5153.4 1412.09  5158.5 1410.76  5196.1 1411.61  5201.3 1409.93
  5238.9 1411.01  5244.0 1409.16  5286.8 1410.91  5291.9 1408.95  5301.6 1409.14
  5329.6 1410.92  5331.7 1408.84  5334.5 1408.34  5337.7 1408.84  5372.3 1411.25
  5377.5 1409.05  5420.2 1412.32  5425.4 1410.73  5505.8 1414.33  5639.2 1415.29
  5777.8 1411.22  5891.5 1413.94  6053.4 1415.50  6268.8 1417.50  6365.4 1420.28
#Mann=5,-1,0
  4293.1    0.05       0  5331.7    0.04       0  5337.7    0.05       0
  5891.5    0.08       0  6053.4    0.05       0
Bank Sta=5331.7,5337.7
Exp/Cntr=0.3,0.1

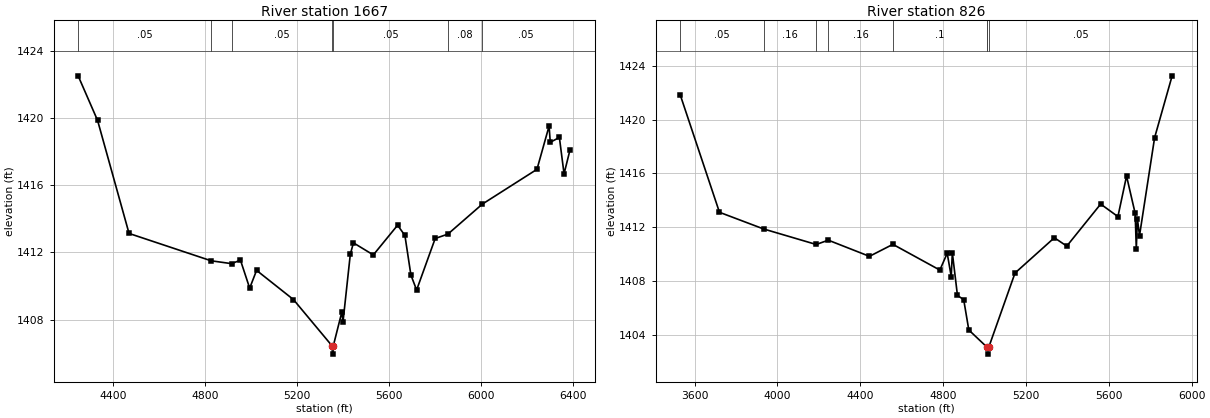
Type RM Length L Ch R = 1,1667,841,841,841
BEGIN DESCRIPTION:
Mapping XS 0c8074d3
END DESCRIPTION:
XS GIS Cut Line= 4
      2839248.37     10053325.96      2839875.95     10053539.50
      2840396.79     10053570.75      2841333.91     10053745.16
#Sta/Elev= 30
  4248.7 1422.52  4333.3 1419.86  4470.0 1413.13  4827.0 1411.50  4915.7 1411.33
  4954.2 1411.54  4994.3 1409.87  5024.3 1410.93  5184.6 1409.19  5351.9 1406.44
  5354.7 1405.94  5357.9 1406.44  5394.9 1408.45  5399.9 1407.86  5431.7 1411.89
  5445.3 1412.57  5531.7 1411.85  5637.2 1413.62  5669.0 1413.01  5695.1 1410.65
  5719.9 1409.76  5800.6 1412.83  5855.8 1413.09  6005.8 1414.88  6243.0 1416.95
  6295.7 1419.53  6300.8 1418.56  6340.4 1418.85  6360.7 1416.68  6386.6 1418.11
#Mann=7,-1,0
  4248.7    0.05       0  4827.0    0.16       0  4915.7    0.05       0
  5351.9    0.04       0  5357.9    0.05       0  5855.8    0.08       0
  6005.8    0.05       0
Bank Sta=5351.9,5357.9
Exp/Cntr=0.3,0.1

Type RM Length L Ch R = 1,826,0,0,0
BEGIN DESCRIPTION:
UNT063 IN SNOGR 2.0
END DESCRIPTION:
XS GIS Cut Line= 4
      2839263.96     10053362.41      2840579.08     10053862.42
      2841112.93     10053862.42      2841529.61     10053740.02
#Sta/Elev= 30
  3530.6 1421.83  3719.9 1413.12  3933.4 1411.88  4187.1 1410.73  4245.4 1411.05
  4444.1 1409.85  4557.4 1410.74  4784.1 1408.83  4819.6 1410.08  4839.0 1408.35
  4844.4 1410.11  4869.1 1406.95  4899.3 1406.63  4924.0 1404.38  5011.5 1403.11
  5014.0 1403.09  5016.7 1402.59  5020.0 1403.09  5147.0 1408.61  5337.0 1411.23
  5397.0 1410.61  5560.6 1413.73  5643.9 1412.80  5685.6 1415.81  5727.3 1413.03
  5732.7 1410.40  5737.9 1412.65  5748.2 1411.39  5821.1 1418.66  5905.7 1423.25
#Mann=8,-1,0
  3530.6    0.05       0  3933.4    0.16       0  4187.1    0.05       0
  4245.4    0.16       0  4557.4     0.1       0  5011.5    0.05       0
  5014.0    0.07       0  5020.0    0.05       0
Bank Sta=5014,5020
Exp/Cntr=0.3,0.1

Chan Stop Cuts=-1