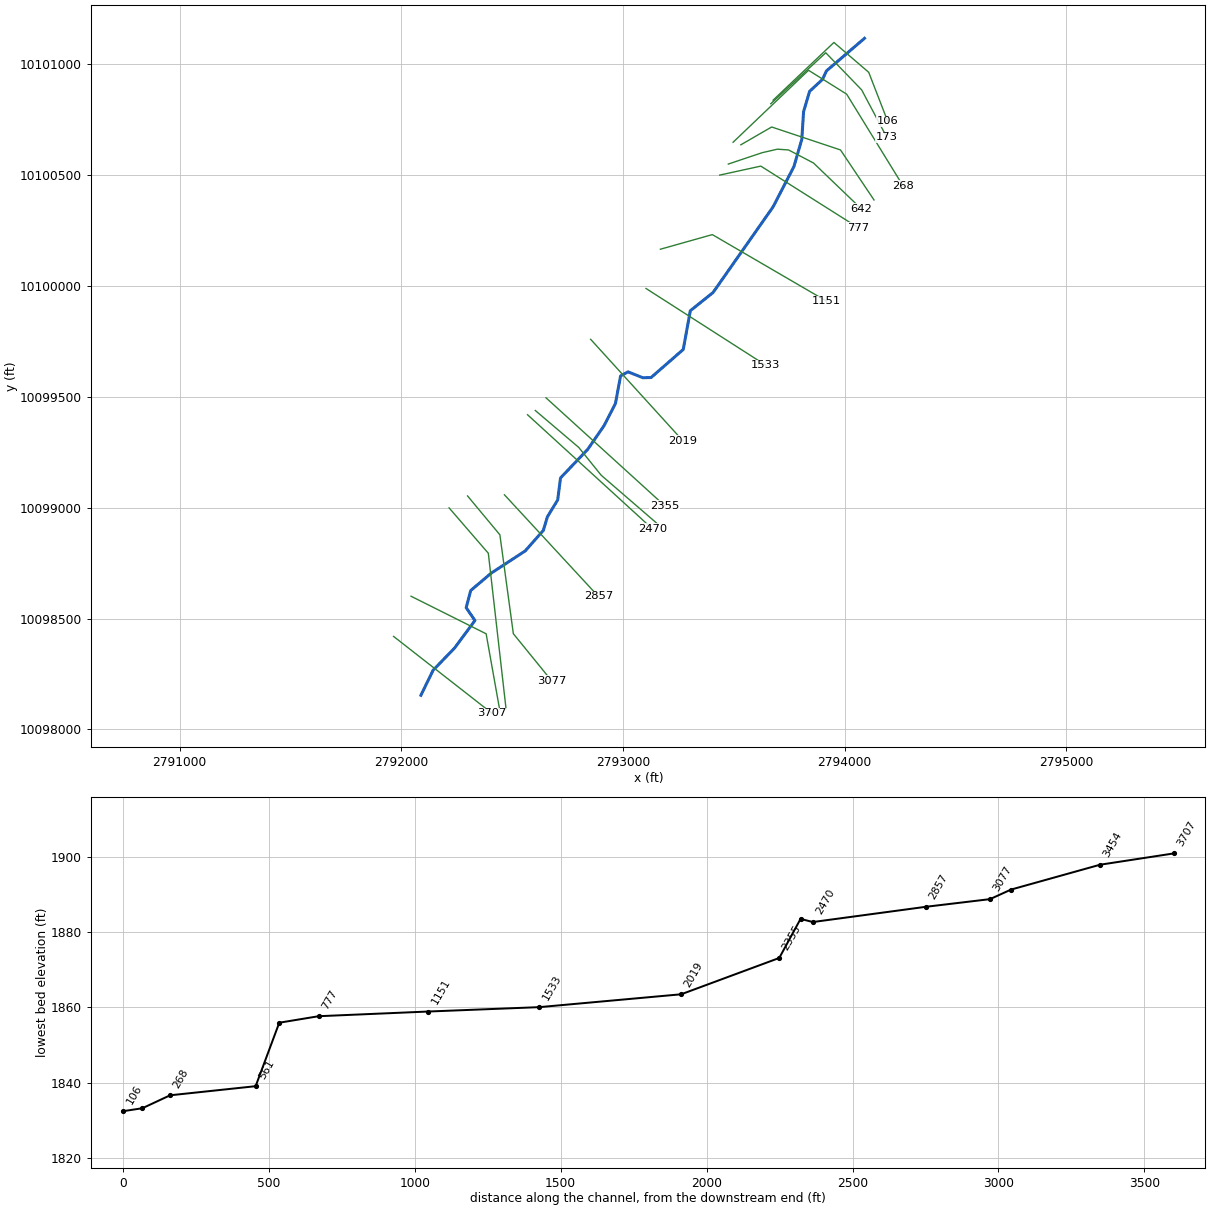
--- UNT064 IN NNOGR.prj (project) ---

Proj Title=UNT064 IN NNOGR Base Level Engineering
Current Plan=p01
Default Exp/Contr=0.3,0.1
English Units
Geom File=g01
Flow File=f01
Plan File=p01
BEGIN DESCRIPTION:
UNT064 IN NNOGR
END DESCRIPTION:

--- UNT064 IN NNOGR.p01 (plan) ---

Plan Title=Multiple Run
Short Identifier=Multiple
Geom File=g01
Flow File=f01
Subcritical Flow
K Sum by GR= 0
Std Step Tol= 0.01
Critical Tol= 0.01
Num of Std Step Trials= 20
Max Error Tol= 0.3
Flow Tol Ratio= 0.001
Split Flow NTrial= 30
Split Flow Tol= 0.02
Split Flow Ratio= 0.02
Log Output Level= 0
Friction Slope Method= 1
Unsteady Friction Slope Method= 2
Unsteady Bridges Friction Slope Method= 1
Parabolic Critical Depth
Global Vel Dist=  1 , 1 , 1
Global Log Level= 0
CheckData=True
Encroach Param= -1, 0, 0, 0
BEGIN DESCRIPTION:
Multiple Run
END DESCRIPTION:

--- UNT064 IN NNOGR.f01 (steady flow) ---

Flow Title=Multiple
Number of Profiles=7
Profile Names=10-year,25-year,50-year,1pct_min,100-year,1pct_plu,500-year
River Rch & RM= UNT064 IN NNOGR,Reach-1,3707
     424     586     721     651     881    1192    1317
Boundary for River Rch & Prof#=UNT064 IN NNOGR,Reach-1,1
Up Type=0
Dn Type=3
Dn Slope=0.005
Boundary for River Rch & Prof#=UNT064 IN NNOGR,Reach-1,2
Up Type=0
Dn Type=3
Dn Slope=0.005
Boundary for River Rch & Prof#=UNT064 IN NNOGR,Reach-1,3
Up Type=0
Dn Type=3
Dn Slope=0.005
Boundary for River Rch & Prof#=UNT064 IN NNOGR,Reach-1,4
Up Type=0
Dn Type=3
Dn Slope=0.005
Boundary for River Rch & Prof#=UNT064 IN NNOGR,Reach-1,5
Up Type=0
Dn Type=3
Dn Slope=0.005
Boundary for River Rch & Prof#=UNT064 IN NNOGR,Reach-1,6
Up Type=0
Dn Type=3
Dn Slope=0.005
Boundary for River Rch & Prof#=UNT064 IN NNOGR,Reach-1,7
Up Type=0
Dn Type=3
Dn Slope=0.005

--- UNT064 IN NNOGR.g01 (geometry) ---

Geom Title=Existing Conditions

River Reach=UNT064 IN NNOGR,Reach-1
Reach XY= 30
      2792088.47     10098153.73      2792143.43     10098266.47
      2792240.45     10098367.02      2792332.22     10098491.02
      2792292.63     10098548.81      2792313.18     10098626.26
      2792405.26     10098704.42      2792558.72     10098804.70
      2792640.78     10098897.48      2792658.95     10098958.53
      2792705.49     10099034.96      2792718.28     10099134.11
      2792840.67     10099262.76      2792914.78     10099370.06
      2792965.99     10099469.76      2792989.07     10099594.13
      2793022.89     10099612.65      2793089.72     10099586.14
      2793126.87     10099587.11      2793271.92     10099713.80
      2793303.69     10099888.28      2793406.30     10099970.57
      2793677.13     10100357.03      2793771.40     10100539.32
      2793806.82     10100662.24      2793814.63     10100786.19
      2793841.72     10100877.86      2793900.05     10100932.03
      2793917.76     10100970.05      2794089.45     10101117.19

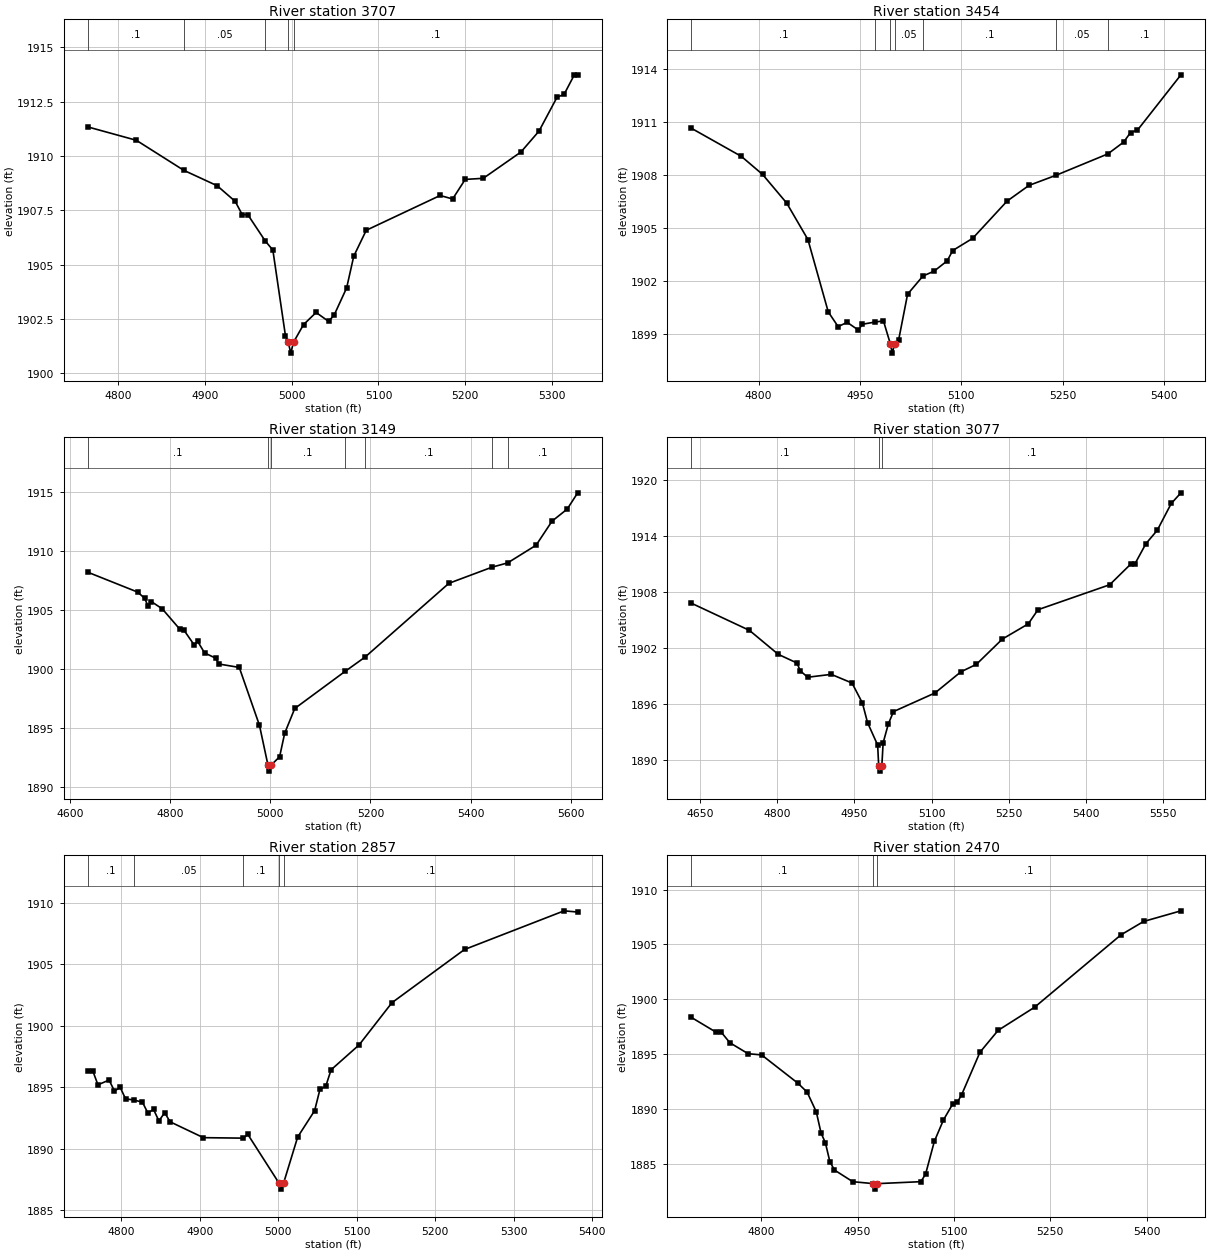
Type RM Length L Ch R = 1,3707,253,253,253
BEGIN DESCRIPTION:
UNT064 IN NNOGR 8.0
END DESCRIPTION:
XS GIS Cut Line= 2
      2791965.17     10098419.29      2792409.61     10098072.07
#Sta/Elev= 30
  4765.5 1911.33  4821.0 1910.72  4875.6 1909.34  4914.1 1908.63  4934.9 1907.91
  4943.0 1907.30  4949.4 1907.30  4969.5 1906.09  4978.3 1905.67  4992.8 1901.73
  4996.1 1901.43  4998.9 1900.93  5002.1 1901.43  5013.6 1902.24  5028.1 1902.80
  5042.5 1902.39  5048.9 1902.68  5063.3 1903.93  5071.5 1905.39  5085.9 1906.58
  5171.0 1908.18  5185.4 1908.02  5199.9 1908.92  5220.7 1908.97  5264.1 1910.18
  5284.9 1911.14  5305.7 1912.70  5313.8 1912.83  5325.6 1913.73  5329.5 1913.73
#Mann=5,-1,0
  4765.5     0.1       0  4875.6    0.05       0  4969.5     0.1       0
  4996.1    0.07       0  5002.1     0.1       0
Bank Sta=4996.1,5002.1
Exp/Cntr=0.3,0.1

Type RM Length L Ch R = 1,3454,305,305,305
BEGIN DESCRIPTION:
Mapping XS 4963c24b
END DESCRIPTION:
XS GIS Cut Line= 3
      2792044.17     10098600.31      2792382.71     10098431.04
      2792443.48     10098090.32
#Sta/Elev= 30
  4700.6 1910.63  4774.6 1909.04  4806.0 1908.02  4841.7 1906.40  4873.1 1904.34
  4903.2 1900.25  4917.8 1899.42  4931.2 1899.66  4947.9 1899.22  4953.5 1899.55
  4972.9 1899.68  4984.9 1899.74  4995.3 1898.42  4998.0 1897.92  5001.3 1898.42
  5007.3 1898.65  5020.6 1901.25  5043.4 1902.28  5059.7 1902.55  5079.1 1903.13
  5087.5 1903.72  5117.0 1904.41  5167.8 1906.51  5200.3 1907.40  5240.2 1907.97
  5317.0 1909.18  5340.5 1909.85  5350.6 1910.39  5360.8 1910.52  5425.2 1913.65
#Mann=7,-1,0
  4700.6     0.1       0  4972.9    0.05       0  4995.3   0.035       0
  5001.3    0.05       0  5043.4     0.1       0  5240.2    0.05       0
  5317.0     0.1       0
Bank Sta=4995.3,5001.3
Exp/Cntr=0.3,0.1

Type RM Length L Ch R = 1,3149,72,72,72
BEGIN DESCRIPTION:
Mapping XS 71a80e36
END DESCRIPTION:
XS GIS Cut Line= 3
      2792215.55     10098999.13      2792392.62     10098794.29
      2792472.48     10098092.88
#Sta/Elev= 30
  4636.8 1908.16  4735.3 1906.49  4749.5 1905.97  4756.1 1905.31  4762.9 1905.68
  4784.6 1905.07  4819.7 1903.34  4827.4 1903.29  4848.3 1902.01  4855.4 1902.30
  4869.1 1901.33  4891.0 1900.89  4897.6 1900.39  4938.3 1900.10  4978.6 1895.19
  4995.6 1891.81  4998.3 1891.31  5001.6 1891.81  5018.8 1892.53  5028.9 1894.52
  5049.0 1896.62  5149.6 1899.77  5189.4 1900.98  5356.5 1907.23  5442.7 1908.60
  5473.7 1908.96  5530.5 1910.46  5562.3 1912.50  5592.5 1913.52  5613.5 1914.90
#Mann=7,-1,0
  4636.8     0.1       0  4995.6    0.07       0  5001.6     0.1       0
  5149.6    0.05       0  5189.4     0.1       0  5442.7    0.05       0
  5473.7     0.1       0
Bank Sta=4995.6,5001.6
Exp/Cntr=0.3,0.1

Type RM Length L Ch R = 1,3077,220,220,220
BEGIN DESCRIPTION:
UNT064 IN NNOGR 7.0
END DESCRIPTION:
XS GIS Cut Line= 4
      2792298.88     10099052.95      2792444.70     10098877.62
      2792505.46     10098431.44      2792678.72     10098218.33
#Sta/Elev= 30
  4632.5 1906.80  4745.6 1903.88  4801.6 1901.31  4838.0 1900.38  4844.5 1899.54
  4858.9 1898.85  4904.8 1899.16  4945.2 1898.23  4965.4 1896.09  4975.5 1893.97
  4995.1 1891.57  4997.2 1889.27  4999.9 1888.77  5003.2 1889.27  5005.8 1891.81
  5015.9 1893.83  5025.9 1895.16  5106.7 1897.16  5157.1 1899.43  5187.4 1900.24
  5237.9 1902.95  5288.3 1904.58  5307.2 1906.10  5446.8 1908.78  5488.4 1911.03
  5496.3 1911.06  5517.2 1913.18  5539.4 1914.63  5566.7 1917.51  5585.5 1918.65
#Mann=3,-1,0
  4632.5     0.1       0  4997.2    0.07       0  5003.2     0.1       0
Bank Sta=4997.2,5003.2
Exp/Cntr=0.3,0.1

Type RM Length L Ch R = 1,2857,387,387,387
BEGIN DESCRIPTION:
UNT064 IN NNOGR 6.0
END DESCRIPTION:
XS GIS Cut Line= 2
      2792465.17     10099058.18      2792888.77     10098599.86
#Sta/Elev= 30
  4757.6 1896.30  4763.7 1896.30  4770.1 1895.20  4784.3 1895.59  4791.1 1894.70
  4798.5 1894.99  4805.3 1894.06  4815.7 1893.97  4826.8 1893.79  4833.7 1892.92
  4841.0 1893.20  4847.8 1892.27  4855.2 1892.94  4862.0 1892.20  4904.5 1890.91
  4955.3 1890.87  4961.2 1891.17  5000.8 1887.23  5003.5 1886.73  5006.8 1887.23
  5024.7 1890.96  5046.3 1893.10  5053.1 1894.83  5060.5 1895.08  5067.3 1896.42
  5103.0 1898.44  5144.9 1901.87  5237.4 1906.19  5364.4 1909.33  5381.7 1909.23
#Mann=5,-1,0
  4757.6     0.1       0  4815.7    0.05       0  4955.3     0.1       0
  5000.8    0.07       0  5006.8     0.1       0
Bank Sta=5000.8,5006.8
Exp/Cntr=0.3,0.1

Type RM Length L Ch R = 1,2470,42,42,42
BEGIN DESCRIPTION:
Mapping XS 6b571e23
END DESCRIPTION:
XS GIS Cut Line= 2
      2792569.35     10099419.28      2793131.86     10098905.39
#Sta/Elev= 30
  4691.3 1898.34  4730.3 1896.97  4737.0 1897.05  4751.2 1896.03  4779.6 1895.03
  4800.6 1894.92  4857.3 1892.33  4871.5 1891.52  4885.7 1889.73  4893.1 1887.80
  4899.9 1886.90  4906.8 1885.19  4914.0 1884.42  4942.4 1883.36  4974.6 1883.18
  4977.3 1882.68  4980.6 1883.18  5048.5 1883.36  5055.8 1884.05  5069.4 1887.03
  5083.6 1888.99  5097.8 1890.42  5105.2 1890.60  5112.0 1891.30  5140.4 1895.16
  5168.7 1897.16  5225.5 1899.27  5359.9 1905.87  5395.1 1907.09  5453.2 1908.06
#Mann=3,-1,0
  4691.3     0.1       0  4974.6    0.07       0  4980.6     0.1       0
Bank Sta=4974.6,4980.6
Exp/Cntr=0.3,0.1

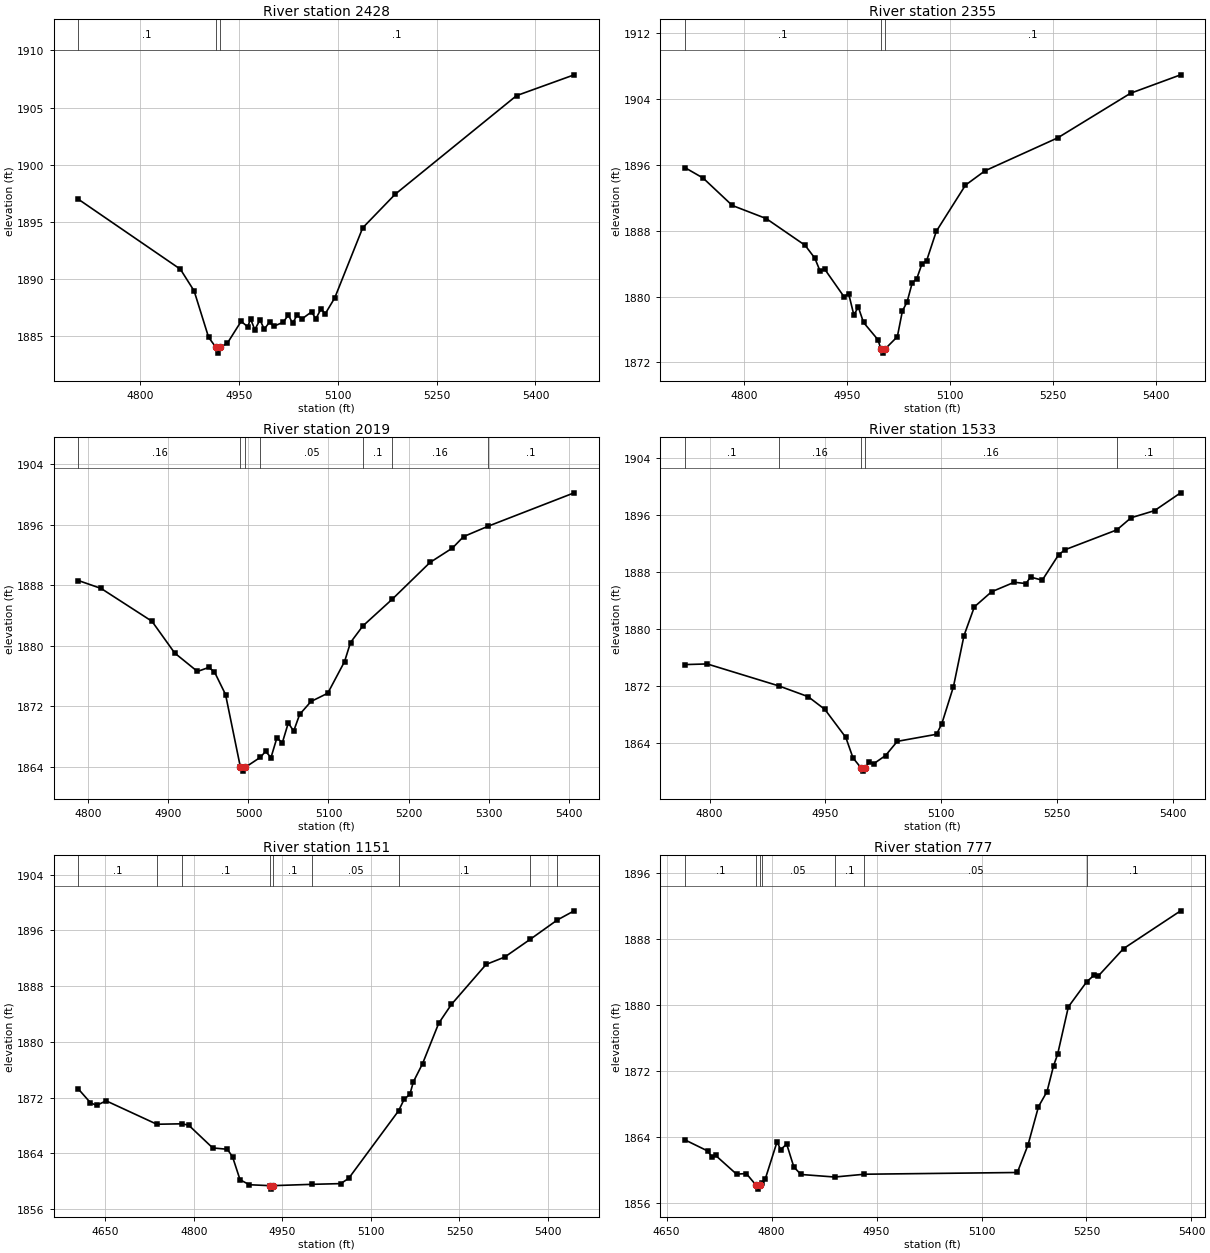
Type RM Length L Ch R = 1,2428,73,73,73
BEGIN DESCRIPTION:
UNT064 IN NNOGR 5.0
END DESCRIPTION:
XS GIS Cut Line= 4
      2792604.46     10099438.35      2792800.60     10099271.72
      2792901.30     10099146.72      2793155.03     10098927.50
#Sta/Elev= 30
  4705.6 1896.98  4860.6 1890.86  4881.5 1888.96  4903.5 1884.90  4914.7 1884.02
  4917.5 1883.52  4920.7 1884.02  4932.0 1884.39  4952.9 1886.30  4963.0 1885.82
  4967.2 1886.53  4973.6 1885.57  4981.6 1886.43  4988.0 1885.61  4996.0 1886.23
  5002.4 1885.87  5016.8 1886.22  5024.6 1886.85  5031.2 1886.13  5037.6 1886.82
  5045.5 1886.52  5059.9 1887.13  5066.4 1886.52  5074.3 1887.39  5080.7 1886.96
  5095.1 1888.35  5137.6 1894.48  5187.0 1897.42  5371.3 1906.04  5458.8 1907.86
#Mann=3,-1,0
  4705.6     0.1       0  4914.7    0.07       0  4920.7     0.1       0
Bank Sta=4914.7,4920.7
Exp/Cntr=0.3,0.1

Type RM Length L Ch R = 1,2355,336,336,336
BEGIN DESCRIPTION:
Mapping XS b978b7a0
END DESCRIPTION:
XS GIS Cut Line= 2
      2792652.66     10099495.69      2793187.41     10099009.55
#Sta/Elev= 30
  4713.6 1895.69  4740.3 1894.41  4782.8 1891.08  4832.2 1889.49  4888.9 1886.24
  4903.1 1884.68  4910.6 1883.14  4917.3 1883.36  4945.7 1879.98  4952.4 1880.37
  4959.9 1877.80  4966.6 1878.70  4974.1 1876.86  4995.0 1874.77  4999.5 1873.63
  5002.2 1873.13  5005.5 1873.63  5023.4 1875.13  5030.8 1878.26  5037.6 1879.35
  5045.0 1881.65  5051.8 1882.20  5059.2 1883.97  5066.0 1884.35  5080.2 1887.94
  5122.7 1893.55  5151.1 1895.29  5257.2 1899.30  5363.3 1904.72  5436.3 1906.96
#Mann=3,-1,0
  4713.6     0.1       0  4999.5    0.07       0  5005.5     0.1       0
Bank Sta=4999.5,5005.5
Exp/Cntr=0.3,0.1

Type RM Length L Ch R = 1,2019,486,486,486
BEGIN DESCRIPTION:
UNT064 IN NNOGR 4.0
END DESCRIPTION:
XS GIS Cut Line= 2
      2792854.08     10099759.55      2793270.73     10099301.23
#Sta/Elev= 30
  4787.5 1888.62  4816.0 1887.57  4879.5 1883.24  4907.9 1879.05  4936.3 1876.62
  4950.4 1877.15  4957.5 1876.57  4971.4 1873.58  4990.0 1863.97  4992.8 1863.47
  4996.0 1863.97  5015.0 1865.30  5021.4 1866.08  5028.2 1865.26  5035.6 1867.88
  5042.3 1867.20  5049.8 1869.83  5056.5 1868.75  5064.0 1870.96  5078.2 1872.66
  5099.1 1873.75  5120.1 1877.93  5127.5 1880.44  5142.9 1882.62  5179.9 1886.18
  5226.8 1891.00  5254.9 1892.91  5268.7 1894.41  5299.3 1895.78  5406.9 1900.19
#Mann=7,-1,0
  4787.5    0.16       0  4990.0    0.07       0  4996.0    0.16       0
  5015.0    0.05       0  5142.9     0.1       0  5179.9    0.16       0
  5299.3     0.1       0
Bank Sta=4990,4996
Exp/Cntr=0.3,0.1

Type RM Length L Ch R = 1,1533,382,382,382
BEGIN DESCRIPTION:
UNT064 IN NNOGR 3.0
END DESCRIPTION:
XS GIS Cut Line= 2
      2793104.04     10099988.74      2793644.61     10099642.22
#Sta/Elev= 30
  4767.9 1875.00  4796.9 1875.09  4889.6 1872.01  4927.6 1870.50  4949.3 1868.71
  4976.4 1864.78  4985.7 1861.91  4995.8 1860.55  4998.6 1860.05  5001.8 1860.55
  5006.8 1861.31  5012.7 1861.10  5027.9 1862.24  5043.1 1864.23  5093.9 1865.22
  5100.6 1866.66  5115.8 1871.90  5129.5 1879.08  5142.9 1883.10  5165.1 1885.21
  5194.5 1886.55  5209.7 1886.37  5215.6 1887.28  5230.8 1886.84  5252.0 1890.41
  5260.2 1891.11  5327.4 1893.90  5345.8 1895.60  5376.2 1896.60  5410.0 1899.10
#Mann=5,-1,0
  4767.9     0.1       0  4889.6    0.16       0  4995.8    0.07       0
  5001.8    0.16       0  5327.4     0.1       0
Bank Sta=4995.8,5001.8
Exp/Cntr=0.3,0.1

Type RM Length L Ch R = 1,1151,374,374,374
BEGIN DESCRIPTION:
UNT064 IN NNOGR 2.0
END DESCRIPTION:
XS GIS Cut Line= 3
      2793168.68     10100165.82      2793403.03     10100231.79
      2793918.67     10099931.43
#Sta/Elev= 30
  4604.2 1873.25  4624.8 1871.27  4635.1 1870.89  4651.3 1871.55  4737.2 1868.19
  4779.2 1868.25  4791.0 1868.07  4831.9 1864.79  4856.7 1864.60  4865.5 1863.52
  4878.2 1860.23  4894.0 1859.51  4928.2 1859.38  4930.9 1858.88  4934.2 1859.38
  5000.7 1859.57  5048.7 1859.67  5062.3 1860.42  5146.9 1870.12  5156.2 1871.75
  5166.1 1872.50  5171.9 1874.27  5187.6 1876.90  5214.9 1882.68  5236.4 1885.38
  5295.2 1891.12  5326.6 1892.17  5369.9 1894.72  5415.9 1897.50  5444.4 1898.81
#Mann=9,-1,0
  4604.2     0.1       0  4737.2    0.05       0  4779.2     0.1       0
  4928.2    0.07       0  4934.2     0.1       0  5000.7    0.05       0
  5146.9     0.1       0  5369.9    0.16       0  5415.9     0.1       0
Bank Sta=4928.2,4934.2
Exp/Cntr=0.3,0.1

Type RM Length L Ch R = 1,777,135,135,135
BEGIN DESCRIPTION:
Mapping XS 14d83f71
END DESCRIPTION:
XS GIS Cut Line= 3
      2793436.26     10100500.23      2793621.78     10100540.81
      2794060.13     10100263.71
#Sta/Elev= 30
  4676.0 1863.63  4709.0 1862.26  4714.9 1861.51  4720.1 1861.73  4749.9 1859.46
  4763.9 1859.53  4777.6 1858.14  4780.4 1857.64  4783.6 1858.14  4786.1 1858.38
  4790.9 1858.85  4807.8 1863.38  4812.9 1862.44  4821.6 1863.11  4831.8 1860.33
  4842.0 1859.42  4890.2 1859.11  4932.7 1859.45  5151.2 1859.66  5166.5 1863.03
  5181.4 1867.66  5193.6 1869.49  5202.9 1872.61  5208.8 1874.04  5224.1 1879.78
  5250.3 1882.82  5260.6 1883.61  5266.5 1883.49  5302.9 1886.85  5384.5 1891.44
#Mann=7,-1,0
  4676.0     0.1       0  4777.6   0.033       0  4783.6     0.1       0
  4786.1    0.05       0  4890.2     0.1       0  4932.7    0.05       0
  5250.3     0.1       0
Bank Sta=4777.6,4783.6
Exp/Cntr=0.3,0.1

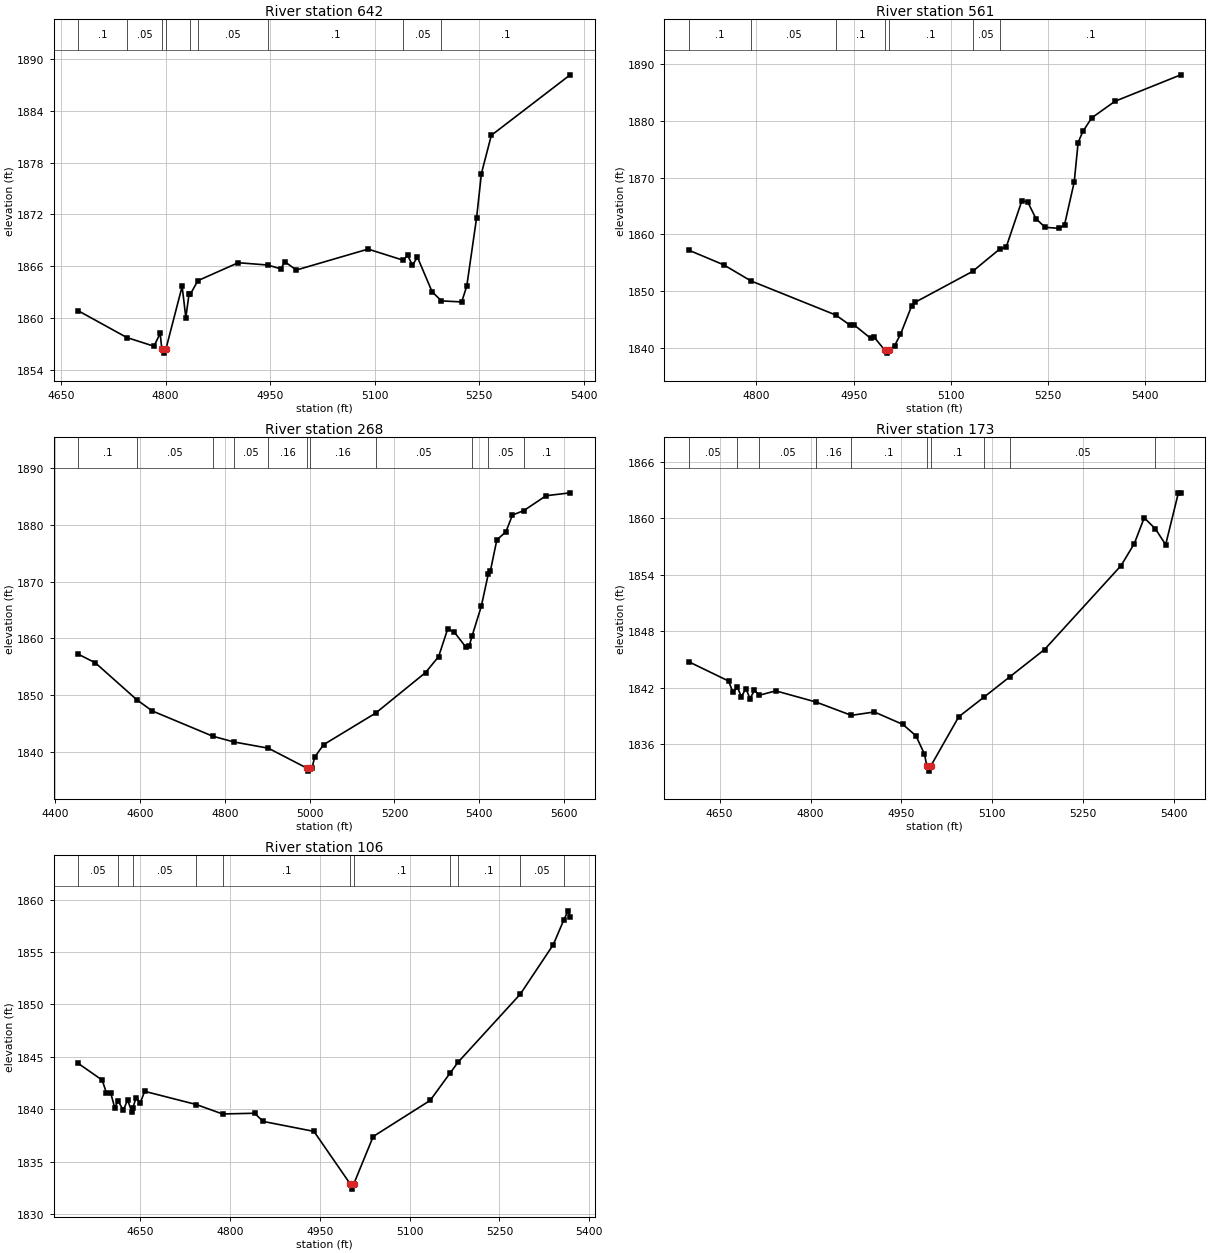
Type RM Length L Ch R = 1,642,81,81,81
BEGIN DESCRIPTION:
Mapping XS 6d21496c
END DESCRIPTION:
XS GIS Cut Line= 6
      2793475.35     10100550.15      2793628.73     10100601.58
      2793696.44     10100617.20      2793746.78     10100613.73
      2793859.63     10100554.70      2794073.86     10100349.11
#Sta/Elev= 30
  4674.4 1860.83  4744.3 1857.72  4783.2 1856.71  4792.1 1858.21  4794.4 1856.41
  4797.1 1855.91  4800.4 1856.41  4823.6 1863.66  4828.9 1860.03  4833.4 1862.72
  4835.2 1862.72  4846.2 1864.32  4904.1 1866.40  4946.6 1866.13  4965.3 1865.68
  4970.9 1866.52  4987.4 1865.55  5090.4 1867.98  5141.2 1866.68  5147.0 1867.28
  5154.0 1866.11  5161.2 1867.04  5182.3 1863.02  5195.7 1861.97  5224.7 1861.85
  5232.0 1863.70  5246.1 1871.63  5253.0 1876.75  5267.2 1881.18  5380.4 1888.20
#Mann=9,-1,0
  4674.4     0.1       0  4744.3    0.05       0  4794.4    0.07       0
  4800.4    0.05       0  4835.2     0.1       0  4846.2    0.05       0
  4946.6     0.1       0  5141.2    0.05       0  5195.7     0.1       0
Bank Sta=4794.4,4800.4
Exp/Cntr=0.3,0.1

Type RM Length L Ch R = 1,561,293,293,293
BEGIN DESCRIPTION:
Mapping XS e3041d4f
END DESCRIPTION:
XS GIS Cut Line= 4
      2793531.73     10100636.94      2793670.63     10100717.24
      2793981.16     10100613.73      2794132.39     10100388.10
#Sta/Elev= 30
  4695.5 1857.19  4749.5 1854.60  4791.4 1851.77  4922.4 1845.75  4944.7 1843.94
  4950.0 1844.07  4976.3 1841.64  4981.6 1841.85  4998.2 1839.53  5001.0 1839.03
  5004.2 1839.53  5013.2 1840.34  5022.3 1842.35  5039.5 1847.35  5044.8 1847.99
  5133.5 1853.44  5175.5 1857.39  5185.3 1857.69  5209.4 1865.83  5218.4 1865.74
  5231.4 1862.74  5245.4 1861.22  5267.5 1861.03  5275.4 1861.64  5290.4 1869.20
  5296.4 1876.16  5303.7 1878.12  5317.4 1880.52  5353.4 1883.45  5454.9 1888.11
#Mann=7,-1,0
  4695.5     0.1       0  4791.4    0.05       0  4922.4     0.1       0
  4998.2    0.07       0  5004.2     0.1       0  5133.5    0.05       0
  5175.5     0.1       0
Bank Sta=4998.2,5004.2
Exp/Cntr=0.3,0.1

Type RM Length L Ch R = 1,268,95,95,95
BEGIN DESCRIPTION:
UNT064 IN NNOGR 1.0
END DESCRIPTION:
XS GIS Cut Line= 4
      2793496.75     10100648.42      2793837.06     10100973.11
      2794008.94     10100865.47      2794263.79     10100451.11
#Sta/Elev= 30
  4454.6 1857.21  4495.0 1855.69  4593.6 1849.13  4629.3 1847.21  4771.8 1842.76
  4822.0 1841.74  4902.8 1840.65  4994.4 1837.11  4997.2 1836.61  5000.4 1837.11
  5005.9 1837.17  5011.8 1839.05  5033.0 1841.27  5155.5 1846.82  5273.3 1853.97
  5304.1 1856.78  5325.4 1861.64  5340.8 1861.11  5367.9 1858.48  5376.3 1858.69
  5383.2 1860.48  5404.6 1865.63  5420.9 1871.24  5425.9 1871.81  5441.3 1877.34
  5462.6 1878.75  5478.0 1881.70  5505.1 1882.50  5557.3 1885.11  5614.2 1885.62
#Mann=11,-1,0
  4454.6     0.1       0  4593.6    0.05       0  4771.8     0.1       0
  4822.0    0.05       0  4902.8    0.16       0  4994.4    0.07       0
  5000.4    0.16       0  5155.5    0.05       0  5383.2     0.1       0
  5420.9    0.05       0  5505.1     0.1       0
Bank Sta=4994.4,5000.4
Exp/Cntr=0.3,0.1

Type RM Length L Ch R = 1,173,67,67,67
BEGIN DESCRIPTION:
Mapping XS a5c0ce6f
END DESCRIPTION:
XS GIS Cut Line= 4
      2793666.87     10100822.28      2793914.78     10101052.13
      2794076.59     10100884.77      2794189.76     10100671.61
#Sta/Elev= 30
  4599.0 1844.78  4664.9 1842.73  4671.7 1841.55  4679.4 1842.07  4685.9 1841.06
  4693.3 1841.93  4700.1 1840.87  4707.4 1841.73  4715.7 1841.23  4742.6 1841.69
  4808.8 1840.51  4867.4 1839.09  4905.3 1839.45  4952.6 1838.12  4974.0 1836.92
  4988.1 1834.98  4992.1 1833.67  4994.8 1833.17  4998.1 1833.67  5044.7 1838.94
  5087.0 1841.06  5128.7 1843.17  5186.3 1846.08  5312.5 1854.98  5334.5 1857.33
  5350.8 1860.06  5369.2 1858.89  5386.2 1857.21  5407.2 1862.71  5411.2 1862.71
#Mann=10,-1,0
  4599.0    0.05       0  4679.4     0.1       0  4715.7    0.05       0
  4808.8    0.16       0  4867.4     0.1       0  4992.1    0.07       0
  4998.1     0.1       0  5087.0     0.1       0  5128.7    0.05       0
  5369.2     0.1       0
Bank Sta=4992.1,4998.1
Exp/Cntr=0.3,0.1

Type RM Length L Ch R = 1,106,0,0,0
BEGIN DESCRIPTION:
UNT064 IN NNOGR 1.1
END DESCRIPTION:
XS GIS Cut Line= 4
      2793677.29     10100838.25      2793951.59     10101098.66
      2794108.53     10100963.94      2794194.04     10100743.28
#Sta/Elev= 30
  4546.4 1844.37  4586.6 1842.77  4593.5 1841.56  4600.7 1841.55  4607.6 1840.12
  4612.9 1840.80  4621.8 1839.90  4629.0 1840.87  4635.9 1839.77  4637.9 1840.14
  4643.2 1841.11  4650.1 1840.58  4657.4 1841.70  4743.7 1840.44  4787.5 1839.54
  4841.0 1839.61  4855.2 1838.83  4940.1 1837.88  5000.7 1832.87  5003.5 1832.37
  5006.7 1832.87  5039.1 1837.39  5134.2 1840.83  5167.6 1843.45  5181.0 1844.49
  5284.7 1850.97  5339.8 1855.69  5357.3 1858.04  5364.4 1858.92  5368.1 1858.29
#Mann=11,-1,0
  4546.4    0.05       0  4612.9     0.1       0  4637.9    0.05       0
  4743.7    0.16       0  4787.5     0.1       0  5000.7    0.07       0
  5006.7     0.1       0  5167.6    0.16       0  5181.0     0.1       0
  5284.7    0.05       0  5357.3     0.1       0
Bank Sta=5000.7,5006.7
Exp/Cntr=0.3,0.1

Chan Stop Cuts=-1