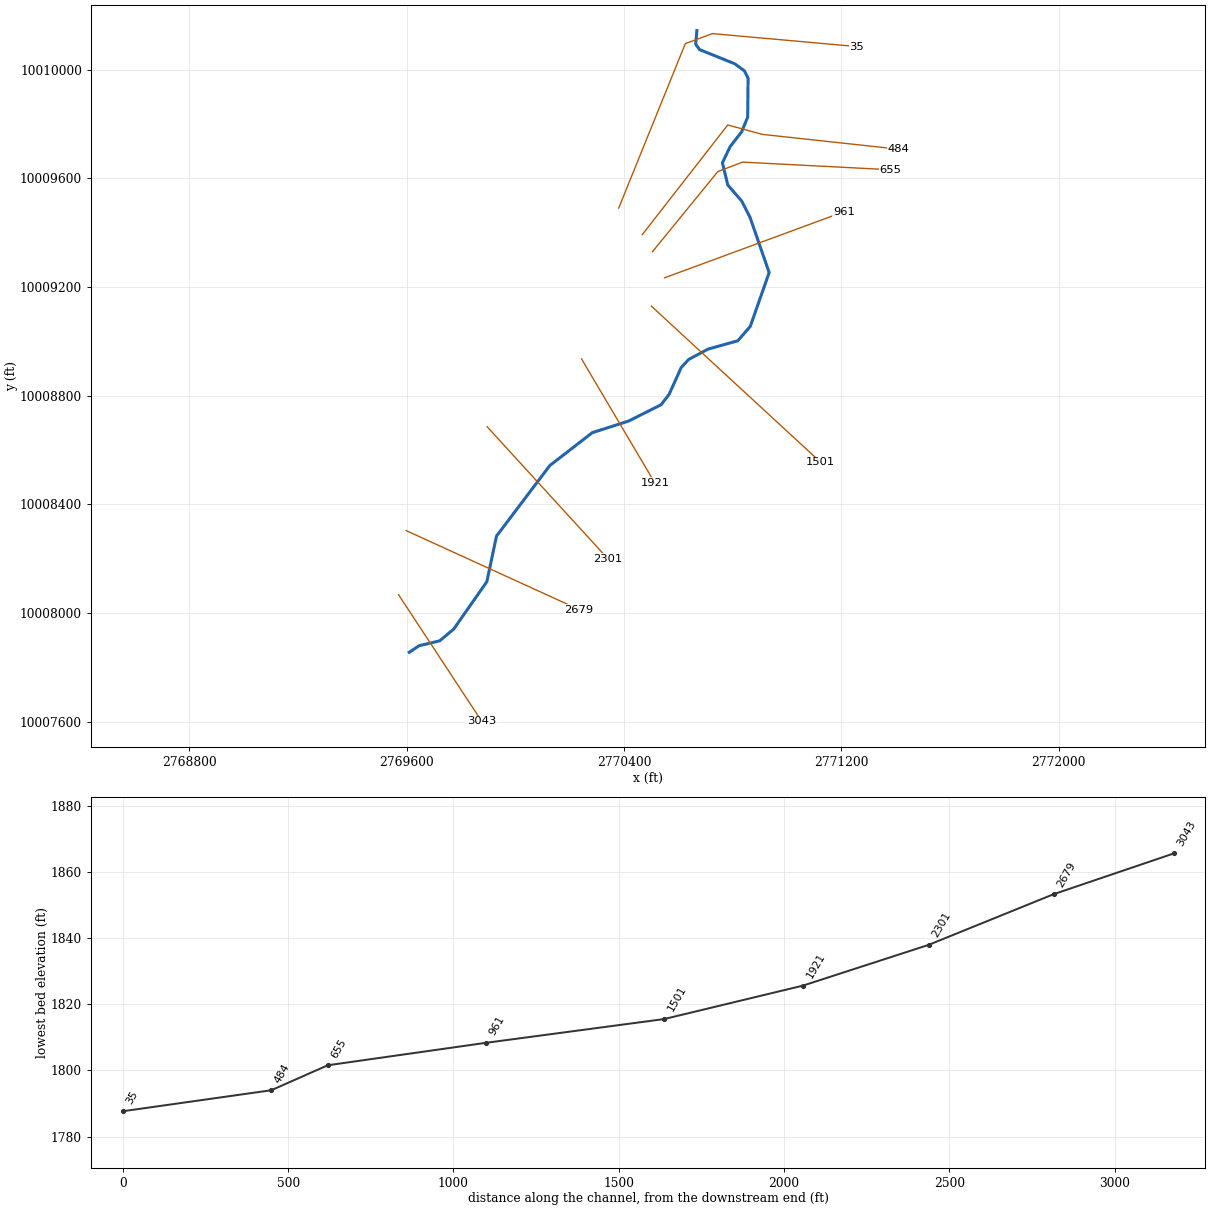
--- UNT064 IN SNOGR.prj (project) ---

Proj Title=UNT064 IN SNOGR Base Level Engineering
Current Plan=p01
Default Exp/Contr=0.3,0.1
English Units
Geom File=g01
Flow File=f01
Plan File=p01
Y Axis Title=Elevation
X Axis Title(PF)=Main Channel Distance
X Axis Title(XS)=Station
BEGIN DESCRIPTION:
UNT064 IN SNOGR
END DESCRIPTION:
DSS Export Rating Curves= 0
DSS Export Rating Curve Sorted= 0
DSS Export Volume Flow Curves= 0
DXF OffsetX= 0
DXF OffsetY= 0
DXF ScaleX= 1
DXF ScaleY= 10

--- UNT064 IN SNOGR.p01 (plan) ---

Plan Title=Multiple Run
Short Identifier=Multiple
Geom File=g01
Flow File=f01
Subcritical Flow
K Sum by GR= 0
Std Step Tol= 0.01
Critical Tol= 0.01
Num of Std Step Trials= 20
Max Error Tol= 0.3
Flow Tol Ratio= 0.001
Split Flow NTrial= 30
Split Flow Tol= 0.02
Split Flow Ratio= 0.02
Log Output Level= 0
Friction Slope Method= 1
Unsteady Friction Slope Method= 2
Unsteady Bridges Friction Slope Method= 1
Parabolic Critical Depth
Global Vel Dist=  1 , 1 , 1
Global Log Level= 0
CheckData=True
Encroach Param= -1, 0, 0, 0
BEGIN DESCRIPTION:
Multiple Run
END DESCRIPTION:

--- UNT064 IN SNOGR.f01 (steady flow) ---

Flow Title=Multiple
Program Version=4.10
Number of Profiles= 7
Profile Names=10-year,25-year,50-year,1pct_min,100-year,1pct_plu,500-year
River Rch & RM=UNT064 IN SNOGR,Reach-1         ,3043
     354     488     600     542     733     991    1094
Boundary for River Rch & Prof#=UNT064 IN SNOGR,Reach-1         , 1
Up Type= 0
Dn Type= 3
Dn Slope=0.014
Boundary for River Rch & Prof#=UNT064 IN SNOGR,Reach-1         , 2
Up Type= 0
Dn Type= 3
Dn Slope=0.014
Boundary for River Rch & Prof#=UNT064 IN SNOGR,Reach-1         , 3
Up Type= 0
Dn Type= 3
Dn Slope=0.014
Boundary for River Rch & Prof#=UNT064 IN SNOGR,Reach-1         , 4
Up Type= 0
Dn Type= 3
Dn Slope=0.014
Boundary for River Rch & Prof#=UNT064 IN SNOGR,Reach-1         , 5
Up Type= 0
Dn Type= 3
Dn Slope=0.014
Boundary for River Rch & Prof#=UNT064 IN SNOGR,Reach-1         , 6
Up Type= 0
Dn Type= 3
Dn Slope=0.014
Boundary for River Rch & Prof#=UNT064 IN SNOGR,Reach-1         , 7
Up Type= 0
Dn Type= 3
Dn Slope=0.014
DSS Import GetInterval= 0
DSS Import GetPeak= 0
DSS Import FillOption= 0

--- UNT064 IN SNOGR.g01 (geometry) ---

Geom Title=Existing Conditions
Program Version=4.10

River Reach=UNT064 IN SNOGR ,Reach-1
Reach XY= 30
      2769609.55     10007854.98      2769645.68     10007879.09
      2769721.78     10007897.28      2769773.65     10007940.82
      2769895.32     10008115.03      2769930.78     10008282.77
      2770127.16     10008542.62      2770283.53     10008663.57
      2770417.34     10008706.45      2770536.91     10008766.45
      2770566.24     10008804.57      2770610.57     10008902.95
      2770638.42     10008933.28      2770709.55     10008971.11
      2770819.17     10009001.86      2770865.18     10009054.95
      2770934.58       10009253.      2770864.03     10009456.62
      2770833.43     10009516.44      2770782.27     10009575.46
      2770762.48     10009657.23      2770790.74     10009716.31
      2770833.23     10009771.13      2770855.49     10009825.04
      2770856.99     10009968.16      2770843.48     10009995.59
      2770807.82     10010021.56      2770678.39     10010073.92
      2770664.16     10010093.47      2770668.47     10010143.73

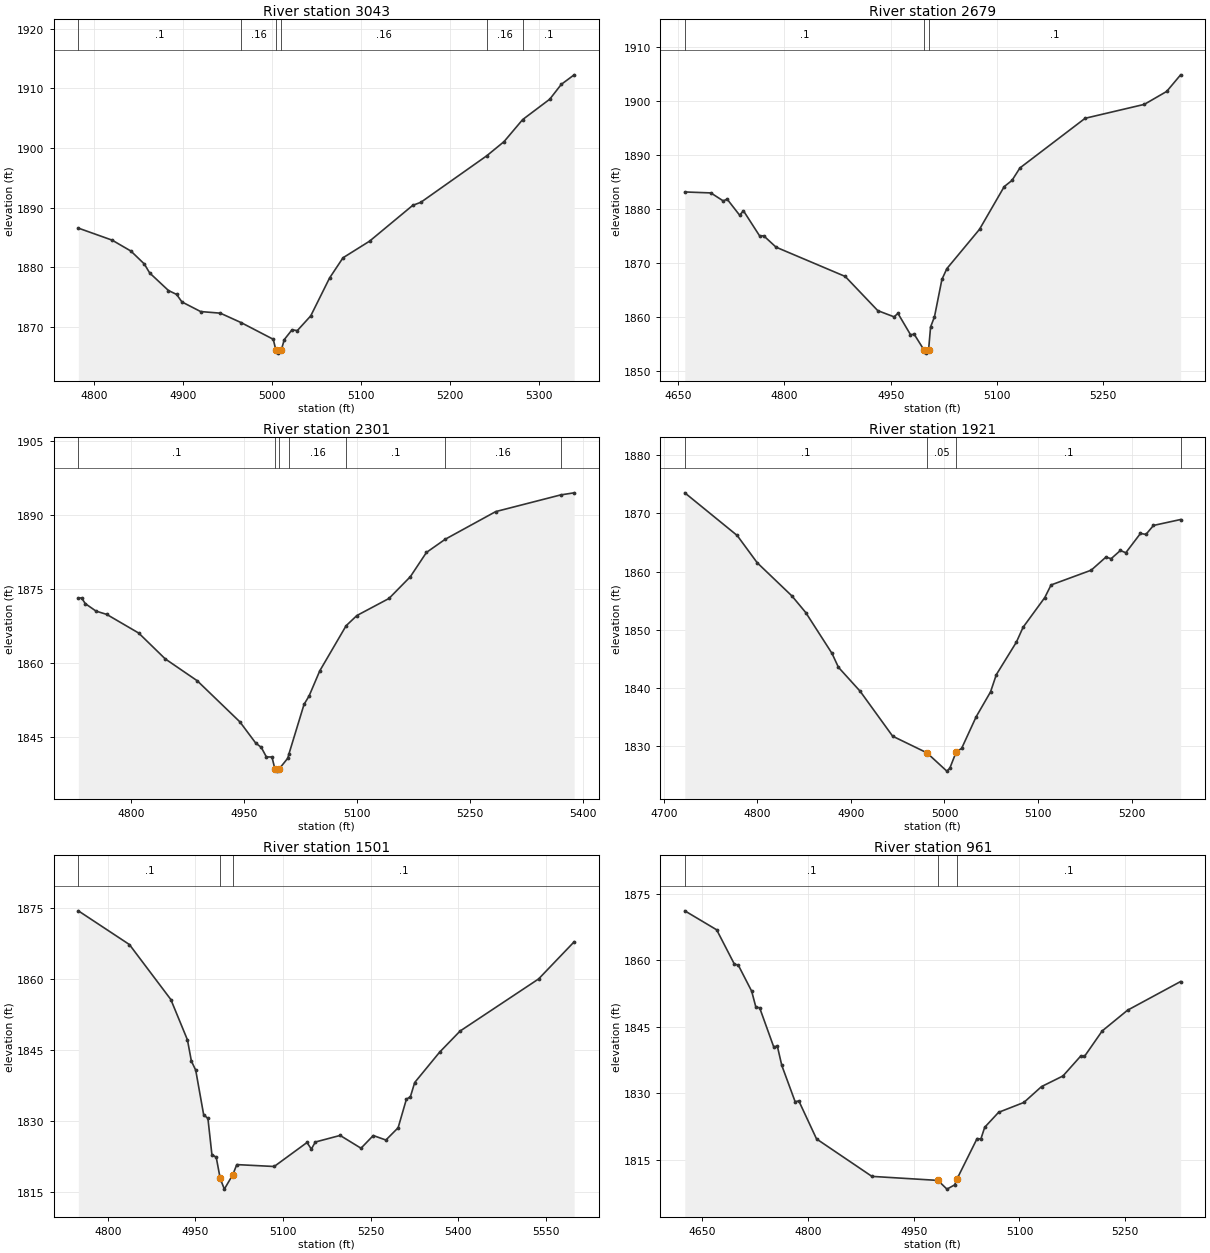
Type RM Length L Ch R = 1 ,3043    ,364,364,364
BEGIN DESCRIPTION:
UNT064 IN SNOGR 7.0
END DESCRIPTION:
XS GIS Cut Line= 2
      2769570.32     10008066.95      2769875.85      10007601.7
#Sta/Elev= 30
  4782.4 1886.59  4820.4 1884.57  4841.4 1882.75  4856.5 1880.58  4862.5 1879.08
  4883.6 1876.14  4892.7 1875.49  4898.7 1874.23  4919.7 1872.62  4941.8 1872.35
  4965.3 1870.76  5001.2 1867.98  5004.2 1866.16  5006.9 1865.66  5010.2 1866.16
  5013.6 1867.93  5022.3 1869.57  5028.2 1869.43  5043.3  1871.9  5064.4 1878.23
  5079.5 1881.62  5109.3  1884.4  5157.8  1890.4  5166.9 1890.91  5240.9  1898.7
  5260.3 1901.07  5281.2 1904.76  5311.6 1908.17  5324.6 1910.66    5339 1912.25
#Mann= 6 ,-1 , 0
  4782.4      .1       0  4965.3     .16       0  5004.2     .07       0
  5010.2     .16       0  5240.9     .16       0  5281.2      .1       0
Bank Sta=5004.2,5010.2
XS Rating Curve= 0 ,0
Exp/Cntr=0.3,0.1

Type RM Length L Ch R = 1 ,2679    ,378,378,378
BEGIN DESCRIPTION:
UNT064 IN SNOGR 6.0
END DESCRIPTION:
XS GIS Cut Line= 2
      2769598.03     10008303.12      2770235.18     10008012.25
#Sta/Elev= 30
  4659.2  1883.2    4696 1883.02  4713.5 1881.54    4719 1881.87  4736.6  1878.9
  4742.1  1879.7  4765.1 1875.01  4770.6 1875.08  4788.1 1872.96  4885.8 1867.53
  4931.8 1861.19  4954.8 1860.04  4960.3 1860.68  4977.9 1856.76  4983.4 1856.78
  4997.5 1853.81  5000.2 1853.31  5003.5 1853.81  5006.4 1858.16  5011.9 1860.05
  5022.4 1866.98  5029.4 1868.98  5075.5 1876.27  5110.4 1884.19  5121.4 1885.34
  5132.6 1887.65  5224.7 1896.86  5308.3 1899.44  5339.9 1901.84  5359.6 1904.92
#Mann= 3 ,-1 , 0
  4659.2      .1       0  4997.5     .07       0  5003.5      .1       0
Bank Sta=4997.5,5003.5
XS Rating Curve= 0 ,0
Exp/Cntr=0.3,0.1

Type RM Length L Ch R = 1 ,2301    ,380,380,380
BEGIN DESCRIPTION:
UNT064 IN SNOGR 5.0
END DESCRIPTION:
XS GIS Cut Line= 2
      2769896.69     10008685.03       2770341.1     10008198.96
#Sta/Elev= 30
  4729.9 1873.14  4734.2 1873.14  4739.2 1871.98  4753.4 1870.47  4767.6  1869.8
  4810.1 1866.01  4845.3 1860.77  4887.8 1856.33  4944.5 1847.98  4965.5 1843.68
  4972.9  1842.8  4979.7 1840.86  4987.1 1840.85  4990.9 1838.48  4993.6 1837.98
  4996.9 1838.48  5008.1  1840.6  5009.8 1841.55  5029.7 1851.53  5036.4 1853.24
  5050.6 1858.34  5085.6  1867.5  5099.9 1869.57  5142.5 1873.03  5170.9 1877.45
  5192.3 1882.38  5217.3 1885.06  5284.3 1890.67  5370.7 1894.06  5388.5 1894.48
#Mann= 7 ,-1 , 0
  4729.9      .1       0  4990.9     .07       0  4996.9      .1       0
  5009.8     .16       0  5085.6      .1       0  5217.3     .16       0
  5370.7      .1       0
Bank Sta=4990.9,4996.9
XS Rating Curve= 0 ,0
Exp/Cntr=0.3,0.1

Type RM Length L Ch R = 1 ,1921    ,420,420,420
BEGIN DESCRIPTION:
UNT064 IN SNOGR 4.0
END DESCRIPTION:
XS GIS Cut Line= 2
      2770243.89     10008935.06      2770513.52     10008478.77
#Sta/Elev= 30
  4722.4 1873.54  4778.4  1866.2  4799.8 1861.51  4836.9  1855.8  4851.7 1852.94
  4879.8  1845.9  4886.6 1843.53  4909.8 1839.41  4944.6 1831.67  4981.2 1828.81
  5002.5 1825.66  5005.7 1826.16  5012.5 1828.97  5018.3 1829.57  5033.9 1835.03
  5049.2 1839.29  5055.4 1842.26  5076.8 1847.84    5084 1850.41  5107.2 1855.52
  5113.9 1857.69  5156.8 1860.23  5172.4 1862.46  5178.2 1862.22    5188 1863.62
  5193.8 1863.23  5209.5 1866.56  5215.3 1866.38  5223.4 1867.93  5252.4 1868.95
#Mann= 4 ,-1 , 0
  4722.4      .1       0  4981.2     .05       0  5012.5      .1       0
  5252.4      .1       0
Bank Sta=4981.2,5012.5
XS Rating Curve= 0 ,0
Exp/Cntr=0.3,0.1

Type RM Length L Ch R = 1 ,1501    ,540,540,540
BEGIN DESCRIPTION:
UNT064 IN SNOGR 3.0
END DESCRIPTION:
XS GIS Cut Line= 2
      2770500.82     10009129.51      2771124.64     10008554.21
#Sta/Elev= 30
  4749.7 1874.32  4837.1  1867.2    4908 1855.59  4936.4 1847.08  4943.2 1842.58
  4950.6 1840.66  4964.2 1831.25  4971.5 1830.47  4978.3 1822.84  4985.7 1822.27
  4992.5 1817.79  4999.6 1815.54  5014.1  1818.6  5020.9 1820.72  5084.9 1820.32
  5141.1 1825.39  5148.5 1823.99  5155.3 1825.49  5197.8 1826.88  5233.5 1824.18
  5254.5 1826.86  5276.1 1825.91    5297  1828.5  5311.2 1834.54    5318 1835.04
  5325.4 1838.06  5367.9 1844.45  5403.1 1848.93  5537.5 1859.94  5598.3 1867.78
#Mann= 3 , 0 , 0
  4749.7      .1       0  4992.5     .05       0  5014.1      .1       0
Bank Sta=4992.5,5014.1
XS Rating Curve= 0 ,0
Exp/Cntr=0.3,0.1

Type RM Length L Ch R = 1 ,961     ,477,477,477
BEGIN DESCRIPTION:
UNT064 IN SNOGR 2.0
END DESCRIPTION:
XS GIS Cut Line= 2
      2770549.48     10009233.66      2771209.13     10009476.69
#Sta/Elev= 30
  4625.5 1871.22  4670.7 1866.93  4695.9 1859.14  4701.2 1858.99  4720.3 1853.07
  4726.3 1849.44  4731.6 1849.32  4751.4 1840.55  4756.8 1840.58    4763  1836.3
  4781.9 1828.11  4787.2 1828.26  4812.3 1819.68  4890.8 1811.22  4984.4 1810.31
  4997.2 1808.34  5008.1  1809.3 5011.36 1810.61  5039.9 1819.76  5045.3 1819.67
  5050.7 1822.31  5070.4 1825.69  5106.2 1827.92  5131.3 1831.51  5161.7 1833.91
  5186.8  1838.4  5192.2 1838.33  5217.3 1844.08  5253.2 1848.76  5328.5 1855.25
#Mann= 3 , 0 , 0
  4625.5      .1       0  4984.4     .05       0 5011.36      .1       0
Bank Sta=4984.4,5011.36
XS Rating Curve= 0 ,0
Exp/Cntr=0.3,0.1

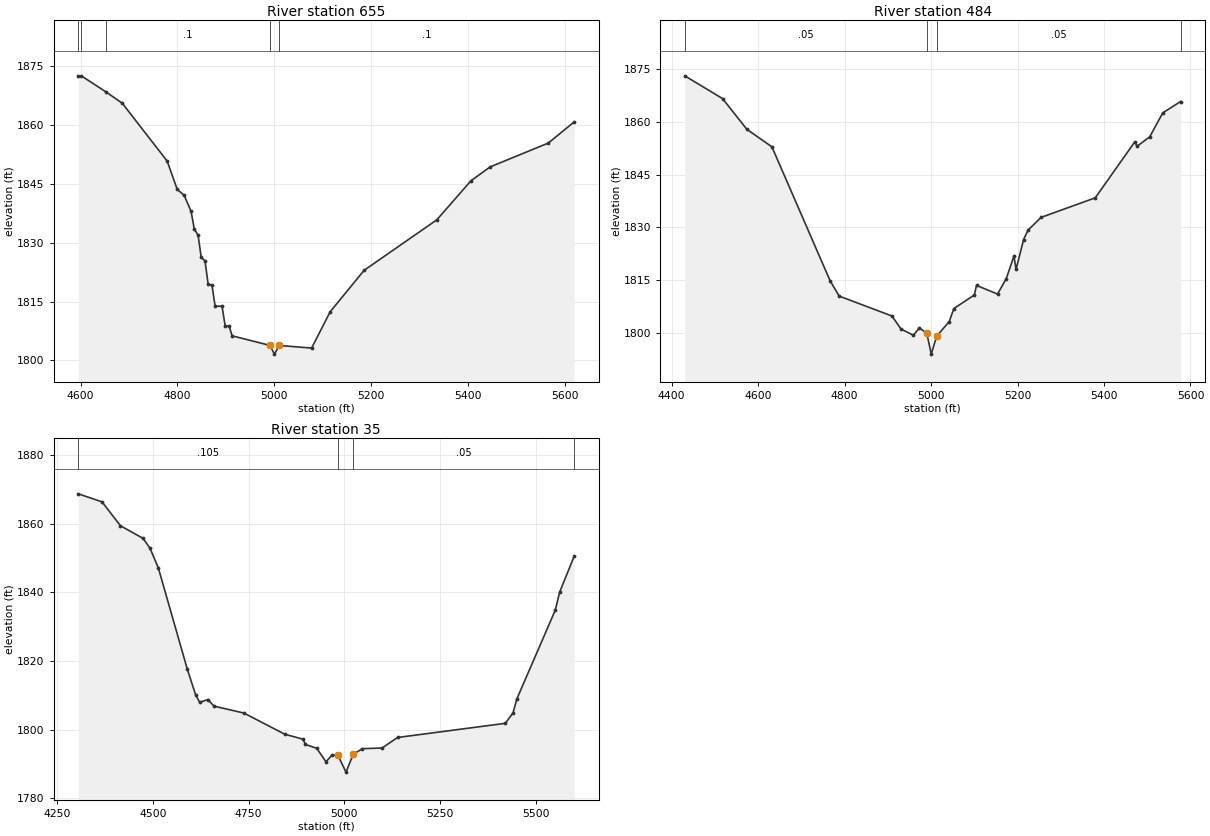
Type RM Length L Ch R = 1 ,655     ,171,171,171
BEGIN DESCRIPTION:
Mapping XS 7711aacc
END DESCRIPTION:
XS GIS Cut Line= 4
      2770504.98     10009329.79      2770745.84     10009624.91
      2770836.99     10009659.63      2771381.69     10009631.42
#Sta/Elev= 30
  4595.4 1872.61  4601.8 1872.59  4652.1 1868.54  4686.1 1865.62  4778.8 1850.86
  4799.6 1843.62  4813.9 1842.12  4828.3 1837.98  4834.8 1833.52  4842.7 1831.93
  4849.1 1826.31    4857 1825.36  4863.5 1819.39  4871.4 1819.18  4877.8 1813.84
  4892.2 1813.78  4898.7 1808.73  4906.6 1808.76    4913 1806.24  4991.1  1803.8
  5000.3 1801.57  5010.5 1803.79  5077.1 1803.11  5115.4 1812.37  5185.5 1822.96
  5335.7 1835.85  5405.8 1845.77  5445.8 1849.36    5566 1855.45  5619.3 1860.85
#Mann= 5 ,-1 , 0
  4595.4      .1       0  4601.8     .16       0  4652.1      .1       0
  4991.1     .05       0  5010.5      .1       0
Bank Sta=4991.1,5010.5
XS Rating Curve= 0 ,0
Exp/Cntr=0.3,0.1

Type RM Length L Ch R = 1 ,484     ,449,449,449
BEGIN DESCRIPTION:
Mapping XS 9d52b92a
END DESCRIPTION:
XS GIS Cut Line= 4
      2770467.52     10009392.69      2770782.19     10009796.35
      2770910.23     10009761.62      2771409.41     10009707.37
#Sta/Elev= 30
  4430.6 1873.01    4518 1866.54  4574.1 1857.83    4632 1852.86  4766.8 1814.79
  4787.6 1810.49  4909.7 1804.83  4930.5 1801.15  4959.3 1799.36  4973.2 1801.49
  4990.4 1799.87  5000.5 1794.01    5013  1799.1  5042.2 1803.27  5052.8 1806.95
  5100.2  1810.8  5105.2 1813.52  5153.8 1811.06  5173.9 1815.41  5191.7 1821.85
  5196.7 1818.09  5214.1 1826.54  5224.2 1829.18  5254.4 1832.82  5379.8 1838.38
  5471.3 1854.28  5476.4    1853  5505.8 1855.71    5536 1862.51  5577.2 1865.72
#Mann= 4 ,-1 , 0
  4430.6     .05       0  4990.4    .035       0    5013     .05       0
  5577.2      .1       0
Bank Sta=4990.4,5013
XS Rating Curve= 0 ,0
Exp/Cntr=0.3,0.1

Type RM Length L Ch R = 1 ,35      ,0,0,0
BEGIN DESCRIPTION:
UNT064 IN SNOGR 1.0
END DESCRIPTION:
XS GIS Cut Line= 4
      2770380.71     10009490.34      2770625.94     10010095.83
      2770725.77     10010132.72      2771257.44     10010084.98
#Sta/Elev= 30
    4306 1868.65  4367.8 1866.31    4416 1859.35    4475 1855.68  4493.1 1852.78
  4514.7 1847.09  4590.2 1817.66  4611.8 1810.21  4622.5 1807.99  4644.1 1808.77
    4660 1806.86  4737.7 1804.86  4844.9 1798.67  4892.3 1797.25  4898.5 1795.71
    4928 1794.59  4952.1 1790.65  4967.5 1792.61  4983.3 1792.54  5004.3 1787.66
    5023 1792.83  5047.2 1794.49  5098.5 1794.68  5138.7 1797.74  5419.8 1801.86
  5439.9 1804.87  5450.3 1809.04  5550.3 1834.81  5561.4 1839.95  5599.5 1850.49
#Mann= 4 ,-1 , 0
    4306    .105       0  4983.3    .035       0    5023     .05       0
  5599.5     .16       0
Bank Sta=4983.3,5023
XS Rating Curve= 0 ,0
Exp/Cntr=0.3,0.1

Chan Stop Cuts=-1
Use User Specified Reach Order=0
Composite Channel Slope=5