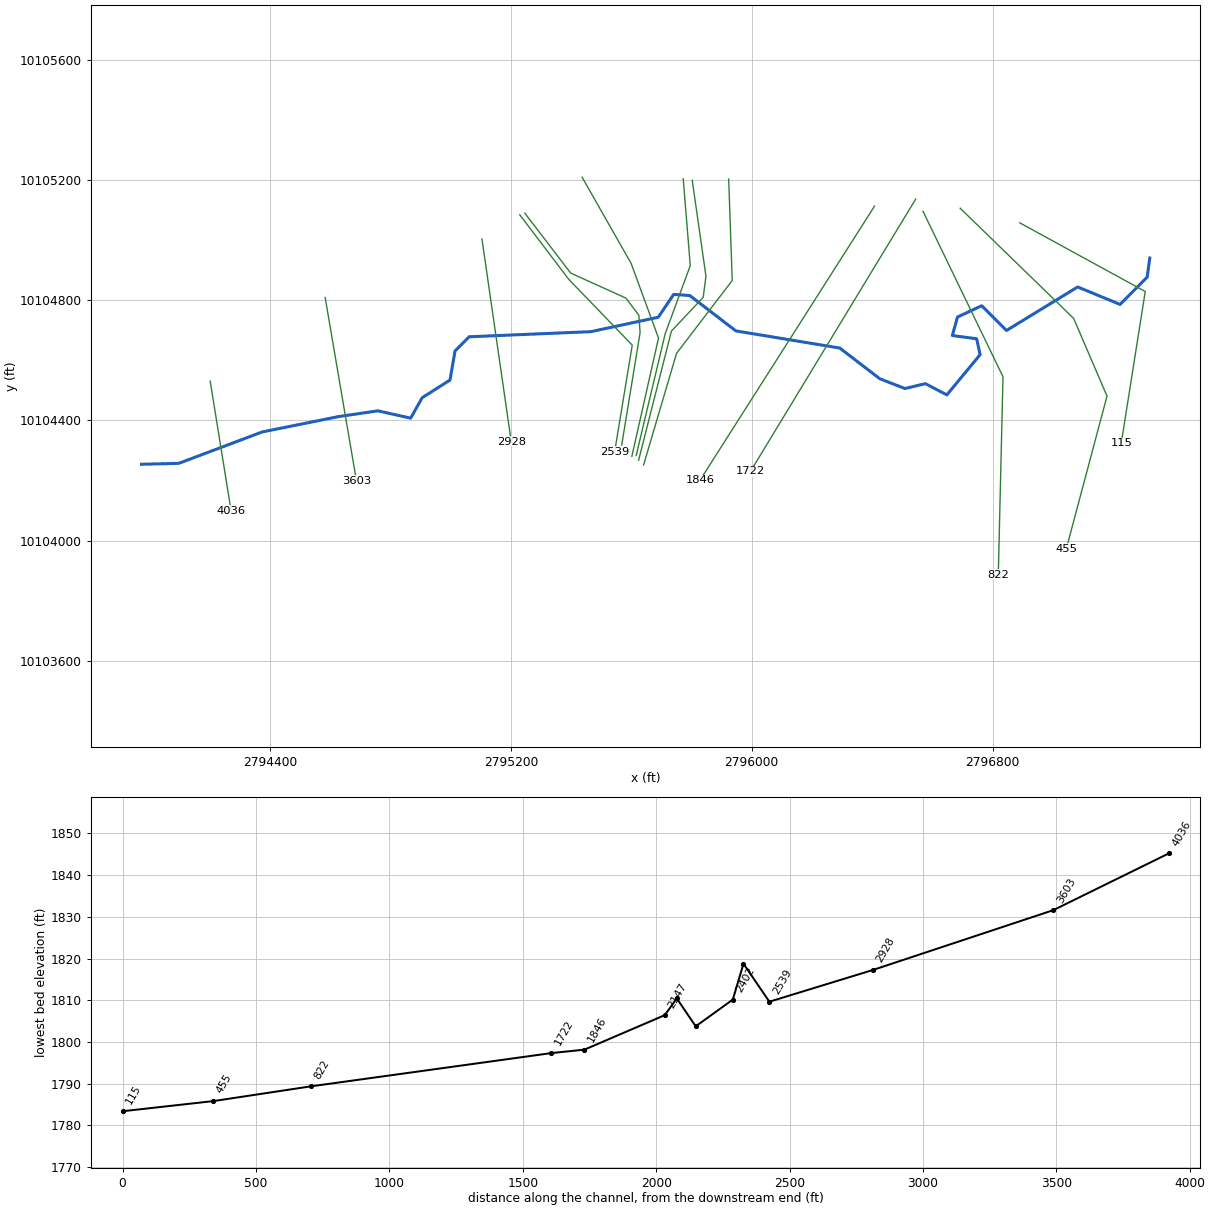
--- UNT065 IN NNOGR.prj (project) ---

Proj Title=UNT065 IN NNOGR Base Level Engineering
Current Plan=p01
Default Exp/Contr=0.3,0.1
English Units
Geom File=g01
Flow File=f01
Plan File=p01
BEGIN DESCRIPTION:
UNT065 IN NNOGR
END DESCRIPTION:

--- UNT065 IN NNOGR.p01 (plan) ---

Plan Title=Multiple Run
Short Identifier=Multiple
Geom File=g01
Flow File=f01
Subcritical Flow
K Sum by GR= 0
Std Step Tol= 0.01
Critical Tol= 0.01
Num of Std Step Trials= 20
Max Error Tol= 0.3
Flow Tol Ratio= 0.001
Split Flow NTrial= 30
Split Flow Tol= 0.02
Split Flow Ratio= 0.02
Log Output Level= 0
Friction Slope Method= 1
Unsteady Friction Slope Method= 2
Unsteady Bridges Friction Slope Method= 1
Parabolic Critical Depth
Global Vel Dist=  1 , 1 , 1
Global Log Level= 0
CheckData=True
Encroach Param= -1, 0, 0, 0
BEGIN DESCRIPTION:
Multiple Run
END DESCRIPTION:

--- UNT065 IN NNOGR.f01 (steady flow) ---

Flow Title=Multiple
Number of Profiles=7
Profile Names=10-year,25-year,50-year,1pct_min,100-year,1pct_plu,500-year
River Rch & RM= UNT065 IN NNOGR,Reach-1,4036
     395     544     667     601     813    1100    1210
Boundary for River Rch & Prof#=UNT065 IN NNOGR,Reach-1,1
Up Type=0
Dn Type=3
Dn Slope=0.005
Boundary for River Rch & Prof#=UNT065 IN NNOGR,Reach-1,2
Up Type=0
Dn Type=3
Dn Slope=0.005
Boundary for River Rch & Prof#=UNT065 IN NNOGR,Reach-1,3
Up Type=0
Dn Type=3
Dn Slope=0.005
Boundary for River Rch & Prof#=UNT065 IN NNOGR,Reach-1,4
Up Type=0
Dn Type=3
Dn Slope=0.005
Boundary for River Rch & Prof#=UNT065 IN NNOGR,Reach-1,5
Up Type=0
Dn Type=3
Dn Slope=0.005
Boundary for River Rch & Prof#=UNT065 IN NNOGR,Reach-1,6
Up Type=0
Dn Type=3
Dn Slope=0.005
Boundary for River Rch & Prof#=UNT065 IN NNOGR,Reach-1,7
Up Type=0
Dn Type=3
Dn Slope=0.005

--- UNT065 IN NNOGR.g01 (geometry) ---

Geom Title=Existing Conditions

River Reach=UNT065 IN NNOGR,Reach-1
Reach XY= 30
      2793973.47     10104253.73      2794097.13     10104256.79
      2794374.47     10104361.31      2794628.49     10104412.41
      2794758.51     10104431.41      2794867.19     10104407.11
      2794905.42     10104474.97      2794997.89     10104533.84
      2795014.56     10104630.76      2795061.31     10104677.73
      2795465.49     10104694.76      2795689.44     10104742.67
      2795740.83     10104818.72      2795794.31     10104814.90
      2795947.43     10104697.19      2796292.35     10104640.29
      2796425.56     10104538.03      2796508.94     10104505.61
      2796576.78     10104521.81      2796648.05     10104484.42
      2796758.51     10104618.17      2796747.11     10104671.10
      2796666.27     10104681.89      2796683.46     10104743.33
      2796763.79     10104780.95      2796846.29     10104698.74
      2797082.66     10104843.43      2797223.47     10104785.38
      2797313.40     10104876.01      2797322.18     10104939.68

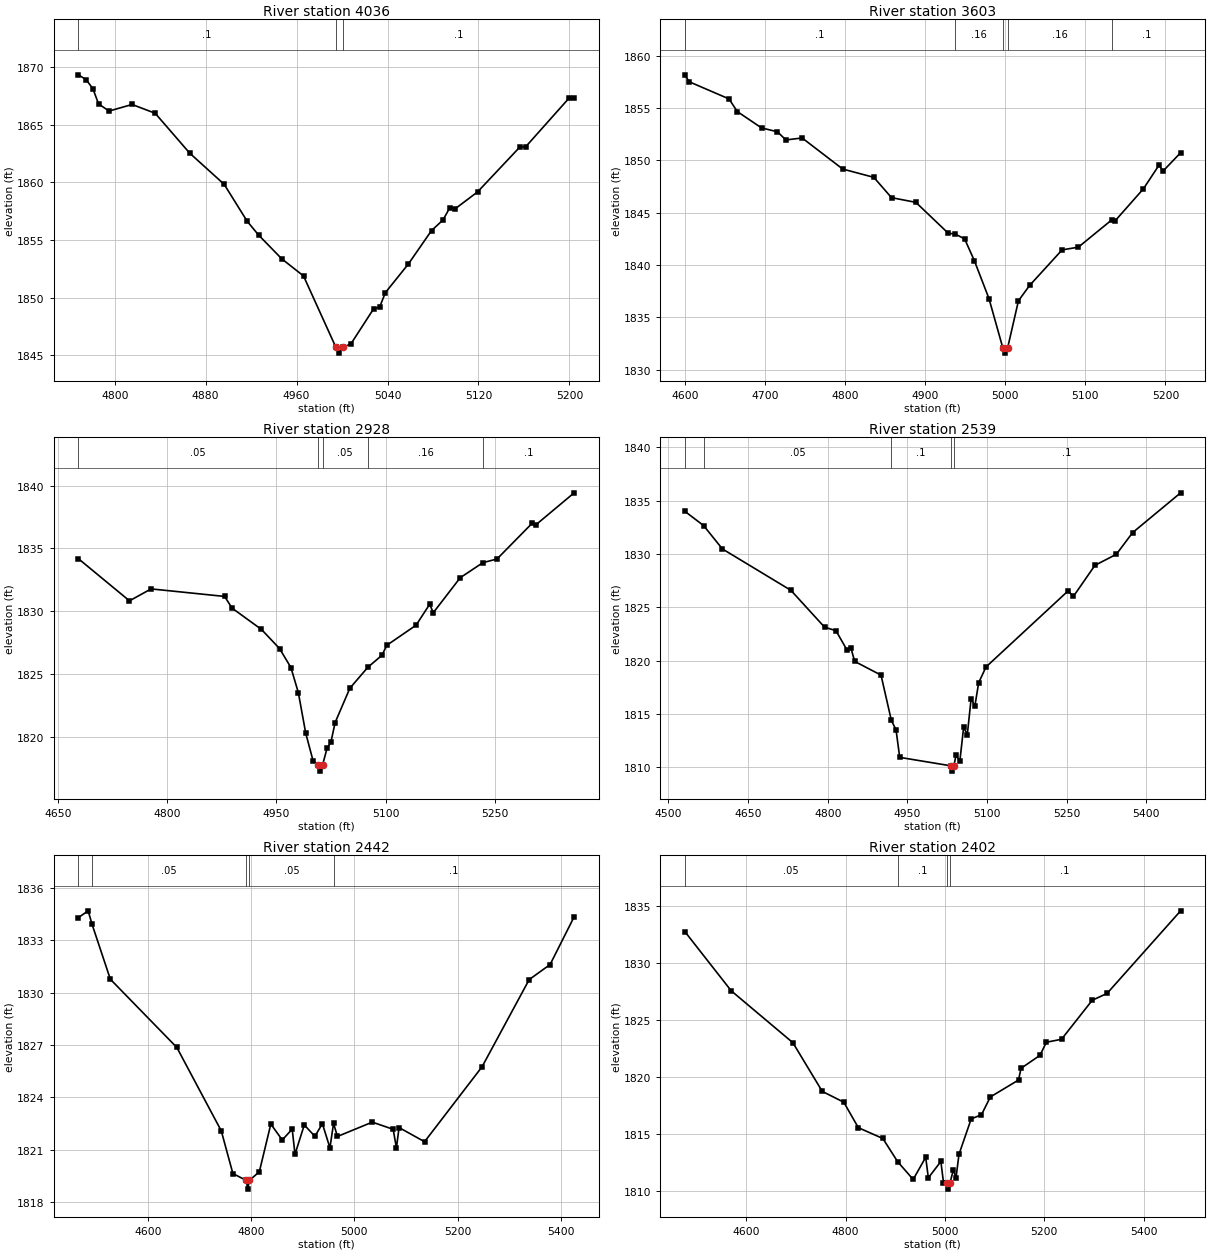
Type RM Length L Ch R = 1,4036,433,433,433
BEGIN DESCRIPTION:
UNT065 IN NNOGR 8.0
END DESCRIPTION:
XS GIS Cut Line= 2
      2794201.29     10104530.43      2794270.75     10104099.80
#Sta/Elev= 30
  4768.0 1869.32  4774.8 1868.91  4780.8 1868.12  4785.8 1866.80  4795.0 1866.18
  4815.3 1866.75  4835.6 1865.99  4865.9 1862.54  4896.3 1859.83  4916.6 1856.62
  4926.7 1855.42  4947.0 1853.37  4966.1 1851.89  4994.6 1845.70  4997.4 1845.20
  5000.6 1845.70  5007.8 1846.00  5027.9 1849.06  5033.0 1849.17  5038.1 1850.44
  5058.4 1852.93  5078.7 1855.82  5088.8 1856.74  5094.8 1857.80  5099.8 1857.73
  5119.2 1859.17  5156.5 1863.07  5161.6 1863.09  5199.7 1867.30  5204.2 1867.30
#Mann=3,-1,0
  4768.0     0.1       0  4994.6    0.07       0  5000.6     0.1       0
Bank Sta=4994.6,5000.6
Exp/Cntr=0.3,0.1

Type RM Length L Ch R = 1,3603,675,675,675
BEGIN DESCRIPTION:
UNT065 IN NNOGR 7.0
END DESCRIPTION:
XS GIS Cut Line= 2
      2794583.25     10104808.15      2794687.28     10104197.85
#Sta/Elev= 30
  4599.9 1858.17  4605.3 1857.51  4655.1 1855.87  4665.5 1854.66  4695.7 1853.10
  4715.6 1852.73  4726.1 1851.95  4746.4 1852.14  4797.1 1849.17  4835.9 1848.38
  4858.0 1846.44  4888.4 1845.99  4929.0 1843.03  4937.1 1842.98  4949.3 1842.50
  4961.4 1840.43  4979.7 1836.80  4997.0 1832.09  4999.8 1831.59  5003.0 1832.09
  5016.5 1836.59  5030.4 1838.05  5071.0 1841.45  5091.3 1841.71  5133.4 1844.34
  5136.9 1844.20  5172.5 1847.28  5192.0 1849.54  5197.1 1848.98  5219.0 1850.73
#Mann=5,-1,0
  4599.9     0.1       0  4937.1    0.16       0  4997.0    0.07       0
  5003.0    0.16       0  5133.4     0.1       0
Bank Sta=4997,5003
Exp/Cntr=0.3,0.1

Type RM Length L Ch R = 1,2928,389,389,389
BEGIN DESCRIPTION:
UNT065 IN NNOGR 6.0
END DESCRIPTION:
XS GIS Cut Line= 2
      2795104.08     10105002.59      2795201.30     10104328.97
#Sta/Elev= 30
  4678.0 1834.19  4748.2 1830.83  4777.9 1831.78  4878.8 1831.18  4889.0 1830.25
  4929.4 1828.55  4954.2 1827.03  4969.8 1825.52  4980.0 1823.52  4990.1 1820.30
  5000.2 1818.10  5007.3 1817.77  5010.0 1817.27  5013.3 1817.77  5019.5 1819.11
  5024.6 1819.55  5030.5 1821.14  5050.7 1823.87  5075.6 1825.55  5094.9 1826.50
  5101.2 1827.28  5141.6 1828.89  5160.2 1830.55  5165.3 1829.89  5202.2 1832.67
  5233.3 1833.87  5252.7 1834.16  5301.0 1837.01  5306.0 1836.88  5358.6 1839.43
#Mann=5,-1,0
  4678.0    0.05       0  5007.3   0.035       0  5013.3    0.05       0
  5075.6    0.16       0  5233.3     0.1       0
Bank Sta=5007.3,5013.3
Exp/Cntr=0.3,0.1

Type RM Length L Ch R = 1,2539,97,97,97
BEGIN DESCRIPTION:
UNT065 IN NNOGR 5.0
END DESCRIPTION:
XS GIS Cut Line= 4
      2795229.52     10105083.60      2795392.26     10104868.79
      2795603.20     10104650.04      2795544.59     10104294.52
#Sta/Elev= 30
  4530.7 1834.00  4566.1 1832.66  4601.5 1830.47  4730.5 1826.59  4794.0 1823.13
  4815.3 1822.81  4836.4 1820.97  4843.6 1821.18  4850.5 1819.93  4900.2 1818.64
  4919.7 1814.39  4928.5 1813.51  4935.4 1810.93  5031.4 1810.14  5034.2 1809.64
  5037.4 1810.14  5041.6 1811.16  5048.6 1810.56  5055.8 1813.76  5062.7 1813.06
  5069.9 1816.44  5076.9 1815.72  5084.1 1817.93  5098.0 1819.41  5252.4 1826.53
  5262.5 1826.02  5303.0 1828.93  5343.4 1829.97  5374.0 1832.00  5464.4 1835.73
#Mann=5,-1,0
  4530.7     0.1       0  4566.1    0.05       0  4919.7     0.1       0
  5031.4    0.07       0  5037.4     0.1       0
Bank Sta=5031.4,5037.4
Exp/Cntr=0.3,0.1

Type RM Length L Ch R = 1,2442,40,40,40
BEGIN DESCRIPTION:
Mapping XS 3874e7fe
END DESCRIPTION:
XS GIS Cut Line= 6
      2795246.45     10105088.81      2795398.77     10104889.62
      2795582.36     10104806.29      2795625.33     10104749.00
      2795629.24     10104691.70      2795568.21     10104317.74
#Sta/Elev= 30
  4465.2 1834.28  4484.2 1834.67  4491.9 1833.89  4527.2 1830.76  4656.0 1826.86
  4742.1 1822.09  4764.6 1819.65  4790.5 1819.26  4793.3 1818.76  4796.5 1819.26
  4815.8 1819.75  4838.1 1822.48  4860.2 1821.57  4879.5 1822.19  4884.9 1820.75
  4902.9 1822.43  4923.4 1821.78  4938.0 1822.50  4952.6 1821.12  4959.6 1822.52
  4967.1 1821.77  5034.7 1822.59  5075.1 1822.18  5081.4 1821.12  5086.5 1822.28
  5135.9 1821.47  5247.4 1825.76  5338.6 1830.74  5379.1 1831.60  5425.7 1834.33
#Mann=5,-1,0
  4465.2     0.1       0  4491.9    0.05       0  4790.5    0.07       0
  4796.5    0.05       0  4959.6     0.1       0
Bank Sta=4790.5,4796.5
Exp/Cntr=0.3,0.1

Type RM Length L Ch R = 1,2402,139,139,139
BEGIN DESCRIPTION:
UNT065 IN NNOGR 4.0
END DESCRIPTION:
XS GIS Cut Line= 4
      2795436.54     10105208.62      2795599.29     10104922.17
      2795690.44     10104673.47      2795601.89     10104280.25
#Sta/Elev= 30
  4476.7 1832.79  4570.1 1827.58  4694.1 1823.02  4753.2 1818.74  4796.5 1817.79
  4825.8 1815.55  4875.1 1814.60  4904.9 1812.56  4936.1 1811.00  4961.3 1812.95
  4966.6 1811.14  4991.8 1812.58  4997.1 1810.73  5003.9 1810.65  5006.6 1810.15
  5009.9 1810.65  5016.9 1811.84  5022.3 1811.15  5028.2 1813.20  5052.8 1816.32
  5073.5 1816.69  5091.3 1818.25  5148.0 1819.74  5153.1 1820.77  5191.2 1821.91
  5204.0 1823.06  5234.5 1823.32  5296.3 1826.75  5326.1 1827.35  5474.1 1834.61
#Mann=4,-1,0
  4476.7    0.05       0  4904.9     0.1       0  5003.9    0.07       0
  5009.9     0.1       0
Bank Sta=5003.9,5009.9
Exp/Cntr=0.3,0.1

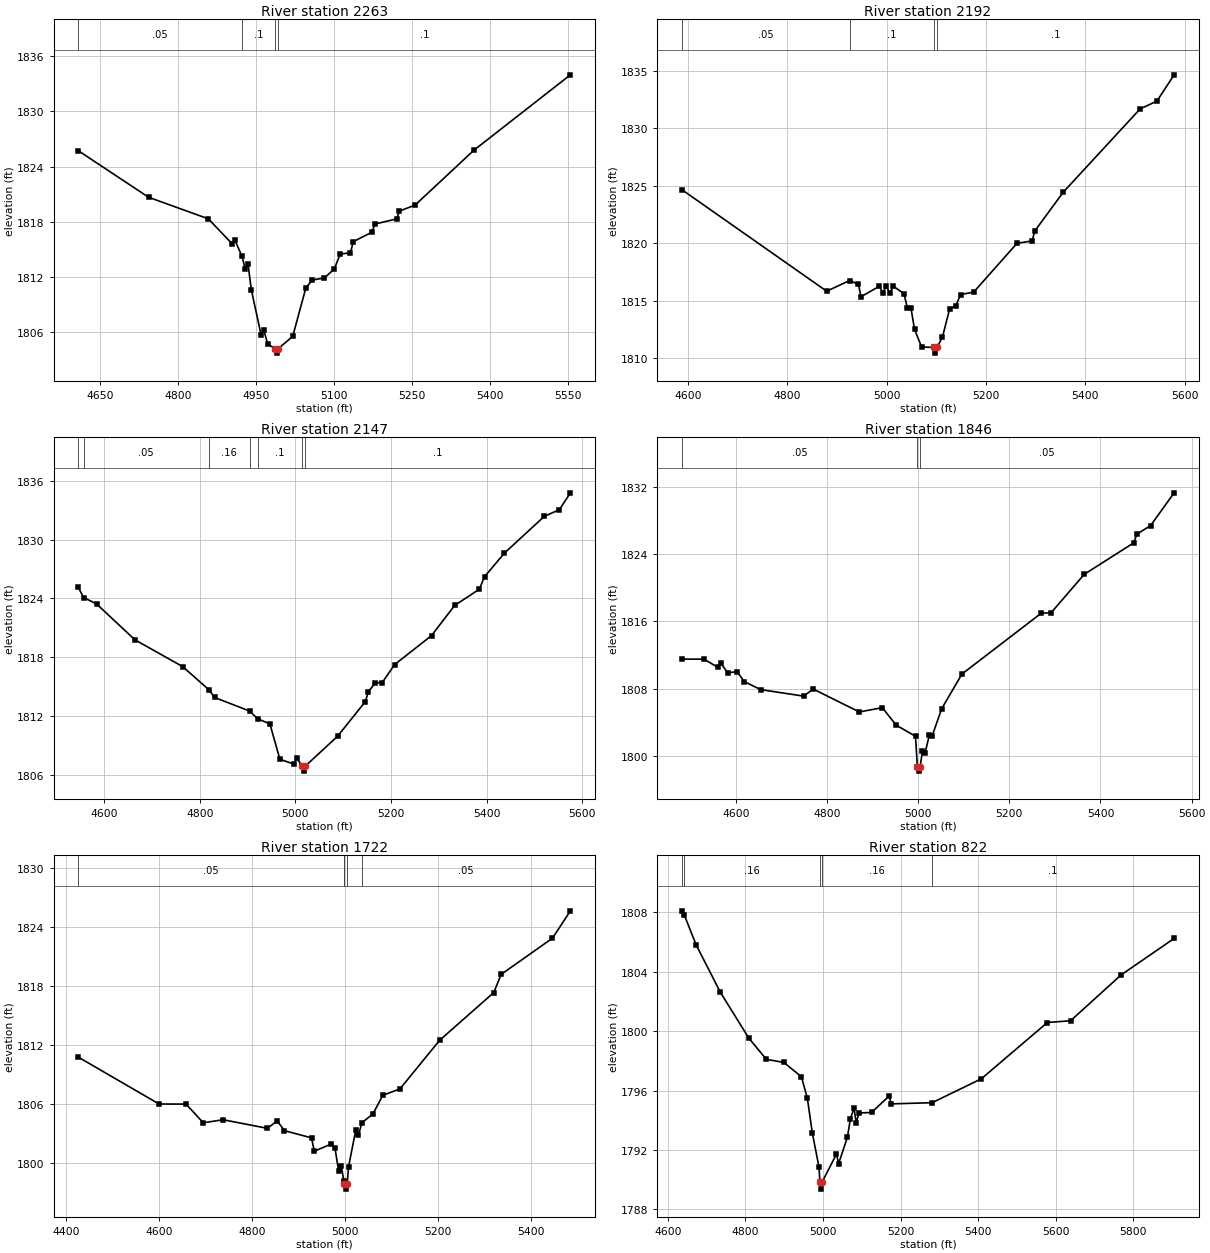
Type RM Length L Ch R = 1,2263,71,71,71
BEGIN DESCRIPTION:
Mapping XS d3d03de2
END DESCRIPTION:
XS GIS Cut Line= 4
      2795772.47     10105203.42      2795795.90     10104914.36
      2795712.57     10104687.80      2795616.21     10104282.82
#Sta/Elev= 30
  4607.8 1825.74  4743.4 1820.67  4858.3 1818.33  4904.3 1815.62  4909.7 1815.99
  4923.4 1814.24  4929.5 1812.83  4934.8 1813.45  4941.1 1810.65  4959.9 1805.75
  4965.3 1806.20  4973.1 1804.68  4987.4 1804.24  4990.2 1803.74  4993.4 1804.24
  5020.9 1805.56  5046.0 1810.79  5058.3 1811.68  5081.8 1811.90  5100.9 1812.88
  5112.3 1814.50  5132.1 1814.64  5137.4 1815.85  5173.8 1816.89  5179.0 1817.76
  5221.1 1818.32  5226.3 1819.17  5256.5 1819.82  5369.5 1825.77  5555.5 1833.97
#Mann=4,-1,0
  4607.8    0.05       0  4923.4     0.1       0  4987.4    0.07       0
  4993.4     0.1       0
Bank Sta=4987.4,4993.4
Exp/Cntr=0.3,0.1

Type RM Length L Ch R = 1,2192,45,45,45
BEGIN DESCRIPTION:
Mapping XS 4320103e
END DESCRIPTION:
XS GIS Cut Line= 5
      2795802.42     10105198.21      2795847.99     10104879.20
      2795838.87     10104808.89      2795733.40     10104696.91
      2795624.38     10104267.31
#Sta/Elev= 30
  4588.3 1824.66  4879.6 1815.82  4925.6 1816.75  4943.5 1816.42  4948.5 1815.34
  4985.5 1816.25  4992.4 1815.70  4999.7 1816.25  5006.5 1815.64  5013.8 1816.25
  5034.9 1815.61  5042.1 1814.35  5049.0 1814.37  5056.3 1812.51  5070.5 1810.96
  5095.4 1810.93  5098.2 1810.43  5101.4 1810.93  5112.5 1811.83  5126.7 1814.25
  5139.5 1814.57  5148.9 1815.53  5175.2 1815.74  5262.4 1819.99  5292.9 1820.20
  5298.1 1821.06  5355.2 1824.43  5510.0 1831.69  5543.8 1832.37  5578.5 1834.66
#Mann=4,-1,0
  4588.3    0.05       0  4925.6     0.1       0  5095.4    0.07       0
  5101.4     0.1       0
Bank Sta=5095.4,5101.4
Exp/Cntr=0.3,0.1

Type RM Length L Ch R = 1,2147,301,301,301
BEGIN DESCRIPTION:
Mapping XS 87801c53
END DESCRIPTION:
XS GIS Cut Line= 4
      2795923.51     10105202.16      2795935.23     10104864.88
      2795750.33     10104622.69      2795640.94     10104251.56
#Sta/Elev= 30
  4545.8 1825.17  4557.1 1824.10  4584.2 1823.45  4664.3 1819.80  4764.4 1817.06
  4819.3 1814.70  4831.0 1813.92  4904.3 1812.54  4921.0 1811.75  4946.7 1811.23
  4967.5 1807.63  4996.6 1807.14  5002.9 1807.73  5014.4 1806.92  5017.2 1806.42
  5020.4 1806.92  5088.1 1809.97  5146.2 1813.50  5152.5 1814.51  5167.1 1815.41
  5181.6 1815.44  5207.4 1817.27  5284.5 1820.22  5332.9 1823.29  5384.4 1824.94
  5395.4 1826.22  5437.1 1828.63  5520.5 1832.37  5551.8 1833.04  5574.9 1834.76
#Mann=7,-1,0
  4545.8     0.1       0  4557.1    0.05       0  4819.3    0.16       0
  4904.3    0.05       0  4921.0     0.1       0  5014.4    0.07       0
  5020.4     0.1       0
Bank Sta=5014.4,5020.4
Exp/Cntr=0.3,0.1

Type RM Length L Ch R = 1,1846,124,124,124
BEGIN DESCRIPTION:
UNT065 IN NNOGR 3.0
END DESCRIPTION:
XS GIS Cut Line= 2
      2796407.89     10105112.29      2795828.43     10104200.78
#Sta/Elev= 30
  4481.5 1811.51  4530.1 1811.51  4560.6 1810.52  4566.5 1811.08  4581.7 1809.89
  4602.9 1810.01  4618.1 1808.84  4654.6 1807.87  4748.6 1807.10  4769.7 1807.94
  4870.8 1805.21  4921.3 1805.72  4951.8 1803.63  4994.1 1802.31  4998.2 1798.65
  5000.9 1798.15  5004.2 1798.65  5009.4 1800.56  5015.3 1800.35  5024.6 1802.50
  5030.5 1802.33  5051.7 1805.61  5096.0 1809.73  5270.2 1817.00  5291.4 1817.03
  5364.2 1821.62  5473.4 1825.40  5479.4 1826.41  5509.9 1827.44  5561.6 1831.35
#Mann=3,-1,0
  4481.5    0.05       0  4998.2    0.04       0  5004.2    0.05       0
Bank Sta=4998.2,5004.2
Exp/Cntr=0.3,0.1

Type RM Length L Ch R = 1,1722,900,900,900
BEGIN DESCRIPTION:
UNT065 IN NNOGR 2.0
END DESCRIPTION:
XS GIS Cut Line= 2
      2796544.60     10105135.71      2795996.44     10104230.79
#Sta/Elev= 30
  4426.0 1810.74  4599.9 1805.97  4658.0 1805.96  4694.9 1804.06  4737.6 1804.37
  4832.6 1803.50  4853.9 1804.25  4869.4 1803.26  4927.6 1802.53  4933.5 1801.17
  4970.3 1801.91  4977.8 1801.54  4985.8 1799.19  4991.6 1799.67  4996.9 1798.18
  4998.2 1797.82  5000.9 1797.32  5004.2 1797.82  5007.1 1799.57  5022.6 1803.31
  5028.5 1802.79  5035.7 1804.07  5059.5 1804.95  5080.8 1806.86  5117.6 1807.50
  5203.0 1812.45  5319.4 1817.30  5334.9 1819.13  5445.4 1822.82  5484.0 1825.60
#Mann=5,-1,0
  4426.0    0.05       0  4996.9    0.16       0  4998.2    0.07       0
  5004.2    0.16       0  5035.7    0.05       0
Bank Sta=4998.2,5004.2
Exp/Cntr=0.3,0.1

Type RM Length L Ch R = 1,822,367,367,367
BEGIN DESCRIPTION:
Mapping XS 294630aa
END DESCRIPTION:
XS GIS Cut Line= 3
      2796568.96     10105095.06      2796834.59     10104544.70
      2796819.01     10103886.90
#Sta/Elev= 30
  4636.0 1808.10  4641.7 1807.85  4672.9 1805.80  4735.1 1802.62  4808.5 1799.53
  4853.7 1798.10  4898.9 1797.89  4944.1 1796.93  4959.5 1795.48  4972.3 1793.14
  4989.4 1790.85  4991.9 1789.86  4994.7 1789.36  4997.9 1789.86  5034.6 1791.72
  5040.1 1791.08  5062.7 1792.85  5070.5 1794.10  5079.8 1794.81  5085.3 1793.84
  5092.7 1794.49  5125.0 1794.52  5170.2 1795.63  5175.8 1795.10  5281.1 1795.18
  5408.1 1796.79  5578.2 1800.58  5638.2 1800.70  5768.2 1803.78  5905.1 1806.24
#Mann=5,-1,0
  4636.0    0.05       0  4641.7    0.16       0  4991.9    0.07       0
  4997.9    0.16       0  5281.1     0.1       0
Bank Sta=4991.9,4997.9
Exp/Cntr=0.3,0.1

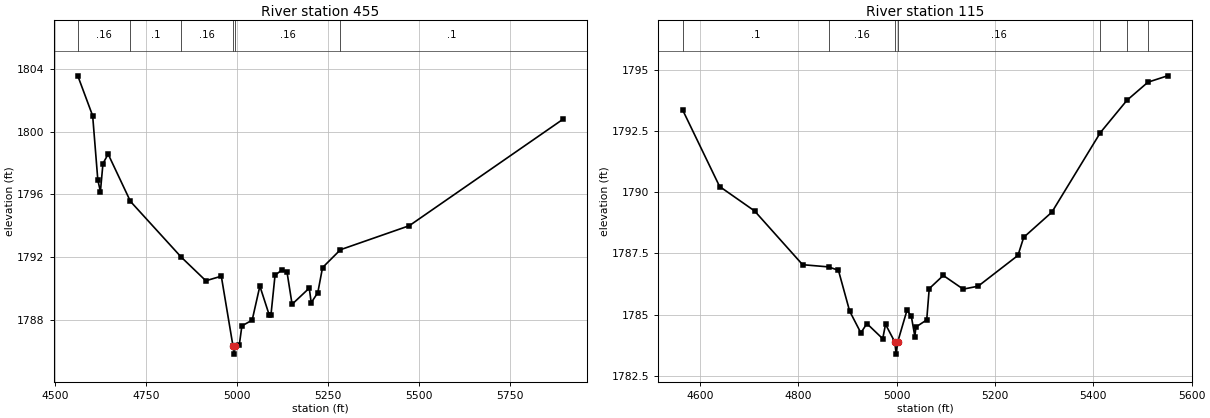
Type RM Length L Ch R = 1,455,340,340,340
BEGIN DESCRIPTION:
UNT065 IN NNOGR 1.0
END DESCRIPTION:
XS GIS Cut Line= 4
      2796692.26     10105105.44      2797069.35     10104738.72
      2797180.08     10104480.46      2797044.66     10103971.78
#Sta/Elev= 30
  4561.3 1803.56  4602.2 1801.01  4616.4 1796.91  4623.5 1796.18  4630.5 1797.96
  4644.7 1798.57  4706.1 1795.55  4845.6 1792.00  4913.4 1790.49  4955.9 1790.78
  4988.1 1786.31  4990.9 1785.81  4994.1 1786.31  5005.3 1786.39  5012.5 1787.61
  5040.8 1787.98  5061.9 1790.15  5087.3 1788.33  5092.5 1788.33  5103.6 1790.84
  5121.5 1791.16  5136.3 1791.08  5150.5 1788.99  5197.7 1790.02  5203.1 1789.09
  5221.2 1789.73  5234.2 1791.33  5283.5 1792.47  5472.7 1794.00  5894.7 1800.78
#Mann=6,-1,0
  4561.3    0.16       0  4706.1     0.1       0  4845.6    0.16       0
  4988.1    0.07       0  4994.1    0.16       0  5283.5     0.1       0
Bank Sta=4988.1,4994.1
Exp/Cntr=0.3,0.1

Type RM Length L Ch R = 1,115,0,0,0
BEGIN DESCRIPTION:
UNT065 IN NNOGR 1.1
END DESCRIPTION:
XS GIS Cut Line= 3
      2796890.41     10105056.63      2797307.10     10104828.32
      2797227.25     10104323.13
#Sta/Elev= 30
  4564.3 1793.38  4639.7 1790.24  4710.8 1789.24  4808.5 1787.04  4861.4 1786.95
  4881.4 1786.81  4904.2 1785.14  4927.0 1784.25  4939.3 1784.63  4971.5 1784.01
  4977.2 1784.60  4996.0 1783.88  4998.8 1783.38  5002.0 1783.88  5020.8 1785.17
  5029.6 1784.94  5036.9 1784.10  5039.0 1784.49  5061.0 1784.78  5066.1 1786.06
  5094.7 1786.60  5135.2 1786.04  5165.6 1786.16  5246.6 1787.42  5258.3 1788.16
  5315.6 1789.19  5414.4 1792.45  5468.4 1793.77  5511.1 1794.51  5550.9 1794.77
#Mann=7,-1,0
  4564.3     0.1       0  4861.4    0.16       0  4996.0    0.07       0
  5002.0    0.16       0  5414.4     0.1       0  5468.4    0.05       0
  5511.1     0.1       0
Bank Sta=4996,5002
Exp/Cntr=0.3,0.1

Chan Stop Cuts=-1