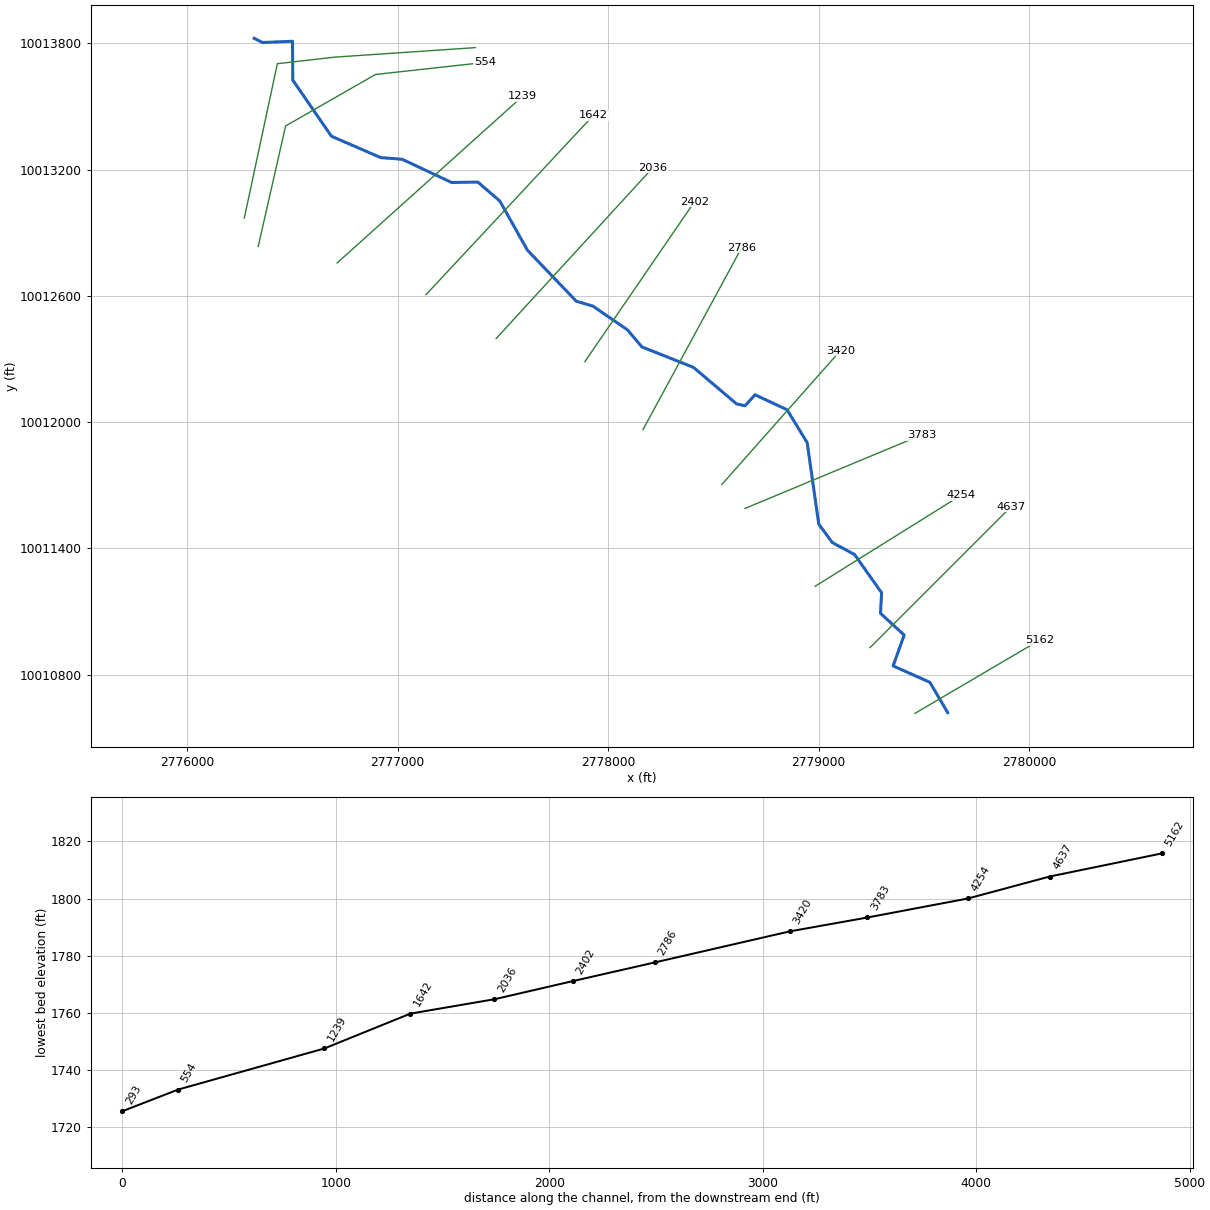
--- UNT065 IN SNOGR.prj (project) ---

Proj Title=UNT065 IN SNOGR Base Level Engineering
Current Plan=p01
Default Exp/Contr=0.3,0.1
English Units
Geom File=g01
Flow File=f01
Plan File=p01
Y Axis Title=Elevation
X Axis Title(PF)=Main Channel Distance
X Axis Title(XS)=Station
BEGIN DESCRIPTION:
UNT065 IN SNOGR
END DESCRIPTION:
DSS Export Rating Curves= 0
DSS Export Rating Curve Sorted= 0
DSS Export Volume Flow Curves= 0
DXF OffsetX= 0
DXF OffsetY= 0
DXF ScaleX= 1
DXF ScaleY= 10

--- UNT065 IN SNOGR.p01 (plan) ---

Plan Title=Multiple Run
Short Identifier=Multiple
Geom File=g01
Flow File=f01
Subcritical Flow
K Sum by GR= 0
Std Step Tol= 0.01
Critical Tol= 0.01
Num of Std Step Trials= 20
Max Error Tol= 0.3
Flow Tol Ratio= 0.001
Split Flow NTrial= 30
Split Flow Tol= 0.02
Split Flow Ratio= 0.02
Log Output Level= 0
Friction Slope Method= 1
Unsteady Friction Slope Method= 2
Unsteady Bridges Friction Slope Method= 1
Parabolic Critical Depth
Global Vel Dist=  1 , 1 , 1
Global Log Level= 0
CheckData=True
Encroach Param= -1, 0, 0, 0
BEGIN DESCRIPTION:
Multiple Run
END DESCRIPTION:

--- UNT065 IN SNOGR.f01 (steady flow) ---

Flow Title=Multiple
Number of Profiles=7
Profile Names=10-year,25-year,50-year,1pct_min,100-year,1pct_plu,500-year
River Rch & RM= UNT065 IN SNOGR,Reach-1,5162
     619     884    1112    1025    1386    1874    2160
Boundary for River Rch & Prof#=UNT065 IN SNOGR,Reach-1,1
Up Type=0
Dn Type=3
Dn Slope=0.005
Boundary for River Rch & Prof#=UNT065 IN SNOGR,Reach-1,2
Up Type=0
Dn Type=3
Dn Slope=0.005
Boundary for River Rch & Prof#=UNT065 IN SNOGR,Reach-1,3
Up Type=0
Dn Type=3
Dn Slope=0.005
Boundary for River Rch & Prof#=UNT065 IN SNOGR,Reach-1,4
Up Type=0
Dn Type=3
Dn Slope=0.005
Boundary for River Rch & Prof#=UNT065 IN SNOGR,Reach-1,5
Up Type=0
Dn Type=3
Dn Slope=0.005
Boundary for River Rch & Prof#=UNT065 IN SNOGR,Reach-1,6
Up Type=0
Dn Type=3
Dn Slope=0.005
Boundary for River Rch & Prof#=UNT065 IN SNOGR,Reach-1,7
Up Type=0
Dn Type=3
Dn Slope=0.005

--- UNT065 IN SNOGR.g01 (geometry) ---

Geom Title=Existing Conditions
Program Version=4.10

River Reach=UNT065 IN SNOGR ,Reach-1
Reach XY= 30
       2779612.9      10010619.3      2779528.38     10010763.29
      2779353.75     10010841.32      2779406.35     10010987.69
      2779293.83     10011091.25      2779298.99     10011188.84
      2779170.91      10011370.2      2779065.14     10011427.35
      2779000.68     10011514.64      2778945.44     10011902.48
      2778850.14     10012058.46       2778697.6      10012129.8
      2778650.43     10012077.39      2778610.18     10012086.48
      2778405.95     10012259.58      2778160.48     10012357.31
      2778091.24     10012438.78      2777927.31     10012551.16
      2777848.67     10012574.42      2777616.47     10012817.11
      2777485.64     10013050.29      2777380.89      10013140.7
      2777256.42     10013138.68       2777021.3      10013249.2
      2776919.76     10013256.85      2776685.54      10013358.5
      2776501.91     10013625.22       2776500.7     10013809.84
      2776358.64     10013803.75      2776318.47     10013823.73

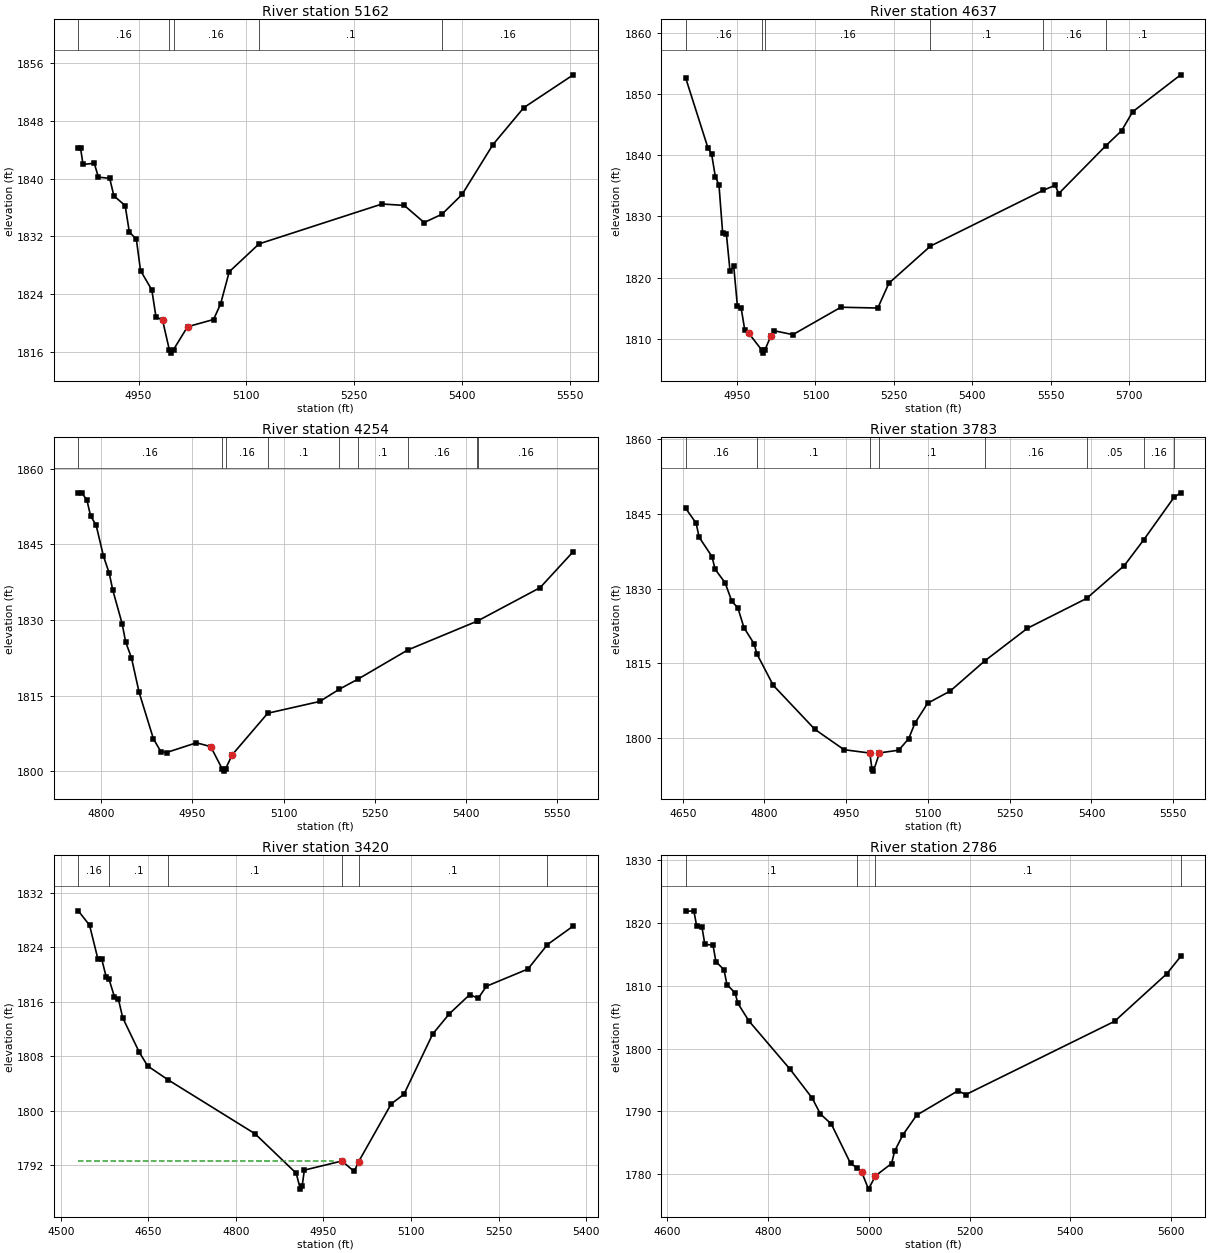
Type RM Length L Ch R = 1 ,5162    ,525,525,525
BEGIN DESCRIPTION:
UNT065 IN SNOGR 11.0
END DESCRIPTION:
XS GIS Cut Line= 2
      2779457.45      10010615.6      2780051.19     10010964.56
#Sta/Elev= 30
  4866.1 1844.25  4869.2 1844.25  4872.7 1841.95  4888.3 1842.12  4894.1 1840.19
  4909.8 1840.03  4915.6  1837.6  4931.3 1836.25  4937.1  1832.6  4946.9 1831.57
  4952.7 1827.24  4968.4 1824.55  4974.2 1820.82  4983.3 1820.37  4992.7 1816.29
  4995.4 1815.79  4998.7 1816.29  5018.1 1819.45  5054.3 1820.45  5064.2 1822.64
  5076.1 1827.07  5117.6 1830.94  5288.7 1836.47  5319.7 1836.27  5347.3  1833.9
  5372.1 1835.05  5400.1 1837.79    5443  1844.7    5486 1849.83  5554.8 1854.38
#Mann= 5 ,-1 , 0
  4866.1     .16       0  4992.7     .07       0  4998.7     .16       0
  5117.6      .1       0  5372.1     .16       0
Bank Sta=4983.3,5018.1
XS Rating Curve= 0 ,0
Exp/Cntr=0.3,0.1

Type RM Length L Ch R = 1 ,4637    ,383,383,383
BEGIN DESCRIPTION:
UNT065 IN SNOGR 10.0
END DESCRIPTION:
XS GIS Cut Line= 2
      2779243.93     10010928.13      2779913.99     10011598.19
#Sta/Elev= 30
  4851.5  1852.6    4894 1841.22  4901.1 1840.21  4908.2 1836.51  4915.2 1835.17
  4922.3 1827.26  4929.4 1827.17  4936.4 1821.06  4943.5 1821.84  4950.6 1815.31
  4957.7 1815.06  4964.7 1811.41  4971.8    1811  4997.1  1808.2  4999.8  1807.7
  5003.1  1808.2  5014.2 1810.43  5021.3 1811.34  5056.7 1810.72  5148.6 1815.19
  5219.3 1815.06  5240.5 1819.11  5320.1 1825.17  5535.8 1834.27  5558.7 1835.09
  5565.8 1833.75  5655.4 1841.51    5686    1844  5707.2 1847.09  5799.1 1853.12
#Mann= 6 ,-1 , 0
  4851.5     .16       0  4997.1     .07       0  5003.1     .16       0
  5320.1      .1       0  5535.8     .16       0  5655.4      .1       0
Bank Sta=4971.8,5014.2
XS Rating Curve= 0 ,0
Exp/Cntr=0.3,0.1

Type RM Length L Ch R = 1 ,4254    ,471,471,471
BEGIN DESCRIPTION:
UNT065 IN SNOGR 9.0
END DESCRIPTION:
XS GIS Cut Line= 2
      2778983.49     10011219.77      2779674.82      10011651.2
#Sta/Elev= 30
    4762 1855.19  4767.9 1855.19  4776.3  1853.7  4782.2 1850.63  4791.4 1848.76
  4803.5 1842.61  4812.9 1839.27  4818.8 1835.89  4834.1 1829.28    4840 1825.62
  4849.5 1822.49  4862.2  1815.6  4885.7 1806.41  4897.8  1803.9  4907.3  1803.7
  4956.5 1805.63    4980 1804.87  4998.7 1800.51  5001.4 1800.01  5004.7 1800.51
  5015.4 1803.25  5073.9 1811.49  5159.7 1813.83  5191.4 1816.23  5222.1 1818.23
  5304.6 1824.04  5417.8  1829.7  5419.9 1829.82  5522.3 1836.39  5576.9 1843.54
#Mann= 9 ,-1 , 0
    4762     .16       0  4998.7     .07       0  5004.7     .16       0
  5073.9      .1       0  5191.4     .16       0  5222.1      .1       0
  5304.6     .16       0  5417.8      .1       0  5419.9     .16       0
Bank Sta=4980,5015.4
XS Rating Curve= 0 ,0
Exp/Cntr=0.3,0.1

Type RM Length L Ch R = 1 ,3783    ,363,363,363
BEGIN DESCRIPTION:
UNT065 IN SNOGR 8.0
END DESCRIPTION:
XS GIS Cut Line= 2
      2778650.14     10011589.56      2779488.73     10011938.53
#Sta/Elev= 30
  4655.4  1846.1  4674.6 1843.11    4680 1840.31  4703.8 1836.39  4709.2  1833.9
  4727.7 1831.16  4740.2 1827.41  4751.1 1826.14  4762.3 1822.15  4780.8 1818.93
  4786.2 1816.85  4816.1 1810.57  4892.4 1801.74    4946 1797.65  4993.2 1796.98
  4997.2 1793.85  4999.9 1793.35    5011 1797.01  5046.3 1797.55  5064.7 1799.88
    5076 1802.97  5099.4 1806.98    5141 1809.44  5204.1 1815.47  5282.6 1822.03
    5391 1828.01  5460.3 1834.61    5496 1839.79  5551.4 1848.29  5563.7 1849.21
#Mann= 8 ,-1 , 0
  4655.4     .16       0  4786.2      .1       0  4993.2     .07       0
    5011      .1       0  5204.1     .16       0    5391     .05       0
    5496     .16       0  5551.4     .05       0
Bank Sta=4993.2,5011
XS Rating Curve= 0 ,0
Exp/Cntr=0.3,0.1

Type RM Length L Ch R = 1 ,3420    ,634,634,634
BEGIN DESCRIPTION:
UNT065 IN SNOGR 7.0
END DESCRIPTION:
XS GIS Cut Line= 2
      2778540.77     10011704.13      2779102.92     10012339.16
#Sta/Elev= 30
  4529.9 1829.34  4549.2 1827.23  4563.4  1822.3  4570.1 1822.25  4577.7 1819.63
  4582.3 1819.38  4591.9 1816.71  4598.6 1816.38  4606.1 1813.63  4634.6 1808.55
  4648.8 1806.57  4683.9 1804.53  4832.8 1796.62  4903.3 1790.83  4910.3  1788.5
  4913.6    1789  4917.2 1791.29  4981.7 1792.63  5002.6 1791.09  5010.1 1792.51
  5066.1 1801.01  5087.9 1802.42  5137.2 1811.27  5165.7 1814.23  5200.8 1817.06
    5215 1816.49  5229.2 1818.27  5300.3  1820.8  5333.8 1824.39    5378 1827.11
#Mann= 6 ,-1 , 0
  4529.9     .16       0  4582.3      .1       0  4683.9      .1       0
  4981.7     .07       0  5010.1      .1       0  5333.8      .1       0
#XS Ineff= 2 , 0
         4966.86 1792.69
Permanent Ineff=
       T       T
Bank Sta=4981.7,5010.1
XS Rating Curve= 0 ,0
Exp/Cntr=0.3,0.1

Type RM Length L Ch R = 1 ,2786    ,384,384,384
BEGIN DESCRIPTION:
UNT065 IN SNOGR 6.0
END DESCRIPTION:
XS GIS Cut Line= 2
      2778165.76     10011964.53       2778633.9     10012827.99
#Sta/Elev= 30
  4636.8 1821.84    4653 1821.93  4658.6  1819.5  4669.1 1819.35  4674.8 1816.59
    4691 1816.47  4696.7 1813.84  4712.9 1812.54  4718.6 1810.18  4734.7 1808.87
  4740.4 1807.19  4762.3 1804.38  4844.1 1796.68  4887.8  1792.1    4904 1789.58
  4925.8 1787.97  4963.9  1781.7  4977.1 1780.96  4985.7 1780.39  4999.6  1777.6
  5013.3 1779.71  5045.4 1781.68  5051.3 1783.63  5067.5 1786.21  5095.1 1789.38
  5176.8 1793.25    5193 1792.67  5487.8 1804.33  5591.4  1811.9    5619 1814.66
#Mann= 4 ,-1 , 0
  4636.8      .1       0  4977.1     .07       0  5013.3      .1       0
    5619     .05       0
Bank Sta=4985.7,5013.3
XS Rating Curve= 0 ,0
Exp/Cntr=0.3,0.1

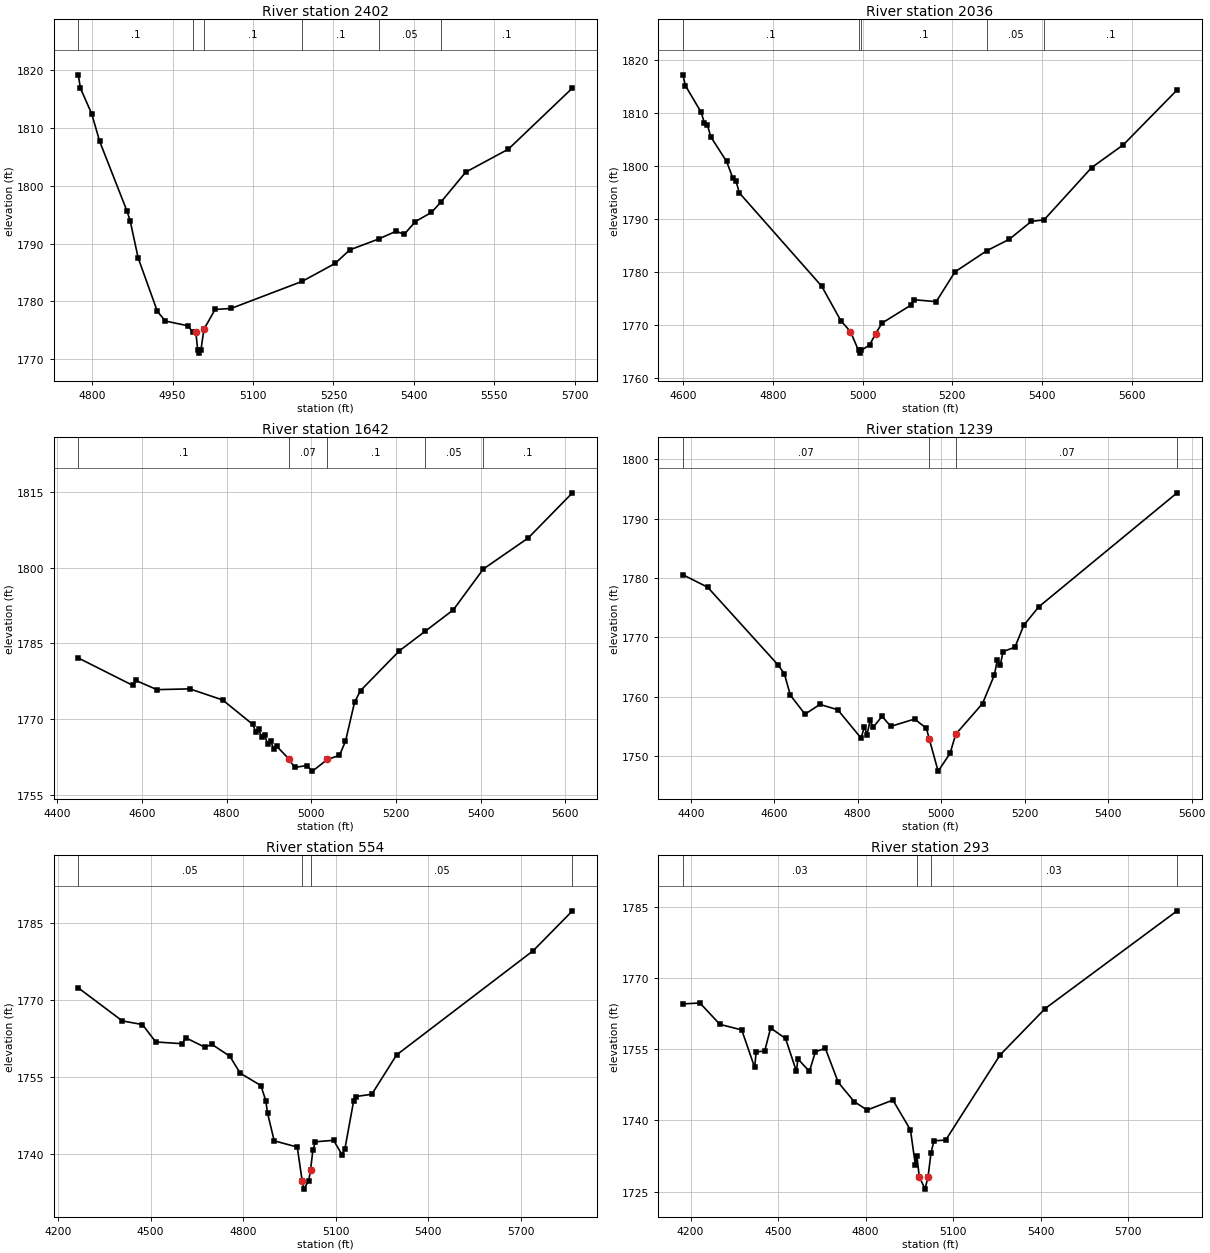
Type RM Length L Ch R = 1 ,2402    ,366,366,366
BEGIN DESCRIPTION:
UNT065 IN SNOGR 5.0
END DESCRIPTION:
XS GIS Cut Line= 2
      2777889.72     10012287.46      2778410.56     10013047.89
#Sta/Elev= 30
    4774 1819.17  4778.1 1816.85  4799.1 1812.43    4814 1807.65  4864.7 1795.67
  4870.8 1793.95  4885.7 1787.53  4921.6 1778.26  4936.5 1776.61  4978.4 1775.79
  4987.3 1774.73  4993.3 1774.69  4996.8 1771.56  4999.5 1771.06  5002.8 1771.56
  5008.3 1775.17  5029.2 1778.61    5059 1778.78    5192 1783.48  5253.3 1786.58
  5280.4 1788.91    5334 1790.78    5367 1792.14  5381.9 1791.59  5402.9 1793.81
  5432.7 1795.38  5450.3 1797.16  5496.7 1802.35  5576.2 1806.32  5695.7 1816.89
#Mann= 6 ,-1 , 0
    4774      .1       0  4987.3     .07       0  5008.3      .1       0
    5192      .1       0    5334     .05       0  5450.3      .1       0
Bank Sta=4993.3,5008.3
XS Rating Curve= 0 ,0
Exp/Cntr=0.3,0.1

Type RM Length L Ch R = 1 ,2036    ,394,394,394
BEGIN DESCRIPTION:
UNT065 IN SNOGR 4.0
END DESCRIPTION:
XS GIS Cut Line= 2
      2777467.87     10012396.86      2778212.38     10013209.06
#Sta/Elev= 30
  4599.4 1817.29  4604.8 1815.27    4640 1810.22  4647.4 1808.16  4654.1  1807.8
  4661.5 1805.58  4696.7 1800.94  4710.9 1797.74  4717.7 1797.25  4725.1    1795
  4908.8 1777.37  4951.4 1770.86  4972.9  1768.8  4990.9 1765.23  4993.7 1764.73
  4996.9 1765.23  5015.5 1766.27  5029.3 1768.42  5043.2  1770.4  5107.4 1773.78
  5114.1 1774.82  5164.1 1774.45    5206 1780.08  5276.9 1784.07  5326.9 1786.23
  5376.2 1789.61  5404.5 1789.89  5510.6 1799.77  5581.5 1804.09  5701.2 1814.44
#Mann= 5 ,-1 , 0
  4599.4      .1       0  4990.9     .07       0  4996.9      .1       0
  5276.9     .05       0  5404.5      .1       0
Bank Sta=4972.9,5029.3
XS Rating Curve= 0 ,0
Exp/Cntr=0.3,0.1

Type RM Length L Ch R = 1 ,1642    ,403,403,403
BEGIN DESCRIPTION:
UNT065 IN SNOGR 3.0
END DESCRIPTION:
XS GIS Cut Line= 2
      2777134.53     10012605.19      2777931.09     10013459.02
#Sta/Elev= 30
  4449.4 1782.12  4578.5 1776.67  4585.4 1777.66  4635.2 1775.84  4712.9 1775.99
  4790.6 1773.79  4861.4 1768.98  4868.7 1767.51  4875.6 1767.97  4882.9  1766.4
  4889.7 1766.81  4897.1 1764.97  4903.9 1765.73  4911.2 1764.03  4918.1 1764.64
  4946.4 1762.17  4960.6 1760.41  4988.9  1760.8  5002.8 1759.69  5038.3 1762.02
  5066.6  1762.8  5080.8  1765.6  5102.3 1773.35  5116.4 1775.65  5208.3 1783.54
  5268.4 1787.36  5335.8 1791.66  5406.5 1799.74  5512.6 1805.89  5617.1 1814.84
#Mann= 5 ,-1 , 0
  4449.4      .1       0  4946.4     .07       0  5038.3      .1       0
  5268.4     .05       0  5406.5      .1       0
Bank Sta=4946.4,5038.3
XS Rating Curve= 0 ,0
Exp/Cntr=0.3,0.1

Type RM Length L Ch R = 1 ,1239    ,685,685,685
BEGIN DESCRIPTION:
UNT065 IN SNOGR 2.0
END DESCRIPTION:
XS GIS Cut Line= 2
      2776712.68     10012756.25      2777592.85     10013547.88
#Sta/Elev= 30
  4381.4 1780.56  4440.6 1778.47  4610.3 1765.29  4624.5 1763.86  4638.7 1760.28
  4673.8 1757.08  4709.7 1758.72  4752.3 1757.82  4808.3 1753.03  4815.8 1754.93
  4822.5 1753.65    4830  1756.1  4836.7 1754.84  4858.4 1756.71  4879.3 1755.02
  4936.2 1756.25  4964.6 1754.71  4971.3 1752.93  4992.7 1747.48  5021.3 1750.46
  5034.8 1753.69  5099.1 1758.87  5127.5 1763.68  5134.2 1766.12  5141.7  1765.4
  5148.4 1767.63  5176.8 1768.36  5197.8 1772.04  5233.6 1775.15  5565.2 1794.37
#Mann= 4 ,-1 , 0
  4381.4     .07       0  4971.3     .05       0  5034.8     .07       0
  5565.2     .16       0
Bank Sta=4971.3,5034.8
XS Rating Curve= 0 ,0
Exp/Cntr=0.3,0.1

Type RM Length L Ch R = 1 ,554     ,261,261,261
BEGIN DESCRIPTION:
UNT065 IN SNOGR 1.5
END DESCRIPTION:
XS GIS Cut Line= 4
      2776337.65     10012834.36      2776467.86     10013407.27
      2776894.94     10013652.06      2777414.62     10013709.22
#Sta/Elev= 30
  4265.6 1772.29  4408.5 1765.85  4473.8 1765.14  4516.8 1761.75    4603 1761.41
  4613.6 1762.58  4675.2 1760.76  4699.4 1761.27  4757.2 1758.97  4790.6 1755.68
  4857.8 1753.26  4873.6 1750.35  4879.4 1747.91    4901  1742.5  4975.8 1741.28
  4991.6 1734.75  4997.1 1733.09  5013.2 1734.77  5018.9 1736.87  5026.7 1740.75
  5034.8 1742.31  5093.7  1742.6  5121.1 1739.76  5130.4 1740.97  5158.5 1750.21
    5165 1751.12  5217.5 1751.56    5298 1759.23  5741.3 1779.54  5868.2 1787.29
#Mann= 4 ,-1 , 0
  4265.6     .05       0  4991.6     .03       0  5018.9     .05       0
  5868.2      .1       0
Bank Sta=4991.6,5018.9
XS Rating Curve= 0 ,0
Exp/Cntr=0.3,0.1

Type RM Length L Ch R = 1 ,293     ,0,0,0
BEGIN DESCRIPTION:
UNT065 IN SNOGR 1.0
END DESCRIPTION:
XS GIS Cut Line= 4
      2776271.67     10012969.73      2776428.64     10013703.24
      2776702.95     10013734.49      2777369.63     10013779.63
#Sta/Elev= 30
  4173.6  1764.5  4231.9 1764.69  4300.4 1760.19  4375.2 1759.02  4419.6 1751.12
  4424.7 1754.41  4453.8 1754.55  4474.3 1759.42  4525.4 1757.22  4562.8  1750.3
  4567.9 1752.92  4607.2 1750.28  4627.7 1754.39  4661.7 1755.18  4706.1 1747.98
  4760.7 1743.94    4805 1742.16  4893.5 1744.25  4953.7 1737.98  4970.5 1730.64
  4975.6 1732.55  4983.9 1728.14  5003.8 1725.51  5014.1 1728.15  5024.2 1733.13
  5034.3 1735.68  5074.5 1735.83  5261.5 1753.79  5415.8 1763.53    5868 1784.09
#Mann= 4 ,-1 , 0
  4173.6     .03       0  4975.6    .025       0  5024.2     .03       0
    5868      .1       0
Bank Sta=4983.9,5014.1
XS Rating Curve= 0 ,0
Exp/Cntr=0.3,0.1

Chan Stop Cuts=-1
Use User Specified Reach Order=0
Composite Channel Slope=5