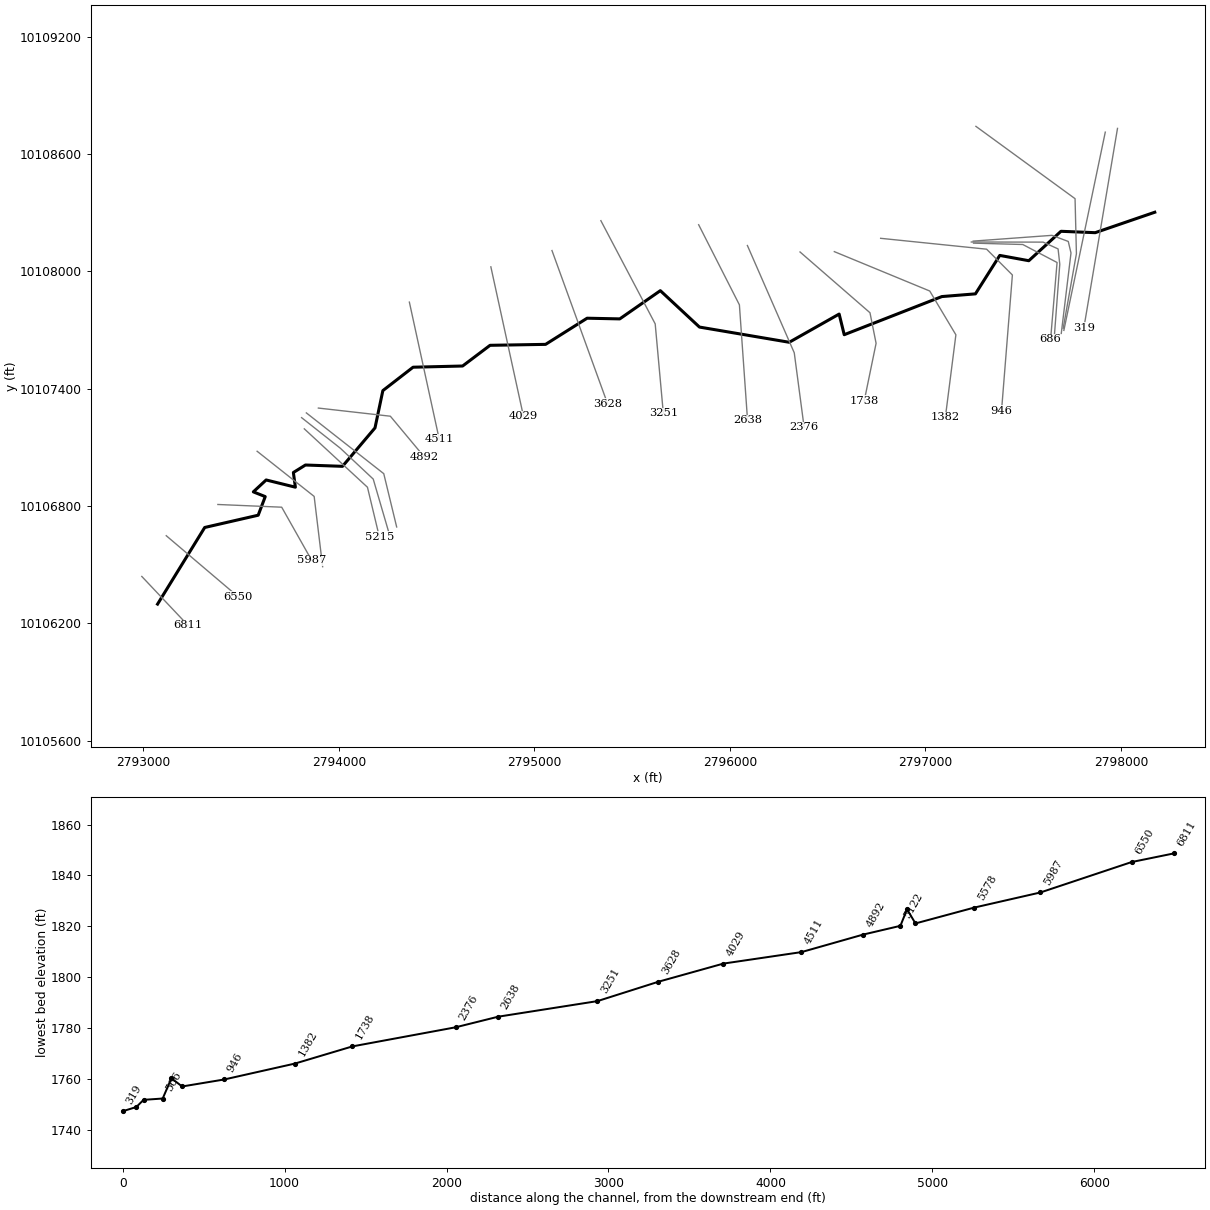
--- UNT066 IN NNOGR.prj (project) ---

Proj Title=UNT066 IN NNOGR Base Level Engineering
Current Plan=p01
Default Exp/Contr=0.3,0.1
English Units
Geom File=g01
Flow File=f01
Plan File=p01
BEGIN DESCRIPTION:
UNT066 IN NNOGR
END DESCRIPTION:

--- UNT066 IN NNOGR.p01 (plan) ---

Plan Title=Multiple Run
Short Identifier=Multiple
Geom File=g01
Flow File=f01
Subcritical Flow
K Sum by GR= 0
Std Step Tol= 0.01
Critical Tol= 0.01
Num of Std Step Trials= 20
Max Error Tol= 0.3
Flow Tol Ratio= 0.001
Split Flow NTrial= 30
Split Flow Tol= 0.02
Split Flow Ratio= 0.02
Log Output Level= 0
Friction Slope Method= 1
Unsteady Friction Slope Method= 2
Unsteady Bridges Friction Slope Method= 1
Parabolic Critical Depth
Global Vel Dist=  1 , 1 , 1
Global Log Level= 0
CheckData=True
Encroach Param= -1, 0, 0, 0
BEGIN DESCRIPTION:
Multiple Run
END DESCRIPTION:

--- UNT066 IN NNOGR.f01 (steady flow) ---

Flow Title=Multiple
Number of Profiles=7
Profile Names=10-year,25-year,50-year,1pct_min,100-year,1pct_plu,500-year
River Rch & RM= UNT066 IN NNOGR,Reach-1,6811
     420     580     712     642     868    1174    1292
River Rch & RM= UNT066 IN NNOGR,Reach-1,566
     495     690     854     775    1048    1417    1582
Boundary for River Rch & Prof#=UNT066 IN NNOGR,Reach-1,1
Up Type=0
Dn Type=3
Dn Slope=0.005
Boundary for River Rch & Prof#=UNT066 IN NNOGR,Reach-1,2
Up Type=0
Dn Type=3
Dn Slope=0.005
Boundary for River Rch & Prof#=UNT066 IN NNOGR,Reach-1,3
Up Type=0
Dn Type=3
Dn Slope=0.005
Boundary for River Rch & Prof#=UNT066 IN NNOGR,Reach-1,4
Up Type=0
Dn Type=3
Dn Slope=0.005
Boundary for River Rch & Prof#=UNT066 IN NNOGR,Reach-1,5
Up Type=0
Dn Type=3
Dn Slope=0.005
Boundary for River Rch & Prof#=UNT066 IN NNOGR,Reach-1,6
Up Type=0
Dn Type=3
Dn Slope=0.005
Boundary for River Rch & Prof#=UNT066 IN NNOGR,Reach-1,7
Up Type=0
Dn Type=3
Dn Slope=0.005

--- UNT066 IN NNOGR.g01 (geometry) ---

Geom Title=Existing Conditions

River Reach=UNT066 IN NNOGR,Reach-1
Reach XY= 30
      2793073.47     10106298.73      2793314.62     10106690.58
      2793588.01     10106753.29      2793624.08     10106848.42
      2793563.17     10106872.67      2793628.68     10106933.53
      2793778.18     10106896.58      2793767.93     10106971.67
      2793829.72     10107010.00      2794018.97     10107003.27
      2794185.29     10107199.80      2794225.44     10107390.43
      2794379.96     10107510.13      2794633.20     10107516.26
      2794773.56     10107622.09      2795057.50     10107626.97
      2795269.82     10107760.73      2795436.81     10107757.22
      2795644.20     10107901.57      2795844.27     10107715.42
      2796303.33     10107637.63      2796558.57     10107781.91
      2796584.51     10107676.36      2797083.77     10107871.40
      2797255.35     10107885.21      2797379.82     10108081.83
      2797528.26     10108054.74      2797692.69     10108205.16
      2797867.75     10108198.08      2798172.35     10108302.62

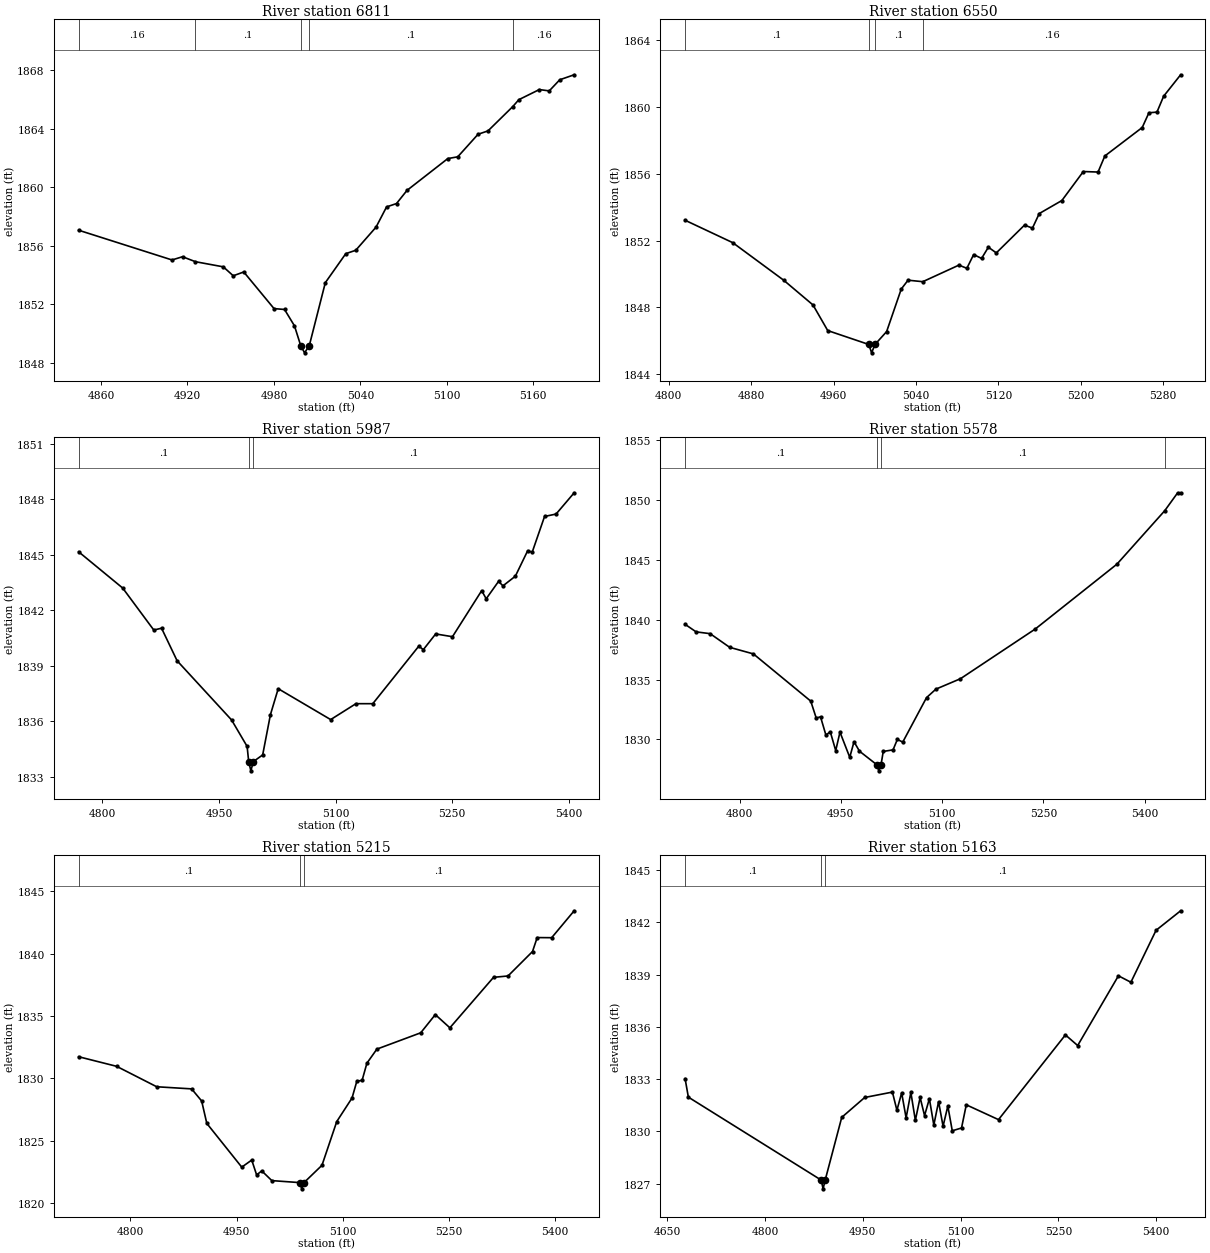
Type RM Length L Ch R = 1,6811,261,261,261
BEGIN DESCRIPTION:
UNT066 IN NNOGR 14.0
END DESCRIPTION:
XS GIS Cut Line= 2
      2792992.97     10106440.11      2793229.10     10106190.09
#Sta/Elev= 30
  4844.5 1857.06  4909.3 1855.03  4916.6 1855.25  4925.6 1854.91  4944.9 1854.56
  4951.8 1853.95  4959.1 1854.21  4980.1 1851.71  4987.4 1851.65  4994.3 1850.53
  4998.6 1849.19  5001.3 1848.69  5004.6 1849.19  5015.7 1853.48  5029.9 1855.46
  5036.8 1855.69  5050.9 1857.27  5058.2 1858.65  5065.1 1858.88  5072.4 1859.78
  5100.7 1861.95  5107.6 1862.07  5121.7 1863.61  5128.6 1863.84  5145.8 1865.50
  5150.0 1865.97  5164.2 1866.66  5171.1 1866.57  5178.4 1867.33  5188.4 1867.67
#Mann=5,-1,0
  4844.5    0.16       0  4925.6     0.1       0  4998.6    0.07       0
  5004.6     0.1       0  5145.8    0.16       0
Bank Sta=4998.6,5004.6
Exp/Cntr=0.3,0.1

Type RM Length L Ch R = 1,6550,563,563,563
BEGIN DESCRIPTION:
UNT066 IN NNOGR 13.0
END DESCRIPTION:
XS GIS Cut Line= 2
      2793117.96     10106648.45      2793484.77     10106337.00
#Sta/Elev= 30
  4815.8 1853.21  4862.1 1851.87  4911.5 1849.63  4940.0 1848.15  4954.3 1846.62
  4994.2 1845.79  4996.9 1845.29  5000.2 1845.79  5011.5 1846.56  5025.7 1849.10
  5032.3 1849.63  5046.6 1849.54  5081.7 1850.53  5089.4 1850.34  5096.0 1851.16
  5103.7 1850.93  5110.3 1851.60  5118.0 1851.26  5145.4 1852.92  5153.1 1852.74
  5159.7 1853.61  5181.7 1854.39  5202.5 1856.12  5216.8 1856.09  5223.4 1857.05
  5259.7 1858.75  5266.2 1859.63  5274.0 1859.67  5280.5 1860.62  5297.0 1861.90
#Mann=4,-1,0
  4815.8     0.1       0  4994.2    0.07       0  5000.2     0.1       0
  5046.6    0.16       0
Bank Sta=4994.2,5000.2
Exp/Cntr=0.3,0.1

Type RM Length L Ch R = 1,5987,409,409,409
BEGIN DESCRIPTION:
UNT066 IN NNOGR 12.0
END DESCRIPTION:
XS GIS Cut Line= 3
      2793381.87     10106808.17      2793708.24     10106794.28
      2793861.01     10106523.47
#Sta/Elev= 30
  4769.4 1845.17  4826.1 1843.21  4866.1 1840.94  4876.1 1841.04  4896.1 1839.28
  4966.2 1836.08  4986.2 1834.65  4988.2 1833.83  4991.0 1833.33  4994.2 1833.83
  5006.2 1834.19  5016.2 1836.37  5026.2 1837.77  5093.7 1836.10  5126.2 1836.96
  5147.9 1836.96  5207.1 1840.07  5212.9 1839.88  5228.8 1840.73  5250.4 1840.58
  5288.0 1843.07  5293.8 1842.63  5309.7 1843.57  5315.4 1843.33  5331.3 1843.85
  5347.2 1845.23  5353.0 1845.15  5368.9 1847.08  5383.7 1847.21  5407.0 1848.36
#Mann=3,-1,0
  4769.4     0.1       0  4988.2    0.07       0  4994.2     0.1       0
Bank Sta=4988.2,4994.2
Exp/Cntr=0.3,0.1

Type RM Length L Ch R = 1,5578,363,363,363
BEGIN DESCRIPTION:
Mapping XS 921dace2
END DESCRIPTION:
XS GIS Cut Line= 3
      2793582.53     10107080.31      2793874.17     10106849.43
      2793917.58     10106490.01
#Sta/Elev= 30
  4719.3 1839.61  4735.6 1838.98  4756.4 1838.83  4785.3 1837.69  4820.5 1837.14
  4905.4 1833.20  4913.5 1831.79  4919.9 1831.89  4927.9 1830.36  4934.3 1830.65
  4942.4 1829.07  4948.7 1830.61  4963.2 1828.51  4969.5 1829.81  4977.6 1829.02
  5003.5 1827.88  5006.2 1827.38  5009.5 1827.88  5012.8 1829.00  5027.3 1829.13
  5033.7 1830.00  5041.7 1829.78  5076.9 1833.49  5090.8 1834.20  5127.2 1835.07
  5238.0 1839.22  5358.9 1844.63  5429.7 1849.09  5448.9 1850.59  5453.3 1850.59
#Mann=4,-1,0
  4719.3     0.1       0  5003.5    0.07       0  5009.5     0.1       0
  5429.7    0.16       0
Bank Sta=5003.5,5009.5
Exp/Cntr=0.3,0.1

Type RM Length L Ch R = 1,5215,52,52,52
BEGIN DESCRIPTION:
UNT066 IN NNOGR 11.0
END DESCRIPTION:
XS GIS Cut Line= 3
      2793823.81     10107194.93      2794146.74     10106896.30
      2794207.51     10106642.83
#Sta/Elev= 30
  4726.7 1831.74  4780.4 1830.97  4837.1 1829.33  4886.4 1829.16  4900.6 1828.19
  4907.9 1826.39  4957.3 1822.88  4971.4 1823.45  4978.3 1822.26  4985.6 1822.58
  4999.8 1821.80  5039.3 1821.64  5042.1 1821.14  5045.3 1821.64  5070.7 1823.03
  5091.6 1826.54  5113.2 1828.43  5120.0 1829.78  5127.4 1829.84  5134.2 1831.22
  5148.3 1832.35  5210.3 1833.66  5230.9 1835.12  5251.5 1834.06  5313.2 1838.11
  5333.7 1838.22  5368.3 1840.18  5374.9 1841.30  5395.4 1841.29  5427.2 1843.45
#Mann=3,-1,0
  4726.7     0.1       0  5039.3    0.07       0  5045.3     0.1       0
Bank Sta=5039.3,5045.3
Exp/Cntr=0.3,0.1

Type RM Length L Ch R = 1,5163,41,41,41
BEGIN DESCRIPTION:
Mapping XS cd95e6a3
END DESCRIPTION:
XS GIS Cut Line= 4
      2793809.97     10107252.18      2794007.85     10107095.96
      2794176.26     10106937.97      2794253.92     10106672.21
#Sta/Elev= 30
  4677.6 1833.03  4682.6 1831.97  4886.4 1827.21  4889.2 1826.71  4892.4 1827.21
  4917.8 1830.81  4953.0 1831.95  4995.5 1832.26  5002.4 1831.22  5009.7 1832.21
  5016.5 1830.78  5023.8 1832.24  5030.7 1830.64  5038.0 1831.95  5044.8 1830.91
  5052.2 1831.88  5059.0 1830.37  5066.3 1831.71  5073.2 1830.30  5080.5 1831.46
  5087.3 1830.04  5101.5 1830.20  5108.8 1831.53  5158.2 1830.68  5260.8 1835.54
  5279.6 1834.93  5342.1 1838.93  5361.2 1838.56  5399.8 1841.54  5437.5 1842.66
#Mann=3,-1,0
  4677.6     0.1       0  4886.4    0.07       0  4892.4     0.1       0
Bank Sta=4886.4,4892.4
Exp/Cntr=0.3,0.1

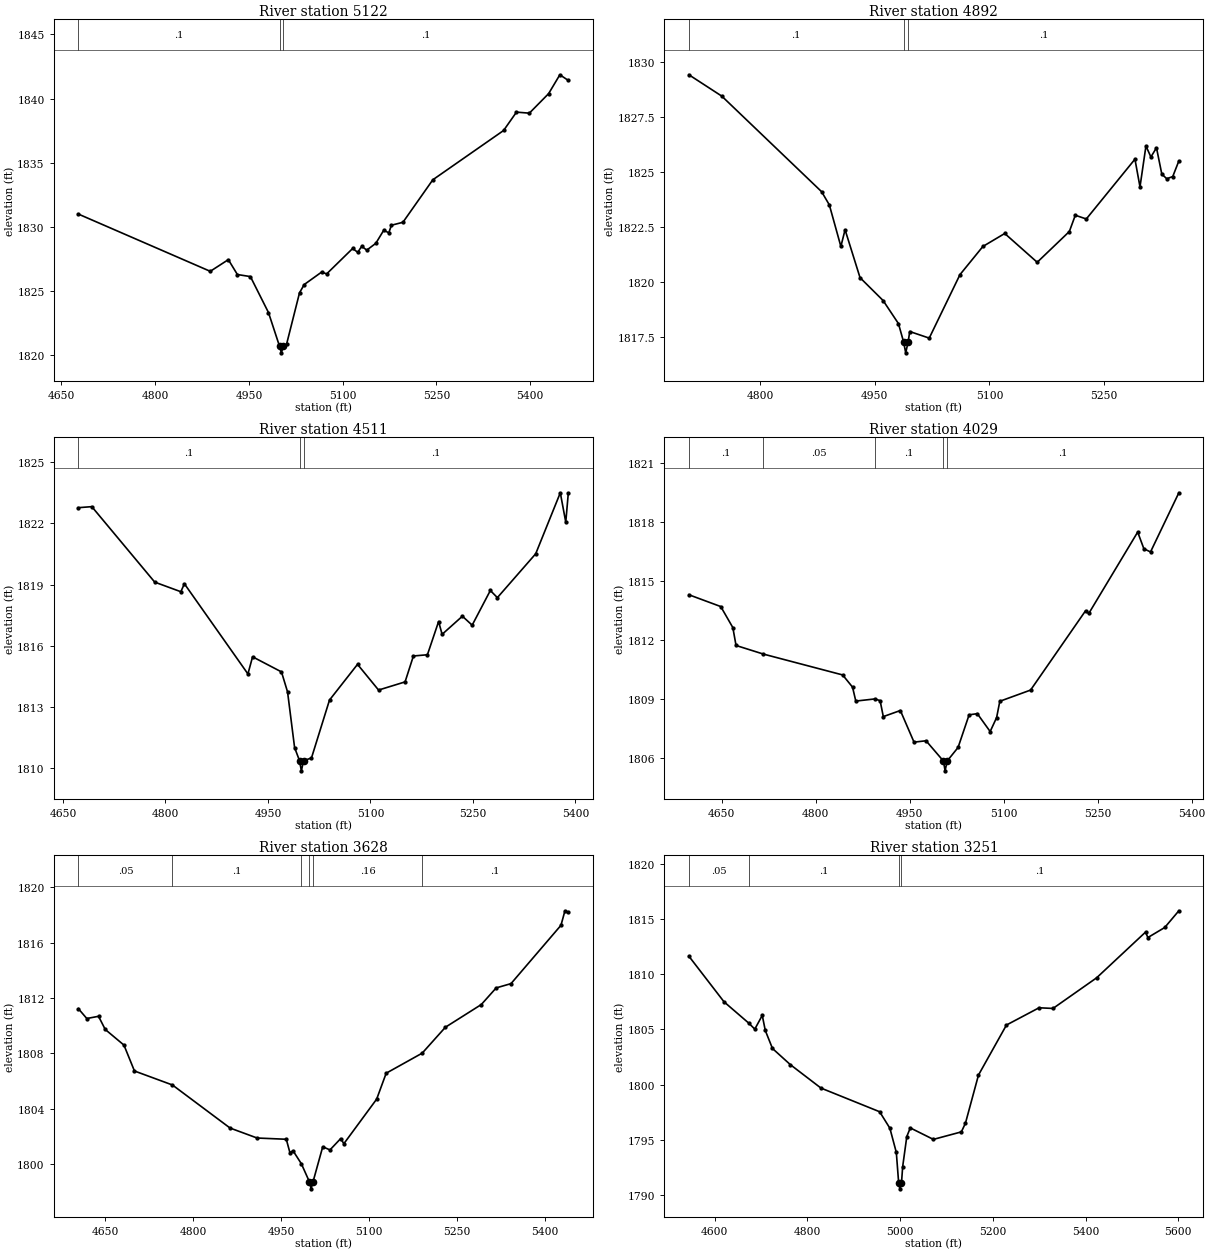
Type RM Length L Ch R = 1,5122,230,230,230
BEGIN DESCRIPTION:
Mapping XS ae60725d
END DESCRIPTION:
XS GIS Cut Line= 3
      2793834.26     10107276.50      2794230.08     10106965.75
      2794296.06     10106693.15
#Sta/Elev= 30
  4677.2 1831.01  4888.2 1826.55  4917.1 1827.46  4931.6 1826.30  4952.4 1826.14
  4981.3 1823.34  4999.1 1820.70  5001.9 1820.20  5005.1 1820.70  5010.2 1820.86
  5031.0 1824.88  5038.5 1825.52  5066.3 1826.49  5074.4 1826.35  5116.0 1828.33
  5124.1 1828.03  5130.5 1828.50  5138.5 1828.20  5153.0 1828.73  5165.7 1829.75
  5173.8 1829.55  5178.0 1830.14  5196.4 1830.37  5244.2 1833.68  5357.4 1837.52
  5378.0 1838.95  5398.6 1838.87  5429.4 1840.39  5447.4 1841.86  5460.9 1841.42
#Mann=3,-1,0
  4677.2     0.1       0  4999.1    0.07       0  5005.1     0.1       0
Bank Sta=4999.1,5005.1
Exp/Cntr=0.3,0.1

Type RM Length L Ch R = 1,4892,381,381,381
BEGIN DESCRIPTION:
UNT066 IN NNOGR 10.0
END DESCRIPTION:
XS GIS Cut Line= 3
      2793895.76     10107301.22      2794263.80     10107259.55
      2794437.43     10107051.20
#Sta/Elev= 30
  4706.5 1829.41  4749.5 1828.44  4880.3 1824.09  4890.4 1823.49  4905.5 1821.60
  4911.0 1822.36  4930.6 1820.18  4960.8 1819.14  4980.9 1818.09  4987.6 1817.26
  4990.4 1816.76  4993.6 1817.26  4995.7 1817.73  5021.2 1817.43  5061.5 1820.32
  5091.5 1821.60  5120.1 1822.19  5162.6 1820.88  5204.7 1822.28  5212.5 1823.02
  5226.9 1822.85  5290.6 1825.57  5297.2 1824.31  5305.0 1826.17  5311.5 1825.67
  5318.8 1826.09  5325.8 1824.89  5332.3 1824.68  5340.1 1824.78  5348.1 1825.49
#Mann=3,-1,0
  4706.5     0.1       0  4987.6    0.07       0  4993.6     0.1       0
Bank Sta=4987.6,4993.6
Exp/Cntr=0.3,0.1

Type RM Length L Ch R = 1,4511,482,482,482
BEGIN DESCRIPTION:
UNT066 IN NNOGR 9.0
END DESCRIPTION:
XS GIS Cut Line= 2
      2794361.01     10107842.93      2794513.63     10107142.26
#Sta/Elev= 30
  4672.5 1822.77  4692.2 1822.82  4784.3 1819.12  4822.5 1818.65  4827.7 1819.04
  4920.7 1814.62  4927.5 1815.46  4969.8 1814.72  4978.7 1813.74  4989.0 1811.01
  4996.2 1810.37  4998.9 1809.87  5002.2 1810.37  5013.7 1810.50  5040.1 1813.34
  5081.1 1815.09  5111.9 1813.83  5150.7 1814.23  5162.9 1815.50  5183.4 1815.56
  5199.8 1817.19  5204.9 1816.56  5234.6 1817.45  5248.9 1817.01  5275.5 1818.71
  5285.8 1818.36  5341.9 1820.51  5377.9 1823.50  5385.9 1822.06  5389.6 1823.48
#Mann=3,-1,0
  4672.5     0.1       0  4996.2    0.07       0  5002.2     0.1       0
Bank Sta=4996.2,5002.2
Exp/Cntr=0.3,0.1

Type RM Length L Ch R = 1,4029,401,401,401
BEGIN DESCRIPTION:
UNT066 IN NNOGR 8.0
END DESCRIPTION:
XS GIS Cut Line= 2
      2794777.70     10108023.40      2794944.35     10107259.57
#Sta/Elev= 30
  4597.7 1814.31  4648.5 1813.71  4667.8 1812.64  4672.9 1811.73  4716.7 1811.29
  4843.0 1810.23  4858.8 1809.61  4864.0 1808.90  4894.7 1809.01  4902.8 1808.92
  4907.9 1808.11  4935.1 1808.42  4956.9 1806.81  4976.1 1806.88  5003.8 1805.85
  5006.5 1805.35  5009.8 1805.85  5027.2 1806.54  5044.8 1808.20  5057.9 1808.26
  5078.4 1807.35  5088.7 1808.06  5093.8 1808.89  5142.9 1809.46  5230.7 1813.50
  5235.8 1813.36  5313.8 1817.50  5323.7 1816.65  5334.3 1816.49  5379.5 1819.50
#Mann=5,-1,0
  4597.7     0.1       0  4716.7    0.05       0  4894.7     0.1       0
  5003.8    0.07       0  5009.8     0.1       0
Bank Sta=5003.8,5009.8
Exp/Cntr=0.3,0.1

Type RM Length L Ch R = 1,3628,377,377,377
BEGIN DESCRIPTION:
UNT066 IN NNOGR 7.0
END DESCRIPTION:
XS GIS Cut Line= 2
      2795090.20     10108106.76      2795374.92     10107322.02
#Sta/Elev= 30
  4604.8 1811.23  4619.2 1810.52  4639.2 1810.68  4650.6 1809.73  4682.5 1808.60
  4700.4 1806.73  4765.1 1805.72  4863.3 1802.61  4909.4 1801.89  4959.1 1801.80
  4965.3 1800.83  4970.6 1800.97  4984.8 1800.03  4998.6 1798.72  5001.4 1798.22
  5004.6 1798.72  5021.2 1801.26  5033.5 1801.03  5051.8 1801.85  5057.2 1801.48
  5113.1 1804.70  5129.3 1806.57  5190.7 1808.02  5230.2 1809.89  5291.4 1811.53
  5316.7 1812.73  5342.0 1813.04  5427.1 1817.25  5433.9 1818.30  5439.6 1818.19
#Mann=6,-1,0
  4604.8    0.05       0  4765.1     0.1       0  4984.8    0.16       0
  4998.6    0.07       0  5004.6    0.16       0  5190.7     0.1       0
Bank Sta=4998.6,5004.6
Exp/Cntr=0.3,0.1

Type RM Length L Ch R = 1,3251,613,613,613
BEGIN DESCRIPTION:
UNT066 IN NNOGR 6.0
END DESCRIPTION:
XS GIS Cut Line= 3
      2795340.21     10108259.52      2795617.97     10107731.78
      2795659.63     10107273.44
#Sta/Elev= 30
  4544.7 1811.62  4620.4 1807.50  4673.3 1805.59  4686.8 1805.03  4702.9 1806.27
  4709.4 1804.91  4724.9 1803.28  4763.4 1801.82  4829.5 1799.70  4956.0 1797.56
  4978.1 1796.07  4992.0 1793.88  4997.1 1791.09  4999.8 1790.59  5003.1 1791.09
  5005.7 1792.60  5014.6 1795.32  5022.1 1796.10  5071.9 1795.06  5132.3 1795.74
  5141.1 1796.53  5169.2 1800.88  5229.5 1805.40  5299.8 1806.96  5329.9 1806.90
  5424.0 1809.67  5529.4 1813.80  5534.5 1813.31  5570.9 1814.22  5601.3 1815.73
#Mann=4,-1,0
  4544.7    0.05       0  4673.3     0.1       0  4997.1    0.07       0
  5003.1     0.1       0
Bank Sta=4997.1,5003.1
Exp/Cntr=0.3,0.1

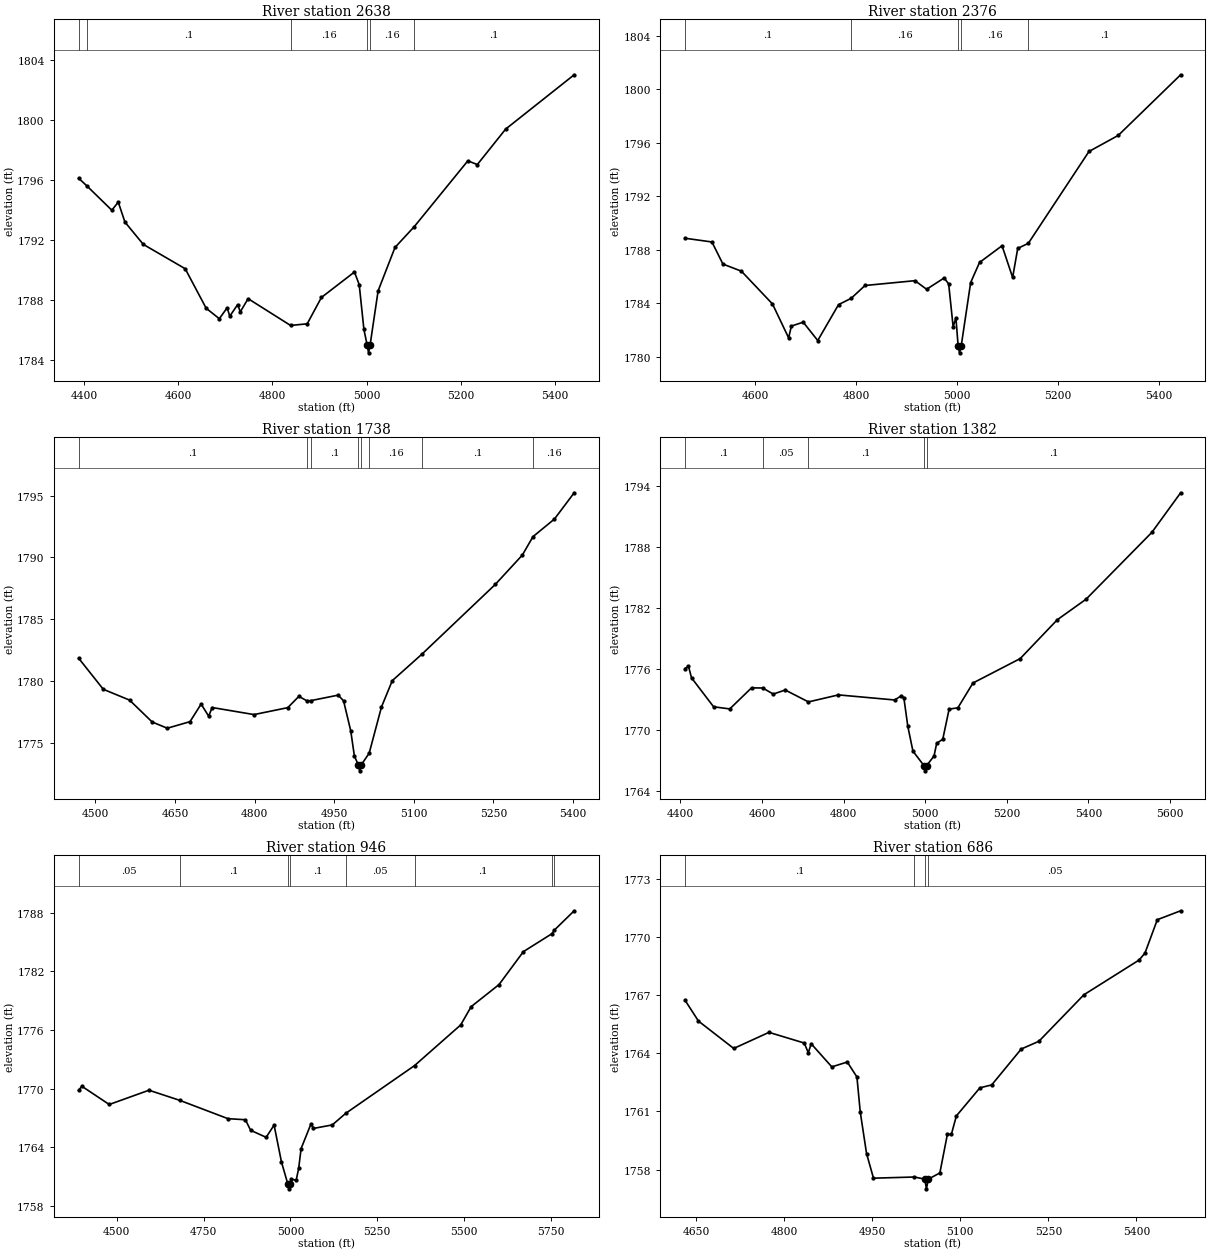
Type RM Length L Ch R = 1,2638,262,262,262
BEGIN DESCRIPTION:
UNT066 IN NNOGR 5.0
END DESCRIPTION:
XS GIS Cut Line= 3
      2795840.18     10108238.73      2796048.52     10107829.00
      2796090.19     10107238.72
#Sta/Elev= 30
  4388.7 1796.13  4407.0 1795.59  4459.1 1793.99  4472.8 1794.53  4486.9 1793.20
  4525.8 1791.71  4614.8 1790.08  4659.3 1787.44  4687.2 1786.74  4703.8 1787.47
  4709.4 1786.91  4726.1 1787.68  4731.7 1787.20  4748.3 1788.08  4838.4 1786.29
  4873.7 1786.40  4903.8 1788.16  4973.9 1789.86  4984.0 1789.02  4994.0 1786.02
  5001.0 1784.96  5003.8 1784.46  5007.0 1784.96  5024.1 1788.60  5059.9 1791.50
  5101.0 1792.90  5214.5 1797.29  5234.6 1797.04  5294.7 1799.41  5440.1 1803.04
#Mann=6,-1,0
  4388.7    0.05       0  4407.0     0.1       0  4838.4    0.16       0
  5001.0    0.07       0  5007.0    0.16       0  5101.0     0.1       0
Bank Sta=5001,5007
Exp/Cntr=0.3,0.1

Type RM Length L Ch R = 1,2376,638,638,638
BEGIN DESCRIPTION:
UNT066 IN NNOGR 4.0
END DESCRIPTION:
XS GIS Cut Line= 3
      2796089.44     10108132.44      2796329.04     10107583.80
      2796379.38     10107203.60
#Sta/Elev= 30
  4460.5 1788.86  4513.7 1788.58  4535.5 1786.93  4572.1 1786.40  4633.7 1783.95
  4665.7 1781.42  4671.2 1782.30  4694.6 1782.59  4723.4 1781.22  4764.6 1783.90
  4789.6 1784.37  4817.1 1785.33  4916.1 1785.69  4939.2 1785.05  4973.9 1785.89
  4982.9 1785.45  4991.8 1782.24  4997.3 1782.92  5001.7 1780.80  5004.4 1780.30
  5007.7 1780.80  5026.5 1785.55  5044.1 1787.05  5088.7 1788.30  5109.7 1785.93
  5119.8 1788.10  5140.8 1788.48  5261.0 1795.34  5319.0 1796.54  5442.7 1801.07
#Mann=5,-1,0
  4460.5     0.1       0  4789.6    0.16       0  5001.7    0.07       0
  5007.7    0.16       0  5140.8     0.1       0
Bank Sta=5001.7,5007.7
Exp/Cntr=0.3,0.1

Type RM Length L Ch R = 1,1738,356,356,356
BEGIN DESCRIPTION:
UNT066 IN NNOGR 3.0
END DESCRIPTION:
XS GIS Cut Line= 4
      2796358.54     10108099.44      2796716.19     10107788.67
      2796747.44     10107632.42      2796686.83     10107338.04
#Sta/Elev= 30
  4468.5 1781.87  4515.0 1779.36  4564.4 1778.49  4607.1 1776.72  4635.6 1776.22
  4678.4 1776.75  4699.3 1778.17  4713.5 1777.19  4720.1 1777.89  4799.0 1777.32
  4862.6 1777.88  4883.5 1778.79  4898.3 1778.44  4905.4 1778.44  4957.5 1778.89
  4967.7 1778.43  4981.2 1776.01  4988.1 1773.97  4995.3 1773.28  4998.1 1772.78
  5001.3 1773.28  5016.0 1774.21  5039.1 1777.93  5059.5 1780.06  5115.7 1782.21
  5253.5 1787.82  5304.5 1790.19  5324.6 1791.68  5365.0 1793.10  5402.2 1795.22
#Mann=8,-1,0
  4468.5     0.1       0  4898.3    0.05       0  4905.4     0.1       0
  4995.3    0.07       0  5001.3     0.1       0  5016.0    0.16       0
  5115.7     0.1       0  5324.6    0.16       0
Bank Sta=4995.3,5001.3
Exp/Cntr=0.3,0.1

Type RM Length L Ch R = 1,1382,436,436,436
BEGIN DESCRIPTION:
Mapping XS 22c79dce
END DESCRIPTION:
XS GIS Cut Line= 4
      2796533.92     10108101.16      2797021.74     10107899.78
      2797155.42     10107675.82      2797101.60     10107253.92
#Sta/Elev= 30
  4411.9 1776.07  4420.2 1776.30  4427.6 1775.16  4481.7 1772.31  4521.3 1772.10
  4574.6 1774.17  4602.0 1774.16  4627.8 1773.56  4657.2 1773.96  4714.0 1772.79
  4787.6 1773.48  4925.3 1772.98  4941.9 1773.40  4947.8 1773.19  4957.5 1770.38
  4970.0 1767.95  4997.3 1766.51  5000.1 1766.01  5003.3 1766.51  5021.7 1767.47
  5028.2 1768.72  5043.1 1769.12  5058.7 1772.08  5080.1 1772.21  5117.1 1774.65
  5232.8 1777.05  5323.6 1780.87  5394.1 1782.89  5555.4 1789.47  5625.8 1793.36
#Mann=5,-1,0
  4411.9     0.1       0  4602.0    0.05       0  4714.0     0.1       0
  4997.3    0.07       0  5003.3     0.1       0
Bank Sta=4997.3,5003.3
Exp/Cntr=0.3,0.1

Type RM Length L Ch R = 1,946,260,260,260
BEGIN DESCRIPTION:
UNT066 IN NNOGR 2.0
END DESCRIPTION:
XS GIS Cut Line= 4
      2796770.73     10108169.28      2797312.41     10108113.72
      2797444.35     10107981.78      2797388.85     10107288.02
#Sta/Elev= 30
  4390.1 1769.83  4399.2 1770.26  4478.3 1768.39  4592.7 1769.85  4680.9 1768.82
  4820.1 1766.94  4870.3 1766.83  4885.5 1765.75  4930.1 1765.03  4953.0 1766.28
  4974.3 1762.50  4992.5 1760.26  4995.2 1759.76  4998.5 1760.26  5002.5 1760.74
  5016.7 1760.65  5023.8 1761.86  5030.8 1763.88  5059.1 1766.39  5066.2 1765.94
  5120.6 1766.30  5159.5 1767.49  5357.5 1772.37  5490.4 1776.53  5520.5 1778.40
  5600.8 1780.66  5671.0 1784.03  5753.4 1785.87  5759.5 1786.21  5817.2 1788.21
#Mann=8,-1,0
  4390.1    0.05       0  4680.9     0.1       0  4992.5    0.07       0
  4998.5     0.1       0  5159.5    0.05       0  5357.5     0.1       0
  5753.4    0.05       0  5759.5     0.1       0
Bank Sta=4992.5,4998.5
Exp/Cntr=0.3,0.1

Type RM Length L Ch R = 1,686,66,66,66
BEGIN DESCRIPTION:
Mapping XS 2993f423
END DESCRIPTION:
XS GIS Cut Line= 4
      2797245.71     10108144.57      2797497.44     10108137.62
      2797672.79     10108045.61      2797639.80     10107653.25
#Sta/Elev= 30
  4631.6 1766.73  4654.4 1765.66  4714.4 1764.25  4774.4 1765.08  4834.4 1764.53
  4841.3 1764.03  4846.3 1764.49  4881.4 1763.30  4907.7 1763.55  4924.1 1762.78
  4929.8 1760.97  4940.5 1758.83  4952.3 1757.56  5022.0 1757.62  5039.7 1757.51
  5042.4 1757.01  5045.7 1757.51  5065.3 1757.83  5078.1 1759.82  5084.9 1759.82
  5093.4 1760.77  5133.5 1762.22  5153.6 1762.37  5203.8 1764.22  5233.9 1764.62
  5310.6 1767.02  5404.5 1768.81  5414.5 1769.17  5435.5 1770.89  5475.2 1771.35
#Mann=4,-1,0
  4631.6     0.1       0  5022.0    0.05       0  5039.7    0.07       0
  5045.7    0.05       0
Bank Sta=5039.7,5045.7
Exp/Cntr=0.3,0.1

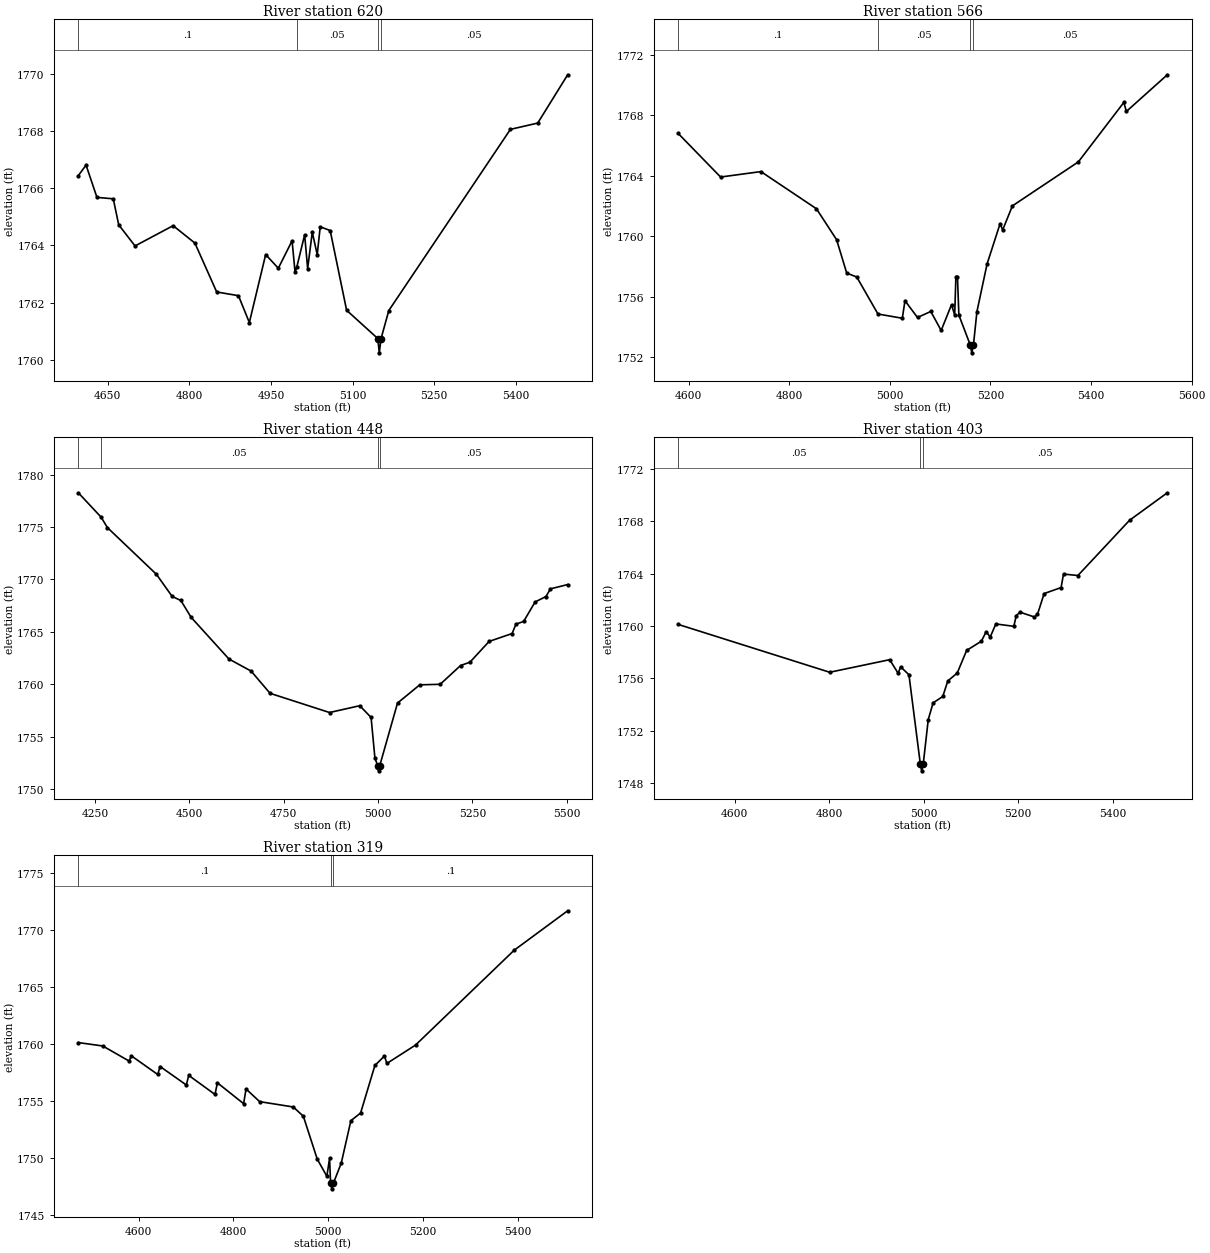
Type RM Length L Ch R = 1,620,54,54,54
BEGIN DESCRIPTION:
Mapping XS ee37a1b9
END DESCRIPTION:
XS GIS Cut Line= 5
      2797234.22     10108150.40      2797601.60     10108149.78
      2797677.99     10108115.05      2797686.67     10108036.93
      2797658.90     10107668.87
#Sta/Elev= 30
  4596.0 1766.44  4610.2 1766.81  4630.2 1765.68  4660.2 1765.63  4670.2 1764.72
  4700.2 1763.98  4770.2 1764.69  4810.2 1764.08  4850.2 1762.37  4890.2 1762.24
  4910.2 1761.30  4940.2 1763.68  4963.4 1763.20  4988.7 1764.16  4994.2 1763.06
  4997.6 1763.26  5011.8 1764.37  5017.3 1763.19  5025.8 1764.46  5034.9 1763.68
  5040.4 1764.65  5058.7 1764.52  5088.9 1761.73  5146.2 1760.74  5148.9 1760.24
  5152.2 1760.74  5166.4 1761.72  5389.8 1768.06  5440.0 1768.28  5495.0 1769.97
#Mann=4,-1,0
  4596.0     0.1       0  4997.6    0.05       0  5146.2    0.04       0
  5152.2    0.05       0
Bank Sta=5146.2,5152.2
Exp/Cntr=0.3,0.1

Type RM Length L Ch R = 1,566,118,118,118
BEGIN DESCRIPTION:
Mapping XS c337da80
END DESCRIPTION:
XS GIS Cut Line= 5
      2797244.01     10108154.99      2797646.74     10108184.50
      2797730.08     10108153.25      2797743.97     10108094.22
      2797693.69     10107678.10
#Sta/Elev= 30
  4579.0 1766.81  4663.7 1763.91  4743.9 1764.27  4854.2 1761.81  4894.3 1759.76
  4914.4 1757.55  4934.4 1757.29  4976.5 1754.84  5024.9 1754.56  5030.2 1755.72
  5055.1 1754.61  5081.5 1755.01  5102.1 1753.75  5122.7 1755.46  5129.0 1754.77
  5131.4 1757.32  5134.5 1757.32  5137.3 1754.77  5160.2 1752.77  5162.9 1752.27
  5166.2 1752.77  5173.2 1755.00  5193.4 1758.16  5219.3 1760.83  5224.3 1760.40
  5243.7 1762.00  5374.7 1764.91  5465.2 1768.85  5470.2 1768.25  5551.6 1770.68
#Mann=4,-1,0
  4579.0     0.1       0  4976.5    0.05       0  5160.2    0.04       0
  5166.2    0.05       0
Bank Sta=5160.2,5166.2
Exp/Cntr=0.3,0.1

Type RM Length L Ch R = 1,448,45,45,45
BEGIN DESCRIPTION:
Mapping XS 91dae95c
END DESCRIPTION:
XS GIS Cut Line= 4
      2797257.88     10108741.77      2797764.80     10108372.00
      2797771.74     10108090.75      2797704.03     10107708.79
#Sta/Elev= 30
  4205.7 1778.26  4266.0 1775.94  4282.8 1774.94  4412.6 1770.49  4454.3 1768.38
  4477.4 1767.99  4504.5 1766.39  4604.9 1762.41  4663.6 1761.26  4713.8 1759.14
  4871.4 1757.31  4951.5 1757.96  4981.5 1756.84  4991.5 1753.02  4998.5 1752.25
  5001.2 1751.75  5004.5 1752.25  5051.5 1758.21  5110.5 1759.95  5164.6 1760.00
  5218.6 1761.79  5243.5 1762.11  5294.3 1764.09  5355.2 1764.84  5365.4 1765.74
  5385.7 1765.99  5416.1 1767.85  5444.9 1768.37  5456.8 1769.10  5502.4 1769.51
#Mann=4,-1,0
  4205.7     0.1       0  4266.0    0.05       0  4998.5    0.04       0
  5004.5    0.05       0
Bank Sta=4998.5,5004.5
Exp/Cntr=0.3,0.1

Type RM Length L Ch R = 1,403,84,84,84
BEGIN DESCRIPTION:
Mapping XS 89bfd739
END DESCRIPTION:
XS GIS Cut Line= 2
      2797919.31     10108712.25      2797707.54     10107698.53
#Sta/Elev= 30
  4480.2 1760.12  4801.3 1756.46  4928.2 1757.42  4946.2 1756.38  4951.3 1756.88
  4969.0 1756.27  4993.2 1749.43  4995.9 1748.93  4999.2 1749.43  5009.9 1752.85
  5020.1 1754.12  5040.6 1754.61  5051.3 1755.80  5071.2 1756.40  5091.1 1758.13
  5122.3 1758.83  5132.5 1759.56  5141.0 1759.15  5152.9 1760.15  5191.0 1759.97
  5196.1 1760.79  5204.0 1761.05  5234.7 1760.68  5241.0 1760.88  5255.1 1762.47
  5291.0 1762.93  5296.1 1763.96  5326.6 1763.85  5435.9 1768.07  5515.8 1770.17
#Mann=3,-1,0
  4480.2    0.05       0  4993.2    0.04       0  4999.2    0.05       0
Bank Sta=4993.2,4999.2
Exp/Cntr=0.3,0.1

Type RM Length L Ch R = 1,319,0,0,0
BEGIN DESCRIPTION:
UNT066 IN NNOGR 1.0
END DESCRIPTION:
XS GIS Cut Line= 2
      2797981.81     10108731.33      2797809.95     10107712.32
#Sta/Elev= 30
  4472.4 1760.10  4524.1 1759.80  4579.6 1758.48  4584.6 1758.93  4640.1 1757.30
  4645.1 1758.00  4700.5 1756.38  4705.6 1757.22  4761.0 1755.55  4766.1 1756.57
  4821.5 1754.74  4826.6 1756.03  4855.3 1754.92  4926.3 1754.45  4947.6 1753.64
  4977.0 1749.87  4997.3 1748.37  5003.0 1749.95  5005.1 1747.77  5007.8 1747.27
  5011.1 1747.77  5027.7 1749.53  5048.0 1753.25  5068.5 1753.92  5098.7 1758.09
  5118.9 1758.92  5124.0 1758.27  5184.5 1759.88  5392.8 1768.20  5505.8 1771.66
#Mann=3,-1,0
  4472.4     0.1       0  5005.1    0.07       0  5011.1     0.1       0
Bank Sta=5005.1,5011.1
Exp/Cntr=0.3,0.1

Chan Stop Cuts=-1