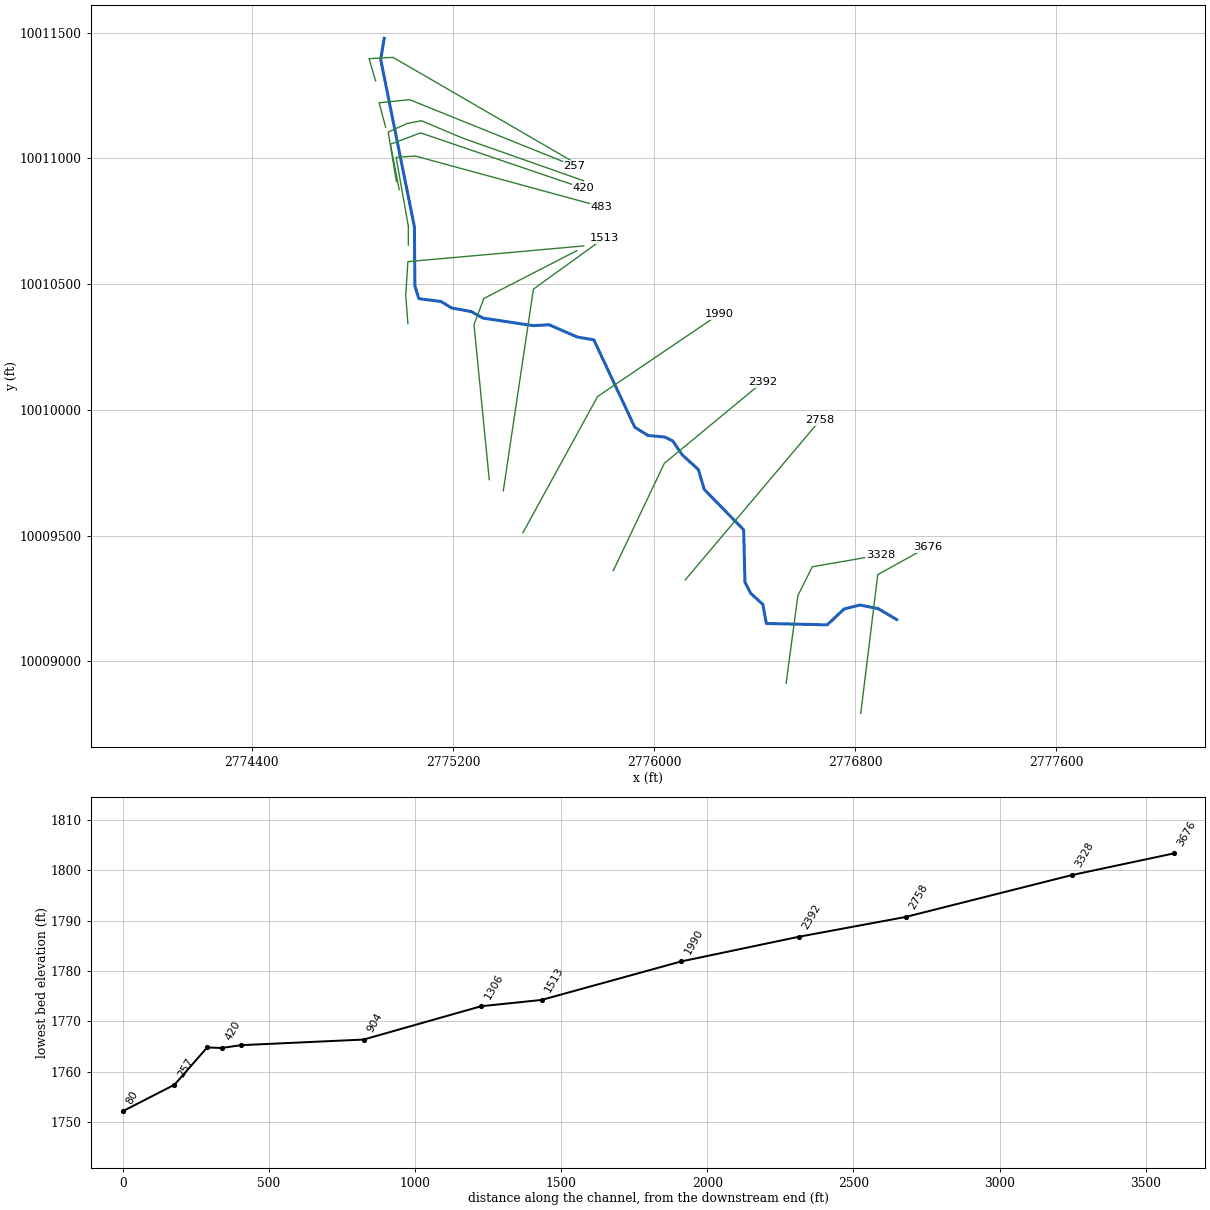
--- UNT066 IN SNOGR.prj (project) ---

Proj Title=UNT066 IN SNOGR Base Level Engineering
Current Plan=p01
Default Exp/Contr=0.3,0.1
English Units
Geom File=g01
Flow File=f01
Plan File=p01
Y Axis Title=Elevation
X Axis Title(PF)=Main Channel Distance
X Axis Title(XS)=Station
BEGIN DESCRIPTION:
UNT066 IN SNOGR
END DESCRIPTION:
DSS Export Rating Curves= 0
DSS Export Rating Curve Sorted= 0
DSS Export Volume Flow Curves= 0
DXF OffsetX= 0
DXF OffsetY= 0
DXF ScaleX= 1
DXF ScaleY= 10

--- UNT066 IN SNOGR.p01 (plan) ---

Plan Title=Multiple Run
Short Identifier=Multiple
Geom File=g01
Flow File=f01
Subcritical Flow
K Sum by GR= 0
Std Step Tol= 0.01
Critical Tol= 0.01
Num of Std Step Trials= 20
Max Error Tol= 0.3
Flow Tol Ratio= 0.001
Split Flow NTrial= 30
Split Flow Tol= 0.02
Split Flow Ratio= 0.02
Log Output Level= 0
Friction Slope Method= 1
Unsteady Friction Slope Method= 2
Unsteady Bridges Friction Slope Method= 1
Parabolic Critical Depth
Global Vel Dist=  1 , 1 , 1
Global Log Level= 0
CheckData=True
Encroach Param= -1, 0, 0, 0
BEGIN DESCRIPTION:
Multiple Run
END DESCRIPTION:

--- UNT066 IN SNOGR.f01 (steady flow) ---

Flow Title=Multiple
Number of Profiles=7
Profile Names=10-year,25-year,50-year,1pct_min,100-year,1pct_plu,500-year
River Rch & RM= UNT066 IN SNOGR,Reach-1,3676
     623     889    1117    1029    1392    1883    2169
Boundary for River Rch & Prof#=UNT066 IN SNOGR,Reach-1,1
Up Type=0
Dn Type=3
Dn Slope=0.005
Boundary for River Rch & Prof#=UNT066 IN SNOGR,Reach-1,2
Up Type=0
Dn Type=3
Dn Slope=0.005
Boundary for River Rch & Prof#=UNT066 IN SNOGR,Reach-1,3
Up Type=0
Dn Type=3
Dn Slope=0.005
Boundary for River Rch & Prof#=UNT066 IN SNOGR,Reach-1,4
Up Type=0
Dn Type=3
Dn Slope=0.005
Boundary for River Rch & Prof#=UNT066 IN SNOGR,Reach-1,5
Up Type=0
Dn Type=3
Dn Slope=0.005
Boundary for River Rch & Prof#=UNT066 IN SNOGR,Reach-1,6
Up Type=0
Dn Type=3
Dn Slope=0.005
Boundary for River Rch & Prof#=UNT066 IN SNOGR,Reach-1,7
Up Type=0
Dn Type=3
Dn Slope=0.005

--- UNT066 IN SNOGR.g01 (geometry) ---

Geom Title=Existing Conditions
Program Version=4.10

River Reach=UNT066 IN SNOGR ,Reach-1
Reach XY= 30
      2776965.15     10009165.76      2776891.33     10009209.36
      2776818.55      10009223.7      2776756.06     10009208.18
       2776688.4     10009144.84      2776446.47      10009150.4
      2776432.72     10009225.89      2776383.44     10009271.32
      2776361.42     10009314.86      2776356.26     10009522.79
      2776199.53      10009683.6      2776176.03     10009762.79
      2776112.28     10009820.66      2776074.46     10009876.18
      2776042.85     10009891.95      2775975.52     10009898.17
      2775923.22     10009930.92      2775760.27     10010278.71
      2775695.51     10010289.46      2775581.78      10010338.7
      2775519.06     10010334.97      2775319.11     10010365.27
      2775272.67     10010390.89      2775194.21     10010405.54
      2775152.58      10010431.1      2775064.21     10010442.41
      2775048.44     10010492.77      2775046.52     10010728.12
       2774912.3     10011394.72      2774926.47     10011477.97

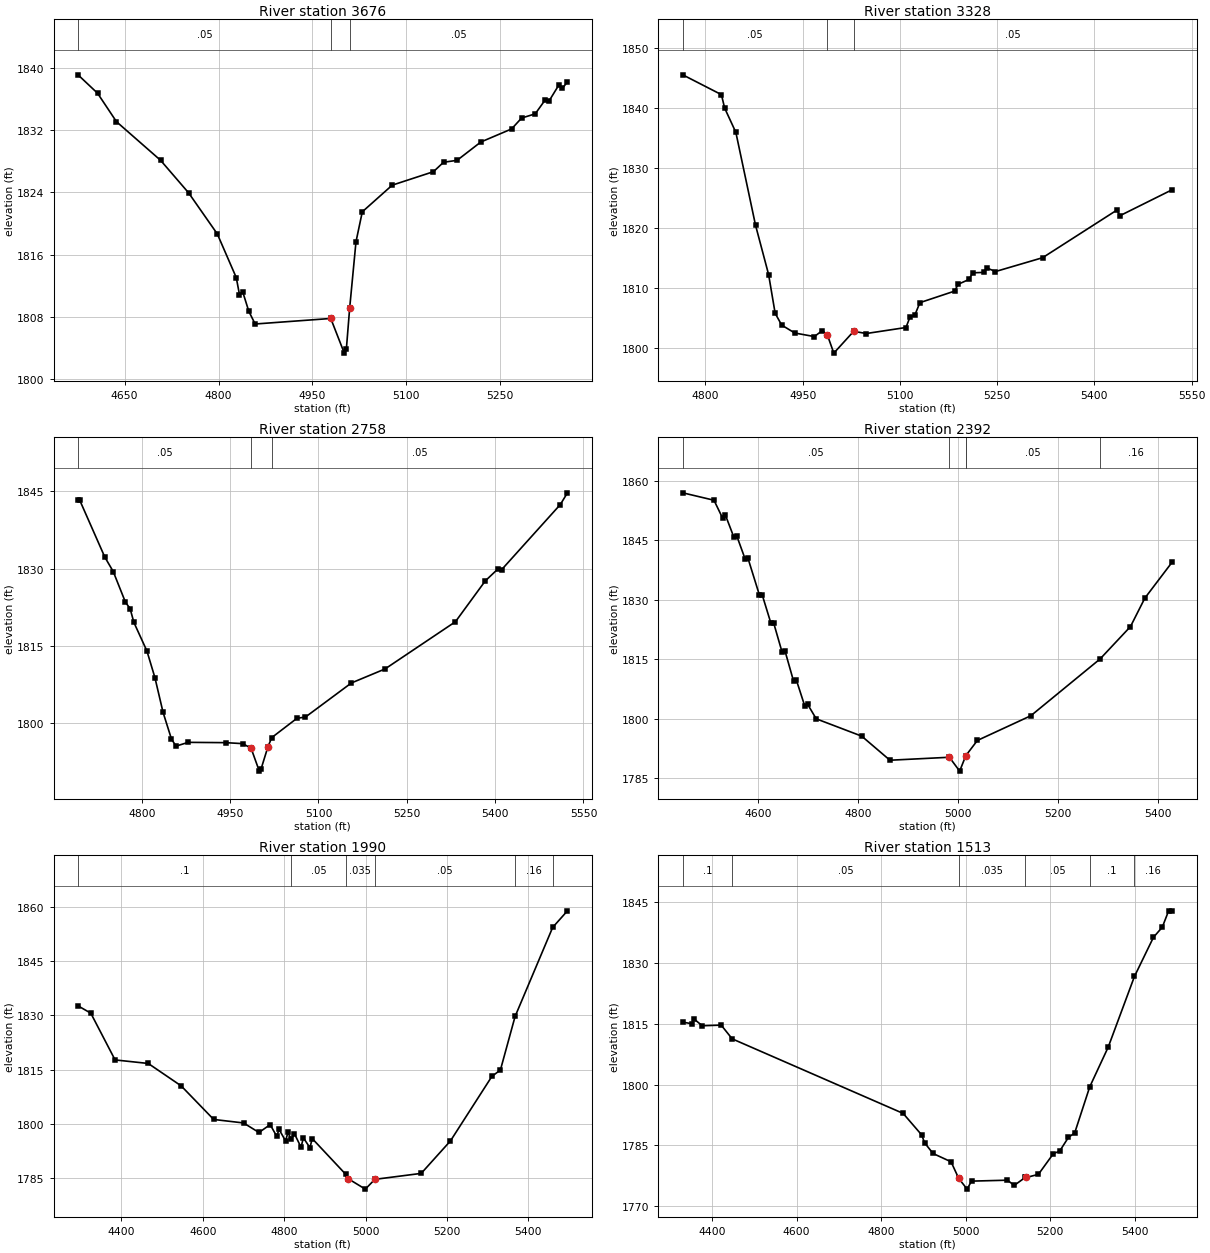
Type RM Length L Ch R = 1 ,3676    ,348,348,348
BEGIN DESCRIPTION:
UNT066 IN SNOGR 7.0
END DESCRIPTION:
XS GIS Cut Line= 3
      2776822.03     10008792.72      2776889.73     10009344.77
      2777087.64     10009454.14
#Sta/Elev= 30
  4575.4 1839.11  4606.6 1836.75  4636.9 1833.09  4707.4 1828.13  4752.1 1823.96
  4798.1 1818.67  4828.3 1813.08  4833.5 1810.89  4838.5 1811.28  4848.4 1808.74
  4858.5 1807.11  4979.4 1807.82    5001 1803.37  5004.3 1803.87  5009.6 1809.15
  5019.7 1817.67  5029.8 1821.52  5077.6 1824.94  5143.5 1826.67  5159.6 1827.88
  5181.3 1828.13  5219.2 1830.48  5268.4 1832.16  5284.4 1833.56  5306.2  1834.1
  5322.3 1835.91    5328 1835.71    5344 1837.81  5349.7 1837.38  5357.7 1838.21
#Mann= 3 , 0 , 0
  4575.4     .05       0  4979.4    .035       0  5009.6     .05       0
Bank Sta=4979.4,5009.6
XS Rating Curve= 0 ,0
Exp/Cntr=0.3,0.1

Type RM Length L Ch R = 1 ,3328    ,570,570,570
BEGIN DESCRIPTION:
UNT066 IN SNOGR 6.0
END DESCRIPTION:
XS GIS Cut Line= 4
      2776525.16     10008912.52      2776572.02     10009261.43
      2776629.32     10009376.02      2776900.13     10009422.89
#Sta/Elev= 30
    4765 1845.45  4824.6 1842.15  4829.6 1839.91  4846.9 1835.86  4877.2 1820.41
  4897.4 1812.18  4907.5 1805.72  4917.6 1803.75  4937.8 1802.43    4968 1801.84
  4980.4 1802.85  4988.2 1802.06    4998 1799.08  5028.6 1802.71  5048.2 1802.35
  5109.3 1803.35  5115.7 1805.14  5122.7 1805.35  5130.8 1807.49  5184.2 1809.41
  5189.8 1810.55  5206.6 1811.36  5212.2 1812.46    5229 1812.53  5234.5 1813.26
  5247.3 1812.67  5320.1 1814.98  5434.5  1822.9  5439.6 1821.99    5520 1826.31
#Mann= 3 , 0 , 0
    4765     .05       0  4988.2    .035       0  5028.6     .05       0
Bank Sta=4988.2,5028.6
XS Rating Curve= 0 ,0
Exp/Cntr=0.3,0.1

Type RM Length L Ch R = 1 ,2758    ,366,366,366
BEGIN DESCRIPTION:
UNT066 IN SNOGR 5.0
END DESCRIPTION:
XS GIS Cut Line= 2
      2776124.12     10009323.95      2776660.32     10009959.06
#Sta/Elev= 30
  4691.6 1843.22  4694.7 1843.22  4737.1 1832.24  4751.4 1829.44  4772.2 1823.48
    4780 1822.27  4786.5 1819.57  4808.6 1814.04  4822.2 1808.87    4836 1802.15
  4850.3 1796.96    4858 1795.59  4878.8 1796.32  4942.6 1796.26  4971.2 1796.07
  4985.5 1795.19  4999.5 1790.74  5002.7 1791.24    5014 1795.41  5020.6 1797.24
  5063.5 1800.99  5077.8 1801.22  5155.8 1807.83    5213 1810.55  5332.6 1819.71
  5383.3 1827.63  5404.1 1829.87  5411.1 1829.81  5510.7 1842.43  5522.8  1844.7
#Mann= 3 ,-1 , 0
  4691.6     .05       0  4985.5    .035       0  5020.6     .05       0
Bank Sta=4985.5,5014
XS Rating Curve= 0 ,0
Exp/Cntr=0.3,0.1

Type RM Length L Ch R = 1 ,2392    ,402,402,402
BEGIN DESCRIPTION:
UNT066 IN SNOGR 4.0
END DESCRIPTION:
XS GIS Cut Line= 3
      2775837.64     10009360.38      2776040.77     10009787.47
      2776430.43     10010109.59
#Sta/Elev= 30
  4449.8 1857.02  4512.2 1855.15  4529.3 1850.68  4534.9 1851.45  4552.1 1845.79
  4557.6  1846.2  4574.8 1840.21  4580.3 1840.46    4603 1831.24  4608.6 1831.28
  4625.7 1824.25  4631.3 1824.29  4648.5 1816.75    4654 1817.21  4671.2 1809.55
  4676.7 1809.86  4693.9 1803.15  4699.4 1803.66  4716.6    1800  4807.5 1795.63
    4864 1789.55  4982.8  1790.3  5003.4  1786.8  5015.6 1790.69  5038.8 1794.54
  5145.6 1800.77  5284.1  1815.1  5344.9 1823.28  5373.6 1830.45  5428.3 1839.55
#Mann= 5 ,-1 , 0
  4449.8     .05       0  4982.8    .035       0  5015.6     .16       0
  5015.6     .05       0  5284.1     .16       0
Bank Sta=4982.8,5015.6
XS Rating Curve= 0 ,0
Exp/Cntr=0.3,0.1

Type RM Length L Ch R = 1 ,1990    ,477,477,477
BEGIN DESCRIPTION:
UNT066 IN SNOGR 3.0
END DESCRIPTION:
XS GIS Cut Line= 3
      2775478.26     10009511.41      2775775.15      10010053.1
      2776259.55     10010381.24
#Sta/Elev= 30
  4293.3 1832.67  4324.7 1830.64  4384.4 1817.69  4465.9 1816.71  4546.8  1810.5
  4626.7  1801.2  4700.1 1800.23    4738 1797.59  4765.5 1799.77  4781.6 1796.54
  4787.3 1798.45  4803.4 1795.25  4809.1  1797.6  4817.3 1795.69  4825.2 1797.24
  4841.4 1793.49  4847.1 1796.12  4863.2 1793.38  4868.9  1795.9    4951 1786.03
    4957  1784.8  4999.3  1781.9  5022.9 1784.61  5136.7 1786.26  5208.6 1795.26
  5310.4 1813.13  5331.4 1814.91  5367.4 1829.72  5459.8  1854.4  5496.1 1858.99
#Mann= 6 ,-1 , 0
  4293.3      .1       0  4817.3     .05       0    4951    .035       0
  5022.9     .05       0  5367.4     .16       0  5459.8      .1       0
Bank Sta=4957,5022.9
XS Rating Curve= 0 ,0
Exp/Cntr=0.3,0.1

Type RM Length L Ch R = 1 ,1513    ,207,207,207
BEGIN DESCRIPTION:
UNT066 IN SNOGR 2.0
END DESCRIPTION:
XS GIS Cut Line= 3
      2775400.15     10009678.12      2775519.94     10010480.18
       2775801.2     10010683.32
#Sta/Elev= 30
  4330.7 1815.36  4352.3 1814.97  4357.4 1816.13  4376.8 1814.47  4421.6 1814.63
  4447.6 1811.25    4852  1792.9  4896.1 1787.58  4902.6 1785.69  4922.8 1783.03
  4965.4 1780.99  4983.5  1776.9  5003.4 1774.26  5013.8 1776.23  5098.8 1776.46
  5114.9 1775.18  5140.9 1777.14  5143.8 1777.14    5172 1777.89  5207.6 1783.01
  5222.3 1783.61  5243.2 1787.01  5257.9 1788.09  5293.5 1799.44  5337.2 1809.21
  5399.3 1826.61  5444.3 1836.25  5465.2 1838.74  5479.9  1842.7  5488.6 1842.76
#Mann= 6 ,-1 , 0
  4330.7      .1       0  4447.6     .05       0  4983.5    .035       0
  5140.9     .05       0  5293.5      .1       0  5399.3     .16       0
Bank Sta=4983.5,5143.8
XS Rating Curve= 0 ,0
Exp/Cntr=0.3,0.1

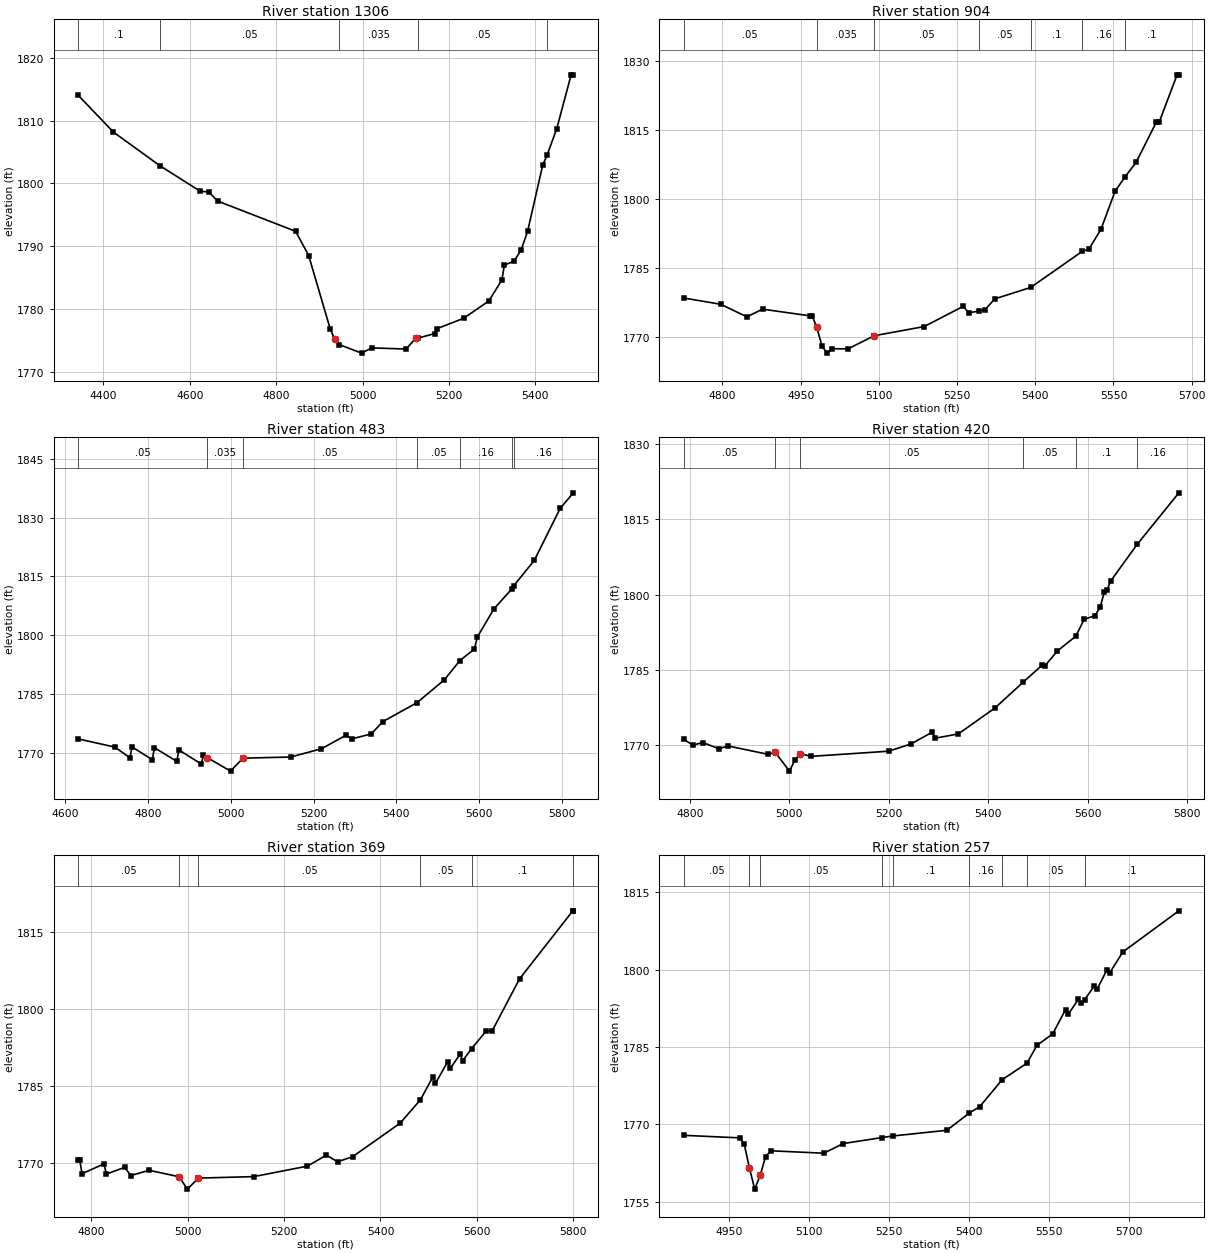
Type RM Length L Ch R = 1 ,1306    ,402,402,402
BEGIN DESCRIPTION:
Mapping XS 1c97459a
END DESCRIPTION:
XS GIS Cut Line= 4
      2775344.13     10009722.79      2775283.66     10010338.98
      2775322.72     10010443.15      2775692.52     10010633.26
#Sta/Elev= 30
  4341.7 1814.02    4423 1808.18  4530.8 1802.82    4624 1798.77  4644.1 1798.65
  4664.2 1797.21    4845 1792.39  4875.2 1788.53  4925.4 1776.77  4935.5 1775.23
  4945.5 1774.38  4997.7 1773.01    5021 1773.84  5100.8 1773.66    5123 1775.39
  5128.6  1775.4  5167.3 1776.13    5173 1776.92  5233.9 1778.55  5292.2  1781.3
  5322.6 1784.65  5328.2 1787.02  5350.4 1787.63    5367 1789.41  5382.1  1792.4
  5416.9 1802.87  5427.1  1804.5  5449.6 1808.72  5482.9 1817.29  5487.9 1817.29
#Mann= 5 ,-1 , 0
  4341.7      .1       0  4530.8     .05       0  4945.5    .035       0
  5128.6     .05       0  5427.1      .1       0
Bank Sta=4935.5,5123
XS Rating Curve= 0 ,0
Exp/Cntr=0.3,0.1

Type RM Length L Ch R = 1 ,904     ,421,421,421
BEGIN DESCRIPTION:
Mapping XS 54cfb647
END DESCRIPTION:
XS GIS Cut Line= 4
      2775020.66     10010343.23      2775011.98     10010456.04
      2775020.66     10010589.72      2775720.27     10010652.21
#Sta/Elev= 30
    4726 1778.37  4796.7 1777.01  4846.9 1774.28  4876.9 1775.95  4967.1 1774.51
  4972.6 1774.37  4980.9 1772.02    4991 1767.91  5000.8 1766.39  5011.1 1767.34
  5041.2 1767.33  5091.3 1770.18  5091.4 1770.18  5186.8 1772.16  5262.1 1776.57
  5272.1 1775.14  5292.9 1775.56  5303.2 1775.77  5322.3 1778.18  5391.5 1780.68
  5490.2 1788.52    5503 1789.03    5526 1793.28  5553.2 1801.59  5571.4 1804.58
  5593.4 1807.85  5632.4 1816.64  5637.5 1816.53  5672.1 1826.89  5675.5 1826.89
#Mann= 7 ,-1 , 0
    4726     .05       0  4980.9    .035       0  5091.4     .05       0
  5292.9     .05       0  5391.5      .1       0  5490.2     .16       0
  5571.4      .1       0
Bank Sta=4980.9,5091.3
XS Rating Curve= 0 ,0
Exp/Cntr=0.3,0.1

Type RM Length L Ch R = 1 ,483     ,63,63,63
BEGIN DESCRIPTION:
Mapping XS a0d67d62
END DESCRIPTION:
XS GIS Cut Line= 5
      2775022.39     10010655.71      2775022.39     10010730.34
      2774973.78     10011004.65      2775050.17     10011009.86
      2775789.28      10010808.6
#Sta/Elev= 30
  4631.6 1773.48  4719.8 1771.42  4756.4 1768.67  4761.5 1771.44  4810.4 1768.19
  4815.5 1771.25  4869.6 1767.76  4874.6 1770.67  4928.7  1767.1  4933.8 1769.37
  4943.3 1768.72  4999.3 1765.27  5029.6 1768.58  5144.7 1768.87  5219.1 1770.99
  5277.3 1774.37  5293.4 1773.53  5339.4 1774.78  5367.7 1777.93  5450.1 1782.77
  5515.6 1788.55  5553.6 1793.51  5588.2 1796.42  5595.9 1799.57  5635.7 1806.69
  5679.5 1811.86    5683 1812.53  5733.3  1819.1  5795.5 1832.32  5827.4 1836.32
#Mann= 7 ,-1 , 0
  4631.6     .05       0  4943.3    .035       0  5029.6     .05       0
  5450.1     .05       0  5553.6     .16       0  5679.5      .1       0
    5683     .16       0
Bank Sta=4943.3,5029.6
XS Rating Curve= 0 ,0
Exp/Cntr=0.3,0.1

Type RM Length L Ch R = 1 ,420     ,51,51,51
BEGIN DESCRIPTION:
Mapping XS ff541486
END DESCRIPTION:
XS GIS Cut Line= 4
      2774985.94     10010876.16      2774951.21     10011056.73
      2775071.01     10011101.87       2775718.6     10010881.38
#Sta/Elev= 30
  4787.7 1771.06  4805.7 1769.92    4826 1770.43  4857.7 1769.21  4876.9 1769.74
  4956.5 1768.09  4971.6 1768.49  5000.2 1764.72  5011.4 1766.98  5022.1 1768.23
  5043.5 1767.67  5199.8  1768.7  5244.8 1770.15  5287.1 1772.48  5293.9 1771.31
  5339.9 1772.15  5413.8 1777.34  5470.4 1782.49  5508.1 1785.84  5513.4 1785.64
  5539.5 1788.75  5576.1 1791.64  5593.4 1795.06  5614.5 1795.75  5625.1 1797.41
  5633.6 1800.43  5638.9 1800.84  5646.2 1802.65  5699.7    1810  5783.7 1820.31
#Mann= 6 ,-1 , 0
  4787.7     .05       0  4971.6    .035       0  5022.1     .05       0
  5470.4     .05       0  5576.1      .1       0  5699.7     .16       0
Bank Sta=4971.6,5022.1
XS Rating Curve= 0 ,0
Exp/Cntr=0.3,0.1

Type RM Length L Ch R = 1 ,369     ,112,112,112
BEGIN DESCRIPTION:
Mapping XS 09e77d73
END DESCRIPTION:
XS GIS Cut Line= 6
      2774974.68     10010909.52      2774942.28     10011105.08
      2775016.94     10011138.94      2775074.23     10011150.22
      2775239.16     10011080.78       2775719.2      10010911.5
#Sta/Elev= 30
  4773.1 1770.43  4776.2 1770.43  4780.8 1767.82  4826.3 1769.74  4831.4 1767.76
  4869.2 1769.06    4882 1767.47    4920 1768.49  4982.1 1767.24  4999.5 1764.82
  5022.3 1766.97  5137.2 1767.26  5248.4  1769.3  5287.8 1771.44  5310.9 1770.15
  5342.2 1771.14  5440.6 1777.66  5482.8 1782.23  5508.8 1786.72  5514.1 1785.44
  5539.7 1789.69    5545 1788.37  5565.2 1791.15  5570.5 1789.85  5589.2 1792.23
  5618.7 1795.59  5632.1 1795.74  5688.4 1805.79    5799 1819.07    5800 1819.07
#Mann= 6 ,-1 , 0
  4773.1     .05       0  4982.1    .035       0  5022.3     .05       0
  5482.8     .05       0  5589.2      .1       0    5799     .16       0
Bank Sta=4982.1,5022.3
XS Rating Curve= 0 ,0
Exp/Cntr=0.3,0.1

Type RM Length L Ch R = 1 ,257     ,177,177,177
BEGIN DESCRIPTION:
Mapping XS cc59c8e6
END DESCRIPTION:
XS GIS Cut Line= 4
      2774932.11     10011124.45      2774906.07     10011221.66
       2775027.6     10011233.81      2775682.13     10010969.92
#Sta/Elev= 30
  4865.6 1767.85    4970 1767.36  4978.7 1766.24  4988.7 1761.45  4998.5 1757.41
  5008.8  1760.1  5018.9 1763.71  5028.9 1764.85  5127.9 1764.38  5164.8 1766.26
  5237.5 1767.42  5258.1 1767.73  5358.9 1768.83    5401 1772.18  5420.5 1773.41
  5462.8 1778.66  5509.2 1781.85  5527.9 1785.31  5557.5 1787.55  5581.6 1792.26
    5587 1791.41  5605.8 1794.27  5611.2 1793.45  5617.5  1794.2  5635.3 1796.81
  5640.7 1796.21  5659.5 1800.03  5664.9 1799.45    5689 1803.44  5794.1 1811.42
#Mann= 9 ,-1 , 0
  4865.6     .05       0  4988.7    .035       0  5008.8     .05       0
  5237.5     .16       0  5258.1      .1       0    5401     .16       0
  5462.8      .1       0  5509.2     .05       0  5617.5      .1       0
Bank Sta=4988.7,5008.8
XS Rating Curve= 0 ,0
Exp/Cntr=0.3,0.1

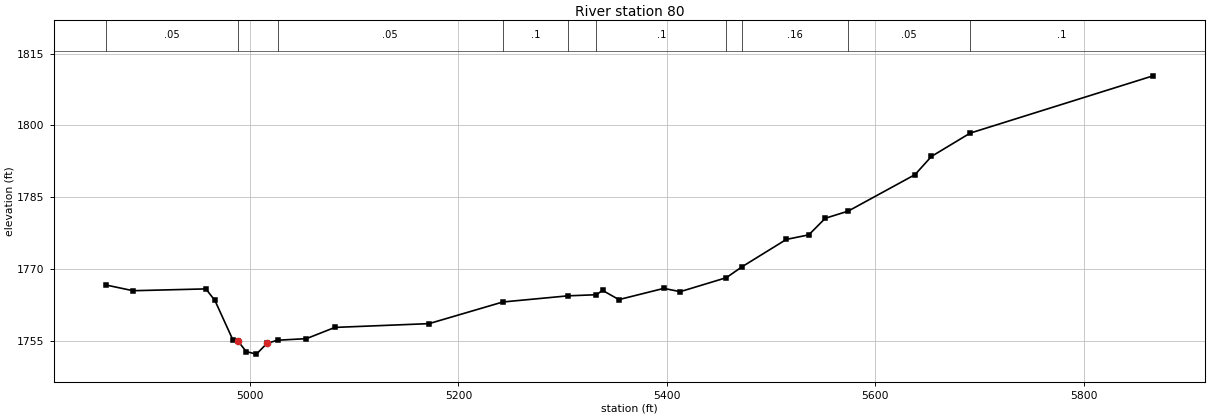
Type RM Length L Ch R = 1 ,80      ,0,0,0
BEGIN DESCRIPTION:
UNT066 IN SNOGR 1.0
END DESCRIPTION:
XS GIS Cut Line= 4
      2774892.18     10011308.49      2774866.14     10011397.01
      2774961.63     10011402.22      2775668.23     10010992.49
#Sta/Elev= 30
  4861.8 1766.62  4887.8 1765.42  4957.7  1765.8  4966.4 1763.38  4983.6 1755.14
  4988.6 1754.85  4996.5 1752.68  5006.2 1752.15  5016.5 1754.43  5026.5 1755.06
  5054.2 1755.39  5081.5 1757.74  5171.8 1758.53  5242.6 1763.06  5305.2 1764.35
  5332.4 1764.58  5338.3 1765.49    5354 1763.56  5397.1 1765.91  5412.8 1765.22
    5457 1768.14  5472.5 1770.48  5514.7 1776.16  5536.2 1777.11    5552 1780.58
    5574 1782.08  5638.1 1789.71  5653.8 1793.51    5691  1798.4  5866.5 1810.39
#Mann= 10 ,-1 , 0
  4861.8     .05       0  4988.6    .035       0  5026.5     .05       0
  5242.6      .1       0  5305.2     .16       0  5332.4      .1       0
    5457     .05       0  5472.5     .16       0    5574     .05       0
    5691      .1       0
Bank Sta=4988.6,5016.5
XS Rating Curve= 0 ,0
Exp/Cntr=0.3,0.1

Chan Stop Cuts=-1
Use User Specified Reach Order=0
Composite Channel Slope=5