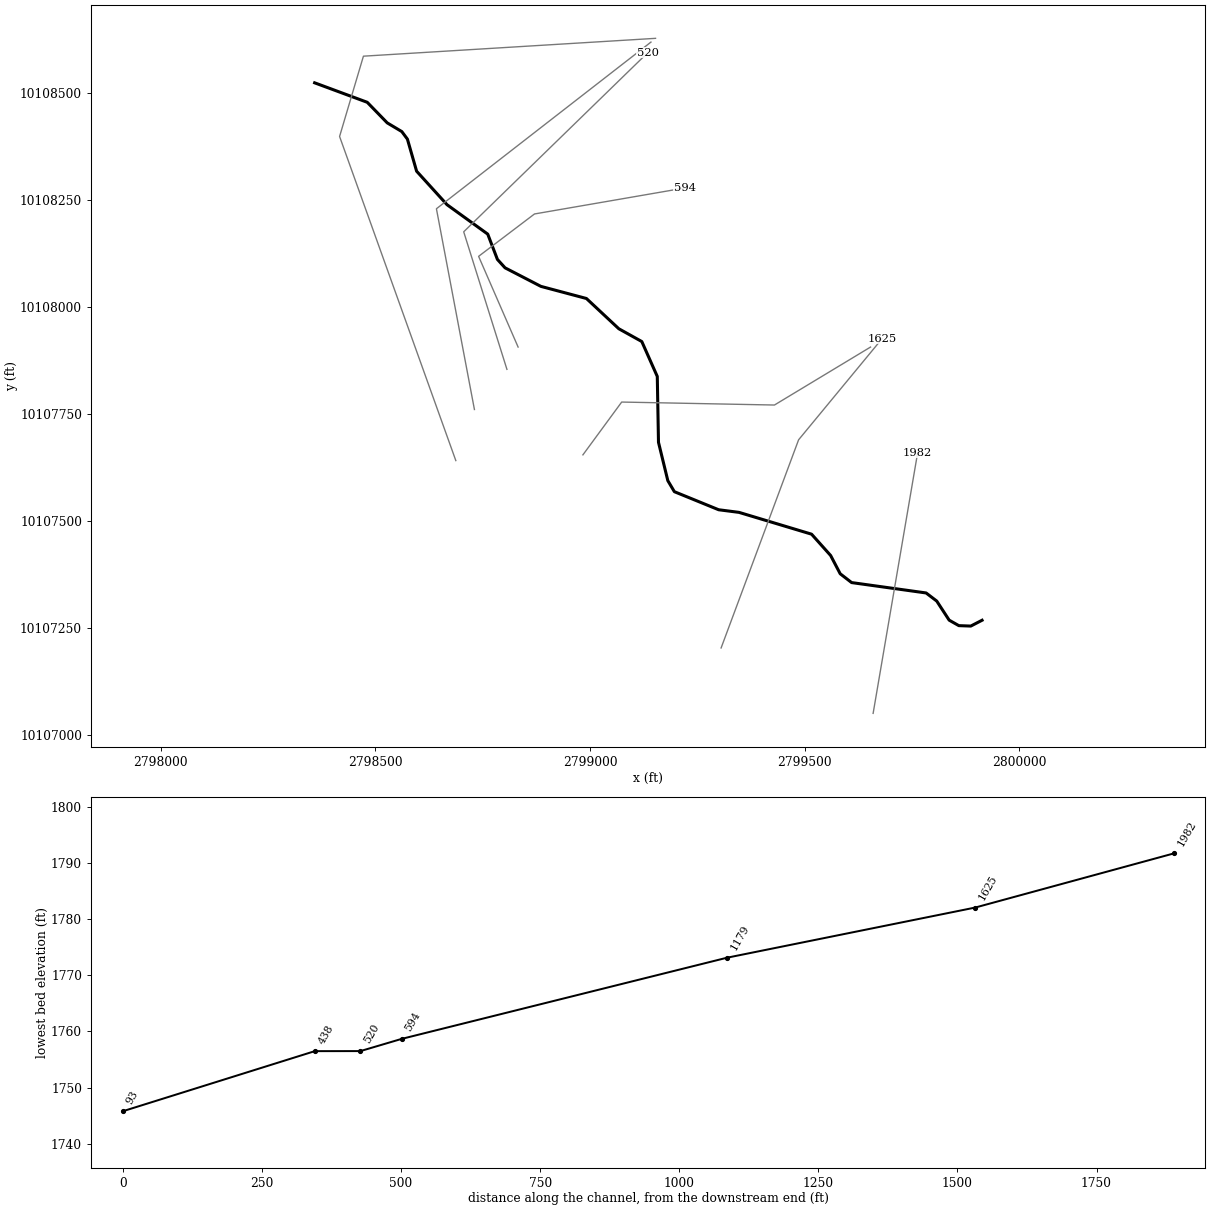
--- UNT067 IN NNOGR.prj (project) ---

Proj Title=UNT067 IN NNOGR Base Level Engineering
Current Plan=p01
Default Exp/Contr=0.3,0.1
English Units
Geom File=g01
Flow File=f01
Plan File=p01
Y Axis Title=Elevation
X Axis Title(PF)=Main Channel Distance
X Axis Title(XS)=Station
BEGIN DESCRIPTION:
UNT067 IN NNOGR
END DESCRIPTION:
DSS Export Rating Curves= 0
DSS Export Rating Curve Sorted= 0
DSS Export Volume Flow Curves= 0
DXF OffsetX= 0
DXF OffsetY= 0
DXF ScaleX= 1
DXF ScaleY= 10

--- UNT067 IN NNOGR.p01 (plan) ---

Plan Title=Multiple Run
Short Identifier=Multiple
Geom File=g01
Flow File=f01
Subcritical Flow
K Sum by GR= 0
Std Step Tol= 0.01
Critical Tol= 0.01
Num of Std Step Trials= 20
Max Error Tol= 0.3
Flow Tol Ratio= 0.001
Split Flow NTrial= 30
Split Flow Tol= 0.02
Split Flow Ratio= 0.02
Log Output Level= 0
Friction Slope Method= 1
Unsteady Friction Slope Method= 2
Unsteady Bridges Friction Slope Method= 1
Parabolic Critical Depth
Global Vel Dist=  1 , 1 , 1
Global Log Level= 0
CheckData=True
Encroach Param= -1, 0, 0, 0
BEGIN DESCRIPTION:
Multiple Run
END DESCRIPTION:

--- UNT067 IN NNOGR.f01 (steady flow) ---

Flow Title=Multiple
Number of Profiles=7
Profile Names=10-year,25-year,50-year,1pct_min,100-year,1pct_plu,500-year
River Rch & RM= UNT067 IN NNOGR,Reach-1,1982
     243     323     389     344     465     629     665
Boundary for River Rch & Prof#=UNT067 IN NNOGR,Reach-1,1
Up Type=0
Dn Type=3
Dn Slope=0.005
Boundary for River Rch & Prof#=UNT067 IN NNOGR,Reach-1,2
Up Type=0
Dn Type=3
Dn Slope=0.005
Boundary for River Rch & Prof#=UNT067 IN NNOGR,Reach-1,3
Up Type=0
Dn Type=3
Dn Slope=0.005
Boundary for River Rch & Prof#=UNT067 IN NNOGR,Reach-1,4
Up Type=0
Dn Type=3
Dn Slope=0.005
Boundary for River Rch & Prof#=UNT067 IN NNOGR,Reach-1,5
Up Type=0
Dn Type=3
Dn Slope=0.005
Boundary for River Rch & Prof#=UNT067 IN NNOGR,Reach-1,6
Up Type=0
Dn Type=3
Dn Slope=0.005
Boundary for River Rch & Prof#=UNT067 IN NNOGR,Reach-1,7
Up Type=0
Dn Type=3
Dn Slope=0.005

--- UNT067 IN NNOGR.g01 (geometry) ---

Geom Title=Existing Conditions
Program Version=4.10

River Reach=UNT067 IN NNOGR ,Reach-1
Reach XY= 30
      2799913.47     10107268.73      2799887.17     10107255.13
      2799859.33     10107256.13      2799836.86      10107268.9
      2799807.84     10107313.53      2799783.07     10107332.45
      2799609.54     10107356.68      2799582.95     10107377.27
      2799560.65     10107419.93      2799516.26      10107469.7
      2799347.18     10107520.64      2799299.71     10107526.77
      2799196.57     10107568.95      2799181.34     10107594.71
      2799159.58     10107684.19      2799156.78     10107838.05
      2799120.69     10107919.58      2799067.14     10107949.41
       2798991.7     10108020.07      2798885.67     10108048.38
      2798802.12     10108091.67      2798784.33      10108111.3
      2798761.75     10108170.43      2798666.86     10108239.15
      2798596.04     10108317.36       2798574.6     10108392.27
      2798561.55     10108409.87      2798527.59      10108430.2
      2798481.01     10108478.26      2798358.47     10108523.73

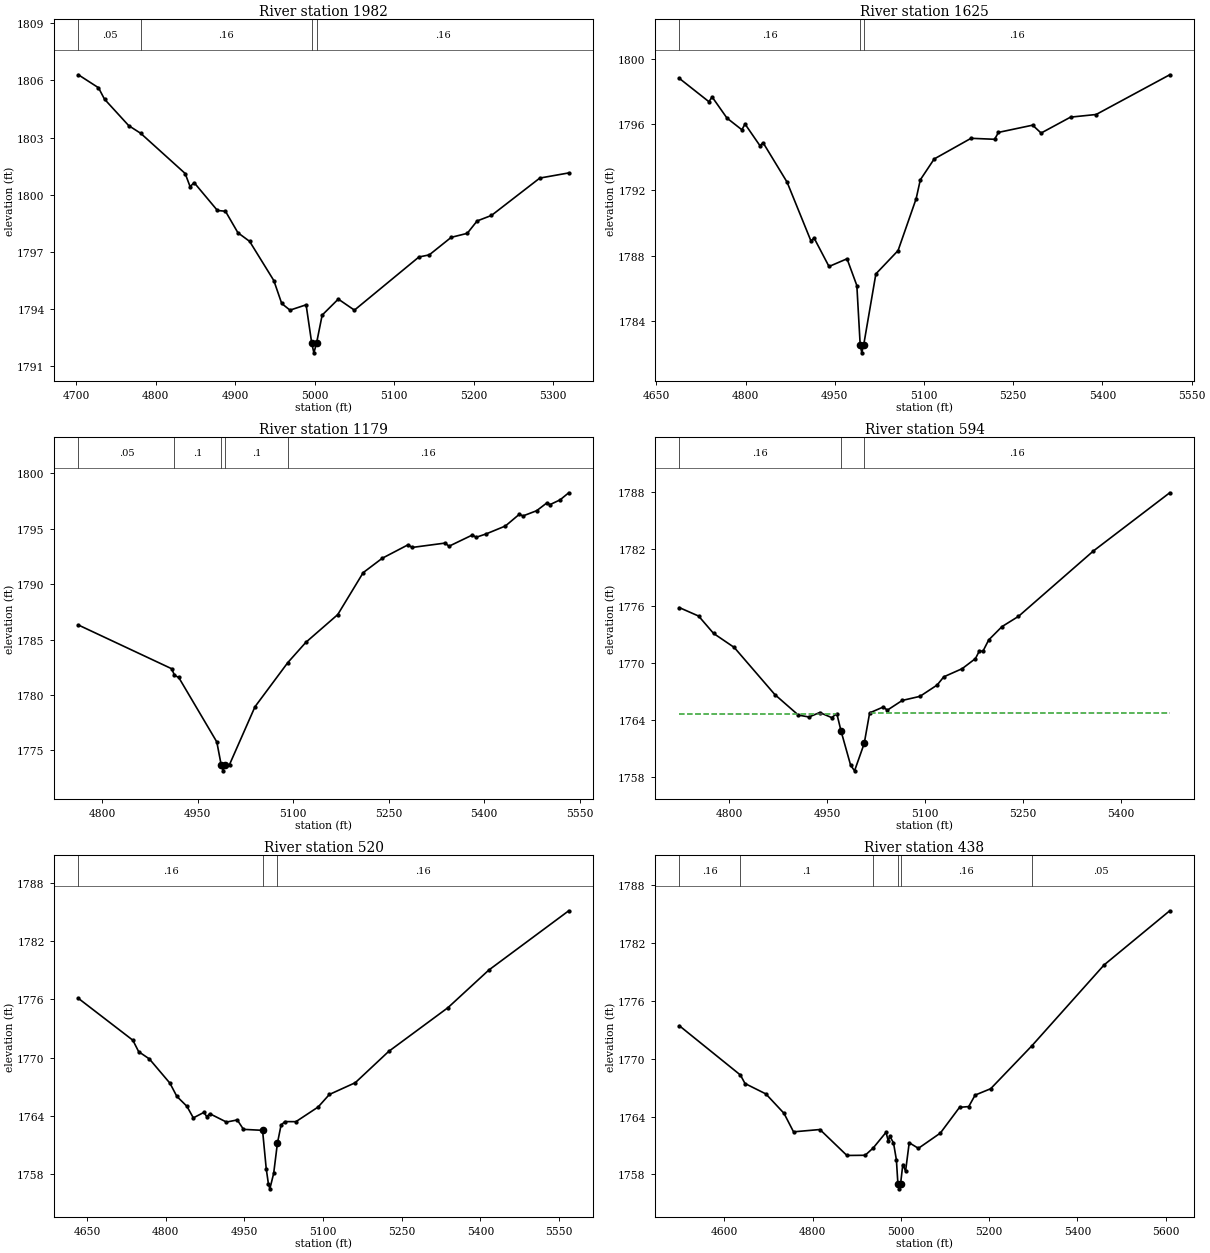
Type RM Length L Ch R = 1 ,1982    ,357,357,357
BEGIN DESCRIPTION:
UNT067 IN NNOGR 4.0
END DESCRIPTION:
XS GIS Cut Line= 2
      2799659.64     10107051.25      2799763.33     10107659.58
#Sta/Elev= 30
  4702.6  1806.3  4727.9 1805.62  4735.5 1805.02    4766 1803.63    4781 1803.23
    4837 1801.12  4843.2 1800.43  4848.3 1800.64  4877.6 1799.18  4887.7 1799.14
  4903.4 1798.01  4918.1 1797.56  4948.6  1795.5  4958.5  1794.3  4968.9 1793.95
  4989.2 1794.23  4996.3 1792.21    4999 1791.71  5002.3 1792.21  5009.4 1793.69
  5029.7 1794.53    5050 1793.95  5131.2 1796.74  5144.2 1796.85  5171.8 1797.77
    5192 1797.98  5204.4 1798.63  5222.5 1798.92  5283.3 1800.88  5319.7 1801.15
#Mann= 4 ,-1 , 0
  4702.6     .05       0    4781     .16       0  4996.3     .07       0
  5002.3     .16       0
Bank Sta=4996.3,5002.3
XS Rating Curve= 0 ,0
Exp/Cntr=0.3,0.1

Type RM Length L Ch R = 1 ,1625    ,446,446,446
BEGIN DESCRIPTION:
Mapping XS fead0b71
END DESCRIPTION:
XS GIS Cut Line= 3
      2799305.46     10107203.99      2799486.02     10107690.11
      2799680.44     10107926.19
#Sta/Elev= 30
  4688.7 1798.79  4738.4 1797.37  4743.8 1797.66  4768.8 1796.37  4793.8 1795.66
  4799.1 1796.01  4824.2 1794.69  4829.5 1794.87  4869.8 1792.47  4909.9 1788.89
  4915.3 1789.06  4940.3 1787.33  4970.6  1787.8  4987.1 1786.17  4992.7 1782.57
  4995.4 1782.07  4998.7 1782.57  5019.1 1786.88  5056.4  1788.3  5086.8 1791.46
  5093.8 1792.61  5117.1 1793.88  5179.1 1795.14  5218.7 1795.08  5225.2  1795.5
  5282.6 1795.94  5296.9 1795.46  5346.4 1796.43  5389.4 1796.59  5513.1 1799.01
#Mann= 3 ,-1 , 0
  4688.7     .16       0  4992.7     .07       0  4998.7     .16       0
Bank Sta=4992.7,4998.7
XS Rating Curve= 0 ,0
Exp/Cntr=0.3,0.1

Type RM Length L Ch R = 1 ,1179    ,585,585,585
BEGIN DESCRIPTION:
UNT067 IN NNOGR 3.0
END DESCRIPTION:
XS GIS Cut Line= 4
      2798983.52     10107654.95      2799073.83     10107778.25
      2799429.73      10107771.3      2799653.59     10107906.66
#Sta/Elev= 30
  4762.4 1786.31    4909 1782.36  4913.4 1781.77  4920.1 1781.57  4979.9 1775.75
  4986.9 1773.64  4989.6 1773.14  4992.9 1773.64  4999.9 1773.71  5039.9 1778.93
  5091.5 1782.92  5119.9 1784.75  5169.9 1787.25  5209.9 1791.04  5239.9 1792.34
  5280.6 1793.56  5286.4 1793.31  5338.8 1793.71  5344.6 1793.42  5381.5 1794.44
  5387.3 1794.23  5402.8 1794.53  5433.3 1795.25  5455.2 1796.31    5461 1796.16
  5482.4 1796.63  5497.9 1797.31  5503.7 1797.19  5519.2 1797.61  5532.8 1798.25
#Mann= 5 ,-1 , 0
  4762.4     .05       0  4913.4      .1       0  4986.9     .07       0
  4992.9      .1       0  5091.5     .16       0
Bank Sta=4986.9,4992.9
XS Rating Curve= 0 ,0
Exp/Cntr=0.3,0.1

Type RM Length L Ch R = 1 ,594     ,74,74,74
BEGIN DESCRIPTION:
UNT067 IN NNOGR 2.0
END DESCRIPTION:
XS GIS Cut Line= 4
      2798832.51      10107906.7      2798740.49     10108118.53
       2798870.7     10108217.48      2799221.39     10108278.25
#Sta/Elev= 30
    4724 1775.84  4753.5 1774.95  4776.3 1773.13    4808 1771.65  4870.1  1766.7
  4906.1 1764.54  4922.4 1764.34  4938.8 1764.81    4957 1764.28    4965 1764.68
  4971.5 1762.85  4986.1 1759.27  4992.1 1758.68  5006.9 1761.56  5015.2 1764.77
    5036 1765.39  5042.3 1765.06  5065.1 1766.08  5092.2 1766.51  5118.5  1767.7
  5128.6 1768.56  5156.8 1769.42  5177.1 1770.48  5183.3 1771.31  5188.4 1771.23
  5197.4 1772.44  5217.7 1773.84    5243 1774.92  5357.4 1781.78  5474.4 1787.91
#Mann= 3 , 0 , 0
    4724     .16       0  4971.5     .07       0  5006.9     .16       0
#XS Ineff= 2 , 0
         4964.99  1764.7 5015.48          1764.8
Permanent Ineff=
       F       F
Bank Sta=4971.5,5006.9
XS Rating Curve= 0 ,0
Exp/Cntr=0.3,0.1

Type RM Length L Ch R = 1 ,520     ,82,82,82
BEGIN DESCRIPTION:
Mapping XS 602ad24a
END DESCRIPTION:
XS GIS Cut Line= 3
      2798806.48     10107854.61      2798705.77     10108175.82
      2799134.06      10108593.7
#Sta/Elev= 30
  4633.3 1776.11  4737.2  1771.8  4748.3 1770.62  4768.6 1769.88  4807.9 1767.38
    4821 1766.03  4840.3    1765  4852.5 1763.81  4872.8 1764.38    4878 1763.94
  4883.9 1764.24  4915.7 1763.38  4936.3  1763.6  4948.1 1762.63  4984.5 1762.53
  4991.5 1758.58  4995.7 1757.01  4998.4 1756.51  5005.7  1758.1  5012.8 1761.19
  5019.8 1763.07    5027 1763.43  5048.1 1763.42  5090.5 1764.93  5111.9 1766.22
  5161.3 1767.43    5225 1770.65    5338 1775.15  5415.9 1779.02  5568.3 1785.12
#Mann= 3 , 0 , 0
  4633.3     .16       0  4984.5     .07       0  5012.8     .16       0
Bank Sta=4984.5,5012.8
XS Rating Curve= 0 ,0
Exp/Cntr=0.3,0.1

Type RM Length L Ch R = 1 ,438     ,345,345,345
BEGIN DESCRIPTION:
Mapping XS 7665de82
END DESCRIPTION:
XS GIS Cut Line= 3
      2798730.75     10107760.86       2798642.2     10108229.64
      2799142.06     10108618.86
#Sta/Elev= 30
  4498.3 1773.41  4636.6  1768.3    4647 1767.42  4694.3 1766.34  4735.3 1764.33
  4756.9 1762.41  4816.7 1762.65  4877.8 1759.96  4919.1 1759.98  4937.4 1760.74
  4966.4 1762.36  4971.5 1761.45  4974.9 1761.96  4983.3 1761.27  4989.9  1759.5
  4993.3    1757    4996  1756.5  4999.3    1757  5004.4 1759.02  5010.7 1758.35
  5018.9 1761.28  5039.7  1760.7  5089.4 1762.28  5132.9 1764.95  5153.7 1765.03
  5168.2 1766.22  5203.4 1766.88  5296.9 1771.34  5460.4 1779.72  5608.9 1785.33
#Mann= 6 ,-1 , 0
  4498.3     .16       0  4636.6      .1       0  4937.4     .16       0
  4993.3     .07       0  4999.3     .16       0  5296.9     .05       0
Bank Sta=4993.3,4999.3
XS Rating Curve= 0 ,0
Exp/Cntr=0.3,0.1

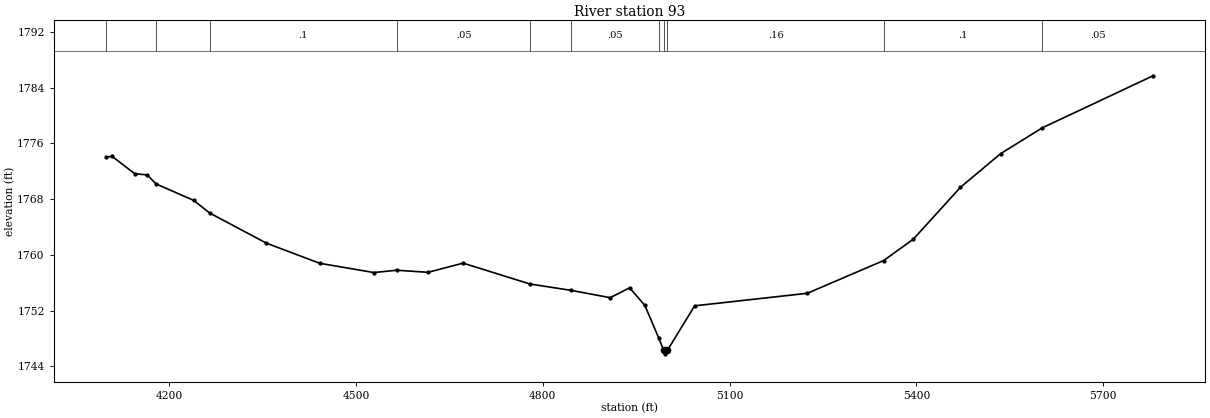
Type RM Length L Ch R = 1 ,93      ,0,0,0
BEGIN DESCRIPTION:
UNT067 IN NNOGR 1.0
END DESCRIPTION:
XS GIS Cut Line= 4
      2798687.39     10107641.55      2798416.58     10108398.44
      2798472.13     10108585.94      2799152.71     10108627.61
#Sta/Elev= 30
  4098.7 1774.05  4108.3 1774.14  4144.4 1771.66  4164.6 1771.48  4178.8 1770.19
  4239.1 1767.83  4265.1    1766  4355.9 1761.69  4441.5  1758.8  4528.5 1757.47
  4565.4  1757.8  4615.6  1757.5  4671.8 1758.82  4779.4 1755.82  4845.4 1754.91
  4908.1 1753.86  4939.4 1755.27  4963.8 1752.75  4985.9 1748.12    4994  1746.3
  4996.7  1745.8    5000  1746.3  5043.7 1752.69  5224.7 1754.49  5347.3 1759.19
    5395 1762.26  5470.6  1769.7  5535.3 1774.54  5602.1 1778.24    5780 1785.71
#Mann= 11 ,-1 , 0
  4098.7     .16       0  4178.8     .05       0  4265.1      .1       0
  4565.4     .05       0  4779.4      .1       0  4845.4     .05       0
  4985.9     .16       0    4994     .07       0    5000     .16       0
  5347.3      .1       0  5602.1     .05       0
Bank Sta=4994,5000
XS Rating Curve= 0 ,0
Exp/Cntr=0.3,0.1

Chan Stop Cuts=-1
Use User Specified Reach Order=0
Composite Channel Slope=5