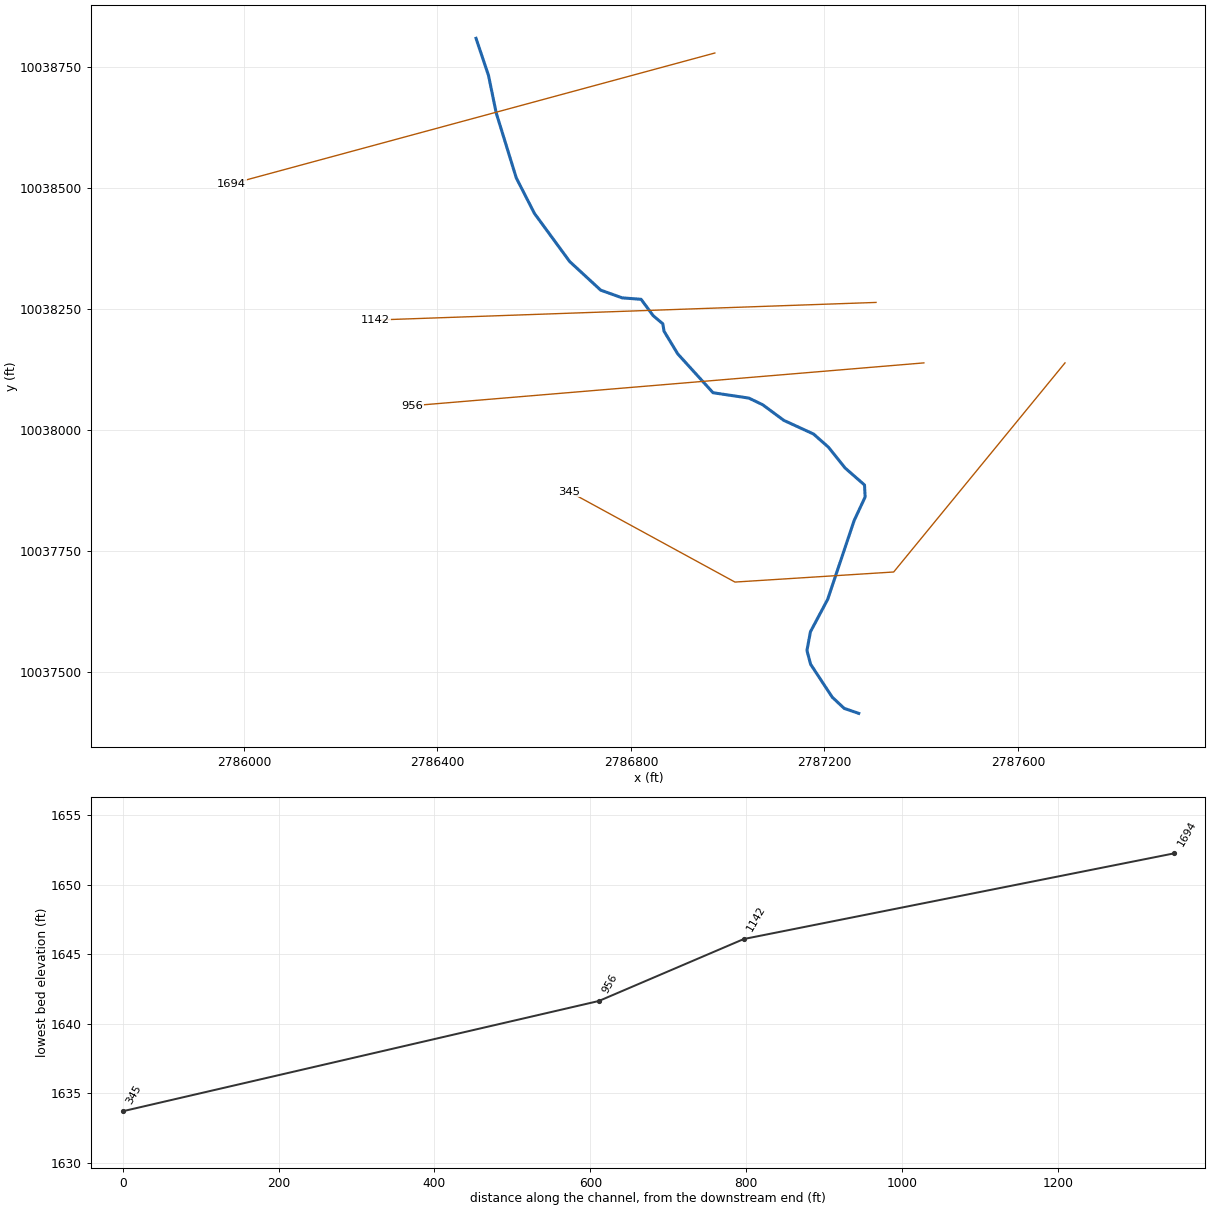
--- UNT067 IN SNOGR.prj (project) ---

Proj Title=UNT067 IN SNOGR Base Level Engineering
Current Plan=p01
Default Exp/Contr=0.3,0.1
English Units
Geom File=g01
Flow File=f01
Plan File=p01
BEGIN DESCRIPTION:
UNT067 IN SNOGR
END DESCRIPTION:

--- UNT067 IN SNOGR.p01 (plan) ---

Plan Title=Multiple Run
Short Identifier=Multiple
Geom File=g01
Flow File=f01
Subcritical Flow
K Sum by GR= 0
Std Step Tol= 0.01
Critical Tol= 0.01
Num of Std Step Trials= 20
Max Error Tol= 0.3
Flow Tol Ratio= 0.001
Split Flow NTrial= 30
Split Flow Tol= 0.02
Split Flow Ratio= 0.02
Log Output Level= 0
Friction Slope Method= 1
Unsteady Friction Slope Method= 2
Unsteady Bridges Friction Slope Method= 1
Parabolic Critical Depth
Global Vel Dist=  1 , 1 , 1
Global Log Level= 0
CheckData=True
Encroach Param= -1, 0, 0, 0
BEGIN DESCRIPTION:
Multiple Run
END DESCRIPTION:

--- UNT067 IN SNOGR.f01 (steady flow) ---

Flow Title=Multiple
Number of Profiles=7
Profile Names=10-year,25-year,50-year,1pct_min,100-year,1pct_plu,500-year
River Rch & RM= UNT067 IN SNOGR,Reach-1,1694
     414     574     707     640     865    1170    1297
Boundary for River Rch & Prof#=UNT067 IN SNOGR,Reach-1,1
Up Type=0
Dn Type=3
Dn Slope=0.005
Boundary for River Rch & Prof#=UNT067 IN SNOGR,Reach-1,2
Up Type=0
Dn Type=3
Dn Slope=0.005
Boundary for River Rch & Prof#=UNT067 IN SNOGR,Reach-1,3
Up Type=0
Dn Type=3
Dn Slope=0.005
Boundary for River Rch & Prof#=UNT067 IN SNOGR,Reach-1,4
Up Type=0
Dn Type=3
Dn Slope=0.005
Boundary for River Rch & Prof#=UNT067 IN SNOGR,Reach-1,5
Up Type=0
Dn Type=3
Dn Slope=0.005
Boundary for River Rch & Prof#=UNT067 IN SNOGR,Reach-1,6
Up Type=0
Dn Type=3
Dn Slope=0.005
Boundary for River Rch & Prof#=UNT067 IN SNOGR,Reach-1,7
Up Type=0
Dn Type=3
Dn Slope=0.005

--- UNT067 IN SNOGR.g01 (geometry) ---

Geom Title=Existing Conditions

River Reach=UNT067 IN SNOGR,Reach-1
Reach XY= 30
      2786479.77     10038809.27      2786505.55     10038732.52
      2786521.51     10038654.99      2786562.92     10038520.85
      2786600.57     10038447.19      2786673.39     10038347.80
      2786737.48     10038288.67      2786781.94     10038272.72
      2786821.05     10038269.72      2786845.76     10038236.16
      2786865.93     10038219.04      2786868.47     10038203.73
      2786896.67     10038157.05      2786969.73     10038076.59
      2787043.83     10038065.51      2787072.37     10038051.78
      2787116.12     10038019.44      2787177.51     10037991.25
      2787208.48     10037963.87      2787242.80     10037920.96
      2787282.89     10037885.90      2787284.21     10037861.12
      2787261.56     10037812.60      2787206.74     10037649.43
      2787171.11     10037582.39      2787163.87     10037543.69
      2787171.53     10037515.13      2787216.09     10037447.32
      2787240.87     10037424.05      2787270.93     10037413.71

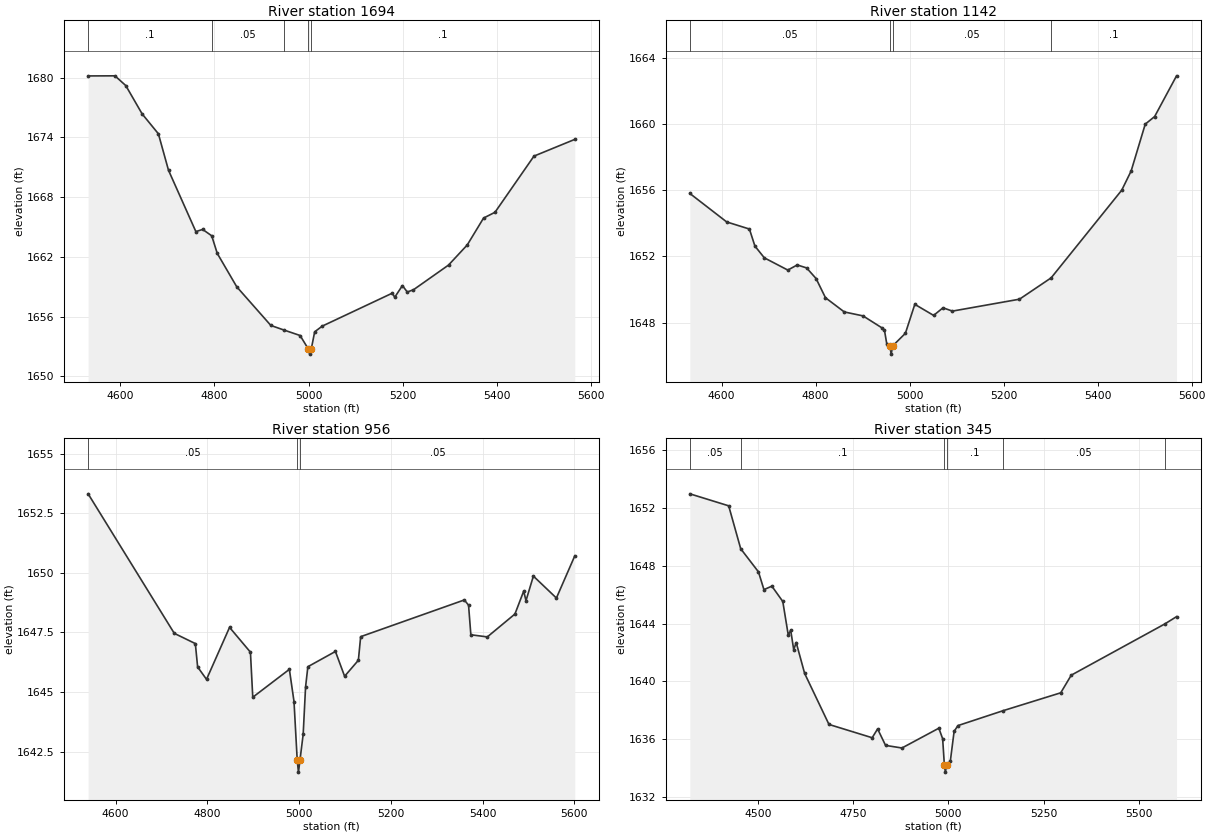
Type RM Length L Ch R = 1,1694,552,552,552
BEGIN DESCRIPTION:
UNT067 IN SNOGR 2.0
END DESCRIPTION:
XS GIS Cut Line= 2
      2786973.46     10038778.94      2785974.64     10038508.42
#Sta/Elev= 30
  4531.4 1680.17  4588.4 1680.18  4611.5 1679.20  4646.2 1676.36  4680.8 1674.36
  4702.3 1670.70  4760.5 1664.54  4774.9 1664.76  4794.2 1664.12  4805.9 1662.36
  4847.4 1659.00  4919.9 1655.12  4947.1 1654.67  4982.1 1654.11  4999.8 1652.74
  5002.5 1652.24  5005.8 1652.74  5013.1 1654.48  5029.1 1655.05  5178.1 1658.36
  5183.3 1657.95  5199.6 1659.12  5210.0 1658.48  5223.1 1658.70  5297.7 1661.18
  5337.5 1663.20  5372.2 1665.90  5396.5 1666.48  5479.4 1672.12  5566.2 1673.80
#Mann=5,-1,0
  4531.4     0.1       0  4794.2    0.05       0  4947.1     0.1       0
  4999.8    0.07       0  5005.8     0.1       0
Bank Sta=4999.8,5005.8
Exp/Cntr=0.3,0.1

Type RM Length L Ch R = 1,1142,186,186,186
BEGIN DESCRIPTION:
Mapping XS c7dba1c1
END DESCRIPTION:
XS GIS Cut Line= 2
      2787306.75     10038263.30      2786271.89     10038226.90
#Sta/Elev= 30
  4532.4 1655.80  4610.7 1654.08  4659.1 1653.65  4670.8 1652.62  4690.8 1651.91
  4740.8 1651.17  4760.8 1651.48  4780.8 1651.30  4800.9 1650.66  4820.9 1649.50
  4860.9 1648.64  4900.9 1648.40  4940.9 1647.68  4946.4 1647.54  4951.4 1646.70
  4958.0 1646.59  4960.7 1646.09  4964.0 1646.59  4991.0 1647.35  5011.0 1649.10
  5051.0 1648.43  5071.0 1648.89  5091.0 1648.69  5233.7 1649.41  5301.1 1650.70
  5451.3 1656.00  5471.3 1657.16  5501.3 1659.99  5521.3 1660.45  5567.9 1662.91
#Mann=4,-1,0
  4532.4    0.05       0  4958.0    0.04       0  4964.0    0.05       0
  5301.1     0.1       0
Bank Sta=4958,4964
Exp/Cntr=0.3,0.1

Type RM Length L Ch R = 1,956,611,611,611
BEGIN DESCRIPTION:
Mapping XS 522abbe8
END DESCRIPTION:
XS GIS Cut Line= 2
      2787405.66     10038138.30      2786348.46     10038049.76
#Sta/Elev= 30
  4540.3 1653.31  4728.1 1647.46  4774.0 1647.03  4779.0 1646.05  4798.4 1645.53
  4848.6 1647.71  4894.1 1646.67  4899.2 1644.78  4979.0 1645.95  4989.1 1644.60
  4996.1 1642.14  4998.8 1641.64  5002.1 1642.14  5009.1 1643.23  5014.3 1645.21
  5019.3 1646.06  5079.4 1646.70  5099.4 1645.66  5129.4 1646.33  5134.4 1647.32
  5360.4 1648.86  5369.6 1648.64  5374.6 1647.40  5410.5 1647.31  5470.7 1648.27
  5489.8 1649.23  5494.8 1648.83  5510.9 1649.86  5561.1 1648.94  5601.2 1650.71
#Mann=3,-1,0
  4540.3    0.05       0  4996.1    0.04       0  5002.1    0.05       0
Bank Sta=4996.1,5002.1
Exp/Cntr=0.3,0.1

Type RM Length L Ch R = 1,345,0,0,0
BEGIN DESCRIPTION:
UNT067 IN SNOGR 1.0
END DESCRIPTION:
XS GIS Cut Line= 4
      2787697.40     10038138.33      2787343.21     10037706.01
      2787015.08     10037685.17      2786672.41     10037872.08
#Sta/Elev= 30
  4321.1 1652.98  4423.0 1652.15  4454.6 1649.18  4501.2 1647.58  4515.6 1646.35
  4536.4 1646.59  4565.1 1645.53  4579.5 1643.20  4585.9 1643.54  4593.8 1642.19
  4600.3 1642.69  4622.5 1640.55  4686.4 1637.02  4799.8 1636.10  4814.1 1636.71
  4835.0 1635.57  4878.0 1635.39  4974.9 1636.76  4984.9 1636.03  4989.4 1634.22
  4992.1 1633.72  4995.4 1634.22  5005.0 1634.47  5015.0 1636.54  5025.0 1636.94
  5144.6 1637.98  5295.0 1639.21  5322.6 1640.43  5567.9 1643.97  5599.1 1644.48
#Mann=6,-1,0
  4321.1    0.05       0  4454.6     0.1       0  4989.4    0.07       0
  4995.4     0.1       0  5144.6    0.05       0  5567.9     0.1       0
Bank Sta=4989.4,4995.4
Exp/Cntr=0.3,0.1

Chan Stop Cuts=-1