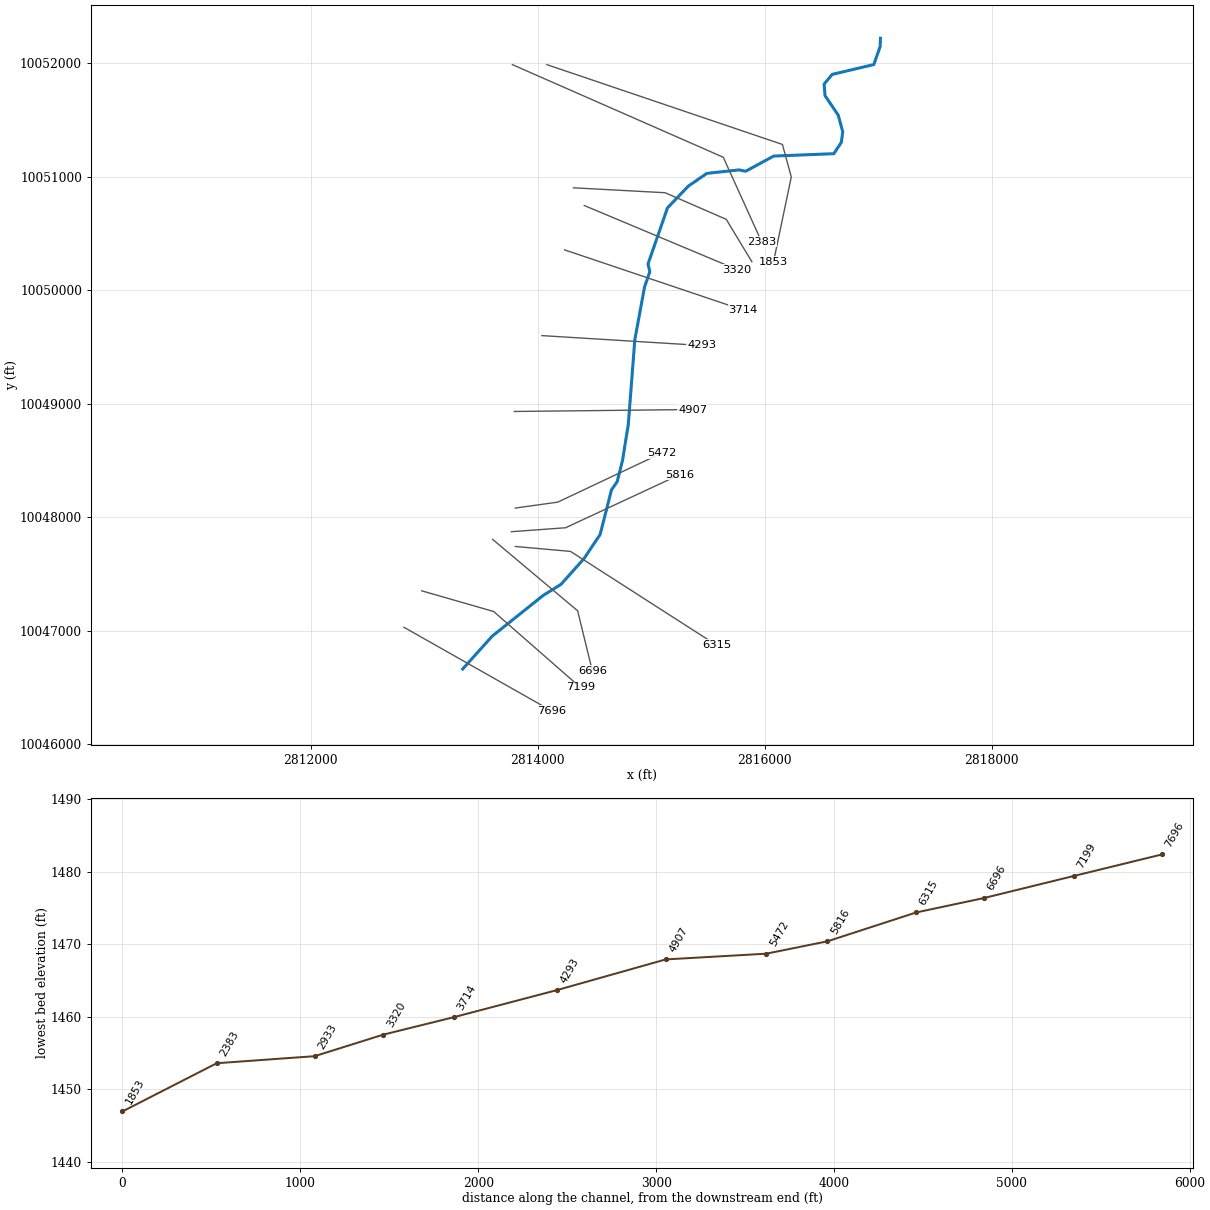
--- UNT068 IN SNOGR.prj (project) ---

Proj Title=UNT068 IN SNOGR Base Level Engineering
Current Plan=p01
Default Exp/Contr=0.3,0.1
English Units
Geom File=g01
Flow File=f01
Plan File=p01
BEGIN DESCRIPTION:
UNT068 IN SNOGR
END DESCRIPTION:

--- UNT068 IN SNOGR.p01 (plan) ---

Plan Title=Multiple Run
Short Identifier=Multiple
Geom File=g01
Flow File=f01
Subcritical Flow
K Sum by GR= 0
Std Step Tol= 0.01
Critical Tol= 0.01
Num of Std Step Trials= 20
Max Error Tol= 0.3
Flow Tol Ratio= 0.001
Split Flow NTrial= 30
Split Flow Tol= 0.02
Split Flow Ratio= 0.02
Log Output Level= 0
Friction Slope Method= 1
Unsteady Friction Slope Method= 2
Unsteady Bridges Friction Slope Method= 1
Parabolic Critical Depth
Global Vel Dist=  1 , 1 , 1
Global Log Level= 0
CheckData=True
Encroach Param= -1, 0, 0, 0
BEGIN DESCRIPTION:
Multiple Run
END DESCRIPTION:

--- UNT068 IN SNOGR.f01 (steady flow) ---

Flow Title=Multiple
Number of Profiles=7
Profile Names=10-year,25-year,50-year,1pct_min,100-year,1pct_plu,500-year
River Rch & RM= UNT068 IN SNOGR,Reach-1,7696
     634     891    1107    1007    1362    1842    2069
River Rch & RM= UNT068 IN SNOGR,Reach-1,6696
     786    1117    1398    1279    1730    2340    2660
River Rch & RM= UNT068 IN SNOGR,Reach-1,5472
     842    1198    1501    1374    1858    2513    2860
Boundary for River Rch & Prof#=UNT068 IN SNOGR,Reach-1,1
Up Type=0
Dn Type=3
Dn Slope=0.005
Boundary for River Rch & Prof#=UNT068 IN SNOGR,Reach-1,2
Up Type=0
Dn Type=3
Dn Slope=0.005
Boundary for River Rch & Prof#=UNT068 IN SNOGR,Reach-1,3
Up Type=0
Dn Type=3
Dn Slope=0.005
Boundary for River Rch & Prof#=UNT068 IN SNOGR,Reach-1,4
Up Type=0
Dn Type=3
Dn Slope=0.005
Boundary for River Rch & Prof#=UNT068 IN SNOGR,Reach-1,5
Up Type=0
Dn Type=3
Dn Slope=0.005
Boundary for River Rch & Prof#=UNT068 IN SNOGR,Reach-1,6
Up Type=0
Dn Type=3
Dn Slope=0.005
Boundary for River Rch & Prof#=UNT068 IN SNOGR,Reach-1,7
Up Type=0
Dn Type=3
Dn Slope=0.005

--- UNT068 IN SNOGR.g01 (geometry) ---

Geom Title=Existing Conditions

River Reach=UNT068 IN SNOGR,Reach-1
Reach XY= 30
      2813338.91     10046663.92      2813598.72     10046953.07
      2814049.06     10047313.13      2814205.19     10047409.82
      2814406.64     10047635.20      2814549.39     10047847.88
      2814649.43     10048241.08      2814700.04     10048315.11
      2814746.32     10048499.16      2814797.69     10048818.37
      2814854.93     10049563.59      2814940.64     10050028.35
      2814987.28     10050163.56      2814971.68     10050232.83
      2815143.05     10050726.55      2815326.95     10050918.30
      2815489.97     10051030.10      2815774.06     10051060.89
      2815831.57     10051049.07      2816078.63     10051182.60
      2816608.47     10051203.73      2816674.82     10051305.27
      2816686.46     10051398.01      2816646.68     10051542.99
      2816530.83     10051714.75      2816522.73     10051816.60
      2816593.91     10051902.36      2816960.33     10051988.69
      2817016.36     10052148.64      2817018.53     10052220.82

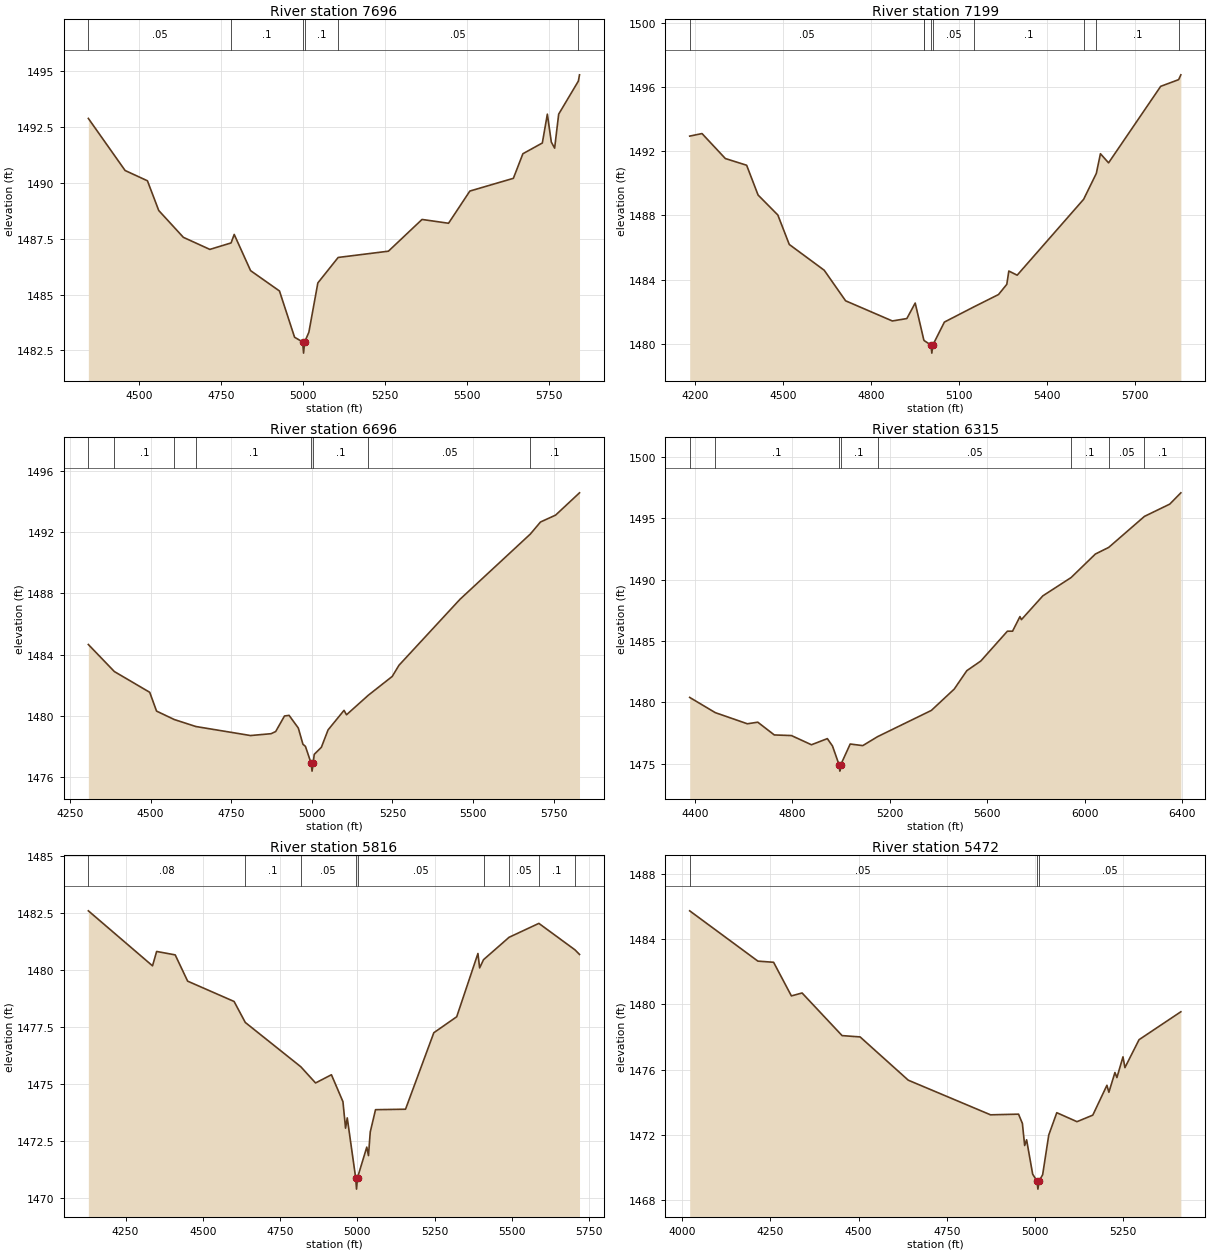
Type RM Length L Ch R = 1,7696,497,497,497
BEGIN DESCRIPTION:
UNT068 IN SNOGR 16.0
END DESCRIPTION:
XS GIS Cut Line= 2
      2812821.84     10047031.55      2814123.74     10046293.81
#Sta/Elev= 30
  4345.5 1492.88  4457.5 1490.55  4525.5 1490.09  4560.0 1488.76  4635.0 1487.56
  4715.7 1487.02  4780.4 1487.31  4789.9 1487.69  4839.8 1486.07  4927.8 1485.16
  4973.8 1483.09  4998.4 1482.88  5001.2 1482.38  5004.4 1482.88  5017.3 1483.31
  5044.7 1485.52  5106.6 1486.66  5259.7 1486.94  5362.1 1488.36  5442.9 1488.19
  5507.8 1489.63  5640.4 1490.20  5669.4 1491.30  5728.6 1491.78  5743.9 1493.07
  5756.0 1491.82  5766.1 1491.55  5778.4 1493.07  5838.4 1494.55  5841.9 1494.83
#Mann=6,-1,0
  4345.5    0.05       0  4780.4     0.1       0  4998.4    0.07       0
  5004.4     0.1       0  5106.6    0.05       0  5838.4     0.1       0
Bank Sta=4998.4,5004.4
Exp/Cntr=0.3,0.1

Type RM Length L Ch R = 1,7199,503,503,503
BEGIN DESCRIPTION:
UNT068 IN SNOGR 15.0
END DESCRIPTION:
XS GIS Cut Line= 3
      2812978.14     10047352.71      2813611.80     10047170.42
      2814374.57     10046503.00
#Sta/Elev= 30
  4182.2 1492.96  4224.2 1493.12  4303.6 1491.56  4376.2 1491.14  4415.1 1489.28
  4482.5 1488.03  4521.4 1486.19  4640.4 1484.58  4713.2 1482.67  4872.4 1481.41
  4921.8 1481.56  4950.3 1482.53  4979.5 1480.23  4981.1 1480.18  5004.2 1479.90
  5006.9 1479.40  5010.2 1479.90  5049.7 1481.34  5151.2 1482.30  5234.0 1483.06
  5262.3 1483.70  5269.2 1484.53  5297.6 1484.27  5523.9 1489.01  5567.2 1490.63
  5581.2 1491.86  5608.9 1491.29  5786.4 1496.07  5847.6 1496.49  5855.1 1496.79
#Mann=9,-1,0
  4182.2    0.05       0  4979.5     0.1       0  4981.1    0.05       0
  5004.2   0.035       0  5010.2    0.05       0  5151.2     0.1       0
  5523.9    0.05       0  5567.2     0.1       0  5847.6    0.05       0
Bank Sta=5004.2,5010.2
Exp/Cntr=0.3,0.1

Type RM Length L Ch R = 1,6696,381,381,381
BEGIN DESCRIPTION:
UNT068 IN SNOGR 14.0
END DESCRIPTION:
XS GIS Cut Line= 3
      2813602.74     10047805.98      2814351.44     10047176.65
      2814481.18     10046646.86
#Sta/Elev= 30
  4306.8 1484.66  4387.4 1482.89  4497.2 1481.53  4518.4 1480.30  4573.1 1479.75
  4640.4 1479.29  4809.8 1478.70  4873.5 1478.82  4887.8 1478.96  4915.2 1479.98
  4929.5 1480.02  4958.1 1479.19  4972.4 1478.13  4980.2 1477.99  4998.0 1476.87
  5000.7 1476.37  5004.0 1476.87  5007.5 1477.47  5029.6 1477.93  5050.4 1479.07
  5099.9 1480.35  5107.6 1480.06  5175.3 1481.34  5249.4 1482.57  5270.3 1483.30
  5459.6 1487.62  5677.7 1491.89  5709.3 1492.68  5756.1 1493.13  5830.3 1494.59
#Mann=8,-1,0
  4306.8    0.05       0  4387.4     0.1       0  4573.1    0.05       0
  4640.4     0.1       0  4998.0    0.07       0  5004.0     0.1       0
  5175.3    0.05       0  5677.7     0.1       0
Bank Sta=4998,5004
Exp/Cntr=0.3,0.1

Type RM Length L Ch R = 1,6315,499,499,499
BEGIN DESCRIPTION:
UNT068 IN SNOGR 13.0
END DESCRIPTION:
XS GIS Cut Line= 3
      2813802.77     10047743.34      2814288.89     10047699.93
      2815573.55     10046875.32
#Sta/Elev= 30
  4378.8 1480.39  4483.6 1479.15  4615.4 1478.24  4658.0 1478.37  4725.9 1477.33
  4796.1 1477.28  4878.2 1476.53  4943.4 1477.03  4964.5 1476.43  4991.9 1474.88
  4994.6 1474.38  4997.9 1474.88  5037.2 1476.59  5088.7 1476.46  5149.4 1477.19
  5370.1 1479.33  5463.9 1481.07  5515.5 1482.57  5573.0 1483.36  5682.0 1485.79
  5703.1 1485.79  5733.5 1486.98  5739.4 1486.73  5827.3 1488.67  5943.1 1490.16
  6042.8 1492.08  6097.5 1492.62  6244.1 1495.15  6347.9 1496.15  6393.4 1497.07
#Mann=8,-1,0
  4378.8    0.05       0  4483.6     0.1       0  4991.9    0.07       0
  4997.9     0.1       0  5149.4    0.05       0  5943.1     0.1       0
  6097.5    0.05       0  6244.1     0.1       0
Bank Sta=4991.9,4997.9
Exp/Cntr=0.3,0.1

Type RM Length L Ch R = 1,5816,344,344,344
BEGIN DESCRIPTION:
UNT068 IN SNOGR 12.0
END DESCRIPTION:
XS GIS Cut Line= 3
      2813768.06     10047873.54      2814245.48     10047908.27
      2815252.44     10048377.02
#Sta/Elev= 30
  4129.7 1482.59  4337.4 1480.18  4350.7 1480.81  4410.8 1480.66  4451.0 1479.51
  4601.3 1478.62  4637.6 1477.70  4817.2 1475.76  4865.0 1475.05  4916.3 1475.41
  4953.6 1474.23  4962.0 1473.07  4967.5 1473.52  4994.7 1470.90  4997.5 1470.40
  5000.7 1470.90  5030.7 1472.24  5036.2 1471.87  5041.9 1472.90  5059.0 1473.88
  5156.1 1473.90  5247.6 1477.25  5321.7 1477.95  5390.4 1480.72  5395.9 1480.09
  5408.5 1480.45  5491.1 1481.43  5587.6 1482.04  5704.5 1480.88  5719.1 1480.68
#Mann=9,-1,0
  4129.7    0.08       0  4637.6     0.1       0  4817.2    0.05       0
  4994.7    0.04       0  5000.7    0.05       0  5408.5     0.1       0
  5491.1    0.05       0  5587.6     0.1       0  5704.5    0.05       0
Bank Sta=4994.7,5000.7
Exp/Cntr=0.3,0.1

Type RM Length L Ch R = 1,5472,565,565,565
BEGIN DESCRIPTION:
UNT068 IN SNOGR 11.0
END DESCRIPTION:
XS GIS Cut Line= 3
      2813802.82     10048081.88      2814176.04     10048133.96
      2815094.82     10048567.35
#Sta/Elev= 30
  4021.0 1485.73  4214.4 1482.65  4258.9 1482.58  4309.4 1480.52  4339.7 1480.70
  4453.1 1478.09  4504.2 1478.01  4640.8 1475.36  4874.1 1473.24  4953.5 1473.28
  4964.4 1472.71  4970.8 1471.36  4976.3 1471.71  4993.5 1469.61  5005.6 1469.19
  5008.4 1468.69  5011.6 1469.19  5021.8 1469.57  5039.1 1472.00  5061.9 1473.37
  5119.2 1472.82  5164.0 1473.22  5204.1 1475.05  5209.6 1474.62  5226.8 1475.83
  5232.4 1475.52  5249.6 1476.79  5255.1 1476.13  5295.2 1477.84  5413.7 1479.55
#Mann=3,-1,0
  4021.0    0.05       0  5005.6    0.04       0  5011.6    0.05       0
Bank Sta=5005.6,5011.6
Exp/Cntr=0.3,0.1

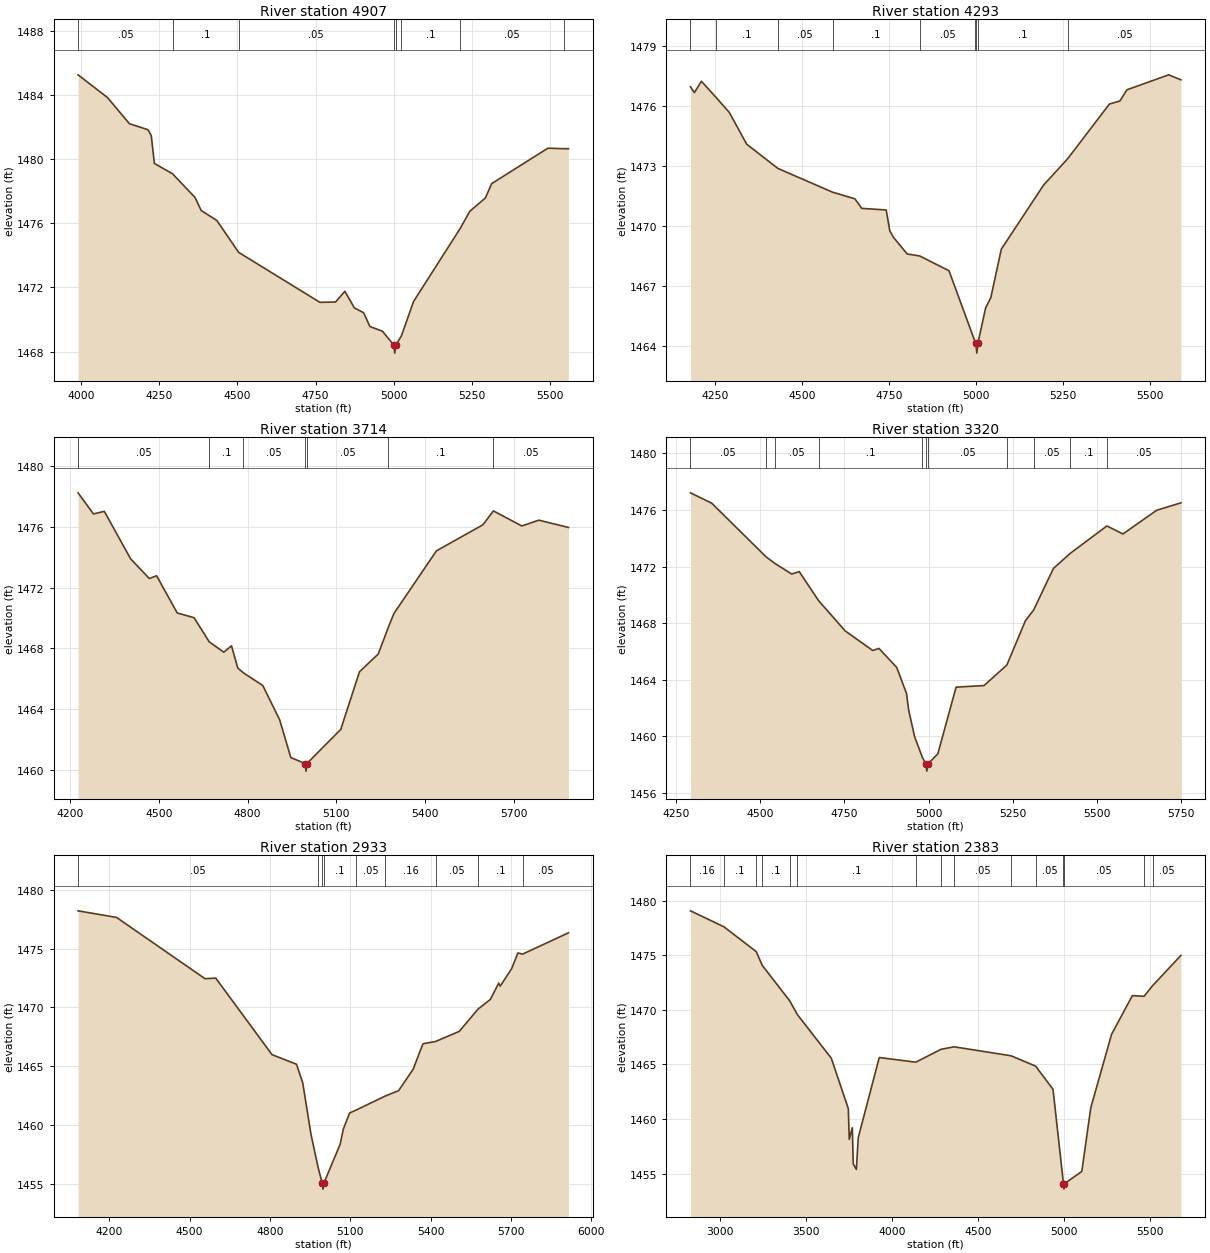
Type RM Length L Ch R = 1,4907,614,614,614
BEGIN DESCRIPTION:
UNT068 IN SNOGR 10.0
END DESCRIPTION:
XS GIS Cut Line= 2
      2813794.07     10048932.57      2815364.37     10048949.92
#Sta/Elev= 30
  3989.5 1485.27  4083.9 1483.85  4153.9 1482.22  4213.9 1481.84  4223.9 1481.48
  4233.9 1479.74  4292.2 1479.09  4363.9 1477.62  4383.9 1476.80  4433.9 1476.18
  4503.7 1474.19  4763.9 1471.07  4814.0 1471.09  4844.0 1471.76  4874.0 1470.73
  4904.0 1470.42  4924.0 1469.56  4964.0 1469.27  5001.0 1468.40  5003.7 1467.90
  5007.0 1468.40  5024.8 1468.97  5064.0 1471.13  5212.5 1475.66  5244.0 1476.75
  5294.0 1477.59  5314.0 1478.48  5494.0 1480.69  5545.5 1480.66  5559.9 1480.66
#Mann=8,-1,0
  3989.5    0.05       0  4292.2     0.1       0  4503.7    0.05       0
  5001.0   0.035       0  5007.0    0.05       0  5024.8     0.1       0
  5212.5    0.05       0  5545.5     0.1       0
Bank Sta=5001,5007
Exp/Cntr=0.3,0.1

Type RM Length L Ch R = 1,4293,579,579,579
BEGIN DESCRIPTION:
UNT068 IN SNOGR 9.0
END DESCRIPTION:
XS GIS Cut Line= 2
      2814037.20     10049600.97      2815443.42     10049514.17
#Sta/Elev= 30
  4179.3 1476.97  4190.6 1476.68  4210.6 1477.25  4252.8 1476.44  4290.8 1475.69
  4340.9 1474.10  4430.3 1472.89  4587.5 1471.70  4651.5 1471.37  4671.5 1470.89
  4741.6 1470.81  4751.7 1469.78  4761.7 1469.46  4801.8 1468.61  4837.8 1468.51
  4922.0 1467.77  4997.3 1464.20  4999.1 1464.15  5001.9 1463.65  5005.1 1464.15
  5027.2 1465.91  5042.2 1466.43  5072.3 1468.85  5193.5 1472.05  5263.2 1473.38
  5382.9 1476.11  5412.9 1476.26  5433.0 1476.82  5553.2 1477.57  5588.2 1477.32
#Mann=9,-1,0
  4179.3    0.05       0  4252.8     0.1       0  4430.3    0.05       0
  4587.5     0.1       0  4837.8    0.05       0  4997.3     0.1       0
  4999.1    0.07       0  5005.1     0.1       0  5263.2    0.05       0
Bank Sta=4999.1,5005.1
Exp/Cntr=0.3,0.1

Type RM Length L Ch R = 1,3714,394,394,394
BEGIN DESCRIPTION:
UNT068 IN SNOGR 8.0
END DESCRIPTION:
XS GIS Cut Line= 2
      2814236.79     10050356.19      2815807.97     10049826.67
#Sta/Elev= 30
  4226.7 1478.24  4278.7 1476.85  4315.4 1477.02  4404.6 1473.89  4467.6 1472.60
  4492.3 1472.78  4562.0 1470.33  4618.9 1470.02  4670.2 1468.43  4719.4 1467.75
  4745.5 1468.17  4766.6 1466.71  4785.7 1466.39  4851.1 1465.56  4908.3 1463.30
  4946.0 1460.81  4994.5 1460.42  4997.3 1459.92  5000.5 1460.42  5114.9 1462.67
  5178.2 1466.46  5241.5 1467.63  5274.6 1469.33  5294.3 1470.29  5438.3 1474.42
  5595.7 1476.14  5630.9 1477.05  5727.0 1476.06  5784.6 1476.44  5884.7 1475.96
#Mann=7,-1,0
  4226.7    0.05       0  4670.2     0.1       0  4785.7    0.05       0
  4994.5   0.035       0  5000.5    0.05       0  5274.6     0.1       0
  5630.9    0.05       0
Bank Sta=4994.5,5000.5
Exp/Cntr=0.3,0.1

Type RM Length L Ch R = 1,3320,387,387,387
BEGIN DESCRIPTION:
UNT068 IN SNOGR 7.0
END DESCRIPTION:
XS GIS Cut Line= 2
      2814410.40     10050746.82      2815754.68     10050183.08
#Sta/Elev= 30
  4292.3 1477.21  4355.3 1476.48  4516.7 1472.69  4544.3 1472.20  4593.0 1471.47
  4615.5 1471.64  4673.3 1469.58  4751.9 1467.45  4834.1 1466.06  4852.4 1466.21
  4905.4 1464.86  4934.6 1463.01  4940.8 1461.85  4958.4 1459.97  4981.5 1458.51
  4992.0 1458.03  4994.8 1457.53  4998.0 1458.03  5027.6 1458.76  5081.8 1463.47
  5164.8 1463.58  5232.6 1465.03  5287.8 1468.16  5312.2 1468.92  5371.3 1471.87
  5421.2 1472.93  5530.1 1474.87  5577.7 1474.30  5678.2 1475.98  5750.0 1476.50
#Mann=11,-1,0
  4292.3    0.05       0  4516.7     0.1       0  4544.3    0.05       0
  4673.3     0.1       0  4981.5    0.05       0  4992.0   0.035       0
  4998.0    0.05       0  5232.6     0.1       0  5312.2    0.05       0
  5421.2     0.1       0  5530.1    0.05       0
Bank Sta=4992,4998
Exp/Cntr=0.3,0.1

Type RM Length L Ch R = 1,2933,550,550,550
BEGIN DESCRIPTION:
UNT068 IN SNOGR 6.0
END DESCRIPTION:
XS GIS Cut Line= 4
      2814314.97     10050903.06      2815122.22     10050859.65
      2815660.42     10050625.28      2815886.10     10050252.04
#Sta/Elev= 30
  4083.7 1478.21  4227.4 1477.65  4557.9 1472.44  4597.9 1472.49  4808.2 1465.98
  4899.4 1465.17  4922.8 1463.59  4953.5 1459.23  4980.5 1456.37  4995.6 1455.05
  4998.3 1454.55  5001.6 1455.05  5062.5 1458.36  5074.3 1459.64  5097.8 1461.02
  5122.0 1461.27  5231.7 1462.47  5280.7 1462.92  5335.2 1464.74  5371.8 1466.91
  5418.7 1467.10  5507.3 1467.96  5577.8 1469.86  5623.7 1470.68  5654.7 1472.06
  5660.5 1471.81  5703.2 1473.30  5726.3 1474.63  5744.0 1474.53  5915.3 1476.34
#Mann=9,-1,0
  4083.7    0.05       0  4980.5     0.1       0  4995.6    0.07       0
  5001.6     0.1       0  5122.0    0.05       0  5231.7    0.16       0
  5418.7    0.05       0  5577.8     0.1       0  5744.0    0.05       0
Bank Sta=4995.6,5001.6
Exp/Cntr=0.3,0.1

Type RM Length L Ch R = 1,2383,530,530,530
BEGIN DESCRIPTION:
UNT068 IN SNOGR 5.0
END DESCRIPTION:
XS GIS Cut Line= 3
      2813776.76     10051988.12      2815634.37     10051172.15
      2815972.20     10050427.20
#Sta/Elev= 30
  2830.2 1479.08  3024.0 1477.62  3212.0 1475.34  3247.3 1474.07  3405.6 1470.85
  3450.9 1469.57  3647.5 1465.58  3746.4 1460.96  3751.8 1458.14  3769.7 1459.20
  3775.2 1455.89  3793.1 1455.39  3804.1 1458.30  3926.2 1465.64  4137.8 1465.21
  4284.4 1466.39  4360.5 1466.62  4690.9 1465.80  4833.7 1464.85  4934.7 1462.73
  4995.4 1454.08  4998.2 1453.58  5001.4 1454.08  5101.8 1455.20  5153.9 1461.03
  5274.6 1467.76  5395.4 1471.31  5463.3 1471.25  5513.3 1472.23  5677.1 1474.99
#Mann=15,-1,0
  2830.2    0.16       0  3024.0     0.1       0  3212.0    0.16       0
  3247.3     0.1       0  3405.6    0.16       0  3450.9     0.1       0
  4137.8    0.05       0  4284.4     0.1       0  4360.5    0.05       0
  4690.9     0.1       0  4833.7    0.05       0  4995.4   0.035       0
  5001.4    0.05       0  5463.3     0.1       0  5513.3    0.05       0
Bank Sta=4995.4,5001.4
Exp/Cntr=0.3,0.1

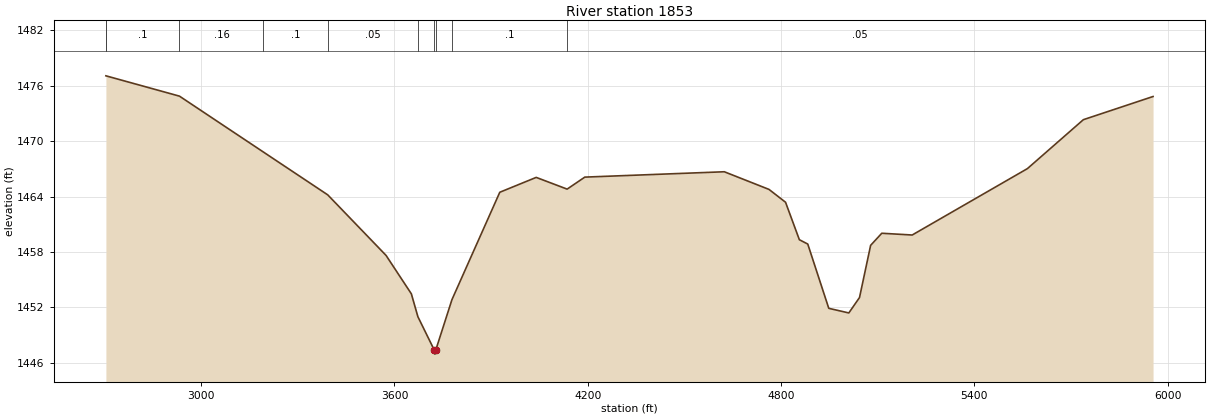
Type RM Length L Ch R = 1,1853,0,0,0
BEGIN DESCRIPTION:
UNT068 IN SNOGR 4.0
END DESCRIPTION:
XS GIS Cut Line= 4
      2814080.58     10051988.12      2816155.21     10051285.00
      2816233.33     10050998.54      2816077.07     10050251.98
#Sta/Elev= 30
  2704.4 1477.07  2705.6 1477.06  2932.7 1474.87  3193.1 1468.82  3392.9 1464.18
  3574.0 1457.62  3652.5 1453.46  3672.8 1450.98  3722.8 1447.43  3725.6 1446.93
  3728.8 1447.43  3778.5 1452.83  3927.0 1464.46  4040.0 1466.07  4136.0 1464.80
  4190.9 1466.10  4623.9 1466.68  4762.5 1464.77  4813.9 1463.38  4856.8 1459.32
  4882.9 1458.85  4948.1 1451.89  5010.3 1451.39  5043.5 1453.06  5078.0 1458.71
  5112.6 1460.02  5207.0 1459.83  5564.6 1467.02  5738.3 1472.32  5954.6 1474.83
#Mann=10,-1,0
  2704.4    0.16       0  2705.6     0.1       0  2932.7    0.16       0
  3193.1     0.1       0  3392.9    0.05       0  3672.8    0.16       0
  3722.8   0.035       0  3728.8    0.16       0  3778.5     0.1       0
  4136.0    0.05       0
Bank Sta=3722.8,3728.8
Exp/Cntr=0.3,0.1

Chan Stop Cuts=-1