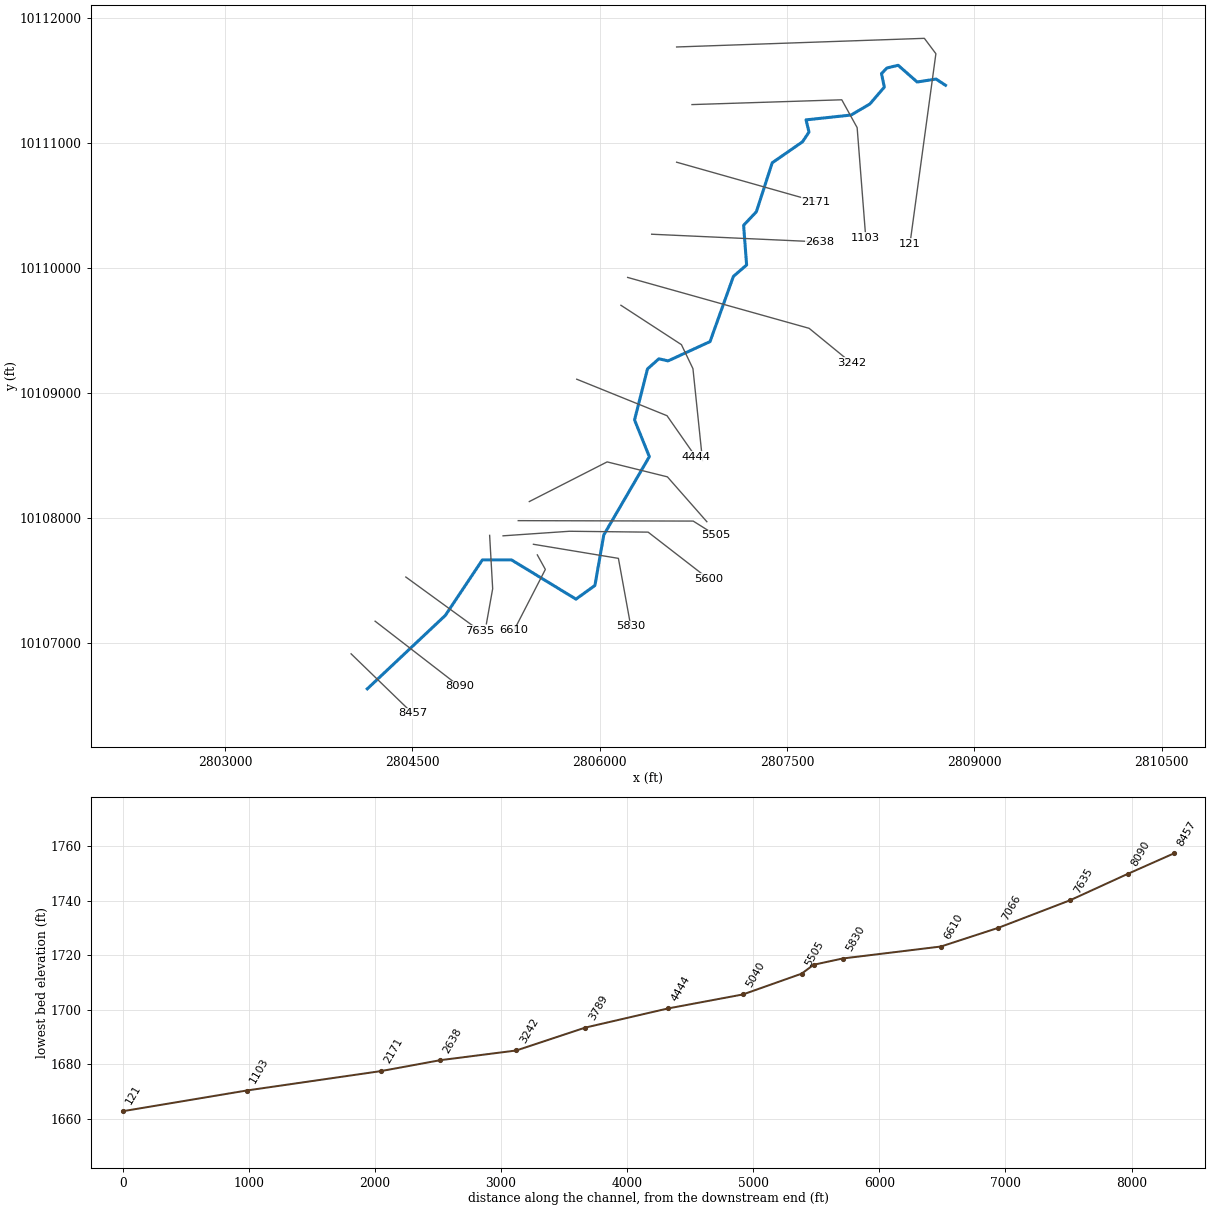
--- UNT069 IN NNOGR.prj (project) ---

Proj Title=UNT069 IN NNOGR Base Level Engineering
Current Plan=p01
Default Exp/Contr=0.3,0.1
English Units
Geom File=g01
Flow File=f01
Plan File=p01
BEGIN DESCRIPTION:
UNT069 IN NNOGR
END DESCRIPTION:

--- UNT069 IN NNOGR.p01 (plan) ---

Plan Title=Multiple Run
Short Identifier=Multiple
Geom File=g01
Flow File=f01
Subcritical Flow
K Sum by GR= 0
Std Step Tol= 0.01
Critical Tol= 0.01
Num of Std Step Trials= 20
Max Error Tol= 0.3
Flow Tol Ratio= 0.001
Split Flow NTrial= 30
Split Flow Tol= 0.02
Split Flow Ratio= 0.02
Log Output Level= 0
Friction Slope Method= 1
Unsteady Friction Slope Method= 2
Unsteady Bridges Friction Slope Method= 1
Parabolic Critical Depth
Global Vel Dist=  1 , 1 , 1
Global Log Level= 0
CheckData=True
Encroach Param= -1, 0, 0, 0
BEGIN DESCRIPTION:
Multiple Run
END DESCRIPTION:

--- UNT069 IN NNOGR.f01 (steady flow) ---

Flow Title=Multiple
Number of Profiles=7
Profile Names=10-year,25-year,50-year,1pct_min,100-year,1pct_plu,500-year
River Rch & RM= UNT069 IN NNOGR,Reach-1,8457
     879    1271    1611    1495    2022    2735    3196
River Rch & RM= UNT069 IN NNOGR,Reach-1,3242
    1127    1649    2106    1967    2660    3598    4262
Boundary for River Rch & Prof#=UNT069 IN NNOGR,Reach-1,1
Up Type=0
Dn Type=3
Dn Slope=0.005
Boundary for River Rch & Prof#=UNT069 IN NNOGR,Reach-1,2
Up Type=0
Dn Type=3
Dn Slope=0.005
Boundary for River Rch & Prof#=UNT069 IN NNOGR,Reach-1,3
Up Type=0
Dn Type=3
Dn Slope=0.005
Boundary for River Rch & Prof#=UNT069 IN NNOGR,Reach-1,4
Up Type=0
Dn Type=3
Dn Slope=0.005
Boundary for River Rch & Prof#=UNT069 IN NNOGR,Reach-1,5
Up Type=0
Dn Type=3
Dn Slope=0.005
Boundary for River Rch & Prof#=UNT069 IN NNOGR,Reach-1,6
Up Type=0
Dn Type=3
Dn Slope=0.005
Boundary for River Rch & Prof#=UNT069 IN NNOGR,Reach-1,7
Up Type=0
Dn Type=3
Dn Slope=0.005

--- UNT069 IN NNOGR.g01 (geometry) ---

Geom Title=Existing Conditions

River Reach=UNT069 IN NNOGR,Reach-1
Reach XY= 30
      2804138.21     10106630.19      2804763.49     10107218.62
      2805059.85     10107662.98      2805293.76     10107662.45
      2805809.35     10107348.68      2805961.02     10107457.83
      2806032.03     10107862.50      2806396.92     10108489.45
      2806278.43     10108783.82      2806382.12     10109192.18
      2806473.23     10109273.31      2806547.00     10109256.66
      2806883.15     10109411.18      2807070.16     10109933.25
      2807175.86     10110024.74      2807151.89     10110342.52
      2807253.96     10110450.80      2807380.84     10110842.88
      2807623.53     10111011.13      2807675.69     10111089.40
      2807651.76     10111186.66      2808012.75     10111225.47
      2808163.22     10111314.09      2808278.71     10111448.86
      2808255.93     10111557.49      2808300.03     10111602.28
      2808389.46     10111623.85      2808541.69     10111490.13
      2808693.16     10111513.57      2808768.47     10111463.73

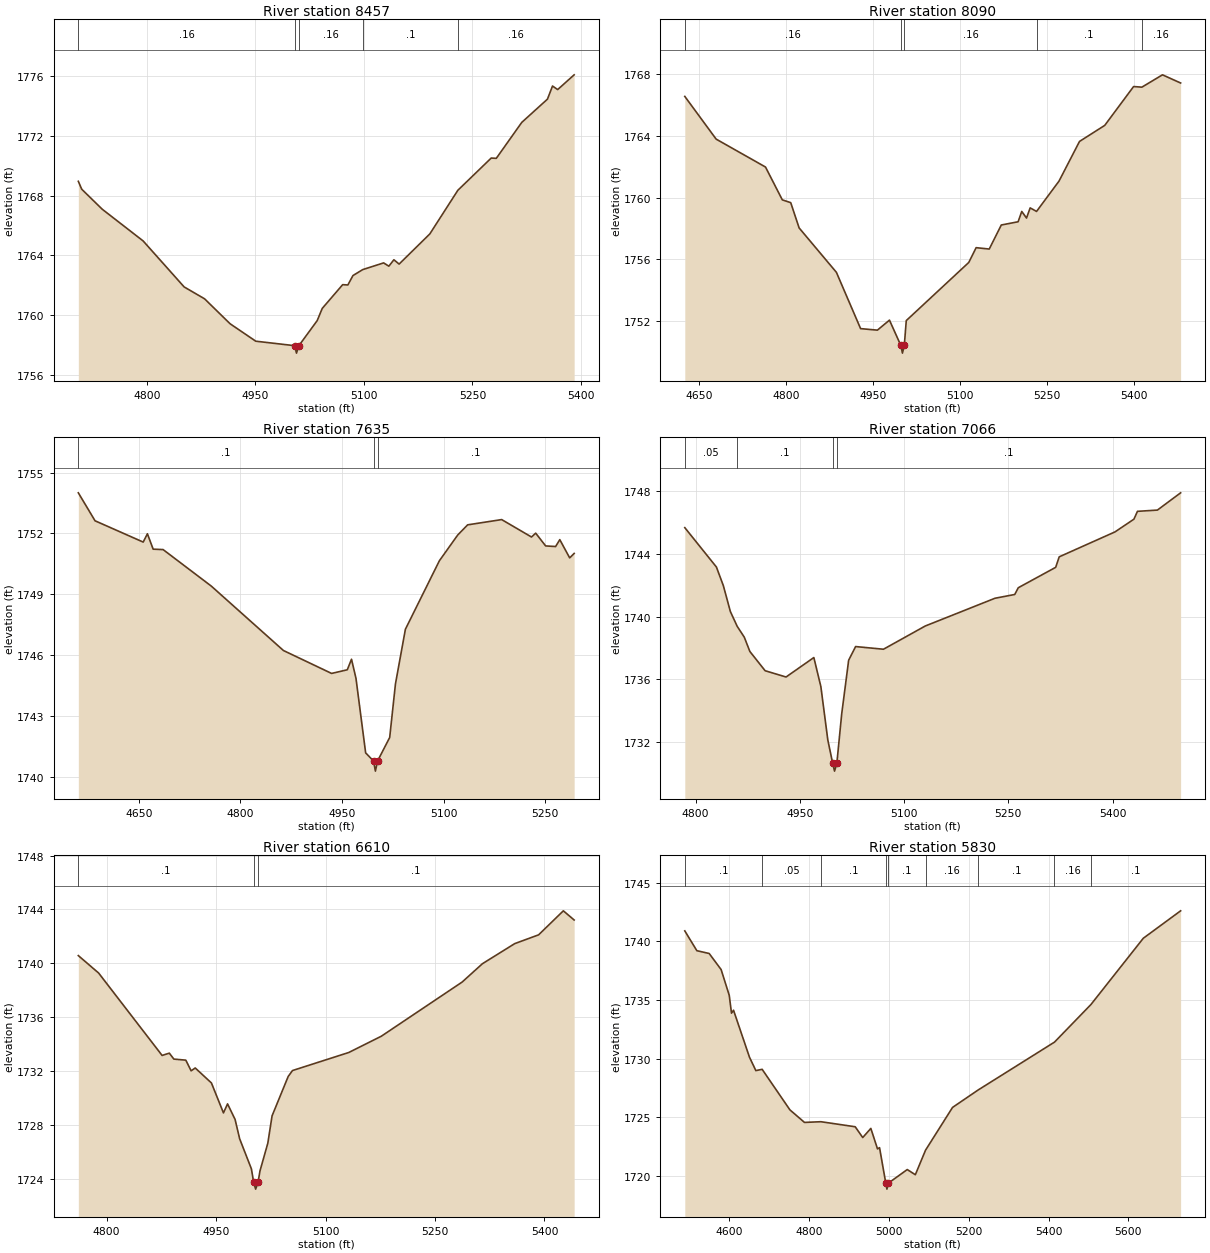
Type RM Length L Ch R = 1,8457,367,367,367
BEGIN DESCRIPTION:
UNT069 IN NNOGR 14.0
END DESCRIPTION:
XS GIS Cut Line= 2
      2804008.57     10106910.53      2804500.71     10106433.77
#Sta/Elev= 30
  4705.4 1768.97  4710.1 1768.44  4738.4 1767.10  4795.0 1764.97  4851.6 1761.89
  4879.9 1761.09  4915.1 1759.42  4950.6 1758.25  5004.2 1757.95  5006.9 1757.45
  5010.2 1757.95  5035.5 1759.63  5042.5 1760.45  5070.7 1762.04  5077.9 1762.02
  5084.9 1762.65  5098.4 1763.05  5127.3 1763.50  5134.5 1763.28  5141.5 1763.71
  5148.7 1763.42  5191.1 1765.44  5229.9 1768.37  5276.0 1770.53  5283.0 1770.51
  5318.2 1772.92  5353.7 1774.48  5360.7 1775.36  5367.8 1775.12  5390.6 1776.11
#Mann=5,-1,0
  4705.4    0.16       0  5004.2    0.07       0  5010.2    0.16       0
  5098.4     0.1       0  5229.9    0.16       0
Bank Sta=5004.2,5010.2
Exp/Cntr=0.3,0.1

Type RM Length L Ch R = 1,8090,455,455,455
BEGIN DESCRIPTION:
UNT069 IN NNOGR 13.0
END DESCRIPTION:
XS GIS Cut Line= 2
      2804200.82     10107171.97      2804877.53     10106649.06
#Sta/Elev= 30
  4624.9 1766.56  4679.0 1763.79  4764.1 1761.98  4793.1 1759.85  4807.6 1759.67
  4822.1 1758.03  4886.4 1755.15  4928.1 1751.50  4957.1 1751.40  4977.9 1752.05
  4997.5 1750.41  5000.3 1749.91  5003.5 1750.41  5006.9 1752.02  5114.7 1755.79
  5127.4 1756.75  5150.0 1756.66  5170.8 1758.22  5199.8 1758.43  5206.1 1759.10
  5214.3 1758.67  5220.6 1759.33  5231.6 1759.10  5270.4 1761.07  5305.7 1763.64
  5349.2 1764.68  5399.0 1767.20  5413.3 1767.16  5448.8 1767.96  5480.1 1767.43
#Mann=5,-1,0
  4624.9    0.16       0  4997.5    0.07       0  5003.5    0.16       0
  5231.6     0.1       0  5413.3    0.16       0
Bank Sta=4997.5,5003.5
Exp/Cntr=0.3,0.1

Type RM Length L Ch R = 1,7635,569,569,569
BEGIN DESCRIPTION:
UNT069 IN NNOGR 12.0
END DESCRIPTION:
XS GIS Cut Line= 2
      2804446.87     10107525.72      2805039.02     10107095.07
#Sta/Elev= 30
  4560.6 1754.00  4585.3 1752.62  4656.4 1751.57  4662.6 1751.98  4671.1 1751.22
  4685.8 1751.20  4756.9 1749.40  4863.5 1746.22  4934.6 1745.09  4957.8 1745.27
  4964.0 1745.79  4970.6 1744.85  4984.9 1741.17  4996.5 1740.77  4999.3 1740.27
  5002.5 1740.77  5020.4 1741.93  5028.9 1744.57  5043.6 1747.27  5093.8 1750.65
  5120.9 1751.92  5135.5 1752.42  5185.8 1752.68  5229.8 1751.82  5236.0 1752.01
  5250.7 1751.38  5265.4 1751.35  5271.6 1751.69  5286.2 1750.79  5292.8 1751.01
#Mann=3,-1,0
  4560.6     0.1       0  4996.5    0.07       0  5002.5     0.1       0
Bank Sta=4996.5,5002.5
Exp/Cntr=0.3,0.1

Type RM Length L Ch R = 1,7066,456,456,456
BEGIN DESCRIPTION:
UNT069 IN NNOGR 11.0
END DESCRIPTION:
XS GIS Cut Line= 3
      2805117.98     10107859.18      2805142.29     10107432.07
      2805091.94     10107150.84
#Sta/Elev= 30
  4784.4 1745.67  4829.9 1743.16  4839.9 1741.97  4850.0 1740.32  4859.8 1739.38
  4870.0 1738.69  4878.0 1737.78  4900.0 1736.55  4930.1 1736.15  4970.1 1737.39
  4980.2 1735.54  4990.2 1732.14  4997.2 1730.65  4999.9 1730.15  5003.2 1730.65
  5010.2 1733.80  5020.2 1737.22  5030.2 1738.09  5070.3 1737.92  5130.4 1739.40
  5230.8 1741.17  5259.2 1741.41  5264.3 1741.84  5318.1 1743.14  5323.2 1743.81
  5403.5 1745.40  5430.7 1746.21  5435.8 1746.71  5464.5 1746.79  5497.9 1747.89
#Mann=4,-1,0
  4784.4    0.05       0  4859.8     0.1       0  4997.2    0.07       0
  5003.2     0.1       0
Bank Sta=4997.2,5003.2
Exp/Cntr=0.3,0.1

Type RM Length L Ch R = 1,6610,780,780,780
BEGIN DESCRIPTION:
UNT069 IN NNOGR 10.0
END DESCRIPTION:
XS GIS Cut Line= 3
      2805499.95     10107702.87      2805564.16     10107586.58
      2805314.15     10107100.44
#Sta/Elev= 30
  4761.2 1740.58  4789.0 1739.29  4876.0 1733.18  4885.9 1733.35  4892.1 1732.91
  4908.5 1732.83  4915.8 1732.04  4921.4 1732.25  4943.6 1731.14  4960.1 1728.92
  4965.7 1729.59  4976.0 1728.44  4982.3 1727.00  4998.4 1724.77  5001.5 1723.77
  5004.2 1723.27  5007.5 1723.77  5010.1 1724.61  5020.9 1726.68  5026.7 1728.70
  5048.8 1731.62  5054.7 1732.06  5131.9 1733.40  5176.3 1734.60  5287.2 1738.62
  5315.0 1739.98  5359.3 1741.47  5392.0 1742.12  5425.9 1743.90  5440.7 1743.22
#Mann=3,-1,0
  4761.2     0.1       0  5001.5    0.07       0  5007.5     0.1       0
Bank Sta=5001.5,5007.5
Exp/Cntr=0.3,0.1

Type RM Length L Ch R = 1,5830,230,230,230
BEGIN DESCRIPTION:
Mapping XS 92456677
END DESCRIPTION:
XS GIS Cut Line= 3
      2805468.66     10107787.97      2806149.23     10107675.12
      2806248.19     10107131.72
#Sta/Elev= 30
  4488.7 1740.90  4518.9 1739.21  4549.8 1738.97  4579.7 1737.60  4600.0 1735.41
  4605.7 1733.88  4610.8 1734.13  4650.7 1730.13  4666.7 1728.98  4682.5 1729.09
  4752.1 1725.63  4788.6 1724.56  4829.7 1724.62  4915.6 1724.19  4934.5 1723.27
  4954.8 1724.05  4971.5 1722.30  4976.6 1722.41  4992.3 1719.37  4995.1 1718.87
  4998.3 1719.37  5046.0 1720.54  5066.3 1720.10  5091.8 1722.19  5159.5 1725.84
  5223.8 1727.33  5414.9 1731.41  5506.3 1734.62  5637.4 1740.27  5730.9 1742.61
#Mann=9,-1,0
  4488.7     0.1       0  4682.5    0.05       0  4829.7     0.1       0
  4992.3    0.07       0  4998.3     0.1       0  5091.8    0.16       0
  5223.8     0.1       0  5414.9    0.16       0  5506.3     0.1       0
Bank Sta=4992.3,4998.3
Exp/Cntr=0.3,0.1

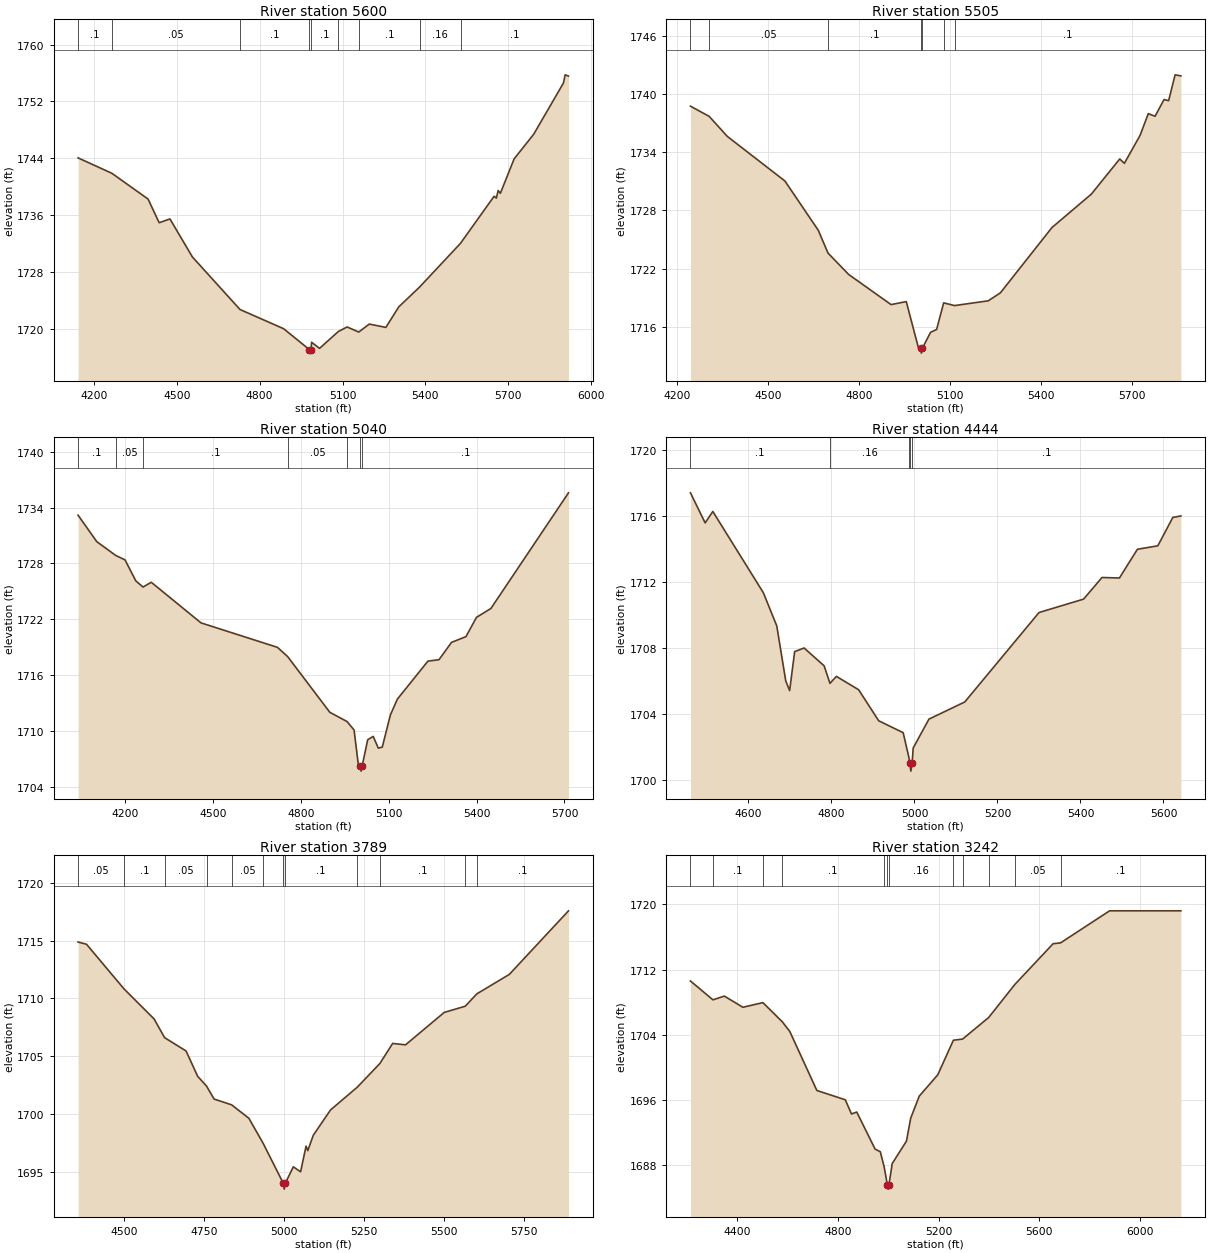
Type RM Length L Ch R = 1,5600,95,95,95
BEGIN DESCRIPTION:
Mapping XS dbc731a7
END DESCRIPTION:
XS GIS Cut Line= 4
      2805225.58     10107855.68      2805756.87     10107892.14
      2806387.08     10107885.19      2806871.49     10107510.17
#Sta/Elev= 30
  4142.7 1744.06  4265.0 1741.89  4396.2 1738.26  4436.3 1734.93  4475.4 1735.46
  4556.6 1730.11  4729.0 1722.71  4886.8 1720.01  4980.1 1717.07  4982.8 1716.57
  4986.1 1717.07  4988.1 1718.10  5016.9 1717.24  5085.1 1719.62  5116.9 1720.25
  5158.8 1719.54  5196.9 1720.66  5256.9 1720.19  5303.7 1723.08  5379.7 1725.90
  5527.2 1732.03  5648.9 1738.66  5657.0 1738.39  5663.4 1739.46  5671.5 1739.07
  5721.3 1743.92  5791.9 1747.37  5899.7 1754.59  5906.0 1755.75  5918.1 1755.57
#Mann=9,-1,0
  4142.7     0.1       0  4265.0    0.05       0  4729.0     0.1       0
  4980.1    0.07       0  4986.1     0.1       0  5085.1    0.16       0
  5158.8     0.1       0  5379.7    0.16       0  5527.2     0.1       0
Bank Sta=4980.1,4986.1
Exp/Cntr=0.3,0.1

Type RM Length L Ch R = 1,5505,465,465,465
BEGIN DESCRIPTION:
UNT069 IN NNOGR 9.0
END DESCRIPTION:
XS GIS Cut Line= 3
      2805347.12     10107977.21      2806748.19     10107973.73
      2806930.49     10107859.15
#Sta/Elev= 30
  4245.3 1738.75  4307.0 1737.70  4366.6 1735.64  4556.6 1731.04  4666.6 1725.96
  4698.7 1723.61  4766.6 1721.41  4906.6 1718.30  4956.6 1718.61  4996.6 1713.86
  5003.6 1713.80  5006.4 1713.30  5009.6 1713.80  5036.6 1715.44  5056.6 1715.74
  5079.9 1718.48  5115.6 1718.20  5226.7 1718.69  5266.7 1719.51  5436.7 1726.24
  5566.7 1729.69  5660.1 1733.31  5675.4 1732.86  5727.2 1735.74  5754.3 1737.98
  5776.6 1737.71  5806.1 1739.43  5821.4 1739.32  5842.6 1741.98  5861.7 1741.87
#Mann=7,-1,0
  4245.3     0.1       0  4307.0    0.05       0  4698.7     0.1       0
  5003.6    0.07       0  5009.6     0.1       0  5079.9    0.16       0
  5115.6     0.1       0
Bank Sta=5003.6,5009.6
Exp/Cntr=0.3,0.1

Type RM Length L Ch R = 1,5040,596,596,596
BEGIN DESCRIPTION:
UNT069 IN NNOGR 8.0
END DESCRIPTION:
XS GIS Cut Line= 4
      2805435.69     10108129.98      2806058.95     10108447.69
      2806541.59     10108327.90      2806857.45     10107968.66
#Sta/Elev= 30
  4038.5 1733.18  4102.6 1730.33  4167.3 1728.85  4198.8 1728.38  4236.0 1726.11
  4260.4 1725.46  4288.6 1725.97  4458.3 1721.61  4719.5 1718.98  4754.3 1717.99
  4898.5 1712.00  4957.2 1711.01  4981.3 1710.10  4995.2 1706.53  5002.5 1706.18
  5005.2 1705.68  5008.5 1706.18  5027.8 1709.05  5046.7 1709.41  5064.0 1708.15
  5077.6 1708.26  5105.4 1711.72  5129.1 1713.41  5233.6 1717.50  5271.3 1717.65
  5314.0 1719.51  5363.4 1720.13  5399.4 1722.20  5448.8 1723.16  5713.7 1735.58
#Mann=7,-1,0
  4038.5     0.1       0  4167.3    0.05       0  4260.4     0.1       0
  4754.3    0.05       0  4957.2     0.1       0  5002.5    0.07       0
  5008.5     0.1       0
Bank Sta=5002.5,5008.5
Exp/Cntr=0.3,0.1

Type RM Length L Ch R = 1,4444,655,655,655
BEGIN DESCRIPTION:
UNT069 IN NNOGR 7.0
END DESCRIPTION:
XS GIS Cut Line= 3
      2805815.64     10109109.81      2806538.50     10108817.59
      2806768.58     10108487.81
#Sta/Elev= 30
  4460.2 1717.38  4495.6 1715.56  4514.1 1716.25  4635.8 1711.33  4668.2 1709.32
  4689.8 1705.99  4699.2 1705.40  4711.3 1707.76  4734.1 1707.98  4782.3 1706.90
  4796.4 1705.84  4811.9 1706.26  4865.5 1705.45  4913.8 1703.57  4972.8 1702.85
  4986.6 1701.35  4988.5 1701.02  4991.3 1700.52  4994.5 1701.02  4996.9 1701.92
  5034.9 1703.67  5121.2 1704.71  5300.2 1710.13  5407.5 1710.94  5451.9 1712.25
  5493.9 1712.22  5537.2 1713.96  5586.4 1714.17  5622.6 1715.89  5642.0 1715.98
#Mann=5,-1,0
  4460.2     0.1       0  4796.4    0.16       0  4986.6     0.1       0
  4988.5    0.07       0  4994.5     0.1       0
Bank Sta=4988.5,4994.5
Exp/Cntr=0.3,0.1

Type RM Length L Ch R = 1,3789,547,547,547
BEGIN DESCRIPTION:
UNT069 IN NNOGR 6.0
END DESCRIPTION:
XS GIS Cut Line= 4
      2806169.40     10109701.90      2806653.85     10109386.63
      2806746.12     10109194.38      2806822.89     10108457.41
#Sta/Elev= 30
  4357.1 1714.87  4383.5 1714.68  4500.6 1710.82  4594.6 1708.22  4627.5 1706.60
  4694.5 1705.45  4730.7 1703.26  4758.6 1702.41  4782.1 1701.29  4836.9 1700.79
  4890.7 1699.63  4935.2 1697.47  4998.4 1694.00  5001.2 1693.50  5004.4 1694.00
  5029.6 1695.43  5052.3 1695.00  5069.4 1697.22  5074.9 1696.83  5092.0 1698.16
  5145.9 1700.35  5229.1 1702.31  5299.9 1704.36  5340.0 1706.10  5380.2 1705.98
  5500.9 1708.78  5566.7 1709.32  5603.0 1710.39  5704.4 1712.07  5889.3 1717.57
#Mann=12,-1,0
  4357.1    0.05       0  4500.6     0.1       0  4627.5    0.05       0
  4758.6     0.1       0  4836.9    0.05       0  4935.2     0.1       0
  4998.4    0.07       0  5004.4     0.1       0  5229.1    0.16       0
  5299.9     0.1       0  5566.7    0.05       0  5603.0     0.1       0
Bank Sta=4998.4,5004.4
Exp/Cntr=0.3,0.1

Type RM Length L Ch R = 1,3242,604,604,604
BEGIN DESCRIPTION:
UNT069 IN NNOGR 5.0
END DESCRIPTION:
XS GIS Cut Line= 3
      2806223.25     10109924.90      2807676.58     10109517.35
      2808014.19     10109241.13
#Sta/Elev= 30
  4215.8 1710.61  4305.1 1708.30  4350.4 1708.76  4423.8 1707.39  4503.2 1707.96
  4580.1 1705.61  4609.8 1704.43  4717.3 1697.19  4830.0 1696.05  4854.7 1694.31
  4875.5 1694.55  4948.2 1690.01  4969.0 1689.68  4984.3 1687.82  4997.1 1685.60
  4999.9 1685.10  5003.1 1685.60  5016.1 1688.23  5072.8 1690.99  5089.5 1693.79
  5123.5 1696.50  5196.9 1699.11  5258.9 1703.35  5295.3 1703.49  5399.0 1706.14
  5502.8 1710.19  5654.5 1715.18  5683.9 1715.28  5878.6 1719.21  6161.4 1719.21
#Mann=12,-1,0
  4215.8    0.05       0  4305.1     0.1       0  4503.2    0.05       0
  4580.1     0.1       0  4984.3    0.16       0  4997.1    0.07       0
  5003.1    0.16       0  5258.9     0.1       0  5295.3    0.05       0
  5399.0     0.1       0  5502.8    0.05       0  5683.9     0.1       0
Bank Sta=4997.1,5003.1
Exp/Cntr=0.3,0.1

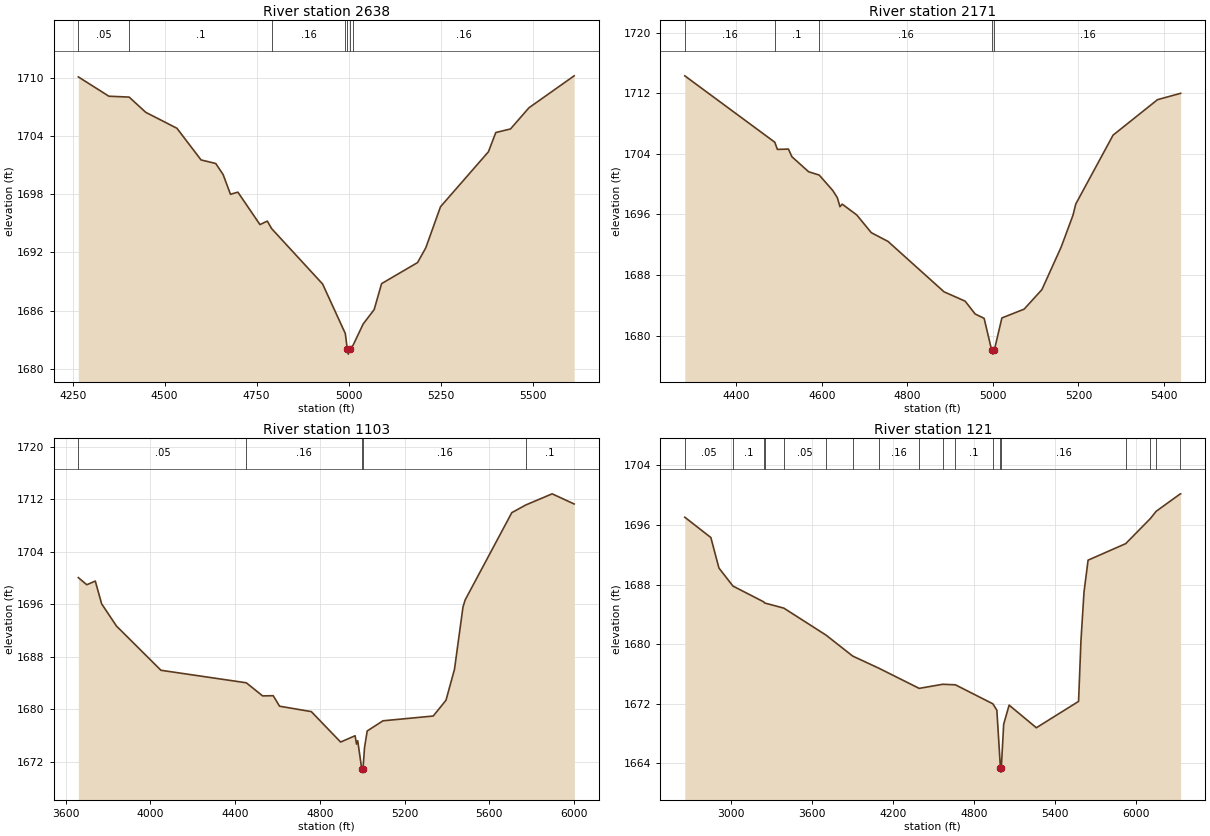
Type RM Length L Ch R = 1,2638,467,467,467
BEGIN DESCRIPTION:
UNT069 IN NNOGR 4.0
END DESCRIPTION:
XS GIS Cut Line= 2
      2806415.46     10110270.95      2807761.15     10110209.43
#Sta/Elev= 30
  4265.5 1710.08  4348.6 1708.09  4403.6 1708.00  4448.7 1706.43  4533.4 1704.79
  4598.9 1701.53  4638.9 1701.16  4658.9 1700.02  4678.9 1697.99  4699.0 1698.21
  4759.0 1694.87  4779.0 1695.23  4790.6 1694.46  4929.2 1688.75  4990.9 1683.65
  4996.3 1682.03  4999.0 1681.53  5002.3 1682.03  5011.9 1682.44  5039.3 1684.63
  5069.3 1686.12  5089.4 1688.79  5187.2 1690.96  5209.5 1692.48  5249.5 1696.71
  5379.7 1702.37  5399.7 1704.35  5439.7 1704.72  5489.8 1706.90  5612.6 1710.19
#Mann=7,-1,0
  4265.5    0.05       0  4403.6     0.1       0  4790.6    0.16       0
  4990.9     0.1       0  4996.3    0.07       0  5002.3     0.1       0
  5011.9    0.16       0
Bank Sta=4996.3,5002.3
Exp/Cntr=0.3,0.1

Type RM Length L Ch R = 1,2171,1068,1068,1068
BEGIN DESCRIPTION:
UNT069 IN NNOGR 3.0
END DESCRIPTION:
XS GIS Cut Line= 2
      2806615.45     10110847.67      2807730.43     10110532.39
#Sta/Elev= 30
  4280.1 1714.32  4490.4 1705.55  4496.5 1704.60  4522.3 1704.64  4530.4 1703.63
  4569.6 1701.64  4594.2 1701.21  4626.2 1699.15  4636.6 1698.22  4642.7 1697.03
  4647.9 1697.37  4681.9 1695.94  4715.9 1693.60  4755.0 1692.44  4886.0 1685.78
  4935.2 1684.55  4958.7 1682.85  4979.6 1682.28  4997.3 1678.05  5000.0 1677.55
  5003.3 1678.05  5021.1 1682.33  5073.0 1683.49  5114.6 1686.07  5159.8 1691.72
  5187.3 1695.91  5193.8 1697.39  5280.9 1706.48  5384.8 1711.17  5438.8 1712.01
#Mann=5,-1,0
  4280.1    0.16       0  4490.4     0.1       0  4594.2    0.16       0
  4997.3    0.07       0  5003.3    0.16       0
Bank Sta=4997.3,5003.3
Exp/Cntr=0.3,0.1

Type RM Length L Ch R = 1,1103,982,982,982
BEGIN DESCRIPTION:
UNT069 IN NNOGR 2.0
END DESCRIPTION:
XS GIS Cut Line= 4
      2806738.41     10111309.06      2807938.03     10111347.51
      2808061.07     10111124.51      2808130.28     10110240.15
#Sta/Elev= 30
  3659.2 1700.08  3699.3 1698.99  3739.3 1699.55  3769.3 1696.08  3839.3 1692.69
  4049.5 1685.94  4452.7 1684.03  4529.7 1682.03  4579.7 1682.06  4609.7 1680.46
  4759.8 1679.63  4898.0 1674.99  4966.5 1675.95  4973.2 1674.68  4978.9 1675.19
  4997.8 1670.90  5000.6 1670.40  5003.8 1670.90  5011.1 1674.17  5023.7 1676.68
  5098.1 1678.23  5335.6 1678.96  5395.8 1681.37  5435.9 1686.08  5476.0 1695.57
  5486.0 1696.65  5706.7 1709.99  5772.7 1711.16  5897.3 1712.86  6001.2 1711.31
#Mann=5,-1,0
  3659.2    0.05       0  4452.7    0.16       0  4997.8    0.07       0
  5003.8    0.16       0  5772.7     0.1       0
Bank Sta=4997.8,5003.8
Exp/Cntr=0.3,0.1

Type RM Length L Ch R = 1,121,0,0,0
BEGIN DESCRIPTION:
UNT069 IN NNOGR 1.0
END DESCRIPTION:
XS GIS Cut Line= 4
      2806615.43     10111770.45      2808599.35     10111839.66
      2808691.63     10111716.62      2808484.01     10110194.04
#Sta/Elev= 30
  2656.6 1697.04  2849.8 1694.31  2909.8 1690.21  3013.7 1687.79  3242.6 1685.66
  3248.0 1685.52  3390.7 1684.83  3703.9 1681.20  3901.1 1678.39  4098.3 1676.73
  4394.2 1674.05  4568.8 1674.60  4662.5 1674.53  4939.9 1671.98  4970.0 1671.12
  4996.6 1663.30  4999.4 1662.80  5002.6 1663.30  5020.5 1669.23  5060.8 1671.80
  5262.7 1668.76  5575.6 1672.30  5593.4 1680.46  5615.9 1686.97  5646.2 1691.27
  5925.1 1693.49  6108.5 1696.87  6150.6 1697.83  6329.4 1700.17  6332.2 1700.18
#Mann=18,-1,0
  2656.6    0.05       0  3013.7     0.1       0  3242.6    0.05       0
  3248.0     0.1       0  3390.7    0.05       0  3703.9    0.16       0
  3901.1     0.1       0  4098.3    0.16       0  4394.2     0.1       0
  4568.8    0.16       0  4662.5     0.1       0  4939.9    0.16       0
  4996.6    0.07       0  5002.6    0.16       0  5925.1     0.1       0
  6108.5    0.16       0  6150.6     0.1       0  6329.4    0.05       0
Bank Sta=4996.6,5002.6
Exp/Cntr=0.3,0.1

Chan Stop Cuts=-1