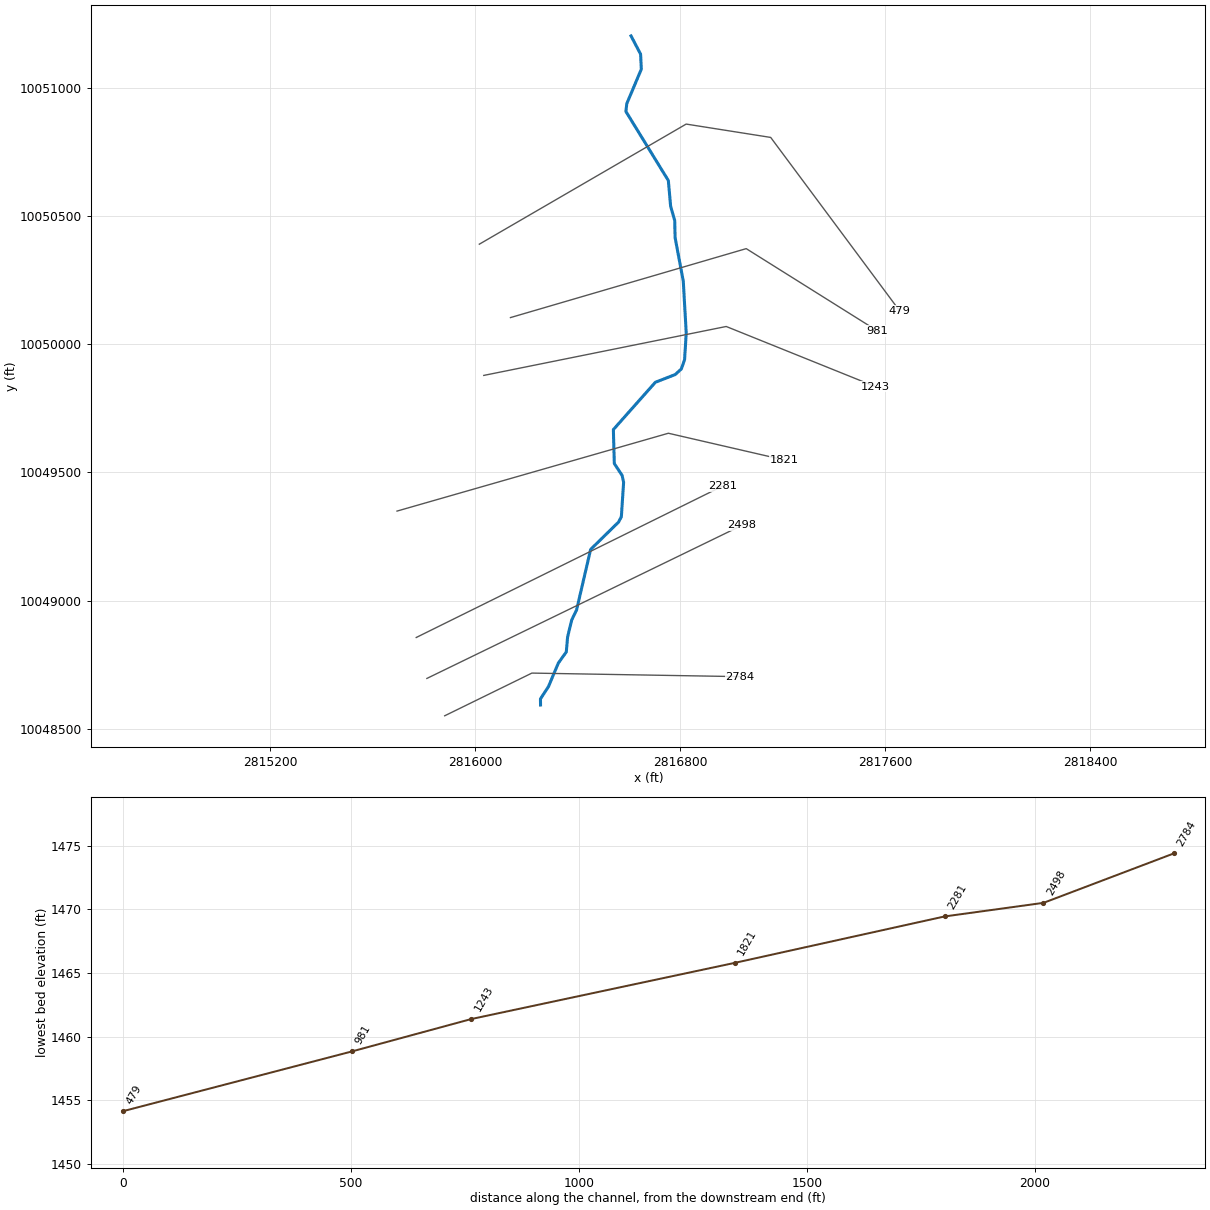
--- UNT069 IN SNOGR.prj (project) ---

Proj Title=UNT069 IN SNOGR Base Level Engineering
Current Plan=p01
Default Exp/Contr=0.3,0.1
English Units
Geom File=g01
Flow File=f01
Plan File=p01
Y Axis Title=Elevation
X Axis Title(PF)=Main Channel Distance
X Axis Title(XS)=Station
BEGIN DESCRIPTION:
UNT069 IN SNOGR
END DESCRIPTION:
DSS Export Rating Curves= 0
DSS Export Rating Curve Sorted= 0
DSS Export Volume Flow Curves= 0
DXF OffsetX= 0
DXF OffsetY= 0
DXF ScaleX= 1
DXF ScaleY= 10

--- UNT069 IN SNOGR.p01 (plan) ---

Plan Title=Multiple Run
Short Identifier=Multiple
Geom File=g01
Flow File=f01
Subcritical Flow
K Sum by GR= 0
Std Step Tol= 0.01
Critical Tol= 0.01
Num of Std Step Trials= 20
Max Error Tol= 0.3
Flow Tol Ratio= 0.001
Split Flow NTrial= 30
Split Flow Tol= 0.02
Split Flow Ratio= 0.02
Log Output Level= 0
Friction Slope Method= 1
Unsteady Friction Slope Method= 2
Unsteady Bridges Friction Slope Method= 1
Parabolic Critical Depth
Global Vel Dist=  1 , 1 , 1
Global Log Level= 0
CheckData=True
Encroach Param= -1, 0, 0, 0
BEGIN DESCRIPTION:
Multiple Run
END DESCRIPTION:

--- UNT069 IN SNOGR.f01 (steady flow) ---

Flow Title=Multiple
Number of Profiles=7
Profile Names=10-year,25-year,50-year,1pct_min,100-year,1pct_plu,500-year
River Rch & RM= UNT069 IN SNOGR,Reach-1,2784
     267     353     421     369     499     675     701
Boundary for River Rch & Prof#=UNT069 IN SNOGR,Reach-1,1
Up Type=0
Dn Type=3
Dn Slope=0.005
Boundary for River Rch & Prof#=UNT069 IN SNOGR,Reach-1,2
Up Type=0
Dn Type=3
Dn Slope=0.005
Boundary for River Rch & Prof#=UNT069 IN SNOGR,Reach-1,3
Up Type=0
Dn Type=3
Dn Slope=0.005
Boundary for River Rch & Prof#=UNT069 IN SNOGR,Reach-1,4
Up Type=0
Dn Type=3
Dn Slope=0.005
Boundary for River Rch & Prof#=UNT069 IN SNOGR,Reach-1,5
Up Type=0
Dn Type=3
Dn Slope=0.005
Boundary for River Rch & Prof#=UNT069 IN SNOGR,Reach-1,6
Up Type=0
Dn Type=3
Dn Slope=0.005
Boundary for River Rch & Prof#=UNT069 IN SNOGR,Reach-1,7
Up Type=0
Dn Type=3
Dn Slope=0.005

--- UNT069 IN SNOGR.g01 (geometry) ---

Geom Title=Existing Conditions
Program Version=4.10

River Reach=UNT069 IN SNOGR ,Reach-1
Reach XY= 30
      2816255.24     10048592.49      2816254.95     10048616.42
      2816286.29     10048664.56      2816324.61      10048755.9
      2816355.79     10048799.51      2816360.86      10048858.1
      2816376.94     10048924.31      2816395.92     10048963.43
       2816450.7     10049199.52      2816559.82     10049306.41
      2816570.68     10049327.38      2816579.47     10049461.52
      2816573.59     10049488.53      2816543.17     10049534.69
      2816539.47      10049667.3      2816703.22     10049851.93
      2816780.64     10049882.04      2816804.68     10049903.86
      2816817.43     10049940.13      2816823.81     10050044.38
      2816812.33     10050246.34       2816780.4     10050416.79
       2816778.9     10050483.44      2816762.95     10050538.81
       2816754.1     10050639.06      2816588.47     10050908.73
      2816591.77     10050939.21      2816648.57     10051073.87
      2816645.76     10051132.49      2816608.47     10051203.73

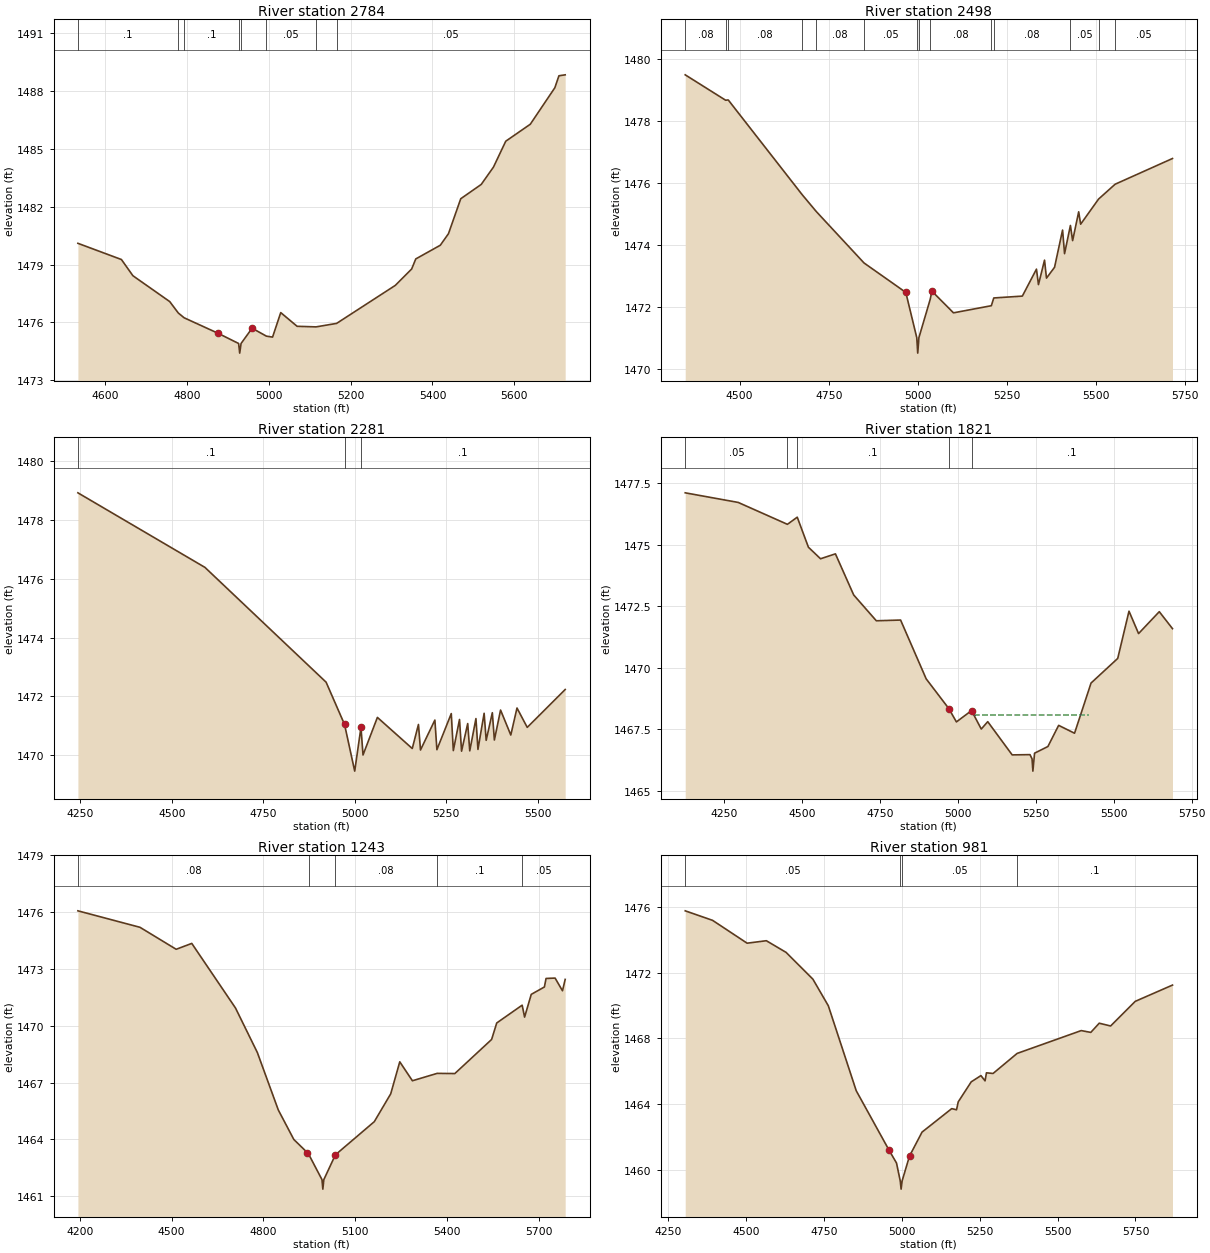
Type RM Length L Ch R = 1 ,2784    ,286,286,286
BEGIN DESCRIPTION:
UNT069 IN SNOGR 5.0
END DESCRIPTION:
XS GIS Cut Line= 3
      2815881.19     10048550.33      2816221.46     10048716.99
      2817033.75     10048703.11
#Sta/Elev= 30
  4533.2  1480.1  4639.6 1479.26  4667.7 1478.42  4757.7 1477.08  4778.6 1476.49
    4793 1476.24  4875.7 1475.44  4926.1 1474.91  4928.8 1474.41  4932.1 1474.91
  4959.1  1475.7    4994 1475.29  5009.1 1475.24  5029.1 1476.51  5069.1  1475.8
  5115.5 1475.77  5165.7 1475.95  5309.2 1477.92  5349.2 1478.77  5359.2 1479.29
  5419.2    1480  5439.2  1480.6  5469.2 1482.41  5519.2 1483.15  5549.2 1484.05
  5579.2 1485.39  5639.2 1486.27  5699.2 1488.16  5709.2 1488.78  5724.5 1488.83
#Mann= 8 ,-1 , 0
  4533.2      .1       0  4778.6     .05       0    4793      .1       0
  4926.1     .03       0  4932.1      .1       0    4994     .05       0
  5115.5      .1       0  5165.7     .05       0
Bank Sta=4875.7,4959.1
XS Rating Curve= 0 ,0
Exp/Cntr=0.3,0.1

Type RM Length L Ch R = 1 ,2498    ,217,217,217
BEGIN DESCRIPTION:
Mapping XS 4474c2e2
END DESCRIPTION:
XS GIS Cut Line= 2
       2815811.7     10048696.14      2817040.89     10049293.37
#Sta/Elev= 30
  4347.3  1479.5  4460.7 1478.68  4467.9 1478.69  4675.5 1475.63  4714.8 1475.09
  4848.7 1473.43  4965.9 1472.48  4996.7 1471.02  4999.4 1470.52  5002.7 1471.02
  5034.5 1472.26  5039.1 1472.52  5099.7 1471.82  5205.8 1472.05  5212.7  1472.3
  5292.8 1472.36  5332.4 1473.23    5338 1472.73    5355 1473.52  5360.5 1472.94
  5383.1 1473.29  5405.6 1474.49  5411.2 1473.73  5427.6 1474.64  5433.8 1474.15
  5450.8 1475.08  5456.3 1474.68  5506.5 1475.49    5553 1475.97  5713.9  1476.8
#Mann= 14 ,-1 , 0
  4347.3     .08       0  4460.7     .05       0  4467.9     .08       0
  4675.5     .05       0  4714.8     .08       0  4848.7     .05       0
  4996.7     .04       0  5002.7     .05       0  5034.5     .08       0
  5205.8     .05       0  5212.7     .08       0  5427.6     .05       0
  5506.5     .08       0    5553     .05       0
Bank Sta=4965.9,5039.1
XS Rating Curve= 0 ,0
Exp/Cntr=0.3,0.1

Type RM Length L Ch R = 1 ,2281    ,460,460,460
BEGIN DESCRIPTION:
Mapping XS 3251603e
END DESCRIPTION:
XS GIS Cut Line= 2
      2815770.11      10048855.9      2816963.98      10049445.9
#Sta/Elev= 30
  4243.7 1478.93  4590.9 1476.39    4922 1472.48  4972.4 1471.04  5000.2 1469.45
  5017.3 1470.94  5022.9    1470  5062.2 1471.28  5157.5 1470.22  5174.4 1471.04
    5180 1470.17  5219.3 1471.19  5224.8 1470.18  5264.1 1471.41  5269.7 1470.15
  5286.6 1471.21  5292.2 1470.13    5309 1471.07  5314.6 1470.14  5331.5 1471.24
    5337 1470.19  5353.9 1471.42  5359.5  1470.5  5376.3 1471.44  5381.9 1470.51
  5398.8 1471.53  5426.8 1470.68  5443.7  1471.6  5471.7 1470.94  5575.4 1472.23
#Mann= 3 ,-1 , 0
  4243.7      .1       0  4972.4     .07       0  5017.3      .1       0
Bank Sta=4972.4,5017.3
XS Rating Curve= 0 ,0
Exp/Cntr=0.3,0.1

Type RM Length L Ch R = 1 ,1821    ,578,578,578
BEGIN DESCRIPTION:
UNT069 IN SNOGR 4.0
END DESCRIPTION:
XS GIS Cut Line= 3
      2815695.09     10049349.23      2816754.17     10049653.06
      2817204.53     10049549.13
#Sta/Elev= 30
  4124.5 1477.11  4294.5 1476.72  4452.5 1475.83  4484.1 1476.12  4519.9  1474.9
  4558.8 1474.43  4606.6 1474.63  4665.2 1472.96  4737.9 1471.91  4815.8 1471.94
  4897.9 1469.55  4970.7 1468.34  4994.9  1467.8  5043.5 1468.26  5074.7 1467.51
  5095.5 1467.81  5173.9 1466.46  5231.1 1466.47  5237.7  1466.3  5240.4  1465.8
  5245.8 1466.53  5288.6  1466.8  5323.1 1467.66  5374.1 1467.34  5427.1 1469.38
  5512.7 1470.38  5548.9  1472.3  5579.6 1471.39  5646.1 1472.28  5688.5 1471.59
#Mann= 5 ,-1 , 0
  4124.5     .05       0  4452.5      .1       0  4484.1      .1       0
  4970.7     .07       0  5043.5      .1       0
#XS Ineff= 1 ,-1
 5053.41 5420.57 1468.08
Permanent Ineff=
       F
Bank Sta=4970.7,5043.5
XS Rating Curve= 0 ,0
Exp/Cntr=0.3,0.1

Type RM Length L Ch R = 1 ,1243    ,262,262,262
BEGIN DESCRIPTION:
UNT069 IN SNOGR 3.0
END DESCRIPTION:
XS GIS Cut Line= 3
      2816033.69     10049878.75      2816979.86     10050069.72
      2817561.46     10049835.35
#Sta/Elev= 30
    4194 1476.07  4396.9  1475.2  4515.1 1474.04  4566.1 1474.35    4709 1470.94
  4780.4 1468.59  4848.8 1465.56  4899.6    1464  4943.6 1463.31  4950.4 1463.15
  4991.6 1461.88  4994.4 1461.38  4997.6 1461.88  5035.4 1463.19  5162.5 1464.94
  5216.2 1466.41  5245.8  1468.1  5287.1  1467.1    5368 1467.49  5425.7 1467.48
  5545.9 1469.28  5562.6 1470.15  5645.7 1471.09  5653.7 1470.46  5675.4 1471.66
  5718.4 1472.05  5723.8  1472.5  5753.3 1472.52  5777.5 1471.85  5786.3 1472.45
#Mann= 5 ,-1 , 0
    4194     .08       0  4950.4     .05       0  5035.4     .08       0
    5368      .1       0  5645.7     .05       0
Bank Sta=4943.6,5035.4
XS Rating Curve= 0 ,0
Exp/Cntr=0.3,0.1

Type RM Length L Ch R = 1 ,981     ,502,502,502
BEGIN DESCRIPTION:
UNT069 IN SNOGR 2.0
END DESCRIPTION:
XS GIS Cut Line= 3
      2816137.87     10050104.45      2817057.98     10050373.54
      2817570.15     10050052.36
#Sta/Elev= 30
  4305.6 1475.77  4393.4 1475.19  4504.2  1473.8  4565.9 1473.95  4629.2 1473.24
  4715.2 1471.61  4764.7 1469.99  4854.2 1464.82  4959.8 1461.19  4983.4 1460.42
  4995.4 1459.33  4998.2 1458.83  5001.4 1459.33  5025.1 1460.84  5065.3  1462.3
  5160.6 1463.73    5176 1463.66  5181.4 1464.14  5223.1 1465.36  5254.3 1465.74
  5267.5 1465.42    5272 1465.91  5293.2 1465.87  5370.4 1467.09    5576 1468.48
  5606.7 1468.37  5633.8 1468.93  5670.3 1468.76  5749.3 1470.26  5868.8 1471.25
#Mann= 4 ,-1 , 0
  4305.6     .05       0  4995.4    .035       0  5001.4     .05       0
  5370.4      .1       0
Bank Sta=4959.8,5025.1
XS Rating Curve= 0 ,0
Exp/Cntr=0.3,0.1

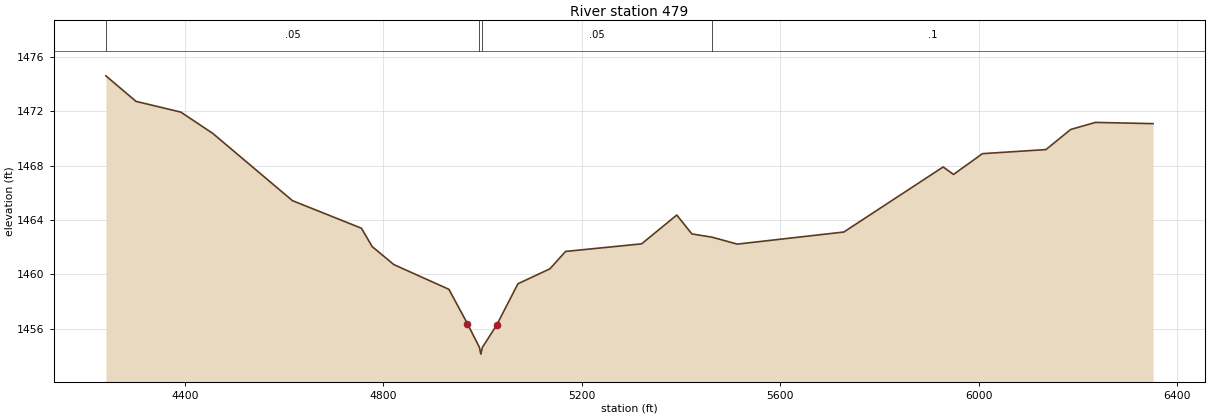
Type RM Length L Ch R = 1 ,479     ,0,0,0
BEGIN DESCRIPTION:
UNT069 IN SNOGR 1.0
END DESCRIPTION:
XS GIS Cut Line= 4
      2816016.34     10050390.92      2816823.61     10050859.65
      2817153.47     10050807.57      2817656.95     10050130.48
#Sta/Elev= 30
  4240.7 1474.62  4301.4 1472.74  4391.7 1471.95  4456.2 1470.38  4616.8 1465.43
  4755.9  1463.4  4777.5 1462.05  4821.3 1460.72  4932.3  1458.9  4969.5 1456.38
  4993.8 1454.63  4996.6 1454.13  4999.8 1454.63  5028.3 1456.25  5071.4 1459.31
  5135.9 1460.41  5167.4 1461.69  5320.8 1462.25  5391.7 1464.37  5422.1 1462.98
  5462.9 1462.74  5513.6 1462.23  5728.5 1463.12  5928.7 1467.91  5949.6 1467.36
    6008 1468.89    6136 1469.19  6185.8 1470.67  6235.7 1471.19  6351.9  1471.1
#Mann= 4 ,-1 , 0
  4240.7     .05       0  4993.8    .035       0  4999.8     .05       0
  5462.9      .1       0
Bank Sta=4969.5,5028.3
XS Rating Curve= 0 ,0
Exp/Cntr=0.3,0.1

Chan Stop Cuts=-1
Use User Specified Reach Order=0
Composite Channel Slope=5