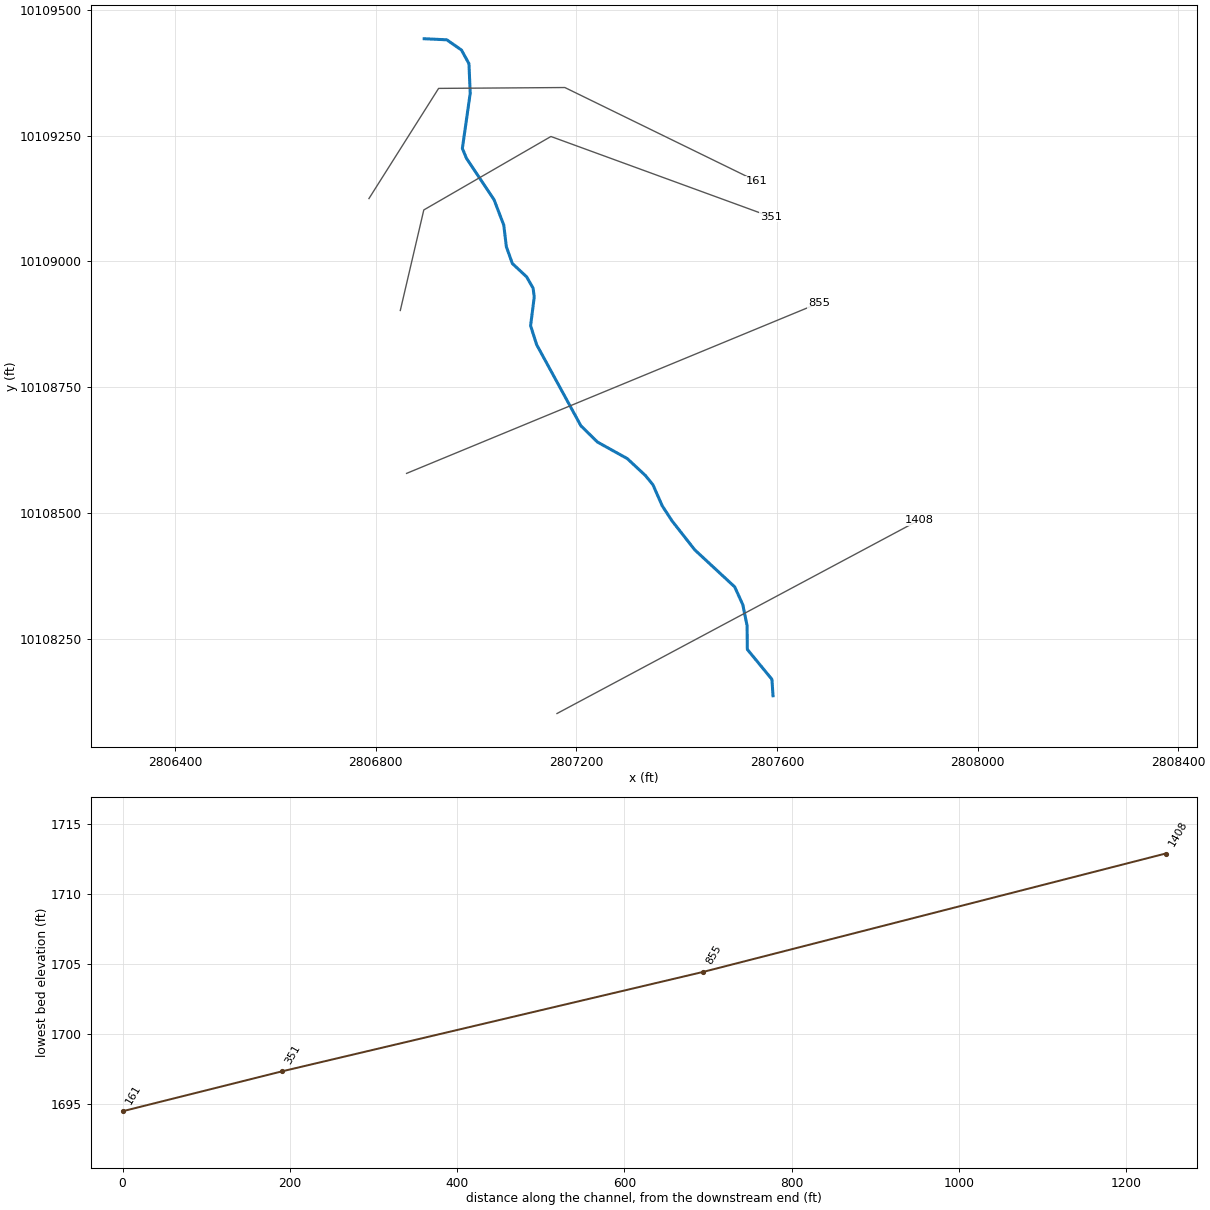
--- UNT070 IN NNOGR.prj (project) ---

Proj Title=UNT070 IN NNOGR Base Level Engineering
Current Plan=p01
Default Exp/Contr=0.3,0.1
English Units
Geom File=g01
Flow File=f01
Plan File=p01
Y Axis Title=Elevation
X Axis Title(PF)=Main Channel Distance
X Axis Title(XS)=Station
BEGIN DESCRIPTION:
UNT070 IN NNOGR
END DESCRIPTION:
DSS Export Rating Curves= 0
DSS Export Rating Curve Sorted= 0
DSS Export Volume Flow Curves= 0
DXF OffsetX= 0
DXF OffsetY= 0
DXF ScaleX= 1
DXF ScaleY= 10

--- UNT070 IN NNOGR.p01 (plan) ---

Plan Title=Multiple Run
Short Identifier=Multiple
Geom File=g01
Flow File=f01
Subcritical Flow
K Sum by GR= 0
Std Step Tol= 0.01
Critical Tol= 0.01
Num of Std Step Trials= 20
Max Error Tol= 0.3
Flow Tol Ratio= 0.001
Split Flow NTrial= 30
Split Flow Tol= 0.02
Split Flow Ratio= 0.02
Log Output Level= 0
Friction Slope Method= 1
Unsteady Friction Slope Method= 2
Unsteady Bridges Friction Slope Method= 1
Parabolic Critical Depth
Global Vel Dist=  1 , 1 , 1
Global Log Level= 0
CheckData=True
Encroach Param= -1, 0, 0, 0
BEGIN DESCRIPTION:
Multiple Run
END DESCRIPTION:

--- UNT070 IN NNOGR.f01 (steady flow) ---

Flow Title=Multiple
Program Version=4.10
Number of Profiles= 7
Profile Names=10-year,25-year,50-year,1pct_min,100-year,1pct_plu,500-year
River Rch & RM=UNT070 IN NNOGR,Reach-1         ,1408
     195     256     303     265     358     484     500
Boundary for River Rch & Prof#=UNT070 IN NNOGR,Reach-1         , 1
Up Type= 0
Dn Type= 3
Dn Slope=0.015
Boundary for River Rch & Prof#=UNT070 IN NNOGR,Reach-1         , 2
Up Type= 0
Dn Type= 3
Dn Slope=0.015
Boundary for River Rch & Prof#=UNT070 IN NNOGR,Reach-1         , 3
Up Type= 0
Dn Type= 3
Dn Slope=0.015
Boundary for River Rch & Prof#=UNT070 IN NNOGR,Reach-1         , 4
Up Type= 0
Dn Type= 3
Dn Slope=0.015
Boundary for River Rch & Prof#=UNT070 IN NNOGR,Reach-1         , 5
Up Type= 0
Dn Type= 3
Dn Slope=0.015
Boundary for River Rch & Prof#=UNT070 IN NNOGR,Reach-1         , 6
Up Type= 0
Dn Type= 3
Dn Slope=0.015
Boundary for River Rch & Prof#=UNT070 IN NNOGR,Reach-1         , 7
Up Type= 0
Dn Type= 3
Dn Slope=0.015
DSS Import GetInterval= 0
DSS Import GetPeak= 0
DSS Import FillOption= 0

--- UNT070 IN NNOGR.g01 (geometry) ---

Geom Title=Existing Conditions
Program Version=4.10

River Reach=UNT070 IN NNOGR ,Reach-1
Reach XY= 30
      2807592.04     10108137.73      2807589.87     10108170.28
      2807540.82     10108229.74      2807540.39     10108276.62
      2807531.83     10108318.43      2807515.65     10108353.87
       2807436.1     10108427.27      2807390.84      10108484.7
      2807371.11     10108514.83      2807352.74     10108556.42
      2807337.47     10108575.13      2807301.41     10108608.58
      2807242.06     10108641.38      2807208.92     10108673.78
      2807120.75     10108834.73      2807108.69     10108872.38
      2807115.94     10108929.44      2807113.73     10108946.74
      2807100.71     10108969.47       2807072.3      10108995.9
      2807060.41       10109029.      2807055.15     10109072.33
       2807035.8     10109122.63      2806980.81     10109204.75
      2806972.63     10109224.43      2806988.32     10109334.02
      2806985.77     10109392.68      2806970.86     10109419.72
      2806941.72       10109440.      2806896.53     10109442.15

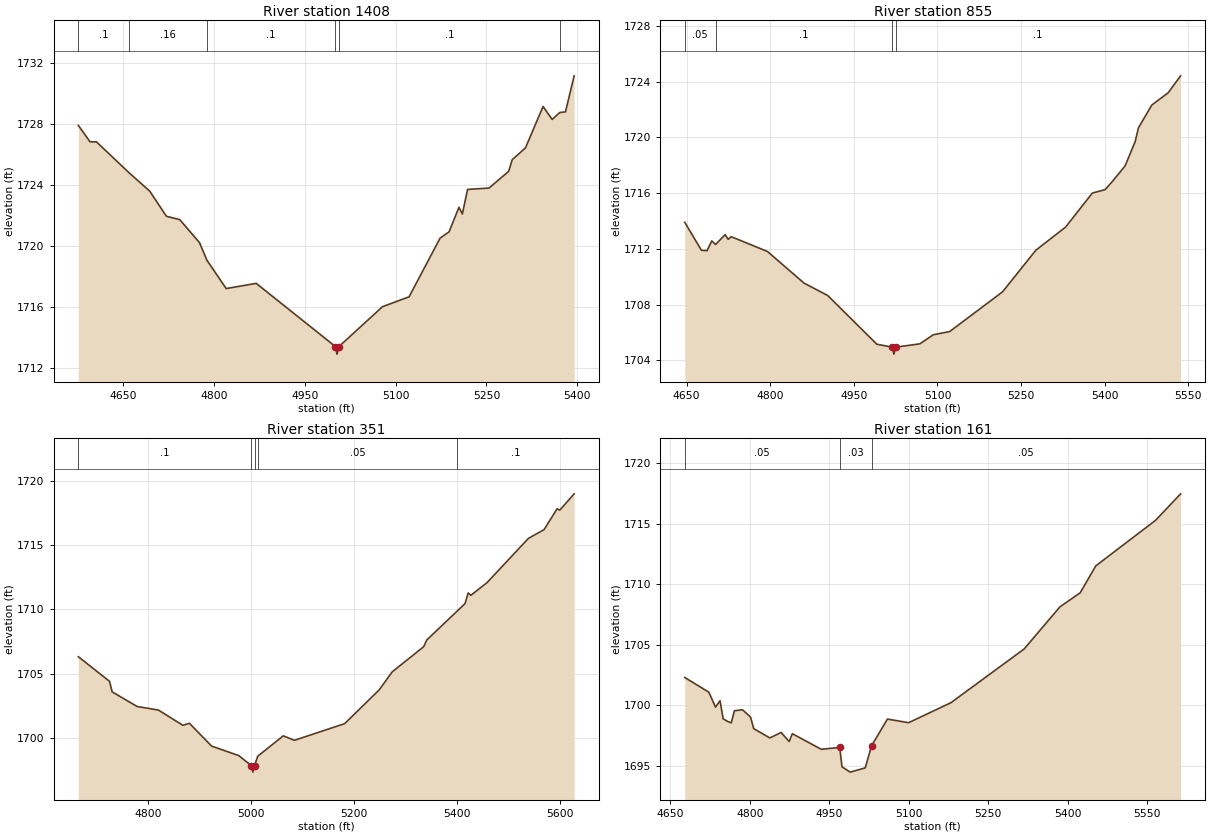
Type RM Length L Ch R = 1 ,1408    ,553,553,553
BEGIN DESCRIPTION:
UNT070 IN NNOGR 3.0
END DESCRIPTION:
XS GIS Cut Line= 2
      2807161.34     10108102.42      2807883.79     10108486.71
#Sta/Elev= 30
  4576.4 1727.92  4595.8 1726.84  4606.3 1726.84  4660.8 1724.79  4694.2 1723.61
  4721.8 1721.96  4743.8 1721.74  4776.4 1720.23  4788.6 1719.08  4820.4 1717.22
    4870 1717.56  5000.6 1713.42  5003.3 1712.92  5006.6 1713.42  5078.4 1716.03
  5122.3 1716.68  5173.5 1720.53  5188.3 1720.94  5204.6 1722.55  5210.2 1722.11
  5218.8 1723.72  5254.2 1723.81  5286.7 1724.91  5292.5 1725.67  5314.4 1726.45
  5343.4 1729.16  5358.4 1728.31  5370.8 1728.76  5380.4 1728.81  5394.7 1731.17
#Mann= 6 ,-1 , 0
  4576.4      .1       0  4660.8     .16       0  4788.6      .1       0
  5000.6     .07       0  5006.6      .1       0  5370.8     .05       0
Bank Sta=5000.6,5006.6
XS Rating Curve= 0 ,0
Exp/Cntr=0.3,0.1

Type RM Length L Ch R = 1 ,855     ,504,504,504
BEGIN DESCRIPTION:
UNT070 IN NNOGR 2.0
END DESCRIPTION:
XS GIS Cut Line= 2
      2806861.44     10108579.19      2807683.83     10108917.37
#Sta/Elev= 30
  4646.9  1713.9  4676.8 1711.89  4686.9 1711.87  4695.3 1712.57  4702.1 1712.31
  4719.3 1713.02  4724.7 1712.68  4730.2 1712.87  4795.1 1711.81  4860.7 1709.54
  4903.2 1708.65  4991.3 1705.15  5019.1 1704.94  5021.9 1704.44  5025.1 1704.94
  5068.6 1705.18  5092.5 1705.83  5121.9 1706.06  5216.7 1708.91  5276.5  1711.9
  5329.8 1713.56  5377.7    1716  5400.6 1716.25  5412.5 1716.78  5436.5 1717.95
  5454.6  1719.7  5460.4 1720.68  5484.4 1722.32  5513.7  1723.2  5536.1 1724.42
#Mann= 4 ,-1 , 0
  4646.9     .05       0  4702.1      .1       0  5019.1     .07       0
  5025.1      .1       0
Bank Sta=5019.1,5025.1
XS Rating Curve= 0 ,0
Exp/Cntr=0.3,0.1

Type RM Length L Ch R = 1 ,351     ,190,190,190
BEGIN DESCRIPTION:
Mapping XS 6f936a88
END DESCRIPTION:
XS GIS Cut Line= 4
      2806848.89     10108902.59      2806895.76     10109102.21
      2807149.23     10109248.04      2807587.86     10109088.54
#Sta/Elev= 30
  4664.2 1706.31  4724.9 1704.39    4730 1703.57  4778.4 1702.43    4820 1702.15
  4867.5 1700.96  4880.2 1701.12  4923.4 1699.34  4976.2  1698.6  5000.8 1697.81
  5003.6 1697.31  5006.8 1697.81  5013.1 1698.55  5062.8 1700.14  5084.3 1699.79
  5182.1 1701.09  5249.4 1703.73  5274.6 1705.13  5335.8 1707.09  5341.7 1707.61
  5401.2 1709.88  5416.2 1710.45  5422.3 1711.28  5427.6  1711.1  5458.8 1712.08
  5539.3 1715.53  5569.9 1716.22  5595.2 1717.84  5600.5 1717.74  5628.4 1719.01
#Mann= 5 ,-1 , 0
  4664.2      .1       0  5000.8     .07       0  5006.8      .1       0
  5013.1     .05       0  5401.2      .1       0
Bank Sta=5000.8,5006.8
XS Rating Curve= 0 ,0
Exp/Cntr=0.3,0.1

Type RM Length L Ch R = 1 ,161     ,0,0,0
BEGIN DESCRIPTION:
UNT070 IN NNOGR 1.0
END DESCRIPTION:
XS GIS Cut Line= 4
       2806786.4     10109124.81      2806925.27     10109343.53
      2807177.01     10109345.26      2807558.91     10109159.52
#Sta/Elev= 30
  4677.4 1702.29  4722.7 1701.08  4735.4 1699.84  4743.9 1700.37  4749.8 1698.87
    4759 1698.64  4765.1 1698.54    4771 1699.54  4786.3 1699.62  4801.5 1699.01
  4807.4 1698.06  4837.9 1697.29  4859.1 1697.74  4874.4 1696.99  4880.3 1697.64
  4934.8 1696.35  4969.7  1696.5 4974.01  1694.9  4989.4 1694.46 5017.81 1694.81
  5029.7 1696.63  5059.7 1698.85  5099.7 1698.55  5179.7 1700.21  5317.6 1704.65
  5385.3 1708.14  5423.4  1709.3  5452.9 1711.53  5565.7  1715.3  5612.9 1717.49
#Mann= 3 , 0 , 0
  4677.4     .05       0  4969.7     .03       0  5029.7     .05       0
Bank Sta=4969.7,5029.7
XS Rating Curve= 0 ,0
Exp/Cntr=0.3,0.1

Chan Stop Cuts=-1
Use User Specified Reach Order=0
Composite Channel Slope=5