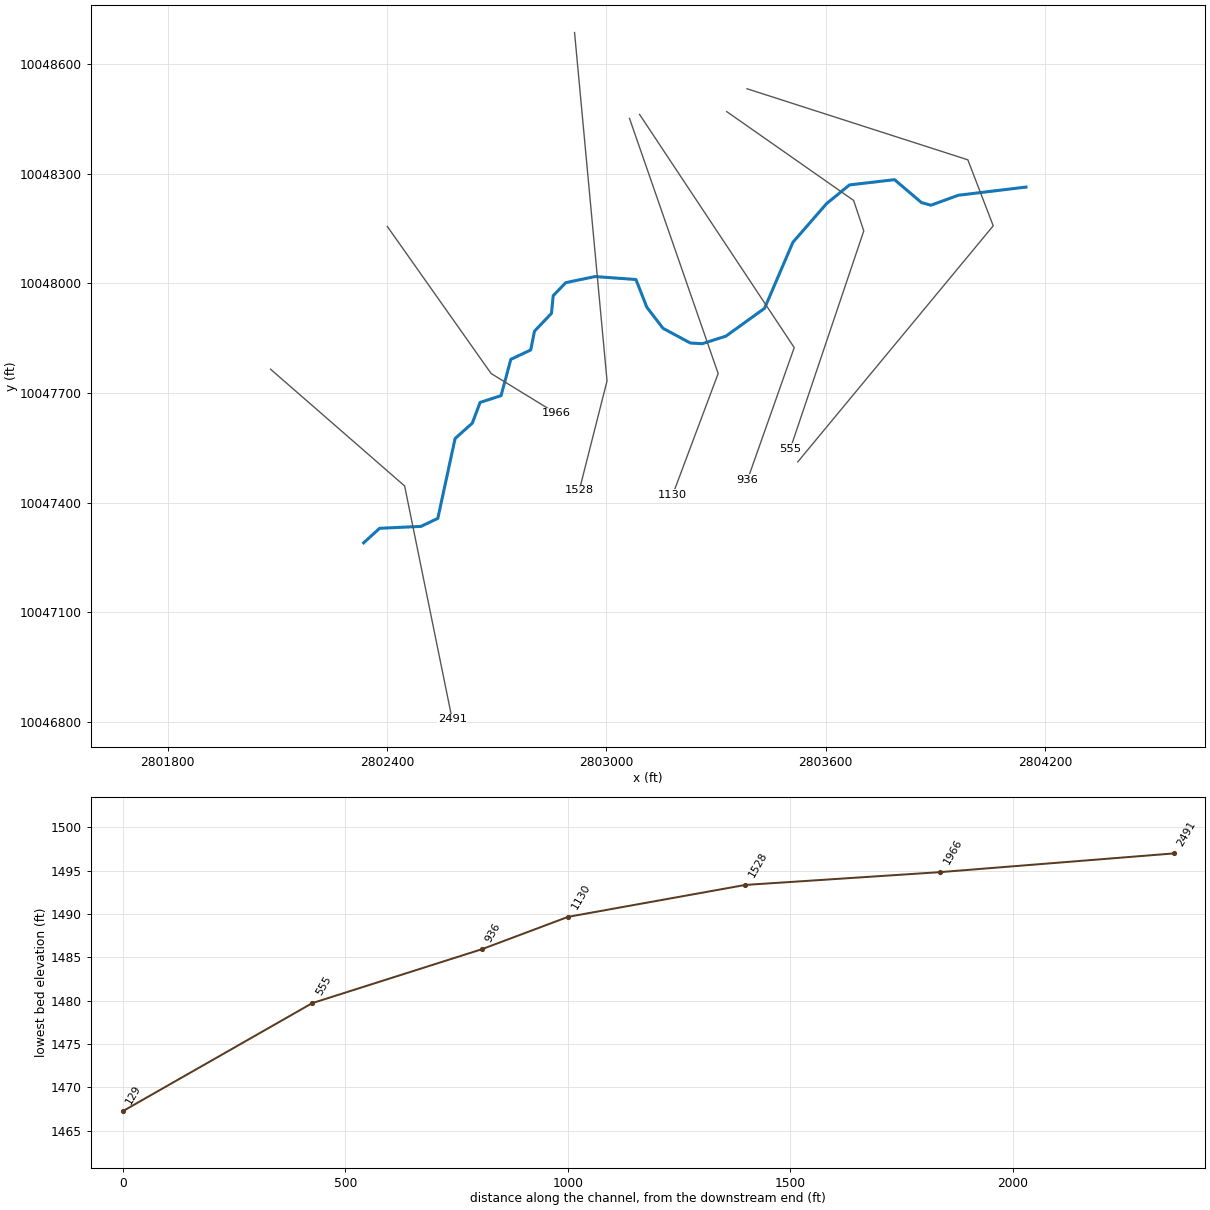
--- UNT070 IN SNOGR.prj (project) ---

Proj Title=UNT070 IN SNOGR Base Level Engineering
Current Plan=p01
Default Exp/Contr=0.3,0.1
English Units
Geom File=g01
Flow File=f01
Plan File=p01
BEGIN DESCRIPTION:
UNT070 IN SNOGR
END DESCRIPTION:

--- UNT070 IN SNOGR.p01 (plan) ---

Plan Title=Multiple Run
Short Identifier=Multiple
Geom File=g01
Flow File=f01
Subcritical Flow
K Sum by GR= 0
Std Step Tol= 0.01
Critical Tol= 0.01
Num of Std Step Trials= 20
Max Error Tol= 0.3
Flow Tol Ratio= 0.001
Split Flow NTrial= 30
Split Flow Tol= 0.02
Split Flow Ratio= 0.02
Log Output Level= 0
Friction Slope Method= 1
Unsteady Friction Slope Method= 2
Unsteady Bridges Friction Slope Method= 1
Parabolic Critical Depth
Global Vel Dist=  1 , 1 , 1
Global Log Level= 0
CheckData=True
Encroach Param= -1, 0, 0, 0
BEGIN DESCRIPTION:
Multiple Run
END DESCRIPTION:

--- UNT070 IN SNOGR.f01 (steady flow) ---

Flow Title=Multiple
Number of Profiles=7
Profile Names=10-year,25-year,50-year,1pct_min,100-year,1pct_plu,500-year
River Rch & RM= UNT070 IN SNOGR,Reach-1,2491
     287     381     455     398     539     728     757
Boundary for River Rch & Prof#=UNT070 IN SNOGR,Reach-1,1
Up Type=0
Dn Type=3
Dn Slope=0.005
Boundary for River Rch & Prof#=UNT070 IN SNOGR,Reach-1,2
Up Type=0
Dn Type=3
Dn Slope=0.005
Boundary for River Rch & Prof#=UNT070 IN SNOGR,Reach-1,3
Up Type=0
Dn Type=3
Dn Slope=0.005
Boundary for River Rch & Prof#=UNT070 IN SNOGR,Reach-1,4
Up Type=0
Dn Type=3
Dn Slope=0.005
Boundary for River Rch & Prof#=UNT070 IN SNOGR,Reach-1,5
Up Type=0
Dn Type=3
Dn Slope=0.005
Boundary for River Rch & Prof#=UNT070 IN SNOGR,Reach-1,6
Up Type=0
Dn Type=3
Dn Slope=0.005
Boundary for River Rch & Prof#=UNT070 IN SNOGR,Reach-1,7
Up Type=0
Dn Type=3
Dn Slope=0.005

--- UNT070 IN SNOGR.g01 (geometry) ---

Geom Title=Existing Conditions

River Reach=UNT070 IN SNOGR,Reach-1
Reach XY= 30
      2802336.13     10047290.31      2802379.77     10047330.09
      2802493.04     10047335.31      2802539.05     10047357.19
      2802586.32     10047575.70      2802633.44     10047617.80
      2802654.80     10047674.50      2802712.07     10047693.00
      2802738.83     10047792.34      2802793.32     10047818.04
      2802803.60     10047869.47      2802849.98     10047918.12
      2802854.84     10047966.66      2802889.10     10048002.18
      2802969.18     10048018.88      2803081.13     10048010.81
      2803111.03     10047934.86      2803155.32     10047877.26
      2803230.01     10047837.08      2803262.63     10047835.13
      2803327.57     10047855.98      2803433.13     10047932.09
      2803510.72     10048112.80      2803603.07     10048218.74
      2803665.47     10048269.63      2803788.73     10048283.99
      2803862.37     10048221.37      2803888.32     10048214.04
      2803963.53     10048241.39      2804148.47     10048263.73

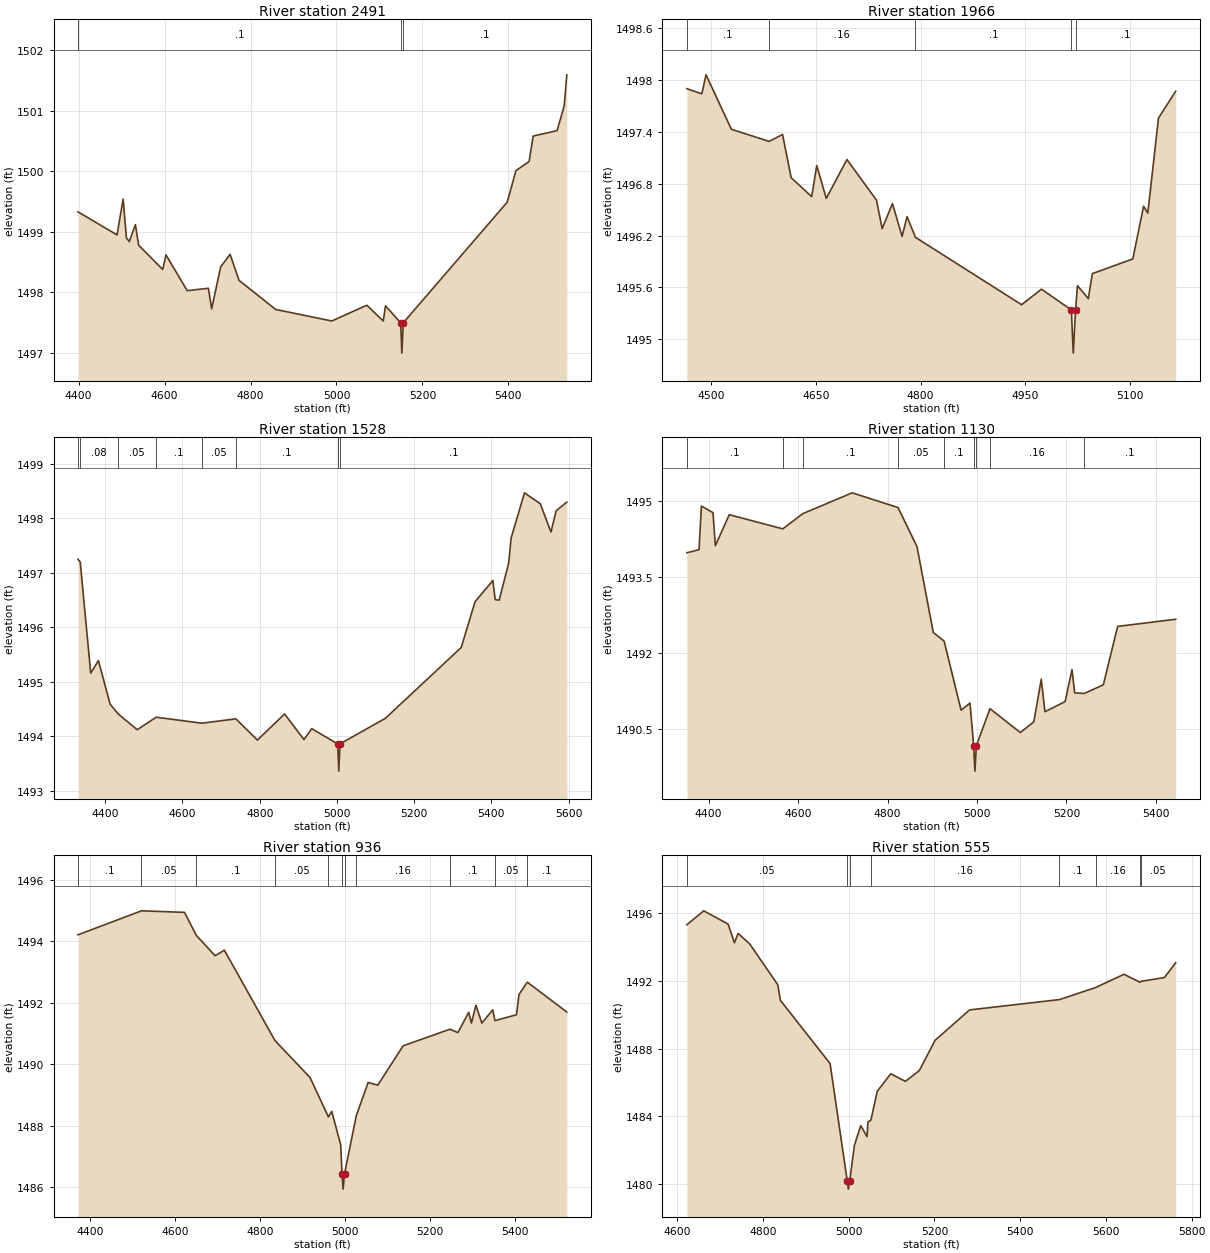
Type RM Length L Ch R = 1,2491,525,525,525
BEGIN DESCRIPTION:
UNT070 IN SNOGR 6.0
END DESCRIPTION:
XS GIS Cut Line= 3
      2802081.45     10047765.37      2802448.25     10047445.89
      2802578.23     10046807.82
#Sta/Elev= 30
  4398.5 1499.33  4489.4 1498.95  4503.6 1499.54  4511.2 1498.90  4517.9 1498.84
  4532.1 1499.12  4539.7 1498.78  4595.7 1498.38  4603.3 1498.62  4652.7 1498.03
  4702.0 1498.07  4709.6 1497.73  4730.5 1498.42  4752.4 1498.63  4773.3 1498.20
  4858.7 1497.72  4989.2 1497.53  5070.8 1497.79  5109.0 1497.53  5114.1 1497.78
  5149.5 1497.50  5152.2 1497.00  5155.5 1497.50  5397.4 1499.49  5417.8 1500.01
  5448.4 1500.16  5457.8 1500.58  5513.5 1500.67  5530.1 1501.08  5536.1 1501.59
#Mann=3,-1,0
  4398.5     0.1       0  5149.5    0.07       0  5155.5     0.1       0
Bank Sta=5149.5,5155.5
Exp/Cntr=0.3,0.1

Type RM Length L Ch R = 1,1966,438,438,438
BEGIN DESCRIPTION:
UNT070 IN SNOGR 5.0
END DESCRIPTION:
XS GIS Cut Line= 3
      2802400.90     10048155.88      2802684.90     10047753.54
      2802862.61     10047644.63
#Sta/Elev= 30
  4464.8 1497.90  4486.2 1497.84  4492.3 1498.06  4528.6 1497.43  4582.7 1497.29
  4602.0 1497.37  4614.3 1496.87  4643.8 1496.65  4651.0 1497.01  4664.7 1496.63
  4694.3 1497.08  4736.7 1496.61  4744.8 1496.28  4759.6 1496.57  4773.4 1496.19
  4780.5 1496.42  4792.5 1496.18  4944.8 1495.40  4973.2 1495.58  5016.1 1495.34
  5018.8 1494.84  5022.1 1495.34  5024.9 1495.62  5040.4 1495.47  5046.2 1495.76
  5104.2 1495.93  5119.7 1496.54  5125.7 1496.46  5141.0 1497.56  5165.7 1497.87
#Mann=5,-1,0
  4464.8     0.1       0  4582.7    0.16       0  4792.5     0.1       0
  5016.1    0.07       0  5022.1     0.1       0
Bank Sta=5016.1,5022.1
Exp/Cntr=0.3,0.1

Type RM Length L Ch R = 1,1528,398,398,398
BEGIN DESCRIPTION:
UNT070 IN SNOGR 4.0
END DESCRIPTION:
XS GIS Cut Line= 3
      2802913.20     10048686.55      2803002.08     10047733.40
      2802926.14     10047433.96
#Sta/Elev= 30
  4329.3 1497.25  4335.1 1497.20  4362.3 1495.16  4382.3 1495.39  4412.5 1494.59
  4433.5 1494.41  4482.8 1494.12  4531.9 1494.35  4650.0 1494.24  4738.3 1494.32
  4794.1 1493.93  4864.4 1494.41  4914.6 1493.94  4934.7 1494.14  5002.0 1493.86
  5004.8 1493.36  5008.0 1493.86  5125.6 1494.33  5322.0 1495.63  5357.8 1496.47
  5403.9 1496.86  5410.0 1496.51  5420.4 1496.50  5444.9 1497.18  5451.3 1497.64
  5485.9 1498.47  5526.8 1498.27  5554.5 1497.75  5567.8 1498.14  5595.5 1498.30
#Mann=8,-1,0
  4329.3    0.05       0  4335.1    0.08       0  4433.5    0.05       0
  4531.9     0.1       0  4650.0    0.05       0  4738.3     0.1       0
  5002.0    0.07       0  5008.0     0.1       0
Bank Sta=5002,5008
Exp/Cntr=0.3,0.1

Type RM Length L Ch R = 1,1130,194,194,194
BEGIN DESCRIPTION:
UNT070 IN SNOGR 3.0
END DESCRIPTION:
XS GIS Cut Line= 3
      2803063.55     10048451.66      2803306.11     10047753.54
      2803181.87     10047422.23
#Sta/Elev= 30
  4351.4 1493.98  4378.6 1494.04  4383.9 1494.90  4409.8 1494.77  4415.1 1494.12
  4446.2 1494.73  4565.8 1494.45  4610.7 1494.75  4720.9 1495.16  4823.5 1494.87
  4865.9 1494.10  4902.3 1492.41  4926.5 1492.24  4964.5 1490.88  4984.4 1491.02
  4992.6 1490.18  4995.4 1489.68  4998.6 1490.18  5029.1 1490.91  5096.8 1490.44
  5127.1 1490.65  5143.7 1491.49  5152.0 1490.85  5197.1 1491.05  5212.5 1491.68
  5218.4 1491.22  5240.1 1491.21  5282.5 1491.38  5314.5 1492.53  5444.3 1492.67
#Mann=9,-1,0
  4351.4     0.1       0  4565.8    0.05       0  4610.7     0.1       0
  4823.5    0.05       0  4926.5     0.1       0  4992.6    0.07       0
  4998.6     0.1       0  5029.1    0.16       0  5240.1     0.1       0
Bank Sta=4992.6,4998.6
Exp/Cntr=0.3,0.1

Type RM Length L Ch R = 1,936,381,381,381
BEGIN DESCRIPTION:
UNT070 IN SNOGR 2.0
END DESCRIPTION:
XS GIS Cut Line= 3
      2803091.03     10048462.59      2803514.23     10047824.54
      2803386.20     10047462.14
#Sta/Elev= 30
  4371.8 1494.21  4521.2 1494.99  4622.4 1494.94  4650.3 1494.19  4694.4 1493.53
  4716.2 1493.71  4835.3 1490.77  4917.7 1489.57  4960.9 1488.29  4968.8 1488.47
  4989.9 1487.38  4992.9 1486.44  4995.6 1485.94  4998.9 1486.44  5026.4 1488.32
  5054.4 1489.41  5077.1 1489.32  5136.7 1490.60  5246.8 1491.14  5265.6 1491.03
  5291.0 1491.69  5297.4 1491.34  5308.0 1491.92  5321.9 1491.34  5347.5 1491.77
  5352.7 1491.42  5403.4 1491.61  5409.3 1492.27  5428.9 1492.67  5521.8 1491.70
#Mann=11,-1,0
  4371.8     0.1       0  4521.2    0.05       0  4650.3     0.1       0
  4835.3    0.05       0  4960.9     0.1       0  4992.9    0.07       0
  4998.9     0.1       0  5026.4    0.16       0  5246.8     0.1       0
  5352.7    0.05       0  5428.9     0.1       0
Bank Sta=4992.9,4998.9
Exp/Cntr=0.3,0.1

Type RM Length L Ch R = 1,555,426,426,426
BEGIN DESCRIPTION:
Mapping XS ffb51981
END DESCRIPTION:
XS GIS Cut Line= 4
      2803329.63     10048470.21      2803676.81     10048227.18
      2803704.59     10048143.85      2803503.68     10047548.05
#Sta/Elev= 30
  4622.4 1495.30  4661.8 1496.12  4718.6 1495.34  4733.3 1494.24  4742.0 1494.79
  4769.0 1494.17  4834.4 1491.77  4840.7 1490.84  4956.5 1487.12  4996.4 1480.22
  4999.1 1479.72  5002.4 1480.22  5013.2 1482.30  5028.0 1483.46  5042.8 1482.82
  5044.8 1483.67  5051.8 1483.79  5066.4 1485.48  5098.1 1486.52  5132.3 1486.07
  5164.7 1486.71  5201.5 1488.49  5281.9 1490.28  5491.6 1490.89  5575.9 1491.60
  5642.1 1492.38  5679.7 1491.91  5681.3 1491.96  5736.6 1492.19  5762.8 1493.06
#Mann=8,-1,0
  4622.4    0.05       0  4996.4   0.035       0  5002.4    0.05       0
  5051.8    0.16       0  5491.6     0.1       0  5575.9    0.16       0
  5679.7     0.1       0  5681.3    0.05       0
Bank Sta=4996.4,5002.4
Exp/Cntr=0.3,0.1

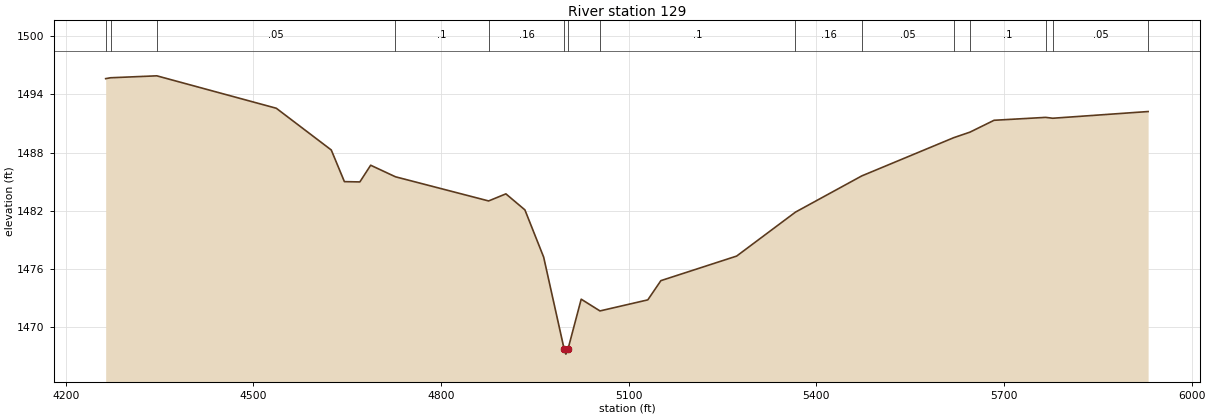
Type RM Length L Ch R = 1,129,0,0,0
BEGIN DESCRIPTION:
UNT070 IN SNOGR 1.0
END DESCRIPTION:
XS GIS Cut Line= 4
      2803385.10     10048532.75      2803989.31     10048338.30
      2804058.76     10048157.74      2803524.00     10047511.87
#Sta/Elev= 30
  4263.7 1495.62  4271.5 1495.71  4345.5 1495.91  4536.5 1492.57  4624.4 1488.27
  4645.4 1485.01  4670.1 1484.98  4687.4 1486.70  4727.0 1485.51  4876.0 1483.02
  4903.6 1483.75  4934.0 1482.10  4964.0 1477.23  4996.8 1467.74  4999.5 1467.24
  5002.8 1467.74  5024.0 1472.90  5054.0 1471.69  5130.5 1472.83  5151.4 1474.81
  5272.5 1477.34  5366.6 1481.87  5472.6 1485.60  5619.7 1489.54  5645.6 1490.11
  5684.1 1491.33  5766.7 1491.63  5778.0 1491.54  5930.2 1492.23  5930.4 1492.23
#Mann=15,-1,0
  4263.7    0.05       0  4271.5    0.08       0  4345.5    0.05       0
  4727.0     0.1       0  4876.0    0.16       0  4996.8    0.07       0
  5002.8    0.16       0  5054.0     0.1       0  5366.6    0.16       0
  5472.6    0.05       0  5619.7    0.16       0  5645.6     0.1       0
  5766.7    0.16       0  5778.0    0.05       0  5930.2     0.1       0
Bank Sta=4996.8,5002.8
Exp/Cntr=0.3,0.1

Chan Stop Cuts=-1