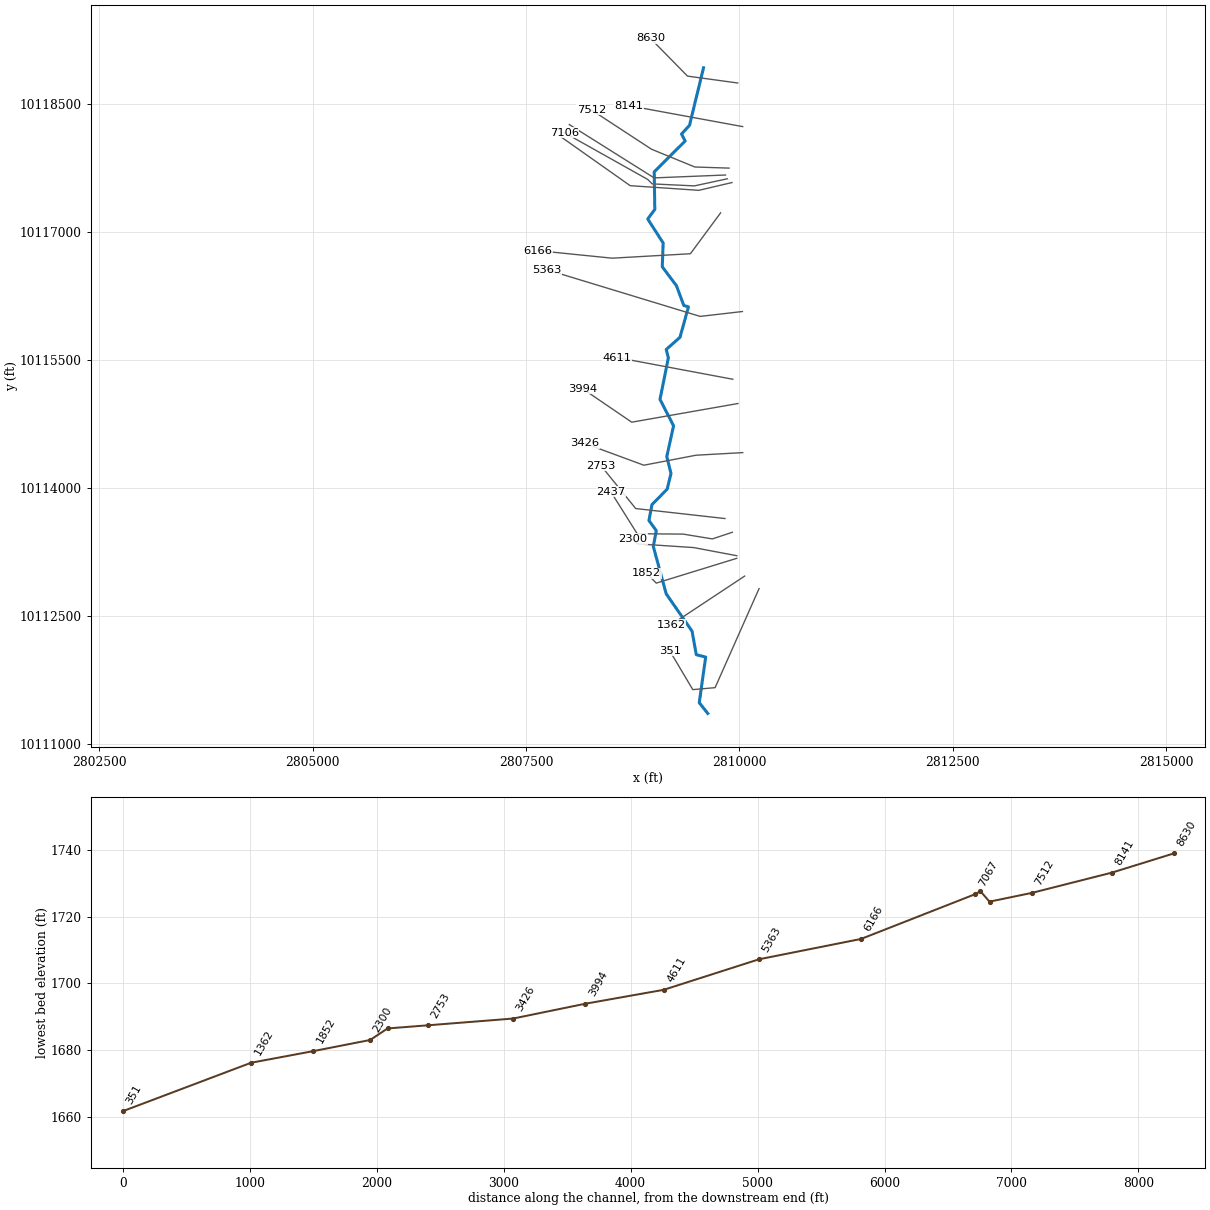
--- UNT071 IN NNOGR.prj (project) ---

Proj Title=UNT071 IN NNOGR Base Level Engineering
Current Plan=p01
Default Exp/Contr=0.3,0.1
English Units
Geom File=g01
Flow File=f01
Plan File=p01
BEGIN DESCRIPTION:
UNT071 IN NNOGR
END DESCRIPTION:

--- UNT071 IN NNOGR.p01 (plan) ---

Plan Title=Multiple Run
Short Identifier=Multiple
Geom File=g01
Flow File=f01
Subcritical Flow
K Sum by GR= 0
Std Step Tol= 0.01
Critical Tol= 0.01
Num of Std Step Trials= 20
Max Error Tol= 0.3
Flow Tol Ratio= 0.001
Split Flow NTrial= 30
Split Flow Tol= 0.02
Split Flow Ratio= 0.02
Log Output Level= 0
Friction Slope Method= 1
Unsteady Friction Slope Method= 2
Unsteady Bridges Friction Slope Method= 1
Parabolic Critical Depth
Global Vel Dist=  1 , 1 , 1
Global Log Level= 0
CheckData=True
Encroach Param= -1, 0, 0, 0
BEGIN DESCRIPTION:
Multiple Run
END DESCRIPTION:

--- UNT071 IN NNOGR.f01 (steady flow) ---

Flow Title=Multiple
Number of Profiles=7
Profile Names=10-year,25-year,50-year,1pct_min,100-year,1pct_plu,500-year
River Rch & RM= UNT071 IN NNOGR,Reach-1,8630
     720    1026    1288    1183    1600    2164    2478
River Rch & RM= UNT071 IN NNOGR,Reach-1,4611
     844    1212    1529    1409    1906    2578    2977
Boundary for River Rch & Prof#=UNT071 IN NNOGR,Reach-1,1
Up Type=0
Dn Type=3
Dn Slope=0.005
Boundary for River Rch & Prof#=UNT071 IN NNOGR,Reach-1,2
Up Type=0
Dn Type=3
Dn Slope=0.005
Boundary for River Rch & Prof#=UNT071 IN NNOGR,Reach-1,3
Up Type=0
Dn Type=3
Dn Slope=0.005
Boundary for River Rch & Prof#=UNT071 IN NNOGR,Reach-1,4
Up Type=0
Dn Type=3
Dn Slope=0.005
Boundary for River Rch & Prof#=UNT071 IN NNOGR,Reach-1,5
Up Type=0
Dn Type=3
Dn Slope=0.005
Boundary for River Rch & Prof#=UNT071 IN NNOGR,Reach-1,6
Up Type=0
Dn Type=3
Dn Slope=0.005
Boundary for River Rch & Prof#=UNT071 IN NNOGR,Reach-1,7
Up Type=0
Dn Type=3
Dn Slope=0.005

--- UNT071 IN NNOGR.g01 (geometry) ---

Geom Title=Existing Conditions

River Reach=UNT071 IN NNOGR,Reach-1
Reach XY= 30
      2809578.47     10118918.73      2809414.32     10118244.81
      2809320.96     10118142.37      2809363.36     10118060.67
      2809001.06     10117699.77      2809007.62     10117258.91
      2808924.76     10117147.38      2809105.66     10116865.57
      2809095.09     10116587.40      2809261.91     10116364.27
      2809347.85     10116133.80      2809402.10     10116117.74
      2809303.07     10115761.02      2809141.48     10115618.19
      2809166.75     10115519.45      2809068.36     10115033.78
      2809227.53     10114723.70      2809148.33     10114363.53
      2809197.34     10114164.21      2809152.87     10113981.24
      2808974.78     10113800.55      2808938.95     10113613.65
      2809025.37     10113494.91      2808990.32     10113309.15
      2809141.22     10112754.87      2809444.36     10112316.88
      2809494.01     10112040.91      2809603.83     10112013.35
      2809528.71     10111478.56      2809628.47     10111353.73

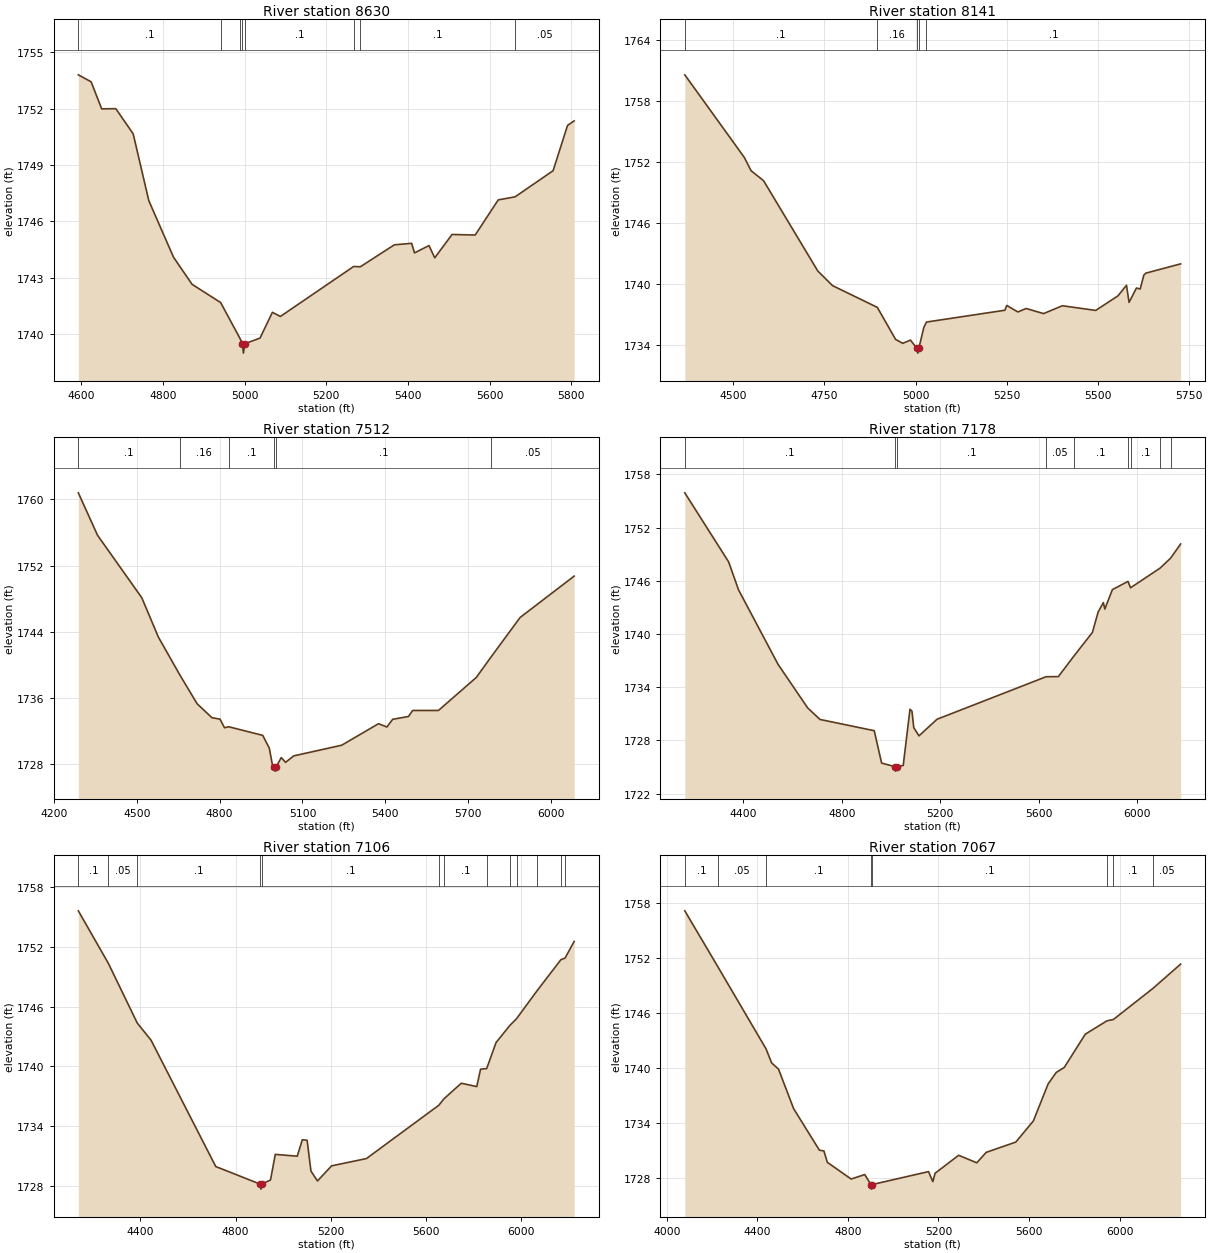
Type RM Length L Ch R = 1,8630,489,489,489
BEGIN DESCRIPTION:
UNT071 IN NNOGR 13.0
END DESCRIPTION:
XS GIS Cut Line= 3
      2809979.48     10118740.86      2809390.97     10118821.59
      2808956.08     10119264.30
#Sta/Elev= 30
  4592.7 1753.80  4624.0 1753.43  4649.9 1751.99  4684.6 1752.00  4727.1 1750.66
  4765.3 1747.11  4825.9 1744.10  4871.3 1742.66  4941.3 1741.69  4988.5 1739.79
  4994.5 1739.50  4997.2 1739.00  5000.5 1739.50  5037.8 1739.80  5068.1 1741.17
  5087.7 1740.95  5267.3 1743.61  5283.4 1743.59  5366.8 1744.76  5409.2 1744.84
  5416.2 1744.33  5451.7 1744.72  5465.8 1744.07  5508.2 1745.31  5564.8 1745.28
  5621.4 1747.15  5662.5 1747.31  5755.7 1748.70  5791.1 1751.11  5807.3 1751.35
#Mann=8,-1,0
  4592.7     0.1       0  4941.3    0.05       0  4988.5     0.1       0
  4994.5    0.07       0  5000.5     0.1       0  5267.3    0.05       0
  5283.4     0.1       0  5662.5    0.05       0
Bank Sta=4994.5,5000.5
Exp/Cntr=0.3,0.1

Type RM Length L Ch R = 1,8141,629,629,629
BEGIN DESCRIPTION:
UNT071 IN NNOGR 12.0
END DESCRIPTION:
XS GIS Cut Line= 2
      2810037.33     10118229.84      2808699.27     10118475.92
#Sta/Elev= 30
  4366.9 1760.54  4530.1 1752.44  4548.8 1751.13  4583.1 1750.15  4731.8 1741.29
  4772.5 1739.85  4895.2 1737.72  4945.3 1734.58  4964.8 1734.19  4986.0 1734.51
  5003.3 1733.73  5006.1 1733.23  5009.3 1733.73  5022.9 1735.77  5030.1 1736.28
  5245.3 1737.44  5250.4 1737.91  5280.8 1737.27  5303.5 1737.61  5351.4 1737.11
  5402.9 1737.88  5494.4 1737.42  5555.4 1738.85  5578.9 1739.89  5585.9 1738.21
  5606.2 1739.62  5616.4 1739.52  5626.5 1740.89  5632.0 1741.08  5727.4 1741.99
#Mann=5,-1,0
  4366.9     0.1       0  4895.2    0.16       0  5003.3    0.07       0
  5009.3    0.16       0  5030.1     0.1       0
Bank Sta=5003.3,5009.3
Exp/Cntr=0.3,0.1

Type RM Length L Ch R = 1,7512,334,334,334
BEGIN DESCRIPTION:
UNT071 IN NNOGR 11.0
END DESCRIPTION:
XS GIS Cut Line= 4
      2809878.00     10117743.46      2809476.91     10117756.48
      2808969.10     10117964.82      2808262.12     10118427.47
#Sta/Elev= 30
  4288.5 1760.78  4358.1 1755.65  4518.2 1748.11  4578.2 1743.36  4656.2 1738.77
  4718.6 1735.30  4772.0 1733.62  4801.4 1733.44  4817.8 1732.40  4832.9 1732.52
  4956.1 1731.48  4980.0 1729.93  4990.9 1727.96  4998.6 1727.66  5001.3 1727.16
  5004.6 1727.66  5023.2 1728.80  5038.8 1728.22  5068.2 1729.00  5242.1 1730.29
  5375.3 1732.89  5405.5 1732.49  5426.6 1733.42  5483.8 1733.76  5498.9 1734.49
  5592.4 1734.49  5729.4 1738.48  5781.2 1740.88  5887.9 1745.72  6083.6 1750.72
#Mann=6,-1,0
  4288.5     0.1       0  4656.2    0.16       0  4832.9     0.1       0
  4998.6    0.07       0  5004.6     0.1       0  5781.2    0.05       0
Bank Sta=4998.6,5004.6
Exp/Cntr=0.3,0.1

Type RM Length L Ch R = 1,7178,72,72,72
BEGIN DESCRIPTION:
Mapping XS 0a59cb66
END DESCRIPTION:
XS GIS Cut Line= 3
      2809836.33     10117662.73      2809000.35     10117628.88
      2808005.56     10118253.88
#Sta/Elev= 30
  4163.5 1755.92  4341.5 1748.12  4381.5 1744.98  4541.7 1736.58  4661.8 1731.67
  4711.8 1730.36  4932.0 1729.09  4962.0 1725.44  5016.4 1725.03  5019.1 1724.53
  5022.4 1725.03  5049.6 1725.17  5077.1 1731.51  5085.1 1731.29  5092.4 1729.43
  5113.6 1728.51  5186.7 1730.38  5629.6 1735.18  5679.0 1735.19  5741.6 1737.49
  5817.3 1740.18  5840.4 1742.48  5861.6 1743.54  5867.5 1742.81  5898.1 1745.00
  5961.6 1745.93  5971.9 1745.21  6091.7 1747.43  6134.5 1748.55  6175.0 1750.15
#Mann=9,-1,0
  4163.5     0.1       0  5016.4    0.07       0  5022.4     0.1       0
  5629.6    0.05       0  5741.6     0.1       0  5961.6    0.16       0
  5971.9     0.1       0  6091.7    0.16       0  6134.5     0.1       0
Bank Sta=5016.4,5022.4
Exp/Cntr=0.3,0.1

Type RM Length L Ch R = 1,7106,39,39,39
BEGIN DESCRIPTION:
Mapping XS abbdb983
END DESCRIPTION:
XS GIS Cut Line= 5
      2809857.13     10117618.46      2809471.70     10117535.13
      2808976.91     10117558.57      2808924.83     10117610.65
      2807946.92     10118159.42
#Sta/Elev= 30
  4138.9 1755.63  4265.2 1750.35  4386.8 1744.35  4444.5 1742.64  4716.7 1729.94
  4903.9 1728.17  4906.6 1727.67  4909.9 1728.17  4946.9 1728.59  4967.0 1731.16
  5059.4 1730.98  5080.6 1732.63  5100.9 1732.58  5117.0 1729.48  5144.4 1728.49
  5203.7 1730.01  5350.3 1730.74  5654.7 1736.10  5676.5 1736.75  5749.1 1738.31
  5814.1 1737.97  5830.1 1739.72  5855.8 1739.78  5895.1 1742.39  5953.3 1744.12
  5981.2 1744.79  6069.2 1747.65  6167.8 1750.72  6185.2 1750.88  6223.6 1752.55
#Mann=13,-1,0
  4138.9     0.1       0  4265.2    0.05       0  4386.8     0.1       0
  4903.9    0.07       0  4909.9     0.1       0  5654.7    0.05       0
  5676.5     0.1       0  5855.8    0.16       0  5953.3     0.1       0
  5981.2    0.16       0  6069.2    0.05       0  6167.8    0.16       0
  6185.2    0.05       0
Bank Sta=4903.9,4909.9
Exp/Cntr=0.3,0.1

Type RM Length L Ch R = 1,7067,901,901,901
BEGIN DESCRIPTION:
UNT071 IN NNOGR 10.0
END DESCRIPTION:
XS GIS Cut Line= 4
      2809911.85     10117574.20      2809523.79     10117483.04
      2808719.10     10117537.73      2807914.38     10118105.46
#Sta/Elev= 30
  4079.9 1757.14  4226.0 1751.04  4439.0 1742.08  4463.5 1740.56  4493.9 1739.88
  4560.7 1735.57  4674.3 1731.05  4694.3 1730.96  4709.6 1729.72  4814.6 1727.90
  4874.8 1728.39  4901.8 1727.30  4904.6 1726.80  4907.8 1727.30  5156.4 1728.71
  5175.5 1727.62  5185.5 1728.53  5289.4 1730.49  5369.5 1729.67  5411.3 1730.81
  5541.9 1731.93  5619.4 1734.23  5684.7 1738.27  5720.4 1739.52  5756.1 1740.07
  5848.8 1743.69  5944.6 1745.15  5972.8 1745.29  6147.0 1748.67  6269.9 1751.33
#Mann=8,-1,0
  4079.9     0.1       0  4226.0    0.05       0  4439.0     0.1       0
  4901.8    0.07       0  4907.8     0.1       0  5944.6    0.16       0
  5972.8     0.1       0  6147.0    0.05       0
Bank Sta=4901.8,4907.8
Exp/Cntr=0.3,0.1

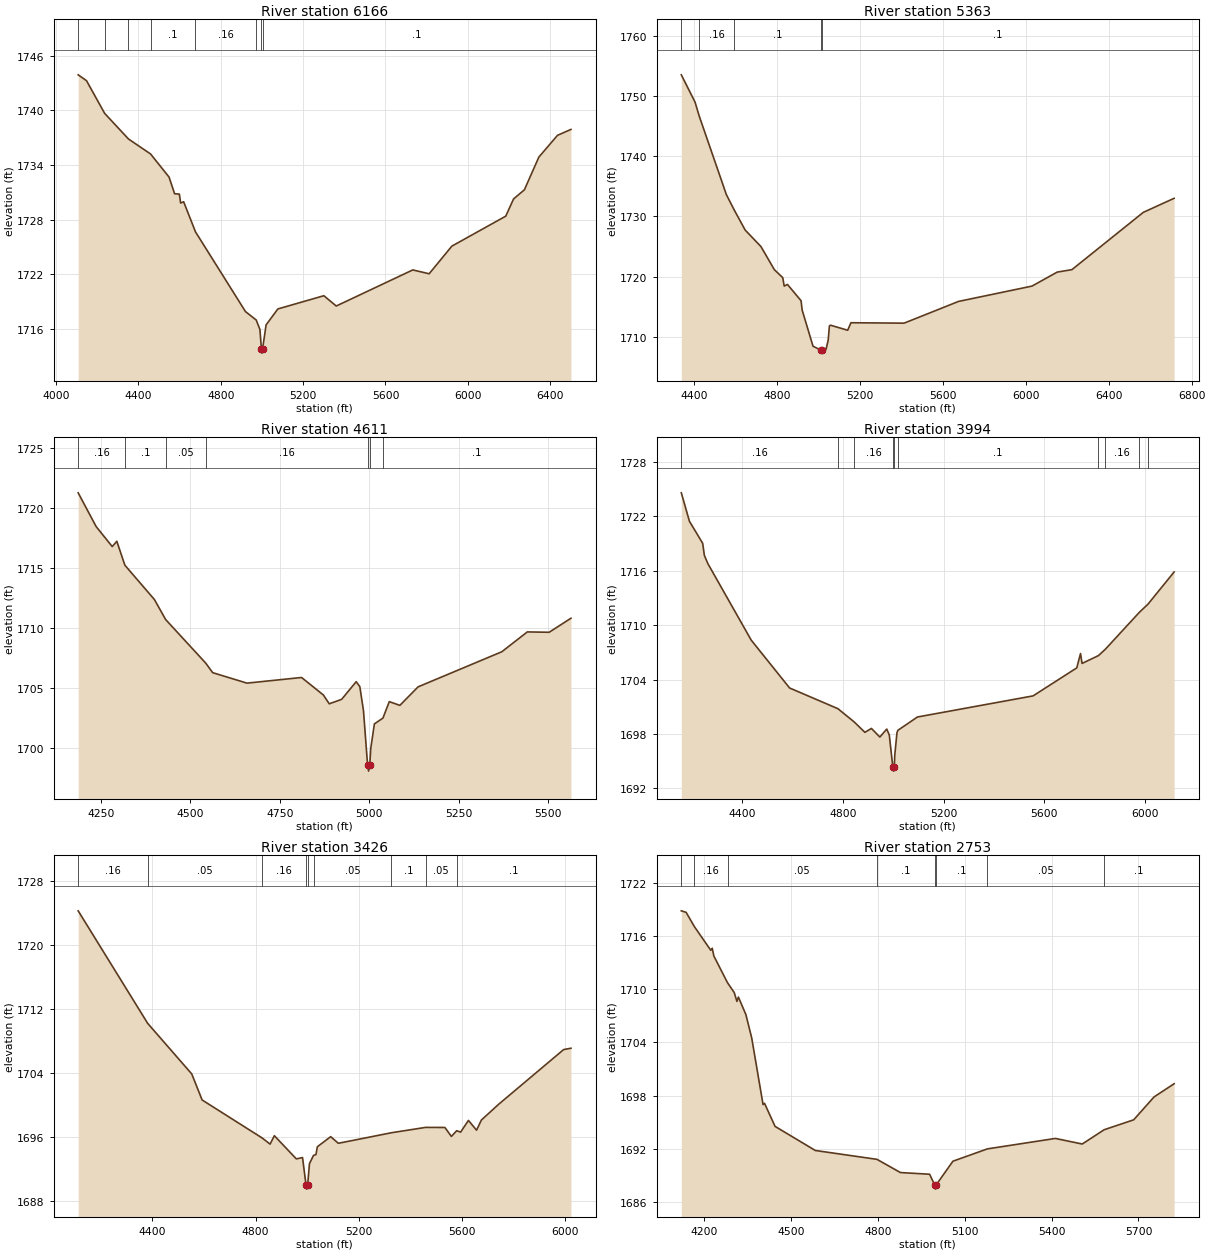
Type RM Length L Ch R = 1,6166,803,803,803
BEGIN DESCRIPTION:
UNT071 IN NNOGR 9.0
END DESCRIPTION:
XS GIS Cut Line= 4
      2809778.99     10117219.23      2809424.83     10116740.08
      2808508.16     10116687.99      2807633.31     10116776.52
#Sta/Elev= 30
  4107.7 1743.88  4148.1 1743.24  4236.3 1739.65  4352.0 1736.84  4459.5 1735.19
  4549.0 1732.66  4576.0 1730.83  4599.1 1730.79  4605.3 1729.81  4619.9 1729.95
  4677.4 1726.65  4920.2 1717.90  4972.5 1716.97  4990.4 1715.93  4997.4 1713.84
  5000.1 1713.34  5003.4 1713.84  5020.4 1716.44  5077.6 1718.19  5300.9 1719.64
  5361.0 1718.51  5732.7 1722.47  5812.3 1722.05  5922.4 1725.08  6184.2 1728.37
  6222.2 1730.26  6274.7 1731.26  6345.0 1734.85  6435.5 1737.24  6501.0 1737.89
#Mann=8,-1,0
  4107.7    0.05       0  4236.3     0.1       0  4352.0    0.16       0
  4459.5     0.1       0  4677.4    0.16       0  4972.5     0.1       0
  4997.4    0.07       0  5003.4     0.1       0
Bank Sta=4997.4,5003.4
Exp/Cntr=0.3,0.1

Type RM Length L Ch R = 1,5363,752,752,752
BEGIN DESCRIPTION:
UNT071 IN NNOGR 8.0
END DESCRIPTION:
XS GIS Cut Line= 3
      2810034.22     10116062.99      2809539.41     10116005.70
      2807742.98     10116552.44
#Sta/Elev= 30
  4339.5 1753.59  4405.7 1749.05  4425.7 1746.74  4556.7 1733.65  4594.7 1731.08
  4647.3 1727.75  4723.6 1724.99  4788.2 1721.14  4828.5 1719.82  4835.6 1718.41
  4851.2 1718.69  4916.9 1715.97  4922.2 1714.41  4974.5 1708.40  5012.4 1707.75
  5015.2 1707.25  5018.4 1707.75  5037.2 1707.89  5047.7 1709.42  5053.5 1711.78
  5058.7 1711.90  5141.7 1711.06  5157.3 1712.31  5413.5 1712.24  5676.2 1715.86
  6030.2 1718.41  6151.8 1720.74  6222.7 1721.15  6566.9 1730.69  6715.4 1733.03
#Mann=5,-1,0
  4339.5     0.1       0  4425.7    0.16       0  4594.7     0.1       0
  5012.4    0.07       0  5018.4     0.1       0
Bank Sta=5012.4,5018.4
Exp/Cntr=0.3,0.1

Type RM Length L Ch R = 1,4611,617,617,617
BEGIN DESCRIPTION:
UNT071 IN NNOGR 7.0
END DESCRIPTION:
XS GIS Cut Line= 2
      2809921.98     10115269.28      2808568.57     10115523.05
#Sta/Elev= 30
  4186.6 1721.23  4236.9 1718.42  4281.7 1716.76  4294.6 1717.20  4317.1 1715.21
  4399.7 1712.35  4431.0 1710.69  4542.6 1707.08  4562.5 1706.27  4658.2 1705.40
  4810.8 1705.87  4871.9 1704.41  4888.1 1703.68  4922.7 1704.05  4963.4 1705.52
  4973.6 1705.11  4983.8 1703.11  4995.3 1698.58  4998.0 1698.08  5001.3 1698.58
  5004.1 1699.96  5014.3 1702.01  5038.1 1702.49  5055.9 1703.86  5085.5 1703.55
  5136.4 1705.09  5370.4 1708.01  5441.6 1709.66  5502.7 1709.63  5563.6 1710.80
#Mann=7,-1,0
  4186.6    0.16       0  4317.1     0.1       0  4431.0    0.05       0
  4542.6    0.16       0  4995.3    0.07       0  5001.3    0.16       0
  5038.1     0.1       0
Bank Sta=4995.3,5001.3
Exp/Cntr=0.3,0.1

Type RM Length L Ch R = 1,3994,568,568,568
BEGIN DESCRIPTION:
UNT071 IN NNOGR 6.0
END DESCRIPTION:
XS GIS Cut Line= 3
      2809982.13     10114984.87      2808737.33     10114766.12
      2808164.41     10115156.75
#Sta/Elev= 30
  4158.2 1724.61  4190.5 1721.47  4243.1 1719.04  4249.8 1717.71  4263.5 1716.81
  4436.1 1708.35  4588.4 1703.08  4780.1 1700.80  4844.3 1699.35  4887.4 1698.19
  4913.3 1698.62  4946.8 1697.67  4974.2 1698.55  4984.3 1697.89  4998.1 1694.41
  5000.8 1693.91  5004.1 1694.41  5006.1 1695.70  5014.8 1698.16  5018.3 1698.41
  5096.0 1699.88  5555.4 1702.21  5728.9 1705.30  5743.8 1706.88  5749.9 1705.79
  5814.8 1706.65  5842.2 1707.35  5977.5 1711.43  6011.5 1712.32  6115.5 1715.88
#Mann=10,-1,0
  4158.2    0.16       0  4780.1    0.05       0  4844.3    0.16       0
  4998.1    0.07       0  5004.1    0.16       0  5018.3     0.1       0
  5814.8    0.05       0  5842.2    0.16       0  5977.5    0.05       0
  6011.5    0.16       0
Bank Sta=4998.1,5004.1
Exp/Cntr=0.3,0.1

Type RM Length L Ch R = 1,3426,673,673,673
BEGIN DESCRIPTION:
UNT071 IN NNOGR 5.0
END DESCRIPTION:
XS GIS Cut Line= 4
      2810038.32     10114409.45      2809491.45     10114379.07
      2808879.47     10114261.89      2808184.99     10114517.98
#Sta/Elev= 30
  4112.1 1724.27  4381.6 1710.20  4552.6 1703.87  4592.7 1700.62  4825.4 1695.87
  4856.3 1695.10  4872.9 1696.15  4958.1 1693.25  4982.1 1693.42  4995.8 1689.97
  4998.6 1689.47  5001.8 1689.97  5009.0 1692.66  5024.8 1693.69  5034.1 1693.79
  5039.6 1694.77  5091.3 1696.03  5121.0 1695.20  5326.7 1696.52  5459.5 1697.19
  5534.2 1697.18  5559.3 1696.06  5579.9 1696.77  5595.1 1696.60  5625.5 1698.06
  5657.0 1696.84  5675.7 1698.11  5742.3 1700.07  5994.6 1706.92  6023.1 1707.09
#Mann=9,-1,0
  4112.1    0.16       0  4381.6    0.05       0  4825.4    0.16       0
  4995.8    0.07       0  5001.8    0.16       0  5024.8    0.05       0
  5326.7     0.1       0  5459.5    0.05       0  5579.9     0.1       0
Bank Sta=4995.8,5001.8
Exp/Cntr=0.3,0.1

Type RM Length L Ch R = 1,2753,316,316,316
BEGIN DESCRIPTION:
UNT071 IN NNOGR 4.0
END DESCRIPTION:
XS GIS Cut Line= 3
      2809829.97     10113636.89      2808783.99     10113754.07
      2808375.97     10114257.58
#Sta/Elev= 30
  4122.3 1718.84  4138.9 1718.67  4167.6 1717.05  4224.0 1714.39  4229.1 1714.62
  4234.5 1713.75  4281.7 1710.73  4304.9 1709.62  4314.2 1708.62  4319.3 1709.11
  4345.2 1707.13  4365.3 1704.49  4404.4 1696.98  4409.5 1697.12  4445.8 1694.52
  4584.8 1691.80  4797.6 1690.80  4878.5 1689.31  4979.1 1689.12  4996.3 1687.94
  4999.0 1687.44  5002.3 1687.94  5059.6 1690.59  5178.5 1691.98  5413.2 1693.16
  5505.9 1692.53  5581.5 1694.14  5683.4 1695.26  5753.7 1697.84  5822.9 1699.33
#Mann=8,-1,0
  4122.3     0.1       0  4167.6    0.16       0  4281.7    0.05       0
  4797.6     0.1       0  4996.3    0.07       0  5002.3     0.1       0
  5178.5    0.05       0  5581.5     0.1       0
Bank Sta=4996.3,5002.3
Exp/Cntr=0.3,0.1

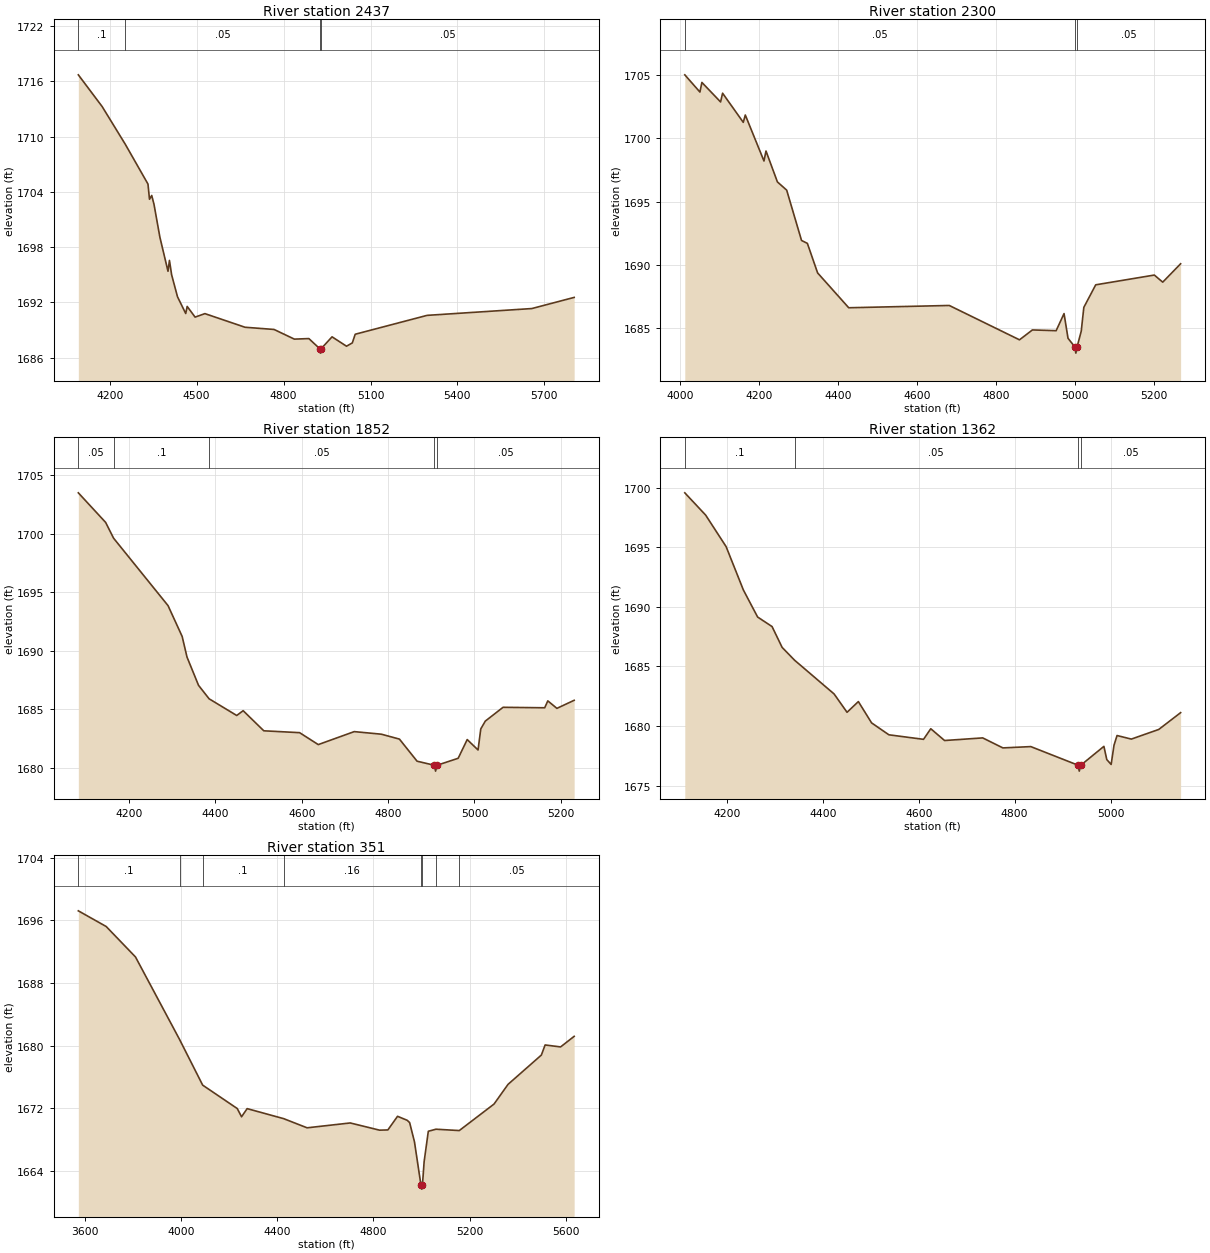
Type RM Length L Ch R = 1,2437,137,137,137
BEGIN DESCRIPTION:
UNT071 IN NNOGR 3.0
END DESCRIPTION:
XS GIS Cut Line= 5
      2809916.82     10113476.30      2809682.42     10113398.17
      2809339.54     10113454.59      2808801.35     10113458.93
      2808493.51     10113948.87
#Sta/Elev= 30
  4091.5 1716.72  4173.8 1713.27  4253.2 1709.20  4331.9 1704.86  4337.1 1703.21
  4344.8 1703.62  4352.7 1702.66  4373.0 1699.09  4401.0 1695.39  4406.0 1696.57
  4413.5 1695.01  4433.8 1692.62  4462.2 1690.80  4467.2 1691.57  4494.6 1690.41
  4528.4 1690.79  4666.9 1689.31  4767.1 1689.07  4837.2 1688.02  4887.2 1688.08
  4924.2 1687.00  4926.9 1686.50  4930.2 1687.00  4967.2 1688.27  5017.2 1687.25
  5037.2 1687.61  5047.2 1688.55  5295.2 1690.60  5656.8 1691.34  5802.9 1692.55
#Mann=4,-1,0
  4091.5     0.1       0  4253.2    0.05       0  4924.2    0.04       0
  4930.2    0.05       0
Bank Sta=4924.2,4930.2
Exp/Cntr=0.3,0.1

Type RM Length L Ch R = 1,2300,448,448,448
BEGIN DESCRIPTION:
Mapping XS 003d8508
END DESCRIPTION:
XS GIS Cut Line= 4
      2809968.90     10113201.23      2809463.24     10113296.72
      2808803.52     10113340.12      2808747.13     10113396.51
#Sta/Elev= 30
  4011.2 1705.00  4049.5 1703.64  4054.5 1704.40  4101.8 1702.86  4106.9 1703.55
  4159.3 1701.25  4164.4 1701.83  4211.7 1698.20  4216.8 1698.99  4245.7 1696.55
  4269.2 1695.90  4306.8 1691.93  4321.6 1691.70  4347.5 1689.37  4426.3 1686.62
  4680.9 1686.80  4858.7 1684.09  4891.4 1684.87  4951.5 1684.81  4971.5 1686.16
  4981.6 1684.21  4998.6 1683.54  5001.4 1683.04  5004.6 1683.54  5015.1 1684.78
  5021.6 1686.65  5051.7 1688.43  5200.1 1689.20  5221.4 1688.64  5266.7 1690.09
#Mann=3,-1,0
  4011.2    0.05       0  4998.6    0.04       0  5004.6    0.05       0
Bank Sta=4998.6,5004.6
Exp/Cntr=0.3,0.1

Type RM Length L Ch R = 1,1852,490,490,490
BEGIN DESCRIPTION:
Mapping XS 8427627b
END DESCRIPTION:
XS GIS Cut Line= 3
      2809968.87     10113170.85      2809024.87     10112880.05
      2808912.73     10112994.35
#Sta/Elev= 30
  4082.9 1703.51  4146.1 1700.98  4164.5 1699.63  4290.6 1693.86  4323.3 1691.22
  4334.5 1689.46  4361.2 1687.04  4385.6 1685.89  4449.6 1684.46  4464.5 1684.87
  4512.3 1683.15  4595.2 1682.99  4638.4 1681.97  4721.6 1683.08  4784.4 1682.86
  4826.3 1682.44  4867.1 1680.55  4907.3 1680.20  4910.0 1679.70  4913.3 1680.20
  4962.3 1680.80  4983.2 1682.40  5008.3 1681.51  5014.6 1683.31  5025.1 1683.98
  5066.2 1685.16  5162.6 1685.12  5169.8 1685.71  5190.9 1685.07  5230.8 1685.76
#Mann=5,-1,0
  4082.9    0.05       0  4164.5     0.1       0  4385.6    0.05       0
  4907.3    0.03       0  4913.3    0.05       0
Bank Sta=4907.3,4913.3
Exp/Cntr=0.3,0.1

Type RM Length L Ch R = 1,1362,1011,1011,1011
BEGIN DESCRIPTION:
UNT071 IN NNOGR 2.0
END DESCRIPTION:
XS GIS Cut Line= 2
      2810060.39     10112962.35      2809197.83     10112391.95
#Sta/Elev= 30
  4112.1 1699.58  4155.6 1697.71  4198.3 1695.06  4234.3 1691.42  4264.0 1689.15
  4294.1 1688.35  4315.1 1686.60  4340.9 1685.53  4423.5 1682.69  4450.5 1681.15
  4474.1 1682.05  4501.7 1680.26  4537.8 1679.26  4610.0 1678.88  4625.1 1679.77
  4653.9 1678.78  4733.4 1679.00  4775.5 1678.16  4833.7 1678.27  4932.1 1676.71
  4934.8 1676.21  4938.1 1676.71  4986.2 1678.29  4992.2 1677.18  5001.3 1676.77
  5007.3 1678.39  5013.6 1679.20  5043.4 1678.90  5100.6 1679.71  5146.2 1681.12
#Mann=4,-1,0
  4112.1     0.1       0  4340.9    0.05       0  4932.1    0.03       0
  4938.1    0.05       0
Bank Sta=4932.1,4938.1
Exp/Cntr=0.3,0.1

Type RM Length L Ch R = 1,351,0,0,0
BEGIN DESCRIPTION:
UNT071 IN NNOGR 1.0
END DESCRIPTION:
XS GIS Cut Line= 4
      2810229.58     10112816.26      2809714.37     10111655.10
      2809452.92     10111632.03      2809183.78     10112085.71
#Sta/Elev= 30
  3573.6 1697.21  3689.3 1695.21  3811.1 1691.32  3994.3 1680.78  4090.3 1674.95
  4234.0 1671.96  4251.8 1670.91  4275.1 1671.95  4426.9 1670.67  4524.2 1669.50
  4703.4 1670.12  4825.3 1669.20  4859.9 1669.23  4900.0 1670.97  4940.2 1670.46
  4950.2 1670.17  4970.3 1667.72  4997.4 1662.17  5000.2 1661.67  5003.4 1662.17
  5010.5 1665.18  5027.9 1669.06  5059.7 1669.32  5156.6 1669.15  5300.8 1672.53
  5359.2 1675.05  5497.6 1678.79  5513.2 1680.08  5577.5 1679.83  5633.9 1681.18
#Mann=8,-1,0
  3573.6     0.1       0  3994.3    0.05       0  4090.3     0.1       0
  4426.9    0.16       0  4997.4    0.07       0  5003.4    0.16       0
  5059.7     0.1       0  5156.6    0.05       0
Bank Sta=4997.4,5003.4
Exp/Cntr=0.3,0.1

Chan Stop Cuts=-1