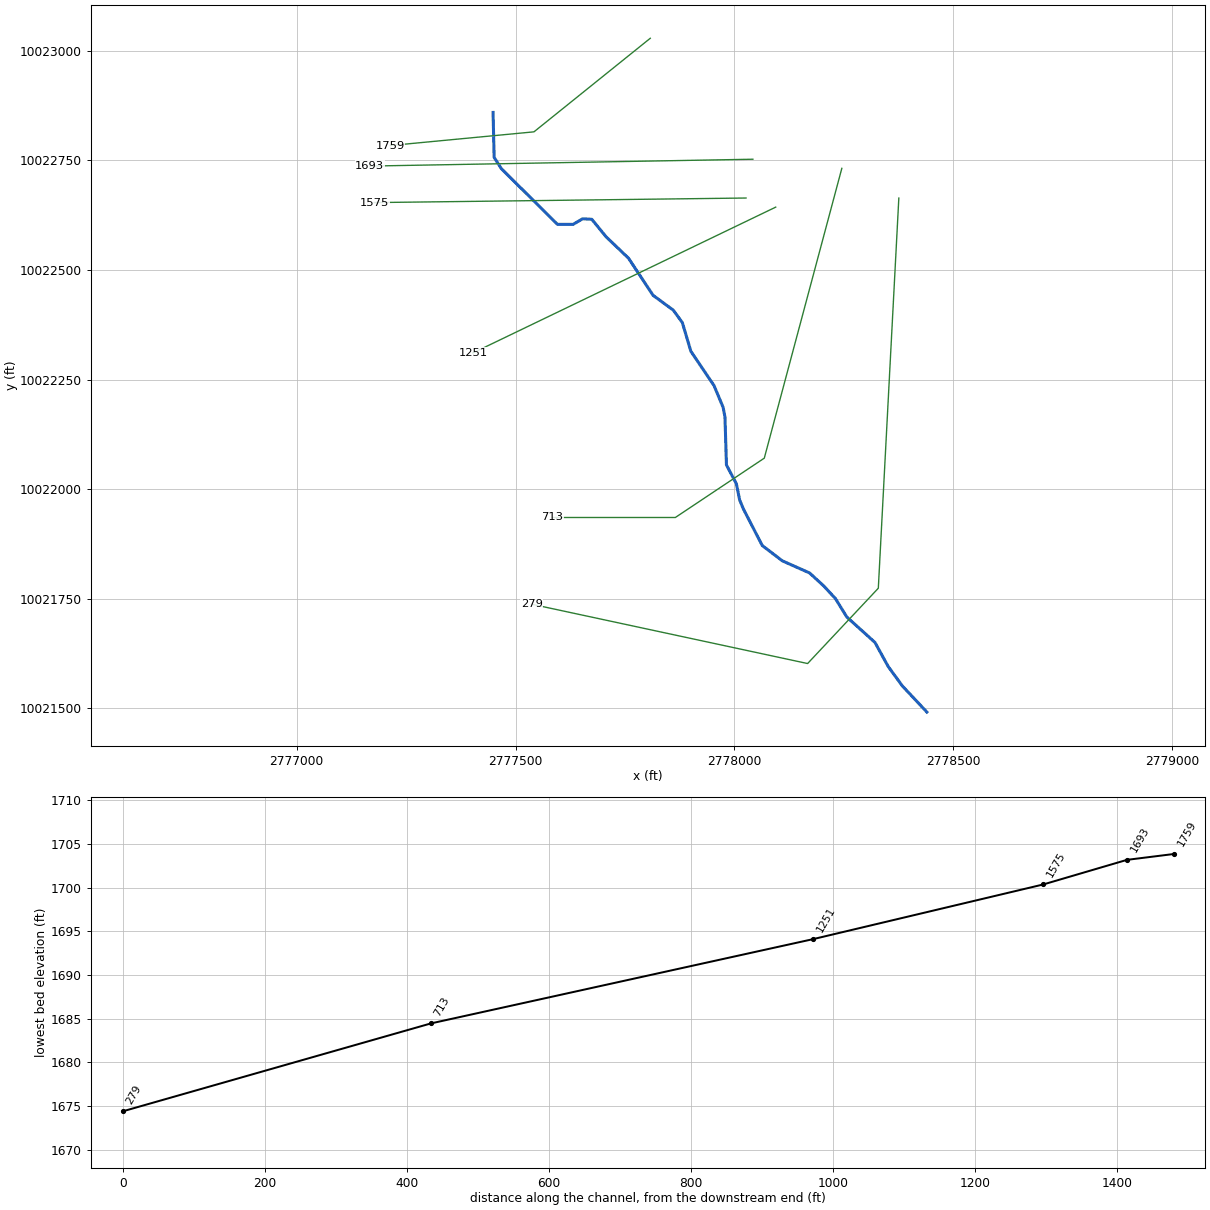
--- UNT071 IN SNOGR.prj (project) ---

Proj Title=UNT071 IN SNOGR Base Level Engineering
Current Plan=p01
Default Exp/Contr=0.3,0.1
English Units
Geom File=g01
Flow File=f01
Plan File=p01
Y Axis Title=Elevation
X Axis Title(PF)=Main Channel Distance
X Axis Title(XS)=Station
BEGIN DESCRIPTION:
UNT071 IN SNOGR
END DESCRIPTION:
DSS Export Rating Curves= 0
DSS Export Rating Curve Sorted= 0
DSS Export Volume Flow Curves= 0
DXF OffsetX= 0
DXF OffsetY= 0
DXF ScaleX= 1
DXF ScaleY= 10

--- UNT071 IN SNOGR.p01 (plan) ---

Plan Title=Multiple Run
Short Identifier=Multiple
Geom File=g01
Flow File=f01
Subcritical Flow
K Sum by GR= 0
Std Step Tol= 0.01
Critical Tol= 0.01
Num of Std Step Trials= 20
Max Error Tol= 0.3
Flow Tol Ratio= 0.001
Split Flow NTrial= 30
Split Flow Tol= 0.02
Split Flow Ratio= 0.02
Log Output Level= 0
Friction Slope Method= 1
Unsteady Friction Slope Method= 2
Unsteady Bridges Friction Slope Method= 1
Parabolic Critical Depth
Global Vel Dist=  1 , 1 , 1
Global Log Level= 0
CheckData=True
Encroach Param= -1, 0, 0, 0
BEGIN DESCRIPTION:
Multiple Run
END DESCRIPTION:

--- UNT071 IN SNOGR.f01 (steady flow) ---

Flow Title=Multiple
Number of Profiles=7
Profile Names=10-year,25-year,50-year,1pct_min,100-year,1pct_plu,500-year
River Rch & RM= UNT071 IN SNOGR,Reach-1,1759
     492     693     864     790    1068    1445    1640
Boundary for River Rch & Prof#=UNT071 IN SNOGR,Reach-1,1
Up Type=0
Dn Type=3
Dn Slope=0.005
Boundary for River Rch & Prof#=UNT071 IN SNOGR,Reach-1,2
Up Type=0
Dn Type=3
Dn Slope=0.005
Boundary for River Rch & Prof#=UNT071 IN SNOGR,Reach-1,3
Up Type=0
Dn Type=3
Dn Slope=0.005
Boundary for River Rch & Prof#=UNT071 IN SNOGR,Reach-1,4
Up Type=0
Dn Type=3
Dn Slope=0.005
Boundary for River Rch & Prof#=UNT071 IN SNOGR,Reach-1,5
Up Type=0
Dn Type=3
Dn Slope=0.005
Boundary for River Rch & Prof#=UNT071 IN SNOGR,Reach-1,6
Up Type=0
Dn Type=3
Dn Slope=0.005
Boundary for River Rch & Prof#=UNT071 IN SNOGR,Reach-1,7
Up Type=0
Dn Type=3
Dn Slope=0.005

--- UNT071 IN SNOGR.g01 (geometry) ---

Geom Title=Existing Conditions
Program Version=4.10

River Reach=UNT071 IN SNOGR ,Reach-1
Reach XY= 30
      2777448.61     10022859.67      2777451.04     10022757.17
       2777467.5     10022731.32      2777595.78     10022604.21
      2777631.37     10022604.21      2777653.22       10022617.
      2777674.15     10022615.76       2777706.4     10022576.21
      2777757.84     10022527.08      2777814.06     10022442.22
      2777860.21     10022408.38      2777880.82      10022380.1
      2777900.36     10022314.53      2777953.22     10022236.27
        2777974.      10022186.6      2777978.23     10022164.38
      2777981.62     10022055.04      2778004.31     10022012.01
      2778011.78      10021975.1      2778020.36     10021954.51
      2778063.42     10021871.12      2778109.36     10021836.18
      2778171.34     10021808.64      2778203.72     10021779.02
      2778230.37     10021750.28      2778256.52     10021708.01
      2778320.76     10021650.04      2778351.16     10021594.83
      2778383.31     10021550.76      2778439.29     10021491.12

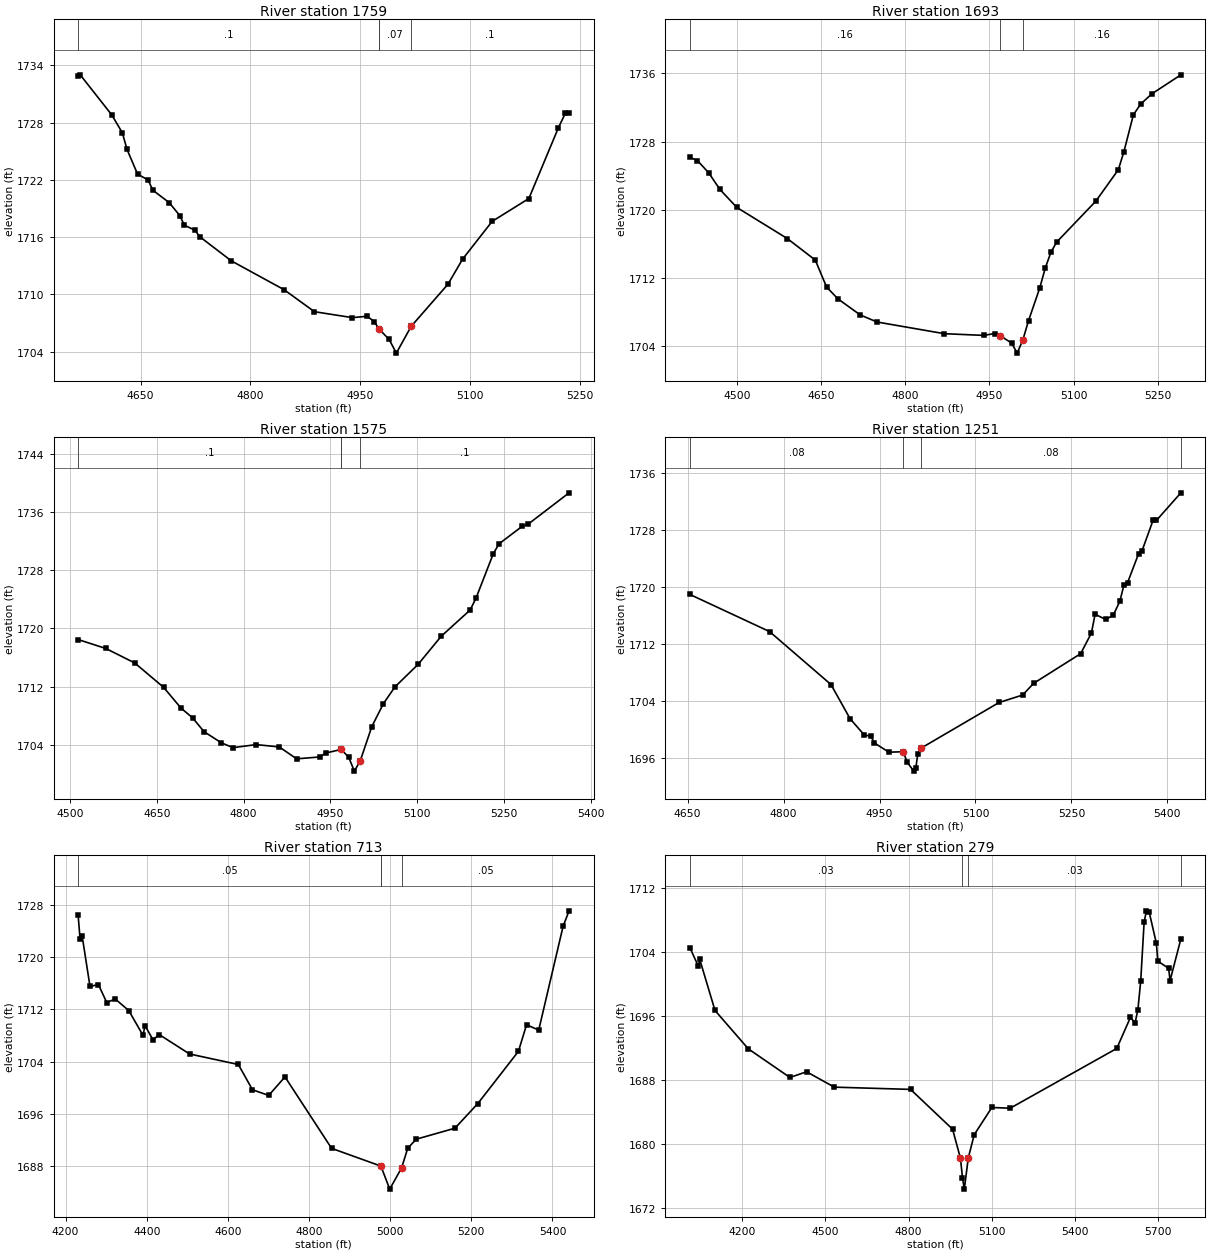
Type RM Length L Ch R = 1 ,1759    ,66,66,66
BEGIN DESCRIPTION:
UNT071 IN SNOGR 3.0
END DESCRIPTION:
XS GIS Cut Line= 3
      2777807.64     10023028.95      2777541.99     10022815.38
      2777213.83     10022784.13
#Sta/Elev= 30
  4564.6 1732.93  4567.5 1733.01  4610.6 1728.81    4625 1726.94  4631.4  1725.2
  4645.8 1722.61  4660.2 1721.99  4666.7 1720.92    4689 1719.62  4703.4 1718.27
  4709.8 1717.25  4724.2 1716.73  4730.7 1716.05  4773.8 1713.52  4845.8  1710.5
  4887.4 1708.19  4939.1 1707.57  4959.2 1707.71  4969.3 1707.15  4974.9 1706.43
  4989.4 1705.28  4999.2 1703.85  5019.5 1706.66  5069.7 1711.07  5089.8 1713.71
    5130 1717.65  5180.2 1720.05  5220.4 1727.44  5230.2 1729.02  5235.1 1729.02
#Mann= 4 ,-1 , 0
  4564.6      .1       0  4974.9     .05       0  4974.9     .07       0
  5019.5      .1       0
Bank Sta=4974.9,5019.5
XS Rating Curve= 0 ,0
Exp/Cntr=0.3,0.1

Type RM Length L Ch R = 1 ,1693    ,118,118,118
BEGIN DESCRIPTION:
Mapping XS 36b63b83
END DESCRIPTION:
XS GIS Cut Line= 2
        2778042.     10022752.88      2777166.94     10022737.26
#Sta/Elev= 30
  4416.1 1726.14  4429.6 1725.76  4449.6 1724.33  4469.6 1722.38  4499.7 1720.27
  4589.7 1716.62  4639.7 1714.09  4659.7 1710.94  4679.7 1709.56  4719.7 1707.66
  4749.7 1706.83  4869.7 1705.46  4939.7 1705.26  4959.7 1705.48  4969.7 1705.21
  4989.7 1704.35  4999.5 1703.18  5009.7 1704.74  5019.7 1706.98  5039.7 1710.81
  5049.7 1713.19  5059.7 1715.01  5069.7 1716.19  5139.8 1721.01  5179.8 1724.69
  5189.8 1726.81  5206.7 1731.14  5219.8  1732.4  5239.8  1733.6  5291.3 1735.82
#Mann= 3 , 0 , 0
  4416.1     .16       0  4969.7     .07       0  5009.7     .16       0
Bank Sta=4969.7,5009.7
XS Rating Curve= 0 ,0
Exp/Cntr=0.3,0.1

Type RM Length L Ch R = 1 ,1575    ,324,324,324
BEGIN DESCRIPTION:
Mapping XS 9fb75265
END DESCRIPTION:
XS GIS Cut Line= 2
      2778026.33     10022664.34       2777177.4     10022653.92
#Sta/Elev= 30
  4513.9 1718.47  4561.8 1717.24  4611.8 1715.25  4661.8 1711.89  4691.8 1709.04
  4711.8  1707.7  4731.8 1705.78  4761.8 1704.25  4781.8 1703.59  4821.8 1704.01
  4861.8 1703.69  4891.8 1702.05  4931.8 1702.31  4941.8 1702.85  4968.9 1703.34
  4981.8 1702.28  4991.6 1700.36  5001.8 1701.77  5021.8 1706.49  5041.8 1709.64
  5061.8 1711.95  5101.8 1715.05  5141.8 1718.92  5191.8 1722.53  5201.8 1724.13
  5231.8 1730.27  5241.8 1731.64  5281.8 1734.05  5291.8 1734.33  5362.9 1738.66
#Mann= 4 ,-1 , 0
  4513.9      .1       0  4968.9     .16       0  4968.9     .07       0
  5001.8      .1       0
Bank Sta=4968.9,5001.8
XS Rating Curve= 0 ,0
Exp/Cntr=0.3,0.1

Type RM Length L Ch R = 1 ,1251    ,538,538,538
BEGIN DESCRIPTION:
Mapping XS 40e5f0c0
END DESCRIPTION:
XS GIS Cut Line= 2
      2778094.09     10022643.52      2777402.41     10022310.68
#Sta/Elev= 30
  4653.5 1718.89  4778.1 1713.68  4874.1 1706.25  4903.9 1701.46  4926.1 1699.17
  4936.5    1699    4942 1698.05  4964.6 1696.76  4987.3 1696.82  4992.8  1695.4
  5003.5  1694.1  5006.8  1694.6  5009.9 1696.56  5015.4 1697.35  5136.9 1703.73
  5173.8 1704.78  5190.9 1706.42  5264.4 1710.58  5281.2 1713.47    5287 1716.11
  5303.4 1715.39  5315.2 1715.95  5325.6 1717.91  5332.2 1720.25  5337.8 1720.55
  5354.9 1724.58  5360.4 1725.02  5377.5 1729.27    5383 1729.29  5421.1 1733.15
#Mann= 4 ,-1 , 0
  4653.5     .08       0  4987.3     .05       0  5015.4     .08       0
  5421.1      .1       0
Bank Sta=4987.3,5015.4
XS Rating Curve= 0 ,0
Exp/Cntr=0.3,0.1

Type RM Length L Ch R = 1 ,713     ,434,434,434
BEGIN DESCRIPTION:
UNT071 IN SNOGR 2.0
END DESCRIPTION:
XS GIS Cut Line= 4
      2778245.12     10022732.06      2778068.03     10022070.59
      2777864.91     10021935.17      2777583.69     10021935.17
#Sta/Elev= 30
  4230.8  1726.5  4235.7 1722.73  4240.9 1723.21  4260.1 1715.52  4280.9  1715.8
  4301.5 1713.03  4322.2  1713.6  4355.8 1711.81  4390.7 1708.02  4395.9  1709.5
  4415.4 1707.33  4430.7 1708.14  4505.6 1705.16  4625.7 1703.55  4660.6 1699.68
  4700.6 1698.81  4740.7 1701.65  4855.6  1690.7  4977.1 1687.98  4998.9 1684.45
  5028.1  1687.7  5043.2 1690.71  5064.2  1692.1  5159.7 1693.79  5216.1 1697.57
  5316.1 1705.57  5336.1 1709.64  5366.1 1708.82  5426.1 1724.71  5440.9  1727.1
#Mann= 4 ,-1 , 0
  4230.8     .05       0  4977.1      .1       0  4977.1     .03       0
  5028.1     .05       0
Bank Sta=4977.1,5028.1
XS Rating Curve= 0 ,0
Exp/Cntr=0.3,0.1

Type RM Length L Ch R = 1 ,279     ,0,0,0
BEGIN DESCRIPTION:
UNT071 IN SNOGR 1.0
END DESCRIPTION:
XS GIS Cut Line= 4
      2778375.32     10022664.32      2778328.45     10021773.72
      2778166.99     10021601.84      2777536.82     10021737.25
#Sta/Elev= 30
  4010.7 1704.52  4041.2 1702.21  4046.2 1703.06  4101.4 1696.68  4221.6 1691.89
  4371.8 1688.32  4431.9 1689.03    4532 1687.11  4807.2 1686.83  4958.9 1681.86
  4987.3 1678.23  4994.6 1675.82  5001.2 1674.38  5015.6 1678.28  5037.1 1681.18
  5100.6 1684.57  5166.8 1684.48  5551.5 1691.94  5600.9 1695.82  5617.6 1695.12
  5627.8 1696.78    5638 1700.38  5650.3 1707.72  5658.5 1709.12  5668.7 1708.94
  5694.5 1705.06  5699.6 1702.84  5738.8 1701.94  5743.9 1700.41  5782.9 1705.61
#Mann= 4 ,-1 , 0
  4010.7     .03       0  4994.6    .025       0  5015.6     .03       0
  5782.9     .16       0
Bank Sta=4987.3,5015.6
XS Rating Curve= 0 ,0
Exp/Cntr=0.3,0.1

Chan Stop Cuts=-1
Use User Specified Reach Order=0
Composite Channel Slope=5