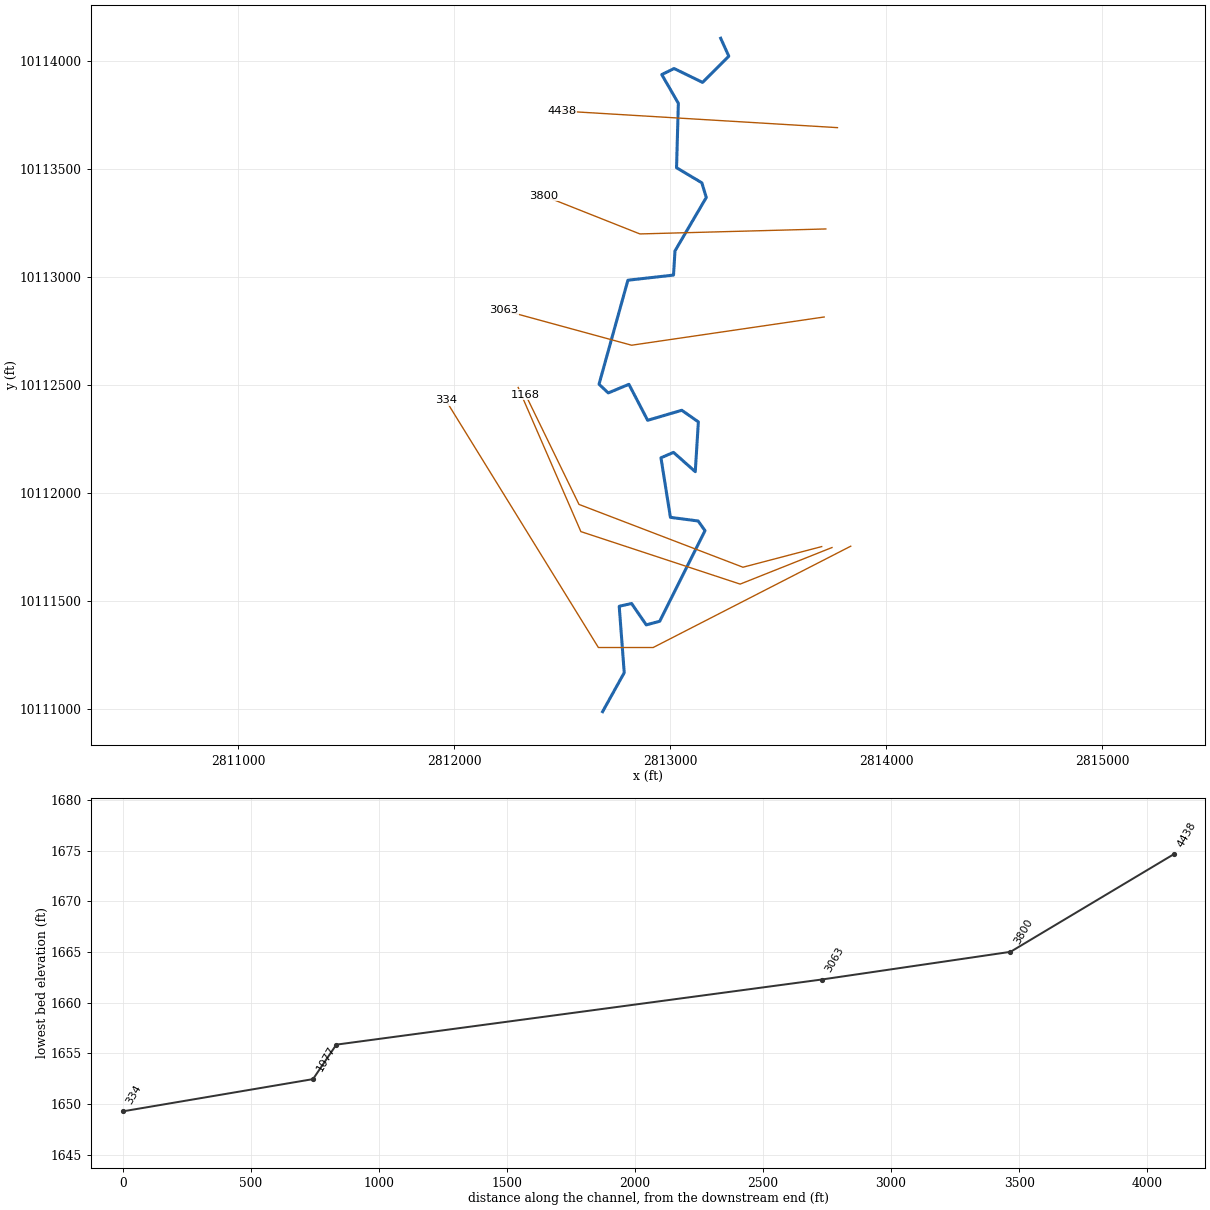
--- UNT072 IN NNOGR.prj (project) ---

Proj Title=UNT072 IN NNOGR Base Level Engineering
Current Plan=p01
Default Exp/Contr=0.3,0.1
English Units
Geom File=g01
Flow File=f01
Plan File=p01
BEGIN DESCRIPTION:
UNT072 IN NNOGR
END DESCRIPTION:

--- UNT072 IN NNOGR.p01 (plan) ---

Plan Title=Multiple Run
Short Identifier=Multiple
Geom File=g01
Flow File=f01
Subcritical Flow
K Sum by GR= 0
Std Step Tol= 0.01
Critical Tol= 0.01
Num of Std Step Trials= 20
Max Error Tol= 0.3
Flow Tol Ratio= 0.001
Split Flow NTrial= 30
Split Flow Tol= 0.02
Split Flow Ratio= 0.02
Log Output Level= 0
Friction Slope Method= 1
Unsteady Friction Slope Method= 2
Unsteady Bridges Friction Slope Method= 1
Parabolic Critical Depth
Global Vel Dist=  1 , 1 , 1
Global Log Level= 0
CheckData=True
Encroach Param= -1, 0, 0, 0
BEGIN DESCRIPTION:
Multiple Run
END DESCRIPTION:

--- UNT072 IN NNOGR.f01 (steady flow) ---

Flow Title=Multiple
Number of Profiles=7
Profile Names=10-year,25-year,50-year,1pct_min,100-year,1pct_plu,500-year
River Rch & RM= UNT072 IN NNOGR,Reach-1,4438
     566     791     979     887    1200    1623    1808
River Rch & RM= UNT072 IN NNOGR,Reach-1,3800
     688     970    1207    1098    1485    2008    2257
Boundary for River Rch & Prof#=UNT072 IN NNOGR,Reach-1,1
Up Type=0
Dn Type=3
Dn Slope=0.005
Boundary for River Rch & Prof#=UNT072 IN NNOGR,Reach-1,2
Up Type=0
Dn Type=3
Dn Slope=0.005
Boundary for River Rch & Prof#=UNT072 IN NNOGR,Reach-1,3
Up Type=0
Dn Type=3
Dn Slope=0.005
Boundary for River Rch & Prof#=UNT072 IN NNOGR,Reach-1,4
Up Type=0
Dn Type=3
Dn Slope=0.005
Boundary for River Rch & Prof#=UNT072 IN NNOGR,Reach-1,5
Up Type=0
Dn Type=3
Dn Slope=0.005
Boundary for River Rch & Prof#=UNT072 IN NNOGR,Reach-1,6
Up Type=0
Dn Type=3
Dn Slope=0.005
Boundary for River Rch & Prof#=UNT072 IN NNOGR,Reach-1,7
Up Type=0
Dn Type=3
Dn Slope=0.005

--- UNT072 IN NNOGR.g01 (geometry) ---

Geom Title=Existing Conditions

River Reach=UNT072 IN NNOGR,Reach-1
Reach XY= 30
      2813233.72     10114106.68      2813271.28     10114023.55
      2813149.75     10113902.37      2813017.81     10113966.61
      2812960.86     10113938.48      2813037.60     10113805.50
      2813029.26     10113507.23      2813146.31     10113437.61
      2813166.97     10113369.55      2813022.03     10113122.15
      2813015.30     10113010.24      2812803.97     10112986.50
      2812670.24     10112504.97      2812712.84     10112464.62
      2812808.61     10112504.52      2812895.38     10112337.88
      2813053.52     10112384.32      2813130.31     10112330.52
      2813115.90     10112100.01      2813015.21     10112189.42
      2812957.05     10112164.24      2813000.89     10111888.64
      2813129.36     10111871.71      2813161.04     10111827.00
      2812951.19     10111407.52      2812888.91     10111390.81
      2812821.04     10111489.70      2812763.71     10111476.99
      2812786.92     10111169.37      2812686.70     10110988.97

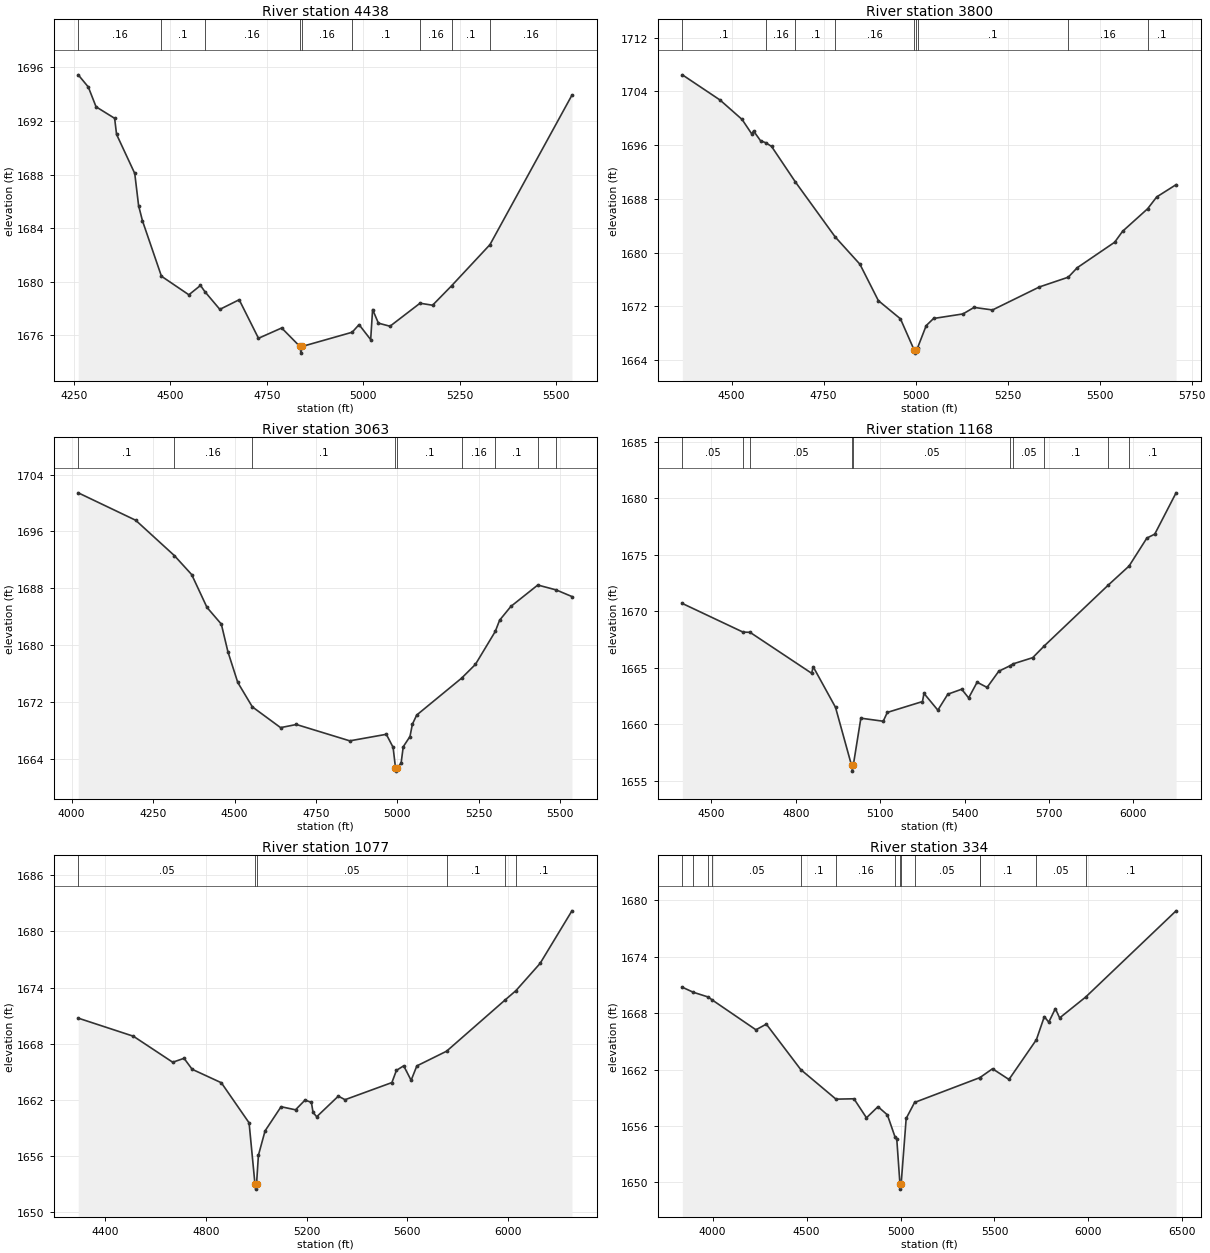
Type RM Length L Ch R = 1,4438,638,638,638
BEGIN DESCRIPTION:
UNT072 IN NNOGR 5.0
END DESCRIPTION:
XS GIS Cut Line= 2
      2813774.56     10113692.88      2812498.08     10113769.78
#Sta/Elev= 30
  4261.7 1695.45  4287.8 1694.54  4307.9 1693.06  4356.0 1692.20  4361.0 1691.00
  4408.1 1688.08  4418.1 1685.67  4428.1 1684.54  4477.2 1680.40  4548.3 1679.01
  4578.4 1679.71  4589.6 1679.25  4628.5 1677.92  4678.6 1678.64  4728.6 1675.76
  4788.7 1676.53  4835.8 1675.15  4838.6 1674.65  4841.8 1675.15  4971.2 1676.21
  4989.1 1676.78  5019.2 1675.66  5024.2 1677.91  5039.2 1676.89  5069.3 1676.66
  5147.0 1678.38  5179.5 1678.23  5229.0 1679.69  5328.2 1682.76  5540.5 1693.93
#Mann=9,-1,0
  4261.7    0.16       0  4477.2     0.1       0  4589.6    0.16       0
  4835.8    0.07       0  4841.8    0.16       0  4971.2     0.1       0
  5147.0    0.16       0  5229.0     0.1       0  5328.2    0.16       0
Bank Sta=4835.8,4841.8
Exp/Cntr=0.3,0.1

Type RM Length L Ch R = 1,3800,737,737,737
BEGIN DESCRIPTION:
UNT072 IN NNOGR 4.0
END DESCRIPTION:
XS GIS Cut Line= 3
      2813720.73     10113223.81      2812859.47     10113200.74
      2812413.43     10113377.62
#Sta/Elev= 30
  4366.3 1706.47  4468.6 1702.72  4528.6 1699.82  4554.8 1697.67  4559.8 1698.10
  4578.6 1696.66  4592.4 1696.36  4608.6 1695.81  4673.2 1690.53  4781.6 1682.32
  4848.7 1678.26  4898.8 1672.84  4958.8 1670.13  4995.8 1665.52  4998.5 1665.02
  5001.8 1665.52  5005.3 1665.80  5028.8 1669.12  5048.8 1670.18  5128.8 1670.86
  5158.8 1671.83  5208.9 1671.45  5336.5 1674.88  5414.8 1676.33  5439.1 1677.74
  5540.9 1681.54  5562.4 1683.17  5630.3 1686.52  5655.2 1688.29  5707.7 1690.11
#Mann=9,-1,0
  4366.3     0.1       0  4592.4    0.16       0  4673.2     0.1       0
  4781.6    0.16       0  4995.8    0.07       0  5001.8    0.16       0
  5005.3     0.1       0  5414.8    0.16       0  5630.3     0.1       0
Bank Sta=4995.8,5001.8
Exp/Cntr=0.3,0.1

Type RM Length L Ch R = 1,3063,1895,1895,1895
BEGIN DESCRIPTION:
UNT072 IN NNOGR 3.0
END DESCRIPTION:
XS GIS Cut Line= 3
      2813713.03     10112816.25      2812821.02     10112685.53
      2812228.89     10112847.02
#Sta/Elev= 30
  4020.3 1701.44  4196.7 1697.58  4315.2 1692.62  4368.5 1689.94  4415.5 1685.32
  4459.5 1682.97  4479.7 1679.09  4510.0 1674.76  4554.7 1671.33  4641.4 1668.41
  4689.9 1668.85  4853.7 1666.55  4965.9 1667.47  4986.7 1665.64  4994.0 1662.79
  4996.8 1662.29  5000.0 1662.79  5011.3 1663.41  5017.8 1665.72  5038.5 1667.16
  5045.9 1668.89  5059.2 1670.18  5196.7 1675.36  5239.3 1677.30  5300.3 1681.94
  5313.6 1683.52  5348.2 1685.46  5430.8 1688.47  5487.3 1687.78  5535.6 1686.85
#Mann=9,-1,0
  4020.3     0.1       0  4315.2    0.16       0  4554.7     0.1       0
  4994.0    0.07       0  5000.0     0.1       0  5196.7    0.16       0
  5300.3     0.1       0  5430.8    0.16       0  5487.3     0.1       0
Bank Sta=4994,5000
Exp/Cntr=0.3,0.1

Type RM Length L Ch R = 1,1168,91,91,91
BEGIN DESCRIPTION:
UNT072 IN NNOGR 2.0
END DESCRIPTION:
XS GIS Cut Line= 4
      2813701.56     10111753.22      2813336.94     10111657.72
      2812577.39     10111948.52      2812330.00     10112456.33
#Sta/Elev= 30
  4396.6 1670.69  4612.1 1668.16  4637.2 1668.14  4856.2 1664.52  4861.6 1665.10
  4941.0 1661.51  4998.1 1656.37  5000.9 1655.87  5004.1 1656.37  5031.1 1660.55
  5110.6 1660.28  5125.2 1661.06  5250.1 1662.02  5255.5 1662.74  5304.8 1661.26
  5340.2 1662.67  5389.6 1663.11  5414.3 1662.34  5444.4 1663.73  5479.8 1663.27
  5521.4 1664.70  5561.0 1665.18  5572.2 1665.35  5642.1 1665.90  5682.8 1666.93
  5910.4 1672.31  5984.6 1674.00  6047.8 1676.47  6075.9 1676.82  6151.7 1680.47
#Mann=10,-1,0
  4396.6    0.05       0  4612.1     0.1       0  4637.2    0.05       0
  4998.1    0.04       0  5004.1    0.05       0  5561.0    0.16       0
  5572.2    0.05       0  5682.8     0.1       0  5910.4    0.16       0
  5984.6     0.1       0
Bank Sta=4998.1,5004.1
Exp/Cntr=0.3,0.1

Type RM Length L Ch R = 1,1077,743,743,743
BEGIN DESCRIPTION:
Mapping XS 711dd452
END DESCRIPTION:
XS GIS Cut Line= 4
      2813749.27     10111748.87      2813323.92     10111579.59
      2812586.07     10111822.65      2812295.78     10112489.89
#Sta/Elev= 30
  4291.7 1670.73  4510.8 1668.80  4667.3 1666.02  4712.3 1666.44  4744.4 1665.27
  4860.5 1663.83  4970.8 1659.55  4994.3 1652.97  4997.0 1652.47  5000.3 1652.97
  5007.9 1656.09  5034.3 1658.69  5097.9 1661.27  5155.3 1660.94  5193.2 1661.98
  5218.5 1661.73  5225.0 1660.66  5239.6 1660.20  5325.5 1662.40  5352.1 1662.02
  5538.4 1663.85  5556.4 1665.15  5585.3 1665.64  5614.8 1664.09  5637.6 1665.63
  5755.8 1667.20  5989.6 1672.70  6031.5 1673.67  6127.3 1676.57  6254.0 1682.19
#Mann=6,-1,0
  4291.7    0.05       0  4994.3    0.04       0  5000.3    0.05       0
  5755.8     0.1       0  5989.6    0.16       0  6031.5     0.1       0
Bank Sta=4994.3,5000.3
Exp/Cntr=0.3,0.1

Type RM Length L Ch R = 1,334,0,0,0
BEGIN DESCRIPTION:
UNT072 IN NNOGR 1.0
END DESCRIPTION:
XS GIS Cut Line= 4
      2813836.03     10111755.05      2812920.99     10111285.99
      2812667.23     10111285.99      2811960.72     10112430.23
#Sta/Elev= 30
  3839.4 1670.74  3897.1 1670.21  3977.3 1669.70  3997.4 1669.40  4230.8 1666.22
  4286.1 1666.82  4469.4 1661.99  4656.7 1658.85  4752.3 1658.89  4818.9 1656.87
  4880.2 1658.05  4930.2 1657.18  4971.8 1654.78  4980.2 1654.60  4997.2 1649.79
  4999.9 1649.29  5003.2 1649.79  5030.2 1656.80  5074.9 1658.50  5421.2 1661.13
  5422.3 1661.14  5489.6 1662.08  5577.1 1660.94  5723.1 1665.17  5765.2 1667.62
  5788.7 1667.03  5823.9 1668.47  5846.7 1667.48  5985.2 1669.70  6466.2 1678.86
#Mann=14,-1,0
  3839.4     0.1       0  3897.1    0.05       0  3977.3     0.1       0
  3997.4    0.05       0  4469.4     0.1       0  4656.7    0.16       0
  4971.8     0.1       0  4997.2    0.07       0  5003.2     0.1       0
  5074.9    0.05       0  5421.2    0.16       0  5422.3     0.1       0
  5723.1    0.05       0  5985.2     0.1       0
Bank Sta=4997.2,5003.2
Exp/Cntr=0.3,0.1

Chan Stop Cuts=-1