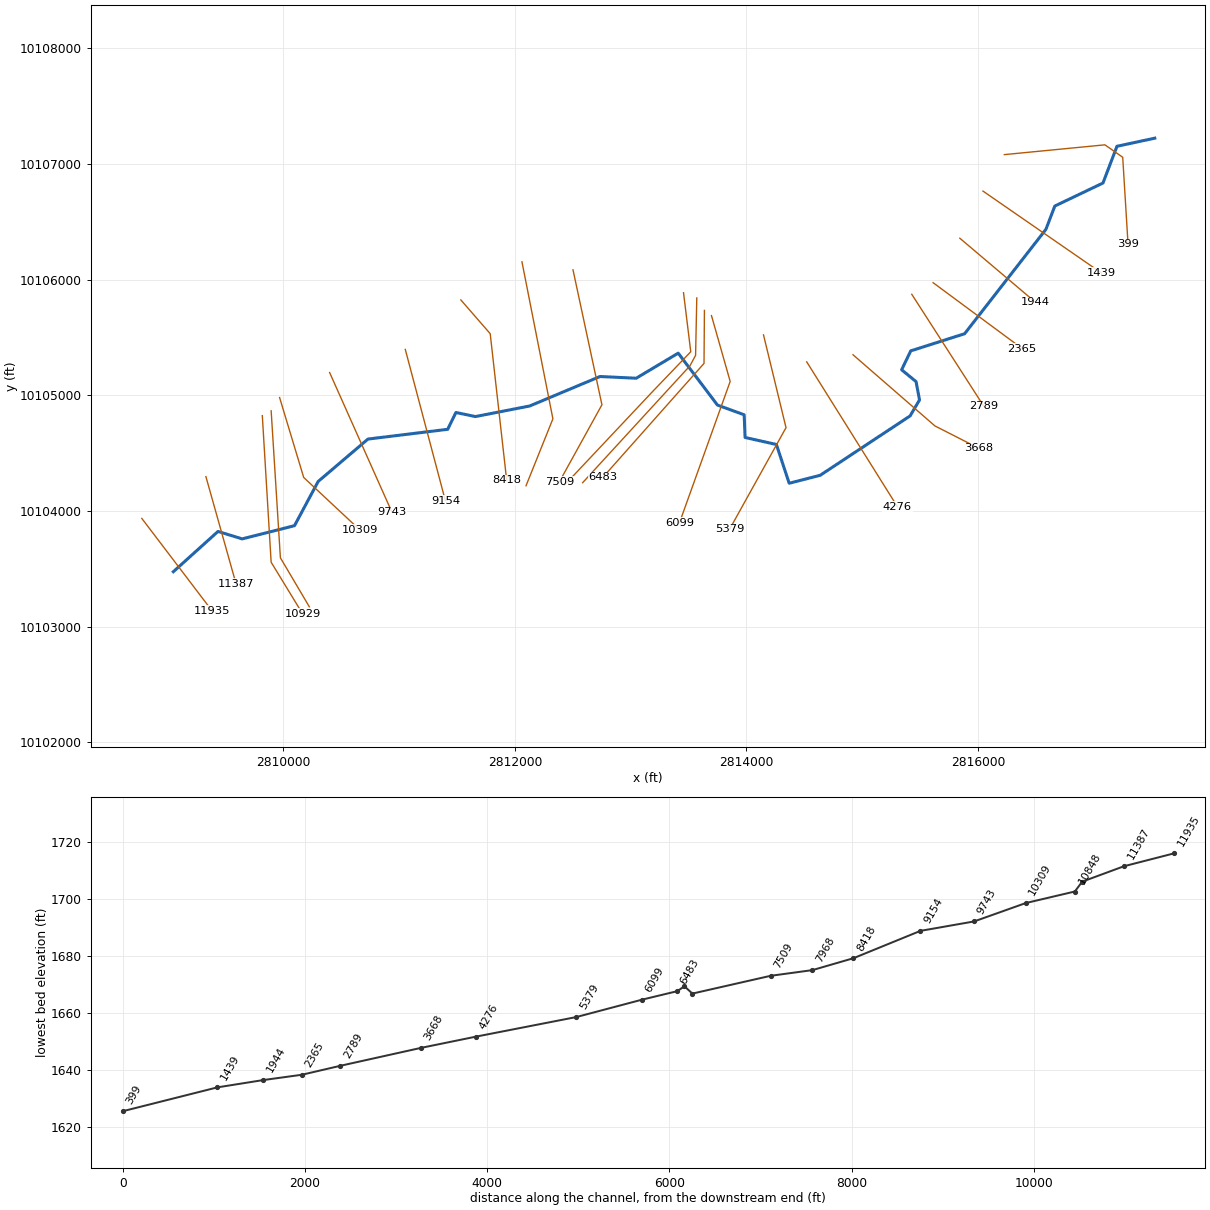
--- UNT073 IN NNOGR.prj (project) ---

Proj Title=UNT073 IN NNOGR Base Level Engineering
Current Plan=p01
Default Exp/Contr=0.3,0.1
English Units
Geom File=g01
Flow File=f01
Plan File=p01
Y Axis Title=Elevation
X Axis Title(PF)=Main Channel Distance
X Axis Title(XS)=Station
BEGIN DESCRIPTION:
UNT073 IN NNOGR
END DESCRIPTION:
DSS Export Rating Curves= 0
DSS Export Rating Curve Sorted= 0
DSS Export Volume Flow Curves= 0
DXF OffsetX= 0
DXF OffsetY= 0
DXF ScaleX= 1
DXF ScaleY= 10

--- UNT073 IN NNOGR.p01 (plan) ---

Plan Title=Multiple Run
Short Identifier=Multiple
Geom File=g01
Flow File=f01
Subcritical Flow
K Sum by GR= 0
Std Step Tol= 0.01
Critical Tol= 0.01
Num of Std Step Trials= 20
Max Error Tol= 0.3
Flow Tol Ratio= 0.001
Split Flow NTrial= 30
Split Flow Tol= 0.02
Split Flow Ratio= 0.02
Log Output Level= 0
Friction Slope Method= 1
Unsteady Friction Slope Method= 2
Unsteady Bridges Friction Slope Method= 1
Parabolic Critical Depth
Global Vel Dist=  1 , 1 , 1
Global Log Level= 0
CheckData=True
Encroach Param= -1, 0, 0, 0
BEGIN DESCRIPTION:
Multiple Run
END DESCRIPTION:

--- UNT073 IN NNOGR.f01 (steady flow) ---

Flow Title=Multiple
Program Version=4.10
Number of Profiles= 7
Profile Names=10-year,25-year,50-year,1pct_min,100-year,1pct_plu,500-year
River Rch & RM=UNT073 IN NNOGR,Reach-1         ,11935
     875    1270    1613    1501    2029    2745    3224
River Rch & RM=UNT073 IN NNOGR,Reach-1         ,10848
    1362    2016    2595    2441    3301    4464    5365
River Rch & RM=UNT073 IN NNOGR,Reach-1         ,5379
    1522    2257    2907    2735    3699    5002    6015
Boundary for River Rch & Prof#=UNT073 IN NNOGR,Reach-1         , 1
Up Type= 0
Dn Type= 3
Dn Slope=0.0061
Boundary for River Rch & Prof#=UNT073 IN NNOGR,Reach-1         , 2
Up Type= 0
Dn Type= 3
Dn Slope=0.0061
Boundary for River Rch & Prof#=UNT073 IN NNOGR,Reach-1         , 3
Up Type= 0
Dn Type= 3
Dn Slope=0.0061
Boundary for River Rch & Prof#=UNT073 IN NNOGR,Reach-1         , 4
Up Type= 0
Dn Type= 3
Dn Slope=0.0061
Boundary for River Rch & Prof#=UNT073 IN NNOGR,Reach-1         , 5
Up Type= 0
Dn Type= 3
Dn Slope=0.0061
Boundary for River Rch & Prof#=UNT073 IN NNOGR,Reach-1         , 6
Up Type= 0
Dn Type= 3
Dn Slope=0.0061
Boundary for River Rch & Prof#=UNT073 IN NNOGR,Reach-1         , 7
Up Type= 0
Dn Type= 3
Dn Slope=0.0061
DSS Import GetInterval= 0
DSS Import GetPeak= 0
DSS Import FillOption= 0

--- UNT073 IN NNOGR.g01 (geometry) ---

Geom Title=Existing Conditions
Program Version=4.10

River Reach=UNT073 IN NNOGR ,Reach-1
Reach XY= 30
      2809048.47     10103473.73      2809434.47       10103822.
      2809643.35     10103757.57      2810095.17     10103871.83
      2810299.73     10104254.06      2810729.86     10104620.58
      2811418.58      10104704.9       2811489.8     10104850.35
      2811658.13      10104815.1      2812127.28      10104906.6
      2812734.46     10105161.32      2813047.19     10105146.55
       2813410.1     10105363.33      2813749.28     10104914.55
      2813980.13     10104830.37      2813987.76     10104634.28
      2814258.23     10104573.91      2814369.01     10104238.65
      2814636.93     10104307.45      2815413.62     10104820.72
      2815494.82     10104958.67      2815465.08     10105117.16
      2815340.31     10105219.61      2815419.15     10105383.04
      2815884.47      10105531.2      2816586.86     10106433.76
      2816663.71     10106635.13      2817079.71     10106834.12
      2817200.59     10107151.61      2817527.21     10107221.87

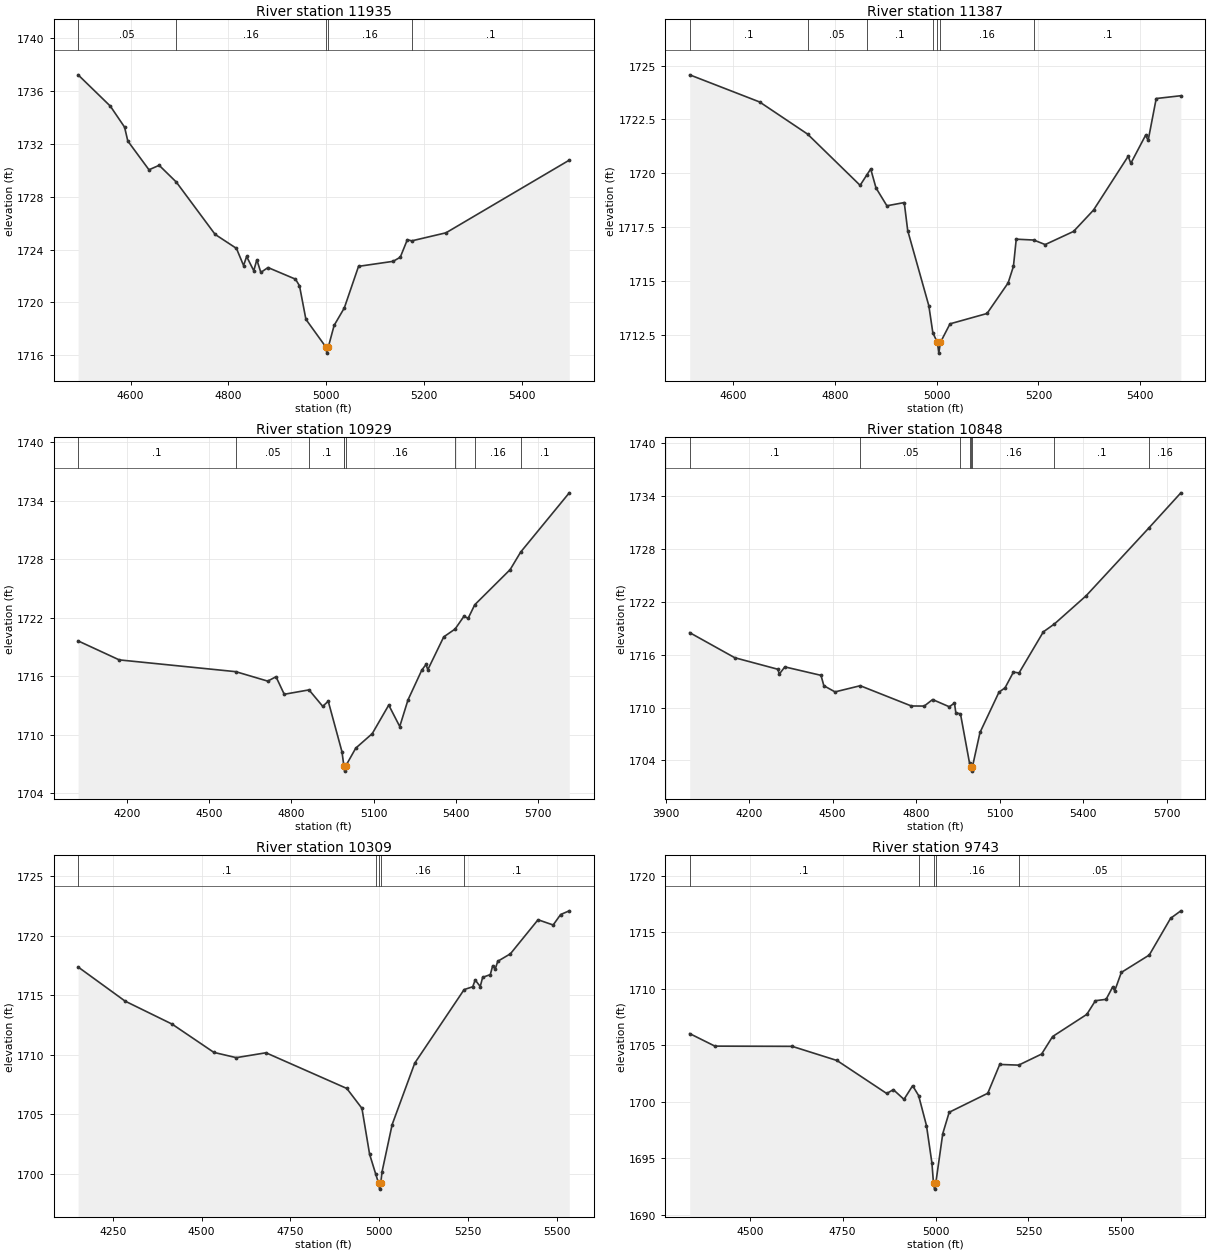
Type RM Length L Ch R = 1 ,11935   ,548,548,548
BEGIN DESCRIPTION:
UNT073 IN NNOGR 22.0
END DESCRIPTION:
XS GIS Cut Line= 2
       2808776.2     10103934.61      2809383.57     10103135.04
#Sta/Elev= 30
  4492.8 1737.23  4558.7 1734.86  4587.8 1733.27  4594.4 1732.22  4637.7 1730.04
  4658.5 1730.38  4693.6 1729.11  4772.9 1725.15  4816.5 1724.09  4831.1 1722.79
  4837.3 1723.48  4851.9  1722.4  4858.2 1723.23  4866.4 1722.27    4881 1722.64
  4937.2 1721.76  4945.4 1721.26  4958.5 1718.72  4998.6 1716.66  5001.4 1716.16
  5004.6 1716.66  5016.2 1718.26    5037 1719.58  5066.1 1722.73  5136.8 1723.11
  5151.4 1723.42  5165.9 1724.75  5174.9 1724.66  5244.9 1725.27  5496.9 1730.77
#Mann= 5 ,-1 , 0
  4492.8     .05       0  4693.6     .16       0  4998.6     .07       0
  5004.6     .16       0  5174.9      .1       0
Bank Sta=4998.6,5004.6
XS Rating Curve= 0 ,0
Exp/Cntr=0.3,0.1

Type RM Length L Ch R = 1 ,11387   ,458,458,458
BEGIN DESCRIPTION:
UNT073 IN NNOGR 21.0
END DESCRIPTION:
XS GIS Cut Line= 2
      2809329.87     10104296.05      2809590.89     10103367.13
#Sta/Elev= 30
    4515 1724.57  4652.4 1723.31  4746.5 1721.82  4849.8 1719.44  4862.9 1719.92
  4870.6  1720.2    4881 1719.32  4902.4 1718.49  4936.5 1718.64  4943.3 1717.34
  4984.8 1713.85  4992.7 1712.59  5001.6 1712.15  5004.4 1711.65  5007.6 1712.15
  5026.4 1713.01  5099.1 1713.49  5140.6 1714.91    5151 1715.68  5156.5 1716.94
    5191  1716.9  5213.4 1716.69  5269.1  1717.3  5308.3 1718.29  5376.4 1720.79
  5381.6 1720.46  5410.5 1721.76  5415.7 1721.53  5431.5 1723.47  5479.9  1723.6
#Mann= 7 ,-1 , 0
    4515      .1       0  4746.5     .05       0  4862.9      .1       0
  4992.7     .16       0  5001.6     .07       0  5007.6     .16       0
    5191      .1       0
Bank Sta=5001.6,5007.6
XS Rating Curve= 0 ,0
Exp/Cntr=0.3,0.1

Type RM Length L Ch R = 1 ,10929   ,81,81,81
BEGIN DESCRIPTION:
Mapping XS 3a404926
END DESCRIPTION:
XS GIS Cut Line= 3
      2809817.19     10104823.28      2809893.58     10103555.94
      2810163.94     10103112.27
#Sta/Elev= 30
  4023.2 1719.61    4173 1717.66  4597.7 1716.45    4714 1715.48  4744.1 1715.93
  4774.1 1714.13  4864.4 1714.58  4914.4 1712.89  4934.4 1713.42  4984.5 1708.22
  4990.7 1706.91  4991.5 1706.74  4994.3 1706.24  4997.5 1706.74  5034.6  1708.6
  5094.7 1710.09  5154.8 1713.02  5194.9 1710.82  5224.9 1713.55    5275  1716.6
  5290.5 1717.19  5297.1 1716.65  5355.1 1720.02  5396.6 1720.83  5428.6 1722.13
  5444.1 1721.93  5468.1 1723.32  5597.1 1726.93  5635.4 1728.73  5812.4 1734.81
#Mann= 9 ,-1 , 0
  4023.2      .1       0  4597.7     .05       0  4864.4      .1       0
  4990.7     .16       0  4991.5     .07       0  4997.5     .16       0
  5396.6      .1       0  5468.1     .16       0  5635.4      .1       0
Bank Sta=4991.5,4997.5
XS Rating Curve= 0 ,0
Exp/Cntr=0.3,0.1

Type RM Length L Ch R = 1 ,10848   ,539,539,539
BEGIN DESCRIPTION:
UNT073 IN NNOGR 20.0
END DESCRIPTION:
XS GIS Cut Line= 3
      2809893.58     10104864.98      2809973.44     10103594.13
      2810223.42     10103170.55
#Sta/Elev= 30
  3986.3 1718.51  4148.4 1715.66  4303.3 1714.35  4308.3  1713.8  4328.2 1714.62
  4458.2 1713.66  4468.5 1712.48  4508.6 1711.78  4599.2 1712.48  4782.9 1710.18
  4829.2 1710.17  4859.3 1710.91  4919.4 1710.09  4937.8 1710.51  4942.8 1709.41
  4959.5 1709.28  4992.2 1703.66  4996.5 1703.28  4999.3 1702.78  5002.5 1703.28
  5029.6 1707.17  5097.7 1711.74  5119.8 1712.25  5149.8 1714.03  5169.9 1713.93
  5257.3  1718.6  5297.2  1719.5  5411.1  1722.7    5638 1730.45  5751.5 1734.39
#Mann= 8 ,-1 , 0
  3986.3      .1       0  4599.2     .05       0  4959.5      .1       0
  4992.2     .16       0  4996.5     .07       0  5002.5     .16       0
  5297.2      .1       0    5638     .16       0
Bank Sta=4996.5,5002.5
XS Rating Curve= 0 ,0
Exp/Cntr=0.3,0.1

Type RM Length L Ch R = 1 ,10309   ,566,566,566
BEGIN DESCRIPTION:
UNT073 IN NNOGR 16.0
END DESCRIPTION:
XS GIS Cut Line= 3
      2809966.51     10104979.52      2810174.83     10104288.58
      2810656.67     10103837.93
#Sta/Elev= 30
  4152.8 1717.39  4285.1 1714.52  4417.1 1712.59  4534.8 1710.21  4597.7 1709.77
  4681.1 1710.18  4908.6 1707.18  4951.1 1705.51  4972.6 1701.66  4989.7    1700
  4997.9 1699.22  5000.7 1698.72  5003.9 1699.22  5007.8  1700.2  5036.1 1704.15
  5099.6 1709.31  5238.5 1715.49  5262.7 1715.73  5269.6  1716.3  5283.8 1715.75
  5290.6 1716.52  5312.1 1716.75  5318.9  1717.5  5326.2 1717.24  5333.1 1717.87
  5368.7  1718.5  5446.4 1721.36  5488.9 1720.92  5509.9  1721.8  5534.2 1722.11
#Mann= 5 ,-1 , 0
  4152.8      .1       0  4989.7     .16       0  4997.9     .07       0
  5003.9     .16       0  5238.5      .1       0
Bank Sta=4997.9,5003.9
XS Rating Curve= 0 ,0
Exp/Cntr=0.3,0.1

Type RM Length L Ch R = 1 ,9743    ,589,589,589
BEGIN DESCRIPTION:
UNT073 IN NNOGR 17.0
END DESCRIPTION:
XS GIS Cut Line= 2
      2810398.76      10105195.7      2810936.98     10103988.55
#Sta/Elev= 30
  4338.3 1706.03  4406.2 1704.92  4614.2  1704.9  4734.6 1703.65  4868.5 1700.73
  4886.3 1701.07    4915 1700.21  4938.2 1701.42  4954.3 1700.55  4975.5 1697.89
  4990.1 1694.59  4994.4 1692.77  4997.1 1692.27  5000.4 1692.77  5019.3 1697.18
  5036.6 1699.07  5140.4 1700.75  5172.6  1703.3  5223.5 1703.24  5285.3 1704.22
  5314.9 1705.77  5406.9 1707.73  5430.1 1708.94  5458.8 1709.06  5476.6 1710.16
    5482 1709.81  5499.8 1711.44    5575 1712.98  5632.4 1716.23    5660 1716.89
#Mann= 5 ,-1 , 0
  4338.3      .1       0  4954.3     .16       0  4994.4     .07       0
  5000.4     .16       0  5223.5     .05       0
Bank Sta=4994.4,5000.4
XS Rating Curve= 0 ,0
Exp/Cntr=0.3,0.1

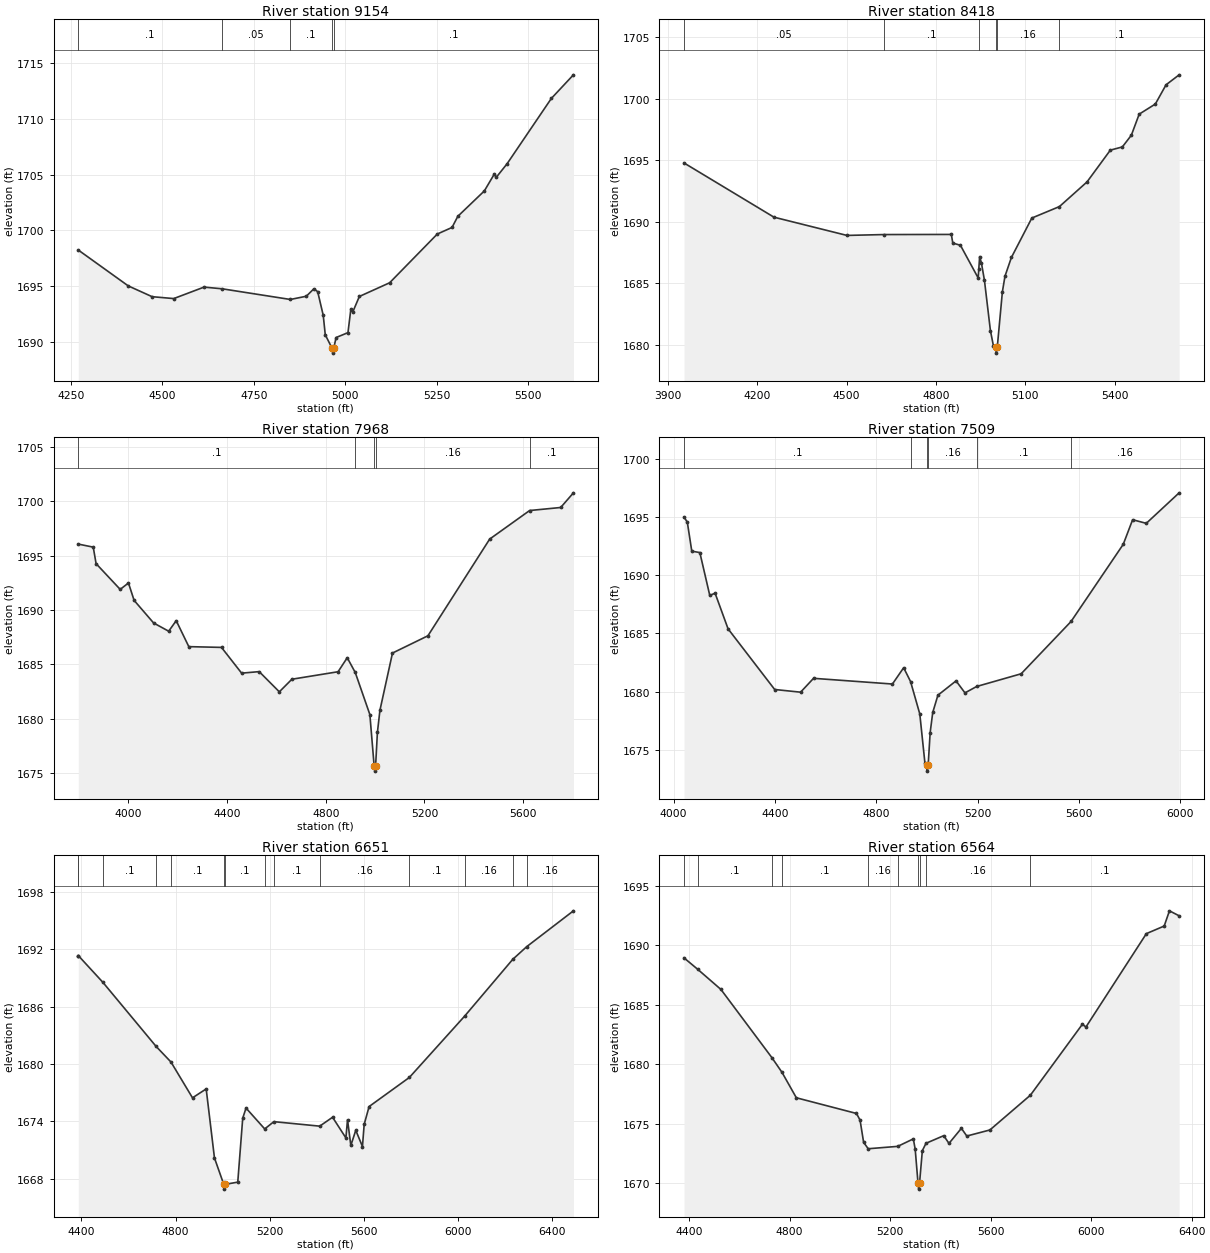
Type RM Length L Ch R = 1 ,9154    ,736,736,736
BEGIN DESCRIPTION:
UNT073 IN NNOGR 15.0
END DESCRIPTION:
XS GIS Cut Line= 2
      2811052.39     10105395.63      2811398.38     10104088.55
#Sta/Elev= 30
  4270.8 1698.22  4407.2    1695  4472.4 1694.03  4531.4 1693.86  4614.1 1694.89
  4663.4 1694.74  4849.9 1693.78  4893.4 1694.07  4914.1 1694.74  4924.5 1694.48
  4939.7 1692.35  4945.2 1690.61  4962.8 1689.46  4965.6 1688.96  4968.8 1689.46
  4974.7 1690.36  5007.2  1690.8    5015 1692.89  5020.1 1692.64  5038.3 1694.05
    5121 1695.28  5251.2 1699.66  5291.4 1700.25  5307.2 1701.25  5379.6 1703.53
  5406.9 1705.05  5412.1 1704.75  5441.7 1705.97  5562.6 1711.84  5622.9 1713.96
#Mann= 5 ,-1 , 0
  4270.8      .1       0  4663.4     .05       0  4849.9      .1       0
  4962.8     .07       0  4968.8      .1       0
Bank Sta=4962.8,4968.8
XS Rating Curve= 0 ,0
Exp/Cntr=0.3,0.1

Type RM Length L Ch R = 1 ,8418    ,450,450,450
BEGIN DESCRIPTION:
UNT073 IN NNOGR 14.0
END DESCRIPTION:
XS GIS Cut Line= 3
      2811532.49     10105823.28      2811785.94     10105531.63
       2811928.3     10104264.29
#Sta/Elev= 30
  3954.4 1694.78  4256.3 1690.38  4501.2  1688.9  4625.7 1688.97  4851.5 1688.98
  4856.5 1688.28  4882.1  1688.1  4941.6 1685.45  4943.8 1686.21  4946.6 1687.18
  4952.5 1686.67  4962.6 1685.27  4982.7 1681.18  4992.8 1679.94  4999.8 1679.85
  5002.6 1679.35  5005.8 1679.85  5022.9 1684.33  5031.6 1685.59  5053.1 1687.11
  5121.7 1690.31  5214.3 1691.24  5306.9 1693.24  5385.2 1695.82  5425.5 1696.08
  5455.7 1697.03    5482 1698.74  5536.2 1699.56  5572.1 1701.12  5616.1 1701.93
#Mann= 6 ,-1 , 0
  3954.4     .05       0  4625.7      .1       0  4943.8     .16       0
  4999.8     .07       0  5005.8     .16       0  5214.3      .1       0
Bank Sta=4999.8,5005.8
XS Rating Curve= 0 ,0
Exp/Cntr=0.3,0.1

Type RM Length L Ch R = 1 ,7968    ,459,459,459
BEGIN DESCRIPTION:
UNT073 IN NNOGR 13.0
END DESCRIPTION:
XS GIS Cut Line= 3
      2812060.25     10106153.16      2812327.61     10104795.52
       2812095.6     10104217.24
#Sta/Elev= 30
  3797.1 1696.07  3857.7 1695.79  3869.2 1694.27  3966.9  1691.9  4000.4 1692.49
  4023.3 1690.89  4102.3 1688.81  4163.4 1688.05    4194 1689.02    4245 1686.63
  4377.5 1686.56    4459 1684.19  4530.3 1684.33  4611.9 1682.47  4662.8 1683.63
  4850.1 1684.32  4887.1 1685.61  4919.6 1684.25  4978.8 1680.38  4996.1 1675.67
  4998.9 1675.17  5002.1 1675.67  5009.4 1678.73  5019.6 1680.77  5070.5 1686.04
  5214.2 1687.63  5464.4 1696.53  5626.3 1699.16  5752.2 1699.44  5803.9 1700.79
#Mann= 5 ,-1 , 0
  3797.1      .1       0  4919.6     .16       0  4996.1     .07       0
  5002.1     .16       0  5626.3      .1       0
Bank Sta=4996.1,5002.1
XS Rating Curve= 0 ,0
Exp/Cntr=0.3,0.1

Type RM Length L Ch R = 1 ,7509    ,858,858,858
BEGIN DESCRIPTION:
UNT073 IN NNOGR 12.0
END DESCRIPTION:
XS GIS Cut Line= 3
      2812501.22     10106083.73      2812751.22     10104917.05
       2812383.3     10104250.63
#Sta/Elev= 30
    4041 1694.98    4054 1694.56  4071.7 1692.06  4103.5 1691.94  4142.7 1688.26
  4163.7 1688.45  4214.9 1685.39  4398.9 1680.18  4501.2 1679.95  4552.3 1681.14
  4863.7 1680.65    4908 1682.05  4935.3 1680.86  4971.7 1678.08  4992.1 1673.83
  4998.7 1673.67  5001.5 1673.17  5004.7 1673.67  5012.6 1676.48  5022.8 1678.21
  5043.2 1679.69  5114.8 1680.92    5150 1679.89  5196.3 1680.44  5371.8 1681.53
  5568.7 1686.02  5774.8 1692.65  5811.8 1694.76  5865.7 1694.45  5995.4 1697.07
#Mann= 6 ,-1 , 0
    4041      .1       0  4935.3     .16       0  4998.7     .07       0
  5004.7     .16       0  5196.3      .1       0  5568.7     .16       0
Bank Sta=4998.7,5004.7
XS Rating Curve= 0 ,0
Exp/Cntr=0.3,0.1

Type RM Length L Ch R = 1 ,6651    ,87,87,87
BEGIN DESCRIPTION:
UNT073 IN NNOGR 11.0
END DESCRIPTION:
XS GIS Cut Line= 4
      2813456.08     10105885.79      2813518.58     10105375.38
      2813195.66     10105038.58      2812424.85     10104219.16
#Sta/Elev= 30
  4386.4 1691.32  4386.9 1691.32  4490.9 1688.54  4717.4 1681.84  4780.6 1680.21
  4872.1 1676.47  4930.3  1677.4  4965.5 1670.19    5005 1667.43  5007.7 1666.93
    5011 1667.43  5064.6 1667.66  5085.7 1674.34  5099.8  1675.4  5179.2 1673.22
  5218.2 1673.98  5413.1 1673.51  5467.8 1674.44  5524.5 1672.28  5531.4 1674.18
  5545.5 1671.49  5566.5 1673.08  5594.9 1671.38  5602.2 1673.69  5623.2 1675.56
  5794.5  1678.6  6029.6 1685.01  6234.1 1690.94  6293.7 1692.27  6492.2 1696.01
#Mann= 14 ,-1 , 0
  4386.4      .1       0  4386.9     .16       0  4490.9      .1       0
  4717.4     .16       0  4780.6      .1       0    5005     .07       0
    5011      .1       0  5179.2     .16       0  5218.2      .1       0
  5413.1     .16       0  5794.5      .1       0  6029.6     .16       0
  6234.1      .1       0  6293.7     .16       0
Bank Sta=5005,5011
XS Rating Curve= 0 ,0
Exp/Cntr=0.3,0.1

Type RM Length L Ch R = 1 ,6564    ,81,81,81
BEGIN DESCRIPTION:
Mapping XS b24278aa
END DESCRIPTION:
XS GIS Cut Line= 4
      2813570.66      10105840.7      2813560.25     10105344.13
      2813511.63     10105253.86      2812584.55     10104243.44
#Sta/Elev= 30
  4379.8 1688.95  4434.2 1687.99  4526.8 1686.29  4729.5 1680.55  4769.8 1679.31
  4826.9 1677.17  5066.2 1675.85  5080.4 1675.29  5094.6 1673.42  5112.8 1672.88
  5230.3 1673.08  5292.5 1673.71  5299.9 1672.83  5311.1 1669.98  5313.8 1669.48
  5317.1 1669.98  5328.3 1672.72  5342.9 1673.34  5413.4 1673.98  5434.3 1673.33
  5483.7  1674.6  5505.2 1673.95  5597.1 1674.46  5758.4 1677.39  5965.2 1683.36
  5979.4 1683.13  6219.9 1690.99  6290.8 1691.63  6311.7 1692.91  6350.3 1692.49
#Mann= 10 ,-1 , 0
  4379.8     .16       0  4434.2      .1       0  4729.5     .16       0
  4769.8      .1       0  5112.8     .16       0  5230.3      .1       0
  5311.1     .07       0  5317.1      .1       0  5342.9     .16       0
  5758.4      .1       0
Bank Sta=5311.1,5317.1
XS Rating Curve= 0 ,0
Exp/Cntr=0.3,0.1

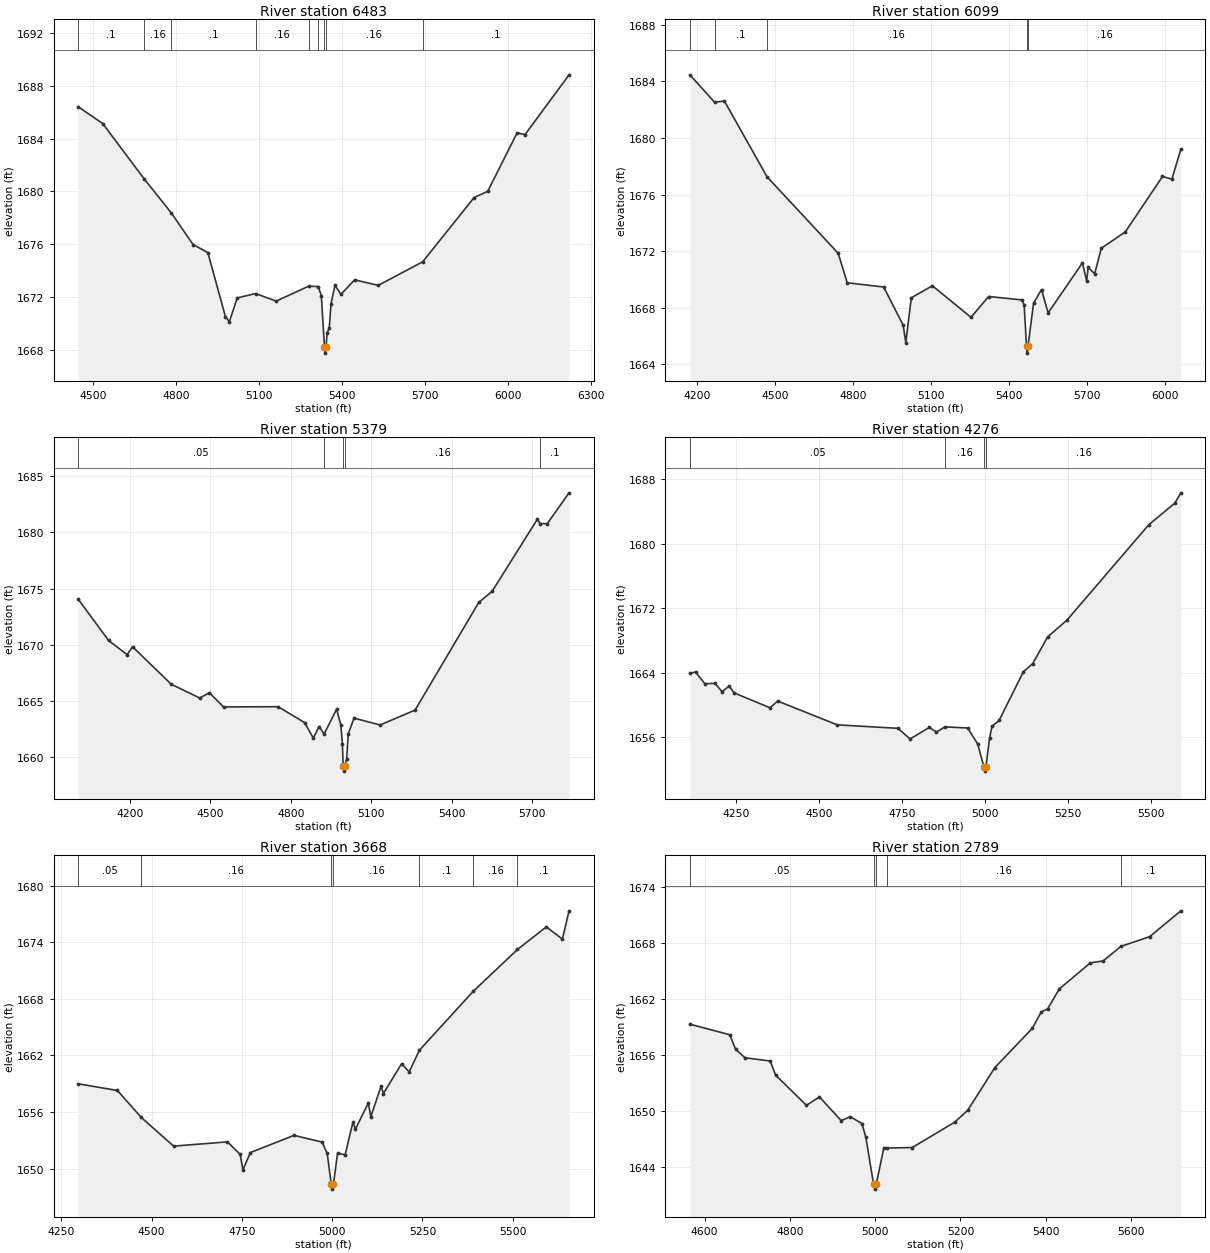
Type RM Length L Ch R = 1 ,6483    ,384,384,384
BEGIN DESCRIPTION:
Mapping XS d77b522f
END DESCRIPTION:
XS GIS Cut Line= 3
      2813636.63     10105732.98      2813633.16     10105274.69
       2812758.2     10104288.62
#Sta/Elev= 30
  4445.7 1686.42    4535 1685.14  4684.5 1680.96  4782.9 1678.38  4861.9 1675.98
  4915.3 1675.37  4978.9 1670.52  4993.1 1670.14  5021.5 1671.94  5087.7 1672.27
  5162.8  1671.7  5280.2 1672.83  5314.7  1672.8  5325.9 1672.11  5337.1 1668.26
  5339.9 1667.76  5343.1 1668.26  5346.8 1669.31  5354.4 1669.63    5361 1671.51
  5375.3 1672.89    5397 1672.21  5446.3 1673.31  5531.7 1672.89  5692.4 1674.67
  5878.7 1679.54  5928.1 1680.01  6034.3 1684.44  6062.7  1684.3  6222.3 1688.83
#Mann= 9 ,-1 , 0
  4445.7      .1       0  4684.5     .16       0  4782.9      .1       0
  5087.7     .16       0  5280.2      .1       0  5314.7     .16       0
  5337.1     .07       0  5343.1     .16       0  5692.4      .1       0
Bank Sta=5337.1,5343.1
XS Rating Curve= 0 ,0
Exp/Cntr=0.3,0.1

Type RM Length L Ch R = 1 ,6099    ,720,720,720
BEGIN DESCRIPTION:
UNT073 IN NNOGR 10.0
END DESCRIPTION:
XS GIS Cut Line= 3
      2813697.65     10105687.89      2813859.14     10105118.82
       2813421.3     10103897.47
#Sta/Elev= 30
  4172.2 1684.46  4267.4 1682.52  4304.9 1682.61  4469.3 1677.25    4743 1671.85
  4777.5 1669.77  4917.9 1669.47  4992.8 1666.77  5002.9 1665.55  5024.1 1668.71
  5105.2 1669.56  5253.6 1667.33  5321.6  1668.8    5449 1668.56  5458.2 1668.23
  5467.3  1665.3    5470  1664.8  5473.3  1665.3  5494.3 1668.32    5525 1669.29
  5550.5 1667.64  5682.7 1671.18  5698.9 1669.88  5704.2 1670.86  5729.7 1670.41
  5755.1 1672.21  5847.4 1673.36  5990.5 1677.28  6026.6 1677.09  6061.2 1679.21
#Mann= 5 ,-1 , 0
  4172.2     .16       0  4267.4      .1       0  4469.3     .16       0
  5467.3     .07       0  5473.3     .16       0
Bank Sta=5467.3,5473.3
XS Rating Curve= 0 ,0
Exp/Cntr=0.3,0.1

Type RM Length L Ch R = 1 ,5379    ,1103,1103,1103
BEGIN DESCRIPTION:
UNT073 IN NNOGR 9.0
END DESCRIPTION:
XS GIS Cut Line= 3
      2814147.05     10105521.23       2814341.5     10104719.13
       2813853.1     10103839.34
#Sta/Elev= 30
  4006.4 1674.06  4120.3 1670.36    4189  1669.1  4209.6  1669.8  4353.7 1666.46
  4459.9 1665.23  4496.6 1665.69  4549.2 1664.43  4752.5 1664.45  4851.7 1663.03
  4883.7 1661.65  4905.5 1662.68  4924.3 1662.01  4970.7 1664.23  4986.6 1662.82
  4992.4 1661.15  4995.1  1659.2  4997.9  1658.7  5001.1  1659.2  5008.4  1659.8
  5014.2 1662.04  5035.9 1663.43  5133.1 1662.82  5263.6 1664.15  5501.3 1673.76
  5550.8 1674.74    5719 1681.16  5731.4 1680.79  5756.7 1680.79    5838 1683.54
#Mann= 5 ,-1 , 0
  4006.4     .05       0  4924.3     .16       0  4995.1     .07       0
  5001.1     .16       0  5731.4      .1       0
Bank Sta=4995.1,5001.1
XS Rating Curve= 0 ,0
Exp/Cntr=0.3,0.1

Type RM Length L Ch R = 1 ,4276    ,608,608,608
BEGIN DESCRIPTION:
UNT073 IN NNOGR 8.0
END DESCRIPTION:
XS GIS Cut Line= 2
      2814520.43     10105288.03      2815304.14     10104035.63
#Sta/Elev= 30
  4111.2 1663.93  4128.1 1664.11  4156.1 1662.66  4186.7 1662.69    4208 1661.66
  4229.2 1662.36  4244.5 1661.51  4352.2 1659.67  4375.4  1660.5  4554.6 1657.55
  4737.3 1657.12  4773.8  1655.8  4831.6 1657.23  4852.8 1656.66  4878.8  1657.3
  4947.2 1657.16  4977.4 1655.16    4996 1652.31  4998.8 1651.81    5002 1652.31
  5012.8 1655.86  5020.2 1657.37  5041.5 1658.09  5114.6 1664.13  5142.6 1665.14
  5187.7 1668.46  5245.4 1670.52  5491.8 1682.36  5570.8 1685.07  5588.6 1686.33
#Mann= 4 ,-1 , 0
  4111.2     .05       0  4878.8     .16       0    4996     .07       0
    5002     .16       0
Bank Sta=4996,5002
XS Rating Curve= 0 ,0
Exp/Cntr=0.3,0.1

Type RM Length L Ch R = 1 ,3668    ,879,879,879
BEGIN DESCRIPTION:
UNT073 IN NNOGR 7.0
END DESCRIPTION:
XS GIS Cut Line= 3
      2814920.36     10105349.48      2815627.78     10104734.33
      2816004.06     10104542.35
#Sta/Elev= 30
  4296.2    1659  4405.2 1658.29  4470.9 1655.44  4560.9 1652.39    4710 1652.84
  4745.1 1651.51  4752.7 1649.87  4773.6 1651.71  4894.2 1653.53    4972 1652.82
  4986.3 1651.61  4997.5 1648.33  5000.3 1647.83  5003.5 1648.33  5014.8 1651.64
  5035.8 1651.47  5057.5 1654.94  5064.1 1654.18  5100.2 1656.97  5106.9  1655.5
  5135.4 1658.74    5142 1657.97  5192.3 1661.13  5213.2 1660.26  5241.6 1662.56
  5390.8 1668.81  5513.2 1673.24  5593.1 1675.64  5637.5 1674.34  5656.1 1677.34
#Mann= 7 ,-1 , 0
  4296.2     .05       0  4470.9     .16       0  4997.5     .07       0
  5003.5     .16       0  5241.6      .1       0  5390.8     .16       0
  5513.2      .1       0
Bank Sta=4997.5,5003.5
XS Rating Curve= 0 ,0
Exp/Cntr=0.3,0.1

Type RM Length L Ch R = 1 ,2789    ,424,424,424
BEGIN DESCRIPTION:
UNT073 IN NNOGR 5.0
END DESCRIPTION:
XS GIS Cut Line= 2
      2815427.87     10105872.38      2816050.71     10104903.51
#Sta/Elev= 30
  4565.4 1659.27  4658.9 1658.14  4672.5 1656.59  4694.6 1655.67    4754 1655.32
  4766.3 1653.82  4838.9 1650.57  4869.3 1651.47  4920.4 1648.93  4941.9 1649.35
    4969 1648.61  4978.3 1647.12  4996.4 1642.08  4999.1 1641.58  5002.4 1642.08
  5020.5 1646.03  5027.5 1645.99  5086.9 1646.04    5187 1648.77  5217.3 1650.04
  5280.7 1654.61  5368.6 1658.82  5389.7 1660.59  5404.9 1660.93    5432 1663.05
  5504.6 1665.84    5535 1666.06  5576.4 1667.61    5644 1668.66  5717.2 1671.43
#Mann= 5 ,-1 , 0
  4565.4     .05       0  4996.4     .03       0  5002.4     .05       0
  5027.5     .16       0  5576.4      .1       0
Bank Sta=4996.4,5002.4
XS Rating Curve= 0 ,0
Exp/Cntr=0.3,0.1

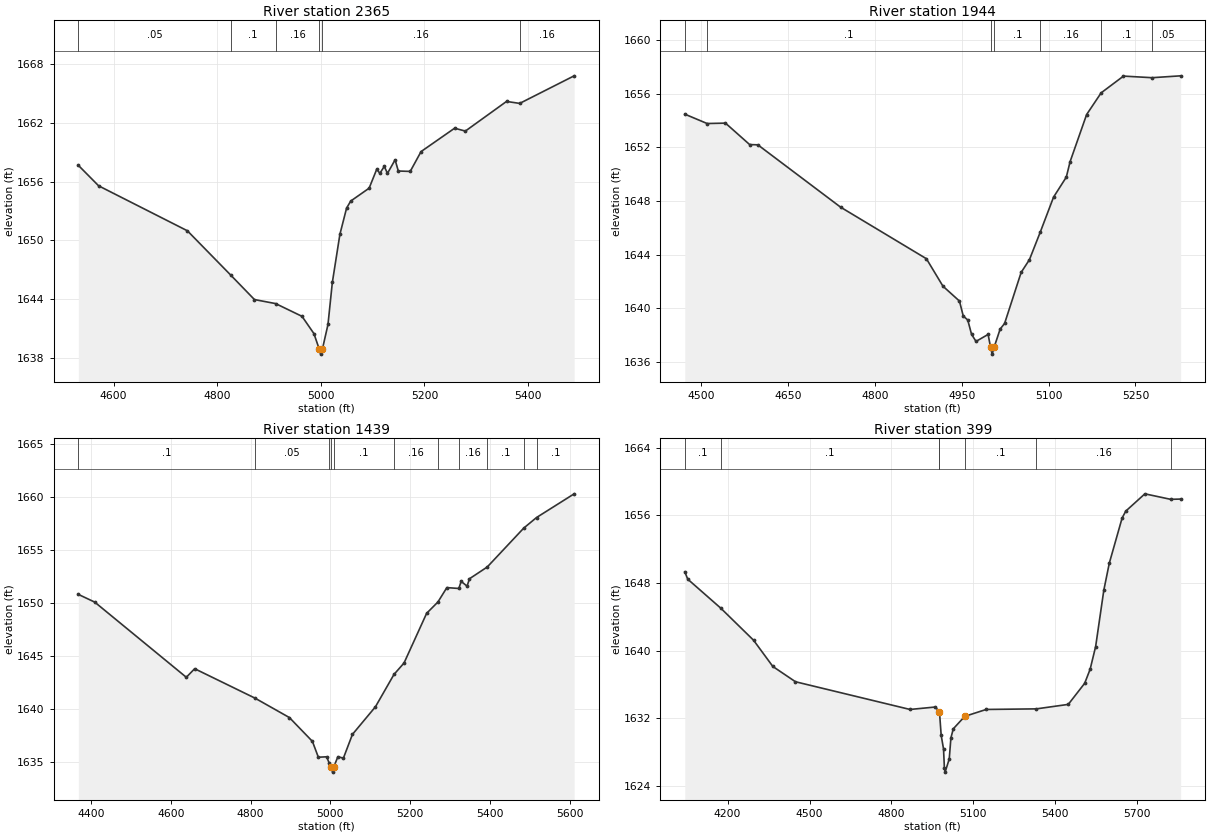
Type RM Length L Ch R = 1 ,2365    ,421,421,421
BEGIN DESCRIPTION:
UNT073 IN NNOGR 4.0
END DESCRIPTION:
XS GIS Cut Line= 2
      2815612.37      10105972.4       2816381.4     10105403.32
#Sta/Elev= 30
  4532.1 1657.66  4571.3 1655.57  4742.5 1650.99  4826.4 1646.46  4871.9 1643.98
  4912.8 1643.57  4963.7 1642.27  4986.7 1640.51    4997 1638.92  4999.7 1638.42
    5003 1638.92  5013.8 1641.44  5022.2 1645.72  5036.8 1650.63  5049.7  1653.3
  5057.7 1654.02  5093.2 1655.33  5107.8 1657.25    5114 1656.85  5122.4 1657.55
  5128.6 1656.84  5143.3 1658.22  5149.5 1657.08  5172.5 1657.04  5193.4 1659.06
  5258.1 1661.44  5278.9 1661.15  5358.3 1664.17  5383.7 1663.97  5488.8 1666.78
#Mann= 6 ,-1 , 0
  4532.1     .05       0  4826.4      .1       0  4912.8     .16       0
    4997     .07       0    5003     .16       0  5383.7     .16       0
Bank Sta=4997,5003
XS Rating Curve= 0 ,0
Exp/Cntr=0.3,0.1

Type RM Length L Ch R = 1 ,1944    ,505,505,505
BEGIN DESCRIPTION:
UNT073 IN NNOGR 3.0
END DESCRIPTION:
XS GIS Cut Line= 2
      2815843.07     10106356.88       2816496.7     10105803.23
#Sta/Elev= 30
  4471.4 1654.48    4510 1653.78  4541.7 1653.81  4583.4 1652.21  4597.6 1652.19
  4740.5 1647.54  4888.8 1643.69  4917.4 1641.64  4945.9 1640.53  4952.5 1639.41
  4960.2 1639.12  4966.8 1638.05  4974.5 1637.52  4995.4 1638.04  4999.7 1637.07
  5002.4 1636.57  5005.7 1637.07  5016.2 1638.44  5023.9 1638.86  5052.5 1642.67
  5066.8 1643.62  5085.9 1645.72  5108.5 1648.29  5130.5 1649.78  5137.1 1650.94
  5165.6 1654.45  5190.7 1656.07  5229.3 1657.32  5278.7  1657.2    5328 1657.34
#Mann= 7 ,-1 , 0
  4471.4     .05       0    4510      .1       0  4999.7     .07       0
  5005.7      .1       0  5085.9     .16       0  5190.7      .1       0
  5278.7     .05       0
Bank Sta=4999.7,5005.7
XS Rating Curve= 0 ,0
Exp/Cntr=0.3,0.1

Type RM Length L Ch R = 1 ,1439    ,1040,1040,1040
BEGIN DESCRIPTION:
UNT073 IN NNOGR 2.0
END DESCRIPTION:
XS GIS Cut Line= 2
      2816043.04     10106764.41       2817065.8     10106056.94
#Sta/Elev= 30
    4368 1650.81  4409.1 1650.08  4638.8 1642.97  4659.8 1643.78    4811    1641
  4897.4 1639.16  4955.1 1636.91    4970 1635.41  4990.9 1635.45    4997 1634.87
  5002.8  1634.5  5005.5    1634  5008.8  1634.5    5019 1635.46  5032.8 1635.32
  5055.5 1637.57  5113.2 1640.18  5159.7 1643.24  5184.9 1644.32  5241.6 1649.02
  5269.9 1650.09  5292.3 1651.45  5322.4 1651.37  5328.2 1652.04    5343 1651.59
  5349.1 1652.29  5393.6  1653.4  5485.2 1657.08  5517.3 1658.08  5611.6 1660.32
#Mann= 11 ,-1 , 0
    4368      .1       0    4811     .05       0    4997      .1       0
  5002.8     .07       0  5008.8      .1       0  5159.7     .16       0
  5269.9      .1       0  5322.4     .16       0  5393.6      .1       0
  5485.2     .16       0  5517.3      .1       0
Bank Sta=5002.8,5008.8
XS Rating Curve= 0 ,0
Exp/Cntr=0.3,0.1

Type RM Length L Ch R = 1 ,399     ,0,0,0
BEGIN DESCRIPTION:
UNT073 IN NNOGR 1.0
END DESCRIPTION:
XS GIS Cut Line= 4
      2816227.62     10107079.71      2817096.52     10107164.29
      2817250.32     10107056.63      2817296.45     10106303.08
#Sta/Elev= 30
  4043.3 1649.33  4054.2 1648.45  4174.8 1645.03  4295.3 1641.22  4365.7 1638.12
  4448.6 1636.31    4868 1633.03  4961.1 1633.32    4976 1632.72  4982.1 1629.98
  4990.8 1628.35  4993.9 1626.11  4996.6 1625.61  5011.7 1627.17  5017.8 1629.66
  5026.5 1630.74  5068.4 1632.21    5147 1633.03  5330.9  1633.1  5447.6 1633.63
  5507.7 1636.13  5527.7  1637.8  5547.8 1640.48  5577.8 1647.16  5597.9 1650.36
  5644.7 1655.69    5658 1656.51  5728.1 1658.56  5822.2 1657.91    5859 1657.94
#Mann= 7 ,-1 , 0
  4043.3      .1       0  4174.8      .1       0    4976     .16       0
    4976     .05       0  5068.4      .1       0  5330.9     .16       0
  5822.2      .1       0
Bank Sta=4976,5068.4
XS Rating Curve= 0 ,0
Exp/Cntr=0.3,0.1

Chan Stop Cuts=-1
Use User Specified Reach Order=0
Composite Channel Slope=5