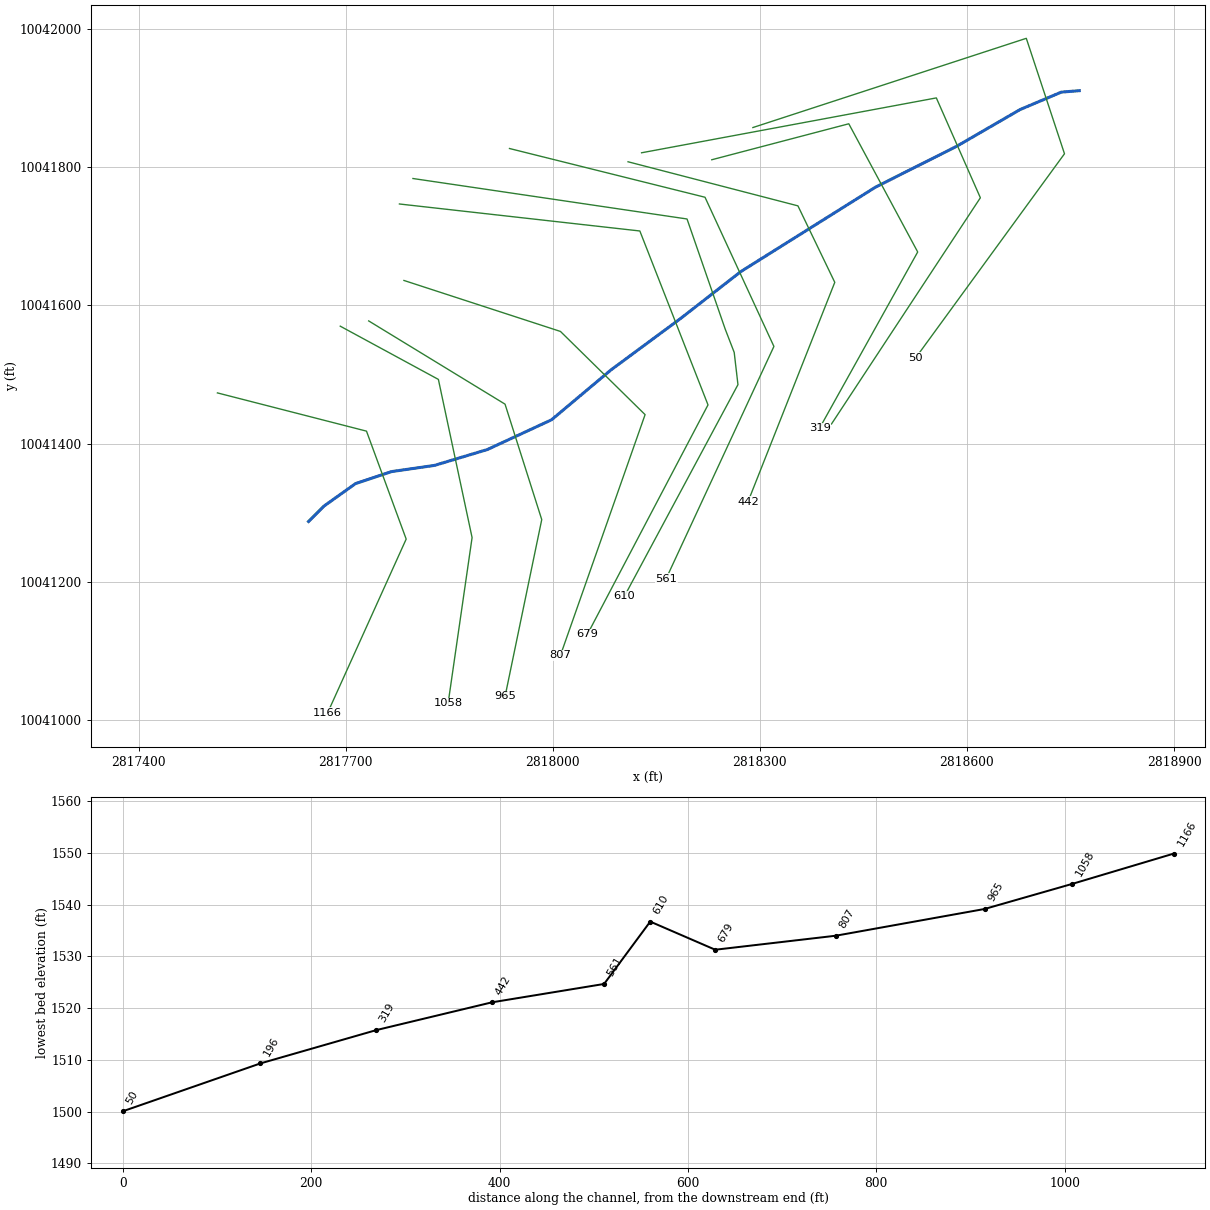
--- UNT073 IN SNOGR.prj (project) ---

Proj Title=UNT073 IN SNOGR Base Level Engineering
Current Plan=p01
Default Exp/Contr=0.3,0.1
English Units
Geom File=g01
Flow File=f01
Plan File=p01
Y Axis Title=Elevation
X Axis Title(PF)=Main Channel Distance
X Axis Title(XS)=Station
BEGIN DESCRIPTION:
UNT073 IN SNOGR
END DESCRIPTION:
DSS Export Rating Curves= 0
DSS Export Rating Curve Sorted= 0
DSS Export Volume Flow Curves= 0
DXF OffsetX= 0
DXF OffsetY= 0
DXF ScaleX= 1
DXF ScaleY= 10

--- UNT073 IN SNOGR.p01 (plan) ---

Plan Title=Multiple Run
Short Identifier=Multiple
Geom File=g01
Flow File=f01
Subcritical Flow
K Sum by GR= 0
Std Step Tol= 0.01
Critical Tol= 0.01
Num of Std Step Trials= 20
Max Error Tol= 0.3
Flow Tol Ratio= 0.001
Split Flow NTrial= 30
Split Flow Tol= 0.02
Split Flow Ratio= 0.02
Log Output Level= 0
Friction Slope Method= 1
Unsteady Friction Slope Method= 2
Unsteady Bridges Friction Slope Method= 1
Parabolic Critical Depth
Global Vel Dist=  1 , 1 , 1
Global Log Level= 0
CheckData=True
Encroach Param= -1, 0, 0, 0
BEGIN DESCRIPTION:
Multiple Run
END DESCRIPTION:

--- UNT073 IN SNOGR.f01 (steady flow) ---

Flow Title=Multiple
Number of Profiles=7
Profile Names=10-year,25-year,50-year,1pct_min,100-year,1pct_plu,500-year
River Rch & RM= UNT073 IN SNOGR,Reach-1,1166
      89     110     125     106     143     193     185
Boundary for River Rch & Prof#=UNT073 IN SNOGR,Reach-1,1
Up Type=0
Dn Type=3
Dn Slope=0.005
Boundary for River Rch & Prof#=UNT073 IN SNOGR,Reach-1,2
Up Type=0
Dn Type=3
Dn Slope=0.005
Boundary for River Rch & Prof#=UNT073 IN SNOGR,Reach-1,3
Up Type=0
Dn Type=3
Dn Slope=0.005
Boundary for River Rch & Prof#=UNT073 IN SNOGR,Reach-1,4
Up Type=0
Dn Type=3
Dn Slope=0.005
Boundary for River Rch & Prof#=UNT073 IN SNOGR,Reach-1,5
Up Type=0
Dn Type=3
Dn Slope=0.005
Boundary for River Rch & Prof#=UNT073 IN SNOGR,Reach-1,6
Up Type=0
Dn Type=3
Dn Slope=0.005
Boundary for River Rch & Prof#=UNT073 IN SNOGR,Reach-1,7
Up Type=0
Dn Type=3
Dn Slope=0.005

--- UNT073 IN SNOGR.g01 (geometry) ---

Geom Title=Existing Conditions
Program Version=4.10

River Reach=UNT073 IN SNOGR ,Reach-1
Reach XY= 15
      2817646.06      10041287.1      2817668.28     10041309.32
      2817714.11     10041341.96       2817766.2     10041359.32
       2817828.7     10041368.35      2817905.08     10041391.26
      2817998.14     10041434.32      2818084.25     10041506.54
      2818184.95     10041580.85      2818272.45      10041648.9
      2818467.58     10041771.13      2818584.87     10041830.07
       2818677.1     10041883.45      2818736.78     10041908.63
      2818762.72      10041910.7

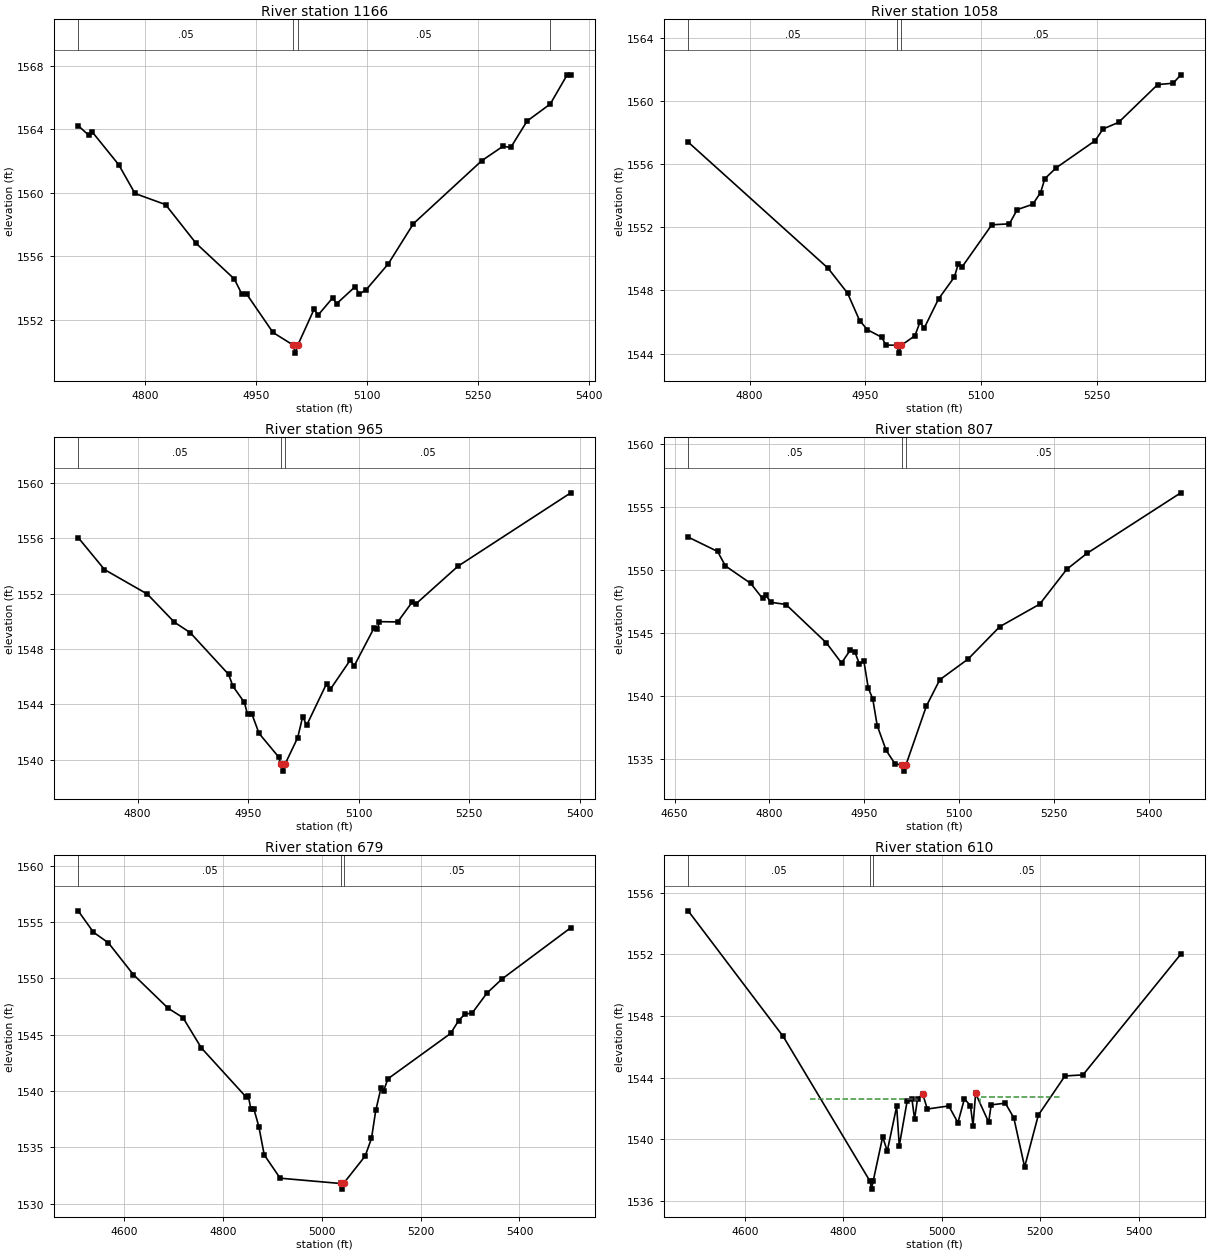
Type RM Length L Ch R = 1 ,1166    ,108,108,108
BEGIN DESCRIPTION:
EAST FORK THREEMILE CREEK 8.1
END DESCRIPTION:
XS GIS Cut Line= 4
      2817514.05     10041473.26      2817730.01     10041417.91
      2817787.52     10041261.66      2817673.57     10041009.88
#Sta/Elev= 30
    4710 1564.22    4724 1563.63  4729.1 1563.82  4764.8 1561.76  4786.8 1559.95
  4828.1 1559.25  4869.4 1556.81    4921 1554.57  4931.3 1553.61  4937.8 1553.61
  4973.3  1551.2  5000.8  1550.4  5003.5  1549.9  5006.8  1550.4  5028.9 1552.67
  5034.2 1552.29    5054 1553.38  5059.3 1553.01  5084.5 1554.09  5089.8 1553.61
  5099.4  1553.9  5129.1 1555.52  5163.1 1558.05  5255.6 1562.02  5284.1 1562.92
  5294.7 1562.85  5316.7 1564.51    5348 1565.58  5370.9 1567.42  5375.8 1567.42
#Mann= 4 ,-1 , 0
    4710     .05       0  5000.8    .035       0  5006.8     .05       0
    5348      .1       0
Bank Sta=5000.8,5006.8
XS Rating Curve= 0 ,0
Exp/Cntr=0.3,0.1

Type RM Length L Ch R = 1 ,1058    ,93,93,93
BEGIN DESCRIPTION:
Mapping XS 603a98b9
END DESCRIPTION:
XS GIS Cut Line= 4
      2817692.01     10041569.83      2817834.18     10041492.78
        2817883.     10041263.83      2817848.28     10041024.03
#Sta/Elev= 30
  4720.3  1557.4  4901.5 1549.41  4926.8 1547.83  4942.4 1546.09  4952.6 1545.51
  4971.2 1545.03  4976.3 1544.54  4990.5 1544.53  4993.3 1544.03  4996.5 1544.53
    5014 1545.13  5020.7 1546.01  5025.9  1545.6  5044.6 1547.46  5065.1 1548.85
  5070.3  1549.7  5075.4 1549.51  5113.6 1552.16  5136.4 1552.22  5146.5 1553.12
  5166.7 1553.46  5176.8  1554.2  5182.3 1555.08    5197 1555.77  5247.5 1557.49
  5257.7 1558.23  5277.9 1558.65  5328.4 1561.04  5348.6 1561.13  5358.4 1561.66
#Mann= 3 ,-1 , 0
  4720.3     .05       0  4990.5    .035       0  4996.5     .05       0
Bank Sta=4990.5,4996.5
XS Rating Curve= 0 ,0
Exp/Cntr=0.3,0.1

Type RM Length L Ch R = 1 ,965     ,158,158,158
BEGIN DESCRIPTION:
Mapping XS 9a9a5ba9
END DESCRIPTION:
XS GIS Cut Line= 4
      2817733.23     10041577.44      2817930.75     10041456.97
      2817983.92     10041289.87      2817930.76     10041033.84
#Sta/Elev= 30
  4719.4 1556.04  4755.1 1553.73  4813.2 1551.96  4849.9 1549.93  4871.3 1549.18
  4923.5 1546.16  4929.3 1545.31  4944.8 1544.14  4949.1 1543.29  4955.1 1543.29
  4964.8  1541.9  4991.8 1540.17    4994 1539.68  4996.8 1539.18    5000 1539.68
  5017.1 1541.59    5024 1543.12  5029.3 1542.49  5056.3 1545.49  5061.5 1545.09
  5088.5  1547.2  5093.7 1546.77  5120.7 1549.51  5125.4 1549.41  5127.8 1549.97
  5152.8 1549.95  5172.8 1551.41  5177.9 1551.27  5234.5 1553.97  5387.6 1559.27
#Mann= 3 ,-1 , 0
  4719.4     .05       0    4994    .035       0    5000     .05       0
Bank Sta=4994,5000
XS Rating Curve= 0 ,0
Exp/Cntr=0.3,0.1

Type RM Length L Ch R = 1 ,807     ,128,128,128
BEGIN DESCRIPTION:
Mapping XS 12001945
END DESCRIPTION:
XS GIS Cut Line= 4
      2817784.27     10041636.01      2818011.04     10041562.22
      2818133.65     10041441.78      2818011.04     10041093.48
#Sta/Elev= 30
  4671.4 1552.58  4717.9 1551.44  4730.4 1550.29  4770.5  1548.9  4789.1 1547.71
  4794.3 1547.98    4802 1547.41  4826.2 1547.23  4890.1 1544.19  4914.1 1542.59
  4928.2 1543.63  4935.2 1543.47  4942.4 1542.51  4949.4 1542.76  4956.5 1540.59
  4963.5 1539.75  4970.6 1537.62  4984.8 1535.65  4998.9 1534.58  5010.1 1534.51
  5012.8 1534.01  5016.1 1534.51  5048.4 1539.17  5069.6 1541.26  5114.6 1542.91
  5164.5 1545.47  5227.8 1547.26  5270.5 1550.02  5302.3 1551.28    5451 1556.09
#Mann= 3 ,-1 , 0
  4671.4     .05       0  5010.1    .035       0  5016.1     .05       0
Bank Sta=5010.1,5016.1
XS Rating Curve= 0 ,0
Exp/Cntr=0.3,0.1

Type RM Length L Ch R = 1 ,679     ,69,69,69
BEGIN DESCRIPTION:
Mapping XS 69f27724
END DESCRIPTION:
XS GIS Cut Line= 4
      2817777.75     10041746.69      2818126.06     10041707.62
       2818224.8     10041455.89       2818050.1     10041123.84
#Sta/Elev= 30
  4507.7 1555.99  4538.6 1554.09  4568.8 1553.15  4619.1 1550.34  4689.5 1547.35
  4719.7 1546.51  4756.7 1543.83  4846.9 1539.49  4851.9 1539.52  4856.9 1538.41
    4863 1538.41  4873.1 1536.83  4883.9 1534.34  4916.1 1532.27  5038.2  1531.8
  5040.9  1531.3  5044.2  1531.8  5087.9 1534.23  5100.8  1535.8  5109.4 1538.28
  5119.9 1540.25  5125.2 1540.02  5134.1 1541.09  5260.7 1545.11    5277 1546.25
  5289.2 1546.81  5304.7 1546.94  5334.4  1548.7  5365.2 1549.96  5503.8 1554.49
#Mann= 3 ,-1 , 0
  4507.7     .05       0  5038.2    .035       0  5044.2     .05       0
Bank Sta=5038.2,5044.2
XS Rating Curve= 0 ,0
Exp/Cntr=0.3,0.1

Type RM Length L Ch R = 1 ,610     ,49,49,49
BEGIN DESCRIPTION:
Mapping XS b30a2c2d
END DESCRIPTION:
XS GIS Cut Line= 6
      2817797.32     10041783.57      2818194.42     10041724.99
      2818249.76     10041565.48      2818262.78     10041531.84
       2818268.2     10041485.18      2818103.53     10041178.58
#Sta/Elev= 30
  4484.6 1554.84  4677.8 1546.67  4854.5 1537.24  4857.3 1536.74  4860.5 1537.24
    4880 1540.14  4889.3 1539.21  4908.4 1542.12  4913.7 1539.56  4929.7 1542.46
  4939.5 1542.59  4944.8 1541.29  4950.8 1542.61  4961.4 1542.92  4970.7 1541.95
  5014.3 1542.15  5032.9 1541.06  5046.1 1542.61  5058.4 1542.17  5063.6 1540.87
  5068.9 1542.96  5095.4 1541.09  5100.5 1542.22  5129.3 1542.33  5146.5 1541.38
  5168.5 1538.18  5196.3 1541.55  5250.5  1544.1  5287.1 1544.17  5485.9 1552.02
#Mann= 3 ,-1 , 0
  4484.6     .05       0  4854.5    .035       0  4860.5     .05       0
#XS Ineff= 2 ,-1
 4732.05 4950.23 1542.63 5078.41 5242.05 1542.73
Permanent Ineff=
       T       T
Bank Sta=4961.4,5068.9
XS Rating Curve= 0 ,0
Exp/Cntr=0.3,0.1

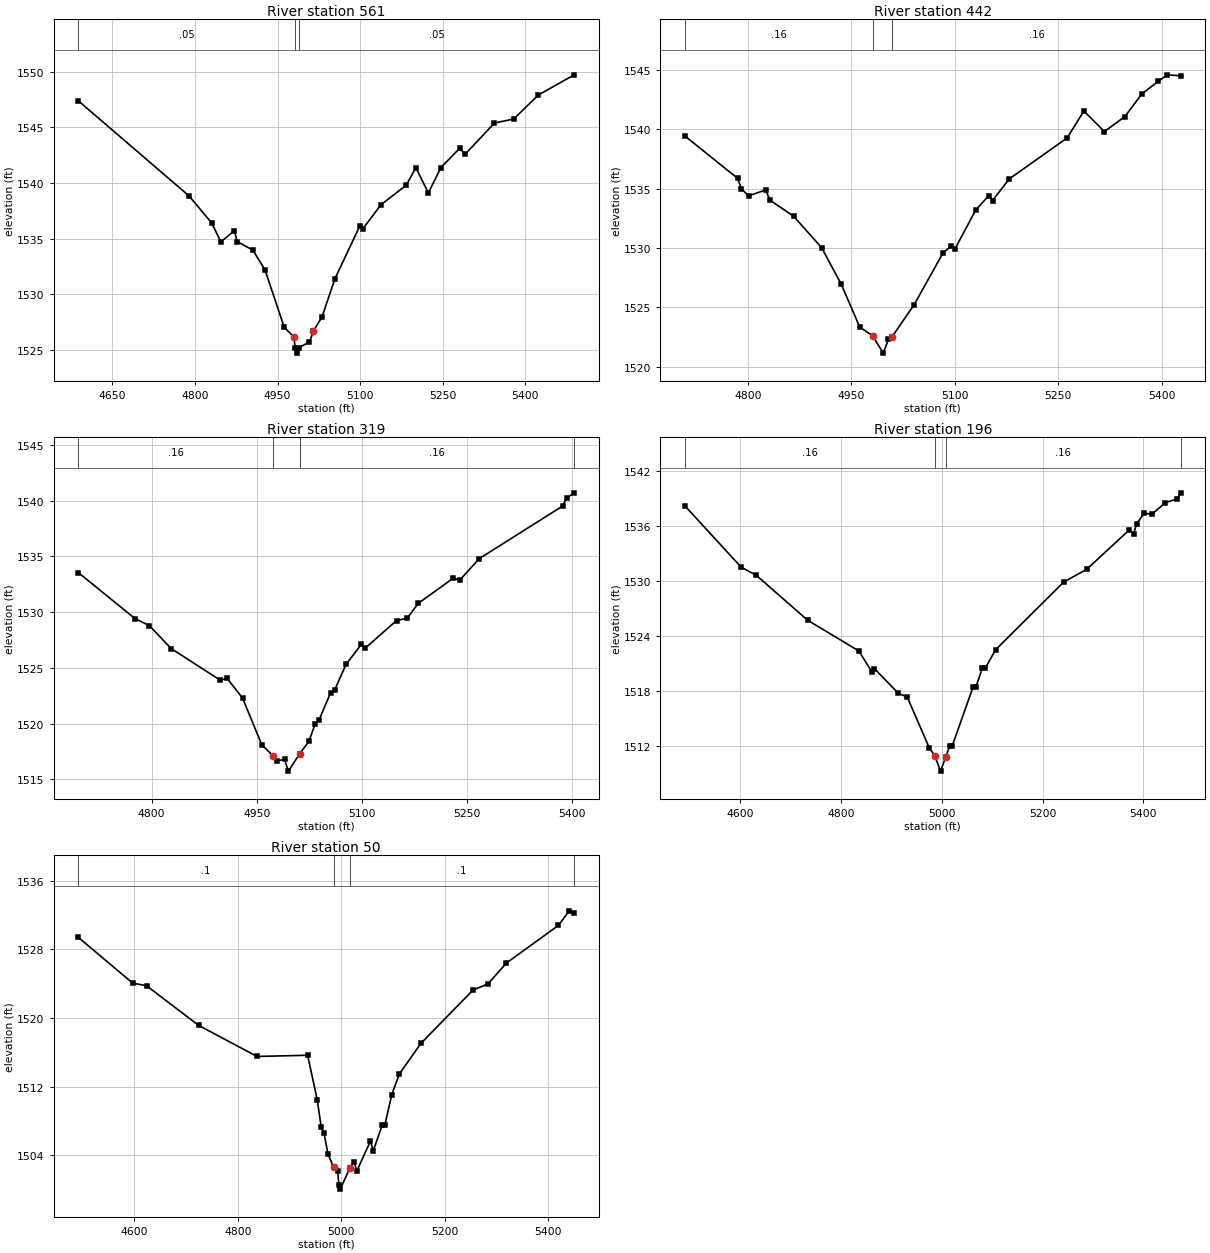
Type RM Length L Ch R = 1 ,561     ,119,119,119
BEGIN DESCRIPTION:
Mapping XS 94fc0474
END DESCRIPTION:
XS GIS Cut Line= 4
      2817937.22     10041826.99      2818220.46     10041756.45
      2818320.29     10041540.52      2818164.02     10041204.12
#Sta/Elev= 30
  4588.2  1547.4  4789.2 1538.84  4830.5  1536.4  4847.1  1534.7  4871.8 1535.71
  4876.5 1534.73  4905.1 1533.96  4927.2 1532.19  4962.2 1527.01  4979.6 1526.14
  4982.2 1525.18  4984.9 1524.68  4988.2 1525.18  5008.1 1525.66  5015.3 1526.68
    5031 1527.95    5054 1531.34  5099.8 1536.16  5105.3 1535.89  5138.1 1538.05
  5183.9  1539.8  5201.3 1541.38  5224.1  1539.1  5246.8 1541.39    5281 1543.13
  5290.9 1542.59  5344.1  1545.4  5379.1 1545.76  5423.8 1547.92  5488.9 1549.74
#Mann= 3 ,-1 , 0
  4588.2     .05       0  4982.2    .035       0  4988.2     .05       0
Bank Sta=4979.6,5015.3
XS Rating Curve= 0 ,0
Exp/Cntr=0.3,0.1

Type RM Length L Ch R = 1 ,442     ,123,123,123
BEGIN DESCRIPTION:
Mapping XS 7145a592
END DESCRIPTION:
XS GIS Cut Line= 4
      2818108.97      10041807.8       2818355.1     10041743.99
      2818408.48     10041633.31      2818282.82     10041315.93
#Sta/Elev= 30
  4708.8 1539.43  4785.3 1535.86  4790.9 1534.97  4801.3 1534.38  4825.9 1534.88
  4832.2 1534.02  4866.4 1532.67    4907 1530.02  4935.6 1526.93  4962.2 1523.34
  4981.2 1522.57  4996.4 1521.13  5003.8 1522.28  5009.3 1522.52  5041.1 1525.21
  5082.9 1529.56  5095.2 1530.18  5100.6 1529.94  5130.3 1533.18  5149.3  1534.4
  5154.7 1533.99    5179 1535.81  5262.8 1539.26  5287.1 1541.53  5316.8  1539.8
  5346.5 1541.06  5370.9 1542.96  5395.2 1544.05  5408.1 1544.58  5427.3  1544.5
#Mann= 3 , 0 , 0
  4708.8     .16       0  4981.2     .07       0  5009.3     .16       0
Bank Sta=4981.2,5009.3
XS Rating Curve= 0 ,0
Exp/Cntr=0.3,0.1

Type RM Length L Ch R = 1 ,319     ,123,123,123
BEGIN DESCRIPTION:
Mapping XS 0bd0f718
END DESCRIPTION:
XS GIS Cut Line= 4
      2818230.27     10041810.72      2818428.79     10041862.79
      2818528.62     10041677.24      2818386.46     10041422.23
#Sta/Elev= 30
  4695.4 1533.55  4776.2 1529.43  4796.9 1528.79  4827.9 1526.74  4897.9 1523.91
  4907.9 1524.06  4929.8 1522.31  4957.4  1518.1  4973.6 1517.12  4979.3 1516.68
  4989.8  1516.8  4995.3 1515.75  5011.7 1517.33  5024.5 1518.41  5033.6 1519.99
  5039.3 1520.37  5055.6 1522.78  5061.2    1523  5077.5 1525.31  5099.4 1527.11
  5105.1 1526.78  5149.7 1529.25  5164.9 1529.46  5180.9  1530.8  5230.1 1533.02
  5240.4  1532.9  5267.8  1534.8  5386.7 1539.51  5392.4 1540.22  5403.3  1540.7
#Mann= 4 ,-1 , 0
  4695.4     .16       0  4973.6     .07       0  5011.7     .16       0
  5403.3     .05       0
Bank Sta=4973.6,5011.7
XS Rating Curve= 0 ,0
Exp/Cntr=0.3,0.1

Type RM Length L Ch R = 1 ,196     ,146,146,146
BEGIN DESCRIPTION:
Mapping XS 42eec7df
END DESCRIPTION:
XS GIS Cut Line= 4
      2818128.58     10041820.82      2818555.62     10041900.24
      2818619.42     10041755.71      2818403.75     10041428.31
#Sta/Elev= 30
  4489.8 1538.21  4601.6 1531.53  4632.1 1530.62  4733.8 1525.74  4835.5 1522.39
  4861.1 1520.13  4866.2 1520.48  4913.9 1517.78  4931.3 1517.39    4975 1511.87
  4985.9 1511.01  4997.5 1509.31  5007.8 1510.84  5015.6 1512.01    5021  1512.1
  5062.2 1518.48  5067.7 1518.45  5080.5 1520.52  5086.3 1520.52  5106.8 1522.53
  5242.3 1529.91  5287.5 1531.28  5371.9 1535.56  5380.9 1535.19  5386.8 1536.25
  5401.9  1537.4    5417 1537.28  5444.1 1538.56  5467.7 1538.97  5474.2 1539.62
#Mann= 4 ,-1 , 0
  4489.8     .16       0  4985.9     .07       0  5007.8     .16       0
  5474.2     .05       0
Bank Sta=4985.9,5007.8
XS Rating Curve= 0 ,0
Exp/Cntr=0.3,0.1

Type RM Length L Ch R = 1 ,50      ,0,0,0
BEGIN DESCRIPTION:
EAST FORK THREEMILE CREEK 1.1
END DESCRIPTION:
XS GIS Cut Line= 4
      2818289.86     10041857.35      2818685.96     10041986.49
      2818741.29     10041819.39      2818525.67     10041523.94
#Sta/Elev= 30
  4491.6 1529.38  4596.7 1524.05  4623.4 1523.75  4724.3 1519.12  4837.2 1515.51
  4934.8 1515.65  4953.3 1510.49  4961.2 1507.24  4966.5 1506.55  4974.3 1504.13
  4984.9 1502.64  4992.9 1502.15  4995.2 1500.56  4997.9 1500.06  5016.5 1502.52
  5024.6 1503.24  5029.9 1502.16  5056.3 1505.67  5061.6 1504.51  5079.3 1507.56
  5084.2 1507.56  5097.5 1511.08  5112.1 1513.47  5153.9 1517.04  5254.3 1523.23
  5283.6 1523.97  5319.2  1526.4  5419.6 1530.77  5440.4 1532.47    5450 1532.17
#Mann= 4 ,-1 , 0
  4491.6      .1       0  4984.9     .05       0  5016.5      .1       0
    5450      .1       0
Bank Sta=4984.9,5016.5
XS Rating Curve= 0 ,0
Exp/Cntr=0.3,0.1

Chan Stop Cuts=-1
Use User Specified Reach Order=0
Composite Channel Slope=5