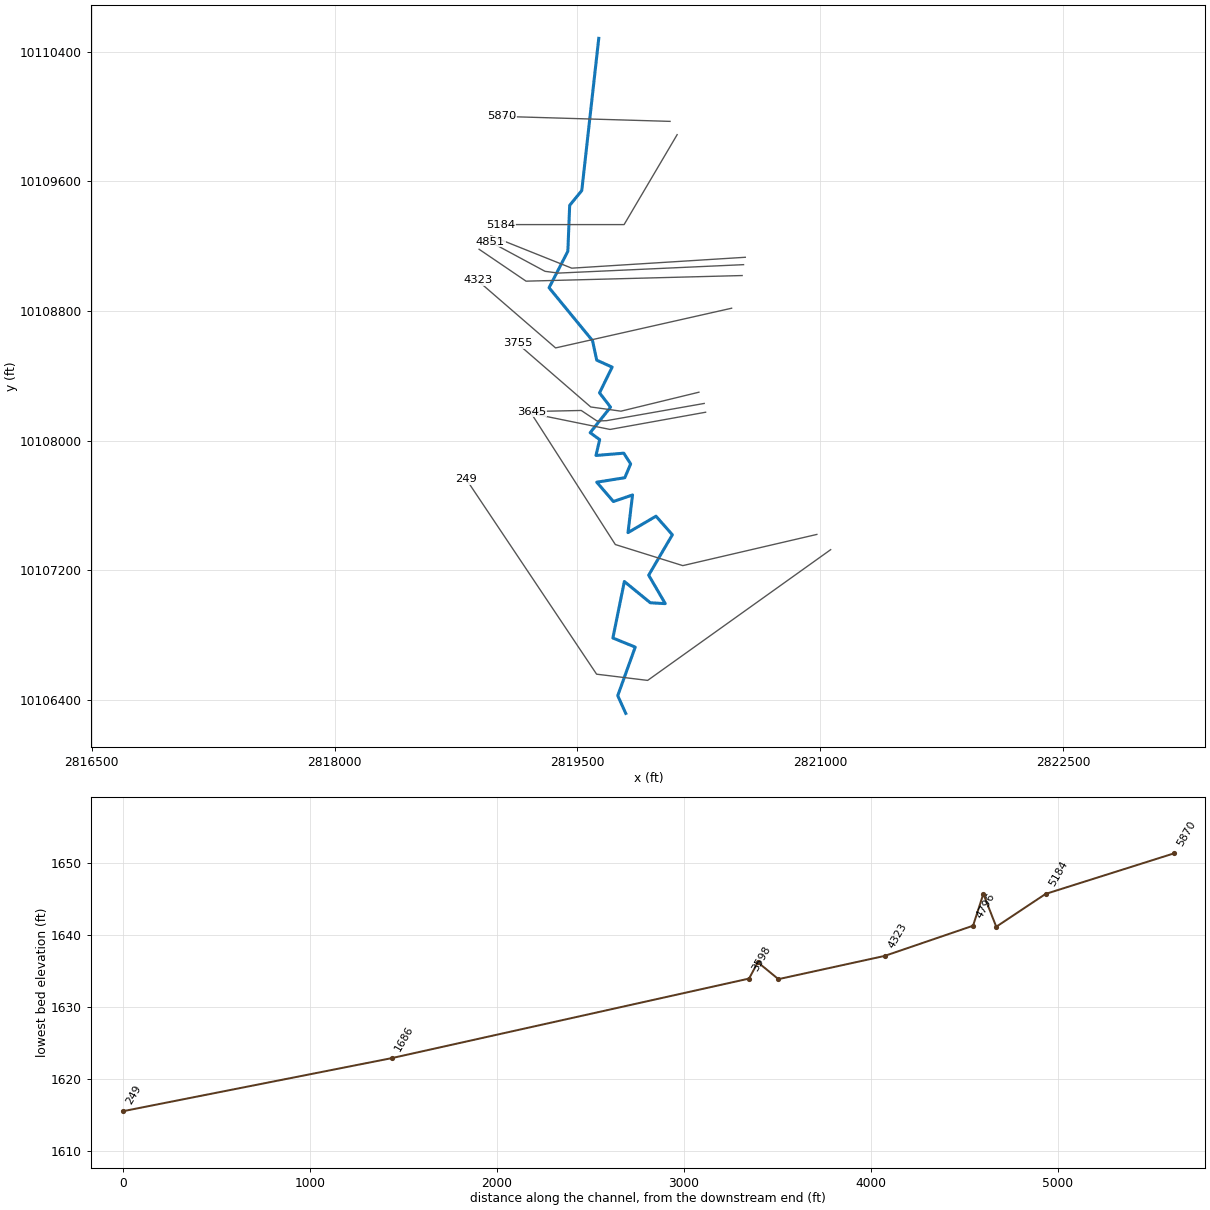
--- UNT074 IN NNOGR.prj (project) ---

Proj Title=UNT074 IN NNOGR Base Level Engineering
Current Plan=p01
Default Exp/Contr=0.3,0.1
English Units
Geom File=g01
Flow File=f01
Plan File=p01
BEGIN DESCRIPTION:
UNT074 IN NNOGR
END DESCRIPTION:

--- UNT074 IN NNOGR.p01 (plan) ---

Plan Title=Multiple Run
Short Identifier=Multiple
Geom File=g01
Flow File=f01
Subcritical Flow
K Sum by GR= 0
Std Step Tol= 0.01
Critical Tol= 0.01
Num of Std Step Trials= 20
Max Error Tol= 0.3
Flow Tol Ratio= 0.001
Split Flow NTrial= 30
Split Flow Tol= 0.02
Split Flow Ratio= 0.02
Log Output Level= 0
Friction Slope Method= 1
Unsteady Friction Slope Method= 2
Unsteady Bridges Friction Slope Method= 1
Parabolic Critical Depth
Global Vel Dist=  1 , 1 , 1
Global Log Level= 0
CheckData=True
Encroach Param= -1, 0, 0, 0
BEGIN DESCRIPTION:
Multiple Run
END DESCRIPTION:

--- UNT074 IN NNOGR.f01 (steady flow) ---

Flow Title=Multiple
Number of Profiles=7
Profile Names=10-year,25-year,50-year,1pct_min,100-year,1pct_plu,500-year
River Rch & RM= UNT074 IN NNOGR,Reach-1,5870
     783    1132    1434    1331    1800    2434    2846
River Rch & RM= UNT074 IN NNOGR,Reach-1,5184
     971    1416    1803    1679    2271    3071    3619
Boundary for River Rch & Prof#=UNT074 IN NNOGR,Reach-1,1
Up Type=0
Dn Type=3
Dn Slope=0.005
Boundary for River Rch & Prof#=UNT074 IN NNOGR,Reach-1,2
Up Type=0
Dn Type=3
Dn Slope=0.005
Boundary for River Rch & Prof#=UNT074 IN NNOGR,Reach-1,3
Up Type=0
Dn Type=3
Dn Slope=0.005
Boundary for River Rch & Prof#=UNT074 IN NNOGR,Reach-1,4
Up Type=0
Dn Type=3
Dn Slope=0.005
Boundary for River Rch & Prof#=UNT074 IN NNOGR,Reach-1,5
Up Type=0
Dn Type=3
Dn Slope=0.005
Boundary for River Rch & Prof#=UNT074 IN NNOGR,Reach-1,6
Up Type=0
Dn Type=3
Dn Slope=0.005
Boundary for River Rch & Prof#=UNT074 IN NNOGR,Reach-1,7
Up Type=0
Dn Type=3
Dn Slope=0.005

--- UNT074 IN NNOGR.g01 (geometry) ---

Geom Title=Existing Conditions

River Reach=UNT074 IN NNOGR,Reach-1
Reach XY= 30
      2819632.06     10110483.90      2819527.29     10109543.81
      2819452.49     10109452.43      2819441.22     10109168.85
      2819325.29     10108943.60      2819593.70     10108616.56
      2819619.56     10108496.20      2819714.79     10108453.29
      2819636.75     10108294.12      2819704.98     10108206.10
      2819578.94     10108048.28      2819637.79     10108005.57
      2819614.88     10107907.66      2819786.75     10107921.72
      2819828.94     10107855.57      2819793.00     10107770.16
      2819619.56     10107742.55      2819722.69     10107623.28
      2819840.73     10107663.74      2819812.79     10107431.10
      2819985.65     10107532.55      2820086.67     10107417.79
      2819940.43     10107168.18      2820042.84     10106992.56
      2819950.82     10106997.69      2819790.20     10107129.13
      2819719.32     10106780.23      2819857.38     10106724.05
      2819749.27     10106424.11      2819798.84     10106314.71

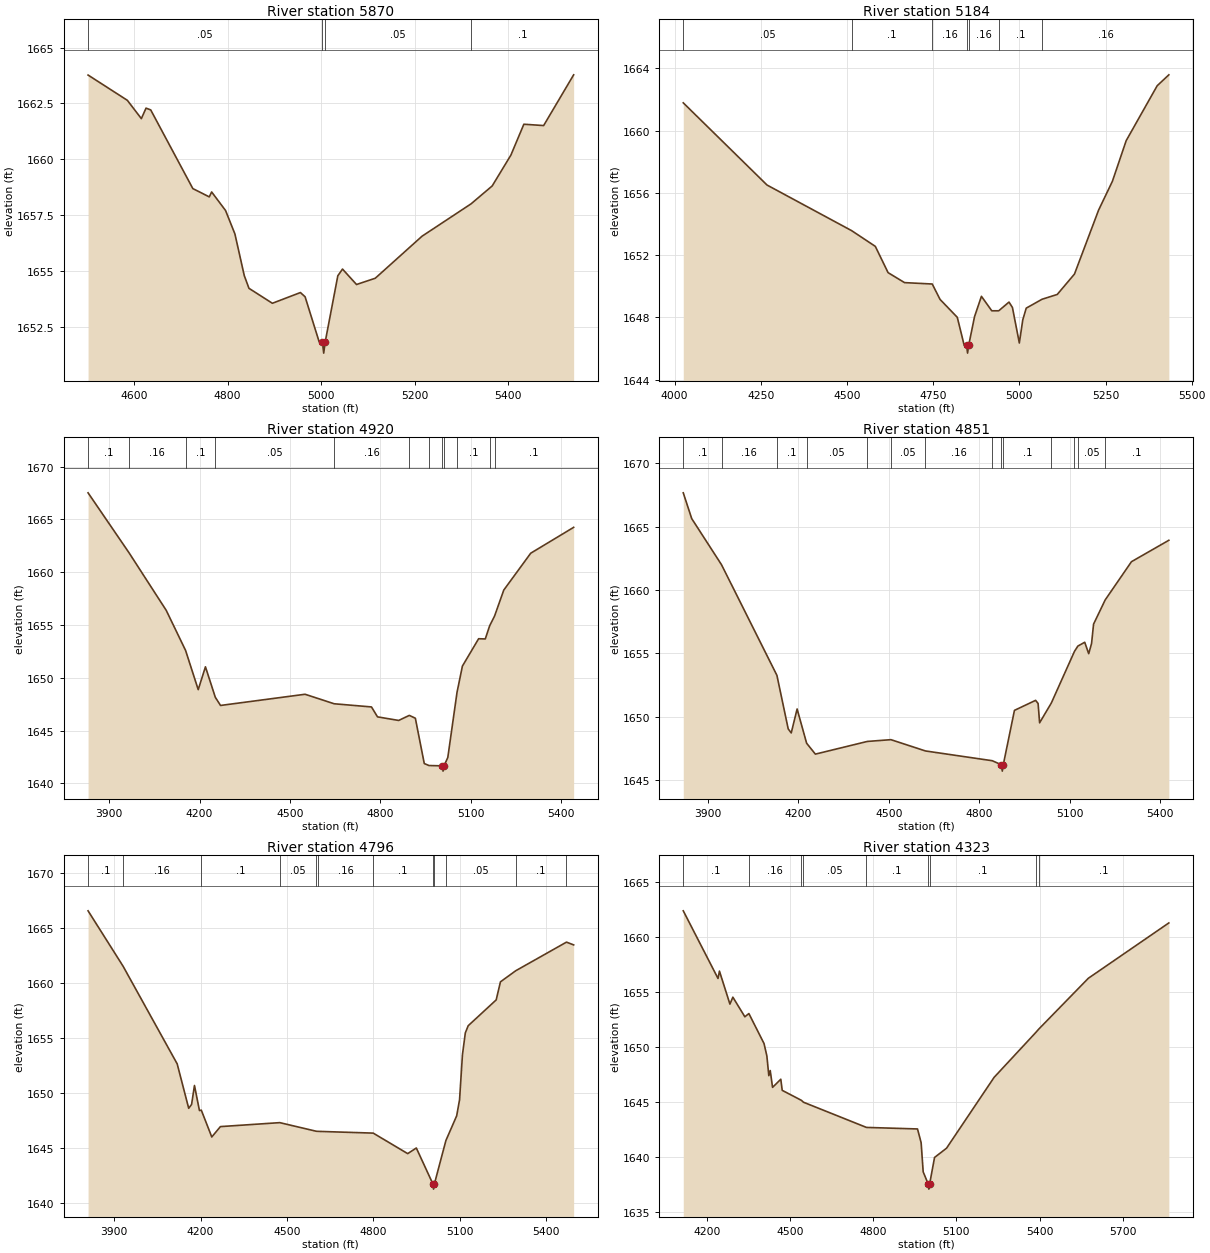
Type RM Length L Ch R = 1,5870,686,686,686
BEGIN DESCRIPTION:
UNT074 IN NNOGR 6.0
END DESCRIPTION:
XS GIS Cut Line= 2
      2820072.45     10109971.05      2819034.31     10110001.81
#Sta/Elev= 30
  4501.4 1663.77  4585.4 1662.64  4615.4 1661.82  4625.4 1662.29  4635.4 1662.21
  4725.5 1658.69  4760.7 1658.32  4765.7 1658.54  4795.5 1657.71  4815.5 1656.66
  4835.5 1654.80  4845.5 1654.23  4895.6 1653.56  4955.6 1654.04  4965.6 1653.85
  4995.6 1651.84  5002.6 1651.83  5005.4 1651.33  5008.6 1651.83  5035.6 1654.79
  5045.6 1655.09  5075.6 1654.40  5115.7 1654.68  5215.7 1656.56  5320.7 1658.01
  5365.8 1658.81  5405.8 1660.19  5433.5 1661.57  5475.8 1661.51  5540.0 1663.78
#Mann=4,-1,0
  4501.4    0.05       0  5002.6   0.035       0  5008.6    0.05       0
  5320.7     0.1       0
Bank Sta=5002.6,5008.6
Exp/Cntr=0.3,0.1

Type RM Length L Ch R = 1,5184,264,264,264
BEGIN DESCRIPTION:
UNT074 IN NNOGR 5.0
END DESCRIPTION:
XS GIS Cut Line= 3
      2820116.29     10109889.06      2819788.61     10109333.52
      2819024.69     10109333.52
#Sta/Elev= 30
  4024.9 1661.79  4267.9 1656.51  4513.3 1653.58  4582.1 1652.57  4619.2 1650.88
  4666.9 1650.24  4747.3 1650.15  4770.0 1649.16  4820.0 1648.01  4840.0 1646.21
  4847.0 1646.21  4849.8 1645.71  4853.0 1646.21  4870.0 1648.05  4890.0 1649.36
  4920.0 1648.43  4940.2 1648.43  4970.0 1648.99  4980.0 1648.64  5000.0 1646.36
  5010.0 1647.85  5020.0 1648.60  5065.8 1649.17  5110.0 1649.48  5160.0 1650.79
  5230.0 1654.90  5270.0 1656.75  5310.0 1659.36  5400.0 1662.89  5433.8 1663.59
#Mann=7,-1,0
  4024.9    0.05       0  4513.3     0.1       0  4747.3    0.16       0
  4847.0    0.07       0  4853.0    0.16       0  4940.2     0.1       0
  5065.8    0.16       0
Bank Sta=4847,4853
Exp/Cntr=0.3,0.1

Type RM Length L Ch R = 1,4920,69,69,69
BEGIN DESCRIPTION:
Mapping XS 4994d299
END DESCRIPTION:
XS GIS Cut Line= 3
      2820537.32     10109131.70      2819465.26     10109064.42
      2818966.17     10109264.05
#Sta/Elev= 30
  3829.9 1667.52  3965.9 1661.84  4089.3 1656.39  4153.6 1652.59  4195.5 1648.88
  4219.5 1651.04  4252.3 1648.15  4269.6 1647.38  4550.2 1648.44  4646.7 1647.54
  4770.6 1647.24  4790.6 1646.30  4860.8 1645.96  4896.2 1646.44  4916.2 1646.17
  4945.8 1641.88  4961.3 1641.69  5005.3 1641.66  5008.1 1641.16  5011.3 1641.66
  5023.9 1642.45  5054.5 1648.62  5072.4 1651.11  5126.2 1653.70  5148.3 1653.68
  5162.7 1654.92  5179.0 1655.84  5209.7 1658.31  5299.1 1661.80  5441.6 1664.25
#Mann=12,-1,0
  3829.9     0.1       0  3965.9    0.16       0  4153.6     0.1       0
  4252.3    0.05       0  4646.7    0.16       0  4896.2     0.1       0
  4961.3    0.05       0  5005.3   0.035       0  5011.3    0.05       0
  5054.5     0.1       0  5162.7    0.05       0  5179.0     0.1       0
Bank Sta=5005.3,5011.3
Exp/Cntr=0.3,0.1

Type RM Length L Ch R = 1,4851,55,55,55
BEGIN DESCRIPTION:
UNT074 IN NNOGR 4.0
END DESCRIPTION:
XS GIS Cut Line= 4
      2820526.42     10109086.12      2819382.79     10109034.04
      2819300.33     10109044.89      2818962.65     10109226.71
#Sta/Elev= 30
  3818.0 1667.66  3846.0 1665.63  3945.0 1661.99  4128.8 1653.27  4166.3 1649.05
  4176.3 1648.73  4195.8 1650.62  4227.4 1647.92  4256.4 1647.06  4428.8 1648.06
  4507.1 1648.20  4621.8 1647.31  4843.5 1646.54  4874.0 1646.22  4876.8 1645.72
  4880.0 1646.22  4917.1 1650.51  4987.3 1651.30  4995.6 1651.05  5000.6 1649.53
  5039.5 1651.09  5116.3 1655.16  5127.6 1655.58  5150.3 1655.88  5163.5 1654.98
  5173.0 1655.78  5179.7 1657.31  5218.3 1659.22  5305.4 1662.23  5429.5 1663.92
#Mann=14,-1,0
  3818.0     0.1       0  3945.0    0.16       0  4128.8     0.1       0
  4227.4    0.05       0  4428.8     0.1       0  4507.1    0.05       0
  4621.8    0.16       0  4843.5     0.1       0  4874.0    0.07       0
  4880.0     0.1       0  5039.5    0.05       0  5116.3     0.1       0
  5127.6    0.05       0  5218.3     0.1       0
Bank Sta=4874,4880
Exp/Cntr=0.3,0.1

Type RM Length L Ch R = 1,4796,473,473,473
BEGIN DESCRIPTION:
Mapping XS 6db9de13
END DESCRIPTION:
XS GIS Cut Line= 3
      2820517.78     10109018.85      2819183.14     10108984.13
      2818892.93     10109181.21
#Sta/Elev= 30
  3809.3 1666.54  3930.8 1661.52  4118.7 1652.66  4158.7 1648.63  4168.7 1648.98
  4178.7 1650.70  4196.0 1648.43  4202.5 1648.46  4238.8 1646.03  4268.8 1646.97
  4474.8 1647.33  4601.4 1646.55  4606.8 1646.54  4799.3 1646.38  4919.0 1644.52
  4949.0 1645.03  5006.0 1641.80  5008.8 1641.30  5012.0 1641.80  5051.7 1645.71
  5089.1 1647.95  5099.1 1649.41  5109.1 1653.48  5119.1 1655.47  5129.1 1656.12
  5226.2 1658.46  5241.1 1660.10  5294.4 1661.11  5470.3 1663.70  5495.2 1663.45
#Mann=12,-1,0
  3809.3     0.1       0  3930.8    0.16       0  4202.5     0.1       0
  4474.8    0.05       0  4601.4     0.1       0  4606.8    0.16       0
  4799.3     0.1       0  5006.0    0.07       0  5012.0     0.1       0
  5051.7    0.05       0  5294.4     0.1       0  5470.3    0.05       0
Bank Sta=5006,5012
Exp/Cntr=0.3,0.1

Type RM Length L Ch R = 1,4323,568,568,568
BEGIN DESCRIPTION:
Mapping XS fd6d4222
END DESCRIPTION:
XS GIS Cut Line= 3
      2820452.68     10108817.03      2819365.43     10108571.80
      2818883.68     10108988.45
#Sta/Elev= 30
  4114.8 1662.41  4240.2 1656.26  4245.3 1656.93  4283.1 1653.93  4293.7 1654.56
  4336.9 1652.78  4351.5 1653.07  4406.2 1650.34  4416.4 1649.21  4423.4 1647.42
  4428.5 1647.89  4436.9 1646.36  4466.6 1647.10  4471.7 1646.09  4541.1 1645.18
  4548.4 1645.01  4775.5 1642.72  4959.7 1642.58  4972.8 1641.33  4980.2 1638.68
  4997.7 1637.61  5000.5 1637.11  5003.7 1637.61  5021.2 1639.99  5064.4 1640.83
  5236.0 1647.27  5387.1 1651.37  5396.8 1651.65  5576.0 1656.28  5866.3 1661.31
#Mann=9,-1,0
  4114.8     0.1       0  4351.5    0.16       0  4541.1     0.1       0
  4548.4    0.05       0  4775.5     0.1       0  4997.7    0.07       0
  5003.7     0.1       0  5387.1    0.05       0  5396.8     0.1       0
Bank Sta=4997.7,5003.7
Exp/Cntr=0.3,0.1

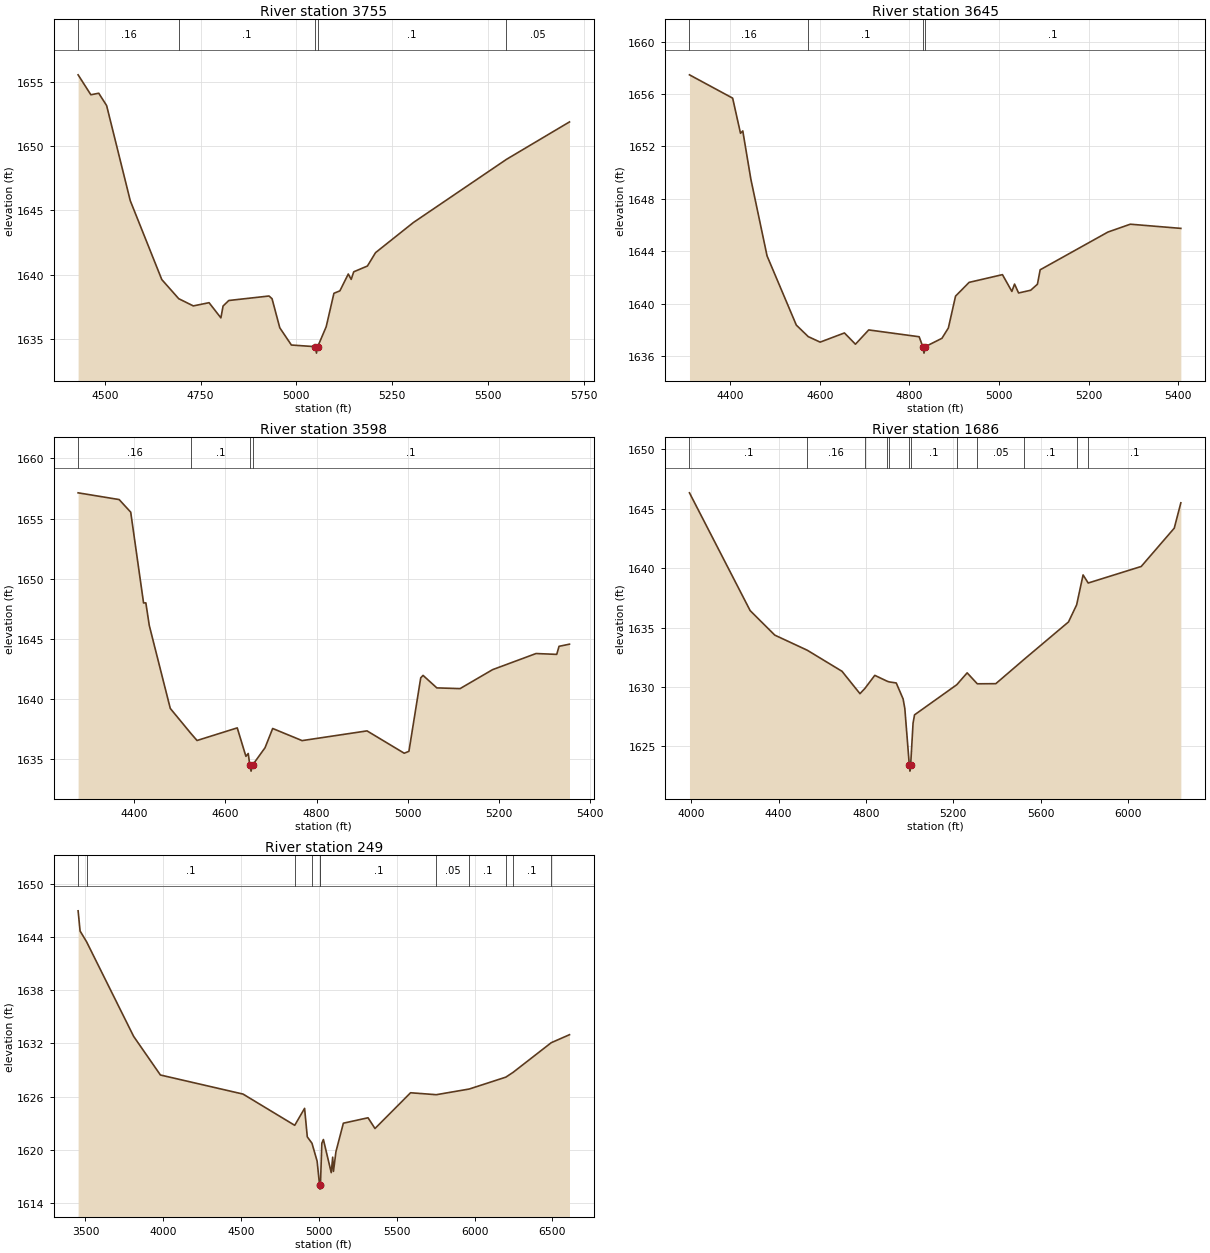
Type RM Length L Ch R = 1,3755,110,110,110
BEGIN DESCRIPTION:
Mapping XS 3728f979
END DESCRIPTION:
XS GIS Cut Line= 4
      2820250.82     10108298.35      2819769.08     10108181.17
      2819582.45     10108207.22      2819129.59     10108599.40
#Sta/Elev= 30
  4430.0 1655.52  4463.3 1653.97  4483.9 1654.09  4504.5 1653.13  4566.2 1645.74
  4648.5 1639.61  4692.8 1638.12  4730.9 1637.56  4772.0 1637.81  4802.9 1636.63
  4808.6 1637.55  4823.5 1637.98  4928.6 1638.33  4936.5 1638.12  4956.7 1635.86
  4987.0 1634.52  5049.7 1634.39  5052.5 1633.89  5055.7 1634.39  5077.9 1635.94
  5098.1 1638.54  5113.7 1638.73  5135.6 1640.04  5143.2 1639.62  5149.8 1640.21
  5185.6 1640.66  5206.8 1641.70  5305.6 1644.04  5548.7 1648.95  5713.3 1651.86
#Mann=5,-1,0
  4430.0    0.16       0  4692.8     0.1       0  5049.7    0.07       0
  5055.7     0.1       0  5548.7    0.05       0
Bank Sta=5049.7,5055.7
Exp/Cntr=0.3,0.1

Type RM Length L Ch R = 1,3645,47,47,47
BEGIN DESCRIPTION:
UNT074 IN NNOGR 3.0
END DESCRIPTION:
XS GIS Cut Line= 5
      2820283.38     10108228.91      2819680.10     10108122.58
      2819621.51     10108120.41      2819523.85     10108185.51
      2819215.70     10108179.00
#Sta/Elev= 30
  4309.0 1657.47  4405.4 1655.69  4422.9 1653.01  4428.0 1653.19  4446.0 1649.51
  4482.2 1643.65  4547.5 1638.37  4574.1 1637.49  4600.7 1637.07  4654.9 1637.77
  4679.5 1636.91  4709.1 1638.00  4821.7 1637.48  4829.7 1636.73  4832.5 1636.23
  4835.7 1636.73  4872.5 1637.36  4886.9 1638.15  4902.9 1640.58  4933.2 1641.63
  5007.6 1642.22  5028.6 1640.94  5034.6 1641.50  5043.6 1640.82  5070.7 1641.03
  5085.7 1641.49  5091.8 1642.59  5243.0 1645.47  5293.0 1646.07  5405.8 1645.75
#Mann=4,-1,0
  4309.0    0.16       0  4574.1     0.1       0  4829.7    0.07       0
  4835.7     0.1       0
Bank Sta=4829.7,4835.7
Exp/Cntr=0.3,0.1

Type RM Length L Ch R = 1,3598,1912,1912,1912
BEGIN DESCRIPTION:
Mapping XS a21de505
END DESCRIPTION:
XS GIS Cut Line= 3
      2820292.08     10108174.66      2819701.81     10108068.33
      2819233.31     10108163.76
#Sta/Elev= 30
  4276.9 1657.14  4366.9 1656.58  4392.3 1655.53  4420.5 1647.97  4425.5 1647.98
  4433.0 1646.10  4479.1 1639.19  4524.5 1637.10  4537.8 1636.52  4626.0 1637.57
  4645.0 1635.20  4650.1 1635.44  4653.5 1634.47  4656.3 1633.97  4659.5 1634.47
  4687.0 1635.92  4703.7 1637.52  4768.3 1636.51  4910.7 1637.32  4992.3 1635.46
  5002.6 1635.62  5028.5 1641.74  5033.6 1641.94  5063.8 1640.90  5114.8 1640.84
  5186.2 1642.42  5281.4 1643.76  5326.8 1643.69  5331.9 1644.36  5354.8 1644.54
#Mann=4,-1,0
  4276.9    0.16       0  4524.5     0.1       0  4653.5    0.07       0
  4659.5     0.1       0
Bank Sta=4653.5,4659.5
Exp/Cntr=0.3,0.1

Type RM Length L Ch R = 1,1686,1437,1437,1437
BEGIN DESCRIPTION:
UNT074 IN NNOGR 2.0
END DESCRIPTION:
XS GIS Cut Line= 4
      2820979.21     10107419.97      2820151.11     10107227.27
      2819734.44     10107357.48      2819214.03     10108169.33
#Sta/Elev= 30
  3991.7 1646.32  4269.7 1636.42  4382.6 1634.36  4531.4 1633.09  4690.6 1631.32
  4772.8 1629.44  4795.4 1629.88  4840.7 1630.98  4898.1 1630.48  4906.7 1630.43
  4939.0 1630.34  4970.4 1629.00  4978.3 1628.19  4998.9 1623.43  5001.6 1622.93
  5004.9 1623.43  5016.0 1626.96  5022.8 1627.66  5216.2 1630.19  5263.8 1631.19
  5310.3 1630.27  5395.1 1630.28  5526.5 1632.35  5728.2 1635.47  5765.5 1636.91
  5794.9 1639.42  5818.4 1638.74  6061.2 1640.13  6212.6 1643.35  6242.8 1645.48
#Mann=12,-1,0
  3991.7     0.1       0  4531.4    0.16       0  4795.4     0.1       0
  4898.1    0.16       0  4906.7     0.1       0  4998.9    0.07       0
  5004.9     0.1       0  5216.2     0.1       0  5310.3    0.05       0
  5526.5     0.1       0  5765.5    0.05       0  5818.4     0.1       0
Bank Sta=4998.9,5004.9
Exp/Cntr=0.3,0.1

Type RM Length L Ch R = 1,249,0,0,0
BEGIN DESCRIPTION:
UNT074 IN NNOGR 1.0
END DESCRIPTION:
XS GIS Cut Line= 4
      2821064.44     10107325.78      2819934.04     10106518.35
      2819618.76     10106556.80      2818812.38     10107762.54
#Sta/Elev= 30
  3452.9 1646.93  3465.7 1644.65  3507.1 1643.45  3809.8 1632.78  3981.8 1628.43
  4512.7 1626.28  4844.7 1622.76  4908.1 1624.67  4925.5 1621.46  4955.6 1620.74
  4988.7 1618.72  5004.1 1616.07  5006.9 1615.57  5010.1 1616.07  5018.9 1620.74
  5029.0 1621.16  5079.4 1617.43  5088.7 1619.17  5093.7 1617.57  5109.6 1619.79
  5157.3 1623.00  5315.7 1623.61  5360.5 1622.40  5589.1 1626.43  5754.3 1626.21
  5966.1 1626.85  6201.3 1628.19  6247.9 1628.73  6493.0 1632.07  6610.2 1632.97
#Mann=11,-1,0
  3452.9    0.05       0  3507.1     0.1       0  4844.7    0.16       0
  4955.6     0.1       0  5004.1    0.07       0  5010.1     0.1       0
  5754.3    0.05       0  5966.1     0.1       0  6201.3    0.05       0
  6247.9     0.1       0  6493.0    0.05       0
Bank Sta=5004.1,5010.1
Exp/Cntr=0.3,0.1

Chan Stop Cuts=-1