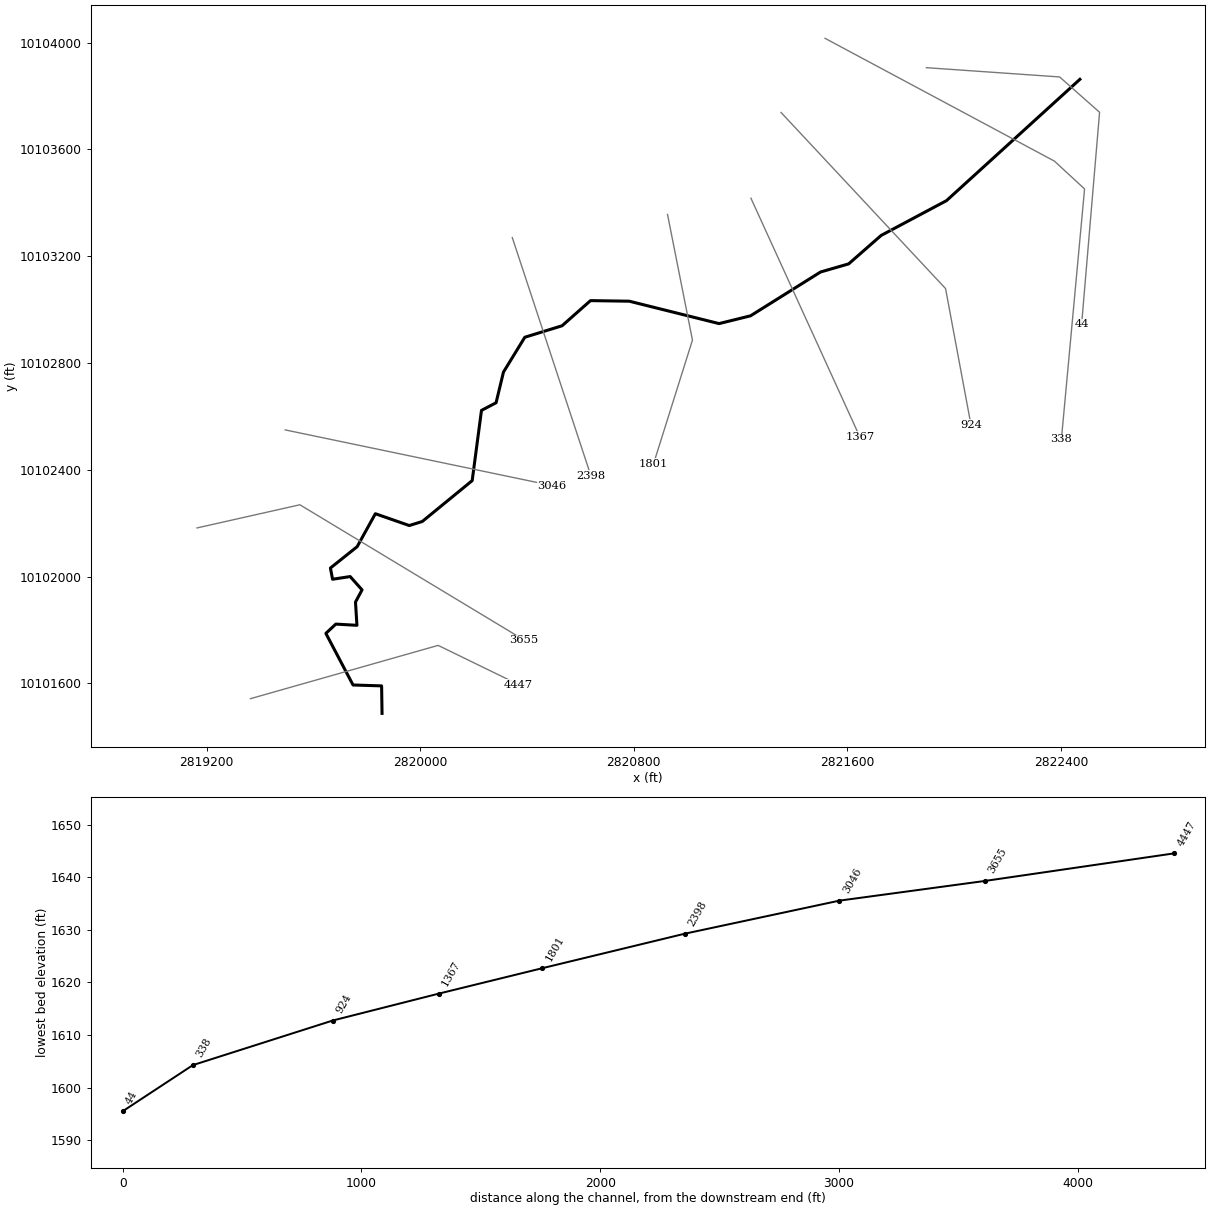
--- UNT075 IN NNOGR.prj (project) ---

Proj Title=UNT075 IN NNOGR Base Level Engineering
Current Plan=p01
Default Exp/Contr=0.3,0.1
English Units
Geom File=g01
Flow File=f01
Plan File=p01
Y Axis Title=Elevation
X Axis Title(PF)=Main Channel Distance
X Axis Title(XS)=Station
BEGIN DESCRIPTION:
UNT075 IN NNOGR
END DESCRIPTION:
DSS Export Rating Curves= 0
DSS Export Rating Curve Sorted= 0
DSS Export Volume Flow Curves= 0
DXF OffsetX= 0
DXF OffsetY= 0
DXF ScaleX= 1
DXF ScaleY= 10

--- UNT075 IN NNOGR.p01 (plan) ---

Plan Title=Multiple Run
Short Identifier=Multiple
Geom File=g01
Flow File=f01
Subcritical Flow
K Sum by GR= 0
Std Step Tol= 0.01
Critical Tol= 0.01
Num of Std Step Trials= 20
Max Error Tol= 0.3
Flow Tol Ratio= 0.001
Split Flow NTrial= 30
Split Flow Tol= 0.02
Split Flow Ratio= 0.02
Log Output Level= 0
Friction Slope Method= 1
Unsteady Friction Slope Method= 2
Unsteady Bridges Friction Slope Method= 1
Parabolic Critical Depth
Global Vel Dist=  1 , 1 , 1
Global Log Level= 0
CheckData=True
Encroach Param= -1, 0, 0, 0
BEGIN DESCRIPTION:
Multiple Run
END DESCRIPTION:

--- UNT075 IN NNOGR.f01 (steady flow) ---

Flow Title=Multiple
Program Version=4.10
Number of Profiles= 7
Profile Names=10-year,25-year,50-year,1pct_min,100-year,1pct_plu,500-year
River Rch & RM=UNT075 IN NNOGR,Reach-1         ,4447
     862    1241    1567    1449    1960    2651    3076
Boundary for River Rch & Prof#=UNT075 IN NNOGR,Reach-1         , 1
Up Type= 0
Dn Type= 3
Dn Slope=0.0126
Boundary for River Rch & Prof#=UNT075 IN NNOGR,Reach-1         , 2
Up Type= 0
Dn Type= 3
Dn Slope=0.0126
Boundary for River Rch & Prof#=UNT075 IN NNOGR,Reach-1         , 3
Up Type= 0
Dn Type= 3
Dn Slope=0.0126
Boundary for River Rch & Prof#=UNT075 IN NNOGR,Reach-1         , 4
Up Type= 0
Dn Type= 3
Dn Slope=0.0126
Boundary for River Rch & Prof#=UNT075 IN NNOGR,Reach-1         , 5
Up Type= 0
Dn Type= 3
Dn Slope=0.0126
Boundary for River Rch & Prof#=UNT075 IN NNOGR,Reach-1         , 6
Up Type= 0
Dn Type= 3
Dn Slope=0.0126
Boundary for River Rch & Prof#=UNT075 IN NNOGR,Reach-1         , 7
Up Type= 0
Dn Type= 3
Dn Slope=0.0126
DSS Import GetInterval= 0
DSS Import GetPeak= 0
DSS Import FillOption= 0

--- UNT075 IN NNOGR.g01 (geometry) ---

Geom Title=Existing Conditions
Program Version=4.10

River Reach=UNT075 IN NNOGR ,Reach-1
Reach XY= 30
      2819856.51     10101487.39      2819854.92     10101590.41
      2819747.88     10101593.72      2819646.12     10101787.06
      2819683.29     10101821.84      2819762.46     10101817.33
      2819757.03     10101904.39       2819781.6     10101950.11
      2819737.11     10101999.98      2819671.14      10101989.9
      2819663.15     10102031.91      2819763.31     10102111.96
      2819831.48     10102235.39      2819958.52     10102191.15
      2820007.18     10102206.27      2820194.23     10102359.36
      2820229.07     10102622.53      2820283.71     10102651.12
      2820311.44      10102766.1      2820391.45     10102896.58
        2820531.     10102939.57       2820637.5     10103033.79
      2820782.76     10103031.62      2821119.18     10102947.69
      2821237.15     10102976.88      2821499.39     10103141.01
      2821604.67     10103171.42      2821726.34     10103277.97
      2821971.35      10103408.4        2822471.     10103862.81

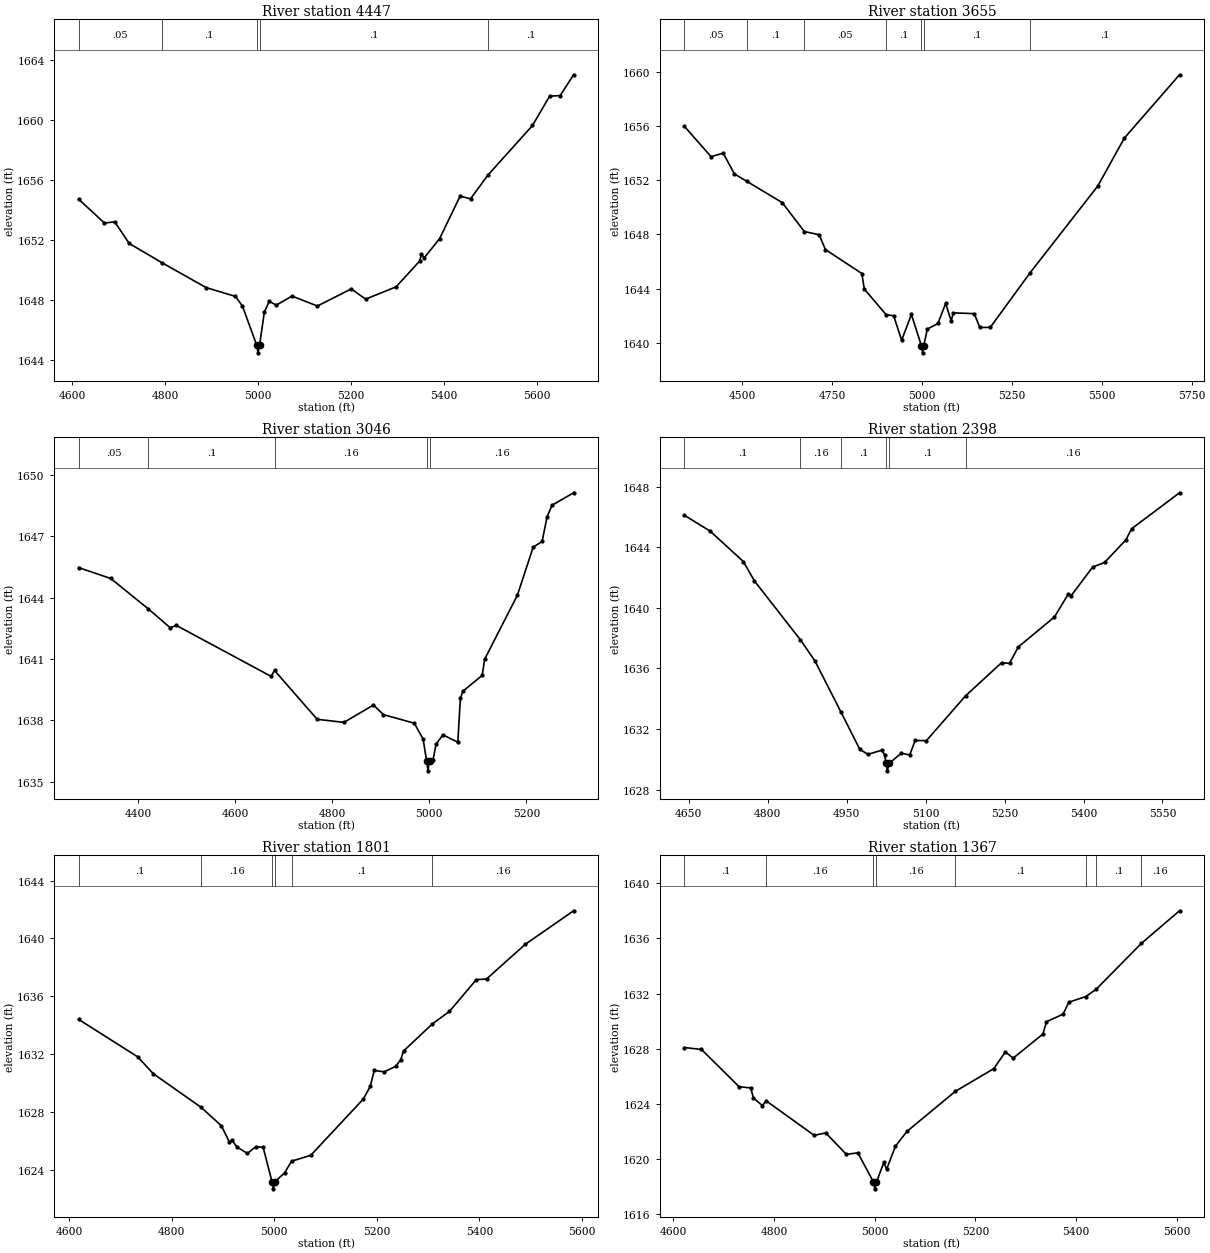
Type RM Length L Ch R = 1 ,4447    ,792,792,792
BEGIN DESCRIPTION:
UNT075 IN NNOGR 9.0
END DESCRIPTION:
XS GIS Cut Line= 3
       2819363.6     10101542.48      2820066.71     10101742.13
      2820368.15     10101595.31
#Sta/Elev= 30
  4613.4 1654.75  4669.1 1653.16  4691.2 1653.24  4722.4  1651.8  4792.7 1650.52
    4888 1648.86  4951.1 1648.27  4966.2 1647.64  4997.1 1645.01  4999.9 1644.51
  5003.1 1645.01  5013.5 1647.23  5023.9 1647.94  5039.2 1647.69  5073.1 1648.29
  5127.8 1647.63  5200.6 1648.77  5231.8 1648.09  5297.3 1648.91  5348.1 1650.63
  5351.9  1651.1  5357.5 1650.83  5390.8 1652.11  5435.2 1654.96  5457.5 1654.77
  5494.6 1656.34    5591 1659.66    5628 1661.62  5650.5 1661.65  5679.6 1663.04
#Mann= 5 ,-1 , 0
  4613.4     .05       0  4792.7      .1       0  4997.1     .07       0
  5003.1      .1       0  5494.6      .1       0
Bank Sta=4997.1,5003.1
XS Rating Curve= 0 ,0
Exp/Cntr=0.3,0.1

Type RM Length L Ch R = 1 ,3655    ,609,609,609
BEGIN DESCRIPTION:
UNT075 IN NNOGR 8.0
END DESCRIPTION:
XS GIS Cut Line= 3
      2819163.27     10102182.13      2819548.68     10102268.93
      2820388.94       10101762.
#Sta/Elev= 30
  4339.9 1655.97  4413.7 1653.74  4447.7    1654  4478.5 1652.47  4513.2 1651.92
  4611.7 1650.35  4673.1 1648.22  4714.2 1647.98  4731.8 1646.89  4833.1 1645.12
  4839.8 1643.98  4900.4 1642.09  4921.6    1642  4943.7  1640.2  4970.9  1642.1
  4998.9 1639.77  5001.7 1639.27  5004.9 1639.77    5015 1641.02  5044.6 1641.44
    5066 1642.91  5081.5 1641.63  5087.4 1642.22  5145.6 1642.16  5161.1 1641.14
  5190.2 1641.15  5301.3 1645.19  5489.2 1651.58  5562.9 1655.11  5716.3 1659.78
#Mann= 7 ,-1 , 0
  4339.9     .05       0  4513.2      .1       0  4673.1     .05       0
  4900.4      .1       0  4998.9     .07       0  5004.9      .1       0
  5301.3      .1       0
Bank Sta=4998.9,5004.9
XS Rating Curve= 0 ,0
Exp/Cntr=0.3,0.1

Type RM Length L Ch R = 1 ,3046    ,648,648,648
BEGIN DESCRIPTION:
UNT075 IN NNOGR 7.0
END DESCRIPTION:
XS GIS Cut Line= 2
      2819493.74     10102549.43      2820492.04      10102341.1
#Sta/Elev= 30
  4277.5 1645.47  4343.6 1644.94  4421.2 1643.45  4466.2 1642.53  4479.1 1642.64
  4674.1 1640.15  4681.1 1640.44    4769 1638.05  4824.1  1637.9    4885 1638.75
  4905.5 1638.28    4969 1637.86  4987.2 1637.09  4994.4 1636.03  4997.2 1635.53
  5000.4 1636.03  5007.6 1636.06    5014 1636.84  5028.1 1637.29  5058.7 1636.93
    5064 1639.07  5069.1 1639.42  5108.9  1640.2    5114 1640.99  5181.3 1644.11
    5214 1646.47  5232.4 1646.75  5242.6 1647.95  5252.8 1648.52  5297.3 1649.13
#Mann= 5 ,-1 , 0
  4277.5     .05       0  4421.2      .1       0  4681.1     .16       0
  4994.4     .07       0  5000.4     .16       0
Bank Sta=4994.4,5000.4
XS Rating Curve= 0 ,0
Exp/Cntr=0.3,0.1

Type RM Length L Ch R = 1 ,2398    ,597,597,597
BEGIN DESCRIPTION:
UNT075 IN NNOGR 5.0
END DESCRIPTION:
XS GIS Cut Line= 2
       2820344.5     10103269.87      2820639.15     10102377.24
#Sta/Elev= 30
  4642.3 1646.11  4690.9 1645.07  4754.1 1643.06  4775.1 1641.78  4862.2  1637.9
    4890  1636.5  4939.4 1633.12  4975.2 1630.66  4990.5 1630.33  5016.9  1630.6
  5022.2 1630.31  5024.9 1629.74  5027.6 1629.24  5030.9 1629.74    5054  1630.4
    5070 1630.29  5080.4 1631.25  5101.6 1631.23    5176 1634.19  5244.4 1636.38
  5259.5 1636.34  5276.2 1637.42  5344.9  1639.4  5371.4 1640.93  5376.7 1640.81
  5417.5  1642.7  5440.2    1643  5480.7  1644.5  5491.2 1645.22  5582.3  1647.6
#Mann= 6 ,-1 , 0
  4642.3      .1       0  4862.2     .16       0  4939.4      .1       0
  5024.9     .07       0  5030.9      .1       0    5176     .16       0
Bank Sta=5024.9,5030.9
XS Rating Curve= 0 ,0
Exp/Cntr=0.3,0.1

Type RM Length L Ch R = 1 ,1801    ,434,434,434
BEGIN DESCRIPTION:
UNT075 IN NNOGR 4.0
END DESCRIPTION:
XS GIS Cut Line= 3
      2820926.08     10103356.71      2821019.47     10102885.91
      2820873.72     10102422.67
#Sta/Elev= 30
  4618.2  1634.4  4733.4 1631.81    4764 1630.64    4857 1628.32  4896.5 1627.05
  4912.5 1625.91  4917.6 1626.04  4927.1 1625.57  4947.5 1625.13  4963.6 1625.59
  4978.1 1625.56  4995.4 1623.18  4998.2 1622.68  5001.4 1623.18  5019.9 1623.78
  5033.6 1624.59  5071.1    1625  5173.8  1628.9  5187.2 1629.77  5194.8 1630.87
  5214.3 1630.77  5236.7 1631.15  5246.7 1631.62    5252 1632.21  5308.4 1634.09
  5341.6 1634.95    5394 1637.15  5413.9 1637.19  5489.1 1639.58  5583.8 1641.91
#Mann= 6 ,-1 , 0
  4618.2      .1       0    4857     .16       0  4995.4     .07       0
  5001.4     .16       0  5033.6      .1       0  5308.4     .16       0
Bank Sta=4995.4,5001.4
XS Rating Curve= 0 ,0
Exp/Cntr=0.3,0.1

Type RM Length L Ch R = 1 ,1367    ,443,443,443
BEGIN DESCRIPTION:
UNT075 IN NNOGR 3.0
END DESCRIPTION:
XS GIS Cut Line= 2
      2821238.58     10103417.48      2821646.58     10102523.37
#Sta/Elev= 30
  4622.5 1628.09  4656.2 1627.95  4730.8 1625.25  4753.9 1625.16  4759.4 1624.43
  4776.9 1623.88  4784.8 1624.22    4880 1621.72  4903.1  1621.9  4943.7 1620.34
  4966.7 1620.45  4997.7 1618.34  5000.5 1617.84  5003.7 1618.34  5018.3 1619.76
  5023.8 1619.26  5041.3 1620.93  5064.3 1622.01  5160.2 1624.91  5236.6 1626.56
  5259.6 1627.77  5275.1 1627.32  5334.2 1629.07  5341.1 1629.96  5374.1 1630.51
  5385.8 1631.38  5419.4 1631.79  5439.6 1632.31  5529.5 1635.64  5605.3 1638.01
#Mann= 8 ,-1 , 0
  4622.5      .1       0  4784.8     .16       0  4997.7     .07       0
  5003.7     .16       0  5160.2      .1       0  5419.4     .16       0
  5439.6      .1       0  5529.5     .16       0
Bank Sta=4997.7,5003.7
XS Rating Curve= 0 ,0
Exp/Cntr=0.3,0.1

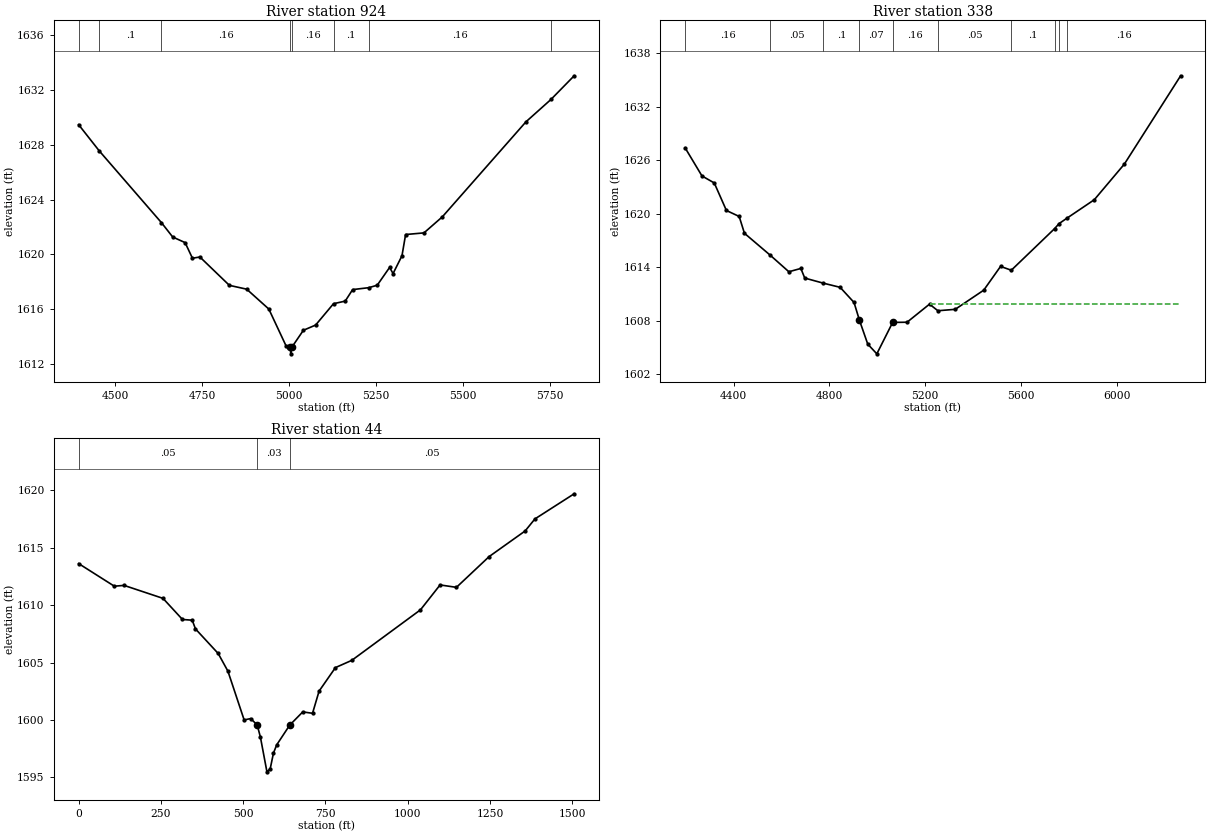
Type RM Length L Ch R = 1 ,924     ,586,586,586
BEGIN DESCRIPTION:
UNT075 IN NNOGR 2.0
END DESCRIPTION:
XS GIS Cut Line= 3
      2821351.46     10103738.63      2821967.75     10103078.94
      2822063.06     10102567.72
#Sta/Elev= 30
  4395.9 1629.47    4455 1627.56  4633.6 1622.32    4666 1621.27  4701.6 1620.86
  4722.7 1619.72  4744.1 1619.81  4828.7 1617.74  4878.5 1617.46    4942 1616.01
  4991.3 1613.33  5002.5 1613.24  5005.3 1612.74  5008.5 1613.24  5041.2 1614.46
  5076.3 1614.84  5127.7  1616.4  5161.3 1616.59  5182.6 1617.43  5228.9 1617.57
  5253.2 1617.75  5288.8 1619.05  5298.7  1618.6  5324.3  1619.9  5334.7 1621.45
  5387.4 1621.57  5440.1 1622.74  5680.3 1629.68    5752 1631.31  5818.7 1633.04
#Mann= 8 ,-1 , 0
  4395.9     .16       0    4455      .1       0  4633.6     .16       0
  5002.5     .07       0  5008.5     .16       0  5127.7      .1       0
  5228.9     .16       0    5752     .05       0
Bank Sta=5002.5,5008.5
XS Rating Curve= 0 ,0
Exp/Cntr=0.3,0.1

Type RM Length L Ch R = 1 ,338     ,294,294,294
BEGIN DESCRIPTION:
UNT075 IN NNOGR 1.0
END DESCRIPTION:
XS GIS Cut Line= 4
      2821516.34     10104016.45      2822375.74     10103556.37
      2822488.58      10103452.2      2822401.78     10102514.69
#Sta/Elev= 30
  4196.9  1627.4  4267.4 1624.24  4318.8 1623.45  4369.5 1620.36  4422.8 1619.69
  4444.8  1617.8  4552.8 1615.33  4630.3 1613.48  4680.4 1613.85  4696.7 1612.77
  4773.9  1612.2  4844.5 1611.73  4902.6 1610.03  4925.3 1608.02  4959.9 1605.35
  4997.8 1604.26  5063.9 1607.79    5124 1607.81  5217.8 1609.84  5252.9  1609.1
  5325.3 1609.26  5444.3 1611.41  5514.6 1614.08  5559.5 1613.65  5740.6 1618.33
  5759.1 1618.89  5793.2 1619.52  5906.2 1621.57  6031.7 1625.57  6266.8 1635.49
#Mann= 10 ,-1 , 0
  4196.9     .16       0  4552.8     .05       0  4773.9      .1       0
  4925.3     .07       0  5063.9     .16       0  5252.9     .05       0
  5559.5      .1       0  5740.6     .05       0  5759.1      .1       0
  5793.2     .16       0
#XS Ineff= 2 , 0
                         5218.37         1609.85
Permanent Ineff=
       F       F
Bank Sta=4925.3,5063.9
XS Rating Curve= 0 ,0
Exp/Cntr=0.3,0.1

Type RM Length L Ch R = 1 ,44      ,,,
XS GIS Cut Line= 4
     2821895.924    10103906.515     2822395.055    10103871.793
     2822544.795    10103739.414     2822477.521    10102945.143
#Sta/Elev= 30
       0 1613.63  108.49 1611.66  138.08 1611.73  256.43  1610.6   315.6 1608.76
  345.19  1608.7  355.06 1607.94  424.09  1605.8  453.68 1604.26  502.99 1600.01
  522.79 1600.13  542.58 1599.58  552.48 1598.51  572.28 1595.49  582.17 1595.75
  592.07 1597.12  601.97 1597.84  641.56 1599.56  681.15 1600.71  710.84 1600.59
  730.72 1602.52  780.42 1604.57  830.11  1605.2 1038.84  1609.6 1098.47 1611.77
 1148.17 1611.56 1247.56 1614.24 1356.89 1616.47 1386.71 1617.52 1505.98 1619.71
#Mann= 3 , 0 , 0
       0     .05       0  542.58     .03       0  641.56     .05       0
Bank Sta=542.58,641.56
XS Rating Curve= 0 ,0
Exp/Cntr=0.3,0.1

Chan Stop Cuts=-1
Use User Specified Reach Order=0
Composite Channel Slope=5