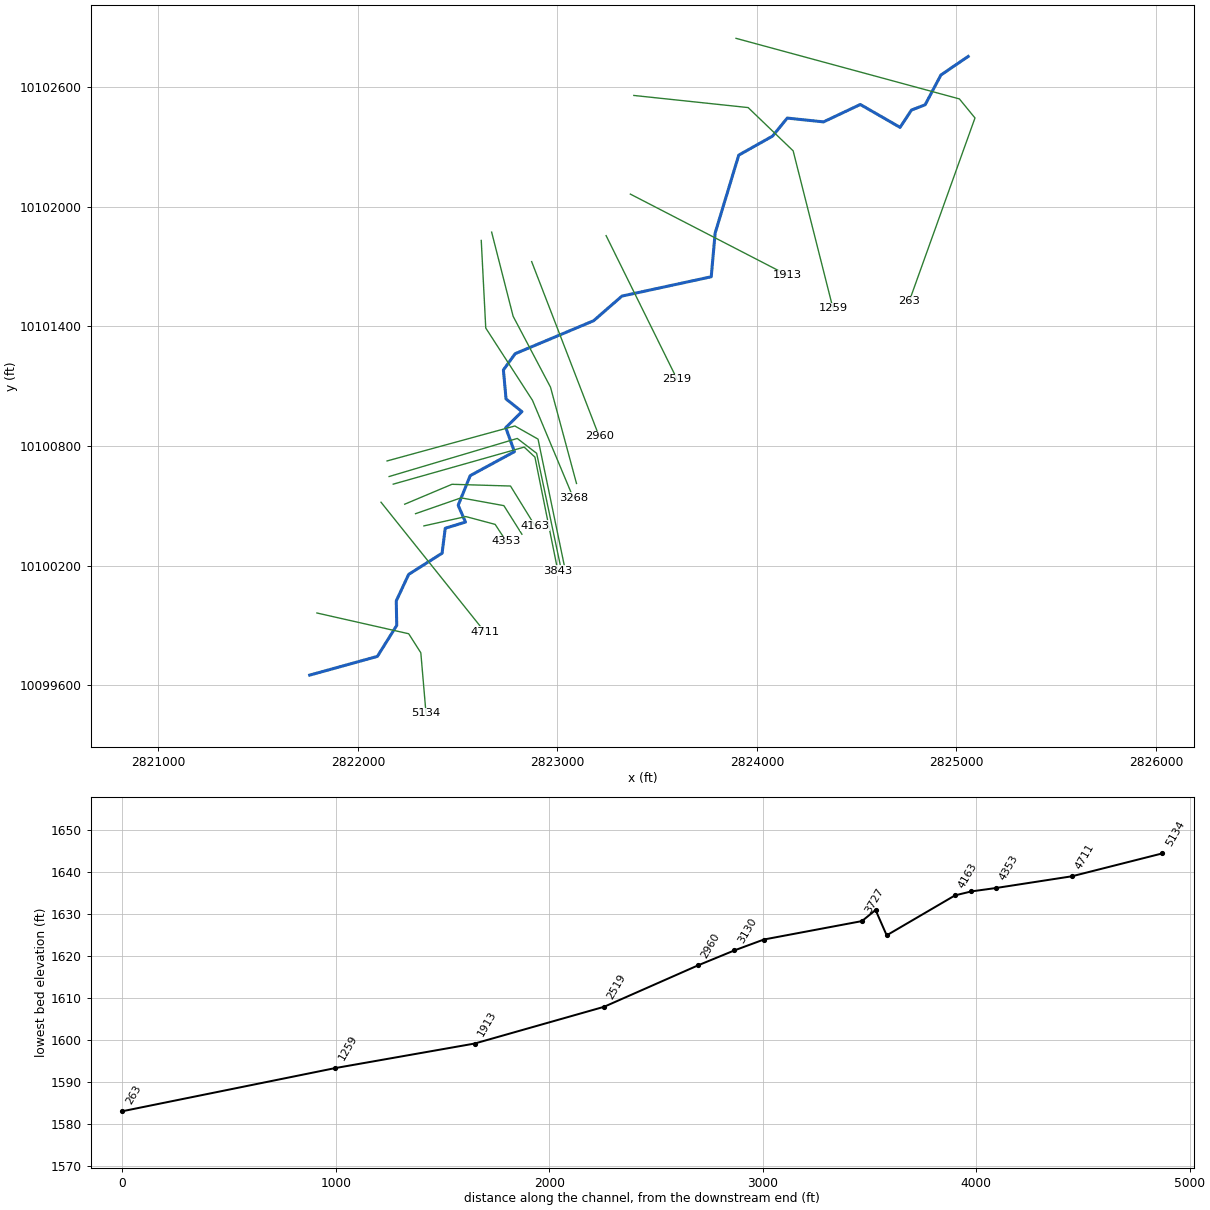
--- UNT076 IN NNOGR.prj (project) ---

Proj Title=UNT076 IN NNOGR Base Level Engineering
Current Plan=p01
Default Exp/Contr=0.3,0.1
English Units
Geom File=g01
Flow File=f01
Plan File=p01
BEGIN DESCRIPTION:
UNT076 IN NNOGR
END DESCRIPTION:

--- UNT076 IN NNOGR.p01 (plan) ---

Plan Title=Multiple Run
Short Identifier=Multiple
Geom File=g01
Flow File=f01
Subcritical Flow
K Sum by GR= 0
Std Step Tol= 0.01
Critical Tol= 0.01
Num of Std Step Trials= 20
Max Error Tol= 0.3
Flow Tol Ratio= 0.001
Split Flow NTrial= 30
Split Flow Tol= 0.02
Split Flow Ratio= 0.02
Log Output Level= 0
Friction Slope Method= 1
Unsteady Friction Slope Method= 2
Unsteady Bridges Friction Slope Method= 1
Parabolic Critical Depth
Global Vel Dist=  1 , 1 , 1
Global Log Level= 0
CheckData=True
Encroach Param= -1, 0, 0, 0
BEGIN DESCRIPTION:
Multiple Run
END DESCRIPTION:

--- UNT076 IN NNOGR.f01 (steady flow) ---

Flow Title=Multiple
Number of Profiles=7
Profile Names=10-year,25-year,50-year,1pct_min,100-year,1pct_plu,500-year
River Rch & RM= UNT076 IN NNOGR,Reach-1,5134
     381     520     634     568     768    1038    1127
Boundary for River Rch & Prof#=UNT076 IN NNOGR,Reach-1,1
Up Type=0
Dn Type=3
Dn Slope=0.005
Boundary for River Rch & Prof#=UNT076 IN NNOGR,Reach-1,2
Up Type=0
Dn Type=3
Dn Slope=0.005
Boundary for River Rch & Prof#=UNT076 IN NNOGR,Reach-1,3
Up Type=0
Dn Type=3
Dn Slope=0.005
Boundary for River Rch & Prof#=UNT076 IN NNOGR,Reach-1,4
Up Type=0
Dn Type=3
Dn Slope=0.005
Boundary for River Rch & Prof#=UNT076 IN NNOGR,Reach-1,5
Up Type=0
Dn Type=3
Dn Slope=0.005
Boundary for River Rch & Prof#=UNT076 IN NNOGR,Reach-1,6
Up Type=0
Dn Type=3
Dn Slope=0.005
Boundary for River Rch & Prof#=UNT076 IN NNOGR,Reach-1,7
Up Type=0
Dn Type=3
Dn Slope=0.005

--- UNT076 IN NNOGR.g01 (geometry) ---

Geom Title=Existing Conditions

River Reach=UNT076 IN NNOGR,Reach-1
Reach XY= 30
      2821757.89     10099651.00      2822097.07     10099744.84
      2822194.23     10099900.32      2822191.82     10100023.19
      2822253.99     10100156.21      2822421.47     10100262.35
      2822437.35     10100387.60      2822538.89     10100418.51
      2822502.18     10100502.85      2822562.60     10100651.45
      2822784.19     10100771.68      2822740.67     10100892.17
      2822821.78     10100972.36      2822742.13     10101035.98
      2822728.86     10101181.41      2822787.89     10101263.00
      2823181.04     10101428.25      2823323.19     10101551.97
      2823770.66     10101648.74      2823790.35     10101868.46
      2823908.56     10102258.84      2824078.32     10102354.39
      2824151.65     10102444.61      2824333.54     10102425.58
      2824517.96     10102512.80      2824717.23     10102398.06
      2824774.18     10102484.78      2824842.89     10102511.31
      2824921.71     10102660.40      2825058.47     10102753.73

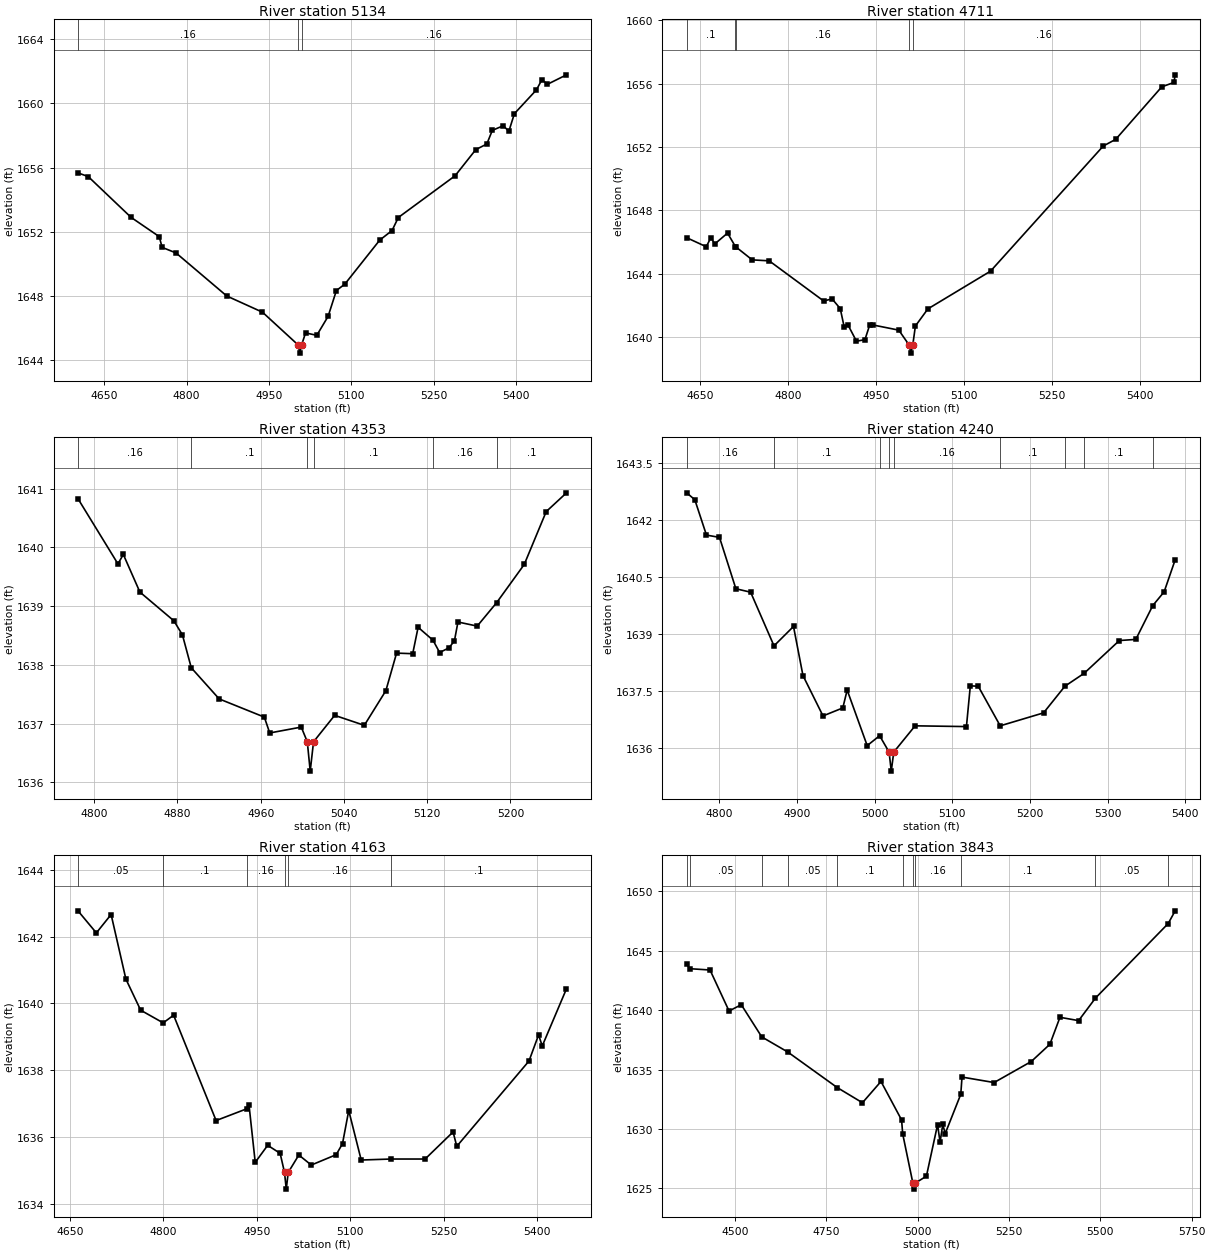
Type RM Length L Ch R = 1,5134,423,423,423
BEGIN DESCRIPTION:
Mapping XS 7335e547
END DESCRIPTION:
XS GIS Cut Line= 4
      2821794.16     10099962.61      2822254.21     10099858.45
      2822314.97     10099762.97      2822341.01     10099459.15
#Sta/Elev= 30
  4602.1 1655.67  4620.8 1655.44  4698.8 1652.90  4750.1 1651.70  4755.4 1651.03
  4780.8 1650.68  4873.1 1648.00  4938.2 1646.99  5003.4 1644.94  5006.1 1644.44
  5009.4 1644.94  5016.6 1645.70  5037.1 1645.55  5057.7 1646.73  5072.8 1648.34
  5088.2 1648.74  5151.7 1651.48  5174.2 1652.08  5185.6 1652.89  5289.0 1655.49
  5326.7 1657.12  5346.8 1657.47  5356.8 1658.32  5376.9 1658.61  5386.9 1658.26
  5397.0 1659.36  5437.1 1660.84  5447.2 1661.48  5457.2 1661.19  5491.9 1661.78
#Mann=3,-1,0
  4602.1    0.16       0  5003.4    0.07       0  5009.4    0.16       0
Bank Sta=5003.4,5009.4
Exp/Cntr=0.3,0.1

Type RM Length L Ch R = 1,4711,358,358,358
BEGIN DESCRIPTION:
UNT076 IN NNOGR 10.0
END DESCRIPTION:
XS GIS Cut Line= 2
      2822115.30     10100518.19      2822635.49     10099867.96
#Sta/Elev= 30
  4627.1 1646.28  4660.5 1645.71  4668.5 1646.29  4674.9 1645.88  4696.8 1646.57
  4710.2 1645.72  4710.6 1645.71  4738.9 1644.88  4767.8 1644.82  4860.6 1642.29
  4875.0 1642.42  4888.9 1641.81  4895.8 1640.62  4902.2 1640.77  4916.6 1639.75
  4931.0 1639.85  4939.0 1640.76  4945.4 1640.77  4988.7 1640.45  5006.5 1639.50
  5009.2 1639.00  5012.5 1639.50  5017.0 1640.71  5038.3 1641.79  5145.1 1644.17
  5337.2 1652.06  5358.4 1652.48  5436.9 1655.79  5457.7 1656.07  5459.8 1656.55
#Mann=5,-1,0
  4627.1     0.1       0  4710.2    0.05       0  4710.6    0.16       0
  5006.5    0.07       0  5012.5    0.16       0
Bank Sta=5006.5,5012.5
Exp/Cntr=0.3,0.1

Type RM Length L Ch R = 1,4353,113,113,113
BEGIN DESCRIPTION:
Mapping XS 3b84ae2d
END DESCRIPTION:
XS GIS Cut Line= 5
      2822330.44     10100399.37      2822539.89     10100446.04
      2822540.98     10100446.04      2822687.46     10100406.97
      2822743.66     10100321.59
#Sta/Elev= 30
  4784.4 1640.83  4822.8 1639.72  4828.0 1639.88  4843.9 1639.24  4876.6 1638.75
  4884.8 1638.51  4893.3 1637.95  4920.1 1637.42  4963.5 1637.11  4968.7 1636.84
  4999.0 1636.94  5004.8 1636.69  5007.6 1636.19  5010.8 1636.69  5031.1 1637.14
  5059.6 1636.97  5080.3 1637.56  5090.6 1638.20  5106.1 1638.19  5111.3 1638.64
  5125.6 1638.42  5132.0 1638.21  5141.0 1638.29  5146.2 1638.41  5149.6 1638.73
  5168.1 1638.66  5186.8 1639.06  5213.3 1639.71  5234.4 1640.61  5253.9 1640.93
#Mann=6,-1,0
  4784.4    0.16       0  4893.3     0.1       0  5004.8    0.07       0
  5010.8     0.1       0  5125.6    0.16       0  5186.8     0.1       0
Bank Sta=5004.8,5010.8
Exp/Cntr=0.3,0.1

Type RM Length L Ch R = 1,4240,77,77,77
BEGIN DESCRIPTION:
Mapping XS 176b91f3
END DESCRIPTION:
XS GIS Cut Line= 4
      2822288.56     10100460.60      2822516.39     10100540.02
      2822731.23     10100500.95      2822821.63     10100357.61
#Sta/Elev= 30
  4758.0 1642.71  4768.5 1642.53  4783.5 1641.60  4800.3 1641.54  4821.4 1640.19
  4840.4 1640.10  4870.5 1638.69  4895.6 1639.20  4907.8 1637.91  4933.6 1636.85
  4959.1 1637.06  4964.7 1637.53  4990.5 1636.07  5006.5 1636.33  5018.7 1635.90
  5021.5 1635.40  5024.7 1635.90  5052.2 1636.59  5118.3 1636.57  5123.3 1637.64
  5133.5 1637.63  5161.8 1636.59  5217.6 1636.93  5245.1 1637.63  5269.9 1637.97
  5315.2 1638.83  5336.4 1638.86  5358.3 1639.75  5372.9 1640.11  5387.1 1640.95
#Mann=9,-1,0
  4758.0    0.16       0  4870.5     0.1       0  5006.5    0.16       0
  5018.7    0.07       0  5024.7    0.16       0  5161.8     0.1       0
  5245.1    0.16       0  5269.9     0.1       0  5358.3    0.16       0
Bank Sta=5018.7,5024.7
Exp/Cntr=0.3,0.1

Type RM Length L Ch R = 1,4163,320,320,320
BEGIN DESCRIPTION:
Mapping XS ac22b7c1
END DESCRIPTION:
XS GIS Cut Line= 4
      2822234.15     10100508.21      2822471.11     10100608.03
      2822764.51     10100599.35      2822886.91     10100400.56
#Sta/Elev= 30
  4663.2 1642.77  4692.7 1642.11  4716.4 1642.66  4740.1 1640.73  4763.8 1639.80
  4800.0 1639.42  4816.7 1639.65  4884.9 1636.50  4933.9 1636.85  4937.7 1636.97
  4947.7 1635.25  4967.7 1635.76  4987.7 1635.52  4994.7 1634.95  4997.5 1634.45
  5000.7 1634.95  5017.7 1635.47  5037.7 1635.17  5077.7 1635.48  5087.8 1635.81
  5097.8 1636.80  5117.8 1635.32  5165.9 1635.35  5220.4 1635.35  5265.3 1636.16
  5271.2 1635.73  5387.1 1638.28  5402.5 1639.06  5408.4 1638.73  5447.3 1640.44
#Mann=6,-1,0
  4663.2    0.05       0  4800.0     0.1       0  4933.9    0.16       0
  4994.7    0.07       0  5000.7    0.16       0  5165.9     0.1       0
Bank Sta=4994.7,5000.7
Exp/Cntr=0.3,0.1

Type RM Length L Ch R = 1,3843,52,52,52
BEGIN DESCRIPTION:
Mapping XS 515a1f78
END DESCRIPTION:
XS GIS Cut Line= 4
      2822176.86     10100608.78      2822833.11     10100794.54
      2822886.93     10100744.19      2823001.52     10100174.74
#Sta/Elev= 30
  4368.3 1643.87  4377.0 1643.49  4432.3 1643.38  4484.3 1639.93  4517.8 1640.46
  4573.8 1637.75  4644.9 1636.48  4780.1 1633.49  4849.3 1632.21  4900.0 1634.00
  4956.4 1630.76  4959.4 1629.59  4987.3 1625.44  4990.1 1624.94  4993.3 1625.44
  5024.3 1626.03  5054.8 1630.36  5061.7 1628.89  5069.0 1630.38  5075.8 1629.62
  5118.3 1632.92  5121.7 1634.37  5209.5 1633.91  5311.2 1635.68  5362.1 1637.13
  5389.7 1639.40  5440.7 1639.12  5486.9 1641.02  5685.8 1647.29  5704.9 1648.36
#Mann=11,-1,0
  4368.3     0.1       0  4377.0    0.05       0  4573.8     0.1       0
  4644.9    0.05       0  4780.1     0.1       0  4959.4    0.16       0
  4987.3    0.07       0  4993.3    0.16       0  5118.3     0.1       0
  5486.9    0.05       0  5685.8     0.1       0
Bank Sta=4987.3,4993.3
Exp/Cntr=0.3,0.1

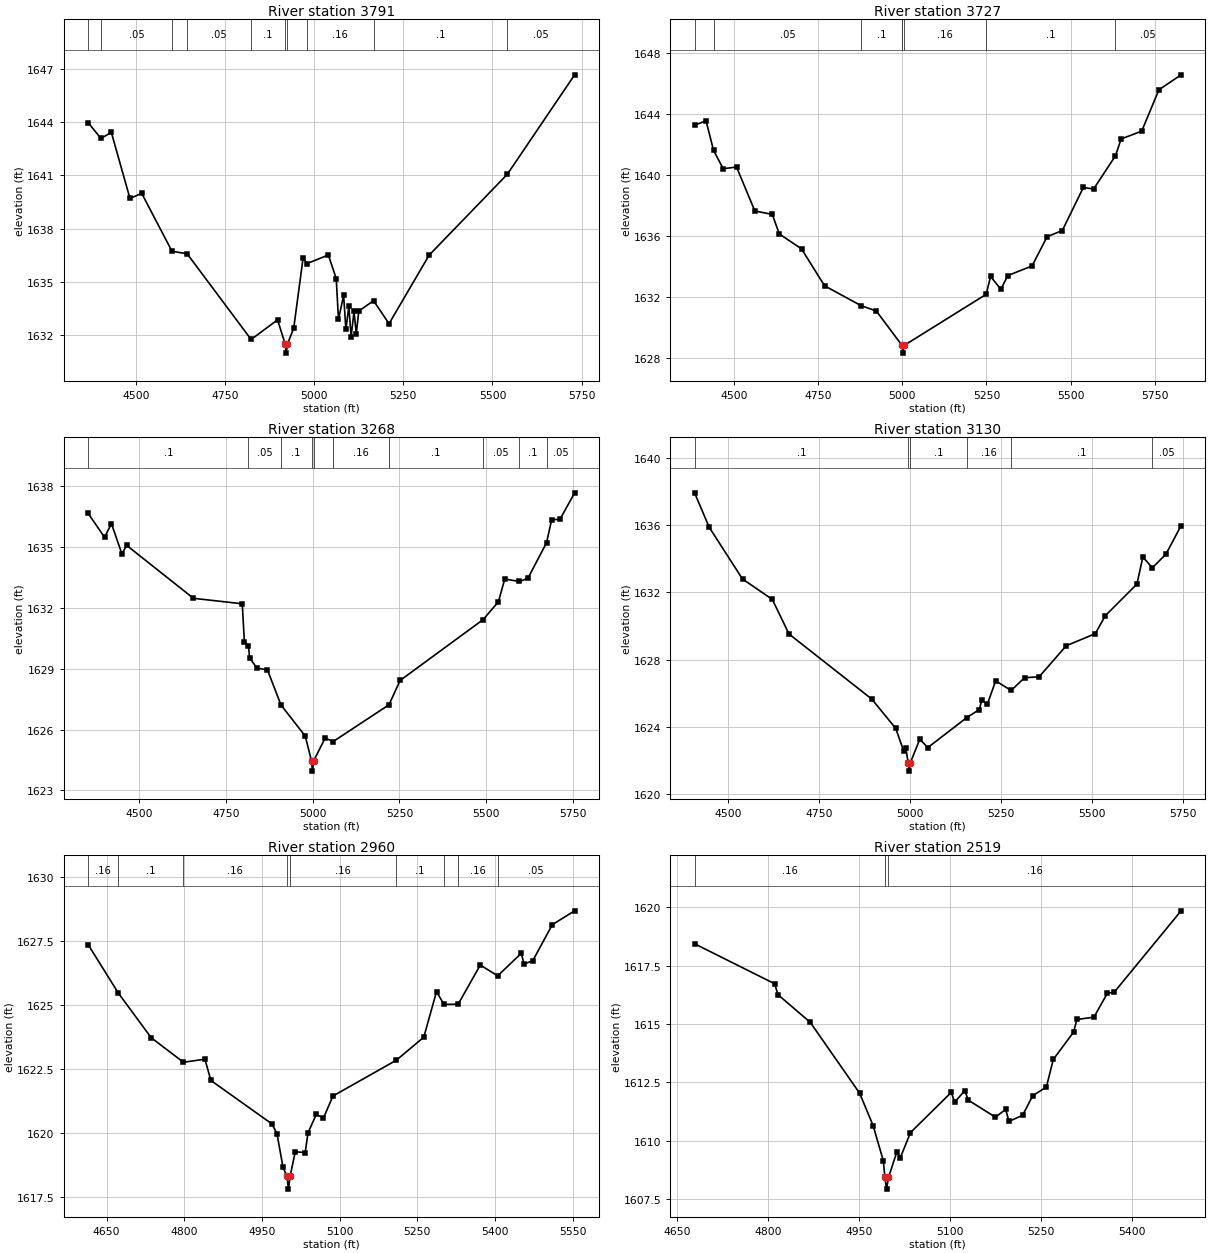
Type RM Length L Ch R = 1,3791,64,64,64
BEGIN DESCRIPTION:
UNT076 IN NNOGR 8.0
END DESCRIPTION:
XS GIS Cut Line= 4
      2822156.03     10100646.97      2822798.39     10100837.94
      2822895.61     10100763.29      2823013.57     10100204.73
#Sta/Elev= 30
  4366.6 1643.98  4402.6 1643.09  4431.7 1643.43  4483.9 1639.70  4516.8 1639.99
  4601.7 1636.72  4644.1 1636.58  4823.5 1631.74  4897.6 1632.85  4919.1 1631.47
  4921.8 1630.97  4925.1 1631.47  4942.9 1632.38  4969.2 1636.35  4979.4 1636.02
  5039.9 1636.51  5062.0 1635.18  5068.3 1632.88  5082.8 1634.23  5089.1 1632.31
  5097.4 1633.61  5103.7 1631.89  5111.9 1633.32  5118.2 1632.05  5125.1 1633.34
  5166.7 1633.93  5210.0 1632.63  5322.4 1636.50  5541.7 1641.07  5730.2 1646.68
#Mann=10,-1,0
  4366.6     0.1       0  4402.6    0.05       0  4601.7     0.1       0
  4644.1    0.05       0  4823.5     0.1       0  4919.1    0.07       0
  4925.1     0.1       0  4979.4    0.16       0  5166.7     0.1       0
  5541.7    0.05       0
Bank Sta=4919.1,4925.1
Exp/Cntr=0.3,0.1

Type RM Length L Ch R = 1,3727,459,459,459
BEGIN DESCRIPTION:
Mapping XS eab2380a
END DESCRIPTION:
XS GIS Cut Line= 4
      2822145.59     10100725.09      2822786.24     10100900.44
      2822902.56     10100834.47      2823034.50     10100199.06
#Sta/Elev= 30
  4382.0 1643.26  4416.1 1643.55  4438.4 1641.61  4467.1 1640.41  4506.8 1640.52
  4561.2 1637.64  4613.1 1637.42  4633.8 1636.14  4700.0 1635.16  4768.6 1632.74
  4877.2 1631.44  4922.5 1631.09  4998.8 1628.84  4998.9 1628.83  5001.6 1628.33
  5004.9 1628.83  5249.1 1632.18  5262.4 1633.35  5293.0 1632.51  5313.5 1633.41
  5385.6 1634.04  5430.6 1635.96  5475.6 1636.36  5538.2 1639.18  5568.8 1639.08
  5633.8 1641.26  5650.5 1642.36  5711.8 1642.87  5762.9 1645.58  5828.9 1646.56
#Mann=8,-1,0
  4382.0     0.1       0  4438.4    0.05       0  4877.2     0.1       0
  4998.8    0.16       0  4998.9    0.07       0  5004.9    0.16       0
  5249.1     0.1       0  5633.8    0.05       0
Bank Sta=4998.9,5004.9
Exp/Cntr=0.3,0.1

Type RM Length L Ch R = 1,3268,138,138,138
BEGIN DESCRIPTION:
Mapping XS 3824a38f
END DESCRIPTION:
XS GIS Cut Line= 4
      2822617.84     10101830.98      2822640.40     10101391.76
      2822874.78     10101028.92      2823079.65     10100539.31
#Sta/Elev= 30
  4352.5 1636.66  4399.8 1635.48  4419.8 1636.15  4449.9 1634.66  4463.6 1635.08
  4656.1 1632.47  4796.9 1632.20  4802.9 1630.34  4814.7 1630.13  4818.0 1629.53
  4839.2 1629.03  4869.5 1628.94  4908.5 1627.21  4978.4 1625.68  4996.5 1624.45
  4999.2 1623.95  5002.5 1624.45  5035.8 1625.58  5059.1 1625.41  5219.8 1627.22
  5251.9 1628.42  5491.2 1631.42  5535.3 1632.30  5553.6 1633.42  5595.9 1633.30
  5620.1 1633.45  5674.1 1635.21  5688.9 1636.35  5712.7 1636.36  5755.0 1637.67
#Mann=10,-1,0
  4352.5     0.1       0  4814.7    0.05       0  4908.5     0.1       0
  4996.5    0.07       0  5002.5     0.1       0  5059.1    0.16       0
  5219.8     0.1       0  5491.2    0.05       0  5595.9     0.1       0
  5674.1    0.05       0
Bank Sta=4996.5,5002.5
Exp/Cntr=0.3,0.1

Type RM Length L Ch R = 1,3130,170,170,170
BEGIN DESCRIPTION:
Mapping XS 662ef8d8
END DESCRIPTION:
XS GIS Cut Line= 4
      2822669.91     10101872.69      2822777.56     10101450.79
      2822965.06     10101094.89      2823095.27     10100612.24
#Sta/Elev= 30
  4408.4 1637.92  4448.6 1635.87  4540.2 1632.79  4622.0 1631.58  4668.0 1629.52
  4895.4 1625.65  4961.5 1623.90  4983.5 1622.54  4989.2 1622.72  4995.7 1621.86
  4998.5 1621.36  5001.7 1621.86  5027.6 1623.26  5049.6 1622.76  5157.1 1624.55
  5190.9 1625.02  5198.2 1625.58  5213.5 1625.35  5236.1 1626.73  5278.8 1626.16
  5315.7 1626.92  5355.6 1626.97  5430.2 1628.82  5510.1 1629.54  5537.3 1630.60
  5624.6 1632.49  5640.9 1634.10  5667.0 1633.46  5704.4 1634.27  5746.0 1635.97
#Mann=6,-1,0
  4408.4     0.1       0  4995.7    0.07       0  5001.7     0.1       0
  5157.1    0.16       0  5278.8     0.1       0  5667.0    0.05       0
Bank Sta=4995.7,5001.7
Exp/Cntr=0.3,0.1

Type RM Length L Ch R = 1,2960,441,441,441
BEGIN DESCRIPTION:
UNT076 IN NNOGR 6.0
END DESCRIPTION:
XS GIS Cut Line= 2
      2822870.52     10101724.79      2823208.94     10100848.36
#Sta/Elev= 30
  4614.3 1627.37  4672.8 1625.47  4736.1 1623.73  4798.4 1622.77  4839.9 1622.89
  4851.3 1622.06  4969.2 1620.36  4979.0 1619.98  4990.6 1618.67  4998.3 1618.31
  5001.1 1617.81  5004.3 1618.31  5014.3 1619.27  5033.5 1619.24  5038.9 1620.01
  5054.9 1620.73  5068.8 1620.59  5087.1 1621.45  5209.5 1622.85  5262.5 1623.75
  5287.1 1625.53  5301.6 1625.03  5328.9 1625.04  5371.6 1626.57  5405.3 1626.15
  5450.8 1627.03  5456.1 1626.61  5473.0 1626.74  5510.7 1628.15  5553.8 1628.69
#Mann=9,-1,0
  4614.3    0.16       0  4672.8     0.1       0  4798.4    0.16       0
  4998.3    0.07       0  5004.3    0.16       0  5209.5     0.1       0
  5301.6    0.05       0  5328.9    0.16       0  5405.3    0.05       0
Bank Sta=4998.3,5004.3
Exp/Cntr=0.3,0.1

Type RM Length L Ch R = 1,2519,606,606,606
BEGIN DESCRIPTION:
UNT076 IN NNOGR 5.0
END DESCRIPTION:
XS GIS Cut Line= 2
      2823243.78     10101855.00      2823599.69     10101134.51
#Sta/Elev= 30
  4678.3 1618.43  4810.5 1616.72  4816.1 1616.25  4869.3 1615.07  4950.8 1612.04
  4973.2 1610.65  4990.1 1609.14  4992.6 1608.43  4995.4 1607.93  4998.6 1608.43
  5012.5 1609.53  5018.1 1609.27  5034.9 1610.35  5102.3 1612.07  5107.9 1611.65
  5124.7 1612.15  5130.3 1611.74  5175.2 1611.01  5192.1 1611.34  5197.6 1610.83
  5220.1 1611.09  5236.9 1611.93  5259.4 1612.30  5270.8 1613.48  5304.3 1614.65
  5309.8 1615.19  5337.9 1615.29  5360.3 1616.32  5371.2 1616.35  5481.9 1619.84
#Mann=3,-1,0
  4678.3    0.16       0  4992.6    0.07       0  4998.6    0.16       0
Bank Sta=4992.6,4998.6
Exp/Cntr=0.3,0.1

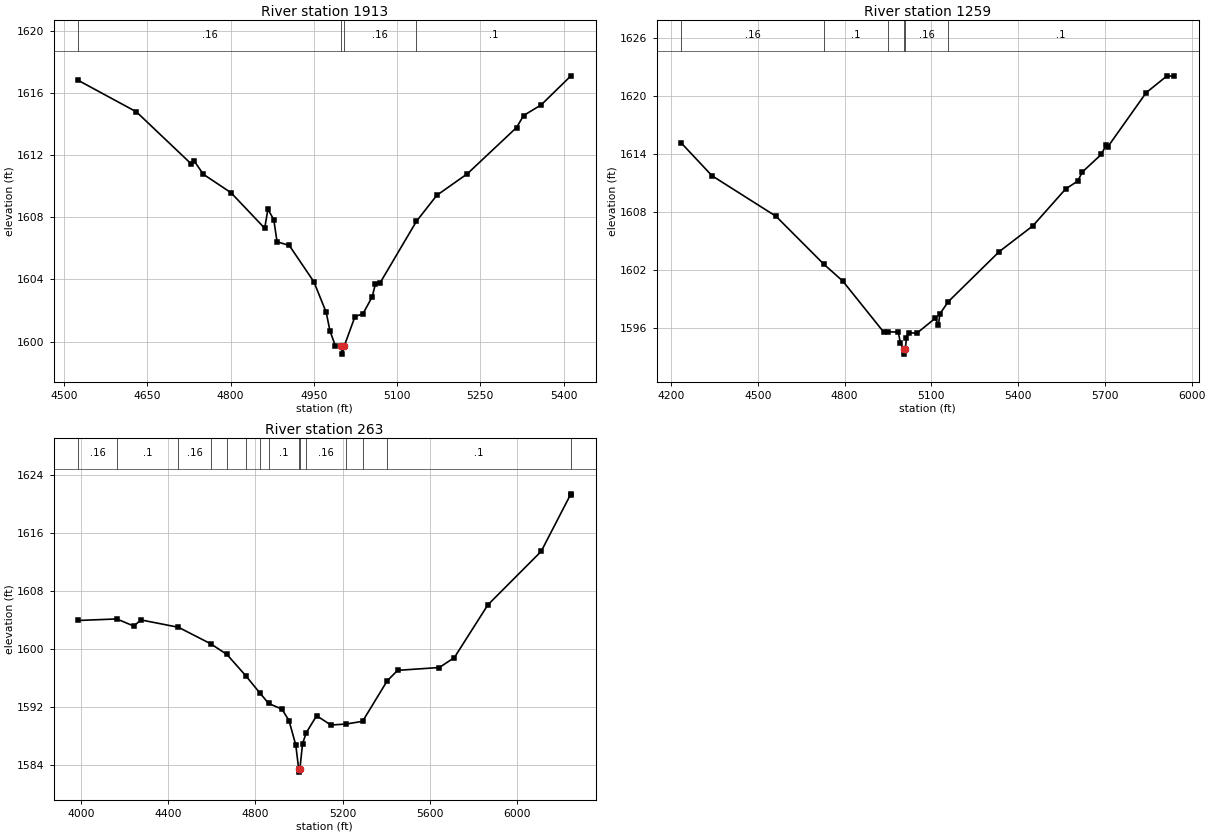
Type RM Length L Ch R = 1,1913,654,654,654
BEGIN DESCRIPTION:
UNT076 IN NNOGR 3.0
END DESCRIPTION:
XS GIS Cut Line= 2
      2823365.30     10102063.32      2824154.37     10101655.78
#Sta/Elev= 30
  4525.3 1616.83  4630.2 1614.80  4728.6 1611.46  4734.3 1611.64  4750.8 1610.78
  4800.7 1609.59  4861.5 1607.30  4867.2 1608.52  4877.8 1607.86  4883.7 1606.43
  4905.8 1606.19  4950.1 1603.85  4972.3 1601.88  4979.1 1600.69  4988.8 1599.72
  4998.6 1599.69  5001.3 1599.19  5004.6 1599.69  5024.1 1601.60  5038.7 1601.80
  5055.3 1602.89  5060.9 1603.70  5069.1 1603.76  5135.0 1607.75  5171.6 1609.42
  5226.7 1610.81  5315.4 1613.79  5328.0 1614.56  5359.8 1615.25  5413.4 1617.12
#Mann=4,-1,0
  4525.3    0.16       0  4998.6    0.07       0  5004.6    0.16       0
  5135.0     0.1       0
Bank Sta=4998.6,5004.6
Exp/Cntr=0.3,0.1

Type RM Length L Ch R = 1,1259,996,996,996
BEGIN DESCRIPTION:
UNT076 IN NNOGR 2.0
END DESCRIPTION:
XS GIS Cut Line= 4
      2823382.68     10102558.10      2823955.60     10102497.34
      2824181.29     10102280.33      2824380.95     10101490.40
#Sta/Elev= 30
  4235.1 1615.18  4341.5 1611.79  4562.7 1607.60  4727.8 1602.65  4793.5 1600.90
  4936.1 1595.58  4948.5 1595.65  4985.5 1595.62  4992.7 1594.51  5003.8 1593.84
  5006.6 1593.34  5009.8 1593.84  5013.8 1595.05  5021.0 1595.57  5049.3 1595.49
  5112.8 1597.04  5124.3 1596.38  5129.6 1597.52  5158.5 1598.77  5334.8 1603.95
  5450.9 1606.61  5564.3 1610.43  5605.6 1611.23  5622.0 1612.18  5688.1 1614.02
  5704.1 1614.99  5709.2 1614.75  5842.8 1620.39  5915.0 1622.13  5939.1 1622.07
#Mann=6,-1,0
  4235.1    0.16       0  4727.8     0.1       0  4948.5    0.16       0
  5003.8    0.07       0  5009.8    0.16       0  5158.5     0.1       0
Bank Sta=5003.8,5009.8
Exp/Cntr=0.3,0.1

Type RM Length L Ch R = 1,263,0,0,0
BEGIN DESCRIPTION:
UNT076 IN NNOGR 1.0
END DESCRIPTION:
XS GIS Cut Line= 4
      2823894.86     10102844.56      2825014.63     10102540.74
      2825092.75     10102445.26      2824762.89     10101525.12
#Sta/Elev= 30
  3986.5 1604.00  4163.4 1604.21  4241.0 1603.24  4275.6 1604.07  4446.7 1603.06
  4594.9 1600.78  4669.2 1599.31  4757.1 1596.32  4819.2 1594.03  4860.6 1592.55
  4921.4 1591.77  4953.9 1590.19  4984.9 1586.83  4998.1 1583.58  5000.8 1583.08
  5004.1 1583.58  5016.0 1587.00  5033.5 1588.54  5080.7 1590.86  5146.1 1589.58
  5215.2 1589.71  5291.5 1590.09  5404.7 1595.68  5452.3 1597.12  5643.6 1597.51
  5712.6 1598.88  5866.6 1606.16  6111.0 1613.53  6245.6 1621.36  6247.6 1621.47
#Mann=15,-1,0
  3986.5    0.16       0  4163.4     0.1       0  4446.7    0.16       0
  4594.9     0.1       0  4669.2    0.16       0  4757.1     0.1       0
  4819.2    0.16       0  4860.6     0.1       0  4998.1    0.07       0
  5004.1     0.1       0  5033.5    0.16       0  5215.2     0.1       0
  5291.5    0.16       0  5404.7     0.1       0  6245.6    0.16       0
Bank Sta=4998.1,5004.1
Exp/Cntr=0.3,0.1

Chan Stop Cuts=-1