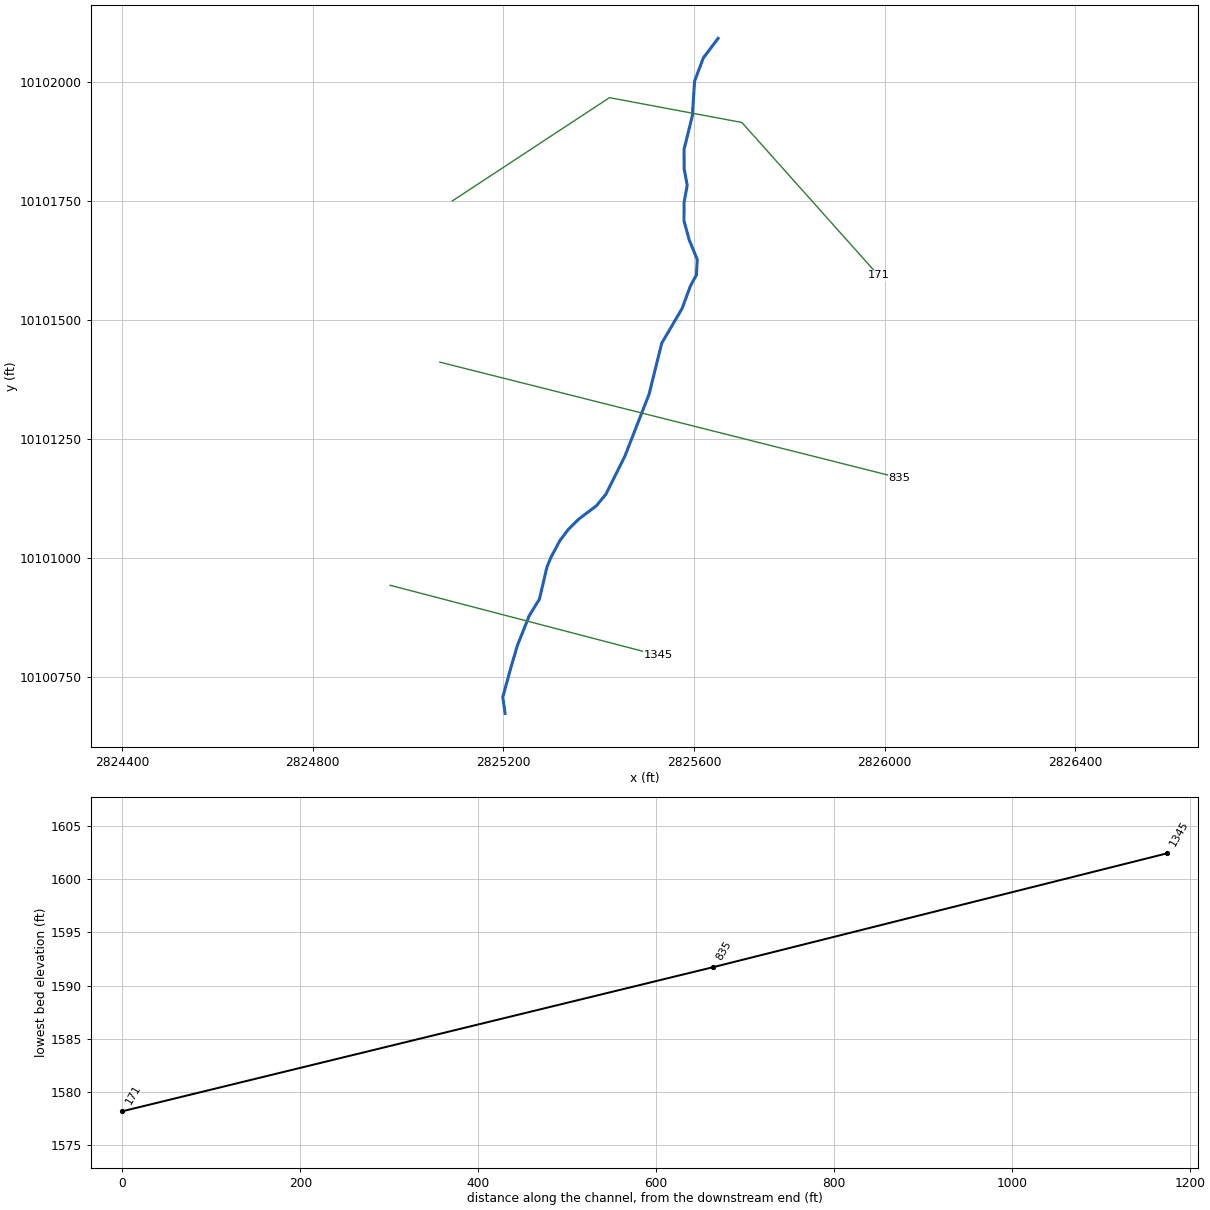
--- UNT077 IN NNOGR.prj (project) ---

Proj Title=UNT077 IN NNOGR Base Level Engineering
Current Plan=p01
Default Exp/Contr=0.3,0.1
English Units
Geom File=g01
Flow File=f01
Plan File=p01
BEGIN DESCRIPTION:
UNT077 IN NNOGR
END DESCRIPTION:

--- UNT077 IN NNOGR.p01 (plan) ---

Plan Title=Multiple Run
Short Identifier=Multiple
Geom File=g01
Flow File=f01
Subcritical Flow
K Sum by GR= 0
Std Step Tol= 0.01
Critical Tol= 0.01
Num of Std Step Trials= 20
Max Error Tol= 0.3
Flow Tol Ratio= 0.001
Split Flow NTrial= 30
Split Flow Tol= 0.02
Split Flow Ratio= 0.02
Log Output Level= 0
Friction Slope Method= 1
Unsteady Friction Slope Method= 2
Unsteady Bridges Friction Slope Method= 1
Parabolic Critical Depth
Global Vel Dist=  1 , 1 , 1
Global Log Level= 0
CheckData=True
Encroach Param= -1, 0, 0, 0
BEGIN DESCRIPTION:
Multiple Run
END DESCRIPTION:

--- UNT077 IN NNOGR.f01 (steady flow) ---

Flow Title=Multiple
Number of Profiles=7
Profile Names=10-year,25-year,50-year,1pct_min,100-year,1pct_plu,500-year
River Rch & RM= UNT077 IN NNOGR,Reach-1,1345
     197     259     308     269     364     492     508
Boundary for River Rch & Prof#=UNT077 IN NNOGR,Reach-1,1
Up Type=0
Dn Type=3
Dn Slope=0.005
Boundary for River Rch & Prof#=UNT077 IN NNOGR,Reach-1,2
Up Type=0
Dn Type=3
Dn Slope=0.005
Boundary for River Rch & Prof#=UNT077 IN NNOGR,Reach-1,3
Up Type=0
Dn Type=3
Dn Slope=0.005
Boundary for River Rch & Prof#=UNT077 IN NNOGR,Reach-1,4
Up Type=0
Dn Type=3
Dn Slope=0.005
Boundary for River Rch & Prof#=UNT077 IN NNOGR,Reach-1,5
Up Type=0
Dn Type=3
Dn Slope=0.005
Boundary for River Rch & Prof#=UNT077 IN NNOGR,Reach-1,6
Up Type=0
Dn Type=3
Dn Slope=0.005
Boundary for River Rch & Prof#=UNT077 IN NNOGR,Reach-1,7
Up Type=0
Dn Type=3
Dn Slope=0.005

--- UNT077 IN NNOGR.g01 (geometry) ---

Geom Title=Existing Conditions

River Reach=UNT077 IN NNOGR,Reach-1
Reach XY= 30
      2825203.56     10100674.47      2825198.76     10100709.05
      2825216.47     10100773.12      2825229.49     10100817.39
      2825254.04     10100879.18      2825275.64     10100914.51
      2825291.59     10100982.51      2825300.21     10101003.10
      2825318.58     10101037.34      2825335.95     10101060.48
      2825358.68     10101082.95      2825395.15     10101110.57
      2825415.17     10101135.01      2825455.08     10101215.13
      2825505.69     10101344.88      2825532.27     10101452.16
      2825575.06     10101525.16      2825592.44     10101572.22
      2825605.06     10101595.36      2825606.75     10101627.79
      2825589.87     10101669.25      2825578.97     10101709.04
      2825579.18     10101748.37      2825585.73     10101783.73
      2825579.30     10101818.11      2825579.13     10101859.34
      2825596.43     10101929.57      2825601.23     10102002.64
      2825619.48     10102051.19      2825650.58     10102092.46

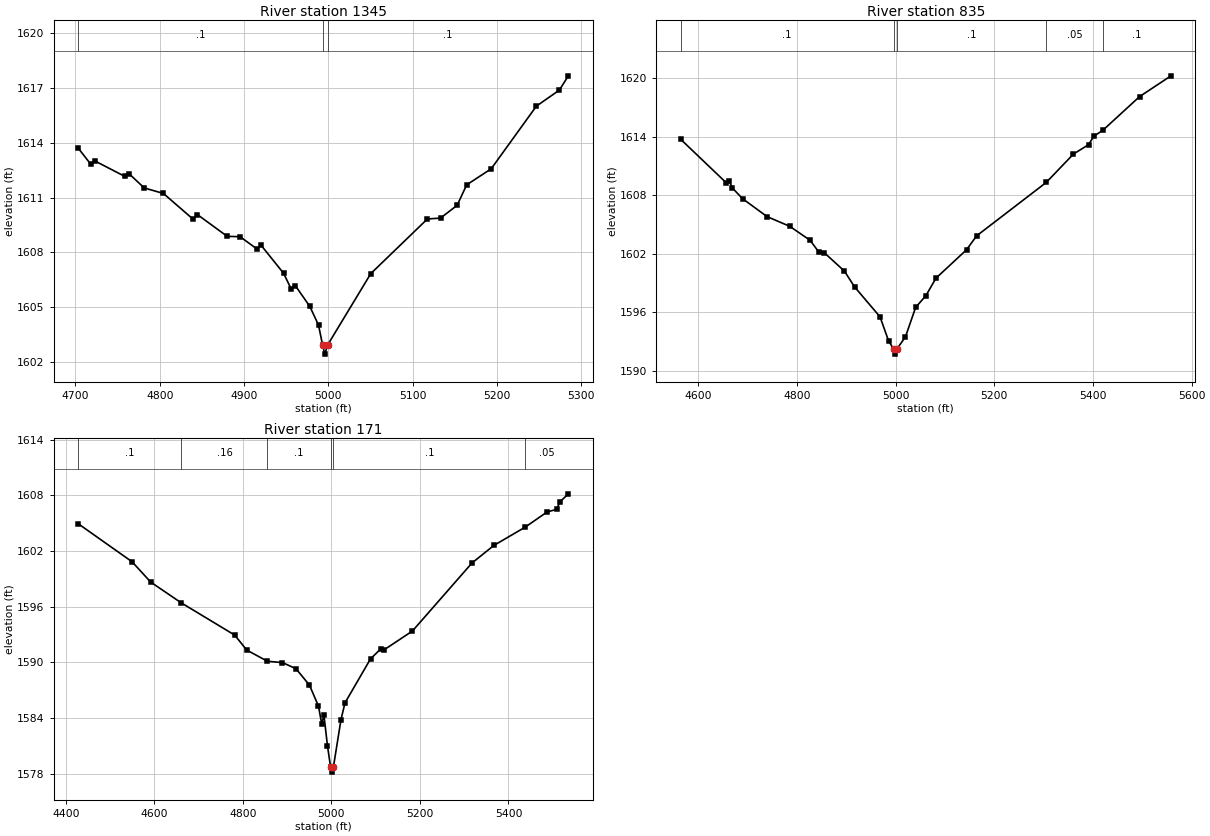
Type RM Length L Ch R = 1,1345,510,510,510
BEGIN DESCRIPTION:
UNT077 IN NNOGR 2.0
END DESCRIPTION:
XS GIS Cut Line= 2
      2824962.52     10100943.53      2825525.10     10100796.39
#Sta/Elev= 30
  4703.1 1613.72  4718.2 1612.83  4723.4 1613.00  4758.7 1612.16  4763.8 1612.30
  4781.6 1611.53  4804.3 1611.23  4839.5 1609.82  4844.7 1610.07  4880.0 1608.88
  4895.3 1608.86  4915.2 1608.19  4920.4 1608.38  4947.0 1606.85  4955.7 1606.01
  4960.8 1606.18  4978.0 1605.04  4988.3 1604.02  4993.1 1602.93  4995.8 1602.43
  4999.1 1602.93  5050.3 1606.84  5117.4 1609.83  5133.0 1609.88  5152.7 1610.58
  5164.0 1611.70  5193.1 1612.58  5246.7 1616.01  5274.0 1616.89  5284.6 1617.67
#Mann=3,-1,0
  4703.1     0.1       0  4993.1    0.07       0  4999.1     0.1       0
Bank Sta=4993.1,4999.1
Exp/Cntr=0.3,0.1

Type RM Length L Ch R = 1,835,664,664,664
BEGIN DESCRIPTION:
Mapping XS 144b60db
END DESCRIPTION:
XS GIS Cut Line= 2
      2825066.75     10101412.26      2826030.26     10101169.21
#Sta/Elev= 30
  4564.4 1613.74  4657.2 1609.26  4662.4 1609.50  4669.3 1608.74  4689.9 1607.65
  4739.4 1605.82  4785.6 1604.82  4826.7 1603.39  4844.6 1602.17  4854.9 1602.14
  4896.2 1600.24  4916.8 1598.62  4968.4 1595.55  4985.8 1593.08  4996.3 1592.23
  4999.1 1591.73  5002.3 1592.23  5020.0 1593.51  5040.6 1596.52  5061.2 1597.71
  5081.8 1599.51  5143.7 1602.42  5164.3 1603.85  5305.3 1609.32  5360.5 1612.23
  5391.2 1613.19  5401.6 1614.05  5420.0 1614.66  5494.4 1618.11  5558.1 1620.24
#Mann=5,-1,0
  4564.4     0.1       0  4996.3    0.07       0  5002.3     0.1       0
  5305.3    0.05       0  5420.0     0.1       0
Bank Sta=4996.3,5002.3
Exp/Cntr=0.3,0.1

Type RM Length L Ch R = 1,171,0,0,0
BEGIN DESCRIPTION:
UNT077 IN NNOGR 1.0
END DESCRIPTION:
XS GIS Cut Line= 4
      2825092.74     10101750.81      2825422.61     10101967.83
      2825700.39     10101915.74      2825986.82     10101594.59
#Sta/Elev= 30
  4427.5 1604.95  4549.6 1600.84  4591.7 1598.65  4660.9 1596.41  4781.5 1592.94
  4808.6 1591.33  4855.5 1590.12  4889.4 1589.98  4919.9 1589.32  4950.4 1587.55
  4970.7 1585.29  4978.0 1583.39  4983.1 1584.30  4991.1 1580.99  4998.3 1578.68
  5001.0 1578.18  5004.3 1578.68  5021.6 1583.84  5030.6 1585.64  5088.3 1590.38
  5112.0 1591.48  5119.5 1591.37  5183.0 1593.38  5317.6 1600.71  5367.0 1602.60
  5438.1 1604.58  5487.4 1606.21  5509.1 1606.49  5515.8 1607.27  5535.3 1608.16
#Mann=6,-1,0
  4427.5     0.1       0  4660.9    0.16       0  4855.5     0.1       0
  4998.3    0.07       0  5004.3     0.1       0  5438.1    0.05       0
Bank Sta=4998.3,5004.3
Exp/Cntr=0.3,0.1

Chan Stop Cuts=-1