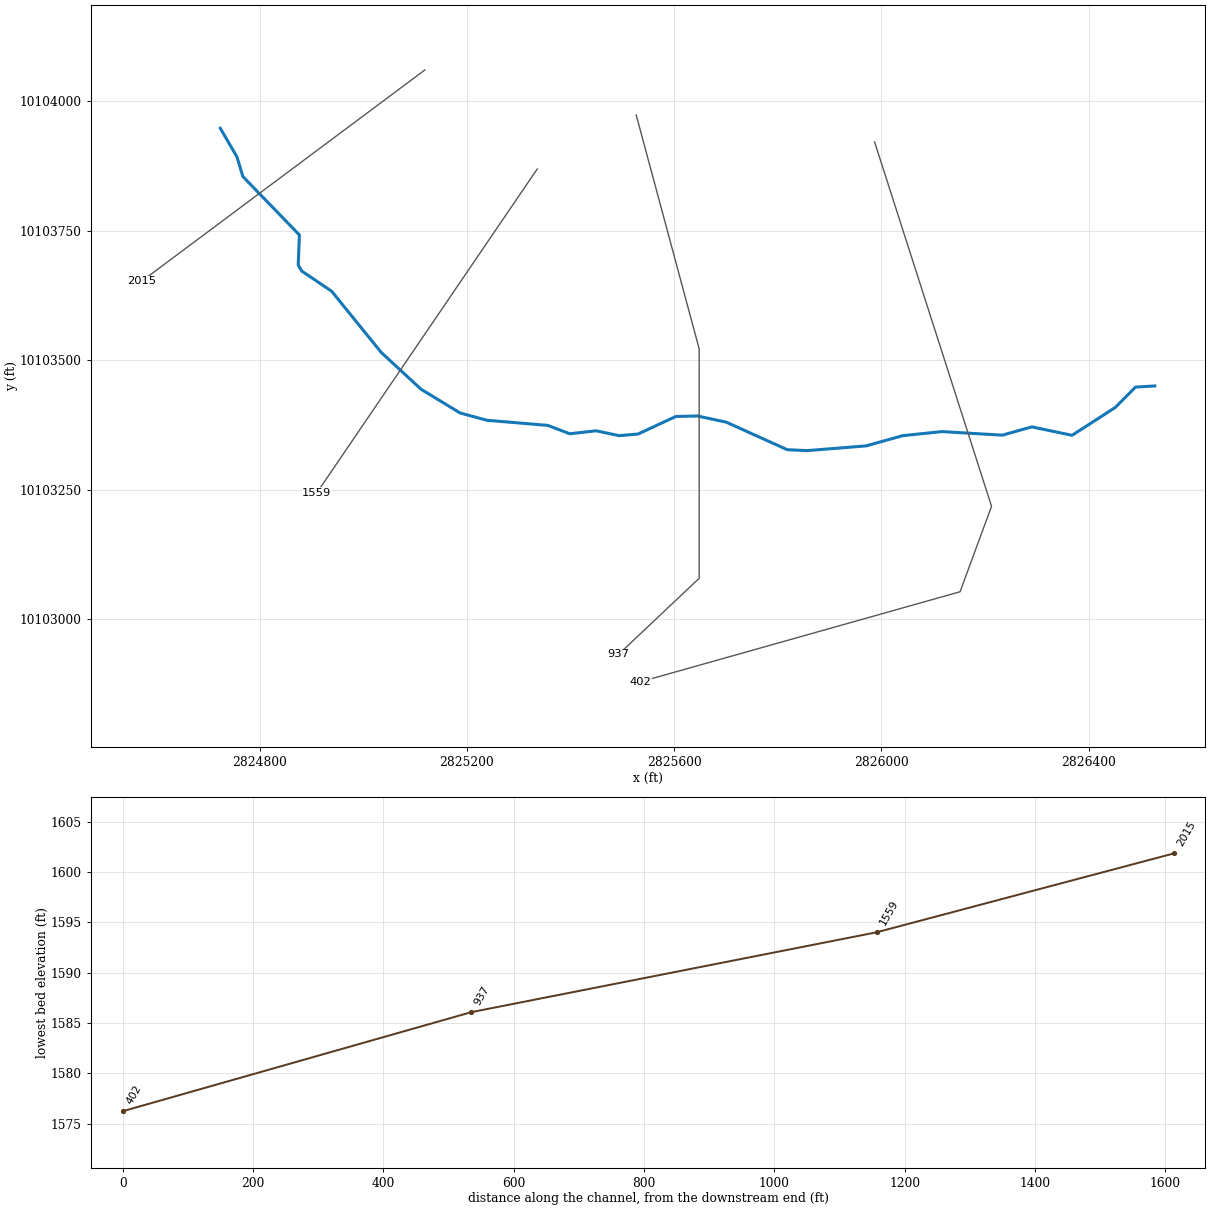
--- UNT078 IN NNOGR.prj (project) ---

Proj Title=UNT078 IN NNOGR Base Level Engineering
Current Plan=p01
Default Exp/Contr=0.3,0.1
English Units
Geom File=g01
Flow File=f01
Plan File=p01
BEGIN DESCRIPTION:
UNT078 IN NNOGR
END DESCRIPTION:

--- UNT078 IN NNOGR.p01 (plan) ---

Plan Title=Multiple Run
Short Identifier=Multiple
Geom File=g01
Flow File=f01
Subcritical Flow
K Sum by GR= 0
Std Step Tol= 0.01
Critical Tol= 0.01
Num of Std Step Trials= 20
Max Error Tol= 0.3
Flow Tol Ratio= 0.001
Split Flow NTrial= 30
Split Flow Tol= 0.02
Split Flow Ratio= 0.02
Log Output Level= 0
Friction Slope Method= 1
Unsteady Friction Slope Method= 2
Unsteady Bridges Friction Slope Method= 1
Parabolic Critical Depth
Global Vel Dist=  1 , 1 , 1
Global Log Level= 0
CheckData=True
Encroach Param= -1, 0, 0, 0
BEGIN DESCRIPTION:
Multiple Run
END DESCRIPTION:

--- UNT078 IN NNOGR.f01 (steady flow) ---

Flow Title=Multiple
Number of Profiles=7
Profile Names=10-year,25-year,50-year,1pct_min,100-year,1pct_plu,500-year
River Rch & RM= UNT078 IN NNOGR,Reach-1,2015
     155     199     234     201     272     368     370
Boundary for River Rch & Prof#=UNT078 IN NNOGR,Reach-1,1
Up Type=0
Dn Type=3
Dn Slope=0.005
Boundary for River Rch & Prof#=UNT078 IN NNOGR,Reach-1,2
Up Type=0
Dn Type=3
Dn Slope=0.005
Boundary for River Rch & Prof#=UNT078 IN NNOGR,Reach-1,3
Up Type=0
Dn Type=3
Dn Slope=0.005
Boundary for River Rch & Prof#=UNT078 IN NNOGR,Reach-1,4
Up Type=0
Dn Type=3
Dn Slope=0.005
Boundary for River Rch & Prof#=UNT078 IN NNOGR,Reach-1,5
Up Type=0
Dn Type=3
Dn Slope=0.005
Boundary for River Rch & Prof#=UNT078 IN NNOGR,Reach-1,6
Up Type=0
Dn Type=3
Dn Slope=0.005
Boundary for River Rch & Prof#=UNT078 IN NNOGR,Reach-1,7
Up Type=0
Dn Type=3
Dn Slope=0.005

--- UNT078 IN NNOGR.g01 (geometry) ---

Geom Title=Existing Conditions

River Reach=UNT078 IN NNOGR,Reach-1
Reach XY= 30
      2824724.16     10103947.31      2824756.29     10103892.19
      2824767.75     10103854.17      2824876.79     10103741.51
      2824874.52     10103683.34      2824881.29     10103671.88
      2824939.10     10103632.82      2825034.65     10103514.85
      2825111.50     10103443.76      2825187.02     10103397.92
      2825238.58     10103383.86      2825356.29     10103373.96
      2825398.48     10103357.82      2825449.52     10103363.55
      2825493.79     10103354.17      2825530.25     10103357.30
      2825603.17     10103391.15      2825644.83     10103392.19
      2825700.56     10103380.21      2825818.27     10103327.09
      2825856.41     10103325.28      2825970.35     10103334.38
      2826041.19     10103354.17      2826116.71     10103361.99
      2826233.55     10103355.16      2826290.28     10103371.13
      2826367.95     10103354.84      2826451.25     10103408.51
      2826490.34     10103447.89      2826527.54     10103450.10

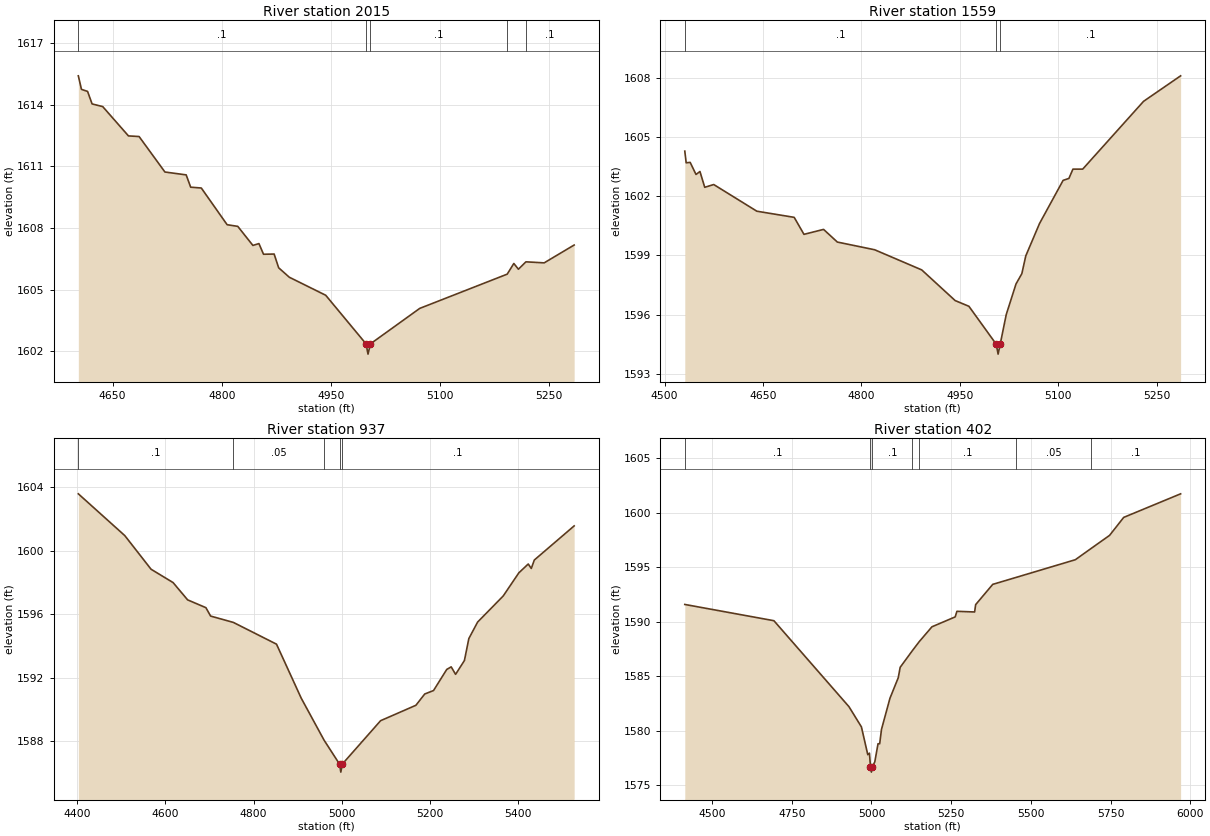
Type RM Length L Ch R = 1,2015,456,456,456
BEGIN DESCRIPTION:
UNT078 IN NNOGR 4.0
END DESCRIPTION:
XS GIS Cut Line= 2
      2825118.83     10104059.87      2824572.67     10103652.42
#Sta/Elev= 30
  4602.9 1615.42  4607.2 1614.76  4615.6 1614.66  4621.8 1614.05  4636.4 1613.92
  4671.8 1612.49  4686.4 1612.46  4721.9 1610.73  4751.1 1610.59  4757.3 1609.99
  4771.9 1609.95  4807.4 1608.16  4822.0 1608.08  4842.8 1607.15  4851.1 1607.24
  4857.4 1606.72  4872.0 1606.73  4878.2 1606.06  4892.8 1605.60  4942.9 1604.72
  4998.3 1602.35  5001.0 1601.85  5004.3 1602.35  5072.1 1604.08  5192.3 1605.75
  5201.4 1606.27  5207.7 1605.99  5218.0 1606.35  5243.1 1606.30  5284.3 1607.17
#Mann=5,-1,0
  4602.9     0.1       0  4998.3    0.07       0  5004.3     0.1       0
  5192.3    0.05       0  5218.0     0.1       0
Bank Sta=4998.3,5004.3
Exp/Cntr=0.3,0.1

Type RM Length L Ch R = 1,1559,622,622,622
BEGIN DESCRIPTION:
UNT078 IN NNOGR 3.0
END DESCRIPTION:
XS GIS Cut Line= 2
      2825335.80     10103868.86      2824910.45     10103243.86
#Sta/Elev= 30
  4530.7 1604.28  4532.8 1603.69  4538.9 1603.71  4547.8 1603.10  4553.8 1603.25
  4561.1 1602.45  4574.8 1602.59  4640.6 1601.24  4697.5 1600.93  4712.4 1600.07
  4742.3 1600.32  4763.3 1599.68  4820.2 1599.29  4892.0 1598.27  4942.9 1596.72
  4963.9 1596.43  5005.6 1594.51  5008.4 1594.01  5011.6 1594.51  5020.8 1596.01
  5035.7 1597.56  5044.6 1598.08  5050.6 1598.98  5071.6 1600.62  5107.5 1602.80
  5116.4 1602.90  5122.5 1603.37  5137.4 1603.37  5230.2 1606.80  5286.7 1608.09
#Mann=3,-1,0
  4530.7     0.1       0  5005.6    0.07       0  5011.6     0.1       0
Bank Sta=5005.6,5011.6
Exp/Cntr=0.3,0.1

Type RM Length L Ch R = 1,937,535,535,535
BEGIN DESCRIPTION:
UNT078 IN NNOGR 2.0
END DESCRIPTION:
XS GIS Cut Line= 4
      2825526.79     10103973.00      2825648.31     10103521.65
      2825648.31     10103078.94      2825492.75     10102932.03
#Sta/Elev= 30
  4402.7 1603.60  4508.0 1600.97  4567.6 1598.85  4617.5 1598.01  4650.5 1596.92
  4691.9 1596.43  4702.6 1595.90  4754.2 1595.50  4852.0 1594.13  4908.0 1590.73
  4959.7 1588.09  4995.0 1586.57  4997.8 1586.07  5001.0 1586.57  5088.0 1589.31
  5168.0 1590.28  5188.0 1590.99  5208.0 1591.21  5238.0 1592.54  5248.0 1592.70
  5258.0 1592.23  5278.0 1593.10  5288.0 1594.48  5307.9 1595.52  5366.1 1597.17
  5401.3 1598.62  5422.7 1599.18  5429.6 1598.90  5436.5 1599.43  5526.8 1601.58
#Mann=5,-1,0
  4402.7     0.1       0  4754.2    0.05       0  4959.7     0.1       0
  4995.0    0.07       0  5001.0     0.1       0
Bank Sta=4995,5001
Exp/Cntr=0.3,0.1

Type RM Length L Ch R = 1,402,0,0,0
BEGIN DESCRIPTION:
UNT078 IN NNOGR 1.0
END DESCRIPTION:
XS GIS Cut Line= 4
      2825986.85     10103920.95      2826212.54     10103217.83
      2826151.78     10103052.90      2825535.49     10102879.29
#Sta/Elev= 30
  4414.8 1591.59  4694.2 1590.10  4929.5 1582.22  4968.5 1580.37  4988.5 1577.82
  4993.7 1577.96  4997.0 1576.72  4999.8 1576.22  5003.0 1576.72  5010.5 1577.16
  5020.6 1578.82  5025.8 1578.82  5031.5 1580.14  5058.0 1582.99  5084.0 1584.87
  5090.1 1585.83  5128.2 1587.35  5149.5 1588.17  5189.6 1589.54  5262.6 1590.45
  5267.9 1590.96  5323.5 1590.90  5326.6 1591.57  5380.2 1593.43  5453.7 1594.07
  5639.2 1595.69  5688.6 1596.72  5746.5 1597.92  5790.9 1599.57  5969.3 1601.73
#Mann=7,-1,0
  4414.8     0.1       0  4997.0    0.07       0  5003.0     0.1       0
  5128.2    0.16       0  5149.5     0.1       0  5453.7    0.05       0
  5688.6     0.1       0
Bank Sta=4997,5003
Exp/Cntr=0.3,0.1

Chan Stop Cuts=-1