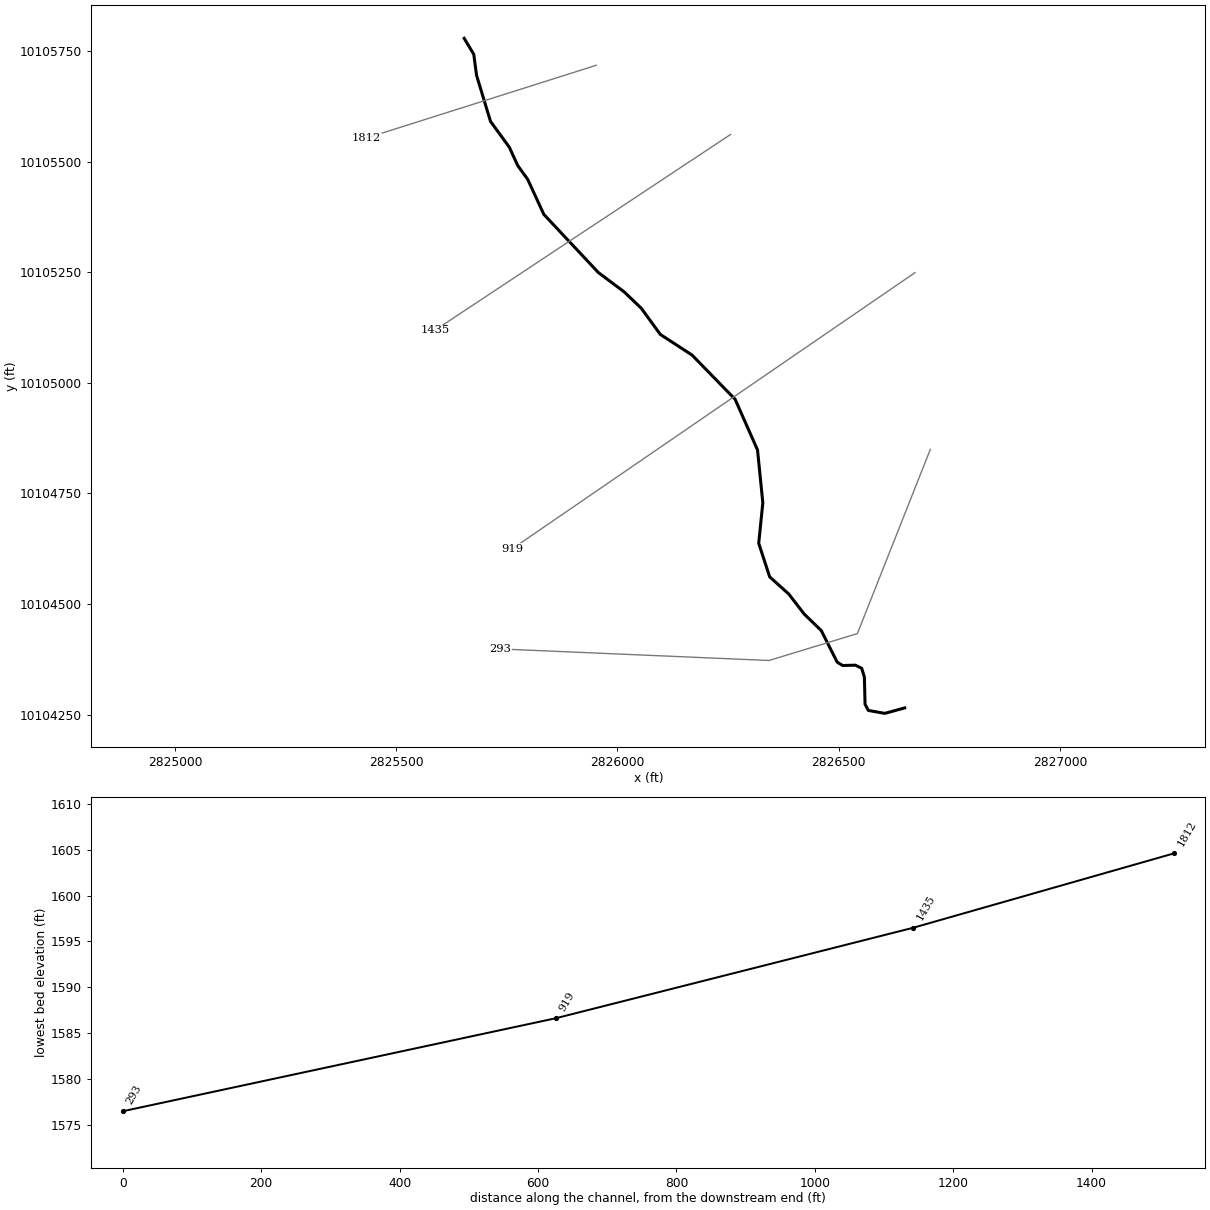
--- UNT079 IN NNOGR.prj (project) ---

Proj Title=UNT079 IN NNOGR Base Level Engineering
Current Plan=p01
Default Exp/Contr=0.3,0.1
English Units
Geom File=g01
Flow File=f01
Plan File=p01
BEGIN DESCRIPTION:
UNT079 IN NNOGR
END DESCRIPTION:

--- UNT079 IN NNOGR.p01 (plan) ---

Plan Title=Multiple Run
Short Identifier=Multiple
Geom File=g01
Flow File=f01
Subcritical Flow
K Sum by GR= 0
Std Step Tol= 0.01
Critical Tol= 0.01
Num of Std Step Trials= 20
Max Error Tol= 0.3
Flow Tol Ratio= 0.001
Split Flow NTrial= 30
Split Flow Tol= 0.02
Split Flow Ratio= 0.02
Log Output Level= 0
Friction Slope Method= 1
Unsteady Friction Slope Method= 2
Unsteady Bridges Friction Slope Method= 1
Parabolic Critical Depth
Global Vel Dist=  1 , 1 , 1
Global Log Level= 0
CheckData=True
Encroach Param= -1, 0, 0, 0
BEGIN DESCRIPTION:
Multiple Run
END DESCRIPTION:

--- UNT079 IN NNOGR.f01 (steady flow) ---

Flow Title=Multiple
Number of Profiles=7
Profile Names=10-year,25-year,50-year,1pct_min,100-year,1pct_plu,500-year
River Rch & RM= UNT079 IN NNOGR,Reach-1,1812
     221     293     350     308     416     563     588
Boundary for River Rch & Prof#=UNT079 IN NNOGR,Reach-1,1
Up Type=0
Dn Type=3
Dn Slope=0.005
Boundary for River Rch & Prof#=UNT079 IN NNOGR,Reach-1,2
Up Type=0
Dn Type=3
Dn Slope=0.005
Boundary for River Rch & Prof#=UNT079 IN NNOGR,Reach-1,3
Up Type=0
Dn Type=3
Dn Slope=0.005
Boundary for River Rch & Prof#=UNT079 IN NNOGR,Reach-1,4
Up Type=0
Dn Type=3
Dn Slope=0.005
Boundary for River Rch & Prof#=UNT079 IN NNOGR,Reach-1,5
Up Type=0
Dn Type=3
Dn Slope=0.005
Boundary for River Rch & Prof#=UNT079 IN NNOGR,Reach-1,6
Up Type=0
Dn Type=3
Dn Slope=0.005
Boundary for River Rch & Prof#=UNT079 IN NNOGR,Reach-1,7
Up Type=0
Dn Type=3
Dn Slope=0.005

--- UNT079 IN NNOGR.g01 (geometry) ---

Geom Title=Existing Conditions

River Reach=UNT079 IN NNOGR,Reach-1
Reach XY= 30
      2825653.47     10105778.73      2825675.15     10105742.75
      2825681.50     10105694.99      2825713.07     10105590.92
      2825755.60     10105532.54      2825774.37     10105491.46
      2825797.15     10105459.86      2825833.52     10105380.83
      2825956.95     10105249.16      2826015.06     10105205.72
      2826054.07     10105168.30      2826097.00     10105109.27
      2826168.52     10105062.86      2826266.02     10104962.72
      2826316.61     10104848.26      2826328.62     10104728.69
      2826319.33     10104637.29      2826344.13     10104561.34
      2826387.27     10104522.55      2826422.09     10104477.34
      2826460.73     10104439.96      2826496.66     10104368.59
      2826509.14     10104360.92      2826538.02     10104361.74
      2826552.10     10104354.60      2826558.19     10104334.93
      2826559.74     10104273.50      2826567.18     10104259.38
      2826604.30     10104252.75      2826649.29     10104265.07

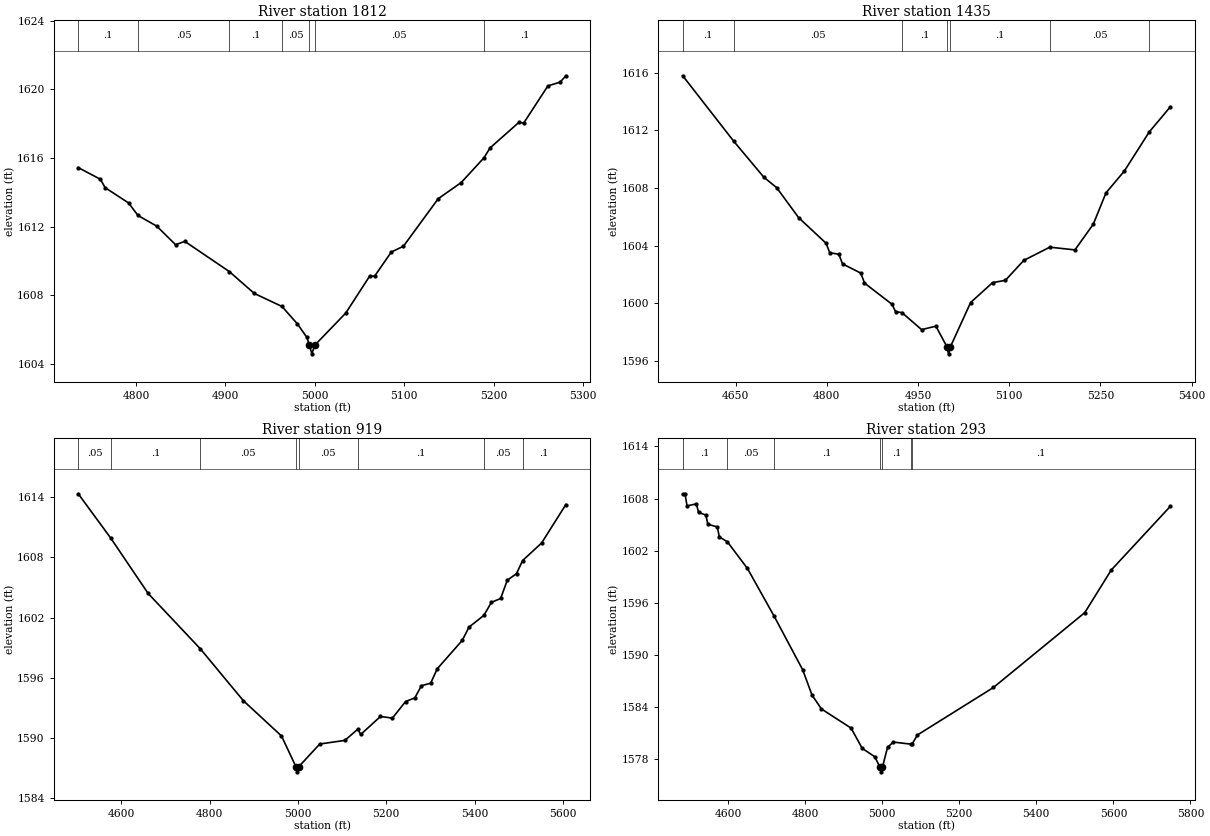
Type RM Length L Ch R = 1,1812,377,377,377
BEGIN DESCRIPTION:
UNT079 IN NNOGR 4.0
END DESCRIPTION:
XS GIS Cut Line= 2
      2825952.15     10105717.83      2825432.39     10105553.24
#Sta/Elev= 30
  4735.4 1615.44  4760.2 1614.76  4765.5 1614.27  4791.7 1613.38  4802.2 1612.65
  4823.2 1612.03  4844.2 1610.95  4854.6 1611.14  4904.4 1609.38  4932.2 1608.11
  4963.2 1607.35  4980.5 1606.33  4991.0 1605.55  4993.8 1605.09  4996.6 1604.59
  4999.8 1605.09  5034.4 1606.96  5061.4 1609.13  5066.7 1609.11  5085.4 1610.52
  5099.0 1610.86  5137.9 1613.63  5163.6 1614.57  5189.0 1616.01  5195.9 1616.59
  5228.2 1618.08  5233.4 1618.03  5260.5 1620.20  5274.2 1620.42  5280.6 1620.79
#Mann=7,-1,0
  4735.4     0.1       0  4802.2    0.05       0  4904.4     0.1       0
  4963.2    0.05       0  4993.8   0.035       0  4999.8    0.05       0
  5189.0     0.1       0
Bank Sta=4993.8,4999.8
Exp/Cntr=0.3,0.1

Type RM Length L Ch R = 1,1435,516,516,516
BEGIN DESCRIPTION:
UNT079 IN NNOGR 3.0
END DESCRIPTION:
XS GIS Cut Line= 2
      2826255.91     10105561.55      2825587.52     10105118.85
#Sta/Elev= 30
  4563.2 1615.78  4647.2 1611.23  4696.6 1608.74  4717.6 1608.02  4753.7 1605.94
  4798.9 1604.16  4804.9 1603.50  4819.9 1603.40  4825.9 1602.73  4856.0 1602.09
  4862.0 1601.40  4907.2 1599.93  4913.2 1599.41  4923.6 1599.35  4955.9 1598.17
  4979.4 1598.41  4997.4 1596.99  5000.2 1596.49  5003.4 1596.99  5036.5 1600.05
  5072.6 1601.43  5093.7 1601.59  5123.8 1602.97  5166.6 1603.89  5208.0 1603.70
  5238.1 1605.48  5259.1 1607.66  5289.2 1609.17  5330.1 1611.88  5364.9 1613.63
#Mann=7,-1,0
  4563.2     0.1       0  4647.2    0.05       0  4923.6     0.1       0
  4997.4    0.07       0  5003.4     0.1       0  5166.6    0.05       0
  5330.1     0.1       0
Bank Sta=4997.4,5003.4
Exp/Cntr=0.3,0.1

Type RM Length L Ch R = 1,919,626,626,626
BEGIN DESCRIPTION:
UNT079 IN NNOGR 2.0
END DESCRIPTION:
XS GIS Cut Line= 2
      2826672.63     10105249.09      2825762.30     10104624.86
#Sta/Elev= 30
  4502.7 1614.33  4576.4 1609.91  4660.9 1604.41  4779.2 1598.89  4876.1 1593.75
  4962.8 1590.22  4995.6 1587.15  4998.4 1586.65  5001.6 1587.15  5049.4 1589.42
  5106.2 1589.78  5135.6 1590.90  5142.1 1590.37  5186.8 1592.16  5213.9 1592.00
  5243.7 1593.65  5264.6 1594.01  5279.5 1595.22  5300.5 1595.48  5315.4 1596.91
  5372.2 1599.75  5387.1 1601.05  5421.0 1602.23  5437.9 1603.52  5458.9 1603.91
  5473.8 1605.72  5494.8 1606.38  5508.5 1607.68  5551.6 1609.43  5606.5 1613.26
#Mann=8,-1,0
  4502.7    0.05       0  4576.4     0.1       0  4779.2    0.05       0
  4995.6   0.035       0  5001.6    0.05       0  5135.6     0.1       0
  5421.0    0.05       0  5508.5     0.1       0
Bank Sta=4995.6,5001.6
Exp/Cntr=0.3,0.1

Type RM Length L Ch R = 1,293,0,0,0
BEGIN DESCRIPTION:
UNT079 IN NNOGR 1.0
END DESCRIPTION:
XS GIS Cut Line= 4
      2826707.32     10104849.75      2826542.40     10104433.10
      2826342.75     10104372.34      2825735.10     10104398.38
#Sta/Elev= 30
  4482.8 1608.49  4488.6 1608.55  4494.0 1607.15  4518.3 1607.39  4523.7 1606.41
  4542.6 1606.10  4548.0 1605.04  4572.4 1604.73  4577.7 1603.59  4598.8 1603.01
  4650.6 1599.95  4719.9 1594.45  4794.0 1588.27  4818.3 1585.35  4842.7 1583.76
  4919.5 1581.56  4948.3 1579.23  4981.2 1578.25  4994.7 1577.02  4997.5 1576.52
  5000.7 1577.02  5014.0 1579.33  5029.1 1579.95  5074.6 1579.71  5077.6 1579.71
  5091.8 1580.77  5288.9 1586.24  5525.8 1594.86  5594.3 1599.76  5747.8 1607.11
#Mann=7,-1,0
  4482.8     0.1       0  4598.8    0.05       0  4719.9     0.1       0
  4994.7    0.07       0  5000.7     0.1       0  5074.6    0.05       0
  5077.6     0.1       0
Bank Sta=4994.7,5000.7
Exp/Cntr=0.3,0.1

Chan Stop Cuts=-1