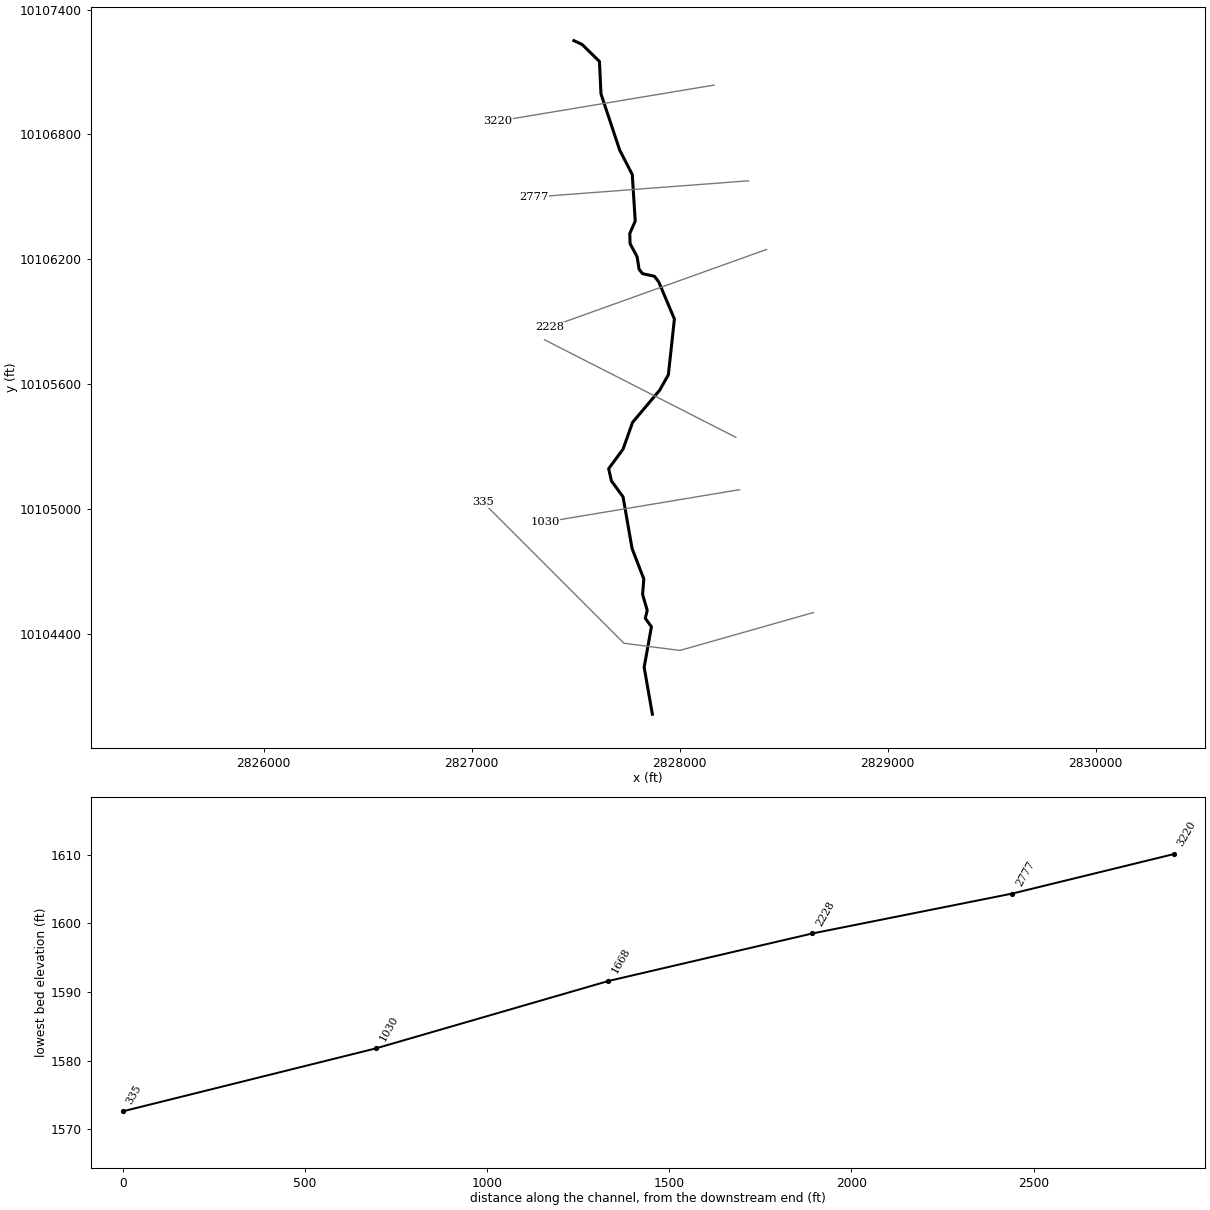
--- UNT080 IN NNOGR.prj (project) ---

Proj Title=UNT080 IN NNOGR Base Level Engineering
Current Plan=p01
Default Exp/Contr=0.3,0.1
English Units
Geom File=g01
Flow File=f01
Plan File=p01
BEGIN DESCRIPTION:
UNT080 IN NNOGR
END DESCRIPTION:

--- UNT080 IN NNOGR.p01 (plan) ---

Plan Title=Multiple Run
Short Identifier=Multiple
Geom File=g01
Flow File=f01
Subcritical Flow
K Sum by GR= 0
Std Step Tol= 0.01
Critical Tol= 0.01
Num of Std Step Trials= 20
Max Error Tol= 0.3
Flow Tol Ratio= 0.001
Split Flow NTrial= 30
Split Flow Tol= 0.02
Split Flow Ratio= 0.02
Log Output Level= 0
Friction Slope Method= 1
Unsteady Friction Slope Method= 2
Unsteady Bridges Friction Slope Method= 1
Parabolic Critical Depth
Global Vel Dist=  1 , 1 , 1
Global Log Level= 0
CheckData=True
Encroach Param= -1, 0, 0, 0
BEGIN DESCRIPTION:
Multiple Run
END DESCRIPTION:

--- UNT080 IN NNOGR.f01 (steady flow) ---

Flow Title=Multiple
Number of Profiles=7
Profile Names=10-year,25-year,50-year,1pct_min,100-year,1pct_plu,500-year
River Rch & RM= UNT080 IN NNOGR,Reach-1,3220
     487     678     838     759    1026    1388    1544
Boundary for River Rch & Prof#=UNT080 IN NNOGR,Reach-1,1
Up Type=0
Dn Type=3
Dn Slope=0.005
Boundary for River Rch & Prof#=UNT080 IN NNOGR,Reach-1,2
Up Type=0
Dn Type=3
Dn Slope=0.005
Boundary for River Rch & Prof#=UNT080 IN NNOGR,Reach-1,3
Up Type=0
Dn Type=3
Dn Slope=0.005
Boundary for River Rch & Prof#=UNT080 IN NNOGR,Reach-1,4
Up Type=0
Dn Type=3
Dn Slope=0.005
Boundary for River Rch & Prof#=UNT080 IN NNOGR,Reach-1,5
Up Type=0
Dn Type=3
Dn Slope=0.005
Boundary for River Rch & Prof#=UNT080 IN NNOGR,Reach-1,6
Up Type=0
Dn Type=3
Dn Slope=0.005
Boundary for River Rch & Prof#=UNT080 IN NNOGR,Reach-1,7
Up Type=0
Dn Type=3
Dn Slope=0.005

--- UNT080 IN NNOGR.g01 (geometry) ---

Geom Title=Existing Conditions

River Reach=UNT080 IN NNOGR,Reach-1
Reach XY= 30
      2827491.12     10107250.81      2827530.72     10107232.32
      2827614.03     10107150.72      2827621.34     10106994.94
      2827711.24     10106724.88      2827771.79     10106607.41
      2827785.99     10106383.65      2827759.78     10106323.77
      2827761.30     10106275.11      2827794.98     10106212.20
      2827804.59     10106152.10      2827820.74     10106131.19
      2827878.64     10106118.30      2827899.29     10106090.86
      2827974.39     10105913.11      2827945.36     10105645.12
      2827903.57     10105570.97      2827773.38     10105416.49
      2827727.42     10105287.50      2827658.20     10105193.64
      2827671.56     10105135.14      2827727.49     10105058.33
      2827770.91     10104809.74      2827827.34     10104663.92
      2827821.42     10104589.24      2827843.68     10104512.98
      2827834.37     10104474.85      2827863.82     10104434.20
      2827828.98     10104239.03      2827868.47     10104013.73

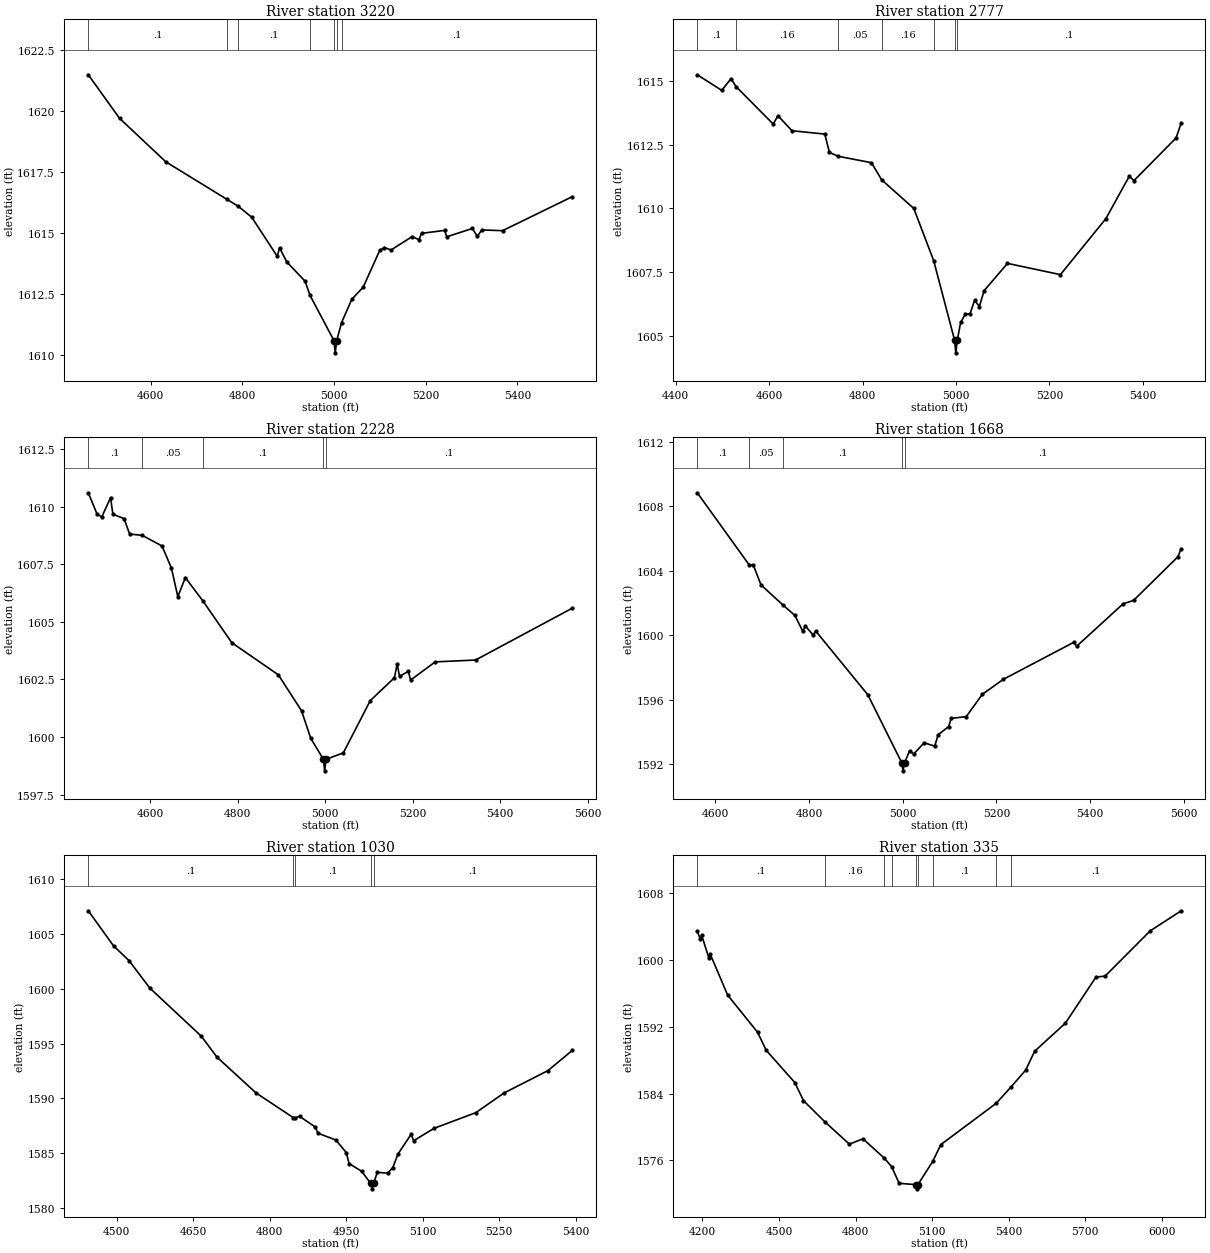
Type RM Length L Ch R = 1,3220,443,443,443
BEGIN DESCRIPTION:
UNT080 IN NNOGR 6.0
END DESCRIPTION:
XS GIS Cut Line= 2
      2828165.67     10107037.27      2827124.04     10106863.67
#Sta/Elev= 30
  4463.8 1621.48  4531.9 1619.70  4632.8 1617.92  4765.6 1616.39  4791.0 1616.10
  4820.4 1615.65  4876.1 1614.05  4881.2 1614.40  4896.9 1613.82  4937.0 1613.03
  4947.4 1612.46  4999.9 1610.60  5002.6 1610.10  5005.9 1610.60  5016.5 1611.34
  5038.8 1612.29  5063.7 1612.79  5099.7 1614.29  5109.8 1614.41  5124.5 1614.31
  5170.6 1614.86  5185.3 1614.73  5190.9 1614.99  5241.1 1615.11  5246.2 1614.85
  5301.9 1615.19  5312.6 1614.87  5322.7 1615.13  5367.8 1615.10  5519.8 1616.49
#Mann=7,-1,0
  4463.8     0.1       0  4765.6    0.05       0  4791.0     0.1       0
  4947.4    0.05       0  4999.9   0.035       0  5005.9    0.05       0
  5016.5     0.1       0
Bank Sta=4999.9,5005.9
Exp/Cntr=0.3,0.1

Type RM Length L Ch R = 1,2777,549,549,549
BEGIN DESCRIPTION:
UNT080 IN NNOGR 5.0
END DESCRIPTION:
XS GIS Cut Line= 2
      2828330.58     10106577.20      2827297.63     10106499.08
#Sta/Elev= 30
  4446.2 1615.23  4498.5 1614.62  4518.5 1615.08  4529.0 1614.77  4608.8 1613.30
  4618.8 1613.63  4648.9 1613.04  4719.1 1612.91  4729.1 1612.19  4748.1 1612.04
  4819.0 1611.79  4840.8 1611.12  4909.6 1610.00  4952.2 1607.96  4996.9 1604.85
  4999.6 1604.35  5002.9 1604.85  5009.9 1605.54  5019.9 1605.86  5030.0 1605.88
  5040.0 1606.41  5050.0 1606.16  5060.1 1606.78  5110.2 1607.85  5223.5 1607.41
  5320.8 1609.60  5370.9 1611.26  5381.0 1611.09  5471.2 1612.76  5482.1 1613.35
#Mann=7,-1,0
  4446.2     0.1       0  4529.0    0.16       0  4748.1    0.05       0
  4840.8    0.16       0  4952.2     0.1       0  4996.9    0.07       0
  5002.9     0.1       0
Bank Sta=4996.9,5002.9
Exp/Cntr=0.3,0.1

Type RM Length L Ch R = 1,2228,560,560,560
BEGIN DESCRIPTION:
UNT080 IN NNOGR 4.0
END DESCRIPTION:
XS GIS Cut Line= 2
      2828417.39     10106247.33      2827375.74     10105874.08
#Sta/Elev= 30
  4458.1 1610.60  4478.2 1609.67  4488.9 1609.55  4509.0 1610.39  4514.3 1609.67
  4539.8 1609.48  4552.6 1608.81  4581.6 1608.75  4626.7 1608.29  4648.2 1607.33
  4662.8 1606.09  4680.0 1606.92  4720.7 1605.89  4786.3 1604.09  4892.5 1602.70
  4945.6 1601.14  4966.8 1599.94  4995.7 1599.03  4998.5 1598.53  5001.7 1599.03
  5041.2 1599.31  5102.9 1601.58  5158.0 1602.57  5164.4 1603.17  5169.7 1602.63
  5189.8 1602.85  5195.1 1602.47  5251.4 1603.26  5343.6 1603.34  5564.6 1605.59
#Mann=5,-1,0
  4458.1     0.1       0  4581.6    0.05       0  4720.7     0.1       0
  4995.7    0.07       0  5001.7     0.1       0
Bank Sta=4995.7,5001.7
Exp/Cntr=0.3,0.1

Type RM Length L Ch R = 1,1668,638,638,638
BEGIN DESCRIPTION:
UNT080 IN NNOGR 3.0
END DESCRIPTION:
XS GIS Cut Line= 2
      2828269.86     10105344.55      2827349.69     10105813.32
#Sta/Elev= 30
  4561.5 1608.83  4672.0 1604.37  4680.9 1604.36  4697.5 1603.12  4744.8 1601.86
  4769.8 1601.23  4786.5 1600.25  4792.1 1600.57  4808.7 1600.02  4814.3 1600.26
  4925.5 1596.31  4997.8 1592.10  5000.5 1591.60  5003.8 1592.10  5014.5 1592.84
  5023.2 1592.64  5045.6 1593.34  5068.1 1593.13  5075.6 1593.84  5097.8 1594.34
  5103.4 1594.85  5135.4 1594.96  5170.1 1596.35  5214.6 1597.27  5364.6 1599.56
  5371.1 1599.32  5470.2 1601.95  5492.5 1602.16  5587.0 1604.86  5594.2 1605.37
#Mann=5,-1,0
  4561.5     0.1       0  4672.0    0.05       0  4744.8     0.1       0
  4997.8    0.07       0  5003.8     0.1       0
Bank Sta=4997.8,5003.8
Exp/Cntr=0.3,0.1

Type RM Length L Ch R = 1,1030,695,695,695
BEGIN DESCRIPTION:
UNT080 IN NNOGR 2.0
END DESCRIPTION:
XS GIS Cut Line= 2
      2828287.16     10105092.82      2827351.57     10104936.89
#Sta/Elev= 30
  4444.5 1607.08  4493.9 1603.89  4524.3 1602.55  4564.8 1600.06  4666.2 1595.66
  4696.6 1593.77  4773.1 1590.51  4845.9 1588.27  4850.5 1588.25  4858.8 1588.37
  4889.2 1587.41  4894.7 1586.84  4929.8 1586.22  4950.1 1585.08  4955.6 1584.08
  4980.5 1583.37  4997.8 1582.28  5000.5 1581.78  5003.8 1582.28  5010.9 1583.28
  5031.2 1583.21  5041.3 1583.71  5051.5 1584.95  5077.2 1586.74  5082.3 1586.16
  5122.4 1587.29  5204.0 1588.71  5259.7 1590.51  5345.5 1592.54  5393.0 1594.37
#Mann=5,-1,0
  4444.5     0.1       0  4845.9    0.16       0  4850.5     0.1       0
  4997.8    0.07       0  5003.8     0.1       0
Bank Sta=4997.8,5003.8
Exp/Cntr=0.3,0.1

Type RM Length L Ch R = 1,335,0,0,0
BEGIN DESCRIPTION:
UNT080 IN NNOGR 1.0
END DESCRIPTION:
XS GIS Cut Line= 4
      2828643.11     10104502.55      2828000.74     10104320.26
      2827731.64     10104354.98      2827054.56     10105032.06
#Sta/Elev= 30
  4179.7 1603.42  4191.7 1602.49  4196.9 1602.96  4225.6 1600.18  4230.8 1600.67
  4298.6 1595.80  4415.9 1591.35  4449.8 1589.19  4562.0 1585.32  4595.9 1583.16
  4680.5 1580.60  4775.8 1577.95  4829.0 1578.59  4912.4 1576.28  4941.6 1575.25
  4970.7 1573.26  5038.3 1573.10  5041.1 1572.60  5044.3 1573.10  5102.6 1575.90
  5134.3 1577.90  5351.6 1582.85  5410.5 1584.84  5466.6 1586.81  5502.0 1589.08
  5622.2 1592.43  5742.4 1597.96  5777.7 1598.06  5954.5 1603.48  6076.3 1605.89
#Mann=9,-1,0
  4179.7     0.1       0  4680.5    0.16       0  4912.4     0.1       0
  4941.6    0.16       0  5038.3    0.07       0  5044.3    0.16       0
  5102.6     0.1       0  5351.6    0.05       0  5410.5     0.1       0
Bank Sta=5038.3,5044.3
Exp/Cntr=0.3,0.1

Chan Stop Cuts=-1