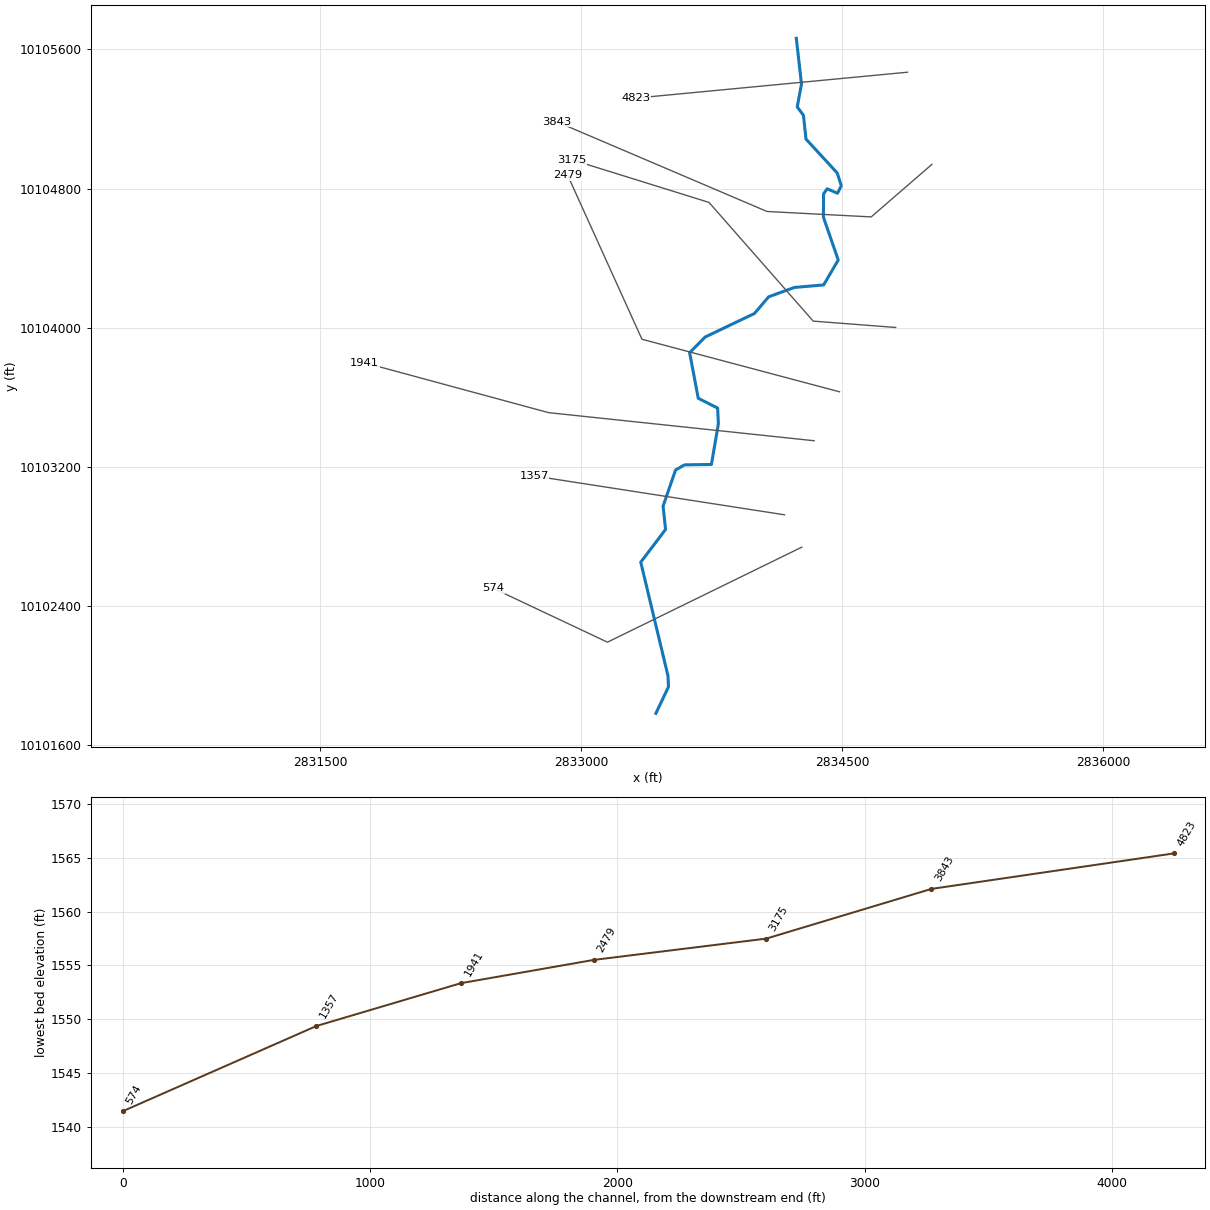
--- UNT081 IN NNOGR.prj (project) ---

Proj Title=UNT081 IN NNOGR Base Level Engineering
Current Plan=p01
Default Exp/Contr=0.3,0.1
English Units
Geom File=g01
Flow File=f01
Plan File=p01
BEGIN DESCRIPTION:
UNT081 IN NNOGR
END DESCRIPTION:

--- UNT081 IN NNOGR.p01 (plan) ---

Plan Title=Multiple Run
Short Identifier=Multiple
Geom File=g01
Flow File=f01
Subcritical Flow
K Sum by GR= 0
Std Step Tol= 0.01
Critical Tol= 0.01
Num of Std Step Trials= 20
Max Error Tol= 0.3
Flow Tol Ratio= 0.001
Split Flow NTrial= 30
Split Flow Tol= 0.02
Split Flow Ratio= 0.02
Log Output Level= 0
Friction Slope Method= 1
Unsteady Friction Slope Method= 2
Unsteady Bridges Friction Slope Method= 1
Parabolic Critical Depth
Global Vel Dist=  1 , 1 , 1
Global Log Level= 0
CheckData=True
Encroach Param= -1, 0, 0, 0
BEGIN DESCRIPTION:
Multiple Run
END DESCRIPTION:

--- UNT081 IN NNOGR.f01 (steady flow) ---

Flow Title=Multiple
Number of Profiles=7
Profile Names=10-year,25-year,50-year,1pct_min,100-year,1pct_plu,500-year
River Rch & RM= UNT081 IN NNOGR,Reach-1,4823
     560     782     967     875    1183    1600    1778
River Rch & RM= UNT081 IN NNOGR,Reach-1,3843
     669     940    1168    1061    1435    1941    2175
Boundary for River Rch & Prof#=UNT081 IN NNOGR,Reach-1,1
Up Type=0
Dn Type=3
Dn Slope=0.005
Boundary for River Rch & Prof#=UNT081 IN NNOGR,Reach-1,2
Up Type=0
Dn Type=3
Dn Slope=0.005
Boundary for River Rch & Prof#=UNT081 IN NNOGR,Reach-1,3
Up Type=0
Dn Type=3
Dn Slope=0.005
Boundary for River Rch & Prof#=UNT081 IN NNOGR,Reach-1,4
Up Type=0
Dn Type=3
Dn Slope=0.005
Boundary for River Rch & Prof#=UNT081 IN NNOGR,Reach-1,5
Up Type=0
Dn Type=3
Dn Slope=0.005
Boundary for River Rch & Prof#=UNT081 IN NNOGR,Reach-1,6
Up Type=0
Dn Type=3
Dn Slope=0.005
Boundary for River Rch & Prof#=UNT081 IN NNOGR,Reach-1,7
Up Type=0
Dn Type=3
Dn Slope=0.005

--- UNT081 IN NNOGR.g01 (geometry) ---

Geom Title=Existing Conditions

River Reach=UNT081 IN NNOGR,Reach-1
Reach XY= 30
      2834235.71     10105663.68      2834265.33     10105401.30
      2834240.98     10105269.26      2834276.53     10105221.61
      2834291.33     10105084.80      2834470.65     10104889.83
      2834494.25     10104816.41      2834472.37     10104772.92
      2834413.18     10104798.87      2834392.19     10104769.69
      2834391.38     10104635.68      2834476.72     10104389.52
      2834392.68     10104246.35      2834224.34     10104231.80
      2834076.79     10104178.13      2833994.79     10104082.00
      2833711.76     10103946.96      2833622.57     10103856.60
      2833671.93     10103594.95      2833783.35     10103538.40
      2833787.79     10103448.43      2833747.65     10103214.32
      2833593.75     10103212.25      2833541.62     10103182.64
      2833469.93     10102974.97      2833484.20     10102840.83
      2833341.56     10102652.83      2833498.01     10101999.47
      2833500.98     10101936.36      2833428.47     10101783.73

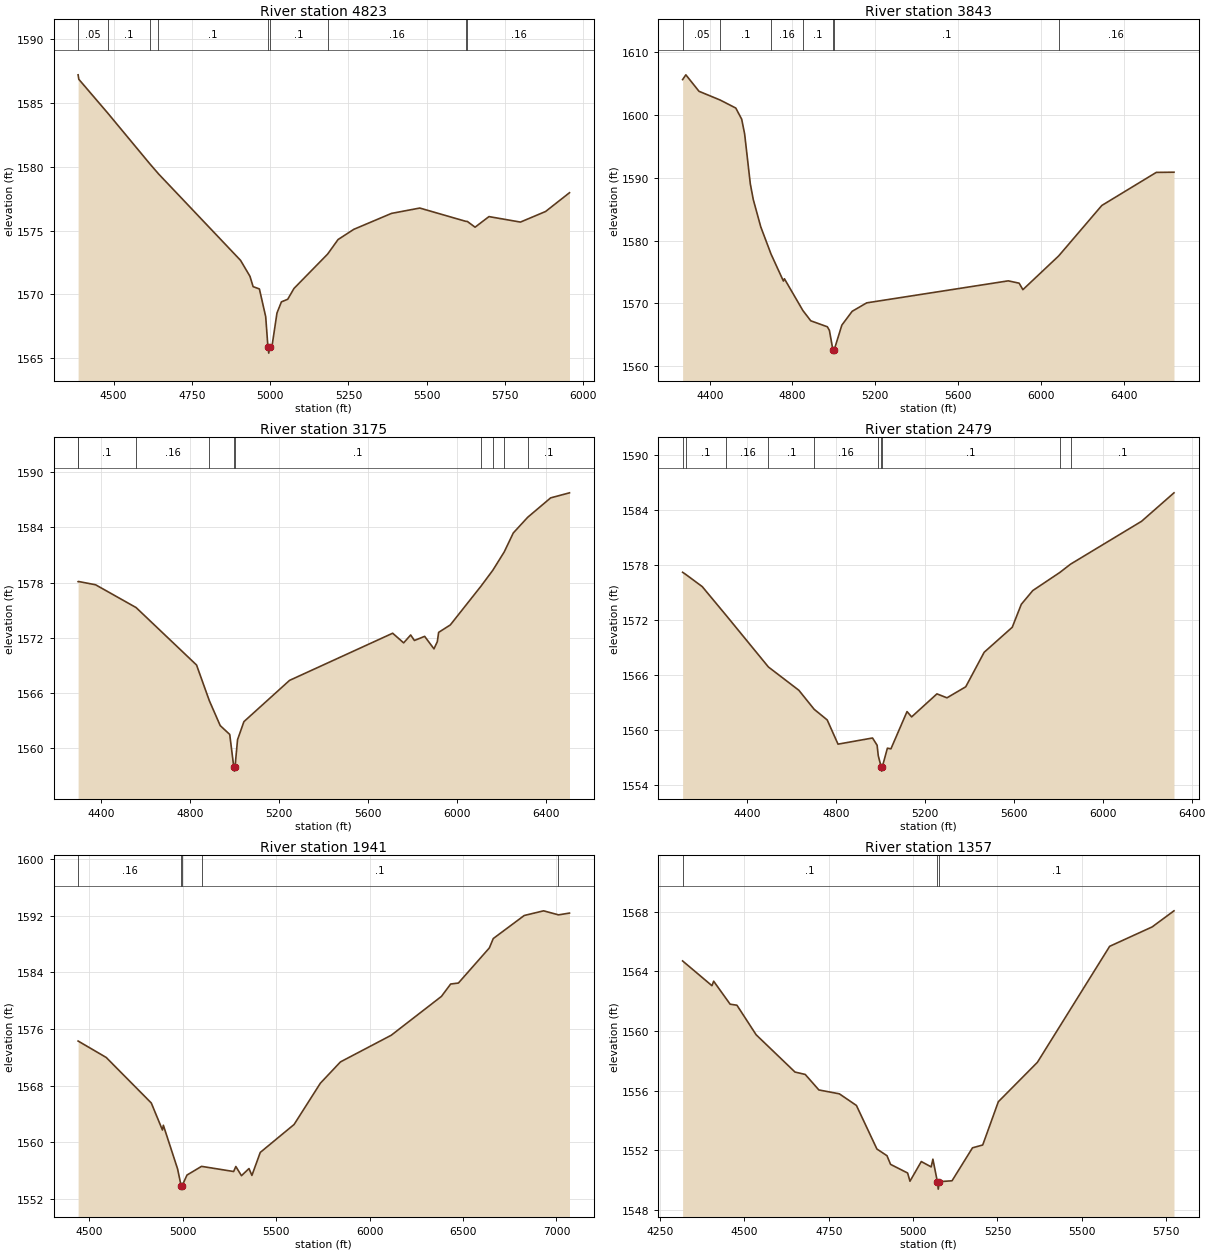
Type RM Length L Ch R = 1,4823,980,980,980
BEGIN DESCRIPTION:
UNT081 IN NNOGR 7.0
END DESCRIPTION:
XS GIS Cut Line= 2
      2834874.99     10105469.03      2833312.46     10105320.21
#Sta/Elev= 30
  4386.6 1587.20  4388.9 1586.85  4481.0 1584.21  4614.9 1580.25  4643.0 1579.45
  4905.5 1572.66  4935.6 1571.41  4945.6 1570.60  4965.7 1570.42  4985.8 1568.25
  4992.9 1565.89  4995.6 1565.39  4998.9 1565.89  5005.9 1565.92  5021.8 1568.53
  5036.1 1569.41  5056.1 1569.61  5076.2 1570.46  5183.6 1573.15  5216.9 1574.29
  5267.1 1575.09  5387.6 1576.34  5478.0 1576.76  5624.7 1575.72  5629.9 1575.71
  5654.6 1575.26  5699.0 1576.09  5799.5 1575.66  5879.9 1576.49  5956.2 1577.96
#Mann=9,-1,0
  4386.6    0.05       0  4481.0     0.1       0  4614.9    0.05       0
  4643.0     0.1       0  4992.9    0.07       0  4998.9     0.1       0
  5183.6    0.16       0  5624.7     0.1       0  5629.9    0.16       0
Bank Sta=4992.9,4998.9
Exp/Cntr=0.3,0.1

Type RM Length L Ch R = 1,3843,668,668,668
BEGIN DESCRIPTION:
UNT081 IN NNOGR 6.0
END DESCRIPTION:
XS GIS Cut Line= 4
      2835015.03     10104939.31      2834666.10     10104637.25
      2834067.14     10104668.50      2832858.83     10105184.11
#Sta/Elev= 30
  4269.0 1605.58  4284.7 1606.34  4348.3 1603.72  4450.1 1602.34  4526.0 1601.06
  4554.5 1599.29  4568.7 1596.97  4596.2 1589.02  4610.5 1586.52  4646.6 1582.19
  4696.2 1577.86  4756.1 1573.56  4761.1 1573.92  4850.2 1568.88  4888.4 1567.24
  4968.5 1566.29  4978.5 1565.72  4995.5 1562.60  4998.3 1562.10  5001.5 1562.60
  5038.6 1566.55  5088.6 1568.75  5158.7 1570.09  5842.9 1573.59  5895.5 1573.22
  5913.7 1572.19  6086.9 1577.56  6295.1 1585.57  6558.4 1590.83  6644.0 1590.86
#Mann=7,-1,0
  4269.0    0.05       0  4450.1     0.1       0  4696.2    0.16       0
  4850.2     0.1       0  4995.5    0.07       0  5001.5     0.1       0
  6086.9    0.16       0
Bank Sta=4995.5,5001.5
Exp/Cntr=0.3,0.1

Type RM Length L Ch R = 1,3175,696,696,696
BEGIN DESCRIPTION:
Mapping XS ee938444
END DESCRIPTION:
XS GIS Cut Line= 4
      2834806.71     10104001.83      2834332.77     10104038.29
      2833733.81     10104720.58      2832947.36     10104965.37
#Sta/Elev= 30
  4297.5 1578.10  4298.5 1578.12  4376.0 1577.76  4558.0 1575.28  4829.5 1569.03
  4886.9 1565.15  4935.8 1562.44  4978.5 1561.48  4996.4 1557.99  4999.1 1557.49
  5002.4 1557.99  5013.6 1560.91  5042.1 1562.87  5247.1 1567.36  5710.3 1572.49
  5759.6 1571.44  5791.1 1572.30  5807.9 1571.70  5853.9 1572.15  5895.8 1570.79
  5910.8 1571.57  5916.7 1572.58  5969.1 1573.39  6106.7 1577.60  6160.1 1579.34
  6211.5 1581.34  6251.9 1583.39  6316.3 1585.09  6419.7 1587.21  6504.4 1587.76
#Mann=10,-1,0
  4297.5    0.16       0  4298.5     0.1       0  4558.0    0.16       0
  4886.9     0.1       0  4996.4    0.07       0  5002.4     0.1       0
  6106.7    0.16       0  6160.1     0.1       0  6211.5    0.16       0
  6316.3     0.1       0
Bank Sta=4996.4,5002.4
Exp/Cntr=0.3,0.1

Type RM Length L Ch R = 1,2479,538,538,538
BEGIN DESCRIPTION:
UNT081 IN NNOGR 5.0
END DESCRIPTION:
XS GIS Cut Line= 3
      2834483.83     10103632.04      2833348.39     10103934.13
      2832921.30     10104876.85
#Sta/Elev= 30
  4110.7 1577.19  4125.9 1576.94  4199.0 1575.63  4308.0 1572.45  4496.6 1566.87
  4633.6 1564.33  4702.3 1562.26  4761.0 1561.10  4809.6 1558.46  4964.8 1559.13
  4985.5 1558.34  4990.6 1557.21  5003.2 1556.02  5005.9 1555.52  5009.2 1556.02
  5031.7 1558.02  5047.6 1557.95  5120.0 1562.01  5140.7 1561.43  5254.5 1563.94
  5299.6 1563.51  5384.0 1564.71  5466.8 1568.47  5593.2 1571.20  5633.9 1573.70
  5685.6 1575.20  5807.1 1577.17  5855.7 1578.08  6174.9 1582.75  6320.6 1585.85
#Mann=10,-1,0
  4110.7    0.16       0  4125.9     0.1       0  4308.0    0.16       0
  4496.6     0.1       0  4702.3    0.16       0  4990.6     0.1       0
  5003.2    0.07       0  5009.2     0.1       0  5807.1    0.16       0
  5855.7     0.1       0
Bank Sta=5003.2,5009.2
Exp/Cntr=0.3,0.1

Type RM Length L Ch R = 1,1941,584,584,584
BEGIN DESCRIPTION:
Mapping XS 64794977
END DESCRIPTION:
XS GIS Cut Line= 3
      2834337.95     10103350.79      2832811.93     10103512.25
      2831754.69     10103798.70
#Sta/Elev= 30
  4439.9 1574.30  4590.2 1571.98  4831.6 1565.54  4891.2 1561.72  4896.2 1562.39
  4972.3 1556.22  4991.0 1553.86  4993.8 1553.36  4997.0 1553.86  5022.6 1555.35
  5100.5 1556.58  5272.3 1555.85  5284.1 1556.56  5314.2 1555.26  5354.5 1556.27
  5370.1 1555.30  5414.8 1558.55  5595.8 1562.50  5736.6 1568.34  5844.1 1571.35
  6115.9 1575.12  6384.4 1580.61  6433.9 1582.36  6475.3 1582.50  6641.1 1587.47
  6661.8 1588.79  6827.6 1592.05  6931.2 1592.71  7011.0 1592.14  7069.8 1592.39
#Mann=5,-1,0
  4439.9    0.16       0  4991.0    0.07       0  4997.0    0.16       0
  5100.5     0.1       0  7011.0    0.05       0
Bank Sta=4991,4997
Exp/Cntr=0.3,0.1

Type RM Length L Ch R = 1,1357,783,783,783
BEGIN DESCRIPTION:
UNT081 IN NNOGR 2.0
END DESCRIPTION:
XS GIS Cut Line= 2
      2834167.68     10102925.11      2832728.21     10103148.48
#Sta/Elev= 30
  4316.7 1564.69  4403.7 1563.03  4408.8 1563.33  4457.6 1561.79  4477.8 1561.72
  4534.7 1559.74  4649.9 1557.24  4680.2 1557.08  4720.7 1556.04  4781.4 1555.78
  4832.0 1555.00  4892.7 1552.08  4922.6 1551.63  4933.2 1551.05  4983.8 1550.47
  4990.7 1549.92  5024.3 1551.24  5053.6 1550.88  5058.7 1551.40  5071.9 1549.89
  5074.6 1549.39  5077.9 1549.89  5115.4 1549.95  5176.1 1552.16  5206.4 1552.35
  5252.7 1555.25  5368.4 1557.89  5582.7 1565.67  5708.6 1566.97  5773.4 1568.05
#Mann=3,-1,0
  4316.7     0.1       0  5071.9    0.07       0  5077.9     0.1       0
Bank Sta=5071.9,5077.9
Exp/Cntr=0.3,0.1

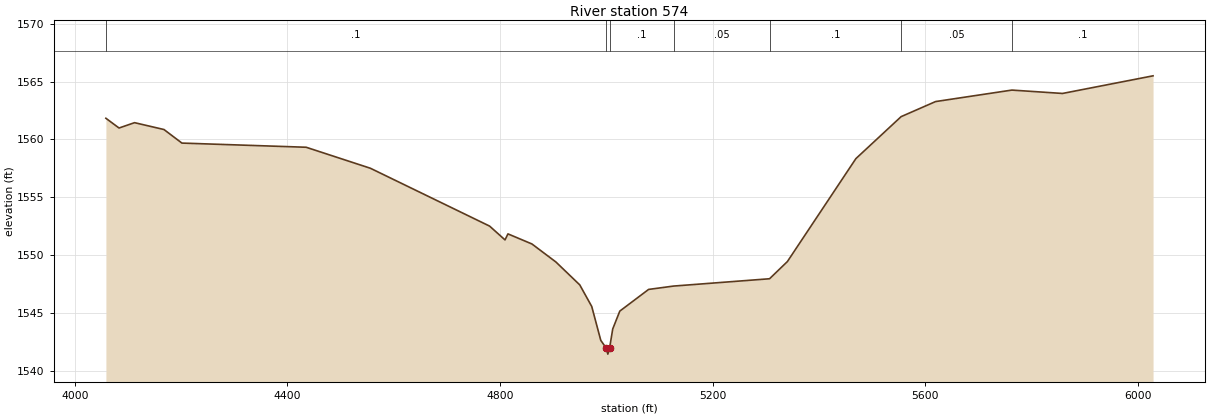
Type RM Length L Ch R = 1,574,0,0,0
BEGIN DESCRIPTION:
UNT081 IN NNOGR 1.0
END DESCRIPTION:
XS GIS Cut Line= 3
      2834266.92     10102738.97      2833150.10     10102192.97
      2832492.89     10102502.97
#Sta/Elev= 30
  4058.4 1561.83  4083.1 1560.99  4112.3 1561.45  4167.6 1560.86  4201.4 1559.69
  4435.1 1559.33  4555.9 1557.52  4780.2 1552.53  4809.2 1551.34  4814.7 1551.86
  4859.8 1550.99  4904.8 1549.44  4949.8 1547.46  4972.3 1545.60  4989.3 1542.68
  4999.8 1541.99  5002.6 1541.49  5005.8 1541.99  5011.8 1543.66  5025.1 1545.20
  5079.3 1547.07  5126.5 1547.36  5306.8 1547.99  5340.3 1549.47  5469.2 1558.35
  5554.3 1561.97  5619.1 1563.27  5762.6 1564.26  5857.9 1563.97  6028.2 1565.49
#Mann=7,-1,0
  4058.4     0.1       0  4999.8    0.07       0  5005.8     0.1       0
  5126.5    0.05       0  5306.8     0.1       0  5554.3    0.05       0
  5762.6     0.1       0
Bank Sta=4999.8,5005.8
Exp/Cntr=0.3,0.1

Chan Stop Cuts=-1