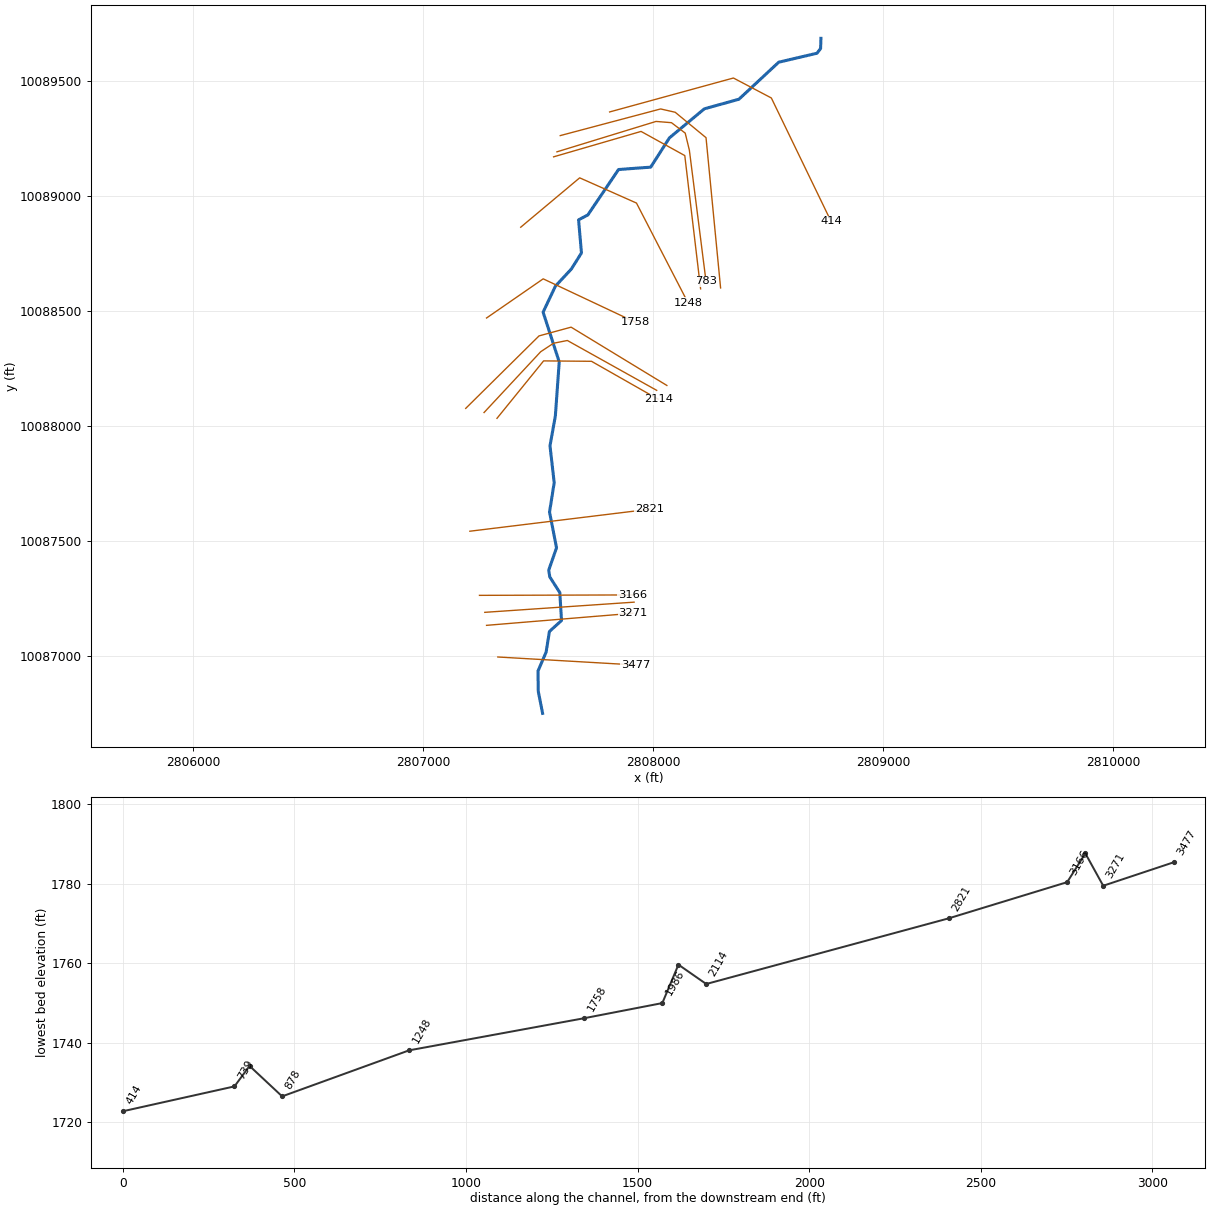
--- UNT084 IN NNOGR.prj (project) ---

Proj Title=UNT084 IN NNOGR Base Level Engineering
Current Plan=p01
Default Exp/Contr=0.3,0.1
English Units
Geom File=g01
Flow File=f01
Plan File=p01
Y Axis Title=Elevation
X Axis Title(PF)=Main Channel Distance
X Axis Title(XS)=Station
BEGIN DESCRIPTION:
UNT084 IN NNOGR
END DESCRIPTION:
DSS Export Rating Curves= 0
DSS Export Rating Curve Sorted= 0
DSS Export Volume Flow Curves= 0
DXF OffsetX= 0
DXF OffsetY= 0
DXF ScaleX= 1
DXF ScaleY= 10

--- UNT084 IN NNOGR.p01 (plan) ---

Plan Title=Multiple Run
Short Identifier=Multiple
Geom File=g01
Flow File=f01
Subcritical Flow
K Sum by GR= 0
Std Step Tol= 0.01
Critical Tol= 0.01
Num of Std Step Trials= 20
Max Error Tol= 0.3
Flow Tol Ratio= 0.001
Split Flow NTrial= 30
Split Flow Tol= 0.02
Split Flow Ratio= 0.02
Log Output Level= 0
Friction Slope Method= 1
Unsteady Friction Slope Method= 2
Unsteady Bridges Friction Slope Method= 1
Parabolic Critical Depth
Global Vel Dist=  1 , 1 , 1
Global Log Level= 0
CheckData=True
Encroach Param= -1, 0, 0, 0
BEGIN DESCRIPTION:
Multiple Run
END DESCRIPTION:

--- UNT084 IN NNOGR.f01 (steady flow) ---

Flow Title=Multiple
Program Version=4.10
Number of Profiles= 7
Profile Names=10-year,25-year,50-year,1pct_min,100-year,1pct_plu,500-year
River Rch & RM=UNT084 IN NNOGR,Reach-1         ,3477
     305     414     503     449     607     821     887
Boundary for River Rch & Prof#=UNT084 IN NNOGR,Reach-1         , 1
Up Type= 0
Dn Type= 3
Dn Slope=0.026
Boundary for River Rch & Prof#=UNT084 IN NNOGR,Reach-1         , 2
Up Type= 0
Dn Type= 3
Dn Slope=0.026
Boundary for River Rch & Prof#=UNT084 IN NNOGR,Reach-1         , 3
Up Type= 0
Dn Type= 3
Dn Slope=0.026
Boundary for River Rch & Prof#=UNT084 IN NNOGR,Reach-1         , 4
Up Type= 0
Dn Type= 3
Dn Slope=0.026
Boundary for River Rch & Prof#=UNT084 IN NNOGR,Reach-1         , 5
Up Type= 0
Dn Type= 3
Dn Slope=0.026
Boundary for River Rch & Prof#=UNT084 IN NNOGR,Reach-1         , 6
Up Type= 0
Dn Type= 3
Dn Slope=0.026
Boundary for River Rch & Prof#=UNT084 IN NNOGR,Reach-1         , 7
Up Type= 0
Dn Type= 3
Dn Slope=0.026
DSS Import GetInterval= 0
DSS Import GetPeak= 0
DSS Import FillOption= 0

--- UNT084 IN NNOGR.g01 (geometry) ---

Geom Title=Existing Conditions
Program Version=4.10

River Reach=UNT084 IN NNOGR ,Reach-1
Reach XY= 30
      2807518.47     10086748.73       2807499.6      10086843.9
      2807498.33     10086932.84      2807533.54     10087014.88
      2807548.04     10087104.71      2807600.55     10087152.46
      2807593.18     10087273.98      2807549.51     10087342.11
        2807545.     10087371.64      2807578.88     10087468.61
      2807548.56     10087623.94      2807568.75     10087751.97
      2807550.51     10087911.97      2807573.71     10088041.43
      2807590.57     10088277.02      2807520.52     10088493.25
      2807574.12     10088606.31      2807643.53     10088680.92
       2807687.3      10088750.6      2807674.77     10088894.64
      2807715.01     10088915.88      2807848.54     10089113.35
      2807988.39     10089123.67      2808069.74     10089250.98
      2808221.65     10089377.28       2808371.8     10089418.87
      2808545.04       10089580.      2808711.12     10089618.87
      2808727.03     10089639.29      2808728.47     10089683.73

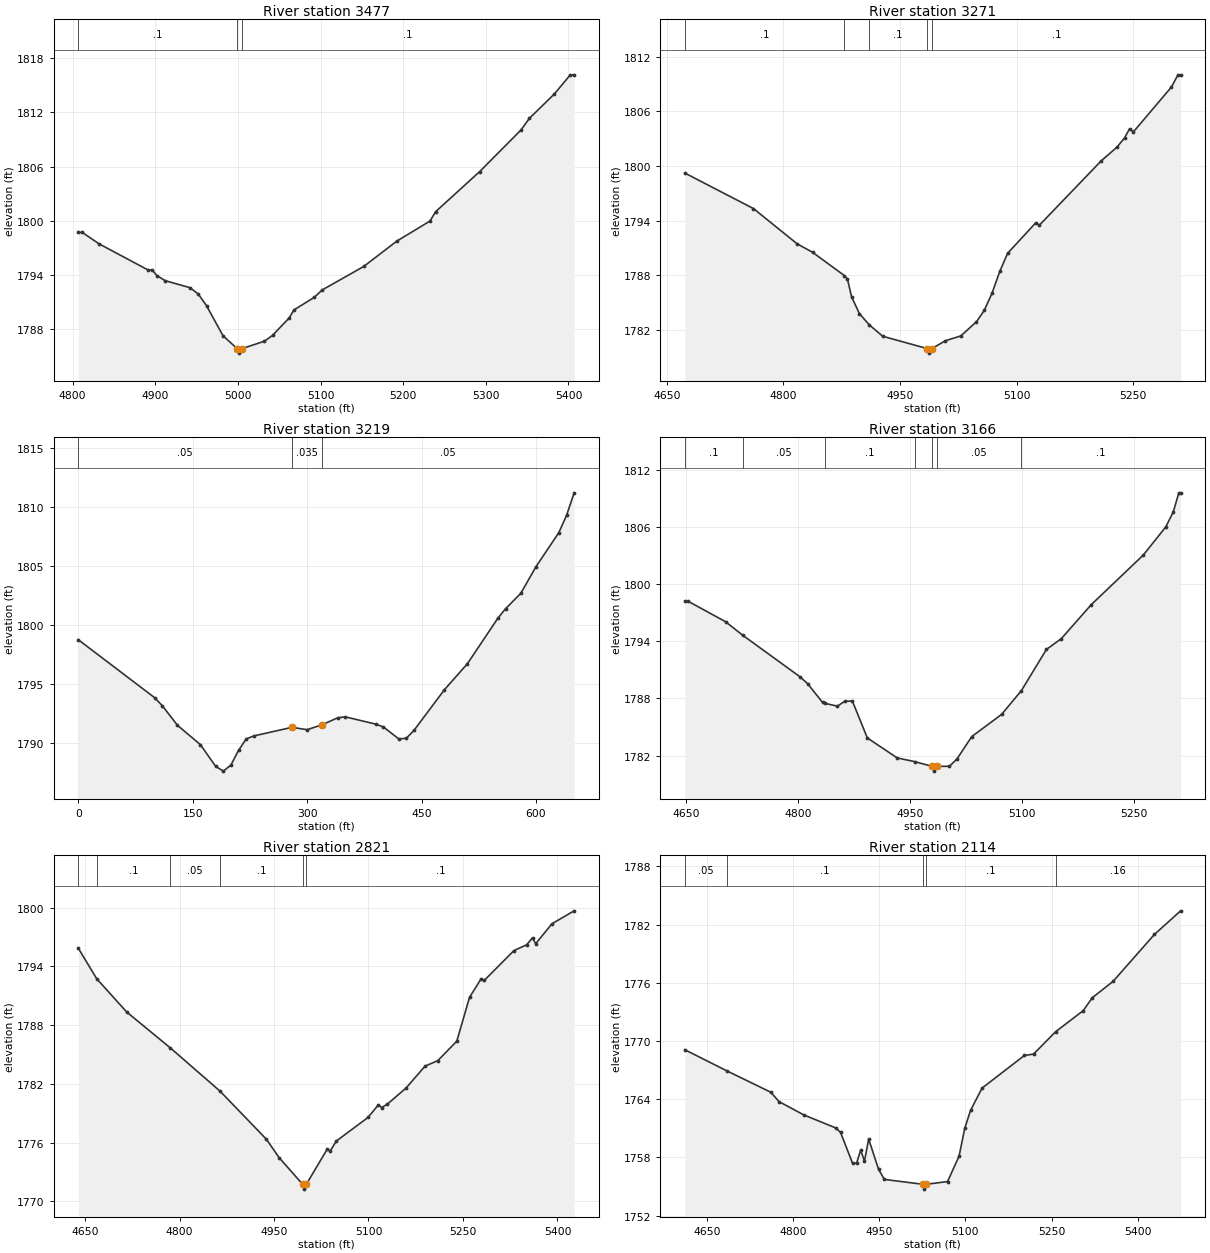
Type RM Length L Ch R = 1 ,3477    ,206,206,206
BEGIN DESCRIPTION:
UNT084 IN NNOGR 3.0
END DESCRIPTION:
XS GIS Cut Line= 2
      2807323.64     10086993.87      2807922.63     10086959.15
#Sta/Elev= 30
  4806.9 1798.72  4811.8 1798.72  4831.8 1797.47  4891.3 1794.57  4896.3 1794.58
  4901.9 1793.95  4911.9 1793.39    4942 1792.61    4952 1791.91    4962 1790.62
    4982 1787.29  4999.1 1785.87  5001.8 1785.37  5005.1 1785.87  5032.1 1786.69
  5042.1 1787.35  5062.2 1789.28  5067.8 1790.15  5092.2 1791.53  5102.2 1792.37
  5152.3 1794.96  5192.4 1797.77  5232.4 1799.98  5239.3 1801.02  5292.5 1805.45
  5342.6 1810.06  5352.6 1811.33  5382.7 1814.02  5402.3 1816.16  5406.9 1816.16
#Mann= 3 ,-1 , 0
  4806.9      .1       0  4999.1     .07       0  5005.1      .1       0
Bank Sta=4999.1,5005.1
XS Rating Curve= 0 ,0
Exp/Cntr=0.3,0.1

Type RM Length L Ch R = 1 ,3271    ,52,52,52
BEGIN DESCRIPTION:
Mapping XS 351ee133
END DESCRIPTION:
XS GIS Cut Line= 2
      2807274.69     10087131.52      2807910.22     10087184.03
#Sta/Elev= 30
  4673.2 1799.22  4761.5 1795.32  4817.5 1791.46  4837.5 1790.52  4878.3 1787.97
  4882.4 1787.58  4887.7 1785.63  4897.7  1783.8  4910.2 1782.57  4927.8  1781.3
    4985 1779.95  4987.8 1779.45    4991 1779.95  5008.4 1780.81  5028.2 1781.34
  5048.3 1782.89  5058.3 1784.13  5068.3 1786.02  5078.4 1788.44  5088.4 1790.41
  5124.3 1793.73  5129.3  1793.5  5208.8 1800.56  5228.9 1802.05  5238.9 1803.09
  5245.2 1804.07  5250.2 1803.74  5299.1 1808.66  5307.5    1810  5310.9    1810
#Mann= 5 ,-1 , 0
  4673.2      .1       0  4878.3     .05       0  4910.2      .1       0
    4985     .07       0    4991      .1       0
Bank Sta=4985,4991
XS Rating Curve= 0 ,0
Exp/Cntr=0.3,0.1

Type RM Length L Ch R = 1 ,3219    ,53,53,53
XS GIS Cut Line= 2
     2807266.902    10087188.032     2807916.208    10087232.303
#Sta/Elev= 30
       0 1798.75   99.99 1793.83  109.99 1793.15  129.99 1791.48  159.99 1789.84
  179.99    1788  189.98 1787.59  199.98  1788.1  209.98 1789.35  219.98 1790.32
  229.98 1790.58  279.98 1791.31  299.98 1791.11  319.97 1791.54  339.97 1792.12
  349.97  1792.2  389.97 1791.58  399.97 1791.34  419.97 1790.33  429.96 1790.38
  439.96 1791.05  479.96 1794.51  509.96 1796.71  549.96 1800.58  559.95 1801.38
  579.95 1802.69  599.95 1804.96  629.95 1807.86  639.95 1809.31  649.95 1811.23
#Mann= 3 , 0 , 0
       0     .05       0  279.98    .035       0  319.97     .05       0
Bank Sta=279.98,319.97
XS Rating Curve= 0 ,0
Exp/Cntr=0.3,0.1

Type RM Length L Ch R = 1 ,3166    ,345,345,345
BEGIN DESCRIPTION:
Mapping XS 213e39a9
END DESCRIPTION:
XS GIS Cut Line= 2
      2807243.87     10087261.89      2807908.36      10087263.7
#Sta/Elev= 30
  4648.1 1798.19  4652.9 1798.19  4702.7 1796.06  4725.5 1794.65  4802.7 1790.26
  4812.7 1789.55  4832.7 1787.58  4836.3 1787.47  4852.7 1787.19  4862.7 1787.71
  4872.7 1787.72  4892.7 1783.85  4932.7 1781.75  4956.1 1781.36  4979.7 1780.86
  4982.5 1780.36  4985.7 1780.86  5002.7 1780.87  5012.7 1781.62  5032.7 1783.99
  5072.7 1786.32  5099.3 1788.83  5132.7 1793.14  5152.7 1794.28  5192.7 1797.84
  5262.7 1803.07  5292.7 1806.02  5302.7 1807.58  5310.2  1809.6  5312.6  1809.6
#Mann= 7 ,-1 , 0
  4648.1      .1       0  4725.5     .05       0  4836.3      .1       0
  4956.1     .05       0  4979.7    .035       0  4985.7     .05       0
  5099.3      .1       0
Bank Sta=4979.7,4985.7
XS Rating Curve= 0 ,0
Exp/Cntr=0.3,0.1

Type RM Length L Ch R = 1 ,2821    ,707,707,707
BEGIN DESCRIPTION:
UNT084 IN NNOGR 2.0
END DESCRIPTION:
XS GIS Cut Line= 2
      2807202.09     10087540.74      2807983.38     10087636.23
#Sta/Elev= 30
  4639.4 1795.86  4668.5 1792.75  4716.3 1789.34  4785.3 1785.69  4864.3 1781.27
    4938 1776.35  4958.1 1774.48  4995.4 1771.76  4998.2 1771.26  5001.4 1771.76
  5034.3 1775.32  5039.4 1775.16  5048.8 1776.16  5099.2 1778.58  5115.8 1779.87
  5120.9 1779.59  5129.4 1779.91  5159.6 1781.58  5189.8 1783.82    5210 1784.38
  5240.2 1786.37  5260.4 1790.84  5278.9 1792.75  5283.9 1792.58  5330.9 1795.62
    5351 1796.21  5360.4 1796.92  5365.4 1796.32  5391.3 1798.36  5426.5 1799.68
#Mann= 6 ,-1 , 0
  4639.4     .05       0  4668.5      .1       0  4785.3     .05       0
  4864.3      .1       0  4995.4     .07       0  5001.4      .1       0
Bank Sta=4995.4,5001.4
XS Rating Curve= 0 ,0
Exp/Cntr=0.3,0.1

Type RM Length L Ch R = 1 ,2114    ,81,81,81
BEGIN DESCRIPTION:
Mapping XS d3bceed5
END DESCRIPTION:
XS GIS Cut Line= 4
      2807319.95     10088031.45      2807522.73      10088281.3
      2807730.96     10088279.49      2808020.66     10088114.72
#Sta/Elev= 30
  4611.5  1769.1  4684.5 1766.93  4761.2 1764.72  4775.6 1763.75  4818.7 1762.38
  4874.7 1761.03  4882.7 1760.57  4903.5 1757.41  4910.7 1757.42  4917.8 1758.76
  4924.3  1757.6  4931.6 1759.89    4949 1756.76    4959 1755.73    5026 1755.23
  5028.8 1754.73    5032 1755.23    5069 1755.51    5089 1758.12    5099 1761.01
    5109 1762.84    5129 1765.14  5202.8 1768.51  5218.7 1768.65  5257.2 1770.96
  5305.2 1773.13    5321 1774.46  5357.2 1776.15  5429.1 1780.98  5474.8 1783.42
#Mann= 5 ,-1 , 0
  4611.5     .05       0  4684.5      .1       0    5026     .07       0
    5032      .1       0  5257.2     .16       0
Bank Sta=5026,5032
XS Rating Curve= 0 ,0
Exp/Cntr=0.3,0.1

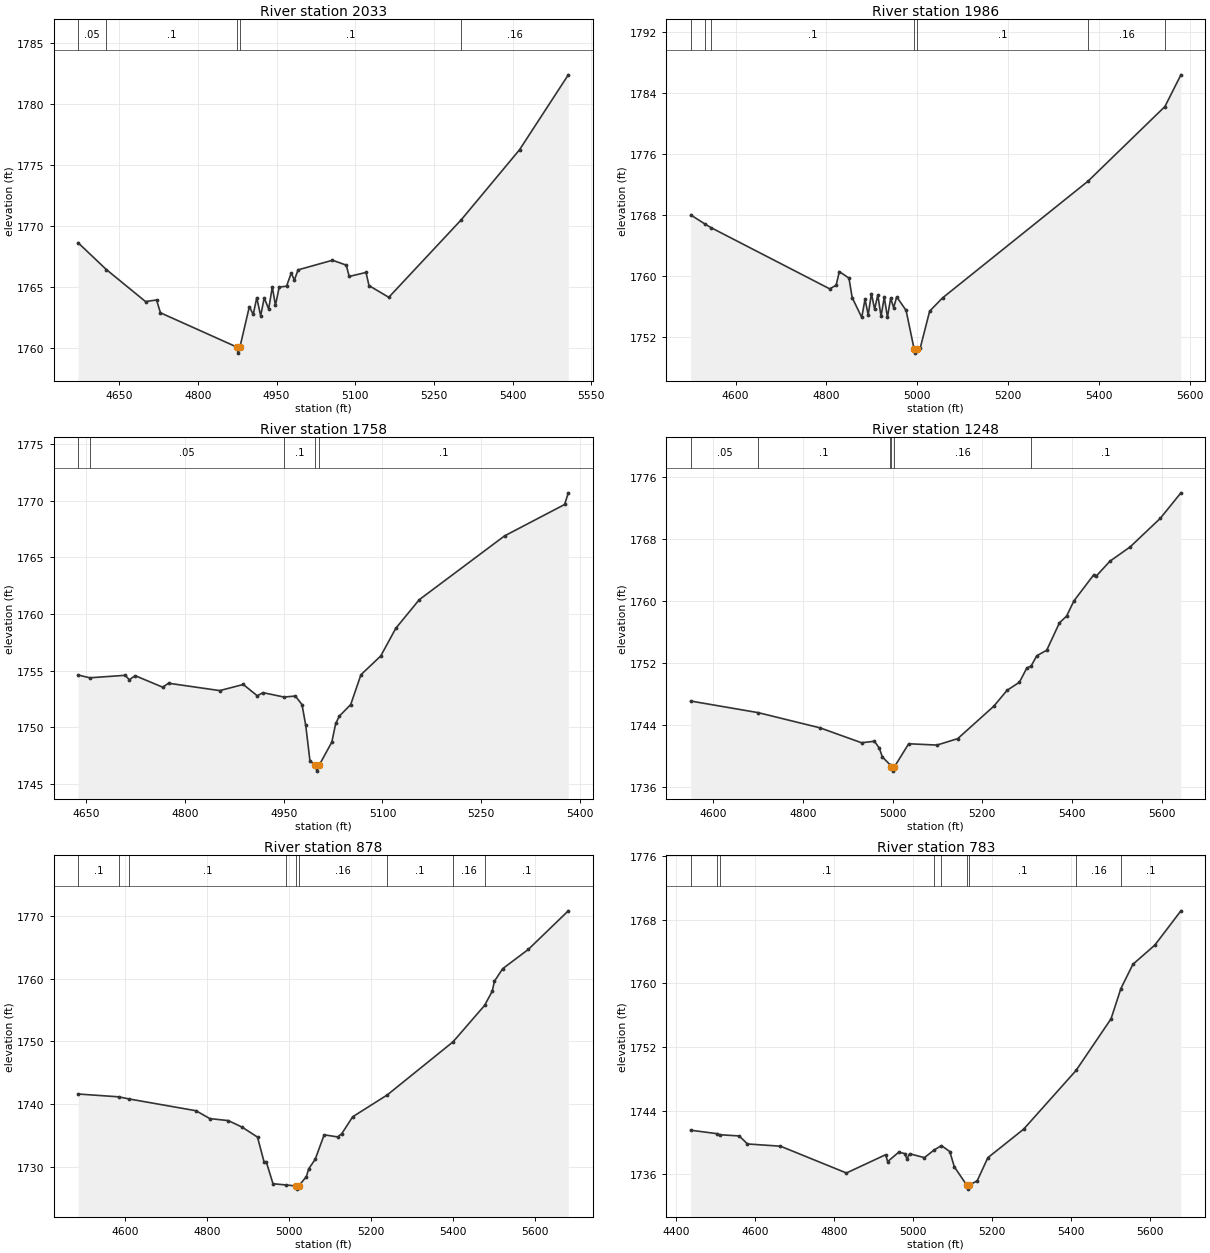
Type RM Length L Ch R = 1 ,2033    ,47,47,47
BEGIN DESCRIPTION:
Mapping XS 6550f52a
END DESCRIPTION:
XS GIS Cut Line= 5
       2807263.8     10088056.77      2807510.06     10088321.13
      2807565.88     10088358.02      2807625.94     10088370.02
      2808014.38     10088153.22
#Sta/Elev= 30
  4571.8 1768.66  4625.6 1766.46  4700.4 1763.83  4721.4 1763.96  4728.8 1762.91
  4874.3  1760.1    4877  1759.6  4880.3  1760.1  4898.3 1763.42  4905.6 1762.77
  4912.4 1764.15  4919.8 1762.66  4926.6 1764.13  4935.1 1763.22    4942 1765.03
    4948 1763.53  4955.2 1765.02  4969.1 1765.09  4978.1 1766.17  4984.1  1765.6
  4991.1 1766.43  5056.7 1767.22  5082.9 1766.82  5088.6 1765.89  5120.6 1766.22
  5126.3 1765.14    5164 1764.18  5302.1 1770.54  5413.1 1776.28  5506.1 1782.43
#Mann= 5 ,-1 , 0
  4571.8     .05       0  4625.6      .1       0  4874.3     .07       0
  4880.3      .1       0  5302.1     .16       0
Bank Sta=4874.3,4880.3
XS Rating Curve= 0 ,0
Exp/Cntr=0.3,0.1

Type RM Length L Ch R = 1 ,1986    ,228,228,228
BEGIN DESCRIPTION:
Mapping XS fa358314
END DESCRIPTION:
XS GIS Cut Line= 4
      2807184.12     10088074.86      2807502.81     10088389.94
      2807642.24     10088427.96      2808058.69     10088174.47
#Sta/Elev= 30
  4500.8 1768.03  4533.1 1766.81  4545.7 1766.36  4807.1 1758.35  4821.3 1758.81
  4828.4 1760.61  4849.6 1759.75  4856.7  1757.2  4877.8  1754.6    4885    1757
    4892 1754.93  4899.1 1757.73  4906.1 1755.68  4913.2 1757.54  4920.3 1754.75
  4927.4 1757.26  4934.4 1754.64  4941.5 1757.12  4948.1 1755.88  4954.8  1757.3
  4975.5 1755.52  4993.3 1750.43    4996 1749.93  4999.3 1750.43  5006.6 1750.59
  5027.4 1755.43  5055.8 1757.16  5376.6 1772.46  5545.8 1782.22    5581 1786.37
#Mann= 7 ,-1 , 0
  4500.8      .1       0  4533.1     .05       0  4545.7      .1       0
  4993.3     .07       0  4999.3      .1       0  5376.6     .16       0
  5545.8      .1       0
Bank Sta=4993.3,4999.3
XS Rating Curve= 0 ,0
Exp/Cntr=0.3,0.1

Type RM Length L Ch R = 1 ,1758    ,510,510,510
BEGIN DESCRIPTION:
Mapping XS 4bacbc16
END DESCRIPTION:
XS GIS Cut Line= 3
      2807274.67      10088467.8      2807520.92       10088638.
      2807923.22     10088448.58
#Sta/Elev= 30
    4638 1754.61  4655.8 1754.36  4709.7 1754.58  4715.8 1754.18  4724.6 1754.55
  4766.5 1753.53  4775.3 1753.88    4853 1753.23  4888.8 1753.77    4910 1752.77
  4918.6 1753.05  4950.6 1752.66  4967.8 1752.75  4977.9 1751.99  4983.5 1750.17
  4989.9 1747.05  4997.7 1746.62  5000.5 1746.12  5003.7 1746.62  5023.1 1748.68
    5029 1750.33  5034.6 1750.98  5051.8    1752  5067.3 1754.63  5097.4 1756.29
  5120.2 1758.73  5155.7 1761.25  5285.3 1766.89  5376.4 1769.66    5382 1770.69
#Mann= 5 ,-1 , 0
    4638      .1       0  4655.8     .05       0  4950.6      .1       0
  4997.7     .07       0  5003.7      .1       0
Bank Sta=4997.7,5003.7
XS Rating Curve= 0 ,0
Exp/Cntr=0.3,0.1

Type RM Length L Ch R = 1 ,1248    ,370,370,370
BEGIN DESCRIPTION:
Mapping XS a67524cb
END DESCRIPTION:
XS GIS Cut Line= 4
      2807423.16     10088862.53      2807679.56      10089077.2
      2807926.51     10088967.54      2808151.02     10088533.02
#Sta/Elev= 30
  4549.4 1747.08  4700.2 1745.58  4838.1 1743.62  4930.6  1741.7  4959.3 1741.89
  4970.1 1741.03  4977.1 1739.87  4994.3 1738.86  4997.4 1738.54  5000.1 1738.04
  5003.4 1738.54  5035.8 1741.57  5098.9  1741.4  5145.2 1742.23  5225.8 1746.42
  5255.1 1748.45  5282.9 1749.51  5299.4 1751.35  5308.8 1751.58  5321.6 1752.92
  5343.7 1753.63  5372.2 1757.17    5388 1758.03  5404.5    1760  5448.8 1763.37
  5454.5 1763.21  5484.7 1765.11  5529.7 1766.95  5597.3 1770.65  5643.1 1773.93
#Mann= 6 ,-1 , 0
  4549.4     .05       0  4700.2      .1       0  4994.3     .16       0
  4997.4     .07       0  5003.4     .16       0  5308.8      .1       0
Bank Sta=4997.4,5003.4
XS Rating Curve= 0 ,0
Exp/Cntr=0.3,0.1

Type RM Length L Ch R = 1 ,878     ,95,95,95
BEGIN DESCRIPTION:
Mapping XS 8f59aec9
END DESCRIPTION:
XS GIS Cut Line= 4
      2807566.23     10089168.54      2807946.43     10089278.98
      2808136.55     10089173.96      2808205.35     10088594.54
#Sta/Elev= 30
  4485.1 1741.62  4584.2 1741.17  4609.6 1740.83  4773.2 1738.95  4806.7  1737.7
  4851.9 1737.38  4885.3 1736.35  4923.1 1734.75  4939.2 1730.78  4944.9 1730.73
  4960.9 1727.32    4992 1727.13  5017.4 1726.96  5020.2 1726.46  5023.4 1726.96
  5042.3 1728.44    5048 1729.69    5064 1731.22  5085.8 1735.12  5118.6 1734.78
  5128.7 1735.29  5155.4 1737.99  5239.8 1741.47  5400.5 1749.94  5477.4 1755.74
  5496.2 1758.02  5501.3 1759.58  5521.4 1761.58  5583.9 1764.65  5681.7 1770.81
#Mann= 9 ,-1 , 0
  4485.1      .1       0  4584.2     .16       0  4609.6      .1       0
    4992     .16       0  5017.4     .07       0  5023.4     .16       0
  5239.8      .1       0  5400.5     .16       0  5477.4      .1       0
Bank Sta=5017.4,5023.4
XS Rating Curve= 0 ,0
Exp/Cntr=0.3,0.1

Type RM Length L Ch R = 1 ,783     ,44,44,44
BEGIN DESCRIPTION:
Mapping XS 3ef1301b
END DESCRIPTION:
XS GIS Cut Line= 6
      2807580.72     10089190.27      2808011.61     10089322.43
      2808078.61       10089317.      2808138.36     10089271.73
      2808156.47      10089197.5      2808228.79     10088627.97
#Sta/Elev= 30
  4436.1 1741.53  4503.8 1741.09  4509.9 1740.96  4559.3 1740.81  4580.2  1739.8
  4663.9 1739.52  4831.2 1736.15  4930.7 1738.45  4935.7 1737.58  4963.9 1738.77
  4978.5  1738.6  4984.7 1737.93  4991.5 1738.57    5029 1738.08  5053.5 1739.04
  5072.1 1739.59  5093.3 1738.85  5104.8 1736.93  5136.4 1734.62  5139.2 1734.12
  5142.4 1734.62  5162.8 1735.16  5189.8 1738.07  5280.6 1741.66  5413.5 1749.04
  5502.3 1755.54  5527.3 1759.35  5557.8  1762.4  5613.2  1764.8  5679.5 1769.12
#Mann= 9 ,-1 , 0
  4436.1      .1       0  4503.8     .16       0  4509.9      .1       0
  5053.5     .16       0  5072.1      .1       0  5136.4     .07       0
  5142.4      .1       0  5413.5     .16       0  5527.3      .1       0
Bank Sta=5136.4,5142.4
XS Rating Curve= 0 ,0
Exp/Cntr=0.3,0.1

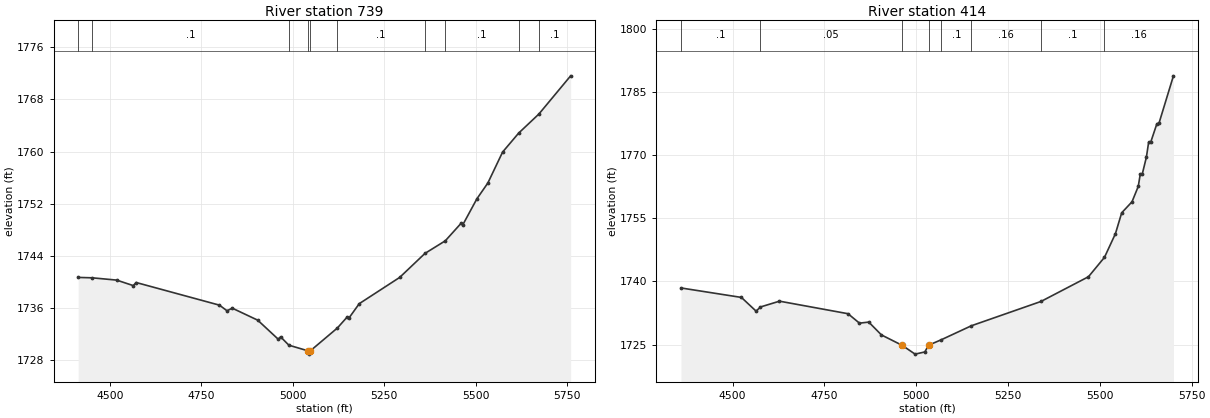
Type RM Length L Ch R = 1 ,739     ,325,325,325
BEGIN DESCRIPTION:
Mapping XS 313c2e3d
END DESCRIPTION:
XS GIS Cut Line= 5
      2807595.13     10089260.86      2808031.53     10089376.75
       2808094.9     10089362.27      2808228.89     10089251.82
      2808292.24     10088598.46
#Sta/Elev= 30
  4413.3 1740.72  4451.4 1740.66  4518.5 1740.31  4563.8 1739.47  4571.9 1739.94
  4799.7 1736.47  4820.3 1735.61  4834.7 1736.01  4904.3 1734.17  4960.4 1731.25
  4966.8 1731.62  4989.4 1730.34    5042 1729.47  5044.8 1728.97    5048 1729.47
    5122 1732.97  5148.8 1734.65  5153.8 1734.51  5181.9  1736.7  5292.4 1740.72
  5361.6  1744.4  5417.2 1746.33    5460 1748.99    5465 1748.78  5503.4 1752.75
  5533.6 1755.19  5573.8 1759.92  5617.8 1762.83  5673.1 1765.75  5759.9  1771.6
#Mann= 10 ,-1 , 0
  4413.3     .16       0  4451.4      .1       0  4989.4     .16       0
    5042     .07       0    5048     .16       0    5122      .1       0
  5361.6     .16       0  5417.2      .1       0  5617.8     .16       0
  5673.1      .1       0
Bank Sta=5042,5048
XS Rating Curve= 0 ,0
Exp/Cntr=0.3,0.1

Type RM Length L Ch R = 1 ,414     ,0,0,0
BEGIN DESCRIPTION:
UNT084 IN NNOGR 1.0
END DESCRIPTION:
XS GIS Cut Line= 4
      2807809.72     10089363.65      2808347.96     10089511.23
      2808512.89     10089424.42      2808772.71     10088887.46
#Sta/Elev= 30
  4359.4 1738.44    4524 1736.19    4564 1732.93  4575.9 1733.92  4627.7  1735.3
  4814.3 1732.32  4845.4 1730.08  4870.8 1730.33  4905.3 1727.28  4961.7 1724.81
  4996.9 1722.72 5023.49 1723.24  5033.5 1724.83  5068.6 1726.15  5150.3 1729.46
  5339.7 1735.23  5469.1 1741.11  5512.6 1745.71  5542.4 1751.32  5559.5 1756.29
  5587.6 1758.91  5604.6 1762.56  5610.2 1765.54  5615.8 1765.59  5626.8 1769.53
  5632.8 1773.02  5638.4 1773.03  5655.4 1777.47  5660.9 1777.53  5700.4 1788.83
#Mann= 8 ,-1 , 0
  4359.4      .1       0  4575.9     .05       0  4961.7     .03       0
  5033.5     .05       0  5068.6      .1       0  5150.3     .16       0
  5339.7      .1       0  5512.6     .16       0
Bank Sta=4961.7,5033.5
XS Rating Curve= 0 ,0
Exp/Cntr=0.3,0.1

Chan Stop Cuts=-1
Use User Specified Reach Order=0
Composite Channel Slope=5