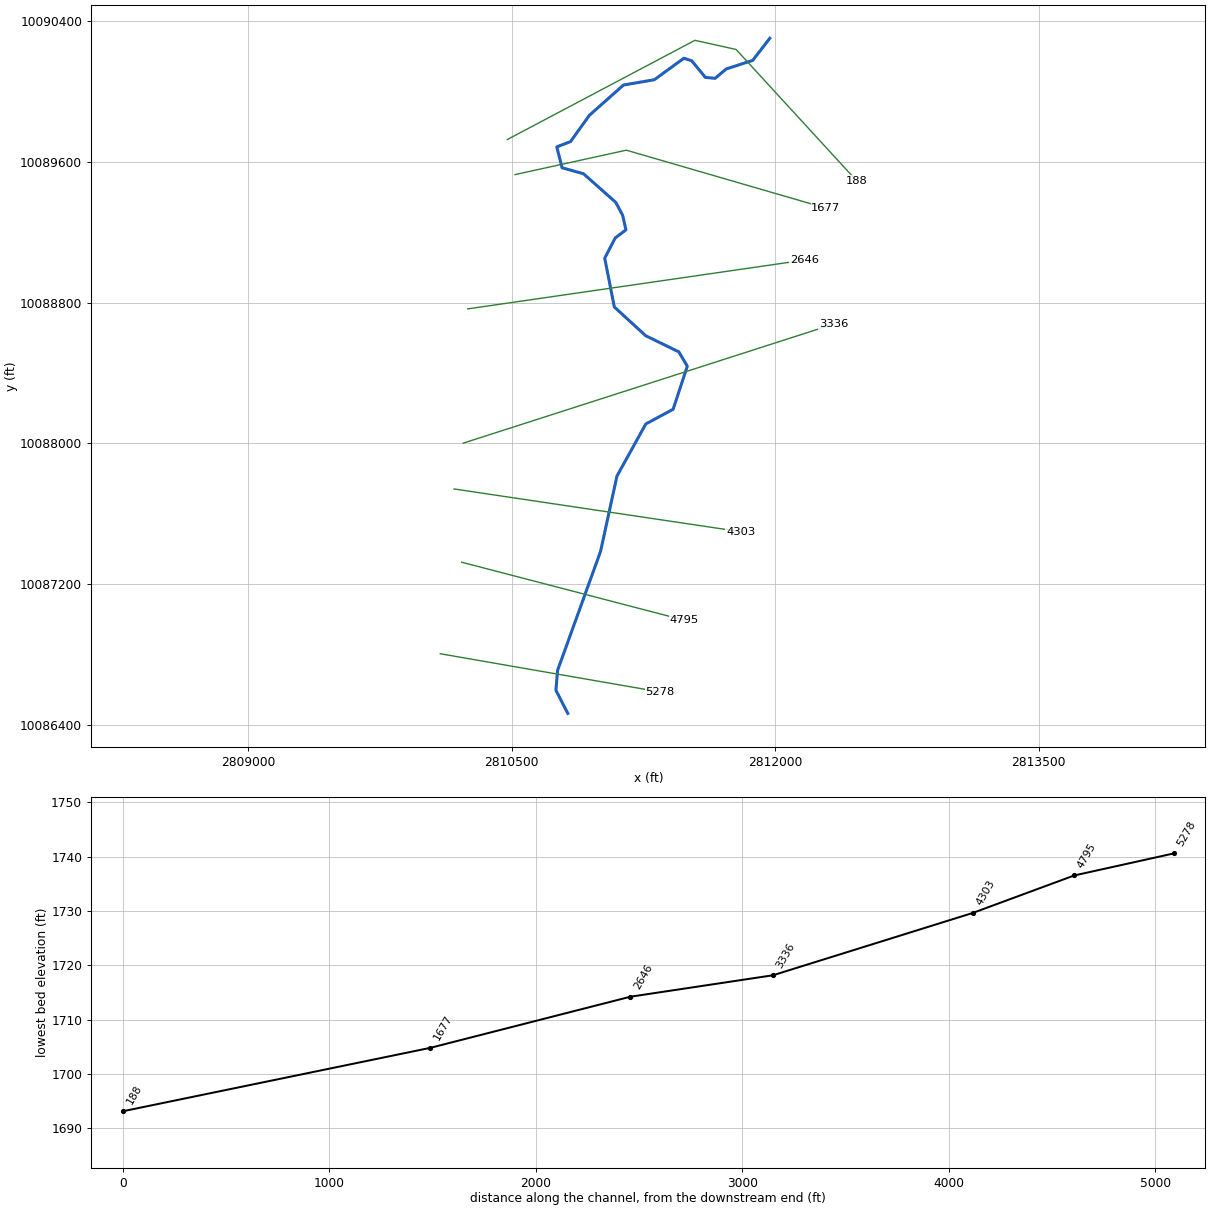
--- UNT086 IN NNOGR.prj (project) ---

Proj Title=UNT086 IN NNOGR Base Level Engineering
Current Plan=p01
Default Exp/Contr=0.3,0.1
English Units
Geom File=g01
Flow File=f01
Plan File=p01
BEGIN DESCRIPTION:
UNT086 IN NNOGR
END DESCRIPTION:

--- UNT086 IN NNOGR.p01 (plan) ---

Plan Title=Multiple Run
Short Identifier=Multiple
Geom File=g01
Flow File=f01
Subcritical Flow
K Sum by GR= 0
Std Step Tol= 0.01
Critical Tol= 0.01
Num of Std Step Trials= 20
Max Error Tol= 0.3
Flow Tol Ratio= 0.001
Split Flow NTrial= 30
Split Flow Tol= 0.02
Split Flow Ratio= 0.02
Log Output Level= 0
Friction Slope Method= 1
Unsteady Friction Slope Method= 2
Unsteady Bridges Friction Slope Method= 1
Parabolic Critical Depth
Global Vel Dist=  1 , 1 , 1
Global Log Level= 0
CheckData=True
Encroach Param= -1, 0, 0, 0
BEGIN DESCRIPTION:
Multiple Run
END DESCRIPTION:

--- UNT086 IN NNOGR.f01 (steady flow) ---

Flow Title=Multiple
Number of Profiles=7
Profile Names=10-year,25-year,50-year,1pct_min,100-year,1pct_plu,500-year
River Rch & RM= UNT086 IN NNOGR,Reach-1,5278
    1132    1653    2108    1966    2658    3595    4244
Boundary for River Rch & Prof#=UNT086 IN NNOGR,Reach-1,1
Up Type=0
Dn Type=3
Dn Slope=0.005
Boundary for River Rch & Prof#=UNT086 IN NNOGR,Reach-1,2
Up Type=0
Dn Type=3
Dn Slope=0.005
Boundary for River Rch & Prof#=UNT086 IN NNOGR,Reach-1,3
Up Type=0
Dn Type=3
Dn Slope=0.005
Boundary for River Rch & Prof#=UNT086 IN NNOGR,Reach-1,4
Up Type=0
Dn Type=3
Dn Slope=0.005
Boundary for River Rch & Prof#=UNT086 IN NNOGR,Reach-1,5
Up Type=0
Dn Type=3
Dn Slope=0.005
Boundary for River Rch & Prof#=UNT086 IN NNOGR,Reach-1,6
Up Type=0
Dn Type=3
Dn Slope=0.005
Boundary for River Rch & Prof#=UNT086 IN NNOGR,Reach-1,7
Up Type=0
Dn Type=3
Dn Slope=0.005

--- UNT086 IN NNOGR.g01 (geometry) ---

Geom Title=Existing Conditions

River Reach=UNT086 IN NNOGR,Reach-1
Reach XY= 30
      2810818.47     10086463.73      2810751.10     10086594.95
      2810760.34     10086707.94      2811005.17     10087385.10
      2811098.51     10087813.71      2811262.75     10088110.16
      2811418.47     10088193.73      2811499.02     10088438.69
      2811450.48     10088520.38      2811262.03     10088612.09
      2811083.48     10088775.55      2811028.96     10089053.33
      2811088.68     10089168.28      2811149.80     10089214.44
      2811130.94     10089296.99      2811091.92     10089370.51
      2810908.32     10089533.27      2810785.93     10089567.51
      2810756.05     10089686.31      2810834.17     10089716.17
      2810941.69     10089866.10      2811135.86     10090038.31
      2811311.35     10090068.15      2811479.22     10090190.40
      2811524.21     10090176.04      2811601.87     10090081.54
      2811657.15     10090076.17      2811720.80     10090129.54
      2811871.38     10090178.42      2811968.47     10090303.73

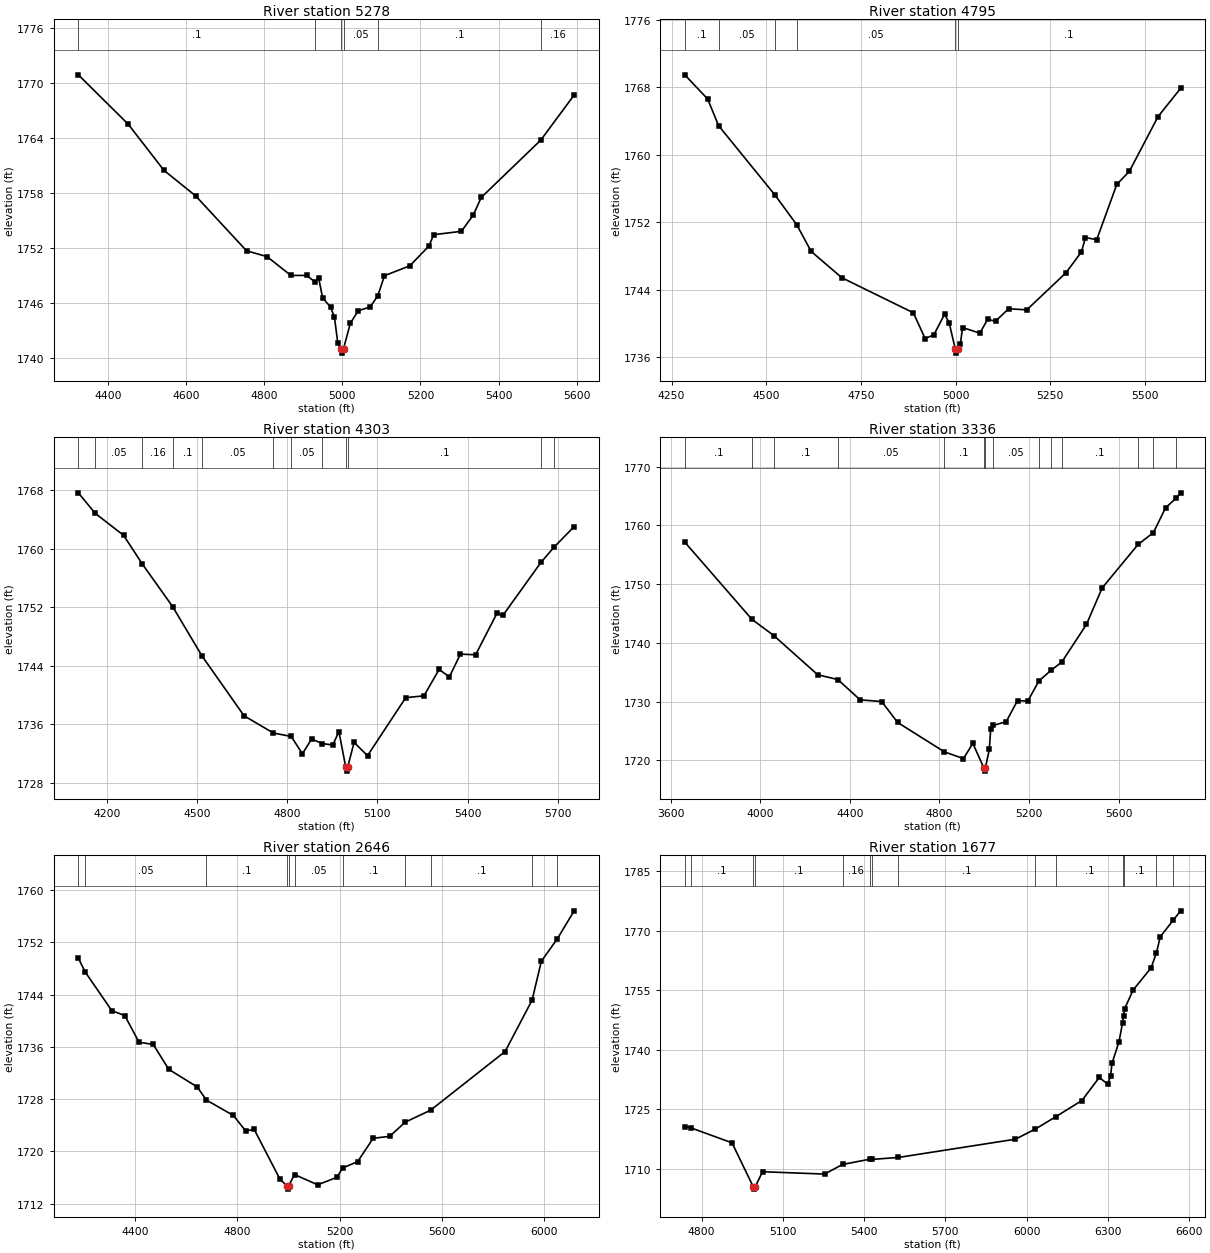
Type RM Length L Ch R = 1,5278,483,483,483
BEGIN DESCRIPTION:
UNT086 IN NNOGR 7.0
END DESCRIPTION:
XS GIS Cut Line= 2
      2810092.72     10086802.90      2811342.72     10086585.89
#Sta/Elev= 30
  4324.7 1770.91  4452.3 1765.53  4543.7 1760.50  4624.9 1757.71  4755.0 1751.73
  4807.6 1751.09  4868.5 1749.04  4909.1 1749.04  4929.8 1748.34  4939.5 1748.81
  4949.7 1746.59  4970.0 1745.60  4980.1 1744.48  4988.7 1741.63  4997.4 1741.07
  5000.2 1740.57  5003.4 1741.07  5020.7 1743.83  5041.0 1745.19  5071.5 1745.61
  5091.1 1746.83  5108.0 1749.01  5172.9 1750.09  5222.3 1752.27  5233.8 1753.48
  5304.9 1753.85  5335.3 1755.63  5355.6 1757.54  5507.9 1763.79  5593.4 1768.71
#Mann=6,-1,0
  4324.7     0.1       0  4929.8    0.05       0  4997.4    0.04       0
  5003.4    0.05       0  5091.1     0.1       0  5507.9    0.16       0
Bank Sta=4997.4,5003.4
Exp/Cntr=0.3,0.1

Type RM Length L Ch R = 1,4795,492,492,492
BEGIN DESCRIPTION:
UNT086 IN NNOGR 6.0
END DESCRIPTION:
XS GIS Cut Line= 2
      2810214.26     10087323.73      2811481.64     10086993.87
#Sta/Elev= 30
  4284.9 1769.50  4345.3 1766.63  4374.2 1763.47  4523.8 1755.21  4580.5 1751.73
  4618.6 1748.57  4699.6 1745.45  4888.6 1741.29  4919.6 1738.24  4942.7 1738.68
  4971.2 1741.13  4983.2 1740.10  4999.2 1737.01  5002.0 1736.51  5005.2 1737.01
  5012.6 1737.56  5018.6 1739.54  5064.2 1738.88  5084.9 1740.52  5105.6 1740.29
  5140.1 1741.77  5188.2 1741.64  5291.6 1746.03  5332.4 1748.50  5343.2 1750.21
  5372.9 1749.96  5425.9 1756.51  5459.1 1758.06  5534.9 1764.55  5594.5 1767.90
#Mann=6,-1,0
  4284.9     0.1       0  4374.2    0.05       0  4523.8     0.1       0
  4580.5    0.05       0  4999.2   0.035       0  5005.2     0.1       0
Bank Sta=4999.2,5005.2
Exp/Cntr=0.3,0.1

Type RM Length L Ch R = 1,4303,967,967,967
BEGIN DESCRIPTION:
UNT086 IN NNOGR 5.0
END DESCRIPTION:
XS GIS Cut Line= 2
      2810170.84     10087740.40      2811802.84     10087497.34
#Sta/Elev= 30
  4104.9 1767.68  4160.7 1764.89  4255.6 1761.86  4318.2 1757.92  4418.6 1752.12
  4516.8 1745.34  4656.4 1737.18  4753.7 1734.83  4813.2 1734.35  4850.7 1731.98
  4881.0 1734.00  4917.4 1733.38  4951.8 1733.18  4972.0 1735.03  4995.0 1730.11
  4997.7 1729.61  5001.0 1730.11  5022.5 1733.54  5067.3 1731.73  5194.4 1739.66
  5255.1 1739.91  5305.6 1743.53  5339.6 1742.49  5376.4 1745.62  5426.9 1745.52
  5497.7 1751.18  5517.9 1750.92  5644.2 1758.15  5688.5 1760.27  5754.9 1763.06
#Mann=12,-1,0
  4104.9     0.1       0  4160.7    0.05       0  4318.2    0.16       0
  4418.6     0.1       0  4516.8    0.05       0  4753.7     0.1       0
  4813.2    0.05       0  4917.4     0.1       0  4995.0    0.07       0
  5001.0     0.1       0  5644.2    0.05       0  5688.5     0.1       0
Bank Sta=4995,5001
Exp/Cntr=0.3,0.1

Type RM Length L Ch R = 1,3336,690,690,690
BEGIN DESCRIPTION:
UNT086 IN NNOGR 4.0
END DESCRIPTION:
XS GIS Cut Line= 2
      2810222.94     10088000.81      2812332.34     10088677.90
#Sta/Elev= 30
  3662.0 1757.16  3961.7 1744.02  4059.3 1741.26  4255.9 1734.57  4345.9 1733.76
  4445.4 1730.30  4541.7 1730.01  4613.0 1726.45  4822.0 1721.44  4907.1 1720.29
  4949.1 1722.89  4998.8 1718.66  5001.5 1718.16  5004.8 1718.66  5022.6 1721.85
  5028.7 1725.27  5040.2 1725.94  5098.1 1726.59  5148.7 1730.17  5194.5 1730.09
  5244.6 1733.55  5299.0 1735.34  5346.8 1736.76  5456.6 1743.14  5526.8 1749.36
  5687.5 1756.78  5755.8 1758.77  5809.9 1763.00  5858.0 1764.69  5877.4 1765.56
#Mann=14,-1,0
  3662.0     0.1       0  3961.7    0.05       0  4059.3     0.1       0
  4345.9    0.05       0  4822.0     0.1       0  4998.8    0.07       0
  5004.8     0.1       0  5040.2    0.05       0  5244.6     0.1       0
  5299.0    0.05       0  5346.8     0.1       0  5687.5    0.16       0
  5755.8     0.1       0  5858.0    0.05       0
Bank Sta=4998.8,5004.8
Exp/Cntr=0.3,0.1

Type RM Length L Ch R = 1,2646,969,969,969
BEGIN DESCRIPTION:
UNT086 IN NNOGR 3.0
END DESCRIPTION:
XS GIS Cut Line= 2
      2810248.97     10088764.70      2812165.39     10089042.19
#Sta/Elev= 30
  4179.5 1749.56  4206.7 1747.43  4310.3 1741.53  4360.9 1740.78  4416.7 1736.69
  4472.0 1736.37  4532.6 1732.55  4643.8 1729.86  4679.7 1727.85  4785.2 1725.49
  4833.2 1723.12  4866.1 1723.37  4967.1 1715.73  4994.4 1714.72  4997.2 1714.22
  5000.4 1714.72  5024.0 1716.45  5114.2 1714.88  5189.5 1716.03  5211.8 1717.46
  5270.3 1718.43  5330.9 1722.00  5395.3 1722.30  5456.2 1724.47  5555.2 1726.30
  5846.2 1735.28  5951.6 1743.14  5987.7 1749.09  6050.7 1752.56  6115.9 1756.81
#Mann=11,-1,0
  4179.5     0.1       0  4206.7    0.05       0  4679.7     0.1       0
  4994.4    0.07       0  5000.4     0.1       0  5024.0    0.05       0
  5211.8     0.1       0  5456.2    0.05       0  5555.2     0.1       0
  5951.6    0.05       0  6050.7     0.1       0
Bank Sta=4994.4,5000.4
Exp/Cntr=0.3,0.1

Type RM Length L Ch R = 1,1677,1489,1489,1489
BEGIN DESCRIPTION:
UNT086 IN NNOGR 2.0
END DESCRIPTION:
XS GIS Cut Line= 3
      2810518.14     10089528.60      2811151.78     10089667.48
      2812287.00     10089338.18
#Sta/Elev= 30
  4738.3 1720.58  4761.4 1720.27  4912.7 1716.50  4991.6 1705.32  4994.3 1704.82
  4997.6 1705.32  5025.3 1709.21  5254.2 1708.62  5320.9 1711.05  5422.3 1712.38
  5428.9 1712.32  5526.4 1712.81  5959.1 1717.42  6032.8 1719.99  6108.7 1723.12
  6204.5 1727.18  6268.6 1732.99  6299.8 1731.32  6310.2 1733.39  6315.6 1736.55
  6341.5 1742.02  6354.6 1746.79  6358.2 1748.45  6362.3 1750.34  6393.5 1755.06
  6460.3 1760.68  6479.9 1764.52  6493.8 1768.50  6541.7 1772.70  6569.0 1775.05
#Mann=14,-1,0
  4738.3    0.05       0  4761.4     0.1       0  4991.6    0.07       0
  4997.6     0.1       0  5320.9    0.16       0  5422.3     0.1       0
  5428.9    0.05       0  5526.4     0.1       0  6032.8    0.05       0
  6108.7     0.1       0  6354.6    0.05       0  6358.2     0.1       0
  6479.9    0.05       0  6541.7     0.1       0
Bank Sta=4991.6,4997.6
Exp/Cntr=0.3,0.1

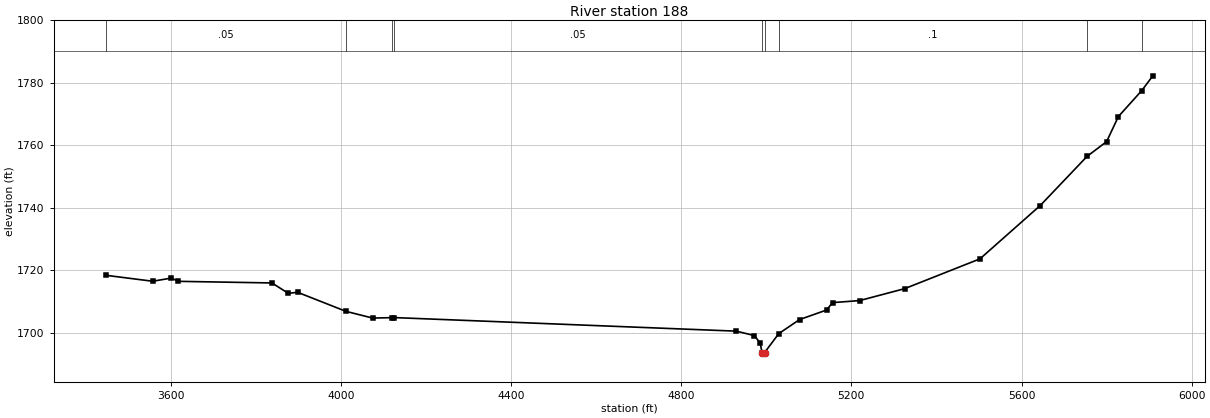
Type RM Length L Ch R = 1,188,0,0,0
BEGIN DESCRIPTION:
UNT086 IN NNOGR 1.0
END DESCRIPTION:
XS GIS Cut Line= 4
      2810474.67     10089728.23      2811542.40     10090292.48
      2811776.78     10090240.40      2812462.51     10089493.90
#Sta/Elev= 30
  3447.3 1718.38  3557.2 1716.48  3601.2 1717.49  3617.6 1716.45  3837.7 1715.93
  3876.1 1712.62  3898.1 1712.94  4011.9 1706.84  4074.2 1704.70  4121.1 1704.83
  4123.7 1704.86  4929.5 1700.51  4972.0 1699.10  4985.6 1696.68  4990.0 1693.66
  4992.7 1693.16  4996.0 1693.66  5029.3 1699.72  5078.1 1704.21  5141.6 1707.27
  5155.8 1709.64  5219.3 1710.29  5325.3 1714.11  5502.3 1723.64  5644.1 1740.71
  5754.3 1756.45  5800.1 1761.15  5827.8 1769.18  5882.7 1777.47  5908.7 1782.20
#Mann=9,-1,0
  3447.3    0.05       0  4011.9    0.16       0  4121.1     0.1       0
  4123.7    0.05       0  4990.0    0.04       0  4996.0    0.05       0
  5029.3     0.1       0  5754.3    0.16       0  5882.7    0.05       0
Bank Sta=4990,4996
Exp/Cntr=0.3,0.1

Chan Stop Cuts=-1