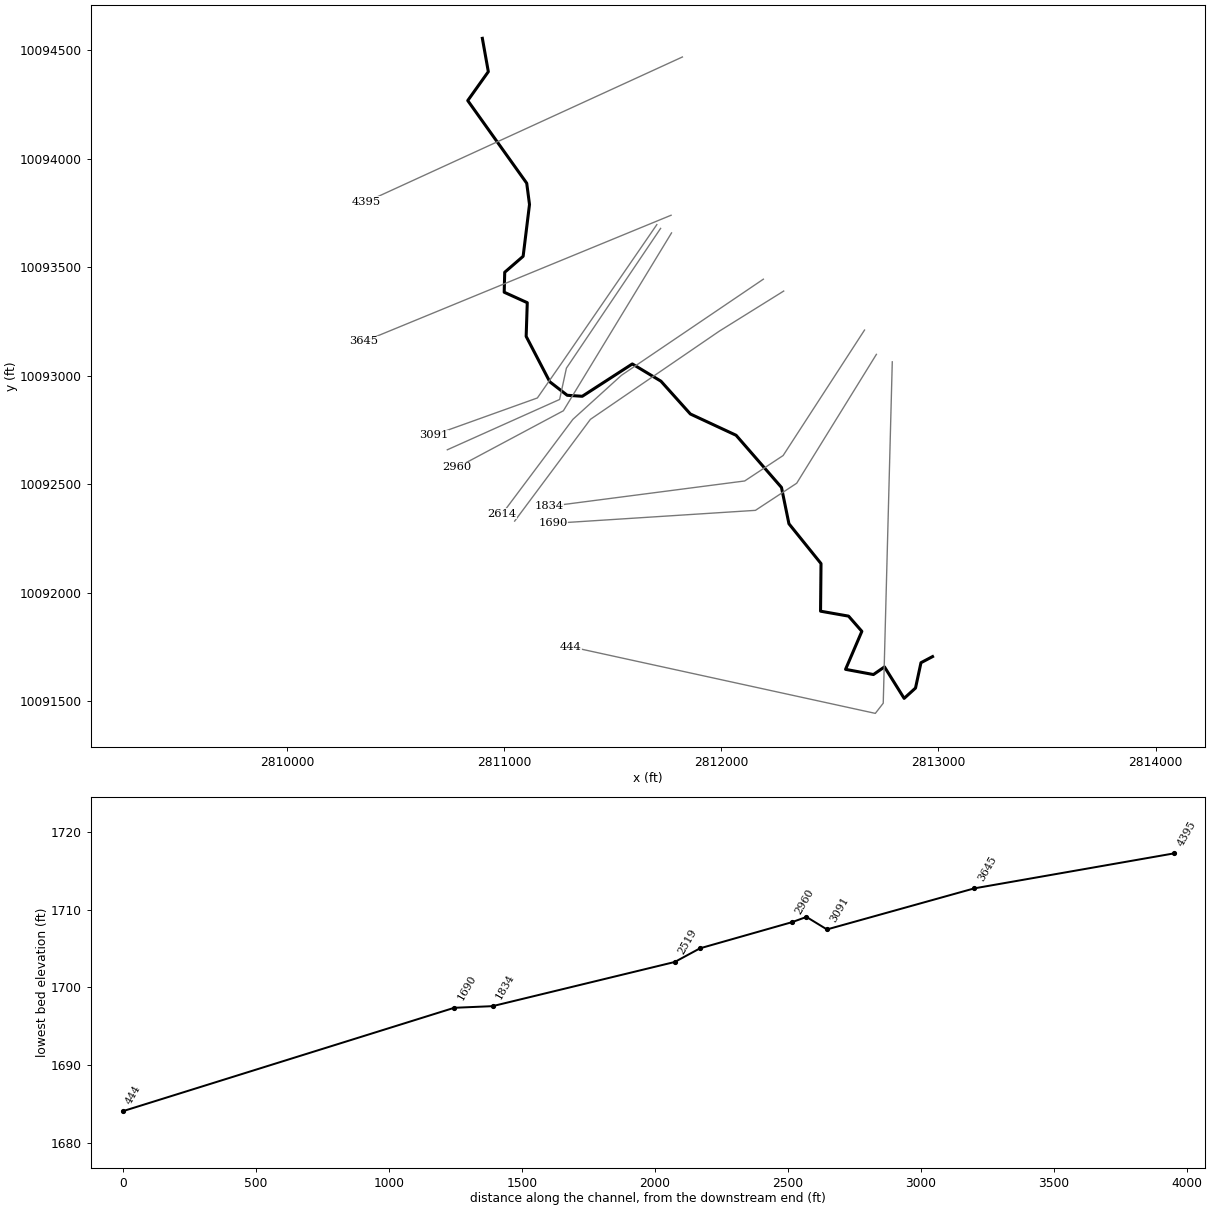
--- UNT087 IN NNOGR.prj (project) ---

Proj Title=UNT087 IN NNOGR Base Level Engineering
Current Plan=p01
Default Exp/Contr=0.3,0.1
English Units
Geom File=g01
Flow File=f01
Plan File=p01
Y Axis Title=Elevation
X Axis Title(PF)=Main Channel Distance
X Axis Title(XS)=Station
BEGIN DESCRIPTION:
UNT087 IN NNOGR
END DESCRIPTION:
DSS Export Rating Curves= 0
DSS Export Rating Curve Sorted= 0
DSS Export Volume Flow Curves= 0
DXF OffsetX= 0
DXF OffsetY= 0
DXF ScaleX= 1
DXF ScaleY= 10

--- UNT087 IN NNOGR.p01 (plan) ---

Plan Title=Multiple Run
Short Identifier=Multiple
Geom File=g01
Flow File=f01
Subcritical Flow
K Sum by GR= 0
Std Step Tol= 0.01
Critical Tol= 0.01
Num of Std Step Trials= 20
Max Error Tol= 0.3
Flow Tol Ratio= 0.001
Split Flow NTrial= 30
Split Flow Tol= 0.02
Split Flow Ratio= 0.02
Log Output Level= 0
Friction Slope Method= 1
Unsteady Friction Slope Method= 2
Unsteady Bridges Friction Slope Method= 1
Parabolic Critical Depth
Global Vel Dist=  1 , 1 , 1
Global Log Level= 0
CheckData=True
Encroach Param= -1, 0, 0, 0
BEGIN DESCRIPTION:
Multiple Run
END DESCRIPTION:

--- UNT087 IN NNOGR.f01 (steady flow) ---

Flow Title=Multiple
Program Version=4.10
Number of Profiles= 7
Profile Names=10-year,25-year,50-year,1pct_min,100-year,1pct_plu,500-year
River Rch & RM=UNT087 IN NNOGR,Reach-1         ,4395
    1054    1531    1946    1808    2445    3307    3878
Boundary for River Rch & Prof#=UNT087 IN NNOGR,Reach-1         , 1
Up Type= 0
Dn Type= 3
Dn Slope=0.01
Boundary for River Rch & Prof#=UNT087 IN NNOGR,Reach-1         , 2
Up Type= 0
Dn Type= 3
Dn Slope=0.01
Boundary for River Rch & Prof#=UNT087 IN NNOGR,Reach-1         , 3
Up Type= 0
Dn Type= 3
Dn Slope=0.01
Boundary for River Rch & Prof#=UNT087 IN NNOGR,Reach-1         , 4
Up Type= 0
Dn Type= 3
Dn Slope=0.01
Boundary for River Rch & Prof#=UNT087 IN NNOGR,Reach-1         , 5
Up Type= 0
Dn Type= 3
Dn Slope=0.01
Boundary for River Rch & Prof#=UNT087 IN NNOGR,Reach-1         , 6
Up Type= 0
Dn Type= 3
Dn Slope=0.01
Boundary for River Rch & Prof#=UNT087 IN NNOGR,Reach-1         , 7
Up Type= 0
Dn Type= 3
Dn Slope=0.01
DSS Import GetInterval= 0
DSS Import GetPeak= 0
DSS Import FillOption= 0

--- UNT087 IN NNOGR.g01 (geometry) ---

Geom Title=Existing Conditions
Program Version=4.10

River Reach=UNT087 IN NNOGR ,Reach-1
Reach XY= 30
      2810898.47     10094553.73      2810925.98     10094400.11
      2810831.19     10094266.96      2811102.91     10093886.13
      2811115.72     10093788.24      2811086.37     10093549.49
      2811001.55     10093475.89      2810999.13     10093383.92
      2811105.43      10093335.7       2811100.3     10093180.53
      2811209.25     10092971.21      2811289.38     10092909.15
      2811358.83     10092904.48      2811589.45     10093053.51
      2811721.34     10092974.06      2811856.88     10092822.89
      2812067.58     10092724.86      2812276.69      10092484.5
      2812311.04     10092317.14      2812458.84     10092133.75
      2812456.68     10091914.36      2812585.81     10091891.57
      2812647.01     10091821.48      2812571.92     10091646.41
      2812700.39     10091622.47      2812751.25     10091657.63
      2812841.88     10091512.66      2812894.24     10091560.27
      2812919.36     10091676.94      2812972.74     10091705.16

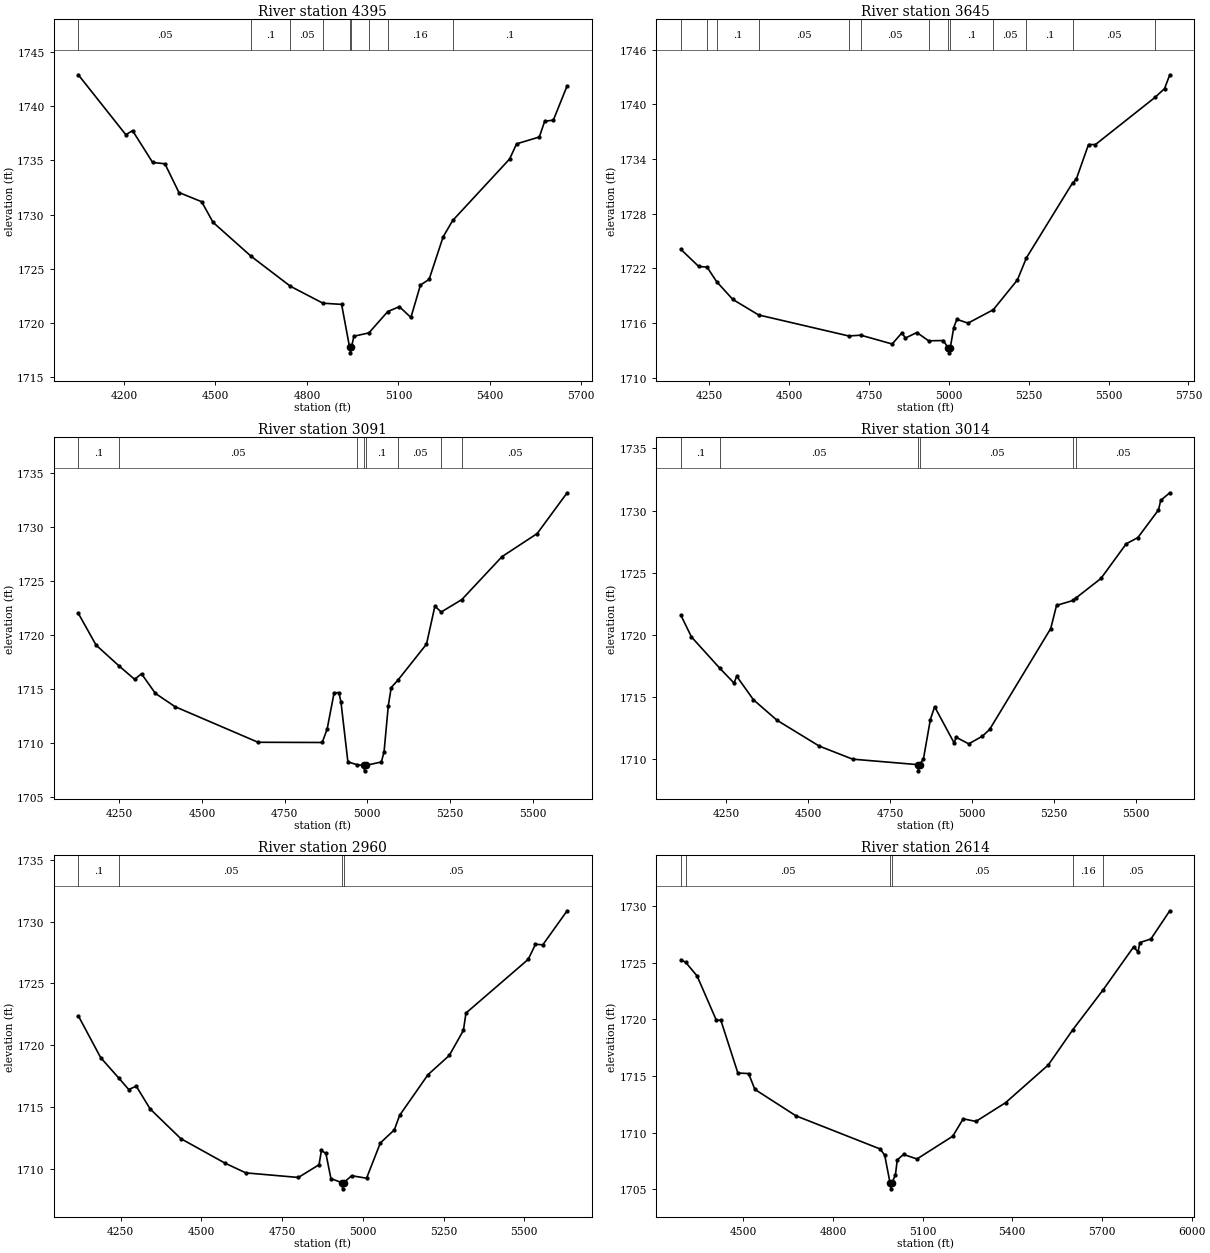
Type RM Length L Ch R = 1 ,4395    ,750,750,750
BEGIN DESCRIPTION:
UNT087 IN NNOGR 8.0
END DESCRIPTION:
XS GIS Cut Line= 2
      2811820.17     10094467.82      2810362.67      10093799.8
#Sta/Elev= 30
  4050.1 1742.89    4206 1737.36    4228 1737.74    4294  1734.8  4334.2 1734.68
  4380.2 1732.03  4454.7 1731.18    4492 1729.28  4617.2 1726.14  4745.9 1723.38
  4852.3 1721.82  4913.7 1721.71    4940 1717.74  4942.8 1717.24    4946 1717.74
    4954 1718.77  5003.2 1719.08  5065.2 1721.05  5103.2  1721.5    5141  1720.5
  5172.2 1723.49  5200.7 1724.02  5246.7 1727.94  5278.1 1729.45  5464.7 1735.12
  5487.7 1736.52  5562.2 1737.15  5579.7  1738.6  5608.2 1738.71  5653.4 1741.87
#Mann= 9 ,-1 , 0
  4050.1     .05       0  4617.2      .1       0  4745.9     .05       0
  4852.3      .1       0    4940     .07       0    4946      .1       0
  5003.2     .05       0  5065.2     .16       0  5278.1      .1       0
Bank Sta=4940,4946
XS Rating Curve= 0 ,0
Exp/Cntr=0.3,0.1

Type RM Length L Ch R = 1 ,3645    ,554,554,554
BEGIN DESCRIPTION:
Mapping XS 93b74610
END DESCRIPTION:
XS GIS Cut Line= 2
      2811768.05     10093738.64      2810353.31     10093157.12
#Sta/Elev= 30
  4161.9 1724.09  4217.6 1722.22  4243.6 1722.15  4273.7 1720.55  4324.3  1718.6
  4404.9  1716.9  4687.1 1714.59  4724.6 1714.68  4822.8 1713.71  4853.4 1714.94
  4864.2 1714.36  4900.1 1714.97  4936.9 1714.06  4983.2 1714.09  4998.4 1713.24
  5001.1 1712.74  5004.4 1713.24  5015.6 1715.52  5025.3 1716.42  5060.1    1716
  5139.2 1717.47  5214.7 1720.74    5243 1723.17  5387.3 1731.39  5398.7 1731.78
  5437.2  1735.6  5458.9  1735.6    5645 1740.77  5675.1 1741.74  5691.5 1743.26
#Mann= 13 ,-1 , 0
  4161.9      .1       0  4243.6     .05       0  4273.7      .1       0
  4404.9     .05       0  4687.1      .1       0  4724.6     .05       0
  4936.9      .1       0  4998.4     .07       0  5004.4      .1       0
  5139.2     .05       0    5243      .1       0  5387.3     .05       0
    5645      .1       0
Bank Sta=4998.4,5004.4
XS Rating Curve= 0 ,0
Exp/Cntr=0.3,0.1

Type RM Length L Ch R = 1 ,3091    ,77,77,77
BEGIN DESCRIPTION:
Mapping XS 7c06c687
END DESCRIPTION:
XS GIS Cut Line= 4
      2811702.36     10093695.42      2811263.14     10093056.54
      2811152.02     10092896.82      2810673.16     10092725.05
#Sta/Elev= 30
  4125.7 1722.01  4179.5 1719.07    4250 1717.12  4295.9 1715.91  4316.9 1716.42
  4358.8 1714.61  4418.4 1713.38  4669.4 1710.09  4863.5 1710.07  4878.4 1711.31
  4899.4 1714.66  4914.2 1714.68  4920.3 1713.78  4941.2 1708.27  4969.1 1708.02
  4988.9 1707.95  4991.6 1707.45  4994.9 1707.95  5042.5 1708.27  5050.6 1709.23
  5063.4 1713.48  5072.2 1715.15  5092.6 1715.84  5178.9 1719.16  5204.3 1722.67
  5223.4 1722.13  5285.8 1723.28  5407.4 1727.25  5513.7 1729.38  5604.3 1733.15
#Mann= 8 ,-1 , 0
  4125.7      .1       0    4250     .05       0  4969.1      .1       0
  4988.9     .07       0  4994.9      .1       0  5092.6     .05       0
  5223.4      .1       0  5285.8     .05       0
Bank Sta=4988.9,4994.9
XS Rating Curve= 0 ,0
Exp/Cntr=0.3,0.1

Type RM Length L Ch R = 1 ,3014    ,54,54,54
BEGIN DESCRIPTION:
Mapping XS 89f63fc6
END DESCRIPTION:
XS GIS Cut Line= 4
      2811719.72     10093678.05       2811285.7     10093033.97
      2811254.45     10092889.87      2810737.05     10092657.99
#Sta/Elev= 30
  4111.1 1721.57  4143.3 1719.83  4229.4 1717.32  4273.1 1716.12  4281.2 1716.67
  4332.2 1714.78  4404.1 1713.13  4533.1 1711.05  4634.8    1710  4832.9 1709.56
  4835.7 1709.06  4838.9 1709.56  4850.9 1710.03  4871.9 1713.18  4884.9 1714.22
  4944.9 1711.28    4950 1711.77    4989 1711.23  5030.7 1711.85  5052.7 1712.39
  5239.1 1720.51  5256.8 1722.37  5307.7 1722.77  5315.7 1722.96  5392.4 1724.54
  5469.2 1727.32    5505 1727.83  5567.8 1730.05  5574.6 1730.82  5602.2 1731.43
#Mann= 6 ,-1 , 0
  4111.1      .1       0  4229.4     .05       0  4832.9    .035       0
  4838.9     .05       0  5307.7      .1       0  5315.7     .05       0
Bank Sta=4832.9,4838.9
XS Rating Curve= 0 ,0
Exp/Cntr=0.3,0.1

Type RM Length L Ch R = 1 ,2960    ,346,346,346
BEGIN DESCRIPTION:
Mapping XS 76dfa75f
END DESCRIPTION:
XS GIS Cut Line= 3
      2811770.07     10093657.22      2811271.82     10092837.79
        2810782.     10092576.44
#Sta/Elev= 30
  4118.7 1722.38  4188.2 1718.99    4245 1717.32  4274.9 1716.42  4298.3 1716.69
  4341.2 1714.85  4436.2 1712.45  4573.7 1710.46  4637.7 1709.68  4800.4 1709.31
  4864.4 1710.34  4871.8 1711.49  4885.7 1711.25  4901.2 1709.22    4935 1708.89
  4937.7 1708.39    4941 1708.89  4965.4 1709.45  5011.6 1709.25  5054.3  1712.1
  5097.7 1713.16    5114 1714.33  5201.9 1717.62  5267.7 1719.17  5311.6  1721.2
  5319.5  1722.6  5512.2 1726.94  5534.9 1728.16  5557.6 1728.12  5632.9 1730.87
#Mann= 4 ,-1 , 0
  4118.7      .1       0    4245     .05       0    4935     .04       0
    4941     .05       0
Bank Sta=4935,4941
XS Rating Curve= 0 ,0
Exp/Cntr=0.3,0.1

Type RM Length L Ch R = 1 ,2614    ,95,95,95
BEGIN DESCRIPTION:
Mapping XS 488cbf21
END DESCRIPTION:
XS GIS Cut Line= 4
       2812193.2     10093444.06      2811539.52     10093001.33
      2811315.57     10092798.21      2810990.03     10092363.29
#Sta/Elev= 30
  4291.7 1725.27  4307.7 1725.04  4345.7 1723.84  4410.2 1719.92  4425.1 1719.93
  4482.1 1715.26    4518 1715.21    4539 1713.81  4676.8 1711.47  4958.3 1708.54
  4973.3 1707.99  4991.3 1705.52    4994 1705.02  4997.3 1705.52  5009.2 1706.27
  5015.3 1707.58  5036.3 1708.06  5081.2 1707.66  5200.8 1709.67  5235.9 1711.21
  5278.5 1710.98  5377.8 1712.64  5520.4 1715.97    5602 1719.07  5703.3 1722.59
  5805.9 1726.41  5820.5 1725.96  5826.7 1726.79  5863.8 1727.11  5926.8  1729.6
#Mann= 6 ,-1 , 0
  4291.7      .1       0  4307.7     .05       0  4991.3     .04       0
  4997.3     .05       0    5602     .16       0  5703.3     .05       0
Bank Sta=4991.3,4997.3
XS Rating Curve= 0 ,0
Exp/Cntr=0.3,0.1

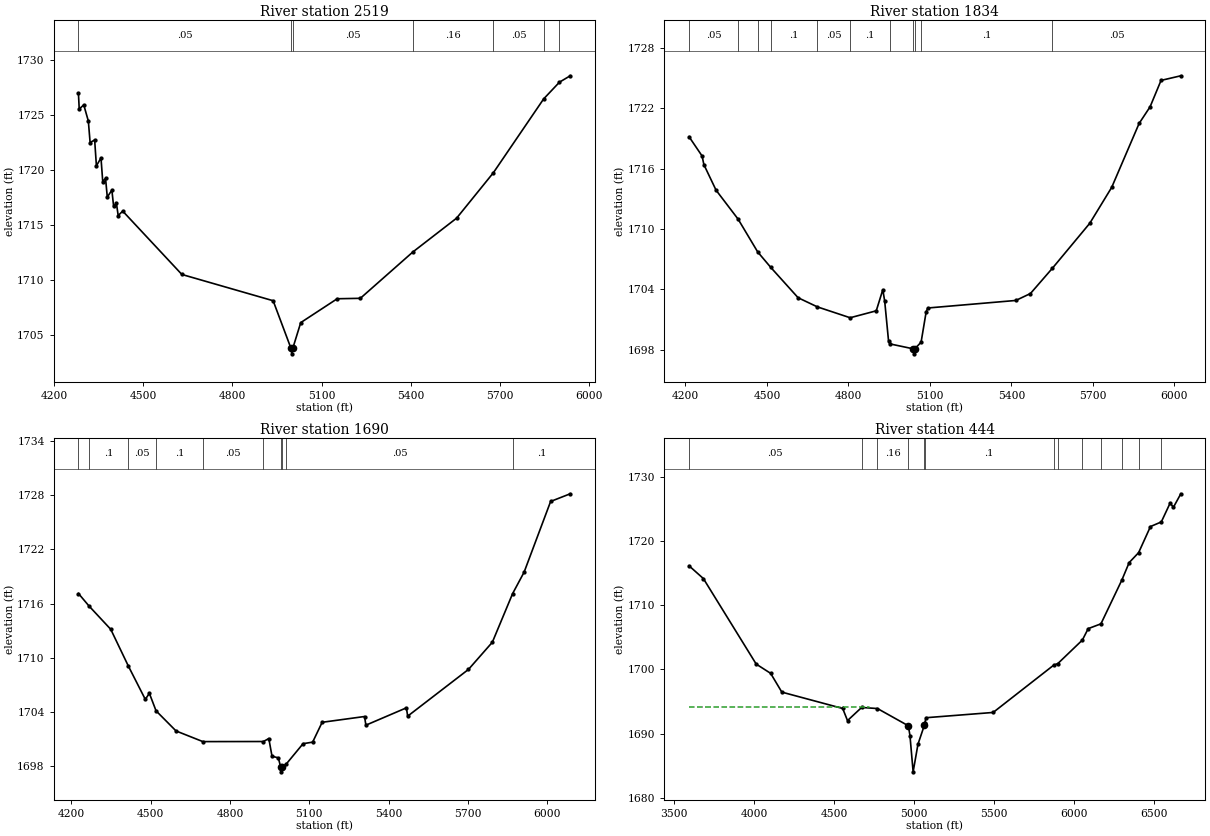
Type RM Length L Ch R = 1 ,2519    ,685,685,685
BEGIN DESCRIPTION:
UNT087 IN NNOGR 3.0
END DESCRIPTION:
XS GIS Cut Line= 4
       2812286.9     10093389.34      2811990.05     10093204.46
       2811396.3     10092798.21      2811047.36     10092329.48
#Sta/Elev= 30
  4282.4 1726.95    4285 1725.53  4300.3  1725.9  4315.7 1724.43  4321.6 1722.48
  4336.9 1722.71  4342.8 1720.36  4358.2 1721.08  4364.1 1718.92  4373.5 1719.22
  4379.4 1717.52  4394.8 1718.15  4400.7 1716.67  4410.1 1716.95    4416 1715.84
  4431.3 1716.24  4630.1 1710.48    4937 1708.09    4997 1703.76  4999.8 1703.26
    5003 1703.76  5029.8  1706.1  5152.4 1708.27  5230.2 1708.31    5407 1712.53
  5553.8  1715.6  5677.4 1719.73  5846.6 1726.45  5899.7 1727.97  5935.9 1728.55
#Mann= 7 ,-1 , 0
  4282.4     .05       0    4997     .04       0    5003     .05       0
    5407     .16       0  5677.4     .05       0  5846.6      .1       0
  5899.7     .05       0
Bank Sta=4997,5003
XS Rating Curve= 0 ,0
Exp/Cntr=0.3,0.1

Type RM Length L Ch R = 1 ,1834    ,144,144,144
BEGIN DESCRIPTION:
UNT087 IN NNOGR 2.0
END DESCRIPTION:
XS GIS Cut Line= 4
       2812659.3     10093209.64      2812284.32     10092631.54
      2812107.23     10092514.35      2811206.23     10092397.17
#Sta/Elev= 30
  4213.3 1719.17  4261.4 1717.25    4268 1716.39  4312.8 1713.85  4393.9 1710.97
  4466.2  1707.7  4514.4 1706.16  4614.8 1703.15  4685.8 1702.24  4806.3 1701.16
  4902.4 1701.85  4926.5 1703.95  4933.4 1702.82  4947.5 1698.88  4952.4 1698.56
  5038.3 1698.07    5041 1697.57  5044.3 1698.07  5067.4 1698.73    5086 1701.74
  5091.9 1702.13    5416 1702.88  5469.9 1703.57  5550.8 1706.09  5688.3 1710.56
  5768.9 1714.13  5869.8 1720.49  5910.1 1722.14  5950.5 1724.77  6023.3 1725.23
#Mann= 11 ,-1 , 0
  4213.3     .05       0  4393.9      .1       0  4466.2     .05       0
  4514.4      .1       0  4685.8     .05       0  4806.3      .1       0
  4952.4     .05       0  5038.3    .035       0  5044.3     .05       0
  5067.4      .1       0  5550.8     .05       0
Bank Sta=5038.3,5044.3
XS Rating Curve= 0 ,0
Exp/Cntr=0.3,0.1

Type RM Length L Ch R = 1 ,1690    ,1246,1246,1246
BEGIN DESCRIPTION:
Mapping XS 55faf497
END DESCRIPTION:
XS GIS Cut Line= 4
      2812713.98     10093097.65      2812346.82     10092503.94
      2812156.71     10092378.94      2811224.43     10092319.04
#Sta/Elev= 30
  4227.2 1717.12    4267 1715.74  4349.4 1713.15  4416.3 1709.06    4480 1705.39
  4495.4 1706.06  4520.7 1704.12  4596.3 1701.89  4697.7 1700.71  4926.7 1700.72
  4947.1 1701.05  4959.2 1699.09  4983.1 1698.91  4992.2 1697.86    4995 1697.36
  4998.2 1697.86  5012.9 1698.22  5076.6 1700.48  5112.8 1700.65  5148.8 1702.85
  5309.1 1703.49  5314.2 1702.53  5467.3 1704.45  5472.3 1703.53  5702.2 1708.71
  5792.4 1711.72  5869.1 1717.11  5912.6 1719.49  6012.8 1727.32    6087 1728.17
#Mann= 10 ,-1 , 0
  4227.2     .05       0    4267      .1       0  4416.3     .05       0
  4520.7      .1       0  4697.7     .05       0  4926.7      .1       0
  4992.2     .07       0  4998.2      .1       0  5012.9     .05       0
  5869.1      .1       0
Bank Sta=4992.2,4998.2
XS Rating Curve= 0 ,0
Exp/Cntr=0.3,0.1

Type RM Length L Ch R = 1 ,444     ,0,0,0
BEGIN DESCRIPTION:
UNT087 IN NNOGR 1.0
END DESCRIPTION:
XS GIS Cut Line= 4
      2812787.19     10093063.28      2812745.53      10091490.4
      2812709.07     10091443.52      2811303.16     10091750.74
#Sta/Elev= 30
  3594.3 1716.17  3683.9 1714.18    4014 1700.84    4104  1699.4    4174 1696.47
  4554.2 1693.92  4584.2 1692.03  4672.5 1694.08  4771.5 1693.91  4964.3 1691.22
  4974.3  1689.7  4994.1 1684.04  5024.3 1688.34  5064.4 1691.31  5066.9  1691.6
  5074.4 1692.48  5493.9  1693.3  5871.4 1700.66  5898.3 1700.93  6051.2 1704.59
  6087.6 1706.37  6167.2 1707.12  6298.1 1713.96  6343.5 1716.67  6402.6 1718.22
  6476.5 1722.29  6544.3 1723.01  6599.4 1725.95  6619.8 1725.29  6666.2  1727.4
#Mann= 13 ,-1 , 0
  3594.3     .05       0  4672.5      .1       0  4771.5     .16       0
  4964.3     .07       0  5064.4     .16       0  5066.9      .1       0
  5871.4     .05       0  5898.3      .1       0  6051.2     .05       0
  6167.2     .16       0  6298.1      .1       0  6402.6     .05       0
  6544.3      .1       0
#XS Ineff= 2 , 0
         4721.03 1694.17
Permanent Ineff=
       F       F
Bank Sta=4964.3,5064.4
XS Rating Curve= 0 ,0
Exp/Cntr=0.3,0.1

Chan Stop Cuts=-1
Use User Specified Reach Order=0
Composite Channel Slope=5