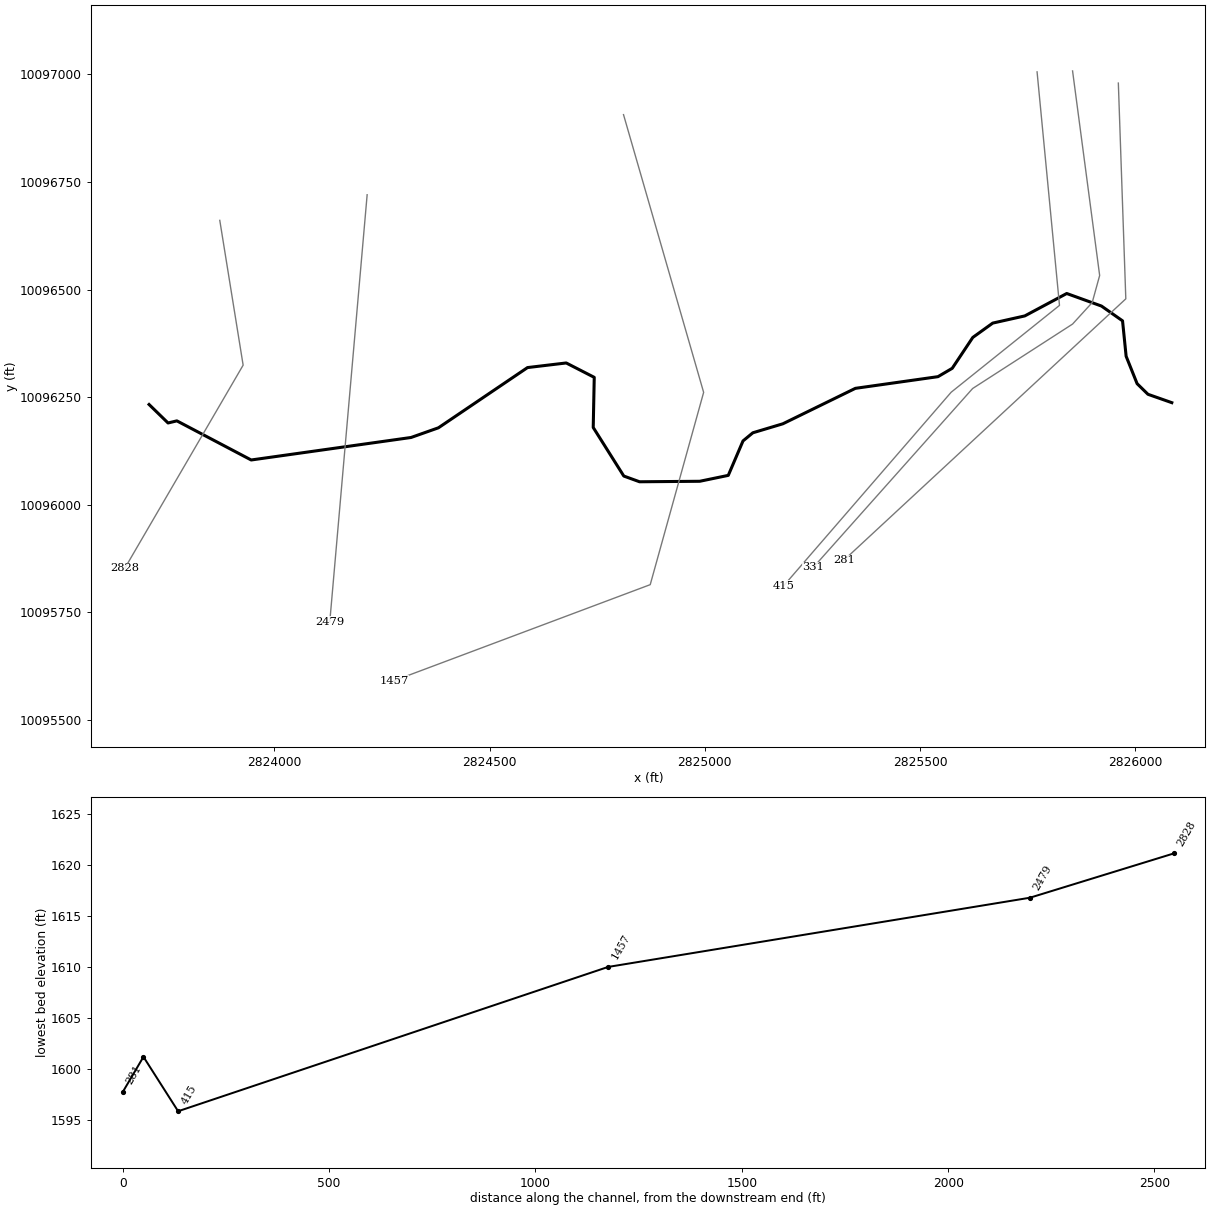
--- UNT089 IN NNOGR.prj (project) ---

Proj Title=UNT089 IN NNOGR Base Level Engineering
Current Plan=p01
Default Exp/Contr=0.3,0.1
English Units
Geom File=g01
Flow File=f01
Plan File=p01
BEGIN DESCRIPTION:
UNT089 IN NNOGR
END DESCRIPTION:

--- UNT089 IN NNOGR.p01 (plan) ---

Plan Title=Multiple Run
Short Identifier=Multiple
Geom File=g01
Flow File=f01
Subcritical Flow
K Sum by GR= 0
Std Step Tol= 0.01
Critical Tol= 0.01
Num of Std Step Trials= 20
Max Error Tol= 0.3
Flow Tol Ratio= 0.001
Split Flow NTrial= 30
Split Flow Tol= 0.02
Split Flow Ratio= 0.02
Log Output Level= 0
Friction Slope Method= 1
Unsteady Friction Slope Method= 2
Unsteady Bridges Friction Slope Method= 1
Parabolic Critical Depth
Global Vel Dist=  1 , 1 , 1
Global Log Level= 0
CheckData=True
Encroach Param= -1, 0, 0, 0
BEGIN DESCRIPTION:
Multiple Run
END DESCRIPTION:

--- UNT089 IN NNOGR.f01 (steady flow) ---

Flow Title=Multiple
Number of Profiles=7
Profile Names=10-year,25-year,50-year,1pct_min,100-year,1pct_plu,500-year
River Rch & RM= UNT089 IN NNOGR,Reach-1,2828
     467     646     793     715     966    1307    1437
Boundary for River Rch & Prof#=UNT089 IN NNOGR,Reach-1,1
Up Type=0
Dn Type=3
Dn Slope=0.005
Boundary for River Rch & Prof#=UNT089 IN NNOGR,Reach-1,2
Up Type=0
Dn Type=3
Dn Slope=0.005
Boundary for River Rch & Prof#=UNT089 IN NNOGR,Reach-1,3
Up Type=0
Dn Type=3
Dn Slope=0.005
Boundary for River Rch & Prof#=UNT089 IN NNOGR,Reach-1,4
Up Type=0
Dn Type=3
Dn Slope=0.005
Boundary for River Rch & Prof#=UNT089 IN NNOGR,Reach-1,5
Up Type=0
Dn Type=3
Dn Slope=0.005
Boundary for River Rch & Prof#=UNT089 IN NNOGR,Reach-1,6
Up Type=0
Dn Type=3
Dn Slope=0.005
Boundary for River Rch & Prof#=UNT089 IN NNOGR,Reach-1,7
Up Type=0
Dn Type=3
Dn Slope=0.005

--- UNT089 IN NNOGR.g01 (geometry) ---

Geom Title=Existing Conditions

River Reach=UNT089 IN NNOGR,Reach-1
Reach XY= 30
      2823708.68     10096233.18      2823752.81     10096190.21
      2823773.31     10096195.12      2823945.97     10096104.23
      2824317.33     10096156.49      2824381.00     10096179.00
      2824587.97     10096318.93      2824677.90     10096329.65
      2824743.01     10096296.22      2824740.65     10096179.71
      2824811.68     10096066.91      2824848.27     10096053.61
      2824988.15     10096054.76      2825054.42     10096068.47
      2825088.66     10096148.52      2825111.52     10096167.43
      2825181.25     10096188.32      2825349.73     10096270.68
      2825541.62     10096297.81      2825574.76     10096317.25
      2825622.53     10096388.96      2825668.88     10096422.29
      2825743.36     10096438.96      2825840.76     10096491.04
      2825921.49     10096461.87      2825970.45     10096427.50
      2825978.78     10096345.21      2826004.27     10096281.56
      2826029.52     10096256.85      2826084.92     10096237.39

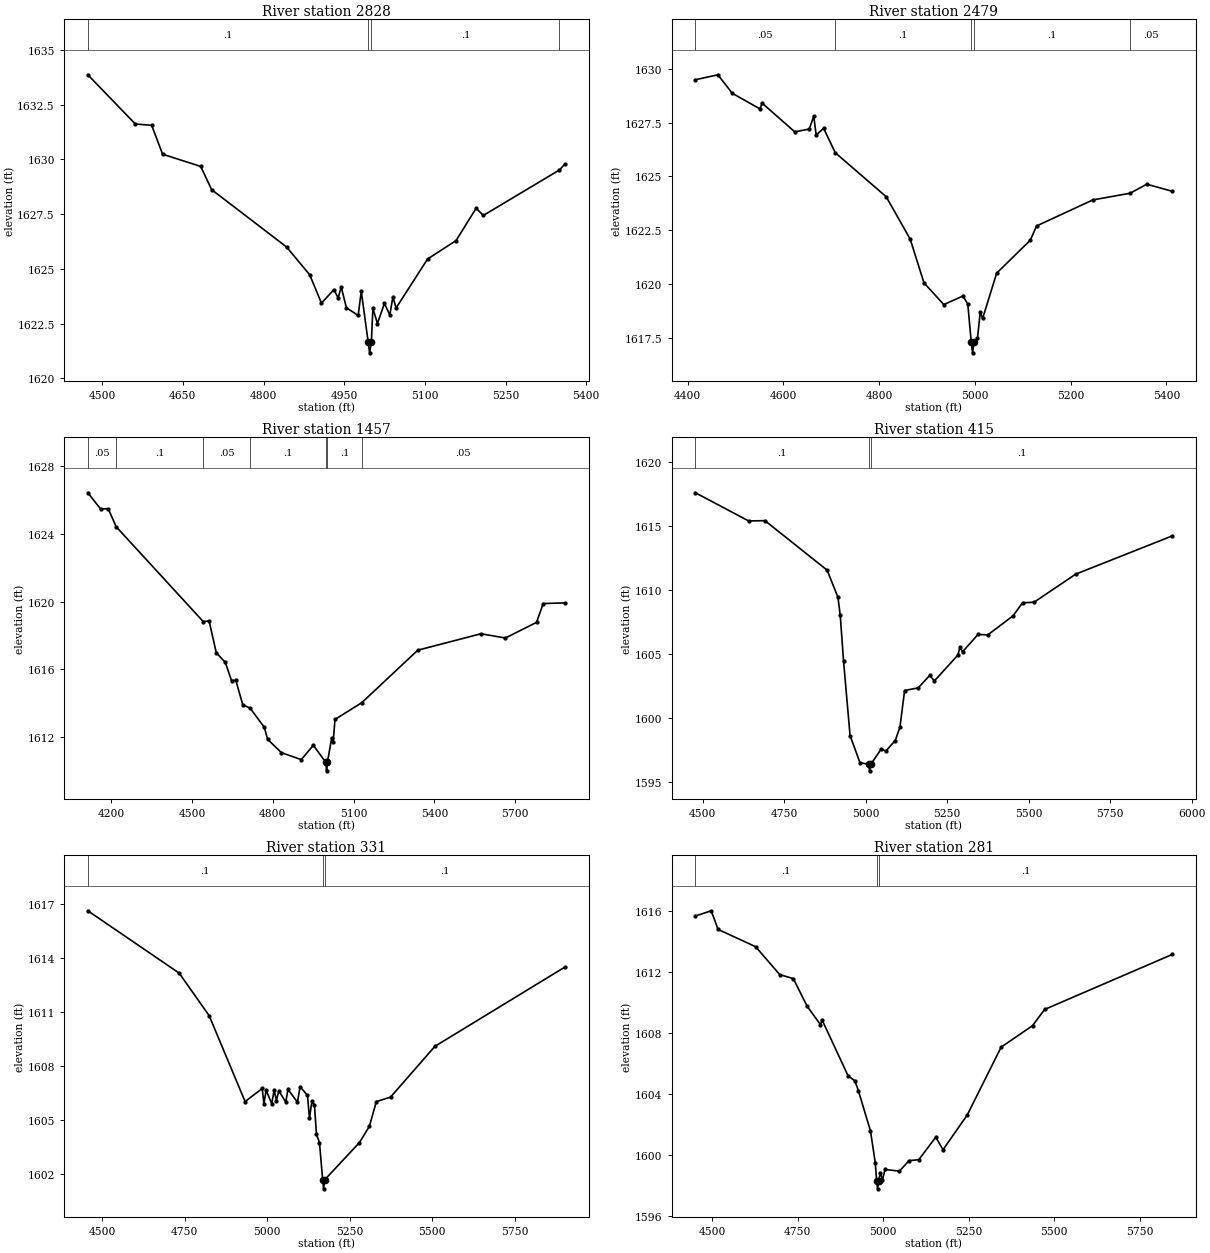
Type RM Length L Ch R = 1,2828,349,349,349
BEGIN DESCRIPTION:
UNT089 IN NNOGR 3.0
END DESCRIPTION:
XS GIS Cut Line= 3
      2823873.00     10096660.94      2823927.26     10096324.54
      2823652.54     10095852.97
#Sta/Elev= 30
  4473.4 1633.87  4561.7 1631.62  4592.1 1631.56  4612.4 1630.24  4683.3 1629.68
  4703.5 1628.62  4842.8 1626.00  4885.8 1624.73  4907.7 1623.43  4930.8 1624.05
  4938.7 1623.67  4944.5 1624.17  4954.0 1623.22  4976.0 1622.87  4981.7 1623.98
  4994.5 1621.66  4997.2 1621.16  5000.5 1621.66  5003.3 1623.19  5011.8 1622.50
  5024.8 1623.42  5034.7 1622.89  5040.5 1623.71  5046.5 1623.21  5105.0 1625.45
  5157.9 1626.29  5195.2 1627.77  5208.6 1627.44  5350.2 1629.52  5359.9 1629.78
#Mann=4,-1,0
  4473.4     0.1       0  4994.5    0.07       0  5000.5     0.1       0
  5350.2    0.05       0
Bank Sta=4994.5,5000.5
Exp/Cntr=0.3,0.1

Type RM Length L Ch R = 1,2479,1022,1022,1022
BEGIN DESCRIPTION:
Mapping XS b0d6b147
END DESCRIPTION:
XS GIS Cut Line= 2
      2824215.39     10096720.48      2824128.57     10095728.27
#Sta/Elev= 30
  4416.4 1629.49  4463.3 1629.72  4493.4 1628.86  4550.9 1628.14  4555.9 1628.40
  4623.9 1627.07  4654.1 1627.20  4663.5 1627.80  4668.5 1626.93  4684.2 1627.23
  4708.5 1626.10  4814.7 1624.06  4864.9 1622.09  4893.7 1620.06  4935.1 1619.05
  4975.3 1619.45  4985.3 1619.06  4992.4 1617.31  4995.1 1616.81  4998.4 1617.31
  5005.4 1617.48  5011.2 1618.70  5016.3 1618.41  5045.5 1620.51  5115.8 1622.04
  5128.8 1622.70  5246.4 1623.91  5324.3 1624.22  5359.0 1624.64  5412.4 1624.31
#Mann=5,-1,0
  4416.4    0.05       0  4708.5     0.1       0  4992.4    0.07       0
  4998.4     0.1       0  5324.3    0.05       0
Bank Sta=4992.4,4998.4
Exp/Cntr=0.3,0.1

Type RM Length L Ch R = 1,1457,1042,1042,1042
BEGIN DESCRIPTION:
UNT089 IN NNOGR 2.0
END DESCRIPTION:
XS GIS Cut Line= 4
      2824811.04     10096906.57      2824997.18     10096261.31
      2824873.08     10095814.58      2824277.41     10095591.20
#Sta/Elev= 30
  4112.8 1626.41  4160.1 1625.46  4188.6 1625.47  4218.0 1624.41  4542.0 1618.81
  4563.3 1618.86  4589.9 1616.98  4623.6 1616.41  4646.5 1615.34  4662.5 1615.36
  4688.2 1613.92  4716.0 1613.71  4768.6 1612.58  4780.5 1611.88  4832.1 1611.09
  4905.8 1610.68  4950.4 1611.53  4996.8 1610.52  4999.6 1610.02  5002.8 1610.52
  5018.9 1611.98  5024.1 1611.71  5030.9 1613.05  5130.5 1614.04  5338.4 1617.13
  5573.0 1618.10  5663.8 1617.85  5779.5 1618.77  5804.4 1619.88  5884.2 1619.92
#Mann=7,-1,0
  4112.8    0.05       0  4218.0     0.1       0  4542.0    0.05       0
  4716.0     0.1       0  4996.8    0.07       0  5002.8     0.1       0
  5130.5    0.05       0
Bank Sta=4996.8,5002.8
Exp/Cntr=0.3,0.1

Type RM Length L Ch R = 1,415,84,84,84
BEGIN DESCRIPTION:
Mapping XS cd5bf88b
END DESCRIPTION:
XS GIS Cut Line= 4
      2825771.87     10097005.98      2825823.96     10096463.43
      2825572.22     10096261.60      2825182.54     10095811.30
#Sta/Elev= 30
  4477.5 1617.60  4640.5 1615.40  4690.7 1615.42  4881.6 1611.55  4914.8 1609.42
  4921.8 1608.01  4931.8 1604.48  4951.9 1598.62  4982.1 1596.51  5009.2 1596.36
  5011.9 1595.86  5015.2 1596.36  5047.4 1597.56  5061.8 1597.41  5090.6 1598.23
  5105.0 1599.29  5119.3 1602.14  5161.1 1602.35  5196.3 1603.32  5210.7 1602.89
  5282.7 1604.91  5289.1 1605.54  5297.1 1605.17  5344.4 1606.52  5374.7 1606.49
  5452.5 1607.99  5481.0 1609.00  5516.2 1609.04  5644.4 1611.24  5940.7 1614.23
#Mann=3,-1,0
  4477.5     0.1       0  5009.2    0.07       0  5015.2     0.1       0
Bank Sta=5009.2,5015.2
Exp/Cntr=0.3,0.1

Type RM Length L Ch R = 1,331,50,50,50
BEGIN DESCRIPTION:
Mapping XS f3d10d22
END DESCRIPTION:
XS GIS Cut Line= 6
      2825854.33     10097008.18      2825917.27     10096532.87
      2825899.91     10096469.94      2825854.34     10096420.02
      2825622.13     10096270.28      2825252.23     10095854.95
#Sta/Elev= 30
  4456.8 1616.63  4733.6 1613.17  4824.4 1610.81  4933.3 1606.04  4985.1 1606.77
  4990.3 1605.92  4997.0 1606.67  5013.9 1605.93  5021.3 1606.68  5028.1 1606.10
  5035.5 1606.64  5056.5 1606.01  5063.2 1606.72  5092.0 1606.01  5099.9 1606.87
  5122.3 1606.38  5128.3 1605.12  5135.6 1606.05  5143.4 1605.86  5149.4 1604.23
  5158.6 1603.77  5168.3 1601.70  5171.1 1601.20  5174.3 1601.70  5279.4 1603.76
  5309.8 1604.67  5330.9 1606.04  5373.9 1606.29  5508.5 1609.11  5901.6 1613.50
#Mann=3,-1,0
  4456.8     0.1       0  5168.3    0.07       0  5174.3     0.1       0
Bank Sta=5168.3,5174.3
Exp/Cntr=0.3,0.1

Type RM Length L Ch R = 1,281,0,0,0
BEGIN DESCRIPTION:
UNT089 IN NNOGR 1.0
END DESCRIPTION:
XS GIS Cut Line= 3
      2825960.68     10096979.91      2825978.04     10096478.62
      2825323.04     10095871.34
#Sta/Elev= 30
  4450.5 1615.65  4496.7 1615.99  4516.7 1614.77  4626.8 1613.63  4696.8 1611.81
  4736.9 1611.54  4776.9 1609.74  4816.0 1608.53  4821.0 1608.83  4896.9 1605.17
  4917.0 1604.84  4927.0 1604.20  4962.5 1601.55  4976.7 1599.44  4980.5 1598.26
  4983.2 1597.76  4986.5 1598.26  4990.8 1598.82  4997.6 1598.36  5005.0 1599.03
  5047.0 1598.92  5075.3 1599.61  5103.7 1599.67  5153.5 1601.15  5174.5 1600.32
  5245.4 1602.60  5344.6 1607.05  5436.5 1608.46  5471.6 1609.52  5845.3 1613.13
#Mann=3,-1,0
  4450.5     0.1       0  4980.5    0.07       0  4986.5     0.1       0
Bank Sta=4980.5,4986.5
Exp/Cntr=0.3,0.1

Chan Stop Cuts=-1