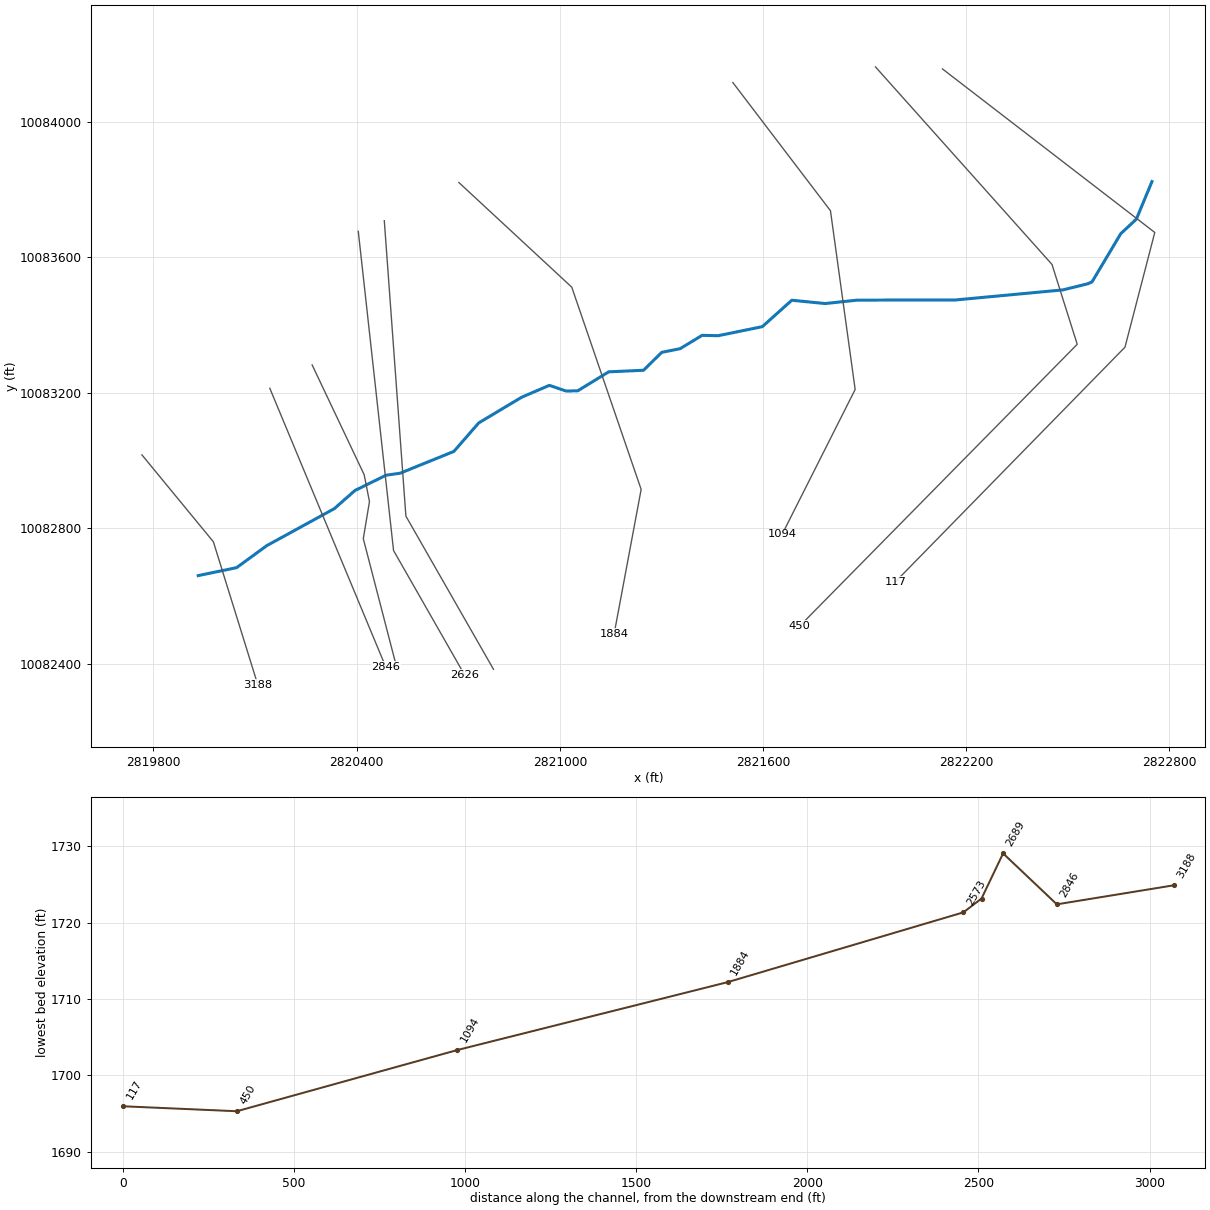
--- UNT091 IN NNOGR.prj (project) ---

Proj Title=UNT091 IN NNOGR Base Level Engineering
Current Plan=p01
Default Exp/Contr=0.3,0.1
English Units
Geom File=g01
Flow File=f01
Plan File=p01
Y Axis Title=Elevation
X Axis Title(PF)=Main Channel Distance
X Axis Title(XS)=Station
BEGIN DESCRIPTION:
UNT091 IN NNOGR
END DESCRIPTION:
DSS Export Rating Curves= 0
DSS Export Rating Curve Sorted= 0
DSS Export Volume Flow Curves= 0
DXF OffsetX= 0
DXF OffsetY= 0
DXF ScaleX= 1
DXF ScaleY= 10

--- UNT091 IN NNOGR.p01 (plan) ---

Plan Title=Multiple Run
Short Identifier=Multiple
Geom File=g01
Flow File=f01
Subcritical Flow
K Sum by GR= 0
Std Step Tol= 0.01
Critical Tol= 0.01
Num of Std Step Trials= 20
Max Error Tol= 0.3
Flow Tol Ratio= 0.001
Split Flow NTrial= 30
Split Flow Tol= 0.02
Split Flow Ratio= 0.02
Log Output Level= 0
Friction Slope Method= 1
Unsteady Friction Slope Method= 2
Unsteady Bridges Friction Slope Method= 1
Parabolic Critical Depth
Global Vel Dist=  1 , 1 , 1
Global Log Level= 0
CheckData=True
Encroach Param= -1, 0, 0, 0
BEGIN DESCRIPTION:
Multiple Run
END DESCRIPTION:

--- UNT091 IN NNOGR.f01 (steady flow) ---

Flow Title=Multiple
Program Version=4.10
Number of Profiles= 7
Profile Names=10-year,25-year,50-year,1pct_min,100-year,1pct_plu,500-year
River Rch & RM=UNT091 IN NNOGR,Reach-1         ,3188
     884    1282    1628    1514    2047    2769    3250
Boundary for River Rch & Prof#=UNT091 IN NNOGR,Reach-1         , 1
Up Type= 0
Dn Type= 3
Dn Slope=0.013
Boundary for River Rch & Prof#=UNT091 IN NNOGR,Reach-1         , 2
Up Type= 0
Dn Type= 3
Dn Slope=0.013
Boundary for River Rch & Prof#=UNT091 IN NNOGR,Reach-1         , 3
Up Type= 0
Dn Type= 3
Dn Slope=0.013
Boundary for River Rch & Prof#=UNT091 IN NNOGR,Reach-1         , 4
Up Type= 0
Dn Type= 3
Dn Slope=0.013
Boundary for River Rch & Prof#=UNT091 IN NNOGR,Reach-1         , 5
Up Type= 0
Dn Type= 3
Dn Slope=0.013
Boundary for River Rch & Prof#=UNT091 IN NNOGR,Reach-1         , 6
Up Type= 0
Dn Type= 3
Dn Slope=0.013
Boundary for River Rch & Prof#=UNT091 IN NNOGR,Reach-1         , 7
Up Type= 0
Dn Type= 3
Dn Slope=0.013
DSS Import GetInterval= 0
DSS Import GetPeak= 0
DSS Import FillOption= 0

--- UNT091 IN NNOGR.g01 (geometry) ---

Geom Title=Existing Conditions
Program Version=4.10

River Reach=UNT091 IN NNOGR ,Reach-1
Reach XY= 30
      2819932.16     10082660.21      2820045.58     10082683.73
      2820134.56     10082748.67      2820334.22     10082858.04
      2820394.98     10082911.51      2820486.99     10082956.65
      2820528.31     10082962.56      2820687.19     10083026.96
       2820760.4     10083111.04      2820887.69     10083187.21
      2820968.84     10083221.99      2821018.35     10083205.23
      2821052.82      10083205.9      2821144.31     10083261.94
      2821247.07     10083266.55      2821300.78     10083319.42
      2821355.13     10083330.28       2821420.1     10083369.67
      2821467.51     10083368.66      2821597.82     10083395.29
      2821684.91     10083473.32      2821783.44     10083463.56
      2821878.06     10083473.67      2822168.57     10083474.19
      2822485.23     10083503.82      2822559.25       10083522.
      2822571.65     10083527.76      2822656.33     10083669.98
      2822702.18     10083712.57      2822748.47     10083823.73

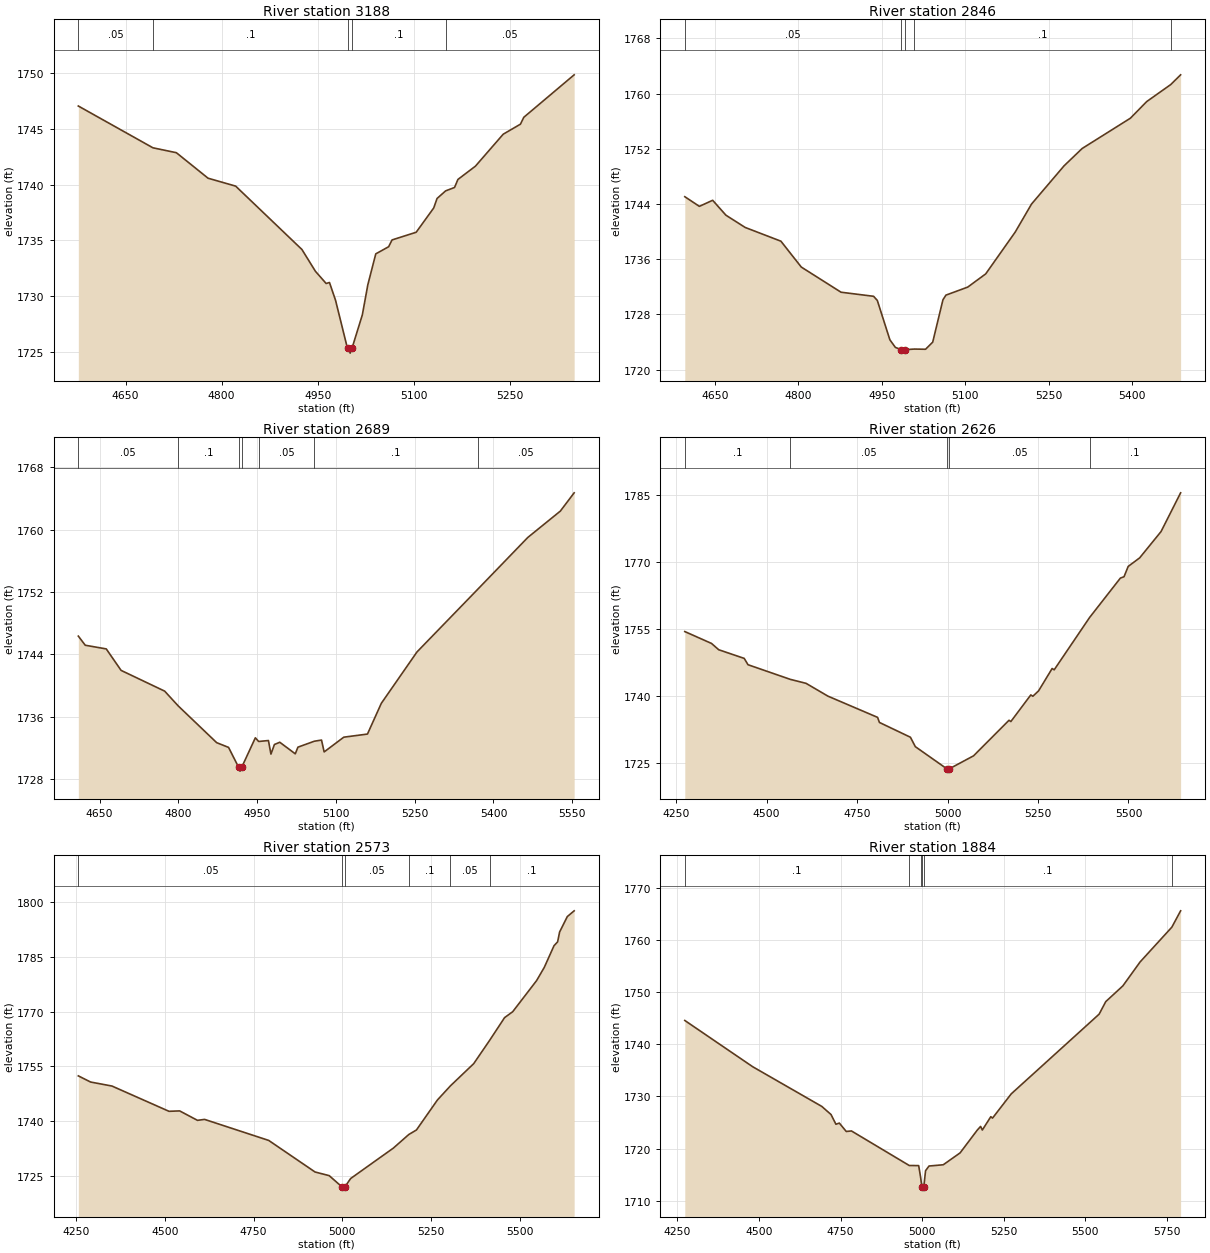
Type RM Length L Ch R = 1 ,3188    ,342,342,342
BEGIN DESCRIPTION:
DRY HOLLOW CREEK 60.1
END DESCRIPTION:
XS GIS Cut Line= 3
      2819765.96     10083016.67      2819976.89     10082760.16
      2820108.12     10082337.88
#Sta/Elev= 30
  4576.2 1747.05  4692.7  1743.3  4729.3 1742.86  4778.8 1740.57  4821.9 1739.86
  4925.4 1734.17  4946.4 1732.22  4963.2 1731.12  4968.4 1731.21  4977.9 1729.61
  4995.7 1725.48  4997.9 1725.37  5000.7 1724.87  5003.9 1725.37  5019.7  1728.3
  5028.3 1731.01  5040.7 1733.78  5060.8 1734.42  5066.1 1735.03  5103.8 1735.72
  5131.2  1737.9  5136.4 1738.75  5149.7 1739.43  5163.7 1739.74    5169 1740.46
  5196.3 1741.65  5239.7 1744.52  5266.6 1745.42  5271.9 1746.04  5350.5 1749.85
#Mann= 5 ,-1 , 0
  4576.2     .05       0  4692.7      .1       0  4997.9     .07       0
  5003.9      .1       0  5149.7     .05       0
Bank Sta=4997.9,5003.9
XS Rating Curve= 0 ,0
Exp/Cntr=0.3,0.1

Type RM Length L Ch R = 1 ,2846    ,157,157,157
BEGIN DESCRIPTION:
Mapping XS 379314e9
END DESCRIPTION:
XS GIS Cut Line= 2
      2820143.55     10083213.31      2820486.02     10082390.33
#Sta/Elev= 30
  4595.7 1745.06  4621.9 1743.66  4645.8 1744.54  4669.6 1742.38  4704.3  1740.6
  4768.5 1738.61  4805.1 1734.86  4876.6 1731.21  4935.1 1730.62  4941.8 1730.02
  4964.4 1724.31  4974.3 1723.21  4985.2 1722.88    4988 1722.38  4991.2 1722.88
  5008.6 1722.97  5028.5 1722.94  5041.4 1723.97  5059.8 1730.11  5065.2 1730.79
  5104.3 1731.95  5136.7 1733.87  5189.8 1739.94  5219.1    1744  5277.6 1749.54
  5310.1 1752.05  5396.8 1756.44  5426.1 1758.85  5469.2 1761.31  5487.1 1762.73
#Mann= 5 ,-1 , 0
  4595.7     .05       0  4985.2    .035       0  4991.2     .05       0
  5008.6      .1       0  5469.2     .05       0
Bank Sta=4985.2,4991.2
XS Rating Curve= 0 ,0
Exp/Cntr=0.3,0.1

Type RM Length L Ch R = 1 ,2689    ,63,63,63
BEGIN DESCRIPTION:
Mapping XS 8e673d8b
END DESCRIPTION:
XS GIS Cut Line= 5
      2820268.56     10083282.28       2820422.2     10082958.08
      2820437.83     10082878.65       2820419.6     10082769.28
      2820518.42     10082388.29
#Sta/Elev= 30
  4609.4 1746.34  4622.6 1745.17  4662.6  1744.7  4690.8 1741.95  4773.8 1739.29
  4799.7 1737.39  4872.8 1732.69  4895.5 1732.08  4914.6 1729.54  4917.4 1729.04
  4920.6 1729.54  4946.5 1733.31  4952.8 1732.84  4971.4 1732.96  4976.2 1731.22
  4982.8 1732.45    4993 1732.74  5022.5 1731.26  5027.6 1732.11  5058.7 1732.87
  5072.5 1733.02  5077.5  1731.5  5114.9 1733.39    5160 1733.79  5186.4 1737.73
  5254.3 1744.31  5369.7 1752.32  5465.3 1758.98  5527.3 1762.36  5553.6  1764.7
#Mann= 7 ,-1 , 0
  4609.4     .05       0  4799.7      .1       0  4914.6    .035       0
  4920.6      .1       0  4952.8     .05       0  5058.7      .1       0
  5369.7     .05       0
Bank Sta=4914.6,4920.6
XS Rating Curve= 0 ,0
Exp/Cntr=0.3,0.1

Type RM Length L Ch R = 1 ,2626    ,53,53,53
BEGIN DESCRIPTION:
DRY HOLLOW CREEK 60.0
END DESCRIPTION:
XS GIS Cut Line= 3
      2820404.79     10083676.95      2820508.96     10082734.27
      2820718.13     10082367.89
#Sta/Elev= 30
  4273.8 1754.45  4347.5 1751.79  4367.6 1750.37    4438 1748.43  4448.5 1747.01
  4565.2 1743.73    4609 1742.83  4669.4 1739.96  4806.6  1735.2  4811.7 1734.06
  4897.4 1730.74  4910.9 1728.63  4998.4 1723.64  5001.2 1723.14  5004.4 1723.64
  5071.8 1726.57  5169.8 1734.55  5174.9 1734.26    5230 1740.23  5235.7 1739.94
  5251.5 1741.14    5289 1746.16  5294.7 1745.87  5392.6 1757.61  5477.6 1766.44
  5487.7 1766.75  5499.2 1769.06  5530.9 1770.98    5590 1776.88  5644.1 1785.57
#Mann= 5 ,-1 , 0
  4273.8      .1       0  4565.2     .05       0  4998.4     .04       0
  5004.4     .05       0  5392.6      .1       0
Bank Sta=4998.4,5004.4
XS Rating Curve= 0 ,0
Exp/Cntr=0.3,0.1

Type RM Length L Ch R = 1 ,2573    ,689,689,689
BEGIN DESCRIPTION:
Mapping XS 5c3e65bd
END DESCRIPTION:
XS GIS Cut Line= 3
      2820481.61     10083708.21      2820545.41     10082835.83
      2820803.99     10082383.65
#Sta/Elev= 30
  4256.7  1752.4  4291.3 1750.71  4351.4 1749.61  4511.9 1742.68  4541.9 1742.79
  4592.1  1740.2  4612.1 1740.46  4792.6 1734.69    4923 1726.03  4962.8 1725.03
  5000.2 1721.83  5002.9 1721.33  5006.2 1721.83  5023.2 1724.24  5143.6  1732.6
  5186.8 1736.31  5208.4 1737.56  5267.4 1745.78  5303.8 1749.64  5369.6 1755.76
  5414.3 1762.13  5456.4 1768.37  5479.4 1770.01  5546.6 1778.54  5568.2 1782.16
  5595.6 1788.11  5605.7 1789.16  5611.4 1791.88    5633  1796.1  5652.3 1797.68
#Mann= 6 ,-1 , 0
  4256.7     .05       0  5000.2     .04       0  5006.2     .05       0
  5186.8      .1       0  5303.8     .05       0  5414.3      .1       0
Bank Sta=5000.2,5006.2
XS Rating Curve= 0 ,0
Exp/Cntr=0.3,0.1

Type RM Length L Ch R = 1 ,1884    ,790,790,790
BEGIN DESCRIPTION:
DRY HOLLOW CREEK 58.0
END DESCRIPTION:
XS GIS Cut Line= 4
      2820701.87     10083820.92       2821035.2      10083511.9
      2821240.06     10082914.68      2821160.31     10082488.19
#Sta/Elev= 30
  4272.5 1744.61  4480.4 1735.73  4692.5 1728.09  4720.8 1726.53  4735.7 1724.67
  4746.2 1724.89  4767.4 1723.28  4783.3 1723.38  4960.5 1716.74  4989.4 1716.72
    4995 1714.61  4999.2  1712.7  5001.9  1712.2  5005.2  1712.7  5010.5 1715.74
  5021.1 1716.64  5064.7 1716.88  5116.3 1719.16  5169.1 1723.55  5179.2 1724.25
  5184.5 1723.56  5210.5 1726.12  5215.8 1725.85    5273  1730.5  5542.5 1745.82
  5562.8 1748.23  5615.3 1751.26    5668 1755.85  5765.4 1762.54  5792.3 1765.68
#Mann= 6 ,-1 , 0
  4272.5      .1       0  4960.5     .16       0    4995      .1       0
  4999.2     .07       0  5005.2      .1       0  5765.4     .05       0
Bank Sta=4999.2,5005.2
XS Rating Curve= 0 ,0
Exp/Cntr=0.3,0.1

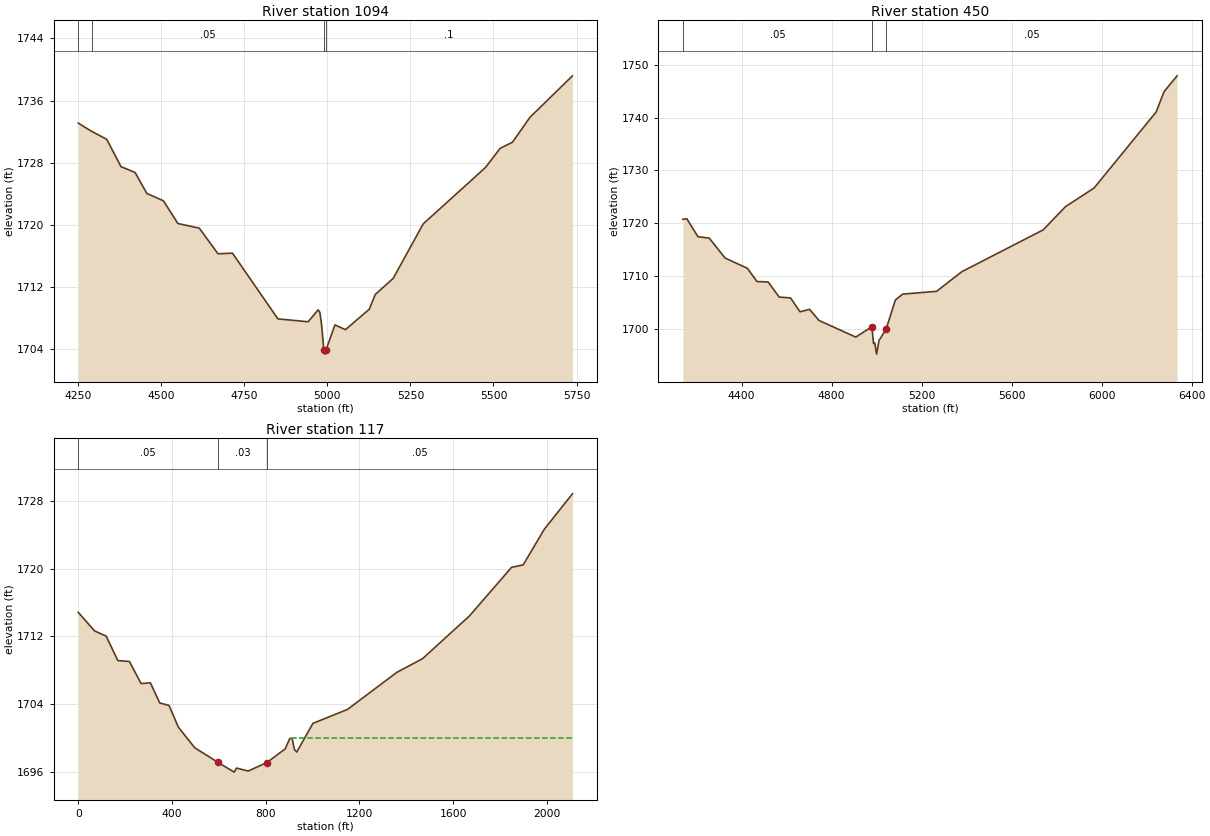
Type RM Length L Ch R = 1 ,1094    ,644,644,644
BEGIN DESCRIPTION:
DRY HOLLOW CREEK 56.0
END DESCRIPTION:
XS GIS Cut Line= 4
      2821510.92     10084116.03      2821799.09      10083737.6
        2821872.     10083209.82      2821656.74     10082782.76
#Sta/Elev= 30
  4250.8 1733.09  4291.3 1732.02  4336.5    1731  4379.4 1727.48  4421.7 1726.73
  4457.1 1724.03    4507 1723.08  4550.6 1720.15    4615 1719.55  4671.2 1716.25
  4714.8 1716.33  4851.5 1707.86  4942.4 1707.49  4972.6 1709.03  4977.7 1708.69
  4982.7 1707.18  4989.8 1703.82  4992.6 1703.32  4995.8 1703.82  5023.1 1707.09
  5054.6 1706.47  5126.5 1709.11  5144.3 1711.01  5198.3 1713.08  5288.5  1720.1
  5475.7 1727.36  5520.3 1729.84  5557.2 1730.63  5609.5 1733.82  5737.5 1739.18
#Mann= 4 ,-1 , 0
  4250.8      .1       0  4291.3     .05       0  4989.8     .07       0
  4995.8      .1       0
Bank Sta=4989.8,4995.8
XS Rating Curve= 0 ,0
Exp/Cntr=0.3,0.1

Type RM Length L Ch R = 1 ,450     ,333,333,333
BEGIN DESCRIPTION:
DRY HOLLOW CREEK 55.0
END DESCRIPTION:
XS GIS Cut Line= 4
      2821932.08     10084162.22      2822453.27     10083578.99
      2822527.72     10083343.21       2821708.7     10082511.79
#Sta/Elev= 30
  4138.8 1720.78  4156.4 1720.87  4205.7 1717.49  4255.9 1717.23  4326.1 1713.47
  4425.6 1711.52  4468.2 1709.02  4517.5 1708.95  4566.9 1706.09    4617 1705.94
  4659.6 1703.31  4701.5 1703.78  4744.1 1701.67  4907.1 1698.54  4978.9 1700.49
  4986.1 1697.32  4991.4 1697.46  4999.6 1695.32  5010.4 1697.89  5041.8 1700.01
  5083.1 1705.53  5115.2 1706.65  5266.3 1707.18  5379.4 1710.91  5740.1 1718.78
  5839.1 1723.16  5966.4 1726.69  6242.2 1741.04  6277.5 1744.89  6335.3 1747.87
#Mann= 3 , 0 , 0
  4138.8     .05       0  4978.9     .03       0  5041.8     .05       0
Bank Sta=4978.9,5041.8
XS Rating Curve= 0 ,0
Exp/Cntr=0.3,0.1

Type RM Length L Ch R = 1 ,117     ,0,0,0
XS GIS Cut Line= 4
     2822129.868    10084156.293     2822756.729    10083673.501
     2822668.778    10083334.799     2821991.373    10082642.423
#Sta/Elev= 30
       0 1714.85   69.54 1712.66  119.22 1712.04  168.89 1709.15  218.57 1709.04
  268.24 1706.43  307.98 1706.52  347.72 1704.14  387.46 1703.85   427.2 1701.29
  496.74 1698.86  596.09 1697.13  665.64 1695.97  675.57 1696.45  725.25  1696.1
  804.55 1697.09  883.32 1698.72  903.01 1699.95  912.86 1699.96   922.7 1698.64
  932.55 1698.34 1001.47 1701.73 1149.32 1703.38 1359.31 1707.75  1469.3 1709.37
 1669.29 1714.41 1849.28 1720.16 1899.28 1720.46 1989.28 1724.67 2109.27 1728.85
#Mann= 3 , 0 , 0
       0     .05       0  596.09     .03       0  804.55     .05       0
#XS Ineff= 2 , 0
                          907.94         1699.99
Permanent Ineff=
       F       F
Bank Sta=596.09,804.55
XS Rating Curve= 0 ,0
Exp/Cntr=0.3,0.1

Chan Stop Cuts=-1
Use User Specified Reach Order=0
Composite Channel Slope=5