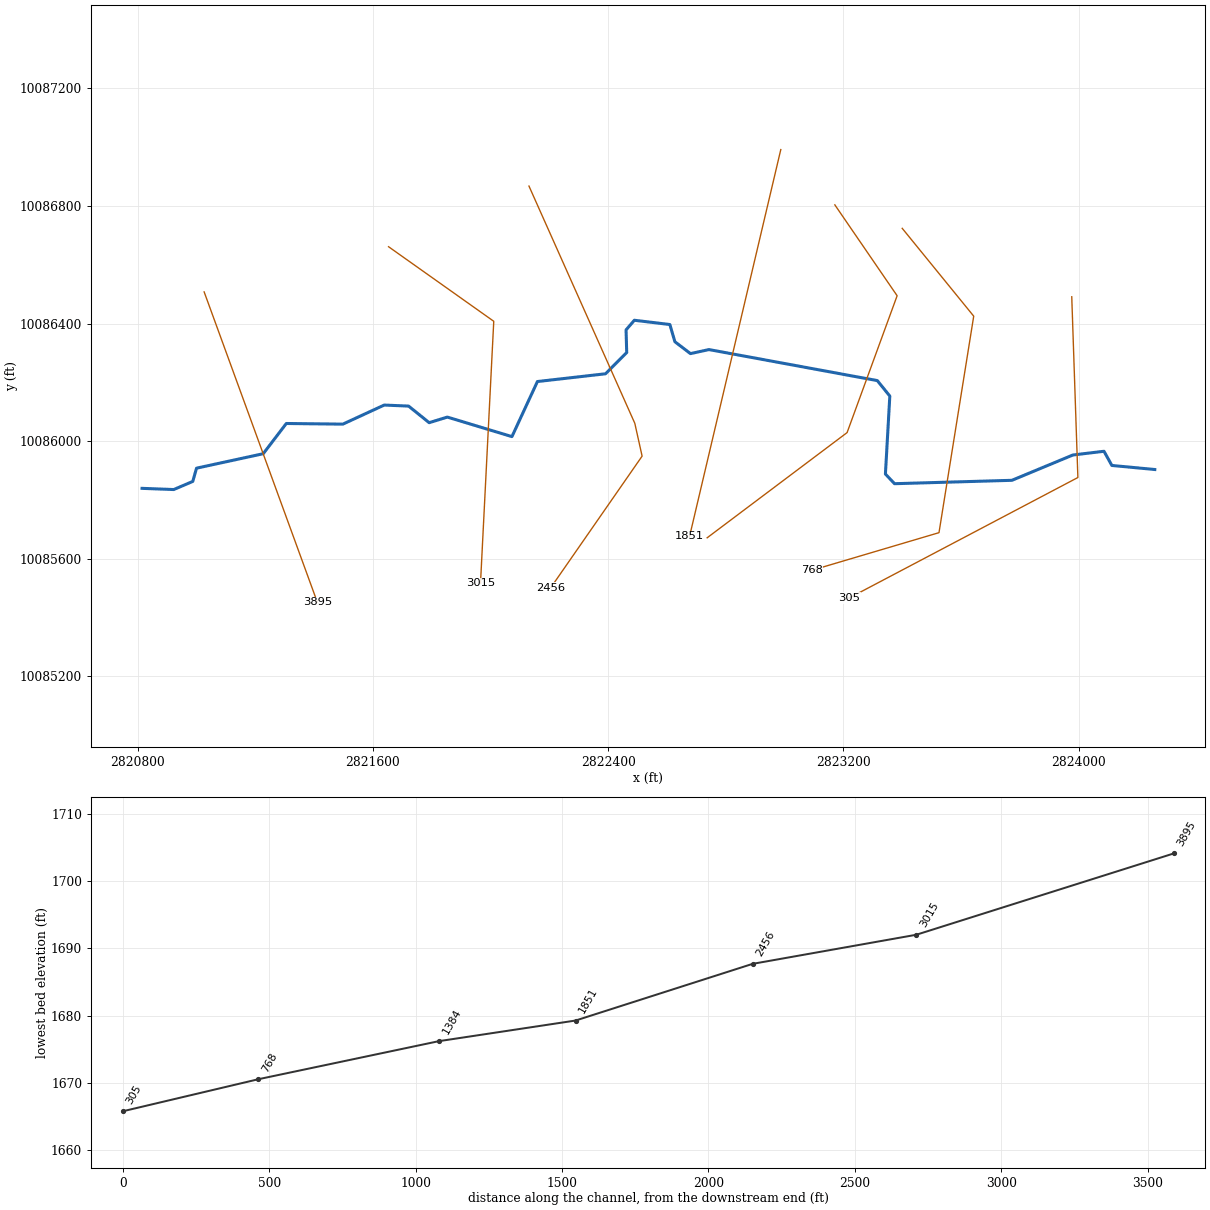
--- UNT094 IN NNOGR.prj (project) ---

Proj Title=UNT094 IN NNOGR Base Level Engineering
Current Plan=p01
Default Exp/Contr=0.3,0.1
English Units
Geom File=g01
Flow File=f01
Plan File=p01
Y Axis Title=Elevation
X Axis Title(PF)=Main Channel Distance
X Axis Title(XS)=Station
BEGIN DESCRIPTION:
UNT094 IN NNOGR
END DESCRIPTION:
DSS Export Rating Curves= 0
DSS Export Rating Curve Sorted= 0
DSS Export Volume Flow Curves= 0
DXF OffsetX= 0
DXF OffsetY= 0
DXF ScaleX= 1
DXF ScaleY= 10

--- UNT094 IN NNOGR.p01 (plan) ---

Plan Title=Multiple Run
Short Identifier=Multiple
Geom File=g01
Flow File=f01
Subcritical Flow
K Sum by GR= 0
Std Step Tol= 0.01
Critical Tol= 0.01
Num of Std Step Trials= 20
Max Error Tol= 0.3
Flow Tol Ratio= 0.001
Split Flow NTrial= 30
Split Flow Tol= 0.02
Split Flow Ratio= 0.02
Log Output Level= 0
Friction Slope Method= 1
Unsteady Friction Slope Method= 2
Unsteady Bridges Friction Slope Method= 1
Parabolic Critical Depth
Global Vel Dist=  1 , 1 , 1
Global Log Level= 0
CheckData=True
Encroach Param= -1, 0, 0, 0
BEGIN DESCRIPTION:
Multiple Run
END DESCRIPTION:

--- UNT094 IN NNOGR.f01 (steady flow) ---

Flow Title=Multiple
Program Version=4.10
Number of Profiles= 7
Profile Names=10-year,25-year,50-year,1pct_min,100-year,1pct_plu,500-year
River Rch & RM=UNT094 IN NNOGR,Reach-1         ,3895
     726    1039    1308    1206    1631    2205    2543
Boundary for River Rch & Prof#=UNT094 IN NNOGR,Reach-1         , 1
Up Type= 0
Dn Type= 3
Dn Slope=0.01
Boundary for River Rch & Prof#=UNT094 IN NNOGR,Reach-1         , 2
Up Type= 0
Dn Type= 3
Dn Slope=0.01
Boundary for River Rch & Prof#=UNT094 IN NNOGR,Reach-1         , 3
Up Type= 0
Dn Type= 3
Dn Slope=0.01
Boundary for River Rch & Prof#=UNT094 IN NNOGR,Reach-1         , 4
Up Type= 0
Dn Type= 3
Dn Slope=0.01
Boundary for River Rch & Prof#=UNT094 IN NNOGR,Reach-1         , 5
Up Type= 0
Dn Type= 3
Dn Slope=0.01
Boundary for River Rch & Prof#=UNT094 IN NNOGR,Reach-1         , 6
Up Type= 0
Dn Type= 3
Dn Slope=0.01
Boundary for River Rch & Prof#=UNT094 IN NNOGR,Reach-1         , 7
Up Type= 0
Dn Type= 3
Dn Slope=0.01
DSS Import GetInterval= 0
DSS Import GetPeak= 0
DSS Import FillOption= 0

--- UNT094 IN NNOGR.g01 (geometry) ---

Geom Title=Existing Conditions
Program Version=4.10

River Reach=UNT094 IN NNOGR ,Reach-1
Reach XY= 30
      2820815.06     10085839.66      2820922.79     10085835.59
      2820987.52     10085863.17      2821000.27     10085908.24
      2821227.09     10085957.42      2821305.56     10086060.19
      2821497.78       10086058.      2821638.42     10086122.85
      2821721.34     10086119.34      2821791.32     10086062.97
      2821853.13     10086081.94      2822072.73     10086015.55
      2822159.38     10086202.83      2822390.95     10086229.22
      2822462.96     10086301.36      2822460.77     10086378.53
      2822489.01     10086411.19      2822609.69     10086396.68
      2822626.81      10086338.1      2822679.69     10086297.81
      2822742.63     10086311.49      2823315.04     10086206.03
      2823357.56     10086153.44      2823342.59     10085888.34
       2823373.6     10085855.49      2823772.77       10085867.
      2823979.88     10085953.01      2824085.77     10085965.75
       2824112.5     10085917.49      2824258.47     10085903.73

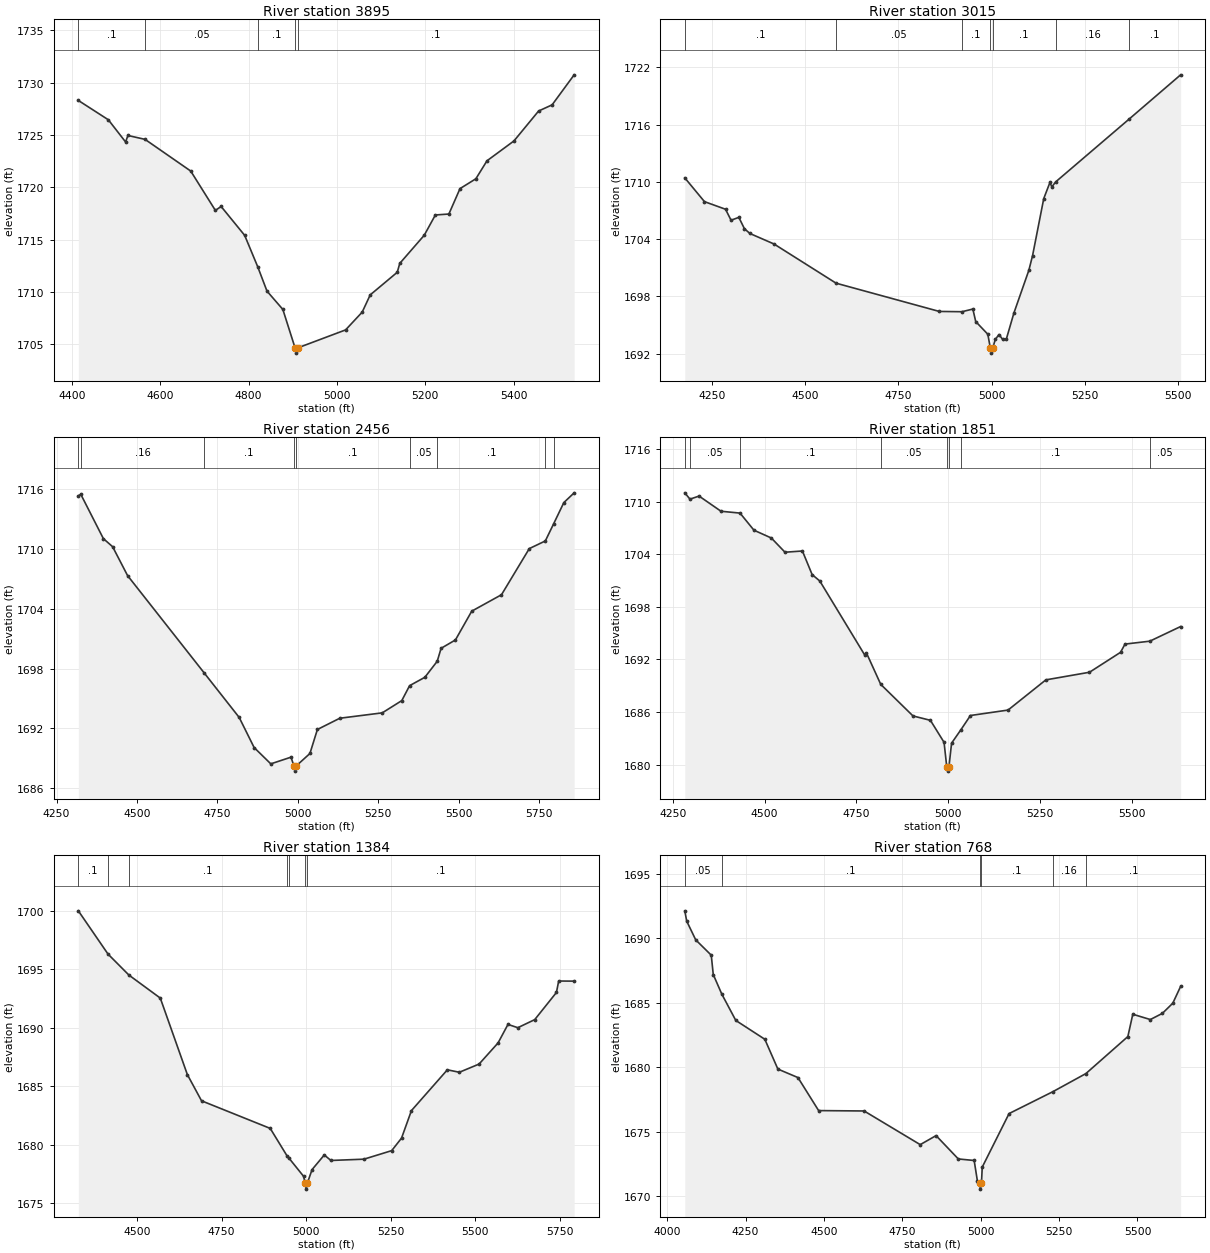
Type RM Length L Ch R = 1 ,3895    ,880,880,880
BEGIN DESCRIPTION:
UNT094 IN NNOGR 6.0
END DESCRIPTION:
XS GIS Cut Line= 2
      2821026.19      10086507.6       2821410.9     10085452.76
#Sta/Elev= 30
  4414.3 1728.31  4482.3 1726.46  4521.3 1724.34  4526.6 1724.96  4565.3 1724.59
  4668.8 1721.56  4724.6  1717.8  4737.7 1718.17    4791 1715.41  4820.7 1712.39
  4841.5 1710.08  4877.4 1708.33  4905.1 1704.65  4907.8 1704.15  4911.1 1704.65
  5019.5 1706.37  5057.1 1708.07  5075.3 1709.72  5136.5 1711.88  5142.2 1712.73
  5197.6 1715.42  5222.8 1717.36  5253.4 1717.45  5278.6 1719.88  5314.5 1720.82
  5339.7 1722.54  5400.8 1724.44  5456.6  1727.3  5487.2 1727.89  5537.1 1730.76
#Mann= 5 ,-1 , 0
  4414.3      .1       0  4565.3     .05       0  4820.7      .1       0
  4905.1     .07       0  4911.1      .1       0
Bank Sta=4905.1,4911.1
XS Rating Curve= 0 ,0
Exp/Cntr=0.3,0.1

Type RM Length L Ch R = 1 ,3015    ,559,559,559
BEGIN DESCRIPTION:
UNT094 IN NNOGR 4.0
END DESCRIPTION:
XS GIS Cut Line= 3
      2821653.24     10086661.22      2822010.89     10086407.74
      2821965.84     10085517.05
#Sta/Elev= 30
  4176.8 1710.41  4229.5 1707.92  4286.1 1707.12  4300.9 1705.97  4321.8 1706.27
  4336.6 1705.09  4351.4 1704.58  4416.1 1703.48  4582.7 1699.37  4859.5 1696.41
  4920.3 1696.38  4949.6 1696.66  4957.3 1695.35  4989.7 1694.02  4996.7 1692.54
  4999.4 1692.04  5002.7 1692.54  5009.7 1693.47  5019.7 1693.99  5029.7 1693.47
  5039.7 1693.55  5059.7 1696.24  5099.8 1700.72  5109.8 1702.26  5139.8 1708.24
  5156.4 1709.93  5161.5 1709.47  5172.1    1710  5368.8 1716.57    5507 1721.21
#Mann= 7 ,-1 , 0
  4176.8      .1       0  4582.7     .05       0  4920.3      .1       0
  4996.7     .07       0  5002.7      .1       0  5172.1     .16       0
  5368.8      .1       0
Bank Sta=4996.7,5002.7
XS Rating Curve= 0 ,0
Exp/Cntr=0.3,0.1

Type RM Length L Ch R = 1 ,2456    ,605,605,605
BEGIN DESCRIPTION:
UNT094 IN NNOGR 3.0
END DESCRIPTION:
XS GIS Cut Line= 4
      2822130.63     10086867.45      2822490.49     10086060.85
      2822515.31     10085949.17      2822205.09     10085502.46
#Sta/Elev= 30
  4317.7 1715.35  4325.4  1715.5  4395.6 1711.05  4424.3 1710.24  4470.8 1707.34
  4708.7 1697.58  4817.8  1693.1  4864.2 1690.08  4916.1 1688.44  4978.8 1689.11
  4988.3 1688.21    4991 1687.71  4994.3 1688.21  5037.7 1689.48  5060.9 1691.89
  5130.6 1693.02  5262.6 1693.56  5323.3 1694.79  5347.6 1696.29    5395 1697.13
  5433.5 1698.74  5445.5 1700.04  5490.1 1700.88  5540.8 1703.77  5633.3 1705.42
  5719.7 1710.05  5769.6 1710.82  5795.7 1712.56  5827.1 1714.67  5859.2 1715.65
#Mann= 9 ,-1 , 0
  4317.7      .1       0  4325.4     .16       0  4708.7      .1       0
  4988.3     .07       0  4994.3      .1       0  5347.6     .05       0
  5433.5      .1       0  5769.6     .05       0  5795.7      .1       0
Bank Sta=4988.3,4994.3
XS Rating Curve= 0 ,0
Exp/Cntr=0.3,0.1

Type RM Length L Ch R = 1 ,1851    ,467,467,467
BEGIN DESCRIPTION:
UNT094 IN NNOGR 2.0
END DESCRIPTION:
XS GIS Cut Line= 2
      2822986.87     10086991.55      2822676.63     10085676.14
#Sta/Elev= 30
  4282.3 1710.99  4296.4 1710.27  4321.2 1710.62    4381 1708.89  4432.8 1708.68
  4470.8 1706.73  4518.2 1705.84  4555.4 1704.22  4602.9 1704.36  4629.4 1701.67
  4650.3 1700.94  4772.2 1692.54  4777.3 1692.75  4816.4 1689.16  4904.3 1685.56
  4951.8 1685.06    4989 1682.55  4996.3 1679.77    4999 1679.27  5002.3 1679.77
  5009.5 1682.46  5035.3 1684.01  5060.9 1685.61  5163.4 1686.23  5266.4 1689.67
  5385.4 1690.54    5470 1692.81  5482.2 1693.75  5549.7 1694.08  5633.8 1695.75
#Mann= 8 ,-1 , 0
  4282.3      .1       0  4296.4     .05       0  4432.8      .1       0
  4816.4     .05       0  4996.3    .035       0  5002.3     .05       0
  5035.3      .1       0  5549.7     .05       0
Bank Sta=4996.3,5002.3
XS Rating Curve= 0 ,0
Exp/Cntr=0.3,0.1

Type RM Length L Ch R = 1 ,1384    ,616,616,616
BEGIN DESCRIPTION:
Mapping XS e6c2216d
END DESCRIPTION:
XS GIS Cut Line= 4
      2823170.64     10086803.53      2823382.42     10086494.54
      2823212.28     10086029.26      2822736.55      10085671.6
#Sta/Elev= 30
  4326.8 1699.99  4414.6 1696.29  4476.2  1694.5    4569 1692.53    4649 1685.99
  4690.9 1683.75  4893.9 1681.39  4943.4 1679.05  4949.5 1678.84  4992.3  1677.3
  4997.4  1676.7  5000.1  1676.2  5003.4  1676.7  5017.5 1677.87  5053.6 1679.12
  5073.2 1678.65  5170.8 1678.76  5252.8 1679.49  5281.9 1680.56  5311.1 1682.91
  5417.3  1686.4  5452.7 1686.19    5511 1686.89  5567.2  1688.7  5596.4 1690.28
  5625.5    1690  5675.5 1690.69  5739.6 1693.01  5746.3 1693.99    5792 1693.98
#Mann= 7 ,-1 , 0
  4326.8      .1       0  4414.6     .05       0  4476.2      .1       0
  4943.4     .05       0  4949.5      .1       0  4997.4     .07       0
  5003.4      .1       0
Bank Sta=4997.4,5003.4
XS Rating Curve= 0 ,0
Exp/Cntr=0.3,0.1

Type RM Length L Ch R = 1 ,768     ,463,463,463
BEGIN DESCRIPTION:
Mapping XS b5ee8a14
END DESCRIPTION:
XS GIS Cut Line= 4
       2823399.8     10086723.68      2823642.84      10086425.1
      2823524.78     10085688.99      2823092.14     10085560.92
#Sta/Elev= 30
    4056 1692.12  4062.1 1691.32  4090.8 1689.87  4140.4 1688.68  4146.8 1687.18
  4173.9 1685.67  4218.7 1683.62  4311.3 1682.16  4352.9 1679.85    4417 1679.19
  4482.9 1676.63  4628.1  1676.6    4807 1673.99  4857.6 1674.69  4928.5 1672.88
  4979.1 1672.76  4989.3 1671.19  4996.4 1671.04  4999.1 1670.54  5002.4 1671.04
  5004.9 1672.25  5090.5  1676.4  5229.7 1678.09  5335.5  1679.5  5469.4 1682.37
  5485.1  1684.1  5541.1 1683.69  5579.6 1684.17  5612.8 1684.96  5637.7 1686.26
#Mann= 6 ,-1 , 0
    4056     .05       0  4173.9      .1       0  4996.4     .07       0
  5002.4      .1       0  5229.7     .16       0  5335.5      .1       0
Bank Sta=4996.4,5002.4
XS Rating Curve= 0 ,0
Exp/Cntr=0.3,0.1

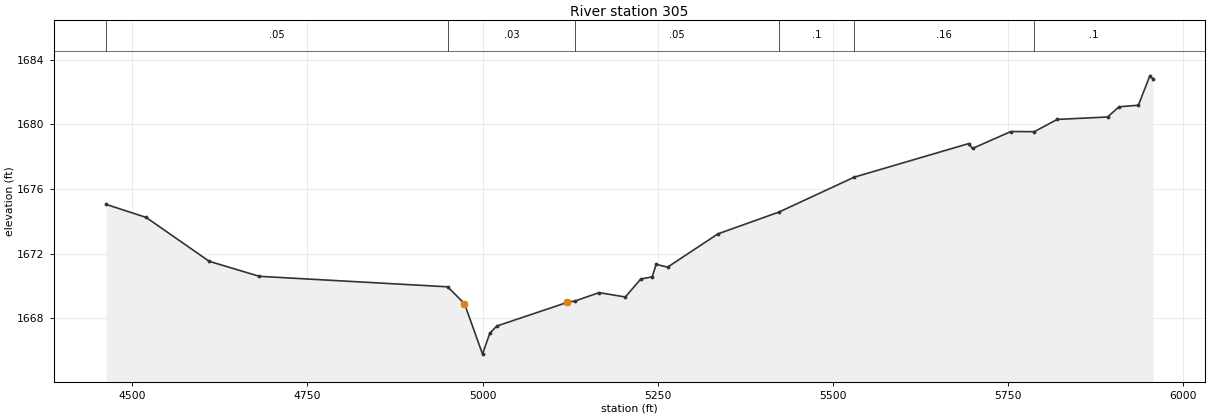
Type RM Length L Ch R = 1 ,305     ,0,0,0
BEGIN DESCRIPTION:
UNT094 IN NNOGR 1.0
END DESCRIPTION:
XS GIS Cut Line= 3
      2823976.17     10086491.09        2823997.     10085876.49
      2823219.18     10085466.74
#Sta/Elev= 30
  4462.5 1675.05  4519.9 1674.24  4609.9 1671.52  4681.4 1670.59  4950.1 1669.94
  4974.1  1668.9  4999.9 1665.77  5010.2 1667.06  5020.2 1667.51  5121.1 1668.98
  5131.8 1669.06  5166.2 1669.58  5203.6 1669.31  5225.6 1670.42    5242 1670.56
  5247.6 1671.33    5264 1671.16  5335.8 1673.22  5422.8 1674.57  5530.1 1676.73
  5693.3 1678.81    5699 1678.51  5753.8 1679.56  5787.1 1679.55  5819.9 1680.31
  5891.6 1680.46    5908 1681.09  5935.7 1681.19    5952 1683.01  5956.6 1682.82
#Mann= 6 ,-1 , 0
  4462.5     .05       0  4950.1     .03       0  5131.8     .05       0
  5422.8      .1       0  5530.1     .16       0  5787.1      .1       0
Bank Sta=4974.1,5121.1
XS Rating Curve= 0 ,0
Exp/Cntr=0.3,0.1

Chan Stop Cuts=-1
Use User Specified Reach Order=0
Composite Channel Slope=5