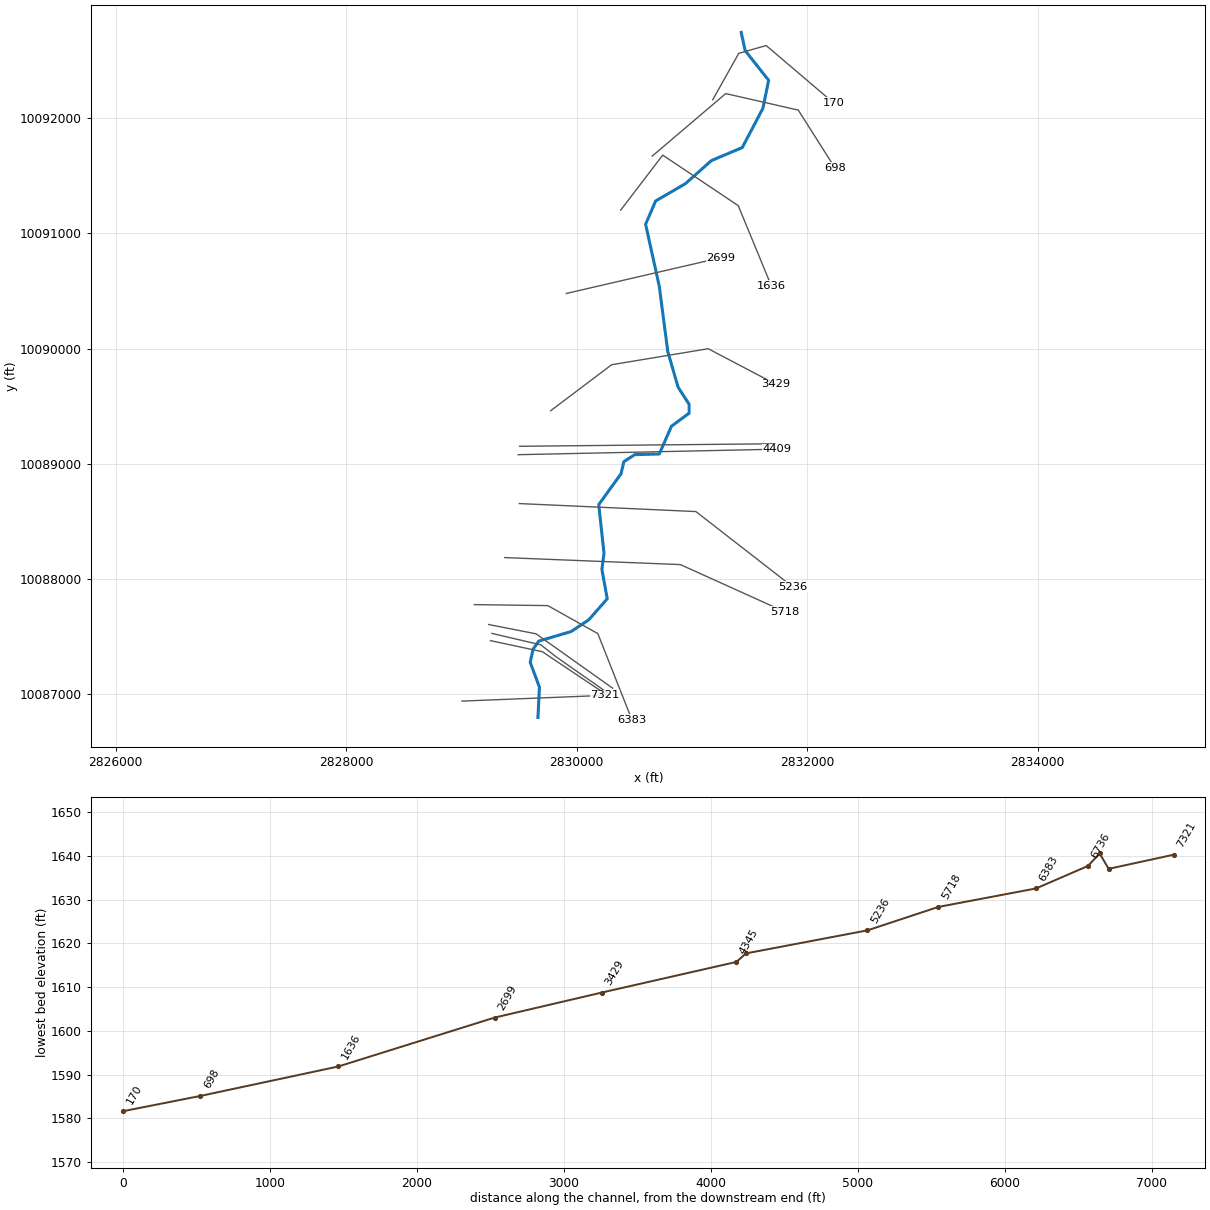
--- UNT095 IN NNOGR.prj (project) ---

Proj Title=UNT095 IN NNOGR Base Level Engineering
Current Plan=p01
Default Exp/Contr=0.3,0.1
English Units
Geom File=g01
Flow File=f01
Plan File=p01
Y Axis Title=Elevation
X Axis Title(PF)=Main Channel Distance
X Axis Title(XS)=Station
BEGIN DESCRIPTION:
UNT095 IN NNOGR
END DESCRIPTION:
DSS Export Rating Curves= 0
DSS Export Rating Curve Sorted= 0
DSS Export Volume Flow Curves= 0
DXF OffsetX= 0
DXF OffsetY= 0
DXF ScaleX= 1
DXF ScaleY= 10

--- UNT095 IN NNOGR.p01 (plan) ---

Plan Title=Multiple Run
Short Identifier=Multiple
Geom File=g01
Flow File=f01
Subcritical Flow
K Sum by GR= 0
Std Step Tol= 0.01
Critical Tol= 0.01
Num of Std Step Trials= 20
Max Error Tol= 0.3
Flow Tol Ratio= 0.001
Split Flow NTrial= 30
Split Flow Tol= 0.02
Split Flow Ratio= 0.02
Log Output Level= 0
Friction Slope Method= 1
Unsteady Friction Slope Method= 2
Unsteady Bridges Friction Slope Method= 1
Parabolic Critical Depth
Global Vel Dist=  1 , 1 , 1
Global Log Level= 0
CheckData=True
Encroach Param= -1, 0, 0, 0
BEGIN DESCRIPTION:
Multiple Run
END DESCRIPTION:

--- UNT095 IN NNOGR.f01 (steady flow) ---

Flow Title=Multiple
Program Version=4.10
Number of Profiles= 7
Profile Names=10-year,25-year,50-year,1pct_min,100-year,1pct_plu,500-year
River Rch & RM=UNT095 IN NNOGR,Reach-1         ,7321
    1615    2397    3088    2905    3929    5314    6390
Boundary for River Rch & Prof#=UNT095 IN NNOGR,Reach-1         , 1
Up Type= 0
Dn Type= 3
Dn Slope=0.009
Boundary for River Rch & Prof#=UNT095 IN NNOGR,Reach-1         , 2
Up Type= 0
Dn Type= 3
Dn Slope=0.009
Boundary for River Rch & Prof#=UNT095 IN NNOGR,Reach-1         , 3
Up Type= 0
Dn Type= 3
Dn Slope=0.009
Boundary for River Rch & Prof#=UNT095 IN NNOGR,Reach-1         , 4
Up Type= 0
Dn Type= 3
Dn Slope=0.009
Boundary for River Rch & Prof#=UNT095 IN NNOGR,Reach-1         , 5
Up Type= 0
Dn Type= 3
Dn Slope=0.009
Boundary for River Rch & Prof#=UNT095 IN NNOGR,Reach-1         , 6
Up Type= 0
Dn Type= 3
Dn Slope=0.009
Boundary for River Rch & Prof#=UNT095 IN NNOGR,Reach-1         , 7
Up Type= 0
Dn Type= 3
Dn Slope=0.009
DSS Import GetInterval= 0
DSS Import GetPeak= 0
DSS Import FillOption= 0

--- UNT095 IN NNOGR.g01 (geometry) ---

Geom Title=Existing Conditions
Program Version=4.10

River Reach=UNT095 IN NNOGR ,Reach-1
Reach XY= 30
      2829665.14     10086800.01      2829677.88     10087063.46
      2829597.78     10087278.15      2829622.48     10087391.55
      2829671.44     10087462.39      2829952.77     10087545.36
      2830106.32     10087647.52      2830266.24     10087829.48
      2830219.83     10088084.03      2830238.19     10088224.57
      2830192.45     10088646.73      2830386.07     10088914.73
      2830409.98     10089018.98      2830505.12     10089080.44
      2830717.87     10089085.81      2830823.28     10089326.58
      2830976.44      10089439.9      2830976.43     10089517.73
      2830881.07     10089664.86      2830791.37     10089974.94
      2830717.21     10090543.61      2830599.12     10091079.17
      2830686.25     10091281.39      2830944.71     10091431.18
      2831169.43     10091631.39      2831437.73     10091744.62
      2831616.66     10092084.48      2831666.53     10092327.89
      2831462.65     10092586.02      2831428.47     10092743.73

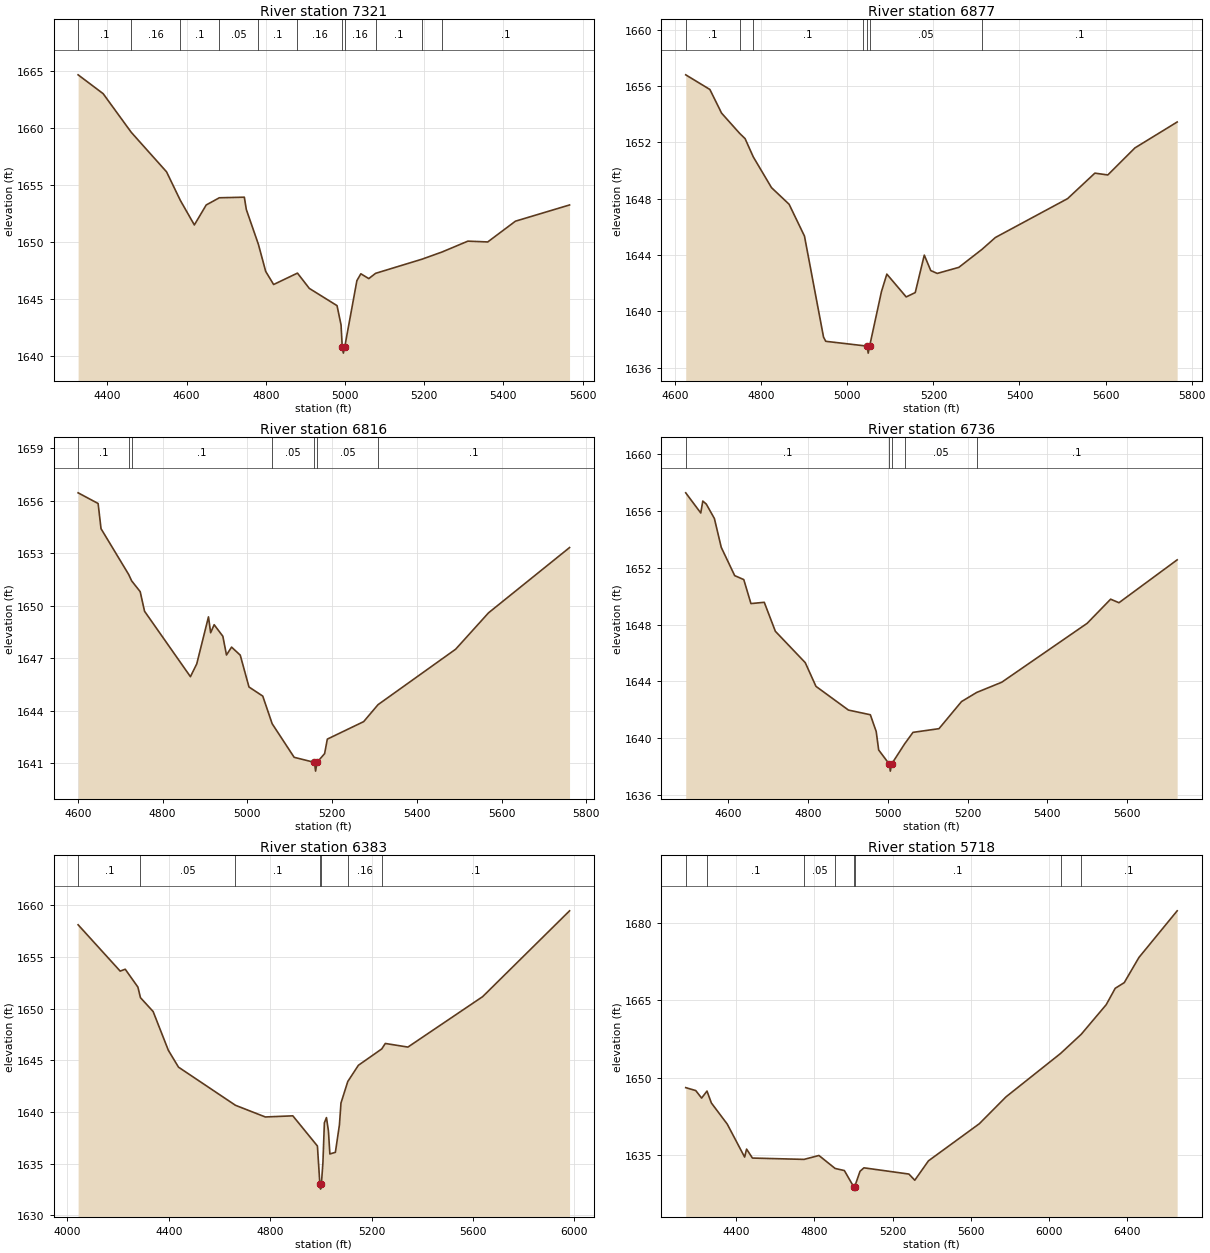
Type RM Length L Ch R = 1 ,7321    ,444,444,444
BEGIN DESCRIPTION:
UNT095 IN NNOGR 9.0
END DESCRIPTION:
XS GIS Cut Line= 2
      2829005.34     10086941.91      2830244.85      10086991.5
#Sta/Elev= 30
  4326.4 1664.65  4389.6    1663  4460.4 1659.62  4549.7 1656.15  4584.3 1653.66
  4619.8  1651.5  4649.8 1653.25  4682.9 1653.88    4746 1653.93    4751 1652.85
  4781.5  1649.8  4799.9 1647.43  4819.9 1646.28  4880.1 1647.28    4910 1645.94
    4980 1644.43  4990.1 1642.75  4993.2 1640.77    4996 1640.27  4999.2 1640.77
  5030.1 1646.62  5040.1 1647.22  5060.1  1646.8  5077.3 1647.26  5194.5  1648.5
  5245.1 1649.13  5310.3 1650.08  5360.4 1650.01  5430.4 1651.83  5566.9 1653.25
#Mann= 11 ,-1 , 0
  4326.4      .1       0  4460.4     .16       0  4584.3      .1       0
  4682.9     .05       0  4781.5      .1       0  4880.1     .16       0
  4993.2     .07       0  4999.2     .16       0  5077.3      .1       0
  5194.5     .05       0  5245.1      .1       0
Bank Sta=4993.2,4999.2
XS Rating Curve= 0 ,0
Exp/Cntr=0.3,0.1

Type RM Length L Ch R = 1 ,6877    ,61,61,61
BEGIN DESCRIPTION:
Mapping XS 66113cde
END DESCRIPTION:
XS GIS Cut Line= 3
      2829253.62     10087466.53      2829703.22     10087370.18
      2830270.09     10086990.83
#Sta/Elev= 30
  4624.5 1656.79  4680.6 1655.75  4707.8 1654.07  4749.6 1652.64  4762.4 1652.26
  4781.5 1650.96  4823.8 1648.78  4864.7  1647.6  4900.4 1645.34  4944.7 1638.17
  4949.8 1637.87  5036.7 1637.56  5045.8 1637.53  5048.5 1637.03  5051.8 1637.53
  5079.3  1641.4  5091.8 1642.64  5136.8 1641.02  5157.8 1641.33  5178.8 1643.99
  5193.9 1642.89  5208.9 1642.69  5259.1 1643.12    5313  1644.4    5344 1645.24
  5511.8    1648  5575.2 1649.81  5605.2 1649.68  5668.2  1651.6  5766.4 1653.44
#Mann= 7 ,-1 , 0
  4624.5      .1       0  4749.6     .16       0  4781.5      .1       0
  5036.7     .05       0  5045.8     .07       0  5051.8     .05       0
    5313      .1       0
Bank Sta=5045.8,5051.8
XS Rating Curve= 0 ,0
Exp/Cntr=0.3,0.1

Type RM Length L Ch R = 1 ,6816    ,80,80,80
BEGIN DESCRIPTION:
Mapping XS 675a2113
END DESCRIPTION:
XS GIS Cut Line= 4
      2829265.74     10087529.03       2829690.2     10087430.08
      2829819.54     10087328.52      2830277.99      10087007.6
#Sta/Elev= 30
  4600.5 1656.45  4647.7 1655.84  4654.6  1654.4  4719.9 1651.78  4726.8 1651.42
    4747  1650.8  4757.3 1649.68  4865.6 1645.94  4880.5 1646.67  4908.2 1649.36
  4913.3 1648.45  4921.6 1648.91  4942.1 1648.25  4950.7 1647.18  4962.7 1647.63
  4983.2 1647.17  5003.8 1645.35  5036.3 1644.83  5058.5 1643.25  5110.4 1641.33
  5158.3 1641.04    5161 1640.54  5164.3 1641.04  5182.3 1641.54  5188.7 1642.37
  5274.5 1643.37  5308.4 1644.34  5491.6 1647.51  5569.2 1649.59  5760.4 1653.32
#Mann= 7 ,-1 , 0
  4600.5      .1       0  4719.9     .16       0  4726.8      .1       0
  5058.5     .05       0  5158.3     .07       0  5164.3     .05       0
  5308.4      .1       0
Bank Sta=5158.3,5164.3
XS Rating Curve= 0 ,0
Exp/Cntr=0.3,0.1

Type RM Length L Ch R = 1 ,6736    ,353,353,353
BEGIN DESCRIPTION:
Mapping XS 5d732ac3
END DESCRIPTION:
XS GIS Cut Line= 3
      2829237.92      10087606.3      2829648.54     10087525.57
      2830312.59     10087054.22
#Sta/Elev= 30
  4492.8 1657.28  4530.5 1655.86  4535.6  1656.7  4544.3 1656.49  4564.7 1655.47
  4581.9 1653.44  4615.6 1651.45  4638.4 1651.17  4656.4 1649.48  4689.8 1649.57
  4717.6 1647.53  4792.6 1645.32  4819.5 1643.65    4901 1641.98  4955.9 1641.65
  4970.6 1640.47  4976.8 1639.17  5003.3 1638.18  5006.1 1637.68  5009.3 1638.18
  5041.7 1639.59  5062.9 1640.41  5128.1 1640.67  5184.7 1642.58  5222.6 1643.22
  5285.5 1643.94  5499.8 1648.09  5558.7 1649.79  5579.6 1649.54  5725.6 1652.56
#Mann= 5 ,-1 , 0
  4492.8      .1       0  5003.3     .07       0  5009.3      .1       0
  5041.7     .05       0  5222.6      .1       0
Bank Sta=5003.3,5009.3
XS Rating Curve= 0 ,0
Exp/Cntr=0.3,0.1

Type RM Length L Ch R = 1 ,6383    ,665,665,665
BEGIN DESCRIPTION:
UNT095 IN NNOGR 8.0
END DESCRIPTION:
XS GIS Cut Line= 4
      2829112.58     10087779.05      2829750.62     10087770.37
      2830184.65     10087527.31      2830479.79     10086780.78
#Sta/Elev= 30
  4042.6 1658.12  4208.5 1653.64  4228.5 1653.82  4278.5 1652.09  4288.5 1651.07
  4338.5 1649.73  4398.5 1645.98  4438.5 1644.35  4663.2 1640.66    4781 1639.53
  4889.5 1639.64  4986.5 1636.72  4996.1 1633.05  4998.9 1632.55  5002.1 1633.05
  5008.2 1635.12  5013.9 1638.96  5022.1 1639.47  5029.9 1638.18  5035.6 1635.95
  5057.3 1636.11  5073.3 1638.77  5079.4 1640.88  5106.2 1642.96  5148.1 1644.53
  5240.1 1646.11  5254.2 1646.64  5343.4 1646.29  5638.2 1651.17  5980.9 1659.47
#Mann= 7 ,-1 , 0
  4042.6      .1       0  4288.5     .05       0  4663.2      .1       0
  4996.1     .07       0  5002.1      .1       0  5106.2     .16       0
  5240.1      .1       0
Bank Sta=4996.1,5002.1
XS Rating Curve= 0 ,0
Exp/Cntr=0.3,0.1

Type RM Length L Ch R = 1 ,5718    ,482,482,482
BEGIN DESCRIPTION:
Mapping XS 567c385a
END DESCRIPTION:
XS GIS Cut Line= 3
      2829377.34     10088187.03      2830900.79     10088126.27
      2831803.07     10087718.51
#Sta/Elev= 30
  4141.8 1648.05    4193 1647.48    4223 1646.02  4250.6 1647.38    4273 1645.07
  4354.1 1640.97  4443.2 1634.55  4453.2  1636.1  4483.2 1634.36  4747.3  1634.1
  4823.5 1634.86  4906.2 1632.34  4953.6 1631.93  5000.6 1628.82  5003.4 1628.32
  5006.6 1628.82  5033.6 1631.78  5053.7 1632.46  5283.8 1631.25  5313.9 1630.05
  5383.9 1633.82  5644.1 1641.03  5780.5 1646.25  6059.9 1654.69  6165.4 1658.41
  6293.4 1664.17  6339.6 1667.36  6385.8 1668.46  6460.7 1673.34  6656.6 1682.42
#Mann= 8 ,-1 , 0
  4141.8     .05       0  4250.6      .1       0  4747.3     .05       0
  4906.2      .1       0  5000.6     .07       0  5006.6      .1       0
  6059.9     .05       0  6165.4      .1       0
Bank Sta=5000.6,5006.6
XS Rating Curve= 0 ,0
Exp/Cntr=0.3,0.1

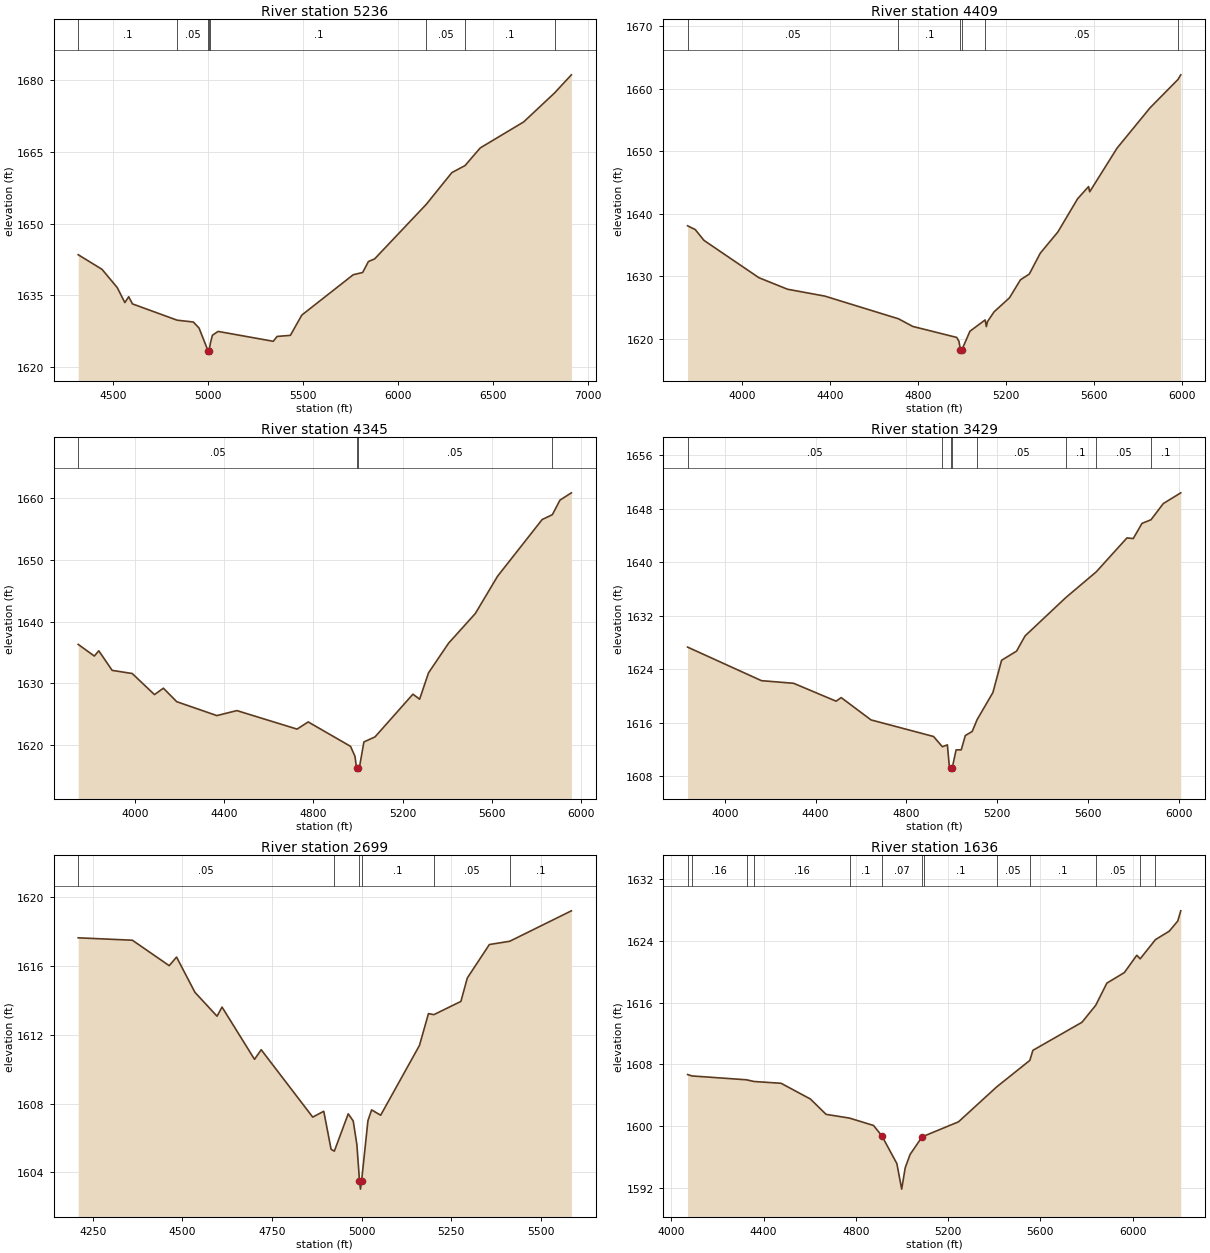
Type RM Length L Ch R = 1 ,5236    ,827,827,827
BEGIN DESCRIPTION:
UNT095 IN NNOGR 6.0
END DESCRIPTION:
XS GIS Cut Line= 3
      2829503.17     10088655.79      2831035.34     10088586.34
      2831873.05     10087935.27
#Sta/Elev= 30
  4317.3  1643.5  4442.7 1640.45  4522.8 1636.64  4562.8 1633.51  4582.9 1634.73
  4602.9 1633.24  4838.1 1629.84  4923.2 1629.46  4953.2  1628.2  5000.3 1623.47
    5003 1622.97  5006.3 1623.47  5012.8 1625.06  5023.3 1626.69  5053.3  1627.5
  5343.6 1625.44  5363.7 1626.45  5433.7 1626.68  5493.8 1630.91  5764.1 1639.32
  5814.1  1639.8  5844.2 1642.08  5876.9 1642.63  6148.5 1654.01  6283.2 1660.63
  6352.6  1662.1  6432.5 1665.78  6660.6 1671.19  6823.3 1677.24    6912 1681.03
#Mann= 8 ,-1 , 0
  4317.3      .1       0  4838.1     .05       0  5000.3     .04       0
  5006.3     .05       0  5012.8      .1       0  6148.5     .05       0
  6352.6      .1       0  6823.3     .05       0
Bank Sta=5000.3,5006.3
XS Rating Curve= 0 ,0
Exp/Cntr=0.3,0.1

Type RM Length L Ch R = 1 ,4409    ,64,64,64
BEGIN DESCRIPTION:
Mapping XS 50b51f6e
END DESCRIPTION:
XS GIS Cut Line= 2
      2829493.76     10089079.81      2831737.75     10089127.55
#Sta/Elev= 30
  3751.5 1638.06  3786.2 1637.47  3826.2 1635.73  4076.3 1629.76  4206.3 1627.92
  4376.3 1626.82  4711.3 1623.19  4776.4 1621.97  4976.5 1620.21  4986.5 1619.59
  4993.5  1618.2  4996.2  1617.7  4999.5  1618.2  5036.5  1621.2  5105.7 1623.01
  5111.3 1621.94  5116.5 1622.74  5146.5 1624.31  5216.5 1626.55  5266.5 1629.43
  5306.6 1630.34  5356.6 1633.68  5436.6 1637.07  5526.6 1642.39  5576.5 1644.34
  5581.5  1643.5  5706.6 1650.51  5856.7 1656.95  5983.7 1661.48    5996 1662.21
#Mann= 6 ,-1 , 0
  3751.5     .05       0  4711.3      .1       0  4993.5     .07       0
  4999.5      .1       0  5105.7     .05       0  5983.7      .1       0
Bank Sta=4993.5,4999.5
XS Rating Curve= 0 ,0
Exp/Cntr=0.3,0.1

Type RM Length L Ch R = 1 ,4345    ,916,916,916
BEGIN DESCRIPTION:
UNT095 IN NNOGR 5.0
END DESCRIPTION:
XS GIS Cut Line= 2
      2829506.09     10089152.87      2831719.68     10089174.57
#Sta/Elev= 30
  3743.9  1636.3  3816.3 1634.41  3836.3 1635.26  3896.3 1632.09  3986.3 1631.58
  4086.3 1628.16  4126.3  1629.2  4186.3 1627.01  4366.3 1624.76  4456.3 1625.57
  4726.3 1622.57  4776.3 1623.73  4966.3 1619.78  4986.3 1618.16  4993.3 1616.26
  4996.1 1615.76  4999.3 1616.26  5006.3 1616.38  5026.3 1620.49  5076.3 1621.31
  5246.4 1628.23  5276.4 1627.42  5316.4 1631.69  5406.4 1636.49  5526.4  1641.3
  5626.4 1647.35  5826.4 1656.53  5872.3 1657.32  5906.4 1659.68  5957.6 1660.86
#Mann= 4 ,-1 , 0
  3743.9     .05       0  4993.3     .04       0  4999.3     .05       0
  5872.3      .1       0
Bank Sta=4993.3,4999.3
XS Rating Curve= 0 ,0
Exp/Cntr=0.3,0.1

Type RM Length L Ch R = 1 ,3429    ,730,730,730
BEGIN DESCRIPTION:
UNT095 IN NNOGR 4.0
END DESCRIPTION:
XS GIS Cut Line= 4
      2829775.17     10089461.01      2830304.71     10089860.34
      2831142.38     10089999.23      2831728.35     10089691.05
#Sta/Elev= 30
  3835.4 1627.31  4161.3 1622.29  4302.9  1621.9  4490.3 1619.22  4512.6 1619.76
  4644.3 1616.42  4919.9 1613.94  4958.8 1612.41  4980.9 1612.69    4989 1609.62
  4996.1 1609.26  4998.9 1608.76  5002.1 1609.26  5019.4 1611.94  5041.9 1611.94
  5059.9 1614.08  5090.4  1614.7  5111.8 1616.45  5181.6 1620.52  5219.8 1625.34
  5285.8 1626.71  5323.5 1628.99    5502 1634.69  5636.9 1638.56  5772.7 1643.65
  5800.4 1643.55  5838.9 1645.82  5878.6 1646.36  5932.7 1648.78  6009.8 1650.39
#Mann= 8 ,-1 , 0
  3835.4     .05       0  4958.8      .1       0  4996.1     .07       0
  5002.1      .1       0  5111.8     .05       0    5502      .1       0
  5636.9     .05       0  5878.6      .1       0
Bank Sta=4996.1,5002.1
XS Rating Curve= 0 ,0
Exp/Cntr=0.3,0.1

Type RM Length L Ch R = 1 ,2699    ,1063,1063,1063
BEGIN DESCRIPTION:
UNT095 IN NNOGR 3.0
END DESCRIPTION:
XS GIS Cut Line= 2
      2829911.22     10090478.56      2831251.29     10090788.76
#Sta/Elev= 30
  4209.7 1617.65  4360.8 1617.51  4463.5 1616.03    4484 1616.53  4535.3 1614.48
  4596.9 1613.09  4610.9 1613.62  4701.5 1610.58  4720.1 1611.14  4863.8 1607.22
  4894.6 1607.56    4915 1605.35  4924.1 1605.24  4962.8 1607.41  4976.7    1607
    4987 1605.62  4994.2 1603.53    4997 1603.03  5000.2 1603.53  5017.8 1607.01
    5028 1607.64  5053.3 1607.33  5161.5 1611.39  5186.6 1613.24  5201.7 1613.18
  5277.1 1613.95  5294.9 1615.31  5356.5 1617.26  5413.4 1617.45  5585.2 1619.22
#Mann= 6 ,-1 , 0
  4209.7     .05       0  4924.1      .1       0  4994.2     .07       0
  5000.2      .1       0  5201.7     .05       0  5413.4      .1       0
Bank Sta=4994.2,5000.2
XS Rating Curve= 0 ,0
Exp/Cntr=0.3,0.1

Type RM Length L Ch R = 1 ,1636    ,938,938,938
BEGIN DESCRIPTION:
UNT095 IN NNOGR 2.0
END DESCRIPTION:
XS GIS Cut Line= 4
      2830382.83     10091201.48      2830747.42     10091678.91
       2831402.8     10091240.55      2831688.72      10090547.4
#Sta/Elev= 30
  4070.2 1606.69  4089.2 1606.51  4325.8 1606.01  4358.8 1605.79  4475.7 1605.56
  4603.1 1603.52  4670.8 1601.54    4773 1601.05  4876.7  1600.1  4912.8 1598.76
    4978 1595.16  4998.8 1591.86    5014 1594.61  5035.1 1596.34  5086.1 1598.57
  5096.6 1598.74  5245.2 1600.57  5410.7 1605.09  5554.6 1608.52  5567.8 1609.82
  5780.9 1613.46  5840.3 1615.65  5888.6 1618.52  5964.6 1619.89  6018.5 1622.13
  6033.2 1621.67  6099.6 1624.16  6159.1 1625.24  6196.2 1626.56  6209.2 1627.88
#Mann= 13 ,-1 , 0
  4070.2      .1       0  4089.2     .16       0  4325.8      .1       0
  4358.8     .16       0    4773      .1       0  4912.8     .07       0
  5086.1     .16       0  5096.6      .1       0  5410.7     .05       0
  5554.6      .1       0  5840.3     .05       0  6033.2      .1       0
  6099.6     .05       0
Bank Sta=4912.8,5086.1
XS Rating Curve= 0 ,0
Exp/Cntr=0.3,0.1

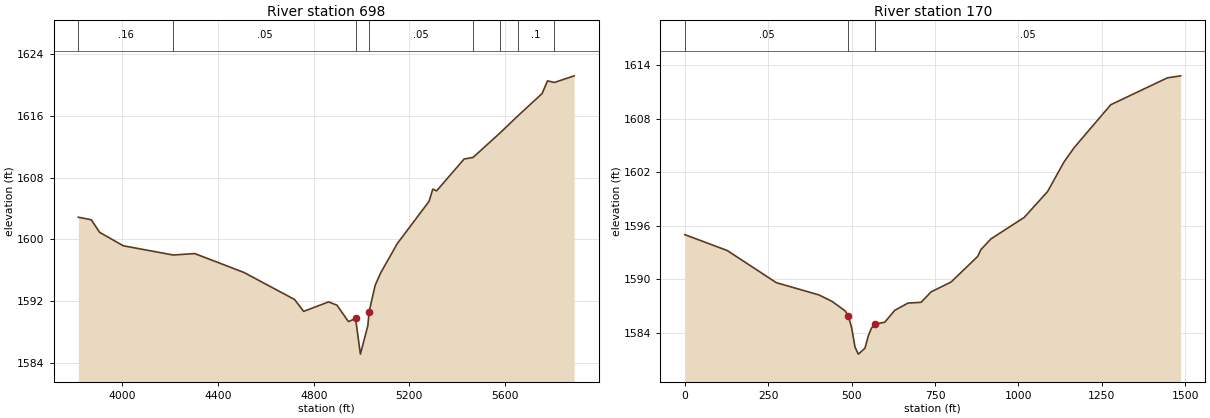
Type RM Length L Ch R = 1 ,698     ,528,528,528
BEGIN DESCRIPTION:
UNT095 IN NNOGR 1.0
END DESCRIPTION:
XS GIS Cut Line= 4
      2830656.29     10091670.25      2831294.29     10092212.77
      2831923.63     10092069.54      2832240.47     10091570.42
#Sta/Elev= 30
  3815.4 1602.87  3869.5 1602.54  3904.6 1600.91  4003.4 1599.17  4212.7 1597.97
  4302.2 1598.16  4507.6 1595.72    4720 1592.21  4757.9 1590.67  4862.3  1591.9
  4897.3 1591.47  4945.4 1589.34  4975.1 1589.76  4995.3 1585.13  5026.4 1588.81
  5031.5 1590.59  5057.1 1594.05  5079.7 1595.63  5149.4 1599.44  5282.8 1604.94
  5298.2 1606.51  5313.9 1606.28  5429.1 1610.41  5466.8 1610.62  5580.2 1613.81
  5654.6 1616.02  5755.3 1618.89  5778.1 1620.54  5806.9 1620.33  5889.5 1621.19
#Mann= 8 ,-1 , 0
  3815.4     .16       0  4212.7     .05       0  4975.1     .03       0
  5031.5     .05       0  5466.8      .1       0  5580.2     .05       0
  5654.6      .1       0  5806.9     .05       0
Bank Sta=4975.1,5031.5
XS Rating Curve= 0 ,0
Exp/Cntr=0.3,0.1

Type RM Length L Ch R = 1 ,170     ,0,0,0
XS GIS Cut Line= 4
     2831181.558    10092159.224     2831407.253    10092562.002
       2831645.1     10092629.71     2832226.697     10092134.92
#Sta/Elev= 30
       0 1595.03  127.43 1593.24  274.46 1589.64  401.89 1588.27   441.1 1587.55
  480.52 1586.48  490.42 1585.91  500.33 1584.54  510.24 1582.42  520.14 1581.63
  539.96 1582.29  549.86 1583.66  559.77 1584.56  569.68 1584.98   599.4 1585.21
  629.12 1586.53  668.75 1587.35  708.38 1587.44  738.23 1588.61  798.07 1589.71
  877.85 1592.58  887.83 1593.36  917.75 1594.55 1017.48 1596.96 1087.29 1599.85
 1137.16  1603.2 1167.08 1604.78 1276.78 1609.59 1446.33  1612.6 1486.22 1612.83
#Mann= 3 , 0 , 0
       0     .05       0  490.42     .03       0  569.68     .05       0
Bank Sta=490.42,569.68
XS Rating Curve= 0 ,0
Exp/Cntr=0.3,0.1

Chan Stop Cuts=-1
Use User Specified Reach Order=0
Composite Channel Slope=5