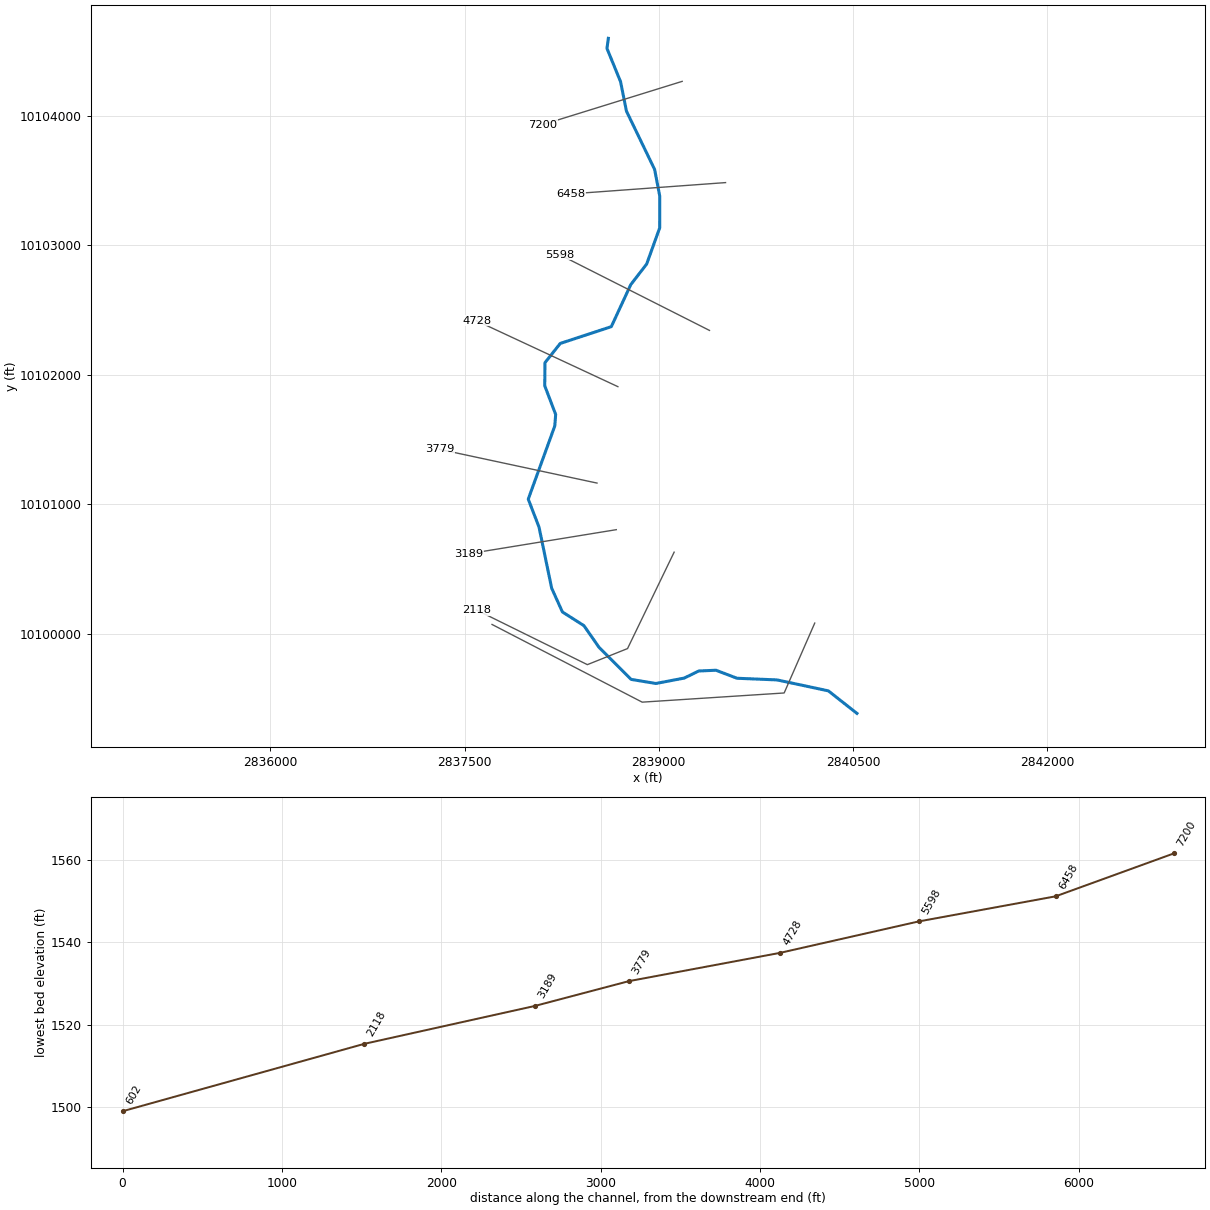
--- UNT096 IN NNOGR.prj (project) ---

Proj Title=UNT096 IN NNOGR Base Level Engineering
Current Plan=p01
Default Exp/Contr=0.3,0.1
English Units
Geom File=g01
Flow File=f01
Plan File=p01
BEGIN DESCRIPTION:
UNT096 IN NNOGR
END DESCRIPTION:

--- UNT096 IN NNOGR.p01 (plan) ---

Plan Title=Multiple Run
Short Identifier=Multiple
Geom File=g01
Flow File=f01
Subcritical Flow
K Sum by GR= 0
Std Step Tol= 0.01
Critical Tol= 0.01
Num of Std Step Trials= 20
Max Error Tol= 0.3
Flow Tol Ratio= 0.001
Split Flow NTrial= 30
Split Flow Tol= 0.02
Split Flow Ratio= 0.02
Log Output Level= 0
Friction Slope Method= 1
Unsteady Friction Slope Method= 2
Unsteady Bridges Friction Slope Method= 1
Parabolic Critical Depth
Global Vel Dist=  1 , 1 , 1
Global Log Level= 0
CheckData=True
Encroach Param= -1, 0, 0, 0
BEGIN DESCRIPTION:
Multiple Run
END DESCRIPTION:

--- UNT096 IN NNOGR.f01 (steady flow) ---

Flow Title=Multiple
Number of Profiles=7
Profile Names=10-year,25-year,50-year,1pct_min,100-year,1pct_plu,500-year
River Rch & RM= UNT096 IN NNOGR,Reach-1,7200
     646     916    1145    1048    1417    1917    2181
River Rch & RM= UNT096 IN NNOGR,Reach-1,6458
    1094    1594    2028    1886    2551    3450    4054
Boundary for River Rch & Prof#=UNT096 IN NNOGR,Reach-1,1
Up Type=0
Dn Type=3
Dn Slope=0.005
Boundary for River Rch & Prof#=UNT096 IN NNOGR,Reach-1,2
Up Type=0
Dn Type=3
Dn Slope=0.005
Boundary for River Rch & Prof#=UNT096 IN NNOGR,Reach-1,3
Up Type=0
Dn Type=3
Dn Slope=0.005
Boundary for River Rch & Prof#=UNT096 IN NNOGR,Reach-1,4
Up Type=0
Dn Type=3
Dn Slope=0.005
Boundary for River Rch & Prof#=UNT096 IN NNOGR,Reach-1,5
Up Type=0
Dn Type=3
Dn Slope=0.005
Boundary for River Rch & Prof#=UNT096 IN NNOGR,Reach-1,6
Up Type=0
Dn Type=3
Dn Slope=0.005
Boundary for River Rch & Prof#=UNT096 IN NNOGR,Reach-1,7
Up Type=0
Dn Type=3
Dn Slope=0.005

--- UNT096 IN NNOGR.g01 (geometry) ---

Geom Title=Existing Conditions

River Reach=UNT096 IN NNOGR,Reach-1
Reach XY= 30
      2838610.90     10104597.64      2838600.22     10104519.62
      2838705.34     10104262.44      2838750.97     10104034.75
      2838968.48     10103584.68      2839007.84     10103379.12
      2839007.37     10103133.79      2838906.75     10102854.42
      2838784.32     10102696.03      2838633.75     10102370.89
      2838239.40     10102241.31      2838121.36     10102092.53
      2838119.71     10101914.25      2838204.05     10101692.95
      2838197.30     10101604.27      2837992.35     10101038.79
      2838075.58     10100822.62      2838173.20     10100350.98
      2838256.15     10100167.65      2838422.20     10100061.94
      2838539.50     10099893.54      2838786.83     10099646.88
      2838978.13     10099615.27      2839197.13     10099656.96
      2839309.10     10099711.75      2839442.27     10099717.48
      2839604.26     10099655.64      2839914.03     10099642.79
      2840310.03     10099558.20      2840530.52     10099384.40

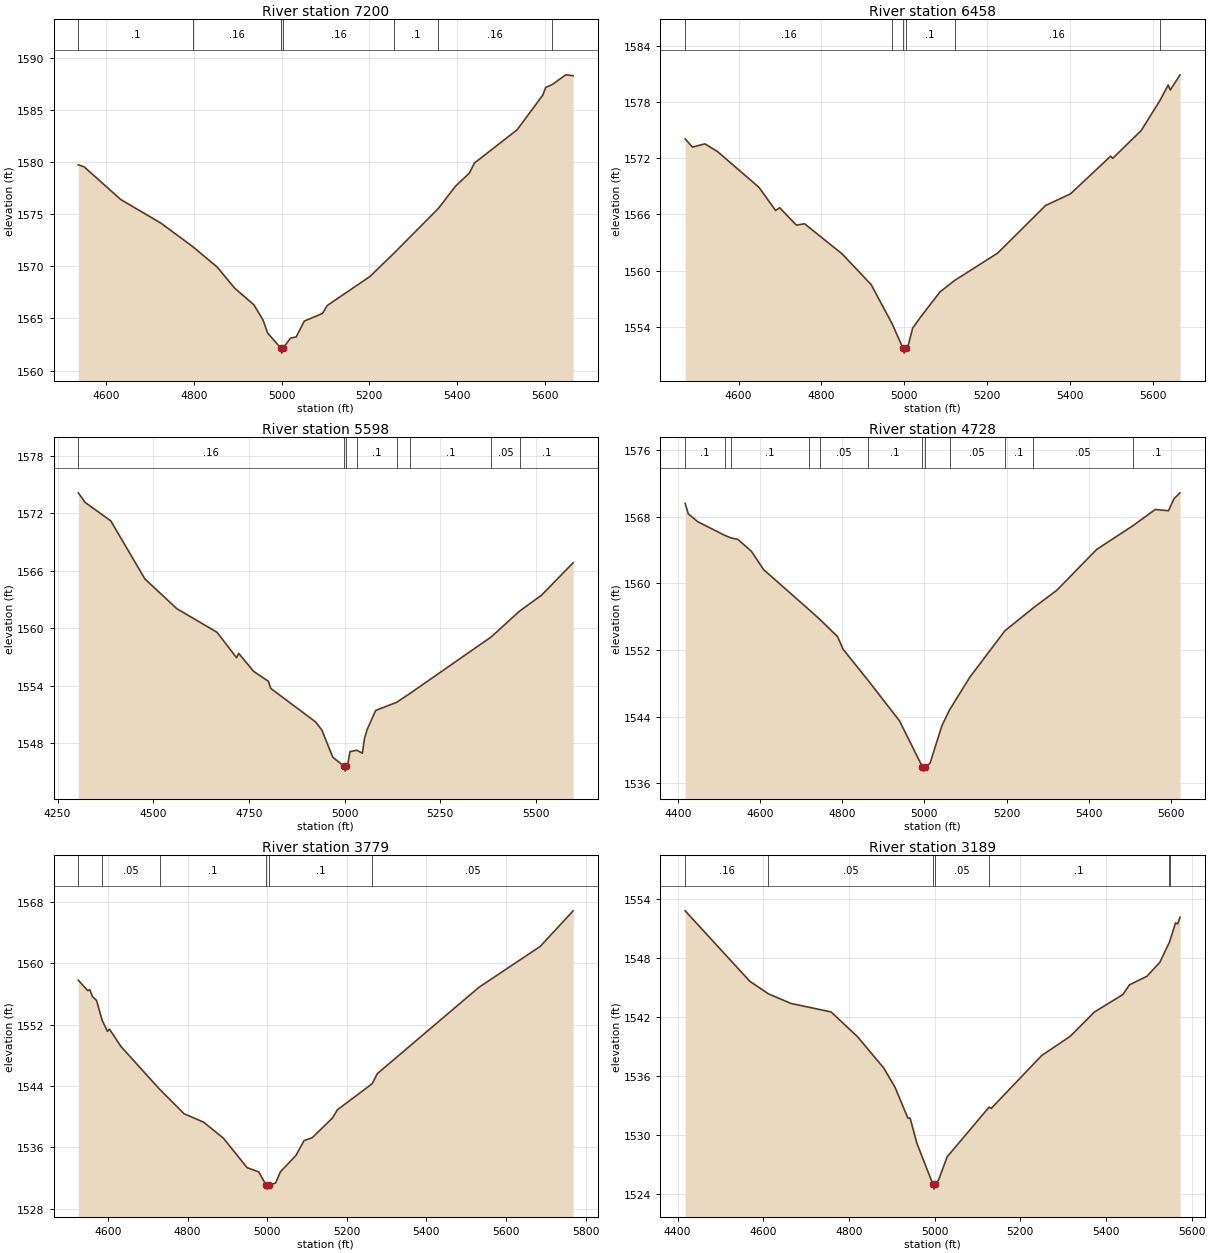
Type RM Length L Ch R = 1,7200,742,742,742
BEGIN DESCRIPTION:
UNT096 IN NNOGR 12.0
END DESCRIPTION:
XS GIS Cut Line= 2
      2839181.07     10104265.34      2838102.42     10103930.58
#Sta/Elev= 30
  4535.8 1579.72  4549.0 1579.53  4632.8 1576.39  4724.3 1574.13  4796.9 1571.88
  4852.6 1569.93  4892.4 1567.91  4936.4 1566.31  4957.3 1564.86  4968.0 1563.60
  4997.6 1562.17  5000.3 1561.67  5003.6 1562.17  5020.2 1563.11  5033.1 1563.22
  5051.6 1564.74  5093.1 1565.47  5103.9 1566.23  5201.3 1569.01  5255.9 1571.23
  5357.9 1575.55  5396.7 1577.67  5428.5 1578.93  5439.8 1579.88  5537.5 1583.08
  5596.0 1586.40  5602.6 1587.14  5616.5 1587.38  5648.4 1588.34  5665.2 1588.26
#Mann=7,-1,0
  4535.8     0.1       0  4796.9    0.16       0  4997.6    0.07       0
  5003.6    0.16       0  5255.9     0.1       0  5357.9    0.16       0
  5616.5     0.1       0
Bank Sta=4997.6,5003.6
Exp/Cntr=0.3,0.1

Type RM Length L Ch R = 1,6458,860,860,860
BEGIN DESCRIPTION:
UNT096 IN NNOGR 10.0
END DESCRIPTION:
XS GIS Cut Line= 2
      2839516.05     10103483.53      2838324.81     10103396.67
#Sta/Elev= 30
  4471.2 1574.06  4488.8 1573.19  4518.9 1573.53  4549.0 1572.72  4649.3 1568.90
  4689.4 1566.43  4699.4 1566.72  4739.5 1564.87  4759.5 1565.01  4849.8 1561.81
  4920.0 1558.53  4970.5 1554.37  4997.2 1551.72  4999.9 1551.22  5003.2 1551.72
  5010.2 1552.16  5020.2 1553.88  5040.3 1555.12  5086.3 1557.75  5121.7 1558.97
  5225.3 1561.88  5341.1 1566.96  5401.2 1568.20  5498.1 1572.22  5503.1 1571.99
  5571.7 1574.94  5617.1 1578.15  5637.1 1579.81  5642.1 1579.27  5665.6 1580.89
#Mann=6,-1,0
  4471.2    0.16       0  4970.5     0.1       0  4997.2    0.07       0
  5003.2     0.1       0  5121.7    0.16       0  5617.1     0.1       0
Bank Sta=4997.2,5003.2
Exp/Cntr=0.3,0.1

Type RM Length L Ch R = 1,5598,870,870,870
BEGIN DESCRIPTION:
UNT096 IN NNOGR 9.0
END DESCRIPTION:
XS GIS Cut Line= 2
      2839391.95     10102341.89      2838237.95     10102925.10
#Sta/Elev= 30
  4304.0 1574.14  4321.9 1573.14  4388.8 1571.22  4478.0 1565.16  4561.5 1562.05
  4666.5 1559.59  4717.6 1556.93  4723.2 1557.39  4762.1 1555.51  4800.9 1554.47
  4806.7 1553.74  4924.2 1550.23  4940.5 1549.38  4969.0 1546.55  4998.7 1545.60
  5001.5 1545.10  5004.7 1545.60  5007.3 1545.62  5013.8 1547.13  5031.5 1547.28
  5046.3 1546.97  5051.9 1548.53  5058.6 1549.42  5081.0 1551.43  5135.9 1552.28
  5169.7 1553.18  5383.1 1559.11  5457.1 1561.80  5514.4 1563.46  5597.0 1566.84
#Mann=8,-1,0
  4304.0    0.16       0  4998.7    0.07       0  5004.7    0.16       0
  5031.5     0.1       0  5135.9    0.05       0  5169.7     0.1       0
  5383.1    0.05       0  5457.1     0.1       0
Bank Sta=4998.7,5004.7
Exp/Cntr=0.3,0.1

Type RM Length L Ch R = 1,4728,949,949,949
BEGIN DESCRIPTION:
UNT096 IN NNOGR 5.0
END DESCRIPTION:
XS GIS Cut Line= 2
      2838684.66     10101907.55      2837593.03     10102416.15
#Sta/Elev= 30
  4417.8 1569.58  4425.4 1568.33  4448.3 1567.39  4513.9 1565.75  4529.2 1565.44
  4546.0 1565.27  4579.1 1563.83  4608.4 1561.65  4719.9 1556.80  4744.9 1555.69
  4788.7 1553.59  4802.4 1552.06  4862.5 1548.37  4939.6 1543.47  4995.3 1537.95
  4998.1 1537.45  5001.3 1537.95  5013.7 1538.39  5042.4 1542.88  5061.3 1544.81
  5110.7 1548.73  5195.8 1554.29  5264.7 1557.03  5322.1 1559.15  5419.1 1564.05
  5507.9 1566.92  5561.8 1568.85  5594.0 1568.70  5607.6 1570.16  5622.1 1570.85
#Mann=12,-1,0
  4417.8     0.1       0  4513.9    0.16       0  4529.2     0.1       0
  4719.9    0.16       0  4744.9    0.05       0  4862.5     0.1       0
  4995.3    0.07       0  5001.3     0.1       0  5061.3    0.05       0
  5195.8     0.1       0  5264.7    0.05       0  5507.9     0.1       0
Bank Sta=4995.3,5001.3
Exp/Cntr=0.3,0.1

Type RM Length L Ch R = 1,3779,590,590,590
BEGIN DESCRIPTION:
UNT096 IN NNOGR 4.0
END DESCRIPTION:
XS GIS Cut Line= 2
      2838523.35     10101162.99      2837307.26     10101423.58
#Sta/Elev= 30
  4525.1 1557.80  4549.0 1556.43  4554.1 1556.57  4560.8 1555.66  4571.0 1555.16
  4585.2 1552.56  4598.4 1551.13  4603.5 1551.42  4632.4 1549.15  4729.3 1543.59
  4791.0 1540.39  4840.4 1539.28  4889.9 1537.20  4949.4 1533.36  4978.5 1532.81
  4997.5 1531.06  5000.3 1530.56  5003.5 1531.06  5021.0 1531.36  5033.1 1532.82
  5072.1 1534.95  5092.6 1536.89  5113.0 1537.26  5164.2 1539.85  5176.2 1540.90
  5263.7 1544.30  5276.7 1545.62  5532.3 1556.88  5685.8 1562.19  5768.8 1566.84
#Mann=6,-1,0
  4525.1     0.1       0  4585.2    0.05       0  4729.3     0.1       0
  4997.5    0.07       0  5003.5     0.1       0  5263.7    0.05       0
Bank Sta=4997.5,5003.5
Exp/Cntr=0.3,0.1

Type RM Length L Ch R = 1,3189,1071,1071,1071
BEGIN DESCRIPTION:
UNT096 IN NNOGR 3.0
END DESCRIPTION:
XS GIS Cut Line= 2
      2838672.22     10100803.12      2837532.07     10100617.23
#Sta/Elev= 30
  4417.8 1552.82  4568.9 1545.65  4612.2 1544.38  4664.8 1543.40  4758.4 1542.54
  4819.9 1540.03  4881.3 1536.84  4907.9 1534.86  4937.7 1531.74  4942.8 1531.76
  4958.6 1529.20  4996.1 1525.02  4998.9 1524.52  5002.1 1525.02  5009.3 1525.45
  5029.5 1527.81  5127.1 1532.85  5132.3 1532.73  5250.1 1538.11  5316.7 1540.06
  5373.1 1542.53  5439.6 1544.31  5455.1 1545.30  5495.6 1546.16  5526.0 1547.59
  5548.3 1549.64  5549.2 1549.75  5562.5 1551.59  5567.6 1551.50  5573.0 1552.17
#Mann=7,-1,0
  4417.8    0.16       0  4612.2    0.05       0  4996.1   0.035       0
  5002.1    0.05       0  5127.1     0.1       0  5548.3    0.05       0
  5549.2     0.1       0
Bank Sta=4996.1,5002.1
Exp/Cntr=0.3,0.1

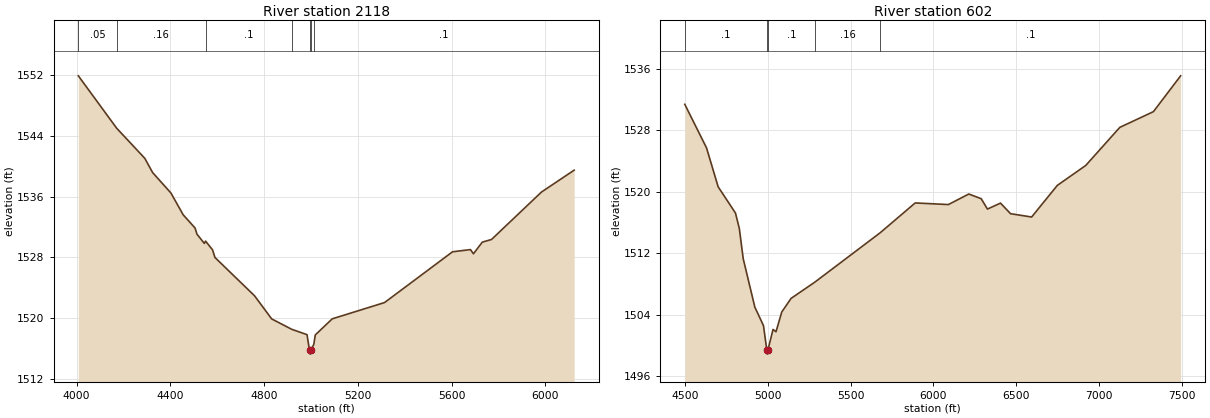
Type RM Length L Ch R = 1,2118,1516,1516,1516
BEGIN DESCRIPTION:
UNT096 IN NNOGR 2.0
END DESCRIPTION:
XS GIS Cut Line= 4
      2839118.98     10100629.40      2838759.11     10099884.83
      2838448.87     10099760.74      2837593.05     10100182.45
#Sta/Elev= 30
  4007.6 1551.87  4171.6 1544.97  4291.0 1541.03  4324.9 1539.14  4402.6 1536.47
  4454.8 1533.61  4505.5 1531.87  4513.7 1531.06  4545.1 1529.84  4550.4 1530.15
  4580.3 1528.99  4590.3 1528.00  4759.6 1522.95  4832.4 1519.92  4918.2 1518.55
  4983.2 1517.85  4993.8 1515.79  4996.6 1515.29  4999.8 1515.79  5012.2 1516.58
  5018.4 1517.81  5090.9 1519.93  5314.1 1522.07  5603.9 1528.74  5680.5 1529.03
  5693.1 1528.48  5731.0 1530.01  5770.3 1530.36  5983.6 1536.60  6122.8 1539.47
#Mann=7,-1,0
  4007.6    0.05       0  4171.6    0.16       0  4550.4     0.1       0
  4918.2    0.16       0  4993.8    0.07       0  4999.8    0.16       0
  5012.2     0.1       0
Bank Sta=4993.8,4999.8
Exp/Cntr=0.3,0.1

Type RM Length L Ch R = 1,602,0,0,0
BEGIN DESCRIPTION:
UNT096 IN NNOGR 1.0
END DESCRIPTION:
XS GIS Cut Line= 4
      2840204.85     10100081.76      2839968.68     10099541.94
      2838872.19     10099471.09      2837712.54     10100071.14
#Sta/Elev= 30
  4499.1 1531.37  4630.3 1525.71  4700.5 1520.65  4805.0 1517.24  4828.4 1515.22
  4851.8 1511.30  4921.9 1505.01  4974.2 1502.59  4994.6 1499.39  4997.3 1498.89
  5000.6 1499.39  5031.9 1502.10  5049.8 1501.80  5084.6 1504.37  5140.9 1506.14
  5283.6 1508.24  5678.1 1514.66  5890.2 1518.55  6090.6 1518.34  6213.8 1519.71
  6288.9 1519.10  6326.4 1517.75  6405.2 1518.53  6466.0 1517.15  6593.2 1516.72
  6748.2 1520.83  6919.7 1523.42  7125.8 1528.38  7328.5 1530.42  7492.8 1535.08
#Mann=5,-1,0
  4499.1     0.1       0  4994.6    0.07       0  5000.6     0.1       0
  5283.6    0.16       0  5678.1     0.1       0
Bank Sta=4994.6,5000.6
Exp/Cntr=0.3,0.1

Chan Stop Cuts=-1