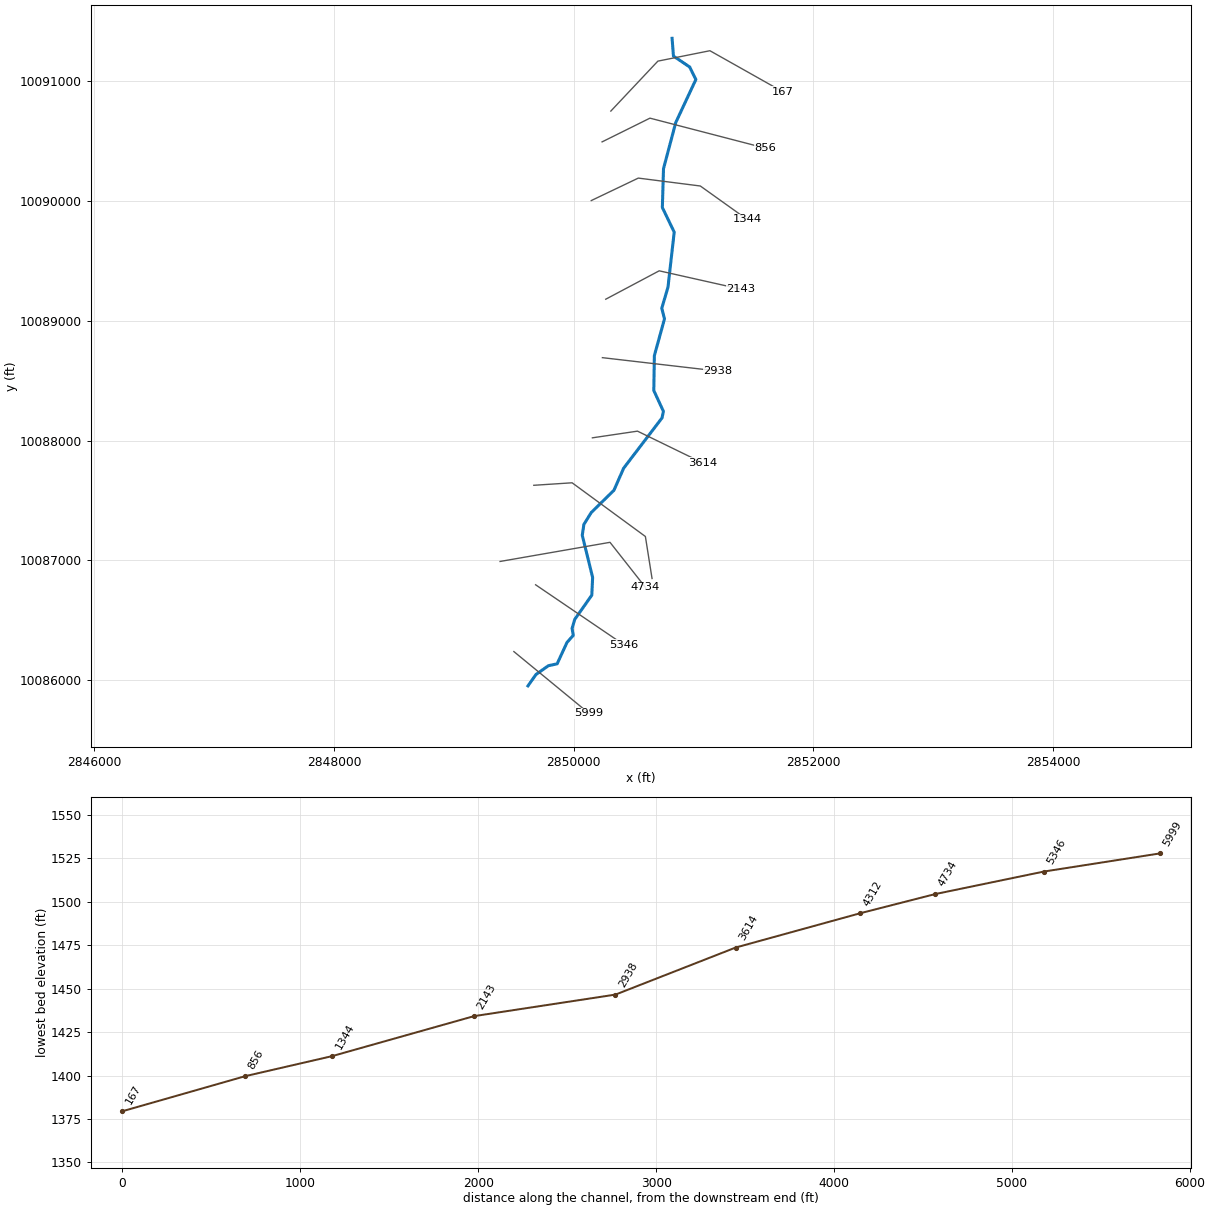
--- UNT098 IN NNOGR.prj (project) ---

Proj Title=UNT098 IN NNOGR Base Level Engineering
Current Plan=p01
Default Exp/Contr=0.3,0.1
English Units
Geom File=g01
Flow File=f01
Plan File=p01
BEGIN DESCRIPTION:
UNT098 IN NNOGR
END DESCRIPTION:

--- UNT098 IN NNOGR.p01 (plan) ---

Plan Title=Multiple Run
Short Identifier=Multiple
Geom File=g01
Flow File=f01
Subcritical Flow
K Sum by GR= 0
Std Step Tol= 0.01
Critical Tol= 0.01
Num of Std Step Trials= 20
Max Error Tol= 0.3
Flow Tol Ratio= 0.001
Split Flow NTrial= 30
Split Flow Tol= 0.02
Split Flow Ratio= 0.02
Log Output Level= 0
Friction Slope Method= 1
Unsteady Friction Slope Method= 2
Unsteady Bridges Friction Slope Method= 1
Parabolic Critical Depth
Global Vel Dist=  1 , 1 , 1
Global Log Level= 0
CheckData=True
Encroach Param= -1, 0, 0, 0
BEGIN DESCRIPTION:
Multiple Run
END DESCRIPTION:

--- UNT098 IN NNOGR.f01 (steady flow) ---

Flow Title=Multiple
Number of Profiles=7
Profile Names=10-year,25-year,50-year,1pct_min,100-year,1pct_plu,500-year
River Rch & RM= UNT098 IN NNOGR,Reach-1,5999
     816    1179    1493    1385    1873    2534    2959
River Rch & RM= UNT098 IN NNOGR,Reach-1,3614
    1435    2143    2776    2630    3557    4810    5862
Boundary for River Rch & Prof#=UNT098 IN NNOGR,Reach-1,1
Up Type=0
Dn Type=3
Dn Slope=0.005
Boundary for River Rch & Prof#=UNT098 IN NNOGR,Reach-1,2
Up Type=0
Dn Type=3
Dn Slope=0.005
Boundary for River Rch & Prof#=UNT098 IN NNOGR,Reach-1,3
Up Type=0
Dn Type=3
Dn Slope=0.005
Boundary for River Rch & Prof#=UNT098 IN NNOGR,Reach-1,4
Up Type=0
Dn Type=3
Dn Slope=0.005
Boundary for River Rch & Prof#=UNT098 IN NNOGR,Reach-1,5
Up Type=0
Dn Type=3
Dn Slope=0.005
Boundary for River Rch & Prof#=UNT098 IN NNOGR,Reach-1,6
Up Type=0
Dn Type=3
Dn Slope=0.005
Boundary for River Rch & Prof#=UNT098 IN NNOGR,Reach-1,7
Up Type=0
Dn Type=3
Dn Slope=0.005

--- UNT098 IN NNOGR.g01 (geometry) ---

Geom Title=Existing Conditions

River Reach=UNT098 IN NNOGR,Reach-1
Reach XY= 30
      2849618.50     10085953.70      2849685.59     10086048.88
      2849789.35     10086122.08      2849862.01     10086137.73
      2849944.16     10086316.16      2849996.27     10086374.98
      2849986.69     10086432.93      2850008.88     10086508.44
      2850151.01     10086710.34      2850157.97     10086858.43
      2850071.64     10087209.46      2850084.81     10087300.32
      2850146.30     10087399.59      2850335.74     10087585.47
      2850416.72     10087769.74      2850736.74     10088188.99
      2850748.47     10088243.73      2850668.21     10088417.18
      2850672.84     10088708.61      2850757.28     10089014.81
      2850734.74     10089103.50      2850786.40     10089279.65
      2850838.42     10089738.71      2850739.46     10089944.19
      2850749.11     10090268.34      2850851.13     10090652.63
      2851019.04     10091011.89      2850967.23     10091116.51
      2850831.94     10091207.28      2850820.61     10091355.32

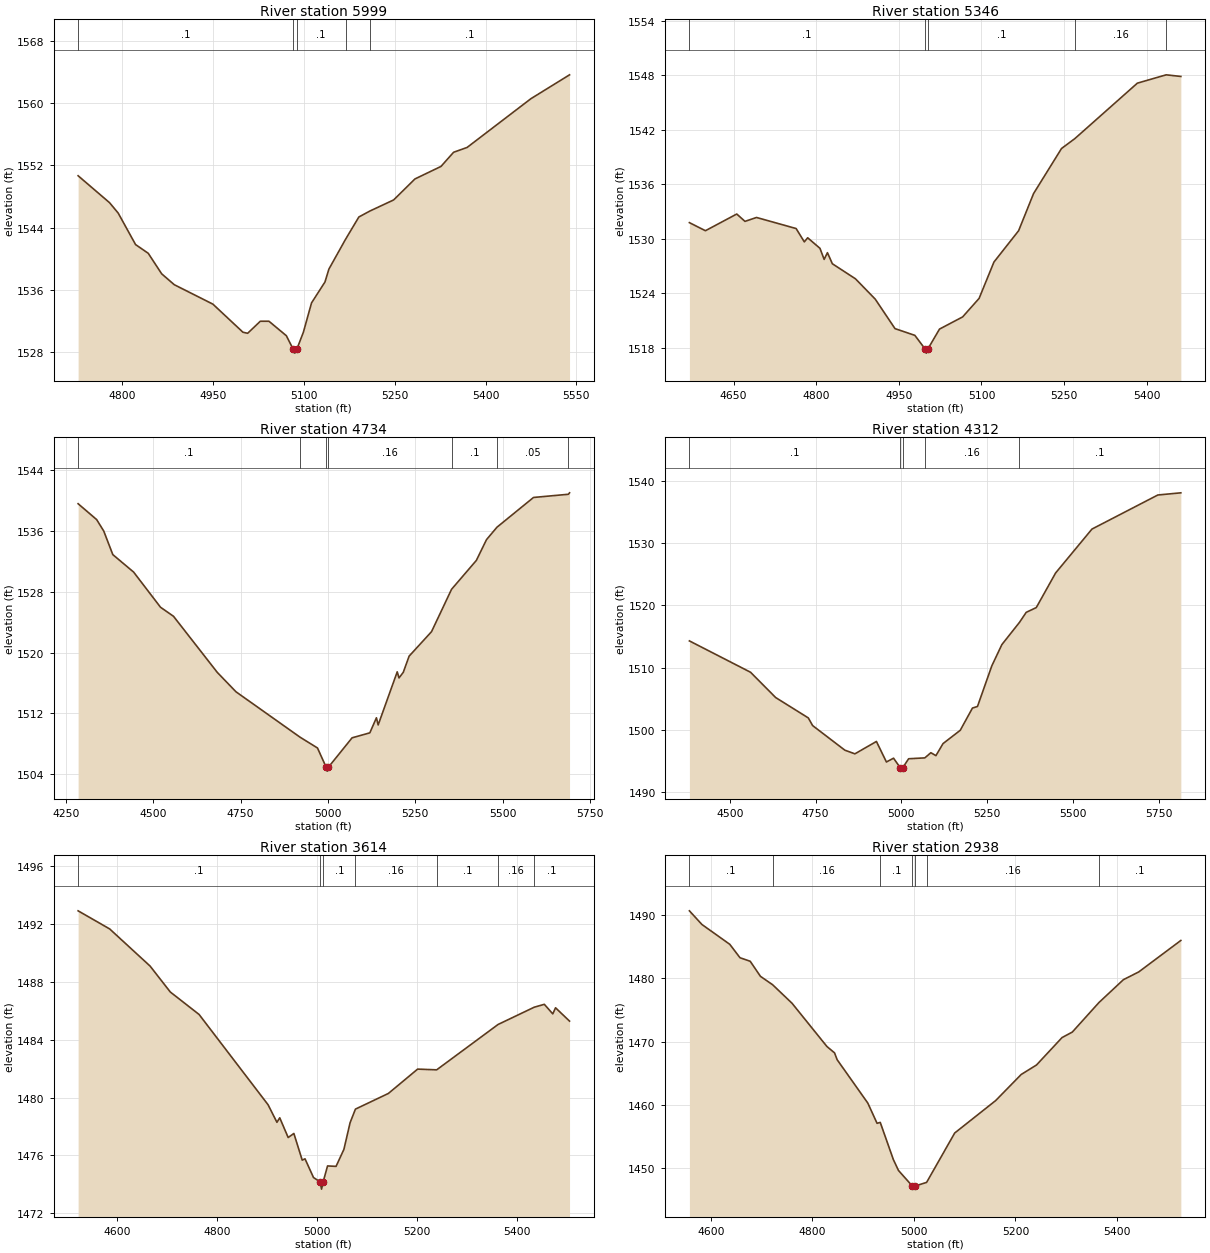
Type RM Length L Ch R = 1,5999,653,653,653
BEGIN DESCRIPTION:
UNT098 IN NNOGR 13.0
END DESCRIPTION:
XS GIS Cut Line= 2
      2849501.16     10086239.87      2850128.06     10085724.42
#Sta/Elev= 30
  4727.1 1550.66  4779.0 1547.20  4793.3 1545.86  4822.0 1541.81  4842.9 1540.69
  4865.1 1538.05  4885.9 1536.65  4949.7 1534.15  4999.3 1530.54  5007.1 1530.40
  5028.0 1531.95  5042.3 1531.95  5071.0 1530.09  5082.3 1528.35  5085.1 1527.85
  5088.3 1528.35  5099.1 1530.53  5112.6 1534.31  5134.8 1537.00  5141.3 1538.66
  5168.7 1542.48  5190.8 1545.36  5208.9 1546.12  5248.2 1547.55  5283.4 1550.25
  5326.4 1551.86  5347.2 1553.68  5369.5 1554.30  5474.9 1560.57  5538.7 1563.64
#Mann=5,-1,0
  4727.1     0.1       0  5082.3    0.07       0  5088.3     0.1       0
  5168.7    0.16       0  5208.9     0.1       0
Bank Sta=5082.3,5088.3
Exp/Cntr=0.3,0.1

Type RM Length L Ch R = 1,5346,612,612,612
BEGIN DESCRIPTION:
UNT098 IN NNOGR 12.0
END DESCRIPTION:
XS GIS Cut Line= 2
      2849682.32     10086797.05      2850420.61     10086295.57
#Sta/Elev= 30
  4569.6 1531.78  4598.7 1530.89  4655.6 1532.73  4670.5 1531.92  4691.5 1532.35
  4763.4 1531.13  4778.3 1529.66  4784.4 1530.11  4806.7 1528.95  4814.3 1527.73
  4820.3 1528.47  4829.2 1527.25  4871.2 1525.59  4907.1 1523.35  4943.0 1520.10
  4979.0 1519.36  4997.1 1517.90  4999.9 1517.40  5003.1 1517.90  5023.8 1520.05
  5065.8 1521.39  5095.7 1523.43  5122.7 1527.44  5167.5 1530.89  5194.6 1534.98
  5245.4 1539.95  5269.6 1541.04  5383.1 1547.15  5435.5 1548.07  5462.1 1547.89
#Mann=5,-1,0
  4569.6     0.1       0  4997.1    0.07       0  5003.1     0.1       0
  5269.6    0.16       0  5435.5     0.1       0
Bank Sta=4997.1,5003.1
Exp/Cntr=0.3,0.1

Type RM Length L Ch R = 1,4734,422,422,422
BEGIN DESCRIPTION:
Mapping XS 3103b8cd
END DESCRIPTION:
XS GIS Cut Line= 3
      2849386.14     10086991.60      2850302.83     10087151.32
      2850597.03     10086777.51
#Sta/Elev= 30
  4285.2 1539.56  4338.3 1537.47  4358.6 1535.96  4384.5 1532.87  4444.1 1530.57
  4521.0 1525.95  4558.2 1524.76  4683.4 1517.39  4736.9 1514.84  4920.0 1508.88
  4970.2 1507.45  4995.1 1504.91  4997.9 1504.41  5001.1 1504.91  5069.2 1508.79
  5119.9 1509.44  5138.8 1511.42  5143.8 1510.48  5198.3 1517.46  5203.4 1516.66
  5215.7 1517.40  5232.3 1519.52  5296.5 1522.74  5353.8 1528.31  5424.8 1532.11
  5453.7 1534.83  5483.7 1536.47  5588.3 1540.38  5688.1 1540.80  5691.4 1540.99
#Mann=7,-1,0
  4285.2     0.1       0  4920.0    0.16       0  4995.1    0.07       0
  5001.1    0.16       0  5353.8     0.1       0  5483.7    0.05       0
  5688.1     0.1       0
Bank Sta=4995.1,5001.1
Exp/Cntr=0.3,0.1

Type RM Length L Ch R = 1,4312,698,698,698
BEGIN DESCRIPTION:
UNT098 IN NNOGR 10.0
END DESCRIPTION:
XS GIS Cut Line= 4
      2849667.46     10087627.02      2849986.86     10087647.85
      2850597.97     10087199.93      2850653.49     10086849.46
#Sta/Elev= 30
  4382.1 1514.30  4560.3 1509.26  4633.6 1505.19  4728.6 1501.92  4741.4 1500.68
  4835.2 1496.73  4864.5 1496.14  4927.3 1498.13  4956.4 1494.83  4977.2 1495.44
  4997.4 1493.86  5000.1 1493.36  5003.4 1493.86  5021.2 1495.35  5068.4 1495.49
  5086.0 1496.32  5100.7 1495.85  5121.5 1497.79  5171.7 1499.93  5207.2 1503.50
  5221.9 1503.76  5263.6 1510.28  5292.9 1513.70  5344.3 1517.28  5363.9 1518.89
  5393.3 1519.66  5449.6 1525.22  5555.6 1532.28  5747.6 1537.76  5814.7 1538.11
#Mann=5,-1,0
  4382.1     0.1       0  4997.4    0.07       0  5003.4     0.1       0
  5068.4    0.16       0  5344.3     0.1       0
Bank Sta=4997.4,5003.4
Exp/Cntr=0.3,0.1

Type RM Length L Ch R = 1,3614,676,676,676
BEGIN DESCRIPTION:
UNT098 IN NNOGR 9.0
END DESCRIPTION:
XS GIS Cut Line= 3
      2850155.98     10088022.97      2850532.06     10088078.69
      2851074.43     10087814.45
#Sta/Elev= 30
  4521.5 1492.88  4584.7 1491.63  4665.5 1489.07  4706.0 1487.28  4763.6 1485.73
  4901.7 1479.50  4919.4 1478.29  4925.0 1478.60  4941.9 1477.24  4953.3 1477.52
  4970.0 1475.68  4975.6 1475.77  4992.6 1474.48  5005.9 1474.18  5008.7 1473.68
  5011.9 1474.18  5020.7 1475.28  5037.7 1475.25  5053.4 1476.42  5065.8 1478.26
  5076.5 1479.20  5142.4 1480.28  5201.0 1481.96  5239.1 1481.91  5362.0 1485.04
  5434.3 1486.23  5454.5 1486.43  5471.5 1485.77  5477.0 1486.19  5505.0 1485.27
#Mann=7,-1,0
  4521.5     0.1       0  5005.9    0.07       0  5011.9     0.1       0
  5076.5    0.16       0  5239.1     0.1       0  5362.0    0.16       0
  5434.3     0.1       0
Bank Sta=5005.9,5011.9
Exp/Cntr=0.3,0.1

Type RM Length L Ch R = 1,2938,795,795,795
BEGIN DESCRIPTION:
UNT098 IN NNOGR 8.0
END DESCRIPTION:
XS GIS Cut Line= 2
      2850239.51     10088691.63      2851200.77     10088580.18
#Sta/Elev= 30
  4558.1 1490.73  4582.8 1488.56  4637.6 1485.42  4657.7 1483.29  4677.8 1482.73
  4698.0 1480.34  4721.9 1479.01  4760.2 1476.07  4828.9 1469.21  4843.9 1468.20
  4849.0 1467.12  4909.4 1460.24  4927.6 1457.03  4933.9 1457.17  4959.7 1451.28
  4969.8 1449.55  4997.0 1447.09  4999.7 1446.59  5003.0 1447.09  5025.2 1447.66
  5080.5 1455.49  5161.1 1460.63  5211.4 1464.77  5241.6 1466.28  5291.9 1470.63
  5312.1 1471.50  5364.5 1476.18  5412.7 1479.81  5442.9 1481.04  5525.8 1486.03
#Mann=7,-1,0
  4558.1     0.1       0  4721.9    0.16       0  4933.9     0.1       0
  4997.0    0.07       0  5003.0     0.1       0  5025.2    0.16       0
  5364.5     0.1       0
Bank Sta=4997,5003
Exp/Cntr=0.3,0.1

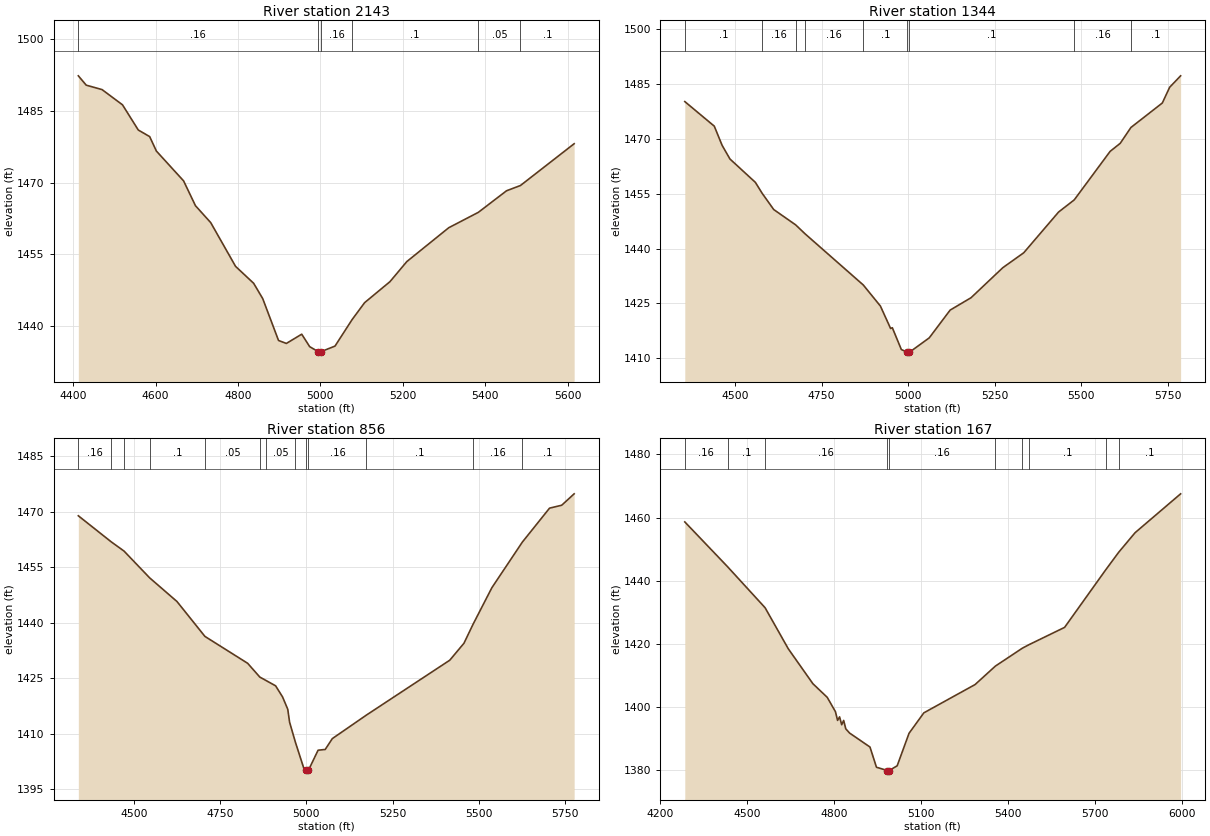
Type RM Length L Ch R = 1,2143,799,799,799
BEGIN DESCRIPTION:
UNT098 IN NNOGR 4.0
END DESCRIPTION:
XS GIS Cut Line= 3
      2850267.40     10089179.22      2850713.16     10089416.03
      2851394.64     10089263.04
#Sta/Elev= 30
  4412.5 1492.27  4431.7 1490.32  4470.0 1489.40  4519.7 1486.22  4558.0 1480.96
  4585.6 1479.59  4601.9 1476.57  4667.9 1470.35  4696.8 1465.16  4733.8 1461.63
  4794.1 1452.50  4838.0 1448.97  4860.0 1445.77  4898.3 1437.04  4917.3 1436.42
  4954.6 1438.35  4973.9 1435.75  4994.9 1434.69  4997.6 1434.19  5000.9 1434.69
  5035.4 1435.87  5076.8 1441.39  5107.2 1444.93  5168.7 1449.31  5209.7 1453.51
  5311.4 1460.57  5383.2 1463.78  5451.6 1468.28  5485.4 1469.38  5615.7 1478.10
#Mann=6,-1,0
  4412.5    0.16       0  4994.9    0.07       0  5000.9    0.16       0
  5076.8     0.1       0  5383.2    0.05       0  5485.4     0.1       0
Bank Sta=4994.9,5000.9
Exp/Cntr=0.3,0.1

Type RM Length L Ch R = 1,1344,488,488,488
BEGIN DESCRIPTION:
UNT098 IN NNOGR 3.0
END DESCRIPTION:
XS GIS Cut Line= 4
      2850146.60     10090002.03      2850538.94     10090189.52
      2851056.30     10090123.54      2851444.30     10089846.40
#Sta/Elev= 30
  4354.5 1480.20  4439.7 1473.48  4462.3 1468.25  4485.0 1464.50  4558.6 1458.10
  4577.6 1455.19  4611.5 1450.68  4675.0 1446.48  4702.2 1444.03  4870.5 1430.04
  4919.9 1424.29  4949.4 1418.15  4954.4 1418.36  4980.4 1412.40  4997.6 1411.64
  5000.3 1411.14  5003.6 1411.64  5061.0 1415.58  5121.5 1423.18  5182.0 1426.57
  5273.8 1434.78  5334.2 1438.85  5434.9 1449.99  5480.2 1453.32  5583.9 1466.58
  5613.1 1468.78  5644.1 1473.12  5734.8 1479.81  5756.0 1484.11  5787.7 1487.24
#Mann=9,-1,0
  4354.5     0.1       0  4577.6    0.16       0  4675.0     0.1       0
  4702.2    0.16       0  4870.5     0.1       0  4997.6    0.07       0
  5003.6     0.1       0  5480.2    0.16       0  5644.1     0.1       0
Bank Sta=4997.6,5003.6
Exp/Cntr=0.3,0.1

Type RM Length L Ch R = 1,856,689,689,689
BEGIN DESCRIPTION:
Mapping XS 3ceee875
END DESCRIPTION:
XS GIS Cut Line= 3
      2850236.87     10090491.61      2850636.16     10090689.52
      2851597.96     10090439.52
#Sta/Elev= 30
  4337.9 1468.86  4434.1 1461.77  4470.3 1459.35  4545.0 1452.09  4624.2 1445.71
  4705.4 1436.28  4829.4 1429.02  4864.8 1425.29  4881.6 1424.43  4910.5 1422.94
  4930.6 1419.97  4945.9 1416.60  4951.2 1413.11  4967.9 1407.75  4992.6 1400.63
  4999.9 1400.12  5002.7 1399.62  5005.9 1400.12  5033.9 1405.54  5054.6 1405.74
  5075.2 1408.67  5174.1 1415.02  5416.2 1429.85  5457.4 1434.43  5483.5 1439.50
  5538.5 1449.44  5626.8 1461.74  5705.8 1470.92  5741.2 1471.71  5777.3 1474.79
#Mann=13,-1,0
  4337.9    0.16       0  4434.1     0.1       0  4470.3    0.16       0
  4545.0     0.1       0  4705.4    0.05       0  4864.8     0.1       0
  4881.6    0.05       0  4967.9    0.16       0  4999.9    0.07       0
  5005.9    0.16       0  5174.1     0.1       0  5483.5    0.16       0
  5626.8     0.1       0
Bank Sta=4999.9,5005.9
Exp/Cntr=0.3,0.1

Type RM Length L Ch R = 1,167,0,0,0
BEGIN DESCRIPTION:
UNT098 IN NNOGR 1.0
END DESCRIPTION:
XS GIS Cut Line= 4
      2850309.75     10090748.53      2850702.13     10091165.21
      2851136.16     10091252.02      2851740.35     10090911.73
#Sta/Elev= 30
  4285.2 1458.66  4432.4 1444.50  4561.8 1431.51  4641.7 1418.52  4726.6 1407.45
  4776.0 1403.14  4804.3 1398.59  4811.6 1395.84  4818.5 1396.96  4825.8 1394.47
  4832.6 1395.83  4839.9 1393.17  4853.1 1391.83  4923.3 1387.41  4945.6 1381.02
  4983.4 1379.97  4986.1 1379.47  4989.4 1379.97  5017.0 1381.48  5057.8 1391.75
  5108.8 1398.23  5285.3 1407.18  5355.4 1413.03  5448.2 1418.69  5471.5 1419.82
  5593.8 1425.28  5735.1 1443.44  5780.0 1449.03  5836.6 1455.24  5993.6 1467.55
#Mann=10,-1,0
  4285.2    0.16       0  4432.4     0.1       0  4561.8    0.16       0
  4983.4    0.07       0  4989.4    0.16       0  5355.4     0.1       0
  5448.2    0.16       0  5471.5     0.1       0  5735.1    0.16       0
  5780.0     0.1       0
Bank Sta=4983.4,4989.4
Exp/Cntr=0.3,0.1

Chan Stop Cuts=-1