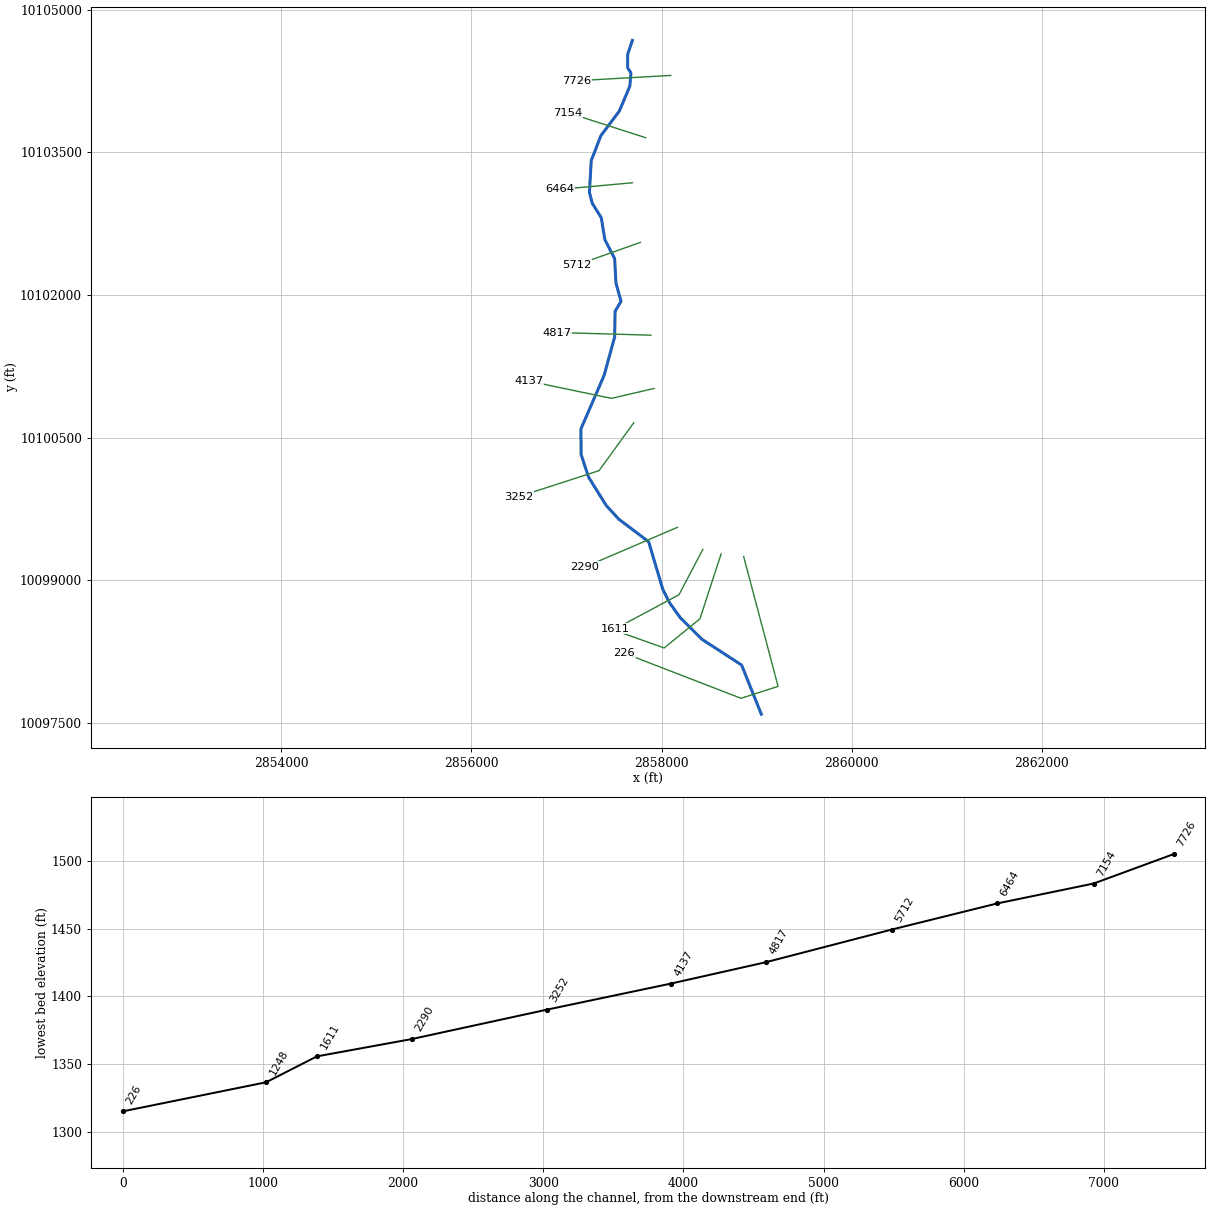
--- UNT099 IN NNOGR.prj (project) ---

Proj Title=UNT099 IN NNOGR Base Level Engineering
Current Plan=p01
Default Exp/Contr=0.3,0.1
English Units
Geom File=g01
Flow File=f01
Plan File=p01
BEGIN DESCRIPTION:
UNT099 IN NNOGR
END DESCRIPTION:

--- UNT099 IN NNOGR.p01 (plan) ---

Plan Title=Multiple Run
Short Identifier=Multiple
Geom File=g01
Flow File=f01
Subcritical Flow
K Sum by GR= 0
Std Step Tol= 0.01
Critical Tol= 0.01
Num of Std Step Trials= 20
Max Error Tol= 0.3
Flow Tol Ratio= 0.001
Split Flow NTrial= 30
Split Flow Tol= 0.02
Split Flow Ratio= 0.02
Log Output Level= 0
Friction Slope Method= 1
Unsteady Friction Slope Method= 2
Unsteady Bridges Friction Slope Method= 1
Parabolic Critical Depth
Global Vel Dist=  1 , 1 , 1
Global Log Level= 0
CheckData=True
Encroach Param= -1, 0, 0, 0
BEGIN DESCRIPTION:
Multiple Run
END DESCRIPTION:

--- UNT099 IN NNOGR.f01 (steady flow) ---

Flow Title=Multiple
Number of Profiles=7
Profile Names=10-year,25-year,50-year,1pct_min,100-year,1pct_plu,500-year
River Rch & RM= UNT099 IN NNOGR,Reach-1,7726
    1455    2181    2831    2687    3634    4915    6016
Boundary for River Rch & Prof#=UNT099 IN NNOGR,Reach-1,1
Up Type=0
Dn Type=3
Dn Slope=0.005
Boundary for River Rch & Prof#=UNT099 IN NNOGR,Reach-1,2
Up Type=0
Dn Type=3
Dn Slope=0.005
Boundary for River Rch & Prof#=UNT099 IN NNOGR,Reach-1,3
Up Type=0
Dn Type=3
Dn Slope=0.005
Boundary for River Rch & Prof#=UNT099 IN NNOGR,Reach-1,4
Up Type=0
Dn Type=3
Dn Slope=0.005
Boundary for River Rch & Prof#=UNT099 IN NNOGR,Reach-1,5
Up Type=0
Dn Type=3
Dn Slope=0.005
Boundary for River Rch & Prof#=UNT099 IN NNOGR,Reach-1,6
Up Type=0
Dn Type=3
Dn Slope=0.005
Boundary for River Rch & Prof#=UNT099 IN NNOGR,Reach-1,7
Up Type=0
Dn Type=3
Dn Slope=0.005

--- UNT099 IN NNOGR.g01 (geometry) ---

Geom Title=Existing Conditions

River Reach=UNT099 IN NNOGR,Reach-1
Reach XY= 30
      2857692.13     10104675.70      2857642.46     10104528.75
      2857642.15     10104388.65      2857677.04     10104334.05
      2857665.31     10104195.05      2857555.89     10103934.80
      2857360.18     10103673.02      2857259.59     10103413.27
      2857240.42     10103079.67      2857270.16     10102964.42
      2857364.76     10102812.25      2857403.05     10102580.94
      2857505.55     10102382.52      2857519.83     10102123.84
      2857573.00     10101933.62      2857510.30     10101828.06
      2857505.87     10101559.17      2857395.23     10101155.07
      2857151.29     10100592.56      2857152.53     10100324.34
      2857231.75     10100085.07      2857416.70     10099787.42
      2857548.64     10099644.29      2857863.31     10099406.31
      2858012.30     10098905.32      2858084.99     10098762.59
      2858195.12     10098608.39      2858426.09     10098378.96
      2858840.65     10098110.43      2859048.47     10097593.73

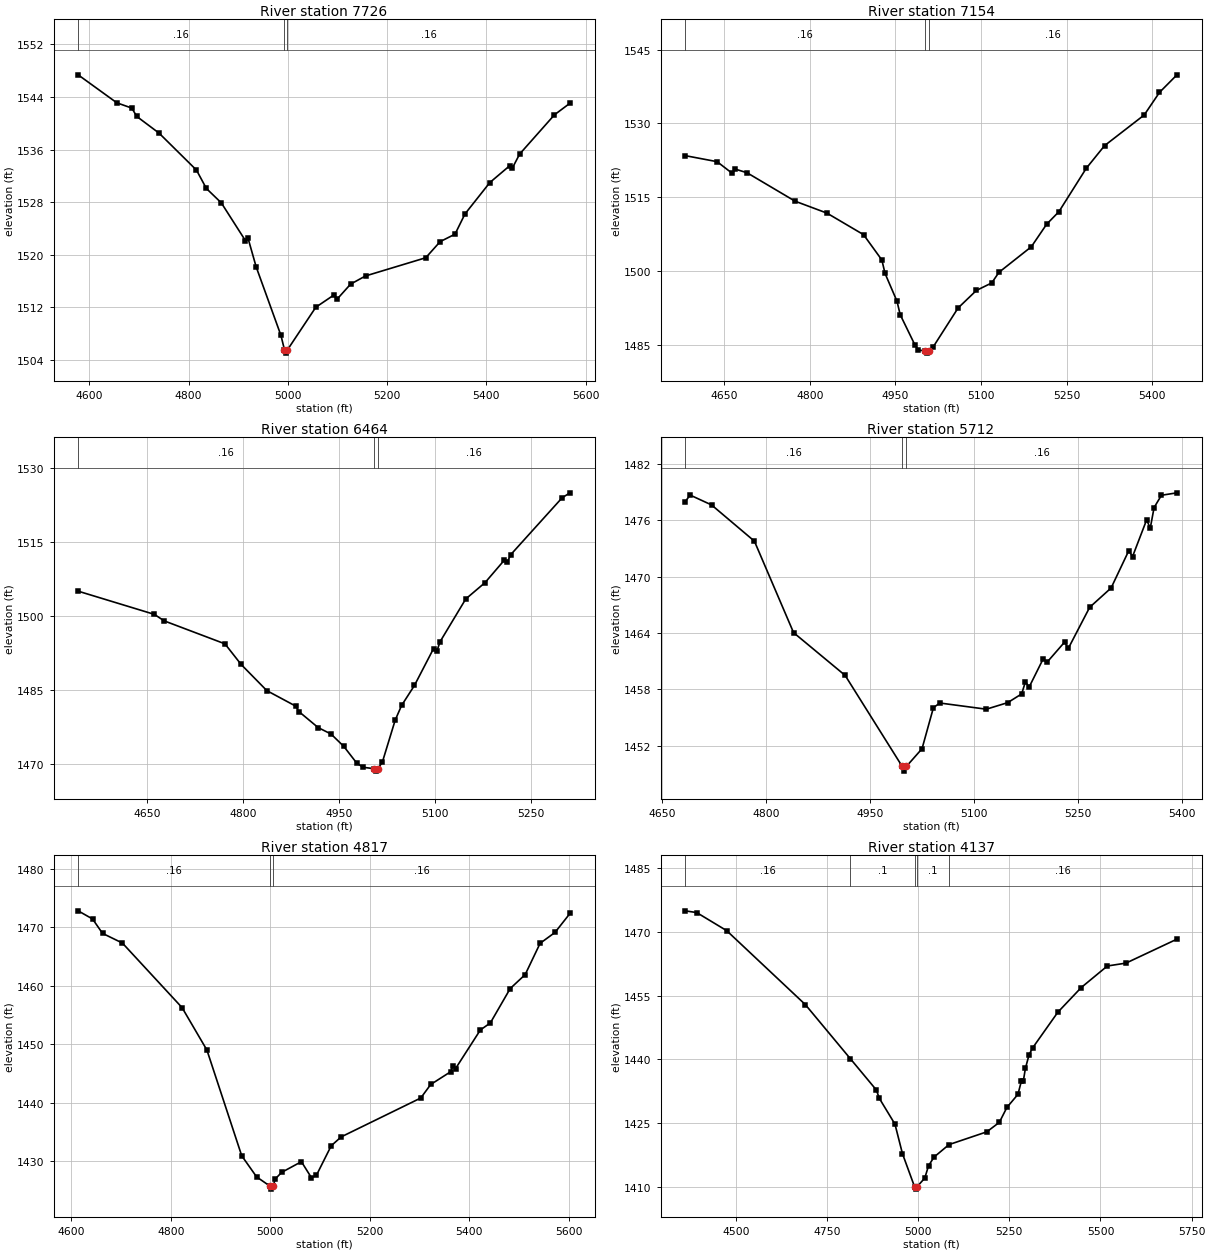
Type RM Length L Ch R = 1,7726,572,572,572
BEGIN DESCRIPTION:
UNT099 IN NNOGR 17.0
END DESCRIPTION:
XS GIS Cut Line= 2
      2858096.37     10104307.89      2857107.34     10104252.17
#Sta/Elev= 30
  4577.7 1547.38  4655.7 1543.12  4685.8 1542.32  4695.8 1541.05  4740.7 1538.51
  4816.0 1532.89  4836.0 1530.09  4866.1 1527.90  4914.7 1522.15  4919.7 1522.58
  4936.2 1518.18  4986.2 1507.73  4993.3 1505.54  4996.0 1505.04  4999.3 1505.54
  5056.4 1512.02  5093.8 1513.93  5098.8 1513.21  5126.5 1515.54  5156.5 1516.78
  5277.8 1519.55  5306.8 1522.00  5336.8 1523.14  5356.8 1526.21  5406.9 1530.99
  5446.8 1533.54  5451.8 1533.13  5467.0 1535.33  5537.1 1541.30  5568.3 1543.06
#Mann=3,-1,0
  4577.7    0.16       0  4993.3    0.07       0  4999.3    0.16       0
Bank Sta=4993.3,4999.3
Exp/Cntr=0.3,0.1

Type RM Length L Ch R = 1,7154,690,690,690
BEGIN DESCRIPTION:
UNT099 IN NNOGR 16.0
END DESCRIPTION:
XS GIS Cut Line= 2
      2857831.69     10103653.16      2857011.66     10103917.24
#Sta/Elev= 30
  4581.7 1523.44  4637.7 1522.21  4664.5 1519.81  4669.7 1520.69  4690.1 1519.96
  4774.2 1514.18  4830.1 1511.75  4894.2 1507.37  4926.3 1502.22  4931.8 1499.50
  4952.8 1493.83  4958.4 1491.10  4984.3 1484.92  4990.4 1483.87  5002.3 1483.78
  5005.1 1483.28  5008.3 1483.78  5015.8 1484.47  5059.8 1492.46  5091.9 1496.03
  5118.7 1497.55  5131.4 1499.71  5188.1 1504.91  5214.9 1509.49  5236.4 1512.04
  5284.3 1520.86  5316.4 1525.47  5385.8 1531.70  5412.6 1536.30  5443.2 1539.87
#Mann=3,-1,0
  4581.7    0.16       0  5002.3    0.07       0  5008.3    0.16       0
Bank Sta=5002.3,5008.3
Exp/Cntr=0.3,0.1

Type RM Length L Ch R = 1,6464,752,752,752
BEGIN DESCRIPTION:
UNT099 IN NNOGR 15.0
END DESCRIPTION:
XS GIS Cut Line= 2
      2857692.42     10103179.51      2856926.18     10103109.85
#Sta/Elev= 30
  4542.1 1505.05  4661.4 1500.34  4676.6 1499.03  4771.8 1494.36  4797.1 1490.18
  4837.3 1484.87  4882.3 1481.74  4887.5 1480.62  4917.6 1477.37  4937.7 1476.07
  4957.8 1473.54  4977.8 1470.19  4987.7 1469.32  5005.0 1469.04  5007.7 1468.54
  5011.0 1469.04  5018.0 1470.36  5038.1 1478.89  5048.1 1481.86  5068.2 1485.92
  5098.1 1493.40  5103.2 1492.87  5108.4 1494.82  5148.5 1503.47  5178.7 1506.79
  5208.6 1511.31  5213.6 1510.99  5218.8 1512.45  5299.2 1523.99  5311.5 1525.00
#Mann=3,-1,0
  4542.1    0.16       0  5005.0    0.07       0  5011.0    0.16       0
Bank Sta=5005,5011
Exp/Cntr=0.3,0.1

Type RM Length L Ch R = 1,5712,895,895,895
BEGIN DESCRIPTION:
UNT099 IN NNOGR 11.0
END DESCRIPTION:
XS GIS Cut Line= 2
      2857776.03     10102552.64      2857107.33     10102315.81
#Sta/Elev= 30
  4682.9 1477.99  4690.1 1478.70  4721.0 1477.65  4782.8 1473.79  4839.3 1464.04
  4913.7 1459.48  4996.0 1449.78  4998.8 1449.28  5002.0 1449.78  5024.6 1451.67
  5041.0 1456.04  5050.2 1456.54  5117.3 1455.88  5148.2 1456.58  5168.3 1457.51
  5173.7 1458.80  5179.1 1458.24  5199.3 1461.24  5204.6 1460.86  5230.2 1463.03
  5235.5 1462.35  5266.4 1466.74  5297.3 1468.80  5322.9 1472.79  5328.2 1472.14
  5348.5 1476.05  5353.8 1475.18  5359.3 1477.37  5369.9 1478.68  5392.3 1478.94
#Mann=3,-1,0
  4682.9    0.16       0  4996.0    0.07       0  5002.0    0.16       0
Bank Sta=4996,5002
Exp/Cntr=0.3,0.1

Type RM Length L Ch R = 1,4817,680,680,680
BEGIN DESCRIPTION:
UNT099 IN NNOGR 10.0
END DESCRIPTION:
XS GIS Cut Line= 2
      2857887.46     10101577.49      2856898.36     10101605.35
#Sta/Elev= 30
  4613.4 1472.79  4642.4 1471.40  4662.5 1468.94  4702.4 1467.29  4822.5 1456.26
  4872.5 1449.01  4942.5 1430.96  4972.5 1427.35  4999.6 1425.76  5002.3 1425.26
  5005.6 1425.76  5010.2 1427.01  5022.6 1428.11  5062.6 1429.95  5082.6 1427.23
  5092.6 1427.59  5122.6 1432.67  5142.6 1434.18  5302.7 1440.82  5322.7 1443.13
  5362.7 1445.30  5367.8 1446.34  5372.8 1445.86  5422.7 1452.45  5442.7 1453.64
  5482.7 1459.52  5512.8 1461.90  5542.8 1467.24  5572.8 1469.10  5602.9 1472.34
#Mann=3,-1,0
  4613.4    0.16       0  4999.6    0.07       0  5005.6    0.16       0
Bank Sta=4999.6,5005.6
Exp/Cntr=0.3,0.1

Type RM Length L Ch R = 1,4137,885,885,885
BEGIN DESCRIPTION:
UNT099 IN NNOGR 9.0
END DESCRIPTION:
XS GIS Cut Line= 3
      2857919.37     10101017.33      2857472.27     10100913.15
      2856601.65     10101095.07
#Sta/Elev= 30
  4361.3 1475.01  4393.0 1474.60  4475.2 1470.34  4690.8 1452.92  4814.2 1440.17
  4885.6 1432.79  4893.6 1430.84  4936.6 1424.74  4957.1 1417.80  4990.6 1409.93
  4993.3 1409.43  4996.6 1409.93  5018.4 1412.05  5028.6 1414.92  5043.6 1416.97
  5084.7 1419.92  5188.4 1422.93  5222.7 1425.16  5243.5 1428.67  5273.8 1431.77
  5283.3 1434.92  5288.4 1434.82  5294.2 1437.86  5304.4 1441.13  5314.6 1442.78
  5383.2 1451.12  5447.4 1456.94  5518.9 1462.01  5570.0 1462.69  5709.8 1468.34
#Mann=5,-1,0
  4361.3    0.16       0  4814.2     0.1       0  4990.6    0.07       0
  4996.6     0.1       0  5084.7    0.16       0
Bank Sta=4990.6,4996.6
Exp/Cntr=0.3,0.1

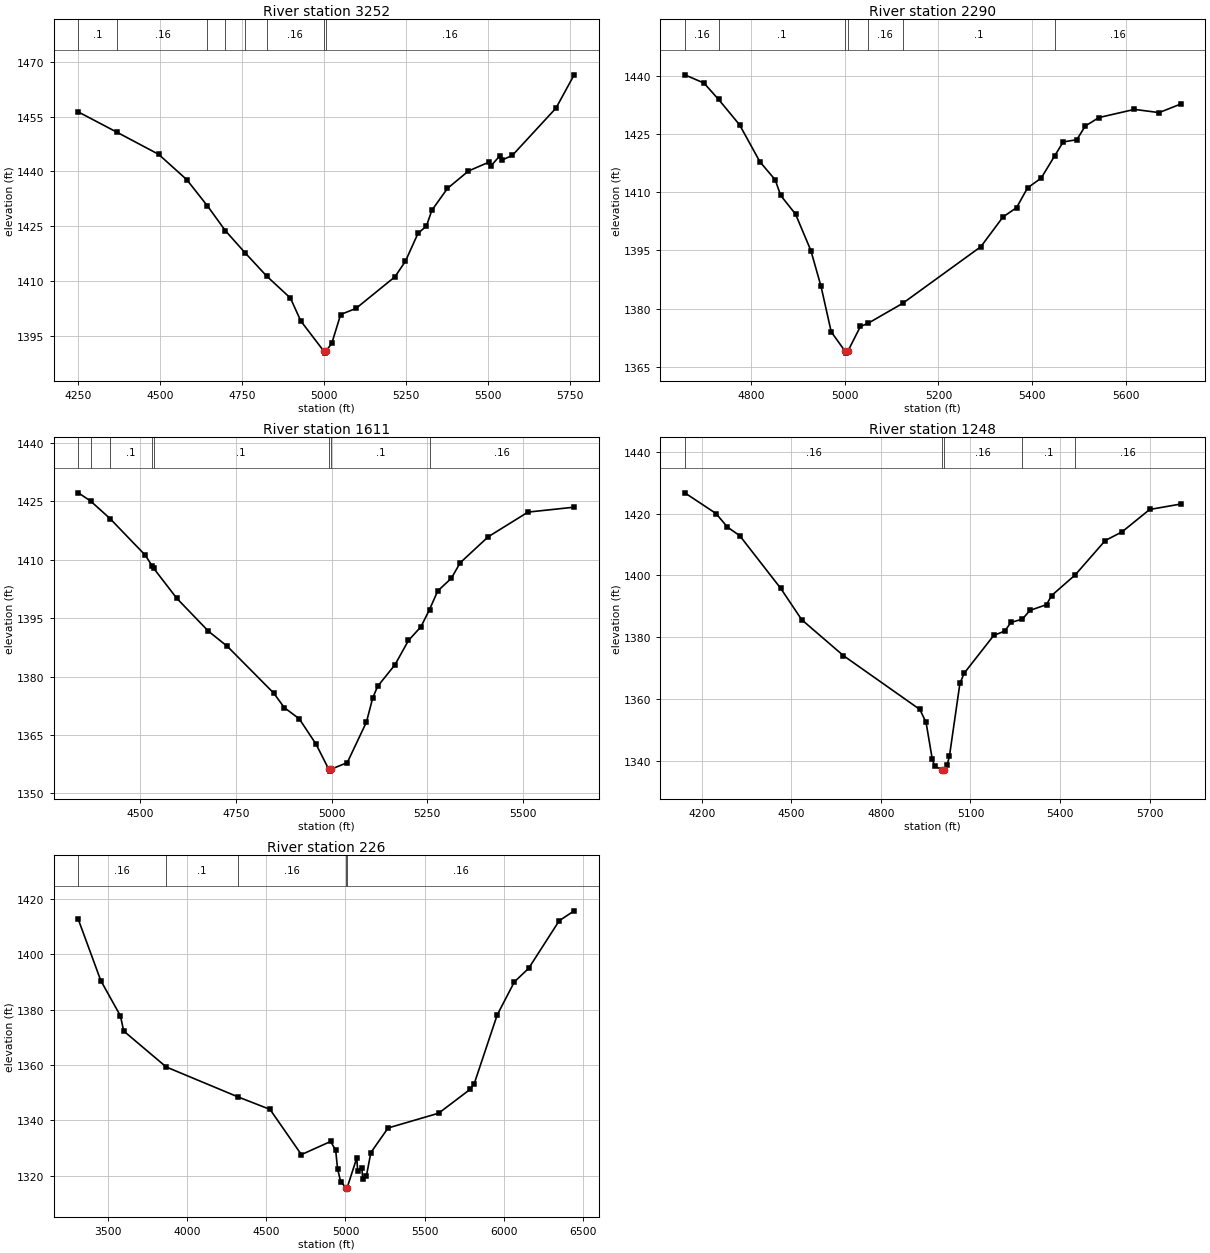
Type RM Length L Ch R = 1,3252,962,962,962
BEGIN DESCRIPTION:
UNT099 IN NNOGR 6.0
END DESCRIPTION:
XS GIS Cut Line= 3
      2857706.63     10100657.05      2857342.07     10100153.60
      2856495.72     10099880.17
#Sta/Elev= 30
  4250.4 1456.32  4369.3 1450.70  4494.9 1444.71  4580.7 1437.76  4643.9 1430.55
  4698.7 1423.73  4759.0 1417.65  4824.0 1411.34  4896.8 1405.27  4928.3 1399.00
  4998.9 1390.68  5001.6 1390.18  5004.9 1390.68  5023.0 1392.93  5049.8 1400.77
  5096.5 1402.44  5215.2 1411.11  5247.2 1415.37  5285.6 1423.05  5311.3 1425.03
  5327.6 1429.33  5375.3 1435.35  5439.4 1440.13  5503.4 1442.62  5508.7 1441.61
  5535.5 1444.35  5540.7 1443.10  5572.8 1444.38  5706.1 1457.38  5761.4 1466.50
#Mann=8,-1,0
  4250.4     0.1       0  4369.3    0.16       0  4643.9     0.1       0
  4698.7    0.16       0  4759.0     0.1       0  4824.0    0.16       0
  4998.9    0.07       0  5004.9    0.16       0
Bank Sta=4998.9,5004.9
Exp/Cntr=0.3,0.1

Type RM Length L Ch R = 1,2290,679,679,679
BEGIN DESCRIPTION:
UNT099 IN NNOGR 5.0
END DESCRIPTION:
XS GIS Cut Line= 2
      2858166.04     10099557.54      2857192.21     10099140.18
#Sta/Elev= 30
  4657.9 1440.29  4698.8 1438.17  4730.0 1433.96  4774.9 1427.41  4818.5 1417.85
  4851.1 1413.22  4862.7 1409.21  4894.6 1404.36  4927.3 1394.98  4949.0 1385.74
  4970.8 1374.02  5000.4 1369.04  5003.2 1368.54  5006.4 1369.04  5033.1 1375.41
  5048.8 1376.18  5123.4 1381.37  5290.6 1395.99  5337.8 1403.64  5366.8 1406.04
  5390.3 1411.14  5419.4 1413.66  5448.4 1419.43  5466.5 1422.99  5495.5 1423.56
  5513.6 1427.08  5542.7 1429.27  5618.8 1431.38  5671.4 1430.55  5717.4 1432.75
#Mann=7,-1,0
  4657.9    0.16       0  4730.0     0.1       0  5000.4    0.07       0
  5006.4     0.1       0  5048.8    0.16       0  5123.4     0.1       0
  5448.4    0.16       0
Bank Sta=5000.4,5006.4
Exp/Cntr=0.3,0.1

Type RM Length L Ch R = 1,1611,363,363,363
BEGIN DESCRIPTION:
Mapping XS 66d39a99
END DESCRIPTION:
XS GIS Cut Line= 3
      2858433.66     10099326.09      2858181.91     10098848.63
      2857515.68     10098492.73
#Sta/Elev= 30
  4338.5 1427.22  4370.4 1425.12  4421.1 1420.62  4513.4 1411.19  4532.0 1408.33
  4535.3 1407.83  4595.9 1400.09  4678.3 1391.67  4728.0 1387.75  4848.9 1375.76
  4876.5 1372.03  4915.5 1369.17  4959.4 1362.65  4992.5 1356.22  4995.3 1355.72
  4998.5 1356.22  5040.9 1357.89  5091.1 1368.34  5107.4 1374.51  5120.3 1377.51
  5165.6 1383.05  5200.8 1389.29  5233.4 1392.81  5255.8 1397.23  5277.3 1402.02
  5313.0 1405.28  5335.7 1409.23  5409.0 1415.92  5513.1 1422.27  5633.6 1423.53
#Mann=8,-1,0
  4338.5     0.1       0  4370.4    0.16       0  4421.1     0.1       0
  4532.0    0.16       0  4535.3     0.1       0  4992.5    0.07       0
  4998.5     0.1       0  5255.8    0.16       0
Bank Sta=4992.5,4998.5
Exp/Cntr=0.3,0.1

Type RM Length L Ch R = 1,1248,1022,1022,1022
BEGIN DESCRIPTION:
UNT099 IN NNOGR 4.0
END DESCRIPTION:
XS GIS Cut Line= 4
      2858625.78     10099278.97      2858402.88     10098596.33
      2858026.75     10098289.85      2857594.92     10098443.08
#Sta/Elev= 30
  4142.7 1426.70  4247.5 1419.99  4285.0 1415.66  4327.0 1412.80  4463.8 1395.81
  4534.5 1385.61  4674.2 1373.99  4930.4 1356.55  4951.2 1352.35  4972.0 1340.47
  4979.9 1338.14  5005.4 1337.09  5008.1 1336.59  5011.4 1337.09  5021.5 1338.50
  5029.4 1341.37  5064.6 1365.00  5079.0 1368.31  5178.1 1380.54  5214.7 1381.93
  5235.5 1384.72  5274.0 1385.82  5299.4 1388.64  5354.8 1390.49  5371.6 1393.42
  5451.0 1400.13  5551.5 1411.24  5608.0 1414.07  5700.6 1421.31  5804.2 1423.06
#Mann=5,-1,0
  4142.7    0.16       0  5005.4    0.07       0  5011.4    0.16       0
  5274.0     0.1       0  5451.0    0.16       0
Bank Sta=5005.4,5011.4
Exp/Cntr=0.3,0.1

Type RM Length L Ch R = 1,226,0,0,0
BEGIN DESCRIPTION:
UNT099 IN NNOGR 1.0
END DESCRIPTION:
XS GIS Cut Line= 4
      2858862.58     10099251.10      2859224.79     10097885.86
      2858834.73     10097760.49      2857608.83     10098234.13
#Sta/Elev= 30
  3310.1 1412.54  3452.2 1390.45  3576.4 1377.72  3597.1 1372.25  3866.2 1359.26
  4318.8 1348.49  4522.7 1343.94  4721.1 1327.61  4905.9 1332.36  4938.0 1329.20
  4949.8 1322.49  4970.1 1317.75  5004.4 1315.65  5007.2 1315.15  5010.4 1315.65
  5071.6 1326.44  5076.9 1321.78  5103.7 1322.92  5109.0 1318.68  5132.3 1319.88
  5160.5 1328.35  5269.6 1337.24  5589.3 1342.57  5790.5 1351.27  5814.4 1353.24
  5959.5 1378.03  6068.6 1390.02  6158.4 1394.87  6352.0 1412.08  6446.5 1415.66
#Mann=5,-1,0
  3310.1    0.16       0  3866.2     0.1       0  4318.8    0.16       0
  5004.4    0.07       0  5010.4    0.16       0
Bank Sta=5004.4,5010.4
Exp/Cntr=0.3,0.1

Chan Stop Cuts=-1