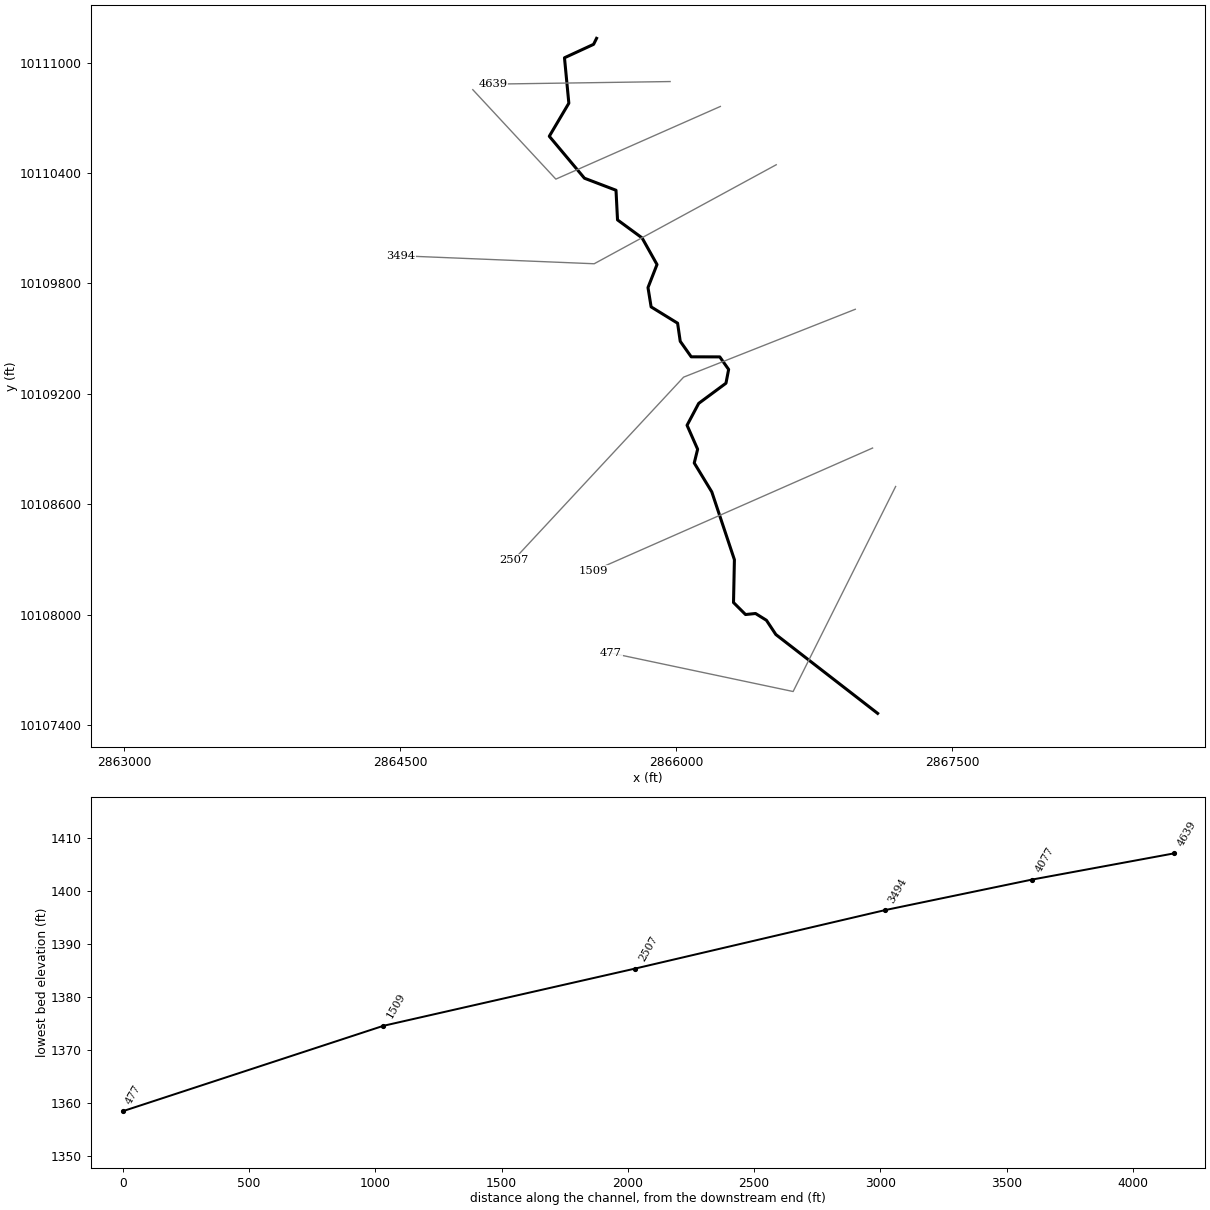
--- UNT101 IN NNOGR.prj (project) ---

Proj Title=UNT101 IN NNOGR Base Level Engineering
Current Plan=p01
Default Exp/Contr=0.3,0.1
English Units
Geom File=g01
Flow File=f01
Plan File=p01
Y Axis Title=Elevation
X Axis Title(PF)=Main Channel Distance
X Axis Title(XS)=Station
BEGIN DESCRIPTION:
UNT101 IN NNOGR
END DESCRIPTION:
DSS Export Rating Curves= 0
DSS Export Rating Curve Sorted= 0
DSS Export Volume Flow Curves= 0
DXF OffsetX= 0
DXF OffsetY= 0
DXF ScaleX= 1
DXF ScaleY= 10

--- UNT101 IN NNOGR.p01 (plan) ---

Plan Title=Multiple Run
Short Identifier=Multiple
Geom File=g01
Flow File=f01
Subcritical Flow
K Sum by GR= 0
Std Step Tol= 0.01
Critical Tol= 0.01
Num of Std Step Trials= 20
Max Error Tol= 0.3
Flow Tol Ratio= 0.001
Split Flow NTrial= 30
Split Flow Tol= 0.02
Split Flow Ratio= 0.02
Log Output Level= 0
Friction Slope Method= 1
Unsteady Friction Slope Method= 2
Unsteady Bridges Friction Slope Method= 1
Parabolic Critical Depth
Global Vel Dist=  1 , 1 , 1
Global Log Level= 0
CheckData=True
Encroach Param= -1, 0, 0, 0
BEGIN DESCRIPTION:
Multiple Run
END DESCRIPTION:

--- UNT101 IN NNOGR.f01 (steady flow) ---

Flow Title=Multiple
Program Version=4.10
Number of Profiles= 7
Profile Names=10-year,25-year,50-year,1pct_min,100-year,1pct_plu,500-year
River Rch & RM=UNT101 IN NNOGR,Reach-1         ,4639
    1214    1806    2334    2206    2984    4035    4899
Boundary for River Rch & Prof#=UNT101 IN NNOGR,Reach-1         , 1
Up Type= 0
Dn Type= 3
Dn Slope=0.014
Boundary for River Rch & Prof#=UNT101 IN NNOGR,Reach-1         , 2
Up Type= 0
Dn Type= 3
Dn Slope=0.014
Boundary for River Rch & Prof#=UNT101 IN NNOGR,Reach-1         , 3
Up Type= 0
Dn Type= 3
Dn Slope=0.014
Boundary for River Rch & Prof#=UNT101 IN NNOGR,Reach-1         , 4
Up Type= 0
Dn Type= 3
Dn Slope=0.014
Boundary for River Rch & Prof#=UNT101 IN NNOGR,Reach-1         , 5
Up Type= 0
Dn Type= 3
Dn Slope=0.014
Boundary for River Rch & Prof#=UNT101 IN NNOGR,Reach-1         , 6
Up Type= 0
Dn Type= 3
Dn Slope=0.014
Boundary for River Rch & Prof#=UNT101 IN NNOGR,Reach-1         , 7
Up Type= 0
Dn Type= 3
Dn Slope=0.014
DSS Import GetInterval= 0
DSS Import GetPeak= 0
DSS Import FillOption= 0

--- UNT101 IN NNOGR.g01 (geometry) ---

Geom Title=Existing Conditions
Program Version=4.10

River Reach=UNT101 IN NNOGR ,Reach-1
Reach XY= 30
      2865567.53       10111132.      2865551.38     10111099.36
      2865393.14     10111026.37      2865416.83     10110779.41
      2865310.57     10110599.69      2865501.75     10110371.62
       2865673.2     10110306.23      2865681.47     10110145.08
      2865814.95     10110047.14      2865896.07     10109902.49
      2865847.06     10109777.16      2865864.09     10109672.26
      2866007.96      10109583.6      2866022.27     10109485.29
        2866082.     10109400.87      2866237.22     10109400.48
      2866285.36     10109332.26      2866270.91     10109257.41
      2866122.66     10109147.73      2866059.37     10109028.75
      2866116.88     10108898.48      2866098.47     10108823.73
      2866193.88     10108666.55      2866316.78     10108298.03
       2866311.9     10108065.32       2866377.2     10108000.09
      2866431.62     10108005.66      2866490.91     10107968.76
      2866542.07     10107891.37      2867095.33     10107462.79

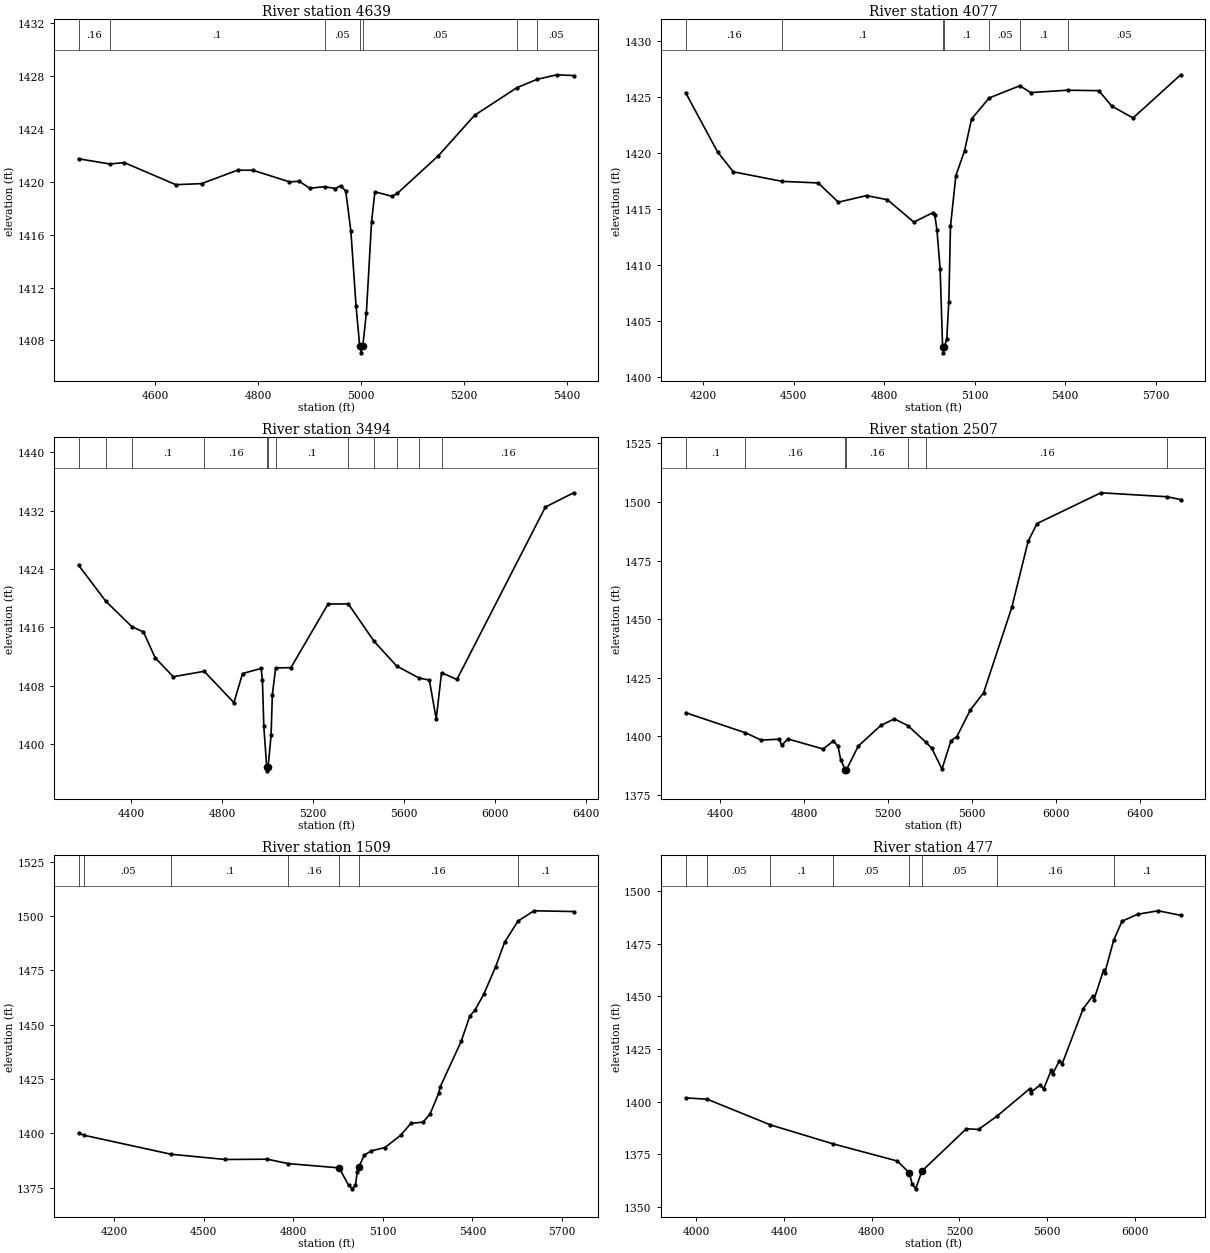
Type RM Length L Ch R = 1 ,4639    ,562,562,562
BEGIN DESCRIPTION:
UNT101 IN NNOGR 10.0
END DESCRIPTION:
XS GIS Cut Line= 2
      2865967.26     10110897.09      2865005.96     10110883.16
#Sta/Elev= 30
  4451.4 1421.75  4511.9 1421.36  4540.2 1421.46  4640.2 1419.79  4690.2 1419.87
  4760.2 1420.89  4790.2 1420.88  4860.2 1420.01  4880.2 1420.04  4900.2 1419.52
    4929 1419.64  4950.2  1419.5  4960.2 1419.71  4970.2 1419.31  4980.2 1416.25
  4990.2  1410.6  4997.3 1407.56    5000 1407.06  5003.3 1407.56  5010.3  1410.1
  5020.3 1416.97  5026.8 1419.25  5060.3 1418.91  5070.3 1419.13  5150.3 1421.99
  5220.3 1425.04  5302.5 1427.13    5342 1427.77  5380.3 1428.11  5412.8 1428.05
#Mann= 7 ,-1 , 0
  4451.4     .16       0  4511.9      .1       0    4929     .05       0
  4997.3    .035       0  5003.3     .05       0  5302.5      .1       0
    5342     .05       0
Bank Sta=4997.3,5003.3
XS Rating Curve= 0 ,0
Exp/Cntr=0.3,0.1

Type RM Length L Ch R = 1 ,4077    ,583,583,583
BEGIN DESCRIPTION:
UNT101 IN NNOGR 9.0
END DESCRIPTION:
XS GIS Cut Line= 3
      2866240.34     10110761.75      2865346.22     10110366.77
      2864894.86     10110852.85
#Sta/Elev= 30
  4141.9 1425.38  4248.1 1420.07  4300.2  1418.3  4462.1 1417.45  4581.2 1417.31
  4648.3 1415.59  4741.5 1416.18  4810.8 1415.81  4898.3 1413.81  4962.2 1414.66
  4967.7 1414.45  4974.8 1413.14  4985.5 1409.63  4993.7 1402.62  4996.4 1402.12
  4999.7 1402.62  5007.6  1403.4  5014.3 1406.71  5019.8 1413.42  5037.6 1417.96
  5066.4 1420.18  5089.7 1423.03  5148.2 1424.91  5249.7    1426  5285.4 1425.39
  5407.8  1425.6  5511.7 1425.56  5554.2 1424.18    5625 1423.12  5782.7 1426.98
#Mann= 7 ,-1 , 0
  4141.9     .16       0  4462.1      .1       0  4993.7     .07       0
  4999.7      .1       0  5148.2     .05       0  5249.7      .1       0
  5407.8     .05       0
Bank Sta=4993.7,4999.7
XS Rating Curve= 0 ,0
Exp/Cntr=0.3,0.1

Type RM Length L Ch R = 1 ,3494    ,987,987,987
BEGIN DESCRIPTION:
UNT101 IN NNOGR 6.0
END DESCRIPTION:
XS GIS Cut Line= 3
      2866544.15      10110444.9      2865554.55      10109906.7
      2864504.24      10109950.1
#Sta/Elev= 30
  4169.1 1424.51  4287.6 1419.62  4403.5 1416.09  4454.3 1415.38  4505.7 1411.84
  4585.4 1409.24  4721.6 1409.98  4852.3 1405.69  4890.3 1409.68    4972 1410.37
  4977.7 1408.78  4983.8 1402.43  4996.6 1396.85  4999.3 1396.35  5002.6 1396.85
  5015.7 1401.19  5021.4  1406.8  5035.9 1410.44  5103.1 1410.48  5266.5  1419.2
  5355.5 1419.21  5468.7  1414.1  5567.6 1410.72  5666.6 1409.06    5712 1408.78
  5742.1 1403.45  5765.6 1409.79  5833.2 1408.86  6222.5 1432.48  6346.8 1434.43
#Mann= 12 ,-1 , 0
  4169.1     .05       0  4287.6     .16       0  4403.5      .1       0
  4721.6     .16       0  4996.6     .07       0  5002.6     .16       0
  5035.9      .1       0  5355.5     .05       0  5468.7     .16       0
  5567.6      .1       0  5666.6     .05       0  5765.6     .16       0
Bank Sta=4996.6,5002.6
XS Rating Curve= 0 ,0
Exp/Cntr=0.3,0.1

Type RM Length L Ch R = 1 ,2507    ,998,998,998
BEGIN DESCRIPTION:
UNT101 IN NNOGR 5.0
END DESCRIPTION:
XS GIS Cut Line= 3
       2866973.8      10109659.3      2866040.67     10109290.38
      2865117.22     10108297.57
#Sta/Elev= 30
  4235.1 1410.15  4520.4 1401.57  4595.7 1398.45  4681.7 1398.85  4692.5 1396.22
  4722.8 1398.93  4890.4 1394.68  4939.1 1398.03  4961.3 1395.88  4974.2 1390.16
  4995.6 1385.85  4998.3 1385.35  5001.6 1385.85  5058.1 1395.93  5166.2 1404.76
  5230.1 1407.49  5294.8 1404.61    5380 1397.57  5407.6 1395.06    5457 1386.12
  5499.5 1398.12  5527.8 1399.96  5591.3 1411.18  5655.3 1418.64  5789.7 1455.06
  5867.4 1483.19  5909.9  1490.8  6214.3 1503.91    6531 1502.21  6594.4 1501.01
#Mann= 7 ,-1 , 0
  4235.1      .1       0  4520.4     .16       0  4995.6     .07       0
  5001.6     .16       0  5294.8      .1       0    5380     .16       0
    6531      .1       0
Bank Sta=4995.6,5001.6
XS Rating Curve= 0 ,0
Exp/Cntr=0.3,0.1

Type RM Length L Ch R = 1 ,1509    ,1032,1032,1032
BEGIN DESCRIPTION:
UNT101 IN NNOGR 3.0
END DESCRIPTION:
XS GIS Cut Line= 2
      2867067.71     10108904.99      2865549.31     10108236.34
#Sta/Elev= 30
  4080.3 1400.17  4098.9 1399.16  4389.6 1390.46    4572 1388.03    4712 1388.17
  4783.6 1386.13  4953.6 1384.18    4985 1376.21  4997.1 1374.54  5008.2 1376.13
  5013.8 1382.12  5019.3 1384.51  5037.1 1389.92  5060.5 1391.98  5106.6 1393.51
  5159.3 1399.11    5194 1404.67  5234.7  1405.2  5258.1 1408.92  5286.9 1418.42
  5292.3 1421.47  5362.3 1442.31  5391.1 1453.86    5409 1456.81  5437.8 1463.91
  5478.1 1476.71  5507.8 1487.86  5552.5 1497.59  5606.6 1502.37  5739.4 1502.02
#Mann= 7 ,-1 , 0
  4080.3      .1       0  4098.9     .05       0  4389.6      .1       0
  4783.6     .16       0  4953.6     .07       0  5019.3     .16       0
  5552.5      .1       0
Bank Sta=4953.6,5019.3
XS Rating Curve= 0 ,0
Exp/Cntr=0.3,0.1

Type RM Length L Ch R = 1 ,477     ,0,0,0
BEGIN DESCRIPTION:
UNT101 IN NNOGR 1.0
END DESCRIPTION:
XS GIS Cut Line= 3
      2867193.14     10108696.09      2866635.89      10107581.6
      2865646.77     10107790.57
#Sta/Elev= 30
  3951.4 1401.74  4049.9  1401.1  4338.4 1388.87  4621.9  1379.9  4916.7 1371.67
  4971.5 1365.99  4983.7  1360.9  5000.3 1358.43  5028.5 1366.86  5231.3 1387.03
  5286.8 1386.71  5369.9 1392.95  5519.5 1406.03  5524.6 1404.26  5569.2 1408.02
  5583.2 1405.91    5619 1415.09  5624.1    1413  5654.7 1419.26  5668.7 1418.09
  5763.1 1443.99  5807.7 1450.33  5812.8 1448.42  5857.5 1462.74  5862.6 1461.25
  5902.9 1476.76  5940.9 1485.82  6012.5 1489.17  6106.2 1490.81  6208.4 1488.64
#Mann= 8 ,-1 , 0
  3951.4      .1       0  4049.9     .05       0  4338.4      .1       0
  4621.9     .05       0  4971.5     .03       0  5028.5     .05       0
  5369.9     .16       0  5902.9      .1       0
Bank Sta=4971.5,5028.5
XS Rating Curve= 0 ,0
Exp/Cntr=0.3,0.1

Chan Stop Cuts=-1
Use User Specified Reach Order=0
Composite Channel Slope=5