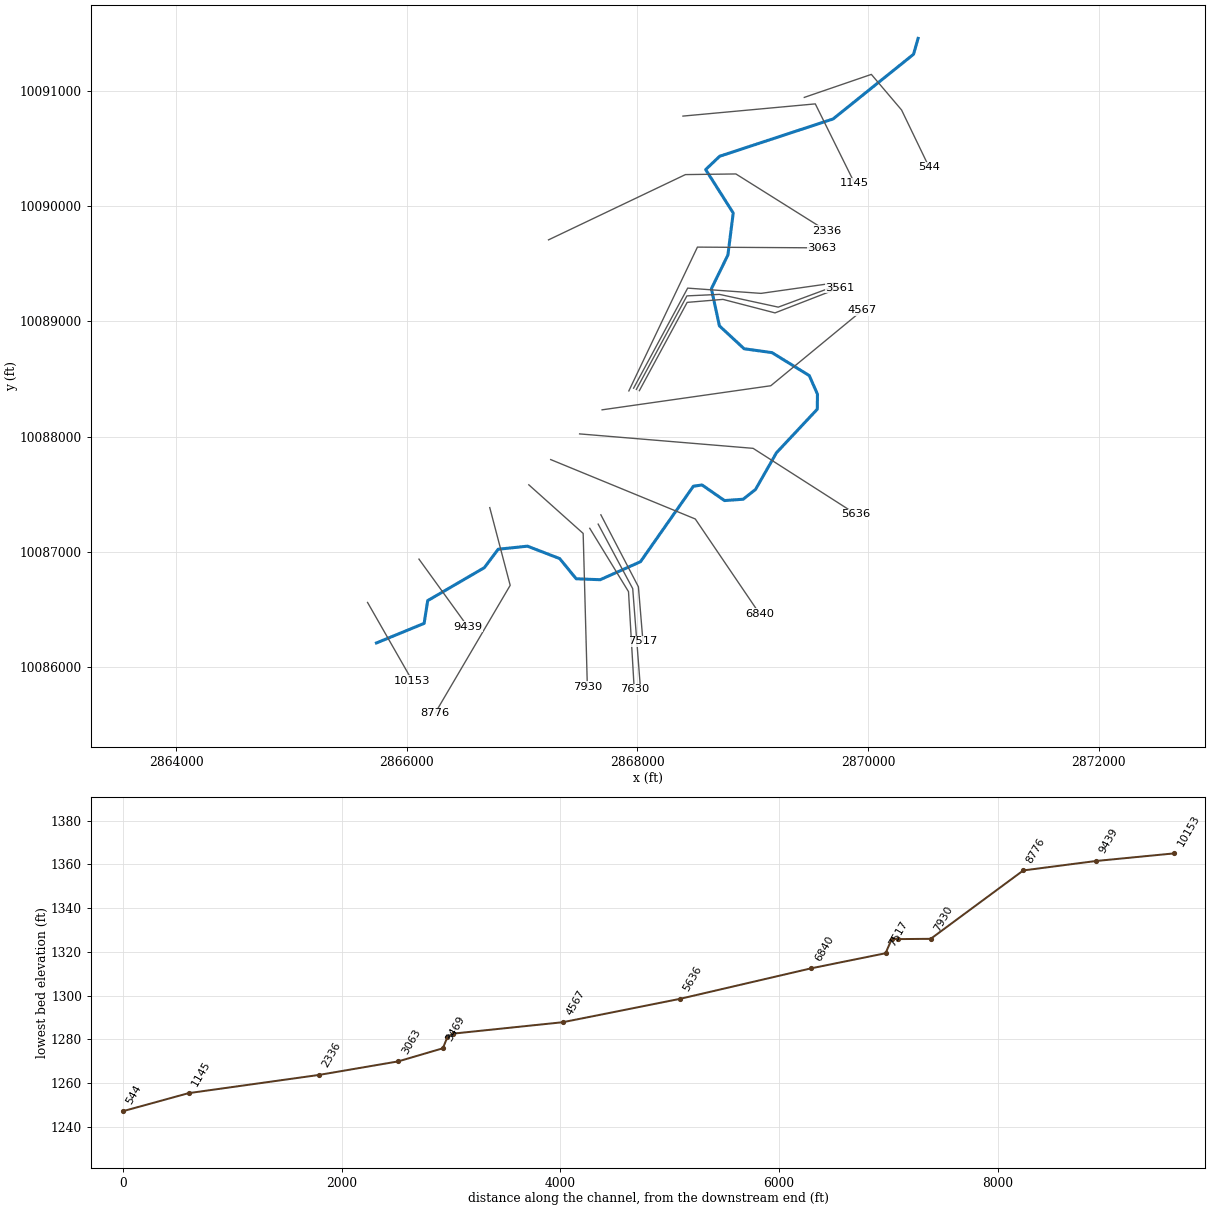
--- UNT104 IN NNOGR.prj (project) ---

Proj Title=UNT104 IN NNOGR Base Level Engineering
Current Plan=p01
Default Exp/Contr=0.3,0.1
English Units
Geom File=g01
Flow File=f01
Plan File=p01
Y Axis Title=Elevation
X Axis Title(PF)=Main Channel Distance
X Axis Title(XS)=Station
BEGIN DESCRIPTION:
UNT104 IN NNOGR
END DESCRIPTION:
DSS Export Rating Curves= 0
DSS Export Rating Curve Sorted= 0
DSS Export Volume Flow Curves= 0
DXF OffsetX= 0
DXF OffsetY= 0
DXF ScaleX= 1
DXF ScaleY= 10

--- UNT104 IN NNOGR.p01 (plan) ---

Plan Title=Multiple Run
Short Identifier=Multiple
Geom File=g01
Flow File=f01
Subcritical Flow
K Sum by GR= 0
Std Step Tol= 0.01
Critical Tol= 0.01
Num of Std Step Trials= 20
Max Error Tol= 0.3
Flow Tol Ratio= 0.001
Split Flow NTrial= 30
Split Flow Tol= 0.02
Split Flow Ratio= 0.02
Log Output Level= 0
Friction Slope Method= 1
Unsteady Friction Slope Method= 2
Unsteady Bridges Friction Slope Method= 1
Parabolic Critical Depth
Global Vel Dist=  1 , 1 , 1
Global Log Level= 0
CheckData=True
Encroach Param= -1, 0, 0, 0
BEGIN DESCRIPTION:
Multiple Run
END DESCRIPTION:

--- UNT104 IN NNOGR.f01 (steady flow) ---

Flow Title=Multiple
Program Version=4.10
Number of Profiles= 7
Profile Names=10-year,25-year,50-year,1pct_min,100-year,1pct_plu,500-year
River Rch & RM=UNT104 IN NNOGR,Reach-1         ,10153
     826    1197    1518    1412    1909    2582    3027
River Rch & RM=UNT104 IN NNOGR,Reach-1         ,7930
    1227    1818    2340    2204    2981    4031    4856
River Rch & RM=UNT104 IN NNOGR,Reach-1         ,4567
    1429    2127    2747    2593    3507    4743    5743
Boundary for River Rch & Prof#=UNT104 IN NNOGR,Reach-1         , 1
Up Type= 0
Dn Type= 3
Dn Slope=0.0087
Boundary for River Rch & Prof#=UNT104 IN NNOGR,Reach-1         , 2
Up Type= 0
Dn Type= 3
Dn Slope=0.0087
Boundary for River Rch & Prof#=UNT104 IN NNOGR,Reach-1         , 3
Up Type= 0
Dn Type= 3
Dn Slope=0.0087
Boundary for River Rch & Prof#=UNT104 IN NNOGR,Reach-1         , 4
Up Type= 0
Dn Type= 3
Dn Slope=0.0087
Boundary for River Rch & Prof#=UNT104 IN NNOGR,Reach-1         , 5
Up Type= 0
Dn Type= 3
Dn Slope=0.0087
Boundary for River Rch & Prof#=UNT104 IN NNOGR,Reach-1         , 6
Up Type= 0
Dn Type= 3
Dn Slope=0.0087
Boundary for River Rch & Prof#=UNT104 IN NNOGR,Reach-1         , 7
Up Type= 0
Dn Type= 3
Dn Slope=0.0087
DSS Import GetInterval= 0
DSS Import GetPeak= 0
DSS Import FillOption= 0

--- UNT104 IN NNOGR.g01 (geometry) ---

Geom Title=Existing Conditions
Program Version=4.10

River Reach=UNT104 IN NNOGR ,Reach-1
Reach XY= 30
      2865737.93     10086208.72      2866151.28      10086378.7
      2866182.25     10086576.07       2866673.3     10086861.96
      2866793.21     10087021.94      2867047.43     10087048.64
       2867326.8     10086940.98      2867470.11     10086765.58
       2867678.2     10086757.54      2868027.62     10086913.88
      2868485.93      10087568.8      2868561.46     10087579.74
      2868756.17     10087444.38      2868917.51     10087455.99
      2869024.74     10087540.44      2869206.69     10087859.42
      2869560.62     10088237.37        2869562.     10088367.63
      2869491.32     10088528.82      2869167.37     10088728.44
      2868926.34     10088761.74      2868711.81     10088960.38
      2868642.24      10089282.9      2868785.42     10089574.95
       2868831.6      10089939.9       2868592.6     10090316.71
      2868714.06     10090432.29      2869697.63     10090756.09
      2870395.08     10091317.26      2870434.68     10091455.65

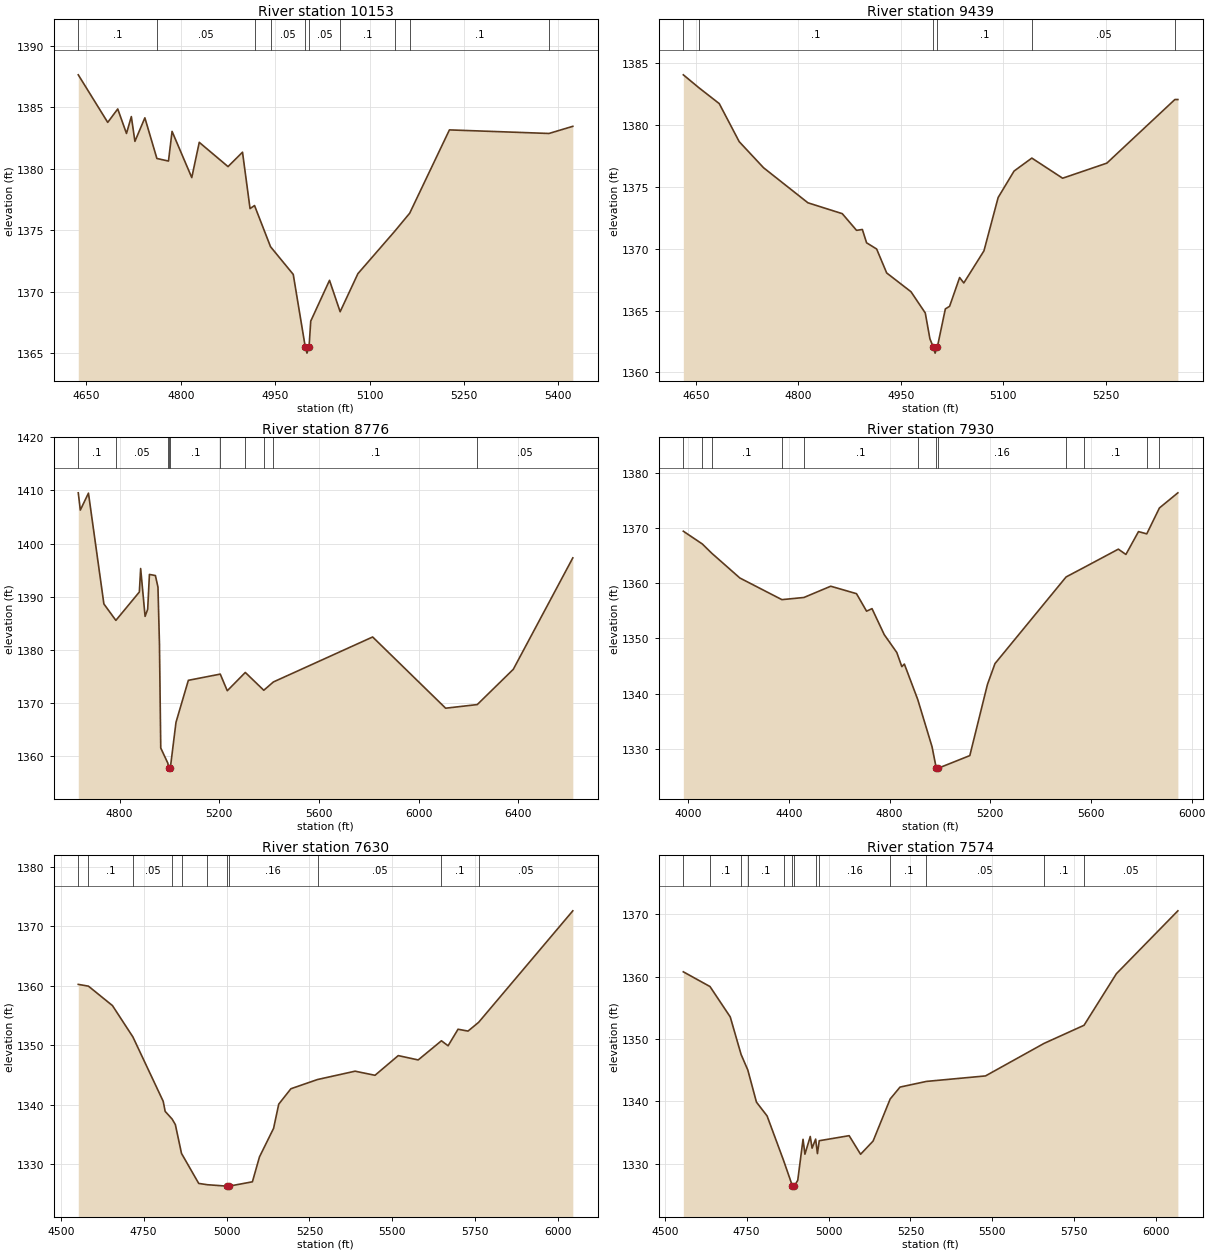
Type RM Length L Ch R = 1 ,10153   ,714,714,714
BEGIN DESCRIPTION:
UNT104 IN NNOGR 19.0
END DESCRIPTION:
XS GIS Cut Line= 2
      2865660.74     10086560.26      2866050.51     10085878.17
#Sta/Elev= 30
  4637.3 1387.62  4684.1 1383.76    4700 1384.85  4713.9 1382.86  4721.6 1384.23
  4727.3 1382.22  4743.1 1384.13  4762.2 1380.83  4780.6 1380.62  4786.3 1383.03
  4817.6 1379.28  4829.5 1382.14  4875.2 1380.17  4898.2 1381.34  4910.2 1376.76
  4917.3 1377.01  4942.7 1373.67  4978.8 1371.42  4997.9 1365.53  5000.6 1365.03
  5003.9 1365.53  5006.6 1367.63  5036.4 1370.94  5053.3 1368.39  5081.5 1371.48
  5139.8 1374.91  5163.8 1376.39  5226.9 1383.15    5385 1382.86  5422.9 1383.44
#Mann= 10 ,-1 , 0
  4637.3      .1       0  4762.2     .05       0  4917.3      .1       0
  4942.7     .05       0  4997.9    .035       0  5003.9     .05       0
  5053.3      .1       0  5139.8     .05       0  5163.8      .1       0
    5385     .05       0
Bank Sta=4997.9,5003.9
XS Rating Curve= 0 ,0
Exp/Cntr=0.3,0.1

Type RM Length L Ch R = 1 ,9439    ,663,663,663
BEGIN DESCRIPTION:
UNT104 IN NNOGR 18.0
END DESCRIPTION:
XS GIS Cut Line= 2
      2866106.51      10086936.4      2866530.33     10086349.42
#Sta/Elev= 30
  4631.6 1384.08  4654.5 1383.03  4684.2 1381.75  4713.4 1378.67    4749 1376.56
    4814 1373.72  4864.3 1372.84  4885.2 1371.49  4893.7 1371.56  4899.9 1370.48
  4914.6 1369.98  4929.3 1368.04  4964.9 1366.52  4985.8  1364.8  4992.6 1362.71
  4997.5 1362.05  5000.2 1361.55  5003.5 1362.05  5015.2 1365.13  5021.4 1365.34
  5036.1 1367.67  5042.2 1367.23  5071.7 1369.83  5092.5 1374.15  5115.8 1376.29
  5141.8 1377.34  5186.9 1375.71  5251.6 1376.93  5351.2 1382.08  5355.6 1382.08
#Mann= 6 ,-1 , 0
  4631.6     .05       0  4654.5      .1       0  4997.5     .07       0
  5003.5      .1       0  5141.8     .05       0  5351.2      .1       0
Bank Sta=4997.5,5003.5
XS Rating Curve= 0 ,0
Exp/Cntr=0.3,0.1

Type RM Length L Ch R = 1 ,8776    ,846,846,846
BEGIN DESCRIPTION:
UNT104 IN NNOGR 15.0
END DESCRIPTION:
XS GIS Cut Line= 3
      2866720.45     10087383.26      2866897.54     10086708.76
      2866245.39     10085597.67
#Sta/Elev= 30
  4633.7 1409.56    4642 1406.32  4674.6  1409.5  4736.6 1388.67  4784.7 1385.58
    4879 1390.92  4884.2 1395.33    4902 1386.34  4912.4 1387.66  4919.4 1394.22
  4943.4 1394.01  4953.7 1391.83  4959.7 1381.13  4964.9 1361.59  4993.3 1358.74
  4997.1 1357.74  4999.9 1357.24  5003.1 1357.74  5026.1 1366.42  5075.7 1374.31
  5203.8 1375.48    5232 1372.35  5304.4 1375.79  5378.6 1372.44    5417    1374
  5815.7 1382.46  6108.8 1369.07  6235.7 1369.75  6380.4 1376.38  6619.4 1397.33
#Mann= 10 ,-1 , 0
  4633.7      .1       0  4784.7     .05       0  4993.3      .1       0
  4997.1     .07       0  5003.1      .1       0  5203.8     .05       0
  5304.4      .1       0  5378.6     .05       0    5417      .1       0
  6235.7     .05       0
Bank Sta=4997.1,5003.1
XS Rating Curve= 0 ,0
Exp/Cntr=0.3,0.1

Type RM Length L Ch R = 1 ,7930    ,300,300,300
BEGIN DESCRIPTION:
Mapping XS cbeb6a46
END DESCRIPTION:
XS GIS Cut Line= 3
      2867059.02     10087581.14      2867530.36     10087159.28
      2867566.78     10085827.34
#Sta/Elev= 30
  3980.3 1369.41  4055.7  1367.1  4092.9 1365.44  4204.9 1360.94  4371.9 1357.02
  4459.4 1357.41    4566 1359.45  4668.4  1358.1  4708.4 1354.93    4730 1355.39
  4778.5 1350.69  4828.5 1347.45  4848.5 1344.89  4858.5 1345.36  4911.7 1338.94
  4968.5 1330.39  4985.5 1326.47  4988.3 1325.97  4991.5 1326.47  5118.6 1328.78
  5188.6 1341.66  5218.6 1345.44  5501.2 1361.13  5571.8 1362.83  5708.8 1366.16
  5738.8  1365.2  5788.8 1369.34  5821.7 1368.93    5872 1373.62  5945.3 1376.36
#Mann= 12 ,-1 , 0
  3980.3      .1       0  4055.7     .05       0  4092.9      .1       0
  4371.9     .05       0  4459.4      .1       0  4911.7     .16       0
  4985.5     .07       0  4991.5     .16       0  5501.2     .05       0
  5571.8      .1       0  5821.7     .05       0    5872      .1       0
Bank Sta=4985.5,4991.5
XS Rating Curve= 0 ,0
Exp/Cntr=0.3,0.1

Type RM Length L Ch R = 1 ,7630    ,56,56,56
BEGIN DESCRIPTION:
UNT104 IN NNOGR 12.0
END DESCRIPTION:
XS GIS Cut Line= 3
      2867587.64     10087203.57      2867923.58     10086654.07
      2867973.03     10085808.27
#Sta/Elev= 30
  4552.8 1360.25  4583.5 1359.95    4656 1356.68  4717.5 1351.42  4808.9  1340.6
  4814.8 1338.91  4835.9 1337.61  4845.6 1336.68  4864.1 1331.84    4916  1326.8
  4942.2 1326.58  5001.4 1326.34  5004.1 1325.84  5007.4 1326.34  5077.9 1327.07
  5099.2 1331.25  5141.8 1336.06  5157.3 1340.12    5194 1342.71  5274.3 1344.26
  5387.5 1345.66  5447.6 1344.97  5517.7 1348.28  5577.8 1347.55  5647.9 1350.77
    5668 1349.93    5698 1352.71  5728.1  1352.4  5760.1 1353.87  6044.1 1372.61
#Mann= 11 ,-1 , 0
  4552.8     .05       0  4583.5      .1       0  4717.5     .05       0
  4835.9      .1       0  4864.1     .05       0  4942.2     .16       0
  5001.4     .07       0  5007.4     .16       0  5274.3     .05       0
  5647.9      .1       0  5760.1     .05       0
Bank Sta=5001.4,5007.4
XS Rating Curve= 0 ,0
Exp/Cntr=0.3,0.1

Type RM Length L Ch R = 1 ,7574    ,57,57,57
BEGIN DESCRIPTION:
Mapping XS 8bbc5861
END DESCRIPTION:
XS GIS Cut Line= 3
      2867660.58     10087239.98      2867960.04     10086680.12
      2868027.71     10085808.26
#Sta/Elev= 30
  4556.7 1360.75  4638.1 1358.39  4699.9 1353.52    4733  1347.5  4753.5 1345.01
  4779.9 1339.86  4812.4 1337.64  4862.5 1330.53  4889.7 1326.41  4892.4 1325.91
  4895.7 1326.41  4905.9 1327.32  4922.1  1333.9  4927.8 1331.51  4944.1 1334.35
  4949.7 1332.48  4960.5 1333.93    4966  1331.6  4971.5 1333.67  5062.8 1334.48
  5097.7  1331.5  5135.9 1333.62    5188 1340.36  5218.1 1342.27  5298.7 1343.18
  5478.9 1344.06  5657.9 1349.28  5779.7 1352.18  5878.5 1360.45  6066.1 1370.53
#Mann= 13 ,-1 , 0
  4556.7     .05       0  4638.1      .1       0    4733     .05       0
  4753.5      .1       0  4862.5     .05       0  4889.7     .07       0
  4895.7     .05       0  4960.5      .1       0  4971.5     .16       0
    5188      .1       0  5298.7     .05       0  5657.9      .1       0
  5779.7     .05       0
Bank Sta=4889.7,4895.7
XS Rating Curve= 0 ,0
Exp/Cntr=0.3,0.1

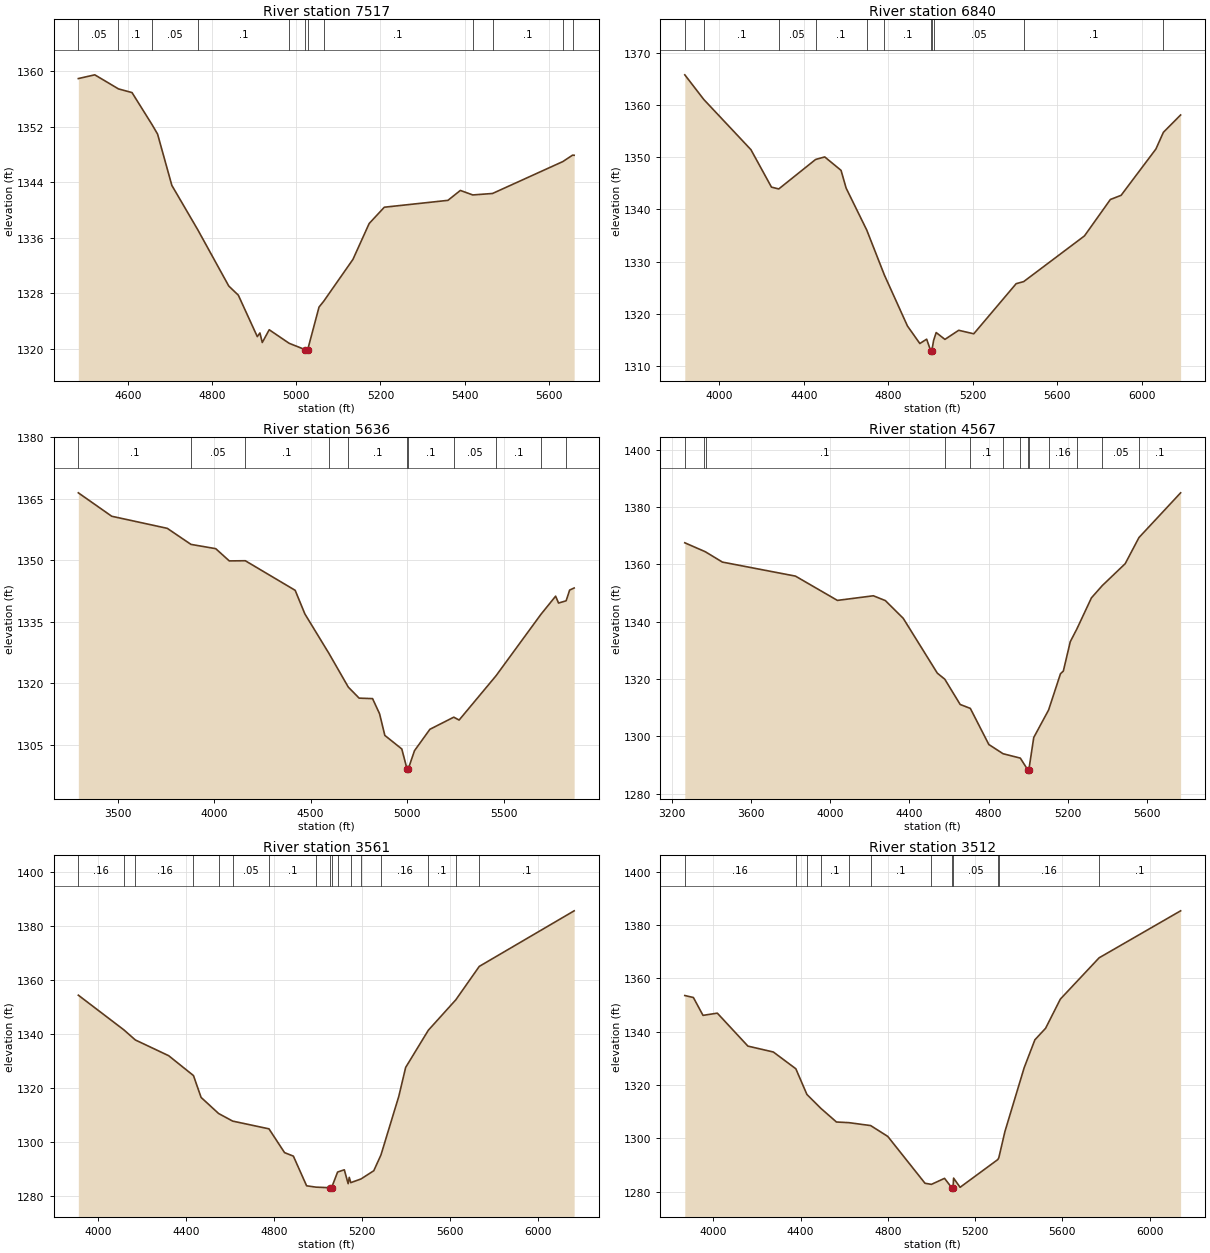
Type RM Length L Ch R = 1 ,7517    ,677,677,677
BEGIN DESCRIPTION:
Mapping XS 60698271
END DESCRIPTION:
XS GIS Cut Line= 3
        2867684.     10087320.74      2868009.52     10086695.74
      2868048.59     10086224.35
#Sta/Elev= 30
  4482.3 1358.96  4521.4  1359.5  4577.7 1357.47  4609.8 1356.94  4657.6  1352.3
  4670.5 1350.96  4704.4 1343.56    4766 1337.16  4839.7 1329.04  4862.3 1327.73
  4907.4 1321.75  4913.6 1322.28  4919.2  1320.9  4935.7 1322.74    4983 1320.79
  5021.1 1319.87  5023.8 1319.37  5027.1 1319.87    5054 1326.01    5065 1326.84
  5134.6 1332.89  5173.1 1338.06  5209.1 1340.41  5360.2  1341.4  5389.7 1342.83
  5419.2 1342.18  5466.1 1342.39  5633.1 1346.99  5656.3 1347.92    5660  1347.9
#Mann= 12 ,-1 , 0
  4482.3     .05       0  4577.7      .1       0  4657.6     .05       0
    4766      .1       0    4983     .16       0  5021.1     .07       0
  5027.1     .16       0    5065      .1       0  5419.2     .05       0
  5466.1      .1       0  5633.1     .05       0  5656.3      .1       0
Bank Sta=5021.1,5027.1
XS Rating Curve= 0 ,0
Exp/Cntr=0.3,0.1

Type RM Length L Ch R = 1 ,6840    ,1204,1204,1204
BEGIN DESCRIPTION:
UNT104 IN NNOGR 10.0
END DESCRIPTION:
XS GIS Cut Line= 3
       2867248.8     10087800.09       2868502.6     10087284.64
      2869059.82     10086462.74
#Sta/Elev= 30
  3836.1 1365.77  3926.1 1361.05  4149.3 1351.45  4246.6 1344.28  4281.2 1343.93
  4455.6 1349.57  4498.9 1350.06  4576.2 1347.49  4600.2  1344.1  4698.1 1336.05
  4781.5 1327.46  4890.8  1317.7  4949.5 1314.35  4981.8 1315.18  5000.4 1313.01
  5003.2 1312.51  5006.4 1313.01  5014.5 1314.91  5026.8 1316.45  5068.3 1315.14
  5133.5 1316.88  5204.9 1316.21  5405.7  1325.8  5441.4  1326.2  5729.2 1334.94
  5851.9 1341.91  5902.8 1342.71  6067.6 1351.57  6103.1 1354.77  6184.7 1358.09
#Mann= 11 ,-1 , 0
  3836.1     .05       0  3926.1      .1       0  4281.2     .05       0
  4455.6      .1       0  4698.1     .16       0  4781.5      .1       0
  5000.4     .07       0  5006.4      .1       0  5014.5     .05       0
  5441.4      .1       0  6103.1     .05       0
Bank Sta=5000.4,5006.4
XS Rating Curve= 0 ,0
Exp/Cntr=0.3,0.1

Type RM Length L Ch R = 1 ,5636    ,1069,1069,1069
BEGIN DESCRIPTION:
UNT104 IN NNOGR 8.0
END DESCRIPTION:
XS GIS Cut Line= 3
      2867499.55     10088022.97       2869004.1     10087897.59
      2869894.58     10087327.12
#Sta/Elev= 30
    3297 1366.44    3470 1360.72  3757.5 1357.77  3880.3 1353.85  4008.4 1352.81
  4078.6 1349.82  4161.6 1349.86  4419.8 1342.64    4470 1336.88  4595.5 1327.17
  4694.9 1319.01  4750.9 1316.32  4820.5  1316.2  4856.9 1312.49    4884 1307.22
  4971.9 1303.91    4999    1299  5001.7  1298.5    5005    1299  5037.6 1303.49
  5117.3 1308.71  5240.9 1311.67  5268.6 1310.97  5459.9 1321.79  5691.7 1336.74
  5768.3 1341.21  5783.5 1339.53  5822.7 1340.08    5841  1342.7  5864.3 1343.21
#Mann= 11 ,-1 , 0
    3297      .1       0  3880.3     .05       0  4161.6      .1       0
  4595.5     .05       0  4694.9      .1       0    4999     .07       0
    5005      .1       0  5240.9     .05       0  5459.9      .1       0
  5691.7     .05       0  5822.7      .1       0
Bank Sta=4999,5005
XS Rating Curve= 0 ,0
Exp/Cntr=0.3,0.1

Type RM Length L Ch R = 1 ,4567    ,1006,1006,1006
BEGIN DESCRIPTION:
UNT104 IN NNOGR 6.0
END DESCRIPTION:
XS GIS Cut Line= 3
      2867694.61     10088231.92      2869157.34     10088440.88
      2869951.43     10089095.65
#Sta/Elev= 30
  3264.3 1367.47  3363.9 1364.48  3369.3  1364.3  3454.5 1360.74  3823.8 1355.85
  4035.9 1347.38  4217.7 1348.99  4278.3 1347.31  4368.7 1341.13    4541 1322.01
  4578.8 1319.89  4656.6 1311.08  4707.9 1309.71  4801.5 1297.11  4873.4  1293.9
  4960.6 1292.37  4997.9 1288.33  5000.6 1287.83  5003.9 1288.33  5028.5 1299.56
  5103.6 1309.16  5163.7  1321.8  5178.1 1322.73  5213.2 1332.98  5246.5 1337.41
  5320.1 1348.26  5375.4 1352.57  5490.8 1360.18  5560.5  1369.3  5771.1  1384.9
#Mann= 13 ,-1 , 0
  3264.3      .1       0  3363.9     .16       0  3369.3      .1       0
  4578.8     .05       0  4707.9      .1       0  4873.4     .05       0
  4960.6      .1       0  4997.9     .07       0  5003.9      .1       0
  5103.6     .16       0  5246.5      .1       0  5375.4     .05       0
  5560.5      .1       0
Bank Sta=4997.9,5003.9
XS Rating Curve= 0 ,0
Exp/Cntr=0.3,0.1

Type RM Length L Ch R = 1 ,3561    ,49,49,49
BEGIN DESCRIPTION:
Mapping XS f8fae01a
END DESCRIPTION:
XS GIS Cut Line= 5
      2868017.73      10088398.2      2868432.23     10089164.26
      2868742.56      10089190.3      2869193.95     10089073.11
      2869758.19      10089292.3
#Sta/Elev= 30
  3909.5 1354.44  4116.6 1341.59  4168.8 1337.85  4320.1 1332.03  4432.9 1324.67
  4467.6 1316.57  4547.3 1310.61  4611.1  1307.8  4776.2 1304.93    4847 1296.12
  4887.1 1294.83  4947.3 1283.83  4989.5 1283.34  5054.7  1283.1  5057.5  1282.6
  5060.7  1283.1  5088.2 1288.93  5118.7 1289.76  5136.1 1284.62  5141.2 1286.96
  5148.1 1285.01  5194.2 1286.35  5252.6 1289.41  5285.2 1295.25  5366.6 1317.04
  5397.6 1327.68  5500.5 1341.44  5625.6 1352.73  5732.2  1365.1  6163.6 1385.69
#Mann= 17 ,-1 , 0
  3909.5     .16       0  4116.6      .1       0  4168.8     .16       0
  4432.9     .05       0  4547.3      .1       0  4611.1     .05       0
  4776.2      .1       0  4989.5     .16       0  5054.7     .07       0
  5060.7     .16       0  5088.2     .05       0  5148.1     .16       0
  5194.2      .1       0  5285.2     .16       0  5500.5      .1       0
  5625.6     .16       0  5732.2      .1       0
Bank Sta=5054.7,5060.7
XS Rating Curve= 0 ,0
Exp/Cntr=0.3,0.1

Type RM Length L Ch R = 1 ,3512    ,43,43,43
BEGIN DESCRIPTION:
UNT104 IN NNOGR 4.0
END DESCRIPTION:
XS GIS Cut Line= 5
      2867991.71     10088409.09      2868430.06     10089220.68
      2868712.18      10089233.7      2869222.16     10089123.03
      2869734.97     10089313.44
#Sta/Elev= 30
  3868.6 1353.56    3908 1352.81  3952.1 1346.12  4017.8 1346.95    4158  1334.6
  4274.7 1332.39  4377.8 1326.11  4428.5  1316.5  4492.2  1311.3  4564.1 1306.16
  4620.9 1305.92    4721 1304.82  4799.4 1300.76  4970.1 1283.21  4999.6  1282.8
  5059.7 1285.05    5093 1281.51  5095.8 1281.01    5099 1281.51  5101.2 1285.14
    5131 1281.69    5304 1292.09  5308.7 1292.81  5336.7 1302.62  5424.8 1326.49
    5474 1336.96  5523.1 1341.28  5590.8 1352.21  5768.5 1367.68  6142.3 1385.29
#Mann= 12 ,-1 , 0
  3868.6     .16       0  4377.8      .1       0  4428.5     .05       0
  4492.2      .1       0  4620.9     .05       0    4721      .1       0
  4999.6     .16       0    5093     .07       0    5099     .05       0
    5304      .1       0  5308.7     .16       0  5768.5      .1       0
Bank Sta=5093,5099
XS Rating Curve= 0 ,0
Exp/Cntr=0.3,0.1

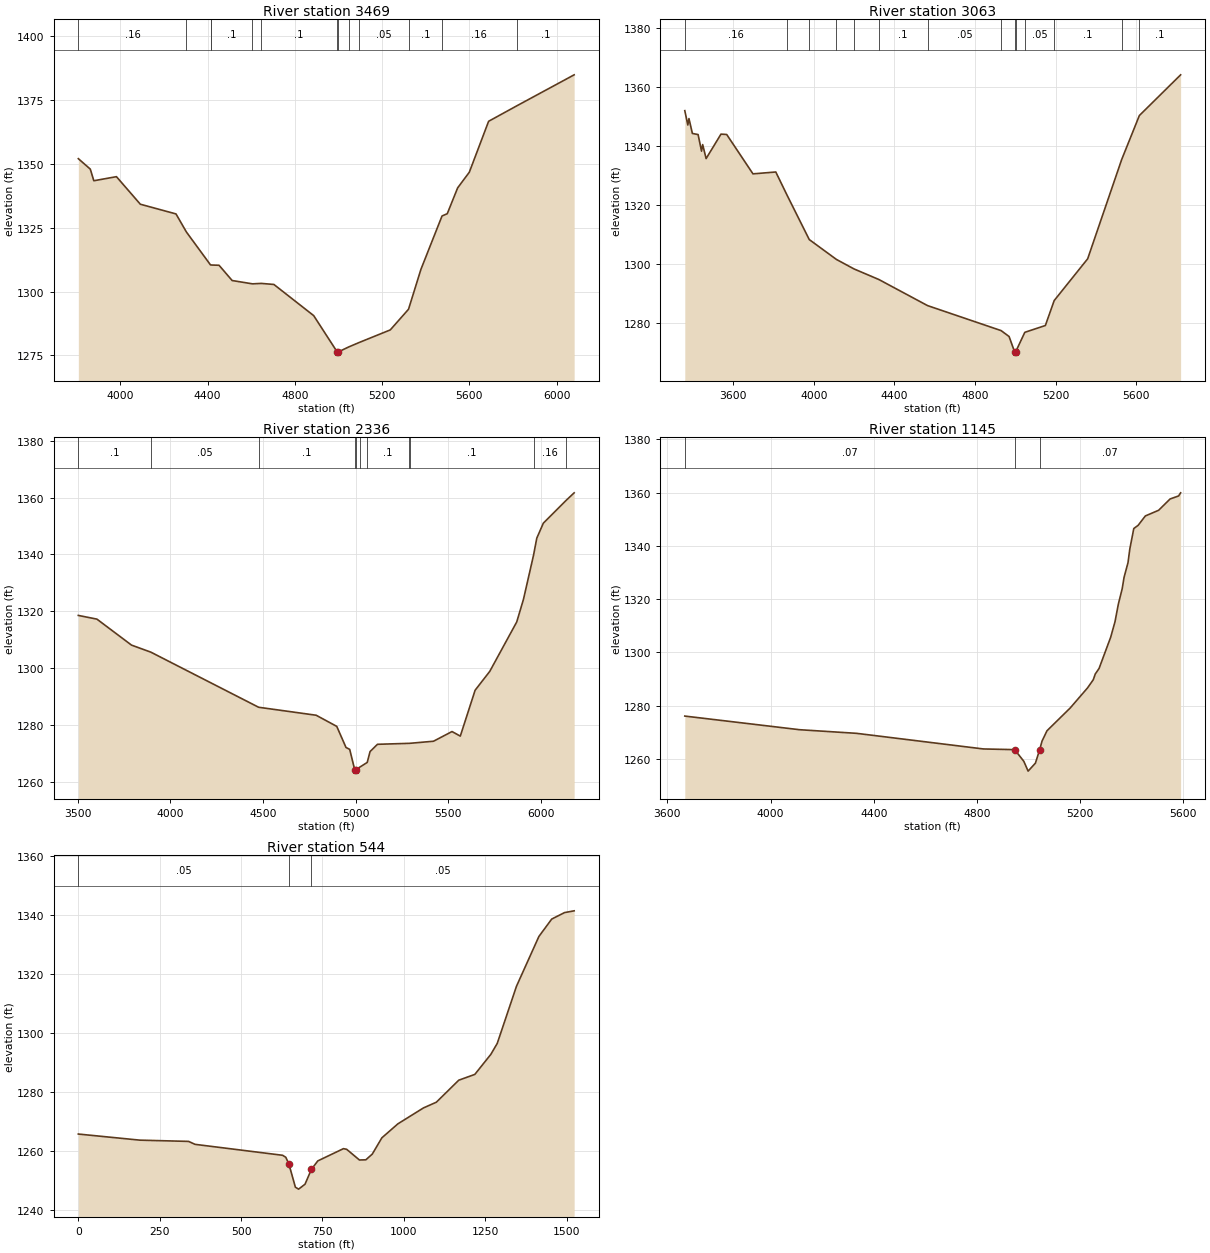
Type RM Length L Ch R = 1 ,3469    ,406,406,406
BEGIN DESCRIPTION:
Mapping XS 0dfc2f14
END DESCRIPTION:
XS GIS Cut Line= 4
      2867967.81     10088419.88      2868436.57     10089287.96
      2869072.42     10089242.39      2869714.15     10089333.44
#Sta/Elev= 30
  3807.9 1352.11  3862.7 1348.01  3878.9 1343.45  3982.6 1345.05  4092.1 1334.25
  4255.5 1330.45  4303.3 1323.35  4413.6 1310.47  4417.7 1310.43  4452.8 1310.33
  4512.8 1304.35    4606 1303.05  4646.5 1303.22  4704.1 1302.81  4886.6 1290.59
  4993.9  1276.4  4996.6  1275.9  4999.9  1276.4  5047.3 1278.33  5094.2 1280.04
  5237.5    1285  5321.1  1293.1  5377.8 1308.71  5474.6 1329.64  5498.6 1330.54
  5546.2 1340.66  5599.7  1346.8  5688.1 1366.75    5816 1372.75  6080.1 1384.96
#Mann= 13 ,-1 , 0
  3807.9     .16       0  4303.3      .1       0  4413.6     .05       0
  4417.7      .1       0    4606     .05       0  4646.5      .1       0
  4993.9     .07       0  4999.9      .1       0  5047.3     .16       0
  5094.2     .05       0  5321.1      .1       0  5474.6     .16       0
    5816      .1       0
Bank Sta=4993.9,4999.9
XS Rating Curve= 0 ,0
Exp/Cntr=0.3,0.1

Type RM Length L Ch R = 1 ,3063    ,727,727,727
BEGIN DESCRIPTION:
Mapping XS 8910cb73
END DESCRIPTION:
XS GIS Cut Line= 3
      2867926.59     10088396.04       2868521.2     10089643.86
      2869599.73     10089637.35
#Sta/Elev= 30
  3359.5    1352  3374.5 1347.15  3380.1 1349.32  3397.2 1344.29  3425.5 1343.91
  3442.6  1338.3  3448.2 1340.52  3465.3 1335.78    3539 1344.05  3567.4 1343.94
  3697.9 1330.61  3811.1 1331.24    3866 1323.54  3977.2 1308.37  4112.1 1301.64
  4199.6 1298.42  4322.6 1294.85  4564.2 1286.02  4929.5 1277.55    4969 1275.55
    4996 1270.43  4998.8 1269.93    5002 1270.43    5047 1276.97    5149 1279.28
  5192.9 1287.73    5359 1301.86  5527.5 1335.41  5615.5 1350.35  5820.3 1364.13
#Mann= 14 ,-1 , 0
  3359.5     .16       0    3866      .1       0  3977.2     .05       0
  4112.1      .1       0  4199.6     .05       0  4322.6      .1       0
  4564.2     .05       0  4929.5      .1       0    4996     .07       0
    5002      .1       0    5047     .05       0  5192.9      .1       0
  5527.5     .16       0  5615.5      .1       0
Bank Sta=4996,5002
XS Rating Curve= 0 ,0
Exp/Cntr=0.3,0.1

Type RM Length L Ch R = 1 ,2336    ,1191,1191,1191
BEGIN DESCRIPTION:
UNT104 IN NNOGR 3.0
END DESCRIPTION:
XS GIS Cut Line= 4
      2867230.01     10089706.81      2868417.04      10090273.2
      2868854.82     10090278.78      2869639.53     10089785.73
#Sta/Elev= 30
  3501.9 1318.51  3602.3 1317.21  3789.4 1308.06    3894 1305.58  4476.3 1286.19
  4787.3 1283.38  4898.6 1279.46  4948.6 1272.04  4968.6 1271.37  4995.6 1264.21
  4998.3 1263.71  5001.6 1264.21  5022.2 1265.08  5063.3 1266.77  5078.6 1270.59
  5118.6 1273.15  5290.2 1273.49  5295.4 1273.51  5421.5 1274.23  5521.6 1277.64
  5566.3 1276.03  5646.4 1292.18  5725.4  1298.8  5871.4 1316.22  5907.9 1324.22
  5962.1 1339.68  5979.7  1345.7  6015.1 1350.98  6138.9 1359.04  6181.7 1361.66
#Mann= 11 ,-1 , 0
  3501.9      .1       0    3894     .05       0  4476.3      .1       0
  4995.6     .07       0  5001.6      .1       0  5022.2     .05       0
  5063.3      .1       0  5290.2     .05       0  5295.4      .1       0
  5962.1     .16       0  6138.9      .1       0
Bank Sta=4995.6,5001.6
XS Rating Curve= 0 ,0
Exp/Cntr=0.3,0.1

Type RM Length L Ch R = 1 ,1145    ,601,601,601
BEGIN DESCRIPTION:
UNT104 IN NNOGR 3.2
END DESCRIPTION:
XS GIS Cut Line= 3
      2868395.74      10090780.9      2869543.29      10090886.8
      2869884.59     10090197.27
#Sta/Elev= 30
  3667.5 1276.07  4112.1 1270.95    4333 1269.59  4824.6 1263.72  4946.1 1263.46
  4981.6 1259.07  4998.2 1255.39  5026.5 1258.39  5042.5  1263.3  5052.1 1266.66
  5071.3 1270.55  5161.1 1279.09  5228.4 1286.64  5250.8 1289.73  5258.5 1291.88
  5273.2 1293.96  5318.1 1305.66  5334.9 1311.49  5347.8 1318.07  5362.9 1323.94
  5370.1 1328.21  5385.4 1333.73  5392.4 1338.86  5407.8 1346.53  5424.6 1347.73
  5452.6 1351.26    5504 1353.38  5548.6 1357.64  5581.6 1358.77  5589.3 1359.94
#Mann= 3 , 0 , 0
  3667.5     .07       0  4946.1     .03       0  5042.5     .07       0
Bank Sta=4946.1,5042.5
XS Rating Curve= 0 ,0
Exp/Cntr=0.3,0.1

Type RM Length L Ch R = 1 ,544     ,0,0,0
XS GIS Cut Line= 4
      2869447.82    10090943.053     2870029.418    10091142.706
      2870291.57    10090833.678     2870530.598     10090337.15
#Sta/Elev= 30
       0 1265.77  189.29  1263.7  338.73 1263.28  358.66 1262.28  627.53 1258.58
  637.37 1257.92  647.22 1255.54   666.9 1247.77  676.75 1247.12  696.43 1248.77
  716.12 1253.81   735.8 1256.68  814.55 1260.82  824.39 1260.61  863.76 1256.98
  883.45 1257.05  903.13 1258.98  932.66  1264.5  981.88 1269.23 1060.64 1274.63
 1100.02 1276.55 1168.95 1284.01 1218.18 1285.96 1267.41 1292.75  1287.1 1296.46
 1346.18  1315.8 1415.11 1332.67 1454.49 1338.56 1493.88 1340.75 1523.42 1341.35
#Mann= 3 , 0 , 0
       0     .05       0  647.22     .03       0  716.12     .05       0
Bank Sta=647.22,716.12
XS Rating Curve= 0 ,0
Exp/Cntr=0.3,0.1

Chan Stop Cuts=-1
Use User Specified Reach Order=0
Composite Channel Slope=5