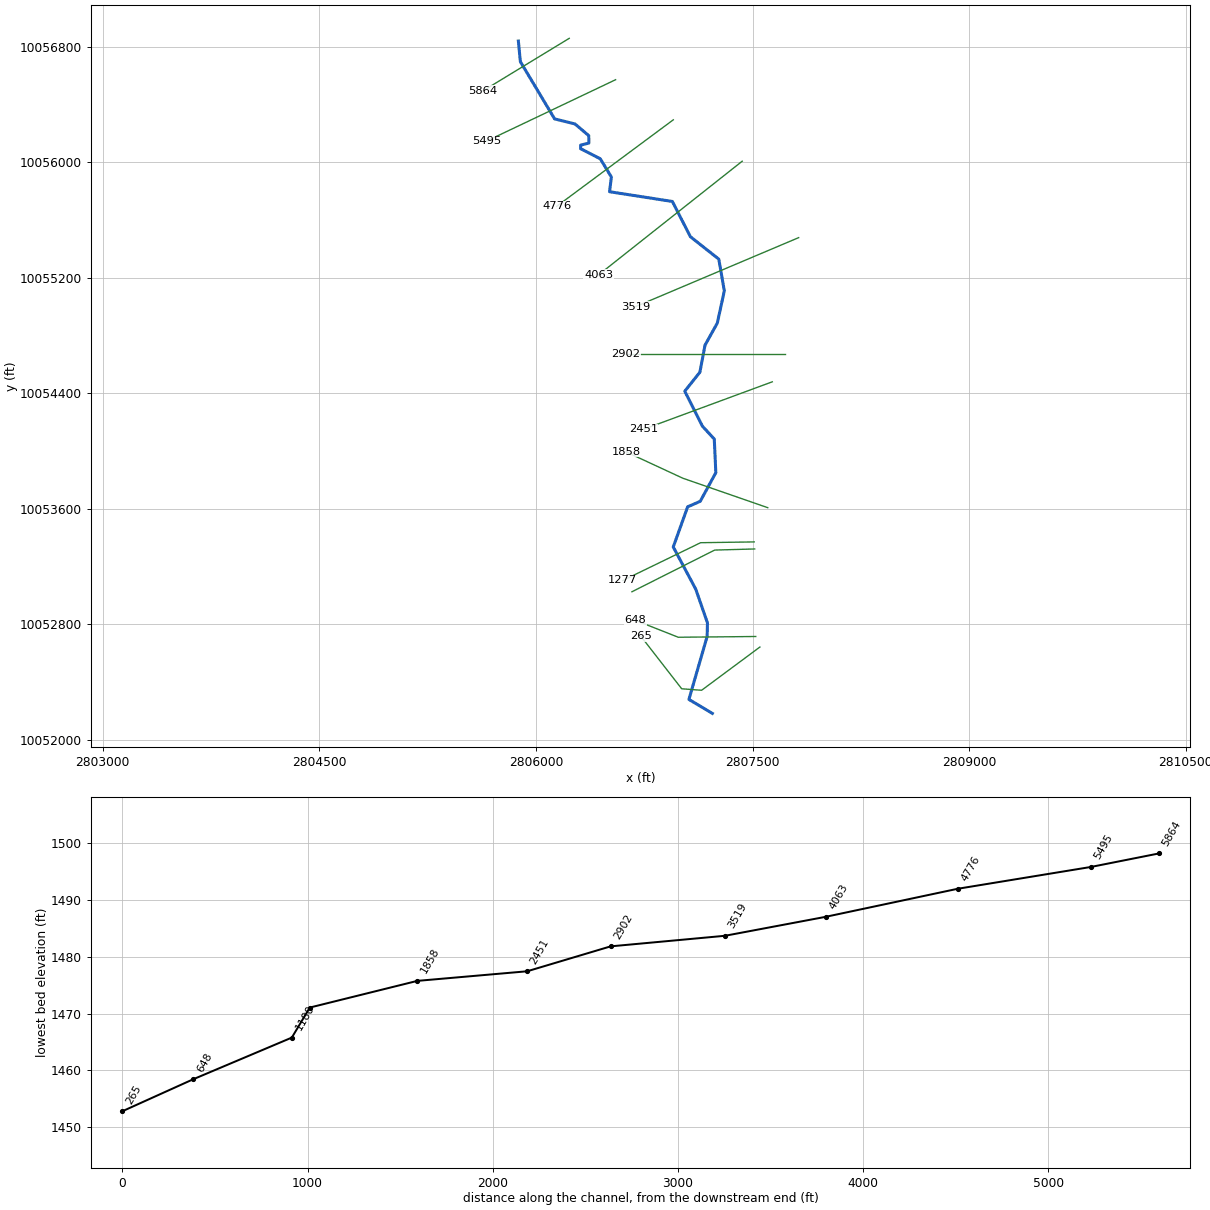
--- UNT107 IN NNOGR.prj (project) ---

Proj Title=UNT107 IN NNOGR Base Level Engineering
Current Plan=p01
Default Exp/Contr=0.3,0.1
English Units
Geom File=g01
Flow File=f01
Plan File=p01
BEGIN DESCRIPTION:
UNT107 IN NNOGR
END DESCRIPTION:

--- UNT107 IN NNOGR.p01 (plan) ---

Plan Title=Multiple Run
Short Identifier=Multiple
Geom File=g01
Flow File=f01
Subcritical Flow
K Sum by GR= 0
Std Step Tol= 0.01
Critical Tol= 0.01
Num of Std Step Trials= 20
Max Error Tol= 0.3
Flow Tol Ratio= 0.001
Split Flow NTrial= 30
Split Flow Tol= 0.02
Split Flow Ratio= 0.02
Log Output Level= 0
Friction Slope Method= 1
Unsteady Friction Slope Method= 2
Unsteady Bridges Friction Slope Method= 1
Parabolic Critical Depth
Global Vel Dist=  1 , 1 , 1
Global Log Level= 0
CheckData=True
Encroach Param= -1, 0, 0, 0
BEGIN DESCRIPTION:
Multiple Run
END DESCRIPTION:

--- UNT107 IN NNOGR.f01 (steady flow) ---

Flow Title=Multiple
Number of Profiles=7
Profile Names=10-year,25-year,50-year,1pct_min,100-year,1pct_plu,500-year
River Rch & RM= UNT107 IN NNOGR,Reach-1,5864
     695     990    1241    1140    1542    2085    2387
River Rch & RM= UNT107 IN NNOGR,Reach-1,4063
     948    1371    1736    1609    2176    2942    3430
Boundary for River Rch & Prof#=UNT107 IN NNOGR,Reach-1,1
Up Type=0
Dn Type=3
Dn Slope=0.005
Boundary for River Rch & Prof#=UNT107 IN NNOGR,Reach-1,2
Up Type=0
Dn Type=3
Dn Slope=0.005
Boundary for River Rch & Prof#=UNT107 IN NNOGR,Reach-1,3
Up Type=0
Dn Type=3
Dn Slope=0.005
Boundary for River Rch & Prof#=UNT107 IN NNOGR,Reach-1,4
Up Type=0
Dn Type=3
Dn Slope=0.005
Boundary for River Rch & Prof#=UNT107 IN NNOGR,Reach-1,5
Up Type=0
Dn Type=3
Dn Slope=0.005
Boundary for River Rch & Prof#=UNT107 IN NNOGR,Reach-1,6
Up Type=0
Dn Type=3
Dn Slope=0.005
Boundary for River Rch & Prof#=UNT107 IN NNOGR,Reach-1,7
Up Type=0
Dn Type=3
Dn Slope=0.005

--- UNT107 IN NNOGR.g01 (geometry) ---

Geom Title=Existing Conditions

River Reach=UNT107 IN NNOGR,Reach-1
Reach XY= 30
      2805878.29     10056838.40      2805892.28     10056695.31
      2806129.27     10056299.26      2806270.93     10056264.01
      2806365.59     10056183.46      2806366.90     10056131.81
      2806309.17     10056117.49      2806309.60     10056092.96
      2806445.92     10056022.83      2806522.04     10055897.41
      2806510.23     10055794.92      2806944.75     10055727.45
      2807069.69     10055483.41      2807266.33     10055327.96
      2807304.63     10055108.65      2807255.88     10054884.92
      2807170.97     10054732.70      2807135.29     10054544.98
      2807030.62     10054413.41      2807153.19     10054170.92
      2807234.98     10054082.24      2807245.72     10053849.23
      2807137.75     10053650.92      2807050.83     10053613.07
      2806950.94     10053334.88      2807106.60     10053042.96
      2807187.86     10052809.11      2807185.60     10052714.94
      2807059.45     10052279.06      2807221.58     10052182.51

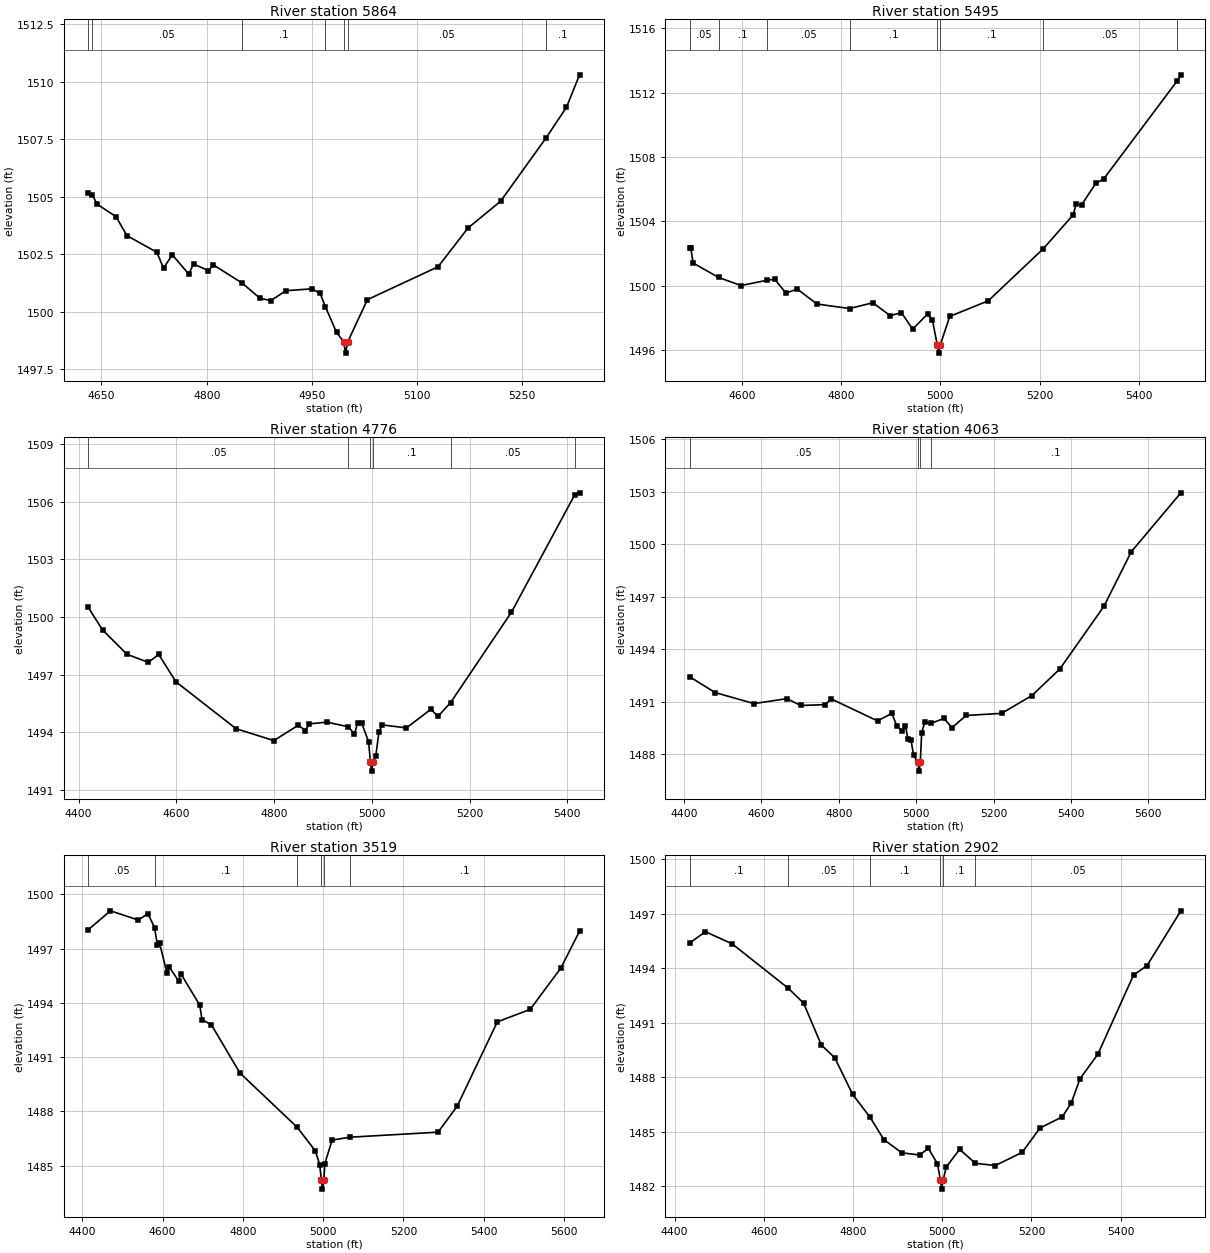
Type RM Length L Ch R = 1,5864,369,369,369
BEGIN DESCRIPTION:
UNT107 IN NNOGR 12.0
END DESCRIPTION:
XS GIS Cut Line= 2
      2806230.71     10056857.14      2805632.60     10056493.07
#Sta/Elev= 30
  4631.3 1505.17  4637.1 1505.08  4643.6 1504.68  4670.8 1504.13  4686.3 1503.31
  4728.9 1502.59  4738.5 1501.90  4751.0 1502.48  4774.4 1501.64  4781.2 1502.08
  4802.5 1501.79  4809.5 1502.04  4850.6 1501.25  4876.1 1500.59  4891.5 1500.49
  4912.9 1500.92  4949.7 1501.00  4961.7 1500.81  4969.1 1500.23  4985.1 1499.11
  4995.2 1498.71  4997.9 1498.21  5001.2 1498.71  5029.1 1500.53  5129.9 1501.96
  5172.5 1503.64  5218.9 1504.80  5283.3 1507.53  5312.9 1508.88  5331.5 1510.29
#Mann=7,-1,0
  4631.3     0.1       0  4637.1    0.05       0  4850.6     0.1       0
  4969.1    0.05       0  4995.2    0.03       0  5001.2    0.05       0
  5283.3     0.1       0
Bank Sta=4995.2,5001.2
Exp/Cntr=0.3,0.1

Type RM Length L Ch R = 1,5495,719,719,719
BEGIN DESCRIPTION:
UNT107 IN NNOGR 11.0
END DESCRIPTION:
XS GIS Cut Line= 2
      2806551.86     10056570.66      2805657.78     10056145.32
#Sta/Elev= 30
  4494.8 1502.34  4497.0 1502.34  4501.7 1501.42  4553.1 1500.52  4598.2 1500.02
  4651.2 1500.35  4666.2 1500.41  4688.9 1499.55  4711.7 1499.80  4751.5 1498.87
  4817.0 1498.59  4864.0 1498.95  4898.9 1498.15  4921.6 1498.33  4944.3 1497.31
  4974.7 1498.26  4984.2 1497.86  4993.9 1496.32  4996.6 1495.82  4999.9 1496.32
  5019.0 1498.10  5096.6 1499.07  5207.4 1502.30  5267.8 1504.41  5273.7 1505.06
  5284.8 1505.03  5313.3 1506.37  5329.1 1506.63  5477.9 1512.75  5484.9 1513.11
#Mann=8,-1,0
  4494.8    0.05       0  4553.1     0.1       0  4651.2    0.05       0
  4817.0     0.1       0  4993.9    0.07       0  4999.9     0.1       0
  5207.4    0.05       0  5477.9     0.1       0
Bank Sta=4993.9,4999.9
Exp/Cntr=0.3,0.1

Type RM Length L Ch R = 1,4776,713,713,713
BEGIN DESCRIPTION:
UNT107 IN NNOGR 10.0
END DESCRIPTION:
XS GIS Cut Line= 2
      2806951.16     10056292.88      2806143.89     10055693.93
#Sta/Elev= 30
  4419.8 1500.50  4448.9 1499.33  4499.0 1498.06  4542.8 1497.64  4563.7 1498.06
  4599.1 1496.63  4722.0 1494.19  4799.5 1493.57  4849.5 1494.37  4864.2 1494.09
  4871.4 1494.44  4908.0 1494.53  4951.9 1494.29  4964.3 1493.91  4971.0 1494.50
  4978.9 1494.50  4993.5 1493.50  4996.8 1492.48  4999.5 1491.98  5002.8 1492.48
  5008.2 1492.79  5014.4 1494.00  5020.8 1494.39  5070.7 1494.23  5120.8 1495.20
  5135.4 1494.83  5161.2 1495.55  5285.6 1500.25  5414.8 1506.35  5425.0 1506.47
#Mann=6,-1,0
  4419.8    0.05       0  4951.9     0.1       0  4996.8    0.07       0
  5002.8     0.1       0  5161.2    0.05       0  5414.8     0.1       0
Bank Sta=4996.8,5002.8
Exp/Cntr=0.3,0.1

Type RM Length L Ch R = 1,4063,544,544,544
BEGIN DESCRIPTION:
UNT107 IN NNOGR 8.0
END DESCRIPTION:
XS GIS Cut Line= 2
      2807428.61     10056006.43      2806433.32     10055218.86
#Sta/Elev= 30
  4414.7 1492.43  4480.2 1491.53  4580.7 1490.90  4666.2 1491.18  4701.4 1490.79
  4765.5 1490.84  4780.0 1491.17  4900.1 1489.91  4937.1 1490.34  4950.5 1489.59
  4964.3 1489.33  4972.3 1489.61  4978.7 1488.88  4986.7 1488.81  4993.1 1487.95
  5004.6 1487.54  5007.3 1487.04  5010.6 1487.54  5014.2 1489.24  5022.0 1489.83
  5038.4 1489.77  5071.7 1490.05  5092.5 1489.52  5129.0 1490.22  5220.7 1490.34
  5299.2 1491.36  5371.3 1492.88  5485.2 1496.46  5555.7 1499.57  5683.9 1502.94
#Mann=4,-1,0
  4414.7    0.05       0  5004.6   0.035       0  5010.6    0.05       0
  5038.4     0.1       0
Bank Sta=5004.6,5010.6
Exp/Cntr=0.3,0.1

Type RM Length L Ch R = 1,3519,617,617,617
BEGIN DESCRIPTION:
UNT107 IN NNOGR 7.0
END DESCRIPTION:
XS GIS Cut Line= 2
      2807819.20     10055476.90      2806692.12     10055000.06
#Sta/Elev= 30
  4414.8 1498.05  4469.9 1499.09  4539.4 1498.58  4563.1 1498.94  4579.8 1498.16
  4586.8 1497.19  4592.3 1497.31  4610.5 1495.65  4615.9 1496.00  4639.6 1495.21
  4645.1 1495.62  4692.4 1493.87  4697.9 1493.08  4721.6 1492.78  4792.6 1490.12
  4935.2 1487.12  4980.2 1485.82  4991.1 1485.06  4995.5 1484.20  4998.2 1483.70
  5001.5 1484.20  5003.9 1485.10  5022.1 1486.41  5065.5 1486.57  5286.2 1486.85
  5333.6 1488.28  5433.8 1492.95  5515.7 1493.64  5592.2 1495.93  5638.6 1497.96
#Mann=6,-1,0
  4414.8    0.05       0  4579.8     0.1       0  4935.2    0.05       0
  4995.5    0.04       0  5001.5    0.05       0  5065.5     0.1       0
Bank Sta=4995.5,5001.5
Exp/Cntr=0.3,0.1

Type RM Length L Ch R = 1,2902,451,451,451
BEGIN DESCRIPTION:
UNT107 IN NNOGR 6.0
END DESCRIPTION:
XS GIS Cut Line= 2
      2807723.73     10054669.62      2806622.43     10054669.62
#Sta/Elev= 30
  4433.8 1495.39  4469.1 1496.01  4529.1 1495.34  4655.2 1492.89  4689.1 1492.08
  4729.1 1489.77  4759.1 1489.07  4799.1 1487.06  4838.1 1485.80  4869.1 1484.57
  4909.1 1483.84  4949.1 1483.72  4969.1 1484.08  4989.1 1483.25  4996.1 1482.34
  4998.8 1481.84  5002.1 1482.34  5009.1 1483.06  5039.1 1484.03  5074.4 1483.26
  5119.1 1483.14  5179.1 1483.86  5219.1 1485.20  5269.1 1485.82  5289.1 1486.57
  5309.1 1487.92  5349.1 1489.27  5429.1 1493.63  5459.1 1494.14  5535.1 1497.16
#Mann=6,-1,0
  4433.8     0.1       0  4655.2    0.05       0  4838.1     0.1       0
  4996.1    0.07       0  5002.1     0.1       0  5074.4    0.05       0
Bank Sta=4996.1,5002.1
Exp/Cntr=0.3,0.1

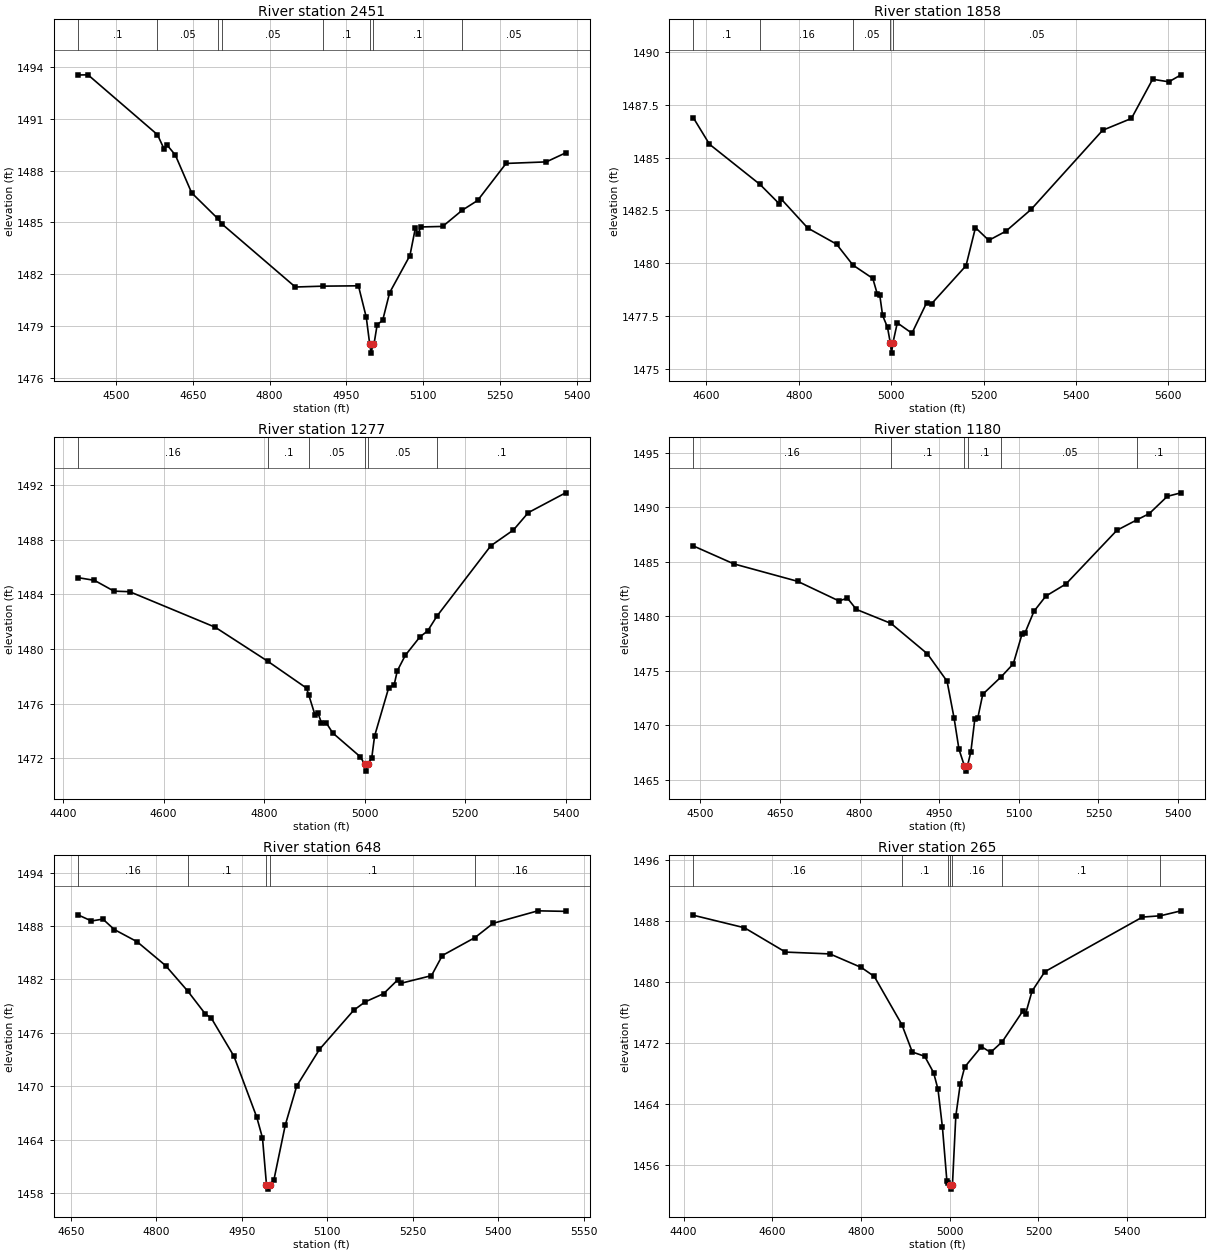
Type RM Length L Ch R = 1,2451,593,593,593
BEGIN DESCRIPTION:
UNT107 IN NNOGR 5.0
END DESCRIPTION:
XS GIS Cut Line= 2
      2807636.95     10054478.66      2806743.14     10054148.90
#Sta/Elev= 30
  4425.6 1493.52  4445.3 1493.53  4581.0 1490.07  4594.0 1489.24  4599.3 1489.49
  4615.8 1488.90  4647.8 1486.71  4698.6 1485.23  4707.8 1484.89  4850.3 1481.27
  4904.4 1481.32  4973.6 1481.34  4988.9 1479.52  4995.7 1477.95  4998.5 1477.45
  5001.7 1477.95  5004.0 1477.97  5010.2 1479.10  5020.9 1479.34  5034.5 1480.94
  5074.2 1483.09  5084.7 1484.66  5090.0 1484.35  5095.5 1484.74  5138.1 1484.77
  5176.5 1485.71  5206.4 1486.27  5262.0 1488.41  5340.6 1488.50  5378.3 1489.02
#Mann=8,-1,0
  4425.6     0.1       0  4581.0    0.05       0  4698.6     0.1       0
  4707.8    0.05       0  4904.4     0.1       0  4995.7    0.07       0
  5001.7     0.1       0  5176.5    0.05       0
Bank Sta=4995.7,5001.7
Exp/Cntr=0.3,0.1

Type RM Length L Ch R = 1,1858,581,581,581
BEGIN DESCRIPTION:
UNT107 IN NNOGR 3.0
END DESCRIPTION:
XS GIS Cut Line= 3
      2807605.45     10053606.93      2807017.35     10053810.92
      2806624.56     10053993.20
#Sta/Elev= 30
  4571.8 1486.88  4606.7 1485.63  4716.1 1483.73  4757.1 1482.83  4762.4 1483.03
  4819.4 1481.67  4881.7 1480.91  4917.2 1479.92  4960.2 1479.29  4969.8 1478.56
  4975.1 1478.53  4981.4 1477.54  4992.0 1476.98  4997.9 1476.26  5000.7 1475.76
  5003.9 1476.26  5013.2 1477.19  5044.9 1476.70  5076.7 1478.14  5087.3 1478.09
  5161.9 1479.89  5182.4 1481.69  5211.2 1481.09  5248.2 1481.52  5302.8 1482.55
  5457.6 1486.29  5520.0 1486.85  5565.8 1488.70  5600.9 1488.58  5627.3 1488.91
#Mann=5,-1,0
  4571.8     0.1       0  4716.1    0.16       0  4917.2    0.05       0
  4997.9    0.04       0  5003.9    0.05       0
Bank Sta=4997.9,5003.9
Exp/Cntr=0.3,0.1

Type RM Length L Ch R = 1,1277,97,97,97
BEGIN DESCRIPTION:
Mapping XS d78ba6d1
END DESCRIPTION:
XS GIS Cut Line= 3
      2807511.37     10053369.84      2807140.32     10053364.41
      2806601.74     10053102.69
#Sta/Elev= 30
  4429.8 1485.23  4462.7 1485.03  4501.5 1484.24  4532.7 1484.20  4702.7 1481.60
  4807.6 1479.10  4884.4 1477.14  4889.1 1476.61  4901.4 1475.16  4907.0 1475.32
  4914.1 1474.61  4924.0 1474.58  4936.4 1473.86  4991.7 1472.10  5000.1 1471.56
  5002.8 1471.06  5006.1 1471.56  5014.2 1472.04  5019.8 1473.63  5047.9 1477.17
  5058.7 1477.37  5064.9 1478.40  5080.9 1479.54  5110.0 1480.89  5125.4 1481.33
  5143.8 1482.41  5250.9 1487.56  5296.0 1488.72  5325.5 1489.99  5399.7 1491.44
#Mann=6,-1,0
  4429.8    0.16       0  4807.6     0.1       0  4889.1    0.05       0
  5000.1    0.04       0  5006.1    0.05       0  5143.8     0.1       0
Bank Sta=5000.1,5006.1
Exp/Cntr=0.3,0.1

Type RM Length L Ch R = 1,1180,532,532,532
BEGIN DESCRIPTION:
UNT107 IN NNOGR 2.0
END DESCRIPTION:
XS GIS Cut Line= 3
      2807514.72     10053321.01      2807237.98     10053313.41
      2806665.02     10053024.76
#Sta/Elev= 30
  4487.1 1486.46  4563.4 1484.81  4683.4 1483.21  4761.2 1481.41  4777.3 1481.66
  4794.0 1480.63  4859.4 1479.34  4927.8 1476.55  4964.9 1474.03  4978.1 1470.65
  4987.3 1467.78  4997.4 1466.27  5000.1 1465.77  5003.4 1466.27  5009.7 1467.54
  5017.1 1470.53  5022.7 1470.64  5032.1 1472.83  5067.3 1474.46  5089.6 1475.63
  5106.3 1478.40  5111.9 1478.50  5128.6 1480.46  5150.9 1481.85  5188.9 1482.97
  5284.8 1487.90  5323.3 1488.88  5345.7 1489.43  5379.7 1491.02  5405.5 1491.34
#Mann=6,-1,0
  4487.1    0.16       0  4859.4     0.1       0  4997.4    0.07       0
  5003.4     0.1       0  5067.3    0.05       0  5323.3     0.1       0
Bank Sta=4997.4,5003.4
Exp/Cntr=0.3,0.1

Type RM Length L Ch R = 1,648,383,383,383
BEGIN DESCRIPTION:
Mapping XS 001ef202
END DESCRIPTION:
XS GIS Cut Line= 3
      2807522.22     10052714.89      2806985.81     10052709.68
      2806688.94     10052826.87
#Sta/Elev= 30
  4662.3 1489.25  4686.1 1488.56  4706.1 1488.77  4726.1 1487.60  4766.1 1486.23
  4816.1 1483.55  4855.3 1480.66  4886.1 1478.09  4896.1 1477.67  4936.1 1473.36
  4976.1 1466.51  4986.1 1464.19  4993.1 1458.94  4995.8 1458.44  4999.1 1458.94
  5006.1 1459.47  5026.1 1465.64  5046.1 1470.02  5086.1 1474.14  5146.1 1478.53
  5166.1 1479.47  5198.7 1480.40  5223.1 1481.93  5228.4 1481.55  5282.6 1482.42
  5301.6 1484.68  5359.0 1486.70  5390.8 1488.30  5469.3 1489.70  5517.9 1489.64
#Mann=5,-1,0
  4662.3    0.16       0  4855.3     0.1       0  4993.1    0.07       0
  4999.1     0.1       0  5359.0    0.16       0
Bank Sta=4993.1,4999.1
Exp/Cntr=0.3,0.1

Type RM Length L Ch R = 1,265,0,0,0
BEGIN DESCRIPTION:
UNT107 IN NNOGR 1.0
END DESCRIPTION:
XS GIS Cut Line= 4
      2807550.95     10052642.00      2807147.27     10052342.49
      2807009.25     10052352.91      2806727.98     10052714.92
#Sta/Elev= 30
  4422.0 1488.71  4537.2 1487.07  4629.7 1483.88  4729.9 1483.64  4800.8 1481.86
  4830.0 1480.68  4892.1 1474.37  4915.6 1470.78  4943.5 1470.22  4963.6 1468.08
  4973.6 1465.88  4983.6 1460.89  4993.6 1453.87  4996.7 1453.60  5000.1 1453.30
  5002.9 1452.80  5006.1 1453.30  5013.7 1462.35  5023.7 1466.56  5033.8 1468.81
  5071.5 1471.48  5092.3 1470.73  5118.5 1472.13  5164.7 1476.14  5171.0 1475.76
  5185.5 1478.75  5214.5 1481.31  5434.4 1488.47  5475.1 1488.64  5521.5 1489.29
#Mann=7,-1,0
  4422.0    0.16       0  4892.1     0.1       0  4996.7    0.16       0
  5000.1    0.07       0  5006.1    0.16       0  5118.5     0.1       0
  5475.1    0.16       0
Bank Sta=5000.1,5006.1
Exp/Cntr=0.3,0.1

Chan Stop Cuts=-1