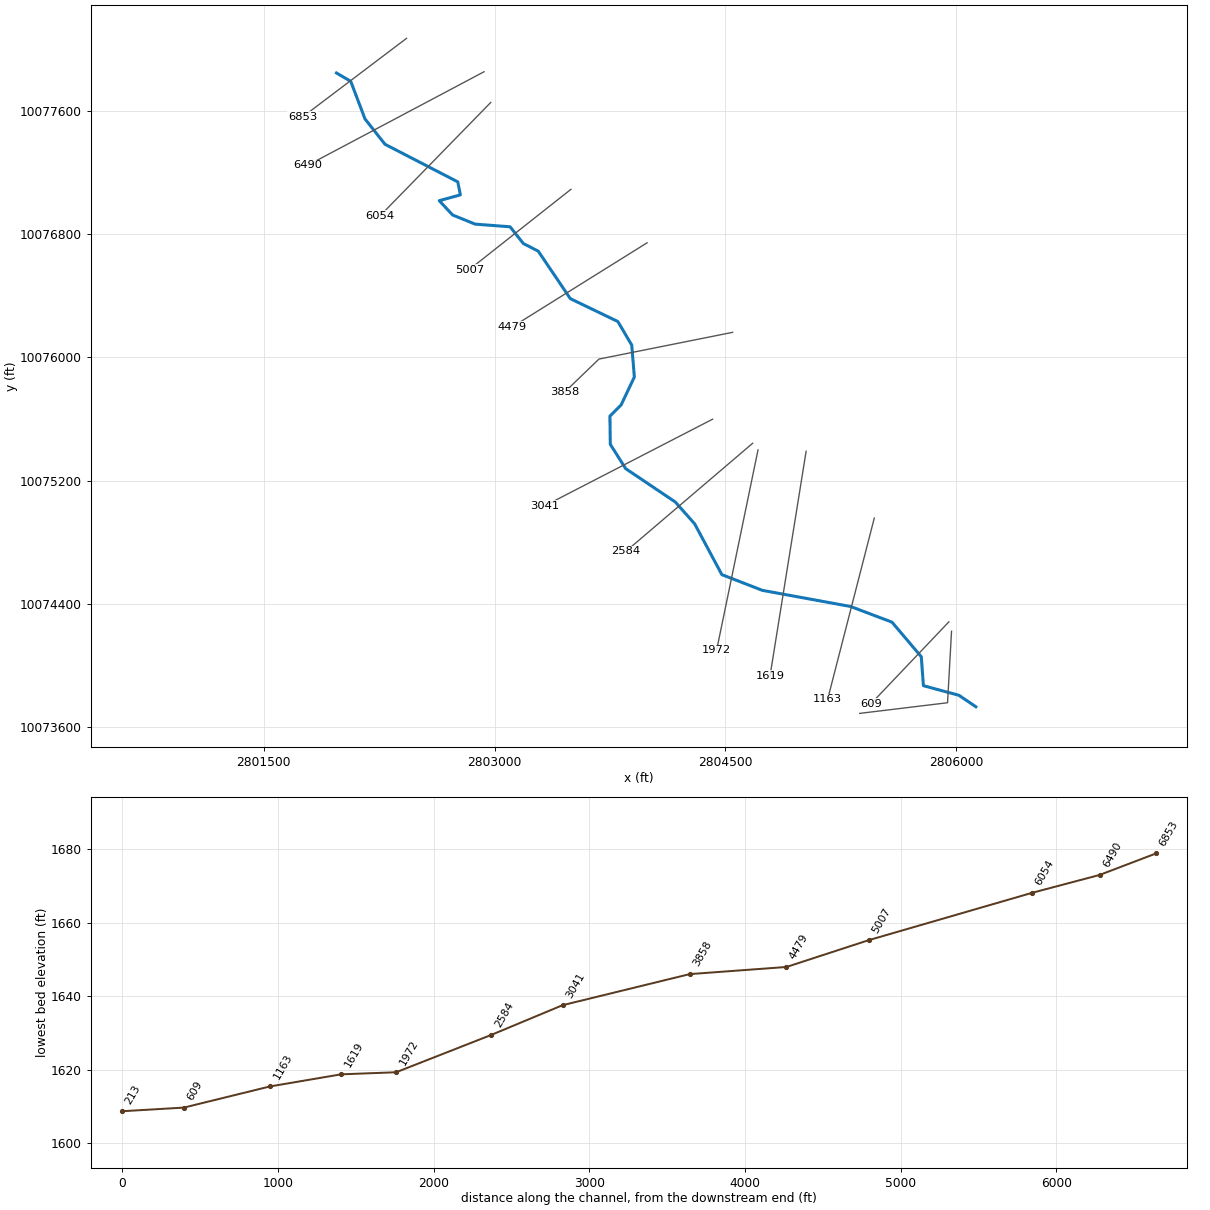
--- UNT108 IN NNOGR.prj (project) ---

Proj Title=UNT108 IN NNOGR Base Level Engineering
Current Plan=p01
Default Exp/Contr=0.3,0.1
English Units
Geom File=g01
Flow File=f01
Plan File=p01
Y Axis Title=Elevation
X Axis Title(PF)=Main Channel Distance
X Axis Title(XS)=Station
BEGIN DESCRIPTION:
UNT108 IN NNOGR
END DESCRIPTION:
DSS Export Rating Curves= 0
DSS Export Rating Curve Sorted= 0
DSS Export Volume Flow Curves= 0
DXF OffsetX= 0
DXF OffsetY= 0
DXF ScaleX= 1
DXF ScaleY= 10

--- UNT108 IN NNOGR.p01 (plan) ---

Plan Title=Multiple Run
Short Identifier=Multiple
Geom File=g01
Flow File=f01
Subcritical Flow
K Sum by GR= 0
Std Step Tol= 0.01
Critical Tol= 0.01
Num of Std Step Trials= 20
Max Error Tol= 0.3
Flow Tol Ratio= 0.001
Split Flow NTrial= 30
Split Flow Tol= 0.02
Split Flow Ratio= 0.02
Log Output Level= 0
Friction Slope Method= 1
Unsteady Friction Slope Method= 2
Unsteady Bridges Friction Slope Method= 1
Parabolic Critical Depth
Global Vel Dist=  1 , 1 , 1
Global Log Level= 0
CheckData=True
Encroach Param= -1, 0, 0, 0
BEGIN DESCRIPTION:
Multiple Run
END DESCRIPTION:

--- UNT108 IN NNOGR.f01 (steady flow) ---

Flow Title=Multiple
Program Version=4.10
Number of Profiles= 7
Profile Names=10-year,25-year,50-year,1pct_min,100-year,1pct_plu,500-year
River Rch & RM=UNT108 IN NNOGR,Reach-1         ,6853
     871    1266    1611    1502    2032    2748    3241
River Rch & RM=UNT108 IN NNOGR,Reach-1         ,6054
    1139    1672    2141    2006    2713    3669    4372
Boundary for River Rch & Prof#=UNT108 IN NNOGR,Reach-1         , 1
Up Type= 0
Dn Type= 3
Dn Slope=0.01
Boundary for River Rch & Prof#=UNT108 IN NNOGR,Reach-1         , 2
Up Type= 0
Dn Type= 3
Dn Slope=0.01
Boundary for River Rch & Prof#=UNT108 IN NNOGR,Reach-1         , 3
Up Type= 0
Dn Type= 3
Dn Slope=0.01
Boundary for River Rch & Prof#=UNT108 IN NNOGR,Reach-1         , 4
Up Type= 0
Dn Type= 3
Dn Slope=0.01
Boundary for River Rch & Prof#=UNT108 IN NNOGR,Reach-1         , 5
Up Type= 0
Dn Type= 3
Dn Slope=0.01
Boundary for River Rch & Prof#=UNT108 IN NNOGR,Reach-1         , 6
Up Type= 0
Dn Type= 3
Dn Slope=0.01
Boundary for River Rch & Prof#=UNT108 IN NNOGR,Reach-1         , 7
Up Type= 0
Dn Type= 3
Dn Slope=0.01
DSS Import GetInterval= 0
DSS Import GetPeak= 0
DSS Import FillOption= 0

--- UNT108 IN NNOGR.g01 (geometry) ---

Geom Title=Existing Conditions
Program Version=4.10

River Reach=UNT108 IN NNOGR ,Reach-1
Reach XY= 30
      2801973.49     10077847.33      2802066.26     10077792.91
      2802158.72     10077548.81      2802288.65     10077384.24
      2802761.25     10077140.19      2802778.42     10077055.57
      2802641.08     10077017.84      2802727.97     10076924.77
      2802874.33     10076865.55       2803101.2     10076848.27
      2803187.13      10076739.7      2803284.08       10076690.
      2803492.49     10076381.49      2803801.15     10076232.88
      2803891.25     10076080.02      2803908.47     10075872.66
      2803822.61     10075691.65       2803749.7     10075618.24
      2803752.09     10075435.23       2803852.1      10075277.3
      2804174.97     10075060.15      2804300.33     10074918.29
      2804476.66     10074588.85      2804739.73     10074486.78
      2805313.24     10074381.84      2805581.85     10074280.14
      2805772.19     10074055.57      2805785.99     10073867.55
      2806016.64     10073805.11      2806126.67     10073730.52

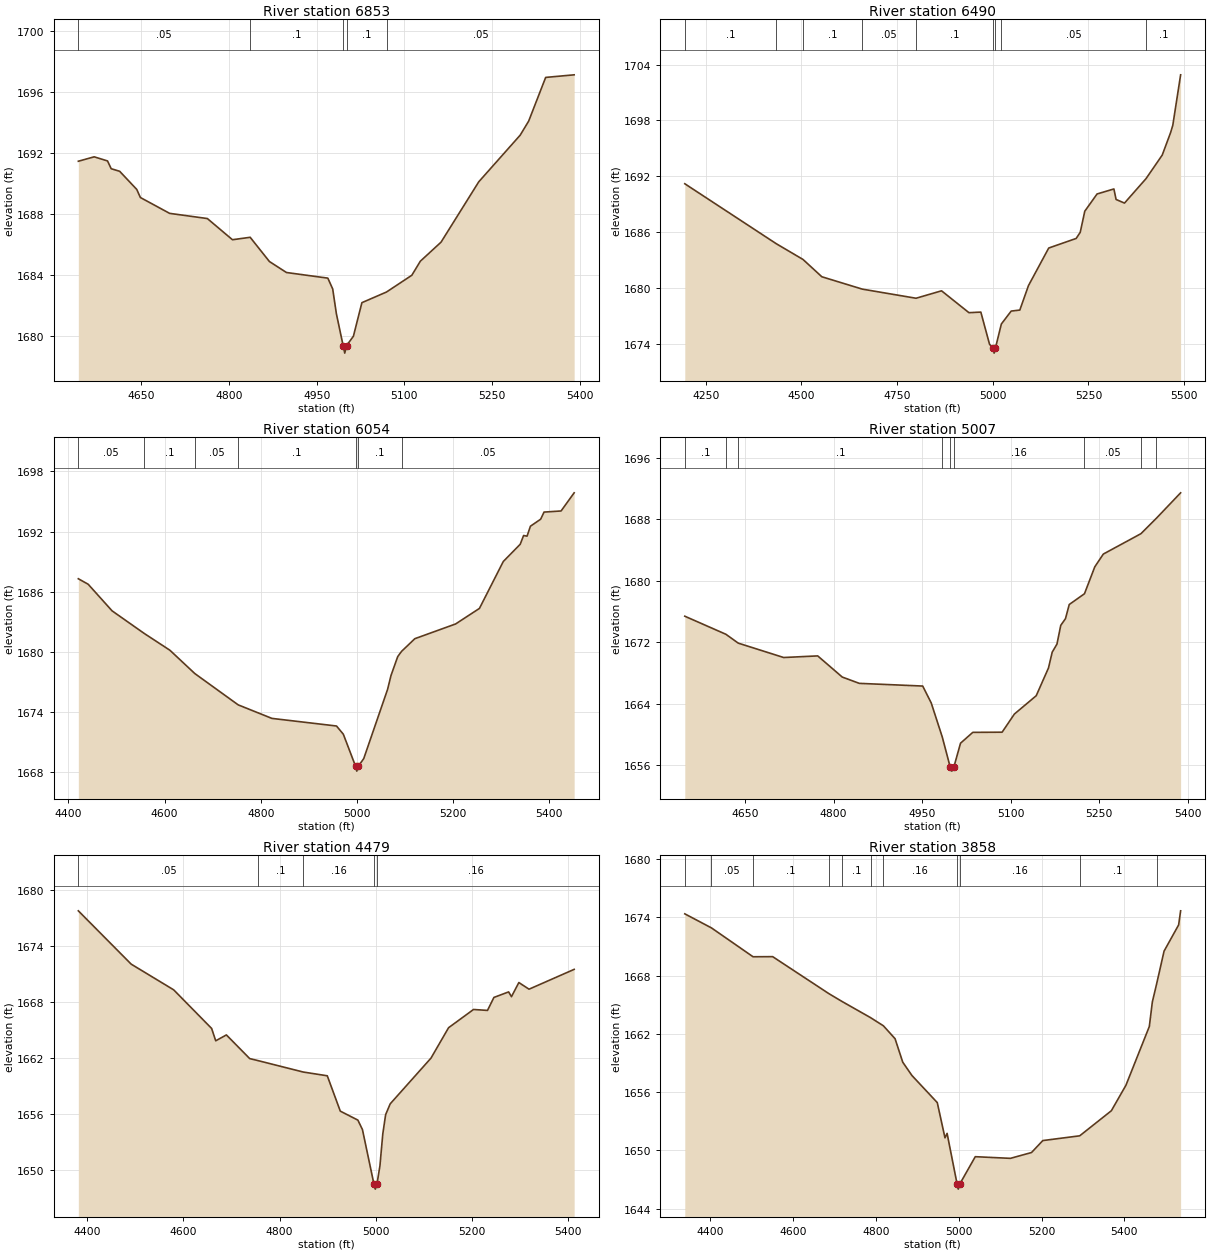
Type RM Length L Ch R = 1 ,6853    ,363,363,363
BEGIN DESCRIPTION:
UNT108 IN NNOGR 15.0
END DESCRIPTION:
XS GIS Cut Line= 2
      2802428.59     10078072.39      2801752.51       10077561.
#Sta/Elev= 30
  4542.5 1691.44  4569.6 1691.73  4592.4 1691.46  4598.7 1690.95  4613.2 1690.78
  4642.4 1689.59  4648.6 1689.06  4698.6 1688.02  4763.1 1687.68    4806 1686.29
  4836.3 1686.45  4869.2 1684.86  4898.3 1684.14  4969.1 1683.77  4977.4 1683.06
  4983.7 1681.43  4995.2 1679.35    4998 1678.85  5001.2 1679.35  5012.8 1679.96
  5027.3 1682.16  5069.4 1682.86  5112.7 1683.96  5127.2 1684.88  5162.6 1686.13
  5227.1 1690.09  5297.9 1693.15  5312.4 1694.07  5341.5 1696.94  5390.2 1697.11
#Mann= 5 ,-1 , 0
  4542.5     .05       0  4836.3      .1       0  4995.2     .07       0
  5001.2      .1       0  5069.4     .05       0
Bank Sta=4995.2,5001.2
XS Rating Curve= 0 ,0
Exp/Cntr=0.3,0.1

Type RM Length L Ch R = 1 ,6490    ,436,436,436
BEGIN DESCRIPTION:
UNT108 IN NNOGR 14.0
END DESCRIPTION:
XS GIS Cut Line= 2
      2802932.11     10077855.41      2801787.15     10077248.23
#Sta/Elev= 30
    4195  1691.2  4434.2 1684.75    4504 1683.06  4553.2  1681.2    4659 1679.87
  4799.4 1678.89  4866.1 1679.69  4937.7 1677.34  4968.8  1677.4  4991.5 1673.95
  5000.7 1673.49  5003.5 1672.99  5006.7 1673.49  5022.4 1676.12  5048.1 1677.51
  5070.7 1677.62  5093.3 1680.25  5146.3 1684.29    5218 1685.32  5228.6 1685.98
  5240.5 1688.25  5272.6  1690.1  5316.6 1690.64  5322.3 1689.51  5344.3 1689.12
  5400.6 1691.75  5442.9 1694.28  5464.9 1696.71  5470.6  1697.5    5491 1702.91
#Mann= 9 ,-1 , 0
    4195      .1       0  4434.2     .05       0    4504      .1       0
    4659     .05       0  4799.4      .1       0  5000.7     .07       0
  5006.7      .1       0  5022.4     .05       0  5400.6      .1       0
Bank Sta=5000.7,5006.7
XS Rating Curve= 0 ,0
Exp/Cntr=0.3,0.1

Type RM Length L Ch R = 1 ,6054    ,1047,1047,1047
BEGIN DESCRIPTION:
UNT108 IN NNOGR 13.0
END DESCRIPTION:
XS GIS Cut Line= 2
       2802975.5     10077655.76      2802255.41     10076918.32
#Sta/Elev= 30
  4420.7 1687.29  4441.2 1686.74  4490.8 1684.09  4557.5 1681.84    4611 1680.16
  4662.9 1677.83    4753 1674.71  4823.1 1673.36  4957.4  1672.6  4971.6 1671.78
  4996.9  1668.6  4999.6  1668.1  5002.9  1668.6    5014 1669.35  5063.6 1676.26
  5070.6 1677.63  5084.7 1679.53  5092.7 1680.05  5120.2 1681.31    5205 1682.78
  5254.5 1684.33  5304.1 1689.01  5339.3 1690.73  5346.3  1691.6  5353.5 1691.54
  5360.5 1692.53  5381.8 1693.23  5388.8 1693.94  5424.2 1694.05  5451.4 1695.86
#Mann= 7 ,-1 , 0
  4420.7     .05       0  4557.5      .1       0  4662.9     .05       0
    4753      .1       0  4996.9     .07       0  5002.9      .1       0
  5092.7     .05       0
Bank Sta=4996.9,5002.9
XS Rating Curve= 0 ,0
Exp/Cntr=0.3,0.1

Type RM Length L Ch R = 1 ,5007    ,528,528,528
BEGIN DESCRIPTION:
UNT108 IN NNOGR 11.0
END DESCRIPTION:
XS GIS Cut Line= 2
      2803496.32     10077091.51      2802836.63      10076570.7
#Sta/Elev= 30
  4547.8 1675.39  4617.5 1673.04  4638.4 1671.89  4715.4 1670.02  4773.1 1670.23
  4814.7 1667.48  4843.6 1666.66  4951.1 1666.31  4965.5 1664.12  4984.3 1659.68
  4997.8 1655.75  5000.5 1655.25  5003.8 1655.75  5015.2 1658.88    5036 1660.29
  5085.7 1660.31  5106.5 1662.67  5143.5 1665.05  5164.3 1668.66  5170.6 1670.71
  5178.7 1671.77  5185.1  1674.2  5193.1 1675.07  5199.5 1676.91  5225.3 1678.31
  5242.8 1681.81  5257.3 1683.47  5321.1 1686.12  5346.9  1688.1  5388.3 1691.43
#Mann= 9 ,-1 , 0
  4547.8      .1       0  4617.5     .05       0  4638.4      .1       0
  4984.3     .16       0  4997.8     .07       0  5003.8     .16       0
  5225.3     .05       0  5321.1      .1       0  5346.9     .05       0
Bank Sta=4997.8,5003.8
XS Rating Curve= 0 ,0
Exp/Cntr=0.3,0.1

Type RM Length L Ch R = 1 ,4479    ,621,621,621
BEGIN DESCRIPTION:
UNT108 IN NNOGR 9.0
END DESCRIPTION:
XS GIS Cut Line= 2
      2803991.11     10076744.28       2803115.4     10076198.05
#Sta/Elev= 30
  4381.1 1677.72  4491.1 1672.02  4579.6 1669.27  4658.6 1665.14  4667.1 1663.82
  4689.3 1664.45  4737.8 1661.92  4756.1 1661.69  4849.4 1660.48  4899.3 1660.08
  4926.4  1656.3    4963 1655.34  4972.5 1654.33  4996.6 1648.46  4999.3 1647.96
  5002.6 1648.46  5008.9 1650.45  5014.9 1653.88  5020.8 1655.93  5030.3 1657.08
  5115.2 1661.97  5151.8 1665.22  5203.7 1667.17  5232.8 1667.07  5246.2 1668.46
  5276.8 1669.05  5282.7 1668.54  5298.1 1670.05  5319.3 1669.34  5413.2 1671.46
#Mann= 5 ,-1 , 0
  4381.1     .05       0  4756.1      .1       0  4849.4     .16       0
  4996.6     .07       0  5002.6     .16       0
Bank Sta=4996.6,5002.6
XS Rating Curve= 0 ,0
Exp/Cntr=0.3,0.1

Type RM Length L Ch R = 1 ,3858    ,817,817,817
BEGIN DESCRIPTION:
UNT108 IN NNOGR 8.0
END DESCRIPTION:
XS GIS Cut Line= 3
      2804546.61     10076162.67       2803678.6     10075989.07
       2803453.2     10075772.33
#Sta/Elev= 30
    4338 1674.37  4402.5 1672.92  4502.9 1669.95  4550.3 1669.96  4686.9 1666.13
  4718.1 1665.34  4786.8 1663.68  4817.8 1662.84    4846 1661.51  4864.6 1659.09
  4886.8 1657.72    4948 1654.93  4966.6  1651.3  4971.7 1651.76    4996 1646.52
  4998.7 1646.02    5002 1646.52  5039.8 1649.36  5124.7 1649.19  5175.7 1649.79
  5202.9 1651.02  5292.1 1651.51  5368.5 1654.09  5403.7 1656.71  5460.3 1662.77
  5467.6  1665.3  5477.8 1667.13  5495.9 1670.53  5531.1 1673.23  5535.9 1674.68
#Mann= 11 ,-1 , 0
    4338      .1       0  4402.5     .05       0  4502.9      .1       0
  4686.9     .05       0  4718.1      .1       0  4786.8     .05       0
  4817.8     .16       0    4996     .07       0    5002     .16       0
  5292.1      .1       0  5477.8     .16       0
Bank Sta=4996,5002
XS Rating Curve= 0 ,0
Exp/Cntr=0.3,0.1

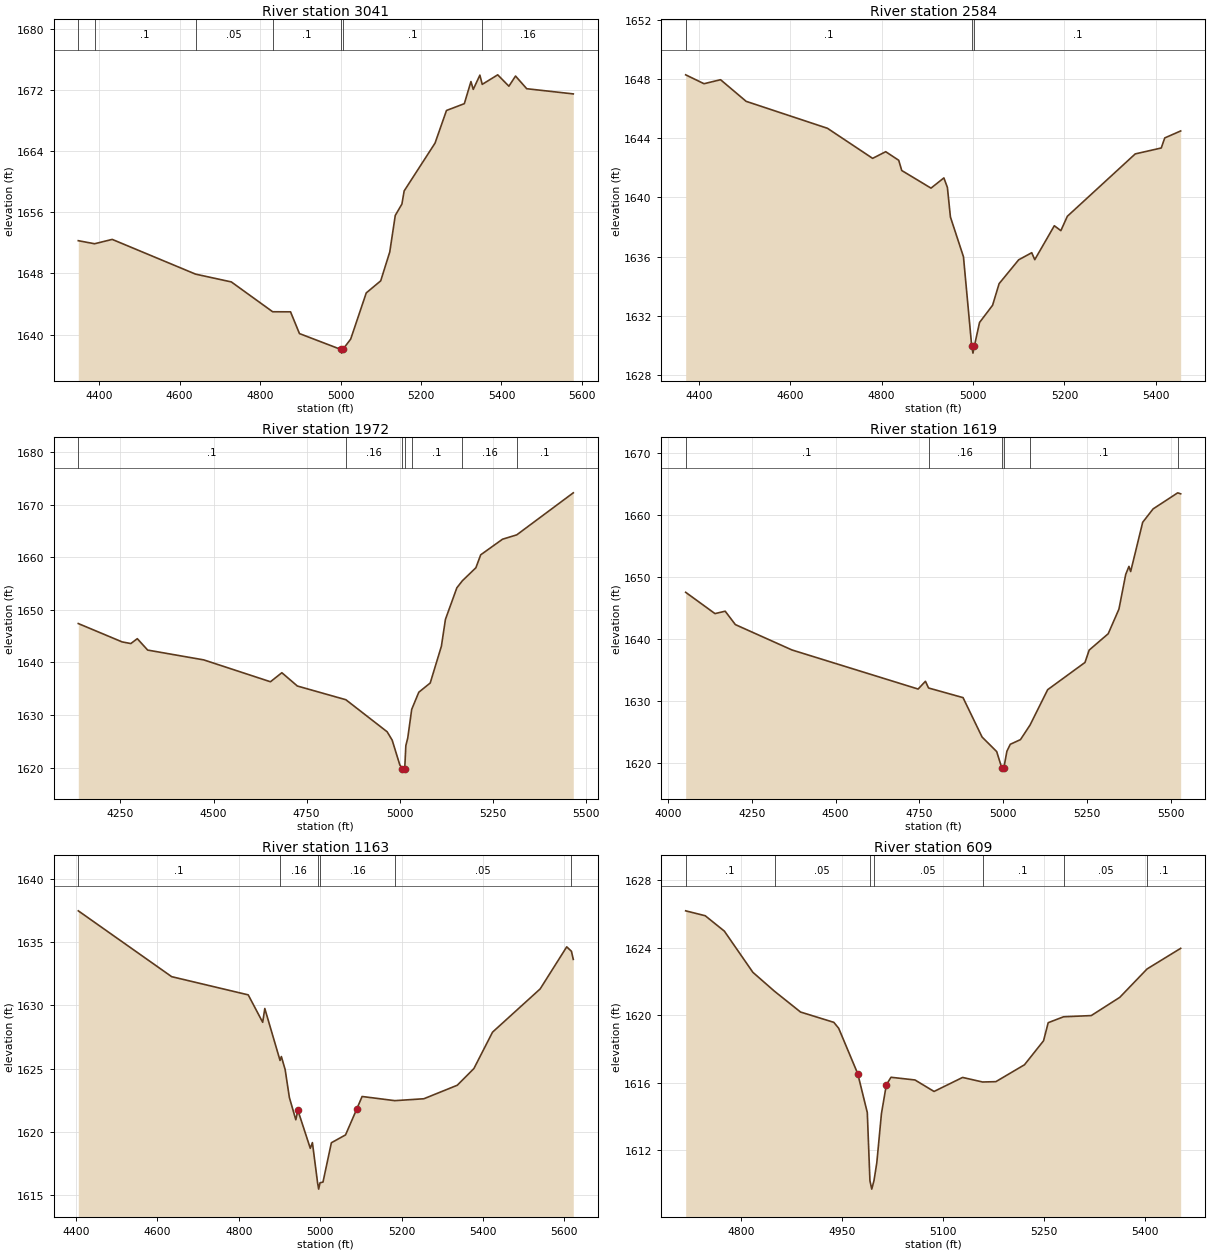
Type RM Length L Ch R = 1 ,3041    ,457,457,457
BEGIN DESCRIPTION:
UNT108 IN NNOGR 6.0
END DESCRIPTION:
XS GIS Cut Line= 2
      2804416.42     10075598.43      2803323.12     10075034.42
#Sta/Elev= 30
  4348.3 1652.29  4388.8 1651.89  4432.6 1652.46  4639.7 1647.91  4728.6 1646.89
  4831.4 1642.98  4875.8 1642.97    4898 1640.12  5000.1 1638.06  5002.9 1637.56
  5006.1 1638.06  5025.3  1639.4    5064 1645.45  5099.9 1647.03  5122.4 1650.81
  5136.1  1655.6  5152.6 1657.09  5158.2 1658.81  5234.9 1665.07  5263.4 1669.35
  5307.7 1670.24  5324.2 1673.14  5329.9 1672.11  5346.4 1673.98  5352.2 1672.77
  5390.7 1674.02  5418.5 1672.53    5435 1673.86  5462.8  1672.2  5578.5 1671.52
#Mann= 7 ,-1 , 0
  4348.3     .05       0  4388.8      .1       0  4639.7     .05       0
  4831.4      .1       0  5000.1     .07       0  5006.1      .1       0
  5352.2     .16       0
Bank Sta=5000.1,5006.1
XS Rating Curve= 0 ,0
Exp/Cntr=0.3,0.1

Type RM Length L Ch R = 1 ,2584    ,612,612,612
BEGIN DESCRIPTION:
UNT108 IN NNOGR 5.0
END DESCRIPTION:
XS GIS Cut Line= 2
      2804676.89     10075442.22      2803852.86     10074739.62
#Sta/Elev= 30
  4371.3 1648.28  4411.4 1647.68  4447.6 1647.95  4503.6 1646.49  4681.5 1644.67
  4780.3 1642.64  4808.9 1643.09  4837.4 1642.51    4844 1641.82    4908 1640.63
  4936.2 1641.32  4943.9 1640.67  4950.5 1638.68    4979    1636    4997 1629.99
  4999.8 1629.49    5003 1629.99  5014.2 1631.56  5042.7 1632.72    5057 1634.18
  5099.8 1635.79  5128.4 1636.27    5135  1635.8  5177.8 1638.09  5192.1 1637.76
  5206.3 1638.73  5354.8 1642.94  5411.7 1643.34  5419.4 1644.02  5454.2 1644.49
#Mann= 3 ,-1 , 0
  4371.3      .1       0    4997     .07       0    5003      .1       0
Bank Sta=4997,5003
XS Rating Curve= 0 ,0
Exp/Cntr=0.3,0.1

Type RM Length L Ch R = 1 ,1972    ,353,353,353
BEGIN DESCRIPTION:
UNT108 IN NNOGR 4.0
END DESCRIPTION:
XS GIS Cut Line= 2
       2804711.6     10075398.83       2804442.7     10074097.72
#Sta/Elev= 30
    4137 1647.41  4254.5 1643.92    4278  1643.6  4295.4 1644.53  4323.2 1642.36
  4473.9 1640.49  4652.8 1636.33  4683.4 1638.05    4725 1635.52  4855.2 1632.91
    4966 1626.81  4979.5 1625.22    5000  1620.5  5007.2 1619.82  5009.9 1619.32
  5013.2 1619.82  5016.2 1624.17  5021.3 1625.62  5031.9 1631.07    5051 1634.34
  5081.6 1636.09  5111.6 1643.09  5122.5 1648.21  5153.1 1654.21  5167.9 1655.55
  5204.2 1658.03  5217.1 1660.49  5275.7 1663.46  5313.9 1664.29  5465.6 1672.29
#Mann= 7 ,-1 , 0
    4137      .1       0  4855.2     .16       0  5007.2     .07       0
  5013.2     .16       0  5031.9      .1       0  5167.9     .16       0
  5313.9      .1       0
Bank Sta=5007.2,5013.2
XS Rating Curve= 0 ,0
Exp/Cntr=0.3,0.1

Type RM Length L Ch R = 1 ,1619    ,456,456,456
BEGIN DESCRIPTION:
UNT108 IN NNOGR 3.0
END DESCRIPTION:
XS GIS Cut Line= 2
      2805024.09     10075390.11      2804789.72     10073931.82
#Sta/Elev= 30
  4052.5 1647.54    4140 1644.11  4170.4  1644.5  4200.8 1642.34  4369.7 1638.26
  4746.1 1631.97  4767.9 1633.22  4777.2 1632.14  4880.1 1630.59  4936.9 1624.25
  4980.6  1621.9  4995.8 1619.26  4998.5 1618.76  5001.8 1619.26    5011 1621.96
  5021.1 1623.08  5051.5 1623.83  5080.1 1626.18  5132.7 1631.87    5244 1636.25
  5256.5 1638.24  5313.3 1640.87  5345.3 1644.83  5365.5 1650.41  5375.2 1651.71
  5380.3 1650.88  5416.2 1658.81  5447.2 1660.96  5520.7 1663.55  5529.5 1663.39
#Mann= 6 ,-1 , 0
  4052.5      .1       0  4777.2     .16       0  4995.8     .07       0
  5001.8     .16       0  5080.1      .1       0  5520.7     .05       0
Bank Sta=4995.8,5001.8
XS Rating Curve= 0 ,0
Exp/Cntr=0.3,0.1

Type RM Length L Ch R = 1 ,1163    ,554,554,554
BEGIN DESCRIPTION:
UNT108 IN NNOGR 2.0
END DESCRIPTION:
XS GIS Cut Line= 2
      2805466.79     10074956.04      2805163.64     10073778.12
#Sta/Elev= 30
  4405.6 1637.49  4635.1 1632.28  4823.2 1630.84  4858.7 1628.67  4863.9 1629.76
  4901.4 1625.65  4904.6 1625.96  4913.9 1624.93  4924.3 1622.72  4940.1 1620.96
  4945.3  1621.7  4975.7  1618.7  4980.9 1619.15  4993.6 1615.97  4996.3 1615.47
  4999.6 1615.97  5006.9 1616.03  5027.5 1619.14  5062.3 1619.76  5089.5 1621.78
    5103  1622.8  5183.4 1622.47  5254.7 1622.62  5336.9 1623.69  5377.7 1625.01
  5423.5 1627.89  5540.5 1631.31  5605.8 1634.64  5617.4 1634.29  5621.9 1633.65
#Mann= 6 ,-1 , 0
  4405.6      .1       0  4901.4     .16       0  4993.6     .07       0
  4999.6     .16       0  5183.4     .05       0  5617.4      .1       0
Bank Sta=4945.3,5089.5
XS Rating Curve= 0 ,0
Exp/Cntr=0.3,0.1

Type RM Length L Ch R = 1 ,609     ,396,396,396
BEGIN DESCRIPTION:
UNT108 IN NNOGR 1.0
END DESCRIPTION:
XS GIS Cut Line= 2
      2805951.24     10074282.13      2805444.71     10073749.55
#Sta/Elev= 30
  4717.4 1626.18  4746.4 1625.89  4774.8 1624.98  4817.2 1622.54  4849.3 1621.42
    4888 1620.19  4937.4 1619.58  4944.6 1619.23  4972.9 1616.54  4987.1 1614.24
    4991 1610.21  4993.7 1609.71    4997 1610.21  5001.2 1611.27  5008.1 1614.18
  5015.4 1615.89  5022.3 1616.33  5057.9 1616.17  5086.2 1615.49  5128.6 1616.32
  5158.3 1616.05    5178 1616.07  5220.5 1617.07  5248.8 1618.49  5255.7 1619.56
  5278.6 1619.91  5319.6 1619.98    5362 1621.06  5402.5 1622.74  5452.4 1623.96
#Mann= 7 ,-1 , 0
  4717.4      .1       0  4849.3     .05       0    4991     .04       0
    4997     .05       0  5158.3      .1       0  5278.6     .05       0
  5402.5      .1       0
Bank Sta=4972.9,5015.4
XS Rating Curve= 0 ,0
Exp/Cntr=0.3,0.1

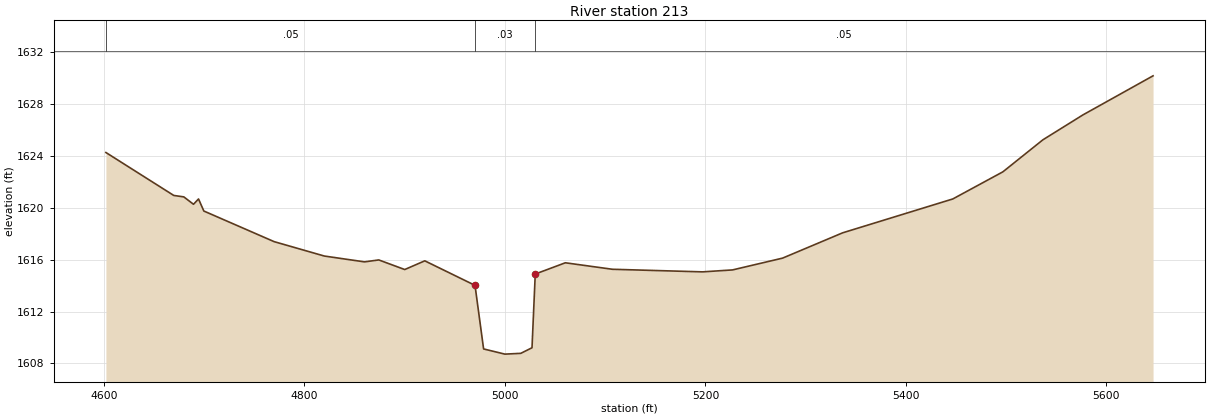
Type RM Length L Ch R = 1 ,213     ,0,0,0
BEGIN DESCRIPTION:
UNT108 IN NNOGR 1.1
END DESCRIPTION:
XS GIS Cut Line= 3
      2805968.59     10074221.32      2805942.66     10073756.74
     2805372.326    10073687.655
#Sta/Elev= 30
    4602 1624.26  4669.7 1620.95  4679.7 1620.84  4689.4 1620.27  4694.4 1620.68
  4699.7 1619.75  4769.8 1617.39  4819.9 1616.28    4860 1615.83  4874.2 1615.98
  4900.1 1615.24  4920.1 1615.91  4970.2 1614.02 4978.76 1609.12    5000 1608.72
 5015.82 1608.78 5027.05 1609.21  5030.3 1614.91  5030.5  1614.9  5060.3 1615.76
 5107.25 1615.26 5197.13 1615.06 5227.09 1615.21 5277.03 1616.12 5336.95 1618.07
 5446.81 1620.68 5496.75 1622.77  5536.7 1625.24 5576.64 1627.16 5646.55 1630.17
#Mann= 3 ,-1 , 0
    4602     .05       0  4970.2     .03       0  5030.5     .05       0
Bank Sta=4970.2,5030.3
XS Rating Curve= 0 ,0
Exp/Cntr=0.3,0.1

Chan Stop Cuts=-1
Use User Specified Reach Order=0
Composite Channel Slope=5