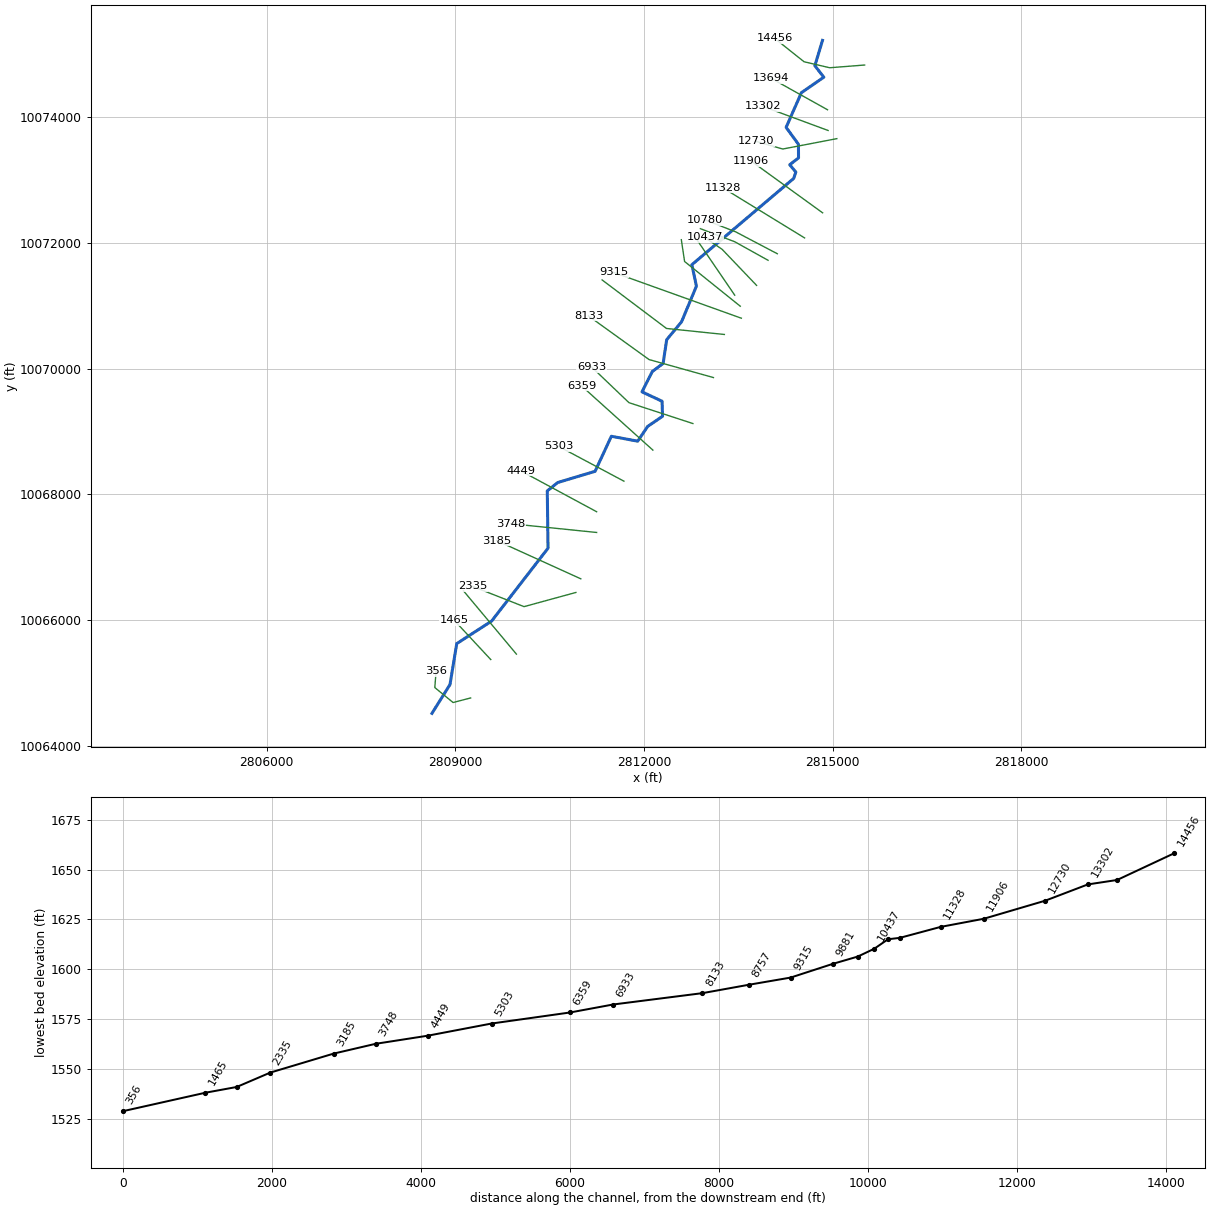
--- UNT110 IN NNOGR.prj (project) ---

Proj Title=UNT110 IN NNOGR Base Level Engineering
Current Plan=p01
Default Exp/Contr=0.3,0.1
English Units
Geom File=g01
Flow File=f01
Plan File=p01
Y Axis Title=Elevation
X Axis Title(PF)=Main Channel Distance
X Axis Title(XS)=Station
BEGIN DESCRIPTION:
UNT110 IN NNOGR
END DESCRIPTION:
DSS Export Rating Curves= 0
DSS Export Rating Curve Sorted= 0
DSS Export Volume Flow Curves= 0
DXF OffsetX= 0
DXF OffsetY= 0
DXF ScaleX= 1
DXF ScaleY= 10

--- UNT110 IN NNOGR.p01 (plan) ---

Plan Title=Multiple Run
Short Identifier=Multiple
Geom File=g01
Flow File=f01
Subcritical Flow
K Sum by GR= 0
Std Step Tol= 0.01
Critical Tol= 0.01
Num of Std Step Trials= 20
Max Error Tol= 0.3
Flow Tol Ratio= 0.001
Split Flow NTrial= 30
Split Flow Tol= 0.02
Split Flow Ratio= 0.02
Log Output Level= 0
Friction Slope Method= 1
Unsteady Friction Slope Method= 2
Unsteady Bridges Friction Slope Method= 1
Parabolic Critical Depth
Global Vel Dist=  1 , 1 , 1
Global Log Level= 0
CheckData=True
Encroach Param= -1, 0, 0, 0
BEGIN DESCRIPTION:
Multiple Run
END DESCRIPTION:

--- UNT110 IN NNOGR.f01 (steady flow) ---

Flow Title=Multiple
Program Version=4.10
Number of Profiles= 7
Profile Names=10-year,25-year,50-year,1pct_min,100-year,1pct_plu,500-year
River Rch & RM=UNT110 IN NNOGR,Reach-1         ,14456
     843    1221    1550    1442    1949    2636    3094
River Rch & RM=UNT110 IN NNOGR,Reach-1         ,12730
    1288    1907    2456    2313    3128    4230    5093
River Rch & RM=UNT110 IN NNOGR,Reach-1         ,8757
    2036    3070    4002    3807    5149    6963    8562
River Rch & RM=UNT110 IN NNOGR,Reach-1         ,1885
    2348    3562    4662    4451    6019    8140   10083
Boundary for River Rch & Prof#=UNT110 IN NNOGR,Reach-1         , 1
Up Type= 0
Dn Type= 3
Dn Slope=0.0099
Boundary for River Rch & Prof#=UNT110 IN NNOGR,Reach-1         , 2
Up Type= 0
Dn Type= 3
Dn Slope=0.0099
Boundary for River Rch & Prof#=UNT110 IN NNOGR,Reach-1         , 3
Up Type= 0
Dn Type= 3
Dn Slope=0.0099
Boundary for River Rch & Prof#=UNT110 IN NNOGR,Reach-1         , 4
Up Type= 0
Dn Type= 3
Dn Slope=0.0099
Boundary for River Rch & Prof#=UNT110 IN NNOGR,Reach-1         , 5
Up Type= 0
Dn Type= 3
Dn Slope=0.0099
Boundary for River Rch & Prof#=UNT110 IN NNOGR,Reach-1         , 6
Up Type= 0
Dn Type= 3
Dn Slope=0.0099
Boundary for River Rch & Prof#=UNT110 IN NNOGR,Reach-1         , 7
Up Type= 0
Dn Type= 3
Dn Slope=0.0099
DSS Import GetInterval= 0
DSS Import GetPeak= 0
DSS Import FillOption= 0

--- UNT110 IN NNOGR.g01 (geometry) ---

Geom Title=Existing Conditions
Program Version=4.10

River Reach=UNT110 IN NNOGR ,Reach-1
Reach XY= 30
       2814839.7     10075226.93      2814718.83     10074823.42
      2814860.78     10074640.78      2814504.78     10074394.91
      2814261.29     10073842.31      2814457.36     10073573.27
      2814458.71     10073356.73      2814318.85     10073247.73
      2814415.38     10073131.05      2814383.11     10073031.07
      2812762.58     10071656.79      2812834.96     10071315.38
      2812598.48     10070748.26      2812361.96     10070462.53
      2812305.17      10070085.1      2812133.16     10069956.73
       2811969.1     10069632.87      2812288.41     10069483.71
      2812296.28     10069244.67      2812059.52     10069082.73
      2811901.37     10068848.06      2811482.21     10068926.32
      2811223.65     10068368.55      2810629.81     10068190.48
      2810463.16     10068056.51      2810475.13     10067145.12
      2809577.56     10065984.62      2809023.37     10065626.45
      2808916.04     10064974.74      2808628.74     10064516.06

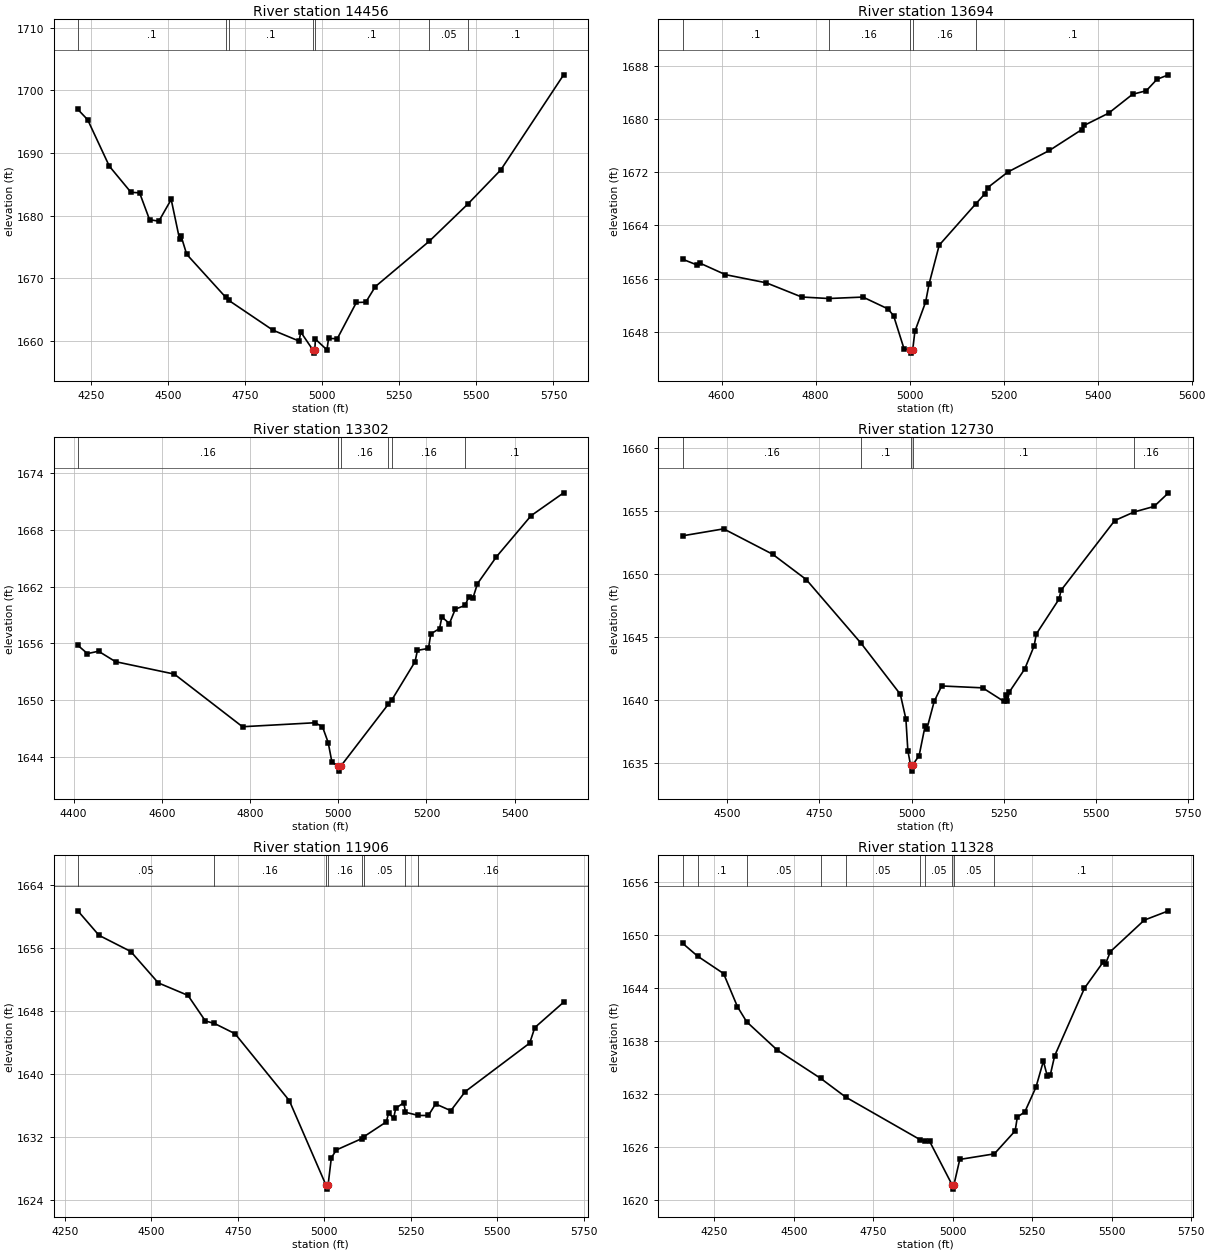
Type RM Length L Ch R = 1 ,14456   ,762,762,762
BEGIN DESCRIPTION:
UNT110 IN NNOGR 30.0
END DESCRIPTION:
XS GIS Cut Line= 4
      2815510.19     10074834.55      2814954.64     10074791.15
      2814546.66     10074886.64      2814078.66     10075259.31
#Sta/Elev= 30
  4208.5 1696.98  4240.3 1695.34  4310.5 1687.93  4380.7 1683.75  4408.7 1683.67
  4440.9 1679.39    4471 1679.14  4511.1 1682.61  4538.1 1676.29  4543.1 1676.78
  4561.3 1673.86  4687.7 1667.01  4698.2 1666.49  4840.9 1661.75  4925.8 1660.01
    4931 1661.46  4970.4 1658.59  4973.2 1658.09  4976.4 1658.59  4978.6 1660.32
  5015.9 1658.61  5021.1 1660.43  5049.4  1660.4  5111.2 1666.17  5141.8 1666.22
  5172.6  1668.7    5348 1675.97  5471.9 1681.85  5579.2 1687.32    5783  1702.5
#Mann= 7 ,-1 , 0
  4208.5      .1       0  4687.7     .05       0  4698.2      .1       0
  4970.4     .07       0  4976.4      .1       0    5348     .05       0
  5471.9      .1       0
Bank Sta=4970.4,4976.4
XS Rating Curve= 0 ,0
Exp/Cntr=0.3,0.1

Type RM Length L Ch R = 1 ,13694   ,392,392,392
BEGIN DESCRIPTION:
UNT110 IN NNOGR 28.0
END DESCRIPTION:
XS GIS Cut Line= 2
       2814919.9     10074122.76      2814017.19      10074626.2
#Sta/Elev= 30
  4517.1 1658.91  4548.6 1658.02  4554.3 1658.31    4608 1656.59  4694.9 1655.36
  4770.3 1653.22  4827.7 1652.99  4900.6 1653.21  4953.8 1651.43  4965.8  1650.4
  4988.2 1645.38  5000.5 1645.26  5003.2 1644.76  5006.5 1645.26  5011.1 1648.04
    5034 1652.47  5041.2 1655.16  5062.9 1661.04  5141.3 1667.31  5159.9 1668.76
  5165.7 1669.69  5209.2 1672.07  5297.3 1675.31  5365.7 1678.43  5371.4 1679.09
  5423.3 1680.93  5474.3 1683.78  5503.4 1684.31  5526.3 1686.04  5550.7 1686.71
#Mann= 5 ,-1 , 0
  4517.1      .1       0  4827.7     .16       0  5000.5     .07       0
  5006.5     .16       0  5141.3      .1       0
Bank Sta=5000.5,5006.5
XS Rating Curve= 0 ,0
Exp/Cntr=0.3,0.1

Type RM Length L Ch R = 1 ,13302   ,572,572,572
BEGIN DESCRIPTION:
UNT110 IN NNOGR 27.0
END DESCRIPTION:
XS GIS Cut Line= 2
      2814928.58      10073792.9      2813895.63     10074174.83
#Sta/Elev= 30
  4409.8  1655.8  4431.6 1654.93  4456.7 1655.18  4495.2 1654.08  4628.5 1652.77
  4783.1 1647.22    4947 1647.64  4964.3 1647.23  4977.4 1645.55  4985.7 1643.51
  4999.5 1643.04  5002.2 1642.54  5005.5 1643.04  5113.9 1649.61  5122.2 1650.09
  5174.3 1654.08  5179.6 1655.27  5204.7 1655.48    5210 1657.01  5229.8 1657.57
  5235.1 1658.79  5252.2  1658.1  5265.5 1659.62  5287.7 1660.01  5295.9 1660.89
  5305.5 1660.78  5315.7  1662.3  5358.8 1665.14  5437.3 1669.47  5511.1 1671.88
#Mann= 6 ,-1 , 0
  4409.8     .16       0  4999.5     .07       0  5005.5     .16       0
  5113.9      .1       0  5122.2     .16       0  5287.7      .1       0
Bank Sta=4999.5,5005.5
XS Rating Curve= 0 ,0
Exp/Cntr=0.3,0.1

Type RM Length L Ch R = 1 ,12730   ,824,824,824
BEGIN DESCRIPTION:
UNT110 IN NNOGR 26.0
END DESCRIPTION:
XS GIS Cut Line= 3
      2815067.52     10073662.69      2814208.12     10073497.75
      2813784.07      10073618.9
#Sta/Elev= 30
  4380.1 1653.06  4491.1 1653.61  4623.5  1651.6  4714.7 1649.59  4863.3 1644.53
  4969.7 1640.48  4984.8 1638.52  4990.1    1636  4997.3 1634.88    5000 1634.38
  5003.3 1634.88  5020.6 1635.61  5036.8 1637.96  5041.9 1637.76  5061.4 1639.91
  5081.7 1641.14  5192.8 1640.99  5249.9 1639.92  5255.2 1640.44  5259.4 1639.92
  5265.2 1640.67  5306.8 1642.49  5332.2 1644.32    5338 1645.26  5399.8 1648.04
    5405 1648.73  5550.6 1654.27  5603.1 1654.95  5657.2 1655.39  5696.2 1656.47
#Mann= 5 ,-1 , 0
  4380.1     .16       0  4863.3      .1       0  4997.3     .07       0
  5003.3      .1       0  5603.1     .16       0
Bank Sta=4997.3,5003.3
XS Rating Curve= 0 ,0
Exp/Cntr=0.3,0.1

Type RM Length L Ch R = 1 ,11906   ,578,578,578
BEGIN DESCRIPTION:
UNT110 IN NNOGR 25.0
END DESCRIPTION:
XS GIS Cut Line= 2
      2814841.82     10072482.11      2813704.66     10073306.76
#Sta/Elev= 30
  4287.6 1660.69  4348.7 1657.58  4440.7 1655.52  4520.3 1651.53  4606.1 1649.94
  4656.4 1646.69  4682.5 1646.38  4742.2 1645.07  4899.1 1636.57  5005.2 1625.82
  5007.9 1625.32  5011.2 1625.82  5020.6  1629.3  5035.2  1630.3  5109.1 1631.75
  5114.2 1631.97  5179.8 1633.87    5186 1634.99  5200.7 1634.33  5206.8 1635.59
  5230.1 1636.31    5235 1635.09  5272.4 1634.68  5301.2 1634.68  5322.1 1636.15
  5366.1 1635.29  5407.9 1637.72  5594.2 1643.88  5608.9 1645.85  5692.3 1649.08
#Mann= 8 ,-1 , 0
  4287.6     .05       0  4682.5     .16       0  5005.2     .07       0
  5011.2     .16       0  5109.1      .1       0  5114.2     .05       0
    5235      .1       0  5272.4     .16       0
Bank Sta=5005.2,5011.2
XS Rating Curve= 0 ,0
Exp/Cntr=0.3,0.1

Type RM Length L Ch R = 1 ,11328   ,548,548,548
BEGIN DESCRIPTION:
UNT110 IN NNOGR 24.0
END DESCRIPTION:
XS GIS Cut Line= 2
       2814555.3     10072082.84      2813253.37     10072881.36
#Sta/Elev= 30
    4151 1649.06  4197.9 1647.61  4279.6 1645.64  4323.3 1641.88  4352.2 1640.18
  4447.8    1637  4584.5 1633.79  4664.1 1631.65  4897.7 1626.84  4913.7 1626.66
  4927.4 1626.65  4997.8 1621.75  5000.6 1621.25  5003.8 1621.75  5022.1 1624.61
  5130.7 1625.24  5196.2 1627.84  5203.1 1629.41  5226.5 1629.98  5261.7 1632.79
    5285 1635.74  5296.9 1634.09  5306.3 1634.11  5320.4 1636.33  5414.2 1643.99
  5472.9 1646.94  5480.4 1646.76  5495.8 1648.13  5602.3 1651.69  5678.3 1652.74
#Mann= 10 ,-1 , 0
    4151     .16       0  4197.9      .1       0  4352.2     .05       0
  4584.5      .1       0  4664.1     .05       0  4897.7      .1       0
  4913.7     .05       0  4997.8    .035       0  5003.8     .05       0
  5130.7      .1       0
Bank Sta=4997.8,5003.8
XS Rating Curve= 0 ,0
Exp/Cntr=0.3,0.1

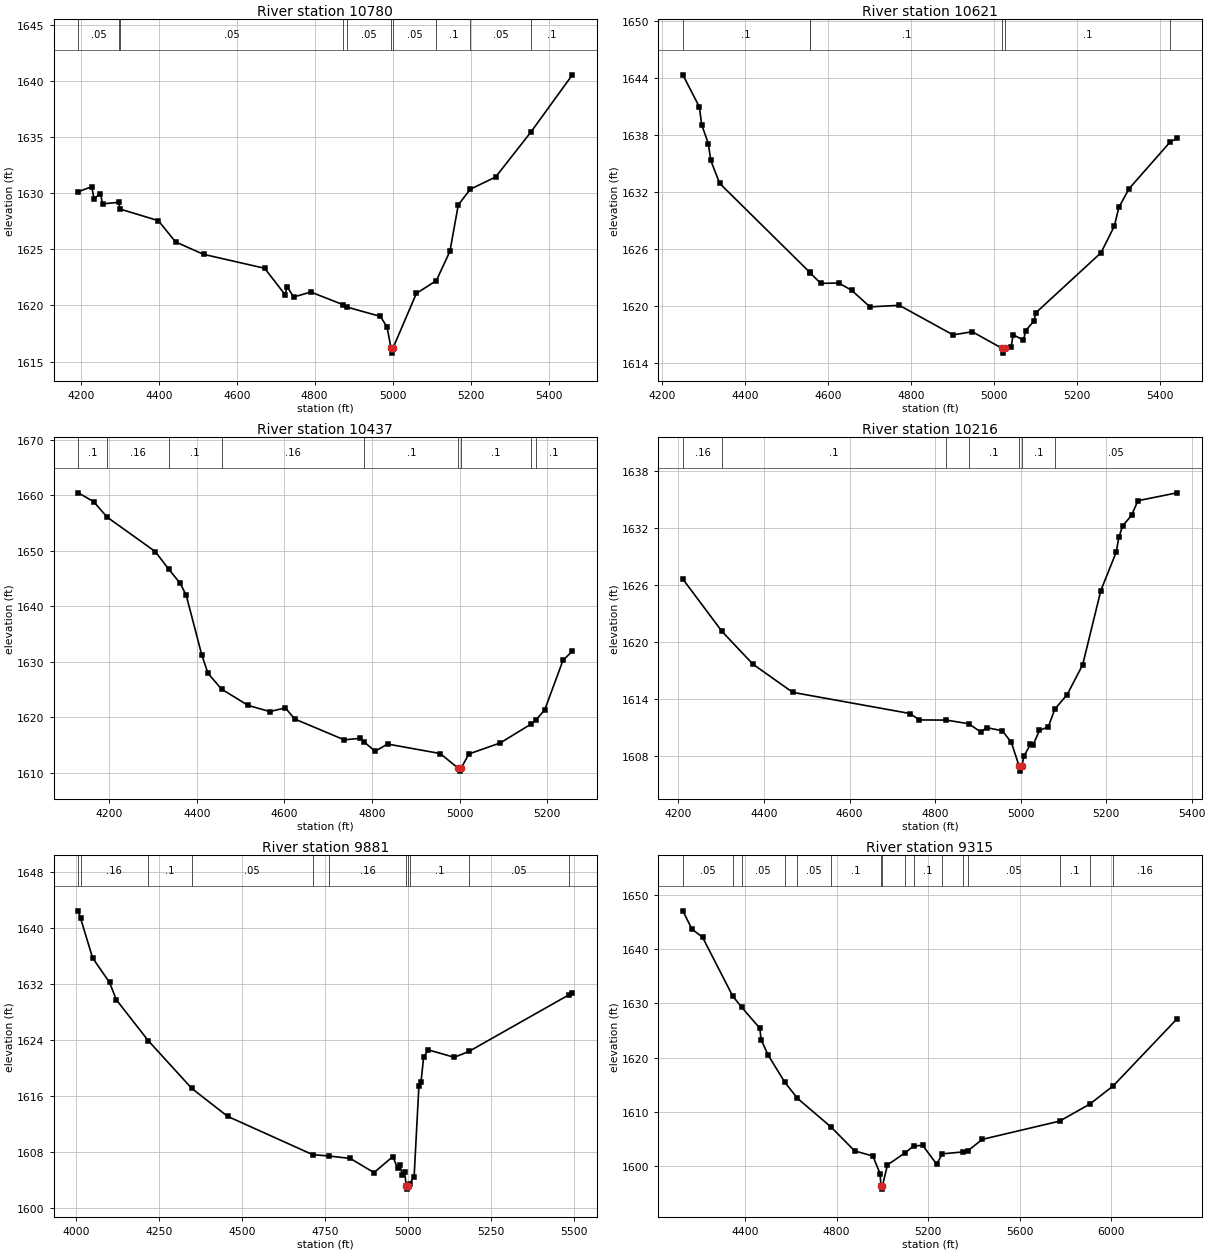
Type RM Length L Ch R = 1 ,10780   ,159,159,159
BEGIN DESCRIPTION:
UNT110 IN NNOGR 23.0
END DESCRIPTION:
XS GIS Cut Line= 3
      2814121.36     10071831.06      2813461.59      10072178.3
      2812976.17       10072369.
#Sta/Elev= 30
  4193.7 1630.13  4228.4 1630.57  4234.1 1629.51  4250.5 1629.96  4256.1 1629.05
  4297.5 1629.18  4301.2 1628.58  4399.1 1627.55  4443.1 1625.66  4514.9 1624.55
  4671.6 1623.31    4724 1620.96  4729.6 1621.66    4746 1620.75  4790.1 1621.19
  4871.7 1620.08  4883.1 1619.85  4968.6 1619.02  4985.6 1618.07  4995.4 1616.25
  4998.2 1615.75  5001.4 1616.25  5060.8 1621.07    5112 1622.21  5146.8 1624.82
  5168.2 1628.95    5199 1630.35  5264.1 1631.44  5354.4 1635.44  5460.8 1640.54
#Mann= 10 ,-1 , 0
  4193.7     .05       0  4297.5      .1       0  4301.2     .05       0
  4871.7      .1       0  4883.1     .05       0  4995.4     .04       0
  5001.4     .05       0    5112      .1       0    5199     .05       0
  5354.4      .1       0
Bank Sta=4995.4,5001.4
XS Rating Curve= 0 ,0
Exp/Cntr=0.3,0.1

Type RM Length L Ch R = 1 ,10621   ,184,184,184
BEGIN DESCRIPTION:
UNT110 IN NNOGR 22.0
END DESCRIPTION:
XS GIS Cut Line= 3
      2813973.78     10071726.89      2813444.23     10072022.05
      2812897.33      10072230.4
#Sta/Elev= 30
  4250.4 1644.33  4290.2 1640.95  4295.9 1639.07  4311.9 1637.09  4317.6 1635.33
  4339.3  1632.9  4555.9 1623.57  4558.2 1623.45  4582.8 1622.38  4626.2 1622.42
  4657.2 1621.66  4701.7 1619.91  4772.5 1620.07  4901.9 1616.96  4948.4 1617.29
  5020.3 1615.54  5023.1 1615.04  5026.3 1615.54  5041.7 1615.64    5047 1616.97
  5071.8 1616.41  5077.1 1617.41  5096.5 1618.39  5101.9  1619.3  5258.8 1625.61
  5290.9 1628.41  5301.8 1630.39  5326.6 1632.36    5426 1637.29  5441.9 1637.63
#Mann= 6 ,-1 , 0
  4250.4      .1       0  4555.9     .16       0  4558.2      .1       0
  5020.3     .07       0  5026.3      .1       0    5426     .05       0
Bank Sta=5020.3,5026.3
XS Rating Curve= 0 ,0
Exp/Cntr=0.3,0.1

Type RM Length L Ch R = 1 ,10437   ,221,221,221
BEGIN DESCRIPTION:
UNT110 IN NNOGR 21.0
END DESCRIPTION:
XS GIS Cut Line= 3
      2813791.45     10071327.61      2813244.58     10071900.53
      2812966.81     10072091.49
#Sta/Elev= 30
  4128.8 1660.42  4163.7 1658.85    4195 1656.03  4304.9 1649.83  4335.1 1646.71
  4361.5 1644.15  4375.6 1641.94  4411.2 1631.18  4425.3 1627.91  4456.2 1625.06
  4517.2 1622.12  4566.6 1621.02  4602.1 1621.68  4623.2 1619.69  4736.4 1615.93
  4771.9 1616.19  4782.3 1615.52  4807.2 1613.87  4835.5 1615.17  4955.8 1613.46
  4997.5 1610.79  5000.2 1610.29  5003.5 1610.79  5021.4 1613.38  5093.1 1615.37
  5162.4 1618.71  5174.6  1619.5  5194.6 1621.31  5236.5 1630.25  5257.9 1631.91
#Mann= 9 ,-1 , 0
  4128.8      .1       0    4195     .16       0  4335.1      .1       0
  4456.2     .16       0  4782.3      .1       0  4997.5     .07       0
  5003.5      .1       0  5162.4     .05       0  5174.6      .1       0
Bank Sta=4997.5,5003.5
XS Rating Curve= 0 ,0
Exp/Cntr=0.3,0.1

Type RM Length L Ch R = 1 ,10216   ,335,335,335
BEGIN DESCRIPTION:
UNT110 IN NNOGR 20.0
END DESCRIPTION:
XS GIS Cut Line= 2
      2813444.21     10071171.39      2812793.33     10072126.01
#Sta/Elev= 30
  4210.3 1626.58  4301.7 1621.08    4374 1617.63  4467.3 1614.66  4741.9 1612.43
  4762.9 1611.76  4826.6 1611.74  4878.5 1611.36  4906.5 1610.51  4921.4 1610.94
  4957.3 1610.62  4978.3  1609.4  4996.8 1606.87  4999.6 1606.37  5002.8 1606.87
  5008.2 1607.99  5023.1 1609.18  5029.1  1609.1  5044.1 1610.65    5065 1611.04
    5080  1612.9  5108.8 1614.41  5145.1 1617.55  5187.7 1625.38  5223.6 1629.42
  5229.8 1630.98  5238.5 1632.16  5259.5  1633.3  5274.4 1634.83  5365.7 1635.66
#Mann= 7 ,-1 , 0
  4210.3     .16       0  4301.7      .1       0  4826.6     .16       0
  4878.5      .1       0  4996.8     .07       0  5002.8      .1       0
    5080     .05       0
Bank Sta=4996.8,5002.8
XS Rating Curve= 0 ,0
Exp/Cntr=0.3,0.1

Type RM Length L Ch R = 1 ,9881    ,566,566,566
BEGIN DESCRIPTION:
Mapping XS 79240332
END DESCRIPTION:
XS GIS Cut Line= 3
      2813532.17       10070996.      2812646.74     10071707.82
      2812594.65     10072055.06
#Sta/Elev= 30
  4006.7 1642.46  4013.5 1641.43  4049.9 1635.74  4100.8 1632.23  4121.6 1629.74
  4217.3 1623.92  4348.5 1617.09    4456 1613.11  4712.4 1607.63  4761.9 1607.44
  4825.6 1607.09  4896.8 1605.07  4953.6 1607.36    4968 1605.69  4974.4 1606.22
  4982.4 1604.69  4988.8 1605.22  4993.8 1603.21  4996.6 1602.71  4999.8 1603.21
  5004.3 1603.49  5017.6 1604.51    5032 1617.46  5038.4 1618.08  5046.4 1621.62
  5060.8 1622.59  5138.5 1621.54  5182.2 1622.37  5484.5 1630.49  5493.9 1630.71
#Mann= 11 ,-1 , 0
  4006.7      .1       0  4013.5     .16       0  4217.3      .1       0
  4348.5     .05       0  4712.4      .1       0  4761.9     .16       0
  4993.8     .07       0  4999.8     .16       0  5004.3      .1       0
  5182.2     .05       0  5484.5      .1       0
Bank Sta=4993.8,4999.8
XS Rating Curve= 0 ,0
Exp/Cntr=0.3,0.1

Type RM Length L Ch R = 1 ,9315    ,558,558,558
BEGIN DESCRIPTION:
UNT110 IN NNOGR 19.0
END DESCRIPTION:
XS GIS Cut Line= 2
      2813549.53     10070805.04      2811518.24     10071534.22
#Sta/Elev= 30
  4128.7 1647.01  4168.1 1643.65  4214.8 1642.15    4346 1631.37  4385.9 1629.26
  4464.9 1625.42  4470.2 1623.34  4501.7 1620.44  4574.3 1615.47    4629 1612.54
  4776.7 1607.22  4879.2 1602.86  4958.6 1601.91  4990.4 1598.65  4993.9 1596.33
  4996.6 1595.83  4999.9 1596.33  5022.3 1600.28  5099.5 1602.51  5136.4 1603.75
    5176 1603.89  5237.4 1600.42    5262 1602.32  5354.1 1602.68  5374.5 1602.91
  5436.6 1604.98  5774.6 1608.34  5906.9 1611.49  6008.5 1614.82  6286.9 1627.14
#Mann= 16 ,-1 , 0
  4128.7     .05       0    4346     .16       0  4385.9     .05       0
  4574.3      .1       0    4629     .05       0  4776.7      .1       0
  4993.9     .07       0  4999.9      .1       0  5099.5     .16       0
  5136.4      .1       0    5262     .16       0  5354.1      .1       0
  5374.5     .05       0  5774.6      .1       0  5906.9     .05       0
  6008.5     .16       0
Bank Sta=4993.9,4999.9
XS Rating Curve= 0 ,0
Exp/Cntr=0.3,0.1

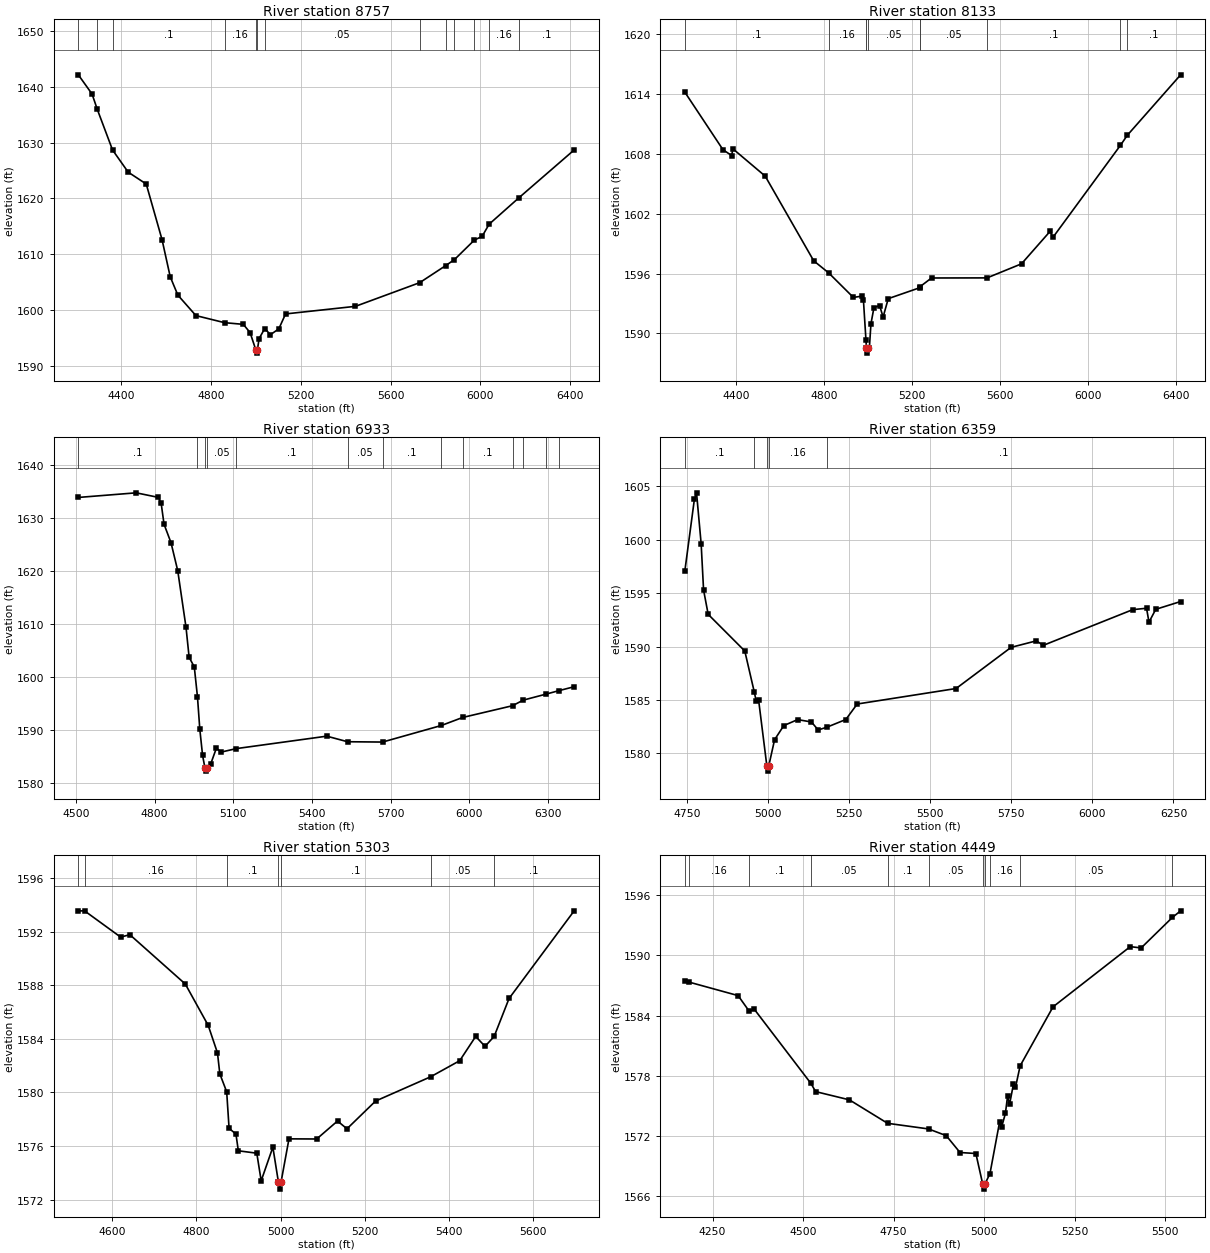
Type RM Length L Ch R = 1 ,8757    ,624,624,624
BEGIN DESCRIPTION:
UNT110 IN NNOGR 18.0
END DESCRIPTION:
XS GIS Cut Line= 3
      2813279.27     10070546.36      2812359.16     10070641.85
      2811334.88     10071414.39
#Sta/Elev= 30
  4209.4 1642.15  4270.5 1638.71  4293.7 1635.97  4361.7 1628.68  4431.4  1624.7
  4511.8 1622.57  4582.2 1612.59  4618.6 1605.94  4652.6 1602.65    4733 1598.98
  4860.6 1597.71  4944.1 1597.41  4974.3 1595.93  5000.4 1592.75  5003.2 1592.25
  5006.4 1592.75  5014.5 1594.87  5039.6 1596.66  5064.8 1595.56  5102.1  1596.6
  5132.3 1599.28  5443.5 1600.64  5729.8 1604.89  5845.2 1607.94  5884.3 1609.02
    5973 1612.52  6007.6 1613.19  6038.8 1615.37  6170.4 1620.07  6417.4 1628.68
#Mann= 13 ,-1 , 0
  4209.4      .1       0  4293.7     .05       0  4361.7      .1       0
  4860.6     .16       0  5000.4     .07       0  5006.4     .16       0
  5039.6     .05       0  5729.8      .1       0  5845.2     .16       0
  5884.3      .1       0    5973     .05       0  6038.8     .16       0
  6170.4      .1       0
Bank Sta=5000.4,5006.4
XS Rating Curve= 0 ,0
Exp/Cntr=0.3,0.1

Type RM Length L Ch R = 1 ,8133    ,1200,1200,1200
BEGIN DESCRIPTION:
UNT110 IN NNOGR 16.0
END DESCRIPTION:
XS GIS Cut Line= 3
      2813105.64     10069860.61      2812081.38     10070147.05
      2811117.82     10070841.51
#Sta/Elev= 30
  4168.5 1614.19    4342 1608.41  4381.4 1607.83  4386.6 1608.51  4533.5 1605.77
  4753.9 1597.28  4821.8 1596.07    4934 1593.61  4974.3 1593.75  4979.5 1593.37
    4991 1589.36  4993.3 1588.53    4996 1588.03  4999.3 1588.53  5006.6 1588.56
  5013.7 1590.97  5027.4  1592.6    5053 1592.79  5068.9 1591.65  5092.3 1593.49
  5234.7 1594.58  5236.7 1594.69  5288.7 1595.56  5540.8 1595.57  5697.3 1596.98
  5827.3 1600.24  5839.7 1599.62  6146.7 1608.86  6177.6 1609.86  6419.8 1615.92
#Mann= 10 ,-1 , 0
  4168.5      .1       0  4821.8     .16       0    4991     .05       0
  4993.3    .035       0  4999.3     .05       0  5234.7      .1       0
  5236.7     .05       0  5540.8      .1       0  6146.7     .05       0
  6177.6      .1       0
Bank Sta=4993.3,4999.3
XS Rating Curve= 0 ,0
Exp/Cntr=0.3,0.1

Type RM Length L Ch R = 1 ,6933    ,574,574,574
BEGIN DESCRIPTION:
UNT110 IN NNOGR 14.0
END DESCRIPTION:
XS GIS Cut Line= 3
      2812778.61     10069128.79      2811761.94       10069461.
      2811169.14     10070028.03
#Sta/Elev= 30
  4509.3 1633.92  4729.8 1634.79  4814.5 1633.93  4825.1 1632.78    4836 1628.87
  4862.6 1625.38  4888.2 1620.11  4919.7 1609.46  4931.6 1603.79  4951.3 1601.97
  4963.4 1596.34  4972.3 1590.23  4982.9 1585.29  4992.3 1582.83  4995.1 1582.33
  4998.3 1582.83  5014.4 1583.76  5035.5 1586.66  5053.8 1585.92  5111.9 1586.58
  5456.3 1588.92  5535.5 1587.87  5668.9 1587.81  5893.4 1590.94  5973.9 1592.44
  6164.3 1594.66  6204.9 1595.71  6290.1 1596.82  6341.1  1597.5  6399.2 1598.24
#Mann= 13 ,-1 , 0
  4509.3      .1       0  4963.4     .05       0  4992.3    .035       0
  4998.3     .05       0  5111.9      .1       0  5535.5     .05       0
  5668.9      .1       0  5893.4     .05       0  5973.9      .1       0
  6164.3     .05       0  6204.9      .1       0  6290.1     .05       0
  6341.1      .1       0
Bank Sta=4992.3,4998.3
XS Rating Curve= 0 ,0
Exp/Cntr=0.3,0.1

Type RM Length L Ch R = 1 ,6359    ,1056,1056,1056
BEGIN DESCRIPTION:
UNT110 IN NNOGR 13.0
END DESCRIPTION:
XS GIS Cut Line= 2
      2812142.15     10068706.08      2811005.93     10069729.54
#Sta/Elev= 30
  4742.9 1597.05  4772.4 1603.77  4779.1 1604.39  4793.3 1599.63  4800.8  1595.3
    4815 1593.02  4927.9 1589.59    4957 1585.78  4963.2  1584.9  4970.5 1585.01
  4995.9 1578.85  4998.6 1578.35  5001.9 1578.85  5019.8 1581.29  5048.2 1582.61
  5090.8 1583.17  5133.4 1582.95  5154.3  1582.2  5181.9 1582.47  5239.5 1583.18
  5274.6 1584.63  5579.6 1586.08  5749.2 1589.93    5827 1590.54  5848.6 1590.12
  6124.4 1593.46    6167 1593.59  6174.5 1592.29  6195.4 1593.49  6272.1 1594.22
#Mann= 5 ,-1 , 0
  4742.9      .1       0    4957     .16       0  4995.9     .07       0
  5001.9     .16       0  5181.9      .1       0
Bank Sta=4995.9,5001.9
XS Rating Curve= 0 ,0
Exp/Cntr=0.3,0.1

Type RM Length L Ch R = 1 ,5303    ,854,854,854
BEGIN DESCRIPTION:
UNT110 IN NNOGR 11.0
END DESCRIPTION:
XS GIS Cut Line= 2
      2811682.04     10068211.31      2810641.92     10068766.04
#Sta/Elev= 30
  4519.3 1593.54    4534 1593.55  4619.9 1591.59  4641.8 1591.77  4773.6 1588.09
  4828.1    1585  4850.1 1582.95  4855.7 1581.39    4872 1580.05  4877.7 1577.32
    4894  1576.9  4899.7 1575.65  4943.6 1575.47    4954 1573.41  4981.8 1575.92
  4995.1 1573.29  4997.9 1572.79  5001.1 1573.29  5020.1 1576.54    5086 1576.53
  5135.5 1577.87    5158 1577.29    5226 1579.36  5356.9 1581.17    5426 1582.37
    5464 1584.18  5486.2 1583.44  5507.9 1584.18  5543.3 1587.01  5698.1 1593.55
#Mann= 7 ,-1 , 0
  4519.3      .1       0    4534     .16       0    4872      .1       0
  4995.1     .07       0  5001.1      .1       0  5356.9     .05       0
  5507.9      .1       0
Bank Sta=4995.1,5001.1
XS Rating Curve= 0 ,0
Exp/Cntr=0.3,0.1

Type RM Length L Ch R = 1 ,4449    ,701,701,701
BEGIN DESCRIPTION:
UNT110 IN NNOGR 9.0
END DESCRIPTION:
XS GIS Cut Line= 2
      2811248.06     10067725.17      2810042.46     10068375.68
#Sta/Elev= 30
  4173.3 1587.45  4184.5 1587.34  4320.6 1585.99  4350.9 1584.45  4365.3 1584.63
  4521.7 1577.24  4534.8 1576.42    4628  1575.6  4733.6 1573.26  4846.7  1572.7
  4895.6 1572.03  4933.7 1570.35  4977.5 1570.25  4996.4  1567.2  4999.1  1566.7
  5002.4  1567.2  5016.4 1568.24  5043.2 1573.43  5048.8 1572.91  5059.1 1574.25
    5065 1575.95  5070.7 1575.18  5081.3 1577.16  5086.9 1576.83  5099.8 1578.99
  5190.7 1584.87    5404 1590.87  5434.1 1590.74  5520.4 1593.78  5543.2 1594.44
#Mann= 11 ,-1 , 0
  4173.3      .1       0  4184.5     .16       0  4350.9      .1       0
  4521.7     .05       0  4733.6      .1       0  4846.7     .05       0
  4996.4     .04       0  5002.4     .05       0  5016.4     .16       0
  5099.8     .05       0  5520.4     .16       0
Bank Sta=4996.4,5002.4
XS Rating Curve= 0 ,0
Exp/Cntr=0.3,0.1

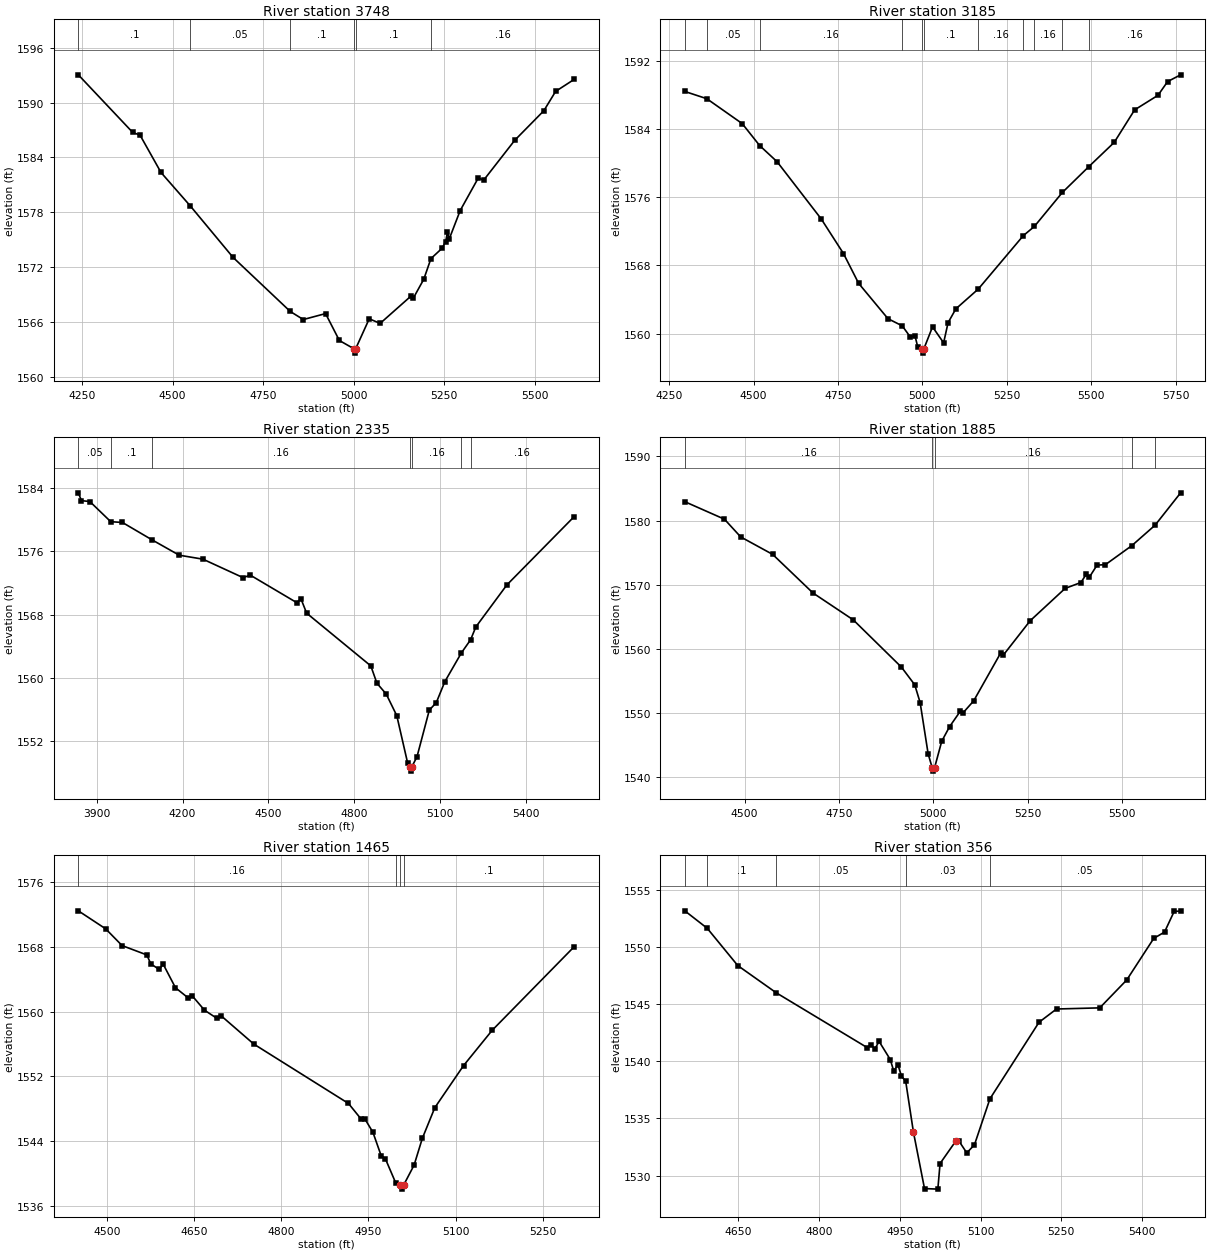
Type RM Length L Ch R = 1 ,3748    ,563,563,563
BEGIN DESCRIPTION:
UNT110 IN NNOGR 7.0
END DESCRIPTION:
XS GIS Cut Line= 2
      2811248.07     10067395.32      2809885.22     10067534.21
#Sta/Elev= 30
  4239.5 1593.03  4389.9 1586.73    4410 1586.44  4467.9 1582.36  4548.7 1578.71
    4667 1573.08  4825.1 1567.17  4861.1 1566.29  4922.6 1566.94  4960.7    1564
    5000 1563.12  5002.8 1562.62    5006 1563.12  5043.2 1566.37  5073.4 1565.87
  5159.9  1568.9  5164.9 1568.62    5194  1570.7  5213.7 1572.95  5244.3 1574.07
  5254.3  1574.8  5259.4 1575.84  5264.5 1575.12  5294.5  1578.2  5344.8 1581.78
    5359  1581.5  5445.3 1585.88  5525.7 1589.11  5558.2 1591.22  5609.4 1592.53
#Mann= 6 ,-1 , 0
  4239.5      .1       0  4548.7     .05       0  4825.1      .1       0
    5000     .07       0    5006      .1       0  5213.7     .16       0
Bank Sta=5000,5006
XS Rating Curve= 0 ,0
Exp/Cntr=0.3,0.1

Type RM Length L Ch R = 1 ,3185    ,850,850,850
BEGIN DESCRIPTION:
UNT110 IN NNOGR 6.0
END DESCRIPTION:
XS GIS Cut Line= 2
      2810996.27     10066657.49      2809659.49     10067265.12
#Sta/Elev= 30
  4296.4  1588.4  4361.5 1587.55  4466.4 1584.63  4518.2 1582.05  4569.7 1580.16
  4700.4 1573.45  4766.3 1569.39  4811.3 1565.89  4898.1 1561.75  4940.3 1560.91
    4964 1559.62  4978.3 1559.71    4986 1558.48  4998.4 1558.21  5001.1 1557.71
  5004.4 1558.21    5030 1560.79  5062.9 1558.92  5076.1 1561.28  5099.1  1562.9
  5165.4 1565.22  5298.7 1571.48  5331.7 1572.57  5414.5 1576.55  5493.1 1579.59
  5568.2 1582.43  5628.6 1586.24  5697.8 1587.95  5726.3 1589.56  5764.8 1590.35
#Mann= 11 ,-1 , 0
  4296.4      .1       0  4361.5     .05       0  4518.2     .16       0
  4940.3      .1       0  4998.4     .07       0  5004.4      .1       0
  5165.4     .16       0  5298.7      .1       0  5331.7     .16       0
  5414.5      .1       0  5493.1     .16       0
Bank Sta=4998.4,5004.4
XS Rating Curve= 0 ,0
Exp/Cntr=0.3,0.1

Type RM Length L Ch R = 1 ,2335    ,450,450,450
BEGIN DESCRIPTION:
UNT110 IN NNOGR 4.0
END DESCRIPTION:
XS GIS Cut Line= 3
       2810918.2     10066440.46      2810093.53     10066214.76
      2809277.56     10066535.94
#Sta/Elev= 30
    3836 1583.39  3846.9  1582.4  3876.2 1582.29  3949.2 1579.74  3990.1 1579.64
  4093.1 1577.45  4188.5  1575.5  4271.2    1575    4411 1572.67  4437.1 1572.97
    4599  1569.5  4613.3 1570.01  4633.5 1568.17  4857.6  1561.5  4879.1  1559.3
  4911.4 1557.94  4948.3 1555.21  4986.6 1549.16  4994.1 1548.69  4996.8 1548.19
  5000.1 1548.69  5018.8 1549.99    5062 1555.91  5086.4 1556.86  5116.2 1559.51
  5173.9 1563.14  5206.1  1564.8  5224.5 1566.43  5332.8 1571.74  5567.9 1580.38
#Mann= 7 ,-1 , 0
    3836     .05       0  3949.2      .1       0  4093.1     .16       0
  4994.1     .07       0  5000.1     .16       0  5173.9      .1       0
  5206.1     .16       0
Bank Sta=4994.1,5000.1
XS Rating Curve= 0 ,0
Exp/Cntr=0.3,0.1

Type RM Length L Ch R = 1 ,1885    ,420,420,420
BEGIN DESCRIPTION:
UNT110 IN NNOGR 3.0
END DESCRIPTION:
XS GIS Cut Line= 2
      2809972.01     10065459.55        2809130.     10066466.49
#Sta/Elev= 30
  4341.8 1582.95  4446.8 1580.22  4489.8 1577.46  4574.4 1574.74  4681.1 1568.73
  4787.8 1564.54  4915.3 1557.18  4950.5 1554.43  4964.8 1551.66    4986 1543.67
  4996.9 1541.48  4999.7 1540.98  5002.9 1541.48    5022 1545.64  5042.8 1547.91
  5071.5 1550.34    5078 1550.03  5106.6 1551.93  5178.2  1559.4  5184.7 1559.03
  5256.2 1564.41  5348.6 1569.44  5390.3 1570.36  5404.6 1571.64  5412.4 1571.16
  5433.2 1573.07  5455.3 1573.14  5525.3 1576.11  5586.8 1579.29  5654.4 1584.33
#Mann= 5 ,-1 , 0
  4341.8     .16       0  4996.9     .07       0  5002.9     .16       0
  5525.3      .1       0  5586.8     .16       0
Bank Sta=4996.9,5002.9
XS Rating Curve= 0 ,0
Exp/Cntr=0.3,0.1

Type RM Length L Ch R = 1 ,1465    ,1109,1109,1109
BEGIN DESCRIPTION:
UNT110 IN NNOGR 2.0
END DESCRIPTION:
XS GIS Cut Line= 2
      2809563.99     10065372.78      2808982.97     10065997.16
#Sta/Elev= 30
  4451.1 1572.44  4498.1 1570.22  4526.4 1568.15  4568.9    1567  4575.7  1565.9
  4589.9 1565.22  4597.2 1565.84  4618.2 1562.95  4639.8 1561.71  4646.6 1561.99
  4668.1 1560.18  4689.1 1559.19  4696.4 1559.51  4752.9    1556  4915.8 1548.67
  4936.8 1546.81  4944.1 1546.75  4957.8 1545.12    4972 1542.23  4979.3 1541.84
  4997.1 1538.86  5004.7  1538.6  5007.4  1538.1  5010.7  1538.6  5028.7 1541.07
  5042.8 1544.36  5064.3 1548.15  5113.7 1553.34    5163  1557.7    5304 1568.01
#Mann= 4 ,-1 , 0
  4451.1     .16       0  4997.1      .1       0  5004.7     .07       0
  5010.7      .1       0
Bank Sta=5004.7,5010.7
XS Rating Curve= 0 ,0
Exp/Cntr=0.3,0.1

Type RM Length L Ch R = 1 ,356     ,0,0,0
BEGIN DESCRIPTION:
UNT110 IN NNOGR 1.0
END DESCRIPTION:
XS GIS Cut Line= 4
      2809243.64     10064761.67      2808964.98     10064688.75
      2808674.61     10064927.03      2808694.14     10065183.53
#Sta/Elev= 30
  4550.6 1553.17  4592.3 1551.64    4649 1548.38  4720.4    1546  4889.1 1541.21
    4897 1541.46  4903.5 1541.07  4911.4 1541.75  4932.2 1540.16  4938.6 1539.16
  4946.5 1539.69    4953 1538.71  4960.9 1538.25  4975.2 1533.82  4995.8 1528.87
 5020.57 1528.82  5024.7 1531.06  5053.4 1532.99  5059.9 1533.02  5074.3 1531.99
  5088.6  1532.7  5117.3 1536.72  5208.5 1543.42    5241 1544.58  5321.3 1544.68
  5371.4 1547.12  5421.6 1550.76  5441.6 1551.31  5459.6 1553.13  5471.5 1553.14
#Mann= 5 ,-1 , 0
  4550.6     .16       0  4592.3      .1       0  4720.4     .05       0
  4960.9     .03       0  5117.3     .05       0
Bank Sta=4975.2,5053.4
XS Rating Curve= 0 ,0
Exp/Cntr=0.3,0.1

Chan Stop Cuts=-1
Use User Specified Reach Order=0
Composite Channel Slope=5