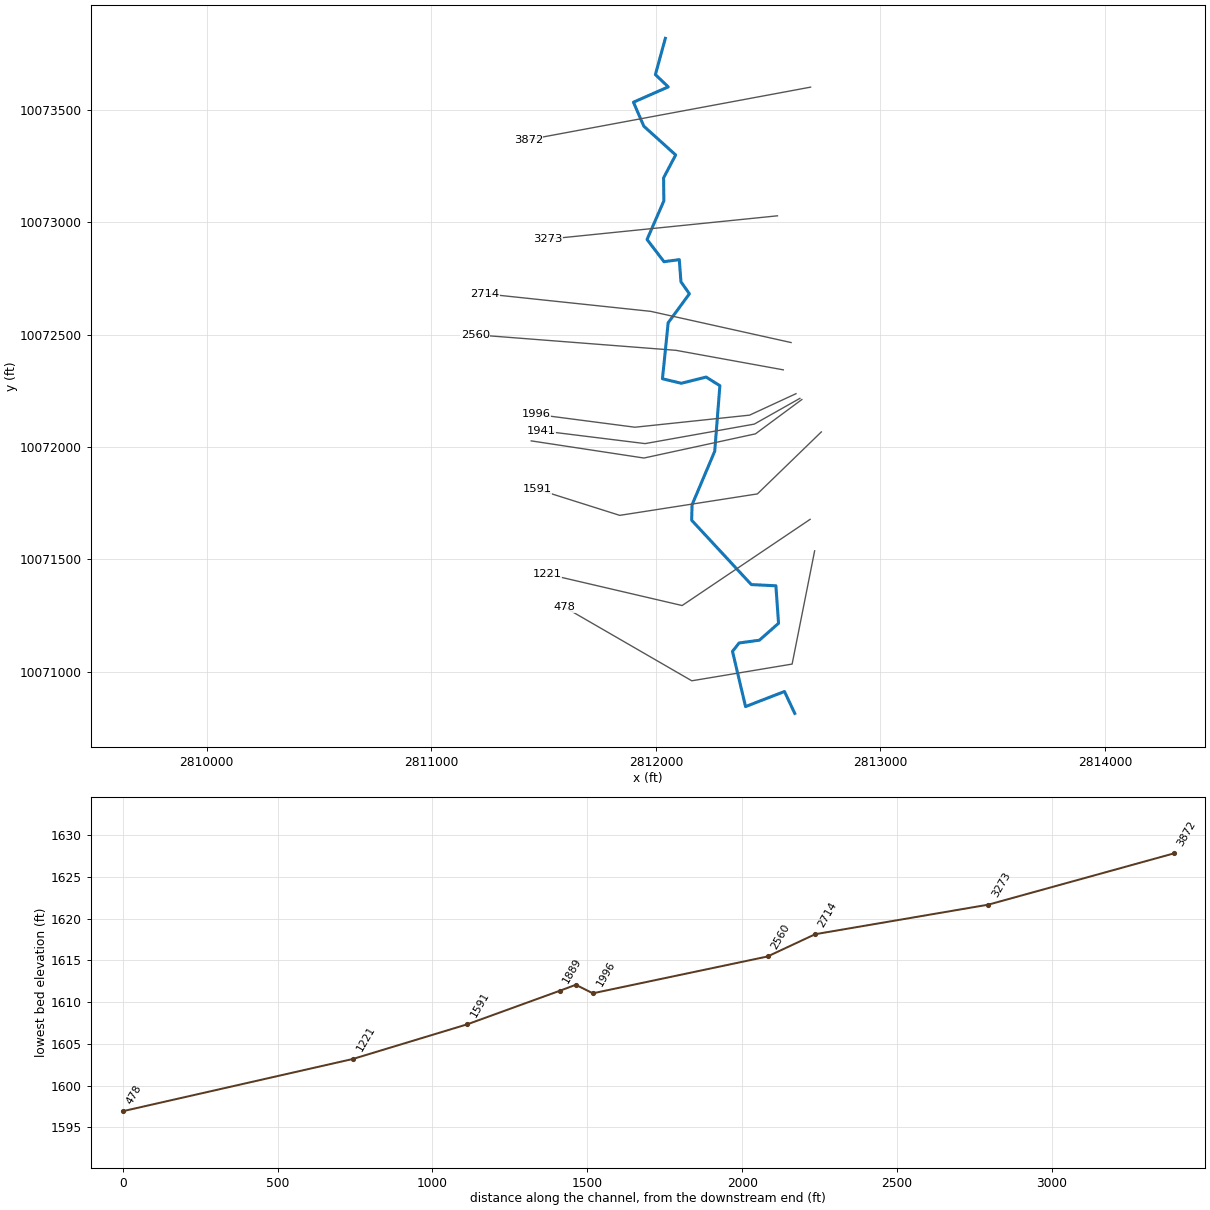
--- UNT111 IN NNOGR.prj (project) ---

Proj Title=UNT111 IN NNOGR Base Level Engineering
Current Plan=p01
Default Exp/Contr=0.3,0.1
English Units
Geom File=g01
Flow File=f01
Plan File=p01
Y Axis Title=Elevation
X Axis Title(PF)=Main Channel Distance
X Axis Title(XS)=Station
BEGIN DESCRIPTION:
UNT111 IN NNOGR
END DESCRIPTION:
DSS Export Rating Curves= 0
DSS Export Rating Curve Sorted= 0
DSS Export Volume Flow Curves= 0
DXF OffsetX= 0
DXF OffsetY= 0
DXF ScaleX= 1
DXF ScaleY= 10

--- UNT111 IN NNOGR.p01 (plan) ---

Plan Title=Multiple Run
Short Identifier=Multiple
Geom File=g01
Flow File=f01
Subcritical Flow
K Sum by GR= 0
Std Step Tol= 0.01
Critical Tol= 0.01
Num of Std Step Trials= 20
Max Error Tol= 0.3
Flow Tol Ratio= 0.001
Split Flow NTrial= 30
Split Flow Tol= 0.02
Split Flow Ratio= 0.02
Log Output Level= 0
Friction Slope Method= 1
Unsteady Friction Slope Method= 2
Unsteady Bridges Friction Slope Method= 1
Parabolic Critical Depth
Global Vel Dist=  1 , 1 , 1
Global Log Level= 0
CheckData=True
Encroach Param= -1, 0, 0, 0
BEGIN DESCRIPTION:
Multiple Run
END DESCRIPTION:

--- UNT111 IN NNOGR.f01 (steady flow) ---

Flow Title=Multiple
Program Version=4.10
Number of Profiles= 7
Profile Names=10-year,25-year,50-year,1pct_min,100-year,1pct_plu,500-year
River Rch & RM=UNT111 IN NNOGR,Reach-1         ,3872
     854    1235    1565    1452    1964    2656    3104
Boundary for River Rch & Prof#=UNT111 IN NNOGR,Reach-1         , 1
Up Type= 0
Dn Type= 3
Dn Slope=0.0099
Boundary for River Rch & Prof#=UNT111 IN NNOGR,Reach-1         , 2
Up Type= 0
Dn Type= 3
Dn Slope=0.0099
Boundary for River Rch & Prof#=UNT111 IN NNOGR,Reach-1         , 3
Up Type= 0
Dn Type= 3
Dn Slope=0.0099
Boundary for River Rch & Prof#=UNT111 IN NNOGR,Reach-1         , 4
Up Type= 0
Dn Type= 3
Dn Slope=0.0099
Boundary for River Rch & Prof#=UNT111 IN NNOGR,Reach-1         , 5
Up Type= 0
Dn Type= 3
Dn Slope=0.0099
Boundary for River Rch & Prof#=UNT111 IN NNOGR,Reach-1         , 6
Up Type= 0
Dn Type= 3
Dn Slope=0.0099
Boundary for River Rch & Prof#=UNT111 IN NNOGR,Reach-1         , 7
Up Type= 0
Dn Type= 3
Dn Slope=0.0099
DSS Import GetInterval= 0
DSS Import GetPeak= 0
DSS Import FillOption= 0

--- UNT111 IN NNOGR.g01 (geometry) ---

Geom Title=Existing Conditions
Program Version=4.10

River Reach=UNT111 IN NNOGR ,Reach-1
Reach XY= 30
      2812042.33     10073819.18      2811997.99     10073657.69
      2812055.28       10073603.      2811900.33     10073534.86
      2811946.54     10073427.95      2812088.29     10073299.85
      2812034.58      10073198.2      2812035.54     10073094.98
      2811960.81     10072923.39       2812036.4     10072824.76
      2812104.37     10072833.88      2812111.81     10072735.01
      2812149.42     10072681.79      2812054.89     10072552.89
      2812029.45     10072303.49      2812113.29     10072283.48
      2812223.93     10072310.99      2812285.12     10072272.65
      2812262.18     10071980.82       2812161.3     10071742.41
      2812159.44     10071673.69      2812425.06     10071387.15
      2812534.54     10071381.77      2812546.26     10071214.75
        2812461.     10071139.49      2812370.72     10071127.17
      2812341.27     10071089.99       2812399.4       10070844.
      2812572.66     10070911.09      2812618.47     10070813.73

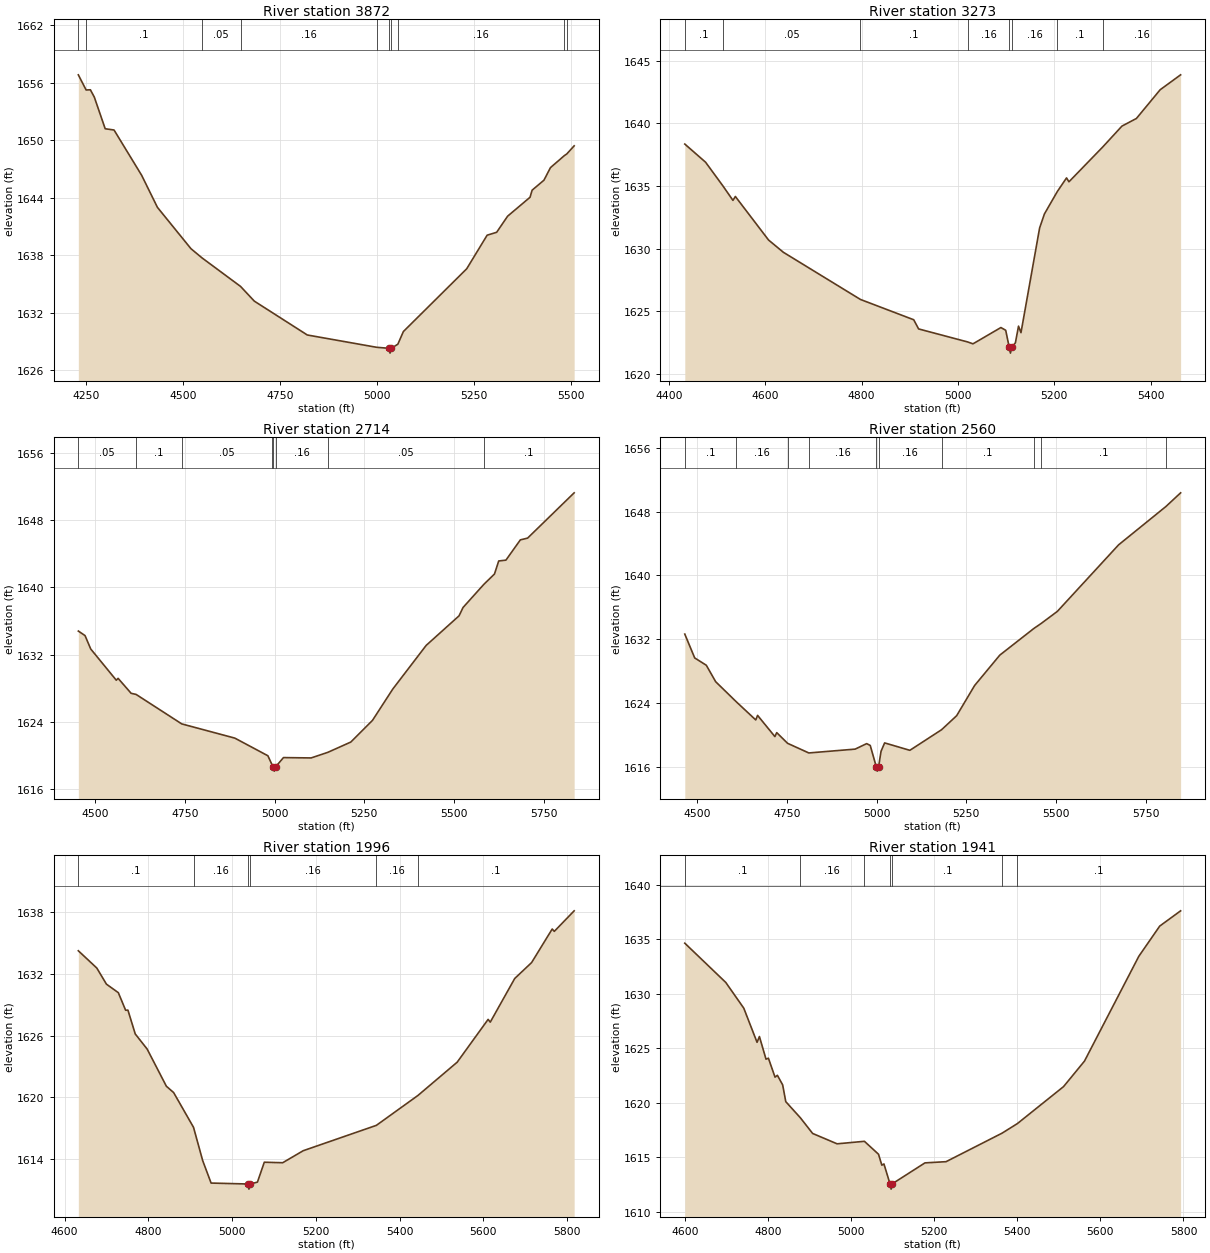
Type RM Length L Ch R = 1 ,3872    ,599,599,599
BEGIN DESCRIPTION:
UNT111 IN NNOGR 5.0
END DESCRIPTION:
XS GIS Cut Line= 2
      2812689.01     10073601.91      2811431.91     10073367.83
#Sta/Elev= 30
  4230.1 1656.81  4250.2 1655.23  4261.2 1655.25  4271.3 1654.49  4299.4 1651.19
  4322.2 1651.06  4393.4 1646.34  4434.1    1643  4520.6 1638.69  4548.9 1637.74
  4648.5 1634.76  4683.9 1633.23  4820.6  1629.7  4999.1 1628.42  5031.2 1628.31
    5034 1627.81  5037.2 1628.31  5054.1 1628.74  5068.4 1630.06  5231.7  1636.6
  5284.4  1640.1  5308.9  1640.4  5337.2 1642.08    5395 1644.05  5400.4 1644.79
  5430.9 1645.83  5447.7 1647.14  5483.8  1648.4  5489.9 1648.57  5508.8 1649.41
#Mann= 10 ,-1 , 0
  4230.1     .05       0  4250.2      .1       0  4548.9     .05       0
  4648.5     .16       0  4999.1      .1       0  5031.2     .07       0
  5037.2      .1       0  5054.1     .16       0  5483.8      .1       0
  5489.9     .16       0
Bank Sta=5031.2,5037.2
XS Rating Curve= 0 ,0
Exp/Cntr=0.3,0.1

Type RM Length L Ch R = 1 ,3273    ,559,559,559
BEGIN DESCRIPTION:
UNT111 IN NNOGR 4.0
END DESCRIPTION:
XS GIS Cut Line= 2
      2812541.46       10073029.      2811517.14     10072924.83
#Sta/Elev= 30
  4432.9 1638.34  4476.1 1636.89  4512.1    1635  4532.9 1633.85  4537.9 1634.16
  4606.8 1630.69  4637.6 1629.71  4797.6 1625.95  4908.3 1624.33  4918.4  1623.6
  5020.4 1622.56  5031.3 1622.41  5089.3 1623.71  5099.3 1623.49  5106.4 1622.17
  5109.1 1621.67  5112.4 1622.17  5119.4 1622.49  5125.9 1623.82    5131  1623.3
  5169.7 1631.65  5179.7 1632.77  5206.7 1634.57  5225.6 1635.64  5230.6 1635.33
  5301.1 1638.12  5340.6 1639.77  5370.7 1640.38    5420 1642.67  5462.5 1643.86
#Mann= 8 ,-1 , 0
  4432.9      .1       0  4512.1     .05       0  4797.6      .1       0
  5020.4     .16       0  5106.4     .07       0  5112.4     .16       0
  5206.7      .1       0  5301.1     .16       0
Bank Sta=5106.4,5112.4
XS Rating Curve= 0 ,0
Exp/Cntr=0.3,0.1

Type RM Length L Ch R = 1 ,2714    ,154,154,154
BEGIN DESCRIPTION:
Mapping XS 5f69b755
END DESCRIPTION:
XS GIS Cut Line= 3
      2812602.18     10072464.77      2811977.21     10072603.65
      2811239.35     10072681.78
#Sta/Elev= 30
  4452.9  1634.8  4471.6 1634.26  4487.4 1632.67  4558.7 1628.95  4563.8 1629.17
  4600.1 1627.39  4613.9 1627.26  4741.2 1623.75  4889.1 1622.06  4981.3 1619.96
  4993.7 1618.82  4996.6 1618.63  4999.4 1618.13  5002.6 1618.63  5024.8 1619.74
  5101.9  1619.7  5148.1 1620.36  5212.5 1621.59  5272.9 1624.17  5329.7 1627.91
  5422.5 1633.09  5514.2 1636.61  5525.3  1637.6  5583.4 1640.36    5613 1641.59
  5624.8 1643.14  5644.9 1643.24  5685.1 1645.65  5705.3 1645.86  5835.1 1651.25
#Mann= 8 ,-1 , 0
  4452.9     .05       0  4613.9      .1       0  4741.2     .05       0
  4993.7     .16       0  4996.6     .07       0  5002.6     .16       0
  5148.1     .05       0  5583.4      .1       0
Bank Sta=4996.6,5002.6
XS Rating Curve= 0 ,0
Exp/Cntr=0.3,0.1

Type RM Length L Ch R = 1 ,2560    ,564,564,564
BEGIN DESCRIPTION:
Mapping XS 34550143
END DESCRIPTION:
XS GIS Cut Line= 3
      2812567.47     10072343.24      2812090.06     10072430.04
      2811195.99     10072499.48
#Sta/Elev= 30
  4465.3 1632.65  4492.9 1629.66  4525.3 1628.74  4551.3 1626.68  4608.8 1624.16
  4663.1 1621.88  4668.2 1622.45  4716.5 1619.79  4721.5 1620.29  4751.8 1618.95
    4811 1617.74  4940.1 1618.22  4972.2 1618.91  4982.2 1618.68  4999.3 1615.96
    5002 1615.46  5005.3 1615.96  5012.3 1617.95  5022.3    1619  5092.6 1618.07
  5180.9 1620.65    5223 1622.41  5273.1  1626.2  5343.3 1630.01  5438.4 1633.36
  5458.2 1633.97  5503.8  1635.5  5674.3 1643.84  5806.5 1648.66  5847.3 1650.37
#Mann= 10 ,-1 , 0
  4465.3      .1       0  4608.8     .16       0  4751.8      .1       0
    4811     .16       0  4999.3     .07       0  5005.3     .16       0
  5180.9      .1       0  5438.4     .16       0  5458.2      .1       0
  5806.5     .16       0
Bank Sta=4999.3,5005.3
XS Rating Curve= 0 ,0
Exp/Cntr=0.3,0.1

Type RM Length L Ch R = 1 ,1996    ,55,55,55
BEGIN DESCRIPTION:
Mapping XS 4112bbed
END DESCRIPTION:
XS GIS Cut Line= 4
      2812623.98     10072237.04      2812417.38     10072141.55
      2811906.97     10072087.73      2811467.73     10072145.02
#Sta/Elev= 30
  4632.9 1634.26    4677 1632.58    4700 1631.01  4728.4 1630.18  4745.8 1628.47
  4751.3 1628.48  4768.8 1626.16  4797.2 1624.69  4843.1 1621.07  4860.5 1620.45
  4907.9 1617.07  4929.8 1613.83  4949.9 1611.64  5037.4 1611.55  5040.2 1611.05
  5043.4 1611.55  5060.5 1611.73  5076.9 1613.67  5120.8 1613.62  5169.8 1614.79
  5344.5 1617.26  5443.7 1620.17  5537.4 1623.41  5611.3 1627.58  5616.4 1627.31
  5674.8 1631.56  5715.1 1633.11  5764.3 1636.38  5769.3 1636.15  5816.7 1638.15
#Mann= 6 ,-1 , 0
  4632.9      .1       0  4907.9     .16       0  5037.4     .07       0
  5043.4     .16       0  5344.5     .16       0  5443.7      .1       0
Bank Sta=5037.4,5043.4
XS Rating Curve= 0 ,0
Exp/Cntr=0.3,0.1

Type RM Length L Ch R = 1 ,1941    ,52,52,52
BEGIN DESCRIPTION:
UNT111 IN NNOGR 3.0
END DESCRIPTION:
XS GIS Cut Line= 4
      2812641.38     10072216.23      2812438.22     10072101.62
      2811952.11     10072014.81       2811488.6      10072072.1
#Sta/Elev= 30
  4599.1 1634.65  4697.9 1631.04  4741.2 1628.68  4773.1 1625.55  4778.8 1626.08
  4794.7    1624  4800.5 1624.09  4816.4 1622.35  4822.1 1622.52  4834.8 1621.64
  4842.3  1620.1  4877.2 1618.63    4907 1617.18  4965.9 1616.23  5031.7 1616.46
  5065.7 1615.27  5073.6 1614.27  5078.7 1614.38  5093.2 1612.57    5096 1612.07
  5099.2 1612.57  5177.5 1614.48  5228.3 1614.59  5363.3 1617.21  5400.2 1618.09
  5511.2 1621.48  5561.6 1623.82  5692.6 1633.45  5742.9 1636.22  5793.2 1637.62
#Mann= 7 ,-1 , 0
  4599.1      .1       0  4877.2     .16       0  5031.7      .1       0
  5093.2     .07       0  5099.2      .1       0  5363.3     .16       0
  5400.2      .1       0
Bank Sta=5093.2,5099.2
XS Rating Curve= 0 ,0
Exp/Cntr=0.3,0.1

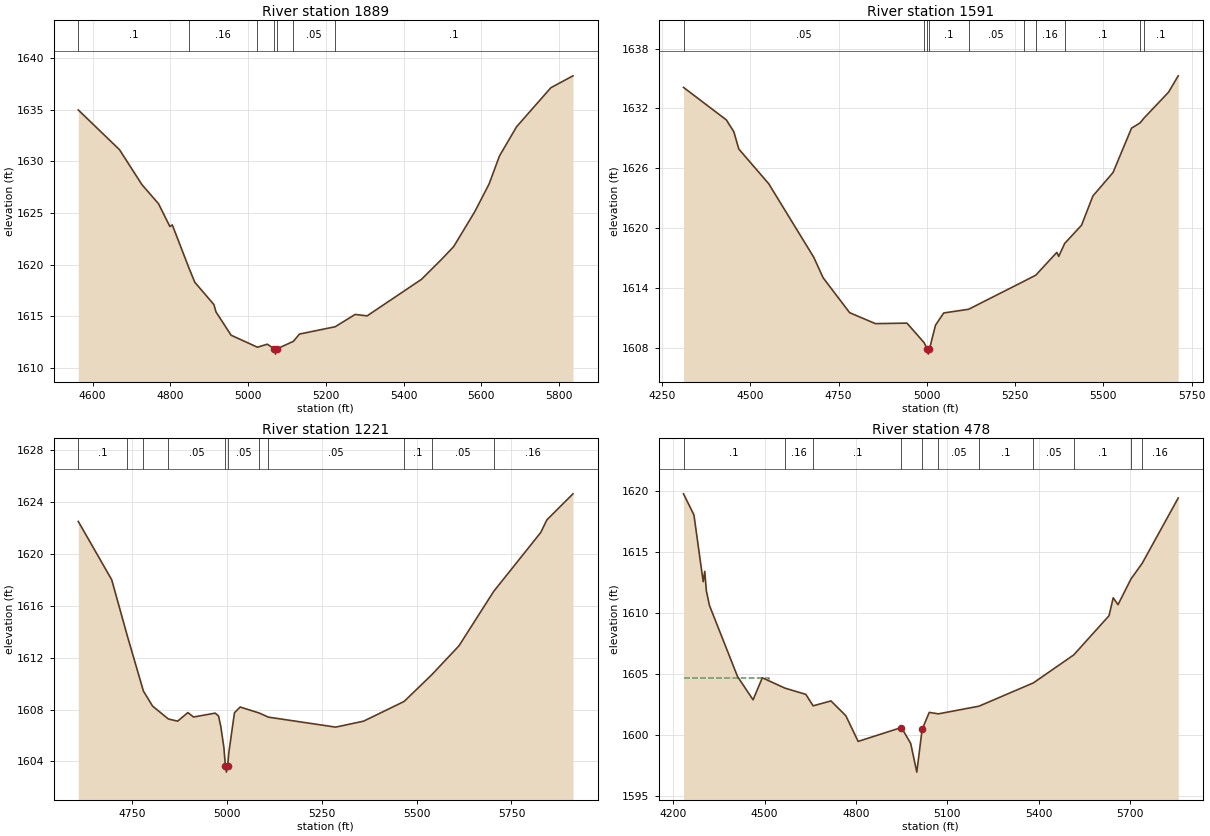
Type RM Length L Ch R = 1 ,1889    ,298,298,298
BEGIN DESCRIPTION:
Mapping XS 7e5bb085
END DESCRIPTION:
XS GIS Cut Line= 4
      2812650.06     10072211.02      2812443.42     10072058.22
       2811946.9     10071950.58      2811445.13     10072026.97
#Sta/Elev= 30
  4563.3 1634.97  4669.5 1631.12    4727 1627.75  4769.7  1625.9    4799 1623.69
  4805.2 1623.85  4847.3 1619.75  4863.1  1618.3  4912.3 1616.14  4917.5 1615.44
  4956.4 1613.18  5024.1 1612.02  5049.6 1612.31  5067.9 1611.85  5070.7 1611.35
  5073.9 1611.85  5116.7 1612.59  5132.3 1613.29  5224.2    1614  5275.6 1615.19
  5306.3 1615.05    5446 1618.58  5498.7 1620.55  5529.1 1621.76  5583.3 1625.13
  5620.1 1627.81  5646.8 1630.52  5690.9 1633.35    5779 1637.12  5835.9 1638.27
#Mann= 7 ,-1 , 0
  4563.3      .1       0  4847.3     .16       0  5024.1      .1       0
  5067.9     .07       0  5073.9      .1       0  5116.7     .05       0
  5224.2      .1       0
Bank Sta=5067.9,5073.9
XS Rating Curve= 0 ,0
Exp/Cntr=0.3,0.1

Type RM Length L Ch R = 1 ,1591    ,370,370,370
BEGIN DESCRIPTION:
UNT111 IN NNOGR 2.0
END DESCRIPTION:
XS GIS Cut Line= 4
       2812736.8     10072066.87      2812452.11     10071790.86
      2811839.26     10071695.37      2811472.32     10071811.34
#Sta/Elev= 30
  4310.4  1634.1  4431.7 1630.84  4452.9 1629.66    4467 1627.92  4551.9 1624.43
  4679.2 1617.07    4706    1615    4781  1611.5    4854  1610.4  4943.4 1610.45
  4992.1 1608.49  5001.1 1607.84  5003.9 1607.34  5007.1 1607.84  5024.4 1610.25
  5047.6 1611.47  5118.1 1611.84  5273.7 1614.63  5308.4 1615.26  5368.1 1617.55
  5373.4 1617.14  5390.2 1618.44    5438 1620.27  5470.3 1623.21  5527.3 1625.56
  5579.7 1630.01    5604 1630.54  5614.7 1631.01  5684.6 1633.62    5712 1635.26
#Mann= 10 ,-1 , 0
  4310.4     .05       0  4992.1      .1       0  5001.1     .07       0
  5007.1      .1       0  5118.1     .05       0  5273.7      .1       0
  5308.4     .16       0  5390.2      .1       0    5604     .16       0
  5614.7      .1       0
Bank Sta=5001.1,5007.1
XS Rating Curve= 0 ,0
Exp/Cntr=0.3,0.1

Type RM Length L Ch R = 1 ,1221    ,743,743,743
BEGIN DESCRIPTION:
Mapping XS c6b55241
END DESCRIPTION:
XS GIS Cut Line= 3
      2812686.95     10071677.62      2812117.06     10071293.87
      2811515.66      10071434.2
#Sta/Elev= 30
  4607.7 1622.51  4695.8 1618.02  4737.5 1613.64  4779.5 1609.43  4803.7 1608.27
  4845.2 1607.28  4869.7 1607.11  4896.7 1607.77  4911.7 1607.43  4968.7 1607.73
  4977.6 1607.51  4983.7 1606.67  4991.7 1605.08  4995.6 1603.68  4998.4 1603.18
  5001.6 1603.68  5004.7 1604.68  5019.6 1607.76  5034.6  1608.2  5084.6 1607.74
  5109.2 1607.42  5286.5 1606.65  5360.1 1607.11    5467 1608.63  5539.9 1610.69
  5611.6 1612.92  5703.3 1617.12  5827.3 1621.66  5843.4 1622.63  5912.3 1624.64
#Mann= 11 ,-1 , 0
  4607.7      .1       0  4737.5     .05       0  4779.5      .1       0
  4845.2     .05       0  4995.6    .035       0  5001.6     .05       0
  5084.6      .1       0  5109.2     .05       0    5467      .1       0
  5539.9     .05       0  5703.3     .16       0
Bank Sta=4995.6,5001.6
XS Rating Curve= 0 ,0
Exp/Cntr=0.3,0.1

Type RM Length L Ch R = 1 ,478     ,0,0,0
BEGIN DESCRIPTION:
UNT111 IN NNOGR 1.0
END DESCRIPTION:
XS GIS Cut Line= 4
      2812707.02     10071537.31      2812606.79     10071033.26
      2812160.02      10070958.8      2811591.82     10071287.16
#Sta/Elev= 30
  4234.3 1619.75  4268.5 1618.02  4298.9 1612.54    4304 1613.39  4309.3 1611.78
  4319.5 1610.59  4411.4 1604.77  4462.5 1602.85  4492.8 1604.66  4567.1 1603.81
  4635.6  1603.3  4659.5 1602.36  4718.1 1602.76  4766.8 1601.55  4807.3 1599.44
  4949.3 1600.58  4979.7 1599.27  4999.7 1596.92  5017.1 1600.42  5040.5 1601.82
  5070.4  1601.7  5203.7 1602.33  5382.1 1604.24  5514.8 1606.54  5630.3 1609.75
  5644.1 1611.22  5659.9 1610.66  5702.5 1612.77  5739.2 1614.05  5857.4 1619.41
#Mann= 11 ,-1 , 0
  4234.3      .1       0  4567.1     .16       0  4659.5      .1       0
  4949.3     .05       0  5017.1      .1       0  5070.4     .05       0
  5203.7      .1       0  5382.1     .05       0  5514.8      .1       0
  5702.5     .05       0  5739.2     .16       0
#XS Ineff= 2 , 0
         4514.02 1604.68
Permanent Ineff=
       F       F
Bank Sta=4949.3,5017.1
XS Rating Curve= 0 ,0
Exp/Cntr=0.3,0.1

Chan Stop Cuts=-1
Use User Specified Reach Order=0
Composite Channel Slope=5