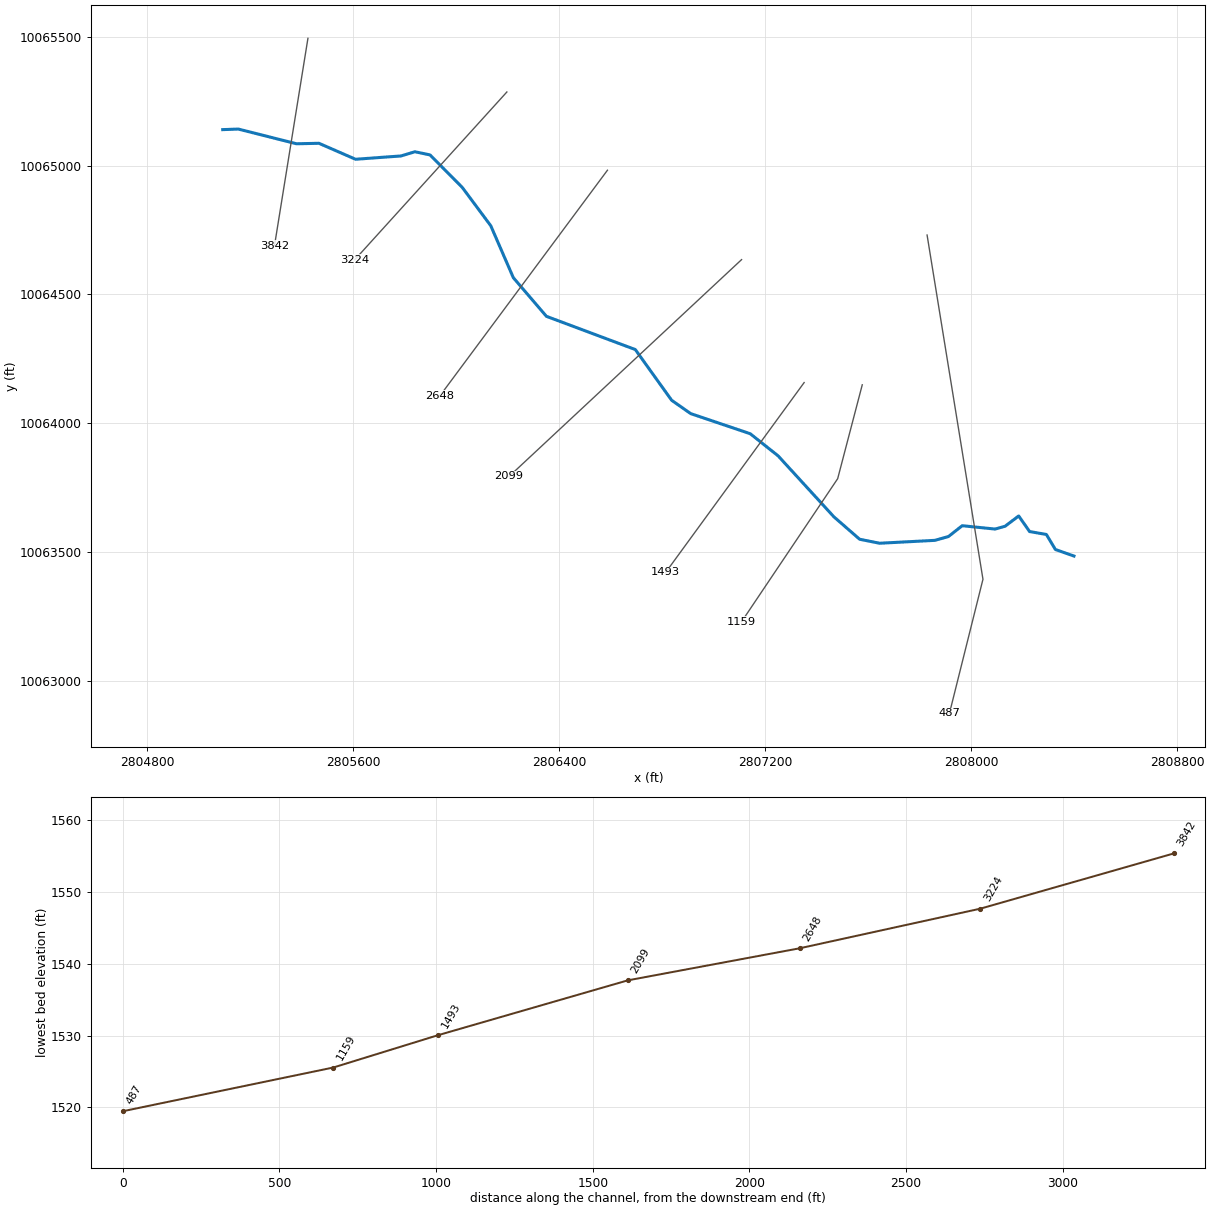
--- UNT112 IN NNOGR.prj (project) ---

Proj Title=UNT112 IN NNOGR Base Level Engineering
Current Plan=p01
Default Exp/Contr=0.3,0.1
English Units
Geom File=g01
Flow File=f01
Plan File=p01
Y Axis Title=Elevation
X Axis Title(PF)=Main Channel Distance
X Axis Title(XS)=Station
BEGIN DESCRIPTION:
UNT112 IN NNOGR
END DESCRIPTION:
DSS Export Rating Curves= 0
DSS Export Rating Curve Sorted= 0
DSS Export Volume Flow Curves= 0
DXF OffsetX= 0
DXF OffsetY= 0
DXF ScaleX= 1
DXF ScaleY= 10

--- UNT112 IN NNOGR.p01 (plan) ---

Plan Title=Multiple Run
Short Identifier=Multiple
Geom File=g01
Flow File=f01
Subcritical Flow
K Sum by GR= 0
Std Step Tol= 0.01
Critical Tol= 0.01
Num of Std Step Trials= 20
Max Error Tol= 0.3
Flow Tol Ratio= 0.001
Split Flow NTrial= 30
Split Flow Tol= 0.02
Split Flow Ratio= 0.02
Log Output Level= 0
Friction Slope Method= 1
Unsteady Friction Slope Method= 2
Unsteady Bridges Friction Slope Method= 1
Parabolic Critical Depth
Global Vel Dist=  1 , 1 , 1
Global Log Level= 0
CheckData=True
Encroach Param= -1, 0, 0, 0
BEGIN DESCRIPTION:
Multiple Run
END DESCRIPTION:

--- UNT112 IN NNOGR.f01 (steady flow) ---

Flow Title=Multiple
Program Version=4.10
Number of Profiles= 7
Profile Names=10-year,25-year,50-year,1pct_min,100-year,1pct_plu,500-year
River Rch & RM=UNT112 IN NNOGR,Reach-1         ,3842
     710    1010    1266    1161    1570    2123    2426
River Rch & RM=UNT112 IN NNOGR,Reach-1         ,3224
     837    1201    1513    1395    1886    2551    2942
Boundary for River Rch & Prof#=UNT112 IN NNOGR,Reach-1         , 1
Up Type= 0
Dn Type= 3
Dn Slope=0.0112
Boundary for River Rch & Prof#=UNT112 IN NNOGR,Reach-1         , 2
Up Type= 0
Dn Type= 3
Dn Slope=0.0112
Boundary for River Rch & Prof#=UNT112 IN NNOGR,Reach-1         , 3
Up Type= 0
Dn Type= 3
Dn Slope=0.0112
Boundary for River Rch & Prof#=UNT112 IN NNOGR,Reach-1         , 4
Up Type= 0
Dn Type= 3
Dn Slope=0.0112
Boundary for River Rch & Prof#=UNT112 IN NNOGR,Reach-1         , 5
Up Type= 0
Dn Type= 3
Dn Slope=0.0112
Boundary for River Rch & Prof#=UNT112 IN NNOGR,Reach-1         , 6
Up Type= 0
Dn Type= 3
Dn Slope=0.0112
Boundary for River Rch & Prof#=UNT112 IN NNOGR,Reach-1         , 7
Up Type= 0
Dn Type= 3
Dn Slope=0.0112
DSS Import GetInterval= 0
DSS Import GetPeak= 0
DSS Import FillOption= 0

--- UNT112 IN NNOGR.g01 (geometry) ---

Geom Title=Existing Conditions
Program Version=4.10

River Reach=UNT112 IN NNOGR ,Reach-1
Reach XY= 30
      2805092.42      10065139.8      2805153.08     10065141.98
      2805379.01     10065084.84      2805466.13     10065086.71
      2805608.37     10065024.68      2805784.92     10065037.55
      2805838.69     10065053.83      2805897.53     10065041.61
      2806022.87     10064915.17      2806133.48     10064766.41
      2806221.06     10064564.81      2806349.49     10064414.73
      2806694.69     10064285.74      2806835.88     10064088.74
      2806909.79     10064036.97      2807141.13     10063958.78
      2807249.26     10063872.95      2807465.98     10063636.09
      2807565.93     10063548.99      2807643.41     10063533.46
      2807858.43     10063544.72      2807910.78     10063559.52
      2807964.42     10063601.56      2808091.97     10063588.55
      2808130.82     10063599.52      2808183.67     10063639.41
      2808226.04     10063578.85      2808291.09     10063567.64
      2808326.29     10063509.14      2808398.47     10063483.73

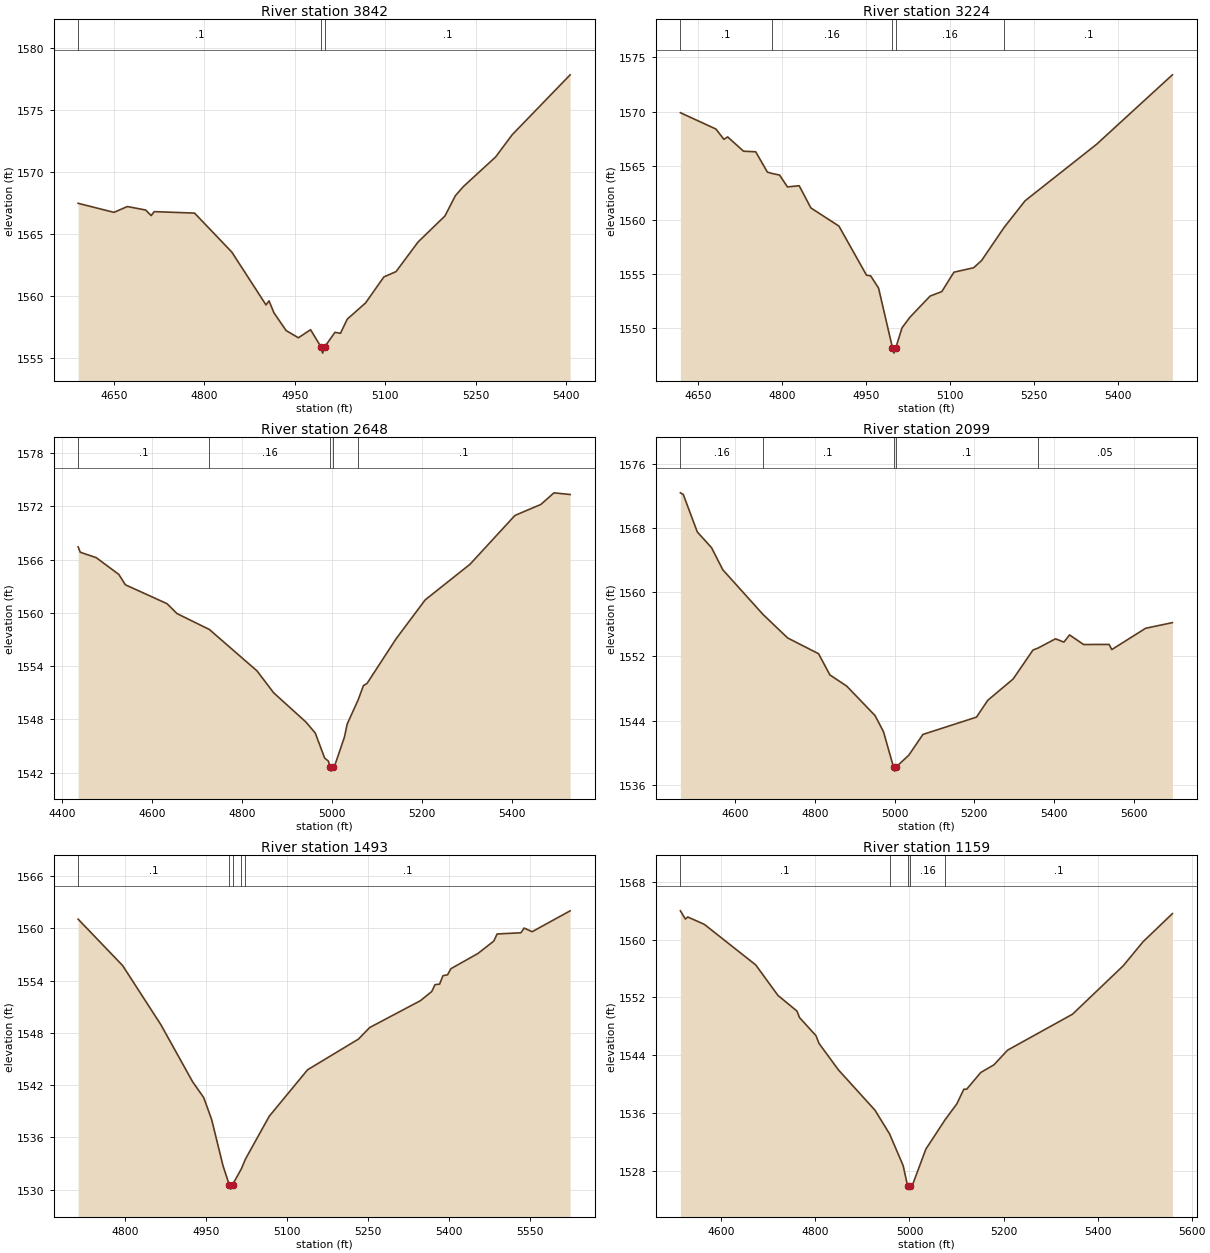
Type RM Length L Ch R = 1 ,3842    ,618,618,618
BEGIN DESCRIPTION:
UNT112 IN NNOGR 8.0
END DESCRIPTION:
XS GIS Cut Line= 2
       2805423.4     10065494.32      2805293.47     10064688.73
#Sta/Elev= 30
  4590.7 1567.46  4650.1 1566.73  4672.3  1567.2  4702.7 1566.92  4711.8 1566.47
  4716.9 1566.79  4783.8 1566.67  4845.5 1563.53  4902.3 1559.26  4907.3 1559.59
  4915.4 1558.63  4935.7 1557.19    4956 1556.61  4976.2 1557.26  4993.5 1555.87
  4996.2 1555.37  4999.5 1555.87  5016.7 1557.05  5025.8 1556.97    5037 1558.11
  5067.4 1559.42  5097.8 1561.52    5118 1561.95  5154.5 1564.34  5199.1 1566.44
  5216.3 1568.07  5229.4  1568.8  5283.1  1571.2  5310.5 1572.99  5406.7 1577.83
#Mann= 3 ,-1 , 0
  4590.7      .1       0  4993.5     .07       0  4999.5      .1       0
Bank Sta=4993.5,4999.5
XS Rating Curve= 0 ,0
Exp/Cntr=0.3,0.1

Type RM Length L Ch R = 1 ,3224    ,576,576,576
BEGIN DESCRIPTION:
UNT112 IN NNOGR 7.0
END DESCRIPTION:
XS GIS Cut Line= 2
      2806195.98     10065285.96       2805605.7     10064634.92
#Sta/Elev= 30
  4618.2 1569.89  4681.7 1568.38  4695.9 1567.43  4702.7 1567.65    4731 1566.33
  4752.7 1566.28  4773.6  1564.4  4781.4 1564.28  4795.3 1564.13  4809.5 1563.03
  4830.4 1563.14  4851.3 1561.09  4901.4 1559.41  4950.7 1554.87  4958.1 1554.81
  4972.2 1553.68    4997 1548.17  4999.8 1547.67    5003 1548.17  5014.2 1550.02
  5028.4    1551  5064.2 1552.94  5085.2 1553.36  5106.8 1555.15    5142 1555.56
  5156.1 1556.22  5196.5 1559.29  5233.9 1561.75  5361.6 1566.97    5497 1573.39
#Mann= 5 ,-1 , 0
  4618.2      .1       0  4781.4     .16       0    4997     .07       0
    5003     .16       0  5196.5      .1       0
Bank Sta=4997,5003
XS Rating Curve= 0 ,0
Exp/Cntr=0.3,0.1

Type RM Length L Ch R = 1 ,2648    ,549,549,549
BEGIN DESCRIPTION:
UNT112 IN NNOGR 5.0
END DESCRIPTION:
XS GIS Cut Line= 2
      2806586.59     10064982.13      2805935.57     10064105.42
#Sta/Elev= 30
  4436.4 1567.45  4441.1 1566.84  4476.6 1566.23  4526.7 1564.34  4541.3 1563.17
  4633.7 1561.04    4656 1559.92  4727.7 1558.13  4833.3 1553.47  4870.4 1550.99
  4941.9  1547.7  4962.7 1546.46  4983.5 1543.64  4991.9 1543.29  4995.2 1542.66
  4997.9 1542.16  5001.2 1542.66  5006.5 1542.87  5027.4 1545.99  5033.6 1547.47
  5058.1 1550.22  5069.6  1551.8  5077.5 1552.04  5142.1 1557.08  5206.7 1561.47
  5306.3 1565.49  5405.9 1570.99  5463.4 1572.23  5492.6 1573.54  5528.4 1573.35
#Mann= 5 ,-1 , 0
  4436.4      .1       0  4727.7     .16       0  4995.2     .07       0
  5001.2     .16       0  5058.1      .1       0
Bank Sta=4995.2,5001.2
XS Rating Curve= 0 ,0
Exp/Cntr=0.3,0.1

Type RM Length L Ch R = 1 ,2099    ,606,606,606
BEGIN DESCRIPTION:
UNT112 IN NNOGR 4.0
END DESCRIPTION:
XS GIS Cut Line= 2
      2807107.44     10064634.92      2806204.66      10063792.9
#Sta/Elev= 30
  4462.6 1572.42  4469.9 1572.21    4505 1567.54  4540.7 1565.58    4569 1562.82
  4669.6 1557.26  4731.7 1554.31  4809.4 1552.34  4837.7  1549.7  4880.2 1548.29
  4951.1 1544.62  4972.1 1542.63  4997.4 1538.19  5000.2 1537.69  5003.4 1538.19
  5035.6 1539.67  5071.2 1542.27  5205.6 1544.43  5233.9 1546.53  5297.4 1549.18
  5347.3  1552.8  5359.7 1553.04  5403.9  1554.2  5424.9 1553.79  5439.1 1554.69
  5474.3 1553.49  5538.3  1553.5  5545.1 1552.86  5630.1 1555.52  5697.1 1556.22
#Mann= 5 ,-1 , 0
  4462.6     .16       0  4669.6      .1       0  4997.4     .07       0
  5003.4      .1       0  5359.7     .05       0
Bank Sta=4997.4,5003.4
XS Rating Curve= 0 ,0
Exp/Cntr=0.3,0.1

Type RM Length L Ch R = 1 ,1493    ,334,334,334
BEGIN DESCRIPTION:
UNT112 IN NNOGR 3.0
END DESCRIPTION:
XS GIS Cut Line= 2
      2807350.46     10064157.45       2806812.9     10063420.47
#Sta/Elev= 30
  4712.7 1561.06  4795.1 1555.74  4866.2 1548.93  4924.9 1542.39  4945.7 1540.55
  4960.4 1538.01  4981.3 1532.74  4992.9 1530.55  4995.7 1530.05  4998.9 1530.55
  5015.3 1532.38  5022.9  1533.5    5067 1538.42  5138.1 1543.76  5232.3 1547.28
  5253.2 1548.61  5347.4  1551.7  5368.3 1552.75  5374.4 1553.54  5382.9  1553.6
  5389.1 1554.57  5397.6 1554.67  5403.8 1555.37    5454 1557.12  5483.4 1558.55
  5489.5 1559.36  5533.6  1559.5  5539.7 1560.04  5554.4 1559.62  5624.9 1562.02
#Mann= 5 ,-1 , 0
  4712.7      .1       0  4992.9     .07       0  4998.9      .1       0
  5015.3     .16       0  5022.9      .1       0
Bank Sta=4992.9,4998.9
XS Rating Curve= 0 ,0
Exp/Cntr=0.3,0.1

Type RM Length L Ch R = 1 ,1159    ,672,672,672
BEGIN DESCRIPTION:
UNT112 IN NNOGR 2.0
END DESCRIPTION:
XS GIS Cut Line= 3
      2807576.18      10064148.8      2807480.69     10063784.21
      2807107.48     10063228.73
#Sta/Elev= 30
  4512.9 1563.96  4523.5 1562.83  4528.6 1563.11  4563.9 1562.09  4673.2 1556.49
  4720.3 1552.29  4760.7 1550.13  4766.2 1549.23  4801.2 1546.73  4807.6 1545.67
  4848.9 1542.01  4926.6 1536.45  4957.7 1533.17  4986.6 1528.79  4995.8 1526.05
  4998.5 1525.55  5001.8 1526.05  5007.6 1526.33  5034.9 1531.08  5075.8 1535.13
  5100.6 1537.31  5115.6 1539.34  5121.6 1539.34  5151.6 1541.65  5179.5  1542.7
  5208.6 1544.73  5346.6 1549.69  5454.6 1556.38  5496.6 1559.69    5559 1563.57
#Mann= 5 ,-1 , 0
  4512.9      .1       0  4957.7     .16       0  4995.8     .07       0
  5001.8     .16       0  5075.8      .1       0
Bank Sta=4995.8,5001.8
XS Rating Curve= 0 ,0
Exp/Cntr=0.3,0.1

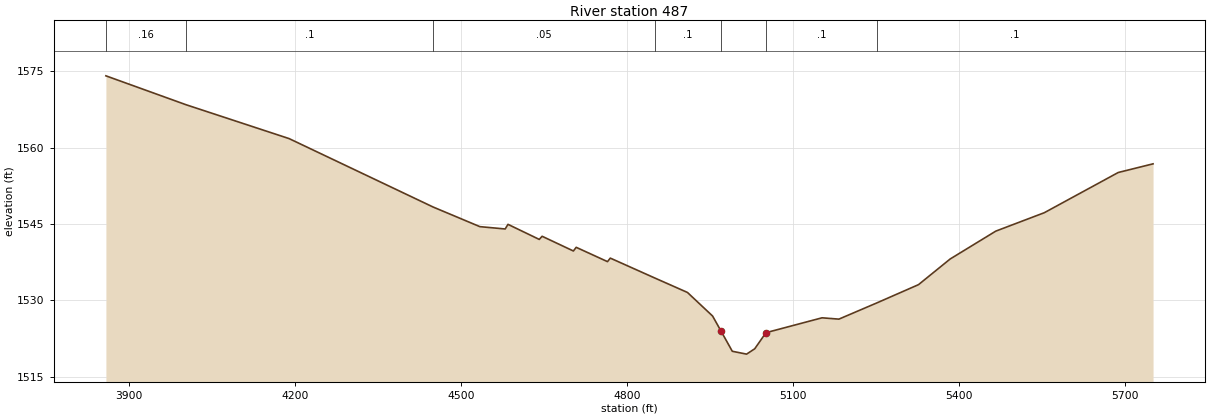
Type RM Length L Ch R = 1 ,487     ,0,0,0
BEGIN DESCRIPTION:
UNT112 IN NNOGR 1.0
END DESCRIPTION:
XS GIS Cut Line= 3
       2807827.9     10064730.43      2808044.92     10063393.58
      2807914.72     10062872.76
#Sta/Elev= 30
  3859.1  1574.1  4003.7 1568.43  4190.1 1561.77  4450.1 1548.34  4534.5 1544.49
  4580.2 1544.03  4585.3 1544.94  4641.8 1541.98  4646.9  1542.6  4703.4 1539.71
  4708.5 1540.43    4765 1537.62  4770.1 1538.31  4849.9 1534.43  4909.4 1531.57
  4954.8 1526.94  4970.2 1523.95  4990.4 1520.02  5016.2 1519.46  5030.9 1520.51
  5051.2 1523.67  5152.5 1526.59  5182.9 1526.33  5252.2 1529.55  5326.7  1533.1
  5383.9 1538.14  5466.3 1543.61    5554 1547.23  5687.4 1555.12  5750.3 1556.82
#Mann= 7 ,-1 , 0
  3859.1     .16       0  4003.7      .1       0  4450.1     .05       0
  4849.9      .1       0  4970.2     .07       0  5051.2      .1       0
  5252.2      .1       0
Bank Sta=4970.2,5051.2
XS Rating Curve= 0 ,0
Exp/Cntr=0.3,0.1

Chan Stop Cuts=-1
Use User Specified Reach Order=0
Composite Channel Slope=5