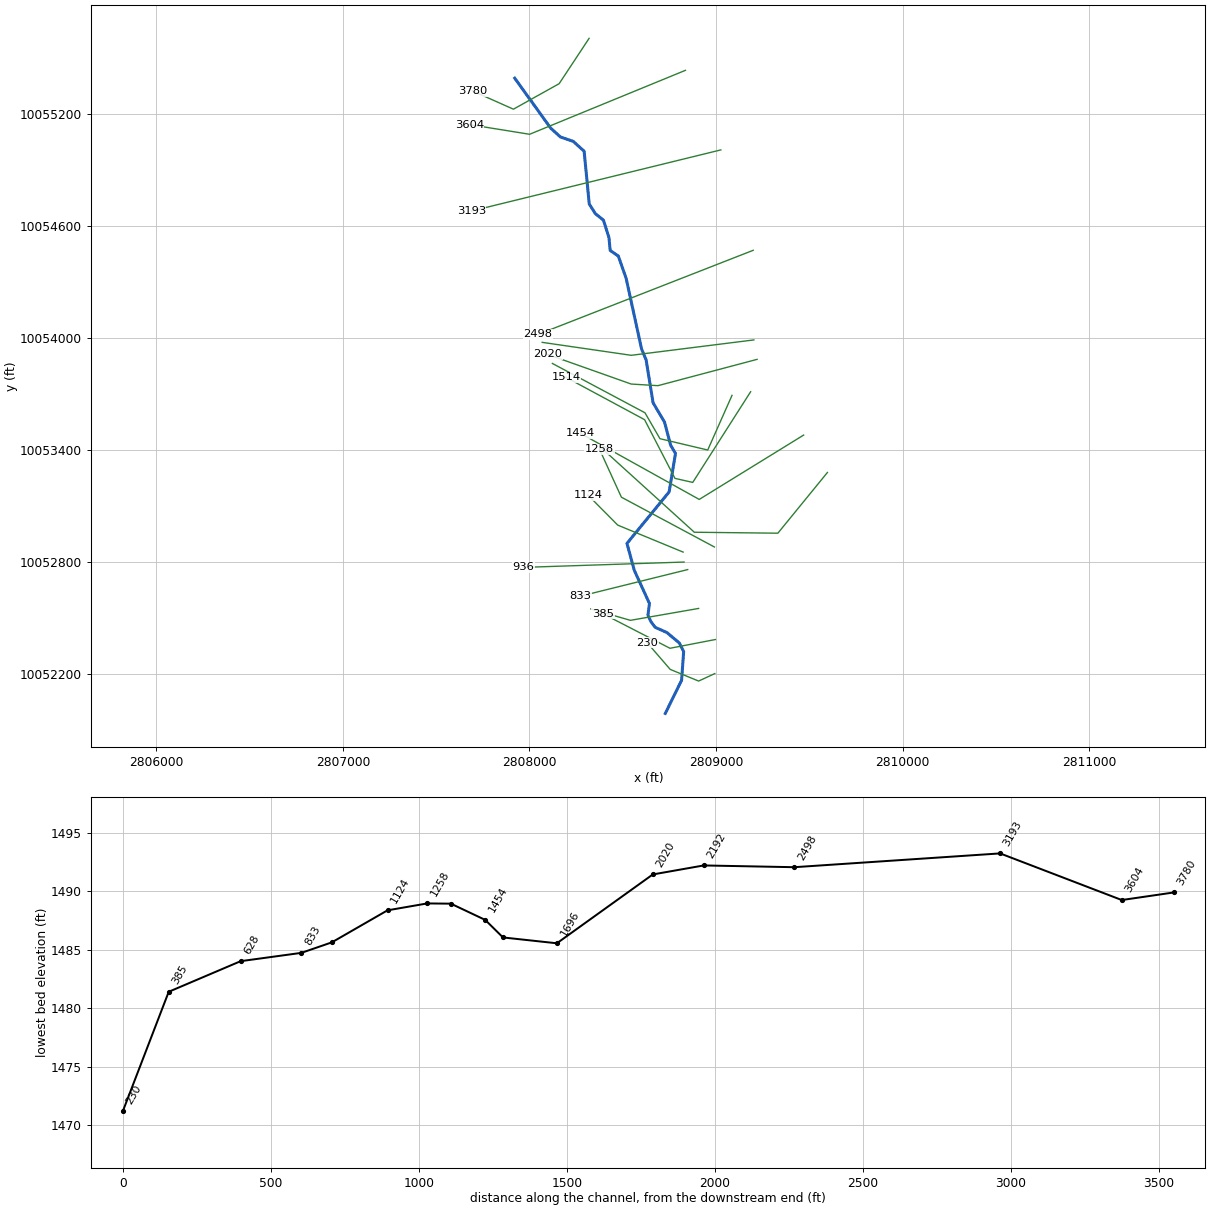
--- UNT114 IN NNOGR.prj (project) ---

Proj Title=UNT114 IN NNOGR Base Level Engineering
Current Plan=p01
Default Exp/Contr=0.3,0.1
English Units
Geom File=g01
Flow File=f01
Plan File=p01
Y Axis Title=Elevation
X Axis Title(PF)=Main Channel Distance
X Axis Title(XS)=Station
BEGIN DESCRIPTION:
UNT114 IN NNOGR
END DESCRIPTION:
DSS Export Rating Curves= 0
DSS Export Rating Curve Sorted= 0
DSS Export Volume Flow Curves= 0
DXF OffsetX= 0
DXF OffsetY= 0
DXF ScaleX= 1
DXF ScaleY= 10

--- UNT114 IN NNOGR.p01 (plan) ---

Plan Title=Multiple Run
Short Identifier=Multiple
Geom File=g01
Flow File=f01
Subcritical Flow
K Sum by GR= 0
Std Step Tol= 0.01
Critical Tol= 0.01
Num of Std Step Trials= 20
Max Error Tol= 0.3
Flow Tol Ratio= 0.001
Split Flow NTrial= 30
Split Flow Tol= 0.02
Split Flow Ratio= 0.02
Log Output Level= 0
Friction Slope Method= 1
Unsteady Friction Slope Method= 2
Unsteady Bridges Friction Slope Method= 1
Parabolic Critical Depth
Global Vel Dist=  1 , 1 , 1
Global Log Level= 0
CheckData=True
Encroach Param= -1, 0, 0, 0
BEGIN DESCRIPTION:
Multiple Run
END DESCRIPTION:

--- UNT114 IN NNOGR.f01 (steady flow) ---

Flow Title=Multiple
Program Version=4.10
Number of Profiles= 7
Profile Names=10-year,25-year,50-year,1pct_min,100-year,1pct_plu,500-year
River Rch & RM=UNT114 IN NNOGR,Reach-1         ,3780
     146     185     215     183     248     335     330
Boundary for River Rch & Prof#=UNT114 IN NNOGR,Reach-1         , 1
Up Type= 0
Dn Type= 3
Dn Slope=0.0708
Boundary for River Rch & Prof#=UNT114 IN NNOGR,Reach-1         , 2
Up Type= 0
Dn Type= 3
Dn Slope=0.0708
Boundary for River Rch & Prof#=UNT114 IN NNOGR,Reach-1         , 3
Up Type= 0
Dn Type= 3
Dn Slope=0.0708
Boundary for River Rch & Prof#=UNT114 IN NNOGR,Reach-1         , 4
Up Type= 0
Dn Type= 3
Dn Slope=0.0708
Boundary for River Rch & Prof#=UNT114 IN NNOGR,Reach-1         , 5
Up Type= 0
Dn Type= 3
Dn Slope=0.0708
Boundary for River Rch & Prof#=UNT114 IN NNOGR,Reach-1         , 6
Up Type= 0
Dn Type= 3
Dn Slope=0.0708
Boundary for River Rch & Prof#=UNT114 IN NNOGR,Reach-1         , 7
Up Type= 0
Dn Type= 3
Dn Slope=0.0708
DSS Import GetInterval= 0
DSS Import GetPeak= 0
DSS Import FillOption= 0

--- UNT114 IN NNOGR.g01 (geometry) ---

Geom Title=Existing Conditions
Program Version=4.10

River Reach=UNT114 IN NNOGR ,Reach-1
Reach XY= 30
      2807920.94     10055392.46      2808113.75     10055124.73
      2808165.83      10055077.5      2808234.58     10055053.89
      2808292.92     10055001.12      2808320.43     10054718.13
      2808353.42     10054666.05      2808396.39     10054631.76
      2808426.05     10054537.86      2808432.56     10054469.29
      2808476.39     10054438.91      2808518.17     10054319.54
       2808600.7     10053941.52      2808625.32     10053882.04
       2808662.5     10053652.73      2808723.88     10053549.17
      2808756.86      10053424.6       2808782.7     10053381.07
      2808748.68     10053174.82      2808522.62     10052898.67
      2808561.55     10052755.01      2808643.07     10052576.77
      2808635.11      10052513.9      2808650.05     10052480.63
      2808673.43     10052449.05       2808737.3     10052420.45
      2808803.07     10052364.91      2808826.49      10052318.9
      2808815.46     10052164.97       2808728.2     10051987.45

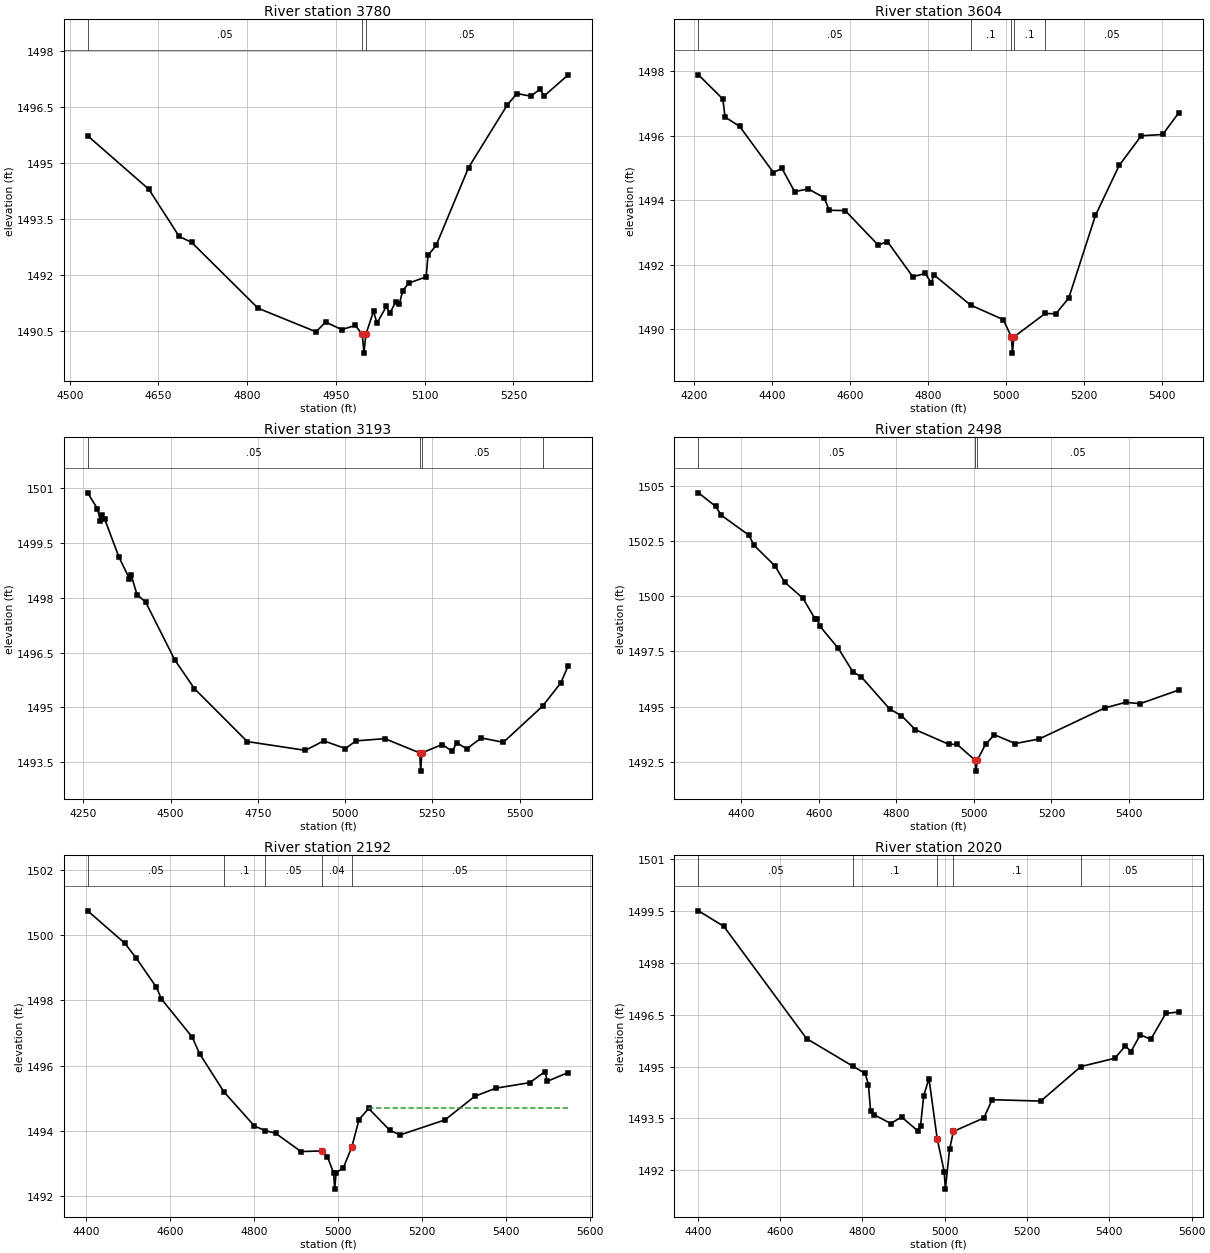
Type RM Length L Ch R = 1 ,3780    ,176,176,176
BEGIN DESCRIPTION:
UNT114 IN NNOGR 2.0
END DESCRIPTION:
XS GIS Cut Line= 4
      2808319.67     10055606.27      2808159.07      10055363.2
      2807913.85     10055226.48      2807694.62     10055324.15
#Sta/Elev= 30
  4530.4 1495.72  4633.8 1494.29    4685 1493.03  4706.1 1492.87  4818.4 1491.11
  4916.4 1490.48  4932.4 1490.74  4959.8 1490.54  4982.7 1490.65  4994.5 1490.41
  4997.3 1489.91  5000.5 1490.41  5013.5 1491.03  5019.3 1490.71  5035.2 1491.16
    5041 1490.97  5051.2 1491.29    5057 1491.22  5062.9 1491.58    5073 1491.78
  5102.5 1491.95  5105.5 1492.52  5119.3 1492.79  5174.1 1494.87  5239.8 1496.55
  5255.8 1496.85  5279.1 1496.78  5294.5 1496.96  5302.3 1496.79  5342.5 1497.35
#Mann= 3 ,-1 , 0
  4530.4     .05       0  4994.5    .035       0  5000.5     .05       0
Bank Sta=4994.5,5000.5
XS Rating Curve= 0 ,0
Exp/Cntr=0.3,0.1

Type RM Length L Ch R = 1 ,3604    ,411,411,411
BEGIN DESCRIPTION:
Mapping XS 2671f4d7
END DESCRIPTION:
XS GIS Cut Line= 3
      2808836.13      10055434.8      2808000.65     10055091.93
      2807677.32     10055144.01
#Sta/Elev= 30
  4212.3 1497.89  4274.6 1497.14  4280.5 1496.58  4317.9 1496.29  4404.3 1494.86
    4426 1494.99  4458.4 1494.27  4493.9 1494.35  4534.1 1494.08  4547.3 1493.69
  4588.1 1493.68  4672.6 1492.61  4696.2 1492.72  4761.1 1491.63  4793.5 1491.73
  4808.7 1491.43  4815.1 1491.69  4909.2 1490.75  4992.8  1490.3  5013.8 1489.76
  5016.5 1489.26  5019.8 1489.76  5100.4 1490.49  5127.7 1490.48  5160.7 1490.97
    5229 1493.53  5289.8 1495.08  5346.2    1496  5401.2 1496.04  5442.9 1496.72
#Mann= 5 ,-1 , 0
  4212.3     .05       0  4909.2      .1       0  5013.8     .07       0
  5019.8      .1       0  5100.4     .05       0
Bank Sta=5013.8,5019.8
XS Rating Curve= 0 ,0
Exp/Cntr=0.3,0.1

Type RM Length L Ch R = 1 ,3193    ,695,695,695
BEGIN DESCRIPTION:
Mapping XS fdabb4fc
END DESCRIPTION:
XS GIS Cut Line= 2
      2809025.81     10055008.16      2807688.01     10054680.23
#Sta/Elev= 30
  4262.1 1500.88  4290.2 1500.44  4298.6 1500.11  4303.7 1500.27  4310.8 1500.16
    4352 1499.11  4381.7 1498.53  4386.9 1498.62  4403.5 1498.09  4428.5 1497.88
  4511.7  1496.3  4568.2 1495.51  4719.6 1494.06    4886 1493.82  4938.9 1494.08
  5000.7 1493.87  5031.6 1494.08  5113.9 1494.14  5213.9 1493.75  5216.6 1493.25
  5219.9 1493.75  5278.7 1493.98  5307.1 1493.79  5319.9 1494.03  5348.7 1493.86
  5390.3 1494.16  5453.7 1494.04  5565.9 1495.03  5618.4 1495.67  5639.5 1496.14
#Mann= 4 ,-1 , 0
  4262.1     .05       0  5213.9    .035       0  5219.9     .05       0
  5565.9      .1       0
Bank Sta=5213.9,5219.9
XS Rating Curve= 0 ,0
Exp/Cntr=0.3,0.1

Type RM Length L Ch R = 1 ,2498    ,306,306,306
BEGIN DESCRIPTION:
Mapping XS c9feb0d8
END DESCRIPTION:
XS GIS Cut Line= 2
      2809199.43     10054469.97      2808045.12     10054018.66
#Sta/Elev= 30
  4289.6 1504.69  4333.6 1504.08  4348.8 1503.67  4419.5 1502.77    4433 1502.31
  4487.3 1501.37  4511.7 1500.64  4559.1 1499.91  4590.5 1498.97  4595.9 1498.98
    4602 1498.66  4650.2 1497.64  4687.9 1496.57  4709.8 1496.34  4783.3 1494.88
  4813.1 1494.59    4849 1493.95  4934.9 1493.29  4956.9 1493.28  5002.8 1492.57
  5005.6 1492.07  5008.8 1492.57  5030.3 1493.29    5053 1493.72  5106.7 1493.32
  5168.8 1493.53    5337 1494.93  5391.3 1495.19  5428.8 1495.13    5529 1495.75
#Mann= 3 ,-1 , 0
  4289.6     .05       0  5002.8    .035       0  5008.8     .05       0
Bank Sta=5002.8,5008.8
XS Rating Curve= 0 ,0
Exp/Cntr=0.3,0.1

Type RM Length L Ch R = 1 ,2192    ,172,172,172
BEGIN DESCRIPTION:
Mapping XS 2f78ada6
END DESCRIPTION:
XS GIS Cut Line= 3
       2809202.9      10053989.5      2808545.36     10053907.03
      2808067.88     10053976.48
#Sta/Elev= 30
    4404 1500.74  4492.3 1499.75  4519.3  1499.3  4567.8  1498.4  4579.8 1498.04
  4653.3 1496.87  4670.5 1496.37  4728.6  1495.2  4801.5 1494.15  4827.5 1494.01
  4851.9 1493.93  4912.4 1493.37  4962.8 1493.39  4975.3 1493.21    4990 1492.72
  4992.8 1492.22    4996 1492.72  5013.2 1492.87  5033.3  1493.5  5050.7 1494.35
  5073.6 1494.69  5124.2 1494.02  5148.7 1493.88  5255.6 1494.34  5326.3 1495.06
  5376.8 1495.31  5457.7 1495.48  5494.2 1495.82  5499.2 1495.52  5549.2 1495.79
#Mann= 5 ,-1 , 0
    4404     .05       0  4728.6      .1       0  4827.5     .05       0
  4962.8     .04       0  5033.3     .05       0
#XS Ineff= 2 , 0
                         5075.05          1494.7
Permanent Ineff=
       F       F
Bank Sta=4962.8,5033.3
XS Rating Curve= 0 ,0
Exp/Cntr=0.3,0.1

Type RM Length L Ch R = 1 ,2020    ,324,324,324
BEGIN DESCRIPTION:
Mapping XS e0f3965f
END DESCRIPTION:
XS GIS Cut Line= 4
      2809220.24     10053885.32      2808688.59     10053744.27
      2808545.36     10053752.95      2808098.33     10053911.36
#Sta/Elev= 30
  4401.4 1499.51  4463.1 1499.06  4664.1 1495.81  4776.8 1495.01  4806.7  1494.8
  4814.5 1494.48  4819.7 1493.71  4827.4 1493.61  4868.8 1493.35  4894.9 1493.54
  4935.1 1493.13  4941.2 1493.29  4948.9 1494.16  4961.6 1494.65  4981.6 1492.91
  4998.7 1491.95  5001.4 1491.45  5011.7  1492.6  5020.9 1493.12  5094.9 1493.51
  5115.2 1494.04  5233.4    1494  5330.9    1495  5413.4 1495.24    5439  1495.6
  5452.4 1495.43  5475.2 1495.92  5500.8 1495.79  5537.2 1496.54  5569.2 1496.58
#Mann= 5 ,-1 , 0
  4401.4     .05       0  4776.8      .1       0  4981.6     .07       0
  5020.9      .1       0  5330.9     .05       0
Bank Sta=4981.6,5020.9
XS Rating Curve= 0 ,0
Exp/Cntr=0.3,0.1

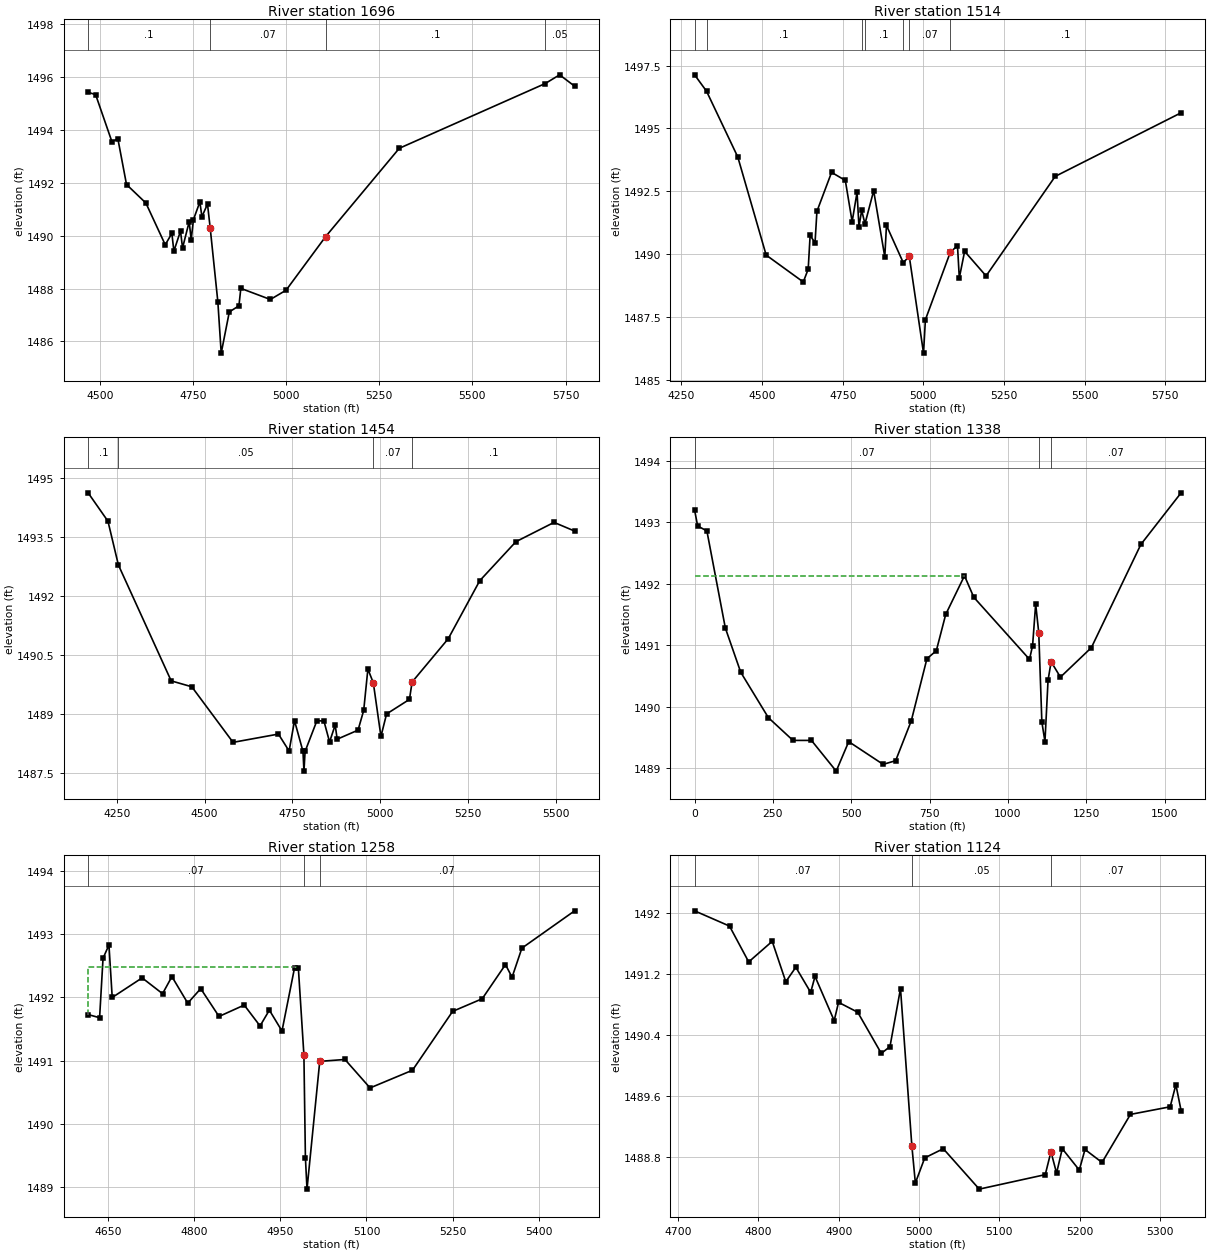
Type RM Length L Ch R = 1 ,1696    ,182,182,182
BEGIN DESCRIPTION:
Mapping XS 3a947f36
END DESCRIPTION:
XS GIS Cut Line= 5
      2809085.71     10053692.16      2808955.51     10053399.22
      2808699.44     10053459.98      2808619.14     10053598.87
      2808122.86     10053863.27
#Sta/Elev= 30
    4468 1495.43  4488.2 1495.34  4531.9 1493.56  4547.9 1493.67  4571.1 1491.94
  4623.1 1491.24  4675.1 1489.66  4692.9 1490.09  4698.3 1489.42  4716.1 1490.18
  4721.6 1489.54  4739.4 1490.53  4744.8 1489.85  4750.8 1490.61  4768.1 1491.28
  4773.6 1490.72  4788.6  1491.2  4795.8  1490.3  4816.4  1487.5  4825.4 1485.56
  4847.2 1487.12    4873 1487.35  4878.1 1488.01  4957.4 1487.59  4999.6 1487.94
  5105.9 1489.97  5303.6 1493.31  5695.5 1495.76  5734.2 1496.09  5774.5 1495.66
#Mann= 4 ,-1 , 0
    4468      .1       0  4795.8     .07       0  5105.9      .1       0
  5695.5     .05       0
Bank Sta=4795.8,5105.9
XS Rating Curve= 0 ,0
Exp/Cntr=0.3,0.1

Type RM Length L Ch R = 1 ,1514    ,60,60,60
BEGIN DESCRIPTION:
Mapping XS e831d0a1
END DESCRIPTION:
XS GIS Cut Line= 6
      2809185.52     10053711.68      2808875.22     10053225.61
      2808779.73     10053247.31      2808745.01     10053314.59
      2808616.97     10053561.98      2808194.85     10053789.28
#Sta/Elev= 30
  4290.7 1497.13  4327.7 1496.48  4424.7 1493.86  4512.6 1489.96  4627.7 1488.89
  4642.9  1489.4  4648.9 1490.74  4664.1 1490.45    4670  1491.7  4715.4 1493.25
    4758 1492.93  4779.2 1491.29  4794.4 1492.46  4800.3 1491.09  4808.8 1491.74
  4818.9  1491.2  4845.9 1492.52  4880.4 1489.89  4885.6 1491.14  4937.6 1489.66
  4956.3 1489.91  5000.5 1486.06  5006.3 1487.39  5083.7 1490.08  5105.8 1490.33
  5111.4 1489.05  5127.9 1490.11  5194.4 1489.13  5408.7 1493.09    5799 1495.62
#Mann= 7 ,-1 , 0
  4290.7     .05       0  4327.7      .1       0  4808.8     .16       0
  4818.9      .1       0  4937.6     .16       0  4956.3     .07       0
  5083.7      .1       0
Bank Sta=4956.3,5083.7
XS Rating Curve= 0 ,0
Exp/Cntr=0.3,0.1

Type RM Length L Ch R = 1 ,1454    ,116,116,116
BEGIN DESCRIPTION:
Mapping XS 27a39e4c
END DESCRIPTION:
XS GIS Cut Line= 3
       2809469.8     10053479.49      2808909.94     10053134.46
      2808274.05     10053488.22
#Sta/Elev= 30
  4168.5 1494.62    4225  1493.9  4254.7 1492.79    4405 1489.85  4463.7  1489.7
  4581.2 1488.29  4710.4  1488.5  4740.8 1488.07  4756.2 1488.84  4780.3 1488.06
  4783.1 1487.56  4786.3 1488.06    4820 1488.84    4840 1488.83    4856  1488.3
    4872 1488.73  4877.7 1488.37  4937.1  1488.6  4953.2  1489.1  4965.1 1490.15
  4980.6  1489.8  5002.3 1488.44  5018.3 1489.01  5083.5 1489.38    5091 1489.82
    5194 1490.92  5283.6 1492.39  5386.6 1493.38  5495.2 1493.87  5553.8 1493.65
#Mann= 4 ,-1 , 0
  4168.5      .1       0  4254.7     .05       0  4980.6     .07       0
    5091      .1       0
Bank Sta=4980.6,5091
XS Rating Curve= 0 ,0
Exp/Cntr=0.3,0.1

Type RM Length L Ch R = 1 ,1338    ,80,80,80
XS GIS Cut Line= 4
     2809597.144    10053278.837      2809331.49    10052953.386
     2808883.602    10052958.525     2808377.092     10053418.16
#Sta/Elev= 30
       0  1493.2    9.81 1492.94   39.25 1492.86   98.13 1491.28   147.2 1490.56
  235.52 1489.82  314.03 1489.45  372.91 1489.45  451.93 1488.95  491.86 1489.43
  601.68 1489.06  641.61 1489.12  691.52 1489.77  741.44 1490.78  771.39 1490.91
  801.34  1491.5  861.24 1492.13  890.97 1491.78 1068.69 1490.77 1078.56 1490.99
 1088.44 1491.67 1098.31  1491.2 1108.18 1489.75 1118.06 1489.43 1127.93 1490.43
  1137.8 1490.73 1167.42 1490.48 1266.16 1490.96 1424.13 1492.64 1552.48 1493.48
#Mann= 3 , 0 , 0
       0     .07       0 1098.31     .05       0  1137.8     .07       0
#XS Ineff= 2 , 0
          861.46 1492.13
Permanent Ineff=
       F       F
Bank Sta=1098.31,1137.8
XS Rating Curve= 0 ,0
Exp/Cntr=0.3,0.1

Type RM Length L Ch R = 1 ,1258    ,134,134,134
BEGIN DESCRIPTION:
Mapping XS d328d427
END DESCRIPTION:
XS GIS Cut Line= 3
      2808991.43     10052879.43       2808492.7     10053146.37
      2808375.51      10053402.9
#Sta/Elev= 30
    4615 1491.73    4635 1491.68    4641 1492.62  4651.3 1492.83    4657    1492
  4709.1 1492.31  4744.7 1492.06    4761 1492.33  4788.6 1491.91  4811.2 1492.14
  4843.1  1491.7    4887 1491.88  4914.6 1491.55  4930.8  1491.8  4952.8 1491.47
  4974.7 1492.47  4981.3 1492.47    4991 1491.09  4993.6 1489.47  4996.4 1488.97
  5018.6 1490.99  5062.5 1491.02  5106.3 1490.57  5180.2 1490.85  5250.1 1491.78
  5301.7 1491.98  5342.2 1492.52  5353.7 1492.32  5370.8 1492.78  5462.7 1493.37
#Mann= 3 , 0 , 0
    4615     .07       0    4991     .05       0  5018.6     .07       0
#XS Ineff= 2 , 0
         4977.14 1492.48
Permanent Ineff=
       F       F
Bank Sta=4991,5018.6
XS Rating Curve= 0 ,0
Exp/Cntr=0.3,0.1

Type RM Length L Ch R = 1 ,1124    ,188,188,188
BEGIN DESCRIPTION:
Mapping XS d8f7bc11
END DESCRIPTION:
XS GIS Cut Line= 3
      2808823.47     10052852.09      2808473.17     10052996.63
      2808313.27     10053157.83
#Sta/Elev= 30
  4720.5 1492.03    4764 1491.83  4787.9 1491.36  4817.2 1491.63  4834.1  1491.1
  4846.6 1491.29  4865.1 1490.96  4870.5 1491.17  4894.4 1490.59  4899.8 1490.83
  4923.7  1490.7  4953.1 1490.16  4963.9 1490.25    4977 1491.01 4991.11 1488.95
  4995.5 1488.46  5007.2 1488.79  5030.3 1488.91  5075.1 1488.38  5157.3 1488.57
  5164.4 1488.87  5171.4 1488.59  5178.5 1488.91  5199.7 1488.63  5206.8  1488.9
    5228 1488.73  5263.4 1489.36  5312.9 1489.46    5320 1489.75  5326.5 1489.41
#Mann= 3 , 0 , 0
  4720.5     .07       0 4991.11     .05       0  5164.4     .07       0
Bank Sta=4991.11,5164.4
XS Rating Curve= 0 ,0
Exp/Cntr=0.3,0.1

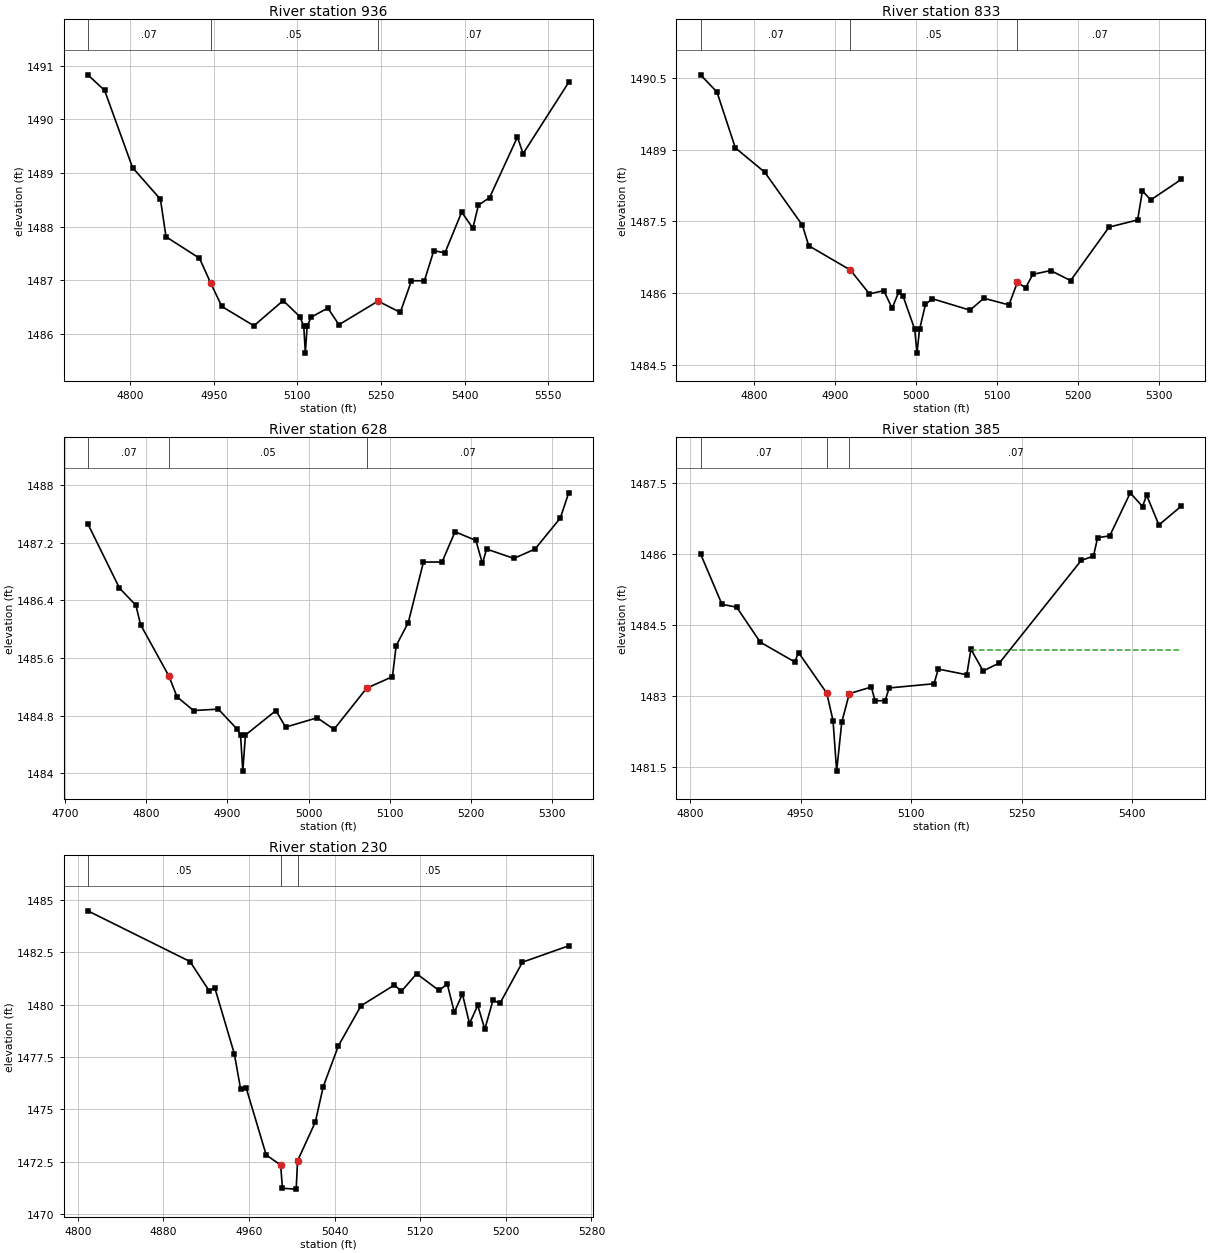
Type RM Length L Ch R = 1 ,936     ,103,103,103
BEGIN DESCRIPTION:
Mapping XS e8974d0a
END DESCRIPTION:
XS GIS Cut Line= 2
      2808828.59     10052798.72      2807966.67     10052770.07
#Sta/Elev= 30
  4724.3 1490.83  4754.4 1490.54  4804.5  1489.1  4854.5 1488.51  4864.5 1487.81
  4924.5 1487.41  4944.5 1486.95  4964.6 1486.51  5022.2 1486.15  5074.6 1486.62
  5104.6 1486.32  5111.6 1486.14  5114.4 1485.64  5117.6 1486.14  5124.6 1486.31
  5154.7 1486.48  5174.7 1486.17  5244.7 1486.61  5284.7  1486.4  5304.7 1486.99
  5327.9 1486.99  5344.8 1487.55  5364.8 1487.51  5394.8 1488.27  5414.8 1487.97
  5424.8  1488.4  5444.8 1488.54  5494.8 1489.67  5504.9 1489.36  5586.7 1490.69
#Mann= 3 , 0 , 0
  4724.3     .07       0  4944.5     .05       0  5244.7     .07       0
Bank Sta=4944.5,5244.7
XS Rating Curve= 0 ,0
Exp/Cntr=0.3,0.1

Type RM Length L Ch R = 1 ,833     ,205,205,205
BEGIN DESCRIPTION:
Mapping XS d4fbf13b
END DESCRIPTION:
XS GIS Cut Line= 2
      2808848.14     10052758.35      2808271.77     10052615.55
#Sta/Elev= 30
  4734.2 1490.57  4754.5 1490.21  4777.2 1489.04  4813.5 1488.53    4860 1487.42
  4867.8 1486.99  4919.3 1486.48  4942.8 1485.98  4960.5 1486.05  4970.8 1485.68
    4979 1486.02  4984.2 1485.94  4998.7 1485.24  5001.5 1484.74  5004.7 1485.24
    5012 1485.76  5020.4 1485.88    5067 1485.64  5084.1 1485.89  5115.1 1485.75
  5125.4 1486.22  5135.7 1486.11  5144.6 1486.39  5166.6 1486.47  5191.2 1486.26
  5238.7 1487.38    5274 1487.53  5279.9 1488.14  5290.2 1487.95    5328 1488.38
#Mann= 3 , 0 , 0
  4734.2     .07       0  4919.3     .05       0  5125.4     .07       0
Bank Sta=4919.3,5125.4
XS Rating Curve= 0 ,0
Exp/Cntr=0.3,0.1

Type RM Length L Ch R = 1 ,628     ,243,243,243
BEGIN DESCRIPTION:
Mapping XS 44993979
END DESCRIPTION:
XS GIS Cut Line= 3
      2808906.74     10052550.02      2808540.88     10052486.22
      2808328.61     10052547.42
#Sta/Elev= 30
  4728.1 1487.46    4767 1486.57  4787.3 1486.33  4793.1 1486.06  4827.9 1485.35
    4838 1485.06  4858.3 1484.87  4888.8 1484.89  4912.2 1484.61  4916.2 1484.53
    4919 1484.03  4922.2 1484.53  4959.8 1484.87  4971.7 1484.64  5010.6 1484.77
  5031.3 1484.61  5071.5 1485.18  5103.3 1485.34  5107.9 1485.77  5122.8 1486.09
  5141.5 1486.93  5164.4 1486.93  5180.4 1487.35  5206.1 1487.23  5214.1 1486.91
  5219.3 1487.11  5252.9 1486.98  5278.9 1487.11  5310.1 1487.54  5320.4 1487.89
#Mann= 3 ,-1 , 0
  4728.1     .07       0  4827.9     .05       0  5071.5     .07       0
Bank Sta=4827.9,5071.5
XS Rating Curve= 0 ,0
Exp/Cntr=0.3,0.1

Type RM Length L Ch R = 1 ,385     ,155,155,155
BEGIN DESCRIPTION:
Mapping XS 2dc00277
END DESCRIPTION:
XS GIS Cut Line= 3
      2808996.59     10052383.35      2808753.12     10052336.48
      2808393.73     10052521.38
#Sta/Elev= 30
  4814.4 1486.01  4843.5 1484.94  4863.4 1484.88  4895.4 1484.14  4942.2 1483.72
  4947.3 1483.92  4985.6 1483.06  4994.1 1482.48    4999 1481.41    5006 1482.45
  5016.2 1483.05    5046 1483.19  5051.1  1482.9  5064.8  1482.9  5070.2 1483.17
  5131.1 1483.26  5136.8 1483.57  5175.5 1483.45  5181.1 1483.99  5197.7 1483.53
  5219.8  1483.7  5330.7 1485.87  5347.3 1485.96  5352.9 1486.35  5369.4 1486.39
  5397.2  1487.3  5413.8 1487.01  5419.4 1487.25    5436 1486.62  5466.5 1487.02
#Mann= 3 ,-1 , 0
  4814.4     .07       0  4985.6     .05       0  5016.2     .07       0
#XS Ineff= 2 , 0
                         5181.78         1483.98
Permanent Ineff=
       F       F
Bank Sta=4985.6,5016.2
XS Rating Curve= 0 ,0
Exp/Cntr=0.3,0.1

Type RM Length L Ch R = 1 ,230     ,0,0,0
BEGIN DESCRIPTION:
UNT114 IN NNOGR 1.0
END DESCRIPTION:
XS GIS Cut Line= 4
       2808993.5     10052200.72      2808906.76      10052160.7
      2808754.42      10052223.2      2808630.75      10052366.4
#Sta/Elev= 30
  4809.3 1484.47  4904.8 1482.05  4922.6 1480.66    4928 1480.79  4946.2 1477.65
    4952 1475.99  4957.4    1476    4976 1472.82  4989.5 1472.34 4991.18 1471.23
 5004.02 1471.19  5005.3 1472.54  5021.9 1474.39  5029.3 1476.08  5043.5 1478.03
  5064.6 1479.94  5095.8 1480.93  5102.4 1480.63  5116.6 1481.47  5137.5 1480.67
  5145.2 1480.98  5151.8 1479.63  5159.4  1480.5    5166 1479.09  5173.7 1479.96
  5180.3 1478.82  5187.9  1480.2  5194.5 1480.06  5215.5 1482.02  5258.7  1482.8
#Mann= 3 , 0 , 0
  4809.3     .05       0  4989.5     .03       0  5005.3     .05       0
Bank Sta=4989.5,5005.3
XS Rating Curve= 0 ,0
Exp/Cntr=0.3,0.1

Chan Stop Cuts=-1
Use User Specified Reach Order=0
Composite Channel Slope=5