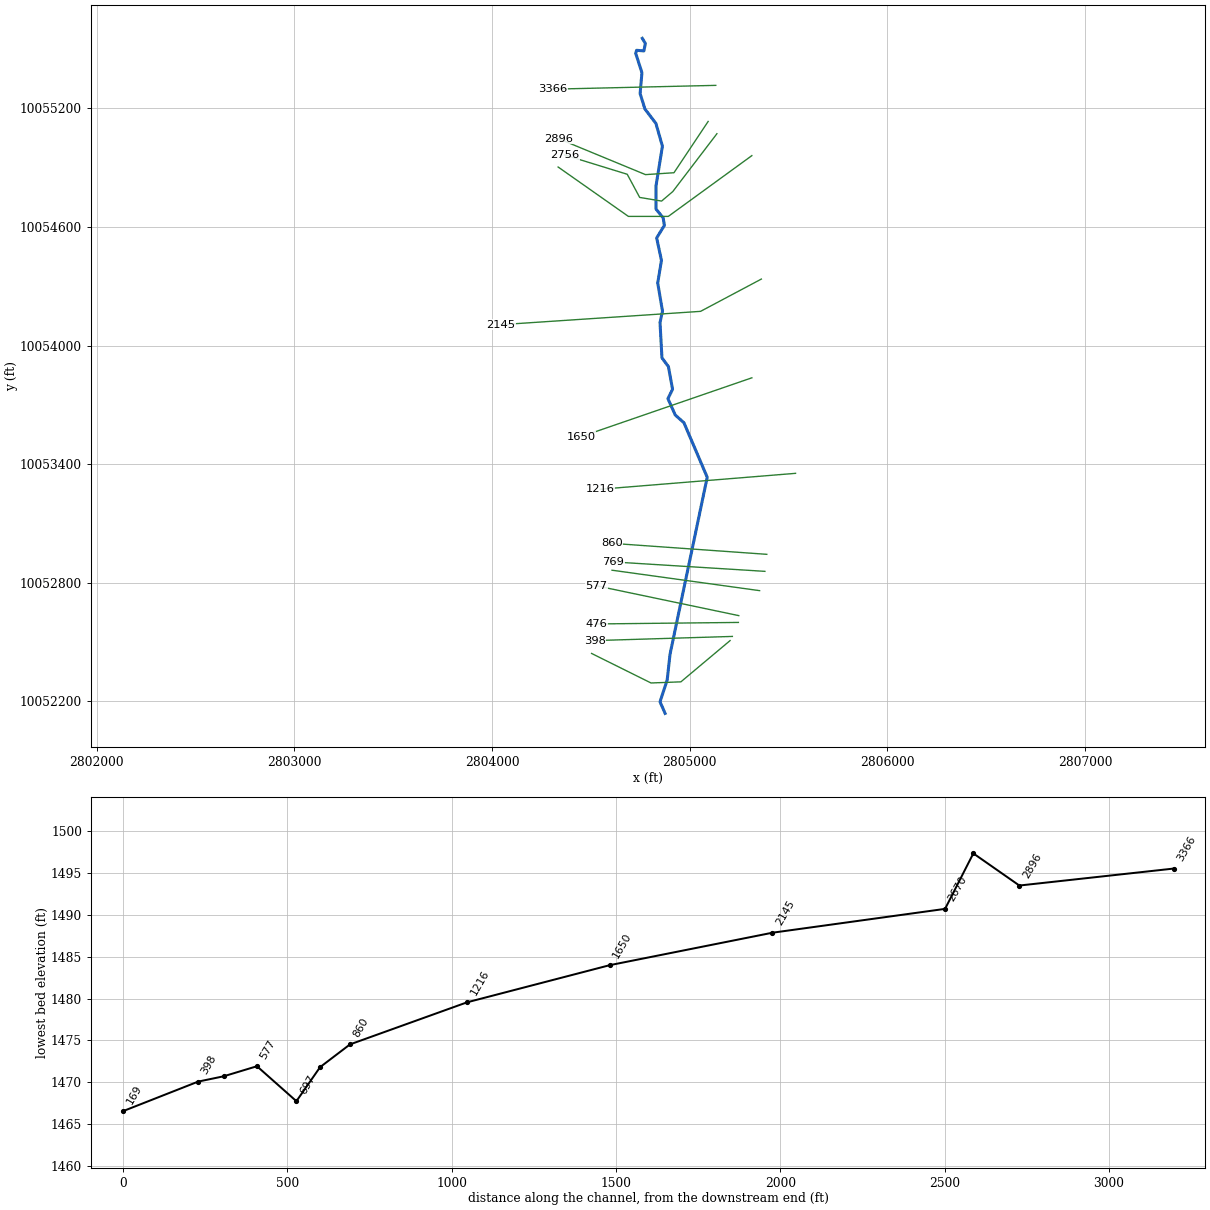
--- UNT115 IN NNOGR.prj (project) ---

Proj Title=UNT115 IN NNOGR Base Level Engineering
Current Plan=p01
Default Exp/Contr=0.3,0.1
English Units
Geom File=g01
Flow File=f01
Plan File=p01
BEGIN DESCRIPTION:
UNT115 IN NNOGR
END DESCRIPTION:

--- UNT115 IN NNOGR.p01 (plan) ---

Plan Title=Multiple Run
Short Identifier=Multiple
Geom File=g01
Flow File=f01
Subcritical Flow
K Sum by GR= 0
Std Step Tol= 0.01
Critical Tol= 0.01
Num of Std Step Trials= 20
Max Error Tol= 0.3
Flow Tol Ratio= 0.001
Split Flow NTrial= 30
Split Flow Tol= 0.02
Split Flow Ratio= 0.02
Log Output Level= 0
Friction Slope Method= 1
Unsteady Friction Slope Method= 2
Unsteady Bridges Friction Slope Method= 1
Parabolic Critical Depth
Global Vel Dist=  1 , 1 , 1
Global Log Level= 0
CheckData=True
Encroach Param= -1, 0, 0, 0
BEGIN DESCRIPTION:
Multiple Run
END DESCRIPTION:

--- UNT115 IN NNOGR.f01 (steady flow) ---

Flow Title=Multiple
Number of Profiles=7
Profile Names=10-year,25-year,50-year,1pct_min,100-year,1pct_plu,500-year
River Rch & RM= UNT115 IN NNOGR,Reach-1,3366
     359     491     598     536     725     980    1065
Boundary for River Rch & Prof#=UNT115 IN NNOGR,Reach-1,1
Up Type=0
Dn Type=3
Dn Slope=0.005
Boundary for River Rch & Prof#=UNT115 IN NNOGR,Reach-1,2
Up Type=0
Dn Type=3
Dn Slope=0.005
Boundary for River Rch & Prof#=UNT115 IN NNOGR,Reach-1,3
Up Type=0
Dn Type=3
Dn Slope=0.005
Boundary for River Rch & Prof#=UNT115 IN NNOGR,Reach-1,4
Up Type=0
Dn Type=3
Dn Slope=0.005
Boundary for River Rch & Prof#=UNT115 IN NNOGR,Reach-1,5
Up Type=0
Dn Type=3
Dn Slope=0.005
Boundary for River Rch & Prof#=UNT115 IN NNOGR,Reach-1,6
Up Type=0
Dn Type=3
Dn Slope=0.005
Boundary for River Rch & Prof#=UNT115 IN NNOGR,Reach-1,7
Up Type=0
Dn Type=3
Dn Slope=0.005

--- UNT115 IN NNOGR.g01 (geometry) ---

Geom Title=Existing Conditions

River Reach=UNT115 IN NNOGR,Reach-1
Reach XY= 30
      2804760.14     10055553.93      2804775.65     10055528.20
      2804768.34     10055490.26      2804731.14     10055493.45
      2804726.81     10055478.50      2804758.36     10055379.89
      2804749.16     10055274.65      2804773.47     10055196.52
      2804829.03     10055123.61      2804862.01     10055008.59
      2804829.46     10054806.77      2804829.46     10054690.45
      2804865.56     10054646.06      2804871.97     10054607.52
      2804832.80     10054544.21      2804857.08     10054430.74
      2804838.17     10054316.26      2804862.39     10054173.80
      2804849.88     10054116.79      2804859.58     10053937.50
      2804892.27     10053893.54      2804913.27     10053778.66
      2804889.79     10053731.25      2804927.12     10053648.24
      2804970.79     10053609.41      2805088.64     10053333.75
      2804900.39     10052437.94      2804886.28     10052309.17
      2804849.86     10052197.56      2804875.61     10052139.25

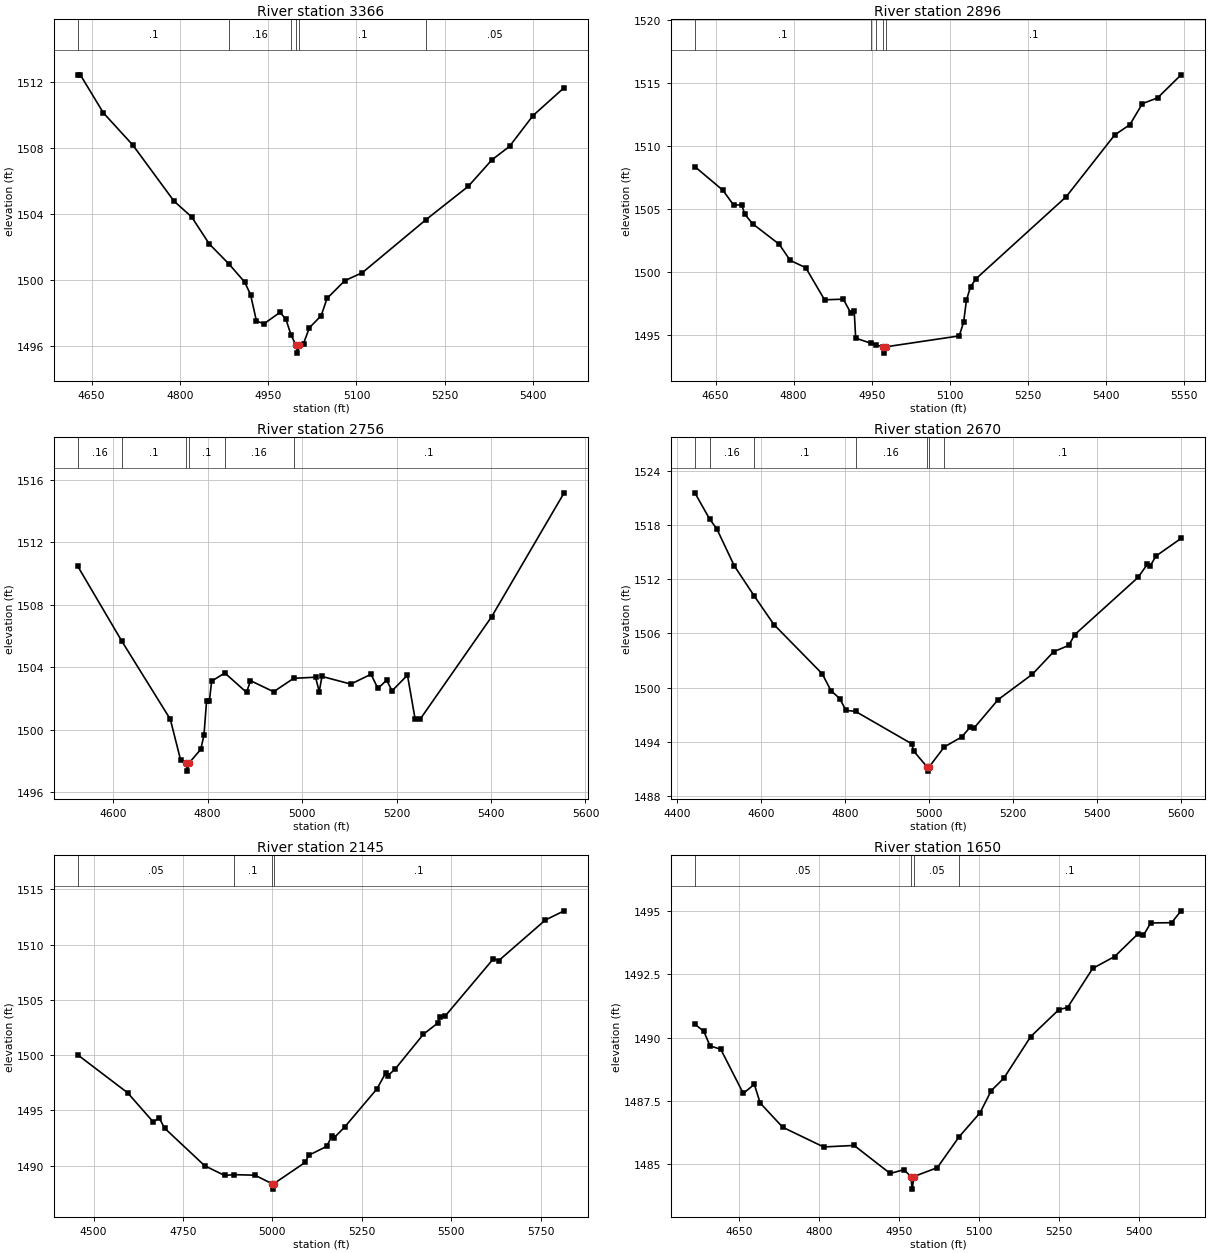
Type RM Length L Ch R = 1,3366,470,470,470
BEGIN DESCRIPTION:
UNT115 IN NNOGR 7.0
END DESCRIPTION:
XS GIS Cut Line= 2
      2805131.85     10055316.04      2804305.68     10055296.82
#Sta/Elev= 30
  4626.5 1512.43  4630.7 1512.43  4669.9 1510.12  4719.9 1508.17  4789.9 1504.77
  4819.9 1503.81  4849.9 1502.17  4883.2 1500.96  4910.0 1499.86  4920.0 1499.10
  4930.0 1497.50  4942.8 1497.33  4970.0 1498.02  4980.0 1497.62  4988.9 1496.64
  4997.0 1496.05  4999.7 1495.55  5003.0 1496.05  5010.0 1496.13  5020.0 1497.09
  5040.0 1497.82  5050.0 1498.87  5080.0 1499.94  5110.0 1500.43  5218.0 1503.64
  5290.1 1505.67  5330.1 1507.27  5360.1 1508.09  5400.1 1509.96  5452.9 1511.65
#Mann=6,-1,0
  4626.5     0.1       0  4883.2    0.16       0  4988.9     0.1       0
  4997.0    0.07       0  5003.0     0.1       0  5218.0    0.05       0
Bank Sta=4997,5003
Exp/Cntr=0.3,0.1

Type RM Length L Ch R = 1,2896,140,140,140
BEGIN DESCRIPTION:
Mapping XS 667a8ceb
END DESCRIPTION:
XS GIS Cut Line= 4
      2805093.39     10055133.47      2804920.50     10054874.14
      2804776.40     10054864.53      2804334.51     10055047.05
#Sta/Elev= 30
  4610.1 1508.35  4664.0 1506.47  4685.0 1505.27  4700.0 1505.33  4706.0 1504.57
  4721.0 1503.81  4772.1 1502.18  4793.2 1500.90  4823.2 1500.31  4859.3 1497.76
  4895.3 1497.81  4910.2 1496.68  4916.3 1496.85  4919.1 1494.71  4948.1 1494.31
  4958.2 1494.19  4970.9 1494.02  4973.7 1493.52  4976.9 1494.02  5118.1 1494.89
  5126.5 1495.99  5131.9 1497.73  5139.7 1498.79  5150.4 1499.44  5323.6 1505.96
  5416.7 1510.87  5446.0 1511.69  5469.9 1513.36  5499.2 1513.82  5544.3 1515.65
#Mann=5,-1,0
  4610.1     0.1       0  4948.1    0.16       0  4958.2     0.1       0
  4970.9    0.07       0  4976.9     0.1       0
Bank Sta=4970.9,4976.9
Exp/Cntr=0.3,0.1

Type RM Length L Ch R = 1,2756,86,86,86
BEGIN DESCRIPTION:
Mapping XS 5879067d
END DESCRIPTION:
XS GIS Cut Line= 6
      2805137.59     10055071.42      2804914.06     10054778.46
      2804857.64     10054730.71      2804746.96     10054749.16
      2804684.03     10054866.35      2804367.18     10054964.00
#Sta/Elev= 30
  4525.5 1510.46  4618.9 1505.66  4721.2 1500.68  4743.1 1498.06  4754.4 1497.86
  4757.1 1497.36  4760.4 1497.86  4785.8 1498.76  4792.5 1499.68  4797.9 1501.83
  4803.9 1501.83  4808.7 1503.12  4836.6 1503.64  4882.6 1502.40  4890.9 1503.15
  4939.9 1502.44  4982.4 1503.30  5028.6 1503.37  5036.5 1502.45  5042.2 1503.42
  5103.3 1502.93  5146.1 1503.56  5160.6 1502.65  5179.1 1503.18  5190.6 1502.50
  5223.2 1503.50  5239.5 1500.68  5250.0 1500.68  5401.4 1507.24  5554.8 1515.17
#Mann=6,-1,0
  4525.5    0.16       0  4618.9     0.1       0  4754.4    0.07       0
  4760.4     0.1       0  4836.6    0.16       0  4982.4     0.1       0
Bank Sta=4754.4,4760.4
Exp/Cntr=0.3,0.1

Type RM Length L Ch R = 1,2670,525,525,525
BEGIN DESCRIPTION:
UNT115 IN NNOGR 6.0
END DESCRIPTION:
XS GIS Cut Line= 4
      2805314.41     10054960.62      2804891.68     10054653.19
      2804689.95     10054653.19      2804334.47     10054902.98
#Sta/Elev= 30
  4441.5 1521.58  4476.7 1518.68  4493.9 1517.58  4535.7 1513.47  4582.6 1510.18
  4629.9 1506.98  4745.1 1501.52  4766.0 1499.64  4786.8 1498.78  4801.5 1497.47
  4824.5 1497.35  4958.4 1493.76  4963.1 1492.95  4994.4 1491.23  4997.2 1490.73
  5000.4 1491.23  5036.1 1493.42  5077.4 1494.51  5097.4 1495.59  5107.4 1495.53
  5164.2 1498.65  5246.2 1501.48  5296.7 1503.97  5332.4 1504.66  5347.2 1505.87
  5497.7 1512.20  5519.8 1513.65  5525.9 1513.42  5540.7 1514.58  5600.4 1516.53
#Mann=7,-1,0
  4441.5     0.1       0  4476.7    0.16       0  4582.6     0.1       0
  4824.5    0.16       0  4994.4    0.07       0  5000.4    0.16       0
  5036.1     0.1       0
Bank Sta=4994.4,5000.4
Exp/Cntr=0.3,0.1

Type RM Length L Ch R = 1,2145,495,495,495
BEGIN DESCRIPTION:
UNT115 IN NNOGR 4.0
END DESCRIPTION:
XS GIS Cut Line= 3
      2805362.44     10054336.20      2805054.99     10054172.87
      2804046.27     10054105.62
#Sta/Elev= 30
  4456.2 1500.02  4595.5 1496.59  4667.1 1493.95  4683.4 1494.33  4698.5 1493.40
  4810.9 1489.99  4866.2 1489.12  4892.3 1489.19  4951.2 1489.14  4998.3 1488.38
  5001.1 1487.88  5004.3 1488.38  5091.5 1490.30  5101.5 1490.94  5151.6 1491.75
  5166.9 1492.71  5171.9 1492.51  5201.7 1493.49  5291.9 1496.94  5317.2 1498.42
  5322.2 1498.14  5342.1 1498.71  5422.2 1501.90  5462.3 1502.91  5467.6 1503.46
  5482.4 1503.52  5617.9 1508.73  5632.7 1508.56  5763.0 1512.23  5815.3 1513.06
#Mann=4,-1,0
  4456.2    0.05       0  4892.3     0.1       0  4998.3    0.07       0
  5004.3     0.1       0
Bank Sta=4998.3,5004.3
Exp/Cntr=0.3,0.1

Type RM Length L Ch R = 1,1650,434,434,434
BEGIN DESCRIPTION:
UNT115 IN NNOGR 3.0
END DESCRIPTION:
XS GIS Cut Line= 2
      2805314.39     10053836.64      2804451.63     10053539.47
#Sta/Elev= 30
  4567.4 1490.53  4584.2 1490.25  4595.9 1489.67  4616.0 1489.54  4658.3 1487.79
  4679.0 1488.15  4690.0 1487.41  4732.3 1486.45  4809.1 1485.67  4866.3 1485.73
  4934.0 1484.62  4959.9 1484.77  4972.6 1484.50  4975.3 1484.00  4978.6 1484.50
  5022.4 1484.85  5063.6 1486.08  5102.5 1487.02  5123.6 1487.90  5147.2 1488.39
  5197.7 1490.04  5250.6 1491.11  5266.8 1491.19  5314.0 1492.74  5355.2 1493.21
  5398.6 1494.10  5409.2 1494.05  5422.9 1494.54  5462.1 1494.55  5479.9 1495.02
#Mann=4,-1,0
  4567.4    0.05       0  4972.6    0.03       0  4978.6    0.05       0
  5063.6     0.1       0
Bank Sta=4972.6,4978.6
Exp/Cntr=0.3,0.1

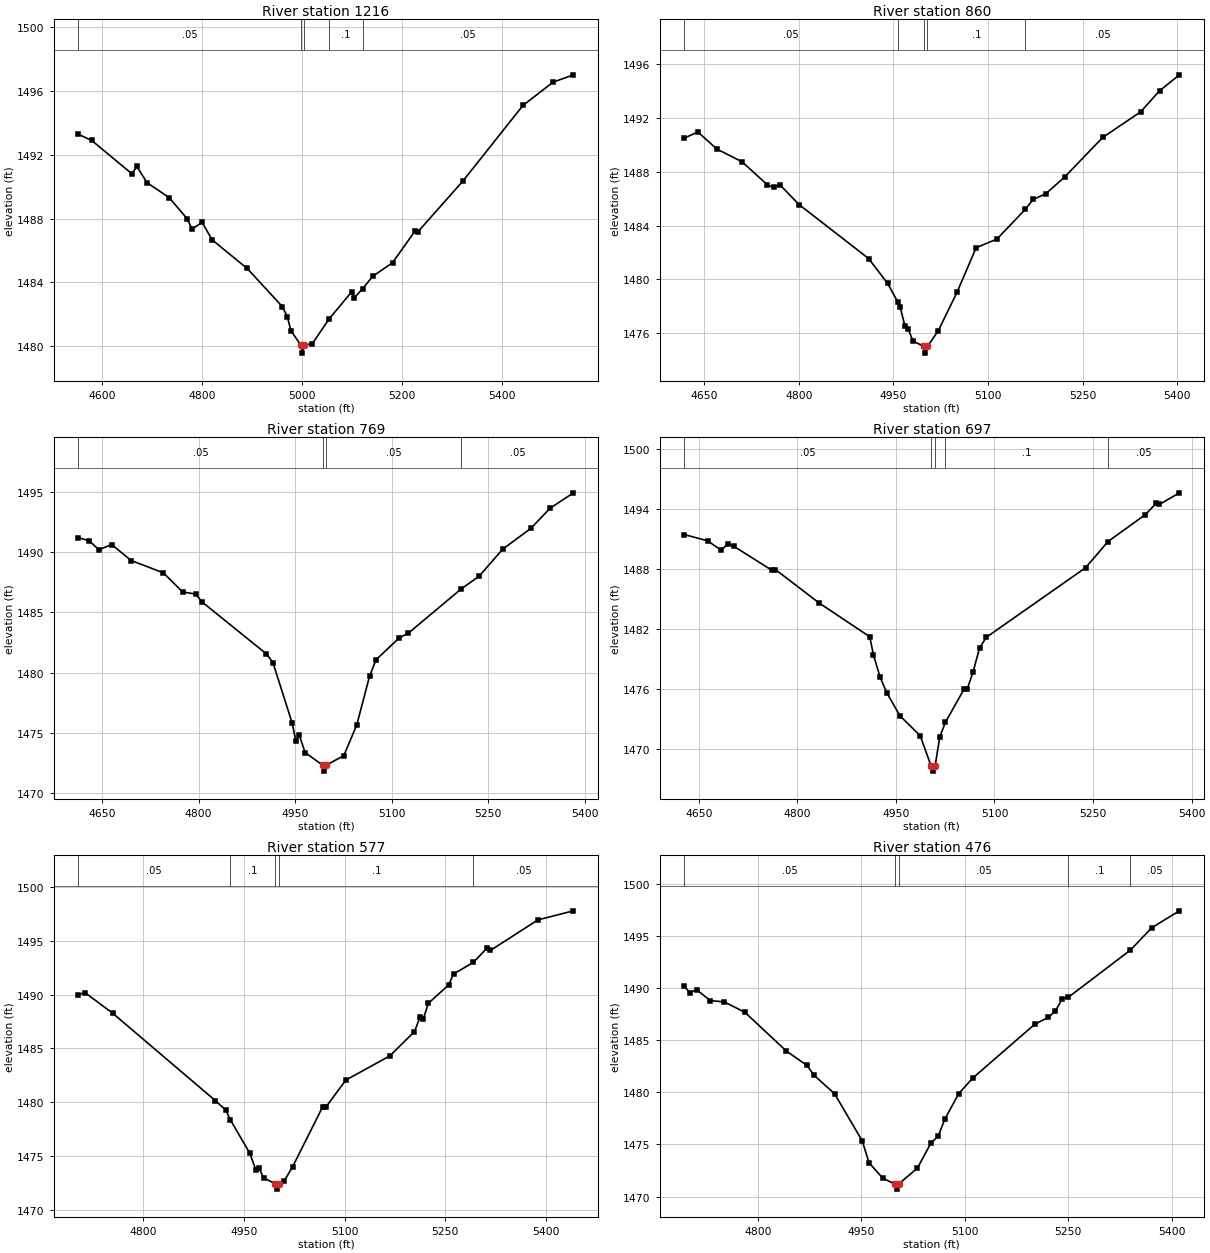
Type RM Length L Ch R = 1,1216,356,356,356
BEGIN DESCRIPTION:
Mapping XS 4eba99fb
END DESCRIPTION:
XS GIS Cut Line= 2
      2805535.40     10053353.45      2804547.76     10053273.06
#Sta/Elev= 30
  4551.9 1493.29  4578.9 1492.90  4659.2 1490.81  4669.2 1491.27  4689.3 1490.26
  4733.9 1489.31  4769.5 1488.00  4779.6 1487.34  4799.6 1487.77  4819.7 1486.67
  4889.9 1484.87  4960.2 1482.48  4970.2 1481.85  4977.5 1480.96  4997.3 1480.06
  5000.1 1479.56  5003.3 1480.06  5020.4 1480.16  5053.9 1481.71  5099.4 1483.42
  5104.4 1483.04  5121.0 1483.61  5140.8 1484.37  5180.9 1485.24  5226.2 1487.24
  5231.2 1487.16  5321.4 1490.35  5441.8 1495.10  5502.0 1496.56  5542.8 1497.02
#Mann=5,-1,0
  4551.9    0.05       0  4997.3    0.03       0  5003.3    0.05       0
  5053.9     0.1       0  5121.0    0.05       0
Bank Sta=4997.3,5003.3
Exp/Cntr=0.3,0.1

Type RM Length L Ch R = 1,860,91,91,91
BEGIN DESCRIPTION:
UNT115 IN NNOGR 2.0
END DESCRIPTION:
XS GIS Cut Line= 2
      2805389.95     10052943.83      2804607.11     10052999.34
#Sta/Elev= 30
  4618.6 1490.49  4640.1 1490.95  4670.2 1489.68  4710.3 1488.73  4750.4 1487.02
  4760.4 1486.83  4770.5 1487.01  4800.5 1485.56  4910.8 1481.55  4940.9 1479.70
  4957.1 1478.33  4960.9 1477.93  4968.3 1476.54  4973.3 1476.35  4981.0 1475.43
  4998.0 1475.03  5000.8 1474.53  5004.0 1475.03  5021.1 1476.19  5051.2 1479.08
  5081.2 1482.36  5114.2 1483.00  5159.0 1485.20  5171.5 1485.94  5191.5 1486.36
  5221.6 1487.61  5281.7 1490.54  5341.9 1492.44  5372.0 1494.01  5403.4 1495.19
#Mann=5,-1,0
  4618.6    0.05       0  4957.1     0.1       0  4998.0    0.07       0
  5004.0     0.1       0  5159.0    0.05       0
Bank Sta=4998,5004
Exp/Cntr=0.3,0.1

Type RM Length L Ch R = 1,769,72,72,72
BEGIN DESCRIPTION:
Mapping XS 945eacd8
END DESCRIPTION:
XS GIS Cut Line= 2
      2805380.36     10052857.70      2804612.24     10052905.47
#Sta/Elev= 30
  4613.0 1491.20  4629.8 1490.94  4645.0 1490.20  4665.0 1490.62  4695.1 1489.30
  4745.1 1488.28  4775.2 1486.69  4795.5 1486.51  4805.3 1485.86  4905.5 1481.54
  4915.5 1480.83  4945.5 1475.78  4951.2 1474.28  4956.2 1474.83  4965.6 1473.35
  4992.6 1472.31  4995.4 1471.81  4998.6 1472.31  5025.7 1473.10  5045.7 1475.63
  5065.8 1479.71  5075.8 1481.06  5111.9 1482.88  5125.9 1483.26  5208.1 1486.94
  5236.1 1488.00  5272.6 1490.24  5316.2 1491.96  5346.3 1493.64  5382.6 1494.92
#Mann=4,-1,0
  4613.0    0.05       0  4992.6    0.07       0  4998.6    0.05       0
  5208.1    0.05       0
Bank Sta=4992.6,4998.6
Exp/Cntr=0.3,0.1

Type RM Length L Ch R = 1,697,120,120,120
BEGIN DESCRIPTION:
Mapping XS 12e865a2
END DESCRIPTION:
XS GIS Cut Line= 2
      2805353.58     10052760.08      2804607.10     10052863.44
#Sta/Elev= 30
  4627.9 1491.42  4663.3 1490.80  4683.5 1489.88  4694.8 1490.46  4703.7 1490.23
  4761.6 1487.83  4766.6 1487.92  4833.4 1484.56  4910.2 1481.19  4915.7 1479.40
  4925.8 1477.17  4935.9 1475.61  4956.1 1473.28  4987.0 1471.28  5003.6 1468.24
  5006.3 1467.74  5009.6 1468.24  5016.7 1471.16  5025.3 1472.63  5053.8 1475.96
  5058.8 1476.01  5067.2 1477.62  5077.3 1480.07  5087.4 1481.13  5238.8 1488.11
  5272.7 1490.72  5329.6 1493.42  5346.0 1494.54  5351.0 1494.44  5381.5 1495.60
#Mann=5,-1,0
  4627.9    0.05       0  5003.6    0.03       0  5009.6    0.05       0
  5025.3     0.1       0  5272.7    0.05       0
Bank Sta=5003.6,5009.6
Exp/Cntr=0.3,0.1

Type RM Length L Ch R = 1,577,101,101,101
BEGIN DESCRIPTION:
Mapping XS 34fa5c25
END DESCRIPTION:
XS GIS Cut Line= 2
      2805248.36     10052633.74      2804526.73     10052784.95
#Sta/Elev= 30
  4703.5 1490.01  4713.6 1490.18  4754.5 1488.28  4907.7 1480.14  4923.0 1479.27
  4929.8 1478.38  4958.8 1475.26  4967.8 1473.73  4972.9 1473.84  4979.3 1472.97
  4996.7 1472.42  4999.4 1471.92  5002.7 1472.42  5009.9 1472.66  5022.8 1474.02
  5067.6 1479.60  5072.7 1479.59  5101.9 1482.06  5167.5 1484.31  5204.0 1486.56
  5212.3 1487.89  5217.4 1487.74  5224.5 1489.18  5255.1 1490.91  5262.2 1491.92
  5291.9 1493.00  5312.1 1494.33  5317.2 1494.11  5387.9 1496.95  5440.8 1497.79
#Mann=5,-1,0
  4703.5    0.05       0  4929.8     0.1       0  4996.7    0.07       0
  5002.7     0.1       0  5291.9    0.05       0
Bank Sta=4996.7,5002.7
Exp/Cntr=0.3,0.1

Type RM Length L Ch R = 1,476,78,78,78
BEGIN DESCRIPTION:
Mapping XS c36cf0e1
END DESCRIPTION:
XS GIS Cut Line= 2
      2805246.36     10052599.29      2804528.60     10052591.63
#Sta/Elev= 30
  4693.5 1490.16  4701.4 1489.57  4711.4 1489.83  4731.4 1488.79  4751.4 1488.67
  4781.4 1487.67  4841.4 1483.96  4871.4 1482.58  4881.4 1481.65  4911.4 1479.86
  4951.4 1475.35  4961.4 1473.24  4981.4 1471.76  4998.4 1471.22  5001.2 1470.72
  5004.4 1471.22  5031.4 1472.73  5051.4 1475.18  5061.4 1475.77  5071.4 1477.46
  5091.4 1479.88  5111.4 1481.35  5201.4 1486.52  5221.4 1487.19  5231.4 1487.80
  5241.4 1488.95  5250.2 1489.11  5340.3 1493.64  5371.4 1495.79  5411.3 1497.40
#Mann=5,-1,0
  4693.5    0.05       0  4998.4    0.04       0  5004.4    0.05       0
  5250.2     0.1       0  5340.3    0.05       0
Bank Sta=4998.4,5004.4
Exp/Cntr=0.3,0.1

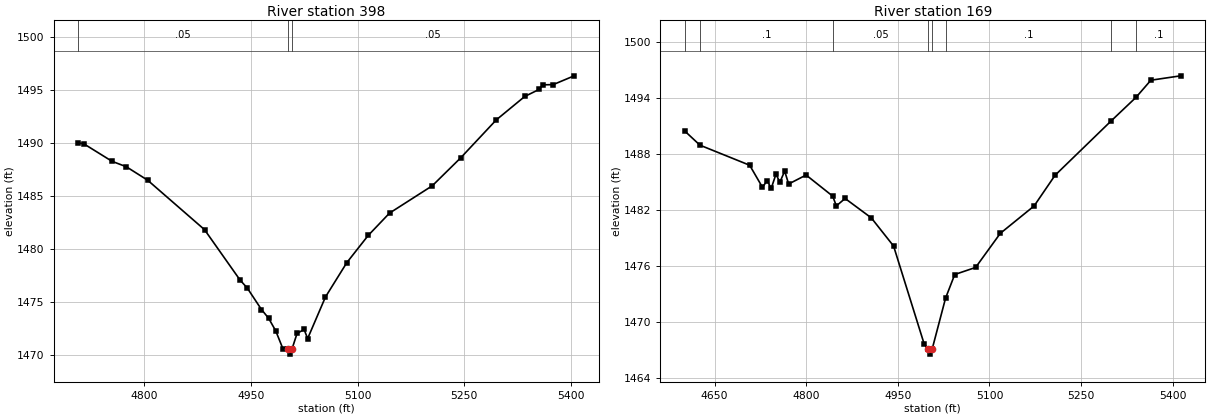
Type RM Length L Ch R = 1,398,229,229,229
BEGIN DESCRIPTION:
Mapping XS c553a109
END DESCRIPTION:
XS GIS Cut Line= 2
      2805215.80     10052528.47      2804519.02     10052507.41
#Sta/Elev= 30
  4707.3 1490.01  4714.6 1489.95  4754.7 1488.28  4774.7 1487.77  4804.7 1486.50
  4884.7 1481.83  4934.7 1477.07  4944.7 1476.33  4964.8 1474.29  4974.8 1473.47
  4984.8 1472.28  4994.8 1470.61  5001.8 1470.58  5004.5 1470.08  5007.8 1470.58
  5014.8 1472.03  5024.7 1472.41  5029.7 1471.55  5054.8 1475.48  5084.8 1478.72
  5114.8 1481.28  5144.8 1483.39  5204.9 1485.97  5244.9 1488.61  5294.9 1492.19
  5334.9 1494.40  5354.9 1495.06  5360.3 1495.50  5374.9 1495.52  5404.4 1496.35
#Mann=3,-1,0
  4707.3    0.05       0  5001.8    0.04       0  5007.8    0.05       0
Bank Sta=5001.8,5007.8
Exp/Cntr=0.3,0.1

Type RM Length L Ch R = 1,169,0,0,0
BEGIN DESCRIPTION:
UNT115 IN NNOGR 1.0
END DESCRIPTION:
XS GIS Cut Line= 4
      2805204.34     10052507.44      2804955.46     10052298.77
      2804804.25     10052293.03      2804503.70     10052442.35
#Sta/Elev= 30
  4601.2 1490.44  4626.0 1488.93  4707.4 1486.78  4728.3 1484.42  4736.1 1485.13
  4742.6 1484.29  4750.4 1485.81  4756.9 1484.97  4764.7 1486.15  4771.2 1484.77
  4799.8 1485.73  4843.3 1483.47  4849.3 1482.42  4863.6 1483.22  4906.5 1481.14
  4943.0 1478.12  4993.0 1467.64  5000.0 1467.04  5002.8 1466.54  5006.0 1467.04
  5028.1 1472.54  5043.1 1475.07  5077.3 1475.83  5117.7 1479.48  5173.1 1482.42
  5207.3 1485.70  5299.2 1491.53  5339.8 1494.05  5364.2 1495.89  5412.9 1496.36
#Mann=8,-1,0
  4601.2    0.05       0  4626.0     0.1       0  4843.3    0.05       0
  5000.0   0.035       0  5006.0    0.05       0  5028.1     0.1       0
  5299.2    0.16       0  5339.8     0.1       0
Bank Sta=5000,5006
Exp/Cntr=0.3,0.1

Chan Stop Cuts=-1