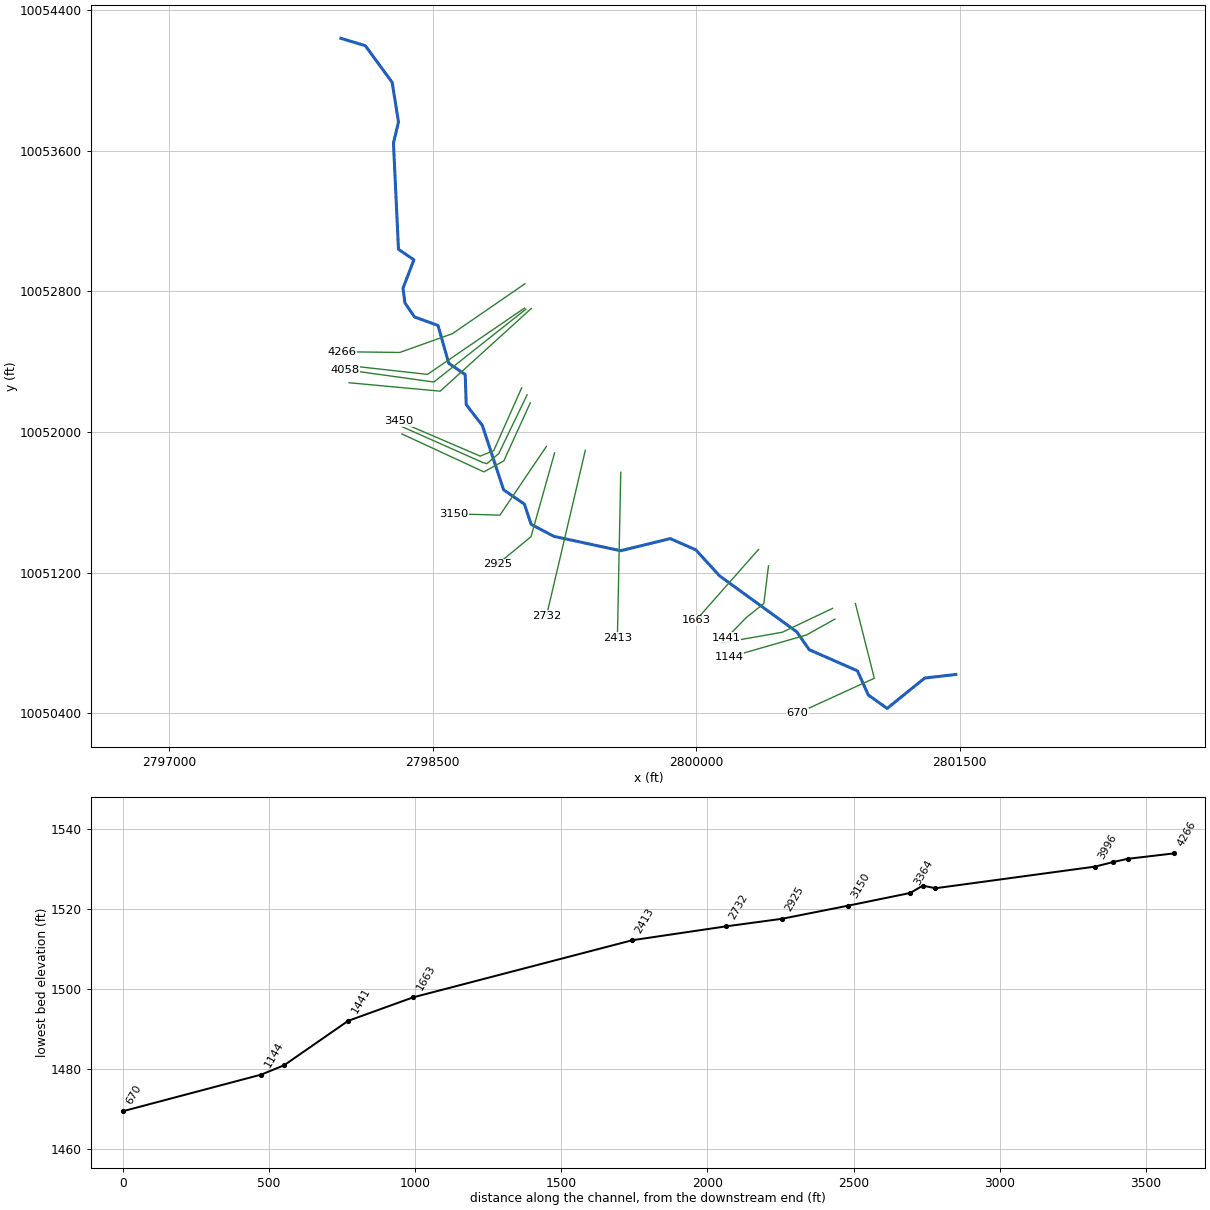
--- UNT116 IN NNOGR.prj (project) ---

Proj Title=UNT116 IN NNOGR Base Level Engineering
Current Plan=p01
Default Exp/Contr=0.3,0.1
English Units
Geom File=g01
Flow File=f01
Plan File=p01
Y Axis Title=Elevation
X Axis Title(PF)=Main Channel Distance
X Axis Title(XS)=Station
BEGIN DESCRIPTION:
UNT116 IN NNOGR
END DESCRIPTION:
DSS File=dss
DSS Export Rating Curves= 0
DSS Export Rating Curve Sorted= 0
DSS Export Volume Flow Curves= 0
DXF OffsetX= 0
DXF OffsetY= 0
DXF ScaleX= 1
DXF ScaleY= 10

--- UNT116 IN NNOGR.p01 (plan) ---

Plan Title=Multiple Run
Program Version=4.10
Short Identifier=Multiple Run
Geom File=g01
Flow File=f01
Subcritical Flow
K Sum by GR= 0
Std Step Tol= 0.01
Critical Tol= 0.01
Num of Std Step Trials= 20
Max Error Tol= 0.3
Flow Tol Ratio= 0.001
Split Flow NTrial= 30
Split Flow Tol= 0.02
Split Flow Ratio= 0.02
Log Output Level= 0
Friction Slope Method= 1
Unsteady Friction Slope Method= 2
Unsteady Bridges Friction Slope Method= 1
Parabolic Critical Depth
Global Vel Dist= 1 , 1 , 1
Global Log Level= 0
CheckData=True
Encroach Param=-1 ,0,0, 0
BEGIN DESCRIPTION:
Multiple Run
END DESCRIPTION:
Computation Interval=1HOUR
Output Interval=1HOUR
Run HTab= 0
Run UNet= 0
Run PostProcess= 0
Run WQNet= 0
UNET Theta= 1
UNET Theta Warmup= 1
UNET ZTol= 0.02
UNET ZSATol= 0.05
UNET MxIter= 20
UNET MaxInSteps= 0
UNET DtIC= 0
UNET DtMin= 0
UNET MaxCRTS= 20
UNET WFStab= 2
UNET SFStab= 1
UNET WFX= 1
UNET SFX= 1
UNET DSS MLevel= 4
UNET DZMax Abort= 100
UNET Convert EG Bridges= 0
UNET Use Existing IB Tables=-1
UNET Froude Reduction=False
UNET Froude Limit= 1
UNET Froude Power= 10
UNET Time Slicing=0,0, 5
UNET Junction Losses=0
Instantaneous Interval=1HOUR
DSS File=dss
Write IC File= 0
Write IC File at Sim End=0
Echo Input=False
Echo Parameters=False
Echo Output=False
Write Detailed= 0
WQ AD Non Conservative
WQ ULTIMATE=-1
WQ Max Comp Step=1HOUR
WQ Output Interval=15MIN
WQ Output Selected Increments= 0
WQ Output face flow=0
WQ Output face velocity=0
WQ Output face area=0
WQ Output face dispersion=0
WQ Output cell volume=0
WQ Output cell surface area=0
WQ Output cell continuity=0
WQ Output cumulative cell continuity=0
WQ Output face conc=0
WQ Output face dconc_dx=0
WQ Output face courant=0
WQ Output face peclet=0
WQ Output face adv mass=0
WQ Output face disp mass=0
WQ Output cell mass=0
WQ Output cell source sink temp=0
WQ Output cell source sink nsm=0
WQ Output MaxMinRange=-1
WQ Daily Max Min Mean=-1
WQ Daily Range=0
WQ Daily Time=0
WQ Create Restart=0
WQ Fixed Restart=0
WQ System Summary=0
WQ Use Fixed Temperature=0
Sorting and Armoring Iterations= 10
XS Update Threshold= 0.02
Hydraulics Update Threshold= 0.02
Energy Slope Method= 1
Volume Change Method= 0
XS Weighting Method= 0
Number of US Weighted Cross Sections= 1
Number of DS Weighted Cross Sections= 1
Upstream XS Weight=0.25
Main XS Weight=0.5
Downstream XS Weight=0.25
Number of DS XS's Weighted with US Boundary= 1
Upstream Boundary Weight= 1
Weight of XSs Associated with US Boundary= 0
Number of US XS's Weighted with DS Boundary= 1
Downstream Boundary Weight= 0.5
Weight of XSs Associated with DS Boundary= 0.5
Sediment Output Level= 4
Mass or Volume Output= 0
Output Increment Type= 1
Profile and TS Output Increment= 10
XS Output Flag= 0
XS Output Increment= 10
Disregard all LS=0
Disregard all Conn=0
Disregard all Breaches=0
Disregard all Pumps=0

--- UNT116 IN NNOGR.f01 (steady flow) ---

Flow Title=Multiple
Program Version=4.10
Number of Profiles= 7
Profile Names=10-year,25-year,50-year,1pct_min,100-year,1pct_plu,500-year
River Rch & RM=UNT116 IN NNOGR,Reach-1         ,4266
     266     354     424     373     505     683     715
Boundary for River Rch & Prof#=UNT116 IN NNOGR,Reach-1         , 1
Up Type= 0
Dn Type= 3
Dn Slope=0.005
Boundary for River Rch & Prof#=UNT116 IN NNOGR,Reach-1         , 2
Up Type= 0
Dn Type= 3
Dn Slope=0.005
Boundary for River Rch & Prof#=UNT116 IN NNOGR,Reach-1         , 3
Up Type= 0
Dn Type= 3
Dn Slope=0.005
Boundary for River Rch & Prof#=UNT116 IN NNOGR,Reach-1         , 4
Up Type= 0
Dn Type= 3
Dn Slope=0.005
Boundary for River Rch & Prof#=UNT116 IN NNOGR,Reach-1         , 5
Up Type= 0
Dn Type= 3
Dn Slope=0.005
Boundary for River Rch & Prof#=UNT116 IN NNOGR,Reach-1         , 6
Up Type= 0
Dn Type= 3
Dn Slope=0.005
Boundary for River Rch & Prof#=UNT116 IN NNOGR,Reach-1         , 7
Up Type= 0
Dn Type= 3
Dn Slope=0.005
DSS Import GetInterval= 0
DSS Import GetPeak= 0
DSS Import FillOption= 0

--- UNT116 IN NNOGR.g01 (geometry) ---

Geom Title=Existing Conditions
Program Version=4.10

River Reach=UNT116 IN NNOGR ,Reach-1
Reach XY= 30
      2797976.67     10054239.51      2798115.56     10054197.85
      2798268.47     10053988.73      2798304.34     10053763.74
      2798275.78     10053643.66      2798304.35     10053039.48
      2798392.14     10052979.64      2798330.17     10052818.22
      2798340.86     10052734.73       2798395.4     10052654.68
      2798529.41     10052606.13      2798590.54     10052391.03
      2798684.16     10052326.92      2798689.99     10052155.97
      2798781.14       10052038.      2798902.99      10051670.8
      2799021.04     10051590.15      2799059.51     10051474.91
      2799189.59     10051406.45      2799568.96     10051324.81
      2799851.32     10051393.78      2799996.91      10051329.9
      2800132.54     10051181.57      2800571.57     10050863.37
      2800642.64     10050761.76      2800917.14     10050641.35
      2800979.06     10050503.85      2801085.82     10050427.81
      2801299.76     10050600.62      2801476.79     10050620.96

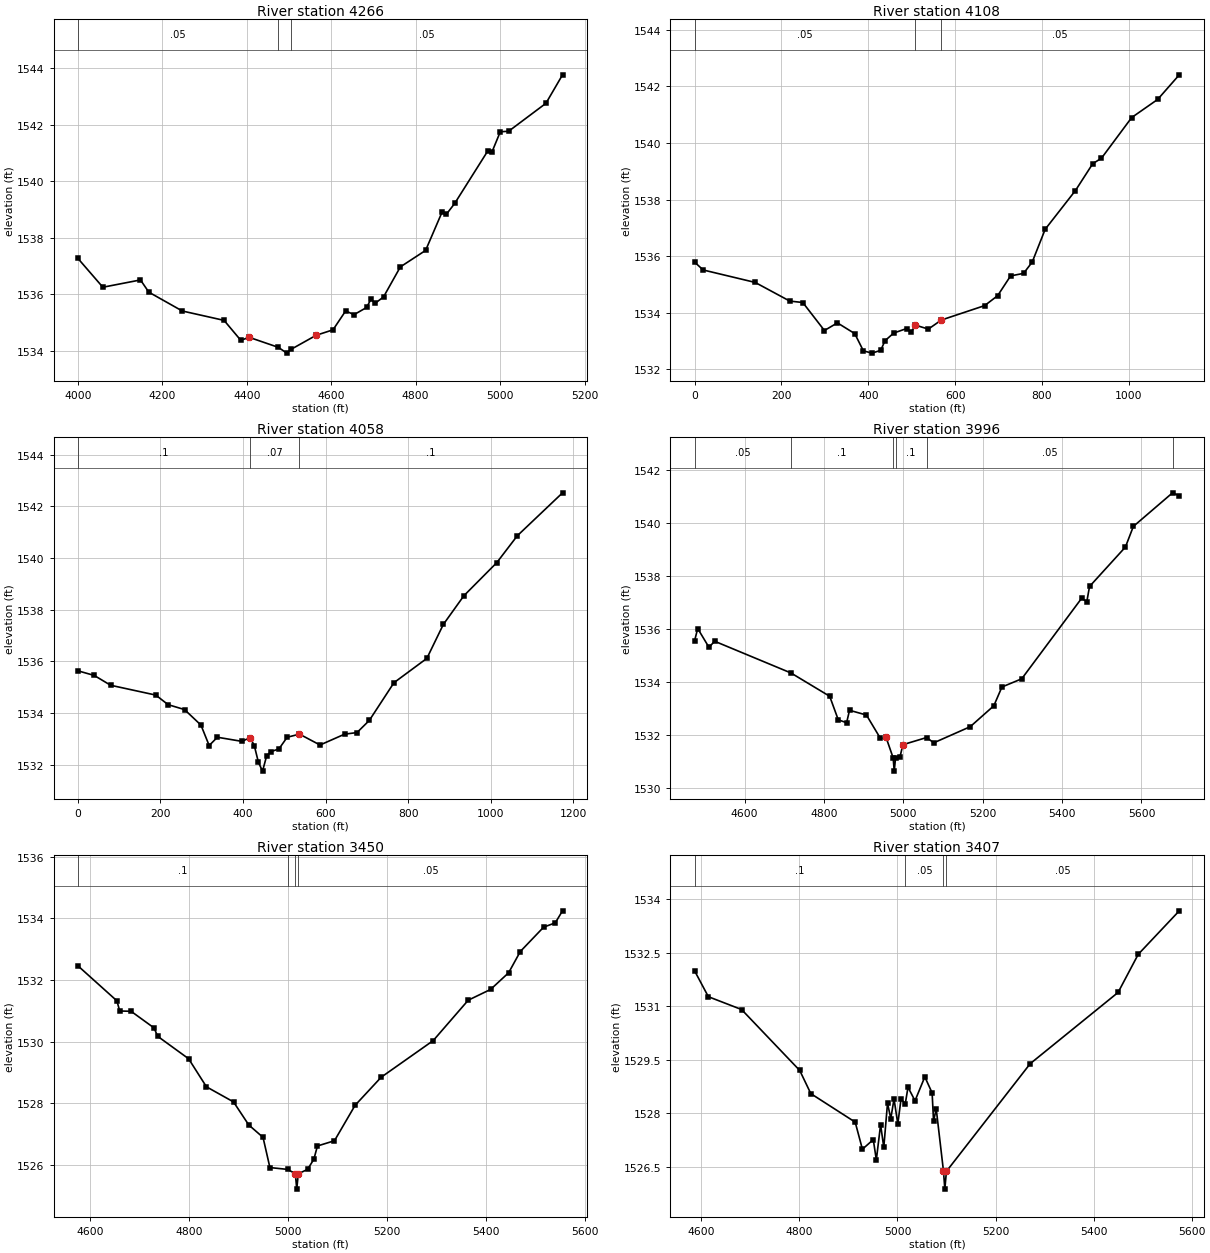
Type RM Length L Ch R = 1 ,4266    ,158,158,158
BEGIN DESCRIPTION:
Mapping XS ab62ff2c
END DESCRIPTION:
XS GIS Cut Line= 4
     2799024.108    10052843.369     2798611.348    10052559.515
     2798311.868    10052452.744     2797985.045    10052456.651
#Sta/Elev= 30
    40001537.279 4059.381536.254 4148.451536.512 4168.25 1536.08 4247.421535.414
 4346.391535.082 4385.971534.377 4405.771534.483 4475.051534.128 4494.841533.924
 4504.741534.056 4564.461534.555 4604.321534.748 4634.221535.416 4654.151535.285
 4684.04 1535.54 4694.01 1535.83 4703.971535.685 4723.91 1535.91 4763.771536.973
 4823.561537.556 4862.861538.922 4872.681538.833 4892.331539.215 4970.931541.077
 4980.761541.039 5000.411541.752 5020.061541.769 5108.481542.758 5147.781543.765
#Mann= 3 ,-1 , 0
    4000     .05       0 4475.05     .03       0 4504.74     .05       0
Bank Sta=4405.77,4564.46
XS Rating Curve= 0 ,0
Exp/Cntr=0.3,0.1

Type RM Length L Ch R = 1 ,4108    ,50,50,50
XS GIS Cut Line= 3
     2799021.289    10052704.766     2798469.348    10052327.933
     2798016.868    10052378.364
#Sta/Elev= 30
       0 1535.79   19.94 1535.51  139.57 1535.07  219.33 1534.41  249.23 1534.36
  299.08 1533.37  328.99 1533.64  368.87 1533.26  388.81 1532.65  408.74 1532.57
  428.68 1532.67  438.65 1533.01  458.59 1533.28   488.5 1533.44  498.47  1533.3
  508.44 1533.56  538.35 1533.42  568.26 1533.74  667.95 1534.25  697.83  1534.6
   727.7  1535.3  757.58 1535.39   777.5 1535.79  807.38 1536.95  877.09 1538.32
  916.93 1539.27  936.85 1539.46 1006.56  1540.9 1066.32 1541.54 1116.11 1542.41
#Mann= 3 , 0 , 0
       0     .05       0  508.44     .03       0  568.26     .05       0
Bank Sta=508.44,568.26
XS Rating Curve= 0 ,0
Exp/Cntr=0.3,0.1

Type RM Length L Ch R = 1 ,4058    ,62,62,62
XS GIS Cut Line= 3
     2799029.694    10052699.163      2798505.77    10052284.506
     2798001.458     10052354.55
#Sta/Elev= 30
       0 1535.64   39.76 1535.46   79.52 1535.08  188.86  1534.7  218.67 1534.33
  258.43 1534.14  298.19 1533.54  318.07 1532.75  337.95 1533.07  397.59 1532.91
  417.47 1533.06  427.41 1532.74  437.35  1532.1  447.29 1531.76  457.23 1532.35
  467.17 1532.51  487.05 1532.62  506.93 1533.07  536.75 1533.19  586.45 1532.77
  646.08 1533.19  675.92 1533.25  705.77 1533.72  765.49 1535.18  845.11 1536.12
  884.92 1537.43  934.68 1538.54  1014.3 1539.82 1064.06 1540.86 1173.54 1542.52
#Mann= 3 , 0 , 0
       0      .1       0  417.47     .07       0  536.75      .1       0
Bank Sta=417.47,536.75
XS Rating Curve= 0 ,0
Exp/Cntr=0.3,0.1

Type RM Length L Ch R = 1 ,3996    ,546,546,546
BEGIN DESCRIPTION:
UNT116 IN NNOGR 8.0
END DESCRIPTION:
XS GIS Cut Line= 3
      2799060.55     10052703.08       2798541.8     10052232.36
       2798023.3     10052280.36
#Sta/Elev= 30
    4474 1535.54    4482 1536.01  4510.4  1535.3  4524.6 1535.53    4717 1534.33
  4814.5 1533.45  4836.1 1532.56  4857.1 1532.45  4864.5 1532.92  4907.1 1532.74
  4942.2 1531.86  4956.4  1531.9  4974.4 1531.12  4977.1 1530.62  4980.4 1531.12
  4991.6 1531.16    4999 1531.62  5058.7 1531.89  5076.7 1531.69  5168.6  1532.3
    5228 1533.09  5248.4  1533.8  5298.3 1534.11    5449 1537.15  5462.3 1537.03
  5469.1  1537.6  5559.5 1539.09  5579.5 1539.87  5678.2 1541.14  5695.2 1541.03
#Mann= 6 ,-1 , 0
    4474     .05       0    4717      .1       0  4974.4     .07       0
  4980.4      .1       0  5058.7     .05       0  5678.2      .1       0
#XS Ineff= 2 , 0
         4865.78 1532.91
Permanent Ineff=
       F       F
Bank Sta=4956.4,4999
XS Rating Curve= 0 ,0
Exp/Cntr=0.3,0.1

Type RM Length L Ch R = 1 ,3450    ,43,43,43
BEGIN DESCRIPTION:
Mapping XS 437eb63a
END DESCRIPTION:
XS GIS Cut Line= 4
      2799005.47     10052251.13      2798846.61     10051894.36
      2798769.79     10051863.11      2798304.95     10052062.32
#Sta/Elev= 30
  4574.7 1532.46  4653.7 1531.32  4659.4 1530.99  4682.4 1530.98  4728.8 1530.44
    4736 1530.17  4798.6 1529.44  4834.6 1528.53  4889.3 1528.04  4920.2 1527.29
  4948.9 1526.89  4962.8 1525.91  4998.6 1525.85  5014.2 1525.71    5017 1525.21
  5020.2 1525.71  5038.8 1525.85  5051.6 1526.18  5058.8 1526.61  5093.2 1526.78
  5134.9 1527.93  5187.5 1528.84  5292.7 1530.03  5363.4 1531.34  5408.6 1531.69
    5445 1532.23  5468.6 1532.92  5515.7 1533.71  5539.2 1533.85  5553.9 1534.24
#Mann= 4 ,-1 , 0
  4574.7      .1       0  4998.6     .05       0  5014.2    .035       0
  5020.2     .05       0
Bank Sta=5014.2,5020.2
XS Rating Curve= 0 ,0
Exp/Cntr=0.3,0.1

Type RM Length L Ch R = 1 ,3407    ,43,43,43
BEGIN DESCRIPTION:
Mapping XS 9ddebd39
END DESCRIPTION:
XS GIS Cut Line= 5
      2799036.72     10052212.08      2798875.26     10051877.43
      2798807.55     10051820.14      2798784.11     10051826.65
      2798323.29     10052031.03
#Sta/Elev= 30
  4586.1    1532  4614.3 1531.27  4682.1 1530.91  4800.7  1529.2  4823.3 1528.55
  4913.8 1527.75  4928.5 1526.99  4950.7 1527.26  4956.9 1526.69  4965.6 1527.68
  4972.1 1527.04  4979.7 1528.28  4986.4 1527.85    4993  1528.4  5000.7  1527.7
  5007.3  1528.4  5015.9 1528.26  5021.5 1528.73  5035.8 1528.35  5055.8 1529.02
  5070.7 1528.57  5073.6 1527.78  5079.1 1528.12  5093.9 1526.37  5096.6 1525.87
  5099.9 1526.37  5270.7 1529.39    5450 1531.39  5491.1 1532.46  5574.8 1533.68
#Mann= 4 ,-1 , 0
  4586.1      .1       0  5015.9     .05       0  5093.9     .07       0
  5099.9     .05       0
Bank Sta=5093.9,5099.9
XS Rating Curve= 0 ,0
Exp/Cntr=0.3,0.1

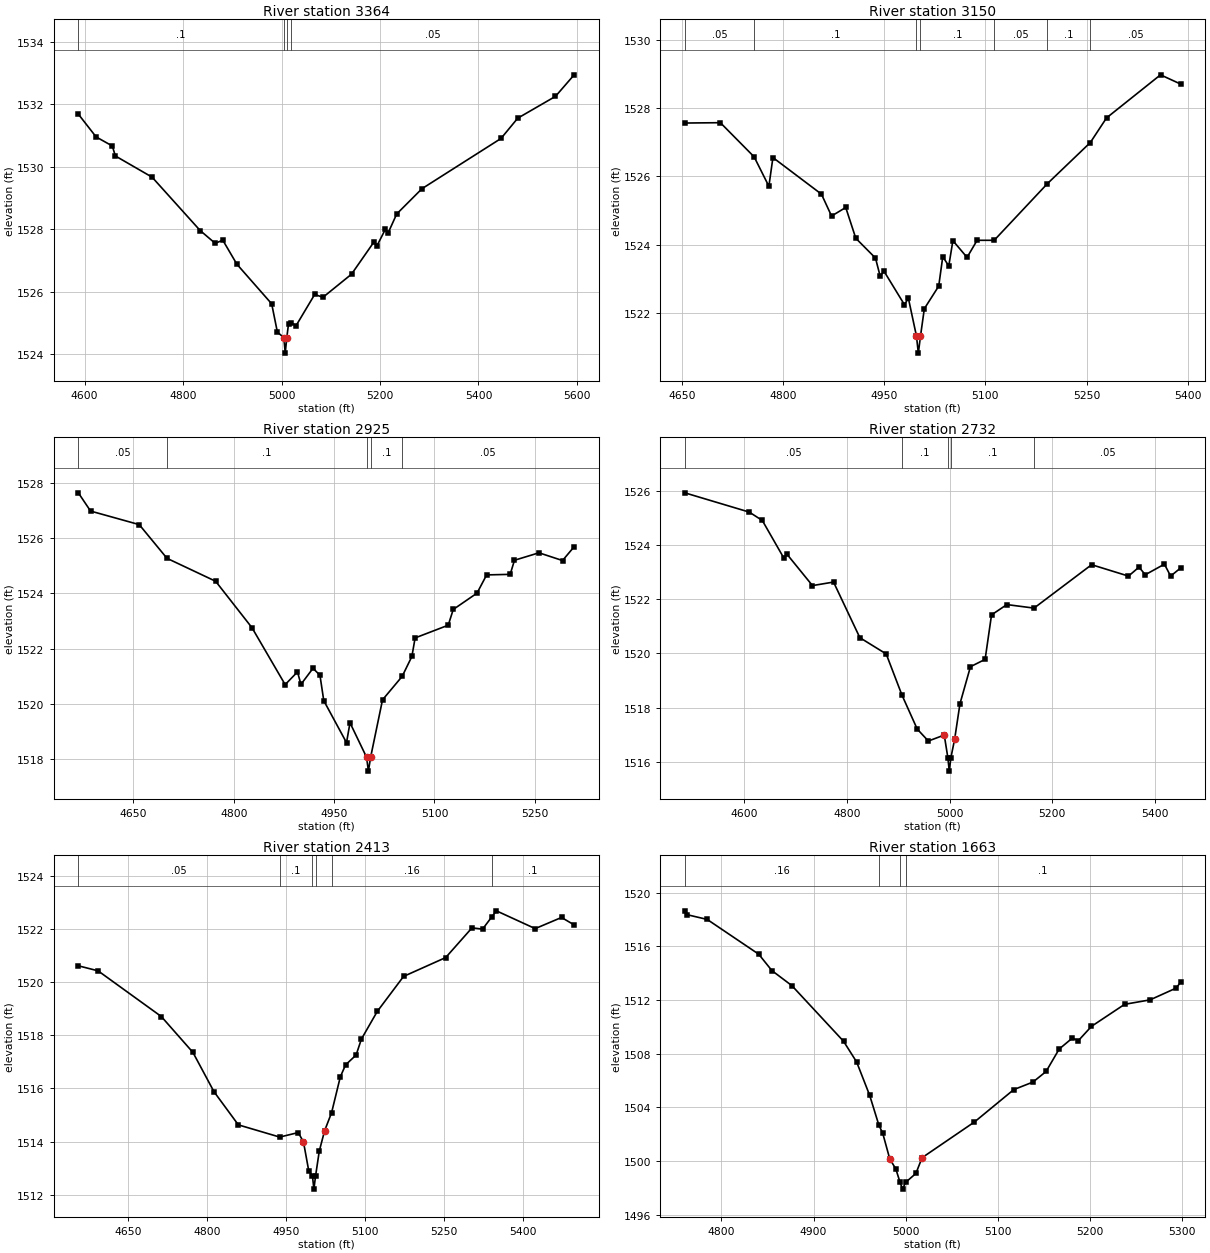
Type RM Length L Ch R = 1 ,3364    ,214,214,214
BEGIN DESCRIPTION:
Mapping XS 09fbbf6e
END DESCRIPTION:
XS GIS Cut Line= 4
      2799054.96     10052166.53      2798903.91     10051835.76
      2798790.62     10051773.26      2798324.09     10051988.99
#Sta/Elev= 30
  4587.3 1531.69  4623.4 1530.96  4656.3 1530.67  4662.5 1530.35  4737.1 1529.67
  4834.7 1527.96  4865.2 1527.55  4880.7 1527.65  4909.3 1526.88    4980 1525.61
  4991.6  1524.7  5004.7 1524.53  5007.5 1524.03  5010.7 1524.53  5014.2 1524.97
  5019.1 1525.01  5029.5 1524.91  5067.3 1525.91  5084.2 1525.82  5142.1 1526.56
    5188  1527.6  5193.5 1527.46  5210.9    1528  5216.4 1527.88  5233.9 1528.49
  5285.2  1529.3  5445.7 1530.91  5479.7 1531.56  5556.4 1532.26  5594.3 1532.95
#Mann= 4 ,-1 , 0
  4587.3      .1       0  5004.7     .07       0  5010.7      .1       0
  5019.1     .05       0
Bank Sta=5004.7,5010.7
XS Rating Curve= 0 ,0
Exp/Cntr=0.3,0.1

Type RM Length L Ch R = 1 ,3150    ,225,225,225
BEGIN DESCRIPTION:
Mapping XS 065866d6
END DESCRIPTION:
XS GIS Cut Line= 3
      2799146.08     10051917.78      2798881.77     10051527.17
      2798618.72     10051534.98
#Sta/Elev= 30
  4654.5 1527.56  4707.2 1527.57  4757.3 1526.57  4779.1 1525.71  4785.1 1526.55
    4857 1525.48    4872 1524.84    4893 1525.09  4907.9 1524.19  4937.1 1523.61
  4943.9 1523.09  4949.9 1523.22  4979.9 1522.25  4985.9 1522.43  4997.8 1521.33
  5000.6 1520.83  5003.8 1521.33  5009.5 1522.13  5030.8 1522.79  5036.8 1523.65
  5045.7 1523.38  5051.8 1524.12  5072.8 1523.63  5087.7 1524.13    5113 1524.13
    5192 1525.79  5255.5 1526.99  5279.5 1527.71  5359.5 1528.97  5389.3  1528.7
#Mann= 7 ,-1 , 0
  4654.5     .05       0  4757.3      .1       0  4997.8     .07       0
  5003.8      .1       0    5113     .05       0    5192      .1       0
  5255.5     .05       0
Bank Sta=4997.8,5003.8
XS Rating Curve= 0 ,0
Exp/Cntr=0.3,0.1

Type RM Length L Ch R = 1 ,2925    ,193,193,193
BEGIN DESCRIPTION:
Mapping XS 6e28e0c8
END DESCRIPTION:
XS GIS Cut Line= 3
      2799192.96     10051881.31      2799058.85     10051404.77
      2798868.84      10051248.6
#Sta/Elev= 30
  4567.8 1527.64  4586.1 1526.98  4658.8 1526.49  4700.3 1525.27    4773 1524.44
  4827.3 1522.76  4876.9  1520.7  4895.3 1521.16  4900.5 1520.71  4918.5 1521.29
  4928.9 1521.04  4934.6 1520.12  4968.6  1518.6  4973.8 1519.32  4998.6 1518.07
  5001.3 1517.57  5004.6 1518.07  5022.4 1520.15  5051.8    1521  5066.3 1521.72
  5071.1 1522.39  5120.6 1522.85  5128.1 1523.42  5163.6 1524.01    5178 1524.67
  5213.2 1524.69  5219.6  1525.2  5256.2 1525.47  5291.4 1525.19  5308.8 1525.69
#Mann= 5 ,-1 , 0
  4567.8     .05       0  4700.3      .1       0  4998.6     .07       0
  5004.6      .1       0  5051.8     .05       0
Bank Sta=4998.6,5004.6
XS Rating Curve= 0 ,0
Exp/Cntr=0.3,0.1

Type RM Length L Ch R = 1 ,2732    ,319,319,319
BEGIN DESCRIPTION:
UNT116 IN NNOGR 5.0
END DESCRIPTION:
XS GIS Cut Line= 2
      2799367.95     10051896.12      2799147.01      10050954.7
#Sta/Elev= 30
  4483.7 1525.92  4609.4 1525.21  4634.9  1524.9  4677.3  1523.5  4682.4 1523.67
  4732.7  1522.5  4773.8 1522.63  4825.1 1520.58  4876.5 1519.98  4907.3 1518.46
    4937 1517.21  4958.7 1516.77  4989.7 1516.99  4996.7 1516.16  4999.5 1515.66
  5002.7 1516.16    5010 1516.84  5020.3 1518.14  5040.8 1519.51  5069.4 1519.78
  5081.9 1521.42  5111.8  1521.8  5164.8 1521.67  5277.1 1523.27    5349 1522.85
  5369.5 1523.18  5381.8  1522.9  5419.1 1523.29  5431.2 1522.85  5450.7 1523.15
#Mann= 5 ,-1 , 0
  4483.7     .05       0  4907.3      .1       0  4996.7     .07       0
  5002.7      .1       0  5164.8     .05       0
Bank Sta=4989.7,5010
XS Rating Curve= 0 ,0
Exp/Cntr=0.3,0.1

Type RM Length L Ch R = 1 ,2413    ,750,750,750
BEGIN DESCRIPTION:
UNT116 IN NNOGR 4.0
END DESCRIPTION:
XS GIS Cut Line= 2
      2799569.69     10051771.27      2799550.48     10050829.76
#Sta/Elev= 30
    4555 1520.62  4592.5 1520.43  4712.6 1518.71  4772.6 1517.36  4812.6 1515.88
  4858.9 1514.63  4937.5 1514.17  4972.6 1514.34  4982.6 1513.99  4992.6  1512.9
  4999.6 1512.71  5002.4 1512.21  5005.6 1512.71  5012.6 1513.64  5022.6  1514.4
    5036 1515.09  5052.6 1516.44  5062.6 1516.89  5082.6 1517.26  5092.6 1517.86
  5122.7  1518.9  5172.7 1520.22  5252.7 1520.93  5302.7 1522.05  5322.7    1522
  5339.8 1522.45    5349 1522.69  5422.7 1522.02  5472.7 1522.44  5496.7 1522.16
#Mann= 6 ,-1 , 0
    4555     .05       0  4937.5      .1       0  4999.6     .07       0
  5005.6      .1       0    5036     .16       0  5339.8      .1       0
Bank Sta=4982.6,5022.6
XS Rating Curve= 0 ,0
Exp/Cntr=0.3,0.1

Type RM Length L Ch R = 1 ,1663    ,222,222,222
BEGIN DESCRIPTION:
UNT116 IN NNOGR 3.0
END DESCRIPTION:
XS GIS Cut Line= 2
      2800353.91     10051332.05      2799997.28     10050928.57
#Sta/Elev= 30
  4760.2 1518.64  4762.8 1518.35  4784.5    1518  4840.5 1515.41  4854.8 1514.19
  4876.5 1513.07  4932.6 1508.93  4946.8 1507.39    4961  1504.9  4970.9  1502.7
  4975.2 1502.07  4982.8 1500.17  4989.4 1499.42    4994 1498.42  4996.7 1497.92
    5000 1498.42  5011.2 1499.09  5017.9 1500.26  5074.8 1502.92  5117.5 1505.33
  5138.3 1505.89  5152.6 1506.68  5166.8 1508.35    5181 1509.16  5187.7 1508.98
  5201.9 1510.04  5237.9 1511.68  5265.5 1512.01  5293.9 1512.89  5298.7 1513.33
#Mann= 4 ,-1 , 0
  4760.2     .16       0  4970.9      .1       0    4994     .07       0
    5000      .1       0
Bank Sta=4982.8,5017.9
XS Rating Curve= 0 ,0
Exp/Cntr=0.3,0.1

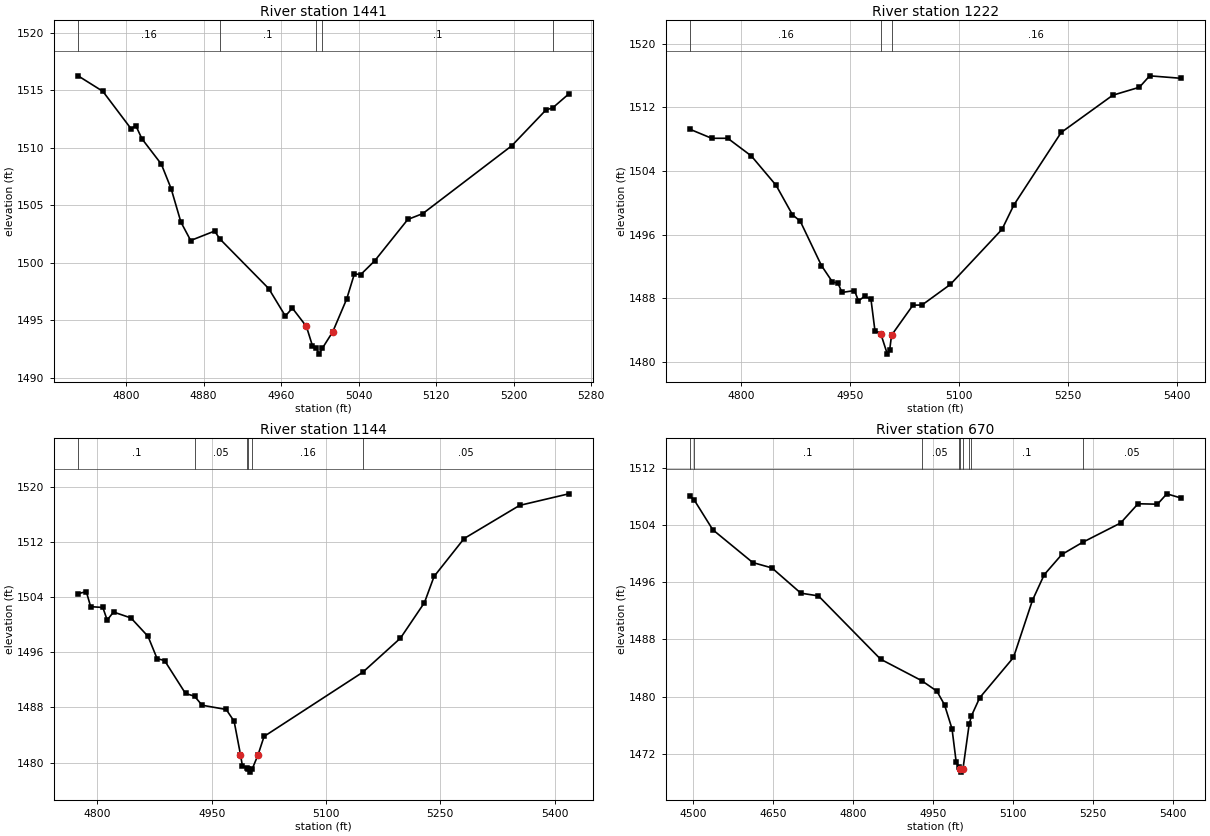
Type RM Length L Ch R = 1 ,1441    ,219,219,219
BEGIN DESCRIPTION:
Mapping XS da9a4bbe
END DESCRIPTION:
XS GIS Cut Line= 4
      2800410.62     10051239.11      2800384.23     10051024.52
      2800284.92     10050945.35      2800170.71     10050828.37
#Sta/Elev= 30
  4750.3 1516.25  4775.9  1514.9    4805 1511.65    4810 1511.91  4816.2 1510.78
  4836.3 1508.57  4846.4 1506.44  4856.5 1503.53  4866.6 1501.93  4891.3 1502.75
  4896.8 1502.06  4947.2 1497.75  4964.4 1495.36  4971.6 1496.05  4986.1 1494.46
  4992.4 1492.76  4996.5 1492.55  4999.2 1492.05  5002.5 1492.55  5013.3 1493.99
  5027.7 1496.84  5035.7 1499.04  5042.1 1498.96  5056.5 1500.15  5090.8 1503.76
  5106.3 1504.27  5198.2 1510.17  5233.6 1513.29  5240.4 1513.46    5257 1514.67
#Mann= 5 ,-1 , 0
  4750.3     .16       0  4896.8      .1       0  4996.5     .07       0
  5002.5      .1       0  5240.4     .05       0
Bank Sta=4986.1,5013.3
XS Rating Curve= 0 ,0
Exp/Cntr=0.3,0.1

Type RM Length L Ch R = 1 ,1222    ,78,78,78
BEGIN DESCRIPTION:
UNT116 IN NNOGR 2.0
END DESCRIPTION:
XS GIS Cut Line= 3
      2800775.09     10050996.89      2800490.36     10050861.46
      2800136.23     10050798.97
#Sta/Elev= 30
  4730.6 1509.23  4760.1 1508.11  4782.2 1508.11  4814.7 1505.88  4848.7 1502.19
  4871.2 1498.49  4881.9 1497.68  4911.1 1492.09  4926.2 1490.03  4933.8 1489.88
  4939.3 1488.71  4956.5 1488.95    4962 1487.65  4970.5 1488.23  4979.2 1487.84
  4984.7 1483.86  4992.6 1483.54  5001.7 1480.95  5004.9 1481.45  5007.5 1483.33
  5036.9 1487.11  5049.4 1487.13  5088.4 1489.72  5159.5 1496.66  5175.7 1499.71
  5240.8 1508.84  5311.8 1513.53  5348.4 1514.53  5362.6 1515.97  5405.5 1515.66
#Mann= 3 , 0 , 0
  4730.6     .16       0  4992.6     .07       0  5007.5     .16       0
Bank Sta=4992.6,5007.5
XS Rating Curve= 0 ,0
Exp/Cntr=0.3,0.1

Type RM Length L Ch R = 1 ,1144    ,474,474,474
BEGIN DESCRIPTION:
Mapping XS e7b92b9a
END DESCRIPTION:
XS GIS Cut Line= 3
      2800789.01     10050936.14      2800627.51     10050845.84
       2800186.5     10050719.09
#Sta/Elev= 30
  4774.7  1504.5  4785.5  1504.8  4791.2 1502.62  4807.2  1502.5  4812.9 1500.67
  4821.2 1501.84  4844.1 1500.98  4866.5 1498.31  4878.4 1495.08  4888.2  1494.8
  4915.7 1490.02  4927.5 1489.63  4937.4 1488.32  4969.1  1487.7  4979.5 1485.99
 4987.82 1481.16  4990.3 1479.56  4996.2 1479.19  4997.4 1479.11  5000.1 1478.61
  5003.4 1479.11  5010.8 1481.09  5018.8 1483.79  5148.3  1493.1  5197.8 1498.05
  5229.3 1503.21  5241.9    1507  5281.3  1512.5  5354.1 1517.31  5418.6 1518.99
#Mann= 6 ,-1 , 0
  4774.7      .1       0  4927.5     .05       0  4996.2     .16       0
  4997.4     .07       0  5003.4     .16       0  5148.3     .05       0
Bank Sta=4987.82,5010.8
XS Rating Curve= 0 ,0
Exp/Cntr=0.3,0.1

Type RM Length L Ch R = 1 ,670     ,0,0,0
BEGIN DESCRIPTION:
UNT116 IN NNOGR 1.0
END DESCRIPTION:
XS GIS Cut Line= 3
      2800905.29     10051024.66      2801012.93     10050599.31
      2800575.39     10050399.64
#Sta/Elev= 30
    4495 1508.01    4502 1507.54  4537.2 1503.33  4612.2 1498.74  4648.1 1497.99
  4702.3 1494.46  4735.3 1494.08  4851.8 1485.23  4928.5 1482.24  4957.2 1480.77
  4971.6 1478.86  4985.7 1475.49  4993.6 1470.79  4998.9 1470.12  5000.3 1469.94
    5003 1469.44  5006.3 1469.94  5017.8 1476.11  5022.1 1477.31  5037.6 1479.84
  5100.9 1485.47  5136.5 1493.47  5158.5 1497.04  5191.5 1499.87  5230.5 1501.57
  5301.7 1504.27  5334.4 1506.96  5370.8  1506.9  5388.3 1508.35  5414.7 1507.77
#Mann= 9 ,-1 , 0
    4495     .05       0    4502      .1       0  4928.5     .05       0
  4998.9      .1       0  5000.3     .07       0  5006.3      .1       0
  5017.8     .16       0  5022.1      .1       0  5230.5     .05       0
Bank Sta=5000.3,5006.3
XS Rating Curve= 0 ,0
Exp/Cntr=0.3,0.1

Chan Stop Cuts=-1
Use User Specified Reach Order=0
Composite Channel Slope=5