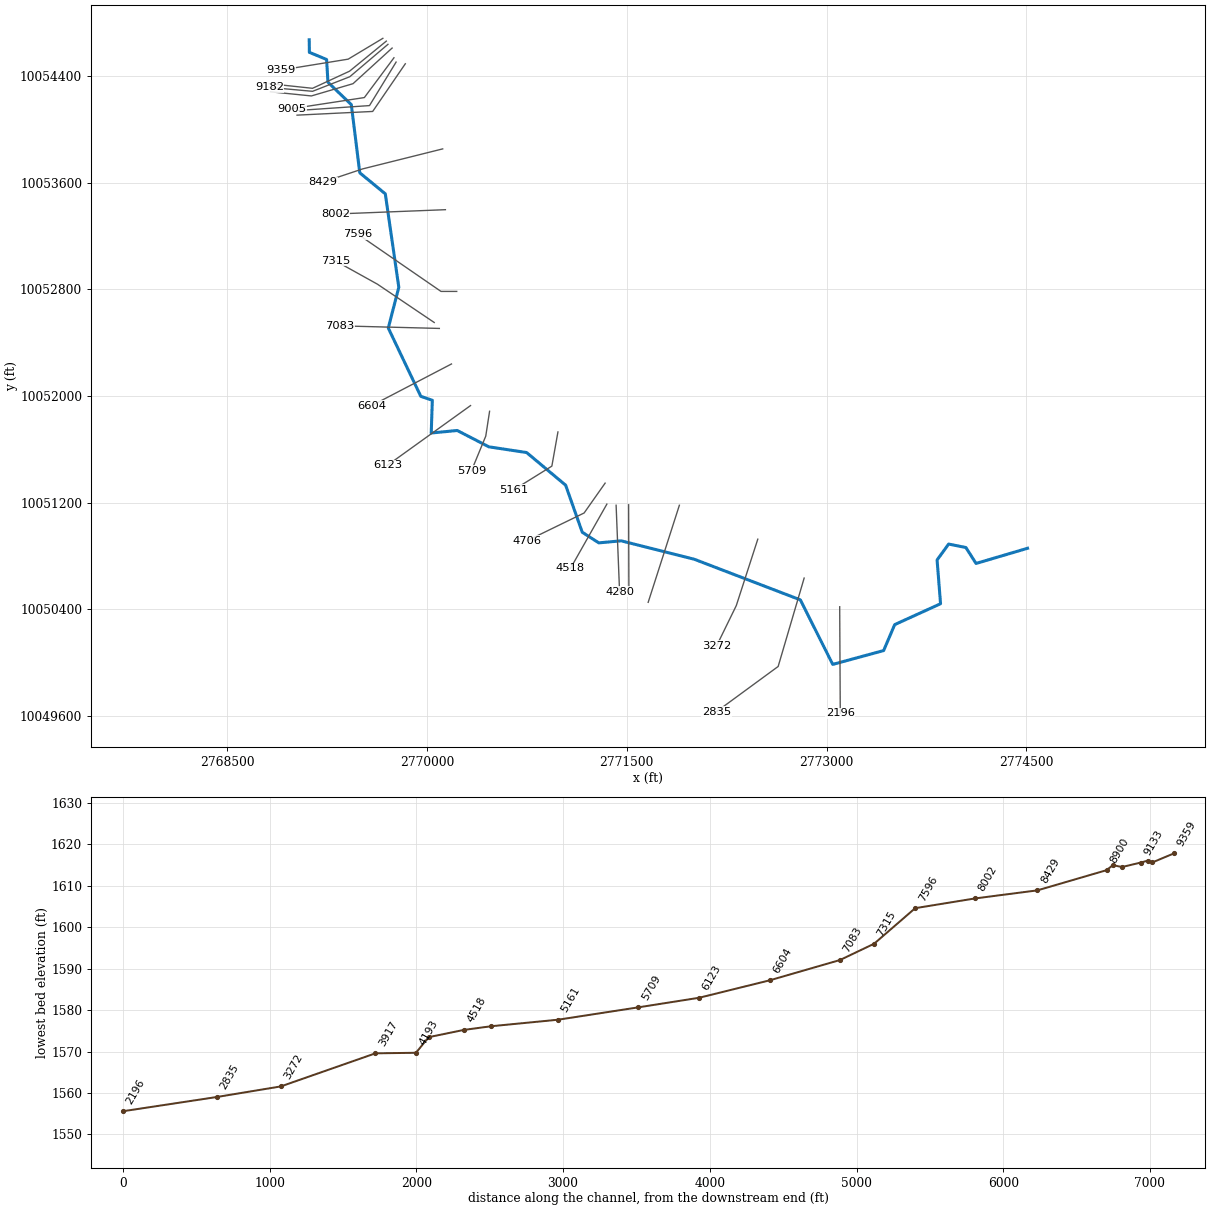
--- UNT117 IN NNOGR.prj (project) ---

Proj Title=UNT117 IN NNOGR Base Level Engineering
Current Plan=p01
Default Exp/Contr=0.3,0.1
English Units
Geom File=g01
Flow File=f01
Plan File=p01
BEGIN DESCRIPTION:
UNT117 IN NNOGR
END DESCRIPTION:

--- UNT117 IN NNOGR.p01 (plan) ---

Plan Title=Multiple Run
Short Identifier=Multiple
Geom File=g01
Flow File=f01
Subcritical Flow
K Sum by GR= 0
Std Step Tol= 0.01
Critical Tol= 0.01
Num of Std Step Trials= 20
Max Error Tol= 0.3
Flow Tol Ratio= 0.001
Split Flow NTrial= 30
Split Flow Tol= 0.02
Split Flow Ratio= 0.02
Log Output Level= 0
Friction Slope Method= 1
Unsteady Friction Slope Method= 2
Unsteady Bridges Friction Slope Method= 1
Parabolic Critical Depth
Global Vel Dist=  1 , 1 , 1
Global Log Level= 0
CheckData=True
Encroach Param= -1, 0, 0, 0
BEGIN DESCRIPTION:
Multiple Run
END DESCRIPTION:

--- UNT117 IN NNOGR.f01 (steady flow) ---

Flow Title=Multiple
Number of Profiles=7
Profile Names=10-year,25-year,50-year,1pct_min,100-year,1pct_plu,500-year
River Rch & RM= UNT117 IN NNOGR,Reach-1,9359
     480     664     817     735     995    1345    1480
Boundary for River Rch & Prof#=UNT117 IN NNOGR,Reach-1,1
Up Type=0
Dn Type=3
Dn Slope=0.005
Boundary for River Rch & Prof#=UNT117 IN NNOGR,Reach-1,2
Up Type=0
Dn Type=3
Dn Slope=0.005
Boundary for River Rch & Prof#=UNT117 IN NNOGR,Reach-1,3
Up Type=0
Dn Type=3
Dn Slope=0.005
Boundary for River Rch & Prof#=UNT117 IN NNOGR,Reach-1,4
Up Type=0
Dn Type=3
Dn Slope=0.005
Boundary for River Rch & Prof#=UNT117 IN NNOGR,Reach-1,5
Up Type=0
Dn Type=3
Dn Slope=0.005
Boundary for River Rch & Prof#=UNT117 IN NNOGR,Reach-1,6
Up Type=0
Dn Type=3
Dn Slope=0.005
Boundary for River Rch & Prof#=UNT117 IN NNOGR,Reach-1,7
Up Type=0
Dn Type=3
Dn Slope=0.005

--- UNT117 IN NNOGR.g01 (geometry) ---

Geom Title=Existing Conditions

River Reach=UNT117 IN NNOGR,Reach-1
Reach XY= 30
      2769116.74     10054672.28      2769117.88     10054578.15
      2769246.99     10054524.66      2769257.39     10054353.90
      2769432.66     10054185.58      2769496.10     10053674.21
      2769687.69     10053516.52      2769789.03     10052815.26
      2769710.04     10052509.60      2769954.13     10051997.00
      2770040.56     10051967.15      2770032.41     10051721.66
      2770227.44     10051740.65      2770465.47     10051617.88
      2770748.28     10051575.17      2771041.08     10051330.34
      2771165.85     10050977.13      2771290.06     10050897.40
      2771457.82     10050912.71      2772006.74     10050774.35
      2772802.88     10050469.57      2773045.77     10049985.39
      2773428.06     10050089.29      2773510.69     10050283.70
      2773855.01     10050440.55      2773829.05     10050769.06
      2773915.82     10050888.53      2774045.26     10050862.21
      2774121.43     10050742.85      2774507.98     10050856.71

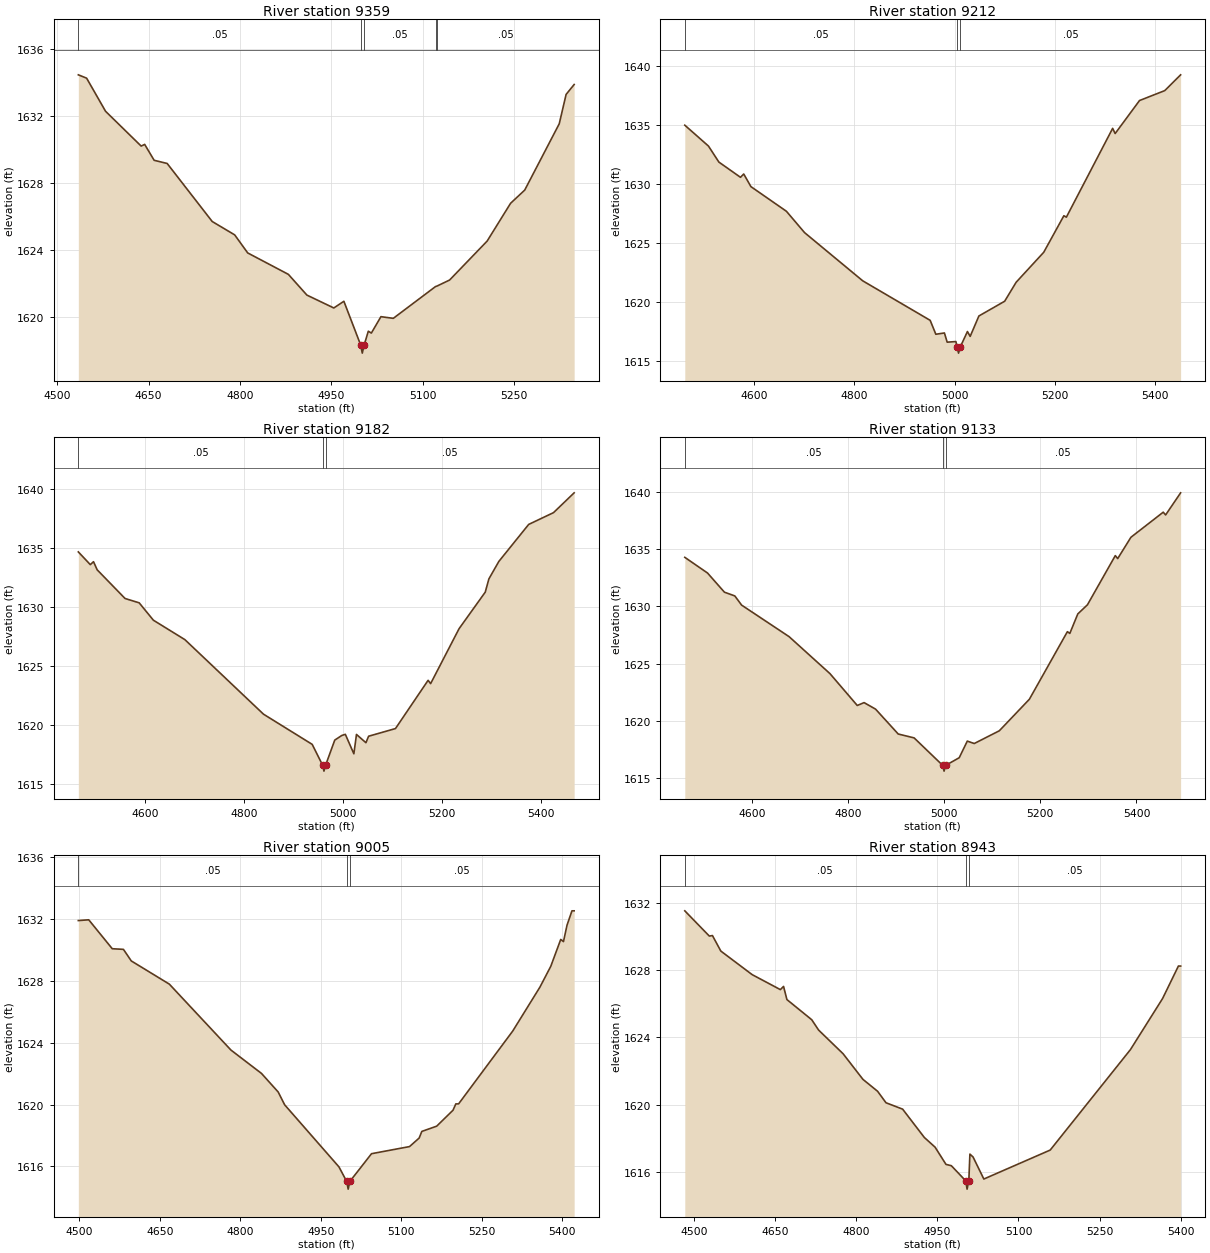
Type RM Length L Ch R = 1,9359,147,147,147
BEGIN DESCRIPTION:
UNT117 IN NNOGR 20.0
END DESCRIPTION:
XS GIS Cut Line= 3
      2769669.33     10054683.25      2769408.92     10054527.01
      2768905.48     10054445.41
#Sta/Elev= 30
  4534.8 1634.46  4548.4 1634.26  4579.5 1632.28  4637.9 1630.20  4643.7 1630.30
  4659.2 1629.35  4680.6 1629.16  4754.5 1625.69  4791.4 1624.89  4812.8 1623.81
  4879.5 1622.53  4909.9 1621.29  4954.1 1620.52  4970.6 1620.92  4998.0 1618.32
  5000.8 1617.82  5004.0 1618.32  5010.7 1619.13  5015.7 1619.02  5031.4 1620.00
  5051.7 1619.90  5121.0 1621.80  5123.4 1621.83  5144.1 1622.19  5205.7 1624.52
  5244.2 1626.78  5267.4 1627.57  5324.0 1631.53  5335.3 1633.29  5348.5 1633.88
#Mann=5,-1,0
  4534.8    0.05       0  4998.0   0.035       0  5004.0    0.05       0
  5121.0     0.1       0  5123.4    0.05       0
Bank Sta=4998,5004
Exp/Cntr=0.3,0.1

Type RM Length L Ch R = 1,9212,30,30,30
BEGIN DESCRIPTION:
Mapping XS 3e31bd54
END DESCRIPTION:
XS GIS Cut Line= 4
      2769695.38     10054662.42      2769419.33     10054436.73
      2769141.55     10054308.26      2768816.92     10054342.98
#Sta/Elev= 30
  4461.7 1634.97  4508.9 1633.20  4529.7 1631.84  4572.8 1630.55  4579.3 1630.83
  4593.6 1629.76  4664.4 1627.67  4700.6 1625.86  4816.7 1621.77  4951.2 1618.42
  4962.5 1617.24  4979.6 1617.35  4985.1 1616.57  5002.5 1616.62  5005.0 1616.14
  5007.8 1615.64  5011.0 1616.14  5025.5 1617.47  5031.0 1617.06  5048.4 1618.79
  5099.8 1620.04  5122.7 1621.65  5177.7 1624.19  5217.9 1627.29  5222.9 1627.17
  5315.2 1634.70  5320.2 1634.26  5368.8 1637.06  5419.1 1637.90  5450.8 1639.24
#Mann=3,-1,0
  4461.7    0.05       0  5005.0    0.04       0  5011.0    0.05       0
Bank Sta=5005,5011
Exp/Cntr=0.3,0.1

Type RM Length L Ch R = 1,9182,49,49,49
BEGIN DESCRIPTION:
Mapping XS 489cfbf0
END DESCRIPTION:
XS GIS Cut Line= 4
      2769707.52     10054638.11      2769421.07     10054395.06
      2769141.55     10054285.69      2768816.91     10054315.20
#Sta/Elev= 30
  4465.3 1634.67  4489.5 1633.59  4496.0 1633.84  4503.4 1633.15  4559.7 1630.72
  4588.3 1630.35  4616.9 1628.88  4680.6 1627.23  4839.4 1620.91  4937.8 1618.35
  4958.9 1616.58  4961.6 1616.08  4964.9 1616.58  4983.4 1618.71  4997.5 1619.10
  5004.8 1619.20  5022.0 1617.55  5027.3 1619.19  5046.4 1618.49  5051.8 1619.04
  5106.1 1619.69  5172.0 1623.78  5177.1 1623.50  5234.6 1628.16  5287.5 1631.26
  5294.8 1632.38  5314.9 1633.86  5375.2 1637.00  5425.4 1638.00  5467.1 1639.68
#Mann=3,-1,0
  4465.3    0.05       0  4958.9    0.04       0  4964.9    0.05       0
Bank Sta=4958.9,4964.9
Exp/Cntr=0.3,0.1

Type RM Length L Ch R = 1,9133,128,128,128
BEGIN DESCRIPTION:
Mapping XS 01ae8e17
END DESCRIPTION:
XS GIS Cut Line= 4
      2769738.74     10054610.31      2769445.37     10054342.98
      2769132.87     10054250.96      2768825.62     10054282.21
#Sta/Elev= 30
  4460.3 1634.27  4507.6 1632.90  4542.7 1631.23  4564.4 1630.90  4578.5 1630.10
  4677.2 1627.35  4762.3 1624.12  4819.1 1621.34  4833.3 1621.59  4857.2 1621.02
  4904.3 1618.85  4937.4 1618.51  4996.9 1616.11  4999.7 1615.61  5002.9 1616.11
  5031.2 1616.78  5048.0 1618.23  5062.5 1618.02  5114.6 1619.13  5177.1 1621.88
  5256.2 1627.78  5261.3 1627.63  5277.9 1629.33  5298.0 1630.13  5355.9 1634.42
  5360.9 1634.16  5388.4 1636.02  5455.6 1638.21  5460.6 1637.97  5491.8 1639.90
#Mann=3,-1,0
  4460.3    0.05       0  4996.9    0.04       0  5002.9    0.05       0
Bank Sta=4996.9,5002.9
Exp/Cntr=0.3,0.1

Type RM Length L Ch R = 1,9005,62,62,62
BEGIN DESCRIPTION:
Mapping XS 1886850f
END DESCRIPTION:
XS GIS Cut Line= 3
      2769752.68     10054537.45      2769530.44     10054238.81
      2768985.33     10054155.48
#Sta/Elev= 30
  4498.3 1631.89  4517.7 1631.94  4561.5 1630.07  4582.3 1630.03  4597.0 1629.28
  4667.9 1627.78  4782.6 1623.52  4839.5 1622.01  4870.6 1620.81  4882.7 1619.98
  4983.8 1615.97  4998.2 1615.03  5001.0 1614.53  5004.2 1615.03  5044.5 1616.82
  5115.3 1617.28  5133.2 1617.83  5138.2 1618.26  5165.9 1618.60  5196.3 1619.63
  5201.6 1620.04  5206.7 1620.04  5307.6 1624.75  5358.1 1627.58  5378.4 1628.93
  5397.0 1630.67  5402.1 1630.53  5408.7 1631.59  5417.9 1632.52  5422.0 1632.52
#Mann=3,-1,0
  4498.3    0.05       0  4998.2    0.04       0  5004.2    0.05       0
Bank Sta=4998.2,5004.2
Exp/Cntr=0.3,0.1

Type RM Length L Ch R = 1,8943,43,43,43
BEGIN DESCRIPTION:
UNT117 IN NNOGR 19.0
END DESCRIPTION:
XS GIS Cut Line= 3
      2769768.65     10054504.97      2769568.99     10054178.57
      2769035.16     10054142.11
#Sta/Elev= 30
  4482.4 1631.52  4527.8 1630.02  4533.6 1630.05  4549.1 1629.13  4607.1 1627.73
  4659.3 1626.84  4665.2 1627.03  4671.4 1626.25  4717.4 1625.05  4730.0 1624.44
  4775.4 1623.03  4812.1 1621.51  4839.3 1620.80  4854.8 1620.12  4885.6 1619.74
  4925.7 1618.06  4945.7 1617.48  4965.8 1616.46  4975.8 1616.38  5002.1 1615.49
  5004.9 1614.99  5008.1 1615.49  5010.1 1617.07  5015.9 1616.90  5035.9 1615.59
  5158.7 1617.31  5307.3 1623.28  5366.7 1626.31  5396.0 1628.24  5400.1 1628.24
#Mann=3,-1,0
  4482.4    0.05       0  5002.1    0.04       0  5008.1    0.05       0
Bank Sta=5002.1,5008.1
Exp/Cntr=0.3,0.1

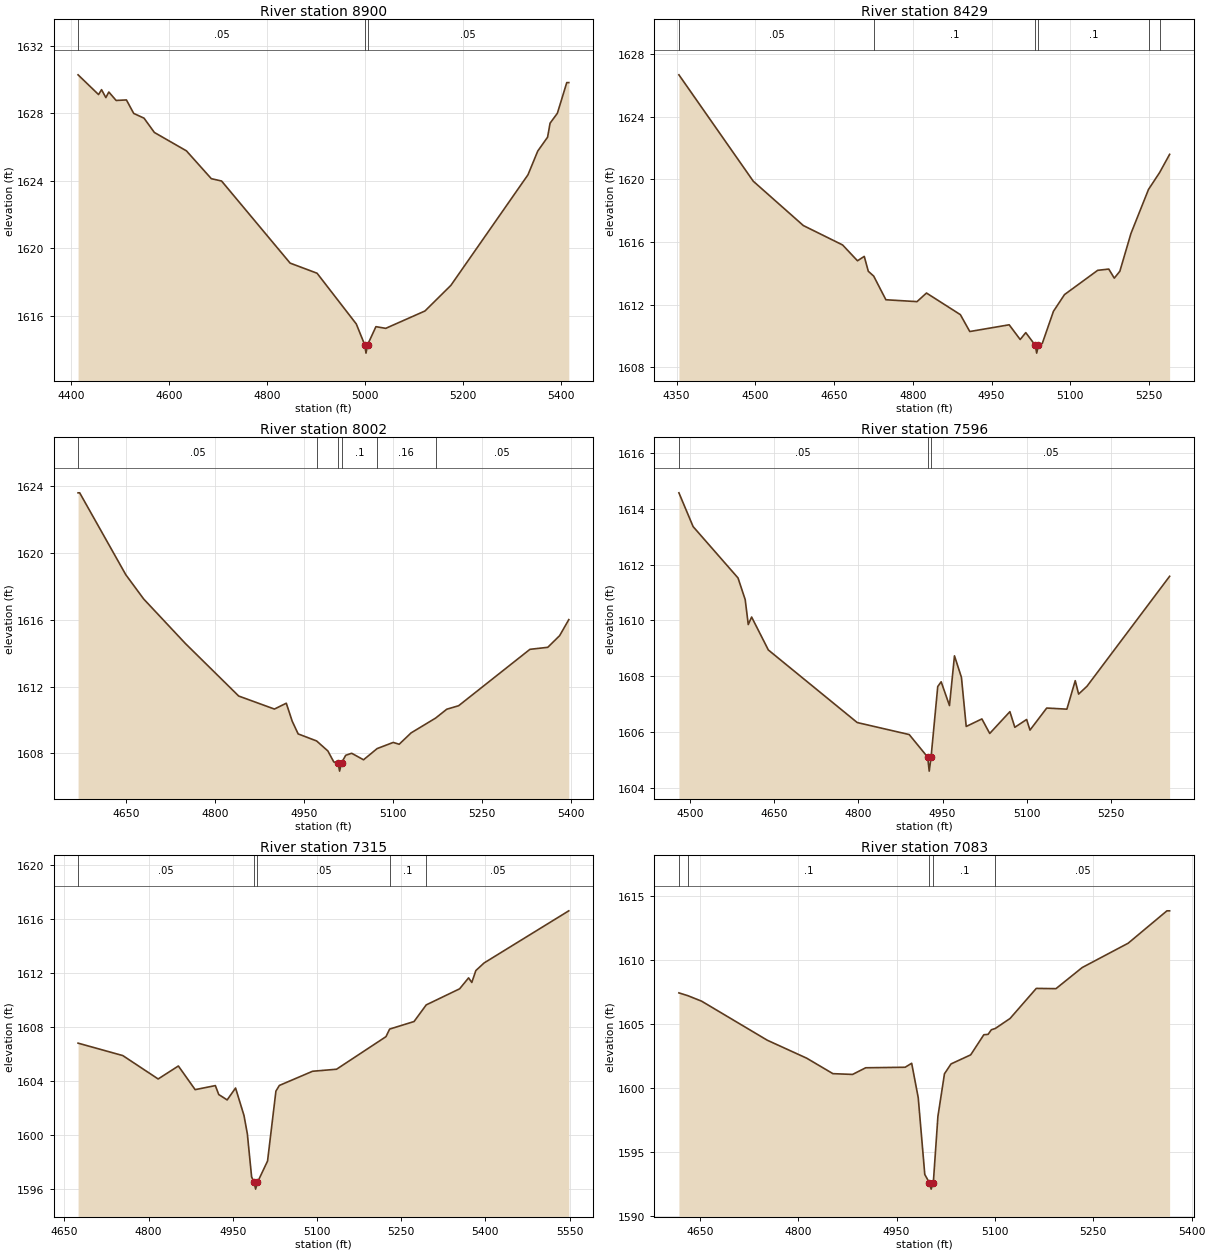
Type RM Length L Ch R = 1,8900,471,471,471
BEGIN DESCRIPTION:
Mapping XS 28eff5af
END DESCRIPTION:
XS GIS Cut Line= 3
      2769837.74     10054492.29      2769592.94     10054134.64
      2769025.23     10054106.87
#Sta/Elev= 30
  4413.6 1630.28  4455.4 1629.11  4461.5 1629.40  4470.3 1628.93  4476.4 1629.26
  4491.3 1628.76  4512.3 1628.79  4527.2 1627.99  4548.2 1627.71  4569.4 1626.86
  4634.8 1625.77  4685.6 1624.12  4706.6 1623.98  4846.5 1619.11  4901.5 1618.51
  4981.6 1615.50  4998.7 1614.27  5001.4 1613.77  5004.7 1614.27  5021.7 1615.34
  5041.7 1615.24  5121.8 1616.27  5174.7 1617.79  5332.1 1624.35  5352.1 1625.76
  5372.1 1626.58  5377.2 1627.41  5392.1 1628.00  5411.3 1629.82  5415.4 1629.82
#Mann=3,-1,0
  4413.6    0.05       0  4998.7    0.04       0  5004.7    0.05       0
Bank Sta=4998.7,5004.7
Exp/Cntr=0.3,0.1

Type RM Length L Ch R = 1,8429,427,427,427
BEGIN DESCRIPTION:
UNT117 IN NNOGR 18.0
END DESCRIPTION:
XS GIS Cut Line= 3
      2770118.42     10053853.72      2769518.47     10053703.73
      2769218.51     10053603.75
#Sta/Elev= 30
  4354.5 1626.68  4496.2 1619.88  4591.5 1617.05  4666.3 1615.81  4694.6 1614.80
  4707.5 1615.08  4715.2 1614.13  4725.5 1613.82  4748.7 1612.31  4808.0 1612.19
  4826.0 1612.74  4890.5 1611.36  4908.5 1610.28  4983.5 1610.71  5004.5 1609.77
  5015.1 1610.21  5033.2 1609.40  5035.9 1608.90  5039.2 1609.40  5046.7 1609.53
  5067.8 1611.57  5088.9 1612.64  5152.1 1614.19  5173.2 1614.27  5183.7 1613.69
  5194.3 1614.13  5215.4 1616.54  5248.9 1619.36  5270.1 1620.44  5289.1 1621.60
#Mann=6,-1,0
  4354.5    0.05       0  4725.5     0.1       0  5033.2    0.07       0
  5039.2     0.1       0  5248.9    0.16       0  5270.1    0.05       0
Bank Sta=5033.2,5039.2
Exp/Cntr=0.3,0.1

Type RM Length L Ch R = 1,8002,406,406,406
BEGIN DESCRIPTION:
Mapping XS 431bdc99
END DESCRIPTION:
XS GIS Cut Line= 2
      2770138.77     10053397.44      2769313.11     10053364.93
#Sta/Elev= 30
  4569.6 1623.62  4572.3 1623.62  4650.0 1618.71  4680.0 1617.26  4750.0 1614.60
  4840.1 1611.44  4900.2 1610.66  4920.2 1611.01  4930.2 1609.93  4940.2 1609.17
  4971.2 1608.75  4990.2 1608.15  5000.2 1607.49  5007.2 1607.44  5010.0 1606.94
  5013.2 1607.44  5020.3 1607.89  5030.3 1608.01  5050.3 1607.62  5073.1 1608.29
  5100.3 1608.66  5110.3 1608.55  5130.3 1609.23  5171.7 1610.12  5190.4 1610.65
  5210.4 1610.86  5330.5 1614.24  5360.5 1614.36  5380.5 1615.06  5395.9 1616.02
#Mann=6,-1,0
  4569.6    0.05       0  4971.2     0.1       0  5007.2    0.07       0
  5013.2     0.1       0  5073.1    0.16       0  5171.7    0.05       0
Bank Sta=5007.2,5013.2
Exp/Cntr=0.3,0.1

Type RM Length L Ch R = 1,7596,281,281,281
BEGIN DESCRIPTION:
UNT117 IN NNOGR 17.0
END DESCRIPTION:
XS GIS Cut Line= 3
      2770223.79     10052784.18      2770105.73     10052784.18
      2769482.96     10053212.66
#Sta/Elev= 30
  4480.5 1614.57  4505.8 1613.36  4585.8 1611.52  4598.6 1610.74  4604.0 1609.85
  4610.0 1610.12  4639.8 1608.94  4798.1 1606.34  4890.7 1605.91  4923.6 1605.10
  4926.3 1604.60  4929.6 1605.10  4941.5 1607.63  4947.6 1607.80  4962.4 1606.95
  4971.3 1608.73  4983.7 1607.96  4992.2 1606.20  5020.1 1606.47  5034.1 1605.95
  5070.0 1606.73  5078.8 1606.17  5099.8 1606.45  5105.8 1606.07  5135.6 1606.86
  5171.5 1606.82  5186.4 1607.84  5192.4 1607.36  5207.3 1607.64  5354.5 1611.58
#Mann=3,-1,0
  4480.5    0.05       0  4923.6    0.04       0  4929.6    0.05       0
Bank Sta=4923.6,4929.6
Exp/Cntr=0.3,0.1

Type RM Length L Ch R = 1,7315,232,232,232
BEGIN DESCRIPTION:
UNT117 IN NNOGR 16.0
END DESCRIPTION:
XS GIS Cut Line= 3
      2770054.84     10052551.02      2769628.37     10052838.58
      2769313.68     10053013.29
#Sta/Elev= 30
  4674.3 1606.80  4754.0 1605.88  4817.0 1604.15  4853.0 1605.11  4882.9 1603.36
  4918.9 1603.66  4924.9 1603.00  4939.9 1602.60  4954.9 1603.48  4969.9 1601.45
  4975.9 1600.09  4983.5 1596.90  4987.9 1596.50  4990.6 1596.00  4993.9 1596.50
  5011.9 1598.08  5026.8 1603.25  5032.9 1603.67  5092.1 1604.72  5134.8 1604.87
  5222.9 1607.28  5229.4 1607.84  5272.9 1608.40  5294.6 1609.63  5354.1 1610.82
  5370.1 1611.63  5375.8 1611.29  5383.0 1612.17  5397.6 1612.73  5548.6 1616.59
#Mann=5,-1,0
  4674.3    0.05       0  4987.9    0.04       0  4993.9    0.05       0
  5229.4     0.1       0  5294.6    0.05       0
Bank Sta=4987.9,4993.9
Exp/Cntr=0.3,0.1

Type RM Length L Ch R = 1,7083,479,479,479
BEGIN DESCRIPTION:
UNT117 IN NNOGR 15.0
END DESCRIPTION:
XS GIS Cut Line= 2
      2770093.20     10052506.40      2769345.26     10052525.91
#Sta/Elev= 30
  4618.2 1607.41  4631.9 1607.19  4652.9 1606.76  4753.0 1603.71  4813.0 1602.31
  4853.0 1601.10  4883.0 1601.04  4903.0 1601.56  4963.1 1601.60  4973.1 1601.91
  4983.1 1599.22  4993.1 1593.22  5000.1 1592.58  5002.8 1592.08  5006.1 1592.58
  5013.1 1597.76  5023.1 1601.09  5033.1 1601.86  5063.1 1602.57  5083.1 1604.14
  5089.6 1604.17  5094.6 1604.53  5100.6 1604.63  5123.1 1605.41  5163.1 1607.76
  5193.1 1607.74  5233.1 1609.39  5303.2 1611.29  5362.3 1613.82  5366.4 1613.82
#Mann=5,-1,0
  4618.2    0.05       0  4631.9     0.1       0  5000.1    0.07       0
  5006.1     0.1       0  5100.6    0.05       0
Bank Sta=5000.1,5006.1
Exp/Cntr=0.3,0.1

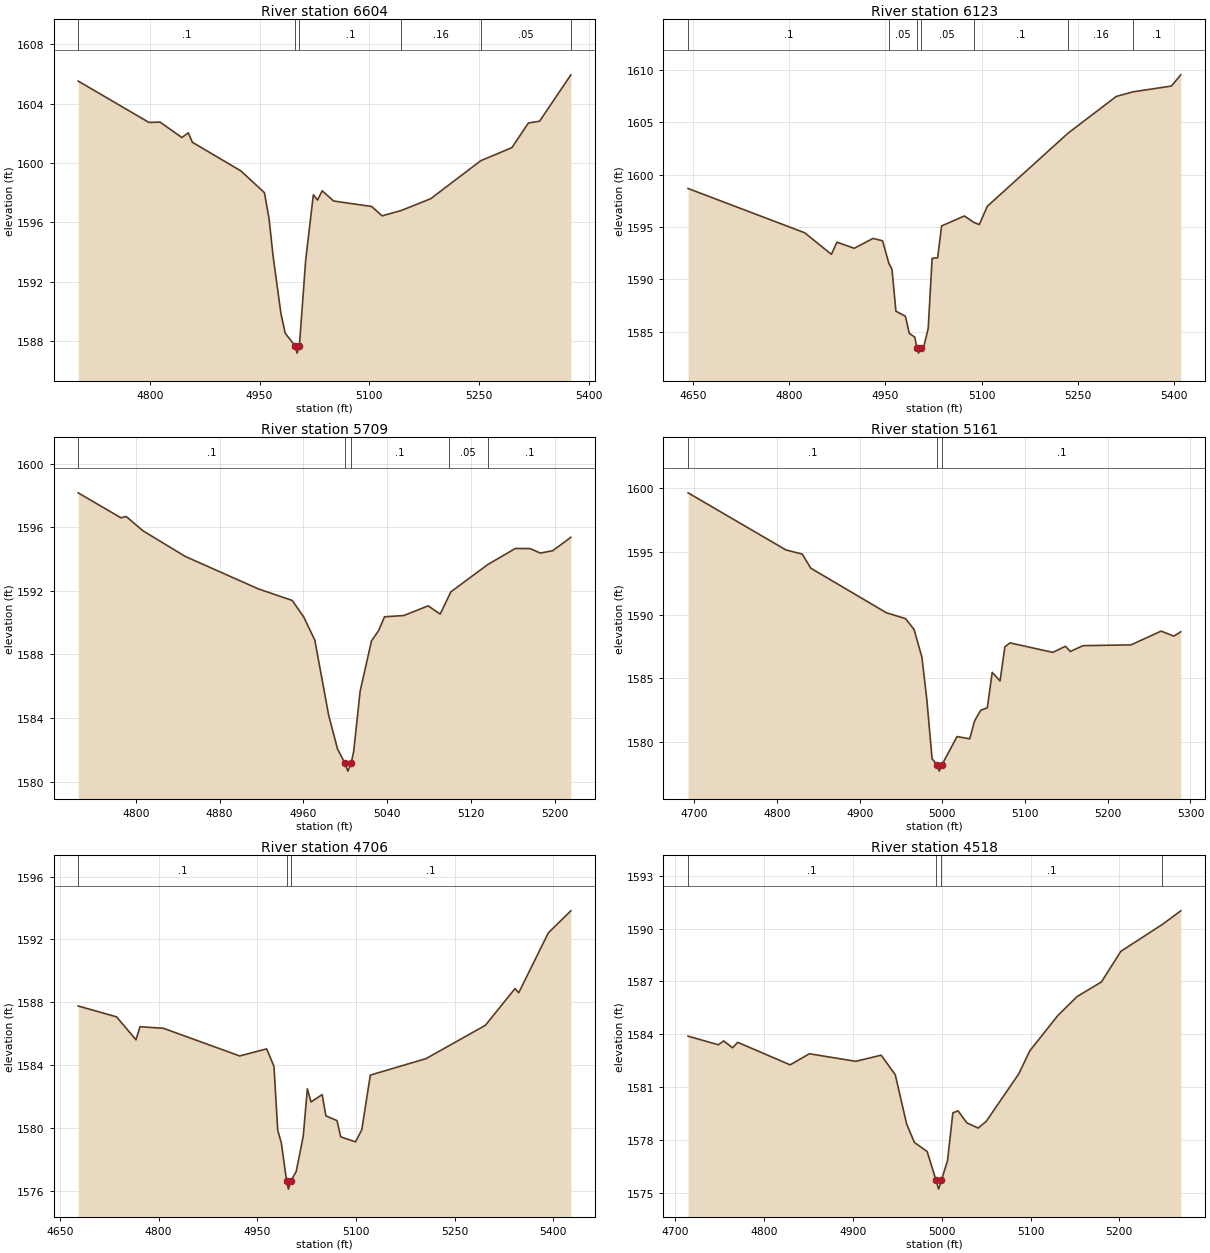
Type RM Length L Ch R = 1,6604,481,481,481
BEGIN DESCRIPTION:
UNT117 IN NNOGR 14.0
END DESCRIPTION:
XS GIS Cut Line= 2
      2770184.28     10052239.75      2769586.99     10051928.12
#Sta/Elev= 30
  4702.0 1605.53  4798.8 1602.74  4814.0 1602.76  4843.9 1601.72  4852.5 1602.04
  4858.2 1601.40  4924.5 1599.47  4956.7 1598.00  4963.0 1596.26  4968.6 1593.69
  4979.3 1589.84  4985.1 1588.52  4998.5 1587.68  5001.3 1587.18  5004.5 1587.68
  5013.1 1593.46  5023.6 1597.86  5029.3 1597.50  5035.7 1598.13  5051.3 1597.44
  5103.3 1597.07  5117.6 1596.44  5143.8 1596.80  5183.9 1597.59  5252.6 1600.16
  5295.1 1601.04  5317.6 1602.70  5332.9 1602.82  5375.6 1605.94  5375.7 1605.95
#Mann=6,-1,0
  4702.0     0.1       0  4998.5    0.07       0  5004.5     0.1       0
  5143.8    0.16       0  5252.6    0.05       0  5375.6     0.1       0
Bank Sta=4998.5,5004.5
Exp/Cntr=0.3,0.1

Type RM Length L Ch R = 1,6123,414,414,414
BEGIN DESCRIPTION:
UNT117 IN NNOGR 13.0
END DESCRIPTION:
XS GIS Cut Line= 2
      2770327.35     10051927.56      2769703.23     10051478.97
#Sta/Elev= 30
  4642.2 1598.67  4824.0 1594.45  4865.8 1592.39  4874.4 1593.55  4901.4 1592.97
  4930.8 1593.91  4945.6 1593.68  4955.3 1591.55  4960.3 1590.96  4966.4 1586.97
  4981.2 1586.49  4987.3 1584.85  4995.9 1584.49  4999.1 1583.47  5001.8 1582.97
  5005.1 1583.47  5010.3 1583.69  5016.8 1585.34  5022.9 1592.01  5031.5 1592.06
  5037.7 1595.10  5073.3 1596.05  5087.9 1595.44  5096.5 1595.23  5108.9 1596.97
  5235.0 1603.95  5310.2 1607.45  5336.3 1607.89  5396.1 1608.44  5410.8 1609.51
#Mann=7,-1,0
  4642.2     0.1       0  4955.3    0.05       0  4999.1    0.04       0
  5005.1    0.05       0  5087.9     0.1       0  5235.0    0.16       0
  5336.3     0.1       0
Bank Sta=4999.1,5005.1
Exp/Cntr=0.3,0.1

Type RM Length L Ch R = 1,5709,548,548,548
BEGIN DESCRIPTION:
UNT117 IN NNOGR 12.0
END DESCRIPTION:
XS GIS Cut Line= 3
      2770470.34     10051884.72      2770441.69     10051698.50
      2770334.02     10051437.76
#Sta/Elev= 30
  4745.0 1598.17  4785.8 1596.60  4790.9 1596.68  4806.7 1595.79  4847.2 1594.17
  4917.3 1592.12  4949.4 1591.40  4960.3 1590.37  4971.0 1588.90  4984.2 1584.18
  4992.7 1582.05  4999.7 1581.16  5002.5 1580.66  5005.7 1581.16  5008.1 1581.90
  5014.3 1585.70  5025.1 1588.85  5032.0 1589.51  5037.5 1590.37  5056.0 1590.45
  5079.2 1591.06  5090.7 1590.54  5098.8 1591.65  5100.9 1591.94  5136.2 1593.66
  5162.5 1594.67  5176.6 1594.66  5186.4 1594.38  5198.2 1594.53  5215.5 1595.37
#Mann=5,-1,0
  4745.0     0.1       0  4999.7    0.07       0  5005.7     0.1       0
  5098.8    0.05       0  5136.2     0.1       0
Bank Sta=4999.7,5005.7
Exp/Cntr=0.3,0.1

Type RM Length L Ch R = 1,5161,455,455,455
BEGIN DESCRIPTION:
UNT117 IN NNOGR 11.0
END DESCRIPTION:
XS GIS Cut Line= 3
      2770983.35     10051729.72      2770937.78     10051473.24
      2770653.02     10051296.40
#Sta/Elev= 30
  4692.6 1599.65  4810.9 1595.14  4830.7 1594.81  4840.9 1593.70  4932.3 1590.18
  4955.6 1589.71  4965.8 1588.86  4975.3 1586.67  4981.2 1583.36  4987.6 1578.65
  4993.5 1578.17  4996.3 1577.67  4999.5 1578.17  5017.8 1580.40  5033.1 1580.22
  5039.0 1581.64  5046.5 1582.48  5054.4 1582.67  5060.3 1585.47  5069.8 1584.79
  5075.6 1587.48  5081.8 1587.80  5133.5 1587.05  5148.9 1587.53  5154.7 1587.12
  5170.1 1587.58  5228.0 1587.64  5264.6 1588.73  5279.9 1588.33  5288.3 1588.68
#Mann=3,-1,0
  4692.6     0.1       0  4993.5    0.07       0  4999.5     0.1       0
Bank Sta=4993.5,4999.5
Exp/Cntr=0.3,0.1

Type RM Length L Ch R = 1,4706,188,188,188
BEGIN DESCRIPTION:
UNT117 IN NNOGR 10.0
END DESCRIPTION:
XS GIS Cut Line= 3
      2771337.52     10051345.63      2771179.97     10051121.68
      2770752.55     10050913.82
#Sta/Elev= 30
  4677.8 1587.76  4736.1 1587.07  4765.7 1585.61  4771.8 1586.44  4807.5 1586.34
  4923.3 1584.58  4964.4 1585.03  4975.5 1583.92  4981.2 1579.85  4986.7 1579.04
  4994.8 1576.60  4997.5 1576.10  5000.8 1576.60  5009.3 1577.22  5020.0 1579.47
  5026.3 1582.49  5031.8 1581.65  5048.8 1582.12  5054.4 1580.77  5071.4 1580.46
  5076.9 1579.43  5099.5 1579.11  5109.0 1579.88  5122.0 1583.36  5206.7 1584.41
  5296.9 1586.53  5342.0 1588.87  5347.6 1588.60  5392.7 1592.42  5426.9 1593.82
#Mann=3,-1,0
  4677.8     0.1       0  4994.8    0.07       0  5000.8     0.1       0
Bank Sta=4994.8,5000.8
Exp/Cntr=0.3,0.1

Type RM Length L Ch R = 1,4518,238,238,238
BEGIN DESCRIPTION:
Mapping XS 6f0e1262
END DESCRIPTION:
XS GIS Cut Line= 2
      2771350.56     10051188.11      2771077.12     10050705.03
#Sta/Elev= 30
  4714.2 1583.89  4748.4 1583.40  4754.2 1583.62  4764.3 1583.23  4770.1 1583.54
  4829.2 1582.26  4850.9 1582.89  4903.1 1582.46  4931.7 1582.81  4947.6 1581.70
  4960.5 1578.89  4969.2 1577.85  4983.5 1577.34  4993.6 1575.70  4996.4 1575.20
  4999.6 1575.70  5006.5 1576.82  5012.5 1579.53  5018.3 1579.65  5028.4 1578.96
  5041.0 1578.67  5050.1 1579.05  5086.9 1581.76  5099.1 1583.05  5130.9 1585.07
  5152.5 1586.14  5179.9 1586.97  5201.8 1588.71  5248.6 1590.24  5269.3 1591.01
#Mann=4,-1,0
  4714.2     0.1       0  4993.6    0.07       0  4999.6     0.1       0
  5248.6    0.16       0
Bank Sta=4993.6,4999.6
Exp/Cntr=0.3,0.1

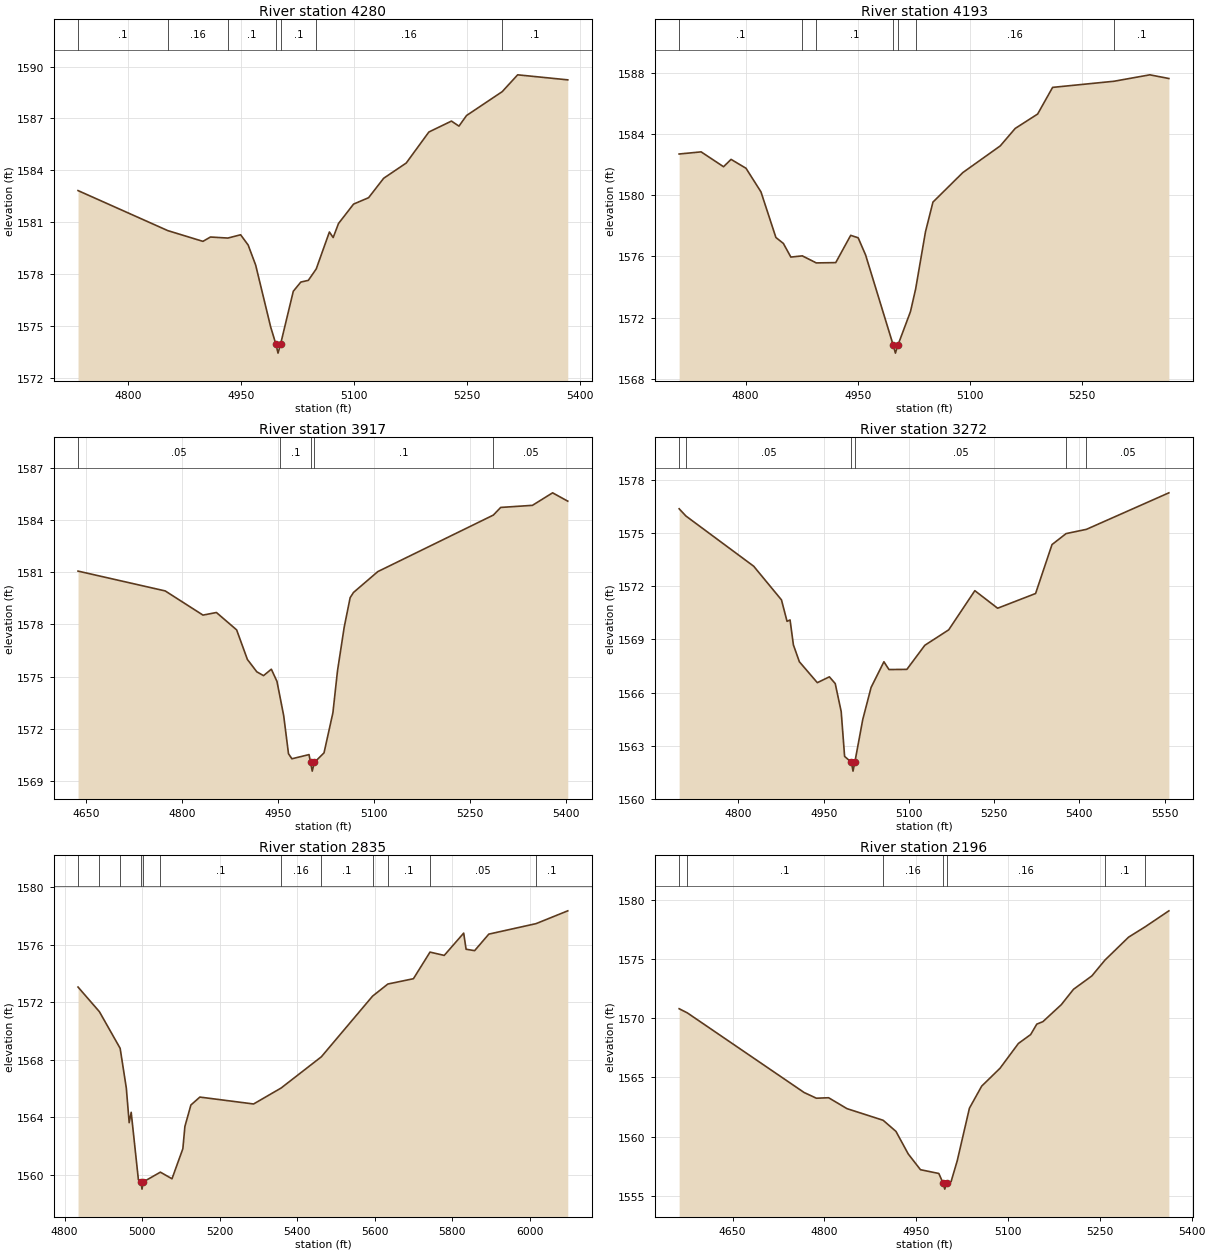
Type RM Length L Ch R = 1,4280,87,87,87
BEGIN DESCRIPTION:
UNT117 IN NNOGR 9.0
END DESCRIPTION:
XS GIS Cut Line= 2
      2771420.00     10051179.62      2771446.01     10050529.24
#Sta/Elev= 30
  4733.1 1582.84  4852.4 1580.53  4899.1 1579.91  4909.1 1580.16  4932.2 1580.10
  4949.2 1580.29  4959.2 1579.70  4969.2 1578.54  4989.2 1574.96  4996.2 1573.96
  4998.9 1573.46  5002.2 1573.96  5019.2 1577.03  5029.2 1577.56  5039.2 1577.66
  5049.7 1578.32  5067.2 1580.45  5072.2 1580.13  5079.3 1580.94  5099.3 1582.06
  5119.3 1582.43  5139.3 1583.55  5169.3 1584.43  5199.4 1586.22  5229.4 1586.85
  5239.4 1586.56  5249.4 1587.17  5296.9 1588.55  5317.4 1589.52  5384.0 1589.23
#Mann=7,-1,0
  4733.1     0.1       0  4852.4    0.16       0  4932.2     0.1       0
  4996.2    0.07       0  5002.2     0.1       0  5049.7    0.16       0
  5296.9     0.1       0
Bank Sta=4996.2,5002.2
Exp/Cntr=0.3,0.1

Type RM Length L Ch R = 1,4193,276,276,276
BEGIN DESCRIPTION:
Mapping XS e1d76bb7
END DESCRIPTION:
XS GIS Cut Line= 2
      2771513.86     10051183.16      2771516.03     10050528.26
#Sta/Elev= 30
  4711.2 1582.69  4740.6 1582.83  4770.6 1581.86  4780.6 1582.34  4800.6 1581.76
  4820.6 1580.22  4840.6 1577.24  4850.6 1576.85  4860.6 1575.96  4875.9 1576.04
  4894.6 1575.58  4920.6 1575.60  4940.6 1577.38  4950.6 1577.22  4960.6 1576.09
  4997.6 1570.19  5000.4 1569.69  5003.6 1570.19  5020.6 1572.41  5027.5 1573.89
  5040.6 1577.61  5050.6 1579.55  5090.6 1581.48  5140.6 1583.22  5160.6 1584.36
  5190.6 1585.30  5210.6 1587.04  5292.7 1587.44  5340.6 1587.86  5366.1 1587.62
#Mann=7,-1,0
  4711.2     0.1       0  4875.9    0.16       0  4894.6     0.1       0
  4997.6    0.07       0  5003.6     0.1       0  5027.5    0.16       0
  5292.7     0.1       0
Bank Sta=4997.6,5003.6
Exp/Cntr=0.3,0.1

Type RM Length L Ch R = 1,3917,645,645,645
BEGIN DESCRIPTION:
UNT117 IN NNOGR 8.0
END DESCRIPTION:
XS GIS Cut Line= 2
      2771894.78     10051179.60      2771660.65     10050451.20
#Sta/Elev= 30
  4637.1 1581.06  4773.3 1579.92  4832.3 1578.53  4853.3 1578.68  4884.9 1577.68
  4901.7 1575.98  4916.4 1575.27  4926.9 1575.05  4939.1 1575.42  4947.9 1574.72
  4952.8 1573.80  4958.4 1572.75  4965.9 1570.56  4971.2 1570.27  4998.0 1570.51
  5000.3 1570.06  5003.0 1569.56  5006.3 1570.06  5021.4 1570.61  5035.3 1572.92
  5042.4 1575.31  5052.9 1577.83  5062.2 1579.53  5067.4 1579.83  5105.4 1581.03
  5285.9 1584.28  5297.4 1584.72  5347.0 1584.84  5378.5 1585.56  5402.2 1585.08
#Mann=5,-1,0
  4637.1    0.05       0  4952.8     0.1       0  5000.3    0.07       0
  5006.3     0.1       0  5285.9    0.05       0
Bank Sta=5000.3,5006.3
Exp/Cntr=0.3,0.1

Type RM Length L Ch R = 1,3272,437,437,437
BEGIN DESCRIPTION:
UNT117 IN NNOGR 7.0
END DESCRIPTION:
XS GIS Cut Line= 3
      2772483.36     10050925.08      2772321.90     10050426.37
      2772173.48     10050123.03
#Sta/Elev= 30
  4695.7 1576.37  4707.7 1575.96  4826.9 1573.13  4875.8 1571.23  4885.6 1570.02
  4890.9 1570.10  4896.8 1568.69  4907.3 1567.74  4938.9 1566.56  4960.1 1566.89
  4970.4 1566.51  4980.9 1564.93  4986.9 1562.40  4998.9 1562.07  5001.7 1561.57
  5004.9 1562.07  5018.9 1564.49  5033.5 1566.29  5056.1 1567.74  5065.0 1567.30
  5096.5 1567.31  5128.1 1568.67  5170.1 1569.54  5216.1 1571.75  5256.2 1570.76
  5323.0 1571.59  5351.9 1574.35  5376.7 1574.97  5412.5 1575.21  5557.6 1577.27
#Mann=6,-1,0
  4695.7     0.1       0  4707.7    0.05       0  4998.9   0.035       0
  5004.9    0.05       0  5376.7     0.1       0  5412.5    0.05       0
Bank Sta=4998.9,5004.9
Exp/Cntr=0.3,0.1

Type RM Length L Ch R = 1,2835,639,639,639
BEGIN DESCRIPTION:
UNT117 IN NNOGR 6.0
END DESCRIPTION:
XS GIS Cut Line= 3
      2772831.33     10050633.24      2772636.23     10049969.88
      2772174.48     10049631.70
#Sta/Elev= 30
  4834.6 1573.06  4889.7 1571.35  4943.3 1568.80  4959.2 1566.04  4966.6 1563.63
  4971.8 1564.35  4990.4 1559.66  4996.9 1559.51  4999.7 1559.01  5002.9 1559.51
  5047.1 1560.19  5077.1 1559.73  5105.1 1561.82  5110.4 1563.37  5125.9 1564.86
  5149.0 1565.41  5287.6 1564.93  5358.7 1566.04  5462.5 1568.21  5594.7 1572.43
  5634.1 1573.27  5700.1 1573.64  5742.9 1575.49  5779.6 1575.26  5829.8 1576.81
  5836.0 1575.69  5858.0 1575.59  5894.6 1576.74  6016.6 1577.47  6098.4 1578.36
#Mann=12,-1,0
  4834.6    0.05       0  4889.7     0.1       0  4943.3    0.05       0
  4996.9   0.035       0  5002.9    0.05       0  5047.1     0.1       0
  5358.7    0.16       0  5462.5     0.1       0  5594.7    0.16       0
  5634.1     0.1       0  5742.9    0.05       0  6016.6     0.1       0
Bank Sta=4996.9,5002.9
Exp/Cntr=0.3,0.1

Type RM Length L Ch R = 1,2196,0,0,0
BEGIN DESCRIPTION:
UNT117 IN NNOGR 5.0
END DESCRIPTION:
XS GIS Cut Line= 2
      2773098.05     10050417.89      2773102.38     10049617.90
#Sta/Elev= 30
  4562.8 1570.80  4576.2 1570.45  4767.0 1563.73  4787.0 1563.25  4807.0 1563.29
  4837.0 1562.37  4896.0 1561.39  4917.0 1560.45  4937.0 1558.55  4957.0 1557.22
  4987.0 1556.90  4994.0 1556.08  4996.7 1555.58  5000.0 1556.08  5007.0 1556.21
  5017.0 1557.96  5037.0 1562.41  5057.0 1564.27  5087.0 1565.78  5117.0 1567.87
  5137.0 1568.62  5147.0 1569.50  5157.0 1569.71  5187.0 1571.14  5207.0 1572.44
  5237.0 1573.57  5258.3 1574.90  5297.0 1576.84  5324.0 1577.71  5362.8 1579.06
#Mann=7,-1,0
  4562.8    0.05       0  4576.2     0.1       0  4896.0    0.16       0
  4994.0    0.07       0  5000.0    0.16       0  5258.3     0.1       0
  5324.0    0.05       0
Bank Sta=4994,5000
Exp/Cntr=0.3,0.1

Chan Stop Cuts=-1