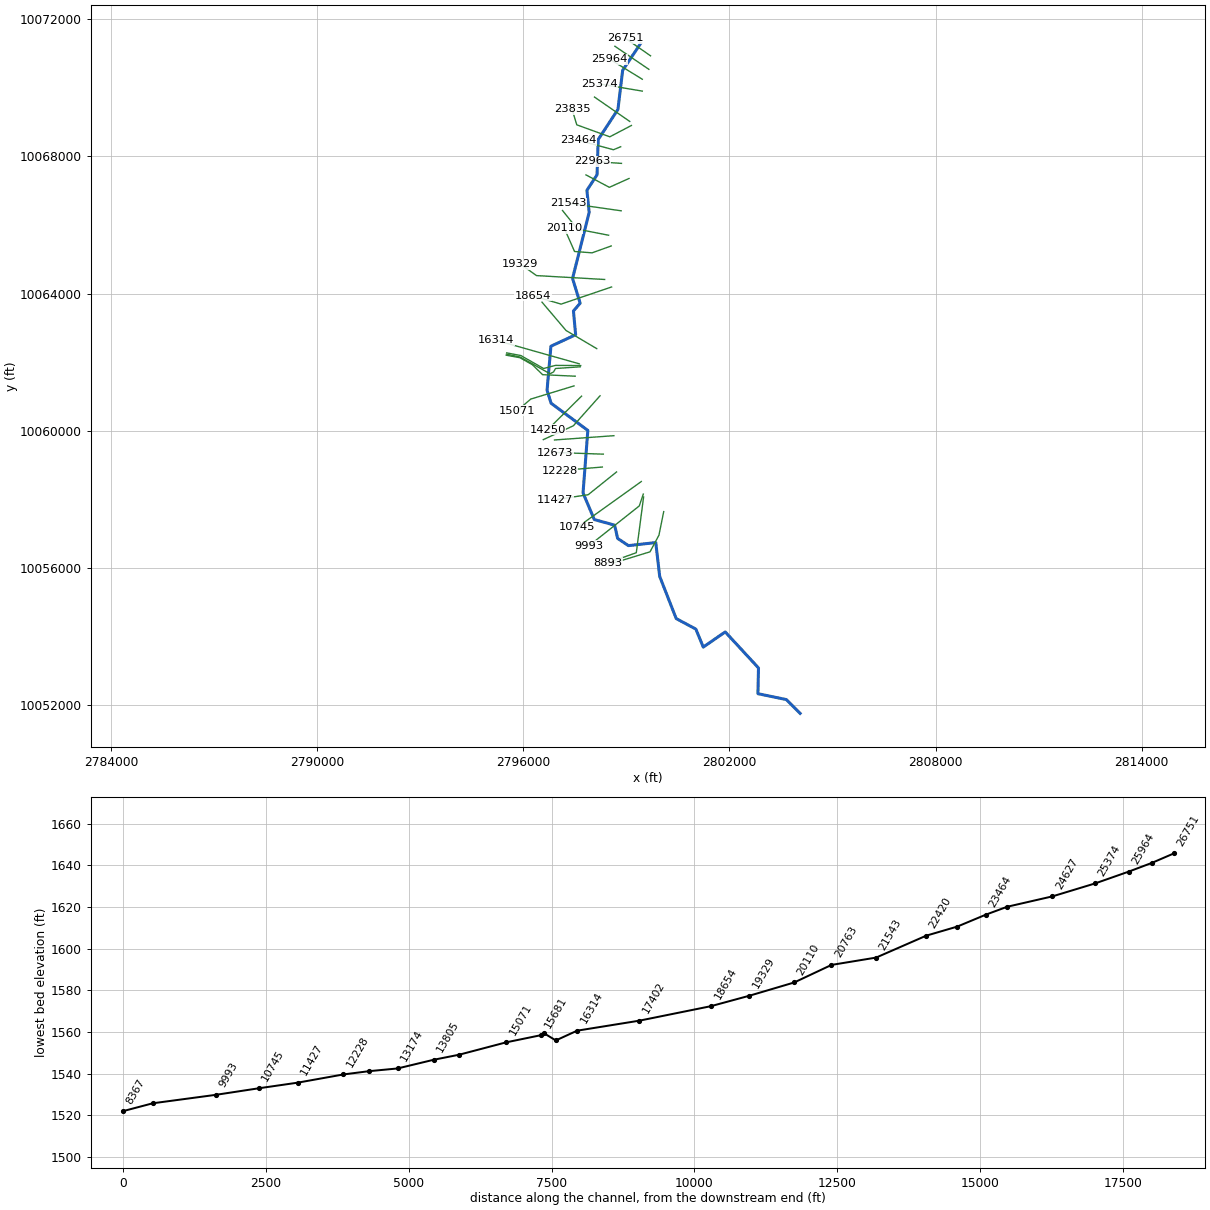
--- UNT118 IN NNOGR.prj (project) ---

Proj Title=UNT118 IN NNOGR Base Level Engineering
Current Plan=p01
Default Exp/Contr=0.3,0.1
English Units
Geom File=g01
Flow File=f01
Plan File=p01
BEGIN DESCRIPTION:
UNT118 IN NNOGR
END DESCRIPTION:

--- UNT118 IN NNOGR.p01 (plan) ---

Plan Title=Multiple Run
Short Identifier=Multiple
Geom File=g01
Flow File=f01
Subcritical Flow
K Sum by GR= 0
Std Step Tol= 0.01
Critical Tol= 0.01
Num of Std Step Trials= 20
Max Error Tol= 0.3
Flow Tol Ratio= 0.001
Split Flow NTrial= 30
Split Flow Tol= 0.02
Split Flow Ratio= 0.02
Log Output Level= 0
Friction Slope Method= 1
Unsteady Friction Slope Method= 2
Unsteady Bridges Friction Slope Method= 1
Parabolic Critical Depth
Global Vel Dist=  1 , 1 , 1
Global Log Level= 0
CheckData=True
Encroach Param= -1, 0, 0, 0
BEGIN DESCRIPTION:
Multiple Run
END DESCRIPTION:

--- UNT118 IN NNOGR.f01 (steady flow) ---

Flow Title=Multiple
Number of Profiles=7
Profile Names=10-year,25-year,50-year,1pct_min,100-year,1pct_plu,500-year
River Rch & RM= UNT118 IN NNOGR,Reach-1,26751
     773    1114    1408    1304    1763    2384    2775
River Rch & RM= UNT118 IN NNOGR,Reach-1,25964
     901    1304    1654    1534    2075    2806    3279
River Rch & RM= UNT118 IN NNOGR,Reach-1,18654
    1683    2512    3251    3071    4153    5616    6810
River Rch & RM= UNT118 IN NNOGR,Reach-1,13174
    2008    3015    3916    3709    5016    6784    8277
River Rch & RM= UNT118 IN NNOGR,Reach-1,7387
    2187    3292    4283    4063    5494    7430    9088
Boundary for River Rch & Prof#=UNT118 IN NNOGR,Reach-1,1
Up Type=0
Dn Type=3
Dn Slope=0.005
Boundary for River Rch & Prof#=UNT118 IN NNOGR,Reach-1,2
Up Type=0
Dn Type=3
Dn Slope=0.005
Boundary for River Rch & Prof#=UNT118 IN NNOGR,Reach-1,3
Up Type=0
Dn Type=3
Dn Slope=0.005
Boundary for River Rch & Prof#=UNT118 IN NNOGR,Reach-1,4
Up Type=0
Dn Type=3
Dn Slope=0.005
Boundary for River Rch & Prof#=UNT118 IN NNOGR,Reach-1,5
Up Type=0
Dn Type=3
Dn Slope=0.005
Boundary for River Rch & Prof#=UNT118 IN NNOGR,Reach-1,6
Up Type=0
Dn Type=3
Dn Slope=0.005
Boundary for River Rch & Prof#=UNT118 IN NNOGR,Reach-1,7
Up Type=0
Dn Type=3
Dn Slope=0.005

--- UNT118 IN NNOGR.g01 (geometry) ---

Geom Title=Existing Conditions

River Reach=UNT118 IN NNOGR,Reach-1
Reach XY= 30
      2799412.10     10071281.50      2798892.09     10070502.29
      2798754.94     10069365.19      2798180.82     10068487.69
      2798146.56     10067459.61      2797851.64     10067007.70
      2797917.26     10066364.38      2797433.80     10064441.12
      2797654.89     10063719.21      2797459.96     10063493.57
      2797523.67     10062800.33      2796804.19     10062466.10
      2796691.45     10061184.97      2796809.19     10060804.58
      2797878.47     10060013.73      2797738.82     10058193.16
      2798066.20     10057417.07      2798658.57     10057253.29
      2798746.01     10056867.45      2799059.93     10056657.18
      2799856.38     10056746.40      2799970.93     10055759.58
      2800451.03     10054532.27      2801023.16     10054225.47
      2801239.31     10053701.54      2801878.69     10054143.21
      2802846.88     10053093.32      2802830.53     10052343.72
      2803657.75     10052172.00      2804059.51     10051770.25

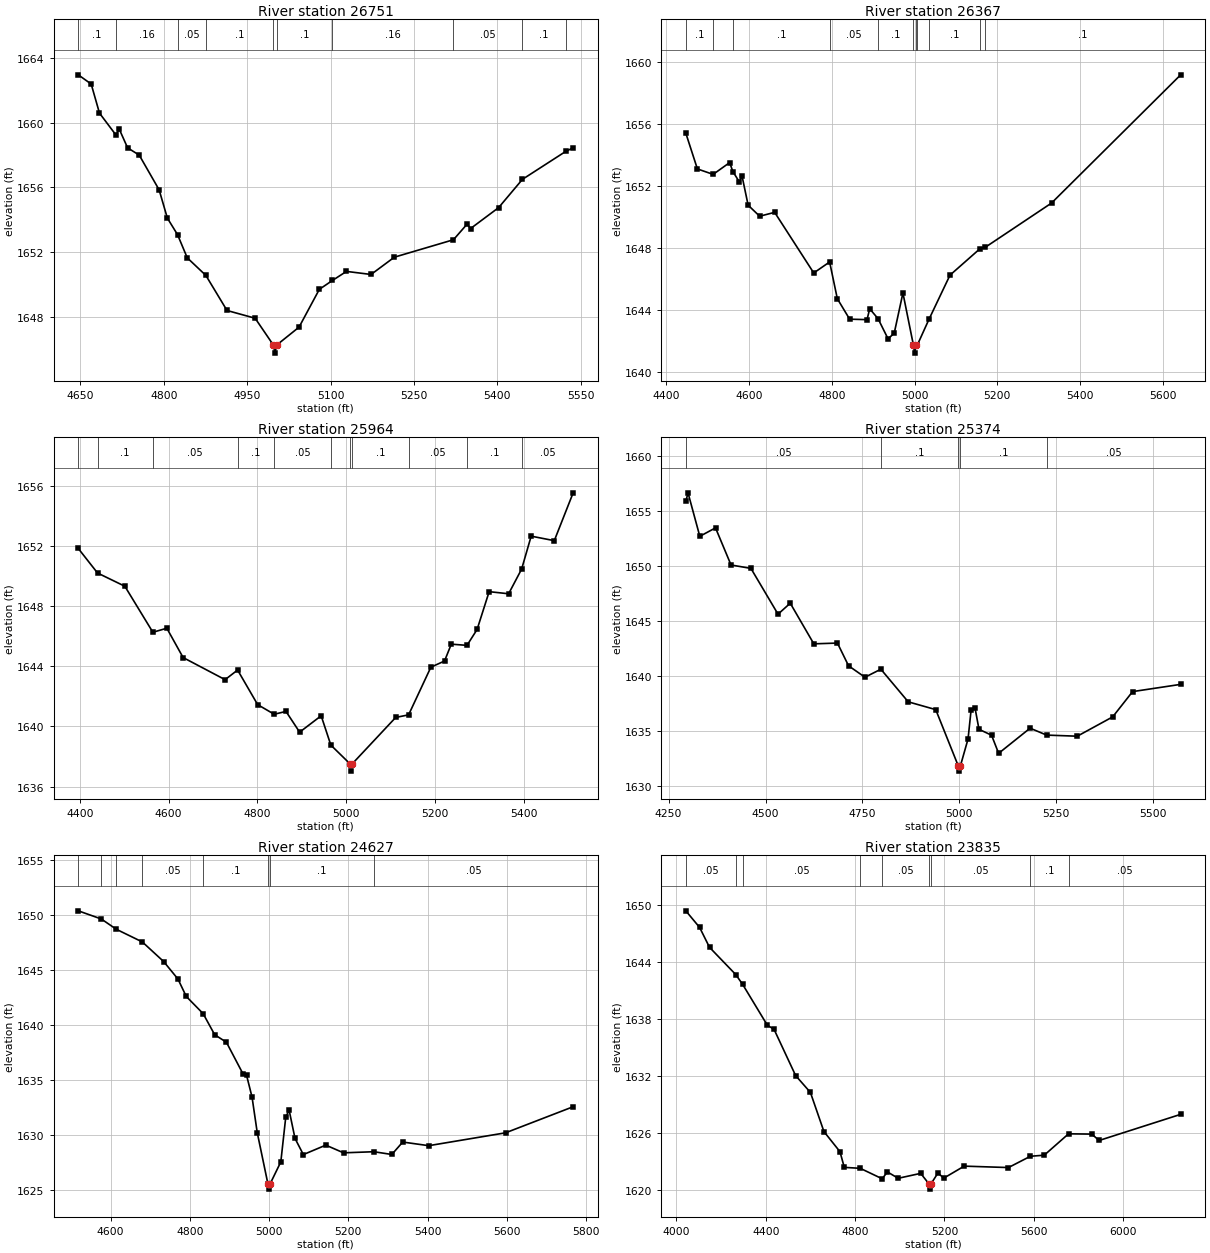
Type RM Length L Ch R = 1,26751,384,384,384
BEGIN DESCRIPTION:
UNT118 IN NNOGR 53.0
END DESCRIPTION:
XS GIS Cut Line= 2
      2799704.16     10070926.59      2798974.06     10071435.73
#Sta/Elev= 30
  4646.3 1662.97  4669.5 1662.40  4684.4 1660.60  4713.9 1659.25  4720.1 1659.60
  4735.0 1658.45  4755.9 1658.00  4791.7 1655.85  4806.5 1654.10  4824.9 1653.07
  4842.3 1651.64  4875.8 1650.55  4913.8 1648.38  4964.4 1647.90  4997.2 1646.24
  4999.9 1645.74  5003.2 1646.24  5043.4 1647.35  5079.9 1649.69  5103.5 1650.24
  5128.7 1650.80  5172.9 1650.61  5214.8 1651.68  5321.1 1652.76  5345.7 1653.73
  5351.8 1653.45  5402.4 1654.75  5445.2 1656.50  5523.6 1658.24  5536.4 1658.45
#Mann=10,-1,0
  4646.3     0.1       0  4713.9    0.16       0  4824.9    0.05       0
  4875.8     0.1       0  4997.2    0.07       0  5003.2     0.1       0
  5103.5    0.16       0  5321.1    0.05       0  5445.2     0.1       0
  5523.6    0.05       0
Bank Sta=4997.2,5003.2
Exp/Cntr=0.3,0.1

Type RM Length L Ch R = 1,26367,403,403,403
BEGIN DESCRIPTION:
UNT118 IN NNOGR 52.0
END DESCRIPTION:
XS GIS Cut Line= 2
      2799656.15     10070532.70      2798666.64     10071205.18
#Sta/Elev= 30
  4447.1 1655.39  4475.1 1653.08  4513.2 1652.73  4553.1 1653.49  4560.9 1652.91
  4576.8 1652.23  4582.9 1652.64  4597.8 1650.74  4625.7 1650.03  4661.9 1650.28
  4756.4 1646.37  4794.8 1647.08  4813.4 1644.71  4843.2 1643.39  4885.2 1643.36
  4891.7 1644.06  4911.9 1643.42  4936.1 1642.12  4951.0 1642.49  4972.0 1645.08
  4997.5 1641.70  5000.2 1641.20  5003.5 1641.70  5006.8 1641.72  5034.8 1643.37
  5085.8 1646.23  5157.7 1647.92  5171.3 1648.03  5331.3 1650.88  5643.5 1659.15
#Mann=11,-1,0
  4447.1     0.1       0  4513.2    0.05       0  4560.9     0.1       0
  4794.8    0.05       0  4911.9     0.1       0  4997.5    0.07       0
  5003.5     0.1       0  5006.8    0.05       0  5034.8     0.1       0
  5157.7    0.05       0  5171.3     0.1       0
Bank Sta=4997.5,5003.5
Exp/Cntr=0.3,0.1

Type RM Length L Ch R = 1,25964,590,590,590
BEGIN DESCRIPTION:
UNT118 IN NNOGR 51.0
END DESCRIPTION:
XS GIS Cut Line= 2
      2799464.02     10070244.51      2798514.67     10070829.46
#Sta/Elev= 30
  4396.3 1651.83  4439.7 1650.20  4501.2 1649.32  4564.4 1646.26  4595.8 1646.53
  4632.5 1644.58  4727.1 1643.11  4755.3 1643.75  4800.5 1641.45  4837.8 1640.81
  4864.3 1641.00  4895.1 1639.62  4943.6 1640.71  4965.4 1638.76  5008.1 1637.53
  5010.8 1637.03  5014.1 1637.53  5111.6 1640.60  5140.6 1640.77  5190.8 1643.94
  5221.6 1644.35  5236.8 1645.47  5272.2 1645.39  5295.0 1646.45  5322.1 1648.96
  5366.0 1648.82  5395.3 1650.46  5416.8 1652.65  5468.9 1652.35  5511.4 1655.53
#Mann=11,-1,0
  4396.3    0.05       0  4439.7     0.1       0  4564.4    0.05       0
  4755.3     0.1       0  4837.8    0.05       0  4965.4     0.1       0
  5008.1    0.07       0  5014.1     0.1       0  5140.6    0.05       0
  5272.2     0.1       0  5395.3    0.05       0
Bank Sta=5008.1,5014.1
Exp/Cntr=0.3,0.1

Type RM Length L Ch R = 1,25374,747,747,747
BEGIN DESCRIPTION:
UNT118 IN NNOGR 50.0
END DESCRIPTION:
XS GIS Cut Line= 2
      2799464.04     10069898.67      2798205.56     10070110.02
#Sta/Elev= 30
  4294.5 1655.90  4300.2 1656.68  4330.6 1652.72  4371.1 1653.49  4411.1 1650.11
  4462.4 1649.80  4532.3 1645.63  4563.8 1646.63  4624.6 1642.93  4685.5 1643.00
  4714.2 1640.93  4756.5 1639.89  4797.5 1640.62  4868.0 1637.65  4939.0 1636.94
  4996.8 1631.84  4999.6 1631.34  5002.8 1631.84  5022.3 1634.27  5030.2 1636.91
  5040.4 1637.07  5050.5 1635.15  5082.9 1634.61  5101.2 1632.96  5182.3 1635.25
  5225.0 1634.62  5304.0 1634.52  5395.3 1636.28  5446.6 1638.58  5570.6 1639.24
#Mann=5,-1,0
  4294.5    0.05       0  4797.5     0.1       0  4996.8    0.07       0
  5002.8     0.1       0  5225.0    0.05       0
Bank Sta=4996.8,5002.8
Exp/Cntr=0.3,0.1

Type RM Length L Ch R = 1,24627,792,792,792
BEGIN DESCRIPTION:
UNT118 IN NNOGR 49.0
END DESCRIPTION:
XS GIS Cut Line= 2
      2799098.98     10069014.87      2798072.29     10069724.92
#Sta/Elev= 30
  4518.7 1650.42  4576.7 1649.68  4614.8 1648.74  4680.3 1647.59  4734.3 1645.80
  4770.1 1644.22  4791.0 1642.64  4833.7 1641.07  4862.7 1639.16  4892.4 1638.47
  4934.3 1635.59  4943.1 1635.48  4957.0 1633.49  4970.1 1630.26  4996.9 1625.62
  4999.6 1625.12  5002.9 1625.62  5029.6 1627.60  5042.1 1631.68  5050.6 1632.29
  5065.4 1629.73  5086.4 1628.26  5143.1 1629.12  5187.8 1628.42  5264.3 1628.52
  5309.6 1628.27  5337.1 1629.40  5402.7 1629.07  5596.6 1630.24  5767.0 1632.61
#Mann=8,-1,0
  4518.7     0.1       0  4576.7    0.05       0  4614.8     0.1       0
  4680.3    0.05       0  4833.7     0.1       0  4996.9    0.07       0
  5002.9     0.1       0  5264.3    0.05       0
Bank Sta=4996.9,5002.9
Exp/Cntr=0.3,0.1

Type RM Length L Ch R = 1,23835,371,371,371
BEGIN DESCRIPTION:
UNT118 IN NNOGR 47.0
END DESCRIPTION:
XS GIS Cut Line= 4
      2799148.30     10068897.59      2798518.09     10068566.87
      2797557.16     10068915.83      2797416.52     10069376.80
#Sta/Elev= 30
  4042.0 1649.42  4103.9 1647.67  4148.1 1645.58  4265.7 1642.71  4296.5 1641.68
  4407.1 1637.38  4437.1 1636.95  4533.8 1632.08  4599.9 1630.31  4660.5 1626.19
  4732.3 1624.07  4751.7 1622.42  4823.1 1622.32  4921.3 1621.22  4944.8 1621.94
  4993.1 1621.27  5093.8 1621.79  5132.5 1620.63  5135.3 1620.13  5138.5 1620.63
  5171.4 1621.84  5196.7 1621.28  5288.6 1622.55  5486.8 1622.40  5585.2 1623.59
  5647.0 1623.70  5755.9 1625.95  5860.0 1625.92  5892.8 1625.25  6258.0 1628.00
#Mann=9,-1,0
  4042.0    0.05       0  4265.7     0.1       0  4296.5    0.05       0
  4823.1     0.1       0  4921.3    0.05       0  5132.5   0.035       0
  5138.5    0.05       0  5585.2     0.1       0  5755.9    0.05       0
Bank Sta=5132.5,5138.5
Exp/Cntr=0.3,0.1

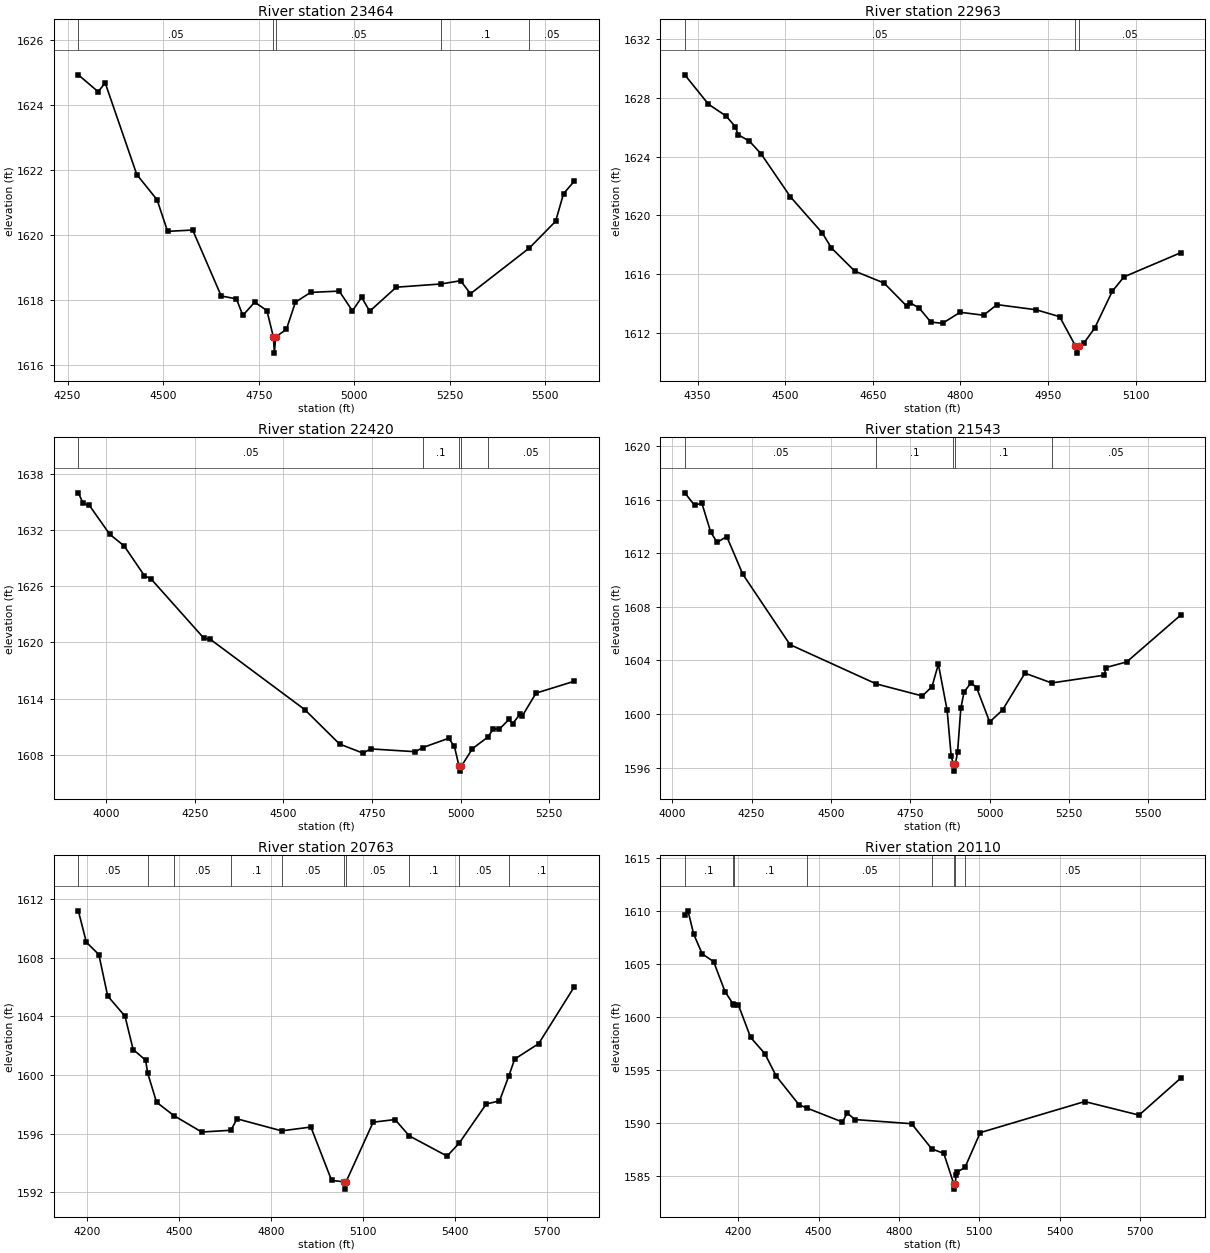
Type RM Length L Ch R = 1,23464,501,501,501
BEGIN DESCRIPTION:
Mapping XS e27483f0
END DESCRIPTION:
XS GIS Cut Line= 3
      2798834.57     10068277.22      2798624.53     10068190.42
      2797591.62     10068469.45
#Sta/Elev= 30
  4278.1 1624.93  4329.9 1624.41  4348.4 1624.68  4431.0 1621.86  4484.2 1621.08
  4511.6 1620.11  4577.3 1620.15  4651.9 1618.12  4691.8 1618.03  4708.5 1617.52
  4739.5 1617.93  4771.5 1617.67  4788.3 1616.86  4791.1 1616.36  4794.3 1616.86
  4822.4 1617.09  4846.1 1617.93  4886.0 1618.23  4960.6 1618.27  4995.3 1617.66
  5019.2 1618.08  5040.4 1617.65  5109.8 1618.39  5227.3 1618.49  5278.2 1618.59
  5304.1 1618.19  5458.4 1619.60  5526.8 1620.42  5547.5 1621.27  5575.3 1621.65
#Mann=5,-1,0
  4278.1    0.05       0  4788.3   0.035       0  4794.3    0.05       0
  5227.3     0.1       0  5458.4    0.05       0
Bank Sta=4788.3,4794.3
Exp/Cntr=0.3,0.1

Type RM Length L Ch R = 1,22963,543,543,543
BEGIN DESCRIPTION:
UNT118 IN NNOGR 46.0
END DESCRIPTION:
XS GIS Cut Line= 2
      2798858.86     10067792.86      2798011.69     10067850.03
#Sta/Elev= 30
  4328.1 1629.56  4368.6 1627.56  4398.7 1626.76  4414.5 1626.04  4419.5 1625.48
  4438.7 1625.05  4458.8 1624.18  4508.9 1621.26  4563.9 1618.78  4579.1 1617.78
  4619.2 1616.20  4669.3 1615.39  4708.4 1613.81  4713.4 1614.06  4729.4 1613.69
  4749.5 1612.73  4769.5 1612.65  4799.6 1613.40  4839.7 1613.20  4862.8 1613.92
  4929.9 1613.57  4970.0 1613.10  4997.0 1611.12  4999.8 1610.62  5003.0 1611.12
  5012.2 1611.34  5030.1 1612.33  5060.2 1614.83  5080.2 1615.81  5177.2 1617.45
#Mann=3,-1,0
  4328.1    0.05       0  4997.0   0.035       0  5003.0    0.05       0
Bank Sta=4997,5003
Exp/Cntr=0.3,0.1

Type RM Length L Ch R = 1,22420,877,877,877
BEGIN DESCRIPTION:
UNT118 IN NNOGR 44.0
END DESCRIPTION:
XS GIS Cut Line= 3
      2799078.03     10067353.34      2798505.07     10067095.51
      2797825.35     10067457.51
#Sta/Elev= 30
  3921.8 1635.94  3935.4 1634.82  3953.1 1634.59  4010.3 1631.52  4051.2 1630.27
  4108.4 1627.09  4126.1 1626.79  4276.0 1620.43  4293.6 1620.33  4560.1 1612.83
  4658.6 1609.15  4724.5 1608.18  4746.5 1608.63  4872.6 1608.33  4893.0 1608.77
  4966.1 1609.76  4982.4 1608.90  4995.7 1606.76  4998.5 1606.26  5001.7 1606.76
  5033.4 1608.66  5077.4 1609.91  5092.3 1610.79  5108.6 1610.71  5136.2 1611.77
  5146.7 1611.33  5168.8 1612.38  5174.5 1612.18  5212.7 1614.58  5320.2 1615.84
#Mann=5,-1,0
  3921.8    0.05       0  4893.0     0.1       0  4995.7    0.07       0
  5001.7     0.1       0  5077.4    0.05       0
Bank Sta=4995.7,5001.7
Exp/Cntr=0.3,0.1

Type RM Length L Ch R = 1,21543,780,780,780
BEGIN DESCRIPTION:
UNT118 IN NNOGR 43.0
END DESCRIPTION:
XS GIS Cut Line= 2
      2798849.19     10066411.52      2797302.99     10066632.41
#Sta/Elev= 30
  4039.7 1616.51  4070.7 1615.57  4093.3 1615.75  4121.2 1613.59  4141.4 1612.81
  4171.8 1613.25  4222.3 1610.44  4371.1 1605.18  4642.8 1602.25  4787.9 1601.35
  4818.3 1602.04  4838.5 1603.72  4866.1 1600.28  4878.9 1596.85  4886.0 1596.24
  4888.7 1595.74  4892.0 1596.24  4899.1 1597.20  4909.2 1600.42  4919.3 1601.64
  4941.9 1602.35  4959.7 1601.92  5000.1 1599.41  5040.5 1600.30  5111.2 1603.05
  5195.2 1602.32  5361.1 1602.90  5366.1 1603.47  5431.8 1603.89  5601.6 1607.38
#Mann=5,-1,0
  4039.7    0.05       0  4642.8     0.1       0  4886.0    0.07       0
  4892.0     0.1       0  5195.2    0.05       0
Bank Sta=4886,4892
Exp/Cntr=0.3,0.1

Type RM Length L Ch R = 1,20763,653,653,653
BEGIN DESCRIPTION:
UNT118 IN NNOGR 42.0
END DESCRIPTION:
XS GIS Cut Line= 3
      2798484.21     10065699.68      2797577.99     10065876.76
      2797141.41     10066419.89
#Sta/Elev= 30
  4170.1 1611.18  4196.3 1609.04  4237.1 1608.20  4266.0 1605.38  4322.6 1604.00
  4349.2 1601.73  4389.9 1601.01  4396.8 1600.12  4425.7 1598.14  4482.3 1597.23
  4573.3 1596.11  4668.7 1596.23  4688.5 1597.01  4834.7 1596.19  4930.0 1596.45
  4997.8 1592.81  5039.0 1592.72  5041.8 1592.22  5045.0 1592.72  5133.5 1596.78
  5205.0 1596.96  5251.3 1595.85  5375.1 1594.47  5414.9 1595.36  5503.1 1598.02
  5546.3 1598.23  5576.5 1599.91  5595.9 1601.08  5674.3 1602.13  5790.3 1605.99
#Mann=10,-1,0
  4170.1    0.05       0  4396.8     0.1       0  4482.3    0.05       0
  4668.7     0.1       0  4834.7    0.05       0  5039.0   0.035       0
  5045.0    0.05       0  5251.3     0.1       0  5414.9    0.05       0
  5576.5     0.1       0
Bank Sta=5039,5045
Exp/Cntr=0.3,0.1

Type RM Length L Ch R = 1,20110,781,781,781
BEGIN DESCRIPTION:
UNT118 IN NNOGR 41.0
END DESCRIPTION:
XS GIS Cut Line= 4
      2798559.72     10065387.17      2798002.47     10065186.66
      2797492.05     10065225.72      2797190.37     10065909.70
#Sta/Elev= 30
  4000.3 1609.69  4012.3 1610.04  4033.5 1607.84  4065.4 1605.98  4107.9 1605.25
  4150.4 1602.43  4181.3 1601.22  4182.6 1601.19  4200.3 1601.17  4246.1 1598.10
  4299.2 1596.57  4341.7 1594.45  4426.7 1591.75  4455.9 1591.44  4588.9 1590.12
  4606.6 1590.96  4636.7 1590.35  4847.3 1589.96  4922.9 1587.58  4967.6 1587.16
  5004.7 1584.29  5007.5 1583.79  5010.7 1584.29  5012.8 1585.12  5017.8 1585.41
  5046.5 1585.83  5103.7 1589.12  5493.8 1592.05  5696.8 1590.77  5852.0 1594.25
#Mann=8,-1,0
  4000.3     0.1       0  4181.3    0.05       0  4182.6     0.1       0
  4455.9    0.05       0  4922.9     0.1       0  5004.7    0.07       0
  5010.7     0.1       0  5046.5    0.05       0
Bank Sta=5004.7,5010.7
Exp/Cntr=0.3,0.1

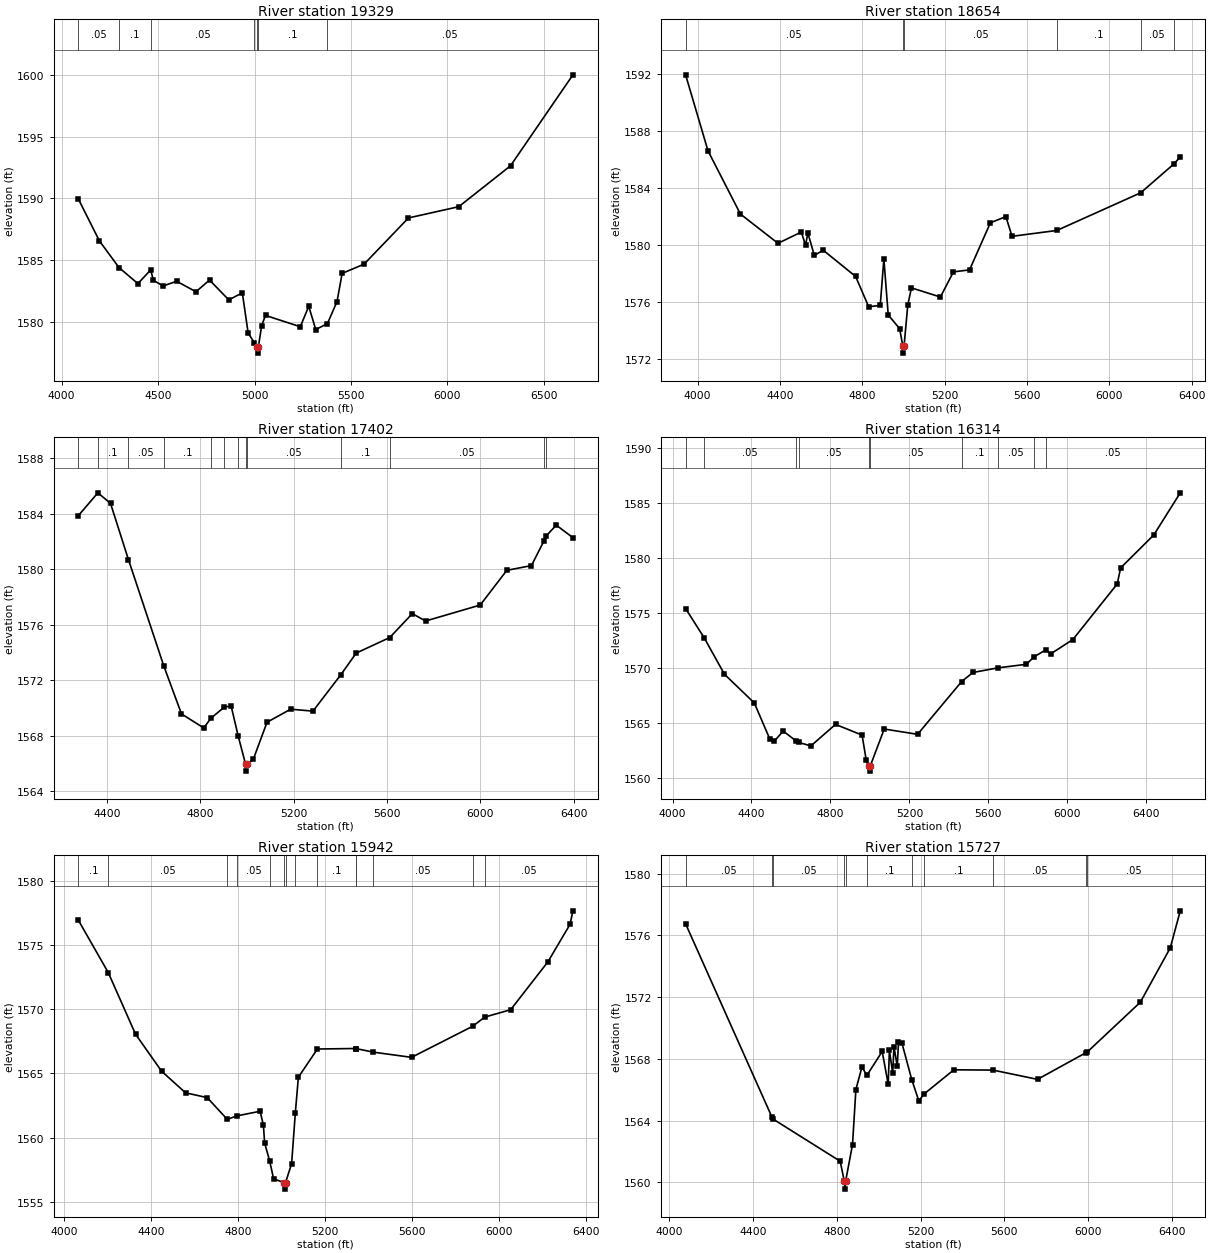
Type RM Length L Ch R = 1,19329,675,675,675
BEGIN DESCRIPTION:
UNT118 IN NNOGR 39.0
END DESCRIPTION:
XS GIS Cut Line= 3
      2798367.64     10064410.91      2796384.95     10064523.76
      2795913.15     10064858.53
#Sta/Elev= 30
  4086.3 1589.97  4195.7 1586.56  4297.5 1584.39  4395.5 1583.09  4461.5 1584.20
  4476.1 1583.35  4526.2 1582.90  4596.3 1583.28  4696.5 1582.43  4766.6 1583.38
  4866.7 1581.77  4936.8 1582.34  4966.9 1579.08  4998.6 1578.31  5014.0 1577.95
  5016.7 1577.45  5020.0 1577.95  5037.0 1579.69  5057.0 1580.51  5237.3 1579.59
  5281.1 1581.25  5317.5 1579.36  5378.0 1579.85  5427.6 1581.63  5454.3 1583.92
  5567.9 1584.67  5798.2 1588.42  6058.7 1589.33  6327.1 1592.65  6650.7 1600.03
#Mann=7,-1,0
  4086.3    0.05       0  4297.5     0.1       0  4461.5    0.05       0
  4998.6     0.1       0  5014.0    0.07       0  5020.0     0.1       0
  5378.0    0.05       0
Bank Sta=5014,5020
Exp/Cntr=0.3,0.1

Type RM Length L Ch R = 1,18654,1252,1252,1252
BEGIN DESCRIPTION:
UNT118 IN NNOGR 37.0
END DESCRIPTION:
XS GIS Cut Line= 3
      2798570.66     10064192.44      2797100.83     10063692.89
      2796284.31     10063933.04
#Sta/Elev= 30
  3941.4 1591.91  4050.4 1586.58  4207.8 1582.16  4390.3 1580.11  4503.5 1580.90
  4524.6 1579.97  4535.2 1580.85  4566.9 1579.26  4609.9 1579.63  4767.5 1577.79
  4830.9 1575.67  4887.1 1575.76  4904.8 1579.01  4926.0 1575.09  4981.2 1574.14
  4996.9 1572.92  4999.6 1572.42  5002.9 1572.92  5021.0 1575.79  5038.7 1576.99
  5179.4 1576.35  5242.8 1578.11  5321.1 1578.25  5422.4 1581.55  5497.6 1581.98
  5527.5 1580.60  5745.0 1581.01  6152.9 1583.65  6313.3 1585.66  6344.9 1586.16
#Mann=6,-1,0
  3941.4    0.05       0  4996.9   0.035       0  5002.9    0.05       0
  5745.0     0.1       0  6152.9    0.05       0  6313.3     0.1       0
Bank Sta=4996.9,5002.9
Exp/Cntr=0.3,0.1

Type RM Length L Ch R = 1,17402,1088,1088,1088
BEGIN DESCRIPTION:
UNT118 IN NNOGR 36.0
END DESCRIPTION:
XS GIS Cut Line= 3
      2798138.35     10062396.00      2797244.92     10062924.37
      2796544.38     10063749.66
#Sta/Elev= 30
  4276.6 1583.85  4360.7 1585.50  4414.8 1584.74  4491.9 1580.68  4643.5 1573.02
  4719.0 1569.58  4814.5 1568.57  4844.8 1569.26  4901.0 1570.05  4931.6 1570.17
  4962.5 1567.96  4993.8 1565.96  4996.5 1565.46  4999.8 1565.96  5027.1 1566.32
  5085.7 1568.98  5187.0 1569.92  5282.6 1569.78  5402.1 1572.40  5468.0 1573.96
  5611.8 1575.08  5708.5 1576.80  5765.6 1576.27  5999.6 1577.42  6113.8 1579.92
  6219.2 1580.26  6273.3 1582.05  6283.4 1582.42  6325.8 1583.17  6397.1 1582.27
#Mann=13,-1,0
  4276.6    0.05       0  4360.7     0.1       0  4491.9    0.05       0
  4643.5     0.1       0  4844.8    0.05       0  4901.0     0.1       0
  4962.5    0.05       0  4993.8   0.035       0  4999.8    0.05       0
  5402.1     0.1       0  5611.8    0.05       0  6273.3     0.1       0
  6283.4    0.05       0
Bank Sta=4993.8,4999.8
Exp/Cntr=0.3,0.1

Type RM Length L Ch R = 1,16314,372,372,372
BEGIN DESCRIPTION:
UNT118 IN NNOGR 34.0
END DESCRIPTION:
XS GIS Cut Line= 2
      2797629.16     10061954.12      2795217.97     10062636.17
#Sta/Elev= 30
  4066.2 1575.41  4160.9 1572.74  4263.0 1569.45  4414.4 1566.84  4493.0 1563.56
  4513.8 1563.35  4560.7 1564.29  4626.7 1563.39  4639.4 1563.26  4700.9 1562.95
  4825.6 1564.90  4960.2 1563.93  4981.4 1561.63  4996.3 1561.16  4999.1 1560.66
  5002.3 1561.16  5072.4 1564.48  5241.3 1564.00  5464.7 1568.79  5521.9 1569.61
  5648.1 1570.03  5792.1 1570.35  5831.6 1571.03  5890.8 1571.66  5915.8 1571.30
  6028.1 1572.60  6252.6 1577.64  6270.1 1579.10  6438.0 1582.09  6572.0 1585.91
#Mann=10,-1,0
  4066.2     0.1       0  4160.9    0.05       0  4626.7     0.1       0
  4639.4    0.05       0  4996.3   0.035       0  5002.3    0.05       0
  5464.7     0.1       0  5648.1    0.05       0  5831.6     0.1       0
  5890.8    0.05       0
Bank Sta=4996.3,5002.3
Exp/Cntr=0.3,0.1

Type RM Length L Ch R = 1,15942,215,215,215
BEGIN DESCRIPTION:
Mapping XS f9c0bcf1
END DESCRIPTION:
XS GIS Cut Line= 5
      2797671.76     10061902.80      2796934.76     10061908.01
      2796591.01     10061816.87      2795929.55     10062194.47
      2795515.46     10062272.60
#Sta/Elev= 30
  4064.2 1576.95  4202.1 1572.86  4327.5 1568.06  4447.5 1565.17  4557.5 1563.49
  4657.5 1563.11  4749.4 1561.42  4794.7 1561.69  4900.8 1562.05  4915.9 1560.96
  4921.5 1559.58  4944.3 1558.20  4962.9 1556.78  5011.6 1556.48  5014.4 1555.98
  5017.6 1556.48  5045.7 1557.97  5062.9 1561.95  5076.7 1564.70  5164.3 1566.90
  5339.9 1566.94  5340.6 1566.94  5419.9 1566.66  5597.3 1566.25  5878.3 1568.67
  5934.4 1569.39  6053.2 1569.96  6224.9 1573.70  6326.7 1576.62  6339.9 1577.67
#Mann=14,-1,0
  4064.2     0.1       0  4202.1    0.05       0  4749.4     0.1       0
  4794.7    0.05       0  4944.3     0.1       0  5011.6    0.07       0
  5017.6     0.1       0  5062.9    0.05       0  5164.3     0.1       0
  5339.9    0.05       0  5340.6     0.1       0  5419.9    0.05       0
  5878.3     0.1       0  5934.4    0.05       0
Bank Sta=5011.6,5017.6
Exp/Cntr=0.3,0.1

Type RM Length L Ch R = 1,15727,46,46,46
BEGIN DESCRIPTION:
UNT118 IN NNOGR 33.0
END DESCRIPTION:
XS GIS Cut Line= 6
      2797658.72     10061866.35      2796937.36     10061816.87
      2796882.68     10061717.91      2796778.51     10061663.22
      2795911.32     10062150.20      2795511.91     10062235.79
#Sta/Elev= 30
  4077.9 1576.76  4489.9 1564.23  4497.1 1564.08  4816.0 1561.36  4835.8 1560.05
  4838.6 1559.55  4841.8 1560.05  4874.9 1562.44  4891.0 1566.01  4920.2 1567.48
  4943.2 1566.92  5016.6 1568.48  5045.3 1566.35  5051.0 1568.55  5067.0 1567.05
  5072.7 1568.80  5088.6 1567.51  5094.4 1569.07  5110.3 1569.05  5157.8 1566.65
  5191.3 1565.28  5218.3 1565.74  5359.0 1567.29  5545.7 1567.27  5758.2 1566.67
  5988.3 1568.39  5995.5 1568.44  6249.0 1571.67  6392.2 1575.20  6439.8 1577.60
#Mann=11,-1,0
  4077.9    0.05       0  4489.9    0.16       0  4497.1    0.05       0
  4835.8    0.07       0  4841.8    0.05       0  4943.2     0.1       0
  5157.8    0.05       0  5218.3     0.1       0  5545.7    0.05       0
  5988.3     0.1       0  5995.5    0.05       0
Bank Sta=4835.8,4841.8
Exp/Cntr=0.3,0.1

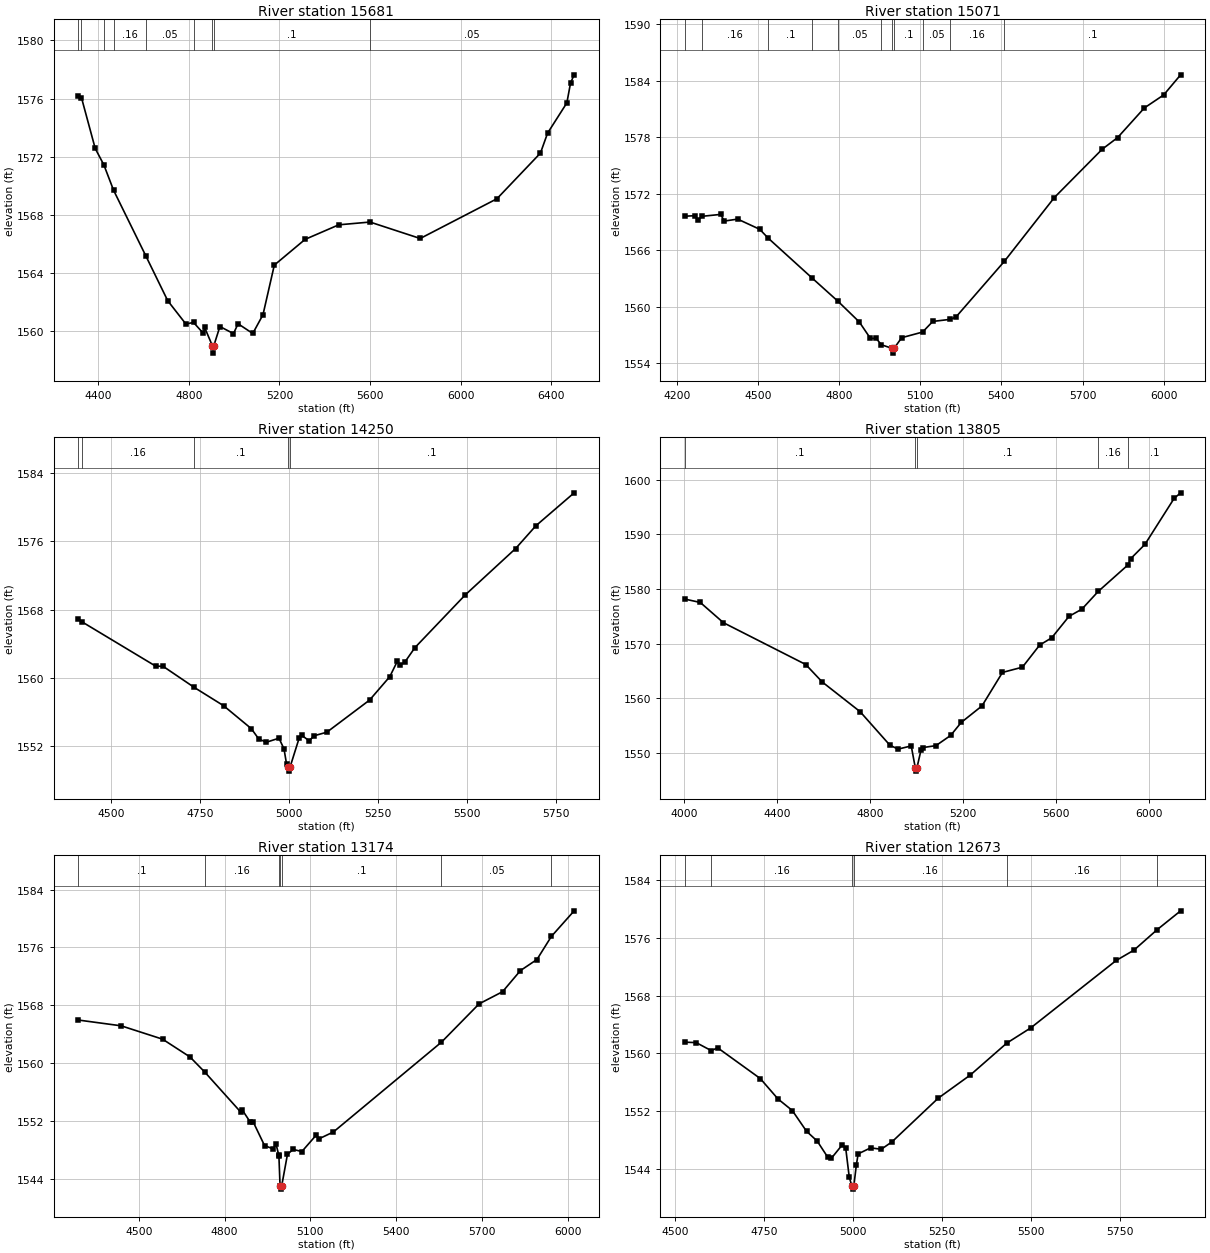
Type RM Length L Ch R = 1,15681,610,610,610
BEGIN DESCRIPTION:
Mapping XS ca2bc7b5
END DESCRIPTION:
XS GIS Cut Line= 5
      2797512.87     10061592.91      2796562.36     10061637.18
      2796262.88     10061928.85      2795900.91     10062131.97
      2795502.97     10062204.80
#Sta/Elev= 30
  4312.0 1576.15  4325.7 1576.07  4386.5 1572.57  4424.7 1571.44  4467.5 1569.70
  4609.2 1565.21  4706.8 1562.10  4786.9 1560.50  4820.6 1560.61  4864.5 1559.85
  4869.5 1560.27  4904.0 1559.00  4906.8 1558.50  4910.0 1559.00  4937.1 1560.33
  4997.1 1559.84  5017.2 1560.52  5082.1 1559.85  5127.3 1561.14  5177.3 1564.55
  5313.3 1566.32  5461.9 1567.32  5599.8 1567.51  5821.4 1566.38  6160.1 1569.11
  6352.3 1572.25  6383.8 1573.62  6468.9 1575.70  6485.4 1577.08  6501.2 1577.63
#Mann=9,-1,0
  4312.0     0.1       0  4325.7    0.16       0  4424.7     0.1       0
  4467.5    0.16       0  4609.2    0.05       0  4820.6     0.1       0
  4904.0    0.07       0  4910.0     0.1       0  5599.8    0.05       0
Bank Sta=4904,4910
Exp/Cntr=0.3,0.1

Type RM Length L Ch R = 1,15071,821,821,821
BEGIN DESCRIPTION:
UNT118 IN NNOGR 31.0
END DESCRIPTION:
XS GIS Cut Line= 3
      2797475.48     10061310.48      2796217.03     10060926.22
      2795823.30     10060590.11
#Sta/Elev= 30
  4229.2 1569.61  4266.1 1569.66  4278.4 1569.21  4294.0 1569.60  4362.0 1569.80
  4374.9 1569.09  4424.7 1569.30  4506.1 1568.22  4537.8 1567.27  4701.3 1563.00
  4796.1 1560.55  4874.3 1558.37  4915.5 1556.62  4937.1 1556.61  4956.0 1555.94
  4996.8 1555.55  4999.6 1555.05  5002.8 1555.55  5031.2 1556.69  5108.5 1557.29
  5146.2 1558.42  5210.4 1558.64  5231.6 1558.88  5410.6 1564.80  5595.7 1571.59
  5772.7 1576.73  5829.8 1577.97  5928.6 1581.12  6000.0 1582.50  6062.7 1584.64
#Mann=11,-1,0
  4229.2     0.1       0  4294.0    0.16       0  4537.8     0.1       0
  4701.3    0.16       0  4796.1    0.05       0  4956.0     0.1       0
  4996.8    0.07       0  5002.8     0.1       0  5108.5    0.05       0
  5210.4    0.16       0  5410.6     0.1       0
Bank Sta=4996.8,5002.8
Exp/Cntr=0.3,0.1

Type RM Length L Ch R = 1,14250,445,445,445
BEGIN DESCRIPTION:
UNT118 IN NNOGR 29.0
END DESCRIPTION:
XS GIS Cut Line= 2
      2797696.42     10061012.67      2796706.98     10060032.84
#Sta/Elev= 30
  4408.1 1566.86  4418.6 1566.57  4625.1 1561.40  4646.3 1561.37  4733.9 1558.90
  4816.0 1556.77  4893.8 1554.09  4915.0 1552.87  4936.3 1552.50  4971.6 1552.97
  4985.7 1551.72  4992.8 1549.97  4996.9 1549.62  4999.6 1549.12  5002.9 1549.62
  5028.1 1552.96  5035.3 1553.31  5056.4 1552.67  5070.6 1553.26  5106.0 1553.67
  5226.1 1557.43  5282.7 1560.16  5304.0 1561.96  5311.0 1561.48  5325.1 1561.87
  5353.4 1563.56  5494.9 1569.73  5636.3 1575.15  5692.9 1577.80  5800.6 1581.66
#Mann=5,-1,0
  4408.1     0.1       0  4418.6    0.16       0  4733.9     0.1       0
  4996.9    0.07       0  5002.9     0.1       0
Bank Sta=4996.9,5002.9
Exp/Cntr=0.3,0.1

Type RM Length L Ch R = 1,13805,631,631,631
BEGIN DESCRIPTION:
UNT118 IN NNOGR 28.0
END DESCRIPTION:
XS GIS Cut Line= 3
      2798234.36     10061022.26      2797456.27     10060148.10
      2796582.80     10059744.96
#Sta/Elev= 30
  4003.0 1578.15  4069.6 1577.53  4169.1 1573.83  4523.1 1566.19  4593.9 1563.00
  4756.9 1557.57  4884.6 1551.46  4919.9 1550.72  4976.8 1551.31  4994.7 1547.20
  4997.5 1546.70  5000.7 1547.20  5018.6 1550.51  5026.1 1551.00  5083.0 1551.36
  5146.5 1553.23  5191.5 1555.59  5281.0 1558.62  5369.1 1564.74  5454.9 1565.70
  5529.3 1569.75  5580.7 1571.06  5655.5 1575.00  5710.5 1576.30  5781.0 1579.55
  5909.3 1584.41  5919.8 1585.50  5981.7 1588.14  6107.5 1596.56  6135.3 1597.57
#Mann=5,-1,0
  4003.0     0.1       0  4994.7    0.07       0  5000.7     0.1       0
  5781.0    0.16       0  5909.3     0.1       0
Bank Sta=4994.7,5000.7
Exp/Cntr=0.3,0.1

Type RM Length L Ch R = 1,13174,501,501,501
BEGIN DESCRIPTION:
UNT118 IN NNOGR 27.0
END DESCRIPTION:
XS GIS Cut Line= 2
      2798637.90     10059859.90      2796908.71     10059735.02
#Sta/Elev= 30
  4288.9 1565.94  4438.7 1565.14  4583.5 1563.29  4679.3 1560.83  4730.9 1558.74
  4857.6 1553.16  4862.6 1553.46  4889.9 1551.82  4899.9 1551.87  4940.0 1548.56
  4970.1 1548.10  4980.1 1548.77  4989.6 1547.26  4990.2 1547.16  4994.2 1543.03
  4997.0 1542.53  5000.2 1543.03  5020.2 1547.36  5040.3 1548.03  5070.4 1547.73
  5120.5 1550.00  5130.5 1549.50  5180.7 1550.44  5558.7 1562.88  5690.2 1568.18
  5772.2 1569.86  5834.8 1572.79  5892.5 1574.32  5942.8 1577.51  6022.6 1581.06
#Mann=7,-1,0
  4288.9     0.1       0  4730.9    0.16       0  4989.6     0.1       0
  4994.2    0.07       0  5000.2     0.1       0  5558.7    0.05       0
  5942.8     0.1       0
Bank Sta=4994.2,5000.2
Exp/Cntr=0.3,0.1

Type RM Length L Ch R = 1,12673,445,445,445
BEGIN DESCRIPTION:
UNT118 IN NNOGR 26.0
END DESCRIPTION:
XS GIS Cut Line= 2
      2798330.46     10059321.94      2796937.49     10059369.97
#Sta/Elev= 30
  4527.5 1561.56  4559.5 1561.50  4602.3 1560.38  4619.6 1560.79  4739.6 1556.53
  4789.7 1553.69  4829.7 1552.10  4869.7 1549.23  4899.7 1547.87  4929.7 1545.61
  4939.7 1545.50  4969.8 1547.33  4979.8 1546.91  4989.8 1542.87  4996.8 1541.72
  4999.5 1541.22  5002.8 1541.72  5009.8 1544.58  5014.8 1546.10  5049.8 1546.93
  5079.8 1546.74  5109.8 1547.76  5239.9 1553.81  5330.0 1557.01  5432.6 1561.43
  5500.1 1563.54  5740.2 1572.87  5790.2 1574.30  5855.3 1577.13  5921.3 1579.74
#Mann=6,-1,0
  4527.5     0.1       0  4602.3    0.16       0  4996.8    0.07       0
  5002.8    0.16       0  5432.6    0.16       0  5855.3     0.1       0
Bank Sta=4996.8,5002.8
Exp/Cntr=0.3,0.1

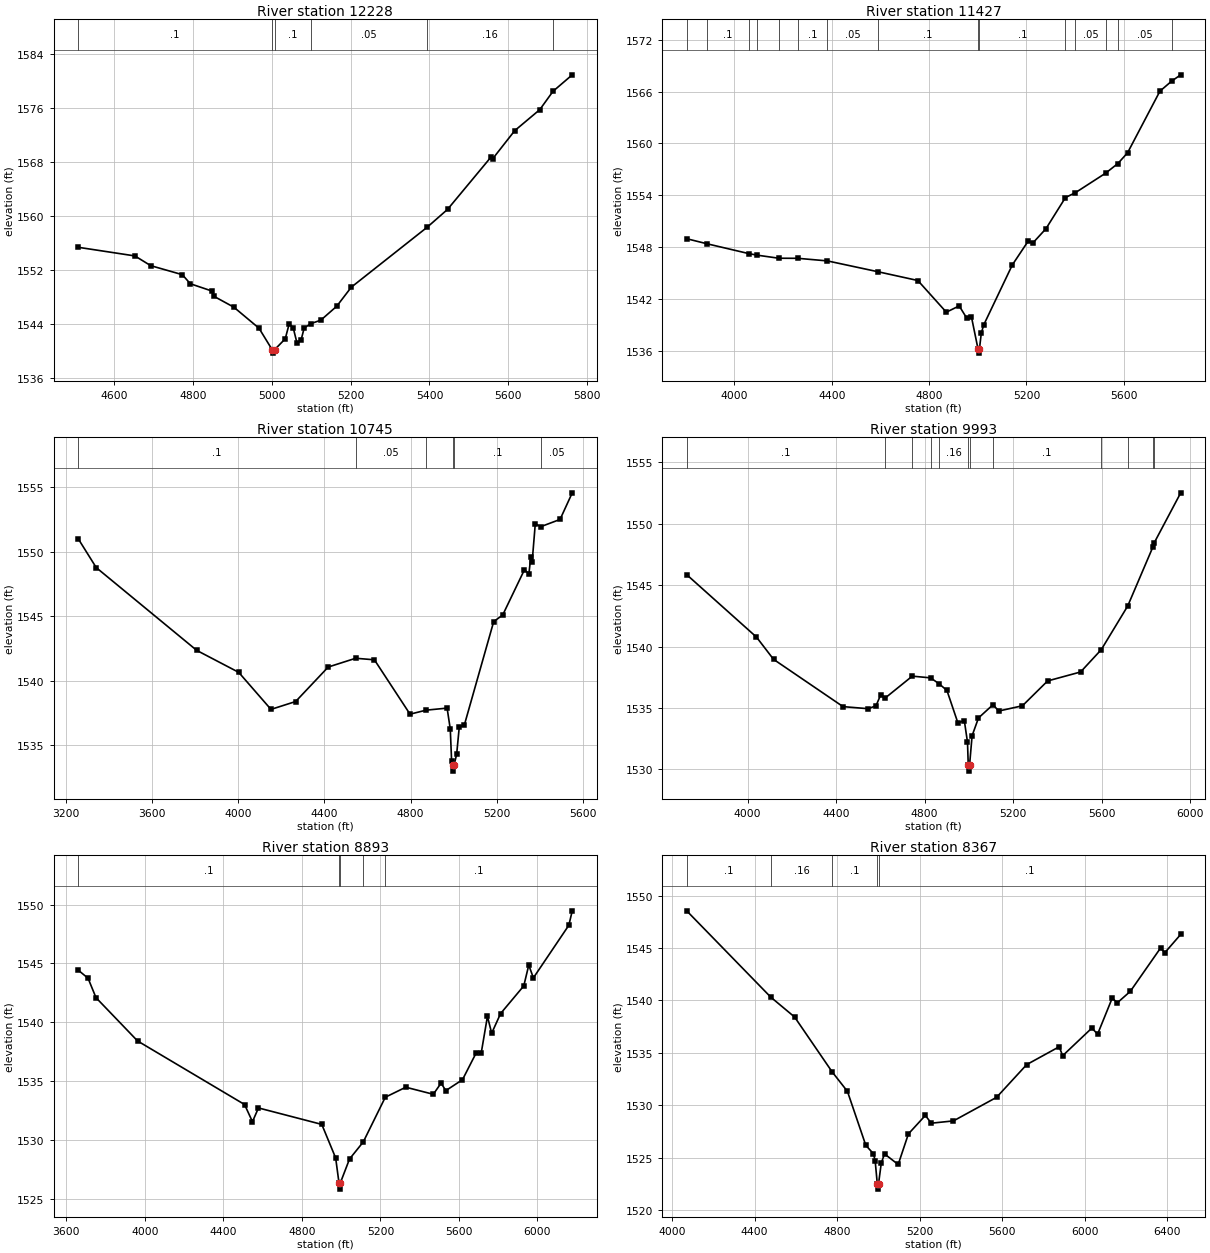
Type RM Length L Ch R = 1,12228,801,801,801
BEGIN DESCRIPTION:
UNT118 IN NNOGR 25.0
END DESCRIPTION:
XS GIS Cut Line= 2
      2798301.63     10058947.29      2797053.10     10058841.64
#Sta/Elev= 30
  4509.2 1555.34  4652.9 1554.06  4693.0 1552.62  4773.3 1551.28  4793.4 1549.94
  4848.2 1548.86  4853.6 1548.07  4903.8 1546.47  4967.7 1543.35  5001.1 1540.16
  5003.9 1539.66  5007.1 1540.16  5034.2 1541.78  5044.3 1544.01  5054.3 1543.44
  5064.3 1541.10  5074.4 1541.60  5082.2 1543.37  5098.4 1544.01  5124.6 1544.55
  5164.7 1546.60  5201.8 1549.43  5394.4 1558.32  5445.8 1560.95  5555.3 1568.65
  5560.3 1568.45  5616.3 1572.62  5679.8 1575.73  5713.4 1578.45  5762.2 1580.89
#Mann=6,-1,0
  4509.2     0.1       0  5001.1    0.07       0  5007.1     0.1       0
  5098.4    0.05       0  5394.4    0.16       0  5713.4     0.1       0
Bank Sta=5001.1,5007.1
Exp/Cntr=0.3,0.1

Type RM Length L Ch R = 1,11427,682,682,682
BEGIN DESCRIPTION:
UNT118 IN NNOGR 23.0
END DESCRIPTION:
XS GIS Cut Line= 3
      2798714.71     10058803.19      2797888.56     10058140.34
      2796927.90     10057996.24
#Sta/Elev= 30
  3803.7 1548.96  3887.8 1548.37  4059.9 1547.23  4094.7 1547.05  4182.1 1546.70
  4260.7 1546.69  4382.2 1546.39  4590.8 1545.13  4753.8 1544.12  4870.9 1540.45
  4923.7 1541.18  4954.0 1539.80  4974.2 1539.90  5001.0 1536.21  5003.8 1535.71
  5007.0 1536.21  5014.7 1538.04  5024.8 1538.99  5142.2 1545.93  5206.3 1548.64
  5227.0 1548.48  5280.4 1550.12  5360.6 1553.73  5401.3 1554.29  5526.1 1556.56
  5576.1 1557.67  5615.8 1558.91  5748.9 1566.05  5797.9 1567.23  5834.3 1567.94
#Mann=15,-1,0
  3803.7    0.05       0  3887.8     0.1       0  4059.9    0.05       0
  4094.7     0.1       0  4182.1    0.16       0  4260.7     0.1       0
  4382.2    0.05       0  4590.8     0.1       0  5001.0    0.07       0
  5007.0     0.1       0  5360.6    0.16       0  5401.3    0.05       0
  5526.1    0.16       0  5576.1    0.05       0  5797.9     0.1       0
Bank Sta=5001,5007
Exp/Cntr=0.3,0.1

Type RM Length L Ch R = 1,10745,752,752,752
BEGIN DESCRIPTION:
UNT118 IN NNOGR 21.0
END DESCRIPTION:
XS GIS Cut Line= 2
      2799435.20     10058524.60      2797572.48     10057189.97
#Sta/Elev= 30
  3258.8 1551.00  3342.3 1548.77  3808.4 1542.36  4003.1 1540.66  4152.8 1537.79
  4267.2 1538.40  4418.3 1541.07  4545.8 1541.75  4632.6 1541.63  4797.8 1537.42
  4872.0 1537.73  4969.8 1537.89  4984.5 1536.27  4990.7 1533.78  4996.3 1533.51
  4999.0 1533.01  5002.3 1533.51  5014.0 1534.30  5026.3 1536.44  5049.6 1536.57
  5185.9 1544.59  5227.7 1545.10  5328.4 1548.60  5349.3 1548.30  5357.9 1549.58
  5364.1 1549.18  5378.8 1552.16  5404.4 1551.94  5493.7 1552.50  5550.3 1554.56
#Mann=6,-1,0
  3258.8     0.1       0  4545.8    0.05       0  4872.0     0.1       0
  4996.3    0.07       0  5002.3     0.1       0  5404.4    0.05       0
Bank Sta=4996.3,5002.3
Exp/Cntr=0.3,0.1

Type RM Length L Ch R = 1,9993,1100,1100,1100
BEGIN DESCRIPTION:
Mapping XS fe6c8521
END DESCRIPTION:
XS GIS Cut Line= 3
      2799493.35     10058160.18      2799376.17     10057812.96
      2797913.47     10056654.09
#Sta/Elev= 30
  3724.9 1545.85  4040.2 1540.77  4117.3 1538.96  4431.4 1535.11  4545.2 1534.94
  4580.4 1535.18  4601.2 1536.05  4622.6 1535.82  4744.3 1537.59  4827.4 1537.45
  4866.0 1536.96  4900.9 1536.43  4950.6 1533.78  4979.5 1533.98  4993.9 1532.21
  4997.3 1530.36  5000.0 1529.86  5003.3 1530.36  5014.7 1532.74  5043.6 1534.19
  5109.4 1535.27  5134.9 1534.75  5242.3 1535.18  5356.0 1537.20  5505.0 1537.93
  5598.6 1539.75  5718.0 1543.30  5832.4 1548.13  5837.4 1548.43  5957.5 1552.51
#Mann=12,-1,0
  3724.9     0.1       0  4622.6    0.05       0  4744.3     0.1       0
  4827.4    0.05       0  4866.0    0.16       0  4997.3    0.07       0
  5003.3    0.16       0  5109.4     0.1       0  5598.6    0.16       0
  5718.0     0.1       0  5832.4    0.16       0  5837.4     0.1       0
Bank Sta=4997.3,5003.3
Exp/Cntr=0.3,0.1

Type RM Length L Ch R = 1,8893,526,526,526
BEGIN DESCRIPTION:
UNT118 IN NNOGR 19.0
END DESCRIPTION:
XS GIS Cut Line= 3
      2799502.03     10058073.35      2799289.36     10056450.11
      2798461.94     10056155.54
#Sta/Elev= 30
  3661.6 1544.43  3711.6 1543.74  3752.0 1542.09  3963.8 1538.41  4508.4 1533.01
  4548.7 1531.55  4579.2 1532.72  4901.7 1531.32  4972.3 1528.47  4989.5 1526.32
  4992.2 1525.82  4995.5 1526.32  5042.9 1528.38  5112.9 1529.83  5225.1 1533.63
  5329.4 1534.48  5469.5 1533.88  5509.1 1534.83  5533.2 1534.19  5618.1 1535.12
  5688.8 1537.43  5713.6 1537.40  5745.1 1540.50  5766.7 1539.07  5812.1 1540.74
  5930.1 1543.09  5955.6 1544.86  5979.0 1543.77  6159.5 1548.24  6177.0 1549.47
#Mann=5,-1,0
  3661.6     0.1       0  4989.5    0.07       0  4995.5     0.1       0
  5112.9    0.05       0  5225.1     0.1       0
Bank Sta=4989.5,4995.5
Exp/Cntr=0.3,0.1

Type RM Length L Ch R = 1,8367,363,363,363
BEGIN DESCRIPTION:
UNT118 IN NNOGR 18.0
END DESCRIPTION:
XS GIS Cut Line= 4
      2800087.96     10057647.99      2799949.08     10056962.27
      2799688.67     10056476.16      2798594.90     10056141.95
#Sta/Elev= 30
  4070.5 1548.55  4477.8 1540.32  4593.5 1538.42  4775.4 1533.19  4849.6 1531.33
  4938.7 1526.18  4975.5 1525.38  4984.0 1524.72  4994.4 1522.50  4997.2 1522.00
  5000.4 1522.50  5013.7 1524.48  5029.4 1525.36  5095.7 1524.35  5145.3 1527.27
  5227.3 1529.03  5256.3 1528.29  5363.7 1528.51  5572.8 1530.76  5718.7 1533.88
  5876.0 1535.58  5893.1 1534.73  6034.8 1537.37  6062.3 1536.78  6133.2 1540.22
  6158.3 1539.78  6221.1 1540.87  6367.5 1545.00  6388.4 1544.56  6465.3 1546.30
#Mann=5,-1,0
  4070.5     0.1       0  4477.8    0.16       0  4775.4     0.1       0
  4994.4    0.07       0  5000.4     0.1       0
Bank Sta=4994.4,5000.4
Exp/Cntr=0.3,0.1