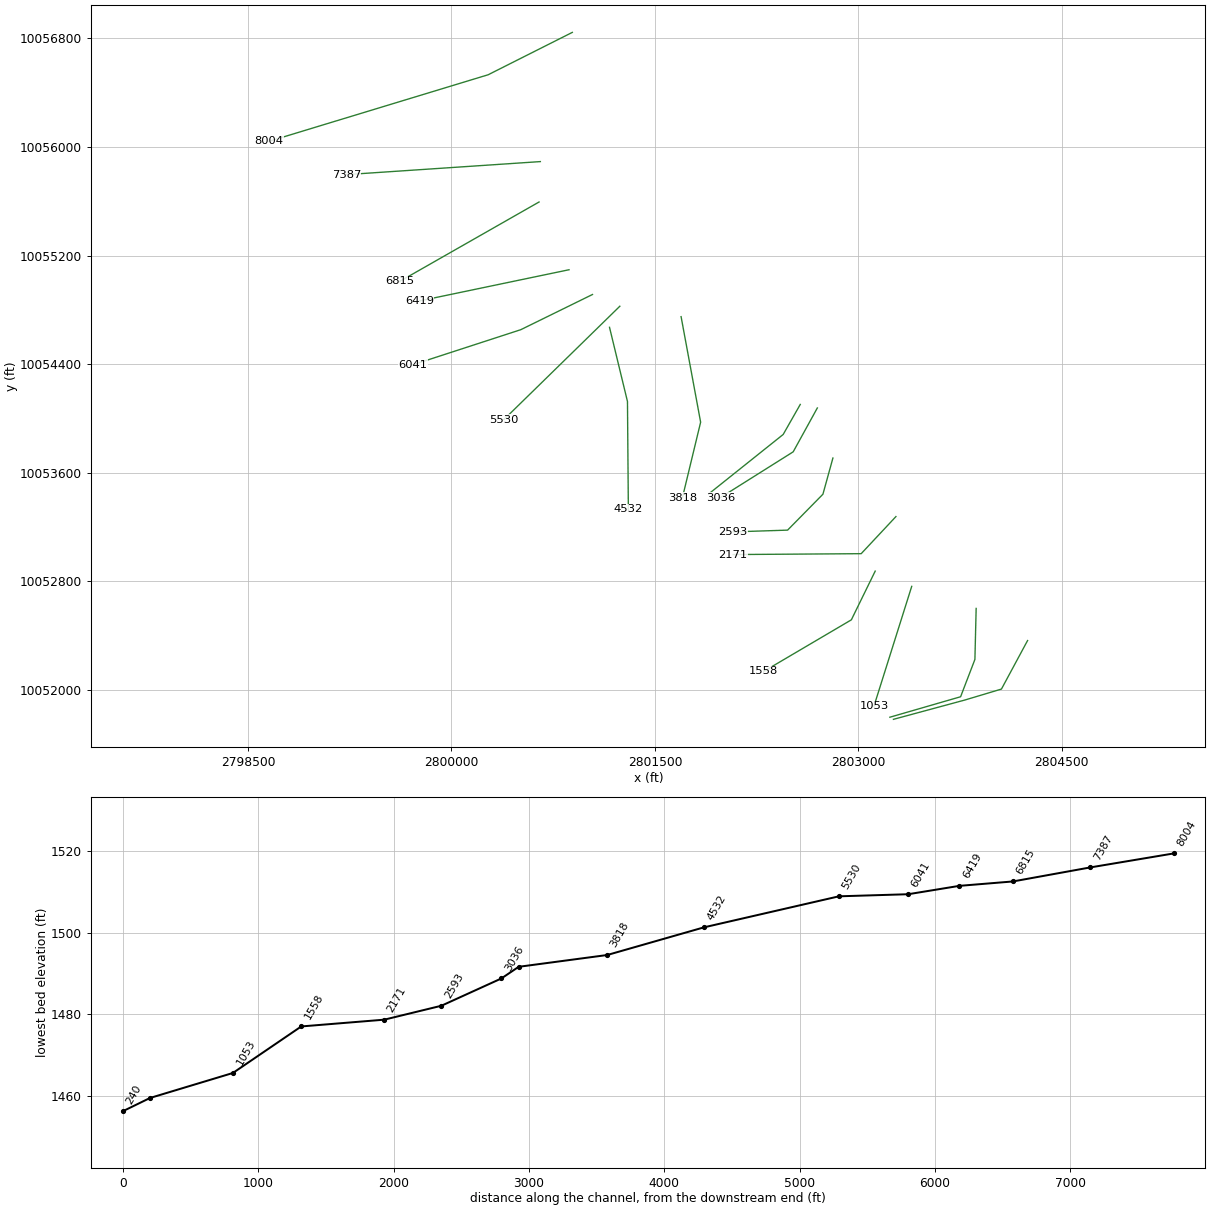
HEC-RAS study UNT118 IN NNOGR.prj: UNT118 IN NNOGR Base Level Engineering

--- UNT118 IN NNOGR.g01 (geometry) --- (continued)

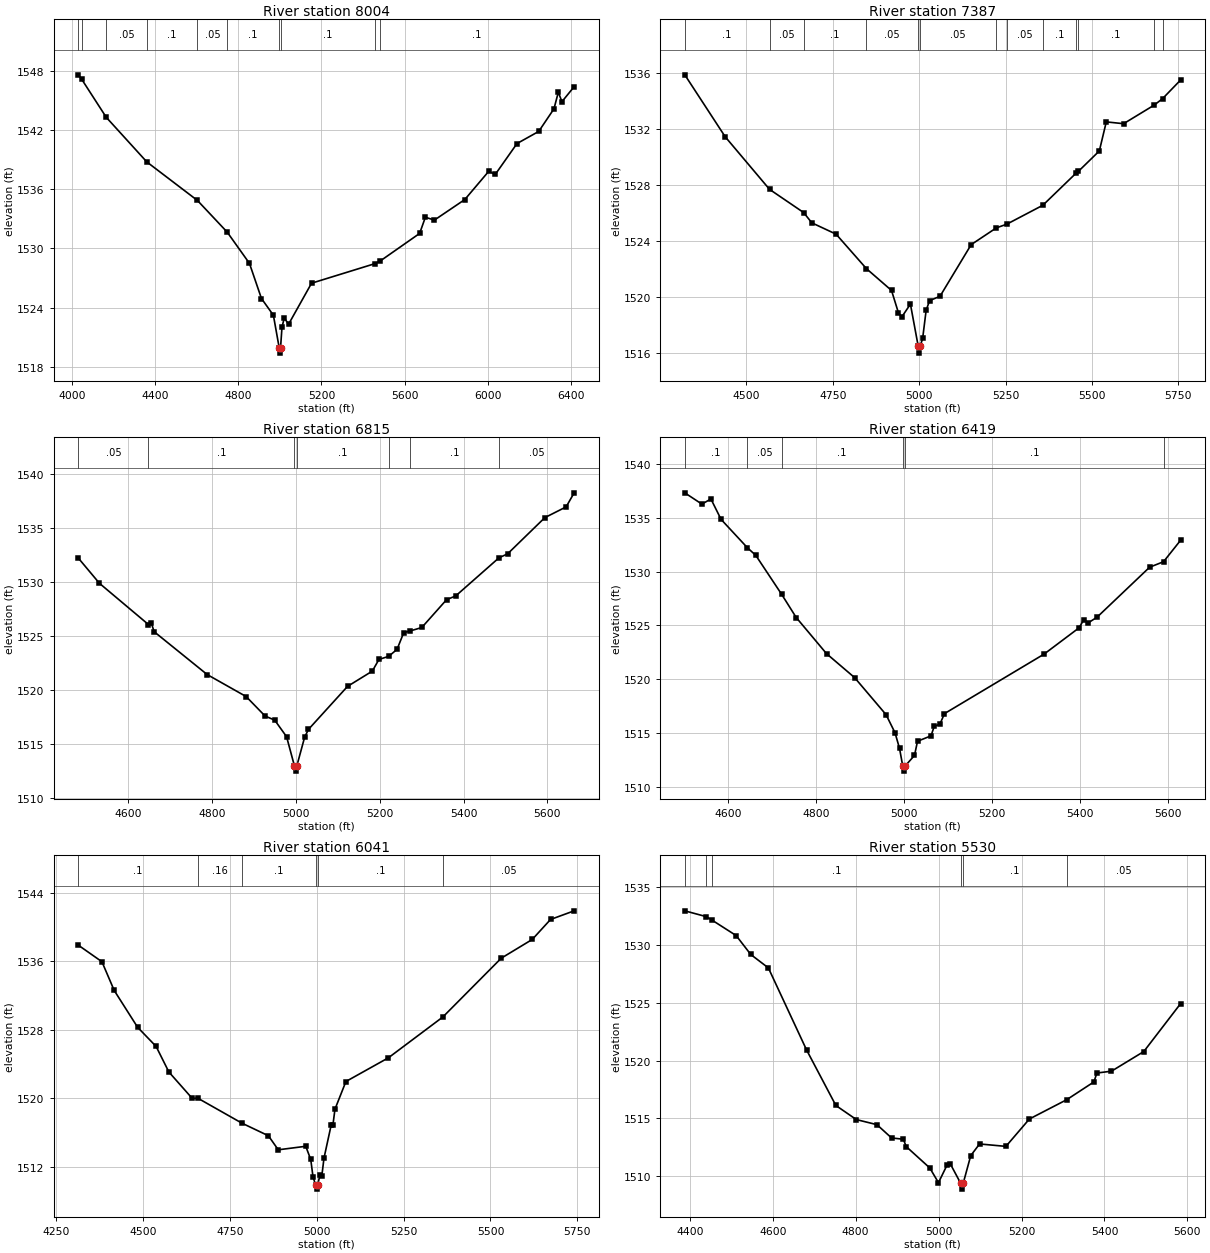
Type RM Length L Ch R = 1,8004,617,617,617
BEGIN DESCRIPTION:
UNT118 IN NNOGR 17.0
END DESCRIPTION:
XS GIS Cut Line= 3
      2800890.96     10056845.10      2800270.26     10056532.58
      2798655.64     10056042.12
#Sta/Elev= 30
  4031.8 1547.57  4047.7 1547.13  4165.9 1543.27  4360.9 1538.75  4604.0 1534.85
  4747.2 1531.64  4854.0 1528.48  4911.7 1524.92  4969.0 1523.23  4997.3 1519.89
  5000.1 1519.39  5003.3 1519.89  5010.4 1522.03  5021.2 1522.94  5042.1 1522.32
  5152.4 1526.47  5456.8 1528.45  5481.0 1528.70  5671.7 1531.51  5699.3 1533.15
  5742.7 1532.86  5888.7 1534.94  6003.7 1537.80  6035.0 1537.48  6139.5 1540.61
  6244.0 1541.84  6317.2 1544.13  6338.1 1545.81  6355.4 1544.85  6414.2 1546.37
#Mann=10,-1,0
  4031.8    0.05       0  4047.7     0.1       0  4165.9    0.05       0
  4360.9     0.1       0  4604.0    0.05       0  4747.2     0.1       0
  4997.3    0.07       0  5003.3     0.1       0  5456.8    0.05       0
  5481.0     0.1       0
Bank Sta=4997.3,5003.3
Exp/Cntr=0.3,0.1

Type RM Length L Ch R = 1,7387,572,572,572
BEGIN DESCRIPTION:
UNT118 IN NNOGR 15.0
END DESCRIPTION:
XS GIS Cut Line= 2
      2800655.20     10055892.42      2799223.82     10055796.36
#Sta/Elev= 30
  4321.8 1535.89  4438.8 1531.45  4566.9 1527.69  4665.5 1526.03  4689.4 1525.29
  4759.5 1524.48  4847.3 1522.01  4919.9 1520.45  4939.9 1518.85  4949.9 1518.56
  4974.6 1519.47  4997.1 1516.46  4999.8 1515.96  5003.1 1516.46  5010.1 1517.04
  5020.1 1519.03  5030.1 1519.72  5060.2 1520.03  5150.4 1523.73  5223.2 1524.93
  5253.1 1525.19  5357.8 1526.55  5453.1 1528.83  5460.3 1528.97  5521.2 1530.44
  5541.3 1532.52  5591.4 1532.39  5679.8 1533.72  5704.0 1534.18  5756.4 1535.52
#Mann=13,-1,0
  4321.8     0.1       0  4566.9    0.05       0  4665.5     0.1       0
  4847.3    0.05       0  4997.1    0.04       0  5003.1    0.05       0
  5223.2     0.1       0  5253.1    0.05       0  5357.8     0.1       0
  5453.1    0.05       0  5460.3     0.1       0  5679.8    0.05       0
  5704.0     0.1       0
Bank Sta=4997.1,5003.1
Exp/Cntr=0.3,0.1

Type RM Length L Ch R = 1,6815,396,396,396
BEGIN DESCRIPTION:
UNT118 IN NNOGR 14.0
END DESCRIPTION:
XS GIS Cut Line= 2
      2800645.58     10055594.61      2799617.78     10055008.66
#Sta/Elev= 30
  4480.9 1532.20  4531.3 1529.87  4648.3 1526.06  4655.1 1526.19  4661.8 1525.40
  4788.4 1521.44  4881.3 1519.41  4926.5 1517.61  4949.5 1517.23  4977.8 1515.70
  4996.4 1513.02  4999.2 1512.52  5002.4 1513.02  5021.0 1515.67  5030.1 1516.38
  5123.3 1520.35  5182.4 1521.76  5198.2 1522.84  5221.3 1523.12  5241.4 1523.77
  5257.3 1525.31  5272.8 1525.47  5300.5 1525.79  5359.6 1528.36  5381.2 1528.70
  5484.7 1532.23  5505.1 1532.59  5594.1 1535.94  5644.8 1536.93  5664.0 1538.23
#Mann=7,-1,0
  4480.9    0.05       0  4648.3     0.1       0  4996.4    0.07       0
  5002.4     0.1       0  5221.3    0.05       0  5272.8     0.1       0
  5484.7    0.05       0
Bank Sta=4996.4,5002.4
Exp/Cntr=0.3,0.1

Type RM Length L Ch R = 1,6419,378,378,378
BEGIN DESCRIPTION:
UNT118 IN NNOGR 13.0
END DESCRIPTION:
XS GIS Cut Line= 2
      2800866.57     10055095.09      2799762.65     10054864.70
#Sta/Elev= 30
  4501.6 1537.33  4540.5 1536.28  4561.0 1536.76  4584.1 1534.86  4643.8 1532.23
  4663.1 1531.51  4722.0 1527.88  4755.0 1525.73  4823.9 1522.37  4887.8 1520.14
  4959.4 1516.69  4979.8 1515.00  4990.0 1513.55  4997.2 1511.94  5000.0 1511.44
  5003.2 1511.94  5024.0 1512.90  5030.9 1514.22  5061.5 1514.72  5068.9 1515.60
  5081.9 1515.82  5092.2 1516.79  5318.9 1522.33  5398.6 1524.78  5408.8 1525.52
  5419.0 1525.23  5439.5 1525.77  5558.8 1530.41  5590.4 1530.92  5629.3 1532.92
#Mann=6,-1,0
  4501.6     0.1       0  4643.8    0.05       0  4722.0     0.1       0
  4997.2    0.07       0  5003.2     0.1       0  5590.4    0.05       0
Bank Sta=4997.2,5003.2
Exp/Cntr=0.3,0.1

Type RM Length L Ch R = 1,6041,511,511,511
BEGIN DESCRIPTION:
UNT118 IN NNOGR 12.0
END DESCRIPTION:
XS GIS Cut Line= 3
      2801039.46     10054912.55      2800511.13     10054653.19
      2799713.81     10054393.82
#Sta/Elev= 30
  4313.9 1537.86  4381.8 1535.93  4417.1 1532.58  4484.5 1528.28  4537.8 1526.04
  4574.5 1523.06  4641.9 1519.97  4657.5 1520.01  4784.7 1517.09  4860.9 1515.62
  4889.3 1513.98  4968.4 1514.39  4982.8 1512.85  4989.4 1510.79  4996.9 1509.89
  4999.7 1509.39  5002.9 1509.89  5009.5 1511.09  5014.8 1510.97  5020.9 1513.01
  5041.4 1516.83  5046.7 1516.90  5052.5 1518.72  5084.0 1521.95  5206.4 1524.72
  5363.0 1529.48  5531.0 1536.34  5620.3 1538.53  5672.9 1540.86  5740.9 1541.87
#Mann=6,-1,0
  4313.9     0.1       0  4657.5    0.16       0  4784.7     0.1       0
  4996.9    0.07       0  5002.9     0.1       0  5363.0    0.05       0
Bank Sta=4996.9,5002.9
Exp/Cntr=0.3,0.1

Type RM Length L Ch R = 1,5530,998,998,998
BEGIN DESCRIPTION:
UNT118 IN NNOGR 11.0
END DESCRIPTION:
XS GIS Cut Line= 2
      2801241.20     10054826.08      2800386.23     10053990.33
#Sta/Elev= 30
  4388.0 1532.97  4439.4 1532.47  4453.9 1532.16  4511.8 1530.83  4547.1 1529.19
  4589.5 1528.03  4681.6 1520.93  4752.3 1516.12  4801.7 1514.90  4851.3 1514.46
  4886.6 1513.31  4914.9 1513.20  4922.0 1512.56  4978.6 1510.72  4999.7 1509.44
  5021.0 1511.01  5028.0 1511.08  5053.3 1509.38  5056.1 1508.88  5059.3 1509.38
  5077.5 1511.78  5098.8 1512.79  5162.3 1512.58  5218.9 1514.95  5308.9 1516.62
  5374.5 1518.16  5381.7 1518.93  5416.9 1519.09  5494.8 1520.79  5583.6 1524.94
#Mann=6,-1,0
  4388.0     0.1       0  4439.4    0.05       0  4453.9     0.1       0
  5053.3    0.07       0  5059.3     0.1       0  5308.9    0.05       0
Bank Sta=5053.3,5059.3
Exp/Cntr=0.3,0.1

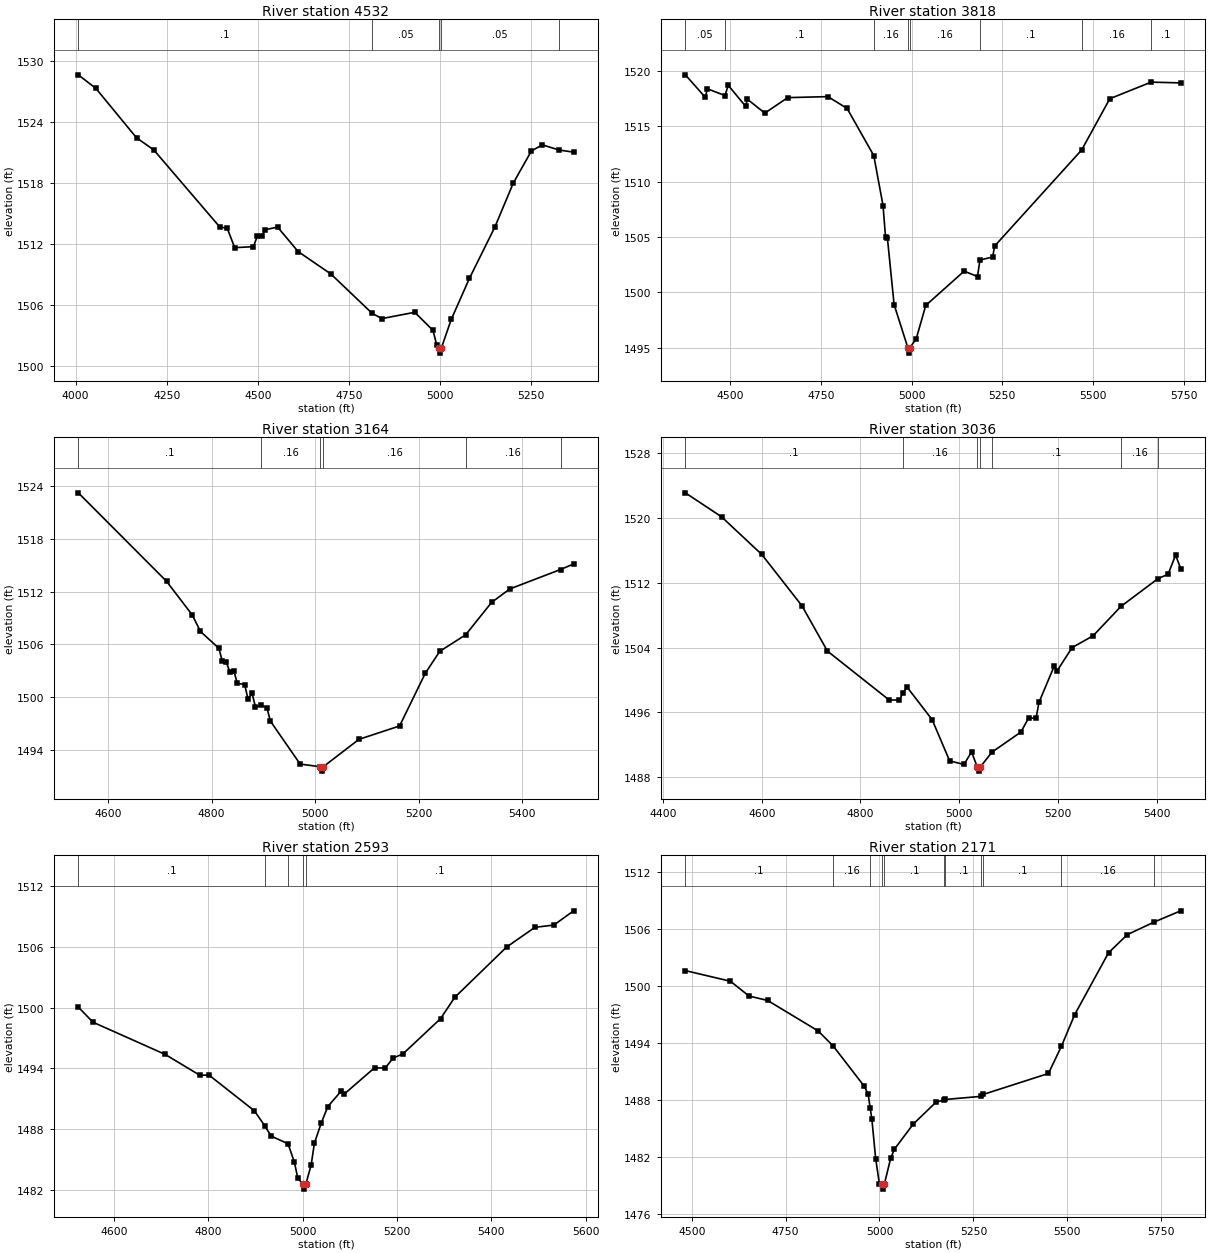
Type RM Length L Ch R = 1,4532,714,714,714
BEGIN DESCRIPTION:
UNT118 IN NNOGR 10.0
END DESCRIPTION:
XS GIS Cut Line= 3
      2801165.08     10054670.63      2801297.46     10054123.72
      2801303.97     10053328.06
#Sta/Elev= 30
  4007.5 1528.66  4055.8 1527.32  4167.2 1522.46  4214.2 1521.28  4395.3 1513.69
  4415.9 1513.56  4436.4 1511.65  4487.9 1511.75  4498.2 1512.76  4512.2 1512.76
  4518.8 1513.40  4554.0 1513.68  4610.2 1511.27  4700.2 1509.06  4813.2 1505.19
  4840.2 1504.67  4930.2 1505.29  4980.2 1503.51  4990.2 1502.11  4997.2 1501.77
  5000.0 1501.27  5003.2 1501.77  5030.2 1504.58  5080.2 1508.63  5150.2 1513.70
  5200.2 1517.99  5250.2 1521.17  5280.2 1521.77  5325.9 1521.26  5365.9 1521.05
#Mann=5,-1,0
  4007.5     0.1       0  4813.2    0.05       0  4997.2    0.04       0
  5003.2    0.05       0  5325.9     0.1       0
Bank Sta=4997.2,5003.2
Exp/Cntr=0.3,0.1

Type RM Length L Ch R = 1,3818,654,654,654
BEGIN DESCRIPTION:
UNT118 IN NNOGR 9.0
END DESCRIPTION:
XS GIS Cut Line= 3
      2801692.73     10054749.24      2801836.82     10053971.13
      2801702.33     10053413.97
#Sta/Elev= 30
  4376.7 1519.65  4431.9 1517.61  4437.0 1518.39  4485.8 1517.78  4494.9 1518.70
  4542.7 1516.81  4547.8 1517.44  4595.6 1516.19  4658.7 1517.59  4769.5 1517.68
  4822.4 1516.61  4895.8 1512.35  4921.3 1507.84  4928.2 1504.99  4933.3 1504.92
  4951.8 1498.89  4989.5 1495.00  4992.3 1494.50  4995.5 1495.00  5012.8 1495.80
  5039.0 1498.81  5144.8 1501.91  5181.6 1501.42  5188.2 1502.91  5223.4 1503.19
  5228.6 1504.17  5468.5 1512.86  5546.0 1517.49  5659.9 1518.99  5741.2 1518.92
#Mann=8,-1,0
  4376.7    0.05       0  4485.8     0.1       0  4895.8    0.16       0
  4989.5    0.07       0  4995.5    0.16       0  5188.2     0.1       0
  5468.5    0.16       0  5659.9     0.1       0
Bank Sta=4989.5,4995.5
Exp/Cntr=0.3,0.1

Type RM Length L Ch R = 1,3164,128,128,128
BEGIN DESCRIPTION:
UNT118 IN NNOGR 7.0
END DESCRIPTION:
XS GIS Cut Line= 3
      2802571.31     10054101.98      2802445.47     10053880.67
      2801896.39     10053442.28
#Sta/Elev= 30
  4542.4 1523.22  4712.9 1513.17  4762.6 1509.35  4778.5 1507.47  4814.2 1505.55
  4820.6 1504.10  4828.6 1503.98  4835.0 1502.91  4843.1 1503.00  4849.5 1501.58
  4863.9 1501.44  4870.3 1499.80  4878.3 1500.43  4884.7 1498.90  4895.6 1499.10
  4907.1 1498.79  4913.5 1497.30  4971.1 1492.41  5009.8 1492.11  5012.5 1491.61
  5015.8 1492.11  5084.8 1495.22  5163.3 1496.74  5212.9 1502.72  5241.0 1505.22
  5290.9 1507.09  5341.0 1510.77  5376.2 1512.30  5474.3 1514.51  5499.6 1515.14
#Mann=6,-1,0
  4542.4     0.1       0  4895.6    0.16       0  5009.8    0.07       0
  5015.8    0.16       0  5290.9    0.16       0  5474.3     0.1       0
Bank Sta=5009.8,5015.8
Exp/Cntr=0.3,0.1

Type RM Length L Ch R = 1,3036,443,443,443
BEGIN DESCRIPTION:
Mapping XS 7113f8d6
END DESCRIPTION:
XS GIS Cut Line= 3
      2802697.18     10054075.95      2802519.25     10053752.63
      2801982.29     10053414.87
#Sta/Elev= 30
  4445.3 1523.12  4518.6 1520.16  4600.1 1515.51  4681.5 1509.17  4733.2 1503.57
  4857.9 1497.55  4879.1 1497.51  4885.9 1498.41  4894.4 1499.13  4945.2 1495.11
  4980.7 1490.02  5009.8 1489.57  5025.1 1491.13  5036.7 1489.25  5039.5 1488.75
  5042.7 1489.25  5066.6 1491.10  5125.2 1493.58  5140.5 1495.30  5155.8 1495.30
  5161.8 1497.26  5192.3 1501.68  5198.3 1501.12  5228.8 1504.01  5271.3 1505.46
  5327.7 1509.09  5402.9 1512.53  5423.2 1513.06  5438.5 1515.43  5448.7 1513.77
#Mann=7,-1,0
  4445.3     0.1       0  4885.9    0.16       0  5036.7    0.07       0
  5042.7    0.16       0  5066.6     0.1       0  5327.7    0.16       0
  5402.9     0.1       0
Bank Sta=5036.7,5042.7
Exp/Cntr=0.3,0.1

Type RM Length L Ch R = 1,2593,422,422,422
BEGIN DESCRIPTION:
UNT118 IN NNOGR 5.0
END DESCRIPTION:
XS GIS Cut Line= 4
      2802812.21     10053707.02      2802738.43     10053440.13
      2802478.02     10053175.37      2802076.49     10053162.35
#Sta/Elev= 30
  4524.3 1500.06  4555.4 1498.57  4708.3 1495.39  4782.1 1493.32  4801.2 1493.35
  4897.6 1489.81  4919.4 1488.34  4933.0 1487.32  4968.9 1486.55  4982.5 1484.72
  4989.6 1483.14  5000.7 1482.57  5003.5 1482.07  5006.7 1482.57  5017.9 1484.46
  5024.9 1486.63  5039.0 1488.56  5053.2 1490.23  5081.5 1491.76  5088.6 1491.49
  5152.2 1494.06  5174.8 1494.04  5192.1 1495.04  5212.1 1495.42  5292.2 1498.92
  5322.2 1501.02  5432.3 1506.00  5492.3 1507.95  5532.3 1508.17  5574.3 1509.58
#Mann=5,-1,0
  4524.3     0.1       0  4919.4    0.16       0  4968.9     0.1       0
  5000.7    0.07       0  5006.7     0.1       0
Bank Sta=5000.7,5006.7
Exp/Cntr=0.3,0.1

Type RM Length L Ch R = 1,2171,613,613,613
BEGIN DESCRIPTION:
Mapping XS 2d6c57b2
END DESCRIPTION:
XS GIS Cut Line= 3
      2803276.64     10053275.22      2803020.55     10053001.76
      2802076.52     10052995.25
#Sta/Elev= 30
  4483.1 1501.62  4603.2 1500.50  4652.5 1498.95  4702.3 1498.48  4836.7 1495.28
  4876.5 1493.71  4959.8 1489.45  4969.8 1488.63  4975.2 1487.20  4979.8 1485.99
  4989.8 1481.86  4999.8 1479.20  5006.8 1479.16  5009.6 1478.66  5012.8 1479.16
  5029.8 1481.91  5039.8 1482.86  5089.8 1485.49  5149.8 1487.77  5172.5 1488.06
  5175.5 1488.08  5271.1 1488.41  5276.2 1488.61  5449.8 1490.81  5484.2 1493.66
  5519.8 1497.00  5609.9 1503.50  5659.9 1505.40  5731.2 1506.72  5801.8 1507.90
#Mann=11,-1,0
  4483.1     0.1       0  4876.5    0.16       0  4975.2     0.1       0
  5006.8    0.07       0  5012.8     0.1       0  5172.5    0.16       0
  5175.5     0.1       0  5271.1    0.16       0  5276.2     0.1       0
  5484.2    0.16       0  5731.2     0.1       0
Bank Sta=5006.8,5012.8
Exp/Cntr=0.3,0.1

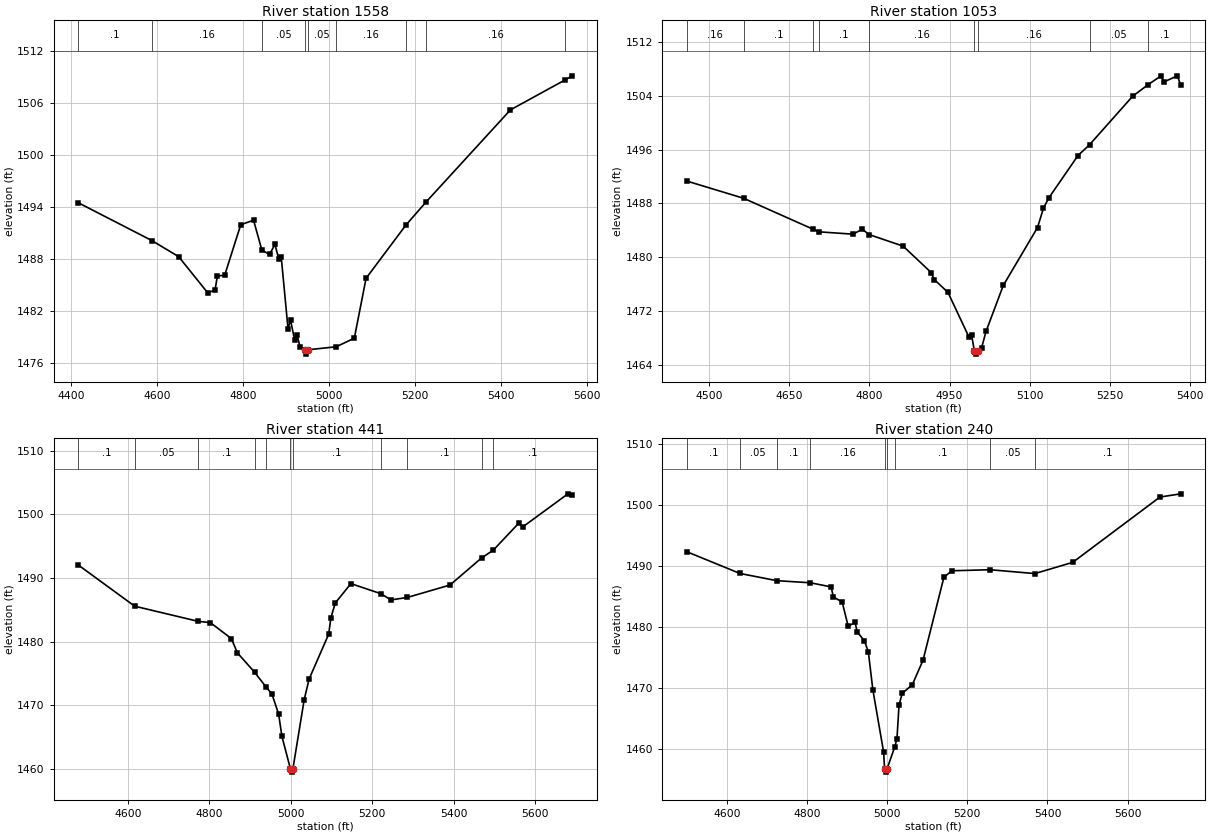
Type RM Length L Ch R = 1,1558,505,505,505
BEGIN DESCRIPTION:
UNT118 IN NNOGR 3.0
END DESCRIPTION:
XS GIS Cut Line= 3
      2803123.83     10052873.16      2802948.07     10052514.01
      2802302.56     10052134.02
#Sta/Elev= 30
  4416.7 1494.49  4587.9 1490.12  4650.2 1488.26  4717.7 1484.09  4734.7 1484.38
  4740.3 1486.03  4757.2 1486.11  4794.6 1491.95  4824.4 1492.47  4843.6 1489.03
  4861.5 1488.51  4874.1 1489.68  4883.0 1487.98  4888.8 1488.17  4904.5 1479.94
  4910.3 1480.93  4920.1 1478.59  4925.9 1479.19  4932.1 1477.86  4944.4 1477.50
  4947.1 1477.00  4950.4 1477.50  5016.5 1477.85  5058.7 1478.84  5086.0 1485.76
  5178.5 1491.90  5225.8 1494.59  5421.8 1505.22  5548.2 1508.66  5565.6 1509.15
#Mann=9,-1,0
  4416.7     0.1       0  4587.9    0.16       0  4843.6    0.05       0
  4944.4   0.033       0  4950.4    0.05       0  5016.5    0.16       0
  5178.5     0.1       0  5225.8    0.16       0  5548.2     0.1       0
Bank Sta=4944.4,4950.4
Exp/Cntr=0.3,0.1

Type RM Length L Ch R = 1,1053,612,612,612
BEGIN DESCRIPTION:
UNT118 IN NNOGR 2.0
END DESCRIPTION:
XS GIS Cut Line= 2
      2803393.07     10052760.70      2803114.77     10051877.83
#Sta/Elev= 30
  4457.5 1491.34  4564.3 1488.77  4694.7 1484.16  4705.8 1483.78  4768.9 1483.44
  4786.7 1484.16  4799.3 1483.38  4863.2 1481.65  4915.7 1477.73  4921.4 1476.69
  4947.1 1474.78  4986.1 1468.20  4991.3 1468.50  4996.5 1466.10  4999.3 1465.60
  5002.5 1466.10  5010.0 1466.51  5018.5 1468.99  5050.8 1475.82  5114.9 1484.42
  5126.0 1487.29  5135.9 1488.81  5190.7 1495.12  5212.3 1496.73  5293.1 1503.94
  5322.1 1505.67  5345.6 1506.93  5352.5 1506.10  5377.0 1506.98  5383.2 1505.58
#Mann=9,-1,0
  4457.5    0.16       0  4564.3     0.1       0  4694.7    0.16       0
  4705.8     0.1       0  4799.3    0.16       0  4996.5    0.07       0
  5002.5    0.16       0  5212.3    0.05       0  5322.1     0.1       0
Bank Sta=4996.5,5002.5
Exp/Cntr=0.3,0.1

Type RM Length L Ch R = 1,441,201,201,201
BEGIN DESCRIPTION:
Mapping XS f1ef62d5
END DESCRIPTION:
XS GIS Cut Line= 4
      2803868.14     10052598.04      2803858.97     10052222.09
      2803753.51     10051946.99      2803232.10     10051796.05
#Sta/Elev= 30
  4477.9 1492.04  4616.5 1485.56  4772.3 1483.18  4802.3 1482.98  4854.0 1480.47
  4868.8 1478.22  4910.9 1475.19  4939.7 1472.82  4953.5 1471.77  4970.0 1468.62
  4978.2 1465.09  4999.1 1459.98  5001.9 1459.48  5005.1 1459.98  5032.9 1470.88
  5045.0 1474.12  5093.0 1481.16  5098.5 1483.76  5109.2 1486.06  5147.6 1489.11
  5220.4 1487.54  5246.3 1486.55  5286.0 1486.93  5391.1 1488.89  5468.8 1493.16
  5497.1 1494.35  5559.8 1498.60  5569.5 1498.01  5680.7 1503.22  5691.4 1502.98
#Mann=11,-1,0
  4477.9     0.1       0  4616.5    0.05       0  4772.3     0.1       0
  4910.9    0.16       0  4939.7     0.1       0  4999.1    0.07       0
  5005.1     0.1       0  5220.4    0.05       0  5286.0     0.1       0
  5468.8    0.05       0  5497.1     0.1       0
Bank Sta=4999.1,5005.1
Exp/Cntr=0.3,0.1

Type RM Length L Ch R = 1,240,0,0,0
BEGIN DESCRIPTION:
UNT118 IN NNOGR 1.0
END DESCRIPTION:
XS GIS Cut Line= 4
      2804247.17     10052361.17      2804054.60     10052003.54
      2803784.08     10051922.53      2803258.33     10051780.40
#Sta/Elev= 30
  4499.4 1492.36  4632.4 1488.79  4724.1 1487.61  4808.3 1487.26  4859.9 1486.59
  4865.7 1484.94  4887.6 1484.11  4902.6 1480.13  4919.8 1480.78  4925.0 1479.22
  4943.3 1477.73  4952.9 1475.94  4964.2 1469.72  4991.2 1459.45  4993.4 1456.73
  4996.1 1456.23  4999.4 1456.73  5018.4 1460.28  5024.3 1461.67  5029.5 1467.19
  5037.3 1469.13  5062.6 1470.54  5089.4 1474.57  5141.6 1488.19  5161.8 1489.23
  5256.7 1489.40  5368.6 1488.77  5463.1 1490.61  5680.7 1501.31  5732.6 1501.84
#Mann=9,-1,0
  4499.4     0.1       0  4632.4    0.05       0  4724.1     0.1       0
  4808.3    0.16       0  4993.4    0.07       0  4999.4    0.16       0
  5018.4     0.1       0  5256.7    0.05       0  5368.6     0.1       0
Bank Sta=4993.4,4999.4
Exp/Cntr=0.3,0.1

Chan Stop Cuts=-1