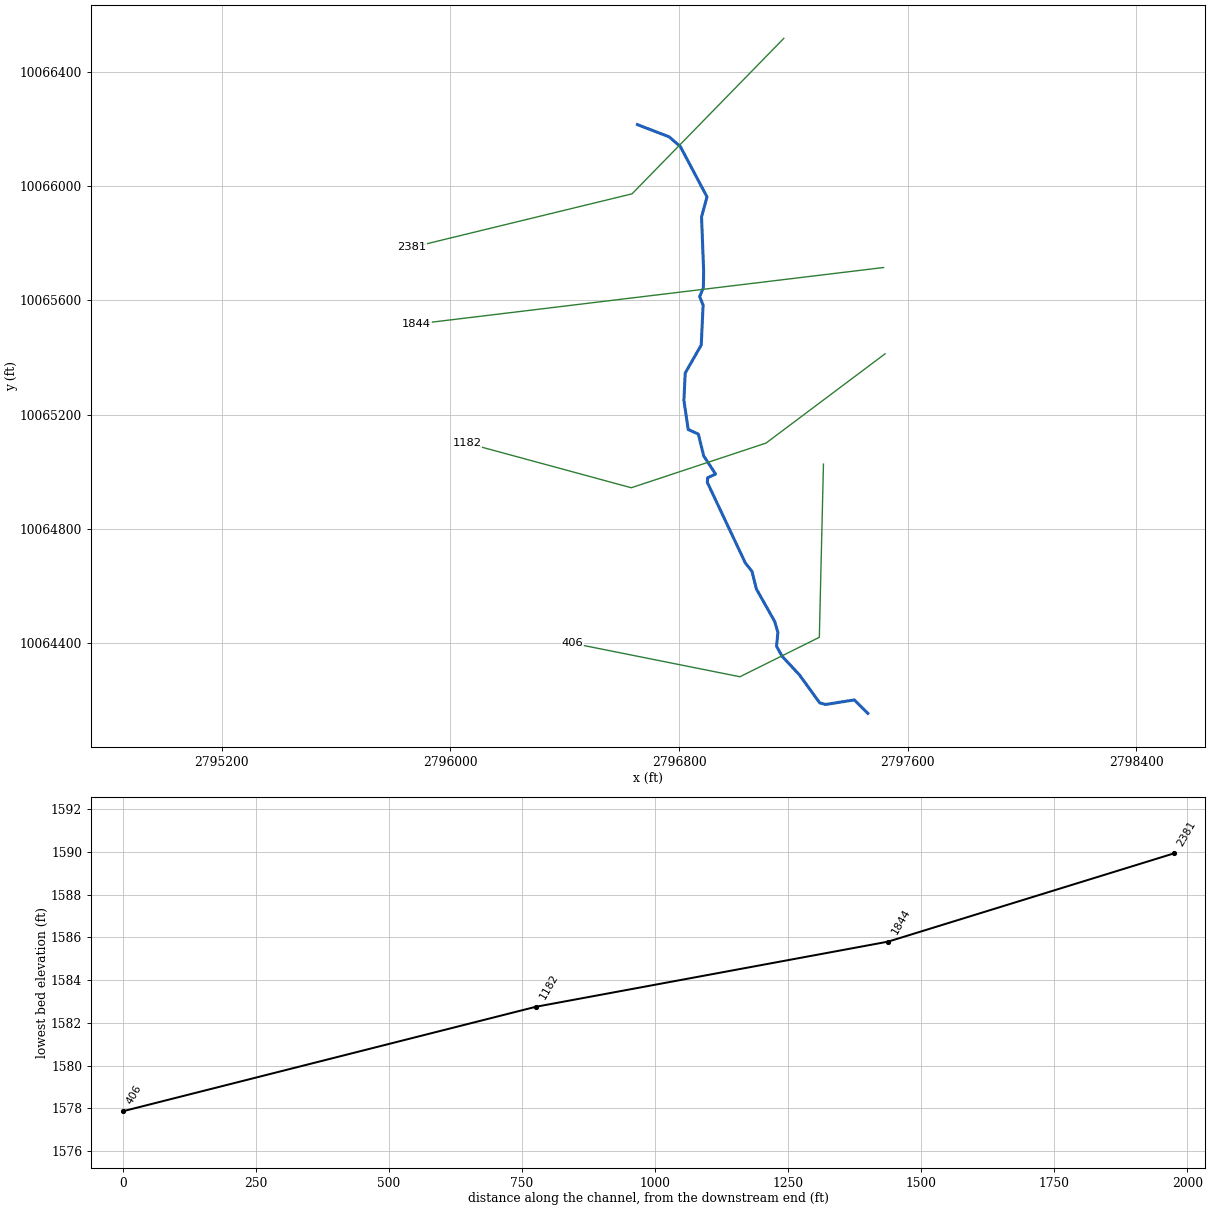
--- UNT119 IN NNOGR.prj (project) ---

Proj Title=UNT119 IN NNOGR Base Level Engineering
Current Plan=p01
Default Exp/Contr=0.3,0.1
English Units
Geom File=g01
Flow File=f01
Plan File=p01
Y Axis Title=Elevation
X Axis Title(PF)=Main Channel Distance
X Axis Title(XS)=Station
BEGIN DESCRIPTION:
UNT119 IN NNOGR
END DESCRIPTION:
DSS Export Rating Curves= 0
DSS Export Rating Curve Sorted= 0
DSS Export Volume Flow Curves= 0
DXF OffsetX= 0
DXF OffsetY= 0
DXF ScaleX= 1
DXF ScaleY= 10

--- UNT119 IN NNOGR.p01 (plan) ---

Plan Title=Multiple Run
Short Identifier=Multiple
Geom File=g01
Flow File=f01
Subcritical Flow
K Sum by GR= 0
Std Step Tol= 0.01
Critical Tol= 0.01
Num of Std Step Trials= 20
Max Error Tol= 0.3
Flow Tol Ratio= 0.001
Split Flow NTrial= 30
Split Flow Tol= 0.02
Split Flow Ratio= 0.02
Log Output Level= 0
Friction Slope Method= 1
Unsteady Friction Slope Method= 2
Unsteady Bridges Friction Slope Method= 1
Parabolic Critical Depth
Global Vel Dist=  1 , 1 , 1
Global Log Level= 0
CheckData=True
Encroach Param= -1, 0, 0, 0
BEGIN DESCRIPTION:
Multiple Run
END DESCRIPTION:

--- UNT119 IN NNOGR.f01 (steady flow) ---

Flow Title=Multiple
Program Version=4.10
Number of Profiles= 7
Profile Names=10-year,25-year,50-year,1pct_min,100-year,1pct_plu,500-year
River Rch & RM=UNT119 IN NNOGR,Reach-1         ,2381
     818    1181    1494    1384    1871    2531    2949
Boundary for River Rch & Prof#=UNT119 IN NNOGR,Reach-1         , 1
Up Type= 0
Dn Type= 3
Dn Slope=0.006
Boundary for River Rch & Prof#=UNT119 IN NNOGR,Reach-1         , 2
Up Type= 0
Dn Type= 3
Dn Slope=0.006
Boundary for River Rch & Prof#=UNT119 IN NNOGR,Reach-1         , 3
Up Type= 0
Dn Type= 3
Dn Slope=0.006
Boundary for River Rch & Prof#=UNT119 IN NNOGR,Reach-1         , 4
Up Type= 0
Dn Type= 3
Dn Slope=0.006
Boundary for River Rch & Prof#=UNT119 IN NNOGR,Reach-1         , 5
Up Type= 0
Dn Type= 3
Dn Slope=0.006
Boundary for River Rch & Prof#=UNT119 IN NNOGR,Reach-1         , 6
Up Type= 0
Dn Type= 3
Dn Slope=0.006
Boundary for River Rch & Prof#=UNT119 IN NNOGR,Reach-1         , 7
Up Type= 0
Dn Type= 3
Dn Slope=0.006
DSS Import GetInterval= 0
DSS Import GetPeak= 0
DSS Import FillOption= 0

--- UNT119 IN NNOGR.g01 (geometry) ---

Geom Title=Existing Conditions
Program Version=4.10

River Reach=UNT119 IN NNOGR ,Reach-1
Reach XY= 30
      2796654.29     10066215.37      2796764.81     10066172.77
      2796804.14     10066138.82      2796897.64     10065962.54
      2796878.51     10065892.24      2796885.86     10065703.56
      2796884.92     10065644.79       2796871.9     10065613.67
      2796883.98     10065583.86      2796877.46      10065444.1
      2796821.35     10065345.98       2796816.8     10065249.84
      2796831.77      10065148.5      2796867.28     10065132.27
       2796885.9     10065056.19      2796927.69     10064992.25
      2796899.91     10064979.66      2796898.83     10064962.95
      2797031.62     10064681.42      2797054.82     10064652.13
      2797070.27     10064590.34      2797134.35     10064476.71
      2797145.65     10064438.25      2797140.93     10064389.58
      2797160.43     10064354.63      2797220.46      10064290.3
      2797292.11     10064191.45      2797312.74       10064186.
      2797413.06     10064201.94      2797460.36     10064154.81

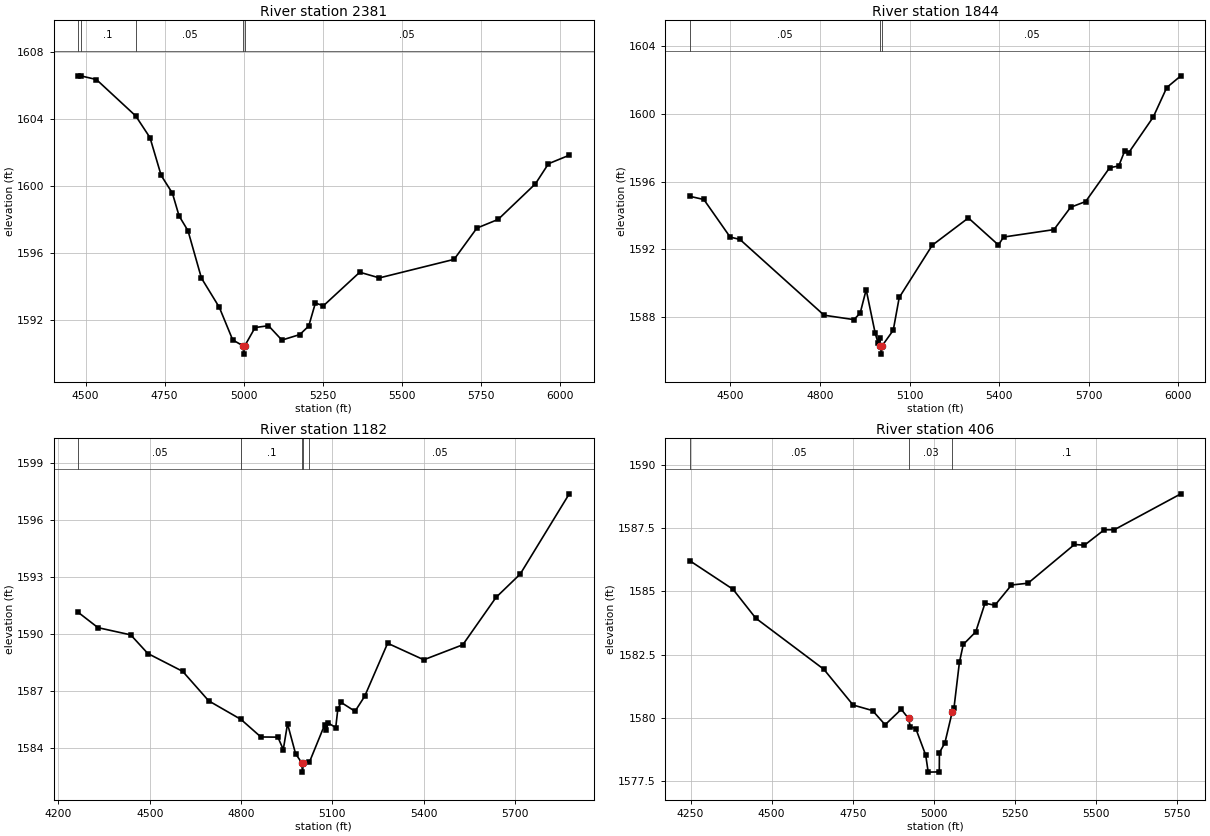
Type RM Length L Ch R = 1 ,2381    ,537,537,537
BEGIN DESCRIPTION:
UNT119 IN NNOGR 1.0
END DESCRIPTION:
XS GIS Cut Line= 3
       2797166.5     10066517.36      2796635.28     10065973.12
      2795864.48     10065785.63
#Sta/Elev= 30
  4476.1 1606.54  4484.1 1606.58  4533.9 1606.36  4658.4 1604.18  4703.6 1602.88
  4738.9 1600.62  4774.4 1599.56  4795.5  1598.2  4823.8 1597.31  4866.2 1594.48
  4922.8 1592.73  4965.2 1590.78  4997.5 1590.43  5000.3 1589.93  5003.5 1590.43
    5036 1591.52  5078.4 1591.63  5120.8 1590.77  5177.4  1591.1  5205.7 1591.61
  5226.8 1592.99    5252 1592.82  5367.1 1594.83  5429.2 1594.49  5665.6  1595.6
  5737.6 1597.47  5804.9 1597.99  5922.9 1600.12    5964 1601.32  6029.9 1601.83
#Mann= 5 ,-1 , 0
  4476.1     .05       0  4484.1      .1       0  4658.4     .05       0
  4997.5    .035       0  5003.5     .05       0
Bank Sta=4997.5,5003.5
XS Rating Curve= 0 ,0
Exp/Cntr=0.3,0.1

Type RM Length L Ch R = 1 ,1844    ,662,662,662
BEGIN DESCRIPTION:
UNT119 IN NNOGR 2.0
END DESCRIPTION:
XS GIS Cut Line= 2
      2797515.52     10065715.31      2795881.74     10065517.59
#Sta/Elev= 30
  4363.3 1595.13  4410.7 1594.94  4498.8 1592.72  4531.6 1592.58  4813.6  1588.1
  4913.4 1587.84  4934.5 1588.22  4954.6 1589.61  4984.9 1587.03  4994.9 1586.44
  5000.3 1586.77  5002.4  1586.3  5005.1  1585.8  5008.4  1586.3  5045.3 1587.21
  5065.4 1589.15  5176.2 1592.24  5297.1 1593.85  5397.8 1592.25  5414.9 1592.72
  5583.8 1593.16  5639.6 1594.48    5690 1594.82  5770.5 1596.82  5800.8 1596.92
  5820.9 1597.81  5834.5 1597.71  5916.4 1599.81  5961.9 1601.56    6009 1602.25
#Mann= 3 ,-1 , 0
  4363.3     .05       0  5002.4    .035       0  5008.4     .05       0
Bank Sta=5002.4,5008.4
XS Rating Curve= 0 ,0
Exp/Cntr=0.3,0.1

Type RM Length L Ch R = 1 ,1182    ,776,776,776
BEGIN DESCRIPTION:
UNT119 IN NNOGR 4.0
END DESCRIPTION:
XS GIS Cut Line= 4
      2797520.72     10065413.24      2797104.03     10065100.72
      2796632.68     10064944.47      2796057.15     10065100.72
#Sta/Elev= 30
  4264.6 1591.16  4329.9 1590.35  4437.5 1589.97  4493.7 1588.99  4608.3 1588.05
  4693.7  1586.5    4800 1585.52  4865.1  1584.6    4921 1584.59  4938.8 1583.94
  4952.7 1585.29  4979.1 1583.72    4999 1583.25  5001.8 1582.75    5005 1583.25
  5024.5 1583.27  5074.2 1585.22  5079.4 1584.94  5086.3 1585.34  5111.1 1585.09
  5117.9 1586.06  5128.5 1586.42  5174.5 1585.95  5206.2 1586.74  5281.6 1589.53
  5400.4 1588.66  5528.6 1589.45  5637.7 1591.94  5717.3 1593.17  5878.4 1597.39
#Mann= 5 ,-1 , 0
  4264.6     .05       0    4800      .1       0    4999     .07       0
    5005      .1       0  5024.5     .05       0
Bank Sta=4999,5005
XS Rating Curve= 0 ,0
Exp/Cntr=0.3,0.1

Type RM Length L Ch R = 1 ,406     ,0,0,0
BEGIN DESCRIPTION:
UNT119 IN NNOGR 3.0
END DESCRIPTION:
XS GIS Cut Line= 4
      2797305.09     10065027.25      2797290.66     10064421.03
      2797012.88     10064283.01      2796426.96      10064400.2
#Sta/Elev= 30
  4247.3 1586.21  4380.9 1585.08  4450.9 1583.94  4660.9 1581.92    4751 1580.51
    4811 1580.29  4849.8 1579.73  4899.5 1580.34  4921.9 1579.98  4927.5 1579.65
  4944.3 1579.58  4974.9 1578.53 4982.51 1577.86 5016.71 1577.87  5017.1 1578.63
  5033.9 1579.01  5056.3 1580.22  5061.9 1580.38  5078.7 1582.19  5090.6  1582.9
  5129.1  1583.4  5157.6 1584.53  5188.3 1584.45  5239.3 1585.25  5290.3 1585.32
  5433.5 1586.85  5464.1 1586.82  5525.3 1587.43  5555.9 1587.43  5761.4 1588.85
#Mann= 3 ,-1 , 0
  4247.3     .05       0  4921.9     .03       0  5056.3      .1       0
Bank Sta=4921.9,5056.3
XS Rating Curve= 0 ,0
Exp/Cntr=0.3,0.1

Chan Stop Cuts=-1
Use User Specified Reach Order=0
Composite Channel Slope=5