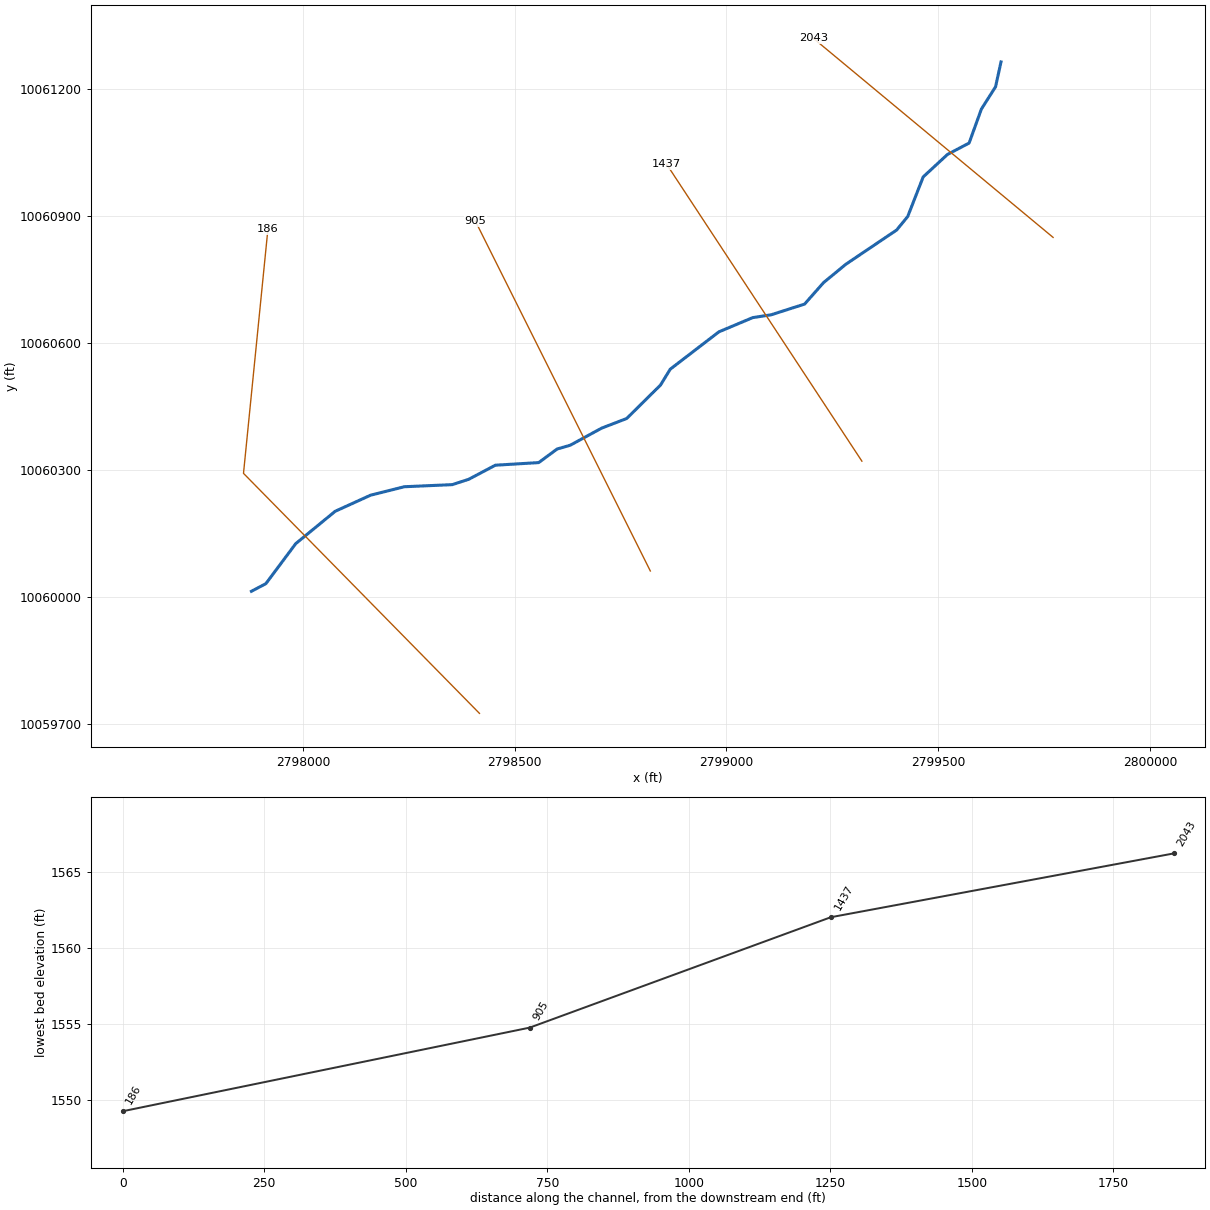
--- UNT120 IN NNOGR.prj (project) ---

Proj Title=UNT120 IN NNOGR Base Level Engineering
Current Plan=p01
Default Exp/Contr=0.3,0.1
English Units
Geom File=g01
Flow File=f01
Plan File=p01
BEGIN DESCRIPTION:
UNT120 IN NNOGR
END DESCRIPTION:

--- UNT120 IN NNOGR.p01 (plan) ---

Plan Title=Multiple Run
Short Identifier=Multiple
Geom File=g01
Flow File=f01
Subcritical Flow
K Sum by GR= 0
Std Step Tol= 0.01
Critical Tol= 0.01
Num of Std Step Trials= 20
Max Error Tol= 0.3
Flow Tol Ratio= 0.001
Split Flow NTrial= 30
Split Flow Tol= 0.02
Split Flow Ratio= 0.02
Log Output Level= 0
Friction Slope Method= 1
Unsteady Friction Slope Method= 2
Unsteady Bridges Friction Slope Method= 1
Parabolic Critical Depth
Global Vel Dist=  1 , 1 , 1
Global Log Level= 0
CheckData=True
Encroach Param= -1, 0, 0, 0
BEGIN DESCRIPTION:
Multiple Run
END DESCRIPTION:

--- UNT120 IN NNOGR.f01 (steady flow) ---

Flow Title=Multiple
Number of Profiles=7
Profile Names=10-year,25-year,50-year,1pct_min,100-year,1pct_plu,500-year
River Rch & RM= UNT120 IN NNOGR,Reach-1,2043
     313     421     508     450     609     823     875
Boundary for River Rch & Prof#=UNT120 IN NNOGR,Reach-1,1
Up Type=0
Dn Type=3
Dn Slope=0.005
Boundary for River Rch & Prof#=UNT120 IN NNOGR,Reach-1,2
Up Type=0
Dn Type=3
Dn Slope=0.005
Boundary for River Rch & Prof#=UNT120 IN NNOGR,Reach-1,3
Up Type=0
Dn Type=3
Dn Slope=0.005
Boundary for River Rch & Prof#=UNT120 IN NNOGR,Reach-1,4
Up Type=0
Dn Type=3
Dn Slope=0.005
Boundary for River Rch & Prof#=UNT120 IN NNOGR,Reach-1,5
Up Type=0
Dn Type=3
Dn Slope=0.005
Boundary for River Rch & Prof#=UNT120 IN NNOGR,Reach-1,6
Up Type=0
Dn Type=3
Dn Slope=0.005
Boundary for River Rch & Prof#=UNT120 IN NNOGR,Reach-1,7
Up Type=0
Dn Type=3
Dn Slope=0.005

--- UNT120 IN NNOGR.g01 (geometry) ---

Geom Title=Existing Conditions

River Reach=UNT120 IN NNOGR,Reach-1
Reach XY= 30
      2799648.47     10061263.73      2799635.58     10061204.92
      2799602.06     10061152.21      2799573.15     10061072.11
      2799522.06     10061045.24      2799464.75     10060992.19
      2799428.20     10060898.76      2799402.12     10060866.82
      2799282.20     10060785.99      2799229.54     10060742.62
      2799184.61     10060691.84      2799105.84     10060666.63
      2799062.15     10060659.90      2798982.22     10060626.25
      2798867.36     10060538.09      2798844.48     10060500.71
      2798764.66     10060421.74      2798705.70     10060399.05
      2798631.18     10060358.55      2798600.18     10060349.59
      2798556.87     10060317.59      2798454.43     10060311.40
      2798391.37     10060278.07      2798352.66     10060265.52
      2798239.72     10060260.60      2798159.79     10060240.57
      2798076.25     10060202.61      2797983.02     10060126.13
      2797912.53     10060031.67      2797878.47     10060013.73

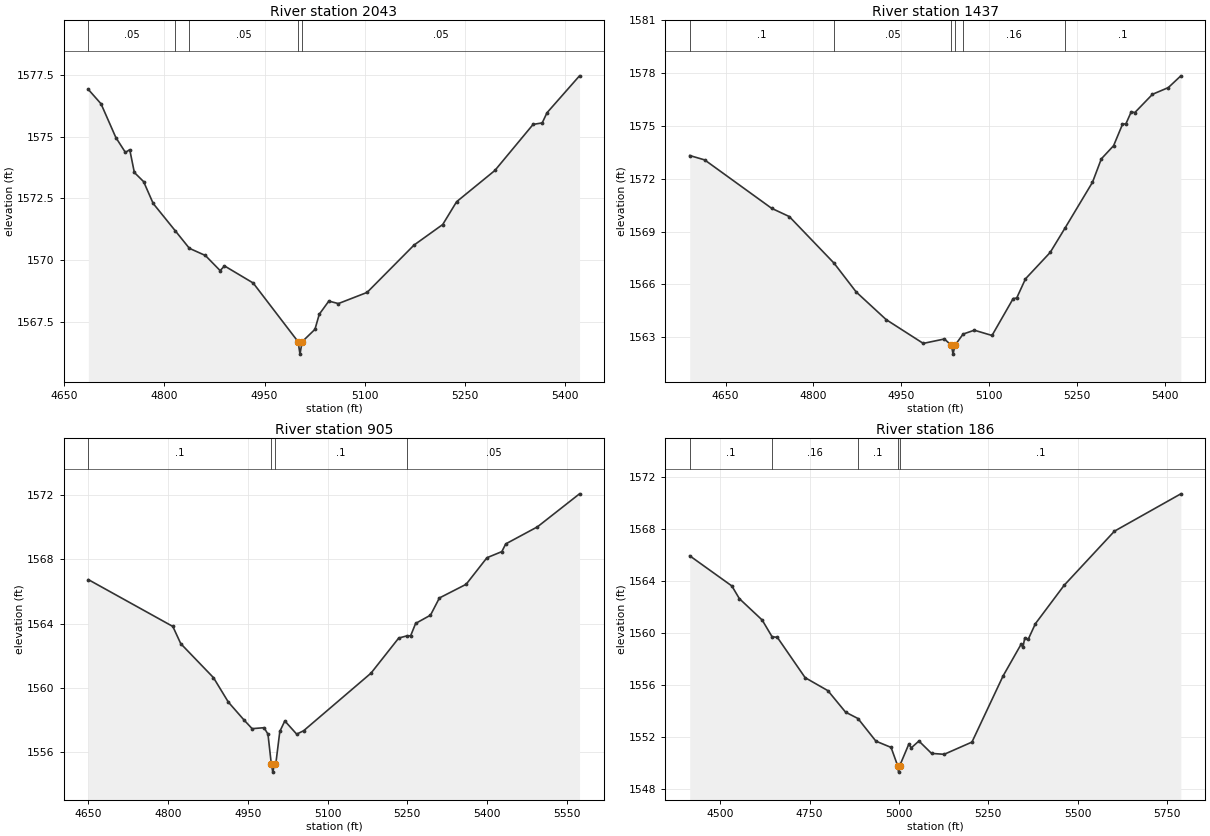
Type RM Length L Ch R = 1,2043,606,606,606
BEGIN DESCRIPTION:
UNT120 IN NNOGR 4.0
END DESCRIPTION:
XS GIS Cut Line= 2
      2799771.44     10060849.36      2799205.48     10061319.40
#Sta/Elev= 30
  4686.0 1576.90  4705.0 1576.32  4727.2 1574.96  4741.5 1574.36  4748.0 1574.47
  4754.9 1573.55  4768.8 1573.18  4783.1 1572.30  4816.1 1571.20  4837.3 1570.49
  4861.3 1570.20  4883.4 1569.59  4889.9 1569.78  4932.9 1569.09  5000.2 1566.72
  5003.0 1566.22  5006.2 1566.72  5025.4 1567.22  5031.9 1567.83  5046.2 1568.36
  5060.5 1568.26  5103.5 1568.71  5173.8 1570.62  5216.8 1571.45  5237.6 1572.37
  5294.9 1573.63  5352.2 1575.49  5365.8 1575.55  5373.0 1575.96  5421.7 1577.45
#Mann=5,-1,0
  4686.0    0.05       0  4816.1     0.1       0  4837.3    0.05       0
  5000.2   0.035       0  5006.2    0.05       0
Bank Sta=5000.2,5006.2
Exp/Cntr=0.3,0.1

Type RM Length L Ch R = 1,1437,532,532,532
BEGIN DESCRIPTION:
UNT120 IN NNOGR 3.0
END DESCRIPTION:
XS GIS Cut Line= 2
      2799319.91     10060321.04      2798858.79     10061022.32
#Sta/Elev= 30
  4588.6 1573.32  4614.2 1573.07  4728.6 1570.32  4758.8 1569.85  4835.3 1567.20
  4873.2 1565.56  4924.4 1563.99  4987.7 1562.64  5023.8 1562.89  5035.9 1562.53
  5038.6 1562.03  5041.9 1562.53  5055.8 1563.17  5075.0 1563.39  5105.2 1563.09
  5141.4 1565.19  5147.4 1565.22  5162.4 1566.31  5204.6 1567.81  5230.4 1569.22
  5276.9 1571.80  5292.0 1573.13  5313.0 1573.88  5328.1 1575.09  5334.1 1575.13
  5343.2 1575.81  5349.2 1575.76  5379.4 1576.80  5406.4 1577.18  5427.9 1577.85
#Mann=6,-1,0
  4588.6     0.1       0  4835.3    0.05       0  5035.9   0.035       0
  5041.9    0.05       0  5055.8    0.16       0  5230.4     0.1       0
Bank Sta=5035.9,5041.9
Exp/Cntr=0.3,0.1

Type RM Length L Ch R = 1,905,719,719,719
BEGIN DESCRIPTION:
UNT120 IN NNOGR 2.0
END DESCRIPTION:
XS GIS Cut Line= 2
      2798820.39     10060061.63      2798407.30     10060887.81
#Sta/Elev= 30
  4650.2 1566.74  4809.1 1563.83  4824.0 1562.76  4885.5 1560.65  4913.5 1559.13
  4943.2 1558.01  4958.2 1557.48  4980.6 1557.54  4988.0 1557.14  4994.3 1555.28
  4997.1 1554.78  5000.3 1555.28  5002.9 1555.34  5010.3 1557.31  5019.7 1557.96
  5042.0 1557.14  5055.0 1557.35  5181.8 1560.93  5233.9 1563.11  5249.8 1563.25
  5256.3 1563.25  5265.7 1564.02  5293.6 1564.53  5310.4 1565.60  5360.7 1566.45
  5399.8 1568.10  5427.8 1568.48  5435.2 1568.96  5494.8 1570.02  5573.9 1572.07
#Mann=4,-1,0
  4650.2     0.1       0  4994.3    0.07       0  5000.3     0.1       0
  5249.8    0.05       0
Bank Sta=4994.3,5000.3
Exp/Cntr=0.3,0.1

Type RM Length L Ch R = 1,186,0,0,0
BEGIN DESCRIPTION:
UNT120 IN NNOGR 1.0
END DESCRIPTION:
XS GIS Cut Line= 3
      2798416.92     10059725.41      2797859.74     10060292.19
      2797917.38     10060868.62
#Sta/Elev= 30
  4414.8 1565.92  4532.7 1563.60  4553.9 1562.62  4617.6 1560.98  4645.2 1559.70
  4660.0 1559.65  4737.8 1556.55  4801.5 1555.55  4850.9 1553.90  4885.6 1553.41
  4935.8 1551.67  4978.2 1551.19  4996.5 1549.79  4999.2 1549.29  5002.5 1549.79
  5027.8 1551.44  5034.8 1551.16  5056.1 1551.68  5091.4 1550.73  5126.8 1550.66
  5204.5 1551.60  5291.5 1556.68  5341.8 1559.11  5347.2 1558.89  5352.2 1559.61
  5361.9 1559.50  5382.0 1560.70  5462.4 1563.65  5603.1 1567.81  5788.9 1570.68
#Mann=5,-1,0
  4414.8     0.1       0  4645.2    0.16       0  4885.6     0.1       0
  4996.5    0.07       0  5002.5     0.1       0
Bank Sta=4996.5,5002.5
Exp/Cntr=0.3,0.1

Chan Stop Cuts=-1