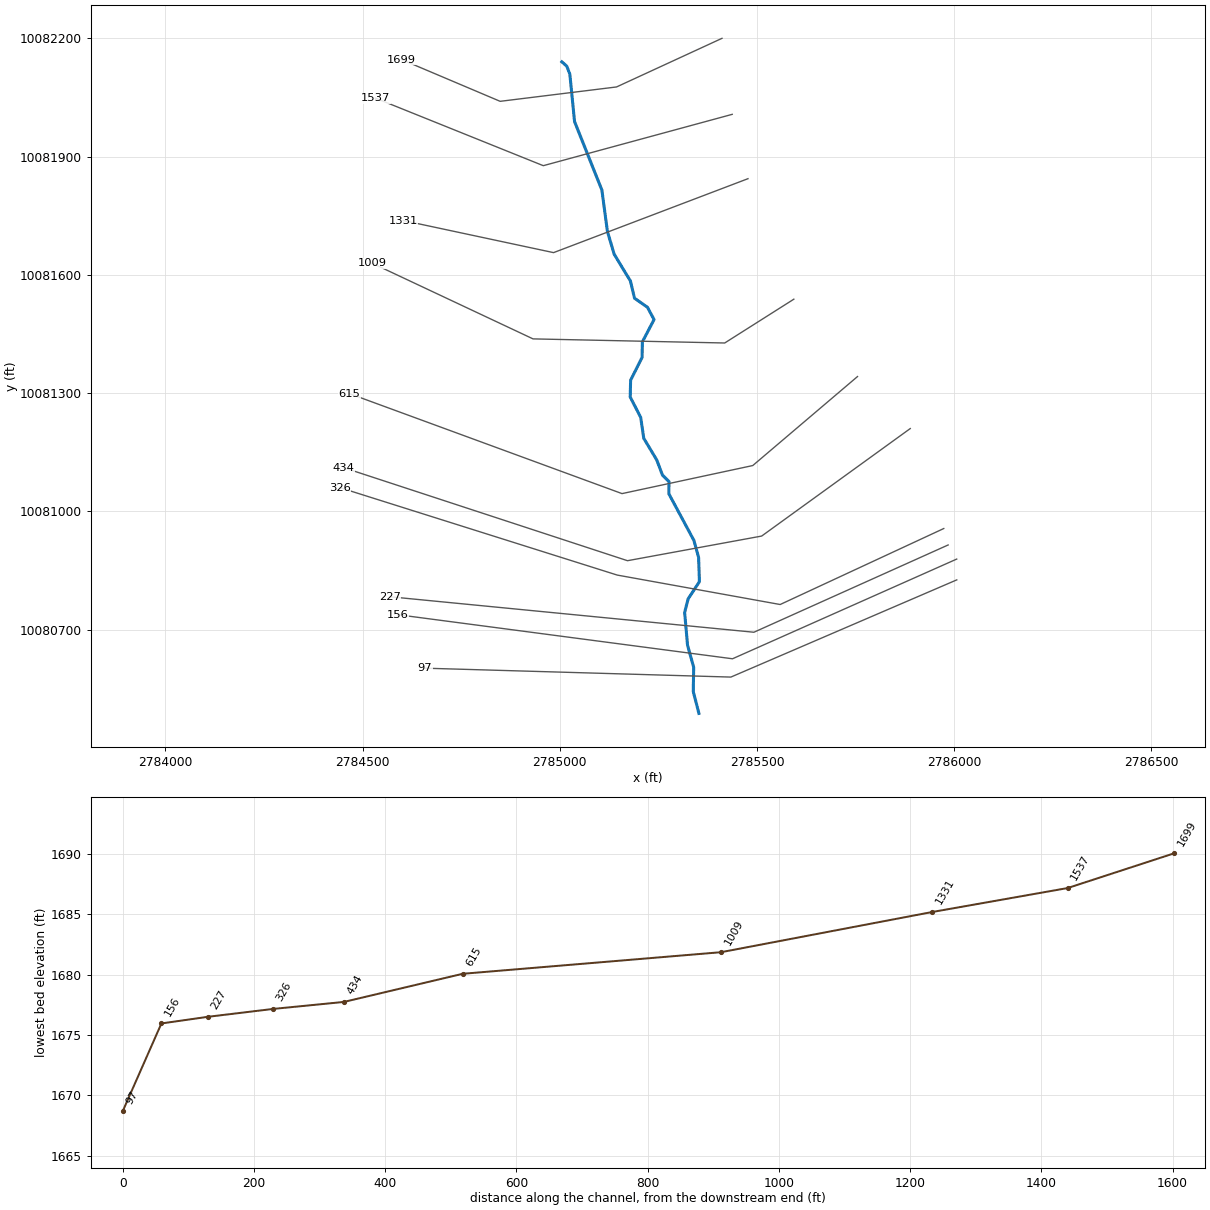
--- UNT121 IN NNOGR.prj (project) ---

Proj Title=UNT121 IN NNOGR Base Level Engineering
Current Plan=p01
Default Exp/Contr=0.3,0.1
English Units
Geom File=g01
Flow File=f01
Plan File=p01
Y Axis Title=Elevation
X Axis Title(PF)=Main Channel Distance
X Axis Title(XS)=Station
BEGIN DESCRIPTION:
UNT121 IN NNOGR
END DESCRIPTION:
DSS Export Rating Curves= 0
DSS Export Rating Curve Sorted= 0
DSS Export Volume Flow Curves= 0
DXF OffsetX= 0
DXF OffsetY= 0
DXF ScaleX= 1
DXF ScaleY= 10

--- UNT121 IN NNOGR.p01 (plan) ---

Plan Title=Multiple Run
Short Identifier=Multiple
Geom File=g01
Flow File=f01
Subcritical Flow
K Sum by GR= 0
Std Step Tol= 0.01
Critical Tol= 0.01
Num of Std Step Trials= 20
Max Error Tol= 0.3
Flow Tol Ratio= 0.001
Split Flow NTrial= 30
Split Flow Tol= 0.02
Split Flow Ratio= 0.02
Log Output Level= 0
Friction Slope Method= 1
Unsteady Friction Slope Method= 2
Unsteady Bridges Friction Slope Method= 1
Parabolic Critical Depth
Global Vel Dist=  1 , 1 , 1
Global Log Level= 0
CheckData=True
Encroach Param= -1, 0, 0, 0
BEGIN DESCRIPTION:
Multiple Run
END DESCRIPTION:

--- UNT121 IN NNOGR.f01 (steady flow) ---

Flow Title=Multiple
Program Version=4.10
Number of Profiles= 7
Profile Names=10-year,25-year,50-year,1pct_min,100-year,1pct_plu,500-year
River Rch & RM=UNT121 IN NNOGR,Reach-1         ,1699
     324     441     537     480     649     878     952
Boundary for River Rch & Prof#=UNT121 IN NNOGR,Reach-1         , 1
Up Type= 0
Dn Type= 3
Dn Slope=0.0368
Boundary for River Rch & Prof#=UNT121 IN NNOGR,Reach-1         , 2
Up Type= 0
Dn Type= 3
Dn Slope=0.0368
Boundary for River Rch & Prof#=UNT121 IN NNOGR,Reach-1         , 3
Up Type= 0
Dn Type= 3
Dn Slope=0.0368
Boundary for River Rch & Prof#=UNT121 IN NNOGR,Reach-1         , 4
Up Type= 0
Dn Type= 3
Dn Slope=0.0368
Boundary for River Rch & Prof#=UNT121 IN NNOGR,Reach-1         , 5
Up Type= 0
Dn Type= 3
Dn Slope=0.0368
Boundary for River Rch & Prof#=UNT121 IN NNOGR,Reach-1         , 6
Up Type= 0
Dn Type= 3
Dn Slope=0.0368
Boundary for River Rch & Prof#=UNT121 IN NNOGR,Reach-1         , 7
Up Type= 0
Dn Type= 3
Dn Slope=0.0368
DSS Import GetInterval= 0
DSS Import GetPeak= 0
DSS Import FillOption= 0

--- UNT121 IN NNOGR.g01 (geometry) ---

Geom Title=Existing Conditions
Program Version=4.10

River Reach=UNT121 IN NNOGR ,Reach-1
Reach XY= 30
      2785005.08     10082140.16      2785017.58     10082129.22
      2785025.39     10082108.91      2785037.37      10081988.6
      2785106.64     10081815.16       2785120.7     10081709.95
      2785137.89     10081652.14      2785179.03     10081584.43
      2785189.45     10081540.68      2785222.26     10081517.76
      2785238.93     10081486.51      2785209.24     10081429.74
      2785208.72     10081390.68      2785179.55     10081332.87
      2785178.51     10081290.16      2785205.08      10081238.6
      2785212.89     10081185.47       2785245.7     10081130.78
      2785260.28     10081092.24      2785276.95     10081075.58
      2785276.43     10081044.85      2785339.97     10080926.62
      2785351.95     10080883.39      2785354.03     10080821.93
      2785325.39     10080778.18      2785316.53      10080743.8
      2785323.83     10080660.99      2785339.45     10080604.74
      2785338.41     10080543.28      2785352.74      10080487.9

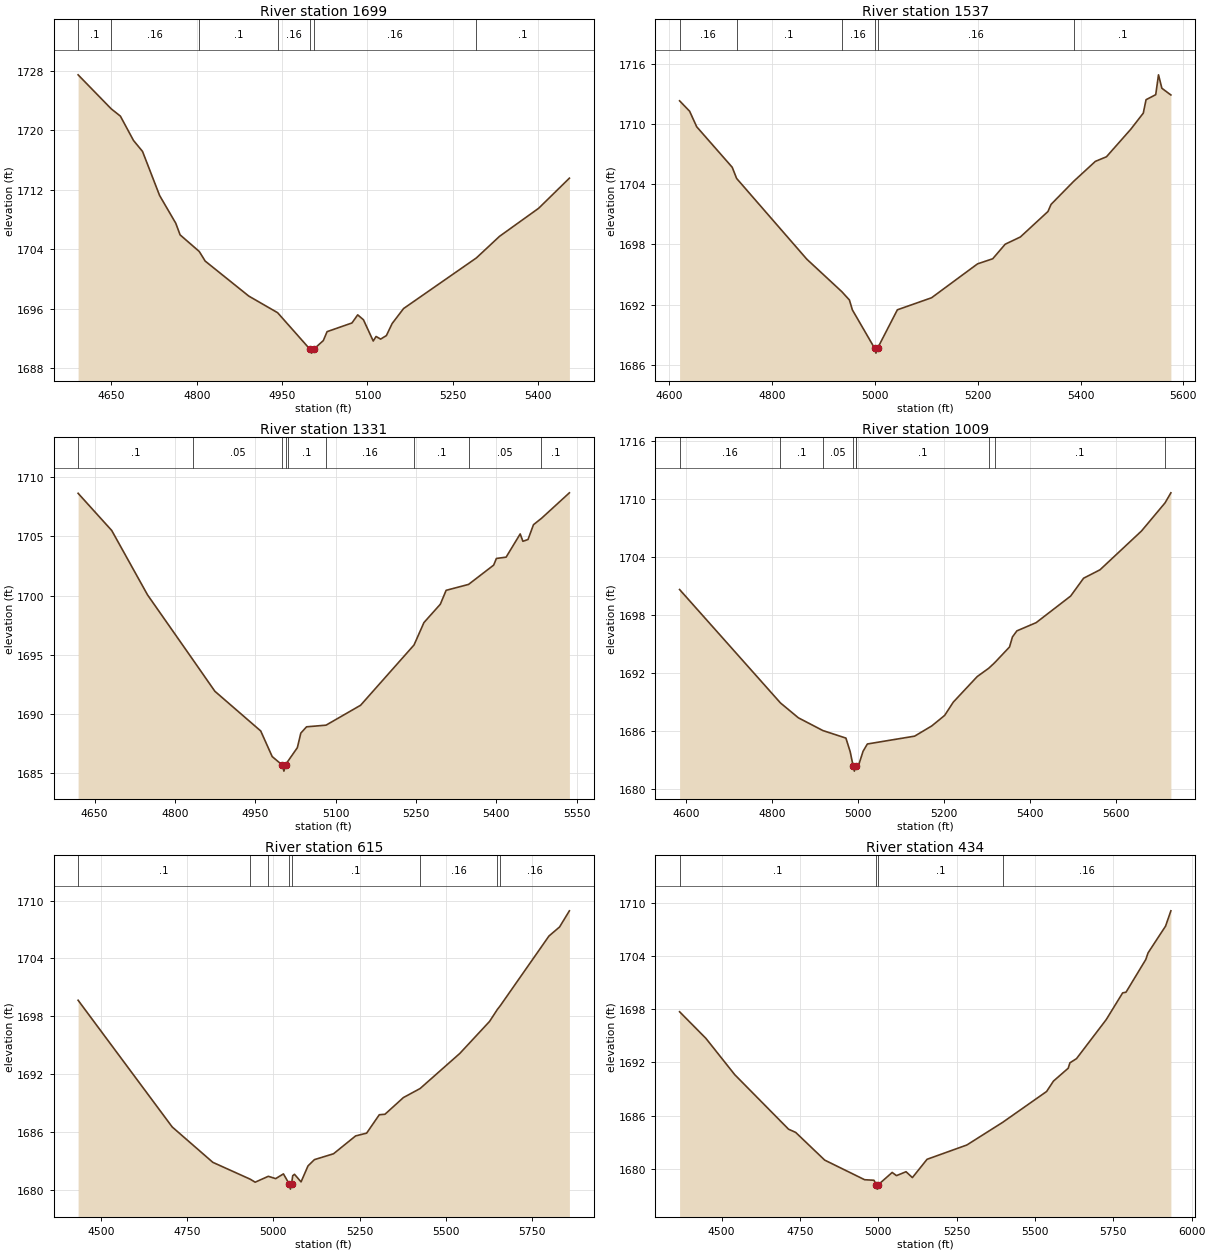
Type RM Length L Ch R = 1 ,1699    ,162,162,162
BEGIN DESCRIPTION:
Mapping XS 851508d0.3
END DESCRIPTION:
XS GIS Cut Line= 4
      2785411.24     10082199.74      2785143.84     10082076.46
       2784848.7       10082040.      2784598.74     10082145.89
#Sta/Elev= 30
  4591.5 1727.49  4649.7 1722.91  4665.8 1721.93  4688.8 1718.66  4704.7 1717.18
  4734.7 1711.25  4763.2  1707.5  4770.7 1705.95  4804.4 1703.71  4814.8 1702.42
  4891.4 1697.71  4942.1 1695.47  4999.2 1690.53    5002 1690.03  5005.2 1690.53
  5022.4 1691.72    5029 1692.92  5072.7 1694.09  5082.8 1695.18  5092.9 1694.52
  5110.1 1691.66  5115.1 1692.27  5123.1 1691.92  5133.2 1692.39  5143.3 1694.01
  5163.4 1696.03  5291.3 1702.84    5332 1705.75  5400.8 1709.53  5454.8 1713.58
#Mann= 7 ,-1 , 0
  4591.5      .1       0  4649.7     .16       0  4804.4      .1       0
  4942.1     .16       0  4999.2     .07       0  5005.2     .16       0
  5291.3      .1       0
Bank Sta=4999.2,5005.2
XS Rating Curve= 0 ,0
Exp/Cntr=0.3,0.1

Type RM Length L Ch R = 1 ,1537    ,206,206,206
BEGIN DESCRIPTION:
Mapping XS 5ed88c1d
END DESCRIPTION:
XS GIS Cut Line= 3
      2785437.25     10082007.02      2784958.08     10081876.81
      2784532.22     10082048.19
#Sta/Elev= 30
  4620.1 1712.32  4639.6 1711.28  4653.4 1709.73  4722.5 1705.69    4731 1704.58
  4867.5 1696.53  4935.6 1693.29  4950.4 1692.46  4956.2 1691.47  4999.3 1687.66
    5002 1687.16  5005.3 1687.66  5043.7 1691.48  5110.2 1692.68  5199.6 1696.06
  5229.2 1696.57  5253.4 1698.02  5282.9 1698.74  5336.6 1701.28  5342.6 1701.99
  5386.6 1704.29  5428.8 1706.28  5450.4 1706.74  5497.8 1709.49    5522 1711.09
  5527.4 1712.43  5546.2 1712.93  5551.6 1714.91  5558.2 1713.57  5575.7  1712.9
#Mann= 6 ,-1 , 0
  4620.1     .16       0    4731      .1       0  4935.6     .16       0
  4999.3     .07       0  5005.3     .16       0  5386.6      .1       0
Bank Sta=4999.3,5005.3
XS Rating Curve= 0 ,0
Exp/Cntr=0.3,0.1

Type RM Length L Ch R = 1 ,1331    ,322,322,322
BEGIN DESCRIPTION:
Mapping XS 8445b7cf
END DESCRIPTION:
XS GIS Cut Line= 3
      2785477.18     10081843.83      2784984.12     10081656.32
      2784602.83     10081737.78
#Sta/Elev= 30
  4619.2 1708.63    4682 1705.49  4748.8 1700.06    4833 1694.62  4874.6 1691.92
  4960.2 1688.57  4981.6 1686.41  5000.8 1685.68  5003.5 1685.18  5006.8 1685.68
  5010.9 1686.01  5028.6 1687.16  5035.1 1688.39  5045.8 1688.92  5082.2 1689.06
  5146.7 1690.74  5246.5 1695.83    5265 1697.72  5295.6 1699.27  5306.4 1700.44
  5348.3 1700.94  5395.2 1702.57  5400.3 1703.13  5418.4 1703.24  5444.7  1705.2
  5449.8 1704.58  5459.3 1704.73  5469.5 1705.98  5484.3 1706.51  5536.6 1708.67
#Mann= 9 ,-1 , 0
  4619.2      .1       0    4833     .05       0  5000.8    .035       0
  5006.8     .05       0  5010.9      .1       0  5082.2     .16       0
  5246.5      .1       0  5348.3     .05       0  5484.3      .1       0
Bank Sta=5000.8,5006.8
XS Rating Curve= 0 ,0
Exp/Cntr=0.3,0.1

Type RM Length L Ch R = 1 ,1009    ,394,394,394
BEGIN DESCRIPTION:
Mapping XS 38ac7d3e
END DESCRIPTION:
XS GIS Cut Line= 4
      2785593.47     10081538.25      2785418.15     10081427.16
      2784932.04     10081437.57      2784524.54     10081629.24
#Sta/Elev= 30
  4584.4 1700.65  4819.3 1688.91    4861 1687.37  4918.1 1686.05  4971.7 1685.27
  4981.7 1683.86  4988.7 1682.35  4991.4 1681.85  4994.7 1682.35    4996 1682.38
  5001.7 1682.52  5011.7 1683.91  5021.7 1684.66  5131.7 1685.47  5171.7 1686.53
  5201.7 1687.62  5221.7 1688.99  5277.5 1691.64  5304.3  1692.5  5317.8 1693.06
  5352.7  1694.7  5359.5 1695.74  5369.9 1696.37  5414.7 1697.22    5495 1699.97
  5525.2 1701.82  5563.4 1702.69  5660.1 1706.71  5714.9 1709.62  5728.5 1710.66
#Mann= 9 ,-1 , 0
  4584.4     .16       0  4819.3      .1       0  4918.1     .05       0
  4988.7     .07       0  4994.7     .05       0    4996      .1       0
  5304.3     .16       0  5317.8      .1       0  5714.9     .05       0
Bank Sta=4988.7,4994.7
XS Rating Curve= 0 ,0
Exp/Cntr=0.3,0.1

Type RM Length L Ch R = 1 ,615     ,181,181,181
BEGIN DESCRIPTION:
Mapping XS ff35721a
END DESCRIPTION:
XS GIS Cut Line= 4
      2785754.98     10081342.11      2785489.33     10081116.39
      2785157.73     10081045.21       2784466.8     10081298.67
#Sta/Elev= 30
  4434.1 1699.66  4706.8 1686.51  4824.5 1682.84  4932.9 1681.09  4947.2 1680.78
  4985.3 1681.39  5006.6 1681.15  5029.1 1681.64  5046.5 1680.56  5049.3 1680.06
  5052.5 1680.56    5056 1681.45  5061.1  1681.6  5080.2 1680.81  5100.3 1682.47
  5118.9 1683.12  5174.3 1683.73  5238.2 1685.58  5270.2 1685.87  5306.9 1687.78
  5323.4 1687.83  5376.7 1689.56  5425.2  1690.5  5540.2 1694.14  5626.4 1697.46
  5649.1 1698.71    5658 1699.12  5798.7 1706.33  5829.2 1707.26  5857.8 1708.94
#Mann= 8 ,-1 , 0
  4434.1      .1       0  4932.9     .05       0  4985.3      .1       0
  5046.5     .07       0  5052.5      .1       0  5425.2     .16       0
  5649.1      .1       0    5658     .16       0
Bank Sta=5046.5,5052.5
XS Rating Curve= 0 ,0
Exp/Cntr=0.3,0.1

Type RM Length L Ch R = 1 ,434     ,108,108,108
BEGIN DESCRIPTION:
Mapping XS 5bc3fdde
END DESCRIPTION:
XS GIS Cut Line= 4
      2785888.66     10081210.16       2785511.9     10080937.57
      2785171.62     10080875.07      2784452.26     10081110.82
#Sta/Elev= 30
  4365.7 1697.71  4449.8 1694.71  4541.8 1690.62  4713.5 1684.48  4736.2 1684.12
  4828.8    1681  4956.2 1678.79    4986 1678.73  4993.9 1678.23  4996.6 1677.73
  4999.9 1678.23  5044.2 1679.61  5057.9 1679.25  5088.4 1679.69  5108.7 1679.03
  5155.5 1681.09  5282.4  1682.7  5396.7 1685.25  5537.1 1688.73  5558.9  1689.9
    5606 1691.35  5611.5 1691.96  5632.5 1692.43  5727.2 1696.82  5779.8 1699.84
  5790.4 1699.91  5853.5 1703.59  5860.8 1704.34  5916.6 1707.35  5933.7 1709.08
#Mann= 4 ,-1 , 0
  4365.7      .1       0  4993.9     .07       0  4999.9      .1       0
  5396.7     .16       0
Bank Sta=4993.9,4999.9
XS Rating Curve= 0 ,0
Exp/Cntr=0.3,0.1

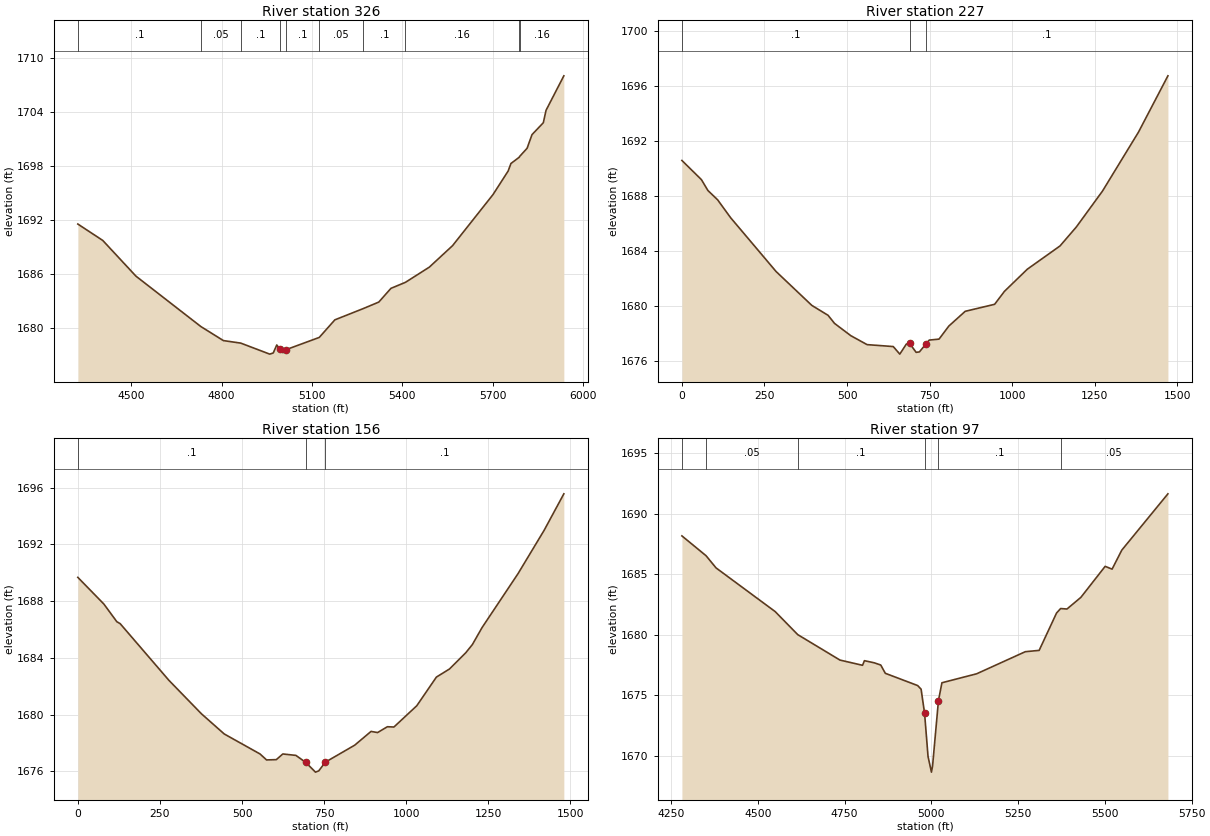
Type RM Length L Ch R = 1 ,326     ,99,99,99
BEGIN DESCRIPTION:
Mapping XS f1d11370
END DESCRIPTION:
XS GIS Cut Line= 4
      2785973.67     10080956.66      2785558.77     10080763.96
      2785145.58     10080838.62      2784442.06     10081060.41
#Sta/Elev= 30
    4322 1691.57  4404.9 1689.75  4515.2 1685.79  4731.1  1680.2  4805.7 1678.65
  4863.4 1678.37  4959.7 1677.15  4971.4 1677.28    4983 1678.16  4993.2 1677.72
  5003.3 1677.31  5013.5 1677.64  5124.2    1679  5176.1 1680.95  5270.6  1682.2
  5322.1 1682.92  5362.4 1684.44  5410.7 1685.11  5489.9 1686.79  5567.1 1689.17
  5701.7 1694.84    5752 1697.45  5761.2 1698.28  5788.9 1698.98  5790.3 1699.07
  5814.9 1699.97  5831.2 1701.48  5868.8  1702.8  5877.9 1704.18    5937    1708
#Mann= 10 ,-1 , 0
    4322      .1       0  4731.1     .05       0  4863.4      .1       0
  4993.2     .07       0  5013.5      .1       0  5124.2     .05       0
  5270.6      .1       0  5410.7     .16       0  5788.9     .05       0
  5790.3     .16       0
Bank Sta=4993.2,5013.5
XS Rating Curve= 0 ,0
Exp/Cntr=0.3,0.1

Type RM Length L Ch R = 1 ,227     ,71,71,71
XS GIS Cut Line= 3
     2785984.778    10080914.992     2785492.156    10080693.638
     2784568.762    10080783.698
#Sta/Elev= 30
       0 1690.57   59.02 1689.18    78.7 1688.39  108.21 1687.71  147.56 1686.41
  285.29  1682.5   393.5 1680.04  442.68 1679.32  462.36 1678.73  511.55 1677.84
  560.86 1677.19  640.09 1677.05   659.9  1676.5   679.7 1677.23  689.61 1677.28
  709.41 1676.63  719.32 1676.66  739.12 1677.24  749.03 1677.52  778.74 1677.59
  808.45 1678.54  857.96 1679.61  947.09 1680.12   976.8 1681.06 1046.13 1682.67
 1145.16 1684.36 1194.68 1685.74  1273.9 1688.35 1382.84 1692.63 1471.97 1696.72
#Mann= 3 , 0 , 0
       0      .1       0  689.61     .05       0  739.12      .1       0
Bank Sta=689.61,739.12
XS Rating Curve= 0 ,0
Exp/Cntr=0.3,0.1

Type RM Length L Ch R = 1 ,156     ,59,59,59
XS GIS Cut Line= 3
     2786006.479    10080879.185     2785437.903    10080626.363
     2784589.378    10080738.126
#Sta/Elev= 30
       0 1689.68   79.27  1687.8   118.9 1686.55  128.81 1686.42  277.44 1682.42
  376.52 1680.06  445.88 1678.64  554.88 1677.23  574.69 1676.81  604.42 1676.83
  624.24 1677.23  664.04 1677.13   693.9 1676.64  723.75 1675.95  733.71 1676.04
  753.61 1676.65  843.17 1677.85  892.93 1678.82  912.84 1678.74  942.69 1679.15
   962.6 1679.13 1032.26 1680.63 1091.97 1682.65 1131.78 1683.22 1181.54 1684.37
 1201.44 1684.94 1231.29 1686.15 1340.76 1689.95 1420.38 1693.01 1480.09 1695.57
#Mann= 3 , 0 , 0
       0      .1       0   693.9     .05       0  753.61      .1       0
Bank Sta=693.9,753.61
XS Rating Curve= 0 ,0
Exp/Cntr=0.3,0.1

Type RM Length L Ch R = 1 ,97      ,0,0,0
BEGIN DESCRIPTION:
Mapping XS 851508d0.2
END DESCRIPTION:
XS GIS Cut Line= 3
      2786006.65     10080826.45      2785433.77     10080579.94
      2784657.76      10080602.5
#Sta/Elev= 30
  4281.6 1688.16    4351 1686.53    4380 1685.52  4550.2 1681.92  4615.2 1680.02
  4736.9 1677.92  4801.9 1677.49  4807.4 1677.87  4836.3 1677.69  4854.4 1677.51
  4867.5 1676.83  4960.6 1675.82  4970.6 1675.52  4980.6 1673.54  4990.6 1669.97
  5000.4 1668.68  5003.6 1669.18  5020.6 1674.58  5030.6 1676.05  5130.7 1676.79
  5270.7 1678.61  5310.7 1678.72  5360.8  1681.8  5372.6 1682.17  5390.8 1682.13
  5430.8 1683.09  5500.8 1685.65  5520.8 1685.42  5548.8 1686.99  5681.6 1691.63
#Mann= 6 ,-1 , 0
  4281.6      .1       0    4351     .05       0  4615.2      .1       0
  4980.6     .05       0  5020.6      .1       0  5372.6     .05       0
Bank Sta=4980.6,5020.6
XS Rating Curve= 0 ,0
Exp/Cntr=0.3,0.1

Chan Stop Cuts=-1
Use User Specified Reach Order=0
Composite Channel Slope=5