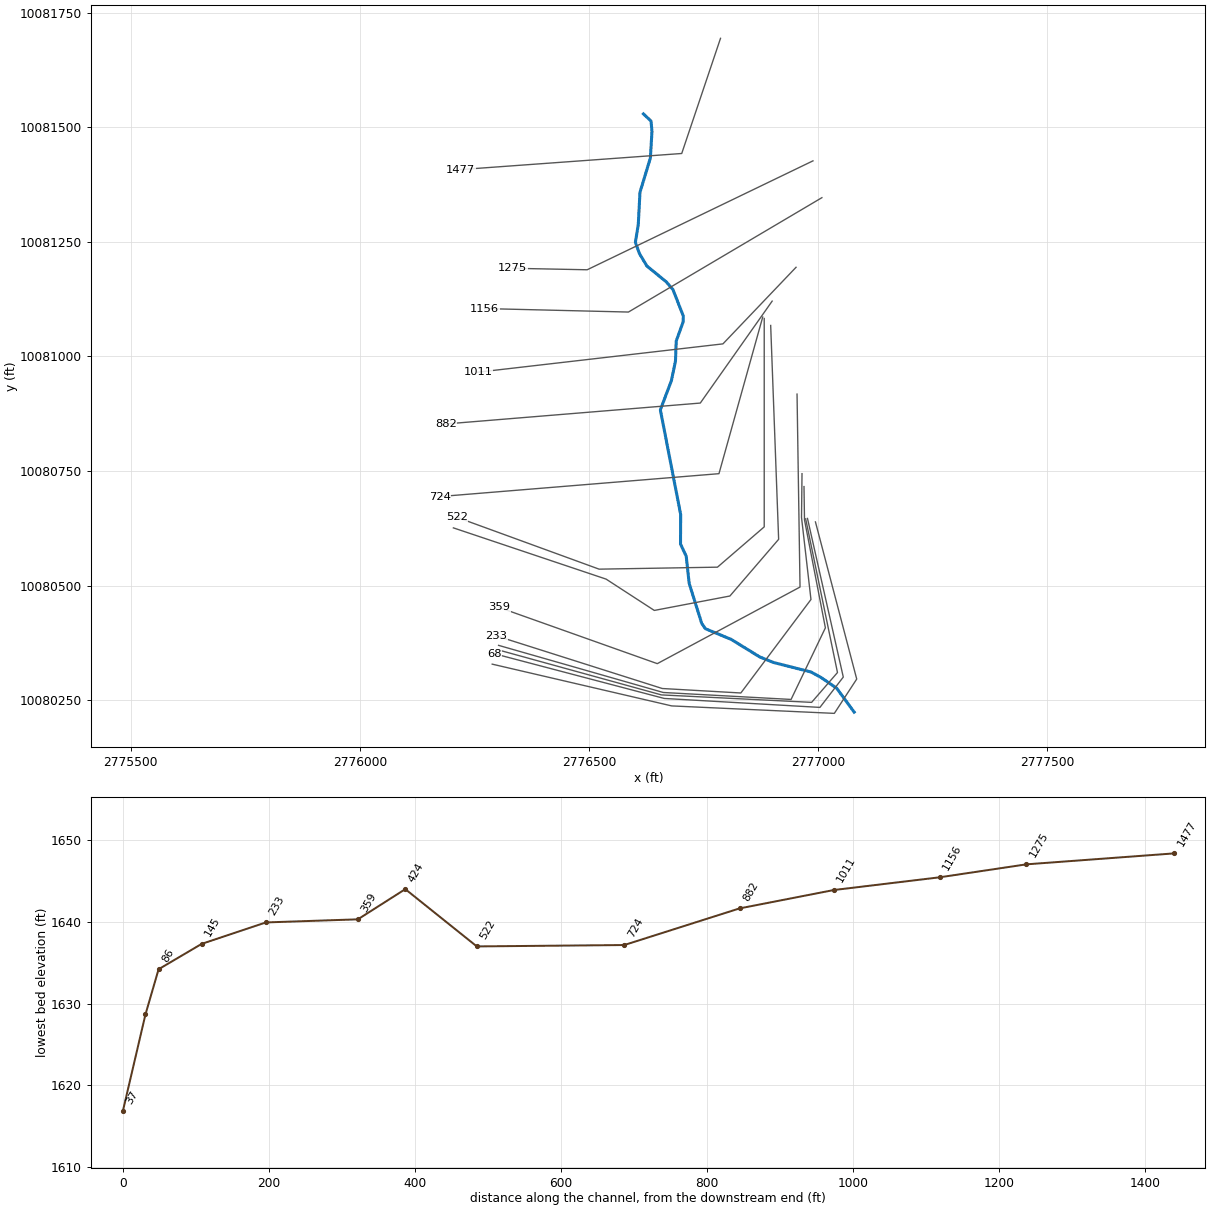
--- UNT997 IN NNOGR.prj (project) ---

Proj Title=UNT997 IN NNOGR Base Level Engineering
Current Plan=p01
Default Exp/Contr=0.3,0.1
English Units
Geom File=g01
Flow File=f01
Plan File=p01
Y Axis Title=Elevation
X Axis Title(PF)=Main Channel Distance
X Axis Title(XS)=Station
BEGIN DESCRIPTION:
UNT997 IN NNOGR
END DESCRIPTION:
DSS Export Rating Curves= 0
DSS Export Rating Curve Sorted= 0
DSS Export Volume Flow Curves= 0
DXF OffsetX= 0
DXF OffsetY= 0
DXF ScaleX= 1
DXF ScaleY= 10

--- UNT997 IN NNOGR.p01 (plan) ---

Plan Title=Multiple Run
Short Identifier=Multiple
Geom File=g01
Flow File=f01
Subcritical Flow
K Sum by GR= 0
Std Step Tol= 0.01
Critical Tol= 0.01
Num of Std Step Trials= 20
Max Error Tol= 0.3
Flow Tol Ratio= 0.001
Split Flow NTrial= 30
Split Flow Tol= 0.02
Split Flow Ratio= 0.02
Log Output Level= 0
Friction Slope Method= 1
Unsteady Friction Slope Method= 2
Unsteady Bridges Friction Slope Method= 1
Parabolic Critical Depth
Global Vel Dist=  1 , 1 , 1
Global Log Level= 0
CheckData=True
Encroach Param= -1, 0, 0, 0
BEGIN DESCRIPTION:
Multiple Run
END DESCRIPTION:

--- UNT997 IN NNOGR.f01 (steady flow) ---

Flow Title=Multiple
Program Version=4.10
Number of Profiles= 7
Profile Names=10-year,25-year,50-year,1pct_min,100-year,1pct_plu,500-year
River Rch & RM=UNT997 IN NNOGR,Reach-1         ,1477
     153     196     229     197     266     360     360
Boundary for River Rch & Prof#=UNT997 IN NNOGR,Reach-1         , 1
Up Type= 0
Dn Type= 3
Dn Slope=0.45
Boundary for River Rch & Prof#=UNT997 IN NNOGR,Reach-1         , 2
Up Type= 0
Dn Type= 3
Dn Slope=0.45
Boundary for River Rch & Prof#=UNT997 IN NNOGR,Reach-1         , 3
Up Type= 0
Dn Type= 3
Dn Slope=0.45
Boundary for River Rch & Prof#=UNT997 IN NNOGR,Reach-1         , 4
Up Type= 0
Dn Type= 3
Dn Slope=0.45
Boundary for River Rch & Prof#=UNT997 IN NNOGR,Reach-1         , 5
Up Type= 0
Dn Type= 3
Dn Slope=0.45
Boundary for River Rch & Prof#=UNT997 IN NNOGR,Reach-1         , 6
Up Type= 0
Dn Type= 3
Dn Slope=0.45
Boundary for River Rch & Prof#=UNT997 IN NNOGR,Reach-1         , 7
Up Type= 0
Dn Type= 3
Dn Slope=0.45
DSS Import GetInterval= 0
DSS Import GetPeak= 0
DSS Import FillOption= 0

--- UNT997 IN NNOGR.g01 (geometry) ---

Geom Title=Existing Conditions
Program Version=4.10

River Reach=UNT997 IN NNOGR ,Reach-1
Reach XY= 30
      2776618.47     10081529.33      2776635.05     10081513.66
      2776637.13     10081490.75      2776633.66     10081433.11
      2776610.95     10081358.25      2776607.27     10081288.23
      2776600.95     10081249.09      2776609.82     10081224.33
      2776625.96     10081197.49       2776668.2     10081162.99
      2776682.87     10081146.09      2776705.55     10081088.12
      2776704.95     10081075.02      2776690.03     10081033.65
      2776688.41     10080990.24      2776679.51     10080947.21
      2776655.43     10080883.68      2776699.71      10080655.4
      2776699.42     10080590.94      2776711.86     10080564.08
      2776718.29     10080505.01      2776745.72     10080417.51
       2776753.7     10080406.05      2776809.95     10080382.78
      2776872.11     10080344.59      2776901.97     10080332.44
      2776984.26      10080311.6      2777005.79      10080299.8
      2777040.16     10080276.19      2777078.33     10080224.08

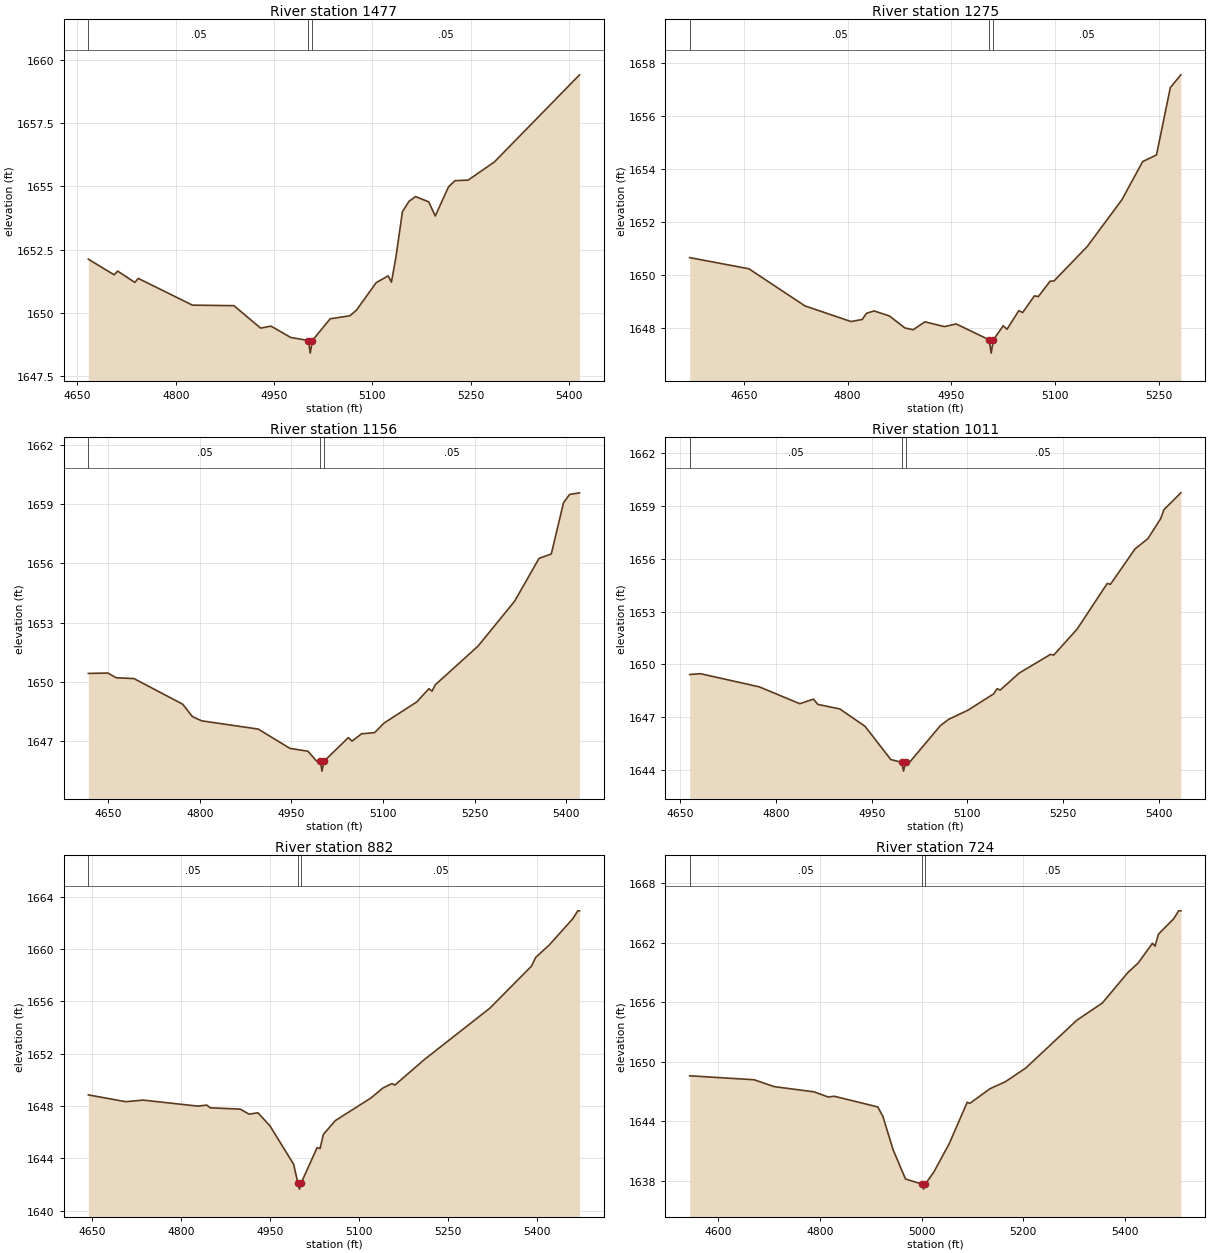
Type RM Length L Ch R = 1 ,1477    ,202,202,202
BEGIN DESCRIPTION:
UNT043 IN NNOGR 3.2
END DESCRIPTION:
XS GIS Cut Line= 3
      2776786.67     10081694.19      2776702.05     10081442.94
      2776218.95     10081407.78
#Sta/Elev= 30
  4666.6 1652.12    4706  1651.5  4711.3 1651.65  4737.5  1651.2  4742.8 1651.36
  4825.4  1650.3  4888.7 1650.28  4929.5 1649.39  4945.3 1649.47  4975.4 1649.02
  5002.5  1648.9  5005.2  1648.4  5008.5  1648.9  5035.6 1649.76  5065.7 1649.88
  5075.7  1650.1  5105.8 1651.19  5124.1 1651.46  5129.1 1651.21  5135.8 1652.18
  5145.9    1654  5155.9 1654.41  5165.9  1654.6    5186 1654.39    5196 1653.83
  5216.1 1654.98  5226.1 1655.23  5246.1 1655.25  5286.2 1655.97  5416.1 1659.42
#Mann= 3 ,-1 , 0
  4666.6     .05       0  5002.5    .035       0  5008.5     .05       0
Bank Sta=5002.5,5008.5
XS Rating Curve= 0 ,0
Exp/Cntr=0.3,0.1

Type RM Length L Ch R = 1 ,1275    ,119,119,119
BEGIN DESCRIPTION:
UNT044 IN NNOGR 1.52
END DESCRIPTION:
XS GIS Cut Line= 3
       2776988.4     10081426.87      2776495.75     10081189.23
      2776333.25     10081192.48
#Sta/Elev= 30
    4572 1650.66  4657.5 1650.24  4738.5 1648.84  4805.1 1648.25  4821.3 1648.33
  4827.3 1648.56  4838.4 1648.65  4860.6 1648.46  4882.8 1648.01  4894.7 1647.94
  4911.8 1648.24  4939.9 1648.06    4957 1648.16  5004.7 1647.56  5007.5 1647.06
  5010.7 1647.56  5024.8 1648.09  5030.4 1647.96  5047.4 1648.66    5053 1648.59
    5070 1649.22  5075.6 1649.19  5092.6 1649.77  5098.2 1649.78  5146.3 1651.08
  5196.3 1652.84  5226.3 1654.28  5246.3 1654.53  5266.3 1657.07  5281.5 1657.55
#Mann= 3 ,-1 , 0
    4572     .05       0  5004.7    .035       0  5010.7     .05       0
Bank Sta=5004.7,5010.7
XS Rating Curve= 0 ,0
Exp/Cntr=0.3,0.1

Type RM Length L Ch R = 1 ,1156    ,145,145,145
BEGIN DESCRIPTION:
UNT044 IN NNOGR 1.47
END DESCRIPTION:
XS GIS Cut Line= 3
      2777007.88     10081346.54      2776585.81     10081096.99
      2776272.32     10081104.56
#Sta/Elev= 30
  4617.6 1650.42  4649.3 1650.44  4663.4  1650.2  4692.2 1650.16  4772.1 1648.86
  4787.7 1648.24  4802.8 1648.02  4895.7  1647.6  4947.7 1646.62    4977 1646.48
  4990.5    1646  4997.3 1645.97    5000 1645.47  5003.3 1645.97  5043.2 1647.17
  5049.1 1646.99  5064.7 1647.36  5086.1 1647.42  5101.8 1647.91  5155.3 1648.98
  5175.1 1649.65  5180.1 1649.52  5185.3 1649.84  5255.3  1651.8  5315.3 1654.08
  5355.3 1656.25  5375.3 1656.47  5395.3 1659.07  5405.4 1659.49  5421.5 1659.57
#Mann= 3 ,-1 , 0
  4617.6     .05       0  4997.3    .035       0  5003.3     .05       0
Bank Sta=4997.3,5003.3
XS Rating Curve= 0 ,0
Exp/Cntr=0.3,0.1

Type RM Length L Ch R = 1 ,1011    ,129,129,129
BEGIN DESCRIPTION:
UNT044 IN NNOGR 1.51
END DESCRIPTION:
XS GIS Cut Line= 3
      2776951.49     10081194.66      2776791.98     10081027.55
      2776257.06      10080965.7
#Sta/Elev= 30
  4664.9 1649.41  4681.7 1649.46  4773.9 1648.71  4837.4 1647.75  4858.8 1648.01
  4865.7 1647.71  4900.2 1647.45  4939.7 1646.46    4980 1644.57  4997.1 1644.41
  4999.9 1643.91  5003.1 1644.41  5010.2 1644.45  5057.6  1646.5  5070.6 1646.86
  5100.8 1647.38  5141.1 1648.31  5146.5  1648.6  5151.5 1648.53  5181.3  1649.5
  5230.3 1650.56  5235.3 1650.52  5271.9    1652  5319.1  1654.6  5324.1 1654.55
  5362.5 1656.56  5382.7 1657.15  5402.8 1658.29  5407.9  1658.8  5434.4 1659.76
#Mann= 3 ,-1 , 0
  4664.9     .05       0  4997.1    .035       0  5003.1     .05       0
Bank Sta=4997.1,5003.1
XS Rating Curve= 0 ,0
Exp/Cntr=0.3,0.1

Type RM Length L Ch R = 1 ,882     ,158,158,158
BEGIN DESCRIPTION:
UNT044 IN NNOGR 1.48
END DESCRIPTION:
XS GIS Cut Line= 3
      2776899.39     10081120.85      2776742.55     10080898.41
      2776187.58     10080852.85
#Sta/Elev= 30
  4643.4 1648.86  4706.4 1648.34    4736 1648.46  4828.4    1648  4843.2 1648.08
  4849.3 1647.87  4899.8 1647.77  4914.6 1647.39  4929.7 1647.49  4949.8  1646.5
  4989.9 1643.56  4996.9 1642.16  4999.7 1641.66  5002.9 1642.16  5029.5 1644.83
  5034.5 1644.76  5040.1 1645.84  5060.1 1646.89  5120.3 1648.62  5140.4 1649.38
  5155.8 1649.72  5160.8 1649.61  5210.6 1651.56    5321 1655.48  5391.2 1658.69
  5398.4 1659.36  5421.3 1660.31  5461.5 1662.34  5469.4 1662.92  5472.4 1662.92
#Mann= 3 ,-1 , 0
  4643.4     .05       0  4996.9    .035       0  5002.9     .05       0
Bank Sta=4996.9,5002.9
XS Rating Curve= 0 ,0
Exp/Cntr=0.3,0.1

Type RM Length L Ch R = 1 ,724     ,202,202,202
BEGIN DESCRIPTION:
UNT044 IN NNOGR 1.49
END DESCRIPTION:
XS GIS Cut Line= 3
      2776878.78     10081086.13       2776783.3     10080744.35
      2776174.61     10080694.44
#Sta/Elev= 30
  4544.1 1648.59  4670.7 1648.19    4710  1647.5  4788.7 1646.97  4816.5 1646.45
  4828.1 1646.53  4913.9 1645.45  4923.9  1644.5    4944 1641.14  4968.4 1638.19
  5001.2 1637.67  5003.9 1637.17  5007.2 1637.67  5024.2  1638.9  5054.3 1641.75
  5089.7 1645.92  5094.8 1645.81  5134.6 1647.29  5164.7 1647.99  5204.8 1649.37
  5305.2 1654.19  5355.3 1655.92  5405.5 1658.99  5425.6 1659.94  5453.9 1661.94
  5458.9 1661.65  5465.7 1662.86  5495.8 1664.42  5505.3 1665.21  5509.7 1665.21
#Mann= 3 ,-1 , 0
  4544.1     .05       0  5001.2    .035       0  5007.2     .05       0
Bank Sta=5001.2,5007.2
XS Rating Curve= 0 ,0
Exp/Cntr=0.3,0.1

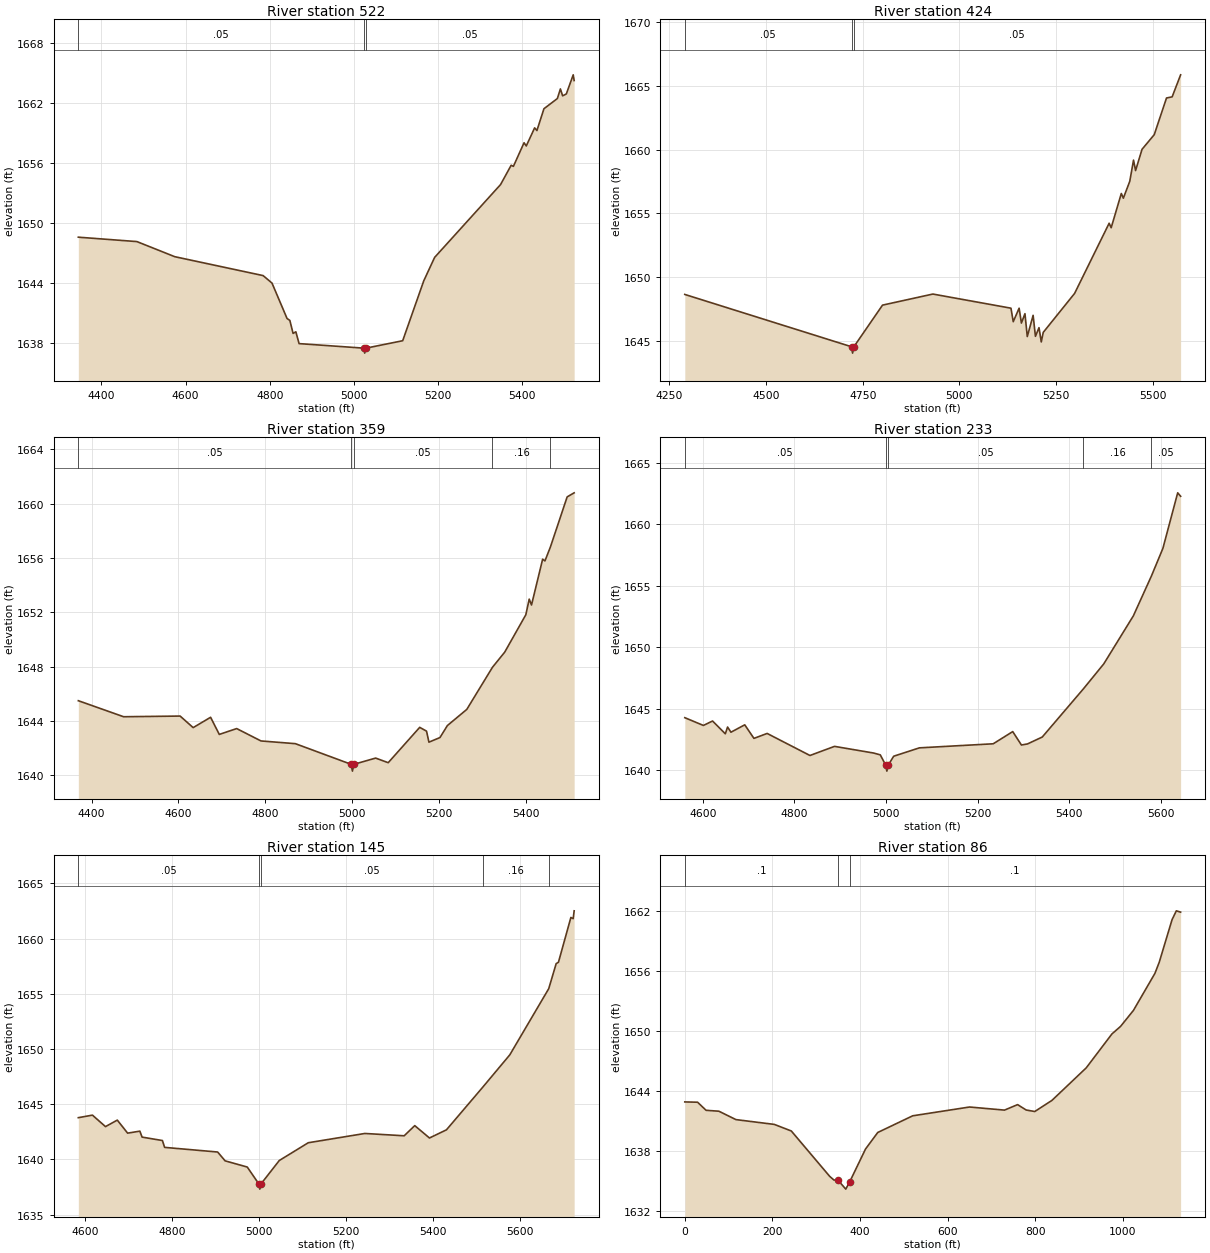
Type RM Length L Ch R = 1 ,522     ,98,98,98
BEGIN DESCRIPTION:
UNT044 IN NNOGR 1.46
END DESCRIPTION:
XS GIS Cut Line= 5
      2776882.04     10081082.91      2776882.04     10080628.24
      2776780.04     10080540.35      2776521.79     10080536.01
        2776211.     10080649.33
#Sta/Elev= 30
  4345.2 1648.59  4484.4 1648.15  4574.4 1646.64  4784.4 1644.75  4805.5    1644
  4841.3 1640.46  4847.9 1640.27  4855.6 1638.97  4862.2 1639.13  4869.9 1637.95
  5023.1  1637.5  5025.8    1637  5029.1  1637.5  5116.1 1638.24  5166.1 1644.22
    5192 1646.57  5348.7 1653.85  5373.9 1655.78  5379.2 1655.67  5404.5 1658.03
  5409.8 1657.71  5429.7 1659.52  5435.1 1659.25  5451.8 1661.43  5483.7 1662.45
  5490.9 1663.41  5496.2 1662.72    5505 1662.91  5521.4 1664.82  5523.6 1664.25
#Mann= 3 ,-1 , 0
  4345.2     .05       0  5023.1    .035       0  5029.1     .05       0
Bank Sta=5023.1,5029.1
XS Rating Curve= 0 ,0
Exp/Cntr=0.3,0.1

Type RM Length L Ch R = 1 ,424     ,65,65,65
BEGIN DESCRIPTION:
UNT044 IN NNOGR 1.41
END DESCRIPTION:
XS GIS Cut Line= 6
      2776896.14     10081067.72       2776913.5     10080601.12
      2776807.17     10080477.42      2776642.24     10080445.95
      2776536.99     10080514.31      2776203.83     10080626.09
#Sta/Elev= 30
  4289.8 1648.63  4721.1 1644.52  4723.8 1644.02  4727.1 1644.52  4801.2 1647.79
  4931.4 1648.66  5133.4 1647.55  5139.3 1646.49  5154.5 1647.55  5160.4 1646.38
  5169.6 1647.12  5175.6 1645.32  5190.7 1646.99  5196.7 1645.34  5205.9 1646.02
  5211.8  1644.9  5216.9 1645.65    5298 1648.71  5387.3 1654.22  5392.6 1653.87
  5418.8 1656.56  5424.1 1656.19  5440.7 1657.52  5450.4 1659.18  5455.7 1658.36
  5472.4 1660.03    5504 1661.18  5535.7 1664.06  5550.3 1664.15  5572.2 1665.88
#Mann= 3 ,-1 , 0
  4289.8     .05       0  4721.1    .035       0  4727.1     .05       0
Bank Sta=4721.1,4727.1
XS Rating Curve= 0 ,0
Exp/Cntr=0.3,0.1

Type RM Length L Ch R = 1 ,359     ,126,126,126
BEGIN DESCRIPTION:
UNT044 IN NNOGR 1.42
END DESCRIPTION:
XS GIS Cut Line= 4
      2776953.65     10080917.95      2776960.16     10080496.95
      2776648.75     10080329.85      2776303.65     10080452.48
#Sta/Elev= 30
  4369.6  1645.5  4473.8 1644.32  4603.8 1644.37  4633.8 1643.52  4673.9 1644.28
  4693.9 1643.02  4733.9 1643.45  4789.8 1642.54  4868.9 1642.34  4997.4 1640.82
  5000.2 1640.32  5003.4 1640.82  5053.6 1641.28  5082.5 1640.94    5155 1643.54
  5170.7 1643.26  5176.2 1642.45  5201.6 1642.79  5218.6 1643.67  5263.3 1644.86
  5322.4 1647.96  5350.5 1649.07  5399.1 1651.82  5406.9 1652.97  5412.2 1652.54
  5437.8 1655.91  5443.1 1655.78  5455.6  1656.8  5494.2 1660.49  5510.3 1660.79
#Mann= 5 ,-1 , 0
  4369.6     .05       0  4997.4    .035       0  5003.4     .05       0
  5322.4     .16       0  5455.6     .05       0
Bank Sta=4997.4,5003.4
XS Rating Curve= 0 ,0
Exp/Cntr=0.3,0.1

Type RM Length L Ch R = 1 ,233     ,88,88,88
BEGIN DESCRIPTION:
UNT044 IN NNOGR 1.45
END DESCRIPTION:
XS GIS Cut Line= 6
       2776964.5     10080744.38      2776963.42     10080648.86
      2776984.03     10080469.82      2776831.04     10080265.83
       2776659.6      10080275.6      2776297.16     10080390.62
#Sta/Elev= 30
  4560.7 1644.28  4601.3 1643.65  4621.3 1644.01  4649.2 1642.97  4654.1 1643.52
  4661.5  1643.1  4691.6  1643.7  4711.7  1642.6  4740.5    1643    4834 1641.21
  4887.6 1641.95    4973 1641.41  4987.6 1641.26  4999.2 1640.44  5001.9 1639.94
  5005.2 1640.44  5016.8 1641.15    5073 1641.83  5234.2 1642.16  5276.8 1643.15
  5295.8 1642.06  5309.1 1642.15  5341.3 1642.71  5431.1 1646.62  5475.6 1648.65
  5540.2 1652.55  5579.7 1655.79  5604.7 1658.03    5637 1662.54  5643.4 1662.26
#Mann= 5 ,-1 , 0
  4560.7     .05       0  4999.2    .035       0  5005.2     .05       0
  5431.1     .16       0  5579.7     .05       0
Bank Sta=4999.2,5005.2
XS Rating Curve= 0 ,0
Exp/Cntr=0.3,0.1

Type RM Length L Ch R = 1 ,145     ,59,59,59
BEGIN DESCRIPTION:
UNT044 IN NNOGR 1.44
END DESCRIPTION:
XS GIS Cut Line= 6
      2776968.84     10080716.16      2776969.93     10080643.44
       2777015.5     10080407.98      2776940.63     10080251.73
      2776661.77     10080266.92      2776302.49     10080369.72
#Sta/Elev= 30
  4584.7 1643.78  4617.1 1644.01  4647.1 1642.97  4674.2 1643.56  4697.9 1642.38
    4726 1642.56  4731.1 1642.02  4777.8 1641.71  4782.9 1641.09  4904.7 1640.67
  4921.9 1639.87  4972.7 1639.31  4998.8 1637.81  5001.5 1637.31  5004.8 1637.81
  5046.2  1639.9  5112.8 1641.51  5242.9 1642.35  5333.1 1642.14  5357.4 1643.06
  5391.2 1641.94  5430.2 1642.68  5514.2 1646.57  5575.7 1649.47  5665.1 1655.46
  5682.2 1657.73  5687.4 1657.85    5716 1661.91  5721.2  1661.8  5723.5 1662.51
#Mann= 5 ,-1 , 0
  4584.7     .05       0  4998.8    .035       0  5004.8     .05       0
  5514.2     .16       0  5665.1     .05       0
Bank Sta=4998.8,5004.8
XS Rating Curve= 0 ,0
Exp/Cntr=0.3,0.1

Type RM Length L Ch R = 1 ,86      ,18,18,18
XS GIS Cut Line= 5
     2776972.448    10080645.753     2777041.892    10080310.467
     2776985.469    10080245.363     2776657.778    10080261.639
     2776299.705     10080360.38
#Sta/Elev= 30
       0 1642.93   29.19  1642.9   48.64 1642.09   77.83    1642  116.74 1641.16
   204.3 1640.68  243.21 1640.02  330.77 1635.48   340.5 1635.11   349.5 1635.11
  367.51  1634.2  376.51 1634.93  412.53 1638.21  440.51 1639.87  520.33 1641.54
  650.02 1642.42  729.84 1642.11  759.77 1642.66  779.36 1642.12  798.95 1641.97
  838.13 1643.08  916.48 1646.34  975.25 1649.74  994.84 1650.49 1024.23 1652.09
  1073.2 1655.79 1082.99 1656.89 1112.38 1661.17 1122.17 1662.06 1131.97 1661.93
#Mann= 3 , 0 , 0
       0      .1       0   349.5     .05       0  376.51      .1       0
Bank Sta=349.5,376.51
XS Rating Curve= 0 ,0
Exp/Cntr=0.3,0.1

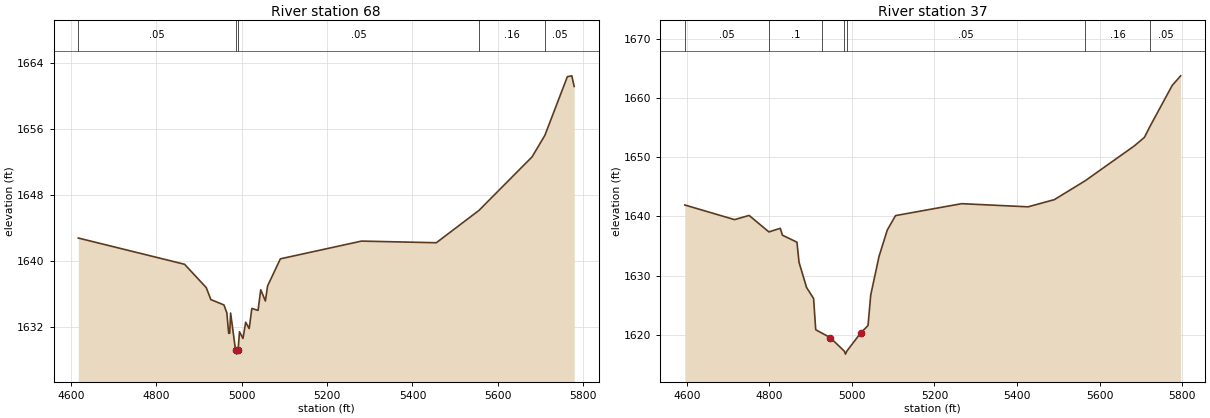
Type RM Length L Ch R = 1 ,68      ,31,31,31
BEGIN DESCRIPTION:
UNT044 IN NNOGR 1.43
END DESCRIPTION:
XS GIS Cut Line= 5
      2776976.44     10080646.67      2777054.56     10080300.55
      2777003.57     10080234.36      2776663.94      10080253.9
      2776293.13     10080351.48
#Sta/Elev= 30
  4616.9 1642.73  4865.9 1639.55  4916.7 1636.72  4927.5 1635.27  4958.2 1634.62
    4965 1633.64  4969.2 1631.19  4971.7 1631.19  4973.8 1633.64  4985.3 1629.16
    4988 1628.66  4991.3 1629.16  4994.6 1631.37  5002.8 1630.56  5009.1 1632.53
  5017.3 1631.76  5023.6  1634.2  5038.1 1633.96  5044.4 1636.46  5055.3  1635.1
  5060.4 1636.92  5090.4 1640.21  5280.7 1642.36  5455.9 1642.16  5555.8 1646.08
  5680.3 1652.57  5710.3 1655.18    5763 1662.29  5773.4 1662.39  5778.9  1661.1
#Mann= 5 ,-1 , 0
  4616.9     .05       0  4985.3    .035       0  4991.3     .05       0
  5555.8     .16       0  5710.3     .05       0
Bank Sta=4985.3,4991.3
XS Rating Curve= 0 ,0
Exp/Cntr=0.3,0.1

Type RM Length L Ch R = 1 ,37      ,0,0,0
BEGIN DESCRIPTION:
UNT044 IN NNOGR 1.4
END DESCRIPTION:
XS GIS Cut Line= 5
      2776993.81     10080639.06      2777083.86     10080296.21
      2777035.03     10080221.34      2776680.21     10080237.62
      2776288.53     10080328.76
#Sta/Elev= 30
  4595.2 1641.94  4715.8 1639.47    4751 1640.18    4799  1637.4  4826.5 1638.01
  4831.7 1636.85  4866.9 1635.67    4872 1632.27  4890.2 1628.04  4907.2 1626.18
  4912.4 1620.91  4947.6 1619.58  4981.7  1617.3  4984.5  1616.8  4987.7  1617.3
    5021 1620.35  5039.1 1621.62  5045.6 1626.75  5065.7 1633.26  5085.7 1637.71
  5105.7 1640.15  5265.9 1642.16  5426.8 1641.63  5490.5 1642.84  5564.5 1645.99
  5683.5 1651.86  5708.6 1653.33  5722.6 1655.24  5775.9 1662.08  5796.4 1663.71
#Mann= 7 ,-1 , 0
  4595.2     .05       0    4799      .1       0  4927.1     .05       0
  4981.7    .035       0  4987.7     .05       0  5564.5     .16       0
  5722.6     .05       0
Bank Sta=4947.6,5021
XS Rating Curve= 0 ,0
Exp/Cntr=0.3,0.1

Chan Stop Cuts=-1
Use User Specified Reach Order=0
Composite Channel Slope=5