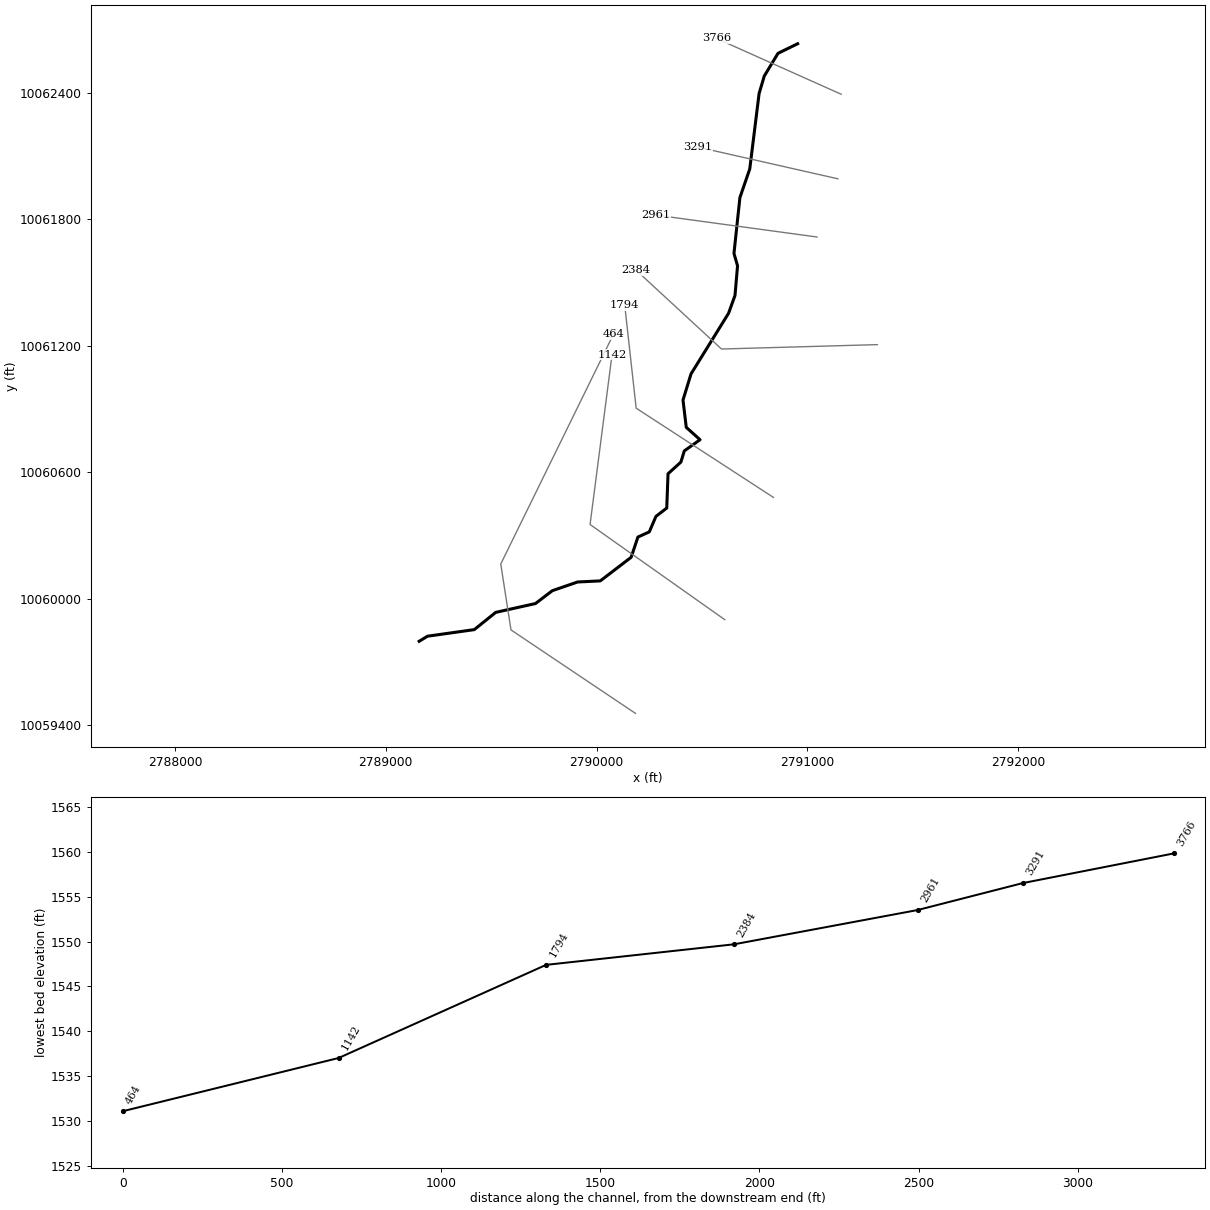
--- UNT998 IN NNOGR.prj (project) ---

Proj Title=UNT998 IN NNOGR Base Level Engineering
Current Plan=p01
Default Exp/Contr=0.3,0.1
English Units
Geom File=g01
Flow File=f01
Plan File=p01
Y Axis Title=Elevation
X Axis Title(PF)=Main Channel Distance
X Axis Title(XS)=Station
BEGIN DESCRIPTION:
UNT998 IN NNOGR
END DESCRIPTION:
DSS Export Rating Curves= 0
DSS Export Rating Curve Sorted= 0
DSS Export Volume Flow Curves= 0
DXF OffsetX= 0
DXF OffsetY= 0
DXF ScaleX= 1
DXF ScaleY= 10

--- UNT998 IN NNOGR.p01 (plan) ---

Plan Title=Multiple Run
Short Identifier=Multiple
Geom File=g01
Flow File=f01
Subcritical Flow
K Sum by GR= 0
Std Step Tol= 0.01
Critical Tol= 0.01
Num of Std Step Trials= 20
Max Error Tol= 0.3
Flow Tol Ratio= 0.001
Split Flow NTrial= 30
Split Flow Tol= 0.02
Split Flow Ratio= 0.02
Log Output Level= 0
Friction Slope Method= 1
Unsteady Friction Slope Method= 2
Unsteady Bridges Friction Slope Method= 1
Parabolic Critical Depth
Global Vel Dist=  1 , 1 , 1
Global Log Level= 0
CheckData=True
Encroach Param= -1, 0, 0, 0
BEGIN DESCRIPTION:
Multiple Run
END DESCRIPTION:

--- UNT998 IN NNOGR.f01 (steady flow) ---

Flow Title=Multiple
Program Version=4.10
Number of Profiles= 7
Profile Names=10-year,25-year,50-year,1pct_min,100-year,1pct_plu,500-year
River Rch & RM=UNT998 IN NNOGR,Reach-1         ,3766
     346     467     565     500     677     915     974
Boundary for River Rch & Prof#=UNT998 IN NNOGR,Reach-1         , 1
Up Type= 0
Dn Type= 3
Dn Slope=0.0125
Boundary for River Rch & Prof#=UNT998 IN NNOGR,Reach-1         , 2
Up Type= 0
Dn Type= 3
Dn Slope=0.0125
Boundary for River Rch & Prof#=UNT998 IN NNOGR,Reach-1         , 3
Up Type= 0
Dn Type= 3
Dn Slope=0.0125
Boundary for River Rch & Prof#=UNT998 IN NNOGR,Reach-1         , 4
Up Type= 0
Dn Type= 3
Dn Slope=0.0125
Boundary for River Rch & Prof#=UNT998 IN NNOGR,Reach-1         , 5
Up Type= 0
Dn Type= 3
Dn Slope=0.0125
Boundary for River Rch & Prof#=UNT998 IN NNOGR,Reach-1         , 6
Up Type= 0
Dn Type= 3
Dn Slope=0.0125
Boundary for River Rch & Prof#=UNT998 IN NNOGR,Reach-1         , 7
Up Type= 0
Dn Type= 3
Dn Slope=0.0125
DSS Import GetInterval= 0
DSS Import GetPeak= 0
DSS Import FillOption= 0

--- UNT998 IN NNOGR.g01 (geometry) ---

Geom Title=Existing Conditions
Program Version=4.10

River Reach=UNT998 IN NNOGR ,Reach-1
Reach XY= 30
      2790953.68      10062633.5      2790860.44     10062587.99
      2790795.33     10062480.17      2790770.86     10062397.73
      2790726.48     10062039.47      2790679.77     10061903.83
      2790651.59     10061638.96      2790668.58     10061580.18
      2790656.49     10061439.55      2790625.83     10061354.82
      2790448.01     10061067.66      2790409.89     10060943.55
      2790425.36     10060814.05      2790490.68     10060755.38
      2790416.04     10060702.35      2790399.89     10060649.25
      2790338.85     10060593.93      2790332.79      10060431.3
      2790281.52     10060391.64      2790249.97     10060318.26
      2790196.06     10060293.84      2790163.94      10060197.7
      2790017.62     10060085.83      2789909.86     10060080.57
      2789790.03     10060039.28      2789710.31     10059978.37
      2789521.73     10059936.49      2789419.95     10059854.68
      2789198.08     10059823.42      2789158.43      10059799.3

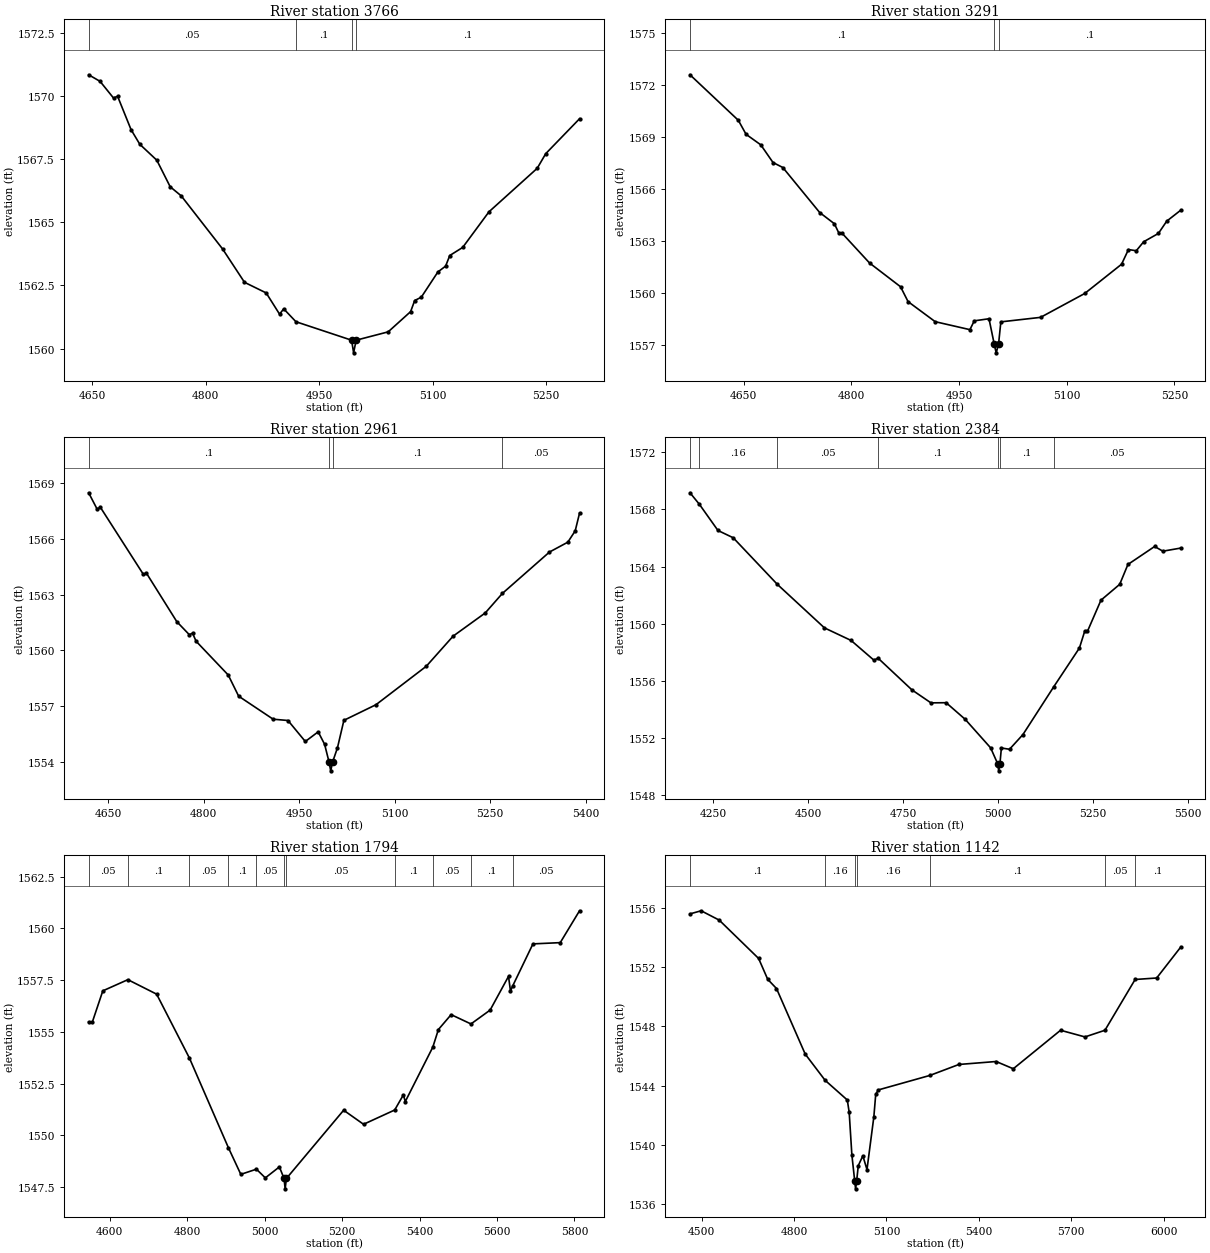
Type RM Length L Ch R = 1 ,3766    ,475,475,475
BEGIN DESCRIPTION:
UNT998 IN NNOGR 7.0
END DESCRIPTION:
XS GIS Cut Line= 2
      2791160.24     10062393.88      2790567.37     10062659.11
#Sta/Elev= 30
    4645 1570.83  4660.1 1570.57  4677.9 1569.91  4683.3 1569.98  4701.1 1568.66
  4712.7 1568.08  4735.2 1567.45  4752.9  1566.4  4767.5 1566.04  4822.2 1563.94
  4851.2 1562.62  4879.9  1562.2  4897.6 1561.36  4903.1 1561.57  4919.3 1561.06
  4992.9 1560.33  4995.6 1559.83  4998.9 1560.33  5041.3 1560.66    5071 1561.46
  5076.4  1561.9  5085.1 1562.03  5107.1 1563.03  5117.3 1563.26  5122.8 1563.68
  5139.9    1564  5174.7 1565.41  5238.5 1567.13  5249.8 1567.71  5294.5 1569.09
#Mann= 4 ,-1 , 0
    4645     .05       0  4919.3      .1       0  4992.9     .07       0
  4998.9      .1       0
Bank Sta=4992.9,4998.9
XS Rating Curve= 0 ,0
Exp/Cntr=0.3,0.1

Type RM Length L Ch R = 1 ,3291    ,330,330,330
BEGIN DESCRIPTION:
UNT998 IN NNOGR 6.0
END DESCRIPTION:
XS GIS Cut Line= 2
      2791144.61     10061992.84      2790477.91     10062143.89
#Sta/Elev= 30
  4575.4 1572.59  4642.7 1569.96  4653.5 1569.15    4674 1568.54    4691 1567.52
  4704.7 1567.23    4756 1564.63  4776.5 1563.98  4782.4 1563.47  4787.5 1563.42
  4825.5 1561.71  4868.6 1560.34  4879.1 1559.48  4916.9 1558.32  4965.2 1557.86
  4971.3 1558.37  4991.8 1558.49  4999.1 1557.02  5001.8 1556.52  5005.1 1557.02
  5008.3 1558.31  5063.6 1558.57  5125.1 1559.95  5176.4 1561.64    5186 1562.49
  5196.9 1562.42  5207.2 1562.94  5227.7 1563.42  5239.3 1564.13    5259 1564.77
#Mann= 3 ,-1 , 0
  4575.4      .1       0  4999.1     .07       0  5005.1      .1       0
Bank Sta=4999.1,5005.1
XS Rating Curve= 0 ,0
Exp/Cntr=0.3,0.1

Type RM Length L Ch R = 1 ,2961    ,577,577,577
BEGIN DESCRIPTION:
UNT998 IN NNOGR 5.0
END DESCRIPTION:
XS GIS Cut Line= 2
      2791045.67      10061716.8      2790281.71     10061820.74
#Sta/Elev= 30
  4619.4 1568.49  4632.7 1567.61  4637.8 1567.71  4705.1 1564.11  4710.2 1564.16
  4757.9 1561.55  4777.5 1560.85  4782.6 1560.93  4788.1  1560.5  4838.6 1558.68
    4855 1557.54  4909.2  1556.3  4932.5 1556.23  4959.7  1555.1  4979.9 1555.62
    4990 1554.95  4996.8 1554.02  4999.6 1553.52  5002.8 1554.02  5010.2 1554.76
  5020.3 1556.24  5070.7 1557.08  5149.7 1559.15  5191.8 1560.77  5242.3 1562.02
  5269.2 1563.07  5343.2  1565.3    5372 1565.83  5383.6 1566.44  5390.4 1567.39
#Mann= 4 ,-1 , 0
  4619.4      .1       0  4996.8     .07       0  5002.8      .1       0
  5269.2     .05       0
Bank Sta=4996.8,5002.8
XS Rating Curve= 0 ,0
Exp/Cntr=0.3,0.1

Type RM Length L Ch R = 1 ,2384    ,590,590,590
BEGIN DESCRIPTION:
UNT998 IN NNOGR 4.0
END DESCRIPTION:
XS GIS Cut Line= 3
      2791332.07     10061206.39       2790592.5     10061185.56
      2790187.23     10061559.65
#Sta/Elev= 30
  4189.1 1569.17  4213.9 1568.36  4262.7 1566.53  4302.8 1566.02  4418.8 1562.76
  4542.8 1559.71  4612.9 1558.83  4672.9 1557.45  4683.9 1557.59  4772.9 1555.37
    4823 1554.46    4863 1554.47    4913 1553.31    4980 1551.31  4998.5  1550.2
  5001.3  1549.7  5004.5  1550.2  5008.3  1551.3  5029.7 1551.21    5065 1552.24
  5146.4  1555.6  5213.6  1558.3  5227.8  1559.5  5234.6 1559.46  5270.3 1561.65
  5319.6 1562.76  5341.2 1564.15  5411.5 1565.41  5433.1 1565.08  5480.5  1565.3
#Mann= 7 ,-1 , 0
  4189.1      .1       0  4213.9     .16       0  4418.8     .05       0
  4683.9      .1       0  4998.5     .07       0  5004.5      .1       0
  5146.4     .05       0
Bank Sta=4998.5,5004.5
XS Rating Curve= 0 ,0
Exp/Cntr=0.3,0.1

Type RM Length L Ch R = 1 ,1794    ,652,652,652
BEGIN DESCRIPTION:
Mapping XS ee6ab181
END DESCRIPTION:
XS GIS Cut Line= 3
      2790838.77     10060481.77      2790187.73     10060904.95
      2790133.47     10061393.26
#Sta/Elev= 30
  4545.2 1555.48  4554.7 1555.47  4581.8 1556.98  4646.5 1557.52  4720.8 1556.82
  4805.5 1553.73  4906.1  1549.4  4938.2 1548.11  4978.5 1548.36  5001.5 1547.94
  5037.8 1548.47  5049.9 1547.91  5052.7 1547.41  5055.9 1547.91  5203.8 1551.21
  5255.2 1550.53  5335.6 1551.22    5358 1551.95    5363 1551.63  5434.1 1554.26
  5448.5 1555.11  5481.4 1555.83  5532.6 1555.38  5582.1 1556.05  5629.6 1557.68
  5634.7 1556.97  5640.7 1557.23  5692.7 1559.25  5763.2 1559.31    5813 1560.85
#Mann= 11 ,-1 , 0
  4545.2     .05       0  4646.5      .1       0  4805.5     .05       0
  4906.1      .1       0  4978.5     .05       0  5049.9     .04       0
  5055.9     .05       0  5335.6      .1       0  5434.1     .05       0
  5532.6      .1       0  5640.7     .05       0
Bank Sta=5049.9,5055.9
XS Rating Curve= 0 ,0
Exp/Cntr=0.3,0.1

Type RM Length L Ch R = 1 ,1142    ,678,678,678
BEGIN DESCRIPTION:
UNT998 IN NNOGR 3.0
END DESCRIPTION:
XS GIS Cut Line= 3
      2790607.99     10059901.87       2789969.1     10060353.27
      2790073.26     10061158.79
#Sta/Elev= 30
  4461.7  1555.6  4497.9 1555.81  4556.6 1555.18  4684.6 1552.59  4714.2 1551.18
  4742.7 1550.56    4836 1546.13  4900.6 1544.36  4972.7 1543.03  4978.8  1542.2
  4987.5 1539.33  4996.9 1537.53  4999.6 1537.03  5002.9 1537.53  5008.4  1538.6
  5023.2 1539.26  5036.6 1538.33  5058.9 1541.89    5065 1543.41  5073.3 1543.71
    5241 1544.69  5335.2 1545.43  5456.2 1545.63  5511.8 1545.14  5665.4 1547.74
  5744.7 1547.29  5809.6 1547.74  5907.6 1551.17  5977.6 1551.27  6056.2 1553.37
#Mann= 7 ,-1 , 0
  4461.7      .1       0  4900.6     .16       0  4996.9     .07       0
  5002.9     .16       0    5241      .1       0  5809.6     .05       0
  5907.6      .1       0
Bank Sta=4996.9,5002.9
XS Rating Curve= 0 ,0
Exp/Cntr=0.3,0.1

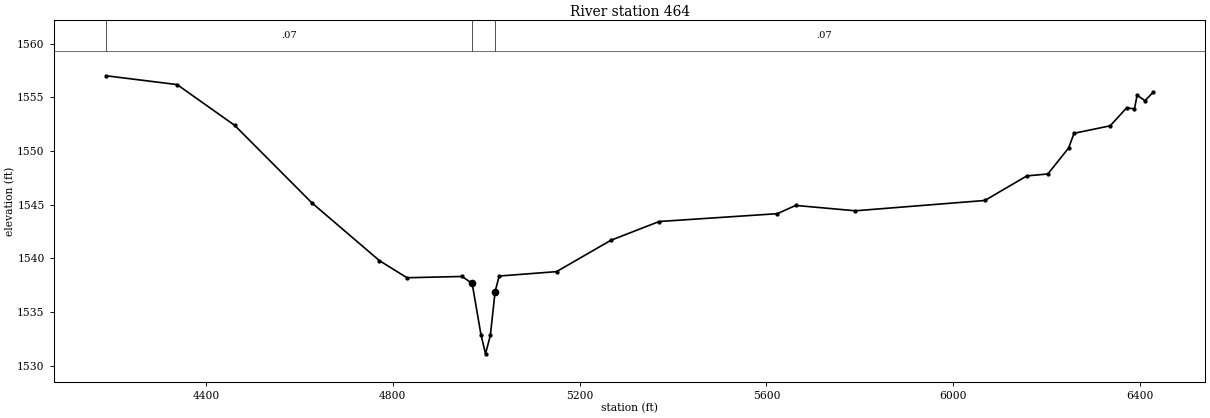
Type RM Length L Ch R = 1 ,464     ,0,0,0
BEGIN DESCRIPTION:
UNT998 IN NNOGR 1.0
END DESCRIPTION:
XS GIS Cut Line= 4
      2790184.38     10059457.43       2789594.1     10059853.27
      2789545.49     10060165.77       2790080.2     10061256.02
#Sta/Elev= 30
  4186.5 1557.01  4338.3 1556.19  4461.3  1552.4  4627.1 1545.16  4771.6 1539.78
  4830.5 1538.19  4948.3 1538.31    4970 1537.66  4988.8  1532.9  4998.6  1531.1
    5009 1532.83  5019.1 1536.89  5027.8 1538.35  5150.7 1538.76  5266.9 1541.68
  5370.3 1543.43  5623.3 1544.16  5662.7 1544.93  5790.4 1544.43  6067.6 1545.39
  6157.5 1547.68  6202.5 1547.86    6247 1550.28  6258.6 1551.65  6336.1 1552.35
  6371.1 1554.02    6388 1553.93  6393.6  1555.2  6410.5 1554.69  6427.8 1555.47
#Mann= 3 , 0 , 0
  4186.5     .07       0    4970     .03       0  5019.1     .07       0
Bank Sta=4970,5019.1
XS Rating Curve= 0 ,0
Exp/Cntr=0.3,0.1

Chan Stop Cuts=-1
Use User Specified Reach Order=0
Composite Channel Slope=5