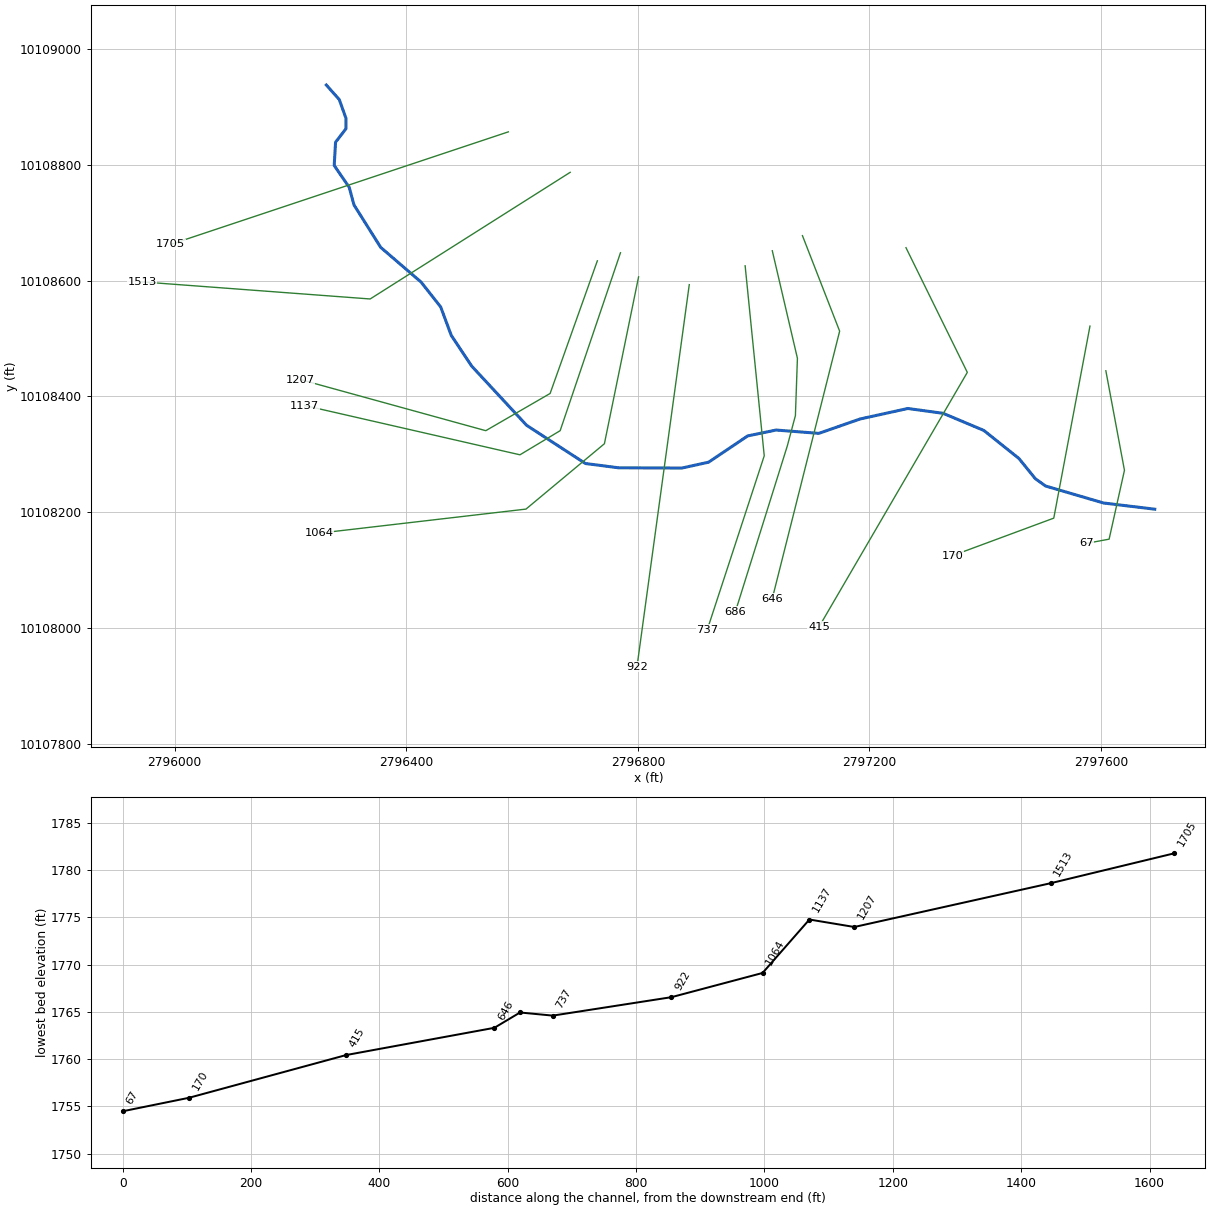
--- UNT999 IN NNOGR.prj (project) ---

Proj Title=UNT999 IN NNOGR Base Level Engineering
Current Plan=p01
Default Exp/Contr=0.3,0.1
English Units
Geom File=g01
Flow File=f01
Plan File=p01
Y Axis Title=Elevation
X Axis Title(PF)=Main Channel Distance
X Axis Title(XS)=Station
BEGIN DESCRIPTION:
UNT999 IN NNOGR
END DESCRIPTION:
DSS Export Rating Curves= 0
DSS Export Rating Curve Sorted= 0
DSS Export Volume Flow Curves= 0
DXF OffsetX= 0
DXF OffsetY= 0
DXF ScaleX= 1
DXF ScaleY= 10

--- UNT999 IN NNOGR.p01 (plan) ---

Plan Title=Multiple Run
Short Identifier=Multiple
Geom File=g01
Flow File=f01
Subcritical Flow
K Sum by GR= 0
Std Step Tol= 0.01
Critical Tol= 0.01
Num of Std Step Trials= 20
Max Error Tol= 0.3
Flow Tol Ratio= 0.001
Split Flow NTrial= 30
Split Flow Tol= 0.02
Split Flow Ratio= 0.02
Log Output Level= 0
Friction Slope Method= 1
Unsteady Friction Slope Method= 2
Unsteady Bridges Friction Slope Method= 1
Parabolic Critical Depth
Global Vel Dist=  1 , 1 , 1
Global Log Level= 0
CheckData=True
Encroach Param= -1, 0, 0, 0
BEGIN DESCRIPTION:
Multiple Run
END DESCRIPTION:

--- UNT999 IN NNOGR.f01 (steady flow) ---

Flow Title=Multiple
Program Version=4.10
Number of Profiles= 7
Profile Names=10-year,25-year,50-year,1pct_min,100-year,1pct_plu,500-year
River Rch & RM=UNT999 IN NNOGR,Reach-1         ,1705
     123     155     180     153     207     281     276
Boundary for River Rch & Prof#=UNT999 IN NNOGR,Reach-1         , 1
Up Type= 0
Dn Type= 3
Dn Slope=0.0155
Boundary for River Rch & Prof#=UNT999 IN NNOGR,Reach-1         , 2
Up Type= 0
Dn Type= 3
Dn Slope=0.0155
Boundary for River Rch & Prof#=UNT999 IN NNOGR,Reach-1         , 3
Up Type= 0
Dn Type= 3
Dn Slope=0.0155
Boundary for River Rch & Prof#=UNT999 IN NNOGR,Reach-1         , 4
Up Type= 0
Dn Type= 3
Dn Slope=0.0155
Boundary for River Rch & Prof#=UNT999 IN NNOGR,Reach-1         , 5
Up Type= 0
Dn Type= 3
Dn Slope=0.0155
Boundary for River Rch & Prof#=UNT999 IN NNOGR,Reach-1         , 6
Up Type= 0
Dn Type= 3
Dn Slope=0.0155
Boundary for River Rch & Prof#=UNT999 IN NNOGR,Reach-1         , 7
Up Type= 0
Dn Type= 3
Dn Slope=0.0155
DSS Import GetInterval= 0
DSS Import GetPeak= 0
DSS Import FillOption= 0

--- UNT999 IN NNOGR.g01 (geometry) ---

Geom Title=Existing Conditions
Program Version=4.10

River Reach=UNT999 IN NNOGR ,Reach-1
Reach XY= 30
      2796262.03     10108937.66       2796284.4      10108912.5
      2796295.89     10108880.37      2796295.89     10108862.14
      2796277.96     10108838.92      2796275.63     10108798.75
      2796301.53     10108761.01      2796309.78     10108730.63
      2796355.89     10108657.33      2796425.66     10108597.38
      2796459.52     10108554.42      2796477.75     10108505.37
       2796512.9     10108452.42      2796607.95     10108349.99
      2796709.52     10108284.02      2796766.81     10108276.64
      2796876.12     10108276.21      2796922.22     10108286.36
      2796989.67     10108331.68      2797038.62     10108341.83
      2797112.58      10108336.1      2797183.42     10108360.84
      2797266.23     10108379.07      2797327.21     10108370.71
      2797397.43     10108341.18      2797458.01     10108292.84
       2797486.4     10108257.84      2797504.08      10108245.2
      2797604.36     10108215.82      2797692.69     10108205.16

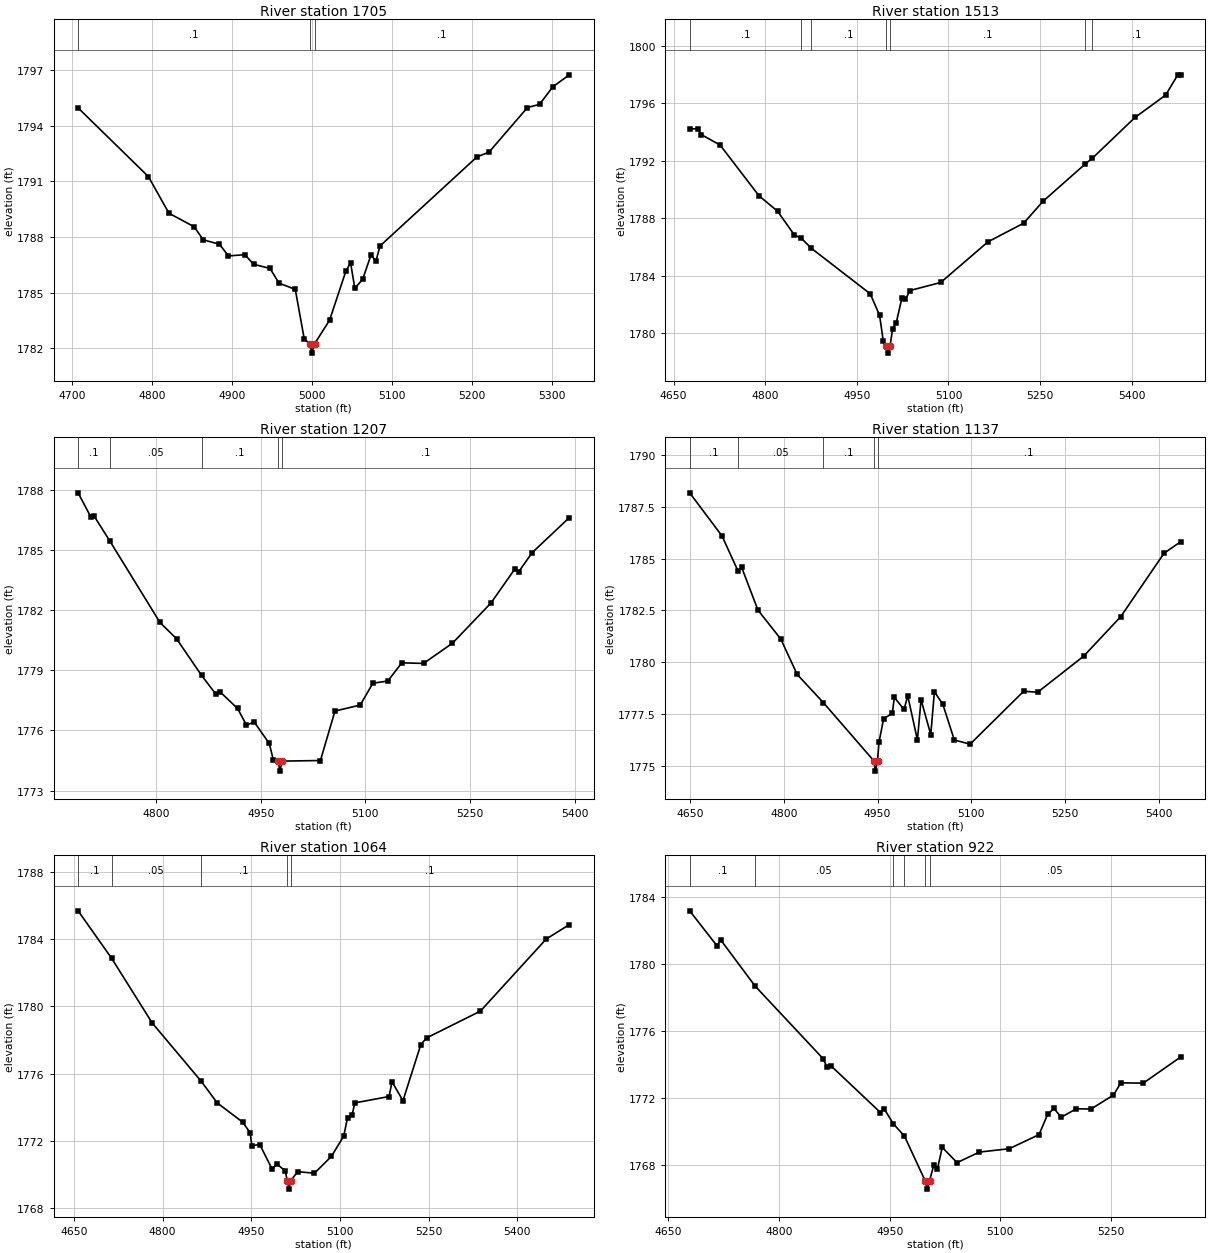
Type RM Length L Ch R = 1 ,1705    ,192,192,192
BEGIN DESCRIPTION:
UNT999 IN NNOGR 1.0
END DESCRIPTION:
XS GIS Cut Line= 2
      2796576.33     10108856.79      2795993.18      10108662.4
#Sta/Elev= 30
  4707.3 1794.95  4795.3 1791.25    4821 1789.28  4852.6 1788.55  4863.9 1787.85
  4884.2 1787.61  4895.5 1786.98  4915.9 1787.05  4927.1 1786.53  4947.5 1786.31
  4958.7 1785.52  4979.1 1785.18  4990.3 1782.52  4997.2 1782.25  4999.9 1781.75
  5003.2 1782.25    5022 1783.52  5042.4 1786.16  5048.3 1786.62  5053.6 1785.24
  5063.4 1785.72    5074 1787.05  5079.9 1786.69  5085.2 1787.52  5206.4 1792.31
  5221.6 1792.57  5269.7 1794.97  5284.8 1795.14  5301.3 1796.08    5322 1796.73
#Mann= 3 ,-1 , 0
  4707.3      .1       0  4997.2     .07       0  5003.2      .1       0
Bank Sta=4997.2,5003.2
XS Rating Curve= 0 ,0
Exp/Cntr=0.3,0.1

Type RM Length L Ch R = 1 ,1513    ,306,306,306
BEGIN DESCRIPTION:
Mapping XS d7fc1eb1
END DESCRIPTION:
XS GIS Cut Line= 3
      2796683.16      10108786.9      2796337.72     10108568.18
      2795943.59      10108597.7
#Sta/Elev= 30
  4676.4 1794.21  4689.8 1794.23  4695.7 1793.81  4726.2 1793.09  4789.8 1789.56
  4820.3 1788.48  4847.7 1786.83  4859.1  1786.6  4875.6  1785.9    4972 1782.73
  4987.3 1781.23  4993.2 1779.47  4998.5  1779.1  5001.3  1778.6  5004.5  1779.1
  5008.5 1780.28  5014.4 1780.69  5023.7 1782.41  5029.6 1782.35    5037 1782.96
  5087.4 1783.52  5164.7 1786.35  5223.2 1787.65    5255 1789.18  5323.4 1791.75
  5335.6 1792.17  5405.4 1795.01  5455.6 1796.57  5475.5 1797.98  5480.5 1797.98
#Mann= 7 ,-1 , 0
  4676.4      .1       0  4859.1     .05       0  4875.6      .1       0
  4998.5     .07       0  5004.5      .1       0  5323.4     .05       0
  5335.6      .1       0
Bank Sta=4998.5,5004.5
XS Rating Curve= 0 ,0
Exp/Cntr=0.3,0.1

Type RM Length L Ch R = 1 ,1207    ,70,70,70
BEGIN DESCRIPTION:
UNT999 IN NNOGR 3.0
END DESCRIPTION:
XS GIS Cut Line= 4
      2796730.06     10108634.11      2796648.48     10108404.98
      2796537.37     10108340.75      2796217.17     10108429.02
#Sta/Elev= 30
  4688.4 1787.87  4706.4 1786.68  4711.7 1786.69  4734.3 1785.44  4805.6  1781.4
  4829.7 1780.57  4865.3 1778.75  4886.1  1777.8  4891.4 1777.94  4916.9  1777.1
  4929.6 1776.27  4940.8 1776.42  4962.3 1775.35  4968.1 1774.53  4974.8 1774.47
  4977.6 1773.97  4980.8 1774.47  5035.6  1774.5  5056.4 1776.97  5092.6 1777.27
  5110.7 1778.36  5132.1 1778.47  5152.2 1779.38  5183.3 1779.35  5224.8 1780.36
    5280 1782.37  5314.4 1784.08  5319.5 1783.92  5338.9 1784.88  5392.1 1786.63
#Mann= 5 ,-1 , 0
  4688.4      .1       0  4734.3     .05       0  4865.3      .1       0
  4974.8     .07       0  4980.8      .1       0
Bank Sta=4974.8,4980.8
XS Rating Curve= 0 ,0
Exp/Cntr=0.3,0.1

Type RM Length L Ch R = 1 ,1137    ,73,73,73
BEGIN DESCRIPTION:
Mapping XS 1455f5d3
END DESCRIPTION:
XS GIS Cut Line= 4
        2796770.     10108648.01      2796665.84     10108340.75
       2796596.4     10108299.08      2796224.83     10108384.16
#Sta/Elev= 30
  4649.1 1788.17  4700.9 1786.09  4726.5  1784.4  4732.3 1784.58  4758.4 1782.52
  4795.1 1781.12  4821.2 1779.42  4863.2 1778.06  4943.9 1775.26  4946.6 1774.76
  4949.9 1775.26  4952.2 1776.15  4959.8 1777.29  4973.5 1777.54  4976.9 1778.31
  4992.4 1777.73  4998.3 1778.39  5013.8 1776.26  5019.6  1778.2  5035.2 1776.52
    5041 1778.59  5054.5 1777.98  5072.9 1776.26  5098.2 1776.06    5184 1778.61
  5206.3 1778.56  5280.1  1780.3  5339.6 1782.21  5408.8 1785.26  5435.7 1785.82
#Mann= 5 ,-1 , 0
  4649.1      .1       0  4726.5     .05       0  4863.2      .1       0
  4943.9     .07       0  4949.9      .1       0
Bank Sta=4943.9,4949.9
XS Rating Curve= 0 ,0
Exp/Cntr=0.3,0.1

Type RM Length L Ch R = 1 ,1064    ,142,142,142
BEGIN DESCRIPTION:
Mapping XS c371beeb
END DESCRIPTION:
XS GIS Cut Line= 4
      2796801.25     10108606.35      2796742.23     10108318.18
      2796606.81     10108205.33      2796249.16     10108163.66
#Sta/Elev= 30
  4657.2  1785.7  4713.7 1782.88  4782.4 1779.02  4865.1 1775.55  4892.5 1774.25
  4935.5  1773.1    4948 1772.48  4951.1  1771.7  4964.4 1771.77  4985.3  1770.3
  4993.1 1770.61  5007.4  1770.2  5010.9 1769.61  5013.7 1769.11  5016.9 1769.61
  5028.2 1770.15  5056.9 1770.06  5085.5 1771.06  5106.3 1772.27  5112.8 1773.37
  5120.6 1773.53    5125 1774.25    5183 1774.63    5188 1775.51  5206.5 1774.38
  5236.7 1777.73  5246.8 1778.13  5337.4 1779.72  5448.5 1784.01  5487.7 1784.88
#Mann= 5 ,-1 , 0
  4657.2      .1       0  4713.7     .05       0  4865.1      .1       0
  5010.9     .07       0  5016.9      .1       0
Bank Sta=5010.9,5016.9
XS Rating Curve= 0 ,0
Exp/Cntr=0.3,0.1

Type RM Length L Ch R = 1 ,922     ,185,185,185
BEGIN DESCRIPTION:
UNT999 IN NNOGR 2.0
END DESCRIPTION:
XS GIS Cut Line= 2
       2796888.8     10108592.93      2796798.52     10107933.18
#Sta/Elev= 30
  4678.9 1783.15  4715.8 1781.07  4720.9 1781.42  4767.6 1778.66  4859.8 1774.33
  4865.3 1773.81  4870.3 1773.91  4937.5 1771.12  4942.6 1771.34  4954.9 1770.45
  4970.1 1769.71  4998.1 1767.05  5000.8 1766.55  5004.1 1767.05  5009.7 1767.96
  5014.8 1767.76  5021.3 1769.04  5041.4 1768.13  5071.7 1768.76  5112.1 1768.96
  5152.5  1769.8  5164.2 1771.01  5172.7 1771.36  5182.7 1770.84  5202.9 1771.34
  5223.1 1771.33  5253.4 1772.16  5263.5 1772.89  5293.8 1772.87  5344.8 1774.44
#Mann= 6 ,-1 , 0
  4678.9      .1       0  4767.6     .05       0  4954.9      .1       0
  4970.1     .05       0  4998.1    .035       0  5004.1     .05       0
Bank Sta=4998.1,5004.1
XS Rating Curve= 0 ,0
Exp/Cntr=0.3,0.1

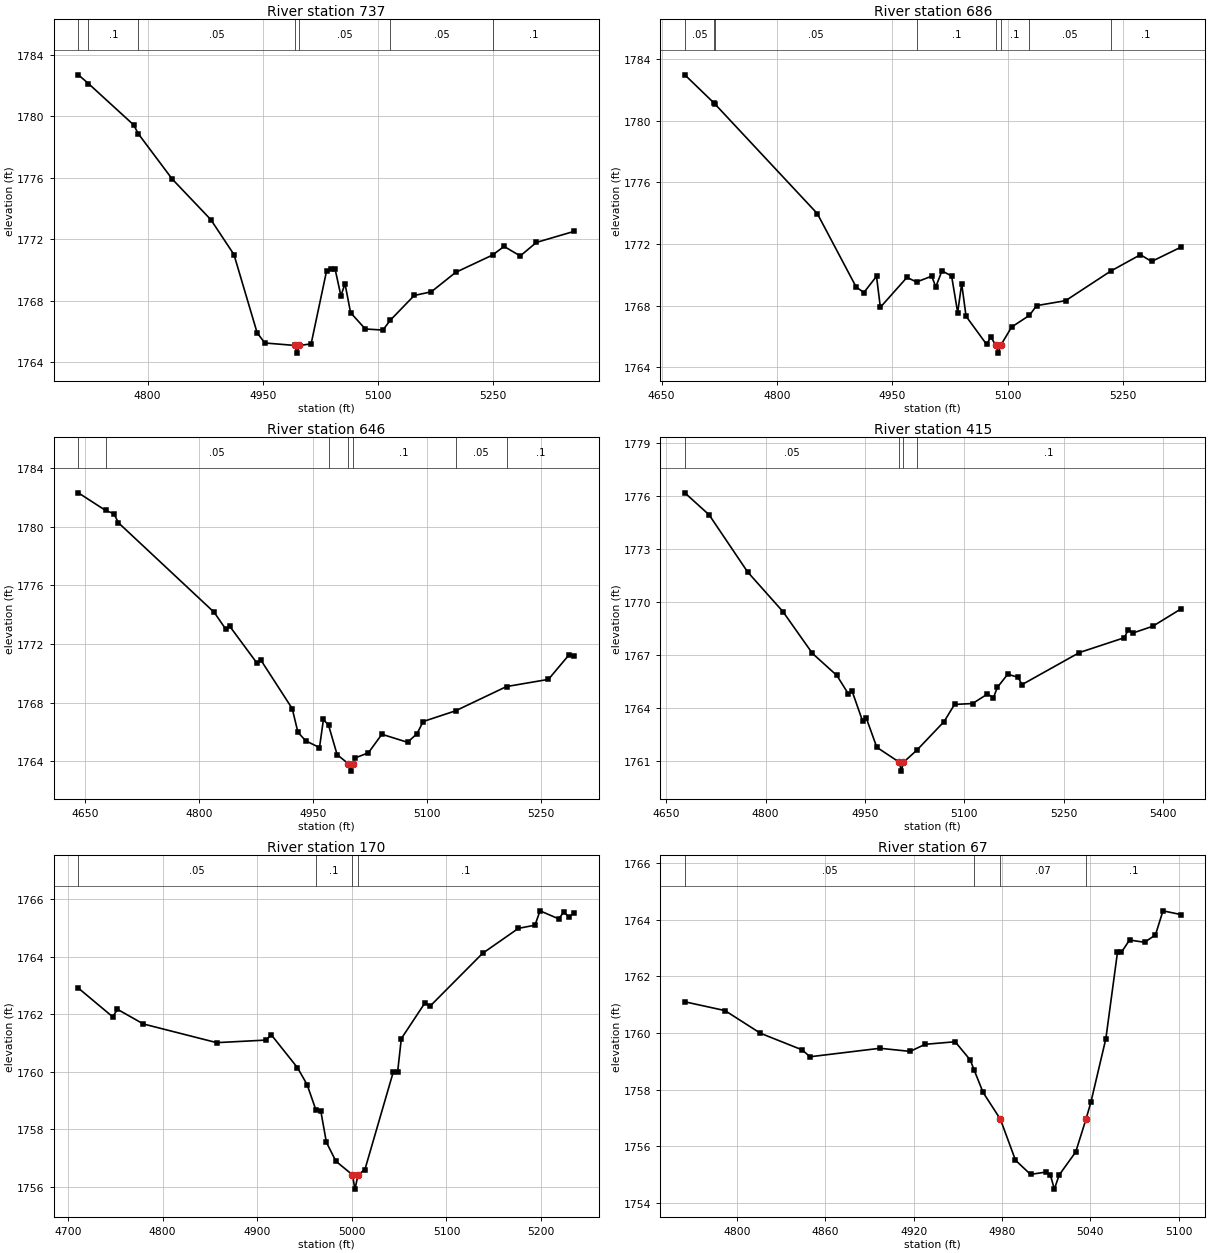
Type RM Length L Ch R = 1 ,737     ,51,51,51
BEGIN DESCRIPTION:
Mapping XS 94f3fead
END DESCRIPTION:
XS GIS Cut Line= 3
      2796985.29     10108625.43      2797018.27     10108297.35
      2796919.88     10107996.99
#Sta/Elev= 30
  4709.9  1782.7  4723.1 1782.13    4782 1779.44  4788.1 1778.86  4832.2 1775.92
  4882.5 1773.28  4912.6 1771.01  4942.8 1765.92  4952.8 1765.26  4991.8  1765.1
  4994.6  1764.6  4997.8  1765.1  5013.1  1765.2  5033.2 1769.94  5038.9  1770.1
  5044.2  1770.1  5051.9 1768.32  5057.2 1769.12  5064.5 1767.23  5083.7 1766.17
  5106.6  1766.1  5116.2 1766.74  5147.4 1768.35  5169.7 1768.59  5201.3 1769.85
  5249.4 1770.98  5264.4 1771.54  5285.5 1770.92  5306.5  1771.8  5355.7 1772.52
#Mann= 7 ,-1 , 0
  4709.9     .05       0  4723.1      .1       0  4788.1     .05       0
  4991.8     .07       0  4997.8     .05       0  5116.2     .05       0
  5249.4      .1       0
Bank Sta=4991.8,4997.8
XS Rating Curve= 0 ,0
Exp/Cntr=0.3,0.1

Type RM Length L Ch R = 1 ,686     ,40,40,40
BEGIN DESCRIPTION:
Mapping XS 3dd93c00
END DESCRIPTION:
XS GIS Cut Line= 5
      2797032.17     10108651.48      2797075.56     10108465.75
      2797072.09     10108366.79       2797058.2     10108314.71
      2796968.27     10108027.62
#Sta/Elev= 30
  4680.1 1782.97  4717.9 1781.15  4719.6 1781.06  4852.4 1773.97  4902.9 1769.21
  4912.9 1768.86  4929.3 1769.91  4934.3  1767.9  4968.9 1769.84  4981.3 1769.54
  5001.1 1769.92  5006.3 1769.22  5014.4 1770.26  5026.9 1769.93  5034.8 1767.56
    5040 1769.43  5045.7 1767.32  5072.5 1765.49  5077.7 1765.97  5084.7 1765.43
  5087.4 1764.93  5090.7 1765.43  5104.9 1766.62  5128.1 1767.38  5137.4 1768.01
  5175.1 1768.33  5233.5 1770.24  5272.4 1771.31  5286.8 1770.87  5324.6 1771.79
#Mann= 8 ,-1 , 0
  4680.1     .05       0  4717.9      .1       0  4719.6     .05       0
  4981.3      .1       0  5084.7     .07       0  5090.7      .1       0
  5128.1     .05       0  5233.5      .1       0
Bank Sta=5084.7,5090.7
XS Rating Curve= 0 ,0
Exp/Cntr=0.3,0.1

Type RM Length L Ch R = 1 ,646     ,231,231,231
BEGIN DESCRIPTION:
Mapping XS fe82e11a
END DESCRIPTION:
XS GIS Cut Line= 3
      2797084.24     10108677.56      2797148.48     10108512.62
      2797032.17     10108050.85
#Sta/Elev= 30
  4640.8 1782.33  4676.6 1781.13  4687.8  1780.9  4693.5 1780.29  4819.8 1774.16
  4835.2    1773  4840.4  1773.2  4876.3 1770.68  4881.5 1770.88  4922.6 1767.58
  4930.1 1765.96  4940.4 1765.38  4958.5 1764.92  4963.7 1766.84  4970.5 1766.44
  4981.7 1764.44  4996.6 1763.81  4999.4 1763.31  5002.6 1763.81  5004.8  1764.2
  5022.9 1764.56  5040.7 1765.83  5074.5 1765.28    5087 1765.87  5095.1  1766.7
  5137.7 1767.43  5204.9 1769.09  5260.1 1769.58  5287.3 1771.26    5294  1771.2
#Mann= 7 ,-1 , 0
  4640.8      .1       0  4676.6     .05       0  4970.5      .1       0
  4996.6     .07       0  5002.6      .1       0  5137.7     .05       0
  5204.9      .1       0
Bank Sta=4996.6,5002.6
XS Rating Curve= 0 ,0
Exp/Cntr=0.3,0.1

Type RM Length L Ch R = 1 ,415     ,245,245,245
BEGIN DESCRIPTION:
Mapping XS 52d993b4
END DESCRIPTION:
XS GIS Cut Line= 3
      2797263.05     10108656.74      2797368.97     10108441.44
      2797112.73     10108001.69
#Sta/Elev= 30
    4678  1776.2  4714.8 1774.95  4772.8 1771.72  4826.2 1769.47  4870.8  1767.1
  4907.7 1765.85    4925 1764.81  4930.8 1764.95  4946.5 1763.27  4952.3 1763.42
    4968 1761.78  5002.2 1760.93    5005 1760.43  5008.2 1760.93  5028.6 1761.62
  5069.7 1763.24  5085.4 1764.21  5112.7 1764.26  5135.2  1764.8  5144.2 1764.59
    5150 1765.17  5165.7 1765.92  5181.4 1765.75  5187.2 1765.33  5274.1 1767.15
  5341.9 1767.99  5347.7 1768.44  5355.1 1768.26  5384.9 1768.64  5426.9 1769.61
#Mann= 4 ,-1 , 0
    4678     .05       0  5002.2    .035       0  5008.2     .05       0
  5028.6      .1       0
Bank Sta=5002.2,5008.2
XS Rating Curve= 0 ,0
Exp/Cntr=0.3,0.1

Type RM Length L Ch R = 1 ,170     ,103,103,103
BEGIN DESCRIPTION:
UNT999 IN NNOGR 4.0
END DESCRIPTION:
XS GIS Cut Line= 3
      2797580.78     10108521.35      2797518.27     10108189.71
      2797343.28     10108124.87
#Sta/Elev= 30
  4710.9 1762.91  4747.2 1761.91  4752.3 1762.17  4779.7 1761.66  4857.2 1761.01
  4909.6  1761.1  4914.7 1761.29  4942.5 1760.14  4952.7 1759.55  4962.1 1758.66
  4967.2 1758.63  4973.1 1757.54  4983.2 1756.88  5000.6 1756.41  5003.3 1755.91
  5006.6 1756.41  5013.8 1756.59  5043.8 1759.99  5048.4 1759.99  5052.3 1761.15
  5077.4  1762.4  5082.7 1762.28  5138.2 1764.12  5176.1 1764.99  5193.6  1765.1
  5198.9  1765.6  5218.7 1765.32    5224 1765.56  5229.5 1765.38    5235 1765.54
#Mann= 4 ,-1 , 0
  4710.9     .05       0  4962.1      .1       0  5000.6     .07       0
  5006.6      .1       0
Bank Sta=5000.6,5006.6
XS Rating Curve= 0 ,0
Exp/Cntr=0.3,0.1

Type RM Length L Ch R = 1 ,67      ,0,0,0
BEGIN DESCRIPTION:
UNT999 IN NNOGR 4.1
END DESCRIPTION:
XS GIS Cut Line= 4
       2797608.2     10108444.24      2797640.33     10108272.34
      2797613.85     10108153.42      2797574.34     10108146.03
#Sta/Elev= 30
  4764.5  1761.1  4791.8 1760.79  4815.9 1759.99  4844.4  1759.4  4849.5 1759.16
  4897.1 1759.46  4917.6 1759.35  4927.8  1759.6  4948.2 1759.69  4958.4 1759.05
  4961.2 1758.68  4967.2  1757.9  4978.9 1756.96  4989.2 1755.51  4999.4 1755.01
  5009.7 1755.09  5012.9 1754.99  5015.6 1754.49  5018.9 1754.99  5030.1  1755.8
 5037.06 1756.95  5040.4 1757.55  5050.6  1759.8  5058.5 1762.85  5061.2 1762.85
  5066.7 1763.28  5076.9  1763.2  5084.3 1763.46  5089.4 1764.31  5101.4 1764.18
#Mann= 4 ,-1 , 0
  4764.5     .05       0  4961.2      .1       0  4978.9     .07       0
 5037.06      .1       0
Bank Sta=4978.9,5037.06
XS Rating Curve= 0 ,0
Exp/Cntr=0.3,0.1

Chan Stop Cuts=-1
Use User Specified Reach Order=0
Composite Channel Slope=5