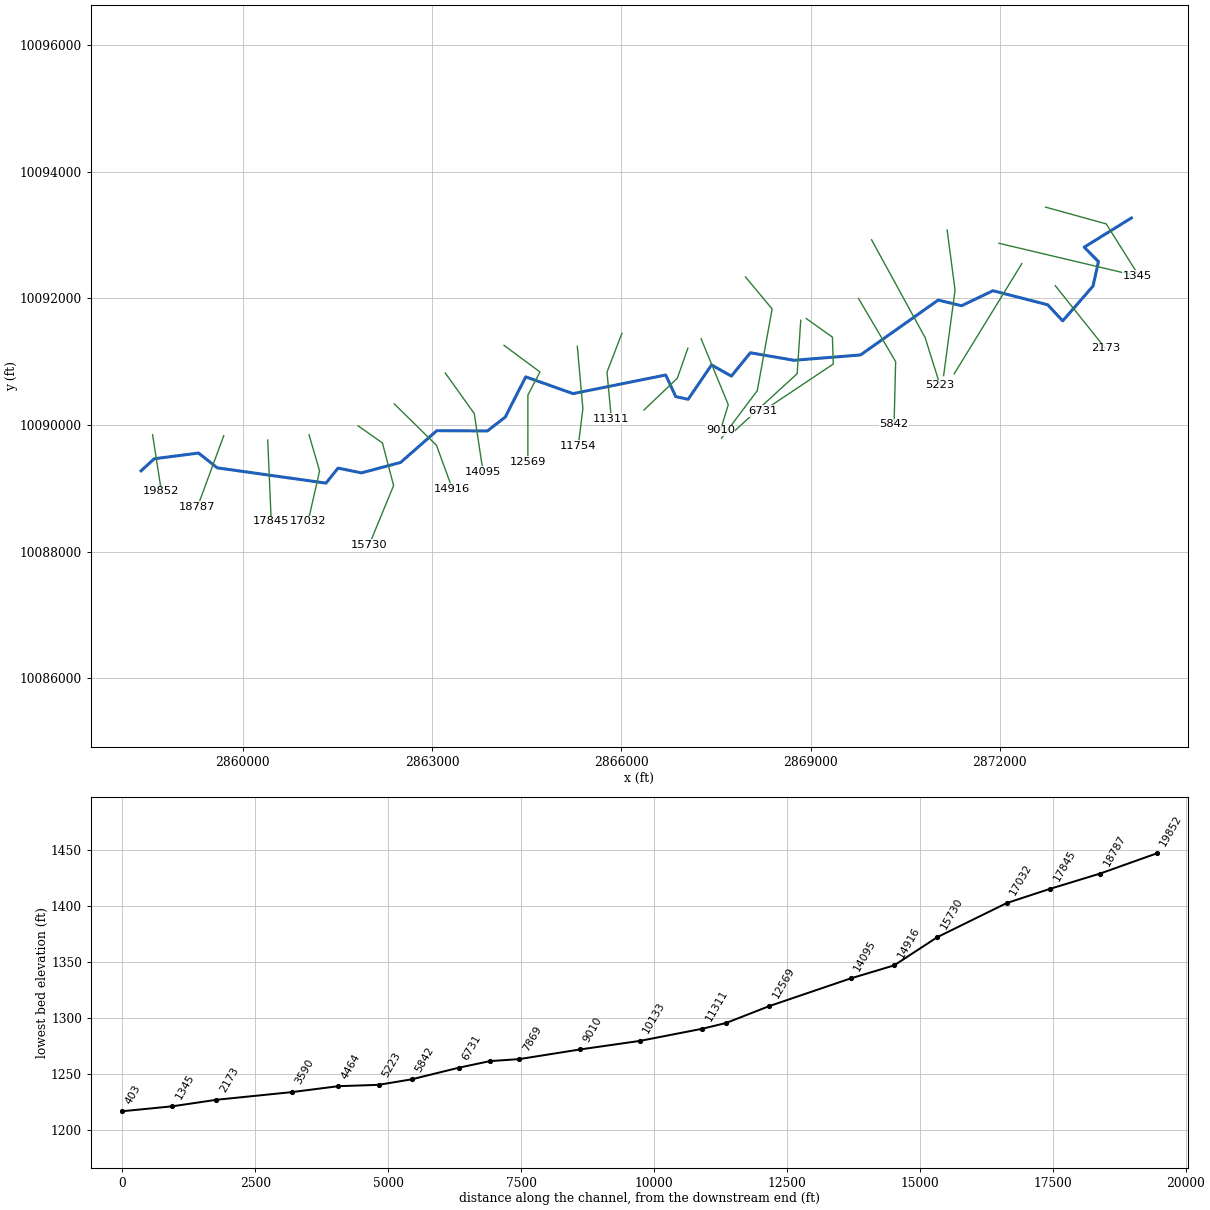
--- WALKER BRANCH.prj (project) ---

Proj Title=WALKER BRANCH Base Level Engineering
Current Plan=p01
Default Exp/Contr=0.3,0.1
English Units
Geom File=g01
Flow File=f01
Plan File=p01
BEGIN DESCRIPTION:
WALKER BRANCH
END DESCRIPTION:

--- WALKER BRANCH.p01 (plan) ---

Plan Title=Multiple Run
Short Identifier=Multiple
Geom File=g01
Flow File=f01
Subcritical Flow
K Sum by GR= 0
Std Step Tol= 0.01
Critical Tol= 0.01
Num of Std Step Trials= 20
Max Error Tol= 0.3
Flow Tol Ratio= 0.001
Split Flow NTrial= 30
Split Flow Tol= 0.02
Split Flow Ratio= 0.02
Log Output Level= 0
Friction Slope Method= 1
Unsteady Friction Slope Method= 2
Unsteady Bridges Friction Slope Method= 1
Parabolic Critical Depth
Global Vel Dist=  1 , 1 , 1
Global Log Level= 0
CheckData=True
Encroach Param= -1, 0, 0, 0
BEGIN DESCRIPTION:
Multiple Run
END DESCRIPTION:

--- WALKER BRANCH.f01 (steady flow) ---

Flow Title=Multiple
Number of Profiles=7
Profile Names=10-year,25-year,50-year,1pct_min,100-year,1pct_plu,500-year
River Rch & RM= WALKER BRANCH,Reach-1,19852
     774    1112    1403    1296    1753    2371    2746
River Rch & RM= WALKER BRANCH,Reach-1,18787
    1308    1936    2492    2345    3172    4289    5161
River Rch & RM= WALKER BRANCH,Reach-1,12569
    1529    2275    2939    2773    3750    5072    6135
River Rch & RM= WALKER BRANCH,Reach-1,5223
    2584    3938    5166    4942    6684    9039   11246
Boundary for River Rch & Prof#=WALKER BRANCH,Reach-1,1
Up Type=0
Dn Type=3
Dn Slope=0.005
Boundary for River Rch & Prof#=WALKER BRANCH,Reach-1,2
Up Type=0
Dn Type=3
Dn Slope=0.005
Boundary for River Rch & Prof#=WALKER BRANCH,Reach-1,3
Up Type=0
Dn Type=3
Dn Slope=0.005
Boundary for River Rch & Prof#=WALKER BRANCH,Reach-1,4
Up Type=0
Dn Type=3
Dn Slope=0.005
Boundary for River Rch & Prof#=WALKER BRANCH,Reach-1,5
Up Type=0
Dn Type=3
Dn Slope=0.005
Boundary for River Rch & Prof#=WALKER BRANCH,Reach-1,6
Up Type=0
Dn Type=3
Dn Slope=0.005
Boundary for River Rch & Prof#=WALKER BRANCH,Reach-1,7
Up Type=0
Dn Type=3
Dn Slope=0.005

--- WALKER BRANCH.g01 (geometry) ---

Geom Title=Existing Conditions

River Reach=WALKER BRANCH,Reach-1
Reach XY= 30
      2858388.60     10089278.81      2858596.82     10089469.27
      2859299.32     10089559.03      2859594.32     10089325.52
      2861318.21     10089084.30      2861509.66     10089321.21
      2861880.28     10089245.87      2862501.81     10089411.30
      2863074.18     10089912.22      2863876.27     10089908.09
      2864160.39     10090127.61      2864484.03     10090761.99
      2865233.53     10090497.44      2866703.01     10090791.35
      2866862.04     10090450.38      2867058.10     10090407.94
      2867429.71     10090950.38      2867743.52     10090773.63
      2868044.16     10091142.25      2868737.20     10091023.59
      2869791.71     10091108.27      2871021.83     10091974.57
      2871392.66     10091885.26      2871889.43     10092122.29
      2872757.15     10091900.24      2872995.03     10091645.72
      2873475.40     10092194.96      2873561.71     10092581.54
      2873335.91     10092809.62      2874084.11     10093270.90

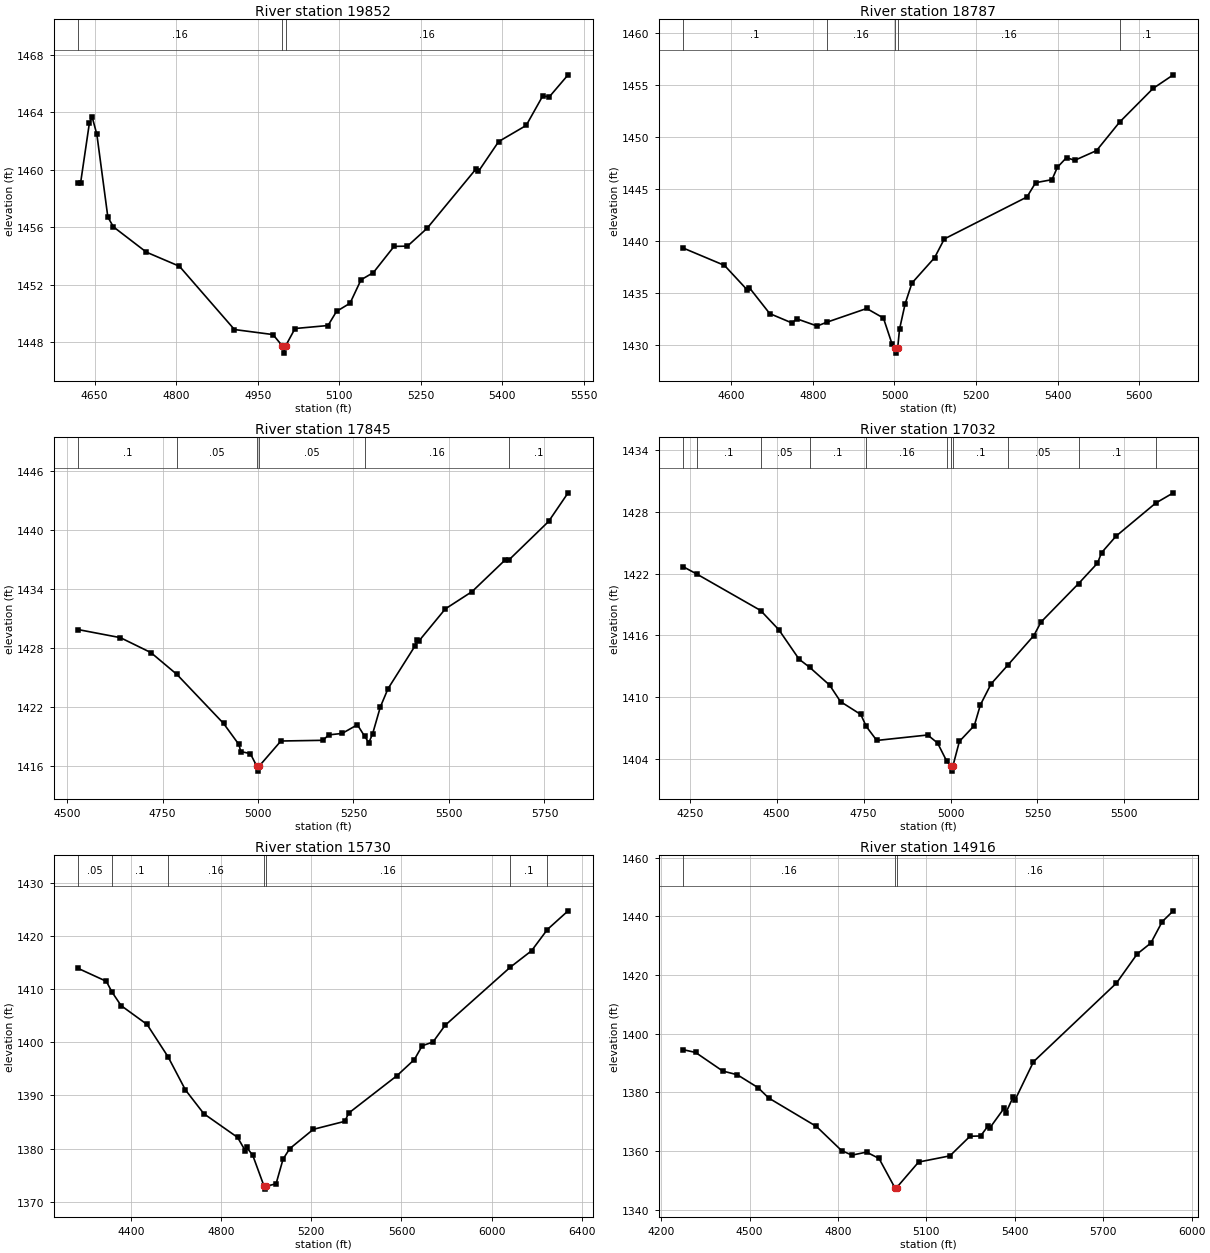
Type RM Length L Ch R = 1,19852,1065,1065,1065
BEGIN DESCRIPTION:
WALKER BRANCH 43.0
END DESCRIPTION:
XS GIS Cut Line= 2
      2858570.04     10089847.91      2858709.16     10088957.52
#Sta/Elev= 30
  4619.7 1459.09  4624.4 1459.09  4640.5 1463.23  4645.6 1463.67  4654.3 1462.46
  4674.5 1456.71  4684.7 1456.03  4745.4 1454.27  4806.1 1453.29  4907.3 1448.89
  4978.2 1448.54  4995.4 1447.75  4998.2 1447.25  5001.4 1447.75  5018.7 1448.96
  5079.4 1449.17  5095.0 1450.15  5119.9 1450.72  5140.1 1452.35  5162.8 1452.85
  5200.8 1454.67  5225.5 1454.69  5261.6 1455.93  5351.0 1460.03  5356.1 1459.89
  5393.2 1461.96  5443.8 1463.08  5474.1 1465.12  5486.6 1465.08  5520.9 1466.60
#Mann=3,-1,0
  4619.7    0.16       0  4995.4    0.07       0  5001.4    0.16       0
Bank Sta=4995.4,5001.4
Exp/Cntr=0.3,0.1

Type RM Length L Ch R = 1,18787,942,942,942
BEGIN DESCRIPTION:
WALKER BRANCH 39.0
END DESCRIPTION:
XS GIS Cut Line= 2
      2859698.44     10089833.97      2859281.11     10088707.17
#Sta/Elev= 30
  4482.1 1439.31  4583.2 1437.64  4638.7 1435.29  4644.0 1435.50  4694.1 1433.00
  4749.0 1432.09  4760.2 1432.50  4810.4 1431.80  4833.6 1432.16  4931.9 1433.49
  4972.9 1432.57  4994.2 1430.05  5001.9 1429.69  5004.6 1429.19  5007.9 1429.69
  5012.4 1431.50  5026.2 1433.95  5042.8 1435.94  5098.3 1438.38  5122.2 1440.19
  5324.8 1444.23  5346.1 1445.61  5386.2 1445.90  5399.4 1447.09  5421.9 1448.03
  5441.7 1447.76  5495.4 1448.70  5551.9 1451.44  5634.1 1454.69  5683.7 1456.00
#Mann=5,-1,0
  4482.1     0.1       0  4833.6    0.16       0  5001.9    0.07       0
  5007.9    0.16       0  5551.9     0.1       0
Bank Sta=5001.9,5007.9
Exp/Cntr=0.3,0.1

Type RM Length L Ch R = 1,17845,813,813,813
BEGIN DESCRIPTION:
WALKER BRANCH 38.0
END DESCRIPTION:
XS GIS Cut Line= 2
      2860394.96     10089764.33      2860450.68     10088482.64
#Sta/Elev= 30
  4528.9 1429.89  4639.6 1429.07  4719.7 1427.55  4787.8 1425.33  4909.9 1420.35
  4949.9 1418.22  4954.9 1417.50  4979.9 1417.29  4996.9 1416.01  4999.7 1415.51
  5002.9 1416.01  5060.0 1418.57  5170.1 1418.64  5185.1 1419.19  5220.2 1419.34
  5260.2 1420.22  5279.1 1419.05  5290.2 1418.40  5300.2 1419.32  5320.2 1422.02
  5340.3 1423.88  5410.3 1428.18  5415.4 1428.79  5420.4 1428.69  5490.4 1431.99
  5560.5 1433.75  5645.6 1436.91  5657.6 1436.99  5760.7 1440.87  5811.8 1443.78
#Mann=6,-1,0
  4528.9     0.1       0  4787.8    0.05       0  4996.9   0.035       0
  5002.9    0.05       0  5279.1    0.16       0  5657.6     0.1       0
Bank Sta=4996.9,5002.9
Exp/Cntr=0.3,0.1

Type RM Length L Ch R = 1,17032,1302,1302,1302
BEGIN DESCRIPTION:
WALKER BRANCH 37.0
END DESCRIPTION:
XS GIS Cut Line= 3
      2861049.70     10089847.88      2861216.87     10089276.72
      2861035.76     10088482.64
#Sta/Elev= 30
  4231.3 1422.66  4271.9 1421.92  4453.9 1418.41  4506.5 1416.53  4564.5 1413.68
  4595.3 1412.88  4652.4 1411.16  4683.7 1409.56  4742.0 1408.31  4757.5 1407.16
  4787.9 1405.79  4934.4 1406.32  4962.8 1405.54  4989.1 1403.78  5000.9 1403.31
  5003.6 1402.81  5006.9 1403.31  5025.6 1405.70  5068.6 1407.24  5085.9 1409.24
  5116.7 1411.28  5164.5 1413.09  5239.8 1415.98  5260.3 1417.29  5368.2 1421.02
  5422.8 1423.01  5434.6 1424.03  5476.1 1425.63  5590.1 1428.84  5640.9 1429.84
#Mann=11,-1,0
  4231.3    0.05       0  4271.9     0.1       0  4453.9    0.05       0
  4595.3     0.1       0  4757.5    0.16       0  4989.1     0.1       0
  5000.9    0.07       0  5006.9     0.1       0  5164.5    0.05       0
  5368.2     0.1       0  5590.1    0.05       0
Bank Sta=5000.9,5006.9
Exp/Cntr=0.3,0.1

Type RM Length L Ch R = 1,15730,814,814,814
BEGIN DESCRIPTION:
WALKER BRANCH 32.0
END DESCRIPTION:
XS GIS Cut Line= 4
      2861827.74     10089988.84      2862213.13     10089718.02
      2862390.22     10089046.15      2862004.79     10088113.83
#Sta/Elev= 30
  4164.8 1413.94  4290.4 1411.50  4314.7 1409.53  4355.7 1406.93  4471.2 1403.37
  4564.3 1397.28  4641.3 1391.05  4723.0 1386.57  4872.8 1382.11  4907.9 1379.53
  4913.1 1380.23  4940.2 1378.73  4990.7 1372.87  4993.4 1372.37  4996.7 1372.87
  5043.6 1373.38  5074.6 1378.02  5104.2 1379.99  5209.0 1383.63  5348.9 1385.14
  5365.7 1386.68  5580.3 1393.74  5657.4 1396.77  5692.2 1399.37  5740.0 1400.07
  5793.2 1403.19  6083.1 1414.16  6177.3 1417.25  6247.5 1421.25  6339.5 1424.77
#Mann=7,-1,0
  4164.8    0.05       0  4314.7     0.1       0  4564.3    0.16       0
  4990.7    0.07       0  4996.7    0.16       0  6083.1     0.1       0
  6247.5    0.16       0
Bank Sta=4990.7,4996.7
Exp/Cntr=0.3,0.1

Type RM Length L Ch R = 1,14916,821,821,821
BEGIN DESCRIPTION:
WALKER BRANCH 31.0
END DESCRIPTION:
XS GIS Cut Line= 3
      2862400.96     10090335.47      2863069.65     10089680.71
      2863320.27     10088998.46
#Sta/Elev= 30
  4275.1 1394.58  4317.0 1393.63  4409.0 1387.30  4458.4 1386.04  4529.1 1381.62
  4564.6 1378.13  4727.1 1368.40  4812.0 1360.21  4847.3 1358.63  4896.9 1359.67
  4939.3 1357.50  4992.9 1347.55  4995.6 1347.05  4998.9 1347.55  5073.6 1356.28
  5179.8 1358.39  5248.0 1365.07  5283.9 1365.17  5309.0 1368.54  5314.3 1367.78
  5364.6 1374.76  5370.0 1373.14  5395.1 1378.58  5400.4 1377.36  5463.4 1390.47
  5744.9 1417.28  5815.0 1427.19  5861.5 1430.92  5900.2 1438.23  5937.8 1441.91
#Mann=3,-1,0
  4275.1    0.16       0  4992.9    0.07       0  4998.9    0.16       0
Bank Sta=4992.9,4998.9
Exp/Cntr=0.3,0.1

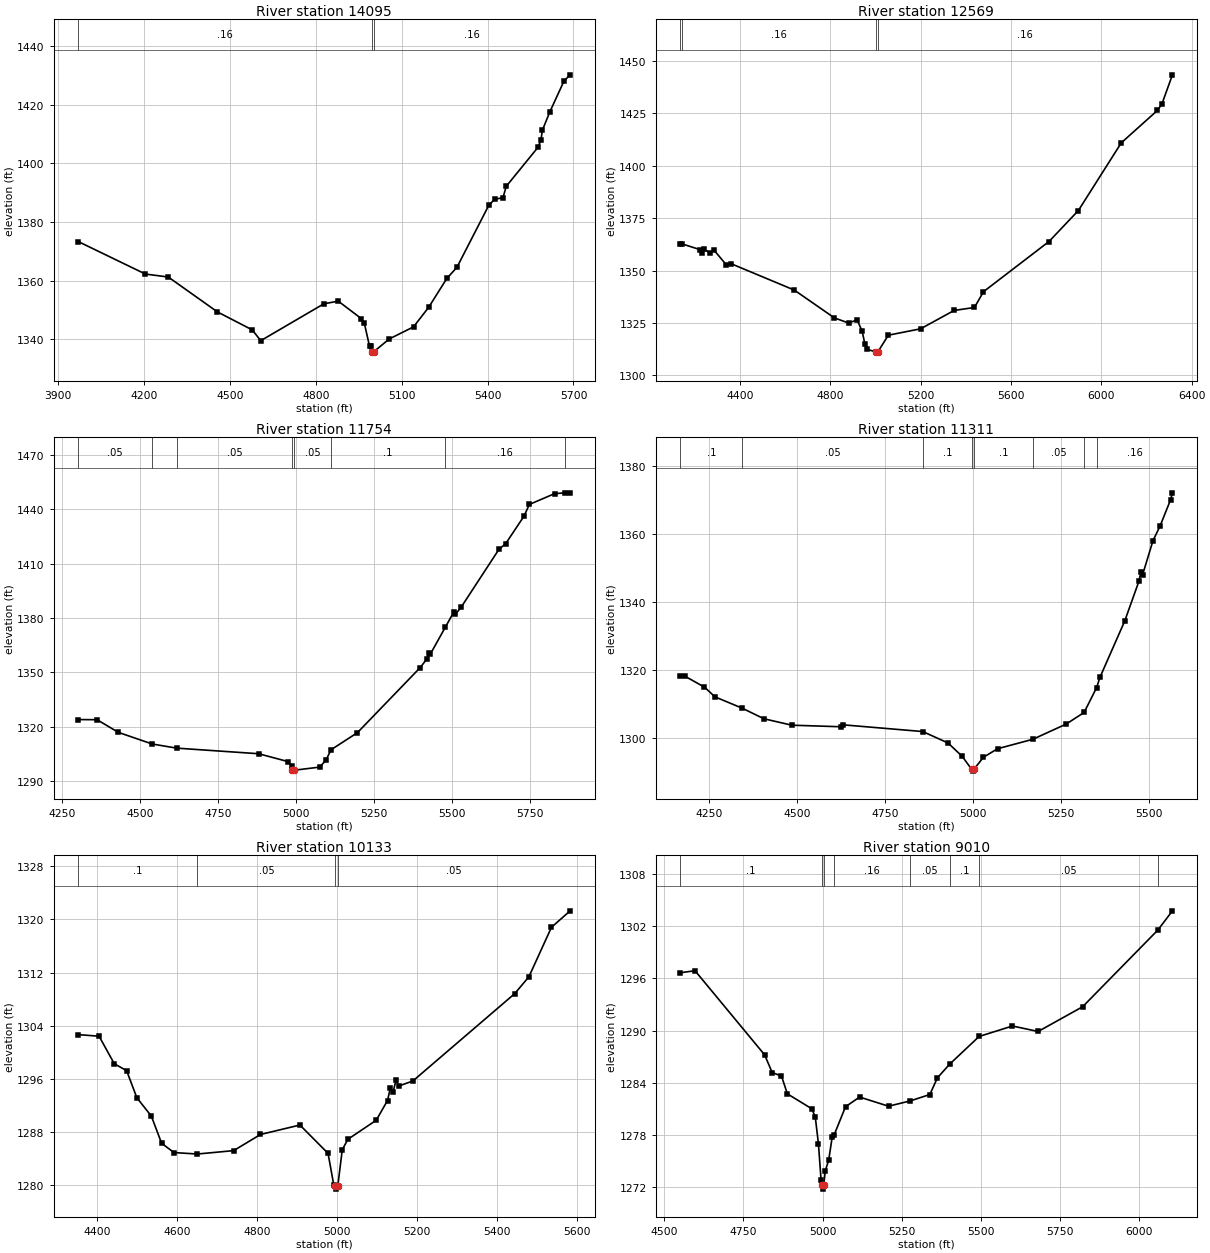
Type RM Length L Ch R = 1,14095,1526,1526,1526
BEGIN DESCRIPTION:
WALKER BRANCH 30.0
END DESCRIPTION:
XS GIS Cut Line= 3
      2863208.93     10090823.06      2863668.66     10090182.21
      2863807.97     10089262.80
#Sta/Elev= 30
  3969.9 1373.37  4204.9 1362.28  4284.7 1361.27  4456.6 1349.37  4578.2 1343.24
  4607.7 1339.57  4827.9 1352.13  4878.4 1353.05  4959.3 1347.08  4969.5 1345.55
  4987.8 1337.64  4992.8 1337.74  4996.8 1335.83  4999.5 1335.33  5002.8 1335.83
  5056.5 1340.15  5141.4 1344.28  5194.1 1350.92  5257.8 1360.79  5293.1 1364.59
  5404.4 1385.73  5424.6 1387.75  5454.0 1388.32  5465.0 1392.15  5576.3 1405.50
  5586.4 1407.98  5591.6 1411.31  5616.8 1417.41  5667.3 1428.13  5688.5 1430.18
#Mann=3,-1,0
  3969.9    0.16       0  4996.8    0.07       0  5002.8    0.16       0
Bank Sta=4996.8,5002.8
Exp/Cntr=0.3,0.1

Type RM Length L Ch R = 1,12569,815,815,815
BEGIN DESCRIPTION:
WALKER BRANCH 26.0
END DESCRIPTION:
XS GIS Cut Line= 4
      2864140.22     10091259.69      2864710.46     10090838.94
      2864518.43     10090474.76      2864518.43     10089417.42
#Sta/Elev= 30
  4137.2 1362.64  4143.2 1362.73  4225.6 1359.90  4234.0 1358.39  4240.3 1360.25
  4269.5 1358.27  4284.2 1359.93  4340.5 1352.69  4361.3 1353.25  4641.2 1340.68
  4818.6 1327.42  4881.2 1324.98  4919.5 1326.45  4941.6 1321.06  4953.5 1315.05
  4963.6 1312.43  5004.6 1311.12  5007.4 1310.62  5010.6 1311.12  5057.4 1319.17
  5200.2 1322.21  5348.6 1330.96  5438.6 1332.38  5478.6 1339.90  5768.6 1363.83
  5898.6 1378.59  6088.6 1410.88  6248.6 1426.32  6268.6 1429.46  6314.9 1443.28
#Mann=4,-1,0
  4137.2     0.1       0  4143.2    0.16       0  5004.6    0.07       0
  5010.6    0.16       0
Bank Sta=5004.6,5010.6
Exp/Cntr=0.3,0.1

Type RM Length L Ch R = 1,11754,443,443,443
BEGIN DESCRIPTION:
Mapping XS e4cc6ebb
END DESCRIPTION:
XS GIS Cut Line= 3
      2865301.67     10091244.09      2865390.22     10090259.69
      2865317.44     10089677.49
#Sta/Elev= 30
  4302.1 1323.94  4362.7 1323.87  4430.8 1316.87  4539.4 1310.44  4617.6 1308.16
  4880.0 1305.07  4975.2 1300.67  4985.2 1298.36  4988.0 1295.96  4990.8 1295.46
  4994.0 1295.96  5075.6 1297.69  5095.6 1301.59  5111.6 1307.26  5196.1 1316.70
  5397.3 1352.69  5417.4 1357.19  5424.0 1360.46  5429.0 1359.93  5477.1 1374.82
  5504.6 1383.33  5509.7 1382.06  5528.3 1386.04  5649.2 1417.99  5670.9 1421.15
  5729.8 1436.42  5746.5 1442.78  5827.1 1448.74  5859.8 1449.19  5877.2 1449.21
#Mann=8,-1,0
  4302.1    0.05       0  4539.4     0.1       0  4617.6    0.05       0
  4988.0   0.035       0  4994.0    0.05       0  5111.6     0.1       0
  5477.1    0.16       0  5859.8     0.1       0
Bank Sta=4988,4994
Exp/Cntr=0.3,0.1

Type RM Length L Ch R = 1,11311,1178,1178,1178
BEGIN DESCRIPTION:
WALKER BRANCH 23.0
END DESCRIPTION:
XS GIS Cut Line= 3
      2866009.02     10091449.93      2865772.19     10090836.95
      2865841.84     10090098.67
#Sta/Elev= 30
  4168.9 1318.24  4182.6 1318.18  4237.2 1315.03  4267.1 1312.17  4344.8 1308.83
  4406.2 1305.74  4485.3 1303.85  4624.4 1303.39  4629.7 1303.97  4857.9 1301.98
  4929.7 1298.62  4969.9 1294.71  4997.0 1290.86  4999.8 1290.36  5003.0 1290.86
  5030.2 1294.42  5070.3 1296.93  5170.7 1299.71  5265.8 1304.19  5316.6 1307.60
  5352.1 1314.90  5361.6 1317.91  5431.9 1334.42  5472.1 1346.05  5477.8 1348.71
  5482.8 1348.02  5512.3 1358.04  5532.4 1362.32  5562.5 1370.09  5567.6 1372.08
#Mann=8,-1,0
  4168.9     0.1       0  4344.8    0.05       0  4857.9     0.1       0
  4997.0    0.07       0  5003.0     0.1       0  5170.7    0.05       0
  5316.6     0.1       0  5352.1    0.16       0
Bank Sta=4997,5003
Exp/Cntr=0.3,0.1

Type RM Length L Ch R = 1,10133,1123,1123,1123
BEGIN DESCRIPTION:
WALKER BRANCH 22.0
END DESCRIPTION:
XS GIS Cut Line= 3
      2867053.82     10091213.12      2866886.64     10090739.44
      2866357.73     10090238.36
#Sta/Elev= 30
  4352.6 1302.68  4405.0 1302.44  4443.0 1298.30  4473.9 1297.26  4499.5 1293.18
  4535.7 1290.43  4561.4 1286.34  4592.3 1284.94  4650.7 1284.72  4741.6 1285.23
  4808.8 1287.66  4907.4 1289.08  4977.8 1284.82  4991.9 1280.13  4996.2 1279.94
  4998.9 1279.44  5002.2 1279.94  5013.4 1285.37  5027.5 1286.94  5098.3 1289.80
  5126.6 1292.77  5133.5 1294.60  5140.8 1294.11  5147.7 1295.80  5154.9 1294.95
  5190.1 1295.71  5444.7 1308.84  5480.2 1311.37  5536.8 1318.83  5583.5 1321.30
#Mann=4,-1,0
  4352.6     0.1       0  4650.7    0.05       0  4996.2   0.035       0
  5002.2    0.05       0
Bank Sta=4996.2,5002.2
Exp/Cntr=0.3,0.1

Type RM Length L Ch R = 1,9010,1141,1141,1141
BEGIN DESCRIPTION:
WALKER BRANCH 19.0
END DESCRIPTION:
XS GIS Cut Line= 3
      2867262.77     10091366.33      2867694.62     10090321.52
      2867569.43     10089918.14
#Sta/Elev= 30
  4551.5 1296.63  4597.6 1296.86  4817.3 1287.21  4841.2 1285.18  4870.5 1284.78
  4889.0 1282.74  4965.5 1281.04  4977.0 1280.12  4987.1 1277.02  4995.5 1272.82
  4997.9 1272.31  5000.6 1271.81  5003.9 1272.31  5008.8 1273.93  5019.4 1275.12
  5030.4 1277.75  5036.4 1278.00  5072.6 1281.26  5117.0 1282.37  5208.4 1281.32
  5277.0 1281.93  5338.7 1282.66  5362.7 1284.58  5401.8 1286.16  5494.2 1289.32
  5599.5 1290.52  5680.5 1289.89  5821.0 1292.73  6058.5 1301.53  6104.4 1303.73
#Mann=8,-1,0
  4551.5     0.1       0  4997.9    0.07       0  5003.9     0.1       0
  5036.4    0.16       0  5277.0    0.05       0  5401.8     0.1       0
  5494.2    0.05       0  6058.5     0.1       0
Bank Sta=4997.9,5003.9
Exp/Cntr=0.3,0.1

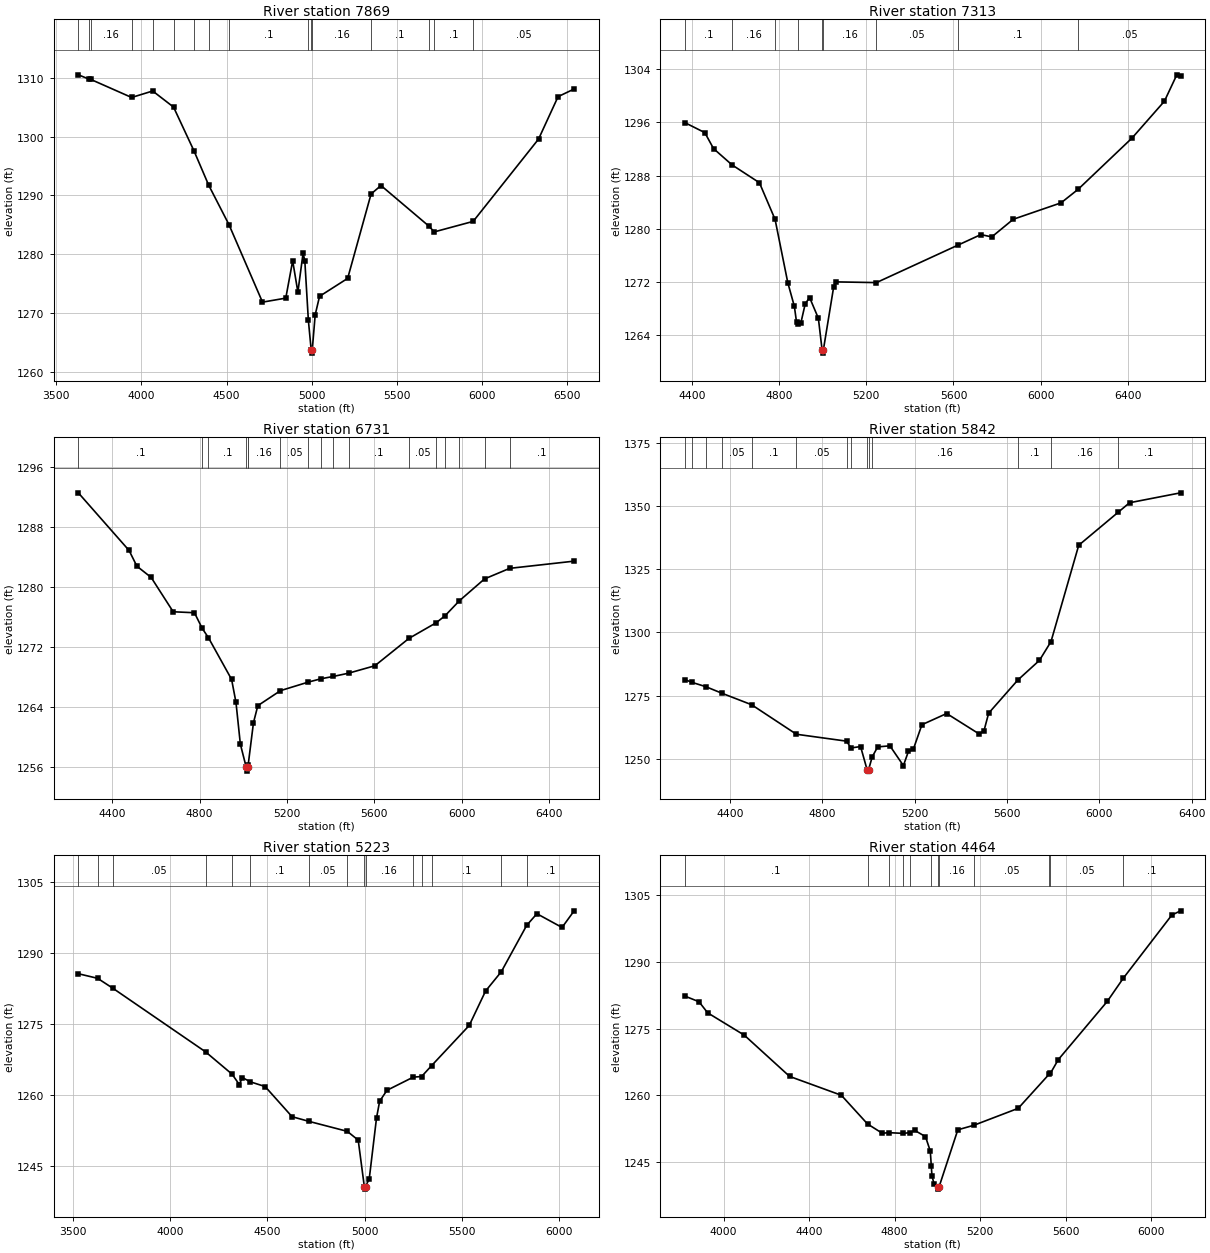
Type RM Length L Ch R = 1,7869,556,556,556
BEGIN DESCRIPTION:
WALKER BRANCH 17.0
END DESCRIPTION:
XS GIS Cut Line= 4
      2867967.56     10092339.53      2868389.47     10091834.28
      2868154.33     10090544.41      2867587.37     10089792.60
#Sta/Elev= 30
  3629.8 1310.50  3695.3 1309.74  3702.1 1309.73  3942.7 1306.65  4066.4 1307.75
  4189.0 1305.01  4309.0 1297.56  4395.1 1291.74  4514.5 1285.01  4711.1 1271.85
  4847.7 1272.53  4888.3 1278.88  4918.8 1273.56  4949.3 1280.17  4959.5 1278.91
  4980.3 1268.80  4997.1 1263.68  4999.9 1263.18  5003.1 1263.68  5020.5 1269.70
  5046.1 1272.84  5211.1 1275.89  5348.6 1290.24  5406.7 1291.68  5689.9 1284.73
  5719.1 1283.79  5948.1 1285.58  6332.0 1299.58  6446.5 1306.79  6540.8 1308.09
#Mann=16,-1,0
  3629.8     0.1       0  3695.3    0.05       0  3702.1    0.16       0
  3942.7    0.05       0  4066.4     0.1       0  4189.0    0.16       0
  4309.0     0.1       0  4395.1    0.16       0  4514.5     0.1       0
  4980.3    0.16       0  4997.1    0.07       0  5003.1    0.16       0
  5348.6     0.1       0  5689.9    0.05       0  5719.1     0.1       0
  5948.1    0.05       0
Bank Sta=4997.1,5003.1
Exp/Cntr=0.3,0.1

Type RM Length L Ch R = 1,7313,582,582,582
BEGIN DESCRIPTION:
Mapping XS e52e3e7d
END DESCRIPTION:
XS GIS Cut Line= 3
      2868843.34     10091655.55      2868786.05     10090811.77
      2867729.05     10089848.50
#Sta/Elev= 30
  4366.6 1295.97  4458.6 1294.46  4498.7 1292.06  4583.4 1289.62  4709.2 1286.94
  4781.1 1281.43  4839.5 1271.93  4869.6 1268.38  4879.6 1266.02  4887.8 1265.71
  4899.6 1265.90  4919.7 1268.78  4939.7 1269.69  4979.8 1266.59  4996.9 1261.85
  4999.6 1261.35  5002.9 1261.85  5050.0 1271.28  5060.0 1272.05  5246.3 1271.94
  5621.4 1277.58  5725.8 1279.15  5775.8 1278.80  5874.4 1281.45  6094.0 1283.92
  6172.2 1285.95  6419.7 1293.65  6568.3 1299.18  6625.1 1303.14  6642.4 1303.03
#Mann=9,-1,0
  4366.6     0.1       0  4583.4    0.16       0  4781.1     0.1       0
  4887.8    0.16       0  4996.9    0.07       0  5002.9    0.16       0
  5246.3    0.05       0  5621.4     0.1       0  6172.2    0.05       0
Bank Sta=4996.9,5002.9
Exp/Cntr=0.3,0.1

Type RM Length L Ch R = 1,6731,889,889,889
BEGIN DESCRIPTION:
WALKER BRANCH 15.0
END DESCRIPTION:
XS GIS Cut Line= 4
      2868931.87     10091681.57      2869344.76     10091389.48
      2869359.32     10090965.22      2868244.61     10090222.78
#Sta/Elev= 30
  4245.1 1292.58  4477.5 1284.89  4513.1 1282.80  4578.4 1281.30  4679.3 1276.72
  4776.6 1276.59  4812.3 1274.50  4840.5 1273.27  4946.7 1267.70  4966.7 1264.64
  4986.8 1259.07  5013.8 1255.97  5016.5 1255.47  5019.8 1255.97  5022.7 1256.32
  5046.8 1261.93  5066.8 1264.20  5170.3 1266.20  5297.5 1267.34  5355.2 1267.78
  5412.8 1268.10  5482.2 1268.53  5602.5 1269.52  5758.6 1273.17  5883.5 1275.26
  5923.9 1276.19  5989.2 1278.18  6104.5 1281.10  6219.7 1282.51  6514.7 1283.47
#Mann=17,-1,0
  4245.1     0.1       0  4812.3    0.05       0  4840.5     0.1       0
  5013.8    0.07       0  5019.8     0.1       0  5022.7    0.16       0
  5170.3    0.05       0  5297.5    0.16       0  5355.2    0.05       0
  5412.8    0.16       0  5482.2     0.1       0  5758.6    0.05       0
  5883.5     0.1       0  5923.9    0.05       0  5989.2     0.1       0
  6104.5    0.05       0  6219.7     0.1       0
Bank Sta=5013.8,5019.8
Exp/Cntr=0.3,0.1

Type RM Length L Ch R = 1,5842,619,619,619
BEGIN DESCRIPTION:
WALKER BRANCH 14.0
END DESCRIPTION:
XS GIS Cut Line= 3
      2869759.33     10091999.29      2870347.18     10091002.65
      2870322.22     10090012.76
#Sta/Elev= 30
  4204.8 1281.34  4237.1 1280.21  4296.3 1278.51  4367.7 1275.85  4494.3 1271.37
  4688.3 1259.67  4905.3 1256.94  4924.8 1254.25  4966.3 1254.79  4994.6 1245.56
  4997.4 1245.06  5000.6 1245.56  5016.7 1250.74  5040.5 1254.67  5093.3 1255.08
  5151.7 1247.25  5173.3 1252.84  5194.7 1253.72  5231.8 1263.45  5339.1 1267.89
  5480.8 1259.73  5500.9 1261.13  5520.9 1268.02  5647.4 1281.17  5740.9 1288.95
  5790.9 1296.38  5911.0 1334.56  6080.7 1347.55  6131.1 1351.41  6352.1 1355.34
#Mann=14,-1,0
  4204.8     0.1       0  4237.1    0.05       0  4296.3     0.1       0
  4367.7    0.05       0  4494.3     0.1       0  4688.3    0.05       0
  4905.3     0.1       0  4924.8    0.05       0  4994.6   0.035       0
  5000.6    0.05       0  5016.7    0.16       0  5647.4     0.1       0
  5790.9    0.16       0  6080.7     0.1       0
Bank Sta=4994.6,5000.6
Exp/Cntr=0.3,0.1

Type RM Length L Ch R = 1,5223,759,759,759
BEGIN DESCRIPTION:
WALKER BRANCH 12.0
END DESCRIPTION:
XS GIS Cut Line= 3
      2869965.31     10092926.57      2870815.09     10091380.25
      2871051.79     10090628.37
#Sta/Elev= 30
  3526.4 1285.62  3625.6 1284.65  3703.6 1282.57  4181.3 1269.13  4318.2 1264.40
  4355.0 1262.23  4371.1 1263.70  4410.9 1262.81  4488.1 1261.80  4626.9 1255.43
  4713.5 1254.45  4911.1 1252.34  4967.4 1250.49  4999.0 1240.64  5001.8 1240.14
  5005.0 1240.64  5024.4 1242.38  5061.7 1255.18  5077.8 1258.71  5115.7 1261.01
  5250.5 1263.78  5293.8 1263.92  5345.4 1266.22  5538.8 1274.69  5623.2 1281.97
  5704.1 1286.04  5835.1 1295.85  5887.4 1298.29  6016.9 1295.39  6079.1 1298.90
#Mann=15,-1,0
  3526.4    0.05       0  3625.6     0.1       0  3703.6    0.05       0
  4181.3     0.1       0  4318.2    0.05       0  4410.9     0.1       0
  4713.5    0.05       0  4911.1    0.16       0  4999.0    0.07       0
  5005.0    0.16       0  5250.5     0.1       0  5293.8    0.05       0
  5345.4     0.1       0  5704.1    0.16       0  5835.1     0.1       0
Bank Sta=4999,5005
Exp/Cntr=0.3,0.1

Type RM Length L Ch R = 1,4464,874,874,874
BEGIN DESCRIPTION:
WALKER BRANCH 10.0
END DESCRIPTION:
XS GIS Cut Line= 3
      2871163.36     10093079.76      2871288.73     10092132.51
      2871107.63     10090781.20
#Sta/Elev= 30
  3818.3 1282.32  3884.9 1281.04  3925.3 1278.55  4096.7 1273.53  4308.6 1264.26
  4550.7 1260.02  4673.2 1253.57  4742.3 1251.48  4771.9 1251.62  4840.7 1251.46
  4871.6 1251.63  4893.7 1252.13  4944.1 1250.73  4966.7 1247.47  4971.4 1244.08
  4974.4 1241.92  4984.5 1240.07  5001.6 1239.43  5004.4 1238.93  5007.6 1239.43
  5095.4 1252.26  5171.0 1253.29  5377.9 1257.09  5522.5 1264.76  5528.4 1264.95
  5565.4 1268.04  5794.4 1281.12  5869.5 1286.34  6096.3 1300.52  6137.2 1301.47
#Mann=12,-1,0
  3818.3     0.1       0  4673.2    0.05       0  4771.9     0.1       0
  4840.7    0.05       0  4871.6     0.1       0  4971.4    0.16       0
  5001.6    0.07       0  5007.6    0.16       0  5171.0    0.05       0
  5522.5     0.1       0  5528.4    0.05       0  5869.5     0.1       0
Bank Sta=5001.6,5007.6
Exp/Cntr=0.3,0.1

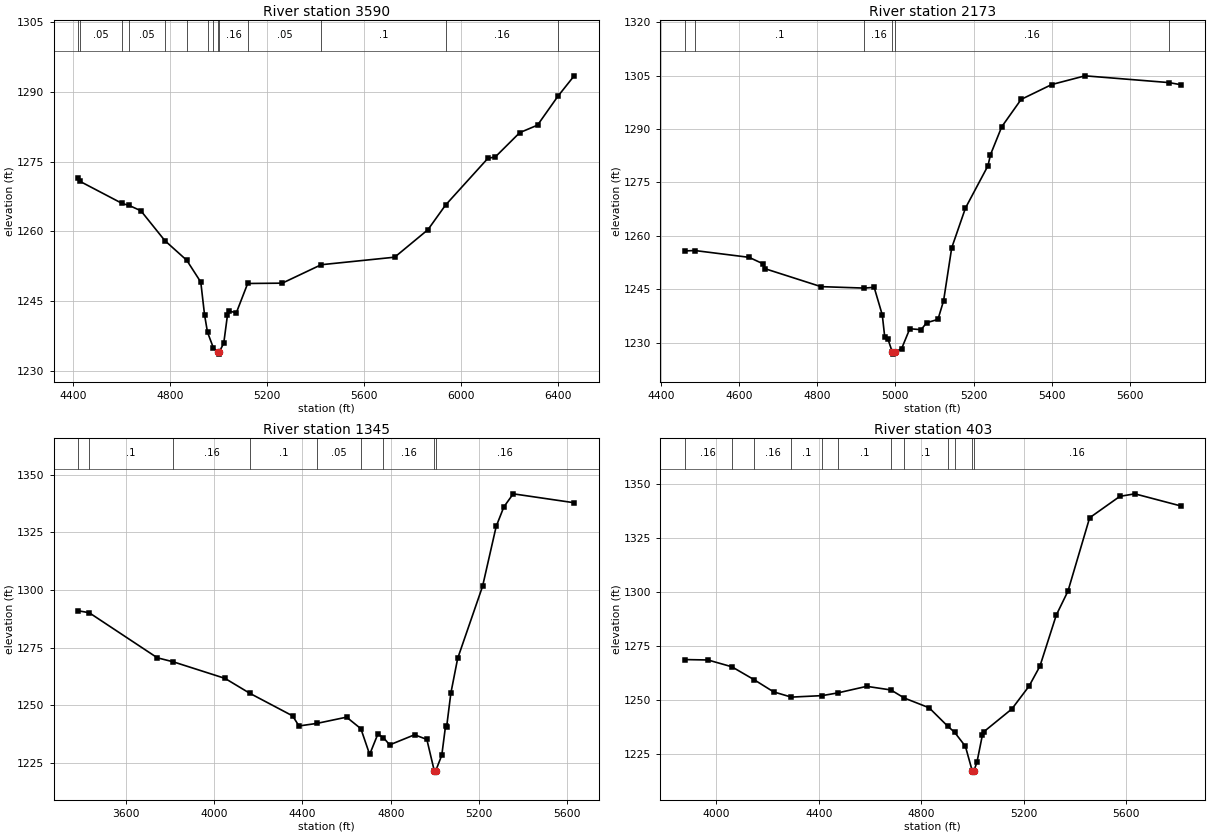
Type RM Length L Ch R = 1,3590,1417,1417,1417
BEGIN DESCRIPTION:
WALKER BRANCH 8.0
END DESCRIPTION:
XS GIS Cut Line= 2
      2872347.44     10092550.39      2871274.78     10090809.06
#Sta/Elev= 30
  4423.0 1271.44  4428.1 1270.79  4604.0 1265.99  4632.9 1265.56  4680.9 1264.43
  4779.9 1258.01  4870.2 1253.79  4928.1 1249.10  4943.6 1242.07  4955.8 1238.33
  4980.5 1234.90  4998.5 1234.12  5001.3 1233.62  5004.5 1234.12  5022.8 1235.96
  5038.2 1242.03  5044.1 1242.85  5074.9 1242.53  5121.5 1248.80  5264.2 1248.87
  5424.7 1252.83  5727.9 1254.45  5865.1 1260.36  5937.7 1265.65  6112.3 1275.69
  6143.1 1276.00  6243.7 1281.21  6317.0 1282.82  6401.3 1289.04  6468.2 1293.42
#Mann=14,-1,0
  4423.0    0.16       0  4428.1    0.05       0  4604.0     0.1       0
  4632.9    0.05       0  4779.9     0.1       0  4870.2    0.16       0
  4955.8     0.1       0  4980.5    0.16       0  4998.5    0.07       0
  5004.5    0.16       0  5121.5    0.05       0  5424.7     0.1       0
  5937.7    0.16       0  6401.3     0.1       0
Bank Sta=4998.5,5004.5
Exp/Cntr=0.3,0.1

Type RM Length L Ch R = 1,2173,828,828,828
BEGIN DESCRIPTION:
WALKER BRANCH 5.0
END DESCRIPTION:
XS GIS Cut Line= 2
      2872876.80     10092202.19      2873670.86     10091213.10
#Sta/Elev= 30
  4461.2 1255.74  4486.7 1255.86  4625.6 1253.95  4660.8 1252.16  4667.2 1250.73
  4809.6 1245.72  4920.6 1245.31  4945.6 1245.53  4966.4 1237.78  4972.8 1231.44
  4980.8 1231.03  4992.2 1227.27  4994.9 1226.77  4998.2 1227.27  5016.0 1228.35
  5036.8 1233.90  5065.6 1233.63  5080.0 1235.59  5108.8 1236.52  5123.2 1241.74
  5144.0 1256.62  5179.2 1267.79  5236.8 1279.67  5243.2 1282.77  5272.0 1290.61
  5321.6 1298.29  5400.0 1302.47  5485.1 1304.91  5700.0 1303.01  5729.6 1302.42
#Mann=6,-1,0
  4461.2    0.16       0  4486.7     0.1       0  4920.6    0.16       0
  4992.2    0.07       0  4998.2    0.16       0  5700.0     0.1       0
Bank Sta=4992.2,4998.2
Exp/Cntr=0.3,0.1

Type RM Length L Ch R = 1,1345,942,942,942
BEGIN DESCRIPTION:
WALKER BRANCH 2.0
END DESCRIPTION:
XS GIS Cut Line= 2
      2871985.22     10092870.84      2874172.41     10092355.39
#Sta/Elev= 30
  3384.1 1290.92  3433.2 1290.10  3742.0 1270.54  3814.5 1268.78  4048.7 1261.61
  4161.1 1255.14  4355.3 1245.33  4384.0 1240.96  4465.2 1242.07  4599.8 1244.78
  4664.6 1239.77  4704.4 1228.60  4741.6 1237.46  4767.1 1235.86  4795.0 1232.75
  4908.0 1237.14  4963.6 1235.11  4997.4 1221.43  5000.2 1220.93  5003.4 1221.43
  5031.3 1228.27  5048.3 1240.92  5053.4 1240.70  5072.4 1255.19  5103.2 1270.25
  5216.2 1301.59  5277.8 1327.53  5312.6 1336.01  5355.0 1341.68  5631.2 1337.81
#Mann=9,-1,0
  3384.1    0.16       0  3433.2     0.1       0  3814.5    0.16       0
  4161.1     0.1       0  4465.2    0.05       0  4664.6     0.1       0
  4767.1    0.16       0  4997.4    0.07       0  5003.4    0.16       0
Bank Sta=4997.4,5003.4
Exp/Cntr=0.3,0.1

Type RM Length L Ch R = 1,403,0,0,0
BEGIN DESCRIPTION:
WALKER BRANCH 1.0
END DESCRIPTION:
XS GIS Cut Line= 3
      2872723.60     10093441.98      2873684.80     10093177.30
      2874186.29     10092383.29
#Sta/Elev= 30
  3876.8 1268.65  3967.2 1268.46  4060.3 1265.32  4146.5 1259.39  4223.5 1253.69
  4292.7 1251.26  4413.3 1251.95  4474.6 1253.22  4587.2 1256.25  4681.8 1254.57
  4733.9 1250.83  4830.8 1246.32  4902.9 1237.85  4930.0 1235.01  4972.6 1228.44
  4999.3 1217.01  5002.0 1216.51  5005.3 1217.01  5017.6 1221.11  5038.7 1233.60
  5044.7 1235.24  5154.1 1245.80  5221.0 1256.33  5263.5 1265.59  5327.4 1289.26
  5372.9 1300.34  5457.6 1334.34  5575.8 1344.27  5634.1 1345.43  5812.9 1339.84
#Mann=12,-1,0
  3876.8    0.16       0  4060.3     0.1       0  4146.5    0.16       0
  4292.7     0.1       0  4413.3    0.05       0  4474.6     0.1       0
  4681.8    0.05       0  4733.9     0.1       0  4902.9    0.05       0
  4930.0    0.16       0  4999.3    0.07       0  5005.3    0.16       0
Bank Sta=4999.3,5005.3
Exp/Cntr=0.3,0.1

Chan Stop Cuts=-1