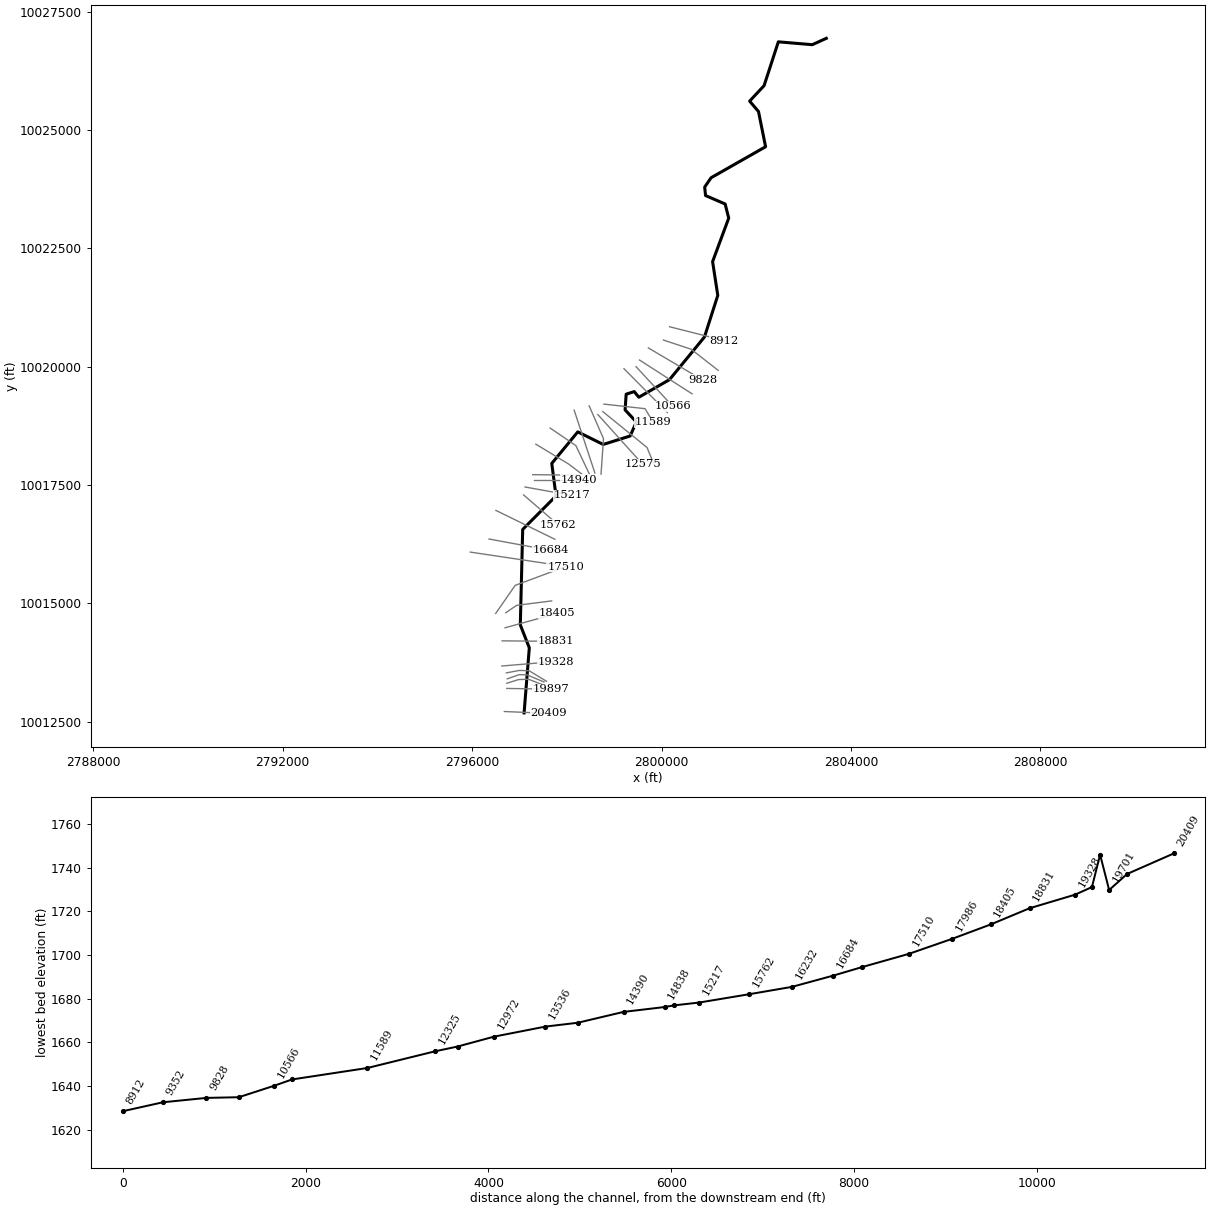
--- WEST FORK HUNTERS CREEK.prj (project) ---

Proj Title=WEST FORK HUNTERS CREEK Base Level Engineering
Current Plan=p01
Default Exp/Contr=0.3,0.1
English Units
Geom File=g01
Flow File=f01
Plan File=p01
Y Axis Title=Elevation
X Axis Title(PF)=Main Channel Distance
X Axis Title(XS)=Station
BEGIN DESCRIPTION:
WEST FORK HUNTERS CREEK
END DESCRIPTION:
DSS Export Rating Curves= 0
DSS Export Rating Curve Sorted= 0
DSS Export Volume Flow Curves= 0
DXF OffsetX= 0
DXF OffsetY= 0
DXF ScaleX= 1
DXF ScaleY= 10

--- WEST FORK HUNTERS CREEK.p01 (plan) ---

Plan Title=Multiple Run
Short Identifier=Multiple
Geom File=g01
Flow File=f01
Subcritical Flow
K Sum by GR= 0
Std Step Tol= 0.01
Critical Tol= 0.01
Num of Std Step Trials= 20
Max Error Tol= 0.3
Flow Tol Ratio= 0.001
Split Flow NTrial= 30
Split Flow Tol= 0.02
Split Flow Ratio= 0.02
Log Output Level= 0
Friction Slope Method= 1
Unsteady Friction Slope Method= 2
Unsteady Bridges Friction Slope Method= 1
Parabolic Critical Depth
Global Vel Dist=  1 , 1 , 1
Global Log Level= 0
CheckData=True
Encroach Param= -1, 0, 0, 0
BEGIN DESCRIPTION:
Multiple Run
END DESCRIPTION:

--- WEST FORK HUNTERS CREEK.f01 (steady flow) ---

Flow Title=Multiple
Program Version=4.10
Number of Profiles= 7
Profile Names=10-year,25-year,50-year,1pct_min,100-year,1pct_plu,500-year
River Rch & RM=WEST FORK HUNTER,Reach-1         ,20409
     808    1170    1483    1379    1865    2522    2955
River Rch & RM=WEST FORK HUNTER,Reach-1         ,16996
    1996    3012    3926    3736    5053    6833    8409
River Rch & RM=WEST FORK HUNTER,Reach-1         ,10764
    2243    3396    4438    4232    5723    7739    9561
River Rch & RM=WEST FORK HUNTER,Reach-1         ,8012
    2457    3724    4868    4641    6276    8488   10484
Boundary for River Rch & Prof#=WEST FORK HUNTER,Reach-1         , 1
Up Type= 0
Dn Type= 1
Dn Known WS=1565.17
Boundary for River Rch & Prof#=WEST FORK HUNTER,Reach-1         , 2
Up Type= 0
Dn Type= 1
Dn Known WS=1567.3
Boundary for River Rch & Prof#=WEST FORK HUNTER,Reach-1         , 3
Up Type= 0
Dn Type= 1
Dn Known WS=1568.88
Boundary for River Rch & Prof#=WEST FORK HUNTER,Reach-1         , 4
Up Type= 0
Dn Type= 1
Dn Known WS=1568.71
Boundary for River Rch & Prof#=WEST FORK HUNTER,Reach-1         , 5
Up Type= 0
Dn Type= 1
Dn Known WS=1570.66
Boundary for River Rch & Prof#=WEST FORK HUNTER,Reach-1         , 6
Up Type= 0
Dn Type= 1
Dn Known WS=1572.67
Boundary for River Rch & Prof#=WEST FORK HUNTER,Reach-1         , 7
Up Type= 0
Dn Type= 1
Dn Known WS=1574.41
Set Internal Change=WEST FORK HUNTER,Reach-1         ,437     , 7 , 3 ,1574.41
Set Internal Change=WEST FORK HUNTER,Reach-1         ,437     , 6 , 3 ,1572.67
Set Internal Change=WEST FORK HUNTER,Reach-1         ,437     , 5 , 3 ,1570.66
Set Internal Change=WEST FORK HUNTER,Reach-1         ,437     , 4 , 3 ,1568.71
Set Internal Change=WEST FORK HUNTER,Reach-1         ,437     , 3 , 3 ,1568.88
Set Internal Change=WEST FORK HUNTER,Reach-1         ,437     , 2 , 3 ,1567.3
Set Internal Change=WEST FORK HUNTER,Reach-1         ,437     , 1 , 3 ,1565.17
DSS Import GetInterval= 0
DSS Import GetPeak= 0
DSS Import FillOption= 0

--- WEST FORK HUNTERS CREEK.g01 (geometry) ---

Geom Title=Existing Conditions
Program Version=4.10

River Reach=WEST FORK HUNTER,Reach-1
Reach XY= 30
      2797098.47     10012683.73       2797208.3     10014058.71
      2797018.56     10014542.94      2797068.83     10016559.34
      2797772.27     10017266.82      2797682.61     10017954.15
      2798231.37     10018620.61      2798768.81     10018354.63
      2799338.39     10018534.22      2799468.24     10018829.77
      2799230.88     10019084.78      2799253.23     10019416.68
      2799423.09     10019471.84      2799520.71     10019352.37
      2800168.52     10019724.34      2800905.99     10020624.52
      2801187.53     10021504.16      2801078.02      10022217.4
      2801418.54     10023136.08      2801342.87     10023434.84
      2800929.03     10023613.05      2800911.13     10023792.58
      2801045.52      10023988.8      2802196.77     10024644.45
      2802047.18      10025388.2      2801859.86     10025607.95
      2802165.27     10025935.04      2802465.84     10026860.49
      2803182.32     10026800.01      2803478.68     10026934.32

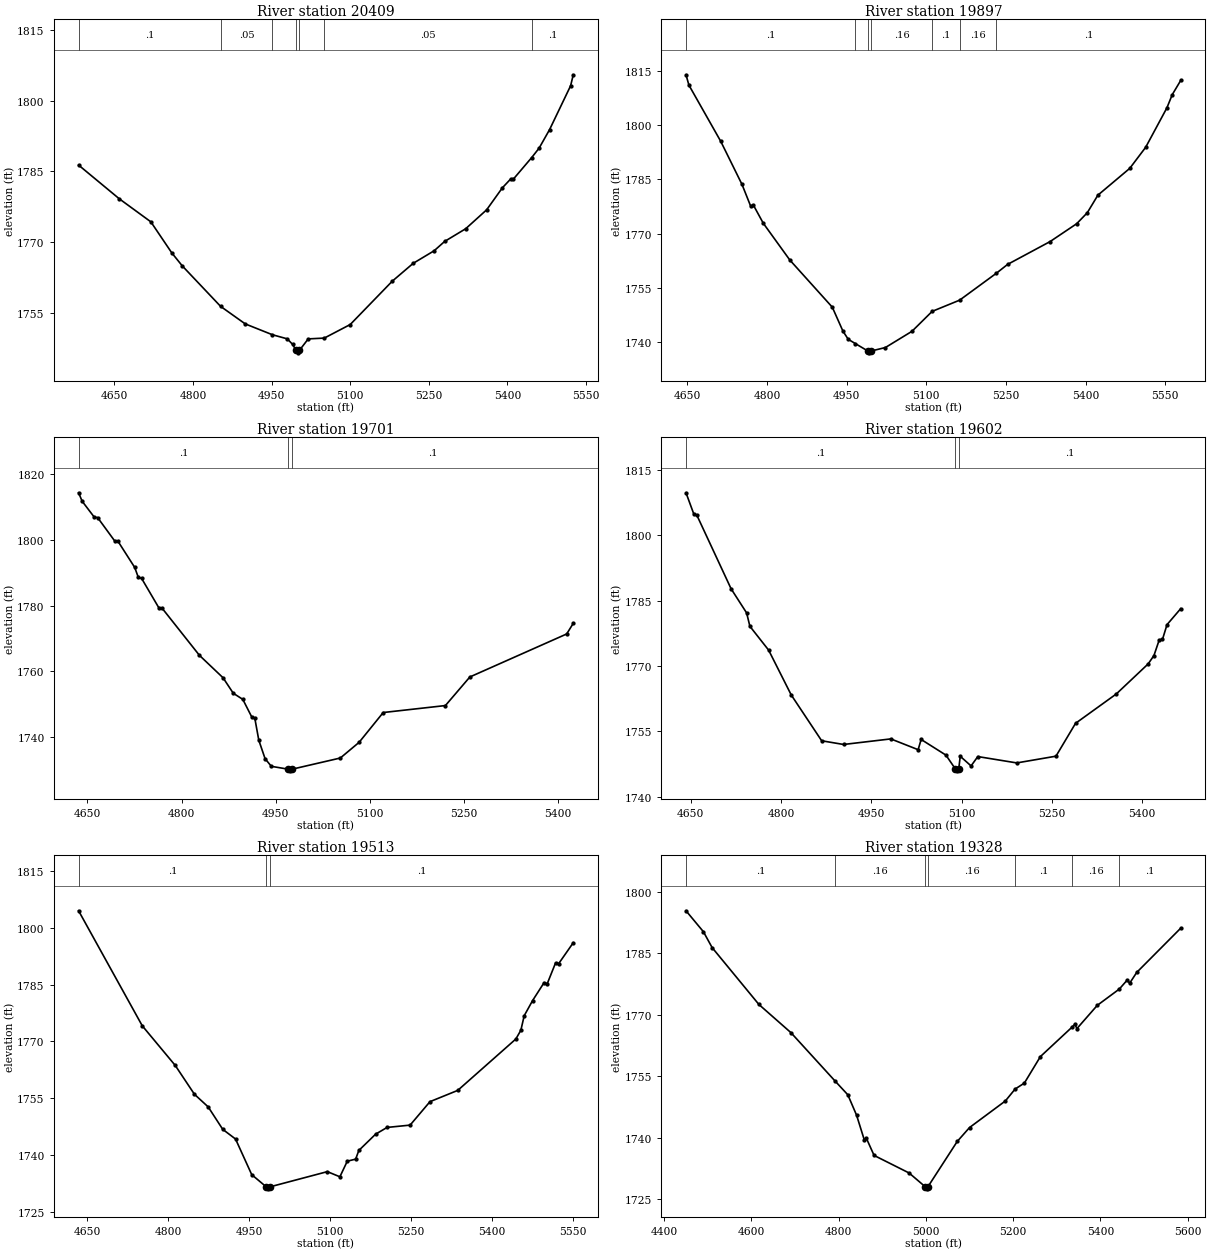
Type RM Length L Ch R = 1 ,20409   ,512,512,512
BEGIN DESCRIPTION:
WEST FORK HUNTERS CREEK 43.0
END DESCRIPTION:
XS GIS Cut Line= 2
      2796680.82     10012712.87      2797623.52     10012673.81
#Sta/Elev= 30
    4582 1786.31  4659.7 1779.15  4719.8 1774.27  4759.8 1767.67  4779.8 1764.91
  4852.8 1756.33  4899.9  1752.6  4951.7  1750.3    4980 1749.43    4990 1748.28
    4997 1746.96  4999.8 1746.46    5003 1746.96    5020 1749.42  5050.6 1749.59
  5100.1 1752.47  5180.2 1761.66  5220.2 1765.46  5260.2 1768.13  5280.2 1770.11
  5320.3  1772.8  5360.3 1776.82  5390.3 1781.49    5406 1783.35    5411  1783.3
  5446.3 1787.92  5460.4 1789.92  5480.4 1793.86  5520.4 1803.14  5525.5 1805.48
#Mann= 7 ,-1 , 0
    4582      .1       0  4852.8     .05       0  4951.7      .1       0
    4997     .07       0    5003      .1       0  5050.6     .05       0
  5446.3      .1       0
Bank Sta=4997,5003
XS Rating Curve= 0 ,0
Exp/Cntr=0.3,0.1

Type RM Length L Ch R = 1 ,19897   ,196,196,196
BEGIN DESCRIPTION:
WEST FORK HUNTERS CREEK 42.0
END DESCRIPTION:
XS GIS Cut Line= 2
      2796732.98      10013200.8      2797664.35     10013185.19
#Sta/Elev= 30
  4647.4 1813.92  4652.9 1811.05  4712.9  1795.5  4752.9 1783.59  4769.3 1777.55
  4774.3 1777.89  4792.9 1772.88  4842.9 1762.71  4922.9 1749.67  4942.9 1743.06
  4952.9 1740.79  4966.5 1739.59  4989.9 1737.55  4992.7 1737.05  4995.9 1737.55
  5022.9 1738.52  5072.9    1743  5110.9 1748.51  5162.6 1751.61  5231.7 1759.04
    5253  1761.5    5333 1767.81    5383 1772.74    5403 1775.77    5423 1780.64
    5483 1788.05    5513 1793.88    5553 1804.79    5563 1808.42  5578.9 1812.34
#Mann= 7 ,-1 , 0
  4647.4      .1       0  4966.5     .16       0  4989.9     .07       0
  4995.9     .16       0  5110.9      .1       0  5162.6     .16       0
  5231.7      .1       0
Bank Sta=4989.9,4995.9
XS Rating Curve= 0 ,0
Exp/Cntr=0.3,0.1

Type RM Length L Ch R = 1 ,19701   ,99,99,99
BEGIN DESCRIPTION:
Mapping XS 96887d0e
END DESCRIPTION:
XS GIS Cut Line= 4
      2796732.99     10013310.18      2796982.96      10013388.3
       2797196.5     10013393.51      2797488.21     10013278.91
#Sta/Elev= 30
  4635.8 1814.31  4641.5 1811.73  4660.9 1806.87  4666.1 1806.78  4693.3 1799.68
  4698.6 1799.56  4725.3  1791.6    4731  1788.6  4736.3 1788.26  4763.5 1779.41
  4768.8 1779.24  4828.5 1764.86  4866.2 1758.03  4882.5 1753.32  4897.7 1751.46
  4911.8 1746.17  4916.8 1745.76  4923.2 1739.03  4933.2 1733.42  4943.2 1731.09
  4970.2 1730.22    4973 1729.72  4976.2 1730.22  5053.2 1733.62  5083.2  1738.4
  5121.6 1747.46  5220.8 1749.58  5259.8 1758.28  5414.2 1771.36  5424.7  1774.6
#Mann= 3 ,-1 , 0
  4635.8      .1       0  4970.2     .07       0  4976.2      .1       0
Bank Sta=4970.2,4976.2
XS Rating Curve= 0 ,0
Exp/Cntr=0.3,0.1

Type RM Length L Ch R = 1 ,19602   ,89,89,89
BEGIN DESCRIPTION:
Mapping XS 24b09dd2
END DESCRIPTION:
XS GIS Cut Line= 4
      2796743.37     10013403.92      2796998.59     10013492.47
      2797160.05     10013487.26      2797519.41     10013336.22
#Sta/Elev= 30
  4642.3 1809.81    4655 1805.02  4660.3 1804.66  4717.2 1787.74    4743 1782.19
  4748.4 1779.12  4779.5 1773.65  4817.1 1763.33  4867.6 1752.81    4904 1751.96
  4982.4 1753.24  5027.8 1750.76  5032.8 1753.11    5074 1749.51  5089.3  1746.4
    5092  1745.9  5095.3  1746.4  5097.7 1749.25  5115.7 1747.03  5126.9 1749.18
  5191.6 1747.72  5256.7 1749.27  5289.2 1756.82  5356.9 1763.57  5409.8 1770.48
  5419.4  1772.4  5428.2    1776  5433.6 1776.12  5441.1  1779.5  5463.8 1783.17
#Mann= 3 ,-1 , 0
  4642.3      .1       0  5089.3     .07       0  5095.3      .1       0
Bank Sta=5089.3,5095.3
XS Rating Curve= 0 ,0
Exp/Cntr=0.3,0.1

Type RM Length L Ch R = 1 ,19513   ,185,185,185
BEGIN DESCRIPTION:
Mapping XS 24499394
END DESCRIPTION:
XS GIS Cut Line= 4
       2796722.5     10013528.92      2796998.59     10013581.01
      2797201.71      10013575.8      2797571.53     10013351.83
#Sta/Elev= 30
  4633.6 1804.48  4751.6 1774.11  4812.7 1763.65  4848.3 1756.03  4873.7 1752.71
  4900.7 1746.78  4924.4 1744.23  4954.4 1734.82  4981.5 1731.58  4984.2 1731.08
  4987.5 1731.58  5094.5 1735.62  5117.7 1734.26  5131.4 1738.38  5146.9 1738.92
  5152.8 1741.21  5183.8  1745.5  5205.1 1747.29  5247.8  1747.9  5284.6 1754.09
  5336.1 1757.07  5443.7 1770.63    5453 1772.94  5459.2 1776.78  5474.7 1780.77
    5496 1785.51  5501.9 1785.24  5517.4 1790.75  5523.2 1790.56  5550.1 1796.05
#Mann= 3 ,-1 , 0
  4633.6      .1       0  4981.5     .07       0  4987.5      .1       0
Bank Sta=4981.5,4987.5
XS Rating Curve= 0 ,0
Exp/Cntr=0.3,0.1

Type RM Length L Ch R = 1 ,19328   ,497,497,497
BEGIN DESCRIPTION:
WEST FORK HUNTERS CREEK 41.0
END DESCRIPTION:
XS GIS Cut Line= 2
      2796628.75     10013674.75      2797758.96      10013768.5
#Sta/Elev= 30
  4449.9 1795.33  4489.8 1790.23  4509.8 1786.36  4617.1  1772.5  4690.4 1765.65
  4791.1 1753.92  4820.9  1750.5    4841 1745.52  4858.5 1739.56  4863.5 1739.89
  4881.1 1735.73  4961.4 1731.45  4998.5 1728.09  5001.3 1727.59  5004.5 1728.09
  5071.7 1739.13  5099.9 1742.52  5182.1    1749  5204.4  1751.9  5225.6 1753.35
  5262.4 1759.81    5335 1766.99  5341.2 1767.65  5346.3 1766.65  5392.8 1772.29
  5443.3 1776.26  5461.9 1778.51  5466.9 1777.66  5483.2 1780.31    5584 1791.08
#Mann= 7 ,-1 , 0
  4449.9      .1       0  4791.1     .16       0  4998.5     .07       0
  5004.5     .16       0  5204.4      .1       0    5335     .16       0
  5443.3      .1       0
Bank Sta=4998.5,5004.5
XS Rating Curve= 0 ,0
Exp/Cntr=0.3,0.1

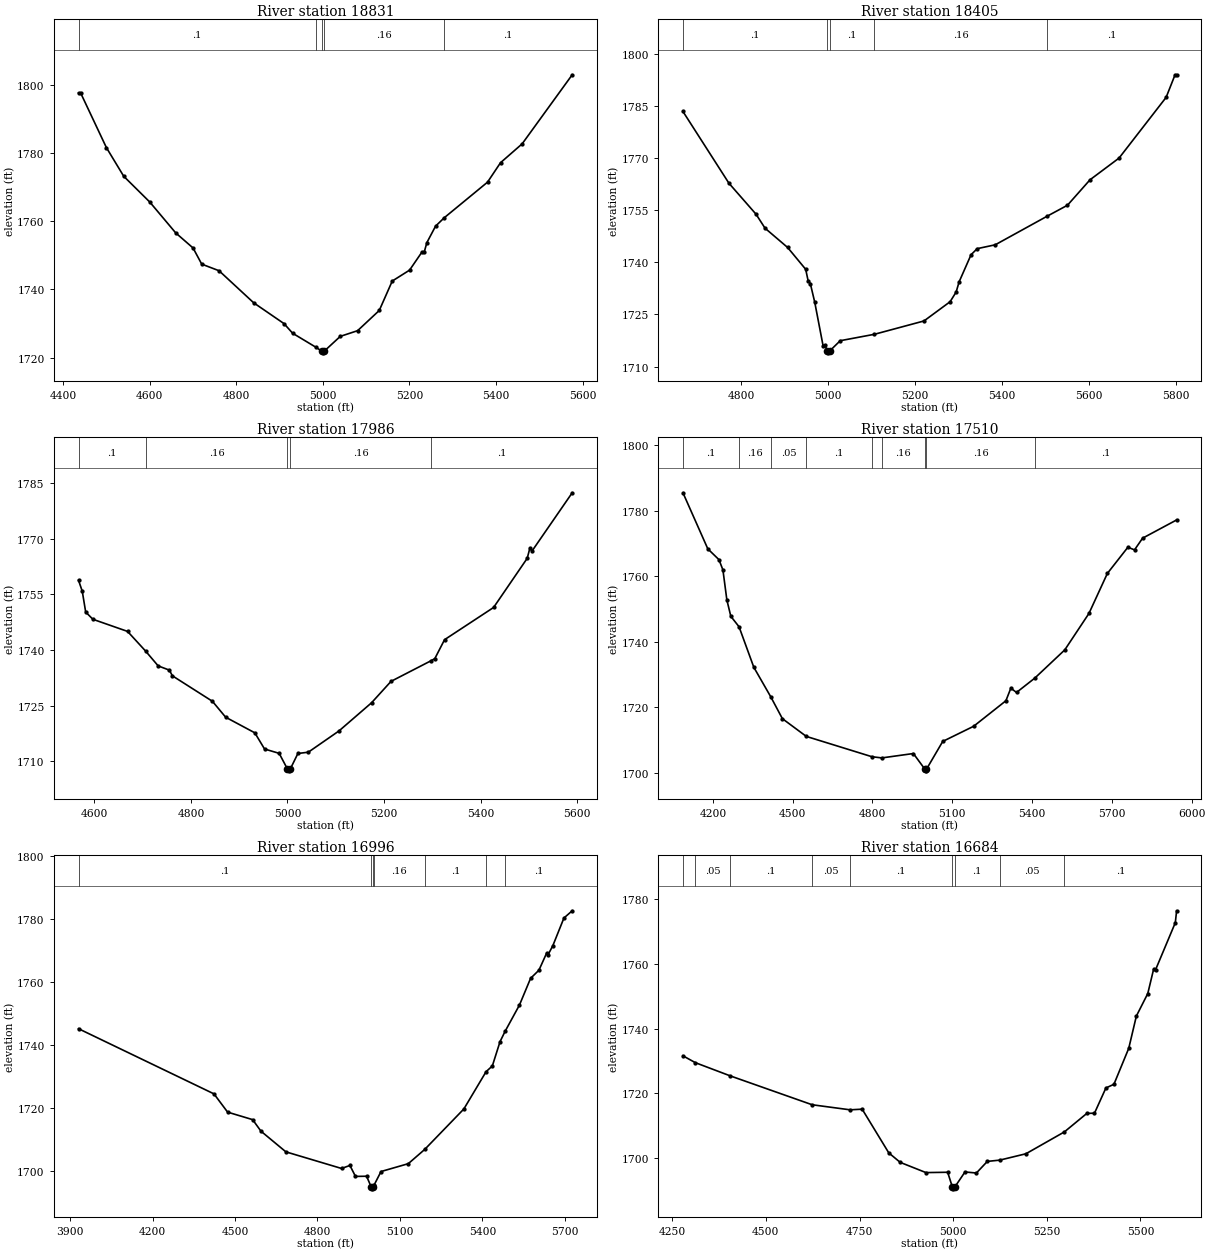
Type RM Length L Ch R = 1 ,18831   ,426,426,426
BEGIN DESCRIPTION:
WEST FORK HUNTERS CREEK 40.0
END DESCRIPTION:
XS GIS Cut Line= 2
      2796634.03     10014206.01      2797774.08      10014195.6
#Sta/Elev= 30
  4435.7 1797.78  4440.4 1797.78  4500.1 1781.67  4540.1 1773.26  4600.1 1765.71
  4660.1 1756.63  4700.2 1752.19  4720.2 1747.45  4760.2 1745.51  4840.2 1736.09
  4910.2 1729.98  4930.2 1727.14  4984.2 1723.01  4997.2 1721.89  4999.9 1721.39
  5003.2 1721.89  5040.2 1726.23  5080.2  1727.9  5130.2 1733.84  5160.2 1742.48
  5200.2 1745.69  5228.8    1751  5233.8 1750.89  5240.2 1753.79  5260.2  1758.6
  5280.2 1761.07  5380.2 1771.53  5410.2 1777.24  5460.2 1782.79  5575.8 1803.08
#Mann= 5 ,-1 , 0
  4435.7      .1       0  4984.2     .16       0  4997.2     .07       0
  5003.2     .16       0  5280.2      .1       0
Bank Sta=4997.2,5003.2
XS Rating Curve= 0 ,0
Exp/Cntr=0.3,0.1

Type RM Length L Ch R = 1 ,18405   ,419,419,419
BEGIN DESCRIPTION:
WEST FORK HUNTERS CREEK 39.0
END DESCRIPTION:
XS GIS Cut Line= 2
      2796696.53     10014482.06      2797790.28     10014784.14
#Sta/Elev= 30
  4666.5  1783.4  4772.2 1762.76  4834.5 1753.85  4855.2 1749.82  4907.1 1744.28
  4948.6    1738  4954.2 1734.71  4959.3 1733.89  4969.4 1728.54  4988.5 1716.07
  4993.7 1716.22  4997.5 1714.47  5000.2 1713.97  5003.5 1714.47    5028 1717.46
  5106.7 1719.31  5220.5 1723.14  5280.6 1728.68  5294.4 1731.46  5301.3  1734.4
  5328.7 1742.19  5342.8 1743.94  5384.3 1745.05  5503.8 1753.29  5550.3 1756.43
  5602.2 1763.76  5668.9    1770  5777.1 1787.47  5797.6 1793.96  5801.2 1793.96
#Mann= 5 ,-1 , 0
  4666.5      .1       0  4997.5     .07       0  5003.5      .1       0
  5106.7     .16       0  5503.8      .1       0
Bank Sta=4997.5,5003.5
XS Rating Curve= 0 ,0
Exp/Cntr=0.3,0.1

Type RM Length L Ch R = 1 ,17986   ,476,476,476
BEGIN DESCRIPTION:
WEST FORK HUNTERS CREEK 38.0
END DESCRIPTION:
XS GIS Cut Line= 3
      2796712.11     10014799.75       2796941.3     10014956.01
      2797680.89     10015049.76
#Sta/Elev= 30
  4567.1 1758.82  4574.8 1755.89  4581.9 1750.27  4596.9 1748.31  4668.7 1745.04
  4705.9 1739.76  4732.1 1735.74  4755.4 1734.59  4761.5 1733.07  4844.5 1726.19
  4871.9  1721.9  4932.4 1717.68  4952.5 1713.32  4982.8 1712.15  4999.9 1707.93
  5002.7 1707.43  5005.9 1707.93  5021.6 1712.11  5043.2 1712.46  5106.7 1718.19
  5174.3  1725.8  5214.6 1731.57  5297.2 1737.11  5305.3  1737.7  5325.5 1742.81
  5427.1  1751.5  5496.8 1764.77  5502.1 1767.43  5507.1  1766.8    5590 1782.44
#Mann= 5 ,-1 , 0
  4567.1      .1       0  4705.9     .16       0  4999.9     .07       0
  5005.9     .16       0  5297.2      .1       0
Bank Sta=4999.9,5005.9
XS Rating Curve= 0 ,0
Exp/Cntr=0.3,0.1

Type RM Length L Ch R = 1 ,17510   ,514,514,514
BEGIN DESCRIPTION:
WEST FORK HUNTERS CREEK 37.0
END DESCRIPTION:
XS GIS Cut Line= 3
      2796498.61     10014784.16      2796910.05     10015377.88
      2797972.56     10015773.72
#Sta/Elev= 30
  4087.4  1785.5  4180.9 1768.36  4222.8 1765.06  4237.7 1761.92  4252.5 1752.75
  4267.4 1747.75  4298.3 1744.55  4353.9 1732.16  4417.4 1723.17  4461.3 1716.46
  4551.3 1711.04  4798.1 1704.83  4835.1 1704.47  4953.8 1705.81  4997.1 1701.02
  4999.9 1700.52  5003.1 1701.02  5064.2 1709.51  5180.4 1714.14  5301.7 1721.94
  5320.3 1725.79  5341.6 1724.47  5410.2 1728.85    5523 1737.48    5614 1748.63
  5683.1 1760.84  5760.3 1768.85  5785.3 1768.05  5815.6 1771.62  5943.6  1777.2
#Mann= 9 ,-1 , 0
  4087.4      .1       0  4298.3     .16       0  4417.4     .05       0
  4551.3      .1       0  4798.1     .05       0  4835.1     .16       0
  4997.1     .07       0  5003.1     .16       0  5410.2      .1       0
Bank Sta=4997.1,5003.1
XS Rating Curve= 0 ,0
Exp/Cntr=0.3,0.1

Type RM Length L Ch R = 1 ,16996   ,312,312,312
BEGIN DESCRIPTION:
WEST FORK HUNTERS CREEK 36.0
END DESCRIPTION:
XS GIS Cut Line= 2
      2795962.15       10016081.       2797738.2     10015815.38
#Sta/Elev= 30
  3930.9 1745.24  4423.6 1724.57  4473.2 1718.78  4564.2  1716.4  4594.5 1712.74
  4685.2 1706.18  4887.7 1700.91  4918.1 1701.87  4938.3 1698.39  4978.7 1698.45
    4996 1694.95  4998.7 1694.45    5002 1694.95  5005.6 1695.58  5031.2 1699.94
  5130.4 1702.43  5190.4 1706.97  5332.6 1719.79  5413.3  1731.6  5436.2 1733.44
  5464.1 1741.13  5482.6 1744.42  5534.9 1752.77  5575.3 1761.22  5605.6  1763.8
  5633.7 1769.23  5638.7 1768.69  5656.2 1771.57  5696.6 1780.36  5726.7 1782.65
#Mann= 7 ,-1 , 0
  3930.9      .1       0    4996     .07       0    5002      .1       0
  5005.6     .16       0  5190.4      .1       0  5413.3     .16       0
  5482.6      .1       0
Bank Sta=4996,5002
XS Rating Curve= 0 ,0
Exp/Cntr=0.3,0.1

Type RM Length L Ch R = 1 ,16684   ,452,452,452
BEGIN DESCRIPTION:
WEST FORK HUNTERS CREEK 35.0
END DESCRIPTION:
XS GIS Cut Line= 2
      2796357.97     10016357.05      2797654.14      10016117.6
#Sta/Elev= 30
  4278.6  1731.6  4311.8 1729.48  4405.4 1725.39  4623.6 1716.51  4724.8 1714.95
  4757.1 1715.15  4828.2 1701.67  4858.7 1698.75  4927.4  1695.6  4985.4  1695.7
  4998.1 1691.09  5000.9 1690.59  5004.1 1691.09  5031.6 1695.79  5062.1 1695.47
  5091.3 1699.05  5124.4 1699.44  5194.3  1701.4    5297 1708.14    5357 1713.85
  5377.4 1713.91  5407.9 1721.69  5429.3 1722.82  5468.9 1733.92  5489.2 1743.85
  5519.7  1750.8  5535.2 1758.28  5540.3 1758.08  5593.2 1772.64  5596.7 1776.31
#Mann= 9 ,-1 , 0
  4278.6      .1       0  4311.8     .05       0  4405.4      .1       0
  4623.6     .05       0  4724.8      .1       0  4998.1     .07       0
  5004.1      .1       0  5124.4     .05       0    5297      .1       0
Bank Sta=4998.1,5004.1
XS Rating Curve= 0 ,0
Exp/Cntr=0.3,0.1

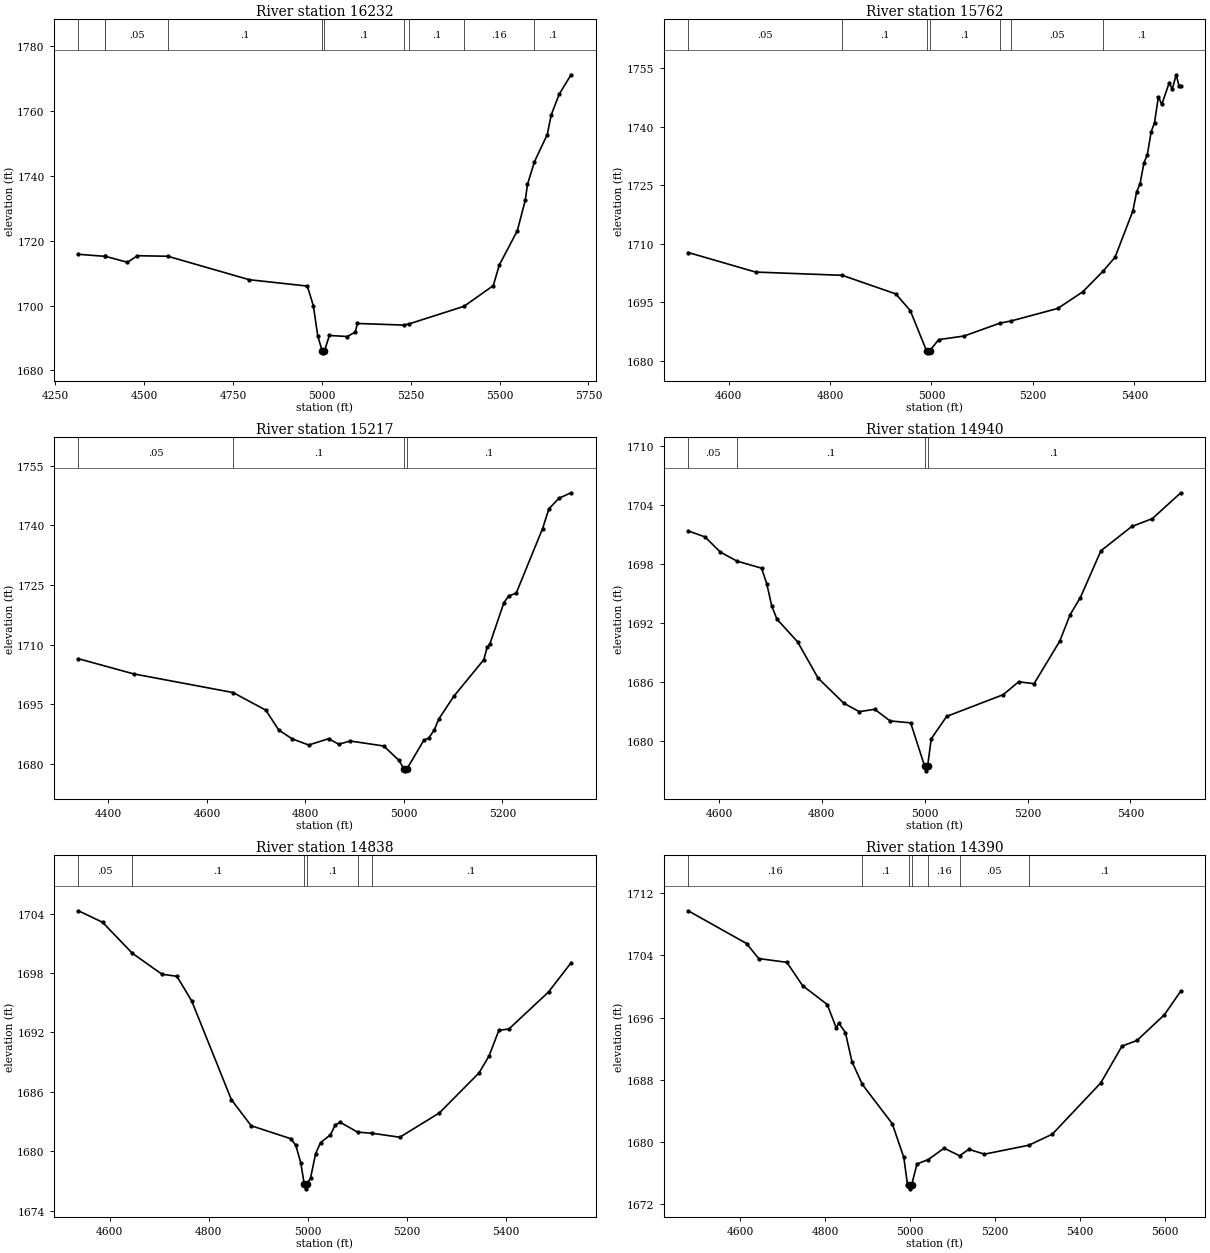
Type RM Length L Ch R = 1 ,16232   ,470,470,470
BEGIN DESCRIPTION:
WEST FORK HUNTERS CREEK 34.0
END DESCRIPTION:
XS GIS Cut Line= 2
      2796503.77     10016961.23      2797748.61     10016351.83
#Sta/Elev= 30
    4315  1715.8  4390.1 1715.16  4390.3 1715.19  4452.7 1713.33  4480.8 1715.36
  4566.3 1715.19  4795.9 1707.96    4959 1706.01  4975.9 1699.94  4988.3 1690.62
    5001 1685.94  5003.7 1685.44    5007 1685.94  5020.9 1690.79  5071.5 1690.47
    5094 1691.85  5099.6 1694.49  5230.5 1693.99  5245.1 1694.35    5400 1699.78
  5482.2 1706.15  5499.1  1712.5  5549.7 1723.02  5572.2 1732.46  5578.4 1737.33
  5597.9 1744.29    5634 1752.67  5645.3 1758.76  5667.8 1765.15    5701  1771.1
#Mann= 10 ,-1 , 0
    4315      .1       0  4390.1     .16       0  4390.3     .05       0
  4566.3      .1       0    5001     .07       0    5007      .1       0
  5230.5     .05       0  5245.1      .1       0    5400     .16       0
  5597.9      .1       0
Bank Sta=5001,5007
XS Rating Curve= 0 ,0
Exp/Cntr=0.3,0.1

Type RM Length L Ch R = 1 ,15762   ,545,545,545
BEGIN DESCRIPTION:
WEST FORK HUNTERS CREEK 33.0
END DESCRIPTION:
XS GIS Cut Line= 2
      2797087.15     10017289.32      2797821.51     10016653.92
#Sta/Elev= 30
  4520.4 1707.76  4653.3 1702.75  4824.1 1701.92  4929.7 1697.15  4958.2 1692.88
  4990.3 1682.56  4993.1 1682.06  4996.3 1682.56  5014.2 1685.44  5064.3 1686.37
    5135 1689.67  5157.1 1690.23  5248.9 1693.43  5298.2 1697.68  5338.6 1703.03
  5361.9 1706.54    5397  1718.4  5404.6 1723.36  5411.2 1725.39  5418.9 1730.74
  5425.5 1732.79  5433.1 1738.71  5439.7    1741  5447.4 1747.69    5454 1745.68
  5468.2 1751.07  5474.9 1749.75  5482.5 1753.29  5487.8  1750.5  5491.5  1750.5
#Mann= 7 ,-1 , 0
  4520.4     .05       0  4824.1      .1       0  4990.3     .07       0
  4996.3      .1       0    5135     .16       0  5157.1     .05       0
  5338.6      .1       0
Bank Sta=4990.3,4996.3
XS Rating Curve= 0 ,0
Exp/Cntr=0.3,0.1

Type RM Length L Ch R = 1 ,15217   ,277,277,277
BEGIN DESCRIPTION:
WEST FORK HUNTERS CREEK 32.0
END DESCRIPTION:
XS GIS Cut Line= 2
      2797118.35     10017456.01      2798102.75     10017278.93
#Sta/Elev= 30
  4339.2 1706.44  4451.1 1702.64  4653.2 1697.94  4719.8  1693.5  4745.7 1688.54
  4773.4 1686.29  4806.7 1684.76  4847.3 1686.35  4867.7 1684.95  4890.9 1685.77
  4959.1 1684.51  4989.6 1680.94  5000.2 1678.77    5003 1678.27  5006.2 1678.77
  5040.4 1685.95  5050.6 1686.52  5061.9 1688.62  5070.9  1691.3  5101.4 1697.02
  5162.3 1706.21  5169.2 1709.39  5174.3 1710.08    5203 1720.52  5213.1 1722.28
  5227.9 1722.87  5281.6 1739.16  5294.4  1744.1  5314.7 1746.77  5339.4 1748.15
#Mann= 4 ,-1 , 0
  4339.2     .05       0  4653.2      .1       0  5000.2     .07       0
  5006.2      .1       0
Bank Sta=5000.2,5006.2
XS Rating Curve= 0 ,0
Exp/Cntr=0.3,0.1

Type RM Length L Ch R = 1 ,14940   ,102,102,102
BEGIN DESCRIPTION:
Mapping XS af68346c
END DESCRIPTION:
XS GIS Cut Line= 2
      2797305.91     10017612.26      2798263.81     10017612.26
#Sta/Elev= 30
  4540.2 1701.37  4572.8 1700.76  4602.8 1699.21  4635.4 1698.29  4682.8 1697.58
  4692.8 1696.02  4702.8  1693.7  4712.8 1692.39  4752.8 1690.09  4792.8 1686.39
  4842.8 1683.84  4872.8 1682.98  4902.8 1683.22  4932.8 1682.04  4972.8 1681.84
  4999.8 1677.46  5002.5 1676.96  5005.8 1677.46  5012.8 1680.22  5042.8  1682.5
  5152.8 1684.71  5182.8 1686.02  5212.8 1685.83  5262.8 1690.16  5282.8 1692.84
  5302.8 1694.59  5342.8 1699.35  5402.8 1701.82  5442.8 1702.62  5498.1 1705.25
#Mann= 4 ,-1 , 0
  4540.2     .05       0  4635.4      .1       0  4999.8     .07       0
  5005.8      .1       0
Bank Sta=4999.8,5005.8
XS Rating Curve= 0 ,0
Exp/Cntr=0.3,0.1

Type RM Length L Ch R = 1 ,14838   ,448,448,448
BEGIN DESCRIPTION:
WEST FORK HUNTERS CREEK 31.0
END DESCRIPTION:
XS GIS Cut Line= 2
      2797279.87     10017716.42      2798274.01     10017706.01
#Sta/Elev= 30
  4537.3 1704.28  4585.9 1703.12  4645.8    1700  4705.9 1697.87  4735.9 1697.67
  4765.9 1695.17  4845.9 1685.21  4885.9 1682.58  4965.9 1681.27  4975.9 1680.61
  4985.9 1678.85  4992.9 1676.71  4995.7 1676.21  4998.9 1676.71  5005.9 1677.34
  5015.9 1679.76  5025.9 1680.88  5045.9 1681.66  5055.9 1682.69  5065.9 1682.92
  5100.8 1681.93  5128.8 1681.83  5185.9 1681.42  5265.9 1683.88  5345.9 1687.92
  5365.9 1689.62  5385.9 1692.22  5405.9 1692.34    5486 1696.08  5531.5 1699.03
#Mann= 6 ,-1 , 0
  4537.3     .05       0  4645.8      .1       0  4992.9     .07       0
  4998.9      .1       0  5100.8     .05       0  5128.8      .1       0
Bank Sta=4992.9,4998.9
XS Rating Curve= 0 ,0
Exp/Cntr=0.3,0.1

Type RM Length L Ch R = 1 ,14390   ,502,502,502
BEGIN DESCRIPTION:
WEST FORK HUNTERS CREEK 30.0
END DESCRIPTION:
XS GIS Cut Line= 3
      2797346.47     10018360.32      2798040.25     10017940.38
       2798318.5     10017728.52
#Sta/Elev= 30
  4477.3 1709.74  4614.8 1705.53  4643.3  1703.6  4709.8 1703.11  4746.7 1700.12
  4804.9 1697.69  4826.2 1694.67  4832.1 1695.29  4847.6 1694.09  4863.1 1690.35
  4887.6 1687.41  4958.1 1682.37  4985.3 1678.03    4994 1674.54  4997.8 1674.49
  5000.5 1673.99  5003.8 1674.49  5016.3 1677.19  5042.9 1677.75  5080.3 1679.22
  5116.7 1678.24  5138.5 1679.07  5175.4 1678.45  5280.1  1679.6  5335.3 1681.02
  5449.4 1687.61  5499.5 1692.34  5534.9 1693.07  5599.3 1696.37    5638 1699.41
#Mann= 7 ,-1 , 0
  4477.3     .16       0  4887.6      .1       0  4997.8     .07       0
  5003.8      .1       0  5042.9     .16       0  5116.7     .05       0
  5280.1      .1       0
Bank Sta=4997.8,5003.8
XS Rating Curve= 0 ,0
Exp/Cntr=0.3,0.1

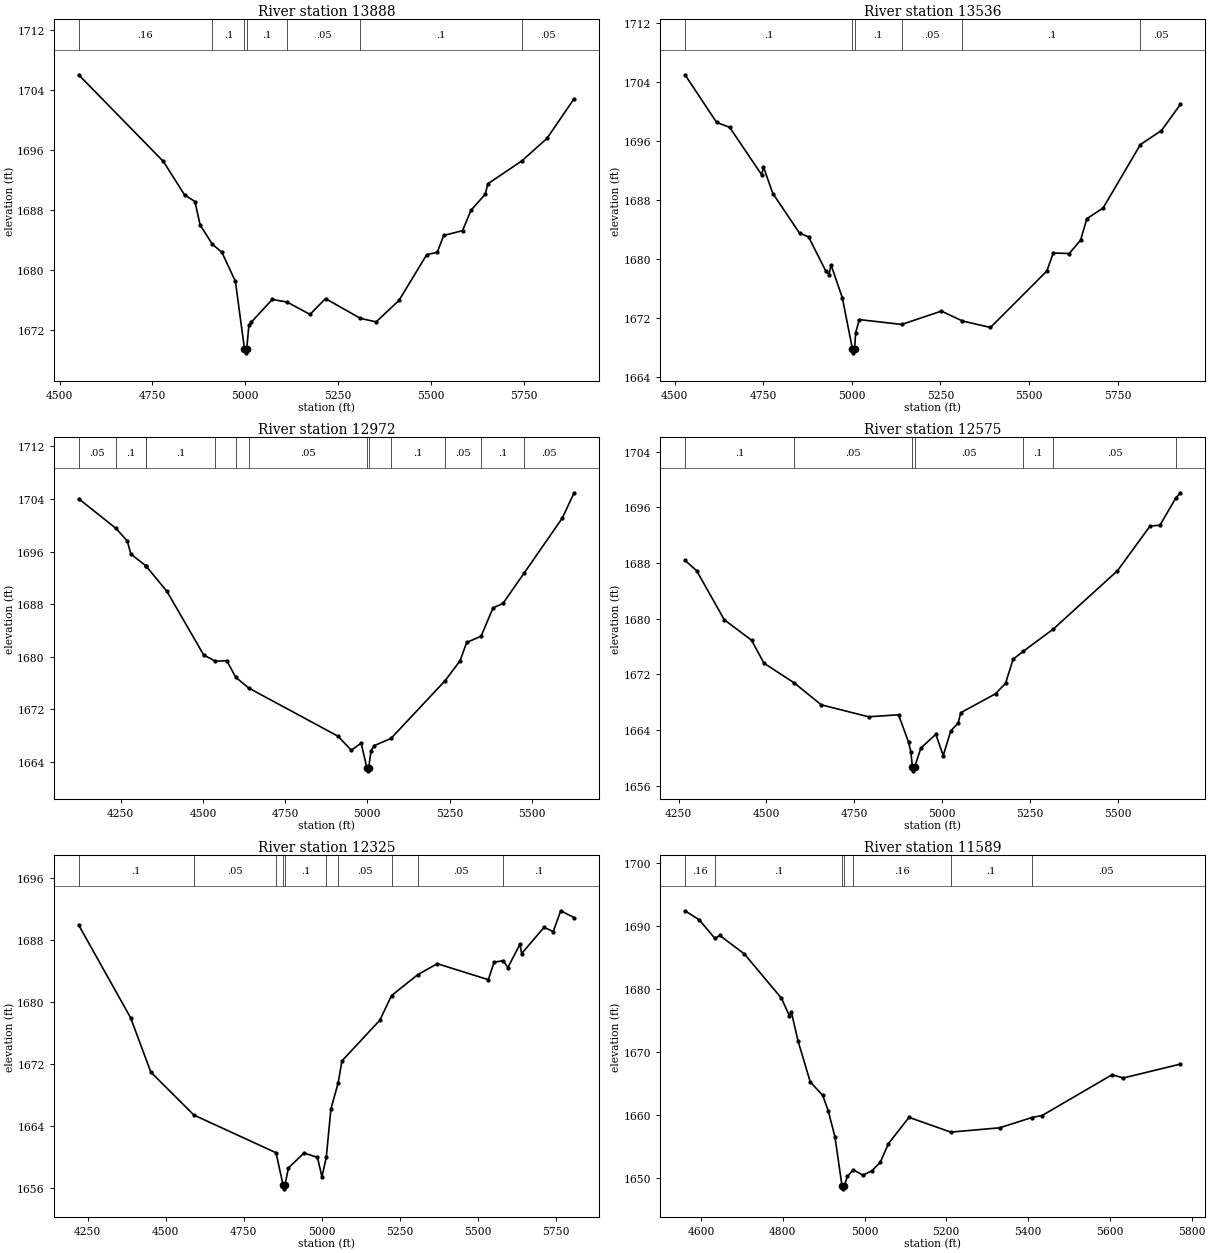
Type RM Length L Ch R = 1 ,13888   ,352,352,352
BEGIN DESCRIPTION:
WEST FORK HUNTERS CREEK 29.0
END DESCRIPTION:
XS GIS Cut Line= 3
       2797649.6     10018700.82       2798191.3     10018331.01
      2798482.42     10017717.58
#Sta/Elev= 30
  4551.1 1706.09  4779.5 1694.53  4836.4 1690.09  4864.5 1689.19  4878.4 1686.07
    4911 1683.53  4937.2  1682.4  4973.5 1678.55    4998 1669.52  5000.7 1669.02
    5004 1669.52  5009.8  1672.7  5015.9 1673.09  5072.8 1676.14  5112.9 1675.79
  5174.4 1674.14  5216.3 1676.25  5310.5 1673.61  5352.7 1673.15  5414.3 1676.01
  5489.1 1682.12  5517.4 1682.42  5534.6 1684.67  5585.5 1685.31  5608.3 1688.03
  5646.7 1690.18  5653.7 1691.56    5745  1694.6  5812.8  1697.6    5886  1702.9
#Mann= 7 ,-1 , 0
  4551.1     .16       0    4911      .1       0    4998     .07       0
    5004      .1       0  5112.9     .05       0  5310.5      .1       0
    5745     .05       0
Bank Sta=4998,5004
XS Rating Curve= 0 ,0
Exp/Cntr=0.3,0.1

Type RM Length L Ch R = 1 ,13536   ,564,564,564
BEGIN DESCRIPTION:
WEST FORK HUNTERS CREEK 28.0
END DESCRIPTION:
XS GIS Cut Line= 2
      2798154.82     10019081.05      2798592.35     10017752.86
#Sta/Elev= 30
  4529.1 1704.99  4618.2 1698.54  4655.2 1697.86  4745.3 1691.44  4750.6 1692.48
  4777.1 1688.88  4852.7 1683.49  4877.7 1683.02  4926.4 1678.38  4935.9  1677.9
  4941.2 1679.22    4973 1674.77  5001.8 1667.78  5004.5 1667.28  5007.8 1667.78
  5010.6 1669.99  5021.1 1671.79  5140.6 1671.13  5252.8 1672.94  5312.1  1671.6
  5391.3 1670.72  5550.2 1678.37  5568.6 1680.82  5613.7 1680.75  5645.5 1682.56
  5663.4 1685.48    5709 1686.91  5814.5 1695.53  5873.9 1697.43  5927.5 1700.99
#Mann= 6 ,-1 , 0
  4529.1      .1       0  5001.8     .07       0  5007.8      .1       0
  5140.6     .05       0  5312.1      .1       0  5814.5     .05       0
Bank Sta=5001.8,5007.8
XS Rating Curve= 0 ,0
Exp/Cntr=0.3,0.1

Type RM Length L Ch R = 1 ,12972   ,397,397,397
BEGIN DESCRIPTION:
WEST FORK HUNTERS CREEK 27.0
END DESCRIPTION:
XS GIS Cut Line= 3
      2798472.53     10019169.59      2798774.63     10018476.84
      2798722.61      10017727.8
#Sta/Elev= 30
  4122.1 1704.03  4235.7 1699.52  4269.7 1697.62  4281.2  1695.6  4325.8 1693.86
  4327.5 1693.76  4390.3 1689.97  4502.3 1680.28  4538.2 1679.31  4572.5 1679.41
  4599.7 1676.89  4639.2 1675.25    4911 1667.92  4951.1 1665.79  4981.2 1666.87
  4998.3 1663.16    5001 1662.66  5004.3 1663.16  5011.3 1665.74  5021.3  1666.5
  5071.8 1667.58  5236.2 1676.35  5281.9 1679.39    5302 1682.17    5346 1683.13
  5382.2 1687.43  5412.3  1688.1  5476.9 1692.73  5592.7 1701.07  5628.7 1704.93
#Mann= 13 ,-1 , 0
  4122.1     .05       0  4235.7      .1       0  4325.8     .05       0
  4327.5      .1       0  4538.2     .05       0  4599.7      .1       0
  4639.2     .05       0  4998.3     .04       0  5004.3     .05       0
  5071.8      .1       0  5236.2     .05       0    5346      .1       0
  5476.9     .05       0
Bank Sta=4998.3,5004.3
XS Rating Curve= 0 ,0
Exp/Cntr=0.3,0.1

Type RM Length L Ch R = 1 ,12575   ,250,250,250
BEGIN DESCRIPTION:
WEST FORK HUNTERS CREEK 26.0
END DESCRIPTION:
XS GIS Cut Line= 2
      2798654.84     10018987.26      2799597.56     10017940.36
#Sta/Elev= 30
  4268.4 1688.38  4301.5 1686.89    4380 1679.85  4457.7 1676.91  4492.8 1673.62
    4579 1670.78  4655.8 1667.64  4790.3 1665.92  4875.5 1666.21  4903.9  1662.3
  4910.6 1660.88  4915.1 1658.66  4917.9 1658.16  4921.1 1658.66    4939 1661.43
  4981.6 1663.41  5002.6 1660.35  5024.2 1663.89  5045.2 1665.04  5052.6 1666.51
  5151.3 1669.22  5179.7 1670.72  5201.4 1674.18  5230.4 1675.33  5315.1 1678.49
  5498.1 1686.89  5590.8 1693.31  5618.8 1693.42  5663.7 1697.31  5677.2 1698.08
#Mann= 7 ,-1 , 0
  4268.4      .1       0    4579     .05       0  4915.1    .035       0
  4921.1     .05       0  5230.4      .1       0  5315.1     .05       0
  5663.7      .1       0
Bank Sta=4915.1,4921.1
XS Rating Curve= 0 ,0
Exp/Cntr=0.3,0.1

Type RM Length L Ch R = 1 ,12325   ,736,736,736
BEGIN DESCRIPTION:
WEST FORK HUNTERS CREEK 24.0
END DESCRIPTION:
XS GIS Cut Line= 3
      2798759.02     10019049.74      2799693.72     10018290.86
      2799839.13     10017937.71
#Sta/Elev= 30
  4221.2 1689.99  4387.9 1677.99  4452.3    1671  4590.2 1665.46    4853  1660.6
  4875.6 1656.44  4878.3 1655.94  4881.6 1656.44  4892.9 1658.64  4942.5 1660.56
  4985.6 1660.01    5000 1657.49    5014 1660.04  5028.7 1666.25  5052.1 1669.63
  5063.9 1672.44  5185.3  1677.7  5222.8 1680.88  5306.9 1683.58  5369.2 1684.99
  5532.6 1682.93  5551.1 1685.18  5580.2 1685.39  5595.1 1684.49  5633.8  1687.5
  5639.2  1686.3    5711 1689.68  5740.4 1689.14  5764.3 1691.82  5807.1 1690.94
#Mann= 10 ,-1 , 0
  4221.2      .1       0  4590.2     .05       0    4853      .1       0
  4875.6     .07       0  4881.6      .1       0    5014     .16       0
  5052.1     .05       0  5222.8      .1       0  5306.9     .05       0
  5580.2      .1       0
Bank Sta=4875.6,4881.6
XS Rating Curve= 0 ,0
Exp/Cntr=0.3,0.1

Type RM Length L Ch R = 1 ,11589   ,825,825,825
BEGIN DESCRIPTION:
WEST FORK HUNTERS CREEK 23.0
END DESCRIPTION:
XS GIS Cut Line= 3
      2798783.97     10019207.53      2799652.05      10019110.3
      2799826.71     10018820.59
#Sta/Elev= 30
  4560.9 1692.37  4595.6 1690.94    4634    1688  4645.9 1688.47  4706.3 1685.52
  4796.9 1678.52  4815.8 1675.79  4820.8 1676.41  4837.1 1671.81  4867.3 1665.26
  4897.5 1663.17    4911 1660.75  4927.7 1656.56  4944.8 1648.85  4947.6 1648.35
  4950.8 1648.85  4957.9 1650.31  4972.4 1651.36  4996.2 1650.51  5018.2 1651.22
  5038.4 1652.54  5058.5 1655.51  5108.8 1659.67  5210.8 1657.33  5330.2 1658.01
  5409.3 1659.64  5434.4 1659.96  5605.6 1666.42  5632.8  1665.9  5772.7  1668.1
#Mann= 7 ,-1 , 0
  4560.9     .16       0    4634      .1       0  4944.8     .07       0
  4950.8      .1       0  4972.4     .16       0  5210.8      .1       0
  5409.3     .05       0
Bank Sta=4944.8,4950.8
XS Rating Curve= 0 ,0
Exp/Cntr=0.3,0.1

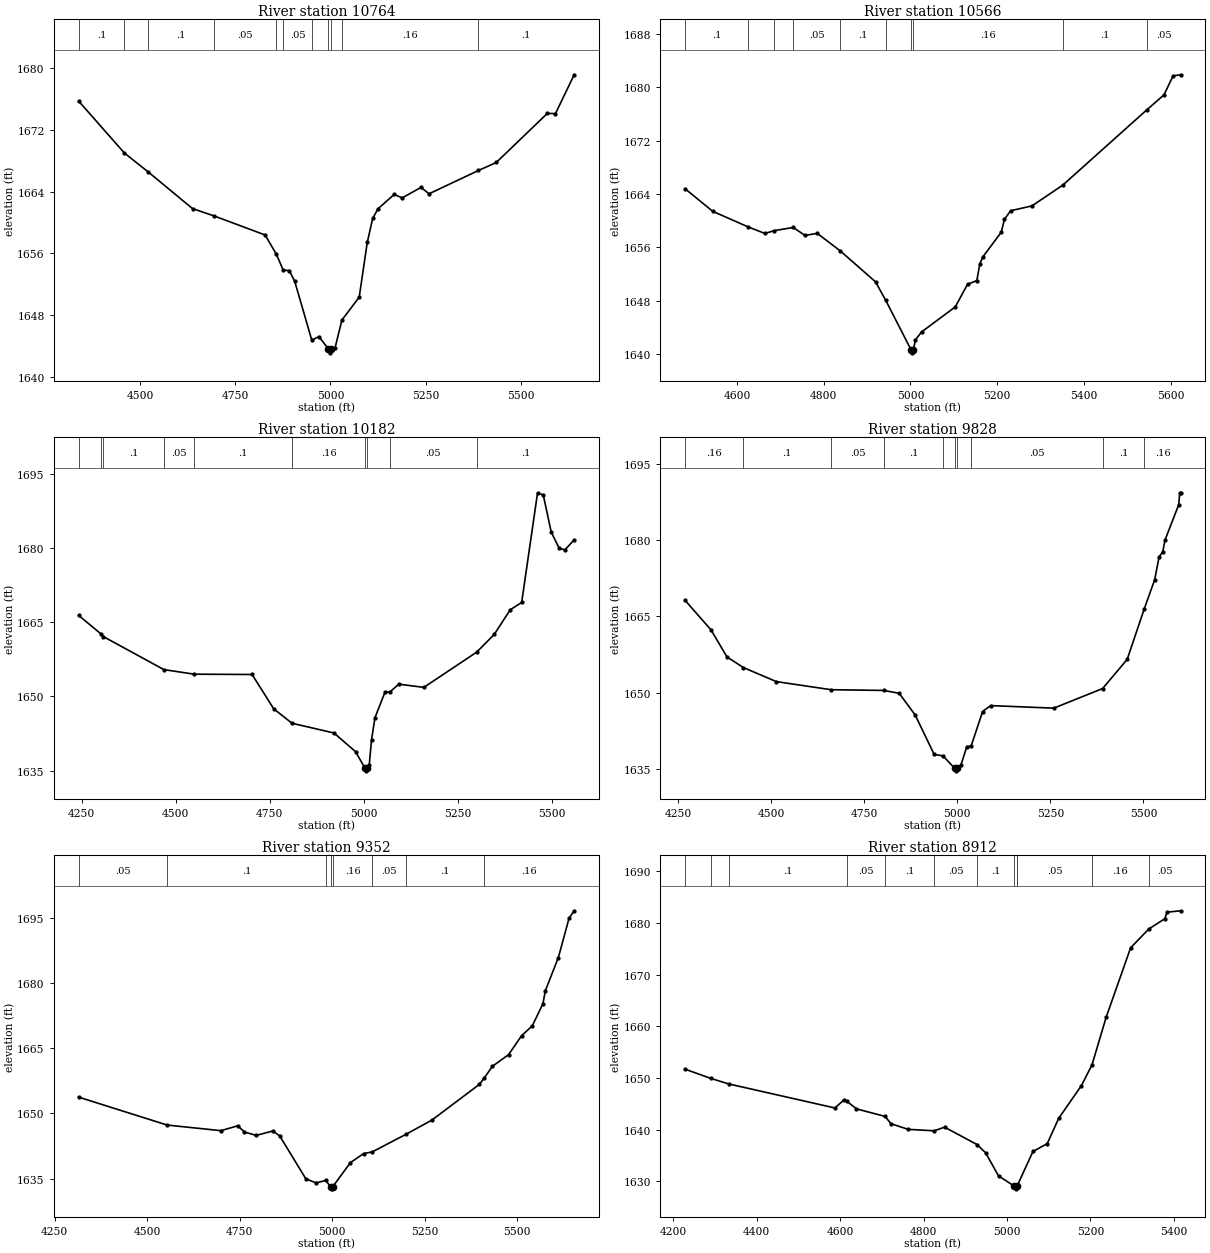
Type RM Length L Ch R = 1 ,10764   ,198,198,198
BEGIN DESCRIPTION:
WEST FORK HUNTERS CREEK 22.0
END DESCRIPTION:
XS GIS Cut Line= 2
      2799206.93     10019955.99       2800123.5     10019029.02
#Sta/Elev= 30
  4337.5 1675.74    4458    1669  4519.4  1666.6  4637.1  1661.8  4692.6 1660.87
  4828.1 1658.38  4857.8 1655.87  4875.6 1653.83  4891.7 1653.76  4905.9 1652.38
  4950.8 1644.75  4969.5  1645.2  4994.8  1643.6  4997.6  1643.1  5000.8  1643.6
    5012 1643.74  5030.1 1647.35  5075.6 1650.32  5096.8 1657.42    5111 1660.52
  5125.1 1661.78  5167.5 1663.63  5188.7 1663.19  5238.2 1664.55  5259.4 1663.72
  5389.2 1666.74  5436.2 1667.78  5570.6 1674.15  5591.8 1674.11  5641.1 1679.15
#Mann= 11 ,-1 , 0
  4337.5      .1       0    4458     .05       0  4519.4      .1       0
  4692.6     .05       0  4857.8      .1       0  4875.6     .05       0
  4950.8      .1       0  4994.8     .07       0  5000.8      .1       0
  5030.1     .16       0  5389.2      .1       0
Bank Sta=4994.8,5000.8
XS Rating Curve= 0 ,0
Exp/Cntr=0.3,0.1

Type RM Length L Ch R = 1 ,10566   ,384,384,384
BEGIN DESCRIPTION:
WEST FORK HUNTERS CREEK 21.0
END DESCRIPTION:
XS GIS Cut Line= 2
       2799462.1      10019997.7      2800238.19     10019159.11
#Sta/Elev= 30
  4480.4 1664.78  4544.2 1661.39  4626.3 1659.05  4664.4 1658.08  4685.9  1658.5
  4729.7 1658.98  4756.8 1657.79  4785.2 1658.09  4838.3 1655.46  4919.5 1650.83
  4943.1 1648.05    5001 1640.69  5003.8 1640.19    5007 1640.69  5011.4 1642.13
  5025.6 1643.32  5103.3 1647.07  5131.6 1650.46  5153.1 1651.02    5160 1653.53
  5167.1 1654.58  5209.3 1658.26  5216.7 1660.18  5230.8 1661.48  5280.2 1662.21
    5351 1665.31  5544.4 1676.57  5584.6 1678.85  5605.6  1681.7    5623 1681.86
#Mann= 10 ,-1 , 0
  4480.4      .1       0  4626.3     .05       0  4685.9      .1       0
  4729.7     .05       0  4838.3      .1       0  4943.1     .16       0
    5001     .07       0    5007     .16       0    5351      .1       0
  5544.4     .05       0
Bank Sta=5001,5007
XS Rating Curve= 0 ,0
Exp/Cntr=0.3,0.1

Type RM Length L Ch R = 1 ,10182   ,354,354,354
BEGIN DESCRIPTION:
WEST FORK HUNTERS CREEK 20.0
END DESCRIPTION:
XS GIS Cut Line= 2
      2799535.08     10020138.28      2800643.92     10019425.08
#Sta/Elev= 30
  4241.6 1666.38  4301.4 1662.61  4307.7 1662.08  4468.4 1655.43    4549  1654.5
  4703.1 1654.44  4760.6 1647.51  4809.3 1644.59  4921.1 1642.62  4978.5 1638.84
  5003.6 1635.48  5006.3 1634.98  5009.6 1635.48  5014.8 1636.15  5020.8  1641.2
    5030 1645.71  5057.1 1650.96  5069.2 1650.88  5093.4 1652.48  5160.1 1651.84
  5300.9 1658.97  5347.7 1662.57  5389.9 1667.52  5420.3 1668.98  5462.6 1691.14
  5477.8 1690.68  5498.9 1683.22    5520 1679.94  5535.2 1679.61    5560 1681.63
#Mann= 10 ,-1 , 0
  4241.6      .1       0  4301.4     .05       0  4307.7      .1       0
  4468.4     .05       0    4549      .1       0  4809.3     .16       0
  5003.6     .07       0  5009.6     .16       0  5069.2     .05       0
  5300.9      .1       0
Bank Sta=5003.6,5009.6
XS Rating Curve= 0 ,0
Exp/Cntr=0.3,0.1

Type RM Length L Ch R = 1 ,9828    ,476,476,476
BEGIN DESCRIPTION:
WEST FORK HUNTERS CREEK 19.0
END DESCRIPTION:
XS GIS Cut Line= 2
      2799722.51     10020393.53       2800868.4     10019716.41
#Sta/Elev= 30
  4268.9 1668.14  4338.5 1662.35  4381.4 1657.04  4425.2 1654.96  4514.1 1652.19
  4661.1  1650.6  4802.3 1650.46  4843.8  1649.9  4886.7 1645.66  4937.9 1637.89
  4961.6 1637.61    4993 1635.17  4995.7 1634.67    4999 1635.17  5009.5 1635.75
  5025.1 1639.33  5037.5 1639.61    5068 1646.32  5089.5 1647.48  5259.2 1646.98
  5390.3 1650.83  5456.3 1656.55  5502.3  1666.5  5530.3 1672.23    5542  1676.7
  5551.9 1677.68  5557.7 1679.93  5594.7 1686.93  5597.6 1689.27  5599.9 1689.27
#Mann= 10 ,-1 , 0
  4268.9     .16       0  4425.2      .1       0  4661.1     .05       0
  4802.3      .1       0  4961.6     .16       0    4993     .07       0
    4999     .16       0  5037.5     .05       0  5390.3      .1       0
  5502.3     .16       0
Bank Sta=4993,4999
XS Rating Curve= 0 ,0
Exp/Cntr=0.3,0.1

Type RM Length L Ch R = 1 ,9352    ,440,440,440
BEGIN DESCRIPTION:
WEST FORK HUNTERS CREEK 18.0
END DESCRIPTION:
XS GIS Cut Line= 3
      2800040.25     10020560.17      2800623.59     10020367.47
      2801194.95     10019920.76
#Sta/Elev= 30
    4315 1653.75  4554.3 1647.33  4699.8 1646.04  4744.9 1647.16  4763.3 1645.73
    4795 1644.95  4839.7 1645.96  4858.5 1644.85  4929.3 1634.96  4957.2 1634.03
  4982.9 1634.61    4996 1633.17  4998.8 1632.67    5002 1633.17  5049.8  1638.7
  5085.6 1640.79  5108.5 1641.15  5200.1 1645.21  5270.1 1648.48  5398.5 1656.69
  5411.3 1658.13  5433.8 1660.85  5477.2 1663.51  5512.4 1667.86  5541.4 1670.14
  5570.2 1675.22  5576.6  1678.2  5611.9 1685.84  5640.8 1694.88  5654.6 1696.58
#Mann= 8 ,-1 , 0
    4315     .05       0  4554.3      .1       0  4982.9     .16       0
    4996     .07       0    5002     .16       0  5108.5     .05       0
  5200.1      .1       0  5411.3     .16       0
Bank Sta=4996,5002
XS Rating Curve= 0 ,0
Exp/Cntr=0.3,0.1

Type RM Length L Ch R = 1 ,8912    ,427,427,427
BEGIN DESCRIPTION:
WEST FORK HUNTERS CREEK 17.0
END DESCRIPTION:
XS GIS Cut Line= 2
      2800170.47     10020841.42       2801321.5     10020549.76
#Sta/Elev= 30
  4228.7  1651.7  4290.2 1649.92  4333.1 1648.85  4587.7  1644.2  4609.8  1645.8
  4616.3  1645.5  4639.3 1644.03    4708 1642.57  4721.8 1641.17  4763.1 1640.07
  4825.4 1639.79  4850.5 1640.49  4928.3 1637.13  4948.8 1635.54  4979.7 1631.07
    5018 1629.07  5020.7 1628.57    5024 1629.07  5024.7 1629.19  5062.2 1635.79
  5096.5 1637.31  5124.1 1642.23  5178.4 1648.53  5203.8 1652.56  5237.6 1661.73
  5296.2 1675.16  5339.8  1678.8  5378.2 1680.78  5383.4 1682.05  5416.1 1682.32
#Mann= 12 ,-1 , 0
  4228.7      .1       0  4290.2     .05       0  4333.1      .1       0
  4616.3     .05       0    4708      .1       0  4825.4     .05       0
  4928.3      .1       0    5018     .07       0    5024      .1       0
  5024.7     .05       0  5203.8     .16       0  5339.8     .05       0
Bank Sta=5018,5024
XS Rating Curve= 0 ,0
Exp/Cntr=0.3,0.1