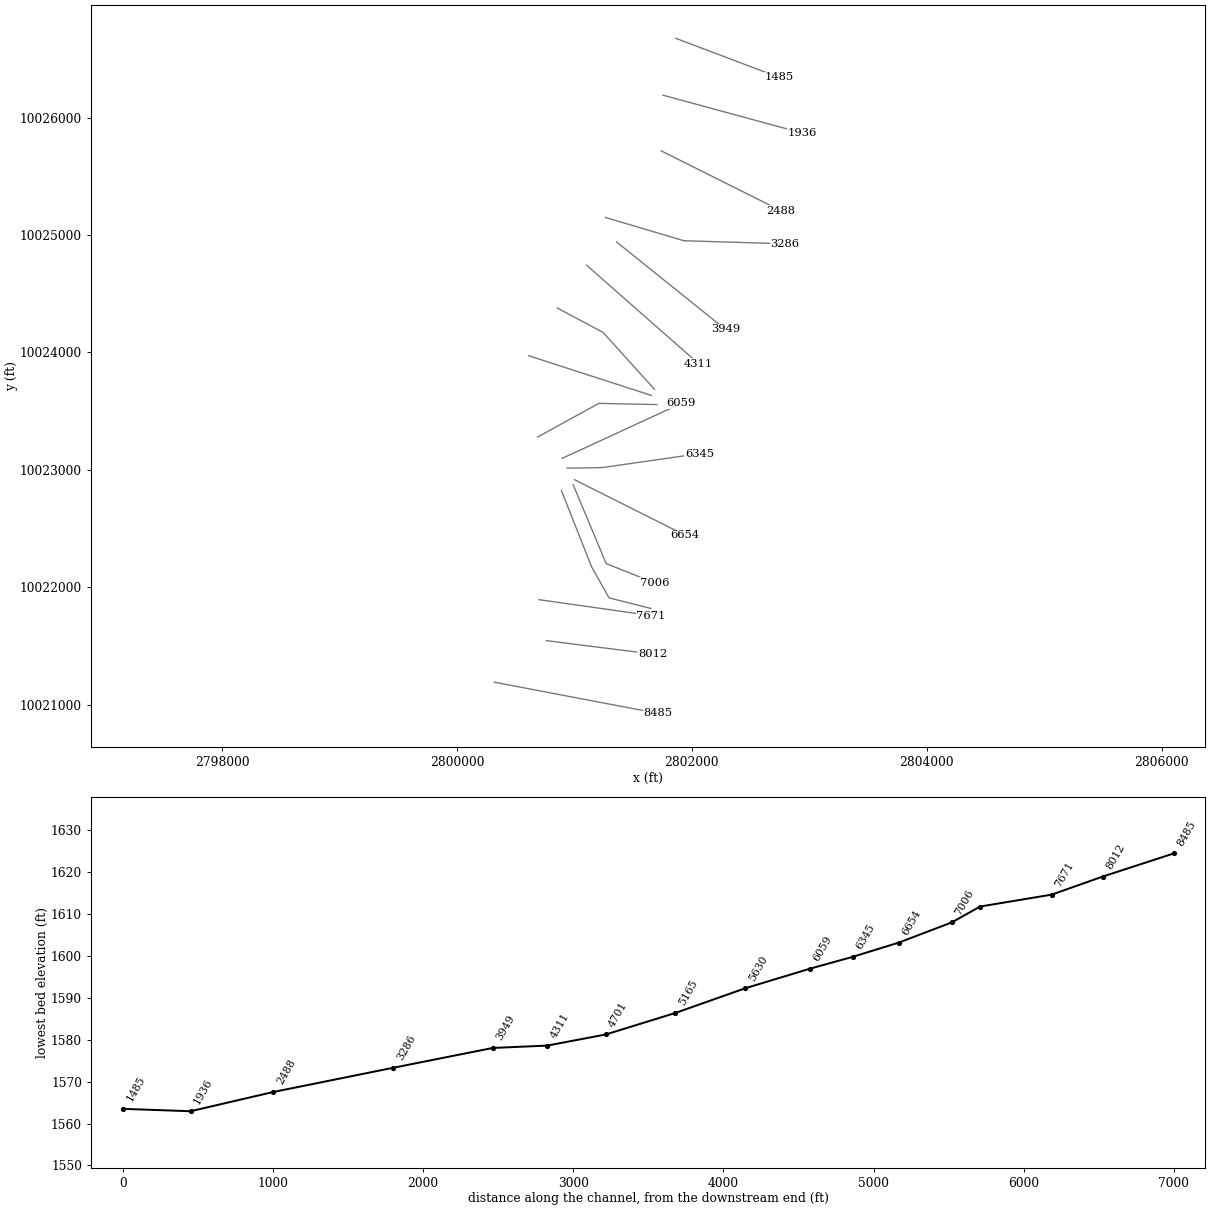
HEC-RAS study WEST FORK HUNTERS CREEK.prj: WEST FORK HUNTERS CREEK Base Level Engineering

--- WEST FORK HUNTERS CREEK.g01 (geometry) --- (continued)

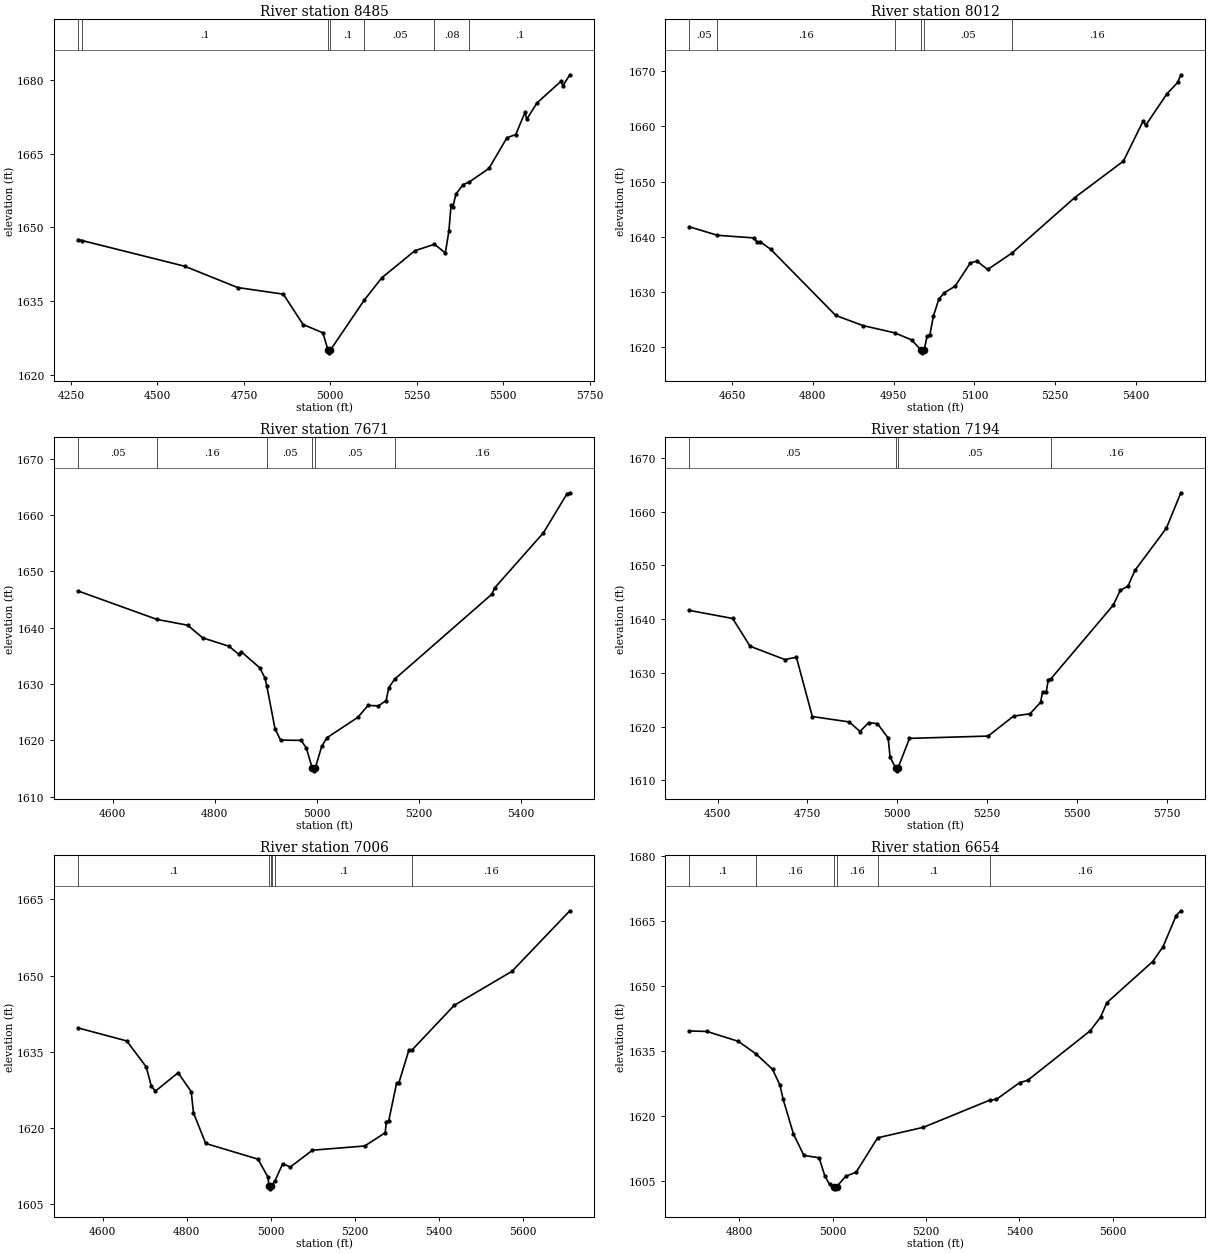
Type RM Length L Ch R = 1 ,8485    ,473,473,473
BEGIN DESCRIPTION:
WEST FORK HUNTERS CREEK 16.0
END DESCRIPTION:
XS GIS Cut Line= 2
      2800316.33     10021190.38      2801712.08     10020924.77
#Sta/Elev= 30
  4271.6 1647.52  4281.9 1647.32  4579.2 1642.08  4731.9 1637.75    4864  1636.4
  4921.2 1630.22  4978.5 1628.52  4993.5 1624.95  4996.3 1624.45  4999.5 1624.95
  5098.6 1635.24  5149.2 1639.76  5244.6 1645.25  5301.1 1646.56  5332.4 1644.78
  5342.6 1649.16    5349 1654.51  5354.1 1654.08    5363 1656.76  5383.3 1658.67
  5402.3 1659.27  5458.5    1662  5510.6 1668.25    5536  1668.9  5562.8 1673.41
  5567.9 1672.02  5597.1 1675.31  5667.2 1679.77  5672.3 1678.84  5692.4 1681.07
#Mann= 7 ,-1 , 0
  4271.6     .05       0  4281.9      .1       0  4993.5     .07       0
  4999.5      .1       0  5098.6     .05       0  5301.1     .08       0
  5402.3      .1       0
Bank Sta=4993.5,4999.5
XS Rating Curve= 0 ,0
Exp/Cntr=0.3,0.1

Type RM Length L Ch R = 1 ,8012    ,341,341,341
BEGIN DESCRIPTION:
WEST FORK HUNTERS CREEK 15.0
END DESCRIPTION:
XS GIS Cut Line= 2
      2800759.02     10021544.55      2801664.31     10021430.09
#Sta/Elev= 30
  4570.9 1641.79  4622.8 1640.25  4691.3 1639.77  4696.7 1638.96  4701.7  1639.1
  4721.5 1637.74  4842.5 1625.72  4892.9 1623.89  4951.8 1622.57  4983.6 1621.28
  5000.8 1619.44  5003.5 1618.94  5006.8 1619.44  5012.3 1622.01  5017.4 1622.24
  5023.9  1625.6    5034 1628.69  5044.1 1629.83  5064.2 1631.02  5092.5 1635.24
  5104.6 1635.57  5124.7 1634.05  5170.4 1637.07    5286 1647.06  5376.7 1653.69
  5413.2 1660.92  5418.3 1660.21  5457.3 1665.86  5477.5 1667.97  5483.4 1669.35
#Mann= 6 ,-1 , 0
  4570.9     .05       0  4622.8     .16       0  4951.8     .05       0
  5000.8     .04       0  5006.8     .05       0  5170.4     .16       0
Bank Sta=5000.8,5006.8
XS Rating Curve= 0 ,0
Exp/Cntr=0.3,0.1

Type RM Length L Ch R = 1 ,7671    ,477,477,477
BEGIN DESCRIPTION:
WEST FORK HUNTERS CREEK 14.0
END DESCRIPTION:
XS GIS Cut Line= 2
      2800696.49     10021893.51      2801649.62     10021758.09
#Sta/Elev= 30
  4533.2 1646.52  4687.1 1641.49  4747.3 1640.46  4776.5 1638.22  4828.1 1636.73
  4847.4  1635.3  4852.4 1635.74  4888.7 1632.88  4898.8 1631.05  4902.3 1629.64
  4918.3 1622.09  4929.1 1620.07  4969.5 1620.01  4979.6 1618.69  4991.2 1615.11
    4994 1614.61  4997.2 1615.11  5009.9 1618.98    5020 1620.48  5080.6 1624.11
  5100.8 1626.23    5121 1626.14    5136 1627.09  5141.2 1629.38  5152.9  1630.9
  5343.2 1645.97  5348.7 1647.09  5444.2 1656.87  5490.5 1663.81  5495.9 1663.97
#Mann= 6 ,-1 , 0
  4533.2     .05       0  4687.1     .16       0  4902.3     .05       0
  4991.2     .04       0  4997.2     .05       0  5152.9     .16       0
Bank Sta=4991.2,4997.2
XS Rating Curve= 0 ,0
Exp/Cntr=0.3,0.1

Type RM Length L Ch R = 1 ,7194    ,188,188,188
BEGIN DESCRIPTION:
Mapping XS d3e756ee
END DESCRIPTION:
XS GIS Cut Line= 4
      2800889.21     10022820.59      2801144.42     10022174.76
      2801294.41     10021908.45      2801650.96     10021818.45
#Sta/Elev= 30
  4421.9 1641.62  4542.2 1640.12  4590.6 1634.96  4687.3 1632.48  4719.6 1632.91
    4764 1621.87  4866.8 1620.87  4896.5 1619.09  4920.9 1620.75  4945.2 1620.55
    4975 1617.88  4980.4  1614.3  4996.2 1612.27  4998.9 1611.77  5002.2 1612.27
  5034.4 1617.81  5253.3 1618.24  5324.1 1621.95    5370 1622.39  5399.2 1624.52
  5404.9 1626.47  5415.1 1626.48  5420.8 1628.74  5428.3 1628.92  5601.5  1642.6
    5621 1645.33  5642.7 1646.16  5662.1 1649.08  5749.4 1656.92  5789.7 1663.51
#Mann= 4 ,-1 , 0
  4421.9     .05       0  4996.2     .04       0  5002.2     .05       0
  5428.3     .16       0
Bank Sta=4996.2,5002.2
XS Rating Curve= 0 ,0
Exp/Cntr=0.3,0.1

Type RM Length L Ch R = 1 ,7006    ,352,352,352
BEGIN DESCRIPTION:
Mapping XS 4346ef03
END DESCRIPTION:
XS GIS Cut Line= 3
      2800988.16     10022872.71      2801269.42      10022200.8
      2801679.81     10022036.93
#Sta/Elev= 30
  4542.2 1639.66  4657.2 1637.12  4703.7    1632  4715.7 1628.22  4725.4 1627.22
  4779.6 1630.85  4810.8 1627.12  4816.2 1622.96  4845.4 1616.92  4969.8 1613.84
  4993.6  1610.3    4996 1608.49  4998.8 1607.99    5002 1608.49  5002.1 1608.51
  5010.3 1609.58  5028.9 1612.96  5046.6 1612.28  5099.6  1615.6    5224 1616.43
  5272.8 1619.03  5275.6 1621.23    5281 1621.31  5299.8 1628.74  5305.2 1628.82
  5329.5 1635.38  5336.5 1635.32  5437.2 1644.13  5574.6 1650.82  5712.5 1662.75
#Mann= 6 ,-1 , 0
  4542.2      .1       0    4996     .07       0    5002      .1       0
  5002.1     .16       0  5010.3      .1       0  5336.5     .16       0
Bank Sta=4996,5002
XS Rating Curve= 0 ,0
Exp/Cntr=0.3,0.1

Type RM Length L Ch R = 1 ,6654    ,309,309,309
BEGIN DESCRIPTION:
WEST FORK HUNTERS CREEK 13.0
END DESCRIPTION:
XS GIS Cut Line= 2
      2800999.28     10022915.39      2801940.24     10022443.17
#Sta/Elev= 30
  4693.1  1639.6  4730.8 1639.47  4797.8  1637.2  4835.4 1634.33  4871.2 1630.74
  4887.1 1627.06  4893.6 1623.93    4916 1615.81  4938.3 1610.88  4970.9 1610.35
  4983.1 1606.16  4993.2 1604.23  5002.5 1603.68  5005.2 1603.18  5008.5 1603.68
  5027.8 1606.07  5050.2 1607.01  5096.3 1614.95  5194.3 1617.37  5336.9 1623.65
  5350.6  1623.8  5400.9  1627.7  5417.6 1628.19  5551.6 1639.62    5574  1642.8
  5587.3 1646.11  5685.6  1655.6    5708 1659.07  5735.9 1666.22  5745.9 1667.31
#Mann= 6 ,-1 , 0
  4693.1      .1       0  4835.4     .16       0  5002.5     .07       0
  5008.5     .16       0  5096.3      .1       0  5336.9     .16       0
Bank Sta=5002.5,5008.5
XS Rating Curve= 0 ,0
Exp/Cntr=0.3,0.1

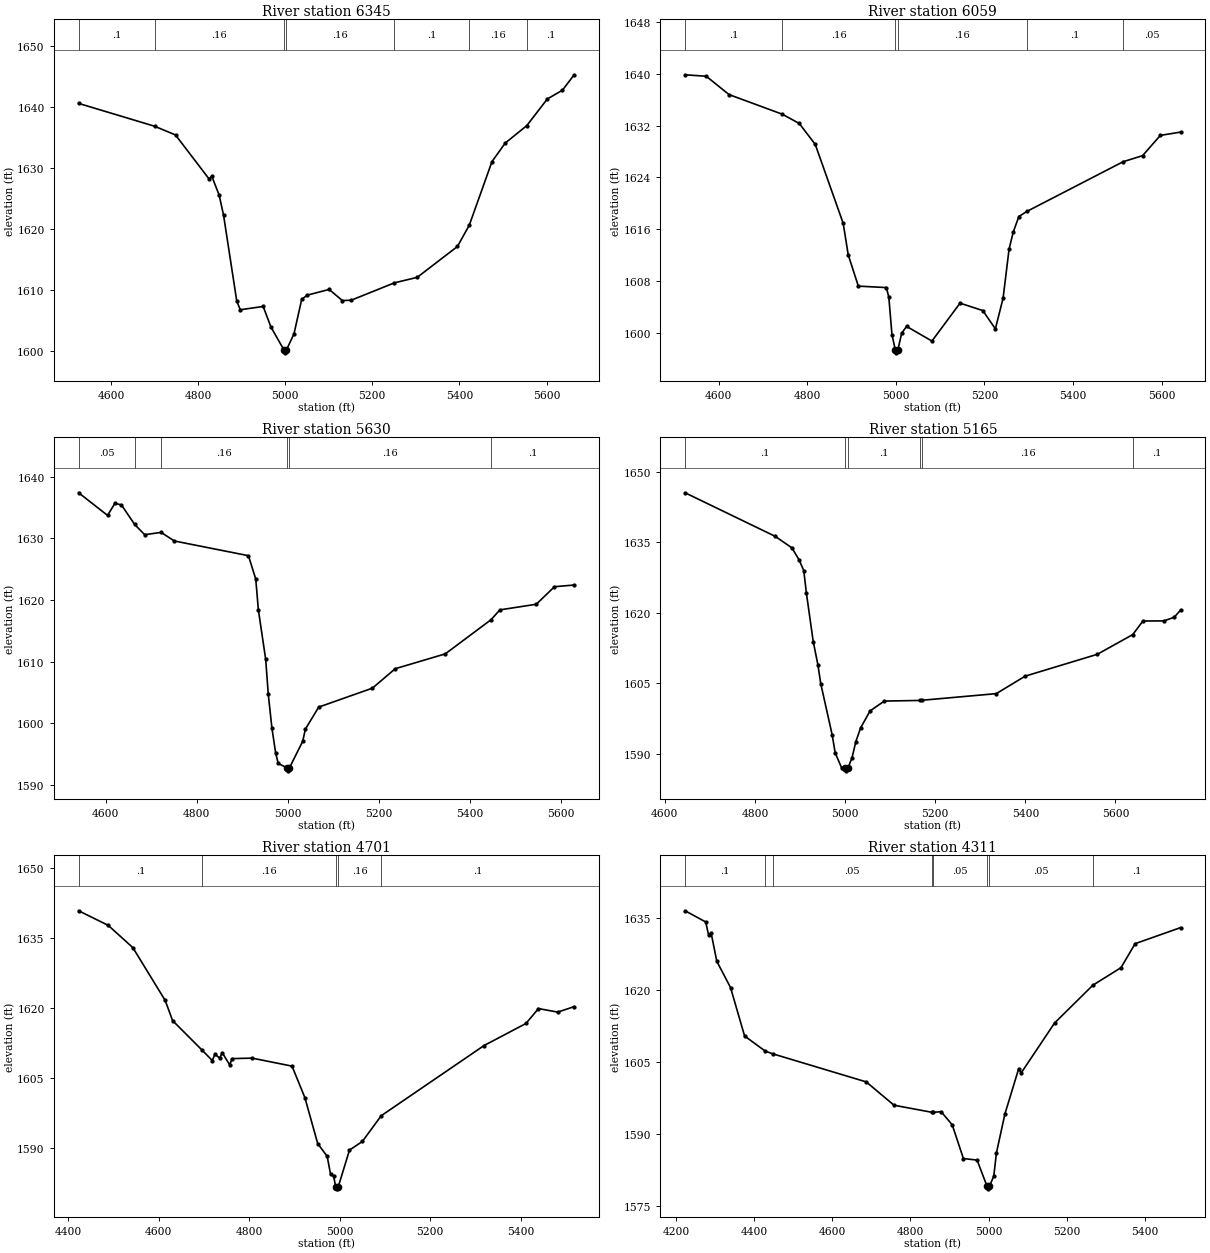
Type RM Length L Ch R = 1 ,6345    ,286,286,286
BEGIN DESCRIPTION:
WEST FORK HUNTERS CREEK 12.0
END DESCRIPTION:
XS GIS Cut Line= 3
      2800936.09      10023013.3      2801238.17     10023018.51
      2802065.24     10023137.37
#Sta/Elev= 30
  4525.8 1640.64  4700.1  1636.9  4748.2 1635.47  4825.6 1628.23  4831.4 1628.72
  4848.4 1625.62  4858.5 1622.33  4888.8 1608.27  4896.8 1606.82  4949.5 1607.36
  4967.4 1603.98    4997 1600.26  4999.7 1599.76    5003 1600.26  5020.2 1602.86
  5037.9 1608.51  5050.5 1609.21    5101 1610.15  5131.3 1608.33  5151.5 1608.38
  5250.7 1611.23  5303.1 1612.13  5395.5 1617.19  5422.8  1620.7  5474.8  1631.1
  5505.1 1634.13  5554.7    1637  5601.9 1641.37  5636.4 1642.79  5663.5 1645.33
#Mann= 7 ,-1 , 0
  4525.8      .1       0  4700.1     .16       0    4997     .07       0
    5003     .16       0  5250.7      .1       0  5422.8     .16       0
  5554.7      .1       0
Bank Sta=4997,5003
XS Rating Curve= 0 ,0
Exp/Cntr=0.3,0.1

Type RM Length L Ch R = 1 ,6059    ,429,429,429
BEGIN DESCRIPTION:
WEST FORK HUNTERS CREEK 11.0
END DESCRIPTION:
XS GIS Cut Line= 2
      2800894.45     10023096.64      2801910.09      10023565.4
#Sta/Elev= 30
  4524.2 1639.86    4572 1639.63  4623.4  1636.8  4743.6 1633.77  4781.9 1632.34
    4818 1629.11  4881.1 1616.91  4892.4 1612.06  4915.3 1607.22  4978.6    1607
  4984.1 1605.49  4991.2 1599.71  4998.6 1597.42  5001.3 1596.92  5004.6 1597.42
  5013.2 1599.97  5024.2    1601  5081.4 1598.74  5144.8 1604.59  5196.2 1603.45
  5224.6 1600.62    5242 1605.36  5255.5 1612.93    5265 1615.59  5277.6 1617.97
  5295.7 1618.76  5513.2 1626.44  5556.9 1627.37    5597  1630.5  5642.8 1631.01
#Mann= 6 ,-1 , 0
  4524.2      .1       0  4743.6     .16       0  4998.6     .07       0
  5004.6     .16       0  5295.7      .1       0  5513.2     .05       0
Bank Sta=4998.6,5004.6
XS Rating Curve= 0 ,0
Exp/Cntr=0.3,0.1

Type RM Length L Ch R = 1 ,5630    ,465,465,465
BEGIN DESCRIPTION:
WEST FORK HUNTERS CREEK 10.0
END DESCRIPTION:
XS GIS Cut Line= 3
      2800686.12     10023278.94      2801206.92     10023565.38
      2801701.74     10023554.97
#Sta/Elev= 30
  4540.6 1637.39  4604.2 1633.72  4620.3 1635.67  4634.6 1635.43  4663.8 1632.25
  4685.7 1630.59  4721.9 1630.96    4751 1629.57  4913.9 1627.18    4930 1623.37
  4935.7 1618.39  4951.8 1610.36  4957.5 1604.67  4965.5  1599.2  4973.6  1595.2
  4979.3 1593.47  4998.1 1592.77  5000.8 1592.27  5004.1 1592.77  5033.2 1597.07
    5039 1599.03  5068.3 1602.61  5186.5 1605.69  5236.5 1608.84  5346.6 1611.25
  5447.1 1616.79  5466.6 1618.39  5546.6  1619.3  5586.6 1622.15  5629.9 1622.42
#Mann= 6 ,-1 , 0
  4540.6     .05       0  4663.8      .1       0  4721.9     .16       0
  4998.1     .07       0  5004.1     .16       0  5447.1      .1       0
Bank Sta=4998.1,5004.1
XS Rating Curve= 0 ,0
Exp/Cntr=0.3,0.1

Type RM Length L Ch R = 1 ,5165    ,464,464,464
BEGIN DESCRIPTION:
WEST FORK HUNTERS CREEK 9.0
END DESCRIPTION:
XS GIS Cut Line= 2
      2800607.95     10023971.64      2801654.11     10023633.33
#Sta/Elev= 30
  4645.1 1645.56  4844.8  1636.3  4882.1 1633.84  4897.9 1631.31  4908.4    1629
  4914.1 1624.31  4929.4 1613.89  4939.9 1608.88  4946.1 1604.92  4971.4 1594.06
  4978.1 1590.21  4992.5 1586.99    5000 1586.88  5002.7 1586.38    5006 1586.88
  5015.4 1589.13    5024 1592.62  5034.5 1595.51  5055.5 1599.13  5087.1 1601.23
  5165.3 1601.36  5171.8 1601.41  5335.5 1602.81  5399.6 1606.53  5559.6 1611.18
  5638.4 1615.38  5660.9 1618.27  5707.1 1618.29  5730.2 1619.06  5744.6  1620.6
#Mann= 6 ,-1 , 0
  4645.1      .1       0    5000     .07       0    5006      .1       0
  5165.3      .1       0  5171.8     .16       0  5638.4      .1       0
Bank Sta=5000,5006
XS Rating Curve= 0 ,0
Exp/Cntr=0.3,0.1

Type RM Length L Ch R = 1 ,4701    ,390,390,390
BEGIN DESCRIPTION:
WEST FORK HUNTERS CREEK 8.0
END DESCRIPTION:
XS GIS Cut Line= 3
      2800852.79     10024377.86      2801243.38     10024169.55
       2801680.9     10023685.15
#Sta/Elev= 30
  4422.7 1640.84    4488 1637.72  4542.5 1632.95  4614.1 1621.61  4630.4  1617.3
  4695.5 1610.98  4718.2 1608.74  4723.9 1610.07  4734.5 1609.28  4740.2 1610.42
  4756.5 1607.83  4762.2 1609.15  4806.1 1609.26  4894.4 1607.54  4922.8 1600.79
  4951.2 1590.94  4972.1 1588.22  4979.6 1584.35  4986.3 1583.98  4990.8 1581.74
  4993.5 1581.24  4996.8 1581.74  5021.4 1589.54  5049.8 1591.39  5091.6 1596.91
  5318.8 1611.95  5411.5 1616.68  5439.2 1619.88  5481.7 1619.12  5518.1 1620.29
#Mann= 5 ,-1 , 0
  4422.7      .1       0  4695.5     .16       0  4990.8     .07       0
  4996.8     .16       0  5091.6      .1       0
Bank Sta=4990.8,4996.8
XS Rating Curve= 0 ,0
Exp/Cntr=0.3,0.1

Type RM Length L Ch R = 1 ,4311    ,362,362,362
BEGIN DESCRIPTION:
WEST FORK HUNTERS CREEK 7.0
END DESCRIPTION:
XS GIS Cut Line= 2
      2801102.78     10024742.44      2802054.64     10023905.01
#Sta/Elev= 30
  4223.7 1636.47  4276.3 1634.15  4283.9 1631.41  4290.5 1631.78  4304.8 1625.95
  4339.9  1620.5  4375.9 1610.41  4428.7 1607.26  4447.4 1606.71  4687.1 1600.85
  4758.3 1595.99  4854.7 1594.53  4857.2  1594.5  4878.8 1594.66  4907.2  1591.9
  4935.7  1584.9  4970.8 1584.57  4996.3 1579.09    4999 1578.59  5002.3 1579.09
  5013.5 1581.26  5020.2 1586.06    5042  1594.2  5077.1 1603.57  5083.7 1602.74
  5169.1 1613.12    5267 1620.98  5338.9 1624.63    5375 1629.62  5491.5 1632.97
#Mann= 8 ,-1 , 0
  4223.7      .1       0  4428.7     .16       0  4447.4     .05       0
  4854.7      .1       0  4857.2     .05       0  4996.3     .07       0
  5002.3     .05       0    5267      .1       0
Bank Sta=4996.3,5002.3
XS Rating Curve= 0 ,0
Exp/Cntr=0.3,0.1

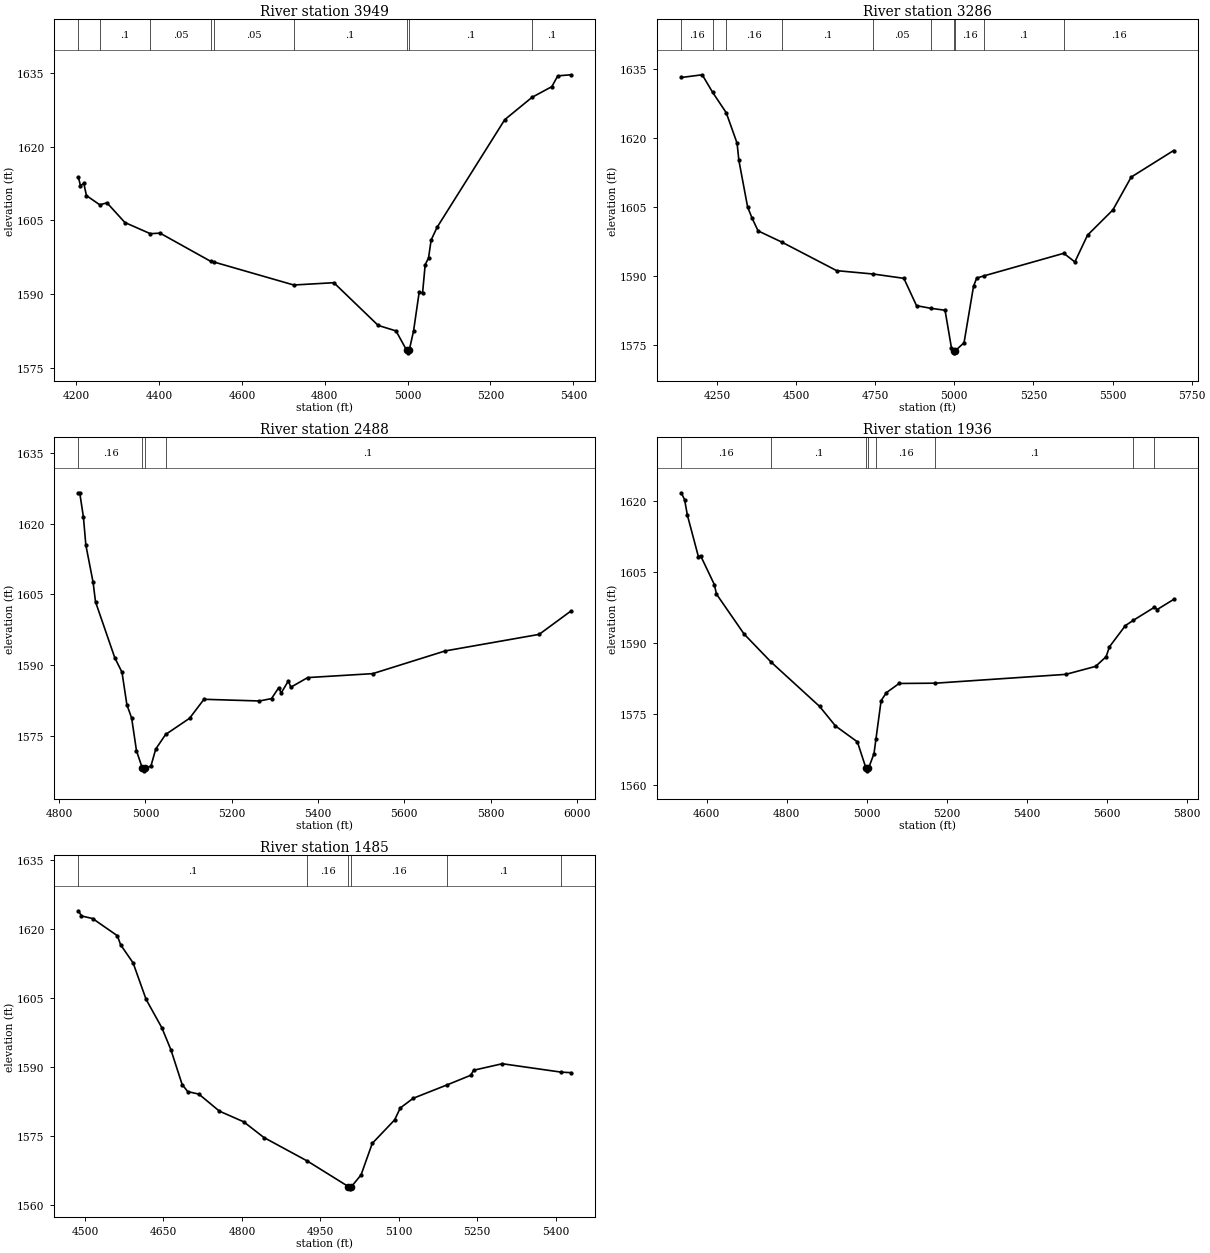
Type RM Length L Ch R = 1 ,3949    ,663,663,663
BEGIN DESCRIPTION:
WEST FORK HUNTERS CREEK 6.0
END DESCRIPTION:
XS GIS Cut Line= 2
      2801357.95     10024940.39      2802284.25     10024196.23
#Sta/Elev= 30
  4205.5 1613.74  4210.4 1612.03  4218.3 1612.54  4224.8 1610.04  4256.9 1608.17
  4274.4 1608.57  4317.6 1604.56  4378.9 1602.29  4402.4  1602.4  4524.4 1596.67
  4533.7 1596.49  4725.2 1591.84  4821.9 1592.31  4928.8 1583.62    4972 1582.49
  4997.8 1578.53  5000.5 1578.03  5003.8 1578.53  5014.3 1582.48    5028 1590.46
    5036 1590.18  5042.4    1596  5050.4 1597.33  5056.8 1601.01  5071.2  1603.6
  5234.4  1625.5  5300.4 1630.06    5348 1632.22  5362.4 1634.42  5393.7 1634.64
#Mann= 9 ,-1 , 0
  4205.5     .16       0  4256.9      .1       0  4378.9     .05       0
  4524.4      .1       0  4533.7     .05       0  4725.2      .1       0
  4997.8     .07       0  5003.8      .1       0  5300.4      .1       0
Bank Sta=4997.8,5003.8
XS Rating Curve= 0 ,0
Exp/Cntr=0.3,0.1

Type RM Length L Ch R = 1 ,3286    ,798,798,798
BEGIN DESCRIPTION:
WEST FORK HUNTERS CREEK 5.0
END DESCRIPTION:
XS GIS Cut Line= 3
      2801264.23     10025148.71      2801930.88      10024950.8
      2802790.27     10024924.76
#Sta/Elev= 30
  4137.8 1633.13  4203.8 1633.72  4236.5 1629.92  4279.6 1625.48  4313.9 1618.85
  4319.6 1615.11  4347.1 1605.01  4361.3 1602.56  4380.3  1599.8  4455.8 1597.34
  4628.5 1591.16  4744.7 1590.42  4840.8 1589.49  4880.8 1583.55  4927.3 1582.96
  4970.9 1582.56  4990.9 1574.46  4997.9  1573.8  5000.6  1573.3  5003.9  1573.8
  5030.9 1575.49  5060.9 1587.77  5070.9 1589.55  5095.2 1590.05    5346 1594.93
    5381 1593.05  5421.1 1598.88  5501.1 1604.35    5559 1611.49    5693 1617.26
#Mann= 10 ,-1 , 0
  4137.8     .16       0  4236.5      .1       0  4279.6     .16       0
  4455.8      .1       0  4744.7     .05       0  4927.3     .16       0
  4997.9     .07       0  5003.9     .16       0  5095.2      .1       0
    5346     .16       0
Bank Sta=4997.9,5003.9
XS Rating Curve= 0 ,0
Exp/Cntr=0.3,0.1

Type RM Length L Ch R = 1 ,2488    ,552,552,552
BEGIN DESCRIPTION:
WEST FORK HUNTERS CREEK 4.0
END DESCRIPTION:
XS GIS Cut Line= 2
      2801738.19     10025716.42        2802759.     10025206.01
#Sta/Elev= 30
  4844.7  1626.6  4847.6  1626.6  4856.2 1621.43  4861.8  1615.5  4878.6 1607.59
  4884.2 1603.44  4928.9 1591.55  4945.6 1588.48  4956.9 1581.59    4968 1578.73
  4979.2  1571.8    4993 1568.03  4995.7 1567.53    4999 1568.03  5012.7 1568.55
  5023.9 1572.17  5046.7 1575.25  5102.2 1578.69  5135.7 1582.73  5264.3 1582.37
  5292.3 1582.88    5309 1585.19  5314.6 1584.06  5331.4 1586.64    5337 1585.29
  5376.1 1587.34    5527 1588.18  5694.8    1593  5912.8 1596.52    5986 1601.45
#Mann= 4 ,-1 , 0
  4844.7     .16       0    4993     .07       0    4999     .16       0
  5046.7      .1       0
Bank Sta=4993,4999
XS Rating Curve= 0 ,0
Exp/Cntr=0.3,0.1

Type RM Length L Ch R = 1 ,1936    ,451,451,451
BEGIN DESCRIPTION:
WEST FORK HUNTERS CREEK 3.0
END DESCRIPTION:
XS GIS Cut Line= 2
      2801753.78     10026190.39      2802941.26     10025867.48
#Sta/Elev= 30
  4537.1 1621.84  4545.3 1620.34  4552.3 1617.06  4579.9 1608.26  4585.1 1608.53
  4619.7 1602.38  4624.9 1600.38    4694 1591.91  4761.5 1585.97  4882.6 1576.59
  4922.4 1572.44  4977.2 1569.07  4998.9 1563.43  5001.7 1562.93  5004.9 1563.43
  5018.7 1566.58  5023.5 1569.62  5036.5  1577.8  5049.7 1579.49  5081.5 1581.44
    5172  1581.5  5498.3 1583.37  5572.7 1585.06    5599 1587.11  5607.3 1589.21
  5647.1  1593.7    5667 1594.82  5719.8 1597.59  5726.7 1597.11  5767.7 1599.24
#Mann= 8 ,-1 , 0
  4537.1     .16       0  4761.5      .1       0  4998.9     .07       0
  5004.9      .1       0  5023.5     .16       0    5172      .1       0
    5667     .16       0  5719.8      .1       0
Bank Sta=4998.9,5004.9
XS Rating Curve= 0 ,0
Exp/Cntr=0.3,0.1

Type RM Length L Ch R = 1 ,1485    ,1048,1048,1048
BEGIN DESCRIPTION:
WEST FORK HUNTERS CREEK 2.0
END DESCRIPTION:
XS GIS Cut Line= 2
      2801863.15     10026674.77      2802743.35     10026341.44
#Sta/Elev= 30
  4487.5    1624  4493.2 1622.87  4514.6 1622.31  4561.9 1618.57    4568 1616.62
    4592 1612.65  4616.8 1604.72    4647 1598.53  4664.3 1593.74  4685.7  1586.2
  4696.4 1584.66  4717.7 1584.11  4756.9 1580.41  4803.3 1578.09    4842 1574.67
  4925.1 1569.55  5003.5    1564  5006.2  1563.5  5009.5    1564  5027.8 1566.53
  5049.2 1573.39    5092  1578.5  5102.8  1581.1  5127.6 1583.21  5191.9  1586.1
  5237.5 1588.21  5242.9  1589.3  5297.8 1590.72  5410.5 1588.89  5428.7 1588.78
#Mann= 6 ,-1 , 0
  4487.5      .1       0  4925.1     .16       0  5003.5     .07       0
  5009.5     .16       0  5191.9      .1       0  5410.5     .16       0
Bank Sta=5003.5,5009.5
XS Rating Curve= 0 ,0
Exp/Cntr=0.3,0.1