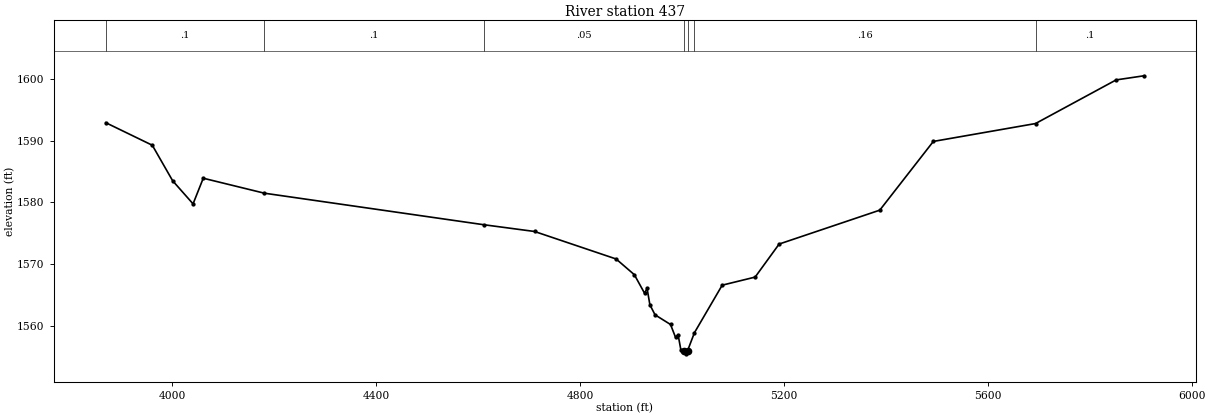
HEC-RAS study WEST FORK HUNTERS CREEK.prj: WEST FORK HUNTERS CREEK Base Level Engineering

--- WEST FORK HUNTERS CREEK.g01 (geometry) --- (continued)

Type RM Length L Ch R = 1 ,437     ,0,0,0
BEGIN DESCRIPTION:
WEST FORK HUNTERS CREEK 1.0
END DESCRIPTION:
XS GIS Cut Line= 4
      2802087.15     10026976.84      2803070.58     10026966.77
      2803118.38     10026679.97      2802977.76     10025929.97
#Sta/Elev= 30
  3869.2 1592.92  3960.5 1589.26  4000.5 1583.49  4040.5 1579.75  4060.5 1583.91
  4180.5 1581.48  4610.6 1576.37  4710.6 1575.27  4870.6 1570.81  4906.4 1568.26
  4926.4 1565.26  4931.4 1566.03  4936.9 1563.38    4947 1561.75  4977.4 1560.18
  4987.2  1558.1  4992.3 1558.51  4997.7 1556.05  5004.8 1555.92  5007.6 1555.42
  5010.8 1555.92  5024.4 1558.86  5078.8 1566.56  5143.4 1567.87  5190.5 1573.23
    5388 1578.73  5493.1 1589.88  5693.6 1592.78  5851.8 1599.86  5906.5 1600.53
#Mann= 7 ,-1 , 0
  3869.2      .1       0  4180.5      .1       0  4610.6     .05       0
  5004.8     .04       0  5010.8     .05       0  5024.4     .16       0
  5693.6      .1       0
Bank Sta=5004.8,5010.8
XS Rating Curve= 0 ,0
Exp/Cntr=0.3,0.1

Chan Stop Cuts=-1
Use User Specified Reach Order=0
Composite Channel Slope=5

--- WEST FORK HUNTERS CREEK.g02 (geometry) ---

Geom Title=raw
Program Version=4.10

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
River Reach=WEST FORK HUNTER,Reach-1

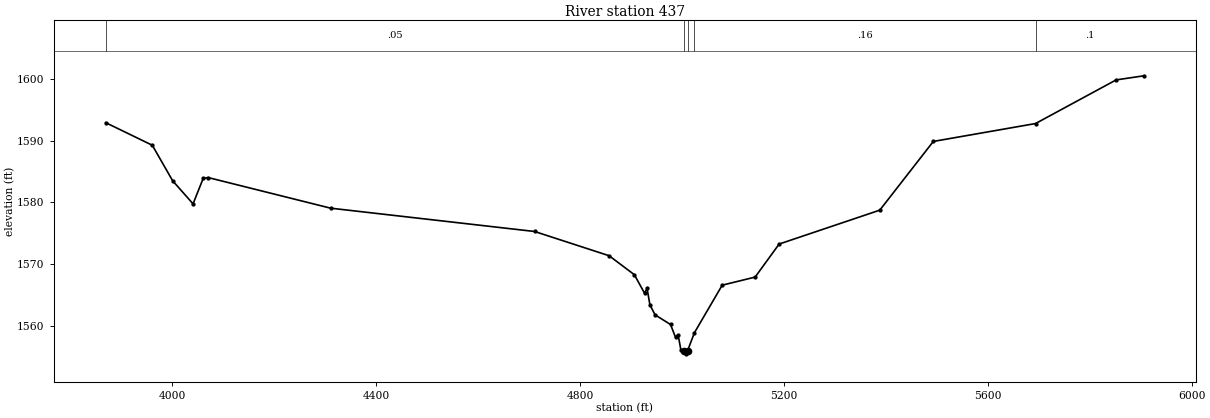
Type RM Length L Ch R = 1 ,437     ,0,0,0
BEGIN DESCRIPTION:
WEST FORK HUNTERS CREEK 1.0
END DESCRIPTION:
XS GIS Cut Line= 4
      2802087.15     10026976.84      2803070.58     10026966.77
      2803118.38     10026679.97      2802977.76     10025929.97
#Sta/Elev= 30
  3869.2 1592.92  3960.5 1589.26  4000.5 1583.49  4040.5 1579.75  4060.5 1583.91
  4070.5 1584.01  4310.5 1579.05  4710.6 1575.27  4856.8 1571.34  4906.4 1568.26
  4926.4 1565.26  4931.4 1566.03  4936.9 1563.38    4947 1561.75  4977.4 1560.18
  4987.2  1558.1  4992.3 1558.51  4997.7 1556.05  5004.8 1555.92  5007.6 1555.42
  5010.8 1555.92  5024.4 1558.86  5078.8 1566.56  5143.4 1567.87  5190.5 1573.23
    5388 1578.73  5493.1 1589.88  5693.6 1592.78  5851.8 1599.86  5906.5 1600.53
#Mann= 5 ,-1 , 0
  3869.2     .05       0  5004.8     .04       0  5010.8     .05       0
  5024.4     .16       0  5693.6      .1       0
Bank Sta=5004.8,5010.8
XS Rating Curve= 0 ,0
Exp/Cntr=0.3,0.1