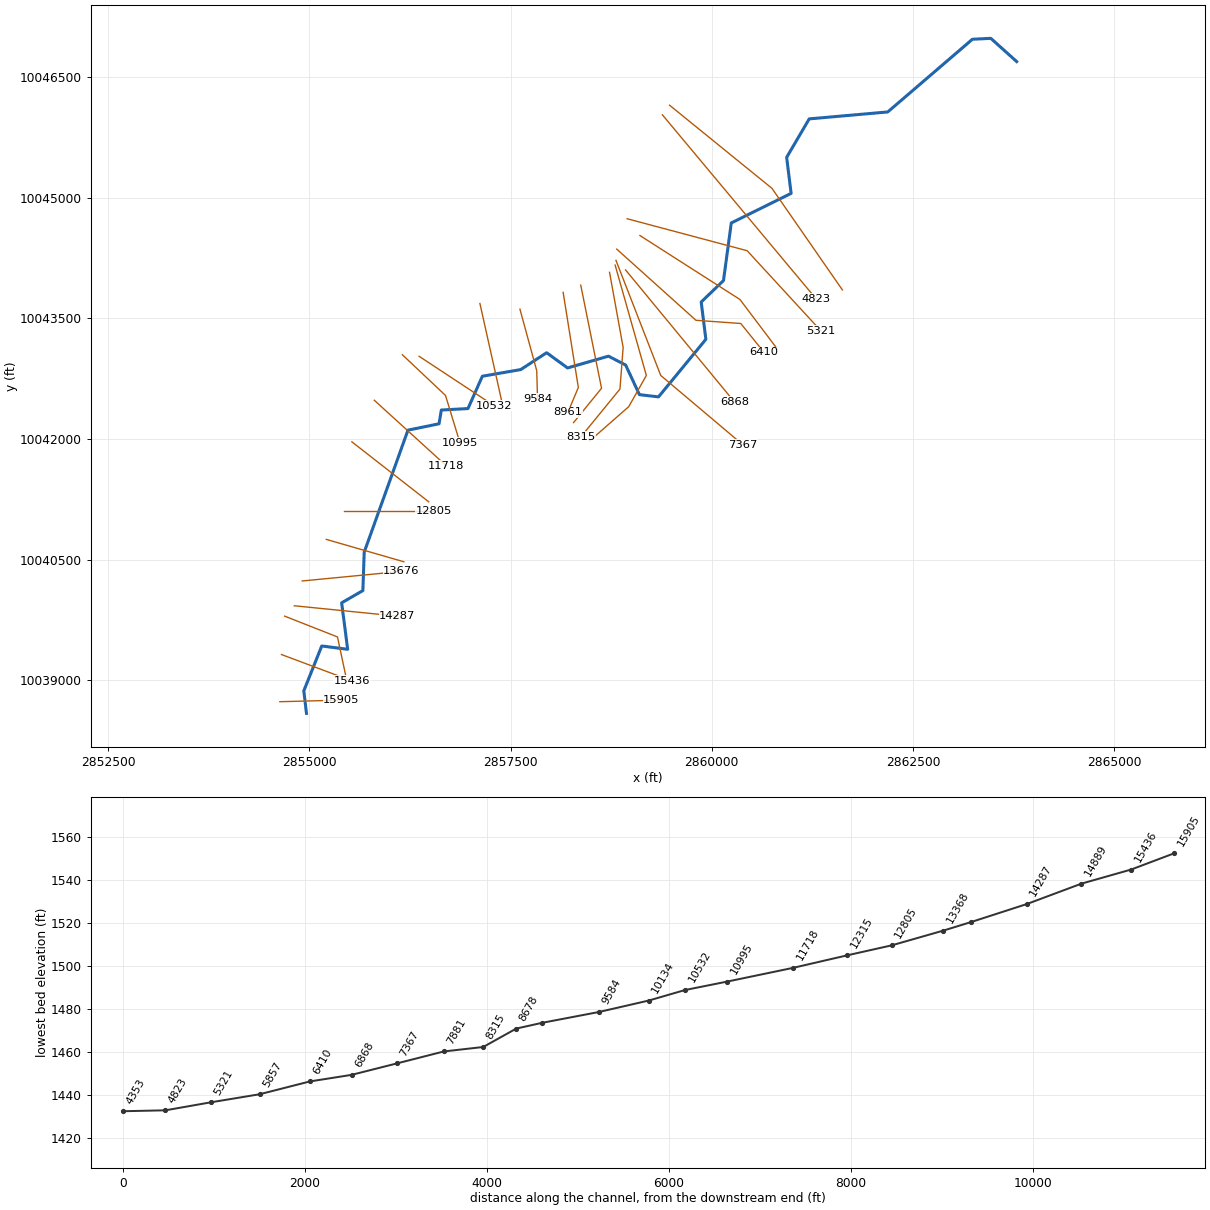
--- WEST FORK ROCKY CREEK.prj (project) ---

Proj Title=WEST FORK ROCKY CREEK Base Level Engineering
Current Plan=p01
Default Exp/Contr=0.3,0.1
English Units
Geom File=g01
Flow File=f01
Plan File=p01
Y Axis Title=Elevation
X Axis Title(PF)=Main Channel Distance
X Axis Title(XS)=Station
BEGIN DESCRIPTION:
WEST FORK ROCKY CREEK
END DESCRIPTION:
DSS Export Rating Curves= 0
DSS Export Rating Curve Sorted= 0
DSS Export Volume Flow Curves= 0
DXF OffsetX= 0
DXF OffsetY= 0
DXF ScaleX= 1
DXF ScaleY= 10

--- WEST FORK ROCKY CREEK.p01 (plan) ---

Plan Title=Multiple Run
Short Identifier=Multiple
Geom File=g01
Flow File=f01
Subcritical Flow
K Sum by GR= 0
Std Step Tol= 0.01
Critical Tol= 0.01
Num of Std Step Trials= 20
Max Error Tol= 0.3
Flow Tol Ratio= 0.001
Split Flow NTrial= 30
Split Flow Tol= 0.02
Split Flow Ratio= 0.02
Log Output Level= 0
Friction Slope Method= 1
Unsteady Friction Slope Method= 2
Unsteady Bridges Friction Slope Method= 1
Parabolic Critical Depth
Global Vel Dist=  1 , 1 , 1
Global Log Level= 0
CheckData=True
Encroach Param= -1, 0, 0, 0
BEGIN DESCRIPTION:
Multiple Run
END DESCRIPTION:

--- WEST FORK ROCKY CREEK.f01 (steady flow) ---

Flow Title=Multiple
Program Version=4.10
Number of Profiles= 7
Profile Names=10-year,25-year,50-year,1pct_min,100-year,1pct_plu,500-year
River Rch & RM=WEST FORK ROCKY,Reach-1         ,15905
     876    1268    1609    1496    2023    2735    3206
River Rch & RM=WEST FORK ROCKY,Reach-1         ,14287
    1271    1874    2405    2257    3052    4128    4937
River Rch & RM=WEST FORK ROCKY,Reach-1         ,7367
    2419    3671    4803    4586    6202    8387   10387
Boundary for River Rch & Prof#=WEST FORK ROCKY,Reach-1         , 1
Up Type= 0
Dn Type= 3
Dn Slope=0.009
Boundary for River Rch & Prof#=WEST FORK ROCKY,Reach-1         , 2
Up Type= 0
Dn Type= 3
Dn Slope=0.009
Boundary for River Rch & Prof#=WEST FORK ROCKY,Reach-1         , 3
Up Type= 0
Dn Type= 3
Dn Slope=0.009
Boundary for River Rch & Prof#=WEST FORK ROCKY,Reach-1         , 4
Up Type= 0
Dn Type= 3
Dn Slope=0.009
Boundary for River Rch & Prof#=WEST FORK ROCKY,Reach-1         , 5
Up Type= 0
Dn Type= 3
Dn Slope=0.009
Boundary for River Rch & Prof#=WEST FORK ROCKY,Reach-1         , 6
Up Type= 0
Dn Type= 3
Dn Slope=0.009
Boundary for River Rch & Prof#=WEST FORK ROCKY,Reach-1         , 7
Up Type= 0
Dn Type= 3
Dn Slope=0.009
DSS Import GetInterval= 0
DSS Import GetPeak= 0
DSS Import FillOption= 0

--- WEST FORK ROCKY CREEK.g01 (geometry) ---

Geom Title=Existing Conditions
Program Version=4.10

River Reach=WEST FORK ROCKY ,Reach-1
Reach XY= 30
      2854964.14     10038588.05      2854930.76     10038868.07
      2855154.01     10039426.38      2855475.86     10039384.61
      2855401.17     10039962.78      2855665.06     10040115.03
      2855681.43     10040592.49      2856225.19     10042110.06
      2856611.72     10042189.13      2856639.68     10042360.26
      2856971.07     10042378.57       2857149.7     10042780.46
      2857626.12     10042863.19      2857948.41     10043072.95
      2858208.57     10042883.69      2858716.86     10043029.85
      2858930.29     10042919.55      2859101.59     10042551.43
      2859338.47     10042523.73      2859927.22     10043239.61
      2859869.23     10043703.49      2860145.98     10043970.12
      2860242.97      10044686.6      2860986.62     10045054.47
      2860931.05     10045502.66      2861211.66     10045980.65
       2862187.1     10046066.96      2863239.63     10046970.91
      2863467.79     10046982.34      2863789.79     10046693.21

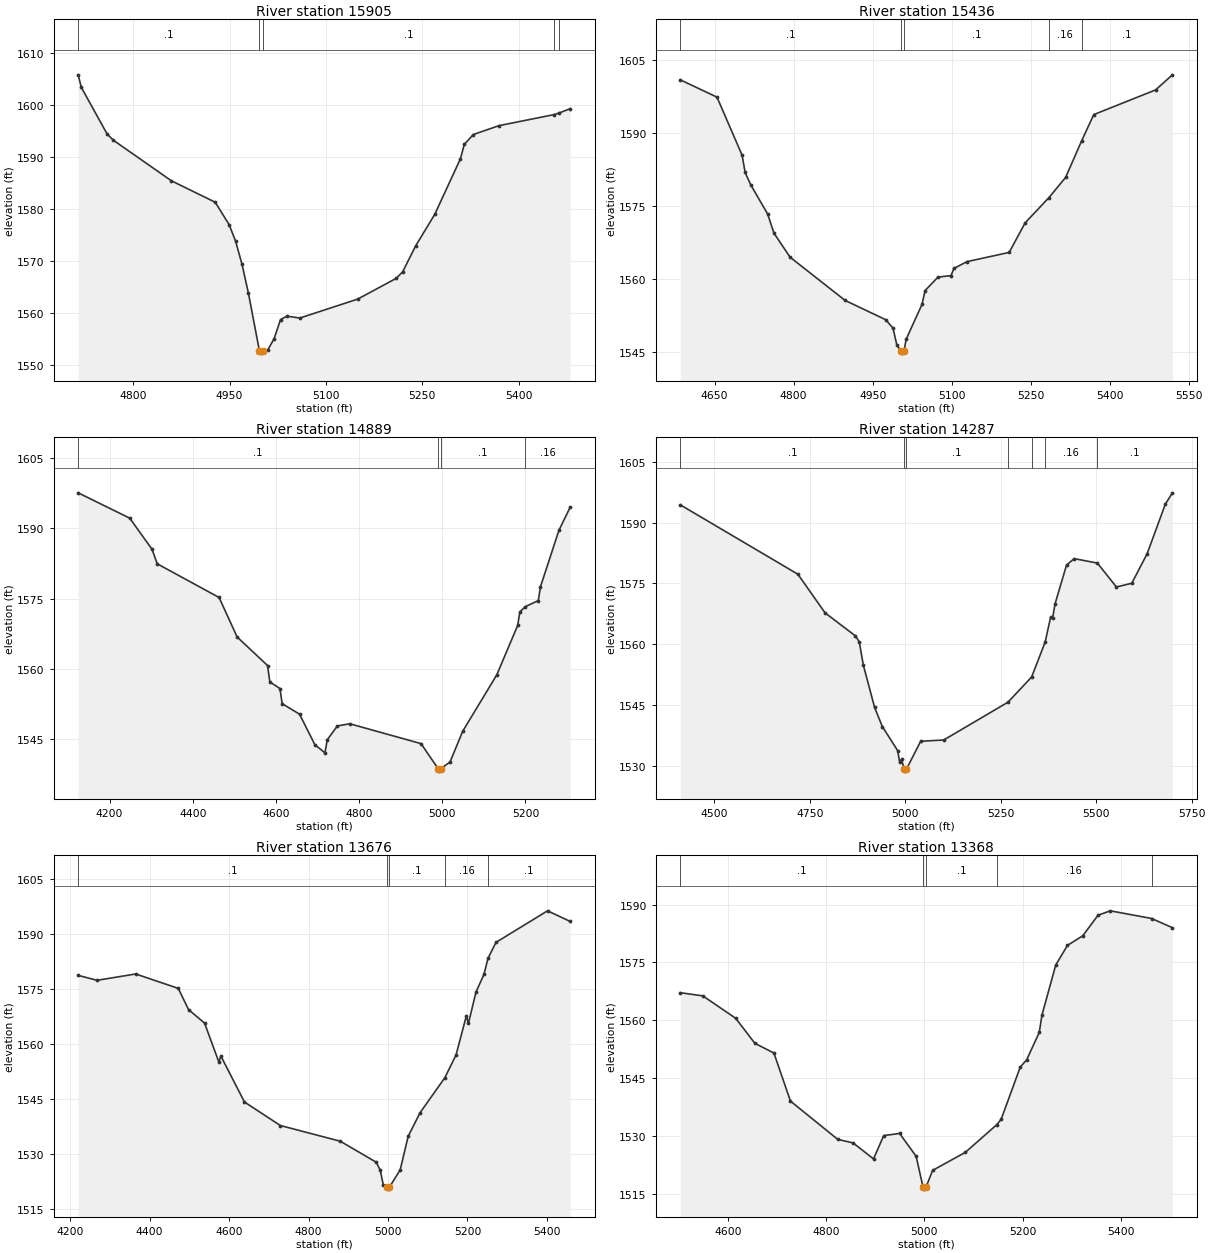
Type RM Length L Ch R = 1 ,15905   ,469,469,469
BEGIN DESCRIPTION:
WEST FORK ROCKY CREEK 34.0
END DESCRIPTION:
XS GIS Cut Line= 2
      2854633.45      10038733.1      2855399.09     10038752.99
#Sta/Elev= 30
  4714.2 1605.89  4719.2 1603.46  4759.2 1594.51  4769.2 1593.27  4859.3 1585.48
  4927.6 1581.34  4949.3 1577.01  4959.3 1573.84  4969.3 1569.38  4979.3  1563.8
  4996.3 1552.77  4999.1 1552.27  5002.3 1552.77  5009.3 1552.88  5019.3 1555.05
  5029.3 1558.74  5039.3  1559.4  5059.3 1559.03  5149.4 1562.68  5209.4 1566.68
  5219.4 1567.94  5239.4 1572.89  5269.4 1579.02  5309.4 1589.74  5315.3 1592.49
  5329.4 1594.39  5369.4  1596.1  5455.6 1598.24  5463.5 1598.56  5480.1 1599.37
#Mann= 5 ,-1 , 0
  4714.2      .1       0  4996.3     .07       0  5002.3      .1       0
  5455.6     .05       0  5463.5      .1       0
Bank Sta=4996.3,5002.3
XS Rating Curve= 0 ,0
Exp/Cntr=0.3,0.1

Type RM Length L Ch R = 1 ,15436   ,547,547,547
BEGIN DESCRIPTION:
WEST FORK ROCKY CREEK 33.0
END DESCRIPTION:
XS GIS Cut Line= 2
      2854653.39     10039319.74      2855528.39     10038991.62
#Sta/Elev= 30
  4584.9 1600.82  4654.4 1597.28  4702.1 1585.37  4707.8 1581.85  4718.5 1579.29
  4750.5 1573.33  4762.6 1569.38  4793.2 1564.45  4897.9 1555.57  4974.8 1551.63
  4988.7 1549.89  4996.2 1546.36  5003.8 1545.27  5006.6 1544.77  5009.8 1545.27
  5013.6  1547.6  5043.8 1554.76  5049.6  1557.6  5074.1 1560.36    5099 1560.68
  5104.4 1562.15  5129.3 1563.54  5209.4 1565.43  5239.6 1571.49    5285 1576.69
  5316.6 1580.82  5347.1 1588.35    5370  1593.7  5487.4 1598.76  5519.4 1601.86
#Mann= 5 ,-1 , 0
  4584.9      .1       0  5003.8     .07       0  5009.8      .1       0
    5285     .16       0  5347.1      .1       0
Bank Sta=5003.8,5009.8
XS Rating Curve= 0 ,0
Exp/Cntr=0.3,0.1

Type RM Length L Ch R = 1 ,14889   ,602,602,602
BEGIN DESCRIPTION:
WEST FORK ROCKY CREEK 32.0
END DESCRIPTION:
XS GIS Cut Line= 3
      2854693.12     10039797.04      2855349.38     10039538.52
      2855448.81     10039071.22
#Sta/Elev= 30
  4124.4 1597.54  4248.4 1592.14  4302.1  1585.5  4314.5 1582.41  4463.3 1575.22
  4506.7  1566.8  4579.9 1560.71  4585.3 1557.22  4609.7  1555.8    4615 1552.58
  4656.8 1550.33  4693.6 1543.83    4718 1542.08  4723.3 1544.86  4747.7 1547.82
  4777.5 1548.29  4948.8 1544.06  4990.3 1538.69  4993.1 1538.19  4996.3 1538.69
  5018.7 1540.15  5049.3 1546.72  5131.1 1558.72  5181.4 1569.28  5186.5 1572.15
  5200.1 1573.28    5231 1574.57  5236.1  1577.5  5280.6 1589.56  5307.5 1594.45
#Mann= 4 ,-1 , 0
  4124.4      .1       0  4990.3     .07       0  4996.3      .1       0
  5200.1     .16       0
Bank Sta=4990.3,4996.3
XS Rating Curve= 0 ,0
Exp/Cntr=0.3,0.1

Type RM Length L Ch R = 1 ,14287   ,611,611,611
BEGIN DESCRIPTION:
WEST FORK ROCKY CREEK 31.0
END DESCRIPTION:
XS GIS Cut Line= 2
      2854812.42     10039926.31      2856094.32     10039797.12
#Sta/Elev= 30
  4411.2 1594.38  4718.8 1577.27  4790.1 1567.73  4869.6 1562.04  4879.6 1560.57
  4890.2 1554.83  4919.8 1544.38  4939.9 1539.68  4980.1 1533.74  4985.3 1530.91
  4990.3 1531.59  4997.2 1529.17    5000 1528.67  5003.2 1529.17  5040.4 1536.05
  5100.7 1536.35  5269.1 1545.69    5331 1551.91  5366.4 1560.53  5380.7  1566.7
  5385.8 1566.41  5392.2 1569.94  5422.3 1579.53  5442.4 1581.12  5503.1 1580.02
    5553 1574.12  5593.2 1575.04  5633.4 1582.32  5681.1 1594.58  5699.6 1597.36
#Mann= 7 ,-1 , 0
  4411.2      .1       0  4997.2     .07       0  5003.2      .1       0
  5269.1     .16       0    5331      .1       0  5366.4     .16       0
  5503.1      .1       0
Bank Sta=4997.2,5003.2
XS Rating Curve= 0 ,0
Exp/Cntr=0.3,0.1

Type RM Length L Ch R = 1 ,13676   ,308,308,308
BEGIN DESCRIPTION:
WEST FORK ROCKY CREEK 30.0
END DESCRIPTION:
XS GIS Cut Line= 2
      2854911.86     10040234.55       2856144.2     10040353.81
#Sta/Elev= 30
  4220.3  1578.6  4267.9 1577.25  4365.1 1578.98  4472.2 1575.06  4498.2 1569.25
  4538.4 1565.59  4574.4 1554.96  4579.4 1556.61  4638.9 1544.06  4729.3 1537.65
    4880 1533.37  4970.4 1527.65  4980.4  1525.5    4988 1521.57  4997.5 1520.81
  5000.3 1520.31  5003.5 1520.81  5030.7 1525.57  5050.8 1534.71  5080.9 1541.17
    5143 1550.68  5171.3  1556.9  5197.3  1567.6  5202.3 1565.48  5221.6 1574.08
  5241.7 1578.92  5251.7 1583.26  5271.8  1587.6  5401.5  1596.2  5458.4 1593.32
#Mann= 5 ,-1 , 0
  4220.3      .1       0  4997.5     .07       0  5003.5      .1       0
    5143     .16       0  5251.7      .1       0
Bank Sta=4997.5,5003.5
XS Rating Curve= 0 ,0
Exp/Cntr=0.3,0.1

Type RM Length L Ch R = 1 ,13368   ,563,563,563
BEGIN DESCRIPTION:
WEST FORK ROCKY CREEK 29.0
END DESCRIPTION:
XS GIS Cut Line= 2
      2855210.15     10040751.61       2856174.1     10040473.36
#Sta/Elev= 30
  4502.4 1567.16  4548.2 1566.34  4615.1 1560.54  4654.3 1554.05  4693.1 1551.54
  4726.8 1539.09  4823.3 1529.17  4854.5 1528.26  4896.2 1524.12    4917 1530.16
  4949.4 1530.71  4983.1 1524.79  4997.2 1516.79    5000 1516.29  5003.2 1516.79
  5016.7 1521.14  5083.5 1525.82  5147.1 1532.93  5156.4 1534.34  5195.3 1547.87
  5208.4 1549.77  5234.2 1556.88  5239.6 1561.33  5267.8 1574.34  5291.7 1579.42
  5322.9 1581.91  5354.1 1587.24  5379.1 1588.37  5463.5 1586.38  5505.7    1584
#Mann= 5 ,-1 , 0
  4502.4      .1       0  4997.2     .07       0  5003.2      .1       0
  5147.1     .16       0  5463.5      .1       0
Bank Sta=4997.2,5003.2
XS Rating Curve= 0 ,0
Exp/Cntr=0.3,0.1

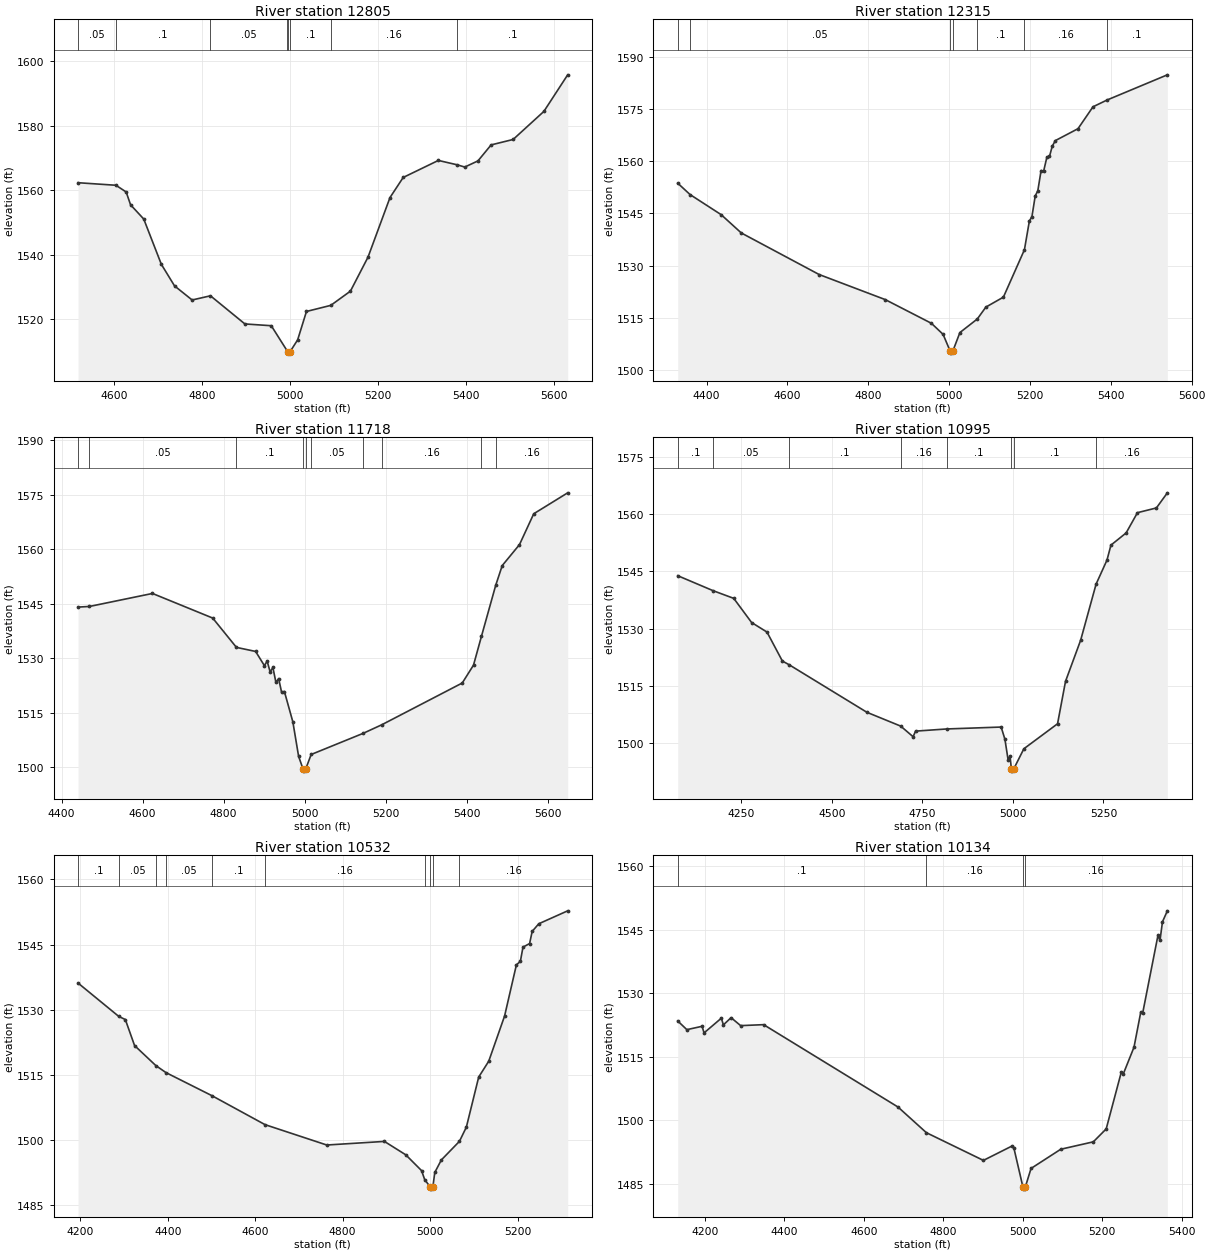
Type RM Length L Ch R = 1 ,12805   ,490,490,490
BEGIN DESCRIPTION:
WEST FORK ROCKY CREEK 28.0
END DESCRIPTION:
XS GIS Cut Line= 2
      2855428.94     10041109.57      2856542.54     10041109.57
#Sta/Elev= 30
  4518.5 1562.33  4604.7 1561.54    4628 1559.45    4638 1555.48    4668 1551.06
    4708 1537.02    4738 1530.33    4778 1525.96  4819.7 1527.26    4898 1518.53
    4958 1517.98  4994.7 1510.06    4995 1509.98  4997.8 1509.48    5001 1509.98
    5018  1513.6    5038  1522.4  5093.3 1524.29    5138  1528.7    5178 1539.25
    5228 1557.73    5258 1563.96    5338 1569.24  5380.9 1567.88    5398 1567.19
    5428 1569.09    5458 1574.06    5508 1575.74    5578 1584.45  5632.1 1595.79
#Mann= 8 ,-1 , 0
  4518.5     .05       0  4604.7      .1       0  4819.7     .05       0
  4994.7      .1       0    4995     .07       0    5001      .1       0
  5093.3     .16       0  5380.9      .1       0
Bank Sta=4995,5001
XS Rating Curve= 0 ,0
Exp/Cntr=0.3,0.1

Type RM Length L Ch R = 1 ,12315   ,597,597,597
BEGIN DESCRIPTION:
WEST FORK ROCKY CREEK 27.0
END DESCRIPTION:
XS GIS Cut Line= 2
       2855528.4     10041964.67      2856482.93     10041218.94
#Sta/Elev= 30
  4328.6 1553.72  4359.1 1550.44  4436.1 1544.65  4485.9 1539.39  4678.5 1527.43
  4842.2 1520.21  4956.2  1513.4  4985.1 1510.22  5002.9 1505.32  5005.7 1504.82
  5008.9 1505.32  5026.7 1510.74  5069.7 1514.64  5090.9 1518.06  5134.3 1520.93
  5186.3 1534.56  5198.5 1542.81  5204.9 1544.12    5213 1550.05  5219.4 1551.52
  5227.5 1557.34  5233.8 1557.16  5241.9 1561.21  5248.3  1561.4  5255.1 1564.34
  5262.8 1565.96  5318.8 1569.38  5355.9 1575.68  5390.8 1577.64  5539.9 1584.88
#Mann= 7 ,-1 , 0
  4328.6      .1       0  4359.1     .05       0  5002.9    .035       0
  5008.9     .05       0  5069.7      .1       0  5186.3     .16       0
  5390.8      .1       0
Bank Sta=5002.9,5008.9
XS Rating Curve= 0 ,0
Exp/Cntr=0.3,0.1

Type RM Length L Ch R = 1 ,11718   ,723,723,723
BEGIN DESCRIPTION:
WEST FORK ROCKY CREEK 25.0
END DESCRIPTION:
XS GIS Cut Line= 2
      2855806.76     10042481.76      2856700.38     10041667.58
#Sta/Elev= 30
  4440.7 1544.11  4468.8 1544.28  4624.5 1547.86  4773.2 1541.09  4831.8 1533.02
  4879.2  1531.9  4900.8    1528  4907.6 1529.24    4915 1526.26  4921.8  1527.5
  4929.2 1523.41    4936 1524.44  4943.4 1520.61  4950.2 1520.88  4971.1 1512.52
  4985.3 1503.03  4996.5 1499.47  4999.3 1498.97  5002.5 1499.47  5016.3 1503.55
  5144.9 1509.38  5190.7 1511.73  5389.3 1523.22  5417.1 1528.14  5436.7 1536.06
  5471.9  1550.1    5488 1555.53  5530.6  1561.3  5565.8 1569.79  5649.6 1575.55
#Mann= 10 ,-1 , 0
  4440.7      .1       0  4468.8     .05       0  4831.8      .1       0
  4996.5     .07       0  5002.5      .1       0  5016.3     .05       0
  5144.9      .1       0  5190.7     .16       0  5436.7      .1       0
  5471.9     .16       0
Bank Sta=4996.5,5002.5
XS Rating Curve= 0 ,0
Exp/Cntr=0.3,0.1

Type RM Length L Ch R = 1 ,10995   ,463,463,463
BEGIN DESCRIPTION:
WEST FORK ROCKY CREEK 24.0
END DESCRIPTION:
XS GIS Cut Line= 3
       2856154.8     10043048.52      2856691.74     10042541.41
      2856870.71     10041954.76
#Sta/Elev= 30
  4074.6 1543.89  4172.4 1539.95  4229.3 1537.94  4278.6  1531.6  4321.1 1529.09
  4363.6 1521.48  4382.5  1520.5    4597 1508.03  4690.2 1504.41  4724.5 1501.62
  4731.3 1503.09  4817.6 1503.66  4967.6 1504.16    4978 1500.95  4986.8 1495.54
  4992.1 1496.58  4995.9 1493.09  4998.7 1492.59  5001.9 1493.09  5030.3 1498.46
  5123.3 1505.02  5145.3 1516.16  5187.1 1526.96  5229.7 1541.68  5259.8 1547.99
  5270.7 1551.91  5312.6 1555.11  5343.9 1560.43  5396.2 1561.67  5426.5 1565.64
#Mann= 8 ,-1 , 0
  4074.6      .1       0  4172.4     .05       0  4382.5      .1       0
  4690.2     .16       0  4817.6      .1       0  4995.9     .07       0
  5001.9      .1       0  5229.7     .16       0
Bank Sta=4995.9,5001.9
XS Rating Curve= 0 ,0
Exp/Cntr=0.3,0.1

Type RM Length L Ch R = 1 ,10532   ,398,398,398
BEGIN DESCRIPTION:
WEST FORK ROCKY CREEK 23.0
END DESCRIPTION:
XS GIS Cut Line= 2
      2856363.61     10043028.63      2857298.31     10042412.13
#Sta/Elev= 30
  4194.9 1536.13  4288.2 1528.43  4303.1 1527.72  4324.2 1521.73  4372.8 1517.12
    4396  1515.5    4501 1510.19  4622.6 1503.51  4763.7 1498.82  4895.5 1499.65
  4944.4 1496.56  4980.5 1492.92  4987.6 1490.86  5000.3 1489.16  5003.1 1488.66
  5006.3 1489.16  5010.7  1492.5  5025.7 1495.38  5067.1 1499.67  5082.9 1502.94
  5111.1 1514.47  5134.1 1518.13  5170.3 1528.53  5197.3 1540.31  5206.4 1541.12
  5212.4  1544.4  5227.5 1545.22  5233.4 1548.02  5248.5 1549.78  5314.6 1552.76
#Mann= 10 ,-1 , 0
  4194.9      .1       0  4288.2     .05       0  4372.8      .1       0
    4396     .05       0    4501      .1       0  4622.6     .16       0
  4987.6      .1       0  5000.3     .07       0  5006.3      .1       0
  5067.1     .16       0
Bank Sta=5000.3,5006.3
XS Rating Curve= 0 ,0
Exp/Cntr=0.3,0.1

Type RM Length L Ch R = 1 ,10134   ,550,550,550
BEGIN DESCRIPTION:
WEST FORK ROCKY CREEK 22.0
END DESCRIPTION:
XS GIS Cut Line= 2
       2857119.3     10043684.89      2857387.77     10042481.77
#Sta/Elev= 30
  4131.2 1523.46  4154.2  1521.4  4192.5 1522.19  4197.6 1520.64  4241.1 1524.11
  4246.2 1522.53  4265.6 1524.23  4289.6 1522.35  4347.5 1522.58  4685.7 1503.15
  4757.2 1497.09  4900.8 1490.55  4972.1 1493.91  4977.2 1493.58  5000.3 1484.27
    5003 1483.77  5006.3 1484.27  5020.7 1488.65  5095.5 1493.18  5177.5 1494.93
  5209.9 1497.98  5248.2 1511.47  5253.3 1511.03  5279.9 1517.26  5296.8 1525.47
  5301.9 1525.38  5340.2 1543.64  5345.3 1542.45  5351.6 1546.86  5363.9 1549.44
#Mann= 4 ,-1 , 0
  4131.2      .1       0  4757.2     .16       0  5000.3     .07       0
  5006.3     .16       0
Bank Sta=5000.3,5006.3
XS Rating Curve= 0 ,0
Exp/Cntr=0.3,0.1

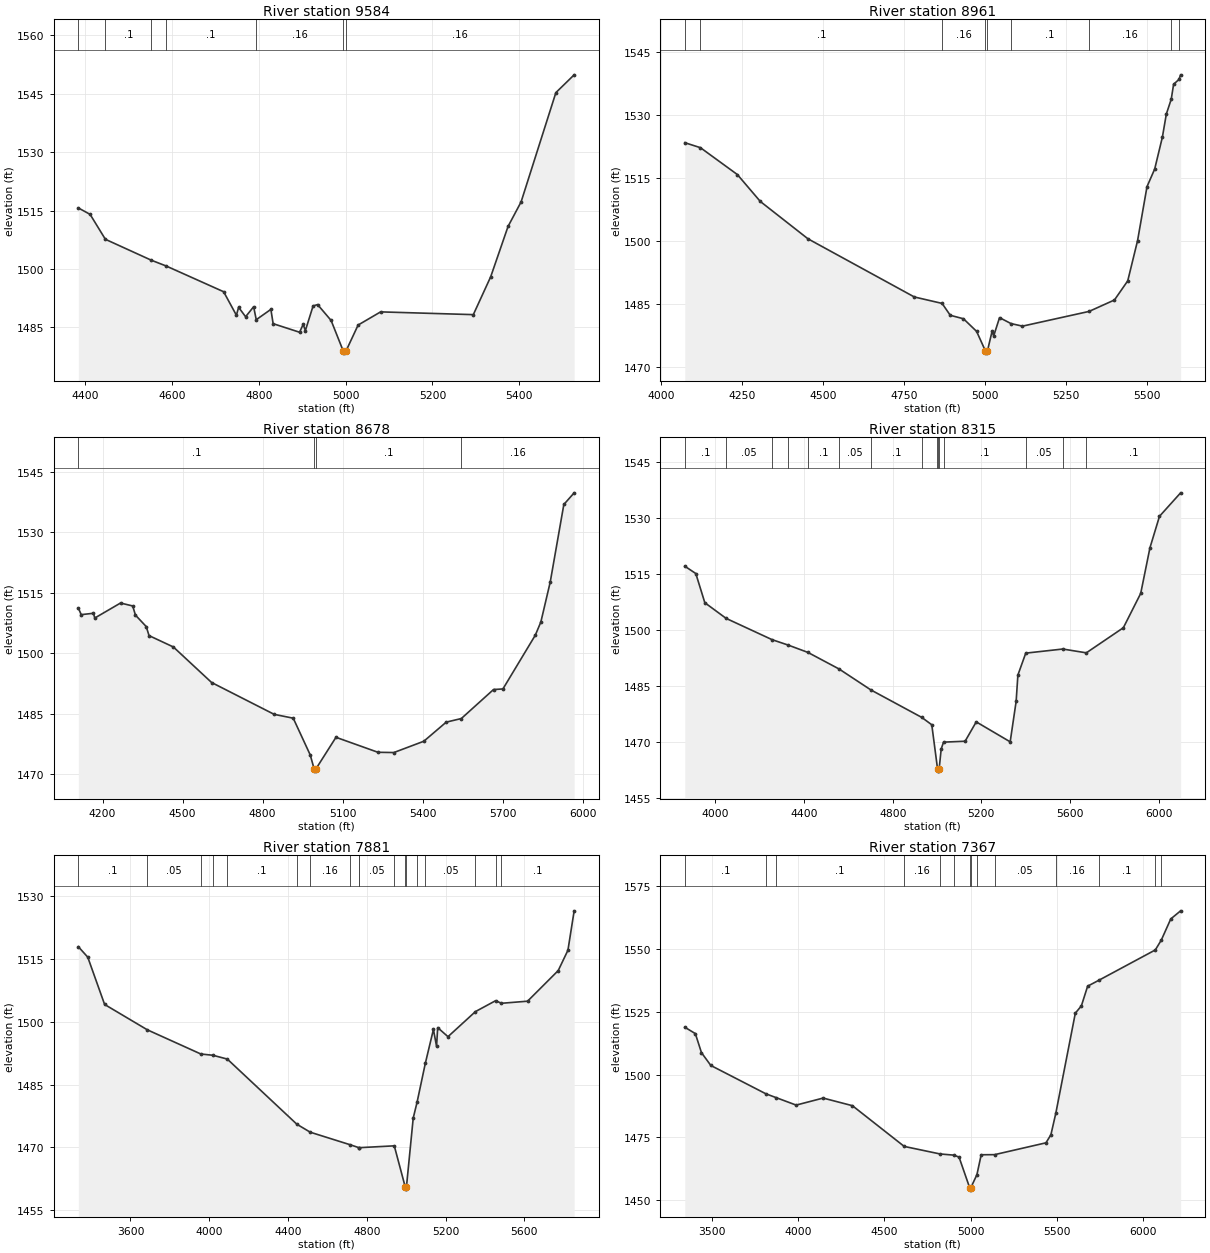
Type RM Length L Ch R = 1 ,9584    ,623,623,623
BEGIN DESCRIPTION:
WEST FORK ROCKY CREEK 21.0
END DESCRIPTION:
XS GIS Cut Line= 3
      2857616.46     10043615.31      2857825.28     10042849.66
      2857835.22     10042501.62
#Sta/Elev= 30
  4384.6 1515.69  4411.7 1514.04  4446.9 1507.64  4552.9 1502.26  4586.6  1500.8
  4719.2 1494.18  4748.6 1488.15  4753.7 1490.18  4769.8 1487.76  4788.3 1490.33
  4794.3    1487    4828 1489.65  4833.2 1485.98  4894.1 1483.78  4902.3 1485.79
  4907.5 1484.22  4925.2 1490.53  4935.6 1490.88  4966.7 1486.81  4994.8 1478.92
  4997.5 1478.42  5000.8 1478.92  5028.9 1485.63  5080.7 1489.01  5294.2  1488.3
  5334.2 1498.02  5374.2 1510.95  5404.2 1517.24  5484.3 1545.29  5526.4 1549.86
#Mann= 7 ,-1 , 0
  4384.6     .16       0  4446.9      .1       0  4552.9     .16       0
  4586.6      .1       0  4794.3     .16       0  4994.8     .07       0
  5000.8     .16       0
Bank Sta=4994.8,5000.8
XS Rating Curve= 0 ,0
Exp/Cntr=0.3,0.1

Type RM Length L Ch R = 1 ,8961    ,283,283,283
BEGIN DESCRIPTION:
WEST FORK ROCKY CREEK 20.0
END DESCRIPTION:
XS GIS Cut Line= 3
      2858153.41     10043824.07      2858342.33     10042640.84
      2858213.25     10042333.03
#Sta/Elev= 30
    4072 1523.38  4120.4 1522.19  4234.4 1515.81  4305.3 1509.42  4452.5 1500.55
  4781.2 1486.73    4867  1485.2  4892.2 1482.38  4933.1 1481.55  4973.6 1478.56
    5001 1473.89  5003.7 1473.39    5007 1473.89  5021.4 1478.56  5026.5  1477.5
  5044.5 1481.82  5079.9 1480.41  5115.4  1479.8  5321.2  1483.3  5399.6 1486.02
  5440.6 1490.56  5470.9 1500.09  5500.1 1512.93  5523.9 1517.13  5547.7 1524.72
  5559.9  1530.2    5575  1533.7  5582.3 1537.26  5598.7 1538.39    5604  1539.5
#Mann= 9 ,-1 , 0
    4072     .16       0  4120.4      .1       0    4867     .16       0
    5001     .07       0    5007     .16       0  5079.9      .1       0
  5321.2     .16       0    5575      .1       0  5598.7     .16       0
Bank Sta=5001,5007
XS Rating Curve= 0 ,0
Exp/Cntr=0.3,0.1

Type RM Length L Ch R = 1 ,8678    ,363,363,363
BEGIN DESCRIPTION:
WEST FORK ROCKY CREEK 19.0
END DESCRIPTION:
XS GIS Cut Line= 3
      2858372.16     10043913.61      2858630.69      10042630.9
      2858283.05      10042203.8
#Sta/Elev= 30
    4109 1511.15  4119.9 1509.53  4165.6 1509.87  4170.7 1508.69  4267.2 1512.41
  4312.9 1511.68  4323.1 1509.42  4363.7 1506.56  4374.1 1504.33  4465.4 1501.51
  4608.7  1492.7  4843.4  1484.8  4914.8 1483.85  4978.6 1474.73  4993.4 1471.22
  4996.1 1470.72  4999.4 1471.22  5075.1 1479.11  5232.6 1475.39  5292.2 1475.33
  5404.4 1478.13  5488.5 1482.87  5545.1 1483.76  5665.9 1490.96  5701.1  1491.1
  5822.5 1504.43  5843.3  1507.7  5878.5 1517.62  5929.5 1536.85  5968.2 1539.74
#Mann= 4 ,-1 , 0
    4109      .1       0  4993.4     .07       0  4999.4      .1       0
  5545.1     .16       0
Bank Sta=4993.4,4999.4
XS Rating Curve= 0 ,0
Exp/Cntr=0.3,0.1

Type RM Length L Ch R = 1 ,8315    ,434,434,434
BEGIN DESCRIPTION:
WEST FORK ROCKY CREEK 18.0
END DESCRIPTION:
XS GIS Cut Line= 4
      2858730.13     10044072.67      2858899.16     10043138.01
      2858859.39     10042620.96      2858372.84     10042025.19
#Sta/Elev= 30
  3861.6 1517.07  3911.3  1515.1    3952 1507.28  4048.2 1503.08  4255.5 1497.38
  4329.5  1495.9    4417 1493.97  4558.2 1489.51  4701.1 1483.92  4930.9 1476.55
  4976.2 1474.57  5001.8 1462.95  5003.3 1462.65    5006 1462.15  5009.3 1462.65
  5018.7 1468.08  5029.2 1469.92  5126.6 1470.16  5176.8 1475.35    5330    1470
  5356.9 1480.83  5364.8  1487.9  5400.3 1493.77  5567.4 1494.87  5673.7 1493.85
  5840.8 1500.58  5919.1 1509.78  5960.7 1521.99  6003.8 1530.44  6099.2 1536.73
#Mann= 15 ,-1 , 0
  3861.6      .1       0  4048.2     .05       0  4255.5      .1       0
  4329.5     .05       0    4417      .1       0  4558.2     .05       0
  4701.1      .1       0  4930.9     .05       0  5001.8     .16       0
  5003.3    .035       0  5009.3     .16       0  5029.2      .1       0
  5400.3     .05       0  5567.4     .16       0  5673.7      .1       0
Bank Sta=5003.3,5009.3
XS Rating Curve= 0 ,0
Exp/Cntr=0.3,0.1

Type RM Length L Ch R = 1 ,7881    ,514,514,514
BEGIN DESCRIPTION:
WEST FORK ROCKY CREEK 17.0
END DESCRIPTION:
XS GIS Cut Line= 4
      2858799.73     10044162.17      2859187.52     10042789.99
      2858968.77      10042402.2       2858482.5     10041975.48
#Sta/Elev= 30
  3335.1 1517.85  3382.9 1515.36  3468.6 1504.08  3685.7 1498.03  3957.3 1492.27
  4018.4 1491.97  4091.7 1491.06  4444.9 1475.53  4512.9 1473.63  4714.9 1470.65
  4760.3 1469.94  4761.3 1469.94  4939.7 1470.38  4995.4 1460.56  4998.1 1460.06
  5001.4 1460.56  5035.9 1477.01  5055.4 1480.77  5097.4 1490.06  5138.5 1498.13
  5154.4  1494.1  5160.1 1498.56  5212.4  1496.4  5351.9 1502.38  5454.4 1504.98
    5484 1504.36  5616.6 1504.86  5772.3 1512.16  5821.6 1517.01  5853.2  1526.4
#Mann= 18 ,-1 , 0
  3335.1      .1       0  3685.7     .05       0  3957.3      .1       0
  4018.4     .05       0  4091.7      .1       0  4444.9     .05       0
  4512.9     .16       0  4714.9     .05       0  4760.3     .16       0
  4761.3     .05       0  4939.7     .16       0  4995.4     .07       0
  5001.4     .16       0  5055.4      .1       0  5097.4     .05       0
  5351.9      .1       0  5454.4     .16       0    5484      .1       0
Bank Sta=4995.4,5001.4
XS Rating Curve= 0 ,0
Exp/Cntr=0.3,0.1

Type RM Length L Ch R = 1 ,7367    ,499,499,499
BEGIN DESCRIPTION:
WEST FORK ROCKY CREEK 16.0
END DESCRIPTION:
XS GIS Cut Line= 3
      2858809.66     10044221.87       2859366.5     10042789.99
       2860390.7      10041924.9
#Sta/Elev= 30
  3342.1 1518.77  3403.4 1516.22  3438.7 1508.68  3493.1 1503.59  3812.7 1492.34
  3872.6 1490.81  3988.2 1487.86  4144.8 1490.65  4314.7 1487.62  4615.3 1471.46
    4823 1468.47  4903.1    1468  4933.4 1467.22  4995.3 1455.01  4998.1 1454.51
  5001.3 1455.01  5037.1 1460.24    5062 1468.15  5139.5 1468.19  5437.8 1472.89
  5466.4 1476.09    5495 1484.66  5608.1 1524.34  5643.3 1527.25  5679.5 1535.05
  5744.3 1537.39  6072.3 1549.44  6106.9 1553.34    6162 1561.75  6219.1 1564.96
#Mann= 14 ,-1 , 0
  3342.1      .1       0  3812.7     .05       0  3872.6      .1       0
  4615.3     .16       0    4823     .05       0  4903.1      .1       0
  4995.3     .07       0  5001.3      .1       0  5037.1     .16       0
  5139.5     .05       0    5495     .16       0  5744.3      .1       0
  6072.3     .05       0  6106.9      .1       0
Bank Sta=4995.3,5001.3
XS Rating Curve= 0 ,0
Exp/Cntr=0.3,0.1

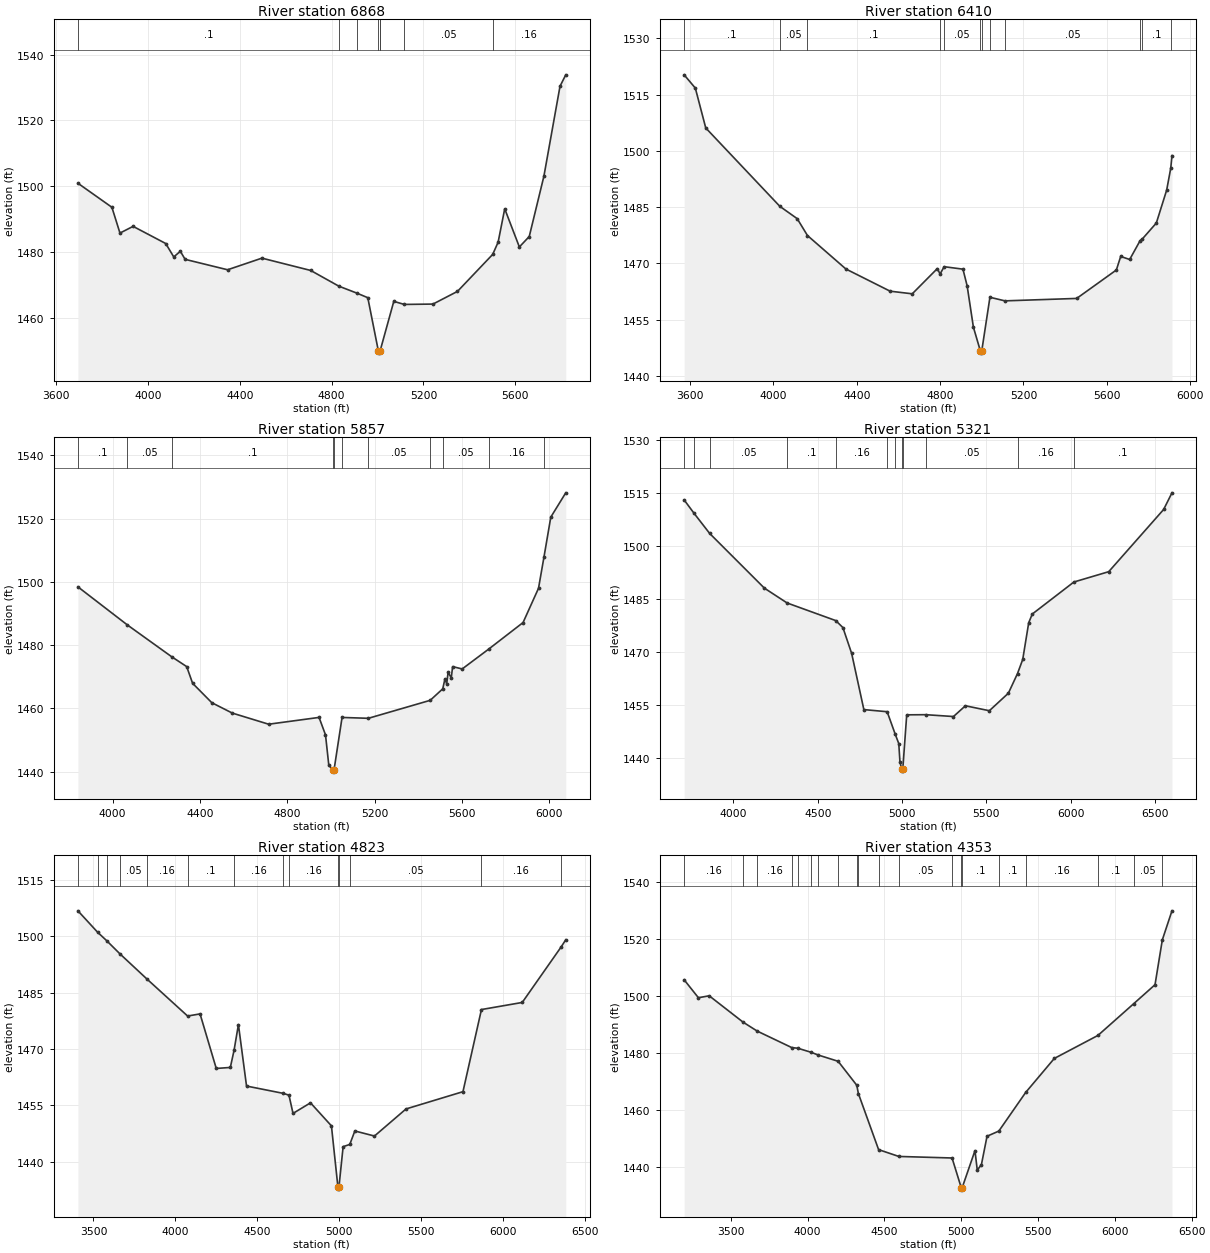
Type RM Length L Ch R = 1 ,6868    ,458,458,458
BEGIN DESCRIPTION:
WEST FORK ROCKY CREEK 15.0
END DESCRIPTION:
XS GIS Cut Line= 2
      2858928.98     10044102.54      2860281.32     10042461.83
#Sta/Elev= 30
  3694.1 1500.87  3842.1 1493.56  3877.3 1485.71  3934.6 1487.75  4076.7 1482.53
  4111.8 1478.45  4140.5 1480.17  4161.3 1477.71  4346.4 1474.54    4496 1478.08
  4708.6 1474.33  4831.3 1469.55  4908.8 1467.46  4957.5 1466.04    5004 1449.67
  5006.8 1449.17    5010 1449.67    5011 1449.81  5070.8 1464.92  5116.7 1463.99
  5241.6  1464.1  5348.4 1467.96    5502 1479.23  5525.6 1482.95  5554.3  1493.1
  5618.1 1481.48  5661.2 1484.66    5725 1502.99  5795.3  1530.4  5820.3 1533.87
#Mann= 8 ,-1 , 0
  3694.1      .1       0  4831.3     .16       0  4908.8      .1       0
    5004     .07       0    5010      .1       0    5011     .16       0
  5116.7     .05       0    5502     .16       0
Bank Sta=5004,5010
XS Rating Curve= 0 ,0
Exp/Cntr=0.3,0.1

Type RM Length L Ch R = 1 ,6410    ,553,553,553
BEGIN DESCRIPTION:
WEST FORK ROCKY CREEK 14.0
END DESCRIPTION:
XS GIS Cut Line= 4
      2858819.61     10044361.05      2859804.01     10043476.09
      2860360.84     10043436.31      2860649.06     10043078.52
#Sta/Elev= 30
  3571.5 1520.29  3625.2 1516.75  3675.2 1506.13  4030.9 1485.23    4114 1481.96
  4163.5 1477.45    4348 1468.53  4560.2 1462.62  4666.4 1461.92  4786.7 1468.65
  4799.9  1467.2  4819.4 1469.15  4909.7 1468.49  4929.8 1464.05  4959.8 1453.04
  4993.7 1446.61  4996.4 1446.11  4999.7 1446.61  5039.2    1461  5111.2 1460.04
  5455.6 1460.69    5646 1468.27  5666.8 1471.88  5709.9 1471.07  5760.2 1476.11
  5771.4 1476.59  5837.9 1480.79  5887.5 1489.57    5907 1495.39  5912.9 1498.74
#Mann= 12 ,-1 , 0
  3571.5      .1       0  4030.9     .05       0  4163.5      .1       0
  4799.9     .16       0  4819.4     .05       0  4993.7    .035       0
  4999.7     .05       0  5039.2     .16       0  5111.2     .05       0
  5760.2     .16       0  5771.4      .1       0    5907     .16       0
Bank Sta=4993.7,4999.7
XS Rating Curve= 0 ,0
Exp/Cntr=0.3,0.1

Type RM Length L Ch R = 1 ,5857    ,536,536,536
BEGIN DESCRIPTION:
WEST FORK ROCKY CREEK 12.0
END DESCRIPTION:
XS GIS Cut Line= 3
      2859108.01     10044530.06      2860350.89     10043734.61
      2860808.04     10043128.39
#Sta/Elev= 30
  3841.1 1498.39  4067.5 1486.36  4270.8 1476.29  4339.4 1473.18  4366.5  1467.9
  4454.4 1461.77  4548.3 1458.49  4714.9 1454.97  4945.8 1457.12  4975.3 1451.61
  4990.5 1441.97  5008.7 1440.64  5011.4 1440.14  5014.7 1440.64  5051.2 1457.11
  5171.6 1456.84  5454.9 1462.52  5512.5 1466.16  5522.4 1469.27  5530.7 1467.76
    5537 1471.38  5551.5 1469.65  5557.8 1473.18  5601.5 1472.44  5723.8 1478.76
  5880.4 1487.11  5951.2 1497.94  5976.2 1507.81  6007.5 1520.44    6076 1528.12
#Mann= 11 ,-1 , 0
  3841.1      .1       0  4067.5     .05       0  4270.8      .1       0
  5008.7     .07       0  5014.7      .1       0  5051.2     .16       0
  5171.6     .05       0  5454.9     .16       0  5512.5     .05       0
  5723.8     .16       0  5976.2      .1       0
Bank Sta=5008.7,5014.7
XS Rating Curve= 0 ,0
Exp/Cntr=0.3,0.1

Type RM Length L Ch R = 1 ,5321    ,498,498,498
BEGIN DESCRIPTION:
WEST FORK ROCKY CREEK 11.0
END DESCRIPTION:
XS GIS Cut Line= 3
      2858948.92     10044738.88      2860440.38     10044341.16
      2861353.47     10043348.67
#Sta/Elev= 30
  3707.9 1513.08  3766.5 1509.31  3859.3  1503.6  4183.5 1488.14  4318.4 1483.94
  4606.7 1478.96  4649.2 1476.98    4701 1469.68  4773.4 1453.79  4911.5 1453.19
  4959.1 1446.86  4980.4 1444.18  4987.4    1439  4998.1 1436.89  5000.9 1436.39
  5004.1 1436.89  5027.5 1452.31  5140.3 1452.35  5304.7 1451.83  5375.6 1454.87
  5517.4 1453.47  5630.3 1458.43  5684.4 1463.99  5715.3 1467.97  5750.8 1478.36
  5772.1 1480.82  6018.6 1489.87  6225.2 1492.79  6550.7 1510.38  6600.1 1515.09
#Mann= 12 ,-1 , 0
  3707.9     .05       0  3766.5      .1       0  3859.3     .05       0
  4318.4      .1       0  4606.7     .16       0  4911.5      .1       0
  4959.1     .16       0  4998.1     .07       0  5004.1     .16       0
  5140.3     .05       0  5684.4     .16       0  6018.6      .1       0
Bank Sta=4998.1,5004.1
XS Rating Curve= 0 ,0
Exp/Cntr=0.3,0.1

Type RM Length L Ch R = 1 ,4823    ,470,470,470
BEGIN DESCRIPTION:
WEST FORK ROCKY CREEK 10.0
END DESCRIPTION:
XS GIS Cut Line= 2
      2859386.36     10046031.57      2861294.46     10043745.82
#Sta/Elev= 30
  3405.4 1506.84  3525.8 1501.12    3580 1498.92  3660.4 1495.43  3827.5 1488.63
  4074.9  1478.8  4150.8 1479.37  4249.7 1464.83  4335.6  1465.1  4358.2 1469.63
    4385 1476.52  4434.5 1460.14  4657.7  1458.2  4693.4 1457.72  4718.2 1452.85
  4824.9 1455.67  4952.7 1449.53  4992.4 1433.17  4995.2 1432.67  4998.4 1433.17
  5024.1 1443.99  5064.6 1444.58  5095.6 1448.17  5215.4 1446.82    5408 1454.04
  5755.5 1458.64  5868.3 1480.53  6117.3 1482.42  6353.7 1497.15  6382.9 1499.12
#Mann= 14 ,-1 , 0
  3405.4     .16       0  3525.8     .05       0    3580      .1       0
  3660.4     .05       0  3827.5     .16       0  4074.9      .1       0
  4358.2     .16       0  4657.7      .1       0  4693.4     .16       0
  4992.4     .07       0  4998.4     .16       0  5064.6     .05       0
  5868.3     .16       0  6353.7      .1       0
Bank Sta=4992.4,4998.4
XS Rating Curve= 0 ,0
Exp/Cntr=0.3,0.1

Type RM Length L Ch R = 1 ,4353    ,815,815,815
BEGIN DESCRIPTION:
WEST FORK ROCKY CREEK 9.0
END DESCRIPTION:
XS GIS Cut Line= 3
      2859475.91     10046150.82      2860748.63     10045116.74
      2861623.53     10043854.09
#Sta/Elev= 30
  3195.8 1505.59  3288.6  1499.3  3358.9 1499.98  3578.9 1490.77  3671.5 1487.61
  3896.9 1481.82  3934.9 1481.62  4023.4 1480.17  4066.7 1479.26  4198.4 1477.03
  4319.8 1468.63  4330.1 1465.74  4461.8 1446.08  4593.5 1443.69  4940.1 1443.15
  4999.9 1432.74  5002.6 1432.24  5005.9 1432.74  5089.3 1445.73  5104.2 1438.89
  5131.3 1440.85  5167.8 1450.77  5244.6 1452.58  5419.6 1466.13  5605.8 1478.03
  5889.8 1486.09  6122.1 1497.18  6261.5 1503.86  6309.1 1519.59  6371.8 1529.75
#Mann= 20 ,-1 , 0
  3195.8     .16       0  3578.9     .05       0  3671.5     .16       0
  3896.9     .05       0  3934.9     .16       0  4023.4     .05       0
  4066.7      .1       0  4198.4     .05       0  4319.8      .1       0
  4330.1     .16       0  4461.8      .1       0  4593.5     .05       0
  4940.1      .1       0  4999.9     .07       0  5005.9      .1       0
  5244.6      .1       0  5419.6     .16       0  5889.8      .1       0
  6122.1     .05       0  6309.1      .1       0
Bank Sta=4999.9,5005.9
XS Rating Curve= 0 ,0
Exp/Cntr=0.3,0.1