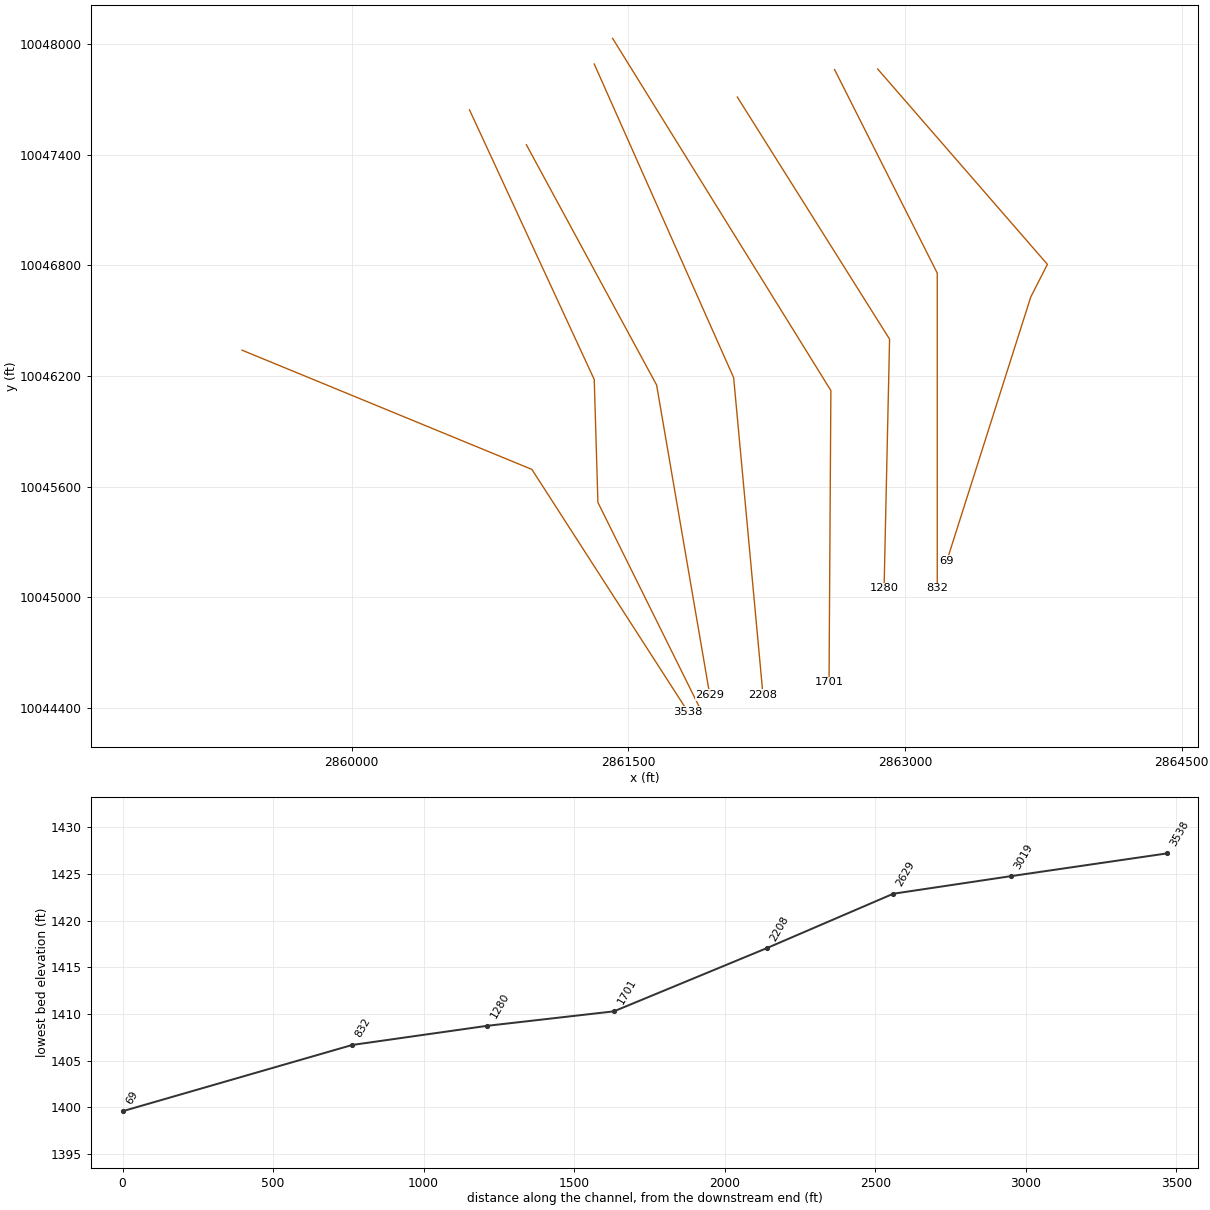
HEC-RAS study WEST FORK ROCKY CREEK.prj: WEST FORK ROCKY CREEK Base Level Engineering

--- WEST FORK ROCKY CREEK.g01 (geometry) --- (continued)

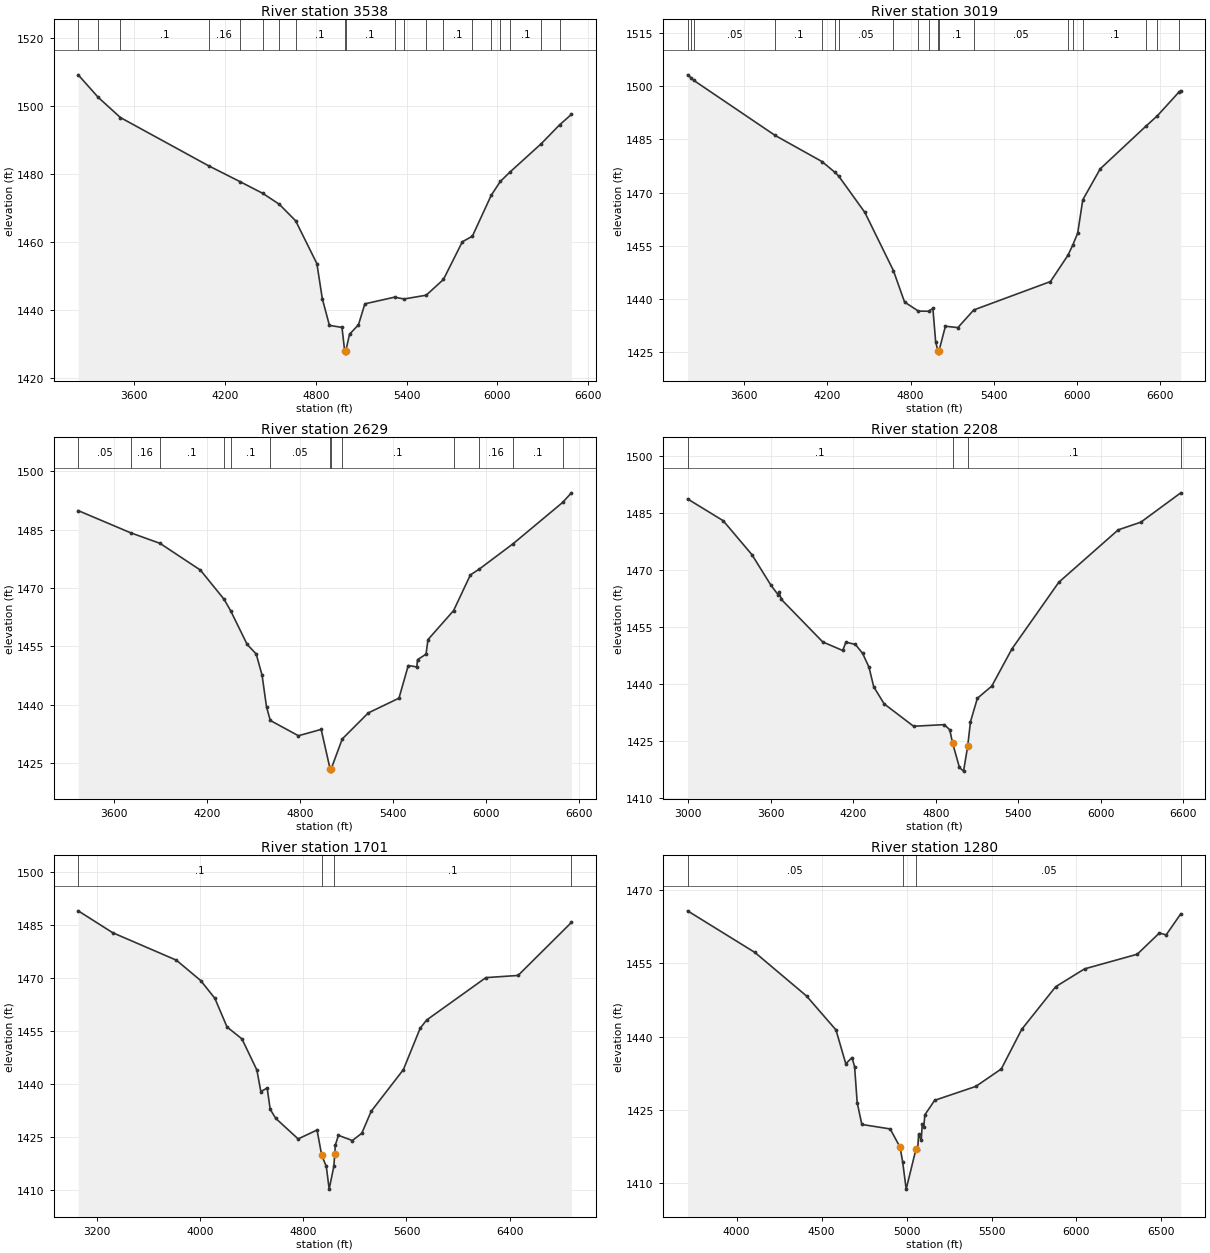
Type RM Length L Ch R = 1 ,3538    ,519,519,519
BEGIN DESCRIPTION:
WEST FORK ROCKY CREEK 8.0
END DESCRIPTION:
XS GIS Cut Line= 3
      2859406.28     10046339.77      2860977.32     10045693.46
      2861822.51     10044380.93
#Sta/Elev= 30
  3229.8 1509.18  3361.7 1502.57  3508.4 1496.61  4092.9 1482.36  4297.6 1477.76
    4450 1474.26  4558.6 1471.07  4667.2 1466.18  4807.5 1453.57  4843.3 1443.24
  4890.2 1435.39  4973.4 1434.78  4991.5 1427.71  4994.3 1427.21  4997.5 1427.71
  5023.4 1432.78  5082.3 1435.56  5124.6 1441.73  5320.7 1443.69  5383.4 1443.16
    5530 1444.27  5643.8  1448.9  5768.9 1460.01  5835.2 1461.65  5960.1 1473.73
  6020.7 1477.82  6084.7 1480.58  6291.7 1488.95  6411.2 1494.43  6489.7 1497.52
#Mann= 20 ,-1 , 0
  3229.8     .16       0  3361.7     .16       0  3508.4      .1       0
  4092.9     .16       0  4297.6      .1       0    4450     .16       0
  4558.6     .05       0  4667.2      .1       0  4991.5     .07       0
  4997.5      .1       0  5320.7      .1       0  5383.4     .05       0
    5530      .1       0  5643.8      .1       0  5835.2     .16       0
  5960.1      .1       0  6020.7     .16       0  6084.7      .1       0
  6291.7     .16       0  6411.2     .05       0
Bank Sta=4991.5,4997.5
XS Rating Curve= 0 ,0
Exp/Cntr=0.3,0.1

Type RM Length L Ch R = 1 ,3019    ,390,390,390
BEGIN DESCRIPTION:
WEST FORK ROCKY CREEK 7.0
END DESCRIPTION:
XS GIS Cut Line= 4
      2860639.24     10047642.38       2861315.4     10046180.68
      2861335.29     10045514.48      2861902.07     10044370.96
#Sta/Elev= 30
  3193.1 1503.17  3218.9 1502.33  3237.3 1501.62  3823.9  1486.1  4161.6 1478.74
  4256.2 1475.66  4282.1 1474.64  4470.4 1464.41    4676 1448.04  4756.5 1439.16
  4856.3 1436.61  4929.9 1436.57  4960.6 1437.36  4980.6 1427.94  4997.7 1425.27
  5000.4 1424.77  5003.7 1425.27  5050.7 1432.35  5140.7 1431.96  5254.9 1436.93
  5807.6 1444.93  5933.1  1452.3    5967 1455.09  6003.8 1458.58  6040.6 1467.97
  6166.3 1476.69  6494.3 1488.67  6578.1 1491.64  6731.7 1498.25  6746.4 1498.69
#Mann= 19 ,-1 , 0
  3193.1     .05       0  3218.9      .1       0  3237.3     .05       0
  3823.9      .1       0  4161.6     .05       0  4256.2      .1       0
  4282.1     .05       0    4676      .1       0  4856.3     .05       0
  4929.9      .1       0  4997.7     .07       0  5003.7      .1       0
  5254.9     .05       0  5933.1      .1       0    5967     .16       0
  6040.6      .1       0  6494.3     .16       0  6578.1     .05       0
  6731.7      .1       0
Bank Sta=4997.7,5003.7
XS Rating Curve= 0 ,0
Exp/Cntr=0.3,0.1

Type RM Length L Ch R = 1 ,2629    ,421,421,421
BEGIN DESCRIPTION:
WEST FORK ROCKY CREEK 6.0
END DESCRIPTION:
XS GIS Cut Line= 3
      2860947.51      10047453.4      2861653.47     10046150.85
      2861941.82     10044470.47
#Sta/Elev= 30
  3366.3 1489.88  3704.6 1484.18  3894.8 1481.46  4155.9 1474.58    4309 1467.07
  4351.5  1464.1  4457.9 1455.47  4516.2 1453.03  4554.3 1447.56    4583 1439.41
  4607.4 1435.92  4789.1 1431.99  4936.2 1433.62  4994.1 1423.39  4996.9 1422.89
  5000.1 1423.39  5072.3 1431.16  5240.6 1437.86  5438.8 1441.65  5498.8 1450.05
  5553.7 1449.68  5558.8 1451.54  5613.7 1452.97  5626.2 1456.71  5791.8 1464.18
  5900.1 1473.34  5956.9 1474.82  6176.1 1481.36  6496.2 1491.98  6552.8 1494.45
#Mann= 13 ,-1 , 0
  3366.3     .05       0  3704.6     .16       0  3894.8      .1       0
    4309     .05       0  4351.5      .1       0  4607.4     .05       0
  4994.1    .035       0  5000.1     .05       0  5072.3      .1       0
  5791.8     .05       0  5956.9     .16       0  6176.1      .1       0
  6496.2     .05       0
Bank Sta=4994.1,5000.1
XS Rating Curve= 0 ,0
Exp/Cntr=0.3,0.1

Type RM Length L Ch R = 1 ,2208    ,507,507,507
BEGIN DESCRIPTION:
WEST FORK ROCKY CREEK 5.0
END DESCRIPTION:
XS GIS Cut Line= 3
       2861315.4     10047890.93      2862071.09     10046190.62
      2862230.19     10044470.45
#Sta/Elev= 30
  2994.4  1488.7    3254 1482.95  3462.4 1474.04  3601.9 1465.93  3653.9 1463.45
  3659.4 1464.27  3677.2 1462.23  3978.1 1451.05  4123.1  1448.8  4146.4    1451
  4216.1 1450.38  4268.1 1448.04  4314.6 1444.38  4348.8 1439.25  4424.9 1434.75
  4638.8 1428.86    4862 1429.29  4902.2 1427.92  4922.3 1424.46  4972.5 1418.01
  5002.3 1417.05  5032.7 1423.66  5052.8 1430.06    5103 1436.23  5207.5 1439.42
  5354.1 1449.21  5695.5 1466.77  6127.4 1480.55  6292.8 1482.59  6582.6  1490.3
#Mann= 4 ,-1 , 0
  2994.4      .1       0  4922.3     .05       0  5032.7      .1       0
  6582.6     .16       0
Bank Sta=4922.3,5032.7
XS Rating Curve= 0 ,0
Exp/Cntr=0.3,0.1

Type RM Length L Ch R = 1 ,1701    ,421,421,421
BEGIN DESCRIPTION:
WEST FORK ROCKY CREEK 4.0
END DESCRIPTION:
XS GIS Cut Line= 3
      2861414.83     10048030.15      2862598.09     10046121.02
      2862588.15     10044540.03
#Sta/Elev= 30
  3052.9 1489.11  3320.6 1482.91  3814.4 1475.14  4003.5 1469.36  4113.4 1464.33
  4207.9 1456.21  4323.6 1452.84  4439.4 1444.02  4470.2 1437.92  4519.3 1438.92
  4542.8 1432.89  4585.9 1430.33  4759.6 1424.51  4906.1 1427.03  4942.7 1419.86
  4978.1 1416.72  5000.4 1410.29    5037 1416.82  5043.1 1420.19    5049 1422.87
  5072.3 1425.52  5180.2 1424.06  5253.4 1426.11  5326.3 1432.33  5576.3 1444.14
  5706.3 1455.84  5756.3 1458.17  6216.3 1470.19  6466.3 1470.81    6880 1485.81
#Mann= 4 ,-1 , 0
  3052.9      .1       0  4942.7     .05       0    5037      .1       0
    6880      .1       0
Bank Sta=4942.7,5043.1
XS Rating Curve= 0 ,0
Exp/Cntr=0.3,0.1

Type RM Length L Ch R = 1 ,1280    ,448,448,448
BEGIN DESCRIPTION:
WEST FORK ROCKY CREEK 3.0
END DESCRIPTION:
XS GIS Cut Line= 3
      2862090.98     10047711.96      2862916.28     10046399.44
      2862886.47     10045047.89
#Sta/Elev= 30
  3711.4 1465.75  4107.8 1457.22  4411.7  1448.3  4584.8 1441.35  4642.5 1434.42
    4679 1435.69  4694.3 1433.84  4709.6 1426.46    4737 1421.99  4903.9 1421.07
  4961.7 1417.34    4977 1414.38  4997.9 1408.74  5055.9 1416.98  5065.3 1416.83
  5071.2 1419.97  5086.5 1418.75  5092.4 1421.99  5101.8 1421.52  5107.7 1423.95
  5165.4 1426.93  5407.6 1429.78  5557.6 1433.36  5677.6 1441.46  5877.7 1450.21
  6047.7 1453.86  6357.8 1456.86  6487.8 1461.21  6527.8 1460.82  6613.7 1465.13
#Mann= 4 ,-1 , 0
  3711.4     .05       0    4977    .035       0  5055.9     .05       0
  6613.7      .1       0
Bank Sta=4961.7,5055.9
XS Rating Curve= 0 ,0
Exp/Cntr=0.3,0.1

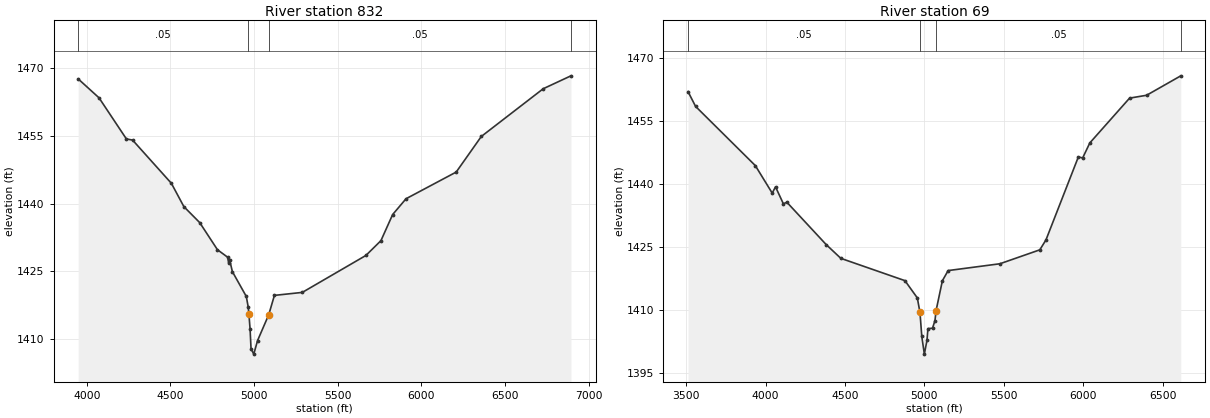
Type RM Length L Ch R = 1 ,832     ,763,763,763
BEGIN DESCRIPTION:
WEST FORK ROCKY CREEK 2.0
END DESCRIPTION:
XS GIS Cut Line= 3
      2862617.97     10047861.13      2863174.81      10046757.4
      2863174.81     10045047.94
#Sta/Elev= 30
  3948.9 1467.64  4073.5 1463.45  4237.2 1454.34  4274.2 1454.09    4506 1444.52
  4580.8 1439.35  4675.6 1435.81  4781.5 1429.81    4842 1428.16  4848.4 1426.89
    4854 1427.61  4870.7 1424.96    4954 1419.46  4965.5 1417.09  4969.6 1415.51
  4976.4 1412.32  4982.2  1407.9  4998.6 1406.69  5021.2 1409.69  5088.1 1415.42
    5122  1419.7  5288.8 1420.36  5668.8 1428.54  5758.8 1431.82  5828.8  1437.6
  5908.8  1441.1  6208.8 1447.01  6358.8 1454.89  6728.8 1465.46  6894.6 1468.32
#Mann= 4 ,-1 , 0
  3948.9     .05       0  4965.5     .35       0  5088.1     .05       0
  6894.6      .1       0
Bank Sta=4969.6,5088.1
XS Rating Curve= 0 ,0
Exp/Cntr=0.3,0.1

Type RM Length L Ch R = 1 ,69      ,0,0,0
BEGIN DESCRIPTION:
WEST FORK ROCKY CREEK 1.0
END DESCRIPTION:
XS GIS Cut Line= 4
      2862851.67     10047864.05      2863771.84     10046804.99
      2863681.56     10046627.91      2863226.93     10045198.08
#Sta/Elev= 30
  3511.7 1462.11  3559.3 1458.59  3935.4 1444.49  4041.7 1437.94  4062.6 1439.43
    4112 1435.39  4133.8 1435.77  4381.7 1425.67  4473.8  1422.4  4877.3 1417.09
  4955.2 1412.98  4971.9 1409.52  4983.4  1403.8  4999.5 1399.59  5016.3 1402.95
  5021.9 1405.66  5050.8 1405.76  5066.4 1407.58  5073.2 1409.94    5113 1417.07
  5149.3 1419.49    5475 1421.11  5726.4 1424.43  5765.2  1426.8  5969.1 1446.56
  5996.1 1446.31  6041.2 1449.89  6291.5 1460.56  6398.7 1461.24  6613.8 1465.87
#Mann= 4 ,-1 , 0
  3511.7     .05       0  4971.9    .035       0  5073.2     .05       0
  6613.8      .1       0
Bank Sta=4971.9,5073.2
XS Rating Curve= 0 ,0
Exp/Cntr=0.3,0.1

Chan Stop Cuts=-1
Use User Specified Reach Order=0
Composite Channel Slope=5