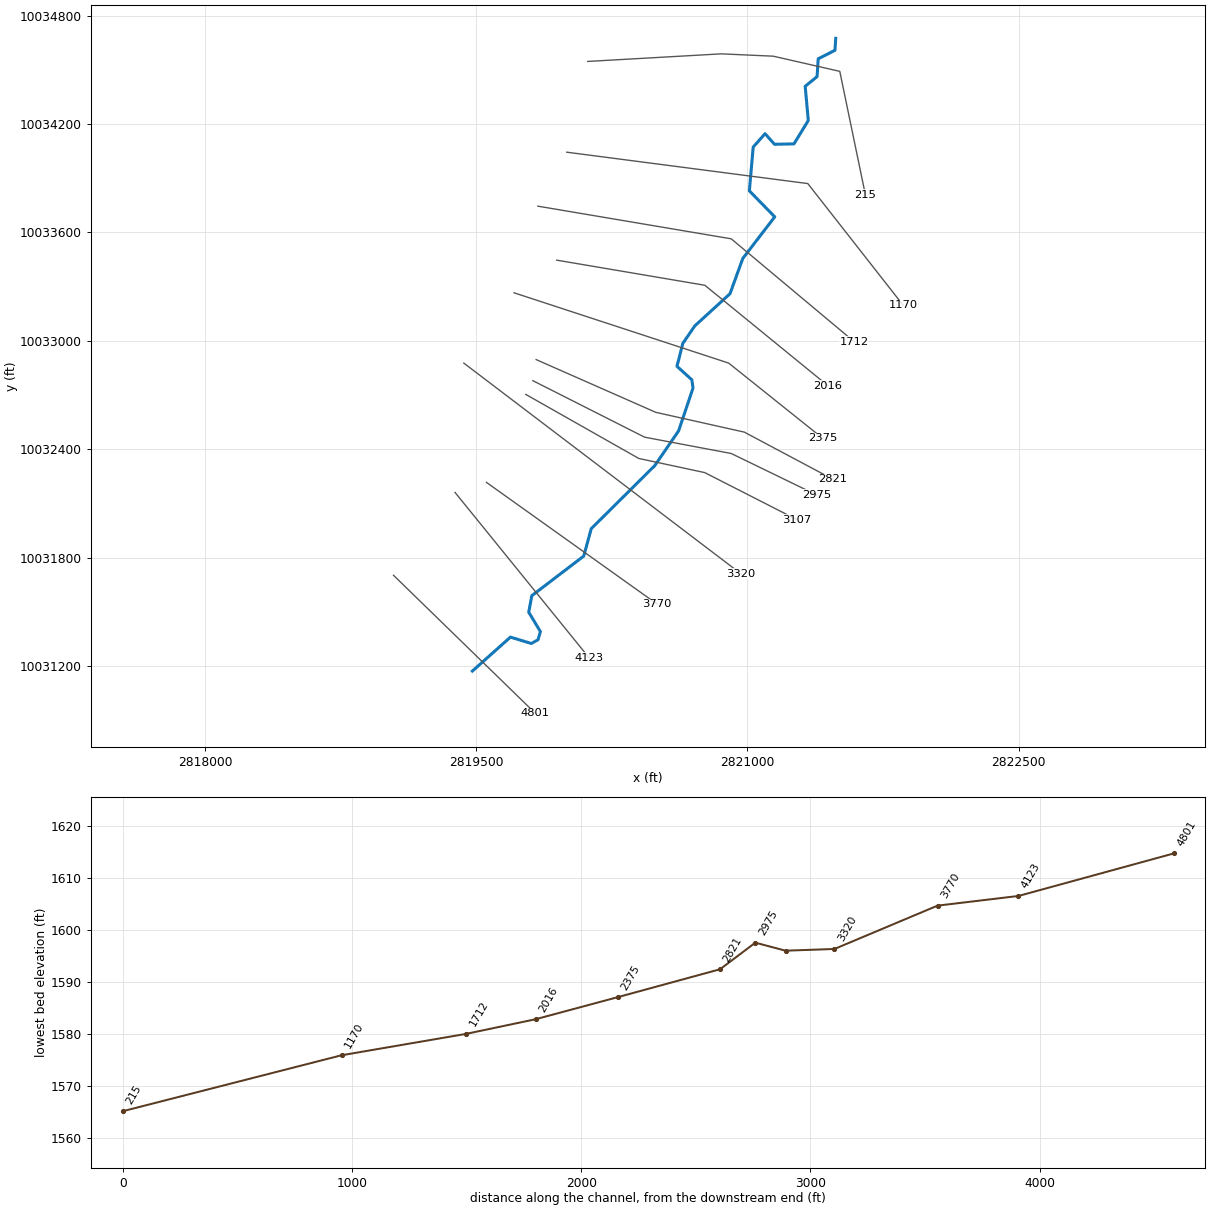
--- WEST FORK THREEMILE CREEK.prj (project) ---

Proj Title=WEST FORK THREEMILE CREEK Base Level Engineering
Current Plan=p01
Default Exp/Contr=0.3,0.1
English Units
Geom File=g01
Flow File=f01
Plan File=p01
Y Axis Title=Elevation
X Axis Title(PF)=Main Channel Distance
X Axis Title(XS)=Station
BEGIN DESCRIPTION:
WEST FORK THREEMILE CREEK
END DESCRIPTION:
DSS Export Rating Curves= 0
DSS Export Rating Curve Sorted= 0
DSS Export Volume Flow Curves= 0
DXF OffsetX= 0
DXF OffsetY= 0
DXF ScaleX= 1
DXF ScaleY= 10

--- WEST FORK THREEMILE CREEK.p01 (plan) ---

Plan Title=Multiple Run
Short Identifier=Multiple
Geom File=g01
Flow File=f01
Subcritical Flow
K Sum by GR= 0
Std Step Tol= 0.01
Critical Tol= 0.01
Num of Std Step Trials= 20
Max Error Tol= 0.3
Flow Tol Ratio= 0.001
Split Flow NTrial= 30
Split Flow Tol= 0.02
Split Flow Ratio= 0.02
Log Output Level= 0
Friction Slope Method= 1
Unsteady Friction Slope Method= 2
Unsteady Bridges Friction Slope Method= 1
Parabolic Critical Depth
Global Vel Dist=  1 , 1 , 1
Global Log Level= 0
CheckData=True
Encroach Param= -1, 0, 0, 0
BEGIN DESCRIPTION:
Multiple Run
END DESCRIPTION:

--- WEST FORK THREEMILE CREEK.f01 (steady flow) ---

Flow Title=Multiple
Program Version=4.10
Number of Profiles= 7
Profile Names=10-year,25-year,50-year,1pct_min,100-year,1pct_plu,500-year
River Rch & RM=WEST FORK THREEM,Reach-1         ,4801
    1229    1821    2345    2210    2989    4042    4875
Boundary for River Rch & Prof#=WEST FORK THREEM,Reach-1         , 1
Up Type= 0
Dn Type= 1
Dn Known WS=1572.72
Boundary for River Rch & Prof#=WEST FORK THREEM,Reach-1         , 2
Up Type= 0
Dn Type= 1
Dn Known WS=1573.5
Boundary for River Rch & Prof#=WEST FORK THREEM,Reach-1         , 3
Up Type= 0
Dn Type= 1
Dn Known WS=1574
Boundary for River Rch & Prof#=WEST FORK THREEM,Reach-1         , 4
Up Type= 0
Dn Type= 1
Dn Known WS=1573.92
Boundary for River Rch & Prof#=WEST FORK THREEM,Reach-1         , 5
Up Type= 0
Dn Type= 1
Dn Known WS=1574.68
Boundary for River Rch & Prof#=WEST FORK THREEM,Reach-1         , 6
Up Type= 0
Dn Type= 1
Dn Known WS=1575.39
Boundary for River Rch & Prof#=WEST FORK THREEM,Reach-1         , 7
Up Type= 0
Dn Type= 1
Dn Known WS=1576.03
DSS Import GetInterval= 0
DSS Import GetPeak= 0
DSS Import FillOption= 0

--- WEST FORK THREEMILE CREEK.g01 (geometry) ---

Geom Title=Existing Conditions
Program Version=4.10

River Reach=WEST FORK THREEM,Reach-1
Reach XY= 30
      2819478.47     10031173.73      2819689.35     10031361.61
      2819804.56     10031326.34      2819841.54     10031346.69
      2819855.01     10031392.07       2819790.3     10031499.48
      2819807.39     10031590.73      2820094.68     10031809.94
      2820136.09     10031961.39      2820487.28     10032309.95
      2820619.55     10032502.79      2820699.02     10032739.06
      2820692.62     10032784.96      2820610.27      10032859.6
      2820642.87     10032986.62      2820709.17     10033083.47
      2820903.64     10033260.97      2820974.32     10033456.02
      2821151.18     10033686.44      2821010.76     10033830.03
        2821032.     10034072.38      2821097.61      10034146.3
      2821149.88     10034087.64      2821257.52     10034089.95
      2821336.71     10034219.27       2821319.5     10034408.24
      2821385.29     10034461.99      2821391.56     10034560.51
      2821484.15     10034607.52      2821488.47     10034673.73

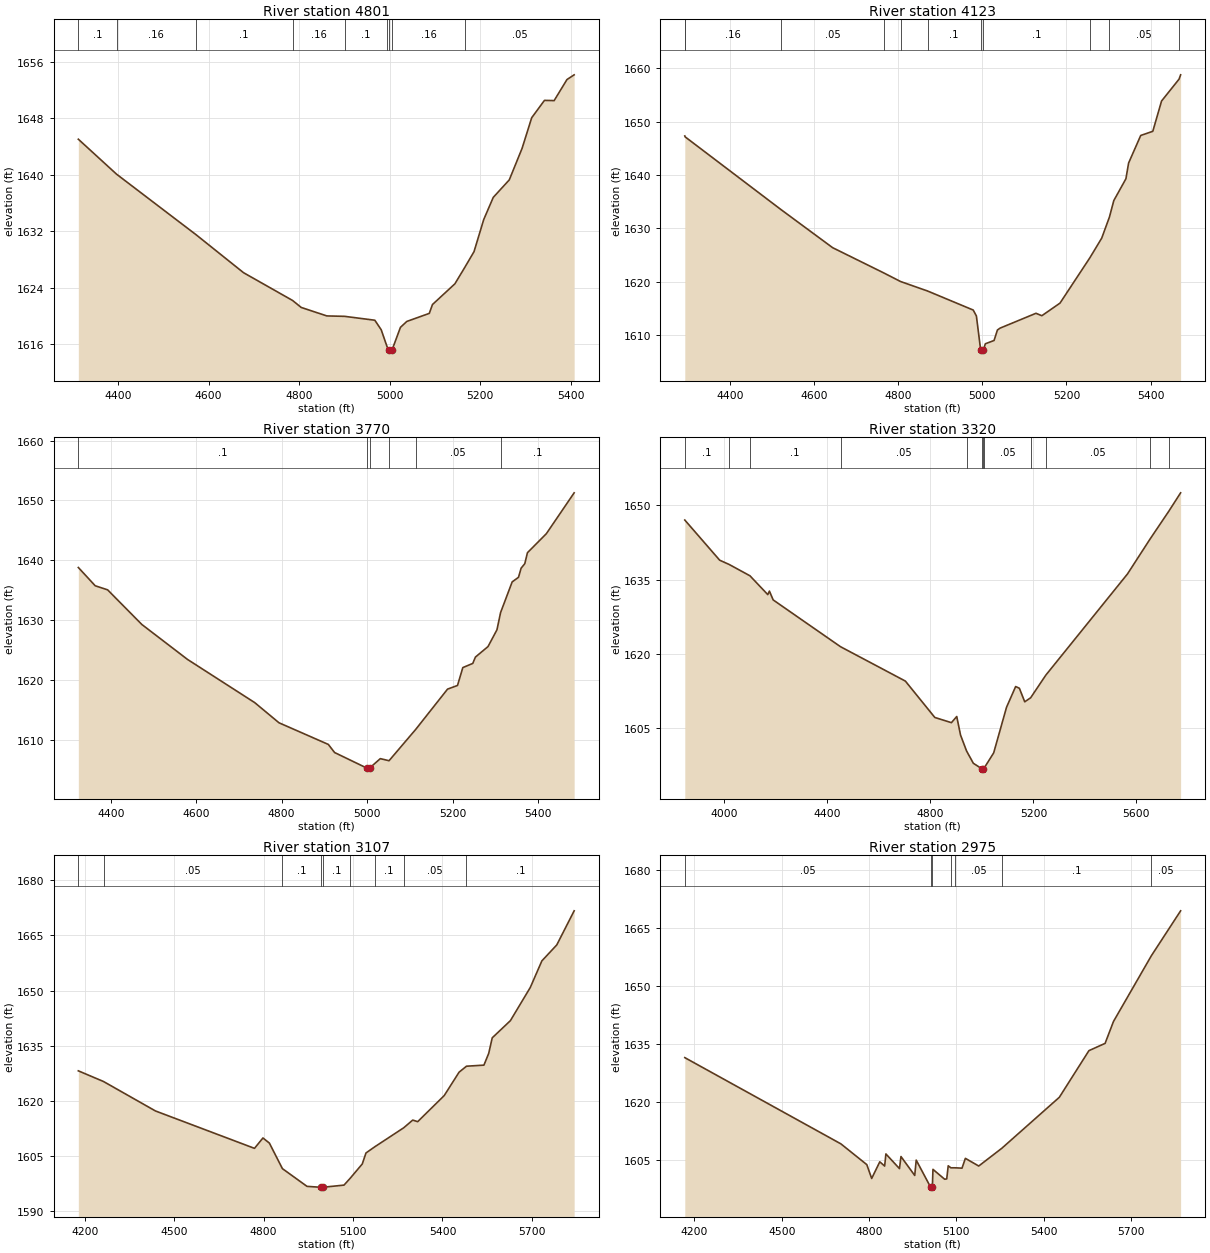
Type RM Length L Ch R = 1 ,4801    ,678,678,678
BEGIN DESCRIPTION:
WEST FORK THREEMILE CREEK 10.0
END DESCRIPTION:
XS GIS Cut Line= 2
      2819042.35     10031703.71      2819827.12     10030939.77
#Sta/Elev= 30
  4312.1 1645.06  4396.5 1640.11  4571.8 1631.55  4677.1 1626.15  4785.3 1622.22
  4804.4 1621.23    4861 1620.03  4900.3 1619.97    4967 1619.42  4981.1 1618.07
  4994.4 1615.61  4999.4 1615.26  5002.2 1614.76  5005.4 1615.26  5023.6 1618.41
  5037.7 1619.25  5087.3 1620.39  5094.3 1621.64  5143.9 1624.58  5165.3 1626.86
  5186.1 1629.13  5207.5 1633.67  5228.6 1636.82    5264  1639.3  5292.3 1643.77
  5313.5  1648.1  5341.7 1650.56  5363.1 1650.53  5391.4 1653.51  5407.3 1654.18
#Mann= 9 ,-1 , 0
  4312.1      .1       0  4396.5     .16       0  4571.8      .1       0
  4785.3     .16       0  4900.3      .1       0  4994.4     .16       0
  4999.4     .07       0  5005.4     .16       0  5165.3     .05       0
Bank Sta=4999.4,5005.4
XS Rating Curve= 0 ,0
Exp/Cntr=0.3,0.1

Type RM Length L Ch R = 1 ,4123    ,353,353,353
BEGIN DESCRIPTION:
WEST FORK THREEMILE CREEK 9.0
END DESCRIPTION:
XS GIS Cut Line= 2
      2819382.63     10032162.03      2820124.55     10031246.77
#Sta/Elev= 30
    4293  1647.3  4293.8 1647.13  4521.3 1633.51  4644.3 1626.35    4766 1621.61
  4805.6 1620.01  4869.8 1618.23  4978.3 1614.66  4985.9 1613.55  4996.2 1607.08
  4998.9 1606.58  5002.2 1607.08  5007.1 1608.33  5027.9 1608.95  5035.9 1610.92
  5042.3 1611.27  5127.5 1614.05  5141.4 1613.59  5184.6 1615.96  5255.5 1624.45
  5283.7 1628.14    5302 1632.08  5312.4 1635.18  5341.2 1639.27  5347.6 1642.22
  5376.4 1647.39  5405.1 1648.17  5425.9 1653.85  5467.5 1657.95  5471.2 1658.76
#Mann= 11 ,-1 , 0
    4293      .1       0  4293.8     .16       0  4521.3     .05       0
    4766      .1       0  4805.6     .05       0  4869.8      .1       0
  4996.2     .07       0  5002.2      .1       0  5255.5     .16       0
    5302     .05       0  5467.5      .1       0
Bank Sta=4996.2,5002.2
XS Rating Curve= 0 ,0
Exp/Cntr=0.3,0.1

Type RM Length L Ch R = 1 ,3770    ,450,450,450
BEGIN DESCRIPTION:
WEST FORK THREEMILE CREEK 8.0
END DESCRIPTION:
XS GIS Cut Line= 2
      2819556.29     10032217.56      2820500.68     10031543.98
#Sta/Elev= 30
  4324.3 1638.79  4363.8 1635.73  4392.8 1635.05  4472.8 1629.26  4579.7 1623.41
    4737 1616.18  4793.7 1612.81  4909.1 1609.19  4923.9 1607.83  4999.5 1605.22
  5002.3 1604.72  5005.5 1605.22  5030.8 1606.81  5051.2 1606.46  5113.6  1611.7
  5188.1 1618.44  5211.4 1619.05  5223.8 1622.04  5247.1 1622.74  5253.3  1623.8
  5282.8 1625.56  5303.7 1628.37  5312.2 1631.25  5339.3 1636.38  5354.1 1637.15
  5360.2 1638.67  5368.8 1639.43    5375 1641.26  5419.2 1644.44  5484.3 1651.28
#Mann= 6 ,-1 , 0
  4324.3      .1       0  4999.5     .07       0  5005.5      .1       0
  5051.2     .16       0  5113.6     .05       0  5312.2      .1       0
Bank Sta=4999.5,5005.5
XS Rating Curve= 0 ,0
Exp/Cntr=0.3,0.1

Type RM Length L Ch R = 1 ,3320    ,213,213,213
BEGIN DESCRIPTION:
WEST FORK THREEMILE CREEK 7.0
END DESCRIPTION:
XS GIS Cut Line= 2
      2819431.27     10032877.29      2820964.71      10031711.6
#Sta/Elev= 30
  3845.8 1647.06  3981.2 1638.96  4017.9  1638.1  4098.9 1635.81  4168.2 1632.01
  4174.5 1632.72  4189.1 1630.94  4450.7  1621.5  4702.7 1614.56  4817.1 1607.22
  4881.5 1606.17  4902.3 1607.41  4916.9 1603.69  4940.5 1600.45  4966.8 1597.97
  4999.2 1596.89  5001.9 1596.39  5005.2 1596.89  5008.3 1596.97  5045.8 1600.08
  5095.7 1609.28  5131.1 1613.46  5145.6 1613.11  5166.4 1610.38  5189.3 1611.19
  5248.2 1615.75  5565.7 1636.19  5653.6 1643.25  5726.4 1648.86    5772 1652.55
#Mann= 12 ,-1 , 0
  3845.8      .1       0  4017.9     .05       0  4098.9      .1       0
  4450.7     .05       0  4940.5     .16       0  4999.2     .07       0
  5005.2     .16       0  5008.3     .05       0  5189.3      .1       0
  5248.2     .05       0  5653.6      .1       0  5726.4     .05       0
Bank Sta=4999.2,5005.2
XS Rating Curve= 0 ,0
Exp/Cntr=0.3,0.1

Type RM Length L Ch R = 1 ,3107    ,132,132,132
BEGIN DESCRIPTION:
WEST FORK THREEMILE CREEK 6.0
END DESCRIPTION:
XS GIS Cut Line= 4
      2819774.21     10032703.97      2820399.18     10032349.82
      2820763.76      10032271.7      2821273.82     10032011.47
#Sta/Elev= 30
  4178.2  1628.2  4262.8  1625.3    4437  1617.3  4769.3 1607.14  4797.7 1609.96
  4819.3 1608.57    4863 1601.63  4945.6 1596.81  4992.1 1596.56  4994.8 1596.06
  4998.1 1596.56  5069.7 1597.15  5089.9 1598.96    5131  1602.9  5143.4 1605.88
  5172.7 1607.55  5270.1 1612.73  5300.3 1614.82  5316.9 1614.39  5405.9 1621.47
  5455.9 1627.84  5480.7 1629.46  5539.2 1629.75  5555.3 1632.95  5567.1 1637.17
  5628.1 1641.84  5694.8 1650.86  5733.7 1658.08  5783.7 1662.42    5842 1671.68
#Mann= 9 ,-1 , 0
  4178.2      .1       0  4262.8     .05       0    4863      .1       0
  4992.1     .07       0  4998.1      .1       0  5089.9     .05       0
  5172.7      .1       0  5270.1     .05       0  5480.7      .1       0
Bank Sta=4992.1,4998.1
XS Rating Curve= 0 ,0
Exp/Cntr=0.3,0.1

Type RM Length L Ch R = 1 ,2975    ,154,154,154
BEGIN DESCRIPTION:
Mapping XS d23b154d
END DESCRIPTION:
XS GIS Cut Line= 4
      2819813.16      10032780.1      2820431.25     10032467.58
      2820910.42     10032377.31      2821382.01     10032148.44
#Sta/Elev= 30
  4166.8 1631.53  4703.4 1609.28  4792.5 1603.92  4809.2 1600.35  4837.1 1604.65
  4853.8 1603.55  4858.1 1606.68  4904.8 1602.89  4909.9 1606.01  4957.2 1601.13
  4962.3 1605.09  5011.8  1598.1  5014.5  1597.6  5017.8  1598.1  5019.9  1602.7
  5060.1 1600.15  5067.2 1600.24  5072.3 1603.62  5081.4  1603.1  5095.7  1603.1
  5119.7 1603.01  5131.3 1605.54  5177.2 1603.56  5256.7 1608.15  5454.3  1621.3
    5556 1633.33  5611.6 1635.21  5640.4 1640.86  5770.7 1657.83  5871.2 1669.41
#Mann= 7 ,-1 , 0
  4166.8     .05       0  5011.8     .04       0  5017.8     .05       0
  5081.4      .1       0  5095.7     .05       0  5256.7      .1       0
  5770.7     .05       0
Bank Sta=5011.8,5017.8
XS Rating Curve= 0 ,0
Exp/Cntr=0.3,0.1

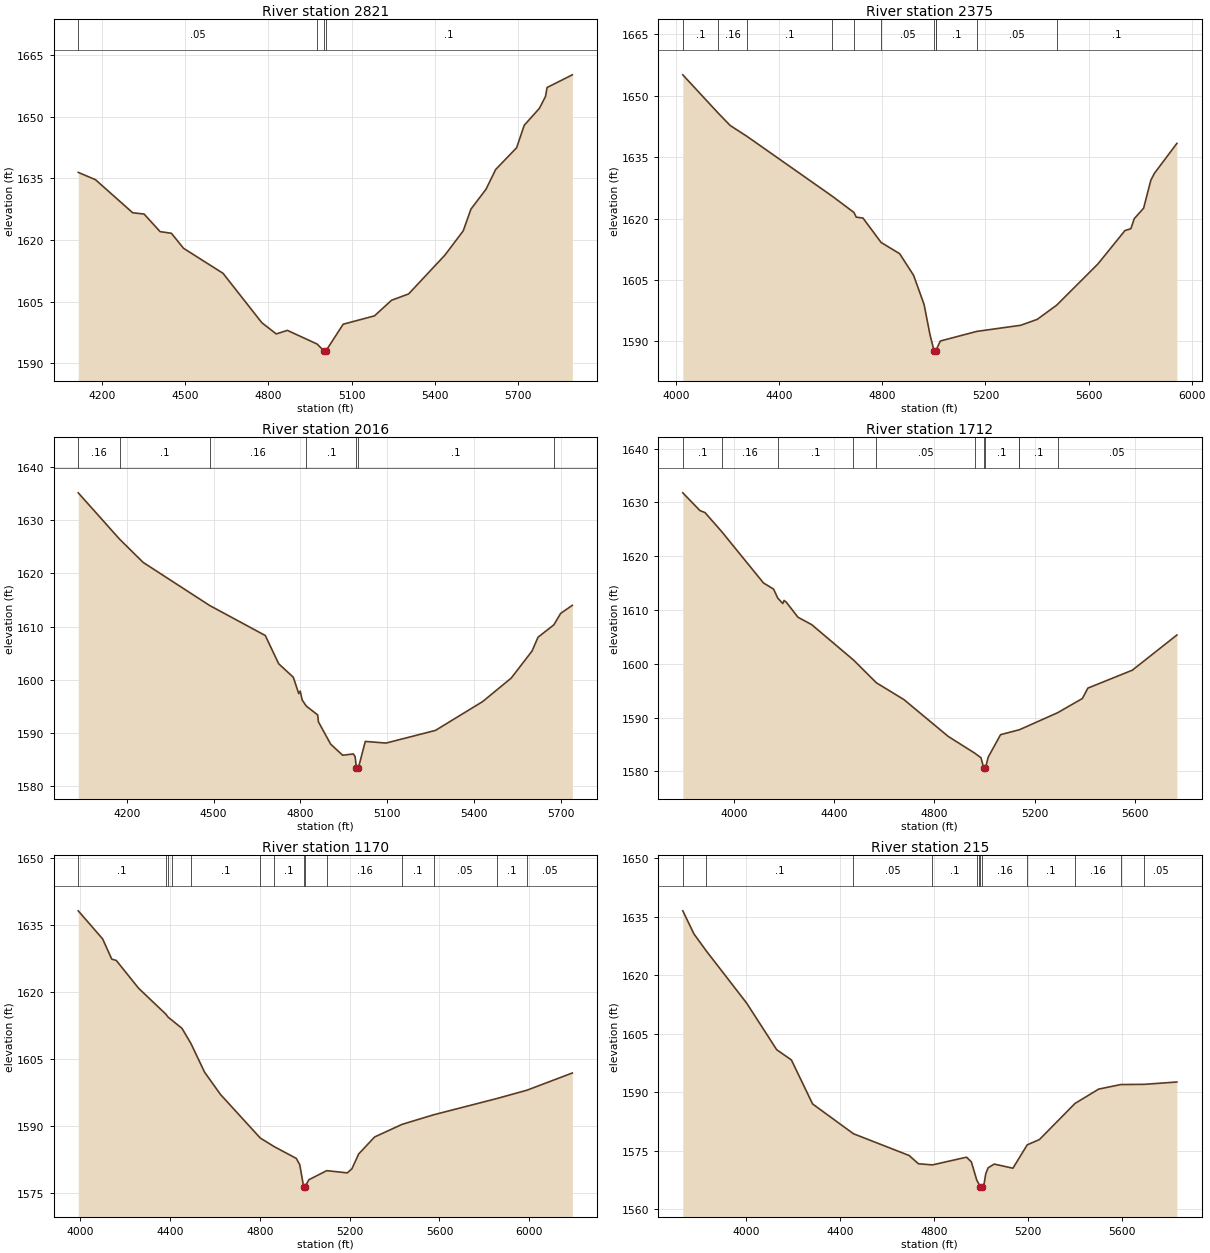
Type RM Length L Ch R = 1 ,2821    ,446,446,446
BEGIN DESCRIPTION:
Mapping XS ba4fa3cb
END DESCRIPTION:
XS GIS Cut Line= 4
      2819831.48     10032896.69      2820492.93     10032605.03
      2820982.51     10032495.66      2821472.11     10032235.23
#Sta/Elev= 30
  4115.3 1636.48  4177.6 1634.69  4311.4 1626.65  4352.4 1626.34  4410.1 1622.06
  4450.8 1621.66  4494.5    1618  4636.6 1611.92  4776.3  1599.9  4828.4 1597.16
  4868.3 1598.03  4975.3 1594.71  5000.7 1592.99  5003.4 1592.49  5006.7 1592.99
  5069.3 1599.53    5182 1601.56  5243.5 1605.36    5305  1606.9  5435.7 1616.35
  5501.6 1622.25  5529.2 1627.52  5583.8  1632.4  5618.4 1637.18  5693.7 1642.47
  5721.3 1647.95  5775.9 1652.07  5797.9 1654.97  5803.5 1657.13  5894.4 1660.22
#Mann= 4 ,-1 , 0
  4115.3     .05       0  4975.3      .1       0  5000.7     .07       0
  5006.7      .1       0
Bank Sta=5000.7,5006.7
XS Rating Curve= 0 ,0
Exp/Cntr=0.3,0.1

Type RM Length L Ch R = 1 ,2375    ,359,359,359
BEGIN DESCRIPTION:
WEST FORK THREEMILE CREEK 5.0
END DESCRIPTION:
XS GIS Cut Line= 3
      2819709.06     10033266.18      2820896.53     10032877.31
      2821417.35     10032460.64
#Sta/Elev= 30
  4026.2 1655.14  4163.7 1645.78  4210.3 1642.75  4276.7 1640.04  4606.6 1625.45
  4690.2  1621.5    4699 1620.36  4725.1 1620.14  4795.5 1614.17  4867.4 1611.43
  4921.5 1606.14  4962.1 1599.03  4985.2  1591.6  5001.2 1587.63  5003.9 1587.13
  5007.2 1587.63  5008.7 1587.88  5025.2 1590.09  5166.3 1592.44  5336.6 1593.93
  5400.7 1595.37  5476.2 1598.84    5636 1608.89  5741.6  1617.1  5764.1 1617.53
  5777.6 1620.01  5813.7 1622.55  5841.7 1629.38  5855.3 1631.05  5942.7 1638.38
#Mann= 11 ,-1 , 0
  4026.2      .1       0  4163.7     .16       0  4276.7      .1       0
  4606.6     .05       0  4690.2      .1       0  4795.5     .05       0
  5001.2    .035       0  5007.2     .05       0  5008.7      .1       0
  5166.3     .05       0  5476.2      .1       0
Bank Sta=5001.2,5007.2
XS Rating Curve= 0 ,0
Exp/Cntr=0.3,0.1

Type RM Length L Ch R = 1 ,2016    ,304,304,304
BEGIN DESCRIPTION:
WEST FORK THREEMILE CREEK 4.0
END DESCRIPTION:
XS GIS Cut Line= 3
      2819945.14     10033446.75      2820764.58     10033307.86
      2821444.33     10032752.97
#Sta/Elev= 30
  4032.1 1635.15  4174.9 1626.46  4256.6 1622.08  4486.9 1613.98    4679 1608.35
  4725.2 1603.05  4775.9 1600.51  4794.6 1597.44  4799.7 1597.91  4806.3 1596.26
  4820.7  1595.1  4860.1 1593.44  4862.7 1592.14  4904.9 1587.96  4946.5 1585.86
  4983.2 1586.11  4989.6 1585.62  4994.3 1583.38  4997.1 1582.88  5000.3 1583.38
  5024.8 1588.46  5096.6 1588.15  5267.5 1590.53  5430.5 1595.94  5529.5 1600.36
  5601.3 1605.43  5622.1 1608.03  5676.7 1610.35  5700.4 1612.51  5740.7 1614.02
#Mann= 7 ,-1 , 0
  4032.1     .16       0  4174.9      .1       0  4486.9     .16       0
  4820.7      .1       0  4994.3    .035       0  5000.3      .1       0
  5676.7      .1       0
Bank Sta=4994.3,5000.3
XS Rating Curve= 0 ,0
Exp/Cntr=0.3,0.1

Type RM Length L Ch R = 1 ,1712    ,542,542,542
BEGIN DESCRIPTION:
WEST FORK THREEMILE CREEK 3.0
END DESCRIPTION:
XS GIS Cut Line= 3
      2819840.98     10033745.36      2820910.42     10033564.81
      2821590.94     10032995.39
#Sta/Elev= 30
  3795.9 1631.79  3864.3 1628.49  3884.6 1628.12  3951.6 1624.56  4117.9 1615.04
  4158.4 1613.89  4174.8 1612.23    4195 1611.21  4200.1 1611.79  4209.2 1611.45
  4255.5 1608.67  4310.6 1607.28  4477.1 1600.72  4568.6 1596.48  4678.7 1593.35
    4855 1586.52  4961.9 1583.38  4986.1 1582.54  4997.4 1580.56  5000.2 1580.06
  5003.4 1580.56  5014.7 1582.65  5064.2 1586.84  5136.6 1587.72  5138.8 1587.74
    5292 1590.92  5390.8 1593.56  5412.5 1595.49  5589.9 1598.82  5767.8 1605.36
#Mann= 11 ,-1 , 0
  3795.9      .1       0  3951.6     .16       0  4174.8      .1       0
  4477.1     .16       0  4568.6     .05       0  4961.9      .1       0
  4997.4     .07       0  5003.4      .1       0  5136.6     .16       0
  5138.8      .1       0    5292     .05       0
Bank Sta=4997.4,5003.4
XS Rating Curve= 0 ,0
Exp/Cntr=0.3,0.1

Type RM Length L Ch R = 1 ,1170    ,955,955,955
BEGIN DESCRIPTION:
WEST FORK THREEMILE CREEK 2.0
END DESCRIPTION:
XS GIS Cut Line= 3
      2820000.65     10034043.98      2821334.03     10033870.36
      2821861.02     10033197.75
#Sta/Elev= 30
  3992.2 1638.15  4100.9 1631.87  4141.3 1627.36  4161.4 1627.07  4261.2 1620.83
  4381.4  1615.1  4393.4 1614.33  4408.2 1613.75  4453.9 1611.89  4493.4 1608.54
  4554.7 1602.08  4625.3 1597.12  4802.4 1587.38  4865.4 1585.43  4962.7 1582.83
  4978.3 1581.39  4995.4 1576.46  4998.2 1575.96  5001.4 1576.46  5018.6 1578.06
  5098.5 1580.09  5189.8 1579.59  5210.2 1580.51  5240.5 1583.82  5311.1 1587.61
  5433.4 1590.43  5573.7 1592.57  5855.8 1596.21  5988.9 1598.06  6191.3 1601.91
#Mann= 14 ,-1 , 0
  3992.2      .1       0  4381.4     .05       0  4393.4      .1       0
  4408.2     .05       0  4493.4      .1       0  4802.4     .05       0
  4865.4      .1       0  4995.4     .07       0  5001.4      .1       0
  5098.5     .16       0  5433.4      .1       0  5573.7     .05       0
  5855.8      .1       0  5988.9     .05       0
Bank Sta=4995.4,5001.4
XS Rating Curve= 0 ,0
Exp/Cntr=0.3,0.1

Type RM Length L Ch R = 1 ,215     ,0,0,0
BEGIN DESCRIPTION:
WEST FORK THREEMILE CREEK 1.0
END DESCRIPTION:
XS GIS Cut Line= 5
      2820116.93     10034545.95      2820855.83      10034587.9
      2821143.02     10034574.99      2821510.89     10034491.09
      2821652.69     10033807.84
#Sta/Elev= 30
  3730.2 1636.54    3778 1630.59    3830 1626.28  4002.2 1612.87  4129.8 1600.94
  4192.5 1598.31  4282.6 1587.04  4456.4  1579.4  4693.2 1573.83  4733.2  1571.7
  4792.4 1571.41  4937.7 1573.39  4958.2 1572.19  4981.2 1567.54  4990.4 1566.49
  4996.3  1565.7    4999  1565.2  5002.3  1565.7  5012.7 1566.63  5019.8 1569.22
    5030 1570.69  5055.7 1571.62  5135.1 1570.56    5196 1576.55    5248 1577.91
  5399.3 1587.16  5500.1 1590.84  5594.3 1592.01  5693.9 1592.06  5832.9 1592.66
#Mann= 12 ,-1 , 0
  3730.2     .05       0    3830      .1       0  4456.4     .05       0
  4792.4      .1       0  4981.2     .05       0  4990.4     .16       0
  4996.3     .07       0  5002.3     .16       0    5196      .1       0
  5399.3     .16       0  5594.3      .1       0  5693.9     .05       0
Bank Sta=4996.3,5002.3
XS Rating Curve= 0 ,0
Exp/Cntr=0.3,0.1

Chan Stop Cuts=-1
Use User Specified Reach Order=0
Composite Channel Slope=5