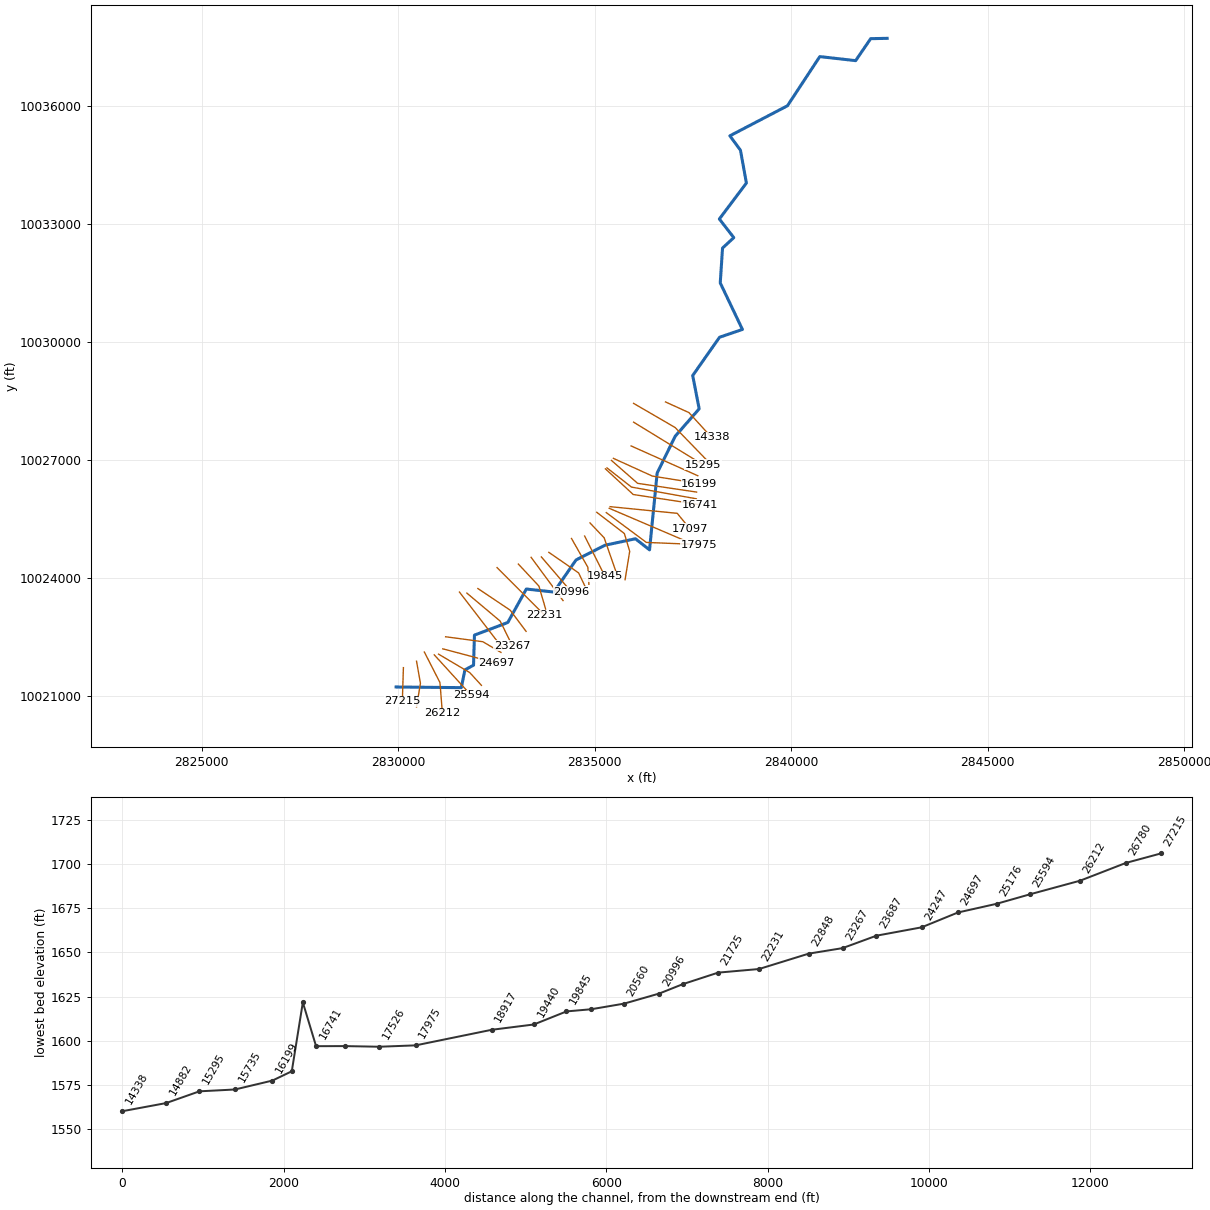
--- WEST FORK WILLIAMS CREEK.prj (project) ---

Proj Title=WEST FORK WILLIAMS CREEK Base Level Engineering
Current Plan=p01
Default Exp/Contr=0.3,0.1
English Units
Geom File=g01
Flow File=f01
Plan File=p01
BEGIN DESCRIPTION:
WEST FORK WILLIAMS CREEK
END DESCRIPTION:

--- WEST FORK WILLIAMS CREEK.p01 (plan) ---

Plan Title=Multiple Run
Short Identifier=Multiple
Geom File=g01
Flow File=f01
Subcritical Flow
K Sum by GR= 0
Std Step Tol= 0.01
Critical Tol= 0.01
Num of Std Step Trials= 20
Max Error Tol= 0.3
Flow Tol Ratio= 0.001
Split Flow NTrial= 30
Split Flow Tol= 0.02
Split Flow Ratio= 0.02
Log Output Level= 0
Friction Slope Method= 1
Unsteady Friction Slope Method= 2
Unsteady Bridges Friction Slope Method= 1
Parabolic Critical Depth
Global Vel Dist=  1 , 1 , 1
Global Log Level= 0
CheckData=True
Encroach Param= -1, 0, 0, 0
BEGIN DESCRIPTION:
Multiple Run
END DESCRIPTION:

--- WEST FORK WILLIAMS CREEK.f01 (steady flow) ---

Flow Title=Multiple
Number of Profiles=7
Profile Names=10-year,25-year,50-year,1pct_min,100-year,1pct_plu,500-year
River Rch & RM= WEST FORK WILLIA,Reach-1,27215
     917    1336    1703    1591    2151    2909    3444
River Rch & RM= WEST FORK WILLIA,Reach-1,26780
    1372    2031    2615    2462    3329    4502    5416
River Rch & RM= WEST FORK WILLIA,Reach-1,17975
    2174    3281    4278    4072    5507    7447    9161
River Rch & RM= WEST FORK WILLIA,Reach-1,16577
    2556    3878    5073    4840    6546    8853   10950
River Rch & RM= WEST FORK WILLIA,Reach-1,5287
    3497    5374    7093    6822    9225   12476   15679
River Rch & RM= WEST FORK WILLIA,Reach-1,2890
    3845    5926    7837    7550   10210   13808   17409
Boundary for River Rch & Prof#=WEST FORK WILLIA,Reach-1,1
Up Type=0
Dn Type=3
Dn Slope=0.005
Boundary for River Rch & Prof#=WEST FORK WILLIA,Reach-1,2
Up Type=0
Dn Type=3
Dn Slope=0.005
Boundary for River Rch & Prof#=WEST FORK WILLIA,Reach-1,3
Up Type=0
Dn Type=3
Dn Slope=0.005
Boundary for River Rch & Prof#=WEST FORK WILLIA,Reach-1,4
Up Type=0
Dn Type=3
Dn Slope=0.005
Boundary for River Rch & Prof#=WEST FORK WILLIA,Reach-1,5
Up Type=0
Dn Type=3
Dn Slope=0.005
Boundary for River Rch & Prof#=WEST FORK WILLIA,Reach-1,6
Up Type=0
Dn Type=3
Dn Slope=0.005
Boundary for River Rch & Prof#=WEST FORK WILLIA,Reach-1,7
Up Type=0
Dn Type=3
Dn Slope=0.005

--- WEST FORK WILLIAMS CREEK.g01 (geometry) ---

Geom Title=Existing Conditions

River Reach=WEST FORK WILLIA,Reach-1
Reach XY= 30
      2829948.47     10021223.73      2831607.05     10021207.10
      2831698.47     10021658.92      2831917.67     10021778.66
      2831940.71     10022542.89      2832788.38     10022864.14
      2833260.81     10023715.84      2833960.83     10023638.82
      2834525.22     10024455.85      2835261.22     10024829.87
      2836036.16     10024994.21      2836394.56     10024711.50
      2836588.52     10026666.66      2837046.28     10027600.02
      2837656.73     10028299.53      2837492.47     10029146.53
      2838174.78     10030119.81      2838757.15     10030319.08
      2838193.25     10031501.99      2838251.22     10032389.40
      2838538.11     10032653.54      2838170.64     10033128.45
      2838858.52     10034042.74      2838707.26     10034878.36
      2838438.47     10035243.73      2839902.48     10036008.10
      2840725.44     10037259.08      2841637.31     10037156.30
      2842019.17     10037715.21      2842438.47     10037723.73

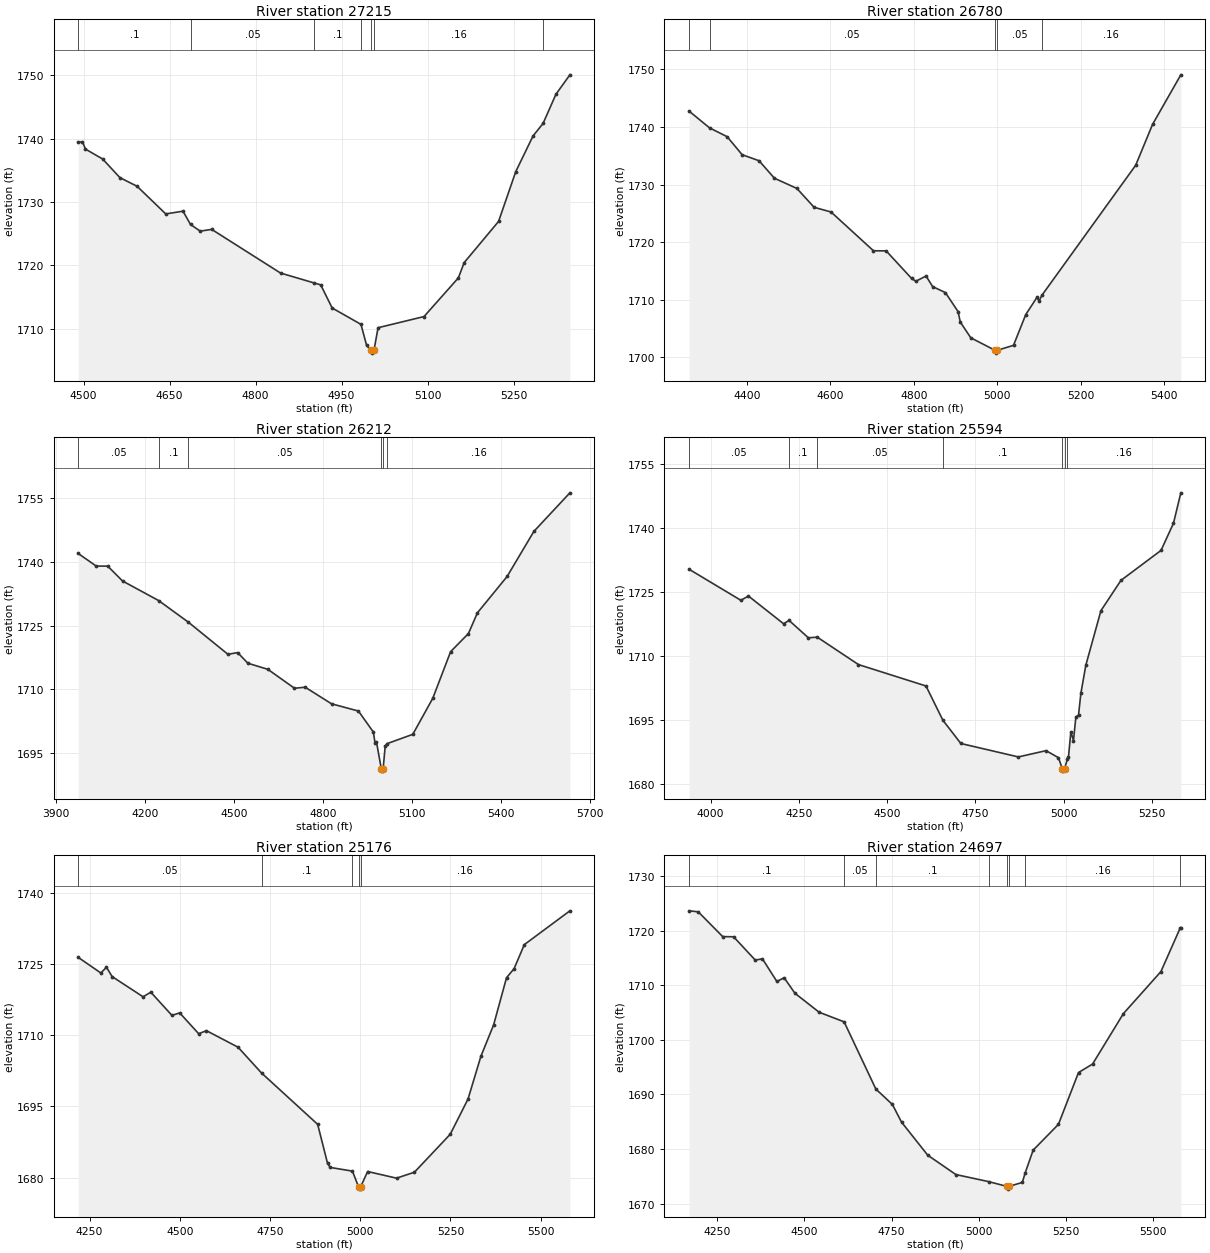
Type RM Length L Ch R = 1,27215,435,435,435
BEGIN DESCRIPTION:
WEST FORK WILLIAMS CREEK 58.0
END DESCRIPTION:
XS GIS Cut Line= 2
      2830133.69     10021716.50      2830106.63     10020859.42
#Sta/Elev= 30
  4490.6 1739.39  4498.1 1739.49  4503.4 1738.33  4533.4 1736.76  4563.4 1733.83
  4593.4 1732.46  4643.4 1728.10  4673.5 1728.53  4686.6 1726.43  4703.5 1725.38
  4723.5 1725.66  4843.5 1718.77  4902.7 1717.19  4913.6 1716.90  4933.6 1713.25
  4983.8 1710.67  4993.6 1707.36  5000.6 1706.63  5003.4 1706.13  5006.6 1706.63
  5013.6 1710.14  5093.7 1711.90  5153.7 1718.01  5163.7 1720.41  5223.7 1726.91
  5253.7 1734.77  5283.8 1740.40  5301.4 1742.39  5323.8 1746.99  5348.1 1750.05
#Mann=7,-1,0
  4490.6     0.1       0  4686.6    0.05       0  4902.7     0.1       0
  4983.8    0.16       0  5000.6    0.07       0  5006.6    0.16       0
  5301.4     0.1       0
Bank Sta=5000.6,5006.6
Exp/Cntr=0.3,0.1

Type RM Length L Ch R = 1,26780,568,568,568
BEGIN DESCRIPTION:
WEST FORK WILLIAMS CREEK 57.0
END DESCRIPTION:
XS GIS Cut Line= 3
      2830467.52     10021878.93      2830566.77     10021319.54
      2830467.83     10020716.93
#Sta/Elev= 30
  4261.4 1742.75  4310.4 1739.84  4352.8 1738.30  4388.6 1735.18  4429.2 1734.13
  4466.0 1731.10  4520.0 1729.32  4561.2 1726.05  4601.8 1725.24  4703.4 1718.51
  4733.9 1718.49  4794.8 1713.71  4805.0 1713.22  4829.5 1714.13  4845.2 1712.30
  4875.9 1711.25  4906.3 1707.95  4911.5 1706.15  4936.7 1703.41  4994.6 1701.25
  4997.3 1700.75  5000.6 1701.25  5039.1 1702.10  5068.5 1707.44  5095.3 1710.42
  5100.4 1709.79  5107.1 1710.78  5332.0 1733.35  5372.5 1740.45  5440.2 1749.04
#Mann=5,-1,0
  4261.4     0.1       0  4310.4    0.05       0  4994.6   0.035       0
  5000.6    0.05       0  5107.1    0.16       0
Bank Sta=4994.6,5000.6
Exp/Cntr=0.3,0.1

Type RM Length L Ch R = 1,26212,618,618,618
BEGIN DESCRIPTION:
WEST FORK WILLIAMS CREEK 56.0
END DESCRIPTION:
XS GIS Cut Line= 3
      2830665.99     10022113.54      2831062.99     10021337.58
      2831126.15     10020552.64
#Sta/Elev= 30
  3974.2 1742.03  4035.1 1739.05  4074.0 1739.03  4124.0 1735.53  4246.0 1730.90
  4346.5 1725.79  4479.5 1718.24  4512.5 1718.63  4546.9 1716.13  4614.3 1714.69
  4704.1 1710.23  4740.3 1710.47  4829.1 1706.56  4919.9 1704.85  4970.1 1699.91
  4975.8 1697.37  4980.8 1697.53  4997.2 1691.18  4999.9 1690.68  5003.2 1691.18
  5010.2 1696.58  5016.1 1697.15  5103.3 1699.36  5170.7 1707.86  5230.9 1718.86
  5291.1 1723.14  5321.2 1728.01  5421.5 1736.59  5511.8 1747.22  5633.3 1756.32
#Mann=6,-1,0
  3974.2    0.05       0  4246.0     0.1       0  4346.5    0.05       0
  4997.2   0.035       0  5003.2    0.05       0  5016.1    0.16       0
Bank Sta=4997.2,5003.2
Exp/Cntr=0.3,0.1

Type RM Length L Ch R = 1,25594,418,418,418
BEGIN DESCRIPTION:
WEST FORK WILLIAMS CREEK 55.0
END DESCRIPTION:
XS GIS Cut Line= 2
      2830918.62     10022041.34      2831856.97     10021012.76
#Sta/Elev= 30
  3939.3 1730.36  4085.9 1723.08  4107.5 1724.07  4206.8 1717.58  4222.4 1718.36
  4277.1 1714.28  4302.2 1714.43  4418.9 1708.00  4610.1 1702.98  4657.9 1694.95
  4708.8 1689.49  4871.6 1686.34  4950.0 1687.81  4985.1 1686.17  4996.3 1683.51
  4999.1 1683.01  5002.3 1683.51  5010.7 1685.93  5013.5 1686.32  5020.3 1692.24
  5027.7 1690.18  5034.5 1695.73  5041.9 1696.12  5048.6 1701.25  5062.8 1707.90
  5105.4 1720.64  5162.1 1727.75  5275.6 1734.78  5310.8 1741.15  5331.6 1748.28
#Mann=7,-1,0
  3939.3    0.05       0  4222.4     0.1       0  4302.2    0.05       0
  4657.9     0.1       0  4996.3    0.07       0  5002.3     0.1       0
  5010.7    0.16       0
Bank Sta=4996.3,5002.3
Exp/Cntr=0.3,0.1

Type RM Length L Ch R = 1,25176,479,479,479
BEGIN DESCRIPTION:
WEST FORK WILLIAMS CREEK 54.0
END DESCRIPTION:
XS GIS Cut Line= 3
      2831026.92     10022059.36      2831820.87     10021590.20
      2832118.59     10021265.42
#Sta/Elev= 30
  4218.2 1726.41  4281.1 1723.11  4296.8 1724.31  4312.4 1722.35  4398.2 1718.09
  4419.6 1719.06  4478.2 1714.17  4499.6 1714.70  4552.3 1710.31  4573.8 1710.95
  4661.4 1707.47  4726.4 1702.04  4882.0 1691.22  4909.3 1683.03  4916.9 1682.14
  4978.4 1681.36  4995.2 1678.07  4998.0 1677.57  5001.2 1678.07  5020.5 1681.28
  5100.5 1679.88  5150.1 1681.13  5249.4 1689.13  5298.7 1696.55  5334.5 1705.58
  5369.6 1712.16  5405.4 1722.11  5426.4 1724.02  5454.7 1729.08  5581.0 1736.20
#Mann=5,-1,0
  4218.2    0.05       0  4726.4     0.1       0  4978.4    0.16       0
  4995.2    0.07       0  5001.2    0.16       0
Bank Sta=4995.2,5001.2
Exp/Cntr=0.3,0.1

Type RM Length L Ch R = 1,24697,450,450,450
BEGIN DESCRIPTION:
WEST FORK WILLIAMS CREEK 53.0
END DESCRIPTION:
XS GIS Cut Line= 2
      2831135.13     10022194.71      2832497.54     10021833.81
#Sta/Elev= 30
  4169.8 1723.61  4196.1 1723.43  4266.2 1718.89  4297.4 1718.86  4359.5 1714.59
  4380.1 1714.82  4421.5 1710.67  4442.2 1711.36  4473.3 1708.51  4542.6 1705.04
  4614.2 1703.28  4705.1 1690.98  4752.6 1688.15  4778.7 1684.92  4853.9 1678.86
  4934.4 1675.32  5029.5 1674.01  5080.6 1673.15  5083.4 1672.65  5086.6 1673.15
  5125.0 1673.88  5132.8 1675.57  5156.0 1679.79  5228.4 1684.51  5286.0 1694.00
  5326.2 1695.55  5414.6 1704.79  5522.1 1712.48  5577.7 1720.51  5579.2 1720.51
#Mann=8,-1,0
  4169.8     0.1       0  4614.2    0.05       0  4705.1     0.1       0
  5029.5    0.05       0  5080.6    0.07       0  5086.6    0.05       0
  5132.8    0.16       0  5577.7     0.1       0
Bank Sta=5080.6,5086.6
Exp/Cntr=0.3,0.1

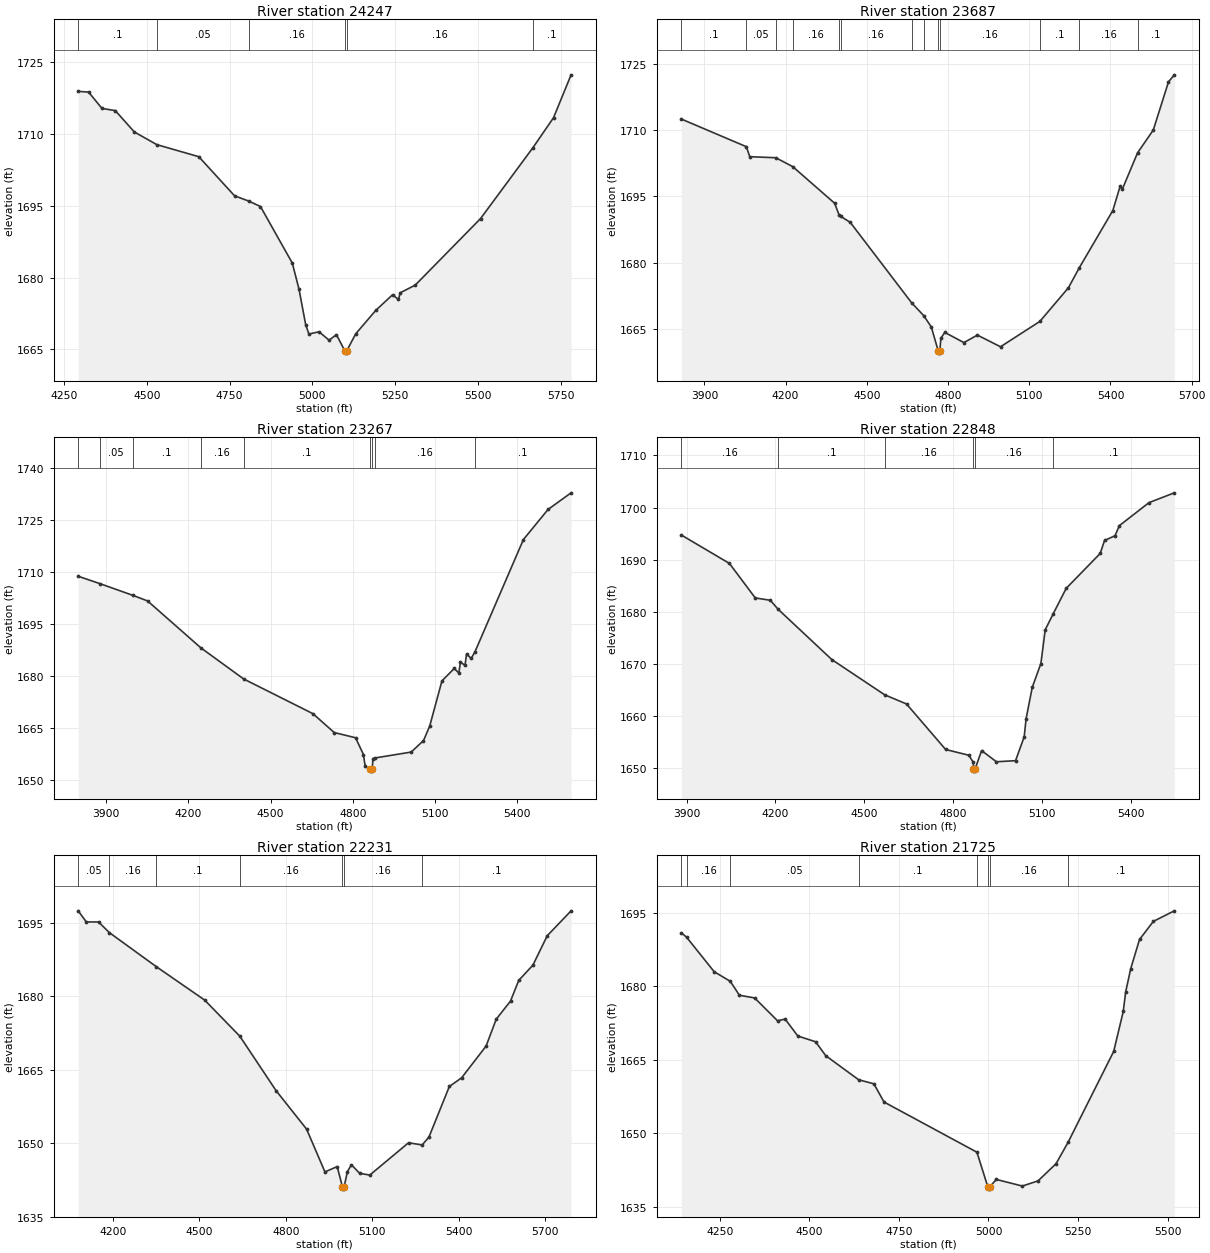
Type RM Length L Ch R = 1,24247,560,560,560
BEGIN DESCRIPTION:
WEST FORK WILLIAMS CREEK 52.0
END DESCRIPTION:
XS GIS Cut Line= 3
      2831207.34     10022501.46      2832154.69     10022375.15
      2832614.16     10022104.87
#Sta/Elev= 30
  4292.7 1718.87  4324.1 1718.73  4364.5 1715.32  4404.8 1714.86  4462.5 1710.39
  4530.2 1707.76  4657.0 1705.24  4765.1 1697.07  4807.4 1695.99  4843.3 1694.84
  4939.5 1683.03  4959.7 1677.58  4979.9 1670.17  4989.6 1668.22  5020.2 1668.70
  5050.5 1666.94  5072.8 1668.09  5097.9 1664.74  5100.7 1664.24  5103.9 1664.74
  5131.2 1668.29  5191.7 1673.17  5242.2 1676.42  5259.9 1675.45  5265.7 1676.84
  5310.8 1678.44  5508.1 1692.33  5665.8 1707.08  5728.5 1713.38  5781.5 1722.33
#Mann=6,-1,0
  4292.7     0.1       0  4530.2    0.05       0  4807.4    0.16       0
  5097.9    0.07       0  5103.9    0.16       0  5665.8     0.1       0
Bank Sta=5097.9,5103.9
Exp/Cntr=0.3,0.1

Type RM Length L Ch R = 1,23687,420,420,420
BEGIN DESCRIPTION:
WEST FORK WILLIAMS CREEK 51.0
END DESCRIPTION:
XS GIS Cut Line= 2
      2831559.24     10023638.25      2832668.96     10022194.70
#Sta/Elev= 30
  3815.2 1712.49  4055.0 1706.24  4067.6 1703.98  4163.6 1703.74  4226.4 1701.73
  4381.1 1693.44  4397.9 1690.73  4403.8 1690.46  4438.9 1689.11  4665.1 1670.94
  4710.0 1668.01  4738.2 1665.44  4763.9 1660.01  4766.6 1659.51  4769.9 1660.01
  4773.5 1662.87  4788.0 1664.20  4858.7 1661.90  4908.5 1663.59  4993.9 1660.95
  5139.3 1666.69  5244.8 1674.31  5284.8 1678.82  5408.8 1691.79  5435.9 1697.32
  5444.1 1696.65  5500.1 1704.84  5558.3 1710.02  5614.4 1720.91  5636.0 1722.51
#Mann=13,-1,0
  3815.2     0.1       0  4055.0    0.05       0  4163.6     0.1       0
  4226.4    0.16       0  4397.9     0.1       0  4403.8    0.16       0
  4665.1     0.1       0  4710.0    0.16       0  4763.9    0.07       0
  4769.9    0.16       0  5139.3     0.1       0  5284.8    0.16       0
  5500.1     0.1       0
Bank Sta=4763.9,4769.9
Exp/Cntr=0.3,0.1

Type RM Length L Ch R = 1,23267,419,419,419
BEGIN DESCRIPTION:
WEST FORK WILLIAMS CREEK 50.0
END DESCRIPTION:
XS GIS Cut Line= 3
      2831748.72     10023611.17      2832596.79     10022898.44
      2832902.79     10022277.43
#Sta/Elev= 30
  3797.3 1708.75  3876.2 1706.63  3996.4 1703.25  4050.7 1701.62  4245.2 1688.08
  4401.7 1679.08  4654.3 1669.07  4732.3 1663.61  4810.3 1662.10  4839.0 1657.26
  4845.5 1653.83  4864.6 1652.96  4867.3 1652.46  4870.6 1652.96  4874.1 1656.08
  4879.7 1656.24  5013.5 1657.97  5058.4 1661.28  5080.9 1665.43  5125.8 1678.53
  5170.7 1682.11  5187.6 1680.79  5193.2 1683.97  5210.0 1682.99  5215.6 1686.28
  5232.5 1685.01  5246.3 1686.91  5423.3 1719.36  5513.2 1728.04  5597.4 1732.85
#Mann=9,-1,0
  3797.3     0.1       0  3876.2    0.05       0  3996.4     0.1       0
  4245.2    0.16       0  4401.7     0.1       0  4864.6    0.07       0
  4870.6     0.1       0  4879.7    0.16       0  5246.3     0.1       0
Bank Sta=4864.6,4870.6
Exp/Cntr=0.3,0.1

Type RM Length L Ch R = 1,22848,617,617,617
BEGIN DESCRIPTION:
WEST FORK WILLIAMS CREEK 49.0
END DESCRIPTION:
XS GIS Cut Line= 3
      2832028.37     10023728.50      2832849.41     10023178.13
      2833253.73     10022639.04
#Sta/Elev= 30
  3882.8 1694.70  4044.7 1689.25  4131.8 1682.62  4182.8 1682.17  4208.4 1680.47
  4389.9 1670.78  4568.1 1664.01  4642.0 1662.24  4773.8 1653.50  4852.1 1652.39
  4867.1 1651.01  4867.7 1649.84  4870.4 1649.34  4873.7 1649.84  4895.1 1653.29
  4945.1 1651.14  5009.7 1651.35  5038.8 1655.94  5045.1 1659.37  5065.9 1665.43
  5095.1 1670.02  5109.7 1676.51  5136.6 1679.57  5180.5 1684.47  5295.1 1691.17
  5309.7 1693.66  5345.1 1694.58  5359.7 1696.51  5459.7 1700.94  5545.1 1702.82
#Mann=6,-1,0
  3882.8    0.16       0  4208.4     0.1       0  4568.1    0.16       0
  4867.7    0.07       0  4873.7    0.16       0  5136.6     0.1       0
Bank Sta=4867.7,4873.7
Exp/Cntr=0.3,0.1

Type RM Length L Ch R = 1,22231,506,506,506
BEGIN DESCRIPTION:
WEST FORK WILLIAMS CREEK 48.0
END DESCRIPTION:
XS GIS Cut Line= 2
      2832515.58     10024260.81      2833724.02     10023052.37
#Sta/Elev= 30
  4080.5 1697.39  4108.8 1695.12  4151.2 1695.12  4188.7 1692.94  4351.4 1686.00
  4518.9 1679.19  4640.9 1671.82  4766.4 1660.73  4872.4 1652.86  4936.1 1644.13
  4978.5 1645.22  4996.7 1641.12  4999.5 1640.62  5002.7 1641.12  5013.9 1644.19
  5028.0 1645.59  5056.3 1643.84  5091.6 1643.49  5226.0 1650.08  5273.0 1649.63
  5296.7 1651.24  5367.4 1661.56  5409.8 1663.32  5494.7 1669.79  5530.0 1675.29
  5579.5 1678.98  5607.8 1683.18  5657.3 1686.33  5706.8 1692.31  5789.5 1697.39
#Mann=7,-1,0
  4080.5    0.05       0  4188.7    0.16       0  4351.4     0.1       0
  4640.9    0.16       0  4996.7    0.07       0  5002.7    0.16       0
  5273.0     0.1       0
Bank Sta=4996.7,5002.7
Exp/Cntr=0.3,0.1

Type RM Length L Ch R = 1,21725,434,434,434
BEGIN DESCRIPTION:
WEST FORK WILLIAMS CREEK 47.0
END DESCRIPTION:
XS GIS Cut Line= 3
      2833056.93     10024351.03      2833580.22     10023791.65
      2833751.11     10023207.00
#Sta/Elev= 30
  4143.4 1690.93  4157.9 1690.02  4234.7 1682.99  4279.6 1681.03  4305.1 1678.18
  4347.6 1677.63  4411.6 1672.96  4432.6 1673.31  4468.2 1669.85  4517.6 1668.68
  4545.9 1665.84  4637.7 1660.92  4680.3 1660.09  4708.6 1656.37  4967.8 1646.12
  4998.0 1639.08  5000.7 1638.58  5004.0 1639.08  5021.8 1640.56  5094.4 1639.21
  5138.2 1640.26  5188.5 1643.77  5222.2 1648.16  5349.3 1666.70  5376.0 1674.87
  5382.8 1678.88  5396.9 1683.62  5421.4 1689.57  5460.1 1693.27  5518.5 1695.42
#Mann=8,-1,0
  4143.4     0.1       0  4157.9    0.16       0  4279.6    0.05       0
  4637.7     0.1       0  4967.8    0.16       0  4998.0    0.07       0
  5004.0    0.16       0  5222.2     0.1       0
Bank Sta=4998,5004
Exp/Cntr=0.3,0.1

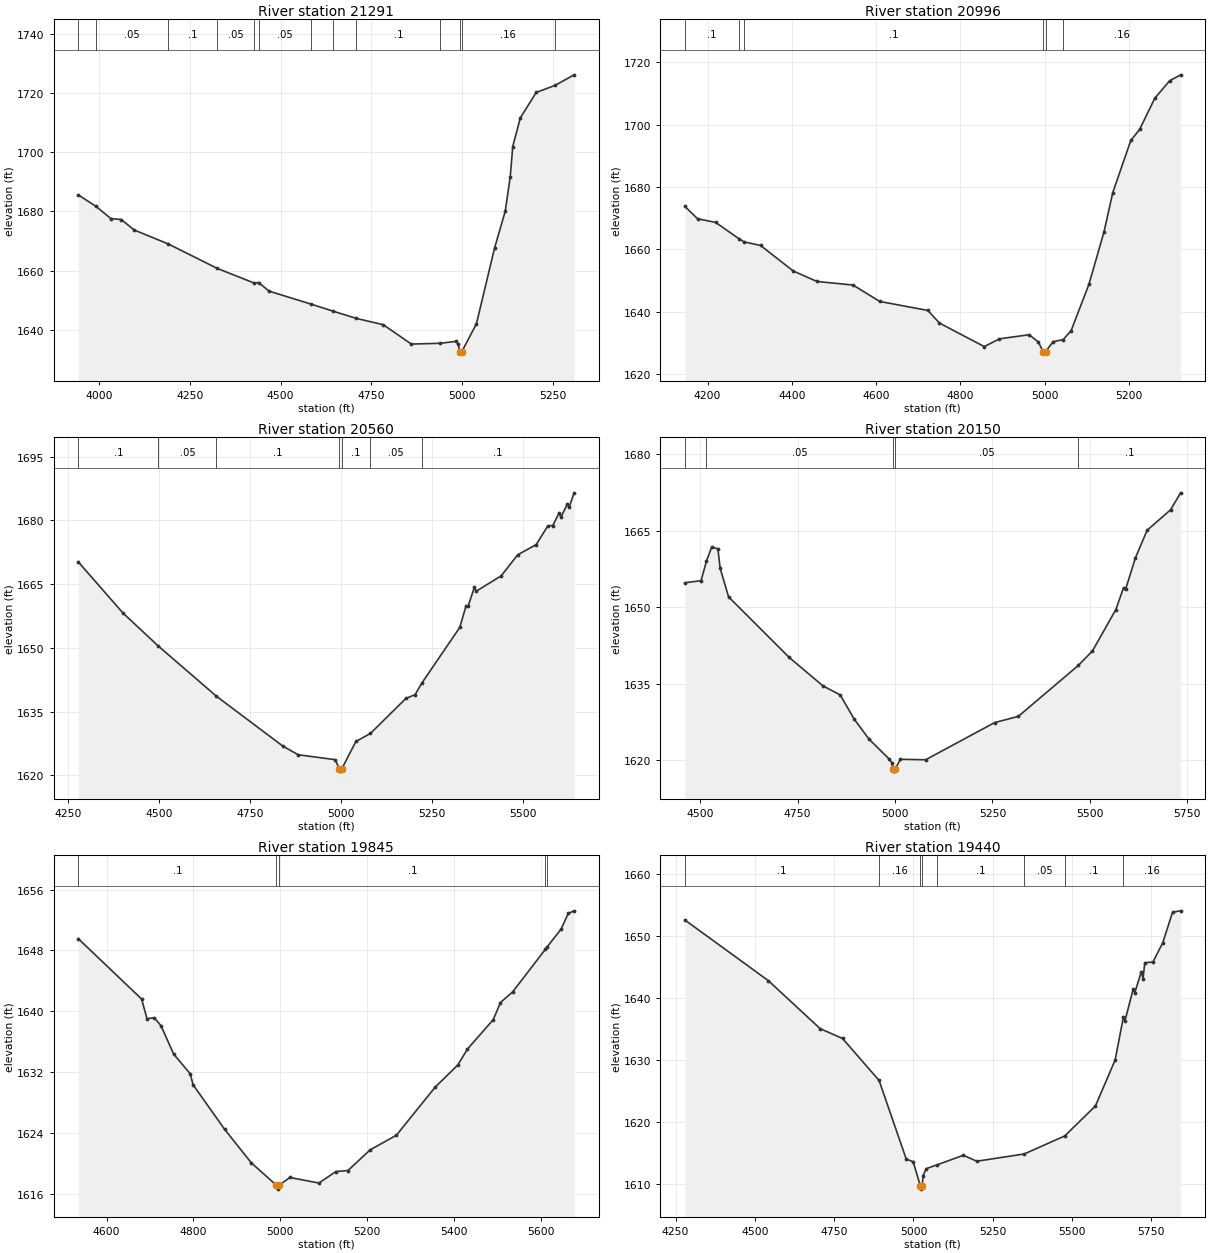
Type RM Length L Ch R = 1,21291,295,295,295
BEGIN DESCRIPTION:
WEST FORK WILLIAMS CREEK 46.0
END DESCRIPTION:
XS GIS Cut Line= 2
      2833381.73     10024522.45      2834193.60     10023421.91
#Sta/Elev= 30
  3942.0 1685.57  3991.2 1681.66  4031.4 1677.60  4060.7 1677.23  4096.1 1673.72
  4190.0 1669.01  4325.2 1660.74  4427.1 1655.80  4439.5 1655.97  4467.8 1653.07
  4585.0 1648.64  4645.6 1646.26  4709.2 1643.84  4783.2 1641.72  4860.4 1635.18
  4940.8 1635.45  4983.7 1636.09  4989.9 1635.20  4993.7 1632.62  4996.4 1632.12
  4999.7 1632.62  5040.0 1642.01  5090.1 1667.63  5119.4 1680.01  5133.4 1691.79
  5140.2 1701.89  5161.1 1711.59  5205.0 1720.19  5256.4 1722.54  5309.6 1726.14
#Mann=13,-1,0
  3942.0    0.16       0  3991.2    0.05       0  4190.0     0.1       0
  4325.2    0.05       0  4427.1     0.1       0  4439.5    0.05       0
  4585.0     0.1       0  4645.6    0.05       0  4709.2     0.1       0
  4940.8    0.16       0  4993.7    0.07       0  4999.7    0.16       0
  5256.4     0.1       0
Bank Sta=4993.7,4999.7
Exp/Cntr=0.3,0.1

Type RM Length L Ch R = 1,20996,436,436,436
BEGIN DESCRIPTION:
WEST FORK WILLIAMS CREEK 45.0
END DESCRIPTION:
XS GIS Cut Line= 2
      2833643.36     10024531.49      2834410.09     10023638.48
#Sta/Elev= 30
  4146.1 1673.81  4176.5 1669.84  4219.3 1668.67  4275.5 1663.36  4286.7 1662.42
  4325.8 1661.29  4403.7 1653.08  4459.7 1649.73  4545.3 1648.59  4608.9 1643.32
  4723.0 1640.44  4750.5 1636.40  4856.9 1628.85  4893.1 1631.34  4963.4 1632.65
  4985.3 1630.33  4996.6 1627.25  4999.3 1626.75  5002.6 1627.25  5020.4 1630.41
  5044.4 1631.10  5063.2 1633.97  5105.3 1648.76  5141.2 1665.61  5162.0 1678.22
  5204.8 1694.95  5225.7 1698.47  5261.9 1708.52  5297.0 1714.08  5323.1 1716.00
#Mann=6,-1,0
  4146.1     0.1       0  4275.5    0.05       0  4286.7     0.1       0
  4996.6    0.07       0  5002.6     0.1       0  5044.4    0.16       0
Bank Sta=4996.6,5002.6
Exp/Cntr=0.3,0.1

Type RM Length L Ch R = 1,20560,410,410,410
BEGIN DESCRIPTION:
WEST FORK WILLIAMS CREEK 44.0
END DESCRIPTION:
XS GIS Cut Line= 3
      2833832.85     10024648.76      2834590.72     10024125.47
      2834780.12     10023728.63
#Sta/Elev= 30
  4278.5 1670.22  4401.3 1658.19  4498.3 1650.42  4657.6 1638.63  4840.0 1626.89
  4881.9 1624.87  4983.3 1623.72  4995.2 1621.52  4997.9 1621.02  5001.2 1621.52
  5040.1 1627.99  5080.2 1629.89  5177.3 1638.11  5202.7 1639.02  5220.9 1641.69
  5325.4 1654.85  5342.5 1659.91  5348.1 1659.82  5365.2 1664.22  5370.8 1663.36
  5438.8 1666.95  5484.2 1671.90  5535.1 1674.32  5567.1 1678.73  5580.5 1678.79
  5597.6 1681.70  5603.2 1680.82  5620.3 1683.81  5625.9 1683.25  5639.2 1686.49
#Mann=7,-1,0
  4278.5     0.1       0  4498.3    0.05       0  4657.6     0.1       0
  4995.2    0.07       0  5001.2     0.1       0  5080.2    0.05       0
  5220.9     0.1       0
Bank Sta=4995.2,5001.2
Exp/Cntr=0.3,0.1

Type RM Length L Ch R = 1,20150,305,305,305
BEGIN DESCRIPTION:
WEST FORK WILLIAMS CREEK 43.0
END DESCRIPTION:
XS GIS Cut Line= 3
      2834410.29     10025000.61      2834825.30     10024269.83
      2834852.30     10023837.77
#Sta/Elev= 30
  4460.1 1654.78  4501.9 1655.18  4515.8 1659.06  4529.3 1661.81  4545.1 1661.41
  4550.9 1657.62  4572.5 1652.01  4728.3 1640.12  4814.8 1634.55  4859.0 1632.78
  4895.5 1627.98  4933.0 1624.12  4985.5 1620.15  4992.1 1619.42  4994.9 1618.32
  4997.6 1617.82  5000.9 1618.32  5013.8 1620.14  5078.6 1620.05  5256.0 1627.35
  5316.6 1628.56  5470.6 1638.55  5507.0 1641.40  5567.1 1649.52  5587.0 1653.84
  5592.0 1653.47  5617.2 1659.64  5647.3 1665.07  5707.4 1669.08  5733.4 1672.42
#Mann=5,-1,0
  4460.1     0.1       0  4515.8    0.05       0  4994.9    0.04       0
  5000.9    0.05       0  5470.6     0.1       0
Bank Sta=4994.9,5000.9
Exp/Cntr=0.3,0.1

Type RM Length L Ch R = 1,19845,405,405,405
BEGIN DESCRIPTION:
WEST FORK WILLIAMS CREEK 42.0
END DESCRIPTION:
XS GIS Cut Line= 2
      2834744.10     10025063.78      2835258.38     10024044.25
#Sta/Elev= 30
  4534.9 1649.54  4680.6 1641.61  4693.1 1639.01  4709.8 1639.16  4725.4 1638.08
  4754.4 1634.37  4792.6 1631.77  4799.1 1630.33  4871.6 1624.49  4932.9 1620.08
  4991.2 1617.10  4993.9 1616.60  4997.2 1617.10  5022.1 1618.13  5089.0 1617.40
  5128.0 1618.91  5155.9 1619.05  5207.0 1621.77  5267.4 1623.69  5356.6 1630.01
  5408.6 1632.91  5431.0 1635.02  5490.4 1638.89  5507.1 1641.15  5535.0 1642.54
  5610.7 1648.16  5614.2 1648.44  5646.5 1650.78  5663.2 1652.87  5676.8 1653.21
#Mann=5,-1,0
  4534.9     0.1       0  4991.2    0.07       0  4997.2     0.1       0
  5610.7    0.16       0  5614.2     0.1       0
Bank Sta=4991.2,4997.2
Exp/Cntr=0.3,0.1

Type RM Length L Ch R = 1,19440,523,523,523
BEGIN DESCRIPTION:
WEST FORK WILLIAMS CREEK 41.0
END DESCRIPTION:
XS GIS Cut Line= 3
      2834879.43     10025397.62      2835240.32     10025018.68
      2835582.55     10024037.02
#Sta/Elev= 30
  4279.2 1652.61  4543.0 1642.80  4705.7 1635.08  4776.4 1633.49  4891.6 1626.72
  4977.2 1614.04  4999.0 1613.62  5021.8 1609.69  5024.5 1609.19  5027.8 1609.69
  5030.1 1611.38  5040.7 1612.50  5074.6 1613.11  5157.2 1614.65  5199.6 1613.69
  5349.1 1614.86  5476.8 1617.77  5573.5 1622.60  5635.7 1630.01  5661.7 1636.94
  5666.7 1636.36  5692.5 1641.43  5697.8 1640.90  5718.3 1644.28  5723.6 1643.13
  5729.1 1645.71  5754.7 1645.82  5785.7 1648.92  5816.8 1653.87  5842.1 1654.08
#Mann=8,-1,0
  4279.2     0.1       0  4891.6    0.16       0  5021.8    0.07       0
  5027.8    0.16       0  5074.6     0.1       0  5349.1    0.05       0
  5476.8     0.1       0  5661.7    0.16       0
Bank Sta=5021.8,5027.8
Exp/Cntr=0.3,0.1

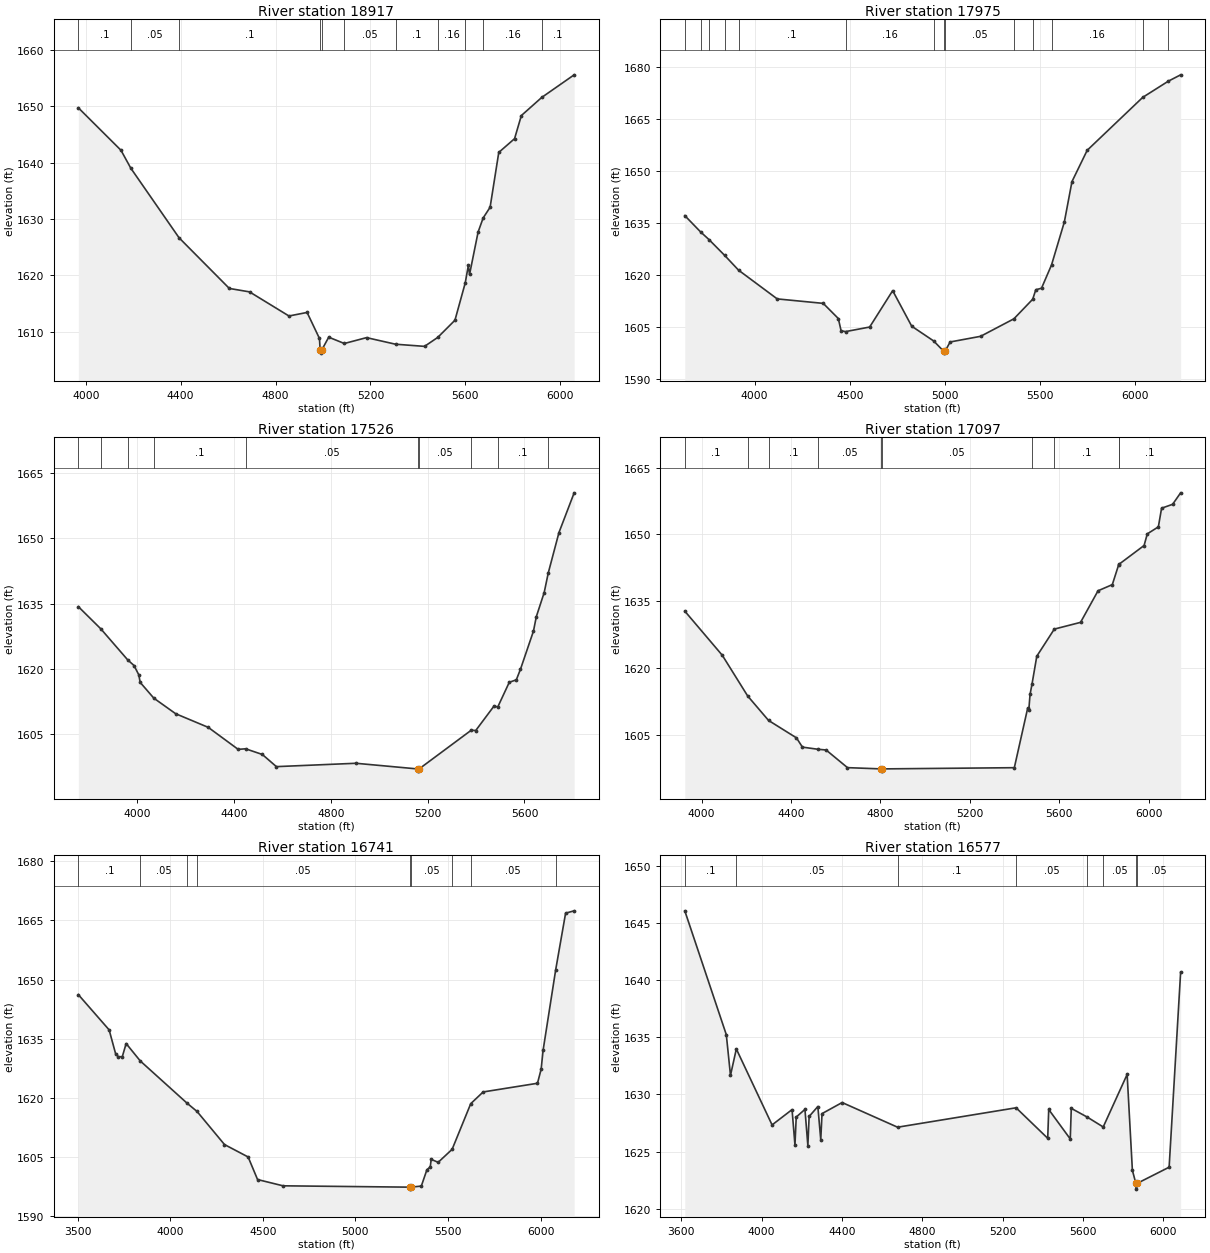
Type RM Length L Ch R = 1,18917,942,942,942
BEGIN DESCRIPTION:
WEST FORK WILLIAMS CREEK 40.0
END DESCRIPTION:
XS GIS Cut Line= 4
      2835050.85     10025668.29      2835754.59     10025126.95
      2835889.93     10024675.83      2835772.64     10023954.05
#Sta/Elev= 30
  3968.7 1649.72  4148.5 1642.18  4189.9 1639.00  4393.3 1626.65  4605.2 1617.66
  4690.4 1617.05  4856.6 1612.77  4933.0 1613.40  4985.2 1608.78  4988.1 1606.68
  4990.9 1606.18  4994.1 1606.68  5024.2 1609.01  5089.9 1607.89  5183.6 1608.93
  5306.0 1607.76  5428.1 1607.38  5483.8 1608.97  5556.3 1612.02  5599.6 1618.63
  5612.8 1621.75  5617.8 1620.14  5653.9 1627.67  5675.2 1630.17  5704.5 1632.07
  5741.0 1641.80  5807.6 1644.24  5836.2 1648.34  5922.2 1651.56  6058.8 1655.57
#Mann=11,-1,0
  3968.7     0.1       0  4189.9    0.05       0  4393.3     0.1       0
  4988.1    0.07       0  4994.1     0.1       0  5089.9    0.05       0
  5306.0     0.1       0  5483.8    0.16       0  5599.6    0.05       0
  5675.2    0.16       0  5922.2     0.1       0
Bank Sta=4988.1,4994.1
Exp/Cntr=0.3,0.1

Type RM Length L Ch R = 1,17975,449,449,449
BEGIN DESCRIPTION:
WEST FORK WILLIAMS CREEK 39.0
END DESCRIPTION:
XS GIS Cut Line= 3
      2835294.44     10025659.28      2836313.98     10024901.39
      2837649.31     10024847.26
#Sta/Elev= 30
  3633.0 1637.05  3715.9 1632.35  3759.8 1630.15  3842.9 1625.55  3915.7 1621.30
  4118.9 1613.01  4360.8 1611.72  4440.1 1607.35  4454.7 1603.82  4477.9 1603.57
  4604.9 1604.89  4725.9 1615.39  4826.0 1605.13  4941.4 1600.87  4994.9 1597.86
  4997.7 1597.36  5000.9 1597.86  5028.0 1600.58  5188.1 1602.21  5363.2 1607.26
  5462.2 1612.92  5478.3 1615.65  5508.4 1616.09  5561.1 1622.81  5628.5 1635.22
  5668.5 1646.86  5748.6 1655.90  6040.7 1671.18  6175.2 1675.85  6239.8 1677.68
#Mann=14,-1,0
  3633.0    0.05       0  3715.9     0.1       0  3759.8    0.05       0
  3842.9    0.16       0  3915.7     0.1       0  4477.9    0.16       0
  4941.4    0.05       0  4994.9   0.033       0  5000.9    0.05       0
  5363.2    0.16       0  5462.2     0.1       0  5561.1    0.16       0
  6040.7     0.1       0  6175.2    0.05       0
Bank Sta=4994.9,5000.9
Exp/Cntr=0.3,0.1

Type RM Length L Ch R = 1,17526,429,429,429
BEGIN DESCRIPTION:
WEST FORK WILLIAMS CREEK 38.0
END DESCRIPTION:
XS GIS Cut Line= 3
      2835368.68     10025769.13      2835456.86     10025731.44
      2837252.34     10024964.53
#Sta/Elev= 30
  3757.1 1634.30  3850.3 1629.19  3961.4 1622.07  3987.2 1620.80  4007.0 1618.65
  4012.5 1616.94  4068.9 1613.32  4159.2 1609.75  4293.9 1606.62  4417.4 1601.58
  4448.0 1601.71  4517.2 1600.41  4575.3 1597.62  4903.9 1598.39  5158.7 1597.09
  5161.4 1596.59  5164.7 1597.09  5380.3 1605.97  5398.8 1605.90  5475.0 1611.56
  5489.6 1611.27  5537.4 1616.96  5566.5 1617.52  5583.7 1619.96  5637.3 1628.69
  5649.0 1631.98  5681.6 1637.53  5698.3 1641.99  5742.6 1651.28  5805.4 1660.39
#Mann=10,-1,0
  3757.1    0.16       0  3850.3     0.1       0  3961.4    0.16       0
  4068.9     0.1       0  4448.0    0.05       0  5158.7   0.033       0
  5164.7    0.05       0  5380.3    0.16       0  5489.6     0.1       0
  5698.3    0.16       0
Bank Sta=5158.7,5164.7
Exp/Cntr=0.3,0.1

Type RM Length L Ch R = 1,17097,356,356,356
BEGIN DESCRIPTION:
WEST FORK WILLIAMS CREEK 37.0
END DESCRIPTION:
XS GIS Cut Line= 3
      2835391.44     10025810.97      2837098.92     10025641.22
      2837417.33     10025252.60
#Sta/Elev= 30
  3924.7 1632.82  4092.6 1622.91  4206.1 1613.79  4299.5 1608.31  4424.2 1604.41
  4451.0 1602.33  4520.4 1601.85  4556.8 1601.69  4652.6 1597.73  4803.1 1597.45
  4805.8 1596.95  4809.1 1597.45  5399.0 1597.72  5458.9 1611.11  5463.9 1610.70
  5469.3 1614.13  5478.3 1616.51  5499.5 1622.71  5577.9 1628.79  5695.3 1630.30
  5773.5 1637.38  5837.4 1638.76  5865.7 1643.20  5867.0 1643.31  5979.5 1647.53
  5993.9 1650.14  6043.4 1651.71  6057.8 1655.89  6107.3 1656.77  6143.0 1659.34
#Mann=10,-1,0
  3924.7     0.1       0  4206.1    0.16       0  4299.5     0.1       0
  4520.4    0.05       0  4803.1   0.033       0  4809.1    0.05       0
  5478.3    0.16       0  5577.9     0.1       0  5865.7    0.05       0
  5867.0     0.1       0
Bank Sta=4803.1,4809.1
Exp/Cntr=0.3,0.1

Type RM Length L Ch R = 1,16741,164,164,164
BEGIN DESCRIPTION:
Mapping XS 9761c381
END DESCRIPTION:
XS GIS Cut Line= 3
      2835272.16     10026772.32      2835980.50     10026119.53
      2837674.18     10025862.71
#Sta/Elev= 30
  3504.3 1646.20  3670.6 1637.26  3705.7 1631.19  3719.9 1630.47  3741.5 1630.46
  3762.4 1633.80  3838.6 1629.39  4091.3 1618.68  4145.2 1616.58  4293.2 1608.20
  4420.8 1605.05  4471.7 1599.33  4609.2 1597.74  5291.9 1597.40  5294.6 1596.90
  5297.9 1597.40  5355.6 1597.67  5385.9 1601.82  5403.9 1602.53  5408.9 1604.45
  5446.6 1603.69  5521.9 1606.99  5622.4 1618.56  5689.3 1621.53  5982.6 1623.73
  6002.4 1627.29  6013.0 1632.10  6080.9 1652.49  6134.4 1666.85  6180.6 1667.44
#Mann=9,-1,0
  3504.3     0.1       0  3838.6    0.05       0  4091.3    0.16       0
  4145.2    0.05       0  5291.9   0.033       0  5297.9    0.05       0
  5521.9    0.16       0  5622.4    0.05       0  6080.9     0.1       0
Bank Sta=5291.9,5297.9
Exp/Cntr=0.3,0.1

Type RM Length L Ch R = 1,16577,137,137,137
BEGIN DESCRIPTION:
Mapping XS 8866dbfa
END DESCRIPTION:
XS GIS Cut Line= 3
      2835312.12     10026797.11      2835935.04     10026308.87
      2837584.78     10026011.38
#Sta/Elev= 30
  3618.1 1646.07  3824.7 1635.23  3845.5 1631.67  3874.6 1633.98  4052.5 1627.33
  4151.9 1628.67  4166.4 1625.57  4172.7 1628.02  4216.1 1628.69  4230.6 1625.52
  4236.9 1628.07  4280.3 1628.94  4294.8 1626.04  4301.1 1628.32  4401.2 1629.29
  4677.1 1627.13  5267.0 1628.83  5424.4 1626.16  5429.4 1628.68  5536.6 1626.10
  5541.7 1628.78  5621.6 1628.01  5700.6 1627.15  5819.7 1631.75  5845.8 1623.36
  5863.1 1622.21  5865.9 1621.71  5869.1 1622.21  6028.7 1623.63  6085.9 1640.69
#Mann=8,-1,0
  3618.1     0.1       0  3874.6    0.05       0  4677.1     0.1       0
  5267.0    0.05       0  5621.6    0.16       0  5700.6    0.05       0
  5863.1    0.07       0  5869.1    0.05       0
Bank Sta=5863.1,5869.1
Exp/Cntr=0.3,0.1

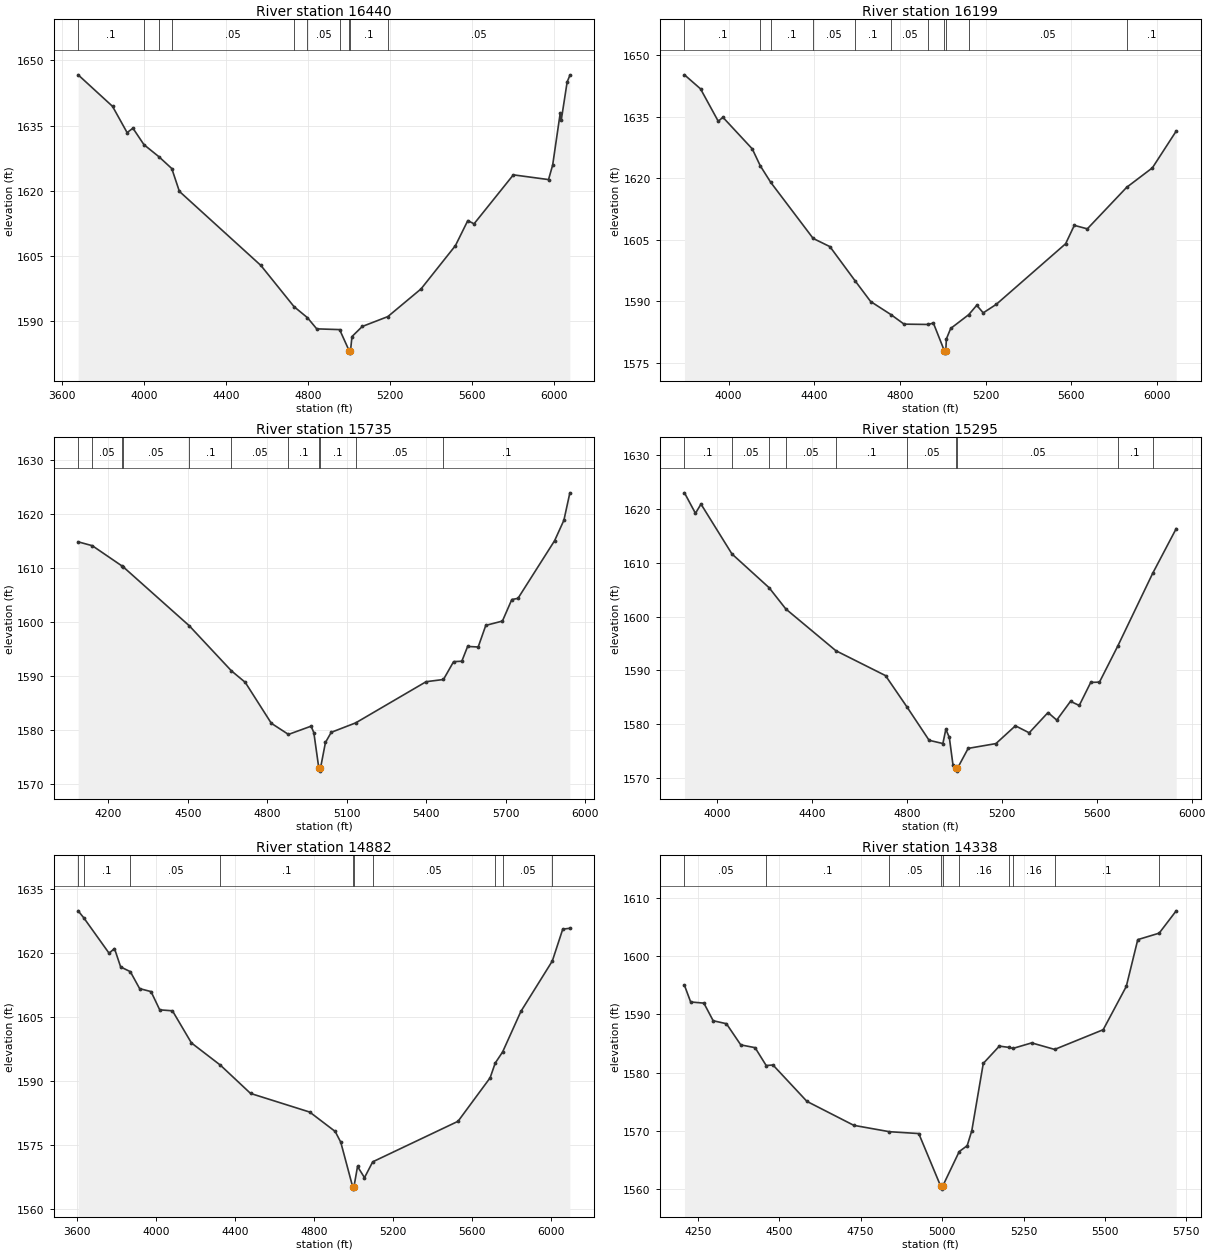
Type RM Length L Ch R = 1,16440,241,241,241
BEGIN DESCRIPTION:
WEST FORK WILLIAMS CREEK 35.0
END DESCRIPTION:
XS GIS Cut Line= 3
      2835424.93     10026987.61      2836091.61     10026404.26
      2837591.57     10026182.04
#Sta/Elev= 30
  3677.3 1646.68  3845.4 1639.43  3916.6 1633.39  3945.0 1634.41  3999.0 1630.61
  4071.4 1627.87  4134.8 1625.13  4171.9 1619.88  4570.1 1602.84  4732.0 1593.37
  4797.1 1590.85  4843.0 1588.26  4954.7 1588.09  5001.8 1583.18  5004.5 1582.68
  5007.8 1583.18  5015.1 1586.49  5065.4 1588.81  5190.2 1591.08  5352.5 1597.45
  5520.4 1607.40  5581.0 1613.17  5611.3 1612.41  5803.4 1623.68  5975.3 1622.59
  5995.5 1625.93  6032.4 1637.87  6037.4 1636.25  6066.3 1645.05  6079.5 1646.56
#Mann=10,-1,0
  3677.3     0.1       0  3999.0    0.05       0  4071.4     0.1       0
  4134.8    0.05       0  4732.0     0.1       0  4797.1    0.05       0
  4954.7     0.1       0  5001.8    0.07       0  5007.8     0.1       0
  5190.2    0.05       0
Bank Sta=5001.8,5007.8
Exp/Cntr=0.3,0.1

Type RM Length L Ch R = 1,16199,464,464,464
BEGIN DESCRIPTION:
WEST FORK WILLIAMS CREEK 36.0
END DESCRIPTION:
XS GIS Cut Line= 3
      2835474.94     10027039.66      2836467.36     10026588.56
      2837658.35     10026399.09
#Sta/Elev= 30
  3794.2 1645.27  3869.2 1641.85  3951.9 1633.95  3973.8 1634.91  4110.9 1627.20
  4148.0 1623.10  4197.1 1619.04  4395.1 1605.37  4473.4 1603.37  4592.3 1594.94
  4663.4 1589.99  4758.5 1586.79  4819.6 1584.47  4933.5 1584.39  4956.3 1584.75
  5008.3 1577.90  5011.0 1577.40  5014.3 1577.90  5017.1 1580.86  5037.3 1583.42
  5121.5 1586.78  5158.9 1589.07  5189.2 1587.22  5250.0 1589.29  5574.0 1604.08
  5614.5 1608.56  5675.3 1607.71  5858.9 1617.83  5979.0 1622.58  6090.3 1631.55
#Mann=11,-1,0
  3794.2     0.1       0  4148.0    0.05       0  4197.1     0.1       0
  4395.1    0.05       0  4592.3     0.1       0  4758.5    0.05       0
  4933.5     0.1       0  5008.3    0.07       0  5014.3     0.1       0
  5121.5    0.05       0  5858.9     0.1       0
Bank Sta=5008.3,5014.3
Exp/Cntr=0.3,0.1

Type RM Length L Ch R = 1,15735,440,440,440
BEGIN DESCRIPTION:
WEST FORK WILLIAMS CREEK 34.0
END DESCRIPTION:
XS GIS Cut Line= 2
      2835925.98     10027355.48      2837620.88     10026598.18
#Sta/Elev= 30
  4086.3 1614.90  4139.8 1614.18  4251.9 1610.42  4255.0 1610.32  4505.6 1599.34
  4664.9 1590.97  4717.2 1588.83  4815.6 1581.24  4880.3 1579.17  4965.8 1580.70
  4976.2 1579.49  4995.1 1572.86  4997.9 1572.36  5001.1 1572.86  5020.0 1577.68
  5041.9 1579.56  5134.1 1581.31  5400.0 1588.95  5465.5 1589.36  5503.8 1592.67
  5534.8 1592.75  5556.7 1595.49  5596.6 1595.39  5625.3 1599.40  5688.1 1600.20
  5723.6 1604.20  5746.8 1604.41  5885.3 1615.13  5920.2 1618.91  5942.7 1623.99
#Mann=11,-1,0
  4086.3     0.1       0  4139.8    0.05       0  4251.9     0.1       0
  4255.0    0.05       0  4505.6     0.1       0  4664.9    0.05       0
  4880.3     0.1       0  4995.1    0.07       0  5001.1     0.1       0
  5134.1    0.05       0  5465.5     0.1       0
Bank Sta=4995.1,5001.1
Exp/Cntr=0.3,0.1

Type RM Length L Ch R = 1,15295,413,413,413
BEGIN DESCRIPTION:
WEST FORK WILLIAMS CREEK 33.0
END DESCRIPTION:
XS GIS Cut Line= 2
      2835989.14     10027959.98      2837756.33     10026878.02
#Sta/Elev= 30
  3862.9 1622.95  3909.2 1619.15  3932.5 1620.86  4063.0 1611.61  4219.5 1605.35
  4290.1 1601.40  4500.9 1593.66  4710.1 1589.04  4800.9 1583.20  4893.8 1577.04
  4951.8 1576.44  4964.3 1579.09  4979.0 1577.56  4994.4 1572.45  5006.9 1571.82
  5009.6 1571.32  5012.9 1571.82  5058.3 1575.54  5175.4 1576.43  5257.4 1579.73
  5315.5 1578.43  5394.8 1582.19  5431.6 1580.79  5489.6 1584.27  5526.4 1583.50
  5574.8 1587.78  5611.6 1587.83  5688.7 1594.52  5835.9 1608.02  5935.0 1616.31
#Mann=10,-1,0
  3862.9     0.1       0  4063.0    0.05       0  4219.5     0.1       0
  4290.1    0.05       0  4500.9     0.1       0  4800.9    0.05       0
  5006.9    0.04       0  5012.9    0.05       0  5688.7     0.1       0
  5835.9    0.05       0
Bank Sta=5006.9,5012.9
Exp/Cntr=0.3,0.1

Type RM Length L Ch R = 1,14882,544,544,544
BEGIN DESCRIPTION:
WEST FORK WILLIAMS CREEK 32.0
END DESCRIPTION:
XS GIS Cut Line= 3
      2835989.17     10028438.14      2837044.78     10027824.62
      2837929.00     10026913.34
#Sta/Elev= 30
  3605.3 1629.89  3633.3 1628.29  3762.0 1619.96  3789.5 1621.05  3820.7 1616.74
  3869.7 1615.63  3916.8 1611.66  3974.6 1610.96  4018.6 1606.68  4083.1 1606.46
  4179.1 1598.93  4325.8 1593.72  4478.7 1587.09  4778.4 1582.72  4907.3 1578.18
  4935.6 1575.66  4996.2 1565.16  4998.9 1564.66  5002.2 1565.16  5020.5 1569.97
  5055.8 1567.35  5097.4 1571.06  5529.6 1580.56  5692.2 1590.76  5717.6 1594.18
  5755.4 1596.82  5847.8 1606.30  6007.1 1618.13  6060.0 1625.60  6096.0 1625.80
#Mann=10,-1,0
  3605.3    0.05       0  3633.3     0.1       0  3869.7    0.05       0
  4325.8     0.1       0  4996.2    0.07       0  5002.2     0.1       0
  5097.4    0.05       0  5717.6     0.1       0  5755.4    0.05       0
  6007.1     0.1       0
Bank Sta=4996.2,5002.2
Exp/Cntr=0.3,0.1

Type RM Length L Ch R = 1,14338,175,175,175
BEGIN DESCRIPTION:
WEST FORK WILLIAMS CREEK 31.0
END DESCRIPTION:
XS GIS Cut Line= 3
      2836801.14     10028474.24      2837396.65     10028203.56
      2837973.75     10027572.36
#Sta/Elev= 30
  4209.3 1594.99  4228.3 1592.14  4268.9 1591.94  4297.4 1588.92  4338.1 1588.41
  4382.1 1584.78  4426.1 1584.30  4460.1 1581.24  4481.0 1581.33  4585.2 1575.09
  4729.1 1570.98  4838.2 1569.89  4928.5 1569.57  4995.8 1560.54  4998.5 1560.04
  5001.8 1560.54  5052.6 1566.48  5077.1 1567.49  5091.3 1570.07  5126.5 1581.60
  5175.8 1584.57  5206.1 1584.34  5217.3 1584.17  5275.1 1585.12  5345.6 1584.00
  5494.6 1587.38  5565.5 1594.81  5600.7 1602.83  5666.4 1603.94  5718.7 1607.77
#Mann=10,-1,0
  4209.3    0.05       0  4460.1     0.1       0  4838.2    0.05       0
  4995.8   0.035       0  5001.8    0.05       0  5052.6    0.16       0
  5206.1    0.05       0  5217.3    0.16       0  5345.6     0.1       0
  5666.4    0.05       0
Bank Sta=4995.8,5001.8
Exp/Cntr=0.3,0.1