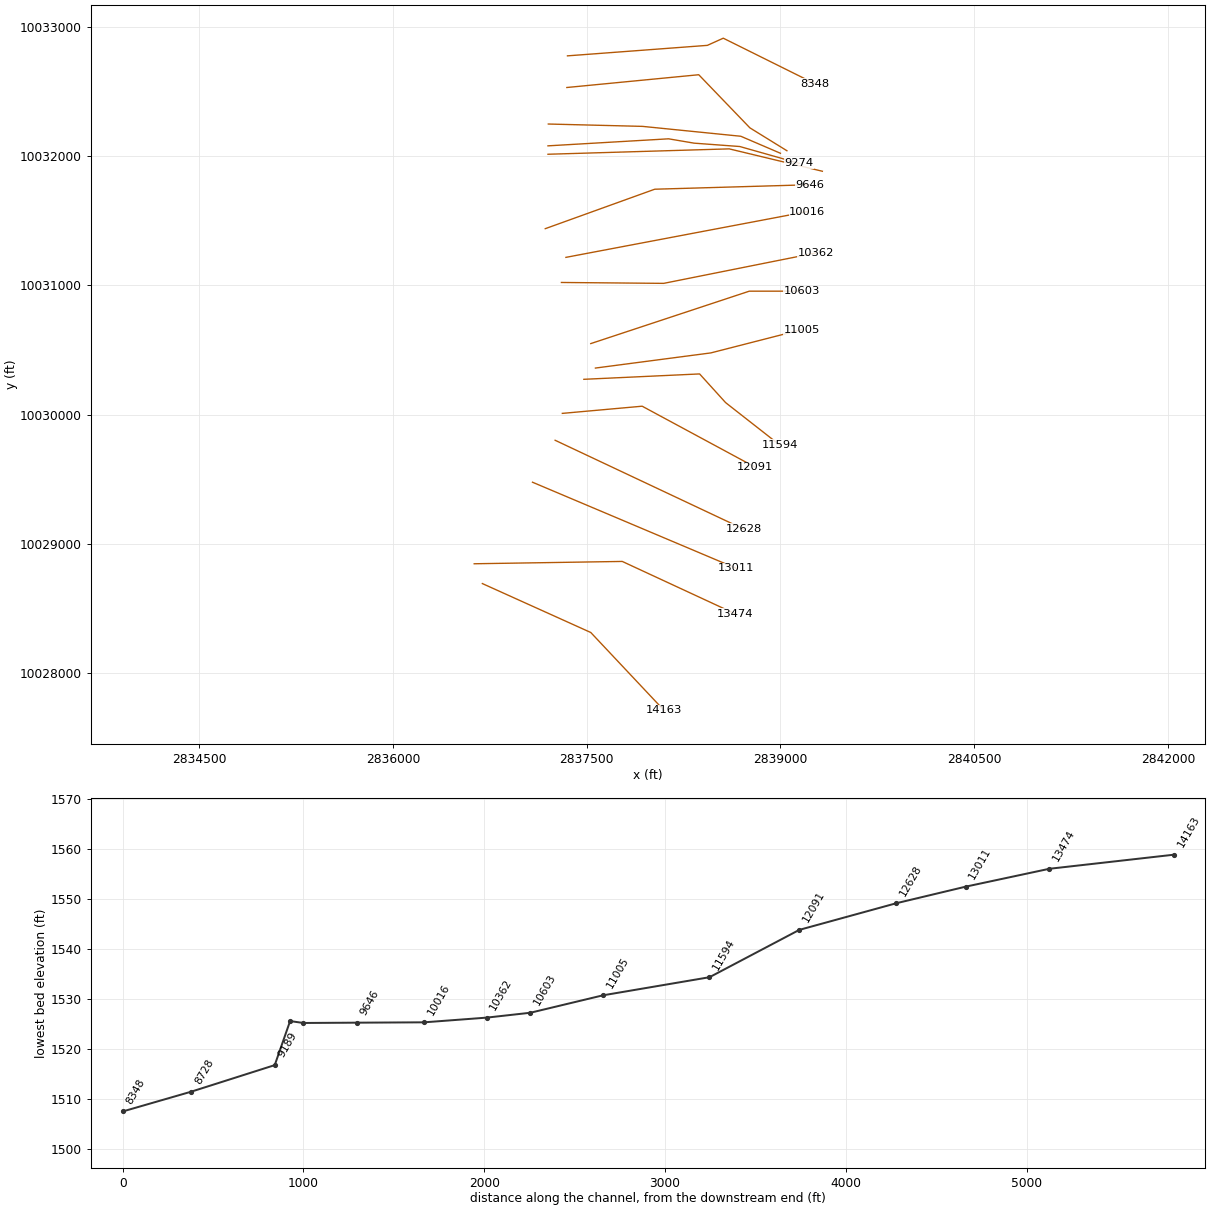
HEC-RAS study WEST FORK WILLIAMS CREEK.prj: WEST FORK WILLIAMS CREEK Base Level Engineering

--- WEST FORK WILLIAMS CREEK.g01 (geometry) --- (continued)

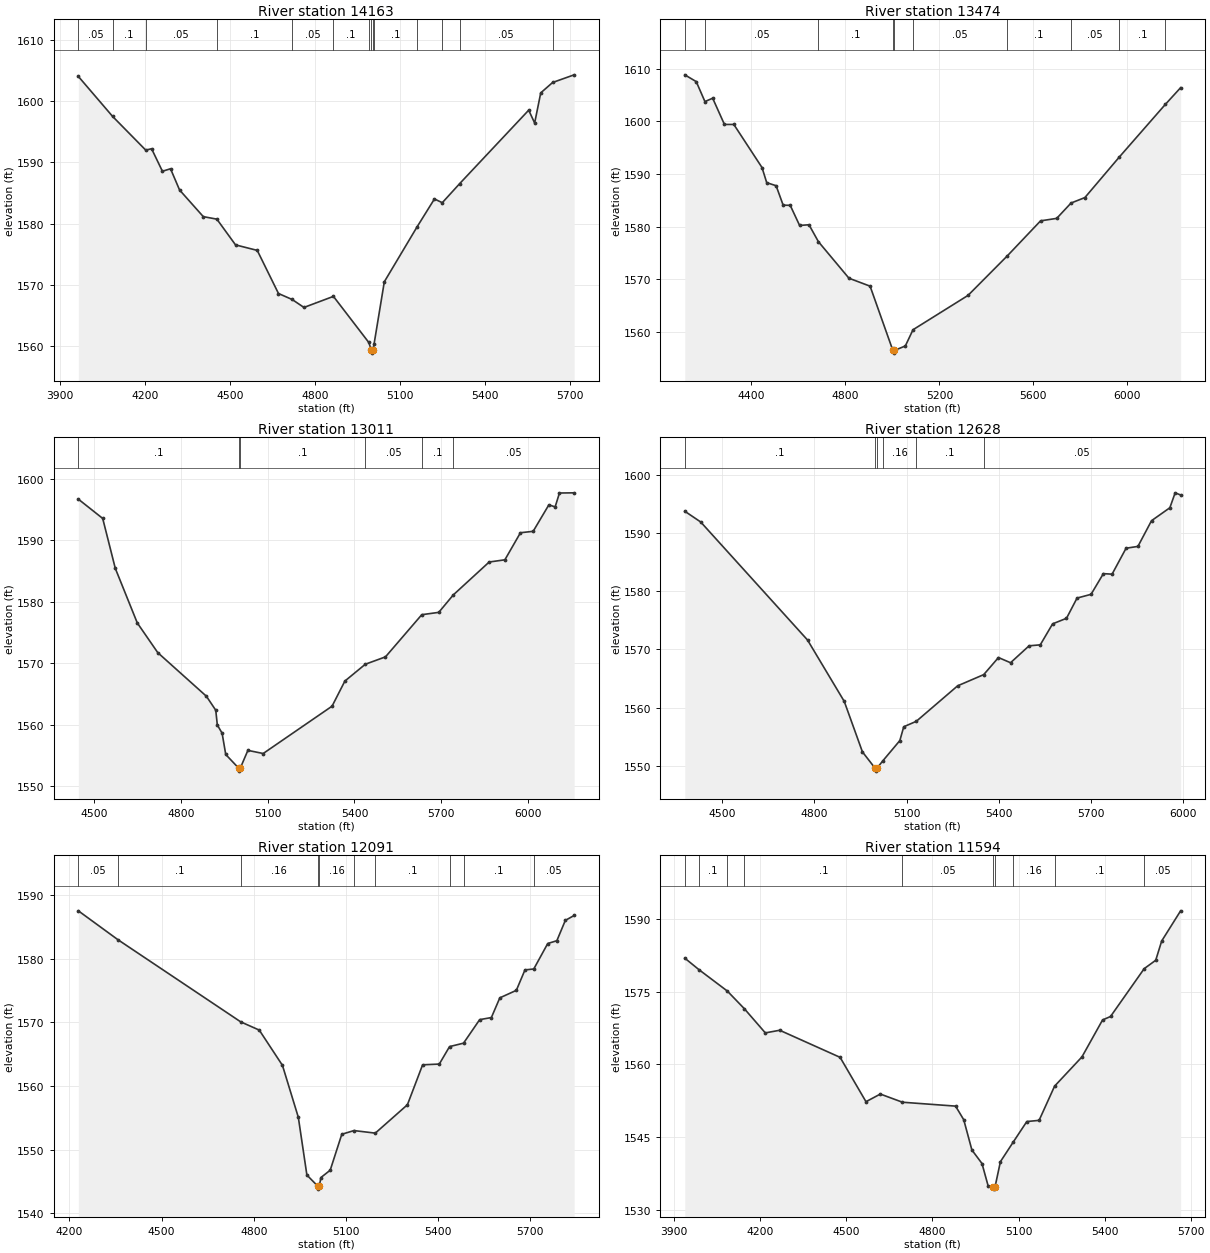
Type RM Length L Ch R = 1,14163,689,689,689
BEGIN DESCRIPTION:
WEST FORK WILLIAMS CREEK 30.0
END DESCRIPTION:
XS GIS Cut Line= 3
      2836692.91     10028690.76      2837531.99     10028311.83
      2838099.75     10027708.01
#Sta/Elev= 30
  3963.9 1604.06  4084.8 1597.52  4201.7 1592.01  4222.4 1592.23  4260.6 1588.55
  4289.2 1588.96  4321.1 1585.49  4404.8 1581.13  4452.7 1580.72  4518.6 1576.51
  4595.2 1575.61  4670.1 1568.56  4718.4 1567.58  4760.0 1566.28  4864.0 1568.09
  4988.5 1560.57  4998.1 1559.31  5000.8 1558.81  5004.1 1559.31  5007.4 1560.30
  5043.6 1570.48  5158.4 1579.40  5220.4 1584.02  5248.1 1583.41  5309.3 1586.52
  5553.0 1598.54  5574.0 1596.44  5595.5 1601.37  5637.5 1603.07  5713.4 1604.32
#Mann=14,-1,0
  3963.9    0.05       0  4084.8     0.1       0  4201.7    0.05       0
  4452.7     0.1       0  4718.4    0.05       0  4864.0     0.1       0
  4988.5    0.16       0  4998.1    0.07       0  5004.1    0.16       0
  5007.4     0.1       0  5158.4    0.05       0  5248.1     0.1       0
  5309.3    0.05       0  5637.5     0.1       0
Bank Sta=4998.1,5004.1
Exp/Cntr=0.3,0.1

Type RM Length L Ch R = 1,13474,463,463,463
BEGIN DESCRIPTION:
WEST FORK WILLIAMS CREEK 29.0
END DESCRIPTION:
XS GIS Cut Line= 3
      2836629.80     10028844.14      2837775.59     10028862.19
      2838650.76     10028456.18
#Sta/Elev= 30
  4116.1 1608.83  4164.8 1607.54  4201.8 1603.75  4234.8 1604.39  4284.8 1599.41
  4324.8 1599.41  4444.8 1591.23  4464.8 1588.36  4504.8 1587.78  4534.8 1584.09
  4564.8 1584.06  4604.8 1580.24  4644.8 1580.37  4684.8 1577.16  4814.9 1570.22
  4904.9 1568.71  5001.9 1556.50  5004.6 1556.00  5007.9 1556.50  5054.9 1557.36
  5087.6 1560.44  5321.8 1566.96  5489.2 1574.47  5630.6 1581.11  5699.3 1581.58
  5760.3 1584.49  5819.3 1585.53  5965.7 1593.22  6161.4 1603.20  6226.8 1606.39
#Mann=10,-1,0
  4116.1     0.1       0  4201.8    0.05       0  4684.8     0.1       0
  5001.9    0.07       0  5007.9     0.1       0  5087.6    0.05       0
  5489.2     0.1       0  5760.3    0.05       0  5965.7     0.1       0
  6161.4    0.05       0
Bank Sta=5001.9,5007.9
Exp/Cntr=0.3,0.1

Type RM Length L Ch R = 1,13011,383,383,383
BEGIN DESCRIPTION:
WEST FORK WILLIAMS CREEK 28.0
END DESCRIPTION:
XS GIS Cut Line= 2
      2837080.87     10029475.71      2838658.98     10028808.39
#Sta/Elev= 30
  4445.8 1596.73  4530.0 1593.59  4573.5 1585.46  4649.5 1576.57  4720.3 1571.73
  4888.3 1564.63  4920.7 1562.35  4926.1 1559.94  4942.6 1558.62  4955.2 1555.14
  4999.6 1552.93  5002.4 1552.43  5005.6 1552.93  5031.7 1555.81  5084.6 1555.30
  5322.6 1563.01  5366.9 1567.10  5437.5 1569.84  5507.2 1571.04  5632.6 1577.91
  5691.3 1578.29  5741.7 1581.14  5865.5 1586.49  5919.8 1586.85  5973.6 1591.26
  6017.5 1591.49  6071.8 1595.80  6093.5 1595.47  6108.4 1597.73  6159.2 1597.76
#Mann=6,-1,0
  4445.8     0.1       0  4999.6    0.07       0  5005.6     0.1       0
  5437.5    0.05       0  5632.6     0.1       0  5741.7    0.05       0
Bank Sta=4999.6,5005.6
Exp/Cntr=0.3,0.1

Type RM Length L Ch R = 1,12628,537,537,537
BEGIN DESCRIPTION:
WEST FORK WILLIAMS CREEK 27.0
END DESCRIPTION:
XS GIS Cut Line= 2
      2837256.21     10029800.52      2838714.03     10029113.26
#Sta/Elev= 30
  4379.2 1593.70  4430.9 1591.86  4778.1 1571.62  4897.5 1561.09  4956.6 1552.43
  4997.8 1549.63  5000.6 1549.13  5003.8 1549.63  5023.6 1550.94  5078.2 1554.37
  5090.9 1556.74  5131.6 1557.67  5266.1 1563.76  5350.8 1565.68  5398.8 1568.61
  5438.1 1567.72  5498.3 1570.62  5534.7 1570.79  5574.8 1574.39  5619.9 1575.34
  5654.2 1578.81  5699.7 1579.45  5739.8 1583.00  5768.1 1582.91  5813.6 1587.36
  5852.1 1587.67  5896.3 1592.08  5955.9 1594.30  5973.1 1596.86  5990.9 1596.49
#Mann=6,-1,0
  4379.2     0.1       0  4997.8    0.07       0  5003.8     0.1       0
  5023.6    0.16       0  5131.6     0.1       0  5350.8    0.05       0
Bank Sta=4997.8,5003.8
Exp/Cntr=0.3,0.1

Type RM Length L Ch R = 1,12091,497,497,497
BEGIN DESCRIPTION:
WEST FORK WILLIAMS CREEK 26.0
END DESCRIPTION:
XS GIS Cut Line= 3
      2837311.79     10030008.85      2837929.83     10030064.41
      2838804.10     10029592.58
#Sta/Elev= 30
  4229.1 1587.49  4357.9 1582.96  4757.8 1570.06  4818.1 1568.77  4893.5 1563.24
  4945.2 1555.09  4973.1 1546.02  5007.9 1544.31  5010.7 1543.81  5013.9 1544.31
  5018.5 1545.62  5049.0 1546.78  5086.7 1552.42  5126.4 1553.00  5195.8 1552.60
  5300.3 1557.05  5349.8 1563.32  5404.1 1563.44  5437.5 1566.18  5483.0 1566.72
  5535.5 1570.41  5573.6 1570.74  5601.1 1573.83  5654.9 1575.01  5683.0 1578.22
  5711.6 1578.36  5757.1 1582.36  5786.8 1582.80  5814.4 1585.99  5843.1 1586.76
#Mann=10,-1,0
  4229.1    0.05       0  4357.9     0.1       0  4757.8    0.16       0
  5007.9    0.07       0  5013.9    0.16       0  5126.4    0.05       0
  5195.8     0.1       0  5437.5    0.05       0  5483.0     0.1       0
  5711.6    0.05       0
Bank Sta=5007.9,5013.9
Exp/Cntr=0.3,0.1

Type RM Length L Ch R = 1,11594,589,589,589
BEGIN DESCRIPTION:
WEST FORK WILLIAMS CREEK 25.0
END DESCRIPTION:
XS GIS Cut Line= 4
      2837478.47     10030272.74      2838374.27     10030314.41
      2838575.66     10030092.18      2838992.36     10029765.77
#Sta/Elev= 30
  3937.8 1581.86  3987.1 1579.49  4085.7 1575.10  4145.1 1571.46  4218.1 1566.49
  4268.2 1567.03  4478.4 1561.46  4568.5 1552.34  4618.5 1553.91  4695.5 1552.23
  4880.4 1551.43  4908.8 1548.63  4937.2 1542.41  4972.3 1539.63  4993.9 1534.99
  5011.9 1534.86  5014.6 1534.36  5017.9 1534.86  5036.5 1540.01  5081.9 1544.11
  5128.4 1548.26  5171.1 1548.50  5225.1 1555.54  5320.3 1561.55  5392.1 1569.15
  5419.8 1569.86  5537.0 1579.70  5577.1 1581.42  5597.9 1585.39  5663.8 1591.59
#Mann=10,-1,0
  3937.8    0.05       0  3987.1     0.1       0  4085.7    0.05       0
  4145.1     0.1       0  4695.5    0.05       0  5011.9   0.035       0
  5017.9    0.05       0  5081.9    0.16       0  5225.1     0.1       0
  5537.0    0.05       0
Bank Sta=5011.9,5017.9
Exp/Cntr=0.3,0.1

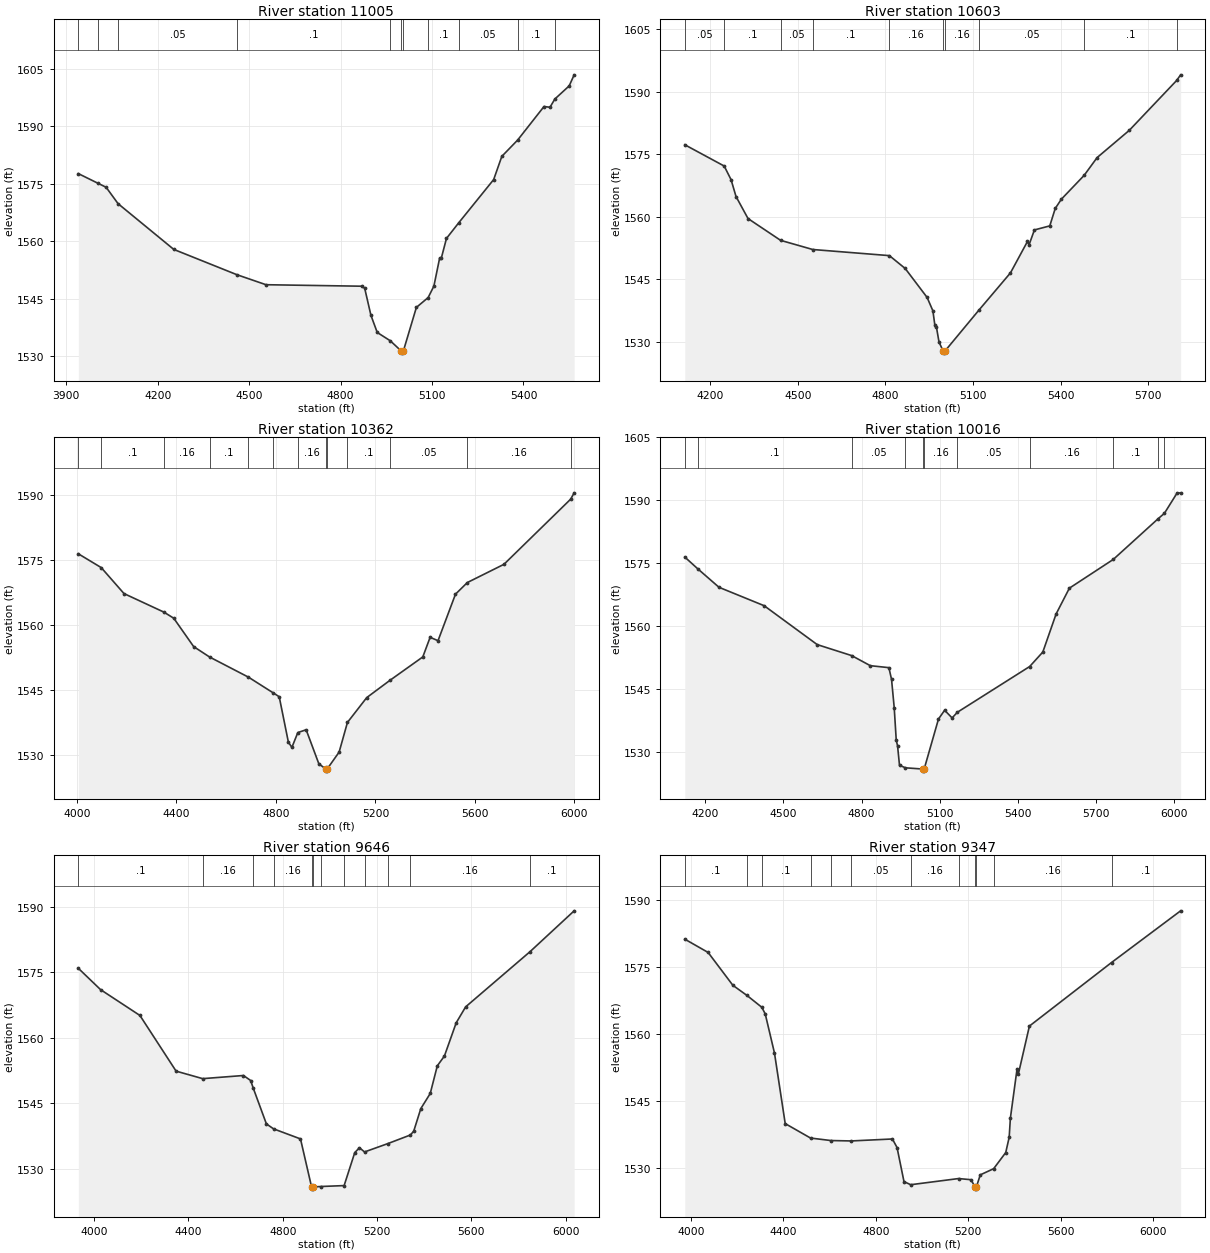
Type RM Length L Ch R = 1,11005,402,402,402
BEGIN DESCRIPTION:
WEST FORK WILLIAMS CREEK 24.0
END DESCRIPTION:
XS GIS Cut Line= 3
      2837568.05     10030359.89      2838461.29     10030477.18
      2839164.24     10030657.42
#Sta/Elev= 30
  3939.7 1577.67  4005.3 1575.10  4030.9 1574.10  4070.0 1569.82  4252.8 1557.86
  4459.8 1551.25  4555.4 1548.63  4868.7 1548.24  4879.0 1547.75  4899.6 1540.63
  4920.3 1536.15  4963.2 1533.97  4999.8 1531.25  5002.6 1530.75  5005.8 1531.25
  5048.7 1542.70  5087.3 1545.27  5106.1 1548.26  5125.1 1555.62  5130.3 1555.51
  5147.4 1560.73  5188.0 1564.85  5302.3 1576.12  5329.0 1582.18  5380.9 1586.44
  5467.4 1595.21  5487.0 1595.01  5502.9 1597.16  5550.0 1600.60  5566.3 1603.49
#Mann=11,-1,0
  3939.7    0.05       0  4005.3     0.1       0  4070.0    0.05       0
  4459.8     0.1       0  4963.2    0.05       0  4999.8   0.035       0
  5005.8    0.05       0  5087.3     0.1       0  5188.0    0.05       0
  5380.9     0.1       0  5502.9    0.05       0
Bank Sta=4999.8,5005.8
Exp/Cntr=0.3,0.1

Type RM Length L Ch R = 1,10603,241,241,241
BEGIN DESCRIPTION:
WEST FORK WILLIAMS CREEK 23.0
END DESCRIPTION:
XS GIS Cut Line= 3
      2837531.99     10030549.36      2838759.02     10030955.36
      2839164.27     10030955.36
#Sta/Elev= 30
  4112.9 1577.30  4247.8 1572.19  4271.3 1568.92  4288.3 1564.87  4329.4 1559.58
  4440.9 1554.35  4551.0 1552.15  4813.4 1550.68  4867.6 1547.59  4942.6 1540.64
  4962.4 1537.42  4969.0 1534.04  4974.3 1533.60  4983.4 1529.90  4997.7 1527.77
  5000.5 1527.27  5003.7 1527.77  5120.7 1537.66  5228.0 1546.54  5286.2 1554.08
  5291.5 1553.25  5310.0 1556.85  5362.6 1557.82  5381.3 1562.01  5402.4 1564.24
  5480.0 1569.93  5524.8 1574.23  5634.8 1580.76  5796.9 1592.73  5810.6 1594.09
#Mann=10,-1,0
  4112.9    0.05       0  4247.8     0.1       0  4440.9    0.05       0
  4551.0     0.1       0  4813.4    0.16       0  4997.7    0.07       0
  5003.7    0.16       0  5120.7    0.05       0  5480.0     0.1       0
  5796.9    0.05       0
Bank Sta=4997.7,5003.7
Exp/Cntr=0.3,0.1

Type RM Length L Ch R = 1,10362,346,346,346
BEGIN DESCRIPTION:
WEST FORK WILLIAMS CREEK 22.0
END DESCRIPTION:
XS GIS Cut Line= 3
      2837304.83     10031022.74      2838096.50     10031015.80
      2839275.25     10031251.55
#Sta/Elev= 30
  4005.3 1576.52  4097.4 1573.33  4188.9 1567.33  4349.5 1563.04  4389.0 1561.63
  4469.0 1555.08  4532.8 1552.68  4689.5 1548.01  4788.2 1544.41  4813.1 1543.49
  4850.0 1532.98  4864.1 1531.79  4887.9 1535.21  4921.4 1535.86  4972.4 1528.00
  5000.0 1526.80  5002.7 1526.30  5006.0 1526.80  5054.0 1530.70  5087.4 1537.55
  5165.0 1543.29  5259.3 1547.32  5390.5 1552.69  5419.9 1557.22  5451.7 1556.44
  5521.9 1567.19  5569.6 1569.88  5716.8 1574.09  5985.1 1589.15  5999.1 1590.61
#Mann=13,-1,0
  4005.3    0.05       0  4097.4     0.1       0  4349.5    0.16       0
  4532.8     0.1       0  4689.5    0.05       0  4788.2     0.1       0
  4887.9    0.16       0  5000.0    0.07       0  5006.0    0.16       0
  5087.4     0.1       0  5259.3    0.05       0  5569.6    0.16       0
  5985.1    0.05       0
Bank Sta=5000,5006
Exp/Cntr=0.3,0.1

Type RM Length L Ch R = 1,10016,370,370,370
BEGIN DESCRIPTION:
WEST FORK WILLIAMS CREEK 21.0
END DESCRIPTION:
XS GIS Cut Line= 2
      2837339.56     10031217.19      2839207.59     10031571.35
#Sta/Elev= 30
  4122.3 1576.46  4171.7 1573.67  4253.5 1569.24  4426.5 1564.85  4630.1 1555.56
  4762.1 1552.94  4833.7 1550.53  4904.9 1550.06  4915.1 1547.26  4925.3 1540.53
  4933.1 1532.77  4938.2 1531.38  4945.6 1526.76  4968.5 1526.15  5034.2 1525.86
  5037.0 1525.36  5040.2 1525.86  5095.1 1537.80  5118.6 1539.89  5147.3 1538.06
  5167.7 1539.42  5444.8 1550.33  5495.2 1553.79  5546.1 1562.87  5597.0 1569.03
  5765.3 1575.89  5937.2 1585.60  5961.3 1586.89  6009.4 1591.68  6023.6 1591.79
#Mann=11,-1,0
  4122.3    0.05       0  4171.7     0.1       0  4762.1    0.05       0
  4968.5    0.16       0  5034.2    0.07       0  5040.2    0.16       0
  5167.7    0.05       0  5444.8    0.16       0  5765.3     0.1       0
  5937.2    0.16       0  5961.3     0.1       0
Bank Sta=5034.2,5040.2
Exp/Cntr=0.3,0.1

Type RM Length L Ch R = 1,9646,299,299,299
BEGIN DESCRIPTION:
WEST FORK WILLIAMS CREEK 20.0
END DESCRIPTION:
XS GIS Cut Line= 3
      2837179.80     10031439.40      2838027.05     10031744.96
      2839228.48     10031779.69
#Sta/Elev= 30
  3933.3 1575.90  4027.6 1571.01  4194.5 1565.09  4347.9 1552.33  4460.6 1550.61
  4633.5 1551.33  4664.1 1550.18  4674.9 1548.46  4730.8 1540.24  4761.3 1539.10
  4875.4 1536.80  4922.4 1525.79  4925.2 1525.29  4928.4 1525.79  4961.8 1525.89
  5060.4 1526.10  5105.5 1533.66  5125.5 1534.78  5146.9 1533.81  5246.1 1535.73
  5341.6 1537.70  5355.6 1538.58  5385.6 1543.74  5425.6 1547.21  5455.6 1553.55
  5485.7 1555.79  5535.7 1563.41  5575.7 1567.06  5849.0 1579.72  6035.9 1589.07
#Mann=12,-1,0
  3933.3     0.1       0  4460.6    0.16       0  4674.9    0.05       0
  4761.3    0.16       0  4922.4    0.07       0  4928.4    0.16       0
  4961.8     0.1       0  5060.4    0.16       0  5146.9     0.1       0
  5246.1    0.05       0  5341.6    0.16       0  5849.0     0.1       0
Bank Sta=4922.4,4928.4
Exp/Cntr=0.3,0.1

Type RM Length L Ch R = 1,9347,73,73,73
BEGIN DESCRIPTION:
WEST FORK WILLIAMS CREEK 19.1
END DESCRIPTION:
XS GIS Cut Line= 3
      2837200.62     10032015.79      2838603.44     10032057.46
      2839324.56     10031884.12
#Sta/Elev= 30
  3973.5 1581.26  4074.4 1578.28  4181.4 1570.92  4242.3 1568.65  4306.7 1565.99
  4321.5 1564.50  4361.5 1555.73  4407.9 1539.92  4517.4 1536.68  4605.5 1536.12
  4693.7 1536.03  4871.7 1536.47  4891.7 1534.56  4921.8 1526.91  4950.9 1526.22
  5158.0 1527.60  5211.9 1527.34  5228.9 1525.73  5231.6 1525.23  5234.9 1525.73
  5251.9 1528.43  5309.7 1529.81  5362.0 1533.43  5376.9 1536.85  5382.1 1541.15
  5411.1 1552.22  5416.2 1550.93  5464.4 1561.78  5819.6 1576.02  6118.6 1587.61
#Mann=12,-1,0
  3973.5     0.1       0  4242.3    0.16       0  4306.7     0.1       0
  4517.4    0.05       0  4605.5     0.1       0  4693.7    0.05       0
  4950.9    0.16       0  5158.0     0.1       0  5228.9    0.07       0
  5234.9     0.1       0  5309.7    0.16       0  5819.6     0.1       0
Bank Sta=5228.9,5234.9
Exp/Cntr=0.3,0.1

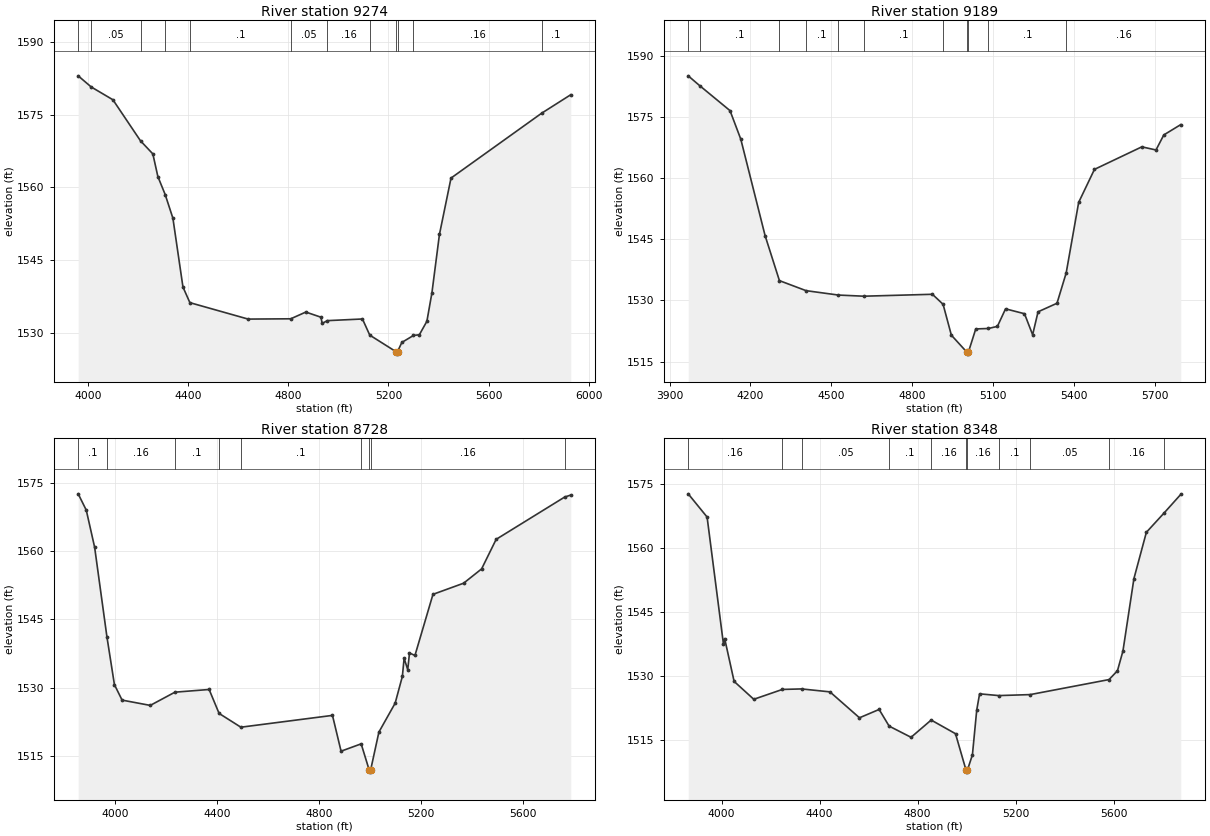
Type RM Length L Ch R = 1,9274,85,85,85
BEGIN DESCRIPTION:
WEST FORK WILLIAMS CREEK 19.0
END DESCRIPTION:
XS GIS Cut Line= 5
      2837200.67     10032080.90      2838134.24     10032135.32
      2838331.73     10032101.68      2838685.46     10032075.64
      2839144.72     10031945.57
#Sta/Elev= 30
  3960.6 1583.03  4012.5 1580.74  4099.4 1578.09  4209.7 1569.61  4258.9 1566.92
  4278.9 1562.25  4308.2 1558.53  4339.0 1553.65  4379.1 1539.46  4406.8 1536.23
  4639.5 1532.84  4809.7 1532.90  4869.9 1534.29  4930.2 1533.23  4935.3 1531.96
  4956.1 1532.52  5096.1 1532.86  5125.3 1529.53  5230.2 1526.11  5232.9 1525.61
  5236.2 1526.11  5253.3 1528.02  5299.8 1529.46  5323.4 1529.61  5353.5 1532.39
  5373.6 1538.27  5403.6 1550.30  5449.8 1561.93  5811.9 1575.32  5928.1 1579.13
#Mann=12,-1,0
  3960.6     0.1       0  4012.5    0.05       0  4209.7     0.1       0
  4308.2    0.16       0  4406.8     0.1       0  4809.7    0.05       0
  4956.1    0.16       0  5125.3     0.1       0  5230.2    0.07       0
  5236.2     0.1       0  5299.8    0.16       0  5811.9     0.1       0
Bank Sta=5230.2,5236.2
Exp/Cntr=0.3,0.1

Type RM Length L Ch R = 1,9189,461,461,461
BEGIN DESCRIPTION:
WEST FORK WILLIAMS CREEK 18.1
END DESCRIPTION:
XS GIS Cut Line= 4
      2837203.30     10032249.90      2837932.42     10032231.67
      2838693.18     10032155.12      2839000.13     10032023.34
#Sta/Elev= 30
  3969.4 1585.09  4011.5 1582.71  4124.6 1576.55  4164.6 1569.54  4254.7 1545.90
  4307.9 1534.85  4406.7 1532.39  4526.7 1531.31  4621.1 1531.03  4875.7 1531.50
  4915.3 1529.04  4946.0 1521.47  5003.3 1517.32  5006.1 1516.82  5009.3 1517.32
  5036.5 1523.00  5083.6 1523.11  5116.9 1523.63  5147.1 1527.93  5217.4 1526.73
  5247.6 1521.57  5267.7 1527.20  5338.0 1529.30  5372.1 1536.73  5418.4 1554.04
  5477.0 1562.14  5652.8 1567.67  5705.4 1566.90  5734.4 1570.59  5797.4 1573.13
#Mann=11,-1,0
  3969.4    0.05       0  4011.5     0.1       0  4307.9    0.16       0
  4406.7     0.1       0  4526.7    0.05       0  4621.1     0.1       0
  4915.3    0.16       0  5003.3    0.07       0  5009.3    0.16       0
  5083.6     0.1       0  5372.1    0.16       0
Bank Sta=5003.3,5009.3
Exp/Cntr=0.3,0.1

Type RM Length L Ch R = 1,8728,380,380,380
BEGIN DESCRIPTION:
WEST FORK WILLIAMS CREEK 18.0
END DESCRIPTION:
XS GIS Cut Line= 4
      2837346.85     10032532.73      2838367.65     10032631.69
      2838763.49     10032220.23      2839049.93     10032043.15
#Sta/Elev= 30
  3854.5 1572.55  3886.3 1568.97  3919.1 1560.84  3967.4 1541.18  3996.8 1530.71
  4026.9 1527.32  4137.4 1526.16  4234.3 1529.06  4368.5 1529.65  4407.6 1524.40
  4493.1 1521.38  4852.6 1523.97  4886.3 1516.12  4965.2 1517.73  4996.5 1512.03
  4999.3 1511.53  5002.5 1512.03  5034.8 1520.31  5098.6 1526.65  5126.9 1532.52
  5133.8 1536.51  5148.0 1533.98  5154.9 1537.65  5176.3 1537.11  5247.0 1550.51
  5367.2 1552.95  5437.9 1556.09  5495.0 1562.57  5763.8 1571.84  5787.8 1572.28
#Mann=9,-1,0
  3854.5     0.1       0  3967.4    0.16       0  4234.3     0.1       0
  4407.6    0.05       0  4493.1     0.1       0  4965.2    0.16       0
  4996.5    0.07       0  5002.5    0.16       0  5763.8     0.1       0
Bank Sta=4996.5,5002.5
Exp/Cntr=0.3,0.1

Type RM Length L Ch R = 1,8348,694,694,694
BEGIN DESCRIPTION:
WEST FORK WILLIAMS CREEK 17.0
END DESCRIPTION:
XS GIS Cut Line= 4
      2837351.57     10032777.87      2838434.22     10032859.07
      2838557.53     10032914.62      2839264.25     10032563.43
#Sta/Elev= 30
  3863.6 1572.76  3940.7 1567.32  4007.4 1537.58  4012.4 1538.85  4051.0 1528.82
  4131.2 1524.63  4247.8 1526.94  4326.4 1527.06  4442.1 1526.37  4562.5 1520.30
  4642.7 1522.25  4683.5 1518.35  4773.0 1515.73  4855.1 1519.77  4954.4 1516.57
  4997.2 1508.07  5000.0 1507.57  5003.2 1508.07  5023.4 1511.62  5041.0 1522.11
  5052.7 1525.91  5130.6 1525.50  5259.1 1525.73  5580.9 1529.25  5615.3 1531.32
  5637.7 1535.95  5682.5 1552.91  5733.2 1563.74  5806.0 1568.30  5873.7 1572.63
#Mann=11,-1,0
  3863.6    0.16       0  4247.8     0.1       0  4326.4    0.05       0
  4683.5     0.1       0  4855.1    0.16       0  4997.2    0.07       0
  5003.2    0.16       0  5130.6     0.1       0  5259.1    0.05       0
  5580.9    0.16       0  5806.0     0.1       0
Bank Sta=4997.2,5003.2
Exp/Cntr=0.3,0.1