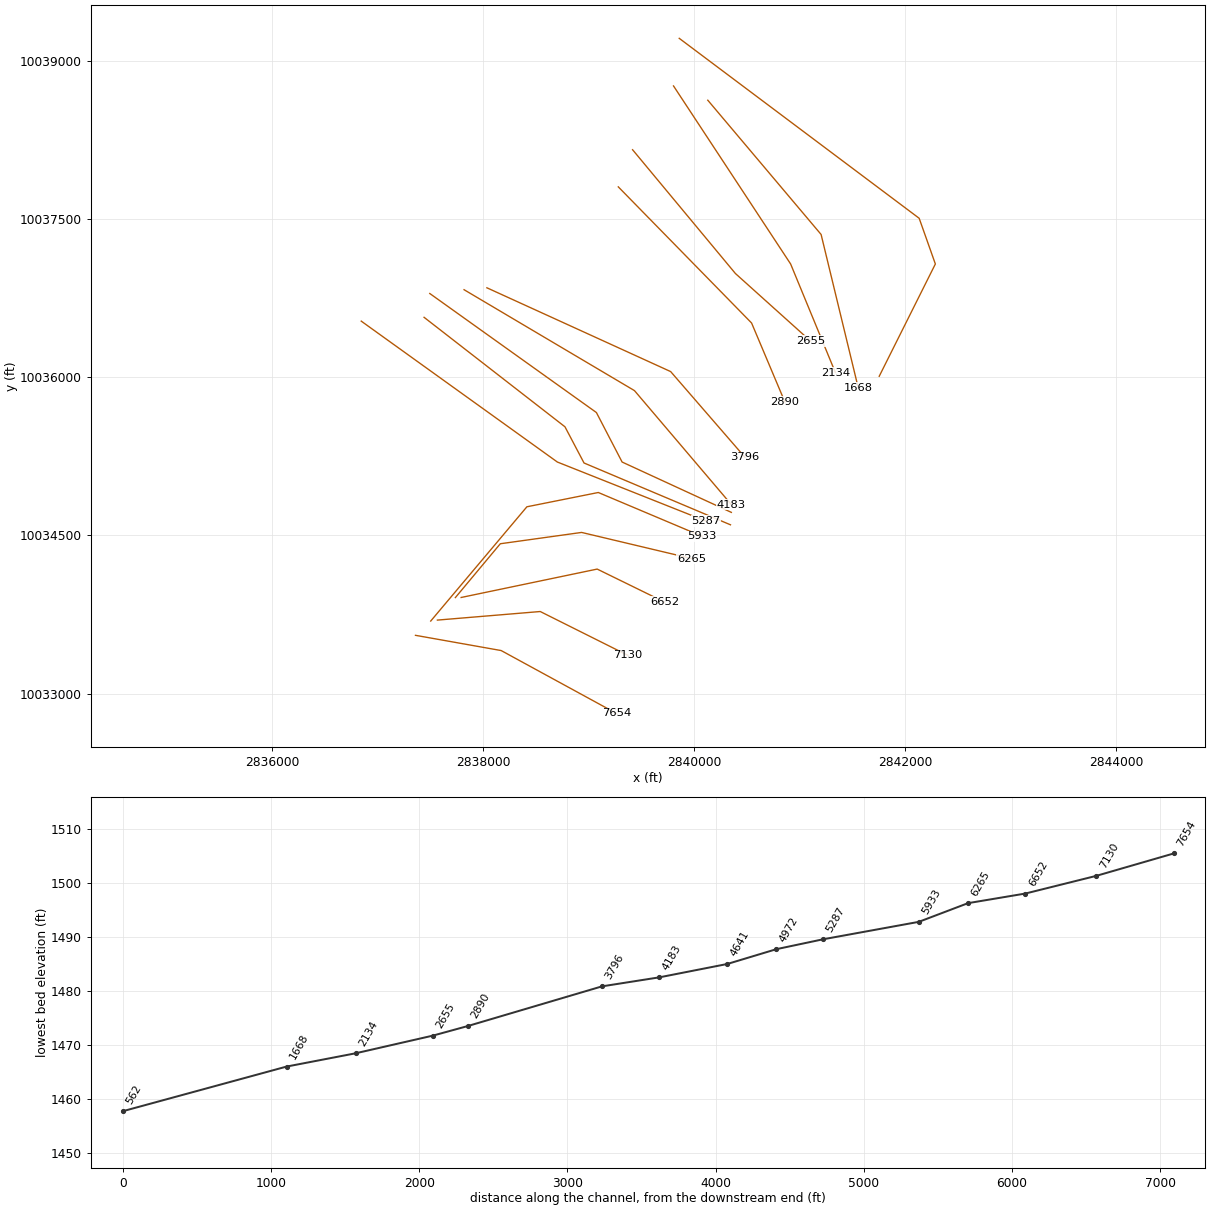
HEC-RAS study WEST FORK WILLIAMS CREEK.prj: WEST FORK WILLIAMS CREEK Base Level Engineering

--- WEST FORK WILLIAMS CREEK.g01 (geometry) --- (continued)

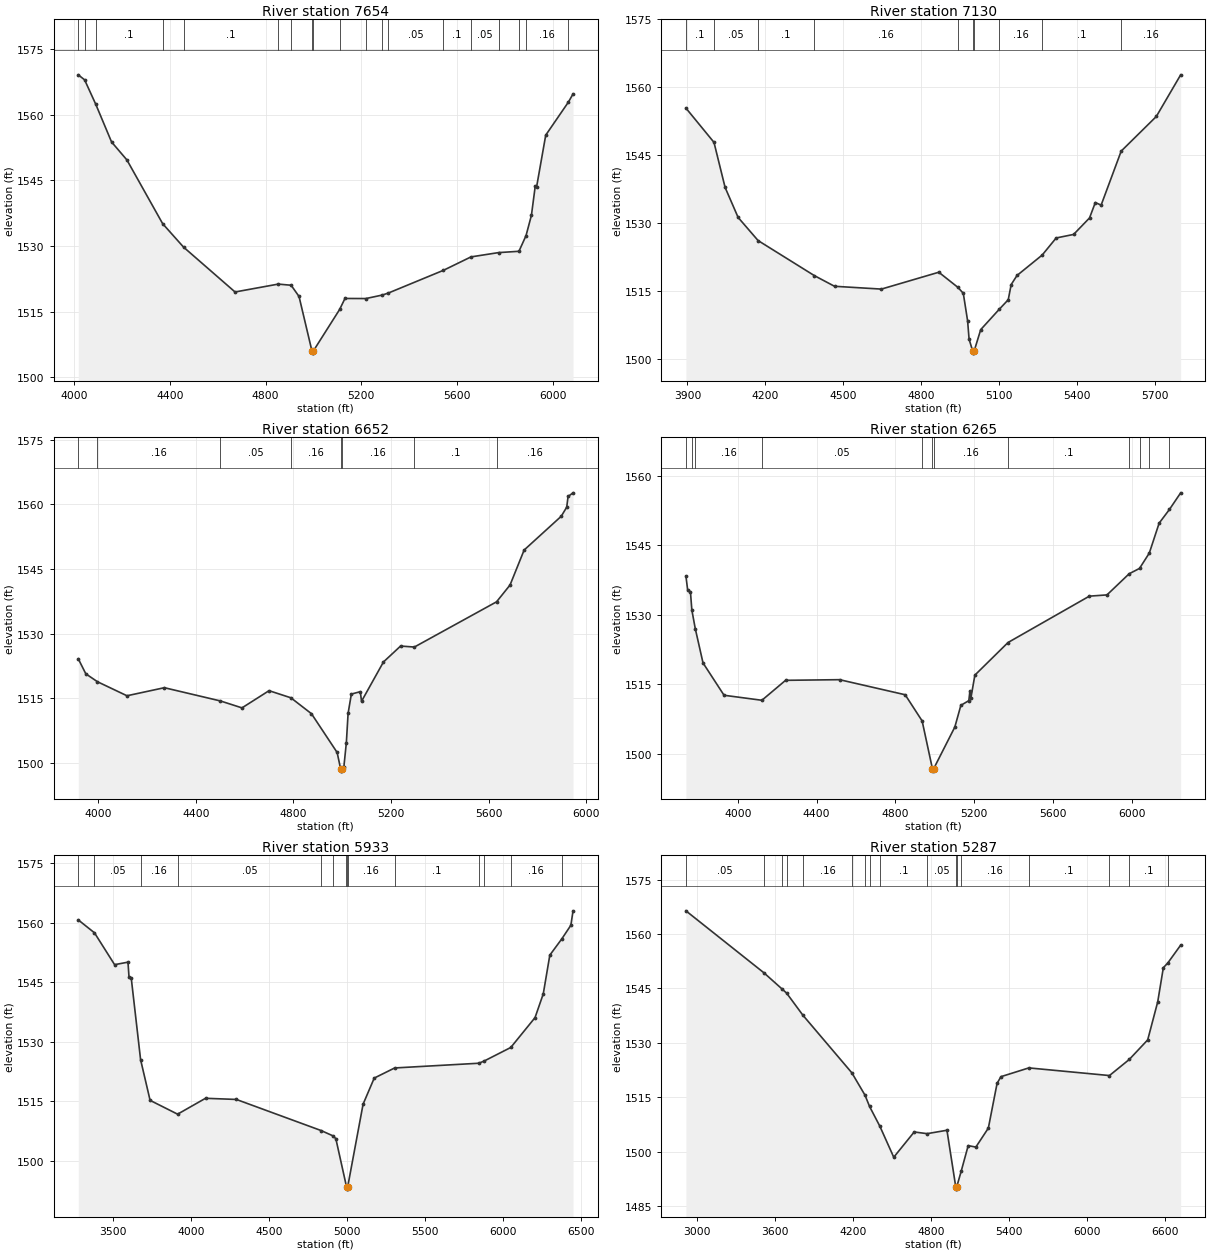
Type RM Length L Ch R = 1,7654,524,524,524
BEGIN DESCRIPTION:
WEST FORK WILLIAMS CREEK 16.0
END DESCRIPTION:
XS GIS Cut Line= 3
      2837360.55     10033553.79      2838172.57     10033409.43
      2839263.84     10032814.19
#Sta/Elev= 30
  4016.9 1569.07  4043.4 1567.92  4090.1 1562.33  4156.0 1553.74  4220.1 1549.64
  4369.6 1535.08  4456.9 1529.73  4672.1 1519.49  4852.6 1521.29  4906.4 1521.03
  4939.5 1518.47  4993.4 1506.03  4996.2 1505.53  4999.4 1506.03  5109.2 1515.50
  5131.5 1518.01  5218.8 1517.99  5287.3 1518.79  5312.9 1519.25  5543.1 1524.44
  5658.2 1527.50  5773.2 1528.48  5858.6 1528.78  5888.3 1532.37  5910.8 1537.00
  5926.9 1543.73  5932.6 1543.55  5970.6 1555.30  6065.6 1562.87  6084.7 1564.71
#Mann=19,-1,0
  4016.9     0.1       0  4043.4    0.16       0  4090.1     0.1       0
  4369.6    0.05       0  4456.9     0.1       0  4852.6    0.05       0
  4906.4     0.1       0  4993.4    0.07       0  4999.4     0.1       0
  5109.2    0.16       0  5218.8    0.05       0  5287.3     0.1       0
  5312.9    0.05       0  5543.1     0.1       0  5658.2    0.05       0
  5773.2    0.16       0  5858.6    0.05       0  5888.3    0.16       0
  6065.6     0.1       0
Bank Sta=4993.4,4999.4
Exp/Cntr=0.3,0.1

Type RM Length L Ch R = 1,7130,478,478,478
BEGIN DESCRIPTION:
WEST FORK WILLIAMS CREEK 15.0
END DESCRIPTION:
XS GIS Cut Line= 3
      2837568.07     10033698.14      2838542.49     10033779.34
      2839372.52     10033364.33
#Sta/Elev= 30
  3893.9 1555.44  4002.0 1547.88  4044.8 1537.94  4095.0 1531.31  4171.9 1526.21
  4388.5 1518.48  4466.3 1516.12  4646.9 1515.50  4868.0 1519.22  4941.9 1515.87
  4962.4 1514.56  4979.0 1508.48  4984.7 1504.43  4998.4 1501.87  5001.1 1501.37
  5004.4 1501.87  5029.5 1506.56  5101.2 1511.07  5135.5 1513.15  5146.8 1516.50
  5169.2 1518.50  5266.2 1523.01  5320.1 1526.78  5387.2 1527.56  5448.6 1531.20
  5470.9 1534.60  5493.3 1534.03  5570.6 1545.95  5705.9 1553.59  5799.7 1562.78
#Mann=10,-1,0
  3893.9     0.1       0  4002.0    0.05       0  4171.9     0.1       0
  4388.5    0.16       0  4941.9     0.1       0  4998.4    0.07       0
  5004.4     0.1       0  5101.2    0.16       0  5266.2     0.1       0
  5570.6    0.16       0
Bank Sta=4998.4,5004.4
Exp/Cntr=0.3,0.1

Type RM Length L Ch R = 1,6652,387,387,387
BEGIN DESCRIPTION:
WEST FORK WILLIAMS CREEK 14.0
END DESCRIPTION:
XS GIS Cut Line= 3
      2837793.22     10033912.43      2839082.24     10034181.51
      2839720.22     10033869.03
#Sta/Elev= 30
  3918.3 1524.15  3949.2 1520.67  3997.0 1518.83  4117.8 1515.58  4271.0 1517.45
  4500.5 1514.38  4589.1 1512.77  4700.0 1516.76  4789.4 1515.11  4873.7 1511.42
  4978.9 1502.43  4993.3 1498.60  4996.0 1498.10  4999.3 1498.60  5006.5 1499.08
  5016.7 1504.71  5023.8 1511.48  5037.2 1515.97  5073.8 1516.53  5078.9 1514.30
  5168.7 1523.42  5238.9 1527.11  5295.4 1526.88  5632.1 1537.37  5687.4 1541.27
  5745.1 1549.38  5897.1 1557.21  5919.6 1559.32  5925.1 1561.80  5945.5 1562.65
#Mann=8,-1,0
  3918.3     0.1       0  3997.0    0.16       0  4500.5    0.05       0
  4789.4    0.16       0  4993.3    0.07       0  4999.3    0.16       0
  5295.4     0.1       0  5632.1    0.16       0
Bank Sta=4993.3,4999.3
Exp/Cntr=0.3,0.1

Type RM Length L Ch R = 1,6265,332,332,332
BEGIN DESCRIPTION:
WEST FORK WILLIAMS CREEK 13.0
END DESCRIPTION:
XS GIS Cut Line= 4
      2837738.41     10033911.37      2838164.30     10034421.56
      2838934.67     10034528.74      2839974.86     10034281.69
#Sta/Elev= 30
  3736.6 1538.38  3745.3 1535.42  3759.7 1534.92  3766.7 1531.04  3784.0 1527.05
  3823.4 1519.64  3930.2 1512.67  4122.3 1511.59  4242.5 1515.89  4516.5 1516.03
  4849.6 1512.78  4935.7 1507.14  4988.0 1496.82  4990.7 1496.32  4994.0 1496.82
  5101.7 1505.82  5132.3 1510.50  5172.7 1511.51  5178.4 1513.62  5183.5 1512.14
  5203.4 1517.01  5371.7 1524.04  5784.5 1534.03  5874.0 1534.30  5986.4 1538.85
  6039.2 1540.01  6088.9 1543.32  6138.7 1549.76  6191.3 1552.73  6248.1 1556.30
#Mann=12,-1,0
  3736.6    0.05       0  3766.7     0.1       0  3784.0    0.16       0
  4122.3    0.05       0  4935.7    0.16       0  4988.0    0.07       0
  4994.0    0.16       0  5371.7     0.1       0  5986.4    0.16       0
  6039.2     0.1       0  6088.9    0.16       0  6191.3    0.05       0
Bank Sta=4988,4994
Exp/Cntr=0.3,0.1

Type RM Length L Ch R = 1,5933,646,646,646
BEGIN DESCRIPTION:
WEST FORK WILLIAMS CREEK 12.0
END DESCRIPTION:
XS GIS Cut Line= 4
      2837504.90     10033689.09      2838416.17     10034771.80
      2839092.85     10034907.13      2840074.85     10034492.71
#Sta/Elev= 30
  3276.6 1560.67  3380.4 1557.42  3509.4 1549.40  3595.2 1550.03  3601.7 1546.29
  3616.0 1546.04  3676.0 1525.47  3736.9 1515.22  3913.2 1511.74  4092.0 1515.74
  4289.7 1515.45  4833.3 1507.61  4906.1 1506.33  4927.3 1505.59  4994.6 1493.67
  4997.0 1493.36  4999.8 1492.86  5003.0 1493.36  5102.0 1514.25  5173.4 1520.83
  5304.3 1523.38  5844.1 1524.57  5878.7 1525.14  6048.6 1528.54  6204.1 1536.06
  6256.9 1542.05  6298.9 1551.80  6375.8 1555.90  6433.8 1559.33  6447.7 1562.96
#Mann=14,-1,0
  3276.6     0.1       0  3380.4    0.05       0  3676.0    0.16       0
  3913.2    0.05       0  4833.3    0.16       0  4906.1    0.05       0
  4994.6    0.16       0  4997.0    0.07       0  5003.0    0.16       0
  5304.3     0.1       0  5844.1    0.16       0  5878.7     0.1       0
  6048.6    0.16       0  6375.8    0.05       0
Bank Sta=4997,5003
Exp/Cntr=0.3,0.1

Type RM Length L Ch R = 1,5287,315,315,315
BEGIN DESCRIPTION:
WEST FORK WILLIAMS CREEK 11.0
END DESCRIPTION:
XS GIS Cut Line= 3
      2836846.30     10036531.14      2838704.89     10035195.85
      2840112.38     10034636.46
#Sta/Elev= 30
  2917.8 1566.40  3517.6 1549.30  3658.0 1544.80  3691.9 1543.70  3817.1 1537.60
  4193.3 1521.71  4294.4 1515.55  4329.5 1512.43  4408.8 1506.96  4515.4 1498.43
  4672.6 1505.40  4771.6 1504.93  4924.3 1505.87  4992.5 1490.13  4995.2 1489.63
  4998.5 1490.13  5033.4 1494.52  5087.6 1501.63  5146.5 1501.23  5242.5 1506.46
  5309.6 1518.80  5339.3 1520.65  5553.8 1523.07  6173.4 1520.96  6325.5 1525.39
  6467.4 1530.80  6544.5 1541.30  6587.6 1550.71  6622.1 1552.02  6720.9 1556.94
#Mann=17,-1,0
  2917.8    0.05       0  3517.6     0.1       0  3658.0    0.05       0
  3691.9     0.1       0  3817.1    0.16       0  4193.3    0.05       0
  4294.4     0.1       0  4329.5    0.05       0  4408.8     0.1       0
  4771.6    0.05       0  4992.5   0.035       0  4998.5    0.05       0
  5033.4    0.16       0  5553.8     0.1       0  6173.4    0.16       0
  6325.5     0.1       0  6622.1    0.05       0
Bank Sta=4992.5,4998.5
Exp/Cntr=0.3,0.1

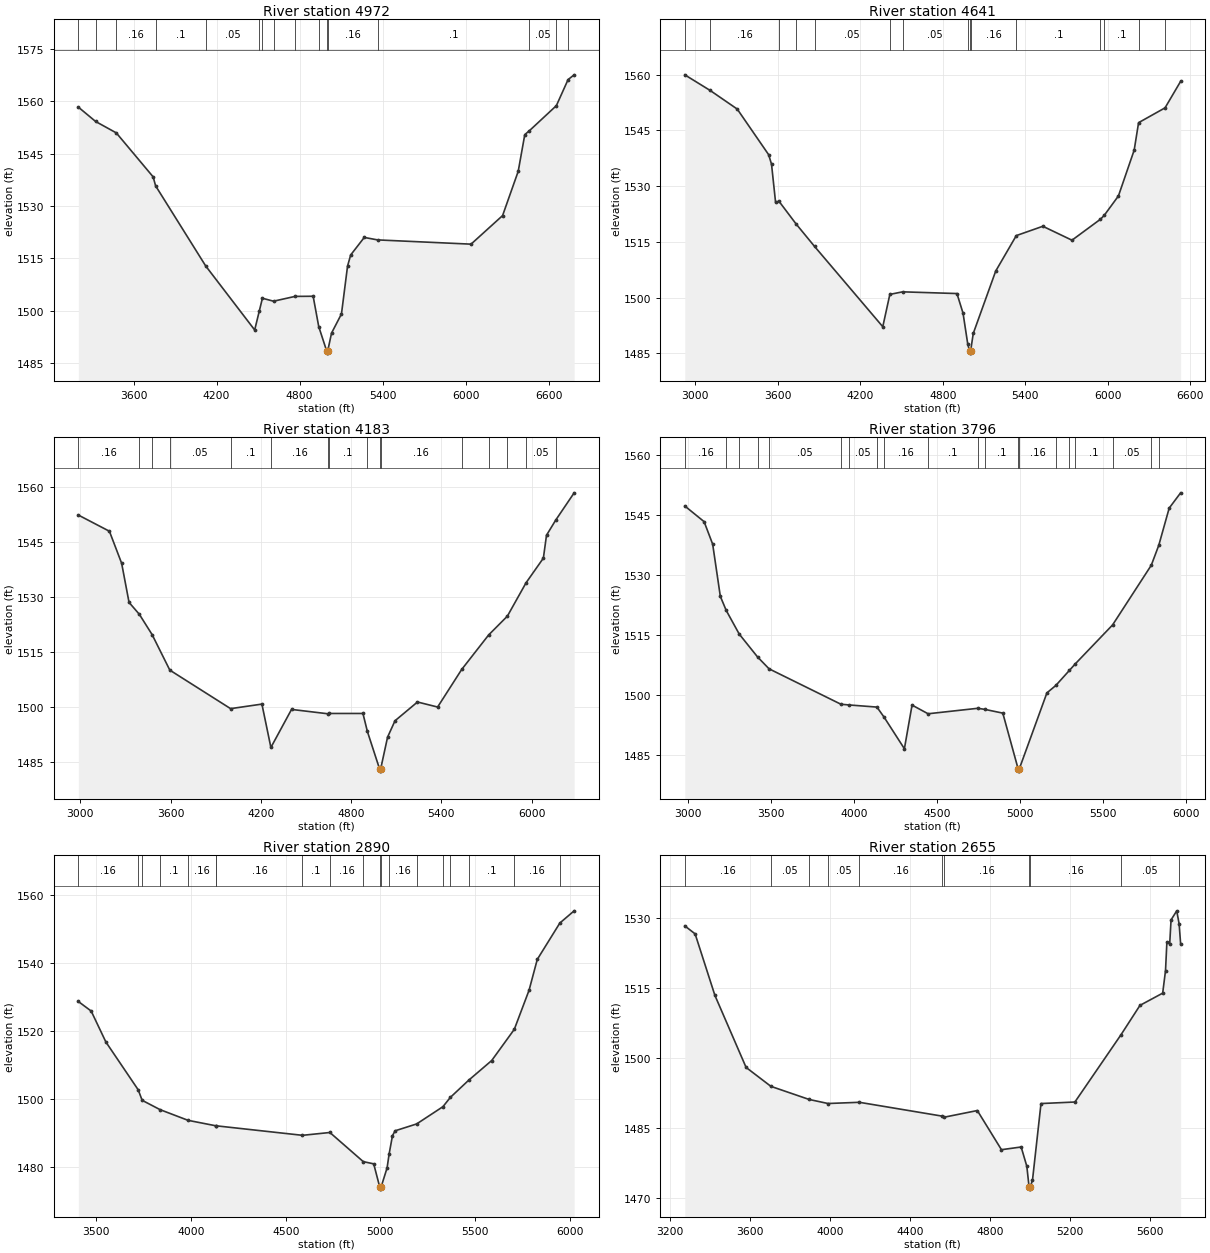
Type RM Length L Ch R = 1,4972,331,331,331
BEGIN DESCRIPTION:
WEST FORK WILLIAMS CREEK 10.0
END DESCRIPTION:
XS GIS Cut Line= 4
      2837441.80     10036567.21      2838777.07     10035529.67
      2838957.51     10035186.83      2840345.25     10034601.09
#Sta/Elev= 30
  3200.2 1558.35  3325.2 1554.23  3474.7 1550.96  3741.2 1538.34  3758.9 1535.77
  4121.0 1512.80  4475.2 1494.44  4508.8 1499.92  4531.1 1503.54  4611.4 1502.69
  4767.4 1504.07  4897.9 1504.11  4938.2 1495.42  4996.6 1488.30  4999.4 1487.80
  5002.6 1488.30  5030.8 1493.54  5102.6 1499.04  5146.6 1512.76  5169.1 1515.94
  5267.5 1520.98  5363.6 1520.27  6039.4 1519.05  6267.4 1527.24  6380.4 1539.93
  6427.9 1550.46  6459.0 1551.50  6656.3 1558.77  6741.0 1566.25  6784.9 1567.61
#Mann=16,-1,0
  3200.2     0.1       0  3325.2    0.05       0  3474.7    0.16       0
  3758.9     0.1       0  4121.0    0.05       0  4508.8     0.1       0
  4531.1    0.16       0  4611.4     0.1       0  4767.4    0.05       0
  4938.2    0.16       0  4996.6    0.07       0  5002.6    0.16       0
  5363.6     0.1       0  6459.0    0.05       0  6656.3     0.1       0
  6741.0    0.16       0
Bank Sta=4996.6,5002.6
Exp/Cntr=0.3,0.1

Type RM Length L Ch R = 1,4641,458,458,458
BEGIN DESCRIPTION:
WEST FORK WILLIAMS CREEK 9.0
END DESCRIPTION:
XS GIS Cut Line= 4
      2837495.90     10036792.79      2839074.80     10035665.01
      2839318.41     10035195.85      2840353.61     10034718.76
#Sta/Elev= 30
  2922.9 1559.98  3107.6 1555.77  3304.6 1550.76  3533.2 1538.48  3554.1 1535.93
  3583.6 1525.66  3608.0 1525.96  3733.0 1519.83  3867.4 1513.78  4363.9 1492.17
  4415.3 1500.87  4508.3 1501.56  4903.7 1501.10  4948.1 1495.81  4982.8 1487.39
  4996.9 1485.56  4999.6 1485.06  5002.9 1485.56  5022.4 1490.35  5185.8 1507.15
  5335.7 1516.70  5528.9 1519.21  5741.0 1515.46  5948.4 1521.11  5975.3 1522.13
  6079.0 1527.37  6193.7 1539.71  6225.7 1547.10  6418.3 1551.09  6531.7 1558.22
#Mann=15,-1,0
  2922.9    0.05       0  3107.6    0.16       0  3608.0    0.05       0
  3733.0     0.1       0  3867.4    0.05       0  4415.3    0.16       0
  4508.3    0.05       0  4982.8    0.16       0  4996.9    0.07       0
  5002.9    0.16       0  5335.7     0.1       0  5948.4    0.05       0
  5975.3     0.1       0  6225.7    0.05       0  6418.3     0.1       0
Bank Sta=4996.9,5002.9
Exp/Cntr=0.3,0.1

Type RM Length L Ch R = 1,4183,387,387,387
BEGIN DESCRIPTION:
WEST FORK WILLIAMS CREEK 8.0
END DESCRIPTION:
XS GIS Cut Line= 3
      2837820.74     10036828.87      2839435.70     10035872.52
      2840354.72     10034791.32
#Sta/Elev= 30
  2987.0 1552.31  3193.6 1547.90  3274.9 1539.18  3324.1 1528.53  3392.8 1525.27
  3477.4 1519.76  3595.1 1510.09  3999.2 1499.60  4207.3 1500.84  4267.0 1489.03
  4404.2 1499.39  4649.1 1498.19  4654.0 1498.29  4878.9 1498.29  4908.4 1493.39
  4990.2 1483.09  4992.9 1482.59  4996.2 1483.09  5042.6 1491.84  5092.0 1496.30
  5241.4 1501.41  5375.3 1500.04  5535.3 1510.27  5714.4 1519.66  5838.9 1524.78
  5963.5 1533.89  6078.3 1540.58  6099.1 1546.81  6160.1 1550.92  6282.9 1558.36
#Mann=16,-1,0
  2987.0    0.16       0  3392.8     0.1       0  3477.4    0.16       0
  3595.1    0.05       0  3999.2     0.1       0  4267.0    0.16       0
  4649.1    0.05       0  4654.0     0.1       0  4908.4    0.16       0
  4990.2    0.07       0  4996.2    0.16       0  5535.3     0.1       0
  5714.4    0.05       0  5838.9     0.1       0  5963.5    0.05       0
  6160.1     0.1       0
Bank Sta=4990.2,4996.2
Exp/Cntr=0.3,0.1

Type RM Length L Ch R = 1,3796,906,906,906
BEGIN DESCRIPTION:
WEST FORK WILLIAMS CREEK 7.0
END DESCRIPTION:
XS GIS Cut Line= 3
      2838037.25     10036846.92      2839778.54     10036052.97
      2840482.29     10035240.95
#Sta/Elev= 30
  2980.6 1547.21  3097.0 1543.29  3148.6 1537.66  3194.7 1524.62  3230.4 1521.08
  3308.6 1515.19  3419.2 1509.46  3488.4 1506.50  3921.8 1497.64  3972.2 1497.46
  4138.6 1496.93  4182.2 1494.38  4304.1 1486.52  4350.2 1497.43  4446.9 1495.26
  4746.4 1496.63  4788.7 1496.36  4897.2 1495.42  4990.0 1481.42  4992.8 1480.92
  4996.0 1481.42  5163.0 1500.48  5216.5 1502.33  5298.2 1506.09  5335.2 1507.79
  5558.8 1517.47  5792.0 1532.39  5837.2 1537.38  5900.0 1546.68  5968.9 1550.50
#Mann=20,-1,0
  2980.6    0.16       0  3230.4     0.1       0  3308.6    0.16       0
  3419.2     0.1       0  3488.4    0.05       0  3921.8     0.1       0
  3972.2    0.05       0  4138.6     0.1       0  4182.2    0.16       0
  4446.9     0.1       0  4746.4    0.16       0  4788.7     0.1       0
  4990.0    0.07       0  4996.0    0.16       0  5216.5     0.1       0
  5298.2    0.16       0  5335.2     0.1       0  5558.8    0.05       0
  5792.0     0.1       0  5837.2    0.16       0
Bank Sta=4990,4996
Exp/Cntr=0.3,0.1

Type RM Length L Ch R = 1,2890,235,235,235
BEGIN DESCRIPTION:
WEST FORK WILLIAMS CREEK 5.0
END DESCRIPTION:
XS GIS Cut Line= 3
      2839282.30     10037803.31      2840545.44     10036513.10
      2840861.22     10035764.25
#Sta/Elev= 30
  3405.0 1528.67  3472.8 1525.86  3550.5 1516.77  3721.2 1502.73  3742.0 1499.65
  3837.0 1496.90  3984.5 1493.77  4132.0 1492.16  4133.6 1492.16  4588.7 1489.37
  4733.4 1490.20  4909.5 1481.65  4964.8 1480.99  4997.1 1474.07  4999.8 1473.57
  5003.1 1474.07  5035.5 1479.82  5046.2 1483.89  5063.8 1489.25  5077.9 1490.70
  5191.5 1492.71  5330.4 1497.78  5369.4 1500.50  5466.3 1505.55  5587.9 1511.33
  5707.3 1520.50  5785.1 1531.96  5828.6 1541.03  5947.8 1551.71  6023.3 1555.29
#Mann=19,-1,0
  3405.0    0.16       0  3721.2     0.1       0  3742.0    0.16       0
  3837.0     0.1       0  3984.5    0.16       0  4132.0    0.05       0
  4133.6    0.16       0  4588.7     0.1       0  4733.4    0.16       0
  4909.5     0.1       0  4997.1    0.07       0  5003.1     0.1       0
  5046.2    0.16       0  5191.5    0.05       0  5330.4     0.1       0
  5369.4    0.05       0  5466.3     0.1       0  5707.3    0.16       0
  5947.8     0.1       0
Bank Sta=4997.1,5003.1
Exp/Cntr=0.3,0.1

Type RM Length L Ch R = 1,2655,521,521,521
BEGIN DESCRIPTION:
WEST FORK WILLIAMS CREEK 4.0
END DESCRIPTION:
XS GIS Cut Line= 3
      2839417.64     10038155.18      2840392.06     10036982.26
      2841104.16     10036342.28
#Sta/Elev= 30
  3272.5 1528.28  3324.2 1526.56  3423.2 1513.37  3579.4 1497.91  3703.6 1493.85
  3894.9 1491.04  3989.5 1490.17  4146.4 1490.43  4558.5 1487.48  4572.0 1487.24
  4737.0 1488.66  4857.8 1480.26  4956.4 1480.84  4984.8 1476.71  4996.0 1472.30
  4998.8 1471.80  5002.0 1472.30  5013.2 1473.73  5055.8 1490.16  5225.5 1490.49
  5456.4 1504.93  5551.4 1511.23  5665.0 1513.85  5679.2 1518.70  5686.0 1524.77
  5700.2 1524.46  5706.9 1529.56  5735.3 1531.51  5747.4 1528.69  5754.8 1524.43
#Mann=11,-1,0
  3272.5    0.16       0  3703.6    0.05       0  3894.9     0.1       0
  3989.5    0.05       0  4146.4    0.16       0  4558.5     0.1       0
  4572.0    0.16       0  4996.0    0.07       0  5002.0    0.16       0
  5456.4    0.05       0  5747.4     0.1       0
Bank Sta=4996,5002
Exp/Cntr=0.3,0.1

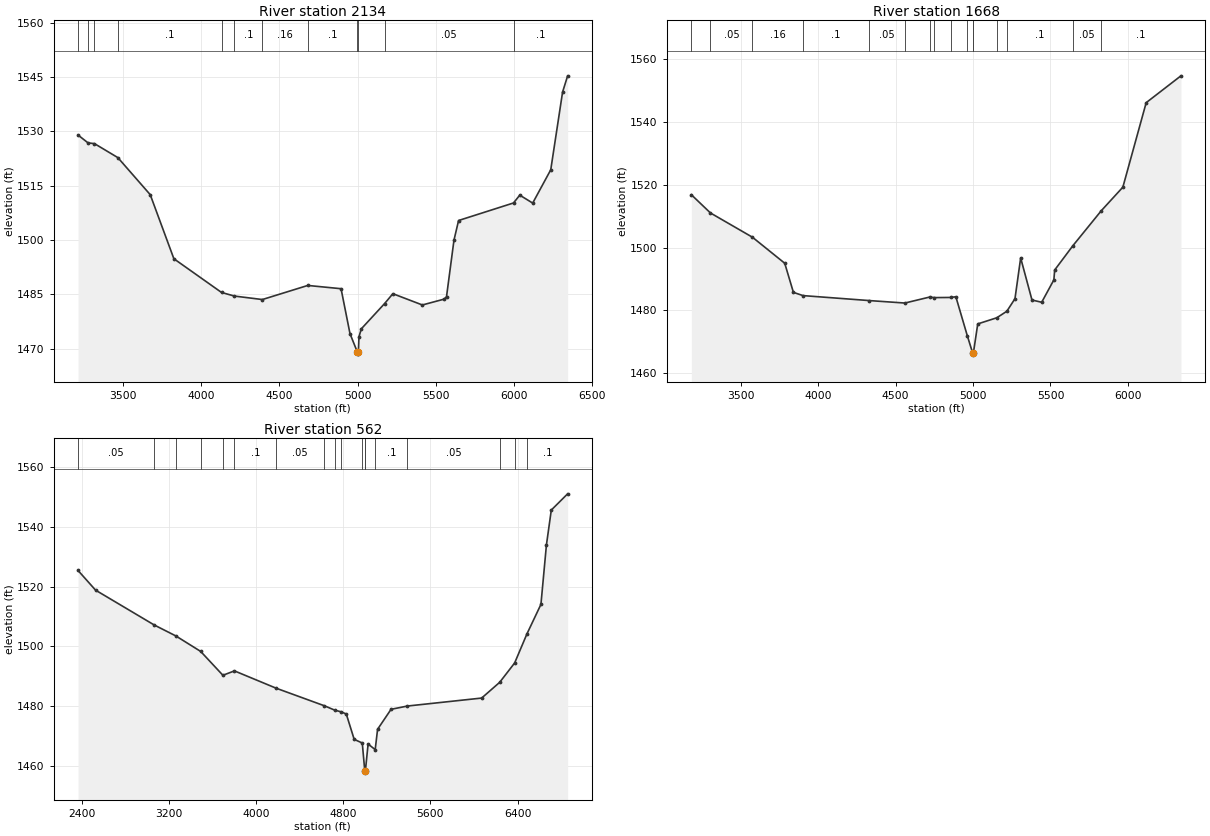
Type RM Length L Ch R = 1,2134,466,466,466
BEGIN DESCRIPTION:
WEST FORK WILLIAMS CREEK 3.0
END DESCRIPTION:
XS GIS Cut Line= 3
      2839805.61     10038759.66      2840915.35     10037072.49
      2841339.42     10036043.90
#Sta/Elev= 30
  3211.9 1529.02  3276.2 1526.84  3317.3 1526.64  3466.7 1522.78  3673.8 1512.55
  3825.1 1494.86  4129.8 1485.56  4212.2 1484.56  4391.0 1483.60  4681.6 1487.49
  4894.5 1486.59  4951.7 1474.18  4999.4 1469.03  5002.2 1468.53  5005.4 1469.03
  5009.0 1473.28  5024.0 1475.51  5172.5 1482.46  5225.9 1485.21  5414.6 1482.10
  5554.5 1483.72  5569.1 1484.38  5616.9 1500.01  5646.3 1505.42  5997.7 1510.26
  6037.7 1512.42  6120.4 1510.23  6235.9 1519.42  6311.6 1540.88  6343.9 1545.36
#Mann=12,-1,0
  3211.9    0.05       0  3276.2     0.1       0  3317.3    0.05       0
  3466.7     0.1       0  4129.8    0.05       0  4212.2     0.1       0
  4391.0    0.16       0  4681.6     0.1       0  4999.4    0.07       0
  5005.4     0.1       0  5172.5    0.05       0  5997.7     0.1       0
Bank Sta=4999.4,5005.4
Exp/Cntr=0.3,0.1

Type RM Length L Ch R = 1,1668,1106,1106,1106
BEGIN DESCRIPTION:
WEST FORK WILLIAMS CREEK 2.0
END DESCRIPTION:
XS GIS Cut Line= 3
      2840130.44     10038624.29      2841204.07     10037352.18
      2841555.93     10035899.61
#Sta/Elev= 30
  3182.5 1516.87  3306.0 1511.05  3576.9 1503.32  3785.2 1495.03  3841.2 1485.75
  3903.2 1484.72  4331.9 1483.13  4560.6 1482.35  4719.6 1484.25  4750.5 1484.08
  4857.0 1484.13  4889.4 1484.35  4964.0 1471.81  4996.9 1466.57  4999.6 1466.07
  5002.9 1466.57  5030.7 1475.70  5153.3 1477.65  5218.3 1479.73  5270.9 1483.74
  5307.6 1496.72  5380.6 1483.31  5443.3 1482.60  5521.8 1489.73  5527.0 1492.87
  5644.5 1500.62  5828.0 1511.78  5967.0 1519.27  6117.5 1546.20  6341.7 1554.75
#Mann=16,-1,0
  3182.5     0.1       0  3306.0    0.05       0  3576.9    0.16       0
  3903.2     0.1       0  4331.9    0.05       0  4560.6     0.1       0
  4719.6    0.05       0  4750.5     0.1       0  4857.0    0.05       0
  4964.0     0.1       0  4996.9    0.07       0  5002.9     0.1       0
  5153.3    0.05       0  5218.3     0.1       0  5644.5    0.05       0
  5828.0     0.1       0
Bank Sta=4996.9,5002.9
Exp/Cntr=0.3,0.1

Type RM Length L Ch R = 1,562,0,0,0
BEGIN DESCRIPTION:
WEST FORK WILLIAMS CREEK 1.0
END DESCRIPTION:
XS GIS Cut Line= 4
      2839859.76     10039210.76      2842133.37     10037505.56
      2842286.75     10037072.49      2841754.67     10036008.33
#Sta/Elev= 30
  2367.9 1525.41  2528.8 1518.81  3067.4 1507.12  3264.2 1503.48  3492.9 1498.27
  3696.9 1490.27  3802.7 1491.74  4185.1 1485.94  4628.7 1480.03  4720.6 1478.61
  4783.8 1477.99  4828.8 1477.27  4901.1 1468.79  4975.4 1467.56  4998.1 1458.30
  5000.8 1457.80  5004.1 1458.30  5028.8 1467.23  5093.9 1465.34  5115.7 1472.16
  5239.3 1478.86  5390.0 1479.96  6070.4 1482.63  6235.9 1487.91  6373.1 1494.40
  6486.2 1504.17  6614.2 1514.04  6664.6 1533.97  6709.3 1545.66  6859.1 1551.10
#Mann=18,-1,0
  2367.9    0.05       0  3067.4     0.1       0  3264.2    0.05       0
  3492.9     0.1       0  3696.9    0.05       0  3802.7     0.1       0
  4185.1    0.05       0  4628.7     0.1       0  4720.6    0.05       0
  4783.8     0.1       0  4975.4    0.05       0  4998.1   0.035       0
  5004.1    0.05       0  5093.9     0.1       0  5390.0    0.05       0
  6235.9    0.16       0  6373.1    0.05       0  6486.2     0.1       0
Bank Sta=4998.1,5004.1
Exp/Cntr=0.3,0.1

Chan Stop Cuts=-1