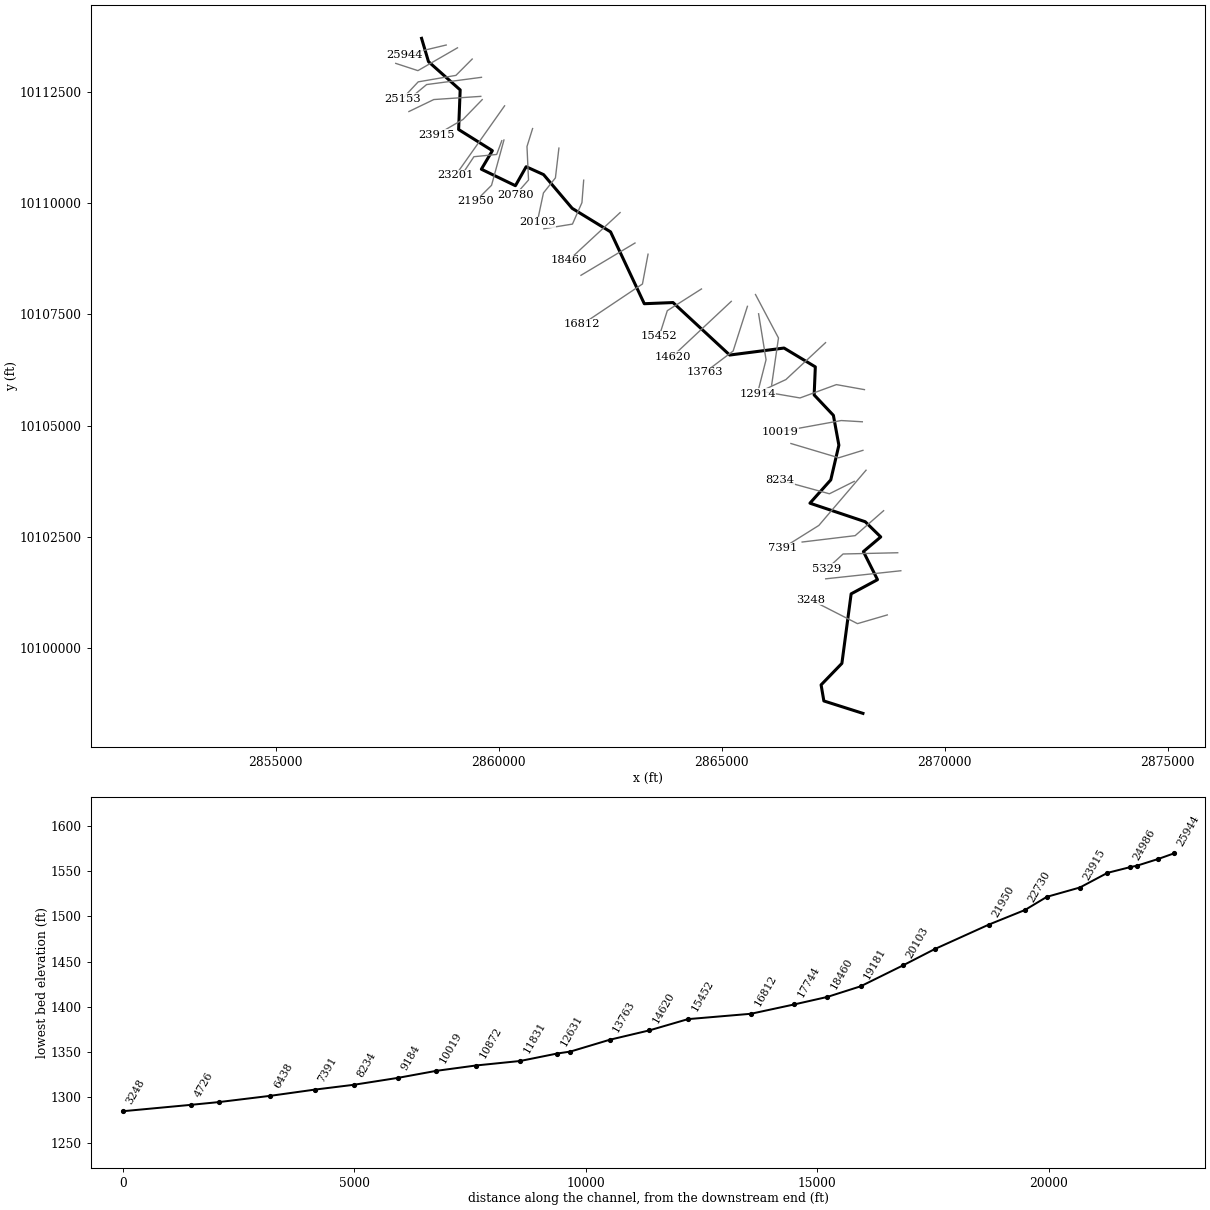
--- WHITE OAK CREEK.prj (project) ---

Proj Title=WHITE OAK CREEK Base Level Engineering
Current Plan=p01
Default Exp/Contr=0.3,0.1
English Units
Geom File=g01
Flow File=f01
Plan File=p01
BEGIN DESCRIPTION:
WHITE OAK CREEK
END DESCRIPTION:

--- WHITE OAK CREEK.p01 (plan) ---

Plan Title=Multiple Run
Short Identifier=Multiple
Geom File=g01
Flow File=f01
Subcritical Flow
K Sum by GR= 0
Std Step Tol= 0.01
Critical Tol= 0.01
Num of Std Step Trials= 20
Max Error Tol= 0.3
Flow Tol Ratio= 0.001
Split Flow NTrial= 30
Split Flow Tol= 0.02
Split Flow Ratio= 0.02
Log Output Level= 0
Friction Slope Method= 1
Unsteady Friction Slope Method= 2
Unsteady Bridges Friction Slope Method= 1
Parabolic Critical Depth
Global Vel Dist=  1 , 1 , 1
Global Log Level= 0
CheckData=True
Encroach Param= -1, 0, 0, 0
BEGIN DESCRIPTION:
Multiple Run
END DESCRIPTION:

--- WHITE OAK CREEK.f01 (steady flow) ---

Flow Title=Multiple
Number of Profiles=7
Profile Names=10-year,25-year,50-year,1pct_min,100-year,1pct_plu,500-year
River Rch & RM= WHITE OAK CREEK,Reach-1,25944
     808    1173    1491    1388    1877    2539    2989
River Rch & RM= WHITE OAK CREEK,Reach-1,25607
    1495    2247    2923    2779    3758    5082    6244
River Rch & RM= WHITE OAK CREEK,Reach-1,20103
    1882    2850    3725    3555    4808    6502    8051
River Rch & RM= WHITE OAK CREEK,Reach-1,11831
    3082    4762    6307    6091    8237   11140   14124
River Rch & RM= WHITE OAK CREEK,Reach-1,6438
    3214    4961    6565    6333    8564   11582   14651
Boundary for River Rch & Prof#=WHITE OAK CREEK,Reach-1,1
Up Type=0
Dn Type=3
Dn Slope=0.005
Boundary for River Rch & Prof#=WHITE OAK CREEK,Reach-1,2
Up Type=0
Dn Type=3
Dn Slope=0.005
Boundary for River Rch & Prof#=WHITE OAK CREEK,Reach-1,3
Up Type=0
Dn Type=3
Dn Slope=0.005
Boundary for River Rch & Prof#=WHITE OAK CREEK,Reach-1,4
Up Type=0
Dn Type=3
Dn Slope=0.005
Boundary for River Rch & Prof#=WHITE OAK CREEK,Reach-1,5
Up Type=0
Dn Type=3
Dn Slope=0.005
Boundary for River Rch & Prof#=WHITE OAK CREEK,Reach-1,6
Up Type=0
Dn Type=3
Dn Slope=0.005
Boundary for River Rch & Prof#=WHITE OAK CREEK,Reach-1,7
Up Type=0
Dn Type=3
Dn Slope=0.005

--- WHITE OAK CREEK.g01 (geometry) ---

Geom Title=Existing Conditions

River Reach=WHITE OAK CREEK,Reach-1
Reach XY= 30
      2858268.47     10113693.73      2858423.49     10113170.88
      2859134.05     10112536.54      2859099.36     10111647.20
      2859856.68     10111172.98      2859609.48     10110756.29
      2860373.46     10110386.38      2860614.02     10110812.33
      2861004.87     10110635.30      2861645.99     10109878.65
      2862507.29     10109350.67      2863263.91     10107737.77
      2863908.47     10107763.73      2865179.33     10106585.90
      2866398.49     10106742.83      2867100.21     10106320.28
      2867074.06     10105690.22      2867505.39     10105232.63
      2867628.53     10104562.45      2867446.80     10103784.26
      2866979.30     10103261.00      2868219.29     10102844.87
      2868567.30     10102503.64      2868178.42     10102174.82
      2868495.03     10101544.60      2867903.67     10101226.31
      2867696.11     10099665.74      2867229.67     10099183.35
      2867291.77     10098822.54      2868168.47     10098543.73

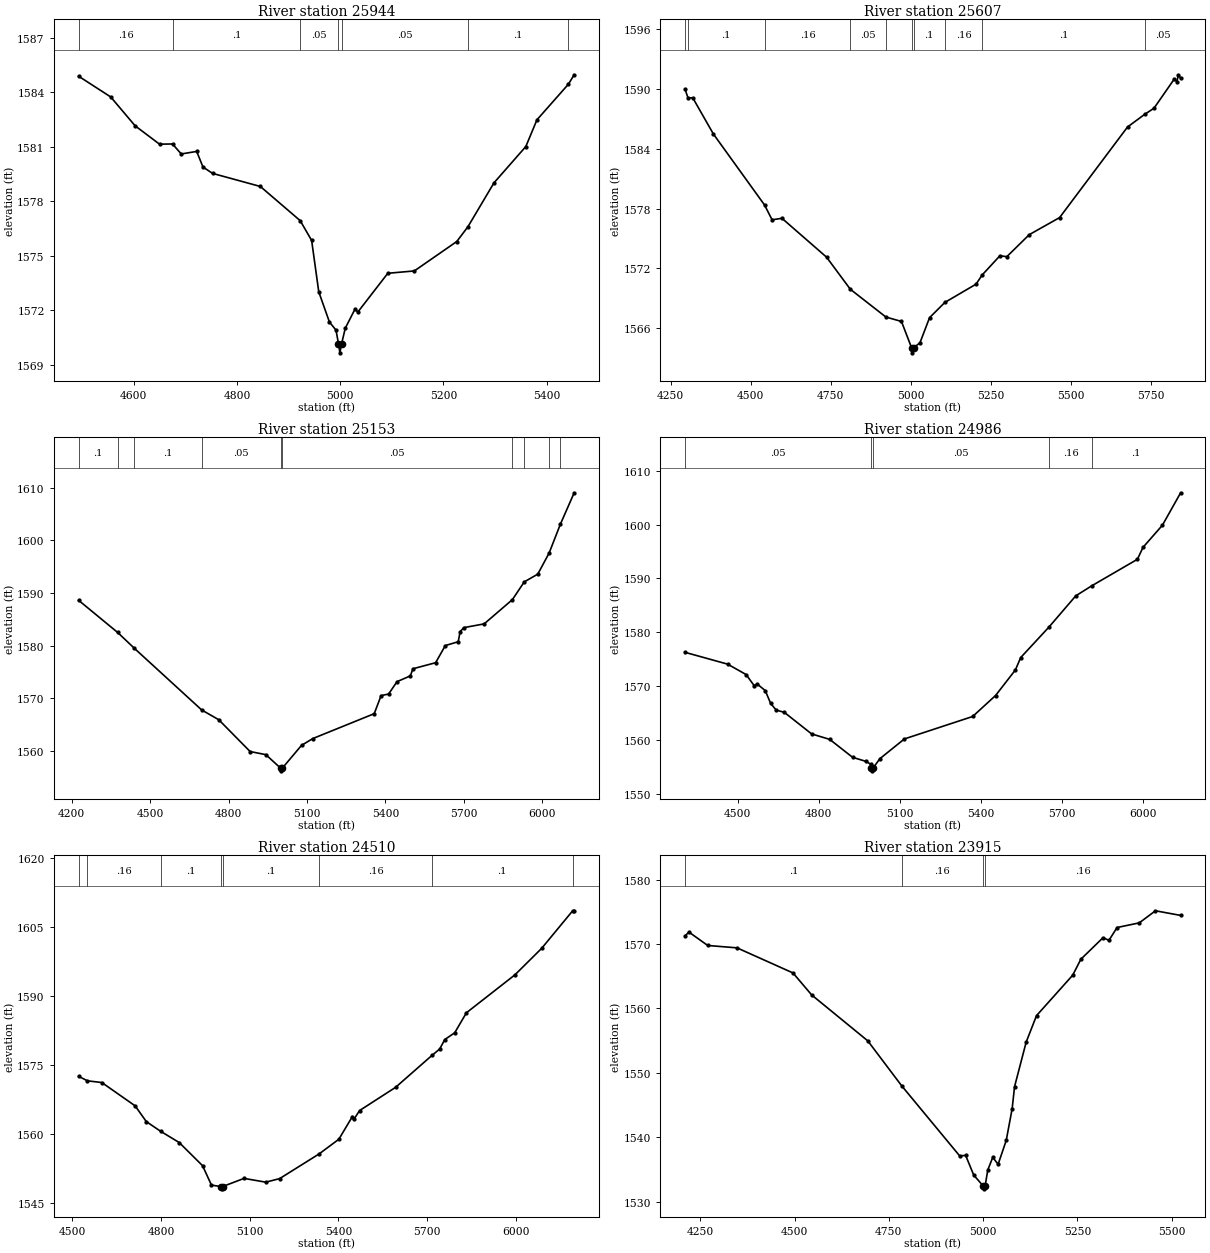
Type RM Length L Ch R = 1,25944,337,337,337
BEGIN DESCRIPTION:
WHITE OAK CREEK 55.0
END DESCRIPTION:
XS GIS Cut Line= 2
      2858820.78     10113543.91      2857887.42     10113321.02
#Sta/Elev= 30
  4493.5 1584.89  4555.6 1583.75  4602.9 1582.16  4650.1 1581.15  4675.3 1581.16
  4692.2 1580.61  4722.1 1580.75  4734.3 1579.89  4752.9 1579.54  4845.4 1578.82
  4922.5 1576.94  4944.7 1575.85  4958.5 1573.02  4979.1 1571.36  4991.9 1570.91
  4996.7 1570.16  4999.4 1569.66  5002.7 1570.16  5009.9 1571.02  5028.9 1572.08
  5034.0 1571.90  5092.2 1574.04  5143.6 1574.17  5225.8 1575.79  5247.3 1576.60
  5297.8 1579.02  5359.5 1581.02  5381.0 1582.49  5441.9 1584.45  5453.1 1584.97
#Mann=7,-1,0
  4493.5    0.16       0  4675.3     0.1       0  4922.5    0.05       0
  4996.7   0.035       0  5002.7    0.05       0  5247.3     0.1       0
  5441.9    0.05       0
Bank Sta=4996.7,5002.7
Exp/Cntr=0.3,0.1

Type RM Length L Ch R = 1,25607,454,454,454
BEGIN DESCRIPTION:
Mapping XS fa47dc0b
END DESCRIPTION:
XS GIS Cut Line= 3
      2859073.75     10113480.90      2858186.21     10112968.77
      2857689.28     10113131.52
#Sta/Elev= 30
  4295.0 1589.96  4304.0 1589.10  4318.9 1589.11  4383.5 1585.47  4543.2 1578.35
  4566.6 1576.87  4597.5 1577.02  4736.8 1573.12  4811.0 1569.90  4922.2 1567.11
  4970.7 1566.67  5002.4 1564.02  5005.1 1563.52  5008.4 1564.02  5028.5 1564.53
  5058.5 1567.05  5106.3 1568.58  5203.6 1570.41  5222.7 1571.33  5278.2 1573.26
  5299.8 1573.17  5369.9 1575.38  5464.6 1577.09  5676.7 1586.18  5730.3 1587.45
  5759.3 1588.06  5822.4 1590.98  5830.7 1590.74  5835.9 1591.42  5842.6 1591.08
#Mann=10,-1,0
  4295.0    0.16       0  4304.0     0.1       0  4543.2    0.16       0
  4811.0    0.05       0  4922.2     0.1       0  5002.4    0.07       0
  5008.4     0.1       0  5106.3    0.16       0  5222.7     0.1       0
  5730.3    0.05       0
Bank Sta=5002.4,5008.4
Exp/Cntr=0.3,0.1

Type RM Length L Ch R = 1,25153,167,167,167
BEGIN DESCRIPTION:
WHITE OAK CREEK 54.0
END DESCRIPTION:
XS GIS Cut Line= 4
      2859403.63     10113229.16      2859039.07     10112862.43
      2858192.72     10112717.03      2857837.52     10112338.01
#Sta/Elev= 30
  4226.6 1588.60  4375.9 1582.49  4439.9 1579.47  4697.4 1567.75  4762.5 1565.90
  4882.5 1559.85  4942.5 1559.26  4999.4 1556.68  5002.2 1556.18  5005.4 1556.68
  5079.2 1561.03  5122.4 1562.32  5357.2 1567.05  5383.5 1570.49  5412.1 1570.78
  5444.4 1573.14  5495.2 1574.23  5505.3 1575.59  5592.0 1576.74  5629.1 1580.00
  5678.4 1580.73  5685.7 1582.64  5699.9 1583.41  5777.6 1584.12  5885.7 1588.74
  5931.0 1592.11  5982.7 1593.58  6026.1 1597.59  6069.0 1603.06  6121.9 1609.05
#Mann=10,-1,0
  4226.6     0.1       0  4375.9    0.16       0  4439.9     0.1       0
  4697.4    0.05       0  4999.4    0.04       0  5005.4    0.05       0
  5885.7     0.1       0  5931.0    0.05       0  6026.1     0.1       0
  6069.0    0.05       0
Bank Sta=4999.4,5005.4
Exp/Cntr=0.3,0.1

Type RM Length L Ch R = 1,24986,476,476,476
BEGIN DESCRIPTION:
WHITE OAK CREEK 53.0
END DESCRIPTION:
XS GIS Cut Line= 3
      2859611.98     10112819.03      2858381.52     10112656.27
      2857928.00     10112278.69
#Sta/Elev= 30
  4306.0 1576.29  4463.3 1574.10  4531.5 1572.17  4561.7 1570.08  4571.8 1570.44
  4602.1 1569.20  4622.2 1566.82  4642.4 1565.59  4672.7 1565.16  4773.5 1561.16
  4840.6 1560.14  4924.9 1556.82  4975.3 1556.05  4992.5 1555.51  4994.5 1554.81
  4997.3 1554.31  5000.5 1554.81  5025.7 1556.56  5116.5 1560.23  5368.7 1564.39
  5453.3 1568.28  5526.7 1573.03  5546.2 1575.32  5651.2 1581.01  5749.7 1586.77
  5809.4 1588.65  5977.5 1593.55  5998.3 1595.77  6069.9 1599.87  6137.3 1605.89
#Mann=5,-1,0
  4306.0    0.05       0  4994.5    0.04       0  5000.5    0.05       0
  5651.2    0.16       0  5809.4     0.1       0
Bank Sta=4994.5,5000.5
Exp/Cntr=0.3,0.1

Type RM Length L Ch R = 1,24510,595,595,595
BEGIN DESCRIPTION:
Mapping XS d68225cd
END DESCRIPTION:
XS GIS Cut Line= 3
      2859596.79     10112391.51      2858542.11     10112319.90
      2857984.35     10112050.78
#Sta/Elev= 30
  4520.9 1572.62  4550.9 1571.64  4599.4 1571.27  4712.1 1566.20  4749.7 1562.79
  4798.5 1560.66  4861.1 1558.23  4940.2 1553.19  4970.3 1548.97  5002.0 1548.66
  5004.8 1548.16  5008.0 1548.66  5080.5 1550.43  5154.0 1549.61  5200.8 1550.38
  5334.2 1555.74  5401.2 1558.94  5447.0 1563.88  5452.0 1563.27  5471.4 1565.18
  5593.2 1570.23  5715.9 1577.15  5742.4 1578.56  5759.5 1580.61  5793.2 1582.09
  5832.8 1586.44  5996.7 1594.67  6087.1 1600.43  6192.0 1608.59  6197.3 1608.61
#Mann=8,-1,0
  4520.9     0.1       0  4550.9    0.16       0  4798.5     0.1       0
  5002.0    0.07       0  5008.0     0.1       0  5334.2    0.16       0
  5715.9     0.1       0  6192.0    0.05       0
Bank Sta=5002,5008
Exp/Cntr=0.3,0.1

Type RM Length L Ch R = 1,23915,714,714,714
BEGIN DESCRIPTION:
WHITE OAK CREEK 52.0
END DESCRIPTION:
XS GIS Cut Line= 3
      2859628.75     10112317.99      2859196.92     10111872.24
      2858597.93     10111523.98
#Sta/Elev= 30
  4210.0 1571.29  4220.2 1571.87  4269.9 1569.79  4347.6 1569.42  4496.0 1565.52
  4545.6 1562.10  4694.1 1554.98  4784.2 1547.98  4937.9 1537.09  4953.6 1537.18
  4975.1 1534.11  4999.4 1532.48  5002.2 1531.98  5005.4 1532.48  5012.4 1534.93
  5025.5 1536.87  5039.7 1535.79  5061.2 1539.50  5076.9 1544.43  5083.3 1547.86
  5114.2 1554.80  5141.5 1558.89  5237.5 1565.18  5259.0 1567.65  5317.8 1571.00
  5333.5 1570.59  5355.0 1572.58  5413.8 1573.30  5456.8 1575.18  5523.5 1574.46
#Mann=4,-1,0
  4210.0     0.1       0  4784.2    0.16       0  4999.4    0.07       0
  5005.4    0.16       0
Bank Sta=4999.4,5005.4
Exp/Cntr=0.3,0.1

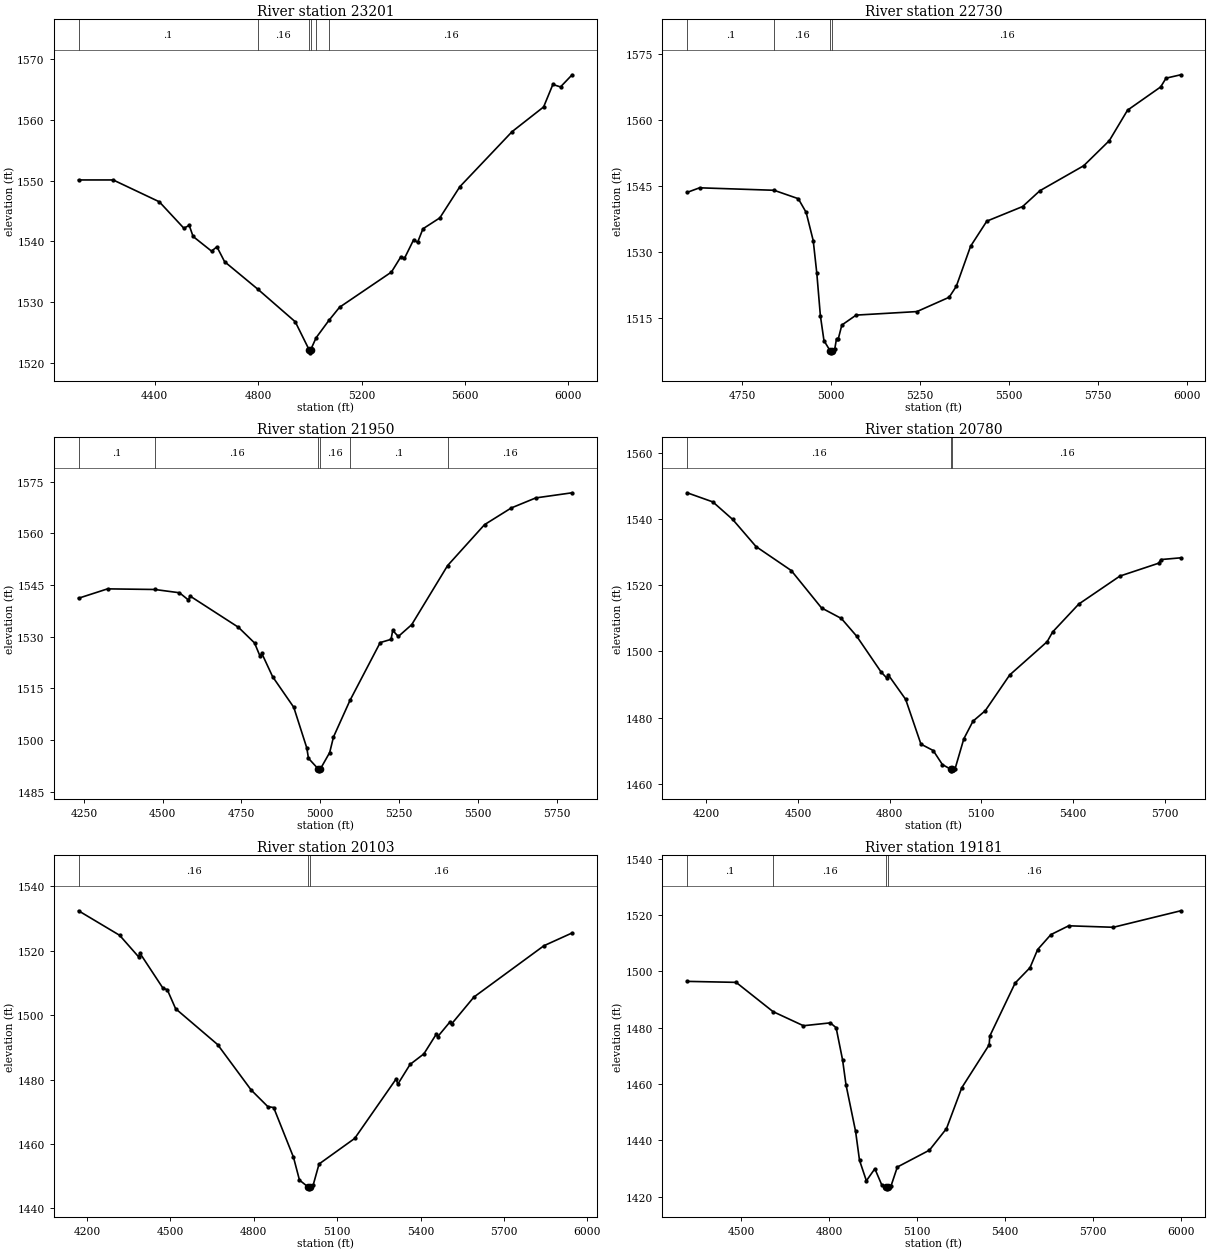
Type RM Length L Ch R = 1,23201,471,471,471
BEGIN DESCRIPTION:
WHITE OAK CREEK 51.0
END DESCRIPTION:
XS GIS Cut Line= 2
      2860130.26     10112178.69      2859029.86     10110618.63
#Sta/Elev= 30
  4105.1 1550.14  4239.0 1550.14  4417.5 1546.54  4512.4 1542.19  4533.3 1542.65
  4548.1 1540.83  4619.5 1538.41  4640.4 1539.12  4670.0 1536.67  4798.2 1532.15
  4943.3 1526.77  4997.0 1522.15  4999.8 1521.65  5003.0 1522.15  5023.9 1524.13
  5073.2 1526.98  5114.6 1529.16  5315.3 1534.96  5351.0 1537.42  5365.8 1537.23
  5401.5 1540.31  5416.3 1539.84  5437.2 1542.09  5502.5 1543.89  5580.0 1549.03
  5782.0 1558.10  5903.9 1562.17  5939.6 1565.87  5969.2 1565.47  6014.2 1567.47
#Mann=6,-1,0
  4105.1     0.1       0  4798.2    0.16       0  4997.0    0.07       0
  5003.0    0.16       0  5023.9     0.1       0  5073.2    0.16       0
Bank Sta=4997,5003
Exp/Cntr=0.3,0.1

Type RM Length L Ch R = 1,22730,780,780,780
BEGIN DESCRIPTION:
Mapping XS 9155f9c7
END DESCRIPTION:
XS GIS Cut Line= 4
      2860067.71     10111396.59      2859953.15     10111087.61
      2859442.73     10111037.26      2859140.66     10110584.15
#Sta/Elev= 30
  4595.7 1543.59  4630.7 1544.63  4839.9 1544.07  4908.0 1542.16  4930.1 1539.05
  4950.0 1532.64  4960.1 1525.21  4970.1 1515.59  4980.2 1509.92  4997.3 1507.65
  5000.0 1507.15  5003.3 1507.65  5010.3 1507.94  5015.5 1510.36  5020.5 1510.35
  5030.4 1513.46  5070.6 1515.72  5241.4 1516.52  5331.9 1519.77  5352.0 1522.25
  5392.2 1531.36  5437.8 1537.06  5538.5 1540.38  5586.8 1543.96  5710.0 1549.64
  5782.1 1555.35  5833.2 1562.26  5926.3 1567.54  5941.4 1569.53  5982.7 1570.30
#Mann=4,-1,0
  4595.7     0.1       0  4839.9    0.16       0  4997.3    0.07       0
  5003.3    0.16       0
Bank Sta=4997.3,5003.3
Exp/Cntr=0.3,0.1

Type RM Length L Ch R = 1,21950,1170,1170,1170
BEGIN DESCRIPTION:
WHITE OAK CREEK 46.0
END DESCRIPTION:
XS GIS Cut Line= 3
      2860116.34     10111412.51      2859837.73     10110395.59
      2859475.55     10110033.41
#Sta/Elev= 30
  4232.8 1541.13  4324.9 1543.85  4474.6 1543.67  4553.0 1542.72  4581.6 1540.62
  4586.8 1541.76  4740.2 1532.70  4791.4 1528.15  4809.2 1524.22  4814.4 1525.13
  4848.8 1518.35  4915.9 1509.46  4957.3 1497.64  4962.6 1494.64  4994.1 1491.51
  4996.9 1491.01  5000.1 1491.51  5029.9 1496.32  5042.0 1500.85  5094.3 1511.46
  5190.2 1528.25  5224.7 1529.19  5229.9 1531.79  5247.7 1530.02  5290.2 1533.45
  5404.1 1550.61  5521.3 1562.49  5606.2 1567.34  5684.0 1570.26  5799.4 1571.75
#Mann=6,-1,0
  4232.8     0.1       0  4474.6    0.16       0  4994.1    0.07       0
  5000.1    0.16       0  5094.3     0.1       0  5404.1    0.16       0
Bank Sta=4994.1,5000.1
Exp/Cntr=0.3,0.1

Type RM Length L Ch R = 1,20780,677,677,677
BEGIN DESCRIPTION:
WHITE OAK CREEK 45.0
END DESCRIPTION:
XS GIS Cut Line= 4
      2860758.54     10111668.83      2860632.68     10111265.21
      2860667.40     10110514.34      2860376.60     10110184.48
#Sta/Elev= 30
  4137.8 1547.92  4221.9 1545.16  4286.9 1539.85  4363.1 1531.67  4478.3 1524.43
  4577.3 1513.13  4642.2 1509.94  4692.2 1504.60  4772.3 1493.75  4790.7 1491.95
  4795.7 1492.89  4852.4 1485.51  4902.4 1471.98  4942.5 1470.05  4972.5 1465.81
  4999.5 1464.41  5002.3 1463.91  5005.5 1464.41  5014.1 1464.55  5042.6 1473.58
  5072.6 1478.91  5112.7 1482.07  5192.7 1492.88  5315.2 1502.93  5333.2 1505.88
  5418.6 1514.30  5553.0 1522.75  5680.4 1526.66  5687.1 1527.74  5752.0 1528.27
#Mann=3,-1,0
  4137.8    0.16       0  4999.5    0.07       0  5005.5    0.16       0
Bank Sta=4999.5,5005.5
Exp/Cntr=0.3,0.1

Type RM Length L Ch R = 1,20103,922,922,922
BEGIN DESCRIPTION:
WHITE OAK CREEK 43.0
END DESCRIPTION:
XS GIS Cut Line= 4
      2861348.83     10111230.53      2861270.70     10110562.08
      2861001.60     10110223.54      2860862.71     10109568.16
#Sta/Elev= 30
  4170.0 1532.40  4317.8 1524.79  4385.9 1518.12  4390.9 1519.23  4474.2 1508.30
  4489.0 1507.94  4519.2 1502.00  4670.2 1490.88  4791.0 1476.76  4850.9 1471.61
  4871.8 1471.33  4943.1 1455.90  4964.7 1448.80  4996.9 1446.59  4999.7 1446.09
  5002.9 1446.59  5014.3 1447.37  5035.1 1453.80  5163.3 1461.74  5312.9 1480.27
  5318.0 1478.53  5362.5 1484.71  5412.2 1487.99  5456.8 1494.11  5461.9 1493.32
  5506.5 1497.96  5511.6 1497.25  5592.1 1505.62  5843.9 1521.55  5945.4 1525.52
#Mann=3,-1,0
  4170.0    0.16       0  4996.9    0.07       0  5002.9    0.16       0
Bank Sta=4996.9,5002.9
Exp/Cntr=0.3,0.1

Type RM Length L Ch R = 1,19181,721,721,721
BEGIN DESCRIPTION:
WHITE OAK CREEK 39.0
END DESCRIPTION:
XS GIS Cut Line= 4
      2861904.38     10110510.00      2861865.32     10110006.53
      2861652.64     10109524.76      2861011.92     10109420.86
#Sta/Elev= 30
  4317.0 1496.47  4483.8 1496.12  4609.5 1485.73  4713.0 1480.72  4804.7 1481.74
  4824.3 1480.01  4846.4 1468.52  4857.8 1459.83  4890.6 1443.20  4903.9 1432.96
  4927.3 1425.65  4956.2 1429.94  4979.3 1424.29  4994.2 1423.30  4996.9 1422.80
  5000.2 1423.30  5010.9 1423.72  5032.7 1430.54  5142.0 1436.53  5200.1 1444.19
  5252.2 1458.71  5345.4 1473.95  5347.6 1477.06  5433.9 1495.89  5484.5 1501.34
  5510.5 1507.78  5555.5 1513.07  5616.2 1516.21  5768.2 1515.68  5997.7 1521.54
#Mann=4,-1,0
  4317.0     0.1       0  4609.5    0.16       0  4994.2    0.07       0
  5000.2    0.16       0
Bank Sta=4994.2,5000.2
Exp/Cntr=0.3,0.1

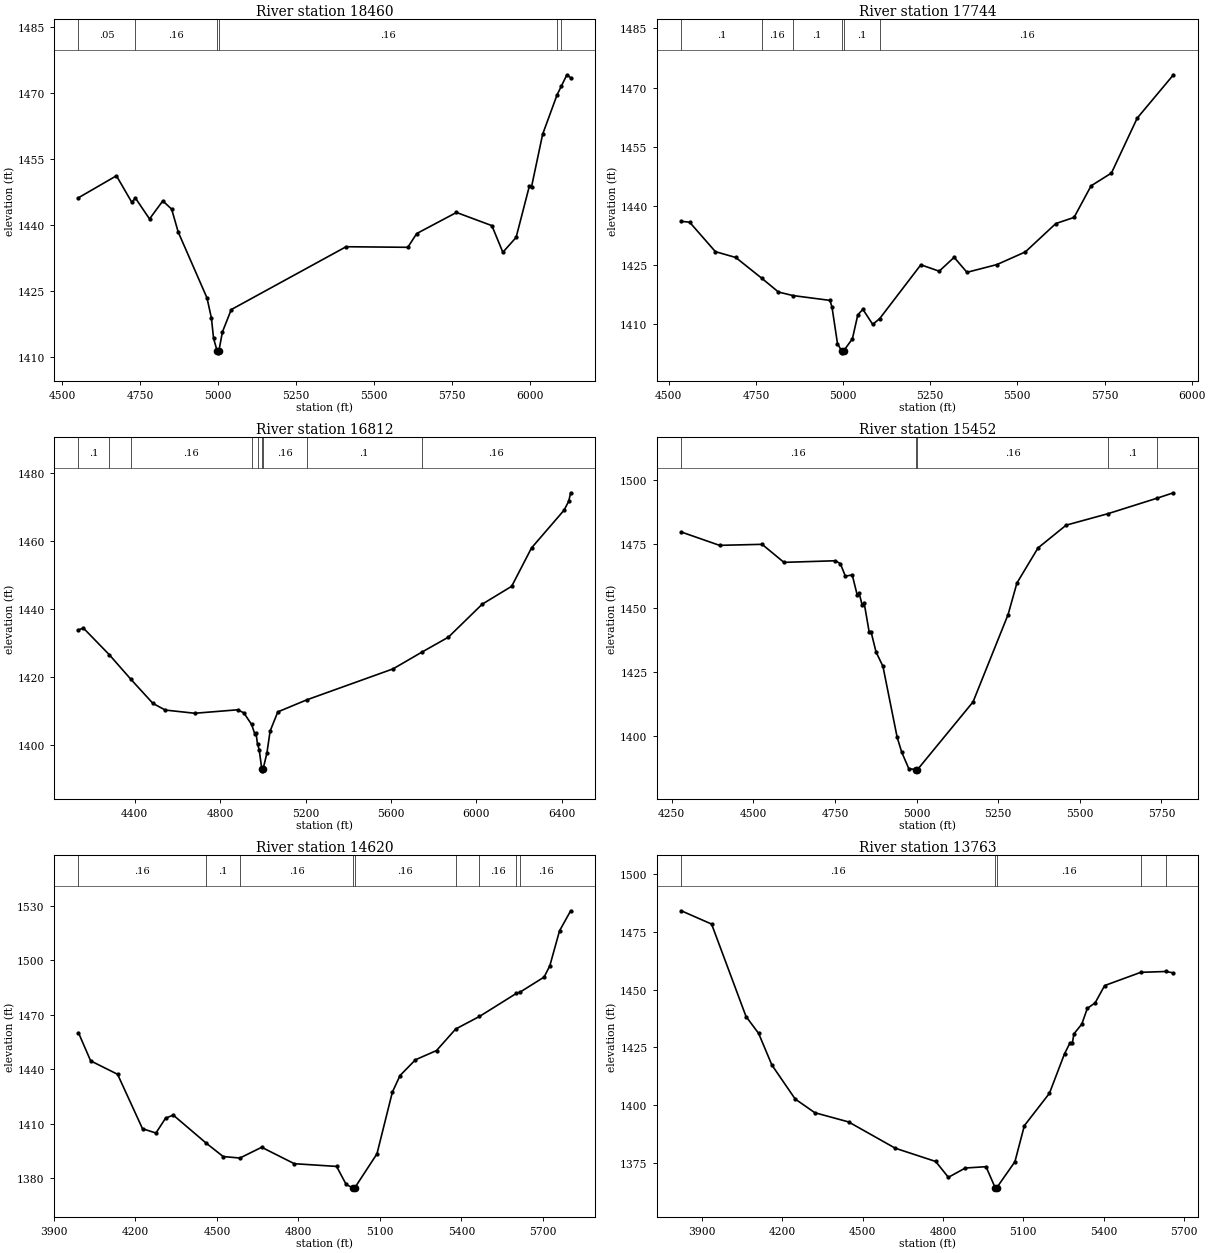
Type RM Length L Ch R = 1,18460,716,716,716
BEGIN DESCRIPTION:
WHITE OAK CREEK 38.0
END DESCRIPTION:
XS GIS Cut Line= 2
      2862721.40     10109782.66      2861565.15     10108709.99
#Sta/Elev= 30
  4553.0 1446.23  4674.7 1451.22  4724.0 1445.19  4735.4 1446.17  4780.7 1441.42
  4823.2 1445.51  4851.6 1443.65  4872.6 1438.45  4964.9 1423.48  4979.1 1418.88
  4985.9 1414.31  4997.1 1411.52  4999.9 1411.02  5003.1 1411.52  5014.3 1415.76
  5042.6 1420.84  5410.6 1435.11  5608.4 1434.98  5636.8 1438.10  5764.3 1442.89
  5877.7 1439.90  5912.9 1433.85  5955.4 1437.23  5997.9 1448.89  6004.7 1448.68
  6040.4 1460.65  6086.6 1469.58  6099.9 1471.51  6118.1 1474.15  6130.2 1473.49
#Mann=6,-1,0
  4553.0    0.05       0  4735.4    0.16       0  4997.1    0.07       0
  5003.1    0.16       0  6086.6     0.1       0  6099.9    0.16       0
Bank Sta=4997.1,5003.1
Exp/Cntr=0.3,0.1

Type RM Length L Ch R = 1,17744,932,932,932
BEGIN DESCRIPTION:
WHITE OAK CREEK 37.0
END DESCRIPTION:
XS GIS Cut Line= 2
      2863055.70     10109100.03      2861843.78     10108375.66
#Sta/Elev= 30
  4535.9 1436.06  4559.9 1435.85  4633.8 1428.38  4692.2 1426.90  4766.2 1421.68
  4814.7 1418.14  4856.5 1417.24  4962.6 1416.02  4968.4 1414.27  4984.0 1405.08
  4995.7 1403.22  4998.4 1402.72  5001.7 1403.22  5026.8 1406.27  5042.3 1412.36
  5056.9 1413.76  5085.1 1409.93  5105.2 1411.41  5223.2 1425.05  5275.8 1423.42
  5318.6 1426.94  5355.5 1423.14  5441.4 1425.10  5522.9 1428.31  5610.4 1435.51
  5662.7 1437.06  5711.5 1445.07  5769.9 1448.31  5843.8 1462.24  5947.8 1473.23
#Mann=6,-1,0
  4535.9     0.1       0  4766.2    0.16       0  4856.5     0.1       0
  4995.7    0.07       0  5001.7     0.1       0  5105.2    0.16       0
Bank Sta=4995.7,5001.7
Exp/Cntr=0.3,0.1

Type RM Length L Ch R = 1,16812,1360,1360,1360
BEGIN DESCRIPTION:
WHITE OAK CREEK 34.0
END DESCRIPTION:
XS GIS Cut Line= 3
      2863348.26     10108849.30      2863222.88     10108180.62
      2861872.56     10107275.76
#Sta/Elev= 30
  4136.1 1433.91  4159.6 1434.38  4281.2 1426.53  4382.0 1419.32  4485.1 1412.25
  4542.8 1410.30  4681.0 1409.36  4881.9 1410.38  4910.8 1409.47  4947.1 1406.07
  4961.9 1403.34  4967.9 1403.54  4974.9 1400.26  4982.9 1398.64  4994.9 1392.93
  4997.6 1392.43  5000.9 1392.93  5018.9 1397.65  5033.9 1404.11  5069.9 1409.76
  5205.9 1413.31  5610.2 1422.42  5744.4 1427.32  5869.0 1431.73  6027.5 1441.43
  6165.5 1446.69  6258.6 1457.98  6410.7 1469.05  6432.7 1471.69  6441.9 1474.19
#Mann=9,-1,0
  4136.1     0.1       0  4281.2    0.05       0  4382.0    0.16       0
  4947.1     0.1       0  4974.9    0.16       0  4994.9    0.07       0
  5000.9    0.16       0  5205.9     0.1       0  5744.4    0.16       0
Bank Sta=4994.9,5000.9
Exp/Cntr=0.3,0.1

Type RM Length L Ch R = 1,15452,832,832,832
BEGIN DESCRIPTION:
WHITE OAK CREEK 30.0
END DESCRIPTION:
XS GIS Cut Line= 3
      2864546.31     10108069.18      2863780.11     10107581.60
      2863599.00     10107010.41
#Sta/Elev= 30
  4279.5 1479.87  4396.7 1474.65  4527.1 1475.05  4594.0 1468.00  4751.5 1468.63
  4766.7 1467.51  4782.0 1462.61  4803.1 1463.09  4818.4 1455.23  4824.3 1456.04
  4833.6 1451.20  4839.5 1452.26  4854.8 1440.91  4860.7 1440.90  4876.0 1432.98
  4897.1 1427.38  4940.7 1399.61  4954.7 1393.78  4976.3 1387.39  4997.0 1387.01
  4999.7 1386.51  5003.0 1387.01  5173.1 1413.45  5280.5 1447.62  5307.5 1459.93
  5372.1 1473.64  5458.2 1482.54  5586.2 1487.02  5735.9 1493.05  5786.9 1495.20
#Mann=5,-1,0
  4279.5    0.16       0  4997.0    0.07       0  5003.0    0.16       0
  5586.2     0.1       0  5735.9    0.16       0
Bank Sta=4997,5003
Exp/Cntr=0.3,0.1

Type RM Length L Ch R = 1,14620,857,857,857
BEGIN DESCRIPTION:
WHITE OAK CREEK 29.0
END DESCRIPTION:
XS GIS Cut Line= 2
      2865214.94     10107790.53      2863892.51     10106551.63
#Sta/Elev= 30
  3990.1 1460.02  4034.9 1444.54  4134.1 1437.14  4225.9 1407.18  4275.3 1404.81
  4310.9 1413.01  4339.2 1414.67  4459.9 1399.30  4522.9 1391.86  4584.5 1391.05
  4664.6 1396.97  4784.7 1387.93  4940.5 1386.43  4975.7 1376.48  5001.0 1374.59
  5003.8 1374.09  5007.0 1374.59  5089.0 1393.33  5145.7 1427.30  5174.0 1436.46
  5230.7 1445.13  5308.4 1450.21  5378.8 1462.06  5466.4 1468.97  5602.0 1481.64
  5617.0 1482.47  5704.5 1490.65  5725.5 1496.90  5761.2 1516.11  5802.2 1527.14
#Mann=9,-1,0
  3990.1    0.16       0  4459.9     0.1       0  4584.5    0.16       0
  5001.0    0.07       0  5007.0    0.16       0  5378.8     0.1       0
  5466.4    0.16       0  5602.0     0.1       0  5617.0    0.16       0
Bank Sta=5001,5007
Exp/Cntr=0.3,0.1

Type RM Length L Ch R = 1,13763,849,849,849
BEGIN DESCRIPTION:
WHITE OAK CREEK 27.0
END DESCRIPTION:
XS GIS Cut Line= 3
      2865577.15     10107679.07      2865256.76     10106676.10
      2864629.87     10106202.46
#Sta/Elev= 30
  3822.5 1484.14  3935.8 1478.38  4064.5 1438.34  4111.5 1431.04  4161.0 1417.34
  4248.0 1402.62  4321.5 1396.68  4447.5 1392.69  4622.0 1381.30  4772.9 1375.56
  4820.3 1368.70  4883.6 1372.73  4961.0 1373.30  4995.0 1364.21  4997.8 1363.71
  5001.0 1364.21  5068.8 1375.44  5104.2 1391.09  5197.8 1405.09  5254.1 1422.19
  5274.9 1426.99  5283.2 1426.77  5289.4 1430.86  5318.6 1435.04  5339.4 1441.88
  5368.5 1444.24  5403.9 1451.74  5538.9 1457.48  5633.3 1457.85  5661.1 1457.22
#Mann=5,-1,0
  3822.5    0.16       0  4995.0    0.07       0  5001.0    0.16       0
  5538.9     0.1       0  5633.3    0.16       0
Bank Sta=4995,5001
Exp/Cntr=0.3,0.1

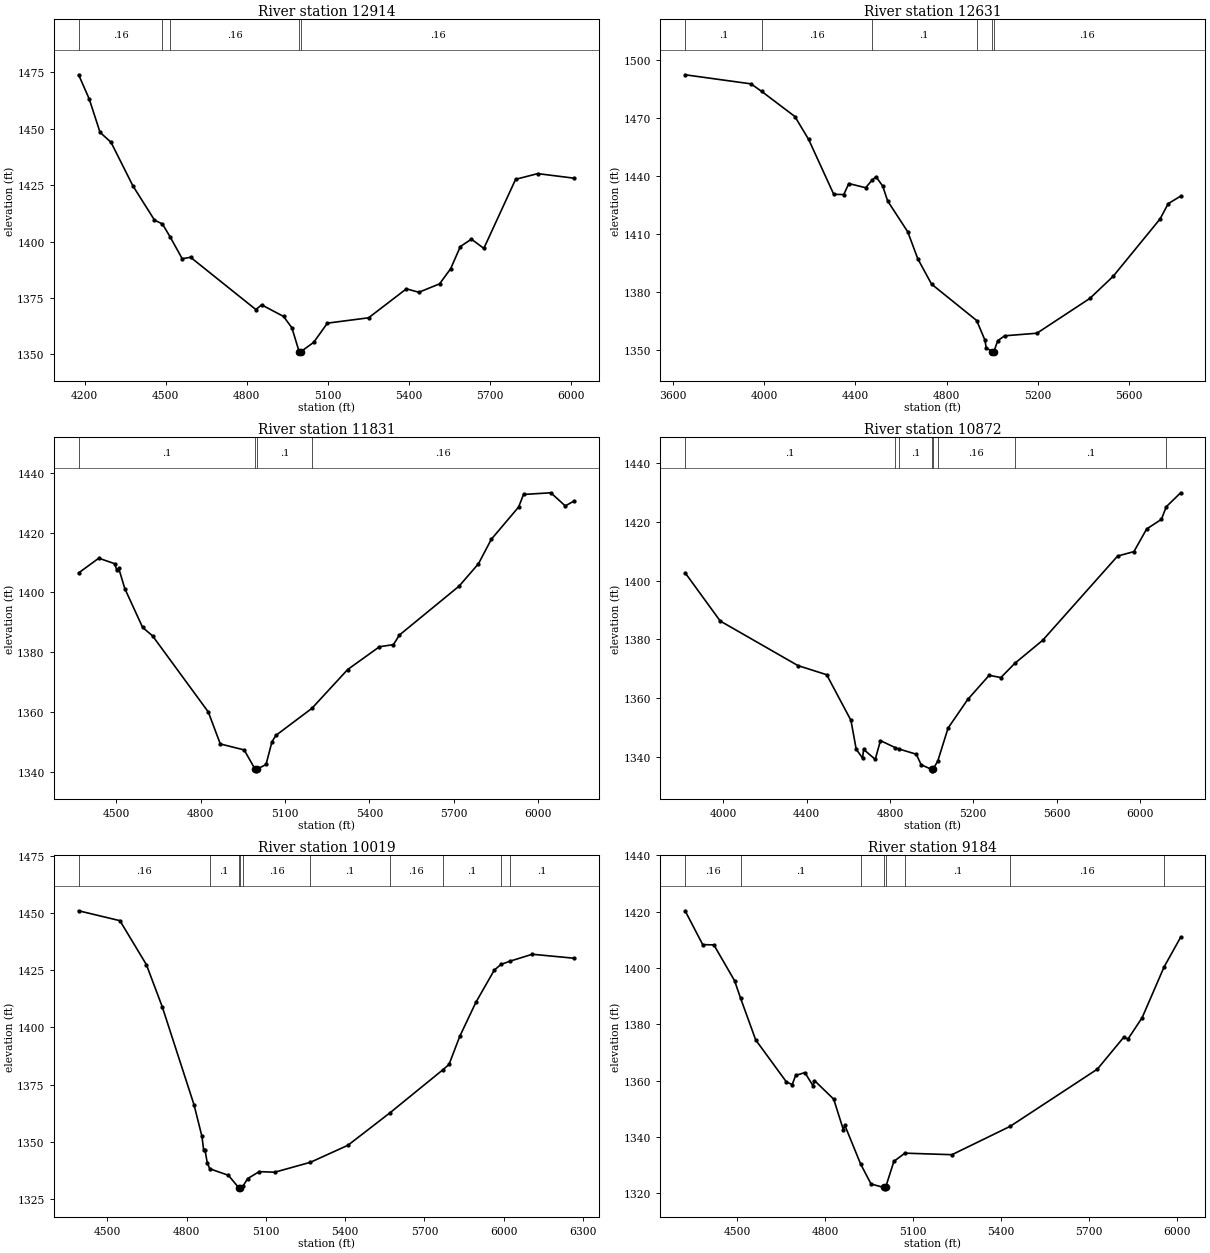
Type RM Length L Ch R = 1,12914,283,283,283
BEGIN DESCRIPTION:
WHITE OAK CREEK 26.0
END DESCRIPTION:
XS GIS Cut Line= 3
      2865827.92     10107511.92      2865995.08     10106481.08
      2865800.55     10105716.85
#Sta/Elev= 30
  4177.9 1473.91  4217.1 1463.19  4257.1 1448.39  4297.6 1444.01  4378.7 1424.66
  4458.5 1409.50  4488.0 1407.76  4516.9 1401.93  4561.0 1392.38  4591.9 1393.02
  4833.4 1369.85  4854.8 1371.93  4935.9 1366.80  4966.8 1361.73  4993.6 1351.16
  4996.4 1350.66  4999.6 1351.16  5047.3 1355.30  5098.0 1363.82  5250.4 1366.19
  5390.3 1379.03  5436.4 1377.51  5513.0 1381.24  5554.0 1387.96  5589.7 1397.76
  5630.6 1401.05  5676.7 1396.96  5794.2 1427.57  5876.0 1430.10  6010.8 1428.07
#Mann=5,-1,0
  4177.9    0.16       0  4488.0     0.1       0  4516.9    0.16       0
  4993.6    0.07       0  4999.6    0.16       0
Bank Sta=4993.6,4999.6
Exp/Cntr=0.3,0.1

Type RM Length L Ch R = 1,12631,800,800,800
BEGIN DESCRIPTION:
WHITE OAK CREEK 25.0
END DESCRIPTION:
XS GIS Cut Line= 3
      2865758.25     10107943.82      2866273.70     10106968.65
      2866120.45     10105909.89
#Sta/Elev= 30
  3653.1 1492.44  3942.0 1487.74  3988.6 1483.86  4134.5 1470.84  4194.9 1458.95
  4304.9 1430.57  4348.9 1430.44  4370.9 1436.15  4445.0 1433.97  4471.9 1437.80
  4490.2 1439.66  4519.4 1434.89  4541.4 1427.09  4629.4 1411.16  4673.4 1397.19
  4733.8 1384.08  4931.6 1365.25  4967.7 1355.13  4973.3 1351.19  5000.6 1349.02
  5003.3 1348.52  5006.6 1349.02  5023.8 1354.77  5054.1 1357.34  5195.6 1358.67
  5428.0 1376.70  5529.8 1388.10  5735.6 1417.80  5771.5 1425.75  5825.9 1429.62
#Mann=6,-1,0
  3653.1     0.1       0  3988.6    0.16       0  4471.9     0.1       0
  4931.6    0.16       0  5000.6    0.07       0  5006.6    0.16       0
Bank Sta=5000.6,5006.6
Exp/Cntr=0.3,0.1

Type RM Length L Ch R = 1,11831,959,959,959
BEGIN DESCRIPTION:
WHITE OAK CREEK 23.0
END DESCRIPTION:
XS GIS Cut Line= 3
      2867329.70     10106864.14      2866439.97     10106035.17
      2865945.19     10105805.14
#Sta/Elev= 30
  4366.0 1406.50  4437.7 1411.42  4494.4 1409.57  4501.7 1407.33  4508.6 1408.01
  4530.1 1401.26  4593.6 1388.24  4628.8 1385.44  4827.1 1359.95  4869.6 1349.27
  4954.6 1347.26  4993.6 1340.77  4996.4 1340.27  4999.6 1340.77  5032.3 1342.41
  5053.3 1350.00  5067.5 1352.15  5195.2 1361.17  5322.5 1374.17  5435.4 1381.79
  5485.2 1382.50  5506.2 1385.69  5718.8 1402.09  5787.4 1409.56  5833.2 1417.76
  5930.3 1428.55  5947.6 1432.75  6044.7 1433.31  6096.0 1428.92  6127.7 1430.57
#Mann=4,-1,0
  4366.0     0.1       0  4993.6    0.07       0  4999.6     0.1       0
  5195.2    0.16       0
Bank Sta=4993.6,4999.6
Exp/Cntr=0.3,0.1

Type RM Length L Ch R = 1,10872,853,853,853
BEGIN DESCRIPTION:
WHITE OAK CREEK 20.0
END DESCRIPTION:
XS GIS Cut Line= 4
      2868202.16     10105809.47      2867572.78     10105922.33
      2866756.81     10105622.85      2865897.40     10105770.42
#Sta/Elev= 30
  3815.6 1402.70  3984.2 1386.27  4357.8 1371.09  4495.7 1367.98  4612.3 1352.45
  4637.5 1342.65  4668.0 1339.60  4673.3 1342.56  4729.0 1339.15  4754.1 1345.55
  4825.7 1343.14  4845.2 1342.65  4926.4 1340.92  4949.6 1337.33  4999.9 1335.76
  5002.6 1335.26  5005.9 1335.76  5029.1 1338.52  5078.9 1349.81  5173.3 1359.55
  5276.3 1367.78  5332.7 1367.02  5399.5 1371.85  5533.4 1379.70  5893.3 1408.37
  5971.9 1409.90  6032.8 1417.59  6103.8 1420.87  6127.0 1425.15  6196.2 1429.92
#Mann=8,-1,0
  3815.6     0.1       0  4825.7    0.16       0  4845.2     0.1       0
  4999.9    0.07       0  5005.9     0.1       0  5029.1    0.16       0
  5399.5     0.1       0  6127.0    0.16       0
Bank Sta=4999.9,5005.9
Exp/Cntr=0.3,0.1

Type RM Length L Ch R = 1,10019,835,835,835
BEGIN DESCRIPTION:
WHITE OAK CREEK 19.0
END DESCRIPTION:
XS GIS Cut Line= 3
      2868154.38     10105088.01      2867680.69     10105115.87
      2866302.49     10104865.29
#Sta/Elev= 30
  4391.3 1451.00  4547.5 1446.67  4647.7 1427.44  4707.8 1408.98  4828.0 1366.13
  4858.0 1352.27  4864.4 1346.35  4869.5 1346.35  4878.2 1340.66  4887.6 1338.13
  4958.0 1335.29  4997.2 1329.86  5000.0 1329.36  5003.2 1329.86  5013.7 1330.61
  5030.7 1333.83  5074.9 1336.89  5133.4 1336.63  5268.6 1340.98  5410.3 1348.41
  5568.0 1362.48  5769.9 1381.46  5793.0 1383.78  5833.6 1396.06  5894.6 1410.94
  5964.3 1425.05  5989.7 1427.53  6024.8 1428.99  6108.1 1431.98  6266.6 1430.24
#Mann=10,-1,0
  4391.3    0.16       0  4887.6     0.1       0  4997.2    0.07       0
  5003.2     0.1       0  5013.7    0.16       0  5268.6     0.1       0
  5568.0    0.16       0  5769.9     0.1       0  5989.7    0.16       0
  6024.8     0.1       0
Bank Sta=4997.2,5003.2
Exp/Cntr=0.3,0.1

Type RM Length L Ch R = 1,9184,950,950,950
BEGIN DESCRIPTION:
WHITE OAK CREEK 18.0
END DESCRIPTION:
XS GIS Cut Line= 3
      2868168.25     10104447.20      2867624.97     10104280.03
      2866552.89     10104600.26
#Sta/Elev= 30
  4323.7 1420.35  4383.7 1408.32  4421.7 1408.23  4492.3 1395.47  4512.9 1389.19
  4564.1 1374.46  4668.7 1359.52  4688.5 1358.58  4700.1 1361.85  4731.6 1362.85
  4759.1 1358.20  4764.3 1360.01  4829.7 1353.41  4862.4 1342.60  4867.6 1344.12
  4921.2 1330.40  4956.9 1323.25  5000.3 1322.04  5003.0 1321.54  5006.3 1322.04
  5034.6 1331.30  5072.2 1334.22  5232.3 1333.67  5430.4 1343.74  5727.4 1364.07
  5817.3 1375.42  5832.0 1374.82  5879.9 1382.36  5954.8 1400.43  6011.0 1410.94
#Mann=8,-1,0
  4323.7    0.16       0  4512.9     0.1       0  4921.2    0.16       0
  5000.3    0.07       0  5006.3    0.16       0  5072.2     0.1       0
  5430.4    0.16       0  5954.8     0.1       0
Bank Sta=5000.3,5006.3
Exp/Cntr=0.3,0.1

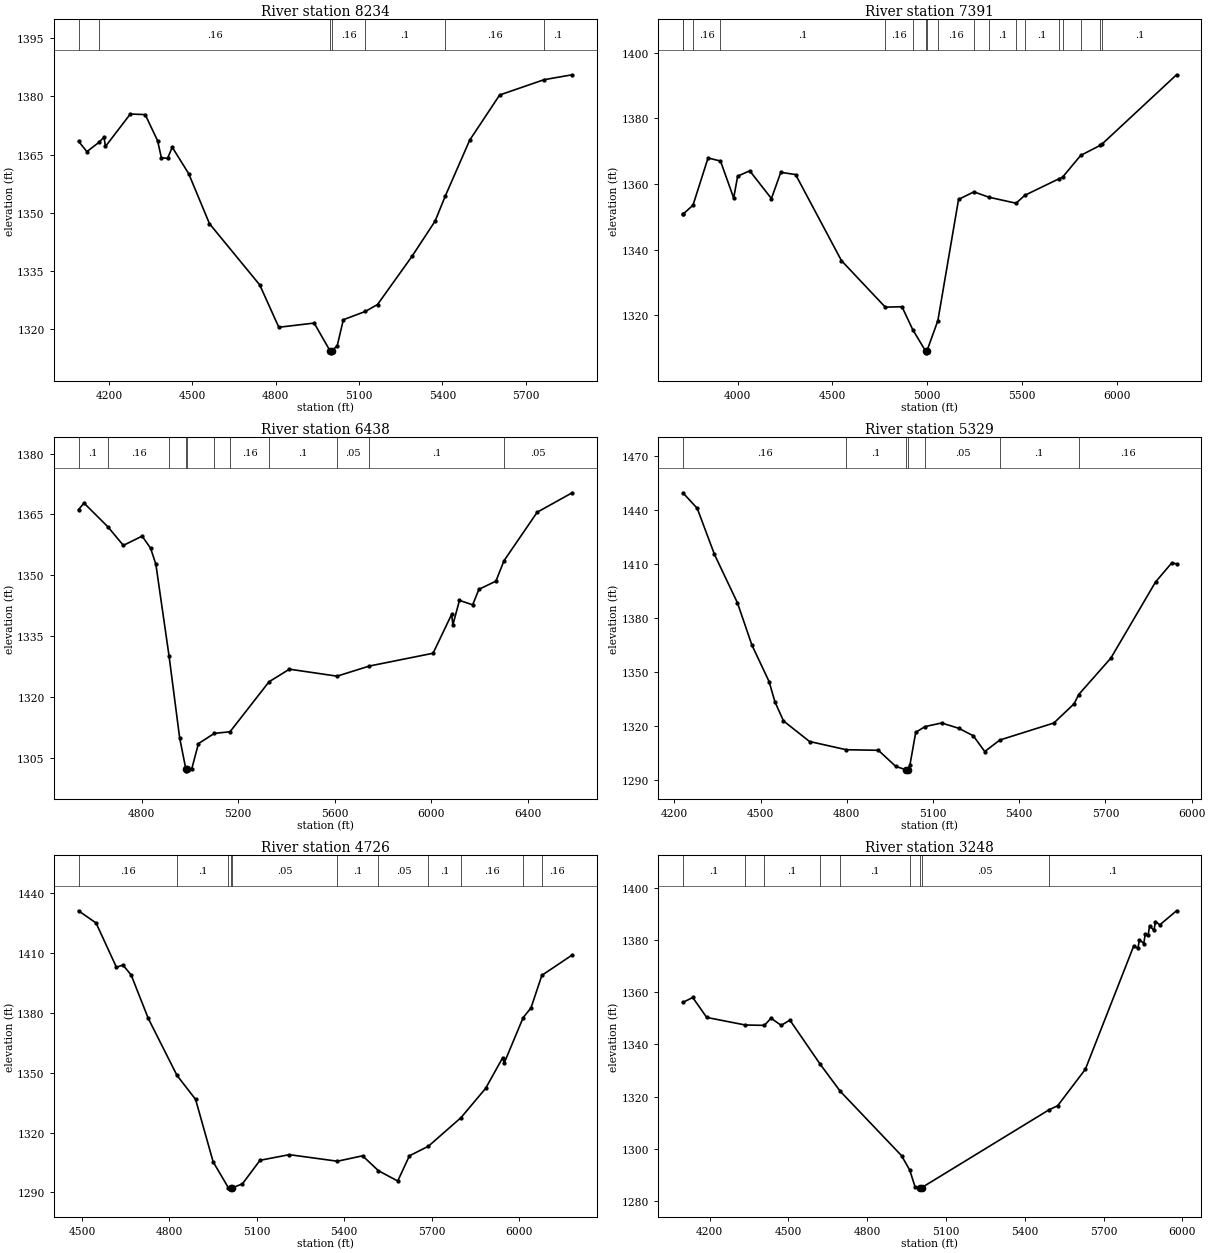
Type RM Length L Ch R = 1,8234,843,843,843
BEGIN DESCRIPTION:
WHITE OAK CREEK 14.0
END DESCRIPTION:
XS GIS Cut Line= 3
      2867973.24     10103750.67      2867416.01     10103472.06
      2866302.55     10103778.26
#Sta/Elev= 30
  4089.6 1368.44  4119.6 1365.75  4162.8 1368.13  4181.1 1369.48  4186.7 1367.10
  4276.1 1375.45  4329.7 1375.30  4374.4 1368.55  4387.9 1364.19  4410.3 1364.03
  4427.1 1366.89  4486.2 1360.10  4561.2 1347.19  4742.1 1331.43  4810.9 1320.51
  4938.2 1321.59  4995.5 1314.42  4998.3 1313.92  5001.5 1314.42  5021.2 1315.73
  5043.3 1322.45  5122.7 1324.59  5166.4 1326.37  5290.8 1338.81  5373.8 1347.87
  5410.1 1354.26  5498.3 1368.71  5606.2 1380.35  5766.0 1384.29  5867.4 1385.56
#Mann=7,-1,0
  4089.6     0.1       0  4162.8    0.16       0  4995.5    0.07       0
  5001.5    0.16       0  5122.7     0.1       0  5410.1    0.16       0
  5766.0     0.1       0
Bank Sta=4995.5,5001.5
Exp/Cntr=0.3,0.1

Type RM Length L Ch R = 1,7391,953,953,953
BEGIN DESCRIPTION:
WHITE OAK CREEK 13.0
END DESCRIPTION:
XS GIS Cut Line= 3
      2868237.92     10104001.42      2867179.19     10102761.59
      2866357.30     10102246.17
#Sta/Elev= 30
  3712.2 1350.95  3713.4 1350.81  3765.5 1353.55  3844.7 1367.91  3910.2 1366.97
  3979.8 1355.72  4000.6 1362.37  4064.3 1364.00  4178.5 1355.55  4227.9 1363.53
  4305.9 1362.86  4547.4 1336.66  4778.4 1322.50  4866.4 1322.62  4923.1 1315.64
  4991.2 1309.09  4994.0 1308.59  4997.2 1309.09  5055.4 1318.39  5164.4 1355.30
  5245.5 1357.59  5323.8 1355.97  5467.5 1354.13  5513.4 1356.54  5694.4 1361.60
  5712.0 1362.04  5807.8 1368.68  5910.6 1371.75  5921.2 1372.19  6312.7 1393.23
#Mann=18,-1,0
  3712.2    0.16       0  3713.4     0.1       0  3765.5    0.16       0
  3910.2     0.1       0  4778.4    0.16       0  4923.1     0.1       0
  4991.2    0.07       0  4997.2     0.1       0  5055.4    0.16       0
  5245.5    0.05       0  5323.8     0.1       0  5467.5    0.05       0
  5513.4     0.1       0  5694.4    0.16       0  5712.0    0.05       0
  5807.8     0.1       0  5910.6    0.05       0  5921.2     0.1       0
Bank Sta=4991.2,4997.2
Exp/Cntr=0.3,0.1

Type RM Length L Ch R = 1,6438,1109,1109,1109
BEGIN DESCRIPTION:
WHITE OAK CREEK 12.0
END DESCRIPTION:
XS GIS Cut Line= 3
      2868631.79     10103092.45      2867993.79     10102532.57
      2866804.51     10102389.34
#Sta/Elev= 30
  4537.8 1366.16  4560.4 1367.79  4659.8 1361.91  4723.6 1357.35  4801.4 1359.63
  4836.5 1356.67  4858.3 1352.73  4912.9 1330.17  4957.0 1309.91  4982.5 1302.27
  4985.3 1301.77  4988.5 1302.27  5007.3 1302.27  5034.9 1308.48  5100.9 1311.01
  5165.9 1311.40  5327.5 1323.72  5412.1 1326.83  5609.7 1325.11  5743.9 1327.61
  6007.8 1330.76  6084.9 1340.36  6089.9 1337.77  6117.2 1343.79  6172.0 1342.70
  6197.8 1346.52  6268.3 1348.53  6302.0 1353.58  6439.5 1365.53  6584.5 1370.32
#Mann=11,-1,0
  4537.8     0.1       0  4659.8    0.16       0  4912.9     0.1       0
  4982.5    0.07       0  4988.5     0.1       0  5100.9    0.05       0
  5165.9    0.16       0  5327.5     0.1       0  5609.7    0.05       0
  5743.9     0.1       0  6302.0    0.05       0
Bank Sta=4982.5,4988.5
Exp/Cntr=0.3,0.1

Type RM Length L Ch R = 1,5329,603,603,603
BEGIN DESCRIPTION:
WHITE OAK CREEK 9.0
END DESCRIPTION:
XS GIS Cut Line= 3
      2868948.36     10102148.64      2867722.48     10102120.78
      2867361.55     10101787.61
#Sta/Elev= 30
  4230.0 1449.36  4279.9 1440.71  4339.9 1415.07  4419.9 1388.16  4470.0 1364.76
  4530.0 1344.40  4550.0 1333.27  4580.0 1322.58  4670.6 1311.16  4798.2 1306.60
  4910.1 1306.27  4970.1 1297.39  5007.1 1295.36  5009.8 1294.86  5013.1 1295.36
  5020.1 1298.33  5040.1 1316.26  5072.6 1319.46  5130.1 1321.46  5190.1 1318.48
  5240.2 1314.35  5280.2 1305.59  5332.6 1311.98  5520.5 1321.43  5591.4 1332.18
  5606.9 1337.23  5719.0 1357.51  5874.4 1399.80  5931.1 1410.45  5947.4 1409.82
#Mann=7,-1,0
  4230.0    0.16       0  4798.2     0.1       0  5007.1    0.07       0
  5013.1     0.1       0  5072.6    0.05       0  5332.6     0.1       0
  5606.9    0.16       0
Bank Sta=5007.1,5013.1
Exp/Cntr=0.3,0.1

Type RM Length L Ch R = 1,4726,1478,1478,1478
BEGIN DESCRIPTION:
WHITE OAK CREEK 8.0
END DESCRIPTION:
XS GIS Cut Line= 2
      2869018.05     10101744.66      2867332.95     10101563.61
#Sta/Elev= 30
  4487.7 1431.11  4547.9 1424.99  4618.0 1402.76  4640.0 1403.97  4668.3 1398.96
  4727.0 1377.23  4825.7 1348.64  4889.6 1336.61  4949.9 1305.32  5001.6 1292.48
  5010.3 1292.31  5013.0 1291.81  5016.3 1292.31  5050.5 1294.34  5110.8 1306.11
  5211.4 1308.93  5376.7 1305.64  5462.9 1308.36  5517.5 1300.87  5583.6 1295.74
  5623.8 1308.37  5688.8 1313.14  5800.9 1327.49  5885.3 1342.13  5944.0 1357.52
  5949.0 1354.78  6014.2 1377.58  6041.1 1382.45  6078.5 1398.77  6182.5 1408.96
#Mann=11,-1,0
  4487.7    0.16       0  4825.7     0.1       0  5001.6    0.05       0
  5010.3    0.07       0  5016.3    0.05       0  5376.7     0.1       0
  5517.5    0.05       0  5688.8     0.1       0  5800.9    0.16       0
  6014.2     0.1       0  6078.5    0.16       0
Bank Sta=5010.3,5016.3
Exp/Cntr=0.3,0.1

Type RM Length L Ch R = 1,3248,876,876,876
BEGIN DESCRIPTION:
WHITE OAK CREEK 3.0
END DESCRIPTION:
XS GIS Cut Line= 3
      2868714.32     10100753.07      2868045.87     10100557.74
      2866992.32     10101095.36
#Sta/Elev= 30
  4098.1 1356.08  4135.5 1357.95  4188.8 1350.32  4335.4 1347.43  4408.7 1347.28
  4433.4 1350.05  4472.1 1347.29  4505.5 1349.29  4620.2 1332.49  4697.5 1322.01
  4930.3 1297.44  4961.4 1291.95  4982.4 1285.35  5001.9 1285.22  5004.6 1284.72
  5007.9 1285.22  5490.9 1314.91  5524.8 1316.53  5630.3 1330.50  5813.8 1377.54
  5830.4 1376.80  5836.0 1380.09  5852.6 1378.61  5858.2 1382.21  5869.2 1381.75
  5874.8 1385.39  5891.5 1383.62  5897.1 1387.02  5913.7 1385.76  5977.3 1391.14
#Mann=9,-1,0
  4098.1     0.1       0  4335.4    0.05       0  4408.7     0.1       0
  4620.2    0.05       0  4697.5     0.1       0  4961.4    0.05       0
  5001.9   0.035       0  5007.9    0.05       0  5490.9     0.1       0
Bank Sta=5001.9,5007.9
Exp/Cntr=0.3,0.1