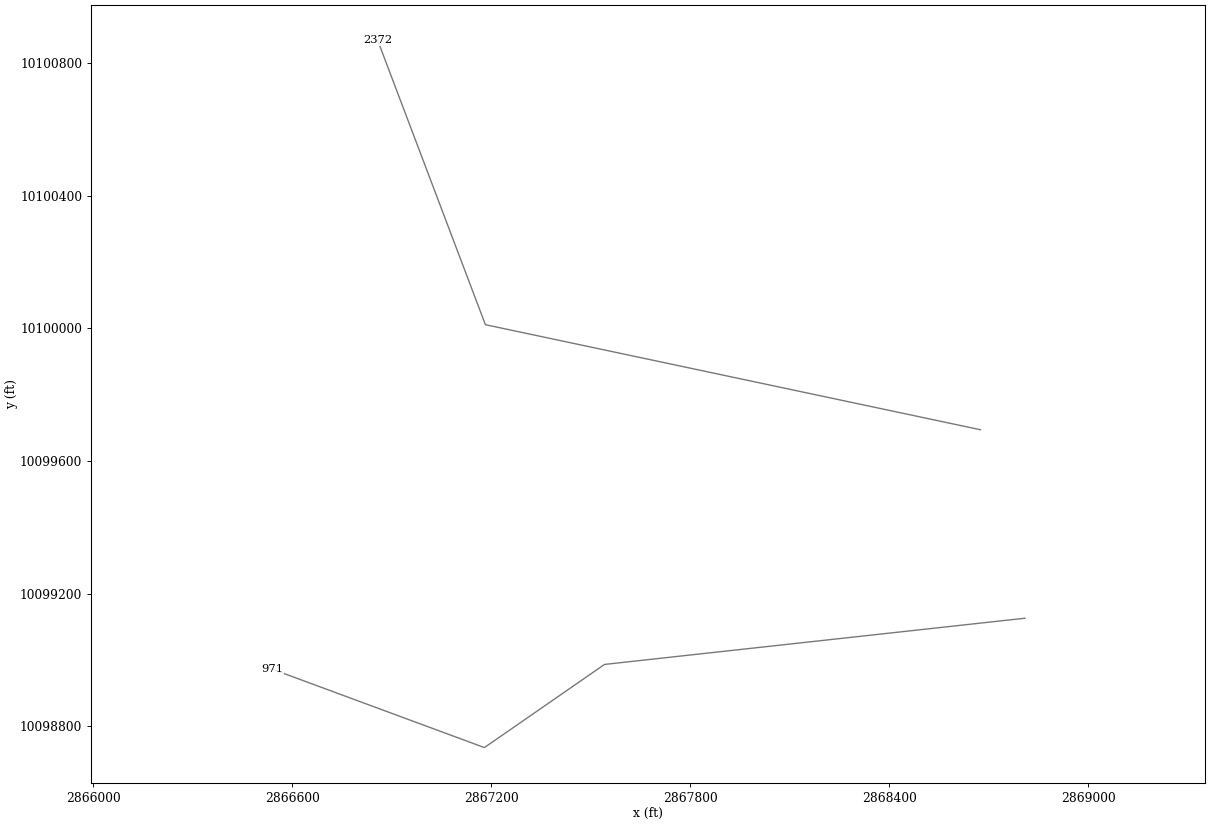
HEC-RAS study WHITE OAK CREEK.prj: WHITE OAK CREEK Base Level Engineering

--- WHITE OAK CREEK.g01 (geometry) --- (continued)

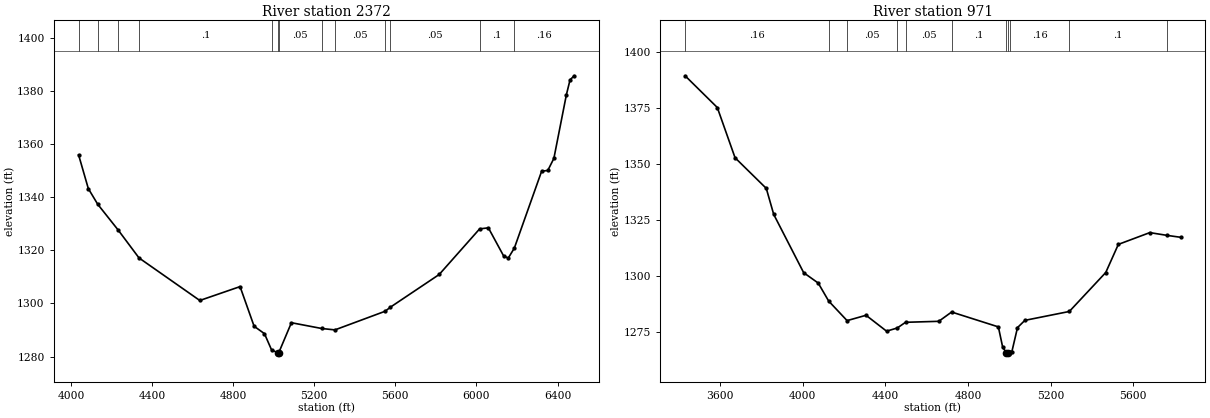
Type RM Length L Ch R = 1,2372,1401,1401,1401
BEGIN DESCRIPTION:
WHITE OAK CREEK 2.0
END DESCRIPTION:
XS GIS Cut Line= 3
      2868675.18     10099694.04      2867182.16     10100010.87
      2866856.93     10100869.47
#Sta/Elev= 30
  4037.7 1355.83  4085.5 1343.19  4131.9 1337.30  4233.7 1327.52  4335.5 1317.13
  4635.4 1301.13  4834.0 1306.35  4903.3 1291.44  4954.4 1288.65  4990.1 1282.43
  5019.3 1281.57  5022.1 1281.07  5025.3 1281.57  5087.3 1292.77  5236.6 1290.60
  5301.8 1290.07  5549.6 1297.08  5575.9 1298.63  5816.3 1310.90  6015.8 1328.05
  6058.9 1328.44  6133.8 1317.92  6156.8 1317.06  6186.9 1320.81  6321.7 1349.75
  6351.9 1350.00  6382.0 1354.55  6443.9 1378.55  6461.8 1384.08  6482.1 1385.61
#Mann=13,-1,0
  4037.7    0.05       0  4131.9     0.1       0  4233.7    0.05       0
  4335.5     0.1       0  4990.1    0.05       0  5019.3   0.035       0
  5025.3    0.05       0  5236.6     0.1       0  5301.8    0.05       0
  5549.6     0.1       0  5575.9    0.05       0  6015.8     0.1       0
  6186.9    0.16       0
Bank Sta=5019.3,5025.3
Exp/Cntr=0.3,0.1

Type RM Length L Ch R = 1,971,0,0,0
BEGIN DESCRIPTION:
WHITE OAK CREEK 1.0
END DESCRIPTION:
XS GIS Cut Line= 4
      2868809.08     10099125.69      2867541.38     10098986.39
      2867179.19     10098735.63      2866538.40     10098972.45
#Sta/Elev= 30
  3429.9 1389.32  3585.8 1375.14  3671.8 1352.69  3822.9 1339.01  3858.9 1327.39
  4003.9 1301.35  4074.4 1296.71  4125.0 1288.67  4214.1 1279.93  4305.8 1282.32
  4405.2 1275.22  4457.1 1276.64  4497.0 1279.18  4657.9 1279.62  4720.2 1283.77
  4946.5 1277.13  4967.5 1268.00  4985.5 1265.59  4988.3 1265.09  4991.5 1265.59
  5000.7 1265.86  5012.0 1266.11  5039.1 1276.82  5074.9 1280.05  5290.0 1284.02
  5466.4 1301.43  5527.3 1313.99  5679.6 1319.25  5763.4 1318.01  5828.9 1317.16
#Mann=11,-1,0
  3429.9    0.16       0  4125.0     0.1       0  4214.1    0.05       0
  4457.1     0.1       0  4497.0    0.05       0  4720.2     0.1       0
  4985.5    0.07       0  4991.5     0.1       0  5000.7    0.16       0
  5290.0     0.1       0  5763.4    0.16       0
Bank Sta=4985.5,4991.5
Exp/Cntr=0.3,0.1

Chan Stop Cuts=-1