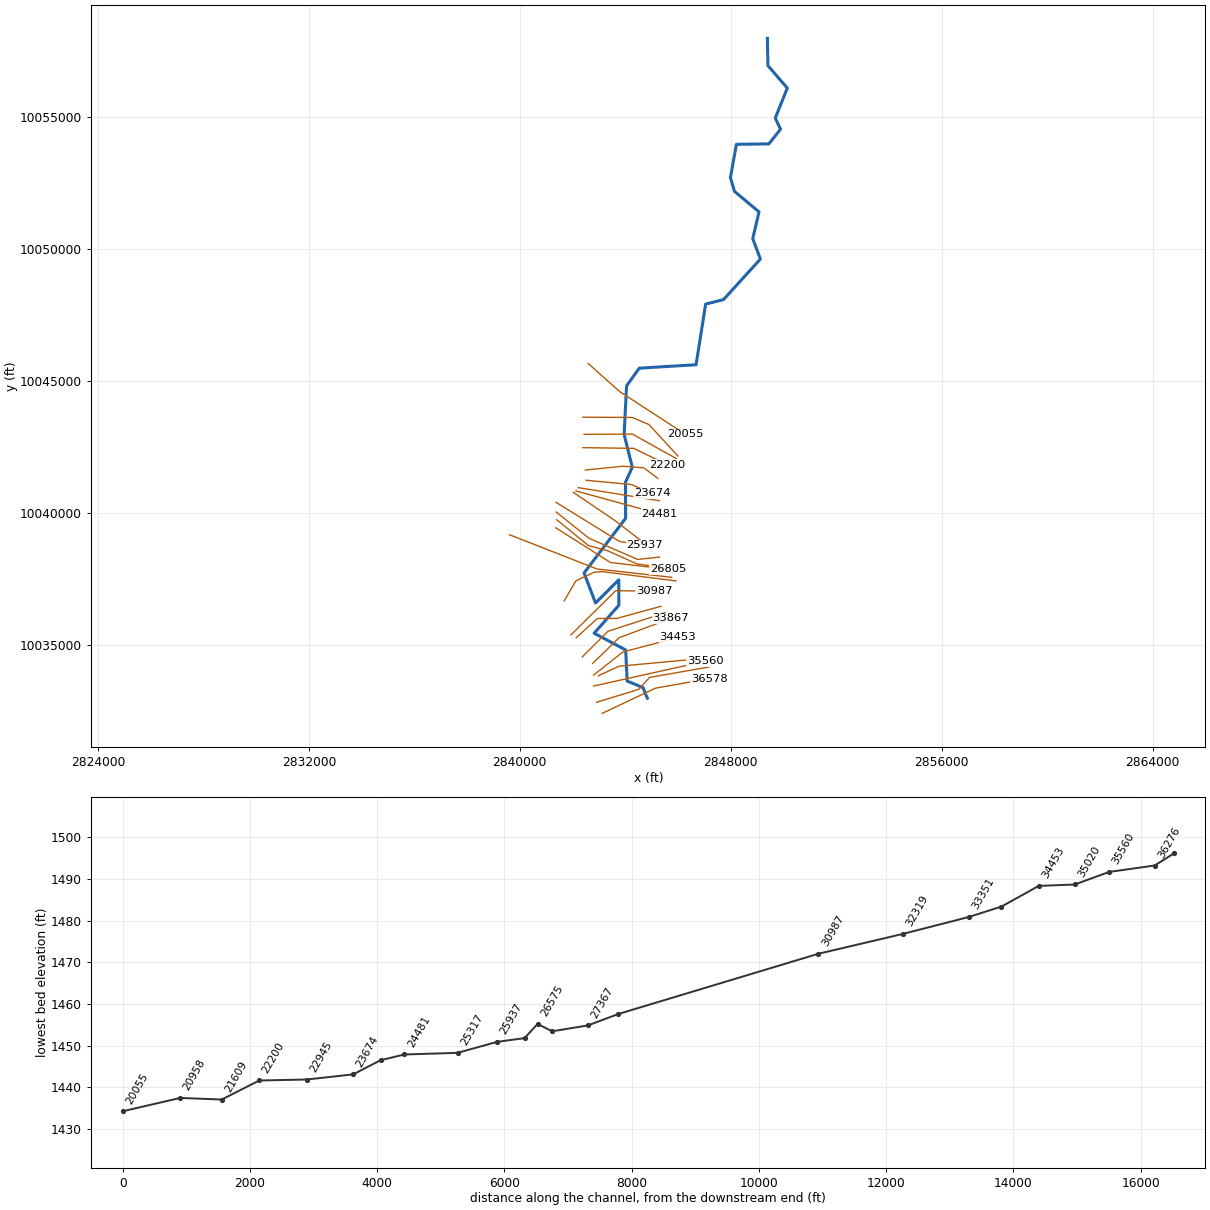
--- WILLIAMS CREEK.prj (project) ---

Proj Title=WILLIAMS CREEK Base Level Engineering
Current Plan=p01
Default Exp/Contr=0.3,0.1
English Units
Geom File=g01
Flow File=f01
Plan File=p01
Y Axis Title=Elevation
X Axis Title(PF)=Main Channel Distance
X Axis Title(XS)=Station
BEGIN DESCRIPTION:
WILLIAMS CREEK
END DESCRIPTION:
DSS File=dss
DSS Export Rating Curves= 0
DSS Export Rating Curve Sorted= 0
DSS Export Volume Flow Curves= 0
DXF OffsetX= 0
DXF OffsetY= 0
DXF ScaleX= 1
DXF ScaleY= 10

--- WILLIAMS CREEK.p01 (plan) ---

Plan Title=Multiple Run
Program Version=4.10
Short Identifier=Multiple Run
Geom File=g01
Flow File=f01
Subcritical Flow
K Sum by GR= 0
Std Step Tol= 0.01
Critical Tol= 0.01
Num of Std Step Trials= 20
Max Error Tol= 0.3
Flow Tol Ratio= 0.001
Split Flow NTrial= 30
Split Flow Tol= 0.02
Split Flow Ratio= 0.02
Log Output Level= 0
Friction Slope Method= 1
Unsteady Friction Slope Method= 2
Unsteady Bridges Friction Slope Method= 1
Parabolic Critical Depth
Global Vel Dist= 1 , 1 , 1
Global Log Level= 0
CheckData=True
Encroach Param=-1 ,0,0, 0
BEGIN DESCRIPTION:
Multiple Run
END DESCRIPTION:
Computation Interval=1HOUR
Output Interval=1HOUR
Run HTab= 0
Run UNet= 0
Run PostProcess= 0
Run WQNet= 0
UNET Theta= 1
UNET Theta Warmup= 1
UNET ZTol= 0.02
UNET ZSATol= 0.05
UNET MxIter= 20
UNET MaxInSteps= 0
UNET DtIC= 0
UNET DtMin= 0
UNET MaxCRTS= 20
UNET WFStab= 2
UNET SFStab= 1
UNET WFX= 1
UNET SFX= 1
UNET DSS MLevel= 4
UNET DZMax Abort= 100
UNET Convert EG Bridges= 0
UNET Use Existing IB Tables=-1
UNET Froude Reduction=False
UNET Froude Limit= 1
UNET Froude Power= 10
UNET Time Slicing=0,0, 5
UNET Junction Losses=0
Instantaneous Interval=1HOUR
DSS File=dss
Write IC File= 0
Write IC File at Sim End=0
Echo Input=False
Echo Parameters=False
Echo Output=False
Write Detailed= 0
WQ AD Non Conservative
WQ ULTIMATE=-1
WQ Max Comp Step=1HOUR
WQ Output Interval=15MIN
WQ Output Selected Increments= 0
WQ Output face flow=0
WQ Output face velocity=0
WQ Output face area=0
WQ Output face dispersion=0
WQ Output cell volume=0
WQ Output cell surface area=0
WQ Output cell continuity=0
WQ Output cumulative cell continuity=0
WQ Output face conc=0
WQ Output face dconc_dx=0
WQ Output face courant=0
WQ Output face peclet=0
WQ Output face adv mass=0
WQ Output face disp mass=0
WQ Output cell mass=0
WQ Output cell source sink temp=0
WQ Output cell source sink nsm=0
WQ Output MaxMinRange=-1
WQ Daily Max Min Mean=-1
WQ Daily Range=0
WQ Daily Time=0
WQ Create Restart=0
WQ Fixed Restart=0
WQ System Summary=0
WQ Use Fixed Temperature=0
Sorting and Armoring Iterations= 10
XS Update Threshold= 0.02
Hydraulics Update Threshold= 0.02
Energy Slope Method= 1
Volume Change Method= 0
XS Weighting Method= 0
Number of US Weighted Cross Sections= 1
Number of DS Weighted Cross Sections= 1
Upstream XS Weight=0.25
Main XS Weight=0.5
Downstream XS Weight=0.25
Number of DS XS's Weighted with US Boundary= 1
Upstream Boundary Weight= 1
Weight of XSs Associated with US Boundary= 0
Number of US XS's Weighted with DS Boundary= 1
Downstream Boundary Weight= 0.5
Weight of XSs Associated with DS Boundary= 0.5
Sediment Output Level= 4
Mass or Volume Output= 0
Output Increment Type= 1
Profile and TS Output Increment= 10
XS Output Flag= 0
XS Output Increment= 10
Disregard all LS=0
Disregard all Conn=0
Disregard all Breaches=0
Disregard all Pumps=0

--- WILLIAMS CREEK.f01 (steady flow) ---

Flow Title=Multiple
Program Version=4.10
Number of Profiles= 7
Profile Names=10-year,25-year,50-year,1pct_min,100-year,1pct_plu,500-year
River Rch & RM=WILLIAMS CREEK,Reach-1         ,36578
    3757    5760    7590    7285    9852   13323   16673
River Rch & RM=WILLIAMS CREEK,Reach-1         ,27367
    6400   10015   13384   13011   17596   23797   30548
River Rch & RM=WILLIAMS CREEK,Reach-1         ,22200
    6392    9978   13310   12914   17465   23620   30202
River Rch & RM=WILLIAMS CREEK,Reach-1         ,17622
    6391    9960   13271   12861   17393   23522   30003
River Rch & RM=WILLIAMS CREEK,Reach-1         ,15463
    6819   10643   14195   13768   18619   25181   32171
River Rch & RM=WILLIAMS CREEK,Reach-1         ,13069
    6819   10643   14195   13768   18619   25181   32171
River Rch & RM=WILLIAMS CREEK,Reach-1         ,10753
    7056   11011   14684   14239   19256   26042   33253
River Rch & RM=WILLIAMS CREEK,Reach-1         ,7372
    7018   10930   14556   14093   19059   25775   32813
River Rch & RM=WILLIAMS CREEK,Reach-1         ,2037
    7218   11244   14976   14500   19610   26520   33764
Boundary for River Rch & Prof#=WILLIAMS CREEK,Reach-1         , 1
Up Type= 0
Dn Type= 3
Dn Slope=0.00318
Boundary for River Rch & Prof#=WILLIAMS CREEK,Reach-1         , 2
Up Type= 0
Dn Type= 3
Dn Slope=0.00318
Boundary for River Rch & Prof#=WILLIAMS CREEK,Reach-1         , 3
Up Type= 0
Dn Type= 3
Dn Slope=0.00318
Boundary for River Rch & Prof#=WILLIAMS CREEK,Reach-1         , 4
Up Type= 0
Dn Type= 3
Dn Slope=0.00318
Boundary for River Rch & Prof#=WILLIAMS CREEK,Reach-1         , 5
Up Type= 0
Dn Type= 3
Dn Slope=0.00318
Boundary for River Rch & Prof#=WILLIAMS CREEK,Reach-1         , 6
Up Type= 0
Dn Type= 3
Dn Slope=0.00318
Boundary for River Rch & Prof#=WILLIAMS CREEK,Reach-1         , 7
Up Type= 0
Dn Type= 3
Dn Slope=0.00318
DSS Import GetInterval= 0
DSS Import GetPeak= 0
DSS Import FillOption= 0

--- WILLIAMS CREEK.g01 (geometry) ---

Geom Title=Existing Conditions
Program Version=4.10

River Reach=WILLIAMS CREEK  ,Reach-1
Reach XY= 30
      2844838.47     10032973.73      2844675.05     10033376.31
      2844071.77     10033625.08      2844017.99     10034803.59
      2842821.57     10035438.69      2843758.79      10036498.7
      2843755.43     10037462.63      2842874.28     10036585.46
      2842438.47     10037723.73      2844016.09     10039799.45
      2844009.53     10041162.94       2844268.6     10041733.78
      2843958.32     10042983.78      2844051.16     10044822.62
      2844534.27     10045491.51      2846686.07     10045621.21
      2847050.78     10047922.77      2847728.47     10048093.73
      2849126.54     10049629.53      2848836.78     10050403.43
      2849073.92     10051416.51      2848143.13     10052197.75
      2847990.09     10052723.43      2848217.04     10053980.88
      2849446.85     10053997.54      2849892.57     10054554.61
       2849689.4     10054973.21      2850147.16     10056113.75
      2849412.16     10056965.31      2849391.31     10058000.51

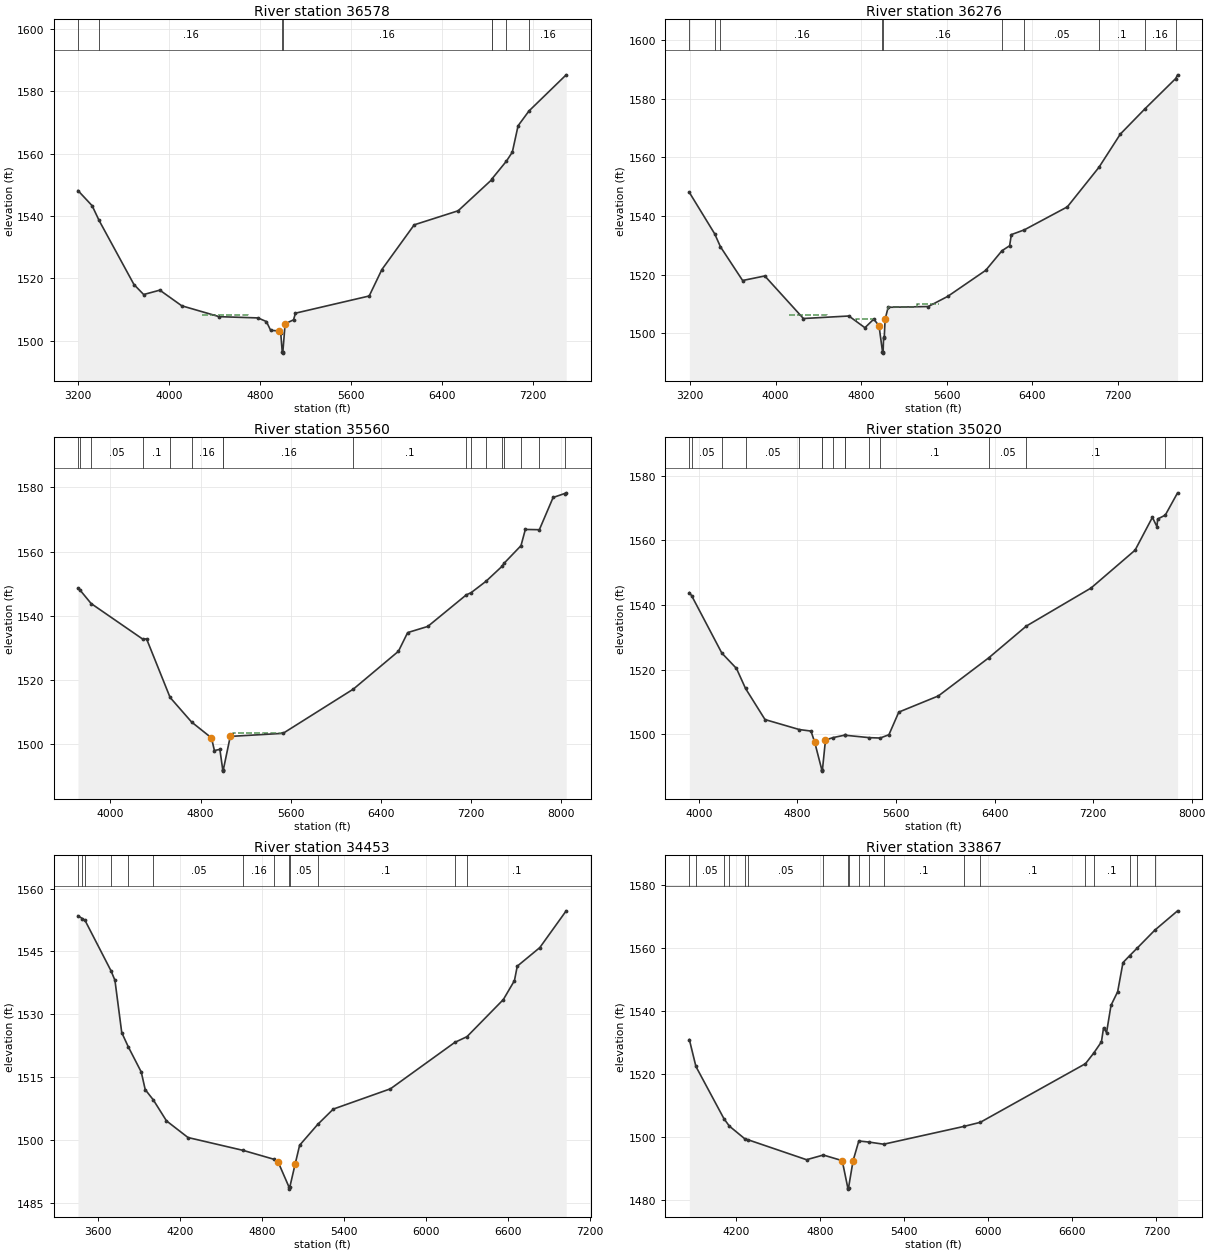
Type RM Length L Ch R = 1 ,36578   ,302,302,302
BEGIN DESCRIPTION:
WILLIAMS CREEK 50.0
END DESCRIPTION:
XS GIS Cut Line= 3
      2843125.81     10032398.93      2845146.82      10033355.3
      2847175.14     10033715.89
#Sta/Elev= 30
  3200.1 1548.15  3324.7  1543.3  3386.1 1538.57    3693 1518.06  3778.3 1514.86
  3920.5 1516.26  4113.6 1511.25  4443.2 1507.77  4784.5 1507.37  4858.3  1506.2
  4895.7  1503.4    4972  1503.2  4984.2 1502.67  4997.3  1496.6  5000.1  1496.1
  5003.3  1496.6  5023.1 1505.51  5096.8 1506.75  5114.1 1508.89  5762.7 1514.39
  5874.4 1522.86  6158.8 1537.17  6545.5 1541.67  6839.3 1551.56  6843.5 1551.91
    6970 1557.55  7022.1 1560.44  7072.9 1568.89  7168.9 1573.63  7496.1 1585.19
#Mann= 8 ,-1 , 0
  3200.1     .16       0  3386.1     .16       0  4997.3     .07       0
  5003.3     .16       0  6839.3      .1       0  6843.5     .05       0
    6970      .1       0  7168.9     .16       0
#XS Ineff= 1 ,-1
  4293.6 4696.95  1508.2
Permanent Ineff=
       T
Bank Sta=4972,5023.1
XS Rating Curve= 0 ,0
Exp/Cntr=0.3,0.1

Type RM Length L Ch R = 1 ,36276   ,716,716,716
BEGIN DESCRIPTION:
WILLIAMS CREEK 49.0
END DESCRIPTION:
XS GIS Cut Line= 4
      2842918.32     10032822.99      2844515.26     10033310.18
      2844921.26      10033761.3      2847175.11     10034157.98
#Sta/Elev= 30
  3192.8 1548.04  3429.9  1533.9  3483.6 1529.49  3690.9 1517.98  3898.3 1519.53
  4259.4 1505.01  4684.4 1505.87  4834.4 1501.87  4916.9 1504.79  4966.2 1502.56
  4998.7  1493.7  5001.5  1493.2  5004.7  1493.7  5008.8 1498.44  5015.5 1498.65
    5023 1504.71  5051.4 1508.83  5426.6  1509.1  5608.6 1512.56    5964 1521.45
  6116.3 1528.16  6187.4 1529.84  6203.6 1533.64  6325.9 1535.28  6727.2 1543.11
  7022.5  1556.6  7223.1 1567.96    7451  1576.5    7740 1586.89  7757.8 1588.16
#Mann= 10 ,-1 , 0
  3192.8      .1       0  3429.9     .05       0  3483.6     .16       0
  4998.7     .07       0  5004.7     .16       0  6116.3      .1       0
  6325.9     .05       0  7022.5      .1       0    7451     .16       0
    7740      .1       0
#XS Ineff= 4 ,-1
 4126.45 4475.29 1506.35 4751.45 4911.34  1504.7 5045.78 5292.88 1508.82
 5321.95 5525.44 1510.05
Permanent Ineff=
       T       T       T       T
Bank Sta=4966.2,5023
XS Rating Curve= 0 ,0
Exp/Cntr=0.3,0.1

Type RM Length L Ch R = 1 ,35560   ,540,540,540
BEGIN DESCRIPTION:
WILLIAMS CREEK 47.0
END DESCRIPTION:
XS GIS Cut Line= 2
      2842801.06     10033436.51      2847032.47     10034374.82
#Sta/Elev= 30
  3711.8 1548.61  3728.6 1548.09  3828.7 1543.83  4289.9 1532.68  4320.6 1532.86
  4529.7  1514.6  4720.1 1506.96  4897.3    1502    4923 1498.08  4971.7 1498.42
  4996.8 1492.16  4999.5 1491.66  5002.8 1492.16    5064 1502.47  5532.4 1503.42
  6157.2 1517.21  6556.7 1528.96  6638.6 1534.78  6817.4  1536.7    7160 1546.55
  7201.2 1547.19  7333.4 1550.73  7477.3 1555.44  7493.2 1556.31  7644.8 1561.84
  7683.4 1566.89  7807.8 1566.81  7929.9 1576.84  8032.9 1578.08    8046 1578.29
#Mann= 17 ,-1 , 0
  3711.8     .05       0  3728.6      .1       0  3828.7     .05       0
  4289.9      .1       0  4529.7     .05       0  4720.1     .16       0
  4996.8     .07       0  5002.8     .16       0  6157.2      .1       0
    7160     .05       0  7201.2      .1       0  7333.4     .05       0
  7477.3      .1       0  7493.2     .05       0  7644.8      .1       0
  7807.8     .16       0  8032.9     .05       0
#XS Ineff= 1 ,-1
  5084.3 5520.35  1503.5
Permanent Ineff=
       T
Bank Sta=4897.3,5064
XS Rating Curve= 0 ,0
Exp/Cntr=0.3,0.1

Type RM Length L Ch R = 1 ,35020   ,567,567,567
BEGIN DESCRIPTION:
WILLIAMS CREEK 46.0
END DESCRIPTION:
XS GIS Cut Line= 3
      2842981.49     10033824.47      2843757.38     10034185.35
      2846852.03     10034474.06
#Sta/Elev= 30
    3922 1543.87  3940.1 1542.95  4185.5 1525.18  4304.7  1520.4  4378.1 1514.23
  4536.3  1504.6  4814.9 1501.51  4909.4 1501.04  4939.5 1497.62  4996.8 1489.15
  4999.5 1488.65  5002.8 1489.15  5027.2 1498.28    5089 1499.02  5185.8  1499.8
  5187.1 1499.75  5384.5    1499  5471.2 1498.89  5542.1  1499.9  5622.5 1506.91
  5943.8 1511.91  6352.6 1523.69  6657.5 1533.51  7183.4 1545.29  7540.7 1556.99
  7681.4 1567.15  7718.6 1564.23  7723.7 1566.62    7786 1567.84  7885.8 1574.73
#Mann= 15 ,-1 , 0
    3922      .1       0  3940.1     .05       0  4185.5      .1       0
  4378.1     .05       0  4814.9     .16       0  4996.8     .07       0
  5002.8     .16       0    5089      .1       0  5185.8     .16       0
  5187.1      .1       0  5384.5     .05       0  5471.2      .1       0
  6352.6     .05       0  6657.5      .1       0    7786     .16       0
Bank Sta=4939.5,5027.2
XS Rating Curve= 0 ,0
Exp/Cntr=0.3,0.1

Type RM Length L Ch R = 1 ,34453   ,586,586,586
BEGIN DESCRIPTION:
WILLIAMS CREEK 45.0
END DESCRIPTION:
XS GIS Cut Line= 3
      2842801.02     10033851.53      2843910.76     10034726.69
      2845994.14     10035276.84
#Sta/Elev= 30
  3456.5 1553.51  3489.5 1552.83  3508.2 1552.41    3698 1540.39  3726.8 1538.12
  3776.5 1525.65  3823.5 1522.31  3919.2 1516.24  3948.1 1512.04    4007 1509.61
  4103.5 1504.59  4260.7 1500.62  4666.2 1497.53  4889.9 1495.42  4920.6 1494.69
  4998.9 1488.81  5001.6 1488.31  5004.9 1488.81  5043.3 1494.21  5076.5 1498.78
  5208.5 1503.74  5322.5  1507.4  5740.4 1512.24  6210.6 1523.31  6299.7 1524.68
  6565.4 1533.53  6646.4 1538.04  6667.1 1541.49  6831.8 1545.92  7024.6 1554.69
#Mann= 13 ,-1 , 0
  3456.5      .1       0  3489.5     .16       0  3508.2      .1       0
    3698     .05       0  3823.5      .1       0    4007     .05       0
  4666.2     .16       0  4889.9     .05       0  4998.9     .04       0
  5004.9     .05       0  5208.5      .1       0  6210.6     .05       0
  6299.7      .1       0
Bank Sta=4920.6,5043.3
XS Rating Curve= 0 ,0
Exp/Cntr=0.3,0.1

Type RM Length L Ch R = 1 ,33867   ,516,516,516
BEGIN DESCRIPTION:
WILLIAMS CREEK 44.0
END DESCRIPTION:
XS GIS Cut Line= 3
      2842764.95     10034293.63       2843766.4     10035268.03
      2845723.72     10035998.64
#Sta/Elev= 30
  3864.4 1530.94  3911.4 1522.37  4111.5 1505.76  4149.8 1503.42  4259.1 1499.41
  4281.9 1499.08  4701.4 1492.71  4821.2  1494.2  4956.1 1492.41  4995.5 1483.85
  4998.3 1483.35  5001.5 1483.85  5033.8 1492.42  5074.6 1498.67  5144.5 1498.34
  5252.1 1497.64  5826.6 1503.32  5942.2 1504.61  6693.3 1523.27    6753 1526.69
  6807.1 1530.21  6822.3 1534.69  6843.6 1533.15  6875.6 1541.84    6923 1546.16
    6961 1555.42  7009.2 1557.66  7062.2 1560.03  7187.8 1565.73  7350.9  1571.9
#Mann= 19 ,-1 , 0
  3864.4      .1       0  3911.4     .05       0  4111.5     .16       0
  4149.8     .05       0  4259.1      .1       0  4281.9     .05       0
  4821.2     .16       0  4995.5     .07       0  5001.5     .16       0
  5074.6      .1       0  5144.5     .05       0  5252.1      .1       0
  5826.6     .05       0  5942.2      .1       0  6693.3     .05       0
    6753      .1       0  7009.2     .16       0  7062.2      .1       0
  7187.8     .16       0
Bank Sta=4956.1,5033.8
XS Rating Curve= 0 ,0
Exp/Cntr=0.3,0.1

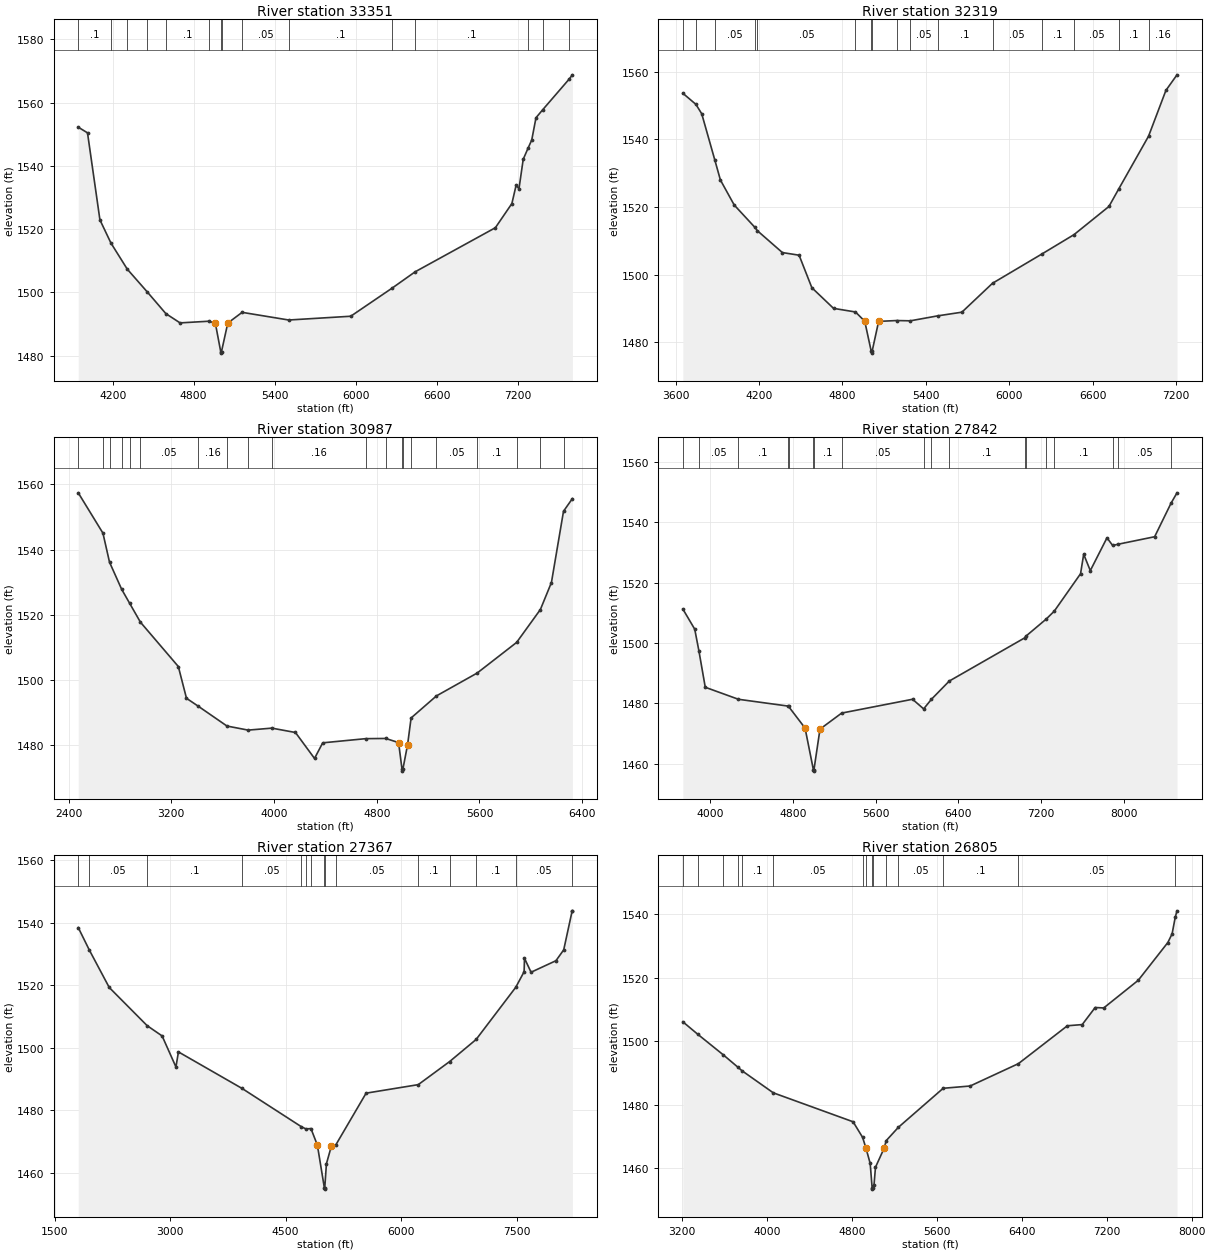
Type RM Length L Ch R = 1 ,33351   ,1032,1032,1032
BEGIN DESCRIPTION:
WILLIAMS CREEK 43.0
END DESCRIPTION:
XS GIS Cut Line= 3
      2842367.94     10034537.21      2843342.36     10035511.63
      2845515.06     10036214.83
#Sta/Elev= 30
  3944.7 1552.21  4013.3 1550.43  4105.3 1522.94  4186.9 1515.62    4308 1507.37
  4456.3 1500.17  4594.1 1493.32  4699.2  1490.4  4913.5 1490.93  4960.9 1490.26
  5000.3 1481.35    5003 1480.85  5006.3 1481.35  5052.8 1490.34    5159 1493.73
  5504.4 1491.31  5963.9  1492.5  6272.2 1501.43  6441.4 1506.54  7035.8 1520.46
    7158 1528.09  7189.6  1533.9  7210.6 1532.76  7242.1 1542.08  7277.2 1545.52
  7305.2 1548.16  7336.7  1555.2  7385.8 1557.69  7582.7 1567.41  7606.4 1568.75
#Mann= 15 ,-1 , 0
  3944.7      .1       0  4186.9     .05       0    4308      .1       0
  4456.3     .16       0  4594.1      .1       0  4913.5     .16       0
  5000.3     .07       0  5006.3     .16       0    5159     .05       0
  5504.4      .1       0  6272.2     .05       0  6441.4      .1       0
  7277.2     .16       0  7385.8      .1       0  7582.7     .16       0
Bank Sta=4960.9,5052.8
XS Rating Curve= 0 ,0
Exp/Cntr=0.3,0.1

Type RM Length L Ch R = 1 ,32319   ,1332,1332,1332
BEGIN DESCRIPTION:
WILLIAMS CREEK 42.0
END DESCRIPTION:
XS GIS Cut Line= 4
      2842142.36       10035268.      2842945.37     10035998.83
      2843676.18     10035998.83      2845353.85     10036458.84
#Sta/Elev= 30
  3651.2 1553.61  3745.2 1550.33    3787 1547.55    3881 1533.91  3921.4 1527.98
  4020.7 1520.59  4170.5 1513.94  4187.7 1512.98  4367.4 1506.53  4487.7 1505.75
  4579.6 1496.14  4735.6 1490.04  4893.6 1488.97  4960.1 1486.24  5007.1 1477.31
  5009.8 1476.81  5013.1 1477.31  5060.1 1486.19  5189.6 1486.44  5288.2 1486.36
    5486 1487.83  5659.3 1488.91  5879.8 1497.46  6233.1 1506.06  6465.9 1511.82
  6717.5 1520.15  6787.9 1525.32  7002.6 1540.92  7127.7 1554.47  7207.4 1559.06
#Mann= 16 ,-1 , 0
  3651.2     .05       0  3745.2      .1       0    3881     .05       0
  4170.5      .1       0  4187.7     .05       0  4893.6     .16       0
  5007.1     .07       0  5013.1     .16       0  5189.6      .1       0
  5288.2     .05       0    5486      .1       0  5879.8     .05       0
  6233.1      .1       0  6465.9     .05       0  6787.9      .1       0
  7002.6     .16       0
Bank Sta=4960.1,5060.1
XS Rating Curve= 0 ,0
Exp/Cntr=0.3,0.1

Type RM Length L Ch R = 1 ,30987   ,3145,3145,3145
BEGIN DESCRIPTION:
WILLIAMS CREEK 41.0
END DESCRIPTION:
XS GIS Cut Line= 3
      2841943.88     10035376.28      2843640.09     10037054.44
      2845101.67     10037027.38
#Sta/Elev= 30
  2475.5 1557.41  2667.8 1545.04  2718.9 1536.15  2813.4 1527.83  2876.2 1523.49
  2959.6 1517.74  3254.8 1504.13  3318.4 1494.38  3408.6 1491.99  3633.7 1485.87
  3798.6 1484.62    3983 1485.23    4167 1483.89  4315.4 1475.93  4379.1 1480.72
    4714    1482    4870 1482.06    4970 1480.79    4997 1472.54  4999.7 1472.04
    5003 1472.54    5040 1480.14  5067.5 1488.35    5265 1495.12  5581.7 1502.12
  5889.1 1511.52  6074.3 1521.62  6160.2  1529.9  6254.3 1551.76  6323.4 1555.64
#Mann= 20 ,-1 , 0
  2475.5      .1       0  2667.8     .05       0  2718.9      .1       0
  2813.4     .05       0  2876.2      .1       0  2959.6     .05       0
  3408.6     .16       0  3633.7      .1       0  3798.6     .16       0
    3983     .16       0    4714     .05       0    4870     .05       0
    4997    .035       0    5003     .05       0  5067.5     .16       0
    5265     .05       0  5581.7      .1       0  5889.1     .05       0
  6074.3      .1       0  6254.3     .16       0
Bank Sta=4970,5040
XS Rating Curve= 0 ,0
Exp/Cntr=0.3,0.1

Type RM Length L Ch R = 1 ,27842   ,475,475,475
BEGIN DESCRIPTION:
WILLIAMS CREEK 40.0
END DESCRIPTION:
XS GIS Cut Line= 5
      2841683.64     10036663.35      2842124.59     10037420.26
      2842805.38     10037749.18       2843116.8     10037776.23
      2845922.76     10037424.36
#Sta/Elev= 30
  3738.2 1511.27  3852.8 1504.61  3893.2 1497.43  3954.6 1485.37  4275.1 1481.39
  4752.3 1479.15  4759.4 1479.01  4918.4 1471.86  4998.6  1458.1  5001.3  1457.6
  5004.6  1458.1  5062.7 1471.51    5272 1476.82  5956.7  1481.4  6063.8 1478.21
  6138.9 1481.39  6311.4 1487.43  7041.4 1501.76  7049.1 1502.22    7246 1507.91
  7325.3 1510.57  7579.3 1522.97  7609.5 1529.42  7673.5    1524  7834.5 1534.86
  7889.6 1532.32  7940.5 1532.73  8294.8 1535.22  8453.8 1546.36  8510.8 1549.76
#Mann= 18 ,-1 , 0
  3738.2      .1       0  3893.2     .05       0  4275.1      .1       0
  4752.3     .05       0  4759.4      .1       0  4998.6     .07       0
  5004.6      .1       0    5272     .05       0  6063.8     .12       0
  6138.9     .05       0  6311.4      .1       0  7041.4     .05       0
  7049.1      .1       0    7246     .05       0  7325.3      .1       0
  7889.6     .16       0  7940.5     .05       0  8453.8     .16       0
Bank Sta=4918.4,5062.7
XS Rating Curve= 0 ,0
Exp/Cntr=0.3,0.1

Type RM Length L Ch R = 1 ,27367   ,562,562,562
BEGIN DESCRIPTION:
WILLIAMS CREEK 39.0
END DESCRIPTION:
XS GIS Cut Line= 3
      2839607.09      10039174.7      2842927.33     10037875.47
       2845760.3      10037559.7
#Sta/Elev= 30
    1808 1538.44  1950.8 1531.31  2210.4  1519.3  2702.7  1507.1    2897 1503.82
  3076.6  1493.9  3108.8 1498.72  3935.5 1487.04  4705.5 1474.81  4764.7 1474.11
  4829.3 1474.23  4912.9 1468.94  5002.9 1455.38  5005.7 1454.88  5008.9 1455.38
  5030.4 1462.99  5095.4 1468.69  5152.6 1469.03  5545.6 1485.54  6222.7 1488.26
  6630.8 1495.65  6973.8 1502.69  7489.5 1519.39    7597 1524.34    7602 1528.62
  7687.4 1524.17  8010.8 1527.86  8111.4 1531.33  8221.1 1543.79  8223.9 1543.79
#Mann= 15 ,-1 , 0
    1808      .1       0  1950.8     .05       0  2702.7      .1       0
  3935.5     .05       0  4705.5      .1       0  4764.7     .05       0
  4829.3      .1       0  5002.9     .07       0  5008.9      .1       0
  5152.6     .05       0  6222.7      .1       0  6630.8     .05       0
  6973.8      .1       0  7489.5     .05       0  8221.1     .16       0
Bank Sta=4912.9,5095.4
XS Rating Curve= 0 ,0
Exp/Cntr=0.3,0.1

Type RM Length L Ch R = 1 ,26805   ,230,230,230
BEGIN DESCRIPTION:
WILLIAMS CREEK 38.0
END DESCRIPTION:
XS GIS Cut Line= 3
       2841366.5     10039436.32       2843441.6     10038119.08
      2845624.26     10037866.54
#Sta/Elev= 30
  3207.1 1506.19  3347.1 1502.27  3587.8 1495.78  3725.6 1491.89  3763.4 1490.79
    4059 1483.81  4810.8 1474.69    4900  1469.8  4931.2 1466.49  4971.8 1461.57
    4990 1453.97  4992.7 1453.47    4996 1453.97  5008.2 1454.91  5021.7 1460.36
  5102.2 1466.29  5123.1 1468.76  5237.2 1472.94  5659.6 1485.24  5913.5 1485.96
  6368.1    1493  6829.6 1504.94  6969.3 1505.31  7091.3 1510.69  7171.8 1510.55
    7497 1519.26  7775.8 1531.16  7816.1  1533.9  7845.4 1539.09  7862.2 1541.15
#Mann= 15 ,-1 , 0
  3207.1      .1       0  3347.1     .05       0  3587.8      .1       0
  3725.6     .05       0  3763.4      .1       0    4059     .05       0
    4900      .1       0  4931.2     .05       0    4990     .04       0
    4996     .05       0  5123.1      .1       0  5237.2     .05       0
  5659.6      .1       0  6368.1     .05       0  7845.4     .16       0
Bank Sta=4931.2,5102.2
XS Rating Curve= 0 ,0
Exp/Cntr=0.3,0.1

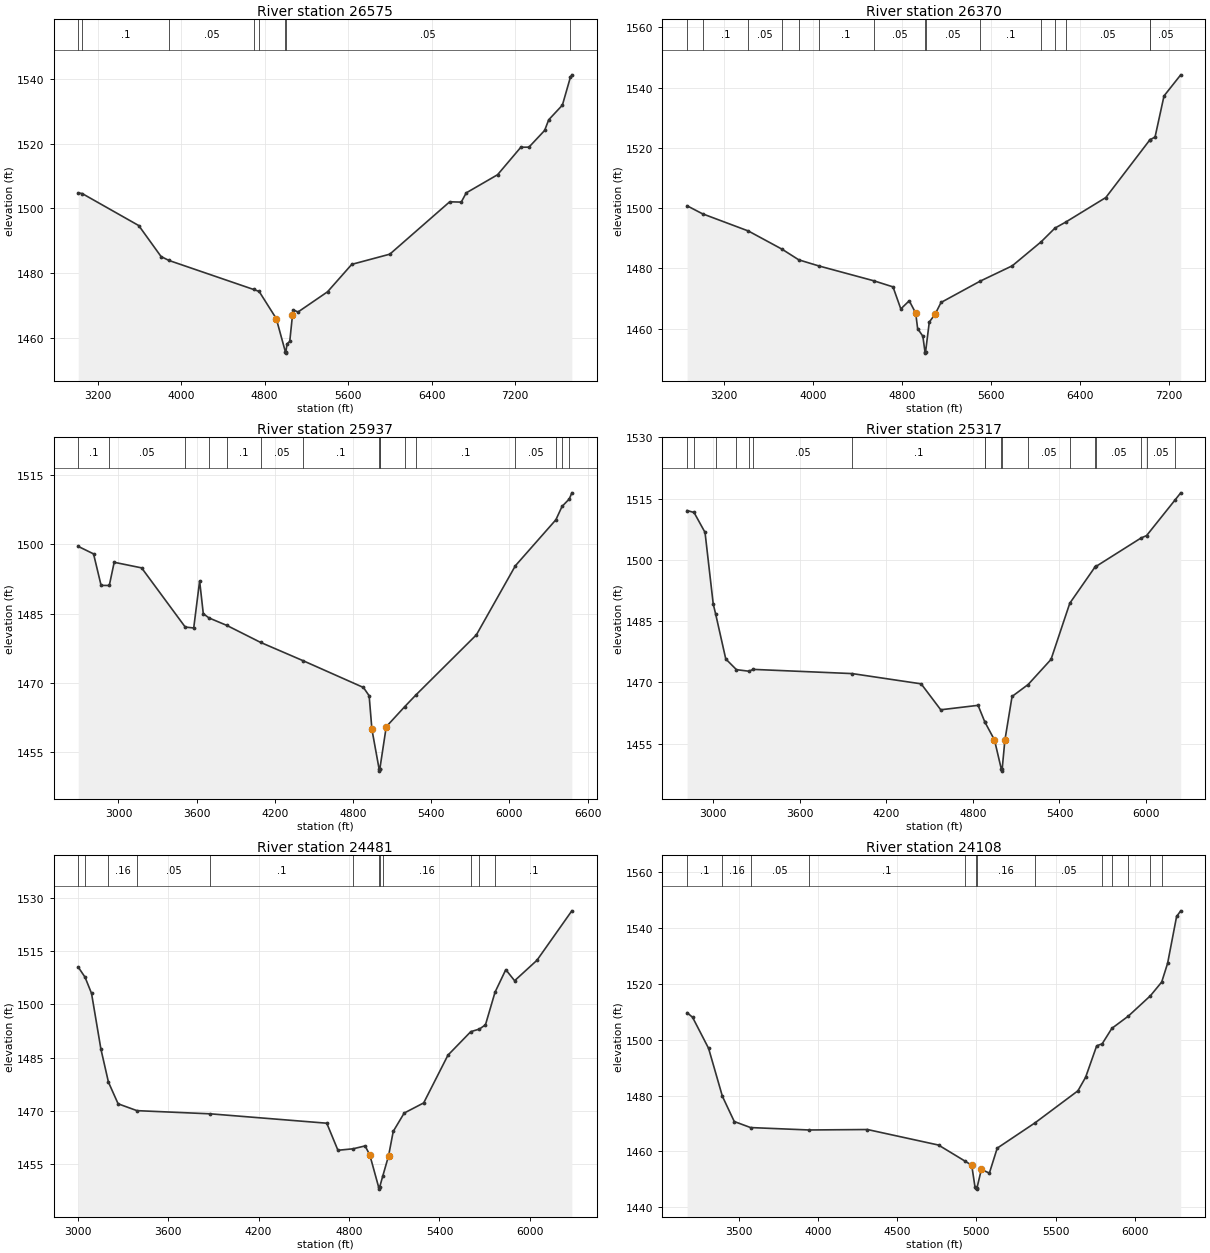
Type RM Length L Ch R = 1 ,26575   ,205,205,205
BEGIN DESCRIPTION:
WILLIAMS CREEK 37.0
END DESCRIPTION:
XS GIS Cut Line= 5
       2841402.1      10039743.6      2842603.51     10038764.41
      2843339.62     10038563.02      2844457.67     10038063.02
      2845638.19     10037903.31
#Sta/Elev= 30
  3013.6  1504.8  3052.4 1504.57  3593.5 1494.68  3807.5 1485.09  3883.6 1483.88
  4694.2 1474.91  4746.6 1474.31  4910.8 1465.92  4997.4 1455.72  5000.1 1455.22
  5003.4 1455.72  5014.4 1458.09  5040.1 1458.83  5066.3 1466.96  5074.6 1468.59
  5119.4 1467.94  5402.1 1474.19  5634.4 1482.68  5998.8 1485.83  6572.4 1502.03
  6683.4 1501.94  6730.7 1504.79  7031.3 1510.41  7254.1 1518.91  7331.8 1518.94
  7482.1 1524.11    7521  1527.4  7652.2 1531.94  7728.3  1540.5  7742.7 1541.31
#Mann= 8 ,-1 , 0
  3013.6     .05       0  3052.4      .1       0  3883.6     .05       0
  4694.2      .1       0  4746.6     .05       0  4997.4     .04       0
  5003.4     .05       0  7728.3     .16       0
Bank Sta=4910.8,5066.3
XS Rating Curve= 0 ,0
Exp/Cntr=0.3,0.1

Type RM Length L Ch R = 1 ,26370   ,433,433,433
BEGIN DESCRIPTION:
Mapping XS 49ca12a8
END DESCRIPTION:
XS GIS Cut Line= 4
      2841381.29     10040035.24      2842624.34     10039042.19
      2844471.56     10038236.63       2845297.9     10038326.91
#Sta/Elev= 30
  2865.4 1500.73  3003.8 1498.08  3416.7 1492.36  3718.2 1486.34  3869.6 1482.79
    4048 1480.79  4543.9 1475.84  4716.3 1473.82  4786.5  1466.5  4862.2 1469.21
    4920 1465.14  4937.9 1459.95  4984.6 1457.45  5003.4 1452.33  5006.1 1451.83
  5009.4 1452.33  5042.5 1462.14  5094.8 1464.76  5148.2 1468.65  5500.1 1475.73
  5788.7 1480.82  6048.4  1488.8  6172.4 1493.34  6267.8  1495.3  6629.5 1503.48
  7027.6 1522.73  7030.3 1522.72  7072.1 1523.57  7152.6 1537.21  7302.9 1544.21
#Mann= 15 ,-1 , 0
  2865.4     .05       0  3003.8      .1       0  3416.7     .05       0
  3718.2      .1       0  3869.6     .05       0    4048      .1       0
  4543.9     .05       0  5003.4    .035       0  5009.4     .05       0
  5500.1      .1       0  6048.4     .16       0  6172.4      .1       0
  6267.8     .05       0  7027.6      .1       0  7030.3     .05       0
Bank Sta=4920,5094.8
XS Rating Curve= 0 ,0
Exp/Cntr=0.3,0.1

Type RM Length L Ch R = 1 ,25937   ,620,620,620
BEGIN DESCRIPTION:
WILLIAMS CREEK 36.0
END DESCRIPTION:
XS GIS Cut Line= 3
       2841375.5     10040401.72      2843775.43     10038922.06
       2844731.6     10038768.71
#Sta/Elev= 30
  2691.2 1499.56  2808.8 1497.94  2866.7 1491.12  2929.6  1491.1  2967.2 1496.12
  3177.7 1494.91  3512.4  1482.1  3577.5 1481.91  3622.8 1492.08  3650.9    1485
  3694.5 1484.08  3831.6 1482.46  4090.2 1478.79  4415.4 1474.84  4879.8 1469.03
  4923.6 1467.24  4944.9 1459.96  4999.8 1451.43  5002.6 1450.93  5005.8 1451.43
  5005.9 1451.45  5054.9 1460.54  5196.2 1464.87  5282.7 1467.42  5746.6 1480.42
  6045.7 1495.37  6356.5 1505.32  6403.9 1508.21  6459.5 1509.83    6479 1511.15
#Mann= 16 ,-1 , 0
  2691.2      .1       0  2929.6     .05       0  3512.4      .1       0
  3694.5     .05       0  3831.6      .1       0  4090.2     .05       0
  4415.4      .1       0  4999.8     .07       0  5005.8      .1       0
  5005.9     .16       0  5196.2     .05       0  5282.7      .1       0
  6045.7     .05       0  6356.5      .1       0  6403.9     .05       0
  6459.5      .1       0
Bank Sta=4944.9,5054.9
XS Rating Curve= 0 ,0
Exp/Cntr=0.3,0.1

Type RM Length L Ch R = 1 ,25317   ,836,836,836
BEGIN DESCRIPTION:
WILLIAMS CREEK 35.0
END DESCRIPTION:
XS GIS Cut Line= 3
      2842034.14     10040780.64        2843604.     10039716.02
      2844811.66     10038787.75
#Sta/Elev= 30
  2820.2  1512.1  2868.2 1511.63  2944.3 1506.75  3001.2 1489.19  3017.8 1486.79
    3088 1475.76  3162.1 1473.14    3247 1472.77    3279 1473.21  3964.6 1472.18
  4441.7 1469.67  4577.4 1463.32  4836.1 1464.41  4882.4 1460.38  4882.9 1460.34
  4949.7 1455.94  4997.1  1448.8  4999.9  1448.3  5003.1  1448.8  5021.7 1455.83
  5071.5 1466.58  5183.1 1469.51  5341.5 1475.65  5471.4  1489.4  5646.8 1498.31
  5652.7 1498.41  5965.6 1505.39  6003.4 1505.96  6201.5 1514.72  6240.2 1516.44
#Mann= 18 ,-1 , 0
  2820.2      .1       0  2868.2     .05       0  3017.8      .1       0
  3162.1     .16       0    3247      .1       0    3279     .05       0
  3964.6      .1       0  4882.4     .05       0  4882.9     .16       0
  4997.1     .07       0  5003.1     .16       0  5183.1     .05       0
  5471.4     .16       0  5646.8      .1       0  5652.7     .05       0
  5965.6      .1       0  6003.4     .05       0  6201.5      .1       0
Bank Sta=4949.7,5021.7
XS Rating Curve= 0 ,0
Exp/Cntr=0.3,0.1

Type RM Length L Ch R = 1 ,24481   ,373,373,373
BEGIN DESCRIPTION:
WILLIAMS CREEK 34.0
END DESCRIPTION:
XS GIS Cut Line= 2
      2842133.33      10040834.8        2845291.      10039968.7
#Sta/Elev= 30
  3003.6 1510.49  3048.8 1507.65  3091.9 1503.08  3154.1 1487.38  3204.1 1478.06
  3268.2 1471.96  3393.2 1470.03    3881 1469.13  4652.3 1466.49  4726.4 1458.86
  4827.1 1459.28  4906.5 1460.09  4937.6 1457.56  4996.8 1448.41  4999.6 1447.91
  5002.8 1448.41  5023.1  1451.5  5062.1 1457.27  5093.2 1464.19  5165.8 1469.35
  5295.1 1472.21  5456.1 1485.67  5607.5 1492.29    5665 1493.03    5705 1494.23
  5768.6 1503.44  5839.8 1509.77  5898.3 1506.65  6046.4 1512.41  6277.9 1526.35
#Mann= 12 ,-1 , 0
  3003.6     .05       0  3048.8      .1       0  3204.1     .16       0
  3393.2     .05       0    3881      .1       0  4827.1     .05       0
  4996.8    .035       0  5002.8     .05       0  5023.1     .16       0
  5607.5      .1       0    5665     .05       0  5768.6      .1       0
Bank Sta=4937.6,5062.1
XS Rating Curve= 0 ,0
Exp/Cntr=0.3,0.1

Type RM Length L Ch R = 1 ,24108   ,434,434,434
BEGIN DESCRIPTION:
WILLIAMS CREEK 33.0
END DESCRIPTION:
XS GIS Cut Line= 2
      2842214.53     10040961.11      2845291.16     10040464.88
#Sta/Elev= 30
  3173.6 1509.62    3208 1507.98  3309.2 1496.87  3396.4 1479.72  3471.3 1470.71
  3574.3 1468.55  3942.6 1467.69  4312.1 1467.85  4760.7  1462.3  4929.2 1456.52
  4970.5 1455.06  4990.7 1447.46  4997.9 1447.04  5000.6 1446.54  5003.9 1447.04
  5031.2 1453.56  5081.9 1452.27  5131.4 1461.19  5370.4 1470.25  5640.9 1481.69
  5689.6 1486.55  5759.4 1497.78    5794  1498.5  5855.2 1504.02  5959.2  1508.4
  6098.8 1515.69  6169.8 1520.58  6207.1 1527.28  6263.9 1544.02    6290 1546.04
#Mann= 13 ,-1 , 0
  3173.6      .1       0  3396.4     .16       0  3574.3     .05       0
  3942.6      .1       0  4929.2     .16       0  4997.9     .07       0
  5003.9     .16       0  5370.4     .05       0    5794      .1       0
  5855.2     .05       0  5959.2      .1       0  6098.8     .05       0
  6169.8      .1       0
Bank Sta=4970.5,5031.2
XS Rating Curve= 0 ,0
Exp/Cntr=0.3,0.1

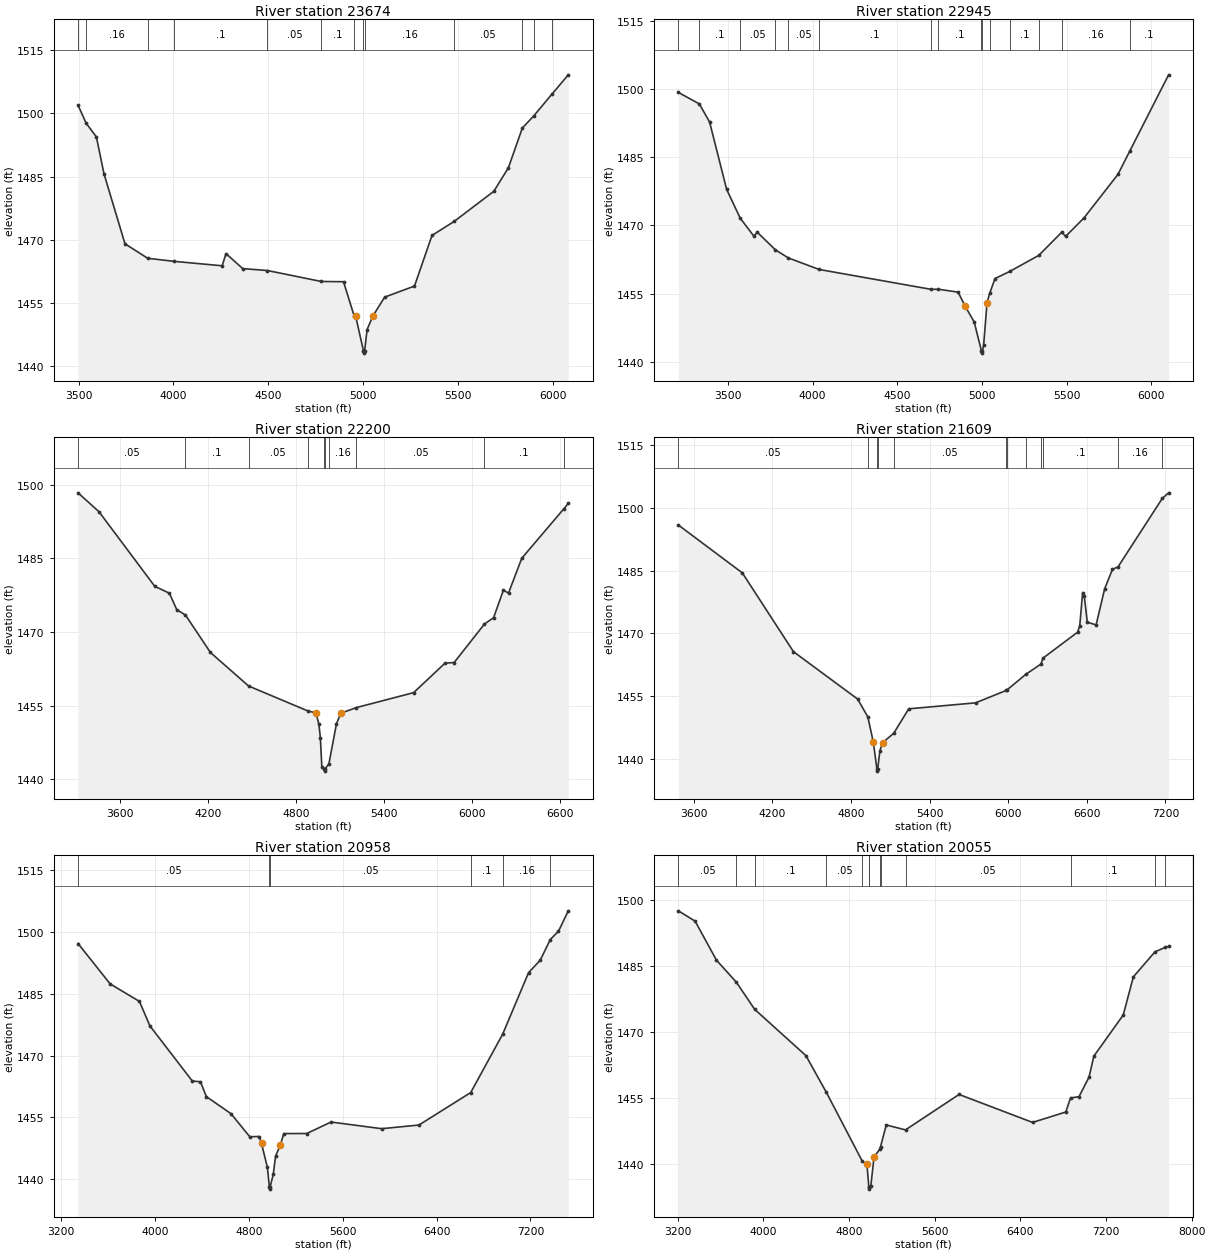
Type RM Length L Ch R = 1 ,23674   ,729,729,729
BEGIN DESCRIPTION:
WILLIAMS CREEK 32.0
END DESCRIPTION:
XS GIS Cut Line= 3
      2842512.26      10041240.8      2844226.54     10041078.39
      2845020.46     10040744.59
#Sta/Elev= 30
  3497.1 1501.91  3539.4 1497.69  3593.7  1494.4  3633.9 1485.64  3744.4 1469.06
  3864.2 1465.63  4003.7  1464.9  4256.4 1463.85  4276.8 1466.74  4364.7 1463.18
  4495.1 1462.73  4778.4 1460.13    4896 1460.07  4951.8 1451.99  4959.8 1451.93
  5001.2 1443.64    5004 1443.14  5007.2 1443.64  5020.1 1448.72  5050.2  1451.9
  5112.5 1456.41  5269.9 1459.05  5362.2 1471.05    5479 1474.37  5687.8 1481.51
  5764.5 1487.07  5838.2 1496.51  5899.5 1499.45    5995 1504.59  6080.3 1509.13
#Mann= 13 ,-1 , 0
  3497.1      .1       0  3539.4     .16       0  3864.2     .05       0
  4003.7      .1       0  4495.1     .05       0  4778.4      .1       0
  4951.8     .16       0  5001.2     .07       0  5007.2     .16       0
    5479     .05       0  5838.2      .1       0  5899.5     .05       0
    5995      .1       0
Bank Sta=4959.8,5050.2
XS Rating Curve= 0 ,0
Exp/Cntr=0.3,0.1

Type RM Length L Ch R = 1 ,22945   ,745,745,745
BEGIN DESCRIPTION:
WILLIAMS CREEK 31.0
END DESCRIPTION:
XS GIS Cut Line= 4
      2842485.21     10041628.75      2843919.78     10041773.11
      2844704.72     10041709.96      2845237.01       10041313.
#Sta/Elev= 30
  3208.3 1499.24  3331.8 1496.72  3392.5 1492.75    3493 1477.94  3573.3 1471.59
  3653.8 1467.64  3673.9  1468.5  3780.4 1464.64  3857.2 1462.85  4037.7 1460.32
  4699.4 1455.94  4743.2 1455.96  4859.5 1455.32  4899.6 1452.31  4954.4 1448.75
  4996.9 1442.41  4999.7 1441.91  5002.9 1442.41    5010 1443.64    5030 1453.04
  5045.9 1455.08    5077  1458.3  5165.7 1459.91  5335.6 1463.41    5471  1468.5
  5494.1 1467.59  5602.6 1471.66  5802.7 1481.22  5872.4 1486.34  6101.6 1503.11
#Mann= 15 ,-1 , 0
  3208.3     .05       0  3331.8      .1       0  3573.3     .05       0
  3780.4      .1       0  3857.2     .05       0  4037.7      .1       0
  4699.4     .05       0  4743.2      .1       0  4996.9     .07       0
  5002.9      .1       0  5045.9     .16       0  5165.7      .1       0
  5335.6     .05       0    5471     .16       0  5872.4      .1       0
Bank Sta=4899.6,5030
XS Rating Curve= 0 ,0
Exp/Cntr=0.3,0.1

Type RM Length L Ch R = 1 ,22200   ,591,591,591
BEGIN DESCRIPTION:
WILLIAMS CREEK 29.0
END DESCRIPTION:
XS GIS Cut Line= 3
      2842394.98     10042476.85      2844325.79     10042449.78
      2845596.41     10041827.99
#Sta/Elev= 30
  3313.3 1498.31  3456.8 1494.44  3836.8 1479.29  3936.8 1477.88  3986.8 1474.54
  4046.4 1473.44  4216.9 1465.82  4477.2    1459  4880.4 1453.94  4936.9 1453.52
  4956.9 1451.22  4966.9 1448.49  4976.9 1442.61  4993.9 1442.18  4996.7 1441.68
  4999.9 1442.18  5025.2 1443.16    5077 1451.34    5107 1453.47    5213 1454.61
  5603.5 1457.65    5818 1463.66    5880 1463.78  6086.7 1471.61  6149.1  1472.9
  6215.9 1478.48  6251.3 1477.93  6341.3 1484.99  6629.6  1495.1  6658.9 1496.16
#Mann= 10 ,-1 , 0
  3313.3     .05       0  4046.4      .1       0  4477.2     .05       0
  4880.4      .1       0  4993.9     .07       0  4999.9      .1       0
  5025.2     .16       0    5213     .05       0  6086.7      .1       0
  6629.6     .05       0
Bank Sta=4936.9,5107
XS Rating Curve= 0 ,0
Exp/Cntr=0.3,0.1

Type RM Length L Ch R = 1 ,21609   ,651,651,651
BEGIN DESCRIPTION:
WILLIAMS CREEK 28.0
END DESCRIPTION:
XS GIS Cut Line= 3
       2842440.1      10042982.1      2844271.65     10042991.12
      2845940.81     10042061.81
#Sta/Elev= 30
    3482  1495.9  3970.4 1484.46  4360.4 1465.65  4850.4 1454.32  4928.2 1450.06
  4970.4 1443.99  4997.4 1437.61  5000.1 1437.11  5003.4 1437.61  5020.4 1441.96
  5040.4 1443.89  5125.5 1446.14  5240.4 1451.99  5750.4 1453.42  5986.5 1456.41
  5988.1 1456.43  6134.2 1460.24  6249.9 1462.69  6264.4 1464.08  6530.1 1470.32
    6546 1471.89  6567.8 1479.77  6580.4 1478.94  6603.3 1472.68  6670.7 1472.04
  6735.9 1480.66  6795.4 1485.32  6837.7 1485.89  7175.5 1502.24    7224 1503.59
#Mann= 12 ,-1 , 0
    3482     .05       0  4928.2     .16       0  4997.4     .07       0
  5003.4     .16       0  5125.5     .05       0  5986.5      .1       0
  5988.1     .05       0  6134.2      .1       0  6249.9     .05       0
  6264.4      .1       0  6837.7     .16       0  7175.5     .05       0
Bank Sta=4970.4,5040.4
XS Rating Curve= 0 ,0
Exp/Cntr=0.3,0.1

Type RM Length L Ch R = 1 ,20958   ,903,903,903
BEGIN DESCRIPTION:
WILLIAMS CREEK 27.0
END DESCRIPTION:
XS GIS Cut Line= 4
      2842395.04     10043631.71      2844262.63     10043622.68
      2844903.22     10043352.02      2845994.21     10042161.83
#Sta/Elev= 30
  3344.4 1497.24  3617.8 1487.42  3867.8 1483.15  3956.5 1477.21  4317.8  1463.8
  4387.8 1463.61  4437.8    1460  4647.8 1455.85  4807.8 1450.24  4887.8  1450.3
  4907.8 1448.62  4957.8 1442.78  4974.8    1438  4977.6  1437.5  4980.8    1438
  5007.8 1441.08  5027.8 1445.54  5067.9 1448.23  5097.9 1451.01  5294.1 1451.03
    5500 1453.82  5931.4  1452.2  6249.6 1453.09  6690.6 1460.99    6963  1475.2
  7183.8 1490.17  7283.1 1493.17  7368.1  1498.2  7438.5 1500.23    7522 1505.19
#Mann= 6 ,-1 , 0
  3344.4     .05       0  4974.8    .035       0  4980.8     .05       0
  6690.6      .1       0    6963     .16       0  7368.1     .05       0
Bank Sta=4907.8,5067.9
XS Rating Curve= 0 ,0
Exp/Cntr=0.3,0.1

Type RM Length L Ch R = 1 ,20055   ,648,648,648
BEGIN DESCRIPTION:
WILLIAMS CREEK 26.0
END DESCRIPTION:
XS GIS Cut Line= 3
      2842593.54     10045670.72      2843784.45     10044606.12
      2846283.56     10042982.15
#Sta/Elev= 30
  3206.8  1497.6  3363.7 1495.24  3562.2 1486.39  3748.1 1481.37  3919.3  1475.2
  4397.8 1464.67  4587.8 1456.36  4925.5  1440.6  4967.3 1440.02  4985.4 1434.81
  4988.1 1434.31  4991.4 1434.81  5003.5 1434.93  5033.8 1441.59  5085.8 1443.34
  5094.9 1443.99  5148.5  1448.9  5327.9 1447.78  5827.9 1455.84  6514.4 1449.48
  6824.5 1451.85  6868.8 1455.04  6948.2 1455.34  7041.7 1459.79  7086.8 1464.56
  7361.1 1473.91  7455.5 1482.58  7657.4 1488.28  7754.7  1489.3  7784.6 1489.51
#Mann= 13 ,-1 , 0
  3206.8     .05       0  3748.1     .16       0  3919.3      .1       0
  4587.8     .05       0  4925.5      .1       0  4985.4     .07       0
  4991.4      .1       0  5085.8     .16       0  5094.9      .1       0
  5327.9     .05       0  6868.8      .1       0  7657.4     .16       0
  7754.7      .1       0
Bank Sta=4967.3,5033.8
XS Rating Curve= 0 ,0
Exp/Cntr=0.3,0.1