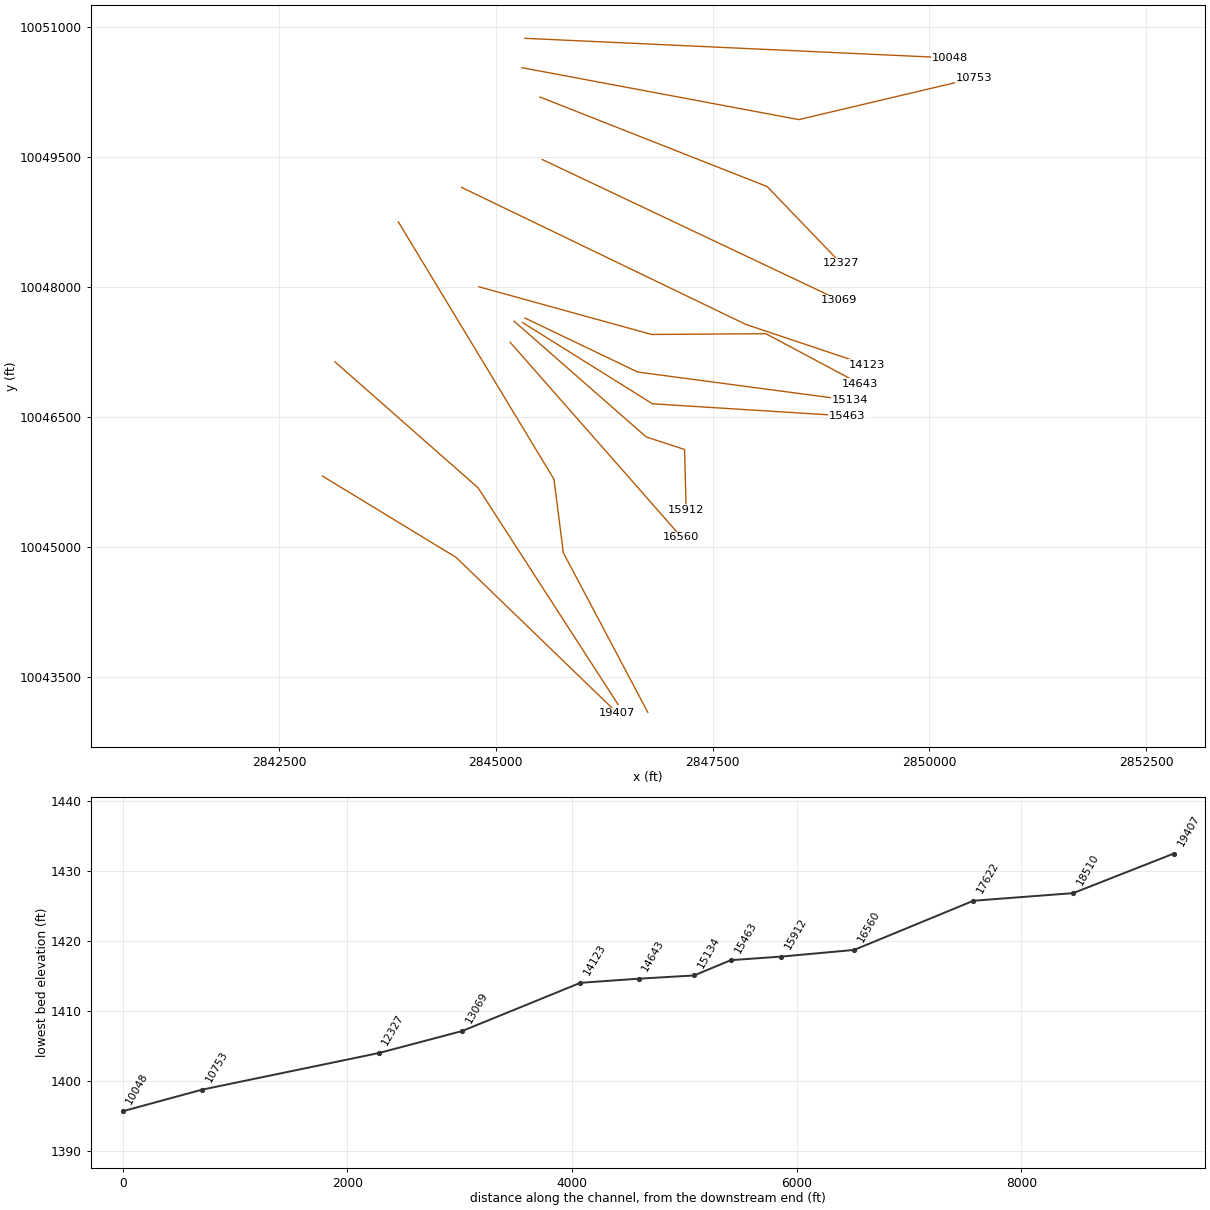
HEC-RAS study WILLIAMS CREEK.prj: WILLIAMS CREEK Base Level Engineering

--- WILLIAMS CREEK.g01 (geometry) --- (continued)

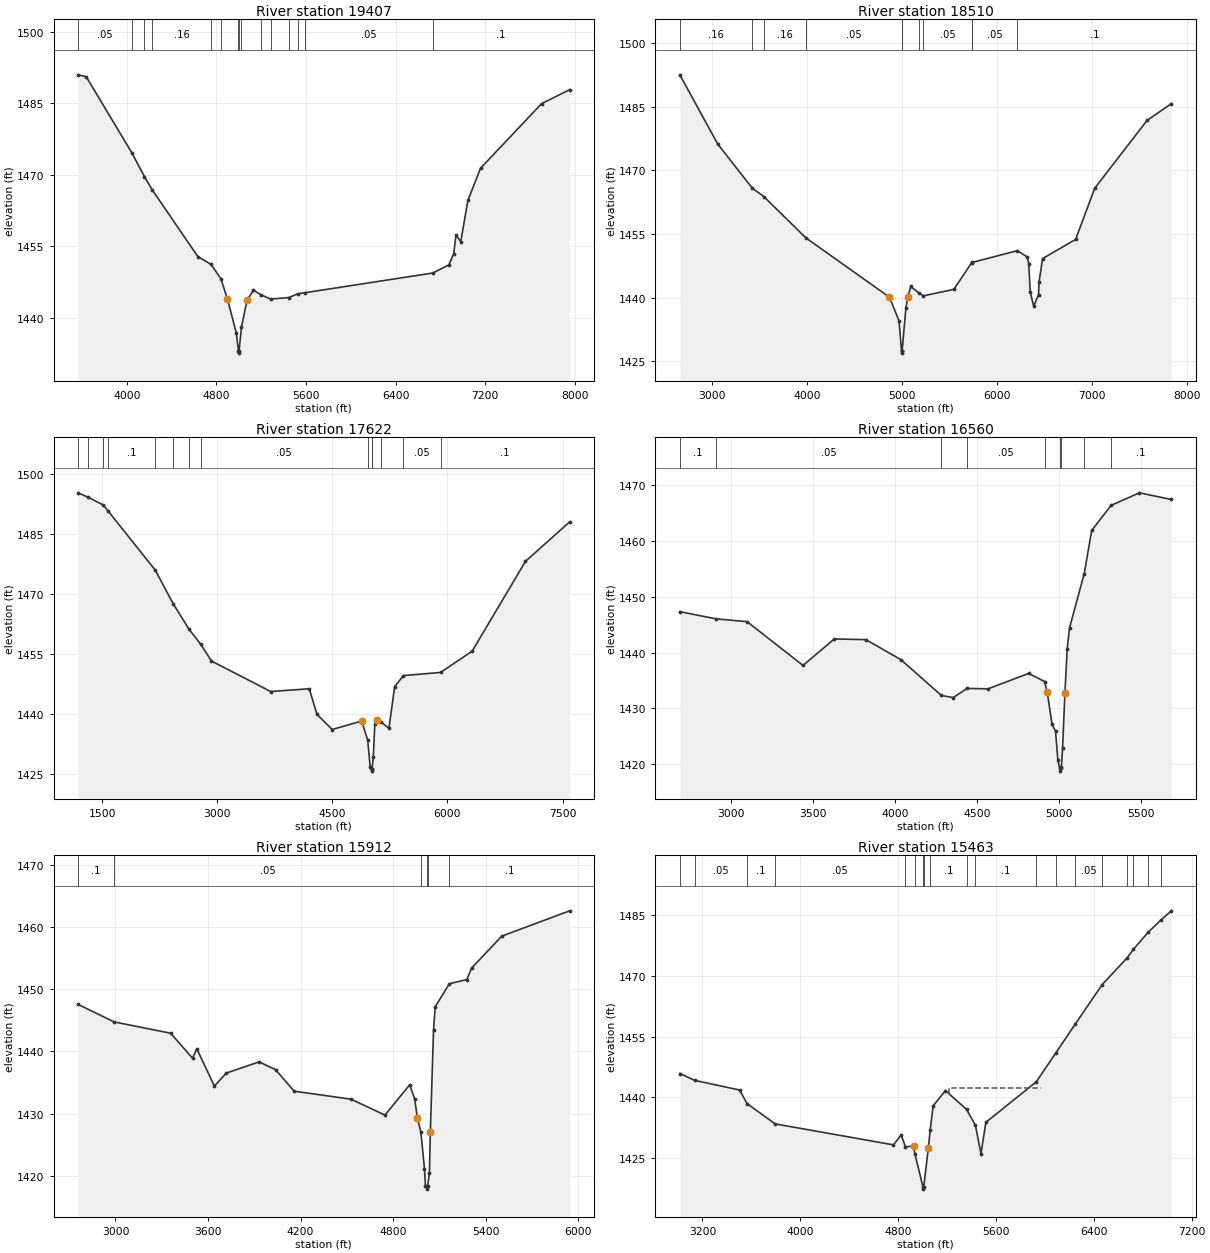
Type RM Length L Ch R = 1 ,19407   ,897,897,897
BEGIN DESCRIPTION:
WILLIAMS CREEK 25.0
END DESCRIPTION:
XS GIS Cut Line= 3
      2842999.49     10045815.12      2844542.32     10044876.79
      2846400.89     10043081.38
#Sta/Elev= 30
  3564.5 1490.98  3636.9 1490.58  4046.7 1474.51  4156.8 1469.62  4224.4  1466.9
  4634.7 1452.79  4752.2 1451.18  4839.9 1448.14  4897.6 1443.96  4977.6 1436.77
    4996 1433.05  4998.7 1432.55    5002 1433.05  5023.6 1437.99  5072.6 1443.63
  5130.7 1445.78  5195.6 1444.82  5282.9 1443.91  5445.7 1444.21  5524.5 1444.99
  5588.8 1445.23  6731.9 1449.37  6876.1 1451.08  6918.6  1453.4  6939.7 1457.34
  6982.1 1455.96  7045.9 1464.62  7158.8 1471.37  7703.4 1484.92  7954.4 1487.87
#Mann= 15 ,-1 , 0
  3564.5     .05       0  4046.7     .16       0  4156.8     .05       0
  4224.4     .16       0  4752.2     .05       0  4839.9      .1       0
    4996     .07       0    5002      .1       0  5023.6     .16       0
  5195.6     .05       0  5282.9      .1       0  5445.7     .05       0
  5524.5      .1       0  5588.8     .05       0  6731.9      .1       0
Bank Sta=4897.6,5072.6
XS Rating Curve= 0 ,0
Exp/Cntr=0.3,0.1

Type RM Length L Ch R = 1 ,18510   ,888,888,888
BEGIN DESCRIPTION:
WILLIAMS CREEK 24.0
END DESCRIPTION:
XS GIS Cut Line= 3
      2843143.88     10047132.35      2844794.95     10045679.77
      2846409.96     10043180.57
#Sta/Elev= 30
  2661.6 1492.54  3060.7 1476.21  3424.5 1465.81  3545.7 1463.83  3988.8 1454.07
  4867.9  1440.1  4968.8 1434.53  4995.8 1427.39  4998.6 1426.89  5001.8 1427.39
  5041.4 1437.52  5062.5 1440.19  5092.8 1442.61  5175.4 1441.14  5224.3  1440.4
  5546.5 1441.93  5733.6 1448.22  5741.4 1448.29  6216.4 1451.07  6320.4 1449.54
  6335.1 1448.02  6350.3 1441.36  6386.6 1437.95    6438 1440.64    6444 1443.77
  6480.3 1449.19  6827.9 1453.71  7030.5 1465.82  7580.7 1481.79  7836.3 1485.74
#Mann= 11 ,-1 , 0
  2661.6     .16       0  3424.5      .1       0  3545.7     .16       0
  3988.8     .05       0  4995.8    .035       0  5001.8     .05       0
  5175.4      .1       0  5224.3     .05       0  5733.6      .1       0
  5741.4     .05       0  6216.4      .1       0
Bank Sta=4867.9,5062.5
XS Rating Curve= 0 ,0
Exp/Cntr=0.3,0.1

Type RM Length L Ch R = 1 ,17622   ,1062,1062,1062
BEGIN DESCRIPTION:
WILLIAMS CREEK 22.0
END DESCRIPTION:
XS GIS Cut Line= 4
       2843874.7     10048747.32      2845670.11     10045779.02
      2845778.38     10044930.92      2846752.79     10043090.37
#Sta/Elev= 30
  1186.3 1495.23  1321.5 1494.07  1514.7 1492.19  1574.1 1490.77  2191.7 1475.95
  2425.6 1467.56  2627.1 1461.34  2783.7 1457.45  2924.4 1453.27  3696.6 1445.66
    4199 1446.35  4299.9 1439.97  4497.9 1436.18  4882.5  1438.3  4961.2 1433.55
    4993  1426.9  5010.5  1426.3  5013.3  1425.8  5016.5  1426.3  5033.7 1429.25
  5053.8  1437.5  5077.9 1438.55  5130.6 1438.11  5237.5 1436.49  5312.3 1446.87
  5426.4 1449.63  5910.6 1450.42  6321.8 1455.72  7017.5 1478.13  7592.9 1487.98
#Mann= 14 ,-1 , 0
  1186.3     .16       0  1321.5      .1       0  1514.7     .16       0
  1574.1      .1       0  2191.7     .16       0  2425.6     .05       0
  2627.1      .1       0  2783.7     .05       0  4961.2     .16       0
  5010.5     .07       0  5016.5     .16       0  5130.6      .1       0
  5426.4     .05       0  5910.6      .1       0
Bank Sta=4882.5,5077.9
XS Rating Curve= 0 ,0
Exp/Cntr=0.3,0.1

Type RM Length L Ch R = 1 ,16560   ,648,648,648
BEGIN DESCRIPTION:
WILLIAMS CREEK 21.0
END DESCRIPTION:
XS GIS Cut Line= 2
      2845164.89     10047357.89      2847140.75     10045111.37
#Sta/Elev= 30
  2691.5 1447.33  2911.5 1446.04  3100.7 1445.54  3441.3  1437.7    3632 1442.44
  3823.7 1442.32  4036.2 1438.75  4283.4 1432.33    4355 1431.94  4440.5 1433.58
  4567.5 1433.51  4815.2 1436.27  4911.8 1434.81  4927.7  1432.9  4957.5 1427.13
  4978.4 1425.94  4992.6 1420.71  5003.8 1419.27  5006.6 1418.77  5009.8 1419.27
  5014.3 1419.59  5021.1  1422.9  5035.3 1432.69  5049.5 1440.72  5063.7 1444.45
  5152.5 1454.08  5198.5 1461.88  5316.8 1466.36  5488.8 1468.61  5683.3 1467.42
#Mann= 9 ,-1 , 0
  2691.5      .1       0  2911.5     .05       0  4283.4      .1       0
  4440.5     .05       0  4911.8     .16       0  5003.8     .07       0
  5009.8     .16       0  5152.5     .05       0  5316.8      .1       0
Bank Sta=4927.7,5035.3
XS Rating Curve= 0 ,0
Exp/Cntr=0.3,0.1

Type RM Length L Ch R = 1 ,15912   ,449,449,449
BEGIN DESCRIPTION:
WILLIAMS CREEK 20.0
END DESCRIPTION:
XS GIS Cut Line= 4
      2845209.96     10047601.54      2846734.74     10046266.22
      2847176.84     10046121.86      2847194.86      10045427.9
#Sta/Elev= 30
  2757.9 1447.59  2991.1 1444.77  3357.4 1442.95  3499.8 1438.92  3527.3 1440.44
  3641.2 1434.43    3719 1436.53  3931.6 1438.33  4037.9 1437.07  4158.4  1433.6
  4526.7 1432.32  4746.9 1429.75  4907.6 1434.64  4939.5 1432.35    4957 1429.27
  4979.5 1427.06  5003.2 1421.08  5009.6 1418.33  5017.1 1418.32  5019.8 1417.82
  5023.1 1418.32  5035.1 1420.34  5041.1 1427.04  5061.7 1443.39  5072.7 1447.22
  5164.4 1450.92  5277.9  1451.6    5308 1453.43  5504.1 1458.59    5944 1462.67
#Mann= 6 ,-1 , 0
  2757.9      .1       0  2991.1     .05       0  4979.5     .16       0
  5017.1     .07       0  5023.1     .16       0  5164.4      .1       0
Bank Sta=4957,5041.1
XS Rating Curve= 0 ,0
Exp/Cntr=0.3,0.1

Type RM Length L Ch R = 1 ,15463   ,329,329,329
BEGIN DESCRIPTION:
Mapping XS 09957f2b
END DESCRIPTION:
XS GIS Cut Line= 3
      2845306.99     10047586.11        2846807.     10046648.61
      2849051.82     10046507.98
#Sta/Elev= 30
  3015.4 1445.88  3137.4 1444.18  3503.8  1441.8  3564.8 1438.45  3794.8 1433.43
  4760.9 1428.25  4825.8 1430.72  4859.5 1427.74    4926 1427.97    4937 1426.03
  5003.2 1417.81  5005.9 1417.31  5009.2 1417.81  5046.3 1427.36  5061.9 1431.87
  5086.3 1437.88  5186.5 1441.66  5359.2 1437.01    5432 1433.07  5477.1 1426.07
  5517.2 1433.81  5929.4 1443.83  6090.8 1451.05  6246.3 1458.01  6467.4 1467.83
  6672.2 1474.46  6723.8  1476.6  6846.1 1480.85  6945.2 1483.73  7033.5 1486.08
#Mann= 19 ,-1 , 0
  3015.4      .1       0  3137.4     .05       0  3564.8      .1       0
  3794.8     .05       0  4859.5      .1       0    4937     .16       0
  5003.2     .07       0  5009.2     .16       0  5061.9      .1       0
  5359.2     .05       0    5432      .1       0  5929.4     .05       0
  6090.8      .1       0  6246.3     .05       0  6467.4      .1       0
  6672.2     .05       0  6723.8      .1       0  6846.1     .05       0
  6945.2      .1       0
#XS Ineff= 1 ,-1
 5218.75 5964.84 1442.18
Permanent Ineff=
       T
Bank Sta=4926,5046.3
XS Rating Curve= 0 ,0
Exp/Cntr=0.3,0.1

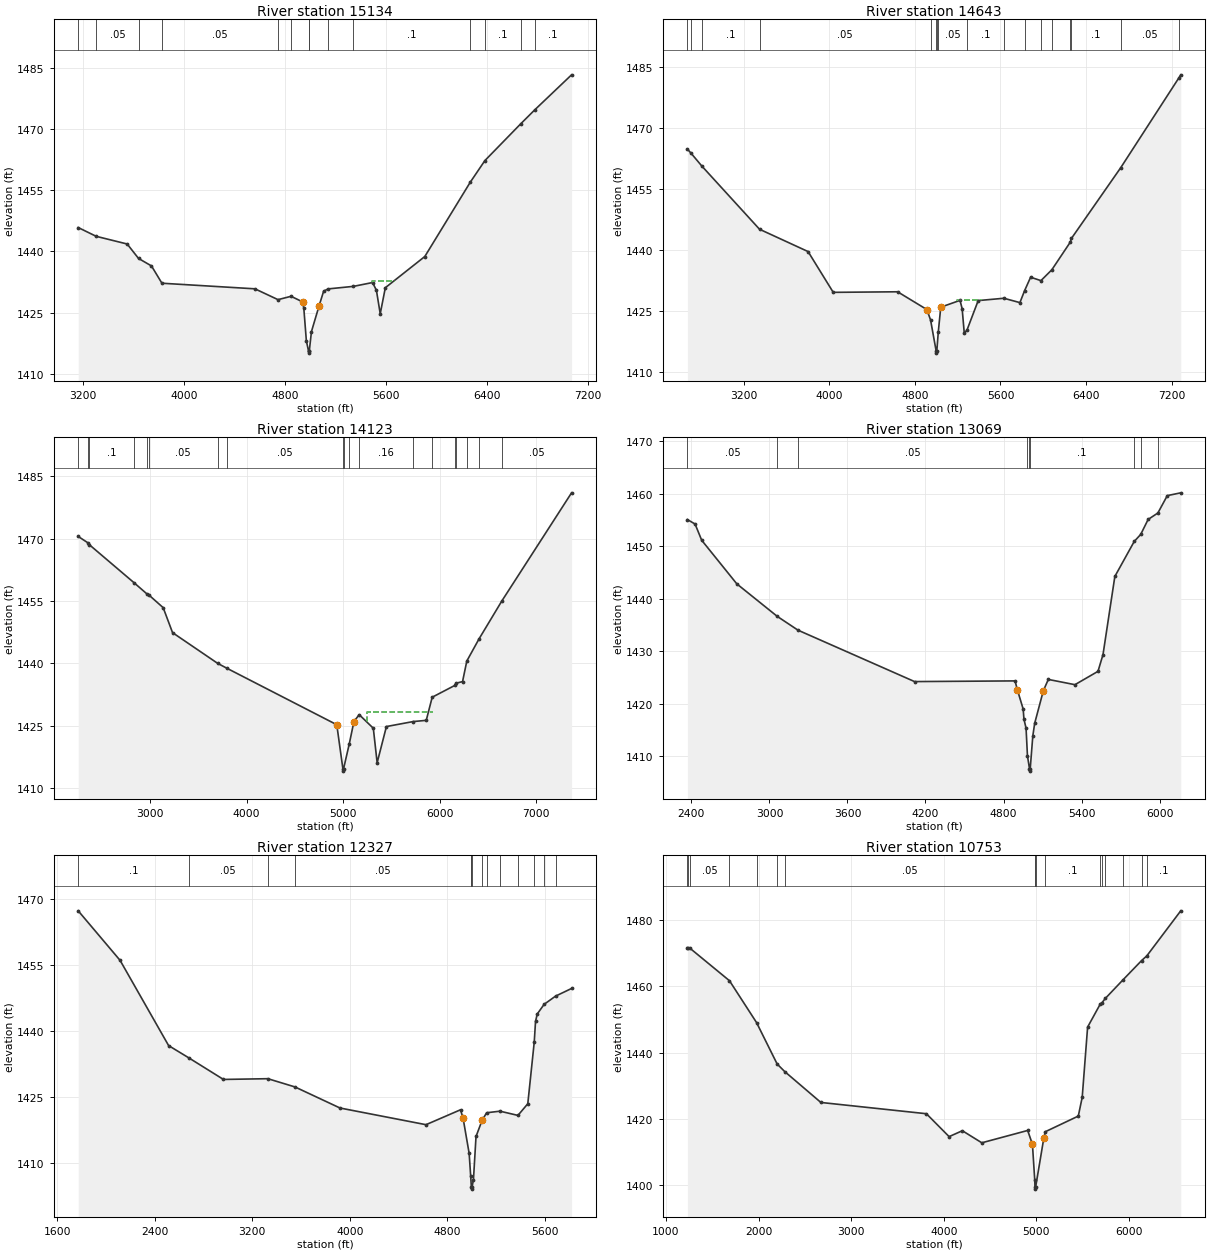
Type RM Length L Ch R = 1 ,15134   ,491,491,491
BEGIN DESCRIPTION:
WILLIAMS CREEK 18.0
END DESCRIPTION:
XS GIS Cut Line= 3
      2845336.27     10047637.62       2846635.5     10047015.07
      2849080.54     10046690.27
#Sta/Elev= 30
  3162.9 1445.86  3305.4 1443.71  3550.8 1441.83  3640.5  1438.3  3743.2 1436.46
  3825.9 1432.23  4562.5 1430.86  4745.2 1428.21  4848.7 1429.03  4939.5 1427.67
  4949.6 1426.11  4969.7 1418.17  4986.9 1415.62  4989.7 1415.12  4992.9 1415.62
  5010.1 1420.39  5070.6  1426.7  5106.6 1430.28    5142 1430.84  5342.2 1431.46
  5494.3  1432.4  5524.6  1430.5  5554.8 1424.75  5595.2 1431.13  5907.9 1438.77
  6268.6 1456.99    6384 1462.26  6668.2 1471.27  6778.7 1474.67  7070.1 1483.24
#Mann= 14 ,-1 , 0
  3162.9      .1       0  3305.4     .05       0  3640.5      .1       0
  3825.9     .05       0  4745.2      .1       0  4848.7     .16       0
  4986.9     .07       0  4992.9     .16       0    5142     .05       0
  5342.2      .1       0  6268.6     .05       0    6384      .1       0
  6668.2     .05       0  6778.7      .1       0
#XS Ineff= 1 ,-1
 5488.68 5670.12 1432.75
Permanent Ineff=
       T
Bank Sta=4939.5,5070.6
XS Rating Curve= 0 ,0
Exp/Cntr=0.3,0.1

Type RM Length L Ch R = 1 ,14643   ,520,520,520
BEGIN DESCRIPTION:
WILLIAMS CREEK 17.0
END DESCRIPTION:
XS GIS Cut Line= 4
      2844804.01     10047998.49       2846797.9     10047448.14
      2848115.16     10047457.17      2849197.86     10046879.72
#Sta/Elev= 30
  2672.9 1464.75    2707 1463.74  2807.7 1460.59  3347.5 1445.07  3801.3 1439.59
  4036.5 1429.58  4638.2 1429.72  4911.9 1425.36  4946.7 1422.79  4998.9 1415.16
  5001.7 1414.66  5004.9 1415.16  5018.6 1419.82  5041.9 1425.94  5221.9 1427.61
  5241.9 1425.56  5261.9 1419.48  5288.2  1420.4  5391.9 1427.56  5631.9 1428.13
  5781.9 1427.06  5825.4 1429.98  5881.9 1433.29  5978.6 1432.46  6080.3 1435.12
    6253 1441.91  6263.1  1442.8  6725.5 1460.22  7269.1 1482.27  7285.7 1482.98
#Mann= 17 ,-1 , 0
  2672.9      .1       0    2707     .05       0  2807.7      .1       0
  3347.5     .05       0  4946.7      .1       0  4998.9     .07       0
  5004.9      .1       0  5018.6     .05       0  5288.2      .1       0
  5631.9     .05       0  5825.4      .1       0  5978.6     .05       0
  6080.3      .1       0    6253     .05       0  6263.1      .1       0
  6725.5     .05       0  7269.1      .1       0
#XS Ineff= 1 ,-1
 5196.95 5428.89 1427.81
Permanent Ineff=
       T
Bank Sta=4911.9,5041.9
XS Rating Curve= 0 ,0
Exp/Cntr=0.3,0.1

Type RM Length L Ch R = 1 ,14123   ,1054,1054,1054
BEGIN DESCRIPTION:
WILLIAMS CREEK 16.0
END DESCRIPTION:
XS GIS Cut Line= 3
      2844605.51     10049144.32      2847880.58     10047565.43
        2849279.     10047096.29
#Sta/Elev= 30
    2256 1470.55  2359.1 1468.98  2370.6 1468.58  2834.1 1459.42  2971.4 1456.65
  2984.7 1456.53  3136.3 1453.41  3233.3  1447.4  3699.9 1440.02  3796.1 1438.83
  4934.6 1425.24  4998.3 1414.57  5001.1 1414.07  5004.3 1414.57  5063.2 1420.54
  5112.3 1426.01  5166.9 1427.66  5313.1 1424.39  5352.8 1416.09  5448.8  1424.8
  5726.2    1426  5861.4 1426.29  5923.2 1431.86  6157.8  1434.7  6170.5 1435.23
  6237.6 1435.62  6281.7 1440.57  6407.6 1445.87  6643.9    1455  7366.8 1481.05
#Mann= 19 ,-1 , 0
    2256      .1       0  2359.1     .16       0  2370.6      .1       0
  2834.1     .05       0  2971.4      .1       0  2984.7     .05       0
  3699.9      .1       0  3796.1     .05       0  4998.3    .035       0
  5004.3     .05       0  5063.2      .1       0  5166.9     .16       0
  5726.2     .05       0  5923.2      .1       0  6157.8     .05       0
  6170.5      .1       0  6281.7     .05       0  6407.6      .1       0
  6643.9     .05       0
#XS Ineff= 1 ,-1
 5244.19 5934.26 1428.23
Permanent Ineff=
       T
Bank Sta=4934.6,5112.3
XS Rating Curve= 0 ,0
Exp/Cntr=0.3,0.1

Type RM Length L Ch R = 1 ,13069   ,742,742,742
BEGIN DESCRIPTION:
WILLIAMS CREEK 15.0
END DESCRIPTION:
XS GIS Cut Line= 2
      2845534.77     10049466.14      2848963.54      10047842.9
#Sta/Elev= 30
  2369.2 1455.07  2428.2 1454.22  2479.2 1451.13  2749.5 1442.82  3060.5 1436.63
  3219.6 1434.01  4115.9 1424.22  4888.8 1424.35    4906 1422.69  4951.2 1418.99
    4957 1417.08  4973.3 1415.34  4984.1 1410.08  4999.5 1407.67  5002.3 1407.17
  5005.5 1407.67  5025.3 1413.88  5039.7 1416.28  5106.1 1422.47  5144.5 1424.63
  5349.3 1423.63  5526.5 1426.17  5565.1 1429.37  5656.1 1444.24  5805.3 1450.91
  5855.2 1452.25  5911.9 1455.09  5986.9 1456.32  6059.4 1459.63  6162.8 1460.16
#Mann= 9 ,-1 , 0
  2369.2     .05       0  3060.5      .1       0  3219.6     .05       0
  4984.1      .1       0  4999.5     .07       0  5005.5      .1       0
  5805.3     .05       0  5855.2      .1       0  5986.9     .05       0
Bank Sta=4906,5106.1
XS Rating Curve= 0 ,0
Exp/Cntr=0.3,0.1

Type RM Length L Ch R = 1 ,12327   ,1574,1574,1574
BEGIN DESCRIPTION:
WILLIAMS CREEK 14.0
END DESCRIPTION:
XS GIS Cut Line= 3
      2845508.76     10050186.61      2848130.26     10049153.63
      2848980.72     10048268.46
#Sta/Elev= 30
  1773.4 1467.26  2116.9    1456  2514.7 1436.64  2678.8 1433.88  2964.3 1428.95
  3328.5 1429.12  3550.5 1427.25  3919.9 1422.46  4625.1 1418.67  4908.1 1422.06
  4929.2 1420.14  4978.9 1412.15  4991.2 1407.09  4996.9 1404.53  4999.7 1404.03
  5002.9 1404.53  5014.1 1406.17  5035.2 1415.99  5082.4 1419.46  5084.8 1419.65
  5122.2 1421.38  5231.5 1421.74    5379 1420.78  5459.7 1423.43  5512.6 1437.43
  5523.2 1442.15  5537.4 1443.83  5593.8 1446.02  5687.4 1447.88  5818.6 1449.62
#Mann= 14 ,-1 , 0
  1773.4      .1       0  2678.8     .05       0  3328.5      .1       0
  3550.5     .05       0  4991.2      .1       0  4996.9     .07       0
  5002.9      .1       0  5082.4     .16       0  5122.2      .1       0
  5231.5     .05       0    5379      .1       0  5512.6     .05       0
  5593.8      .1       0  5687.4     .05       0
Bank Sta=4929.2,5084.8
XS Rating Curve= 0 ,0
Exp/Cntr=0.3,0.1

Type RM Length L Ch R = 1 ,10753   ,705,705,705
BEGIN DESCRIPTION:
WILLIAMS CREEK 13.0
END DESCRIPTION:
XS GIS Cut Line= 3
      2845300.37     10050525.17      2848494.85      10049926.2
      2850517.42     10050403.64
#Sta/Elev= 30
  1231.8 1471.62  1239.9 1471.58  1262.6  1471.4  1686.3 1461.67  1978.6 1449.05
    2201 1436.55  2282.2 1434.28  2673.5 1424.94  3813.1 1421.54  4058.3 1414.63
  4201.4 1416.41  4411.6 1412.77  4906.9 1416.49  4958.3 1412.32  4983.2 1401.54
  4986.1 1399.29  4988.9 1398.79  4992.1 1399.29  5081.6 1414.26  5098.8 1416.13
  5453.6 1420.83  5495.9 1426.49  5554.2 1447.68    5691 1454.64    5710 1455.06
  5746.3 1456.35  5937.5 1461.97  6137.6 1467.76  6193.4 1469.16  6560.1 1482.76
#Mann= 17 ,-1 , 0
  1231.8     .05       0  1239.9      .1       0  1262.6     .05       0
  1686.3      .1       0  1978.6     .05       0    2201      .1       0
  2282.2     .05       0  4983.2     .16       0  4986.1     .07       0
  4992.1     .16       0  5098.8      .1       0    5691     .05       0
    5710      .1       0  5746.3     .05       0  5937.5      .1       0
  6137.6     .05       0  6193.4      .1       0
Bank Sta=4958.3,5081.6
XS Rating Curve= 0 ,0
Exp/Cntr=0.3,0.1

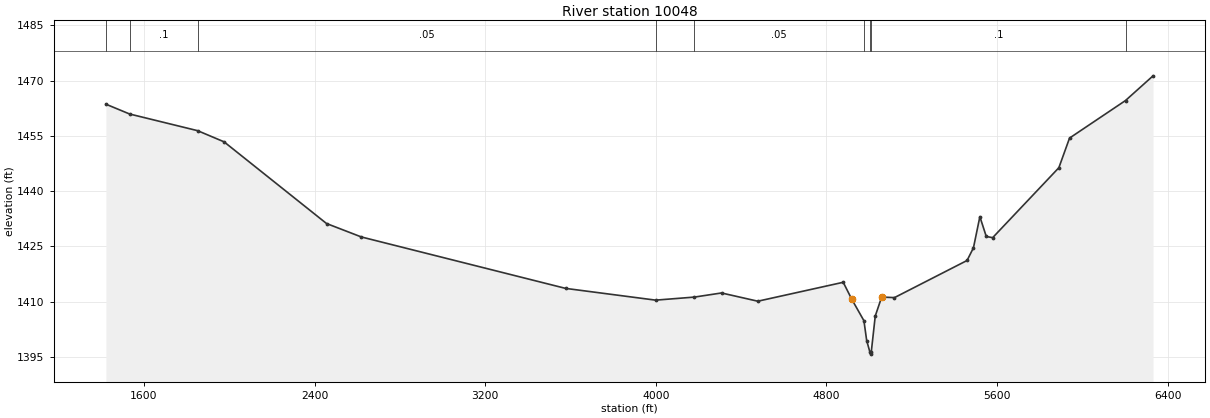
Type RM Length L Ch R = 1 ,10048   ,804,804,804
BEGIN DESCRIPTION:
Mapping XS 5e9378ca
END DESCRIPTION:
XS GIS Cut Line= 2
      2845335.12      10050863.7      2850239.63     10050638.01
#Sta/Elev= 30
  1421.9 1463.59  1533.2 1460.92  1852.1 1456.39  1975.8 1453.37  2456.3 1431.18
  2619.6 1427.53  3577.5 1413.56  3999.4 1410.37    4181  1411.2  4308.3 1412.32
  4478.5 1410.08  4878.9 1415.22  4918.9 1410.62    4976 1404.78    4989 1399.36
  5004.3 1396.21  5007.1 1395.71  5010.3 1396.21  5029.1 1406.06  5059.1  1411.2
  5119.2 1411.06  5459.5 1421.14  5489.5 1424.58  5519.6 1433.04  5549.6 1427.66
  5579.6 1427.34    5890 1446.34    5940 1454.38  6202.4 1464.58  6331.6 1471.29
#Mann= 9 ,-1 , 0
  1421.9     .05       0  1533.2      .1       0  1852.1     .05       0
  3999.4      .1       0    4181     .05       0    4976      .1       0
  5004.3     .07       0  5010.3      .1       0  6202.4     .16       0
Bank Sta=4918.9,5059.1
XS Rating Curve= 0 ,0
Exp/Cntr=0.3,0.1