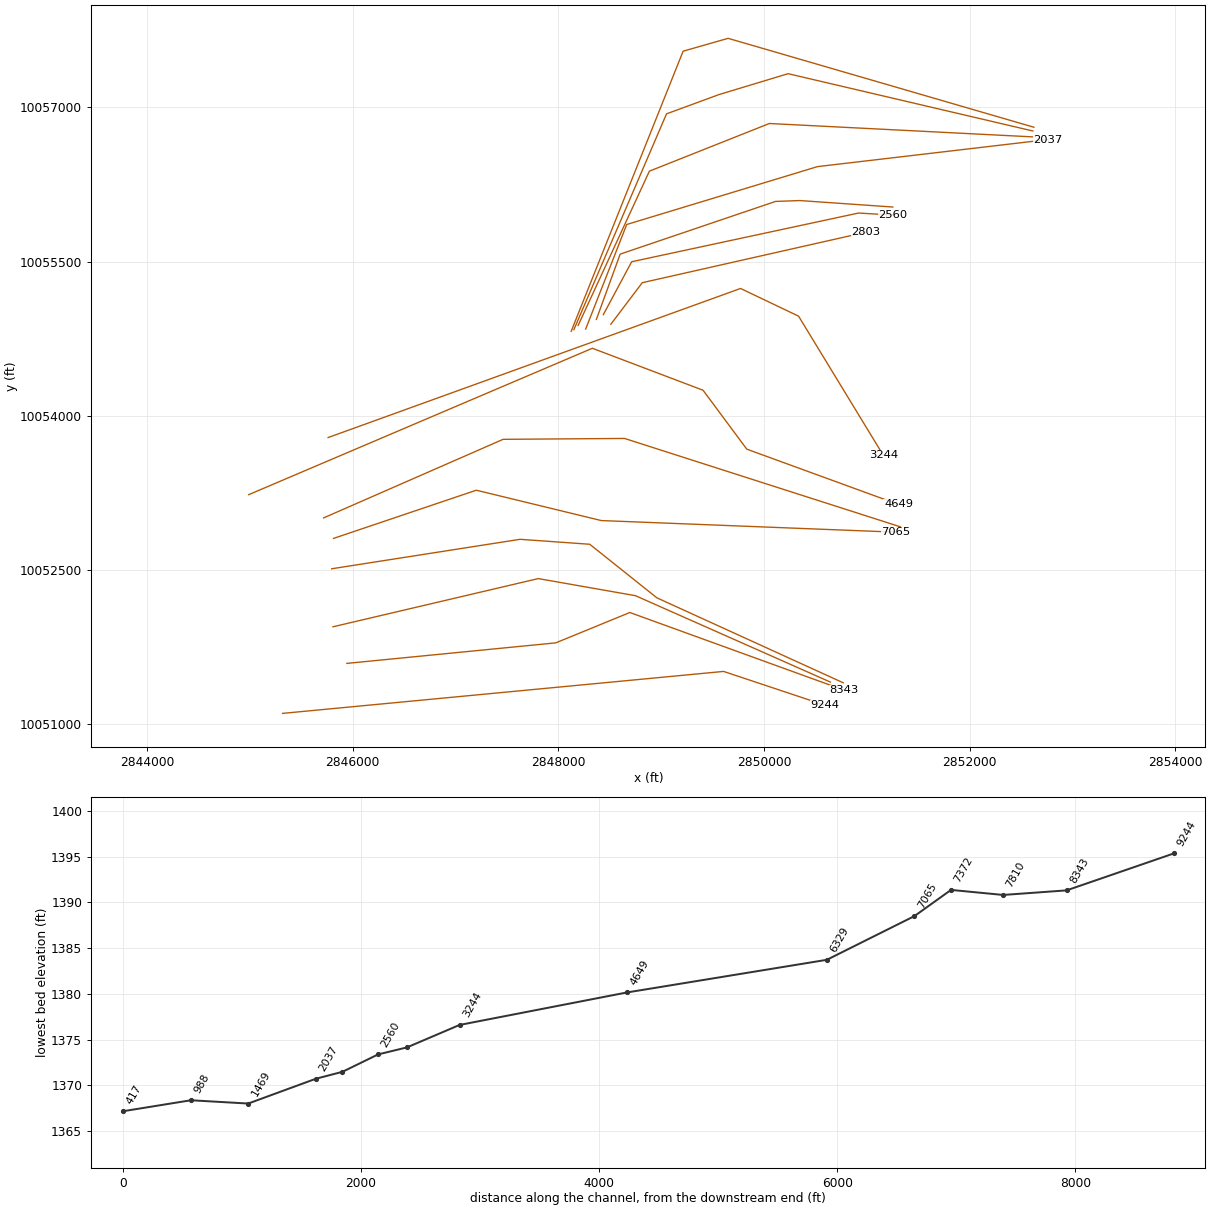
HEC-RAS study WILLIAMS CREEK.prj: WILLIAMS CREEK Base Level Engineering

--- WILLIAMS CREEK.g01 (geometry) --- (continued)

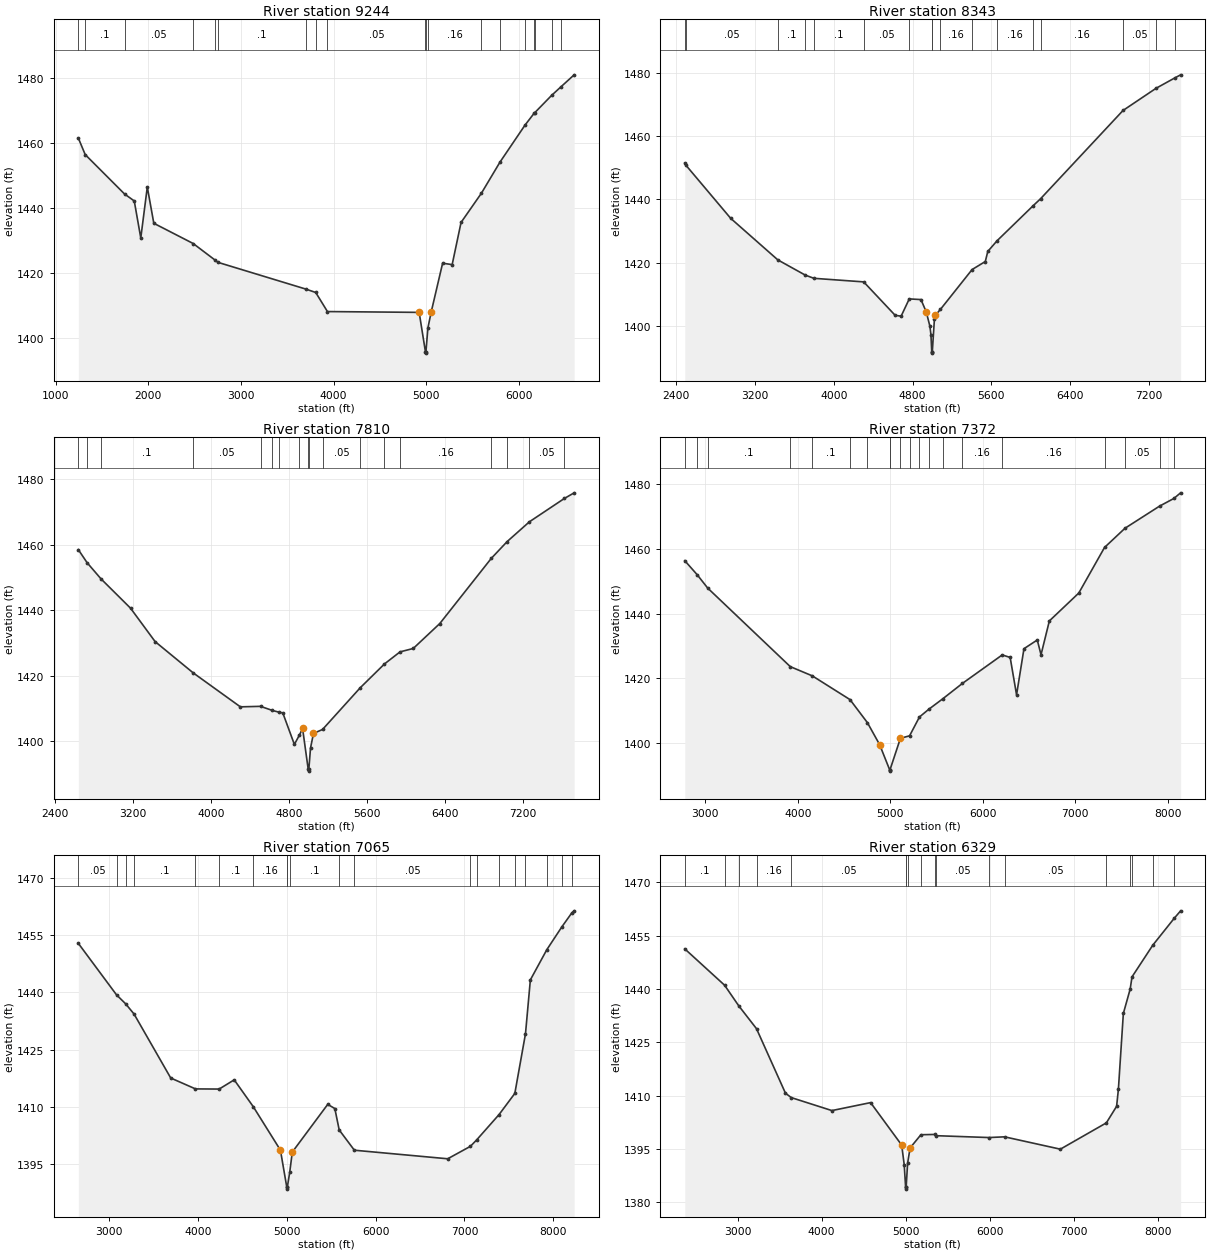
Type RM Length L Ch R = 1 ,9244    ,901,901,901
BEGIN DESCRIPTION:
Mapping XS 035d0e1a
END DESCRIPTION:
XS GIS Cut Line= 3
      2845317.73     10051106.76      2849605.96     10051514.75
       2850594.5     10051185.23
#Sta/Elev= 30
    1246 1461.63    1320 1456.55  1744.7  1444.4  1849.4 1442.25  1919.8 1430.84
  1990.1 1446.54  2060.4 1435.37  2484.8 1429.14  2721.6 1424.02  2752.3 1423.33
  3701.7 1415.08  3807.4 1414.04  3933.7 1408.16  4923.3 1407.91  4990.6 1395.85
  4993.3 1395.35  4996.6 1395.85  5017.6 1403.11  5053.8  1408.1  5176.4 1423.07
  5279.4 1422.63  5375.3 1435.63  5594.5 1444.62  5795.6 1454.24  6066.1 1465.66
  6165.2 1469.34  6170.8 1469.47  6352.7  1474.8  6450.6 1477.37  6595.6 1481.13
#Mann= 19 ,-1 , 0
    1246     .05       0    1320      .1       0  1744.7     .05       0
  2484.8      .1       0  2721.6     .05       0  2752.3      .1       0
  3701.7     .05       0  3807.4     .16       0  3933.7     .05       0
  4990.6    .035       0  4996.6     .05       0  5017.6     .16       0
  5594.5      .1       0  5795.6     .16       0  6066.1      .1       0
  6165.2     .16       0  6170.8      .1       0  6352.7     .05       0
  6450.6      .1       0
Bank Sta=4923.3,5053.8
XS Rating Curve= 0 ,0
Exp/Cntr=0.3,0.1

Type RM Length L Ch R = 1 ,8343    ,533,533,533
BEGIN DESCRIPTION:
WILLIAMS CREEK 12.0
END DESCRIPTION:
XS GIS Cut Line= 4
      2845942.75     10051592.87      2847974.01     10051792.52
       2848694.5     10052087.66       2850777.8     10051332.46
#Sta/Elev= 30
  2486.2 1451.47  2499.3 1450.75  2952.1    1434  3431.3 1420.83  3710.7    1416
  3797.8    1415    4303 1413.87  4623.3 1403.26  4683.4 1403.03  4765.8 1408.48
  4884.9 1408.27  4938.3 1404.36  4975.1 1399.89  4985.9 1397.19  4994.1 1391.81
  4996.9 1391.31  5000.1 1391.81  5021.1 1401.98  5029.2 1403.24  5081.8 1405.14
  5404.1 1417.78  5538.1 1420.32  5563.4 1423.51  5657.4 1426.89    6025 1438.02
  6099.5  1440.2  6936.7 1468.15  7272.5 1475.18  7463.8 1478.48  7521.8 1479.44
#Mann= 17 ,-1 , 0
  2486.2      .1       0  2499.3     .05       0  3431.3      .1       0
  3710.7     .05       0  3797.8      .1       0    4303     .05       0
  4765.8      .1       0  4994.1     .07       0  5000.1      .1       0
  5081.8     .16       0  5404.1      .1       0  5657.4     .16       0
    6025      .1       0  6099.5     .16       0  6936.7     .05       0
  7272.5      .1       0  7463.8     .05       0
Bank Sta=4938.3,5029.2
XS Rating Curve= 0 ,0
Exp/Cntr=0.3,0.1

Type RM Length L Ch R = 1 ,7810    ,438,438,438
BEGIN DESCRIPTION:
WILLIAMS CREEK 11.0
END DESCRIPTION:
XS GIS Cut Line= 4
      2845807.47     10051948.74      2847803.97     10052417.49
       2848748.9     10052251.28      2850644.06      10051411.3
#Sta/Elev= 30
  2642.4 1458.47  2732.4 1454.48  2874.7 1449.55  3177.6 1440.59  3429.6 1430.38
  3819.8 1420.83  4303.6 1410.45  4510.5  1410.6  4631.7 1409.35  4703.1 1408.79
  4738.4 1408.61  4857.2 1398.97  4908.5  1401.8  4941.4 1403.84  4999.4 1391.31
  5002.1 1390.81  5005.4 1391.31  5022.7 1397.85  5053.1 1402.33  5145.8 1403.53
  5532.5 1416.28  5781.2 1423.56  5940.4 1427.24  6075.9 1428.28  6348.3  1435.9
  6875.8  1455.8    7039 1460.95  7267.2 1466.99  7624.8  1474.1  7725.6 1475.83
#Mann= 18 ,-1 , 0
  2642.4      .1       0  2732.4     .05       0  2874.7      .1       0
  3819.8     .05       0  4510.5     .16       0  4631.7     .05       0
  4703.1     .16       0  4908.5      .1       0  4999.4     .07       0
  5005.4      .1       0  5145.8     .05       0  5532.5     .16       0
  5781.2      .1       0  5940.4     .16       0  6875.8     .05       0
    7039     .16       0  7267.2     .05       0  7624.8      .1       0
Bank Sta=4941.4,5053.1
XS Rating Curve= 0 ,0
Exp/Cntr=0.3,0.1

Type RM Length L Ch R = 1 ,7372    ,307,307,307
BEGIN DESCRIPTION:
WILLIAMS CREEK 10.0
END DESCRIPTION:
XS GIS Cut Line= 5
      2845795.17     10052513.01      2847626.79     10052799.47
      2848304.45     10052751.28      2848957.23     10052230.44
      2850769.77     10051404.04
#Sta/Elev= 30
  2779.1 1456.41    2913 1452.07  3026.8 1447.94  3919.6 1423.66  4157.6 1420.81
  4565.1 1413.47  4753.2 1406.35  4885.3 1399.56  4992.6 1391.86  4995.3 1391.36
  4998.6 1391.86  5110.1  1401.5  5209.3 1402.28    5316  1408.1  5418.6 1410.52
  5568.7 1413.73    5779 1418.45  6210.8 1427.28  6296.7  1426.5  6365.8 1414.95
  6445.9 1429.21  6589.7  1431.9  6630.3 1427.35  6720.3 1437.79  7038.5 1446.41
  7316.9  1460.5  7538.1 1466.44  7912.4 1473.29    8066 1475.64  8139.5 1477.39
#Mann= 20 ,-1 , 0
  2779.1     .05       0    2913     .05       0  3026.8      .1       0
  3919.6     .05       0  4157.6      .1       0  4565.1      .1       0
  4753.2     .16       0  4992.6     .07       0  4998.6      .1       0
  5110.1     .16       0  5209.3      .1       0    5316     .16       0
  5418.6      .1       0  5568.7     .05       0    5779     .16       0
  6210.8     .16       0  7316.9     .16       0  7538.1     .05       0
  7912.4      .1       0    8066     .05       0
Bank Sta=4885.3,5110.1
XS Rating Curve= 0 ,0
Exp/Cntr=0.3,0.1

Type RM Length L Ch R = 1 ,7065    ,736,736,736
BEGIN DESCRIPTION:
WILLIAMS CREEK 9.0
END DESCRIPTION:
XS GIS Cut Line= 4
      2845812.59     10052808.16      2847201.44      10053276.9
      2848416.72     10052981.76      2851281.28     10052868.91
#Sta/Elev= 30
  2651.8  1452.8  3082.1 1439.32  3184.7 1436.98  3279.5  1434.3  3692.3 1417.57
  3971.1 1414.72  4237.6 1414.68  4407.1 1417.09  4621.6 1410.07  4927.5  1398.7
  4999.2    1389  5001.9  1388.5  5005.2    1389    5032  1392.9  5061.3  1398.2
    5460 1410.67  5540.1 1409.58  5589.4 1403.98    5760 1398.68  6811.1 1396.44
  7066.2 1399.69  7135.7 1401.34  7389.8 1408.02  7566.9 1413.54    7687 1429.16
  7741.8 1443.24  7926.8 1451.13    8096  1457.1  8209.2 1460.79    8235 1461.31
#Mann= 20 ,-1 , 0
  2651.8     .05       0  3082.1      .1       0  3184.7     .05       0
  3279.5      .1       0  3971.1     .05       0  4237.6      .1       0
  4621.6     .16       0  4999.2     .07       0  5005.2     .16       0
    5032      .1       0  5589.4     .16       0    5760     .05       0
  7066.2      .1       0  7135.7     .05       0  7389.8      .1       0
  7566.9     .16       0    7687      .1       0  7926.8     .05       0
    8096     .16       0  8209.2      .1       0
Bank Sta=4927.5,5061.3
XS Rating Curve= 0 ,0
Exp/Cntr=0.3,0.1

Type RM Length L Ch R = 1 ,6329    ,1680,1680,1680
BEGIN DESCRIPTION:
WILLIAMS CREEK 8.0
END DESCRIPTION:
XS GIS Cut Line= 4
      2845717.07      10053007.8      2847461.86     10053771.69
      2848642.42     10053780.37      2851324.07      10052921.2
#Sta/Elev= 30
  2371.2 1451.25  2844.8 1441.04  3013.2 1435.25  3224.7 1428.82  3569.2 1410.69
  3638.3 1409.45  4121.9  1405.8  4582.5 1408.04  4952.5 1396.11  4982.5 1390.61
  4999.5 1384.22  5002.3 1383.72  5005.5 1384.22  5023.1 1391.01  5052.5  1395.3
  5181.4 1399.01  5343.9 1399.09  5365.1 1398.74  5991.5 1398.22  6177.1 1398.42
    6841 1394.95  7388.7 1402.35  7510.5    1407  7531.7 1411.76  7590.7 1433.09
  7671.8 1439.94    7694 1443.39  7941.3  1452.3  8197.1 1459.88  8272.4 1461.95
#Mann= 18 ,-1 , 0
  2371.2      .1       0  2844.8     .05       0  3013.2      .1       0
  3224.7     .16       0  3638.3     .05       0  4999.5    .035       0
  5005.5     .05       0  5023.1      .1       0  5181.4     .05       0
  5343.9      .1       0  5365.1     .05       0  5991.5      .1       0
  6177.1     .05       0  7388.7      .1       0  7671.8     .16       0
    7694      .1       0  7941.3     .16       0  8197.1     .05       0
Bank Sta=4952.5,5052.5
XS Rating Curve= 0 ,0
Exp/Cntr=0.3,0.1

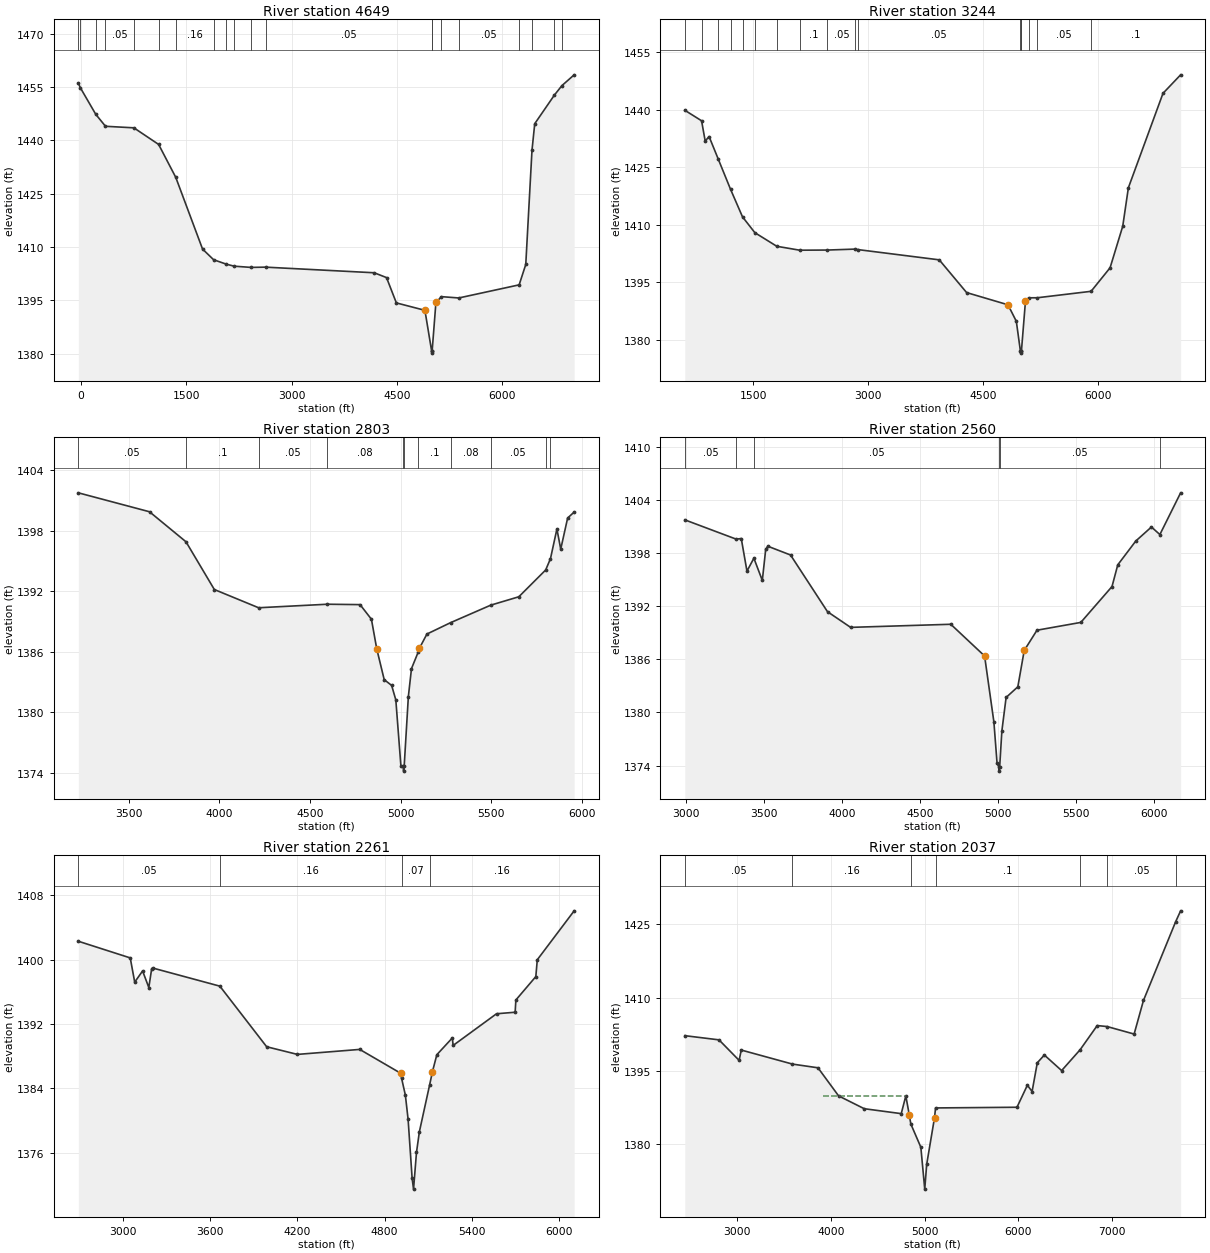
Type RM Length L Ch R = 1 ,4649    ,1405,1405,1405
BEGIN DESCRIPTION:
WILLIAMS CREEK 7.0
END DESCRIPTION:
XS GIS Cut Line= 5
      2844987.89     10053233.49      2848329.92     10054657.11
       2849406.3     10054249.12      2849831.65      10053676.2
      2851306.36     10053138.37
#Sta/Elev= 30
   -38.9 1456.16   -11.6 1454.86   210.2 1447.32   348.2 1443.97   752.6 1443.54
  1105.4 1438.87  1349.9  1429.6  1731.6 1409.43  1888.9 1406.43  2070.2 1405.18
  2182.2 1404.61  2421.7 1404.27  2630.6 1404.34  4178.3 1402.76  4353.9  1401.4
  4493.9 1394.28    4901 1392.19  4997.6 1380.65  5000.4 1380.15  5003.6 1380.65
  5057.7  1394.4  5136.9 1396.04  5383.8 1395.67  6244.1 1399.36  6338.5  1405.1
  6427.1 1437.22  6466.2  1444.7  6747.2 1452.77  6853.9 1455.42  7028.1 1458.45
#Mann= 20 ,-1 , 0
   -38.9      .1       0   -11.6     .05       0   210.2      .1       0
   348.2     .05       0   752.6      .1       0  1105.4     .05       0
  1349.9     .16       0  1888.9      .1       0  2070.2     .05       0
  2182.2      .1       0  2421.7      .1       0  2630.6     .05       0
  4997.6    .035       0  5003.6     .05       0  5136.9      .1       0
  5383.8     .05       0  6244.1      .1       0  6427.1     .16       0
  6747.2     .05       0  6853.9      .1       0
Bank Sta=4901,5057.7
XS Rating Curve= 0 ,0
Exp/Cntr=0.3,0.1

Type RM Length L Ch R = 1 ,3244    ,441,441,441
BEGIN DESCRIPTION:
WILLIAMS CREEK 6.0
END DESCRIPTION:
XS GIS Cut Line= 4
      2845760.47     10053789.05      2849770.89      10055238.7
      2850335.12     10054969.61      2851158.78     10053617.07
#Sta/Elev= 30
   606.3 1439.82   825.3 1437.08   872.7 1431.79   923.2 1432.98  1040.9 1427.21
  1203.6 1419.24  1359.7 1412.07    1521 1407.95  1807.4 1404.41  2106.6 1403.39
  2466.7 1403.43  2834.8 1403.68  2865.7 1403.55  3928.3 1400.88  4285.5 1392.36
  4825.6 1389.18  4934.5 1384.88  4988.1  1377.1  4990.8  1376.6  4994.1  1377.1
  5001.4 1377.22  5053.6 1390.09  5095.5    1391  5207.1 1391.01  5910.6 1392.69
  6158.3 1398.81  6323.7 1409.63  6397.3 1419.64  6849.1 1444.22  7079.4 1449.04
#Mann= 17 ,-1 , 0
   606.3      .1       0   825.3     .05       0  1040.9     .16       0
  1203.6      .1       0  1359.7     .05       0    1521      .1       0
  1807.4     .05       0  2106.6      .1       0  2466.7     .05       0
  2834.8      .1       0  2865.7     .05       0  4988.1    .035       0
  4994.1     .05       0  5001.4      .1       0  5095.5     .16       0
  5207.1     .05       0  5910.6      .1       0
Bank Sta=4825.6,5053.6
XS Rating Curve= 0 ,0
Exp/Cntr=0.3,0.1

Type RM Length L Ch R = 1 ,2803    ,243,243,243
BEGIN DESCRIPTION:
Mapping XS c41c68c8
END DESCRIPTION:
XS GIS Cut Line= 3
      2848509.74     10054891.06      2848815.24     10055294.87
      2850991.35     10055786.03
#Sta/Elev= 30
  3220.9 1401.78  3613.8  1399.9  3815.2 1396.92  3971.7 1392.18  4216.2 1390.37
  4596.3 1390.72  4776.2 1390.68  4838.9 1389.23  4868.5 1386.27  4909.5 1383.23
  4950.5 1382.66  4973.6 1381.22  5001.7 1374.66  5013.8 1374.65  5016.6 1374.15
  5019.8 1374.65  5042.8 1381.55  5060.1 1384.33  5097.2 1385.97  5103.3 1386.33
  5145.3 1387.76  5275.9 1388.89  5497.9 1390.63  5652.6 1391.46  5800.8 1394.12
  5827.3 1395.24  5862.9 1398.19    5884 1396.19  5922.1 1399.28  5958.1 1399.87
#Mann= 11 ,-1 , 0
  3220.9     .05       0  3815.2      .1       0  4216.2     .05       0
  4596.3     .08       0  5013.8     .07       0  5019.8     .08       0
  5097.2      .1       0  5275.9     .08       0  5497.9     .05       0
  5800.8      .1       0  5827.3     .08       0
Bank Sta=4868.5,5103.3
XS Rating Curve= 0 ,0
Exp/Cntr=0.3,0.1

Type RM Length L Ch R = 1 ,2560    ,299,299,299
BEGIN DESCRIPTION:
Mapping XS 99dc2d53
END DESCRIPTION:
XS GIS Cut Line= 4
      2848436.84     10054984.83      2848712.14     10055498.62
      2850918.12     10055972.17      2851255.23     10055952.79
#Sta/Elev= 30
  2994.8 1401.75  3324.2 1399.57  3356.6 1399.64  3393.1 1395.96  3437.4 1397.42
  3491.4 1394.91  3513.4 1398.44  3526.8 1398.77  3672.3 1397.78  3909.1 1391.38
  4057.2 1389.61    4699 1389.96  4915.6 1386.38  4975.2 1378.93  4995.6 1374.25
  5006.3 1373.88    5009 1373.38  5012.3 1373.88  5026.3 1377.92  5053.5  1381.7
  5128.6  1382.9  5169.5    1387  5251.3 1389.29  5532.1 1390.17    5732 1394.22
  5768.9 1396.67  5884.4 1399.36  5984.5 1400.94  6038.7 1400.09  6171.6  1404.8
#Mann= 6 ,-1 , 0
  2994.8     .05       0  3324.2      .1       0  3437.4     .05       0
  5006.3     .04       0  5012.3     .05       0  6038.7     .08       0
Bank Sta=4915.6,5169.5
XS Rating Curve= 0 ,0
Exp/Cntr=0.3,0.1

Type RM Length L Ch R = 1 ,2261    ,224,224,224
BEGIN DESCRIPTION:
WILLIAMS CREEK 4.0
END DESCRIPTION:
XS GIS Cut Line= 5
      2848369.12     10054937.94      2848600.42     10055572.87
      2850110.83     10056085.02      2850345.21      10056093.7
      2851251.77     10056030.82
#Sta/Elev= 30
  2691.5 1402.28  3048.9 1400.21  3079.7  1397.2    3134 1398.59  3176.8 1396.53
  3196.7 1398.89  3208.5 1398.93  3665.9  1396.7  3988.2 1389.17  4199.9 1388.22
  4629.1 1388.84  4911.8 1385.87  4917.4 1385.24  4943.2 1383.16  4962.1 1380.15
  4989.8 1372.81  4999.5 1371.48  5019.8 1376.04  5039.8 1378.62  5109.9  1384.4
  5129.9 1386.09  5159.9 1388.18  5266.8 1390.27  5271.8 1389.33  5570.8 1393.27
  5699.1 1393.46  5704.1 1394.98  5841.5 1397.89  5851.5 1399.98  6105.4 1406.06
#Mann= 4 ,-1 , 0
  2691.5     .05       0  3665.9     .16       0  4917.4     .07       0
  5109.9     .16       0
Bank Sta=4911.8,5129.9
XS Rating Curve= 0 ,0
Exp/Cntr=0.3,0.1

Type RM Length L Ch R = 1 ,2037    ,568,568,568
BEGIN DESCRIPTION:
Mapping XS a2028eaa
END DESCRIPTION:
XS GIS Cut Line= 4
      2848264.95     10054844.16       2848664.1     10055860.85
      2850518.82     10056423.56      2852762.16     10056687.06
#Sta/Elev= 30
  2442.8 1402.19  2807.6 1401.33  3022.5 1397.12    3045 1399.24  3591.6 1396.36
  3863.6  1395.6  4083.5 1389.84  4357.2 1387.21  4751.8  1386.2  4800.5 1389.84
  4838.6 1385.83  4854.1 1384.07  4960.8 1379.31  5002.4 1370.72  5023.5 1375.84
    5107  1385.4  5117.6 1387.37  5986.4 1387.51  6097.1 1392.03  6147.5 1390.74
  6203.1 1396.63  6278.4 1398.22  6462.6 1395.03  6660.2 1399.31  6842.2 1404.26
  6947.8 1404.06    7236 1402.52  7335.6 1409.41  7678.2 1425.52    7732 1427.79
#Mann= 7 ,-1 , 0
  2442.8     .05       0  3591.6     .16       0  4854.1     .07       0
  5117.6      .1       0  6660.2      .1       0  6947.8     .05       0
  7678.2      .1       0
#XS Ineff= 1 ,-1
 3914.24 4799.42 1389.86
Permanent Ineff=
       T
Bank Sta=4838.6,5107
XS Rating Curve= 0 ,0
Exp/Cntr=0.3,0.1

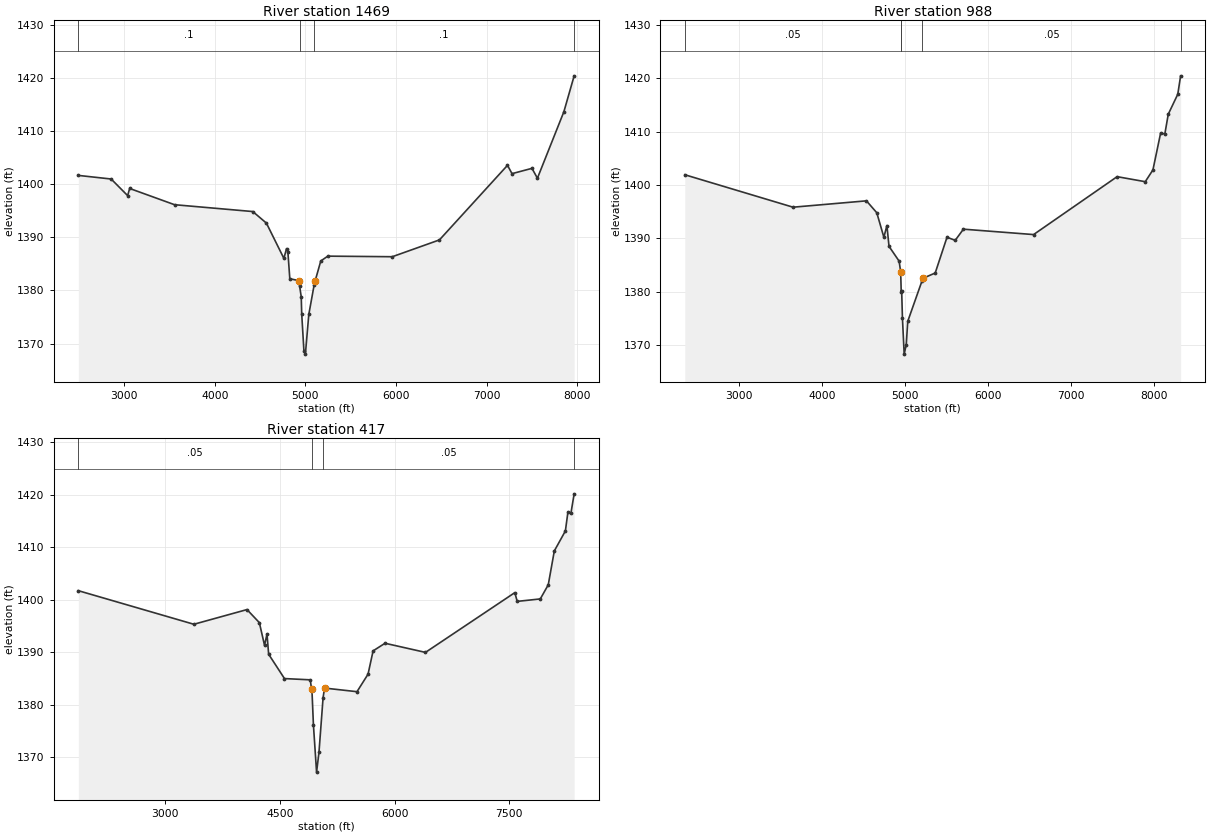
Type RM Length L Ch R = 1 ,1469    ,481,481,481
BEGIN DESCRIPTION:
Mapping XS 08c0f5a9
END DESCRIPTION:
XS GIS Cut Line= 4
      2848191.67     10054879.46      2848884.39     10056379.48
      2850051.06     10056843.02      2852613.53     10056712.82
#Sta/Elev= 30
  2494.2 1401.68  2856.6    1401  3038.6 1397.87  3060.7 1399.22  3556.3 1396.16
  4420.2 1394.87  4570.5 1392.69  4763.1 1386.05  4792.7 1387.89  4807.2 1387.33
  4828.7 1382.21    4925 1381.87  4936.3 1380.91  4954.7 1378.83  4960.1 1375.59
  4984.4 1368.64  5000.7 1368.01  5038.3 1375.48  5097.7 1381.08  5108.5 1381.81
  5170.6 1385.56  5248.4 1386.47    5960 1386.36  6480.6 1389.53  7231.6 1403.58
  7281.7 1402.01  7501.9 1403.01    7562 1401.15  7854.2 1413.68  7967.6 1420.44
#Mann= 4 ,-1 , 0
  2494.2      .1       0  4936.3     .05       0  5097.7      .1       0
  7967.6     .05       0
Bank Sta=4925,5108.5
XS Rating Curve= 0 ,0
Exp/Cntr=0.3,0.1

Type RM Length L Ch R = 1 ,988     ,571,571,571
BEGIN DESCRIPTION:
Mapping XS df360fd1
END DESCRIPTION:
XS GIS Cut Line= 5
        2848150.     10054837.78      2849051.06     10056936.77
      2849561.47     10057124.27      2850233.35      10057327.4
      2852613.48     10056770.13
#Sta/Elev= 30
    2347 1401.92  3651.3 1395.85  4535.7 1397.04  4660.4 1394.81  4745.7 1390.23
  4782.4 1392.42  4807.6 1388.53  4929.5 1385.76  4948.1 1383.77  4954.7 1380.03
    4960 1380.27  4969.4 1375.15  4990.4 1368.37  5015.6 1370.16  5033.3  1374.5
    5207 1382.14  5221.9 1382.59  5364.2 1383.54  5506.4 1390.23  5605.2 1389.65
  5704.1 1391.74  6549.7 1390.73  7556.2 1401.56  7895.2 1400.62  7987.6 1402.82
    8080 1409.68  8131.4 1409.56  8172.5 1413.24  8287.1 1416.98  8321.4 1420.42
#Mann= 5 ,-1 , 0
    2347     .05       0  4948.1     .16       0  4948.1    .035       0
    5207     .05       0  8321.4     .05       0
Bank Sta=4948.1,5221.9
XS Rating Curve= 0 ,0
Exp/Cntr=0.3,0.1

Type RM Length L Ch R = 1 ,417     ,0,0,0
BEGIN DESCRIPTION:
Mapping XS a2028eaaaaaa
END DESCRIPTION:
XS GIS Cut Line= 4
      2848123.99     10054822.23      2849212.51     10057546.15
      2849650.01     10057671.15      2852623.73     10056806.64
#Sta/Elev= 30
  1862.9 1401.75  3374.1 1395.35    4069 1398.15  4230.6 1395.66  4298.3 1391.34
  4330.6 1393.48  4352.1 1389.64  4559.2    1385  4896.1 1384.76  4913.3 1383.04
  4918.5 1382.79  4937.7  1376.2    4979 1367.17  5010.5 1370.96  5064.1 1381.35
  5083.3 1383.19  5507.7  1382.5  5652.3 1385.84  5718.3 1390.28  5874.5 1391.73
  6403.3 1389.99    7572 1401.38  7603.2 1399.71  7905.2 1400.18  8009.4 1402.87
  8088.7 1409.33  8233.2 1413.13  8266.7 1416.74  8305.5 1416.48  8348.1 1420.21
#Mann= 4 ,-1 , 0
  1862.9     .05       0  4918.5    .035       0  5064.1     .05       0
  8348.1     .05       0
Bank Sta=4913.3,5083.3
XS Rating Curve= 0 ,0
Exp/Cntr=0.3,0.1

Chan Stop Cuts=-1
Use User Specified Reach Order=0
Composite Channel Slope=5