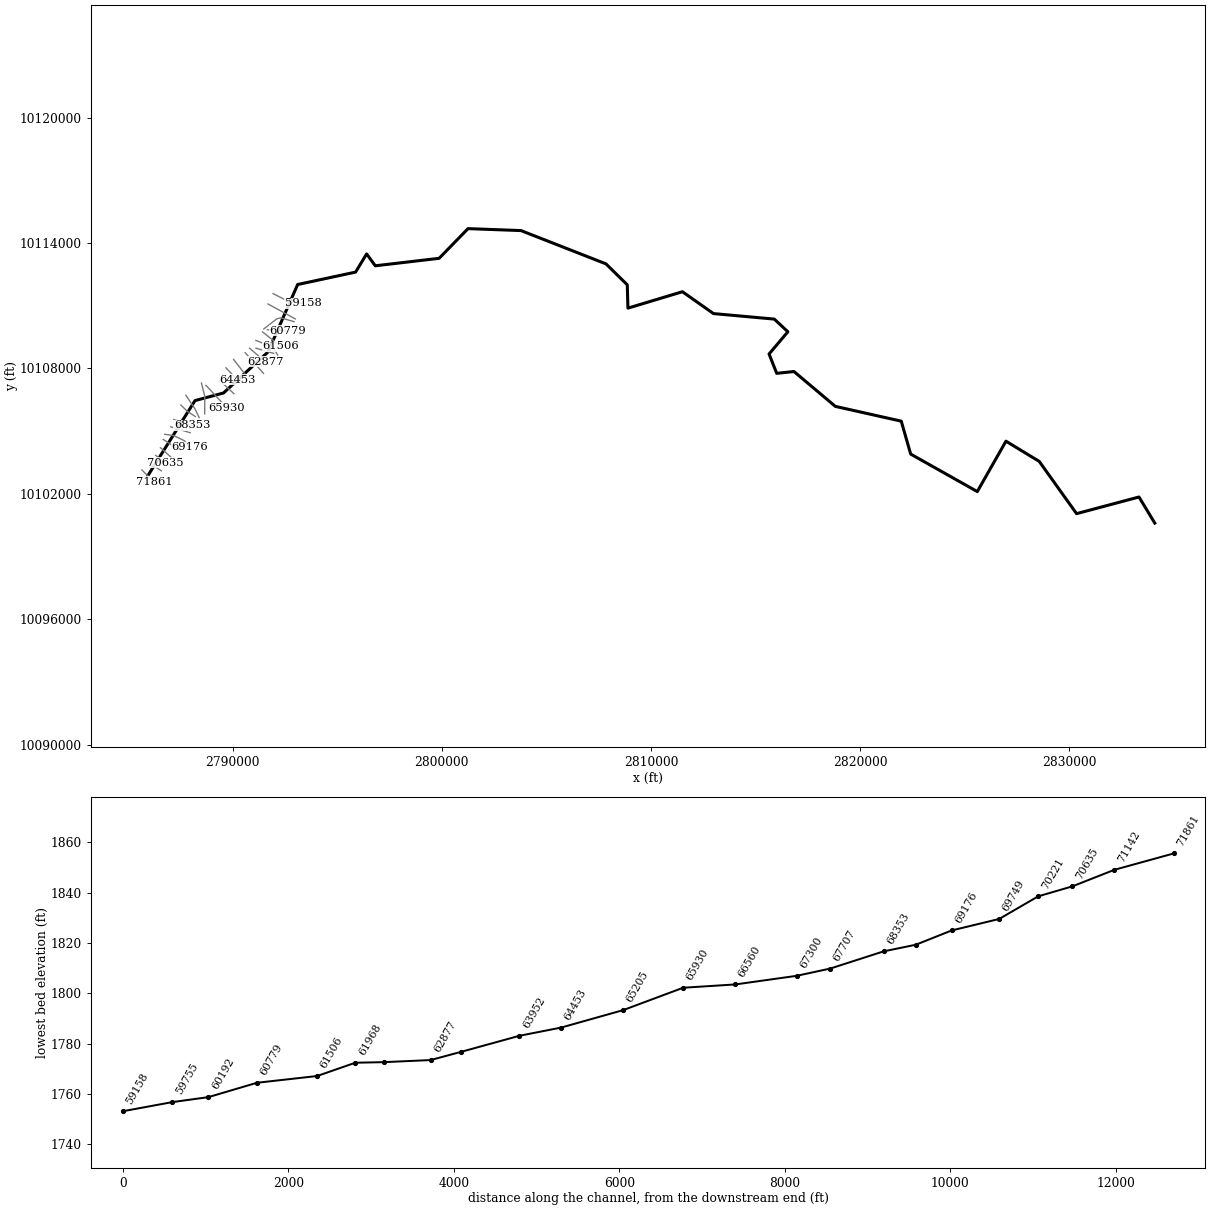
--- WILLOW CREEK.prj (project) ---

Proj Title=WILLOW CREEK Base Level Engineering
Current Plan=p01
Default Exp/Contr=0.3,0.1
English Units
Geom File=g01
Flow File=f01
Plan File=p01
Y Axis Title=Elevation
X Axis Title(PF)=Main Channel Distance
X Axis Title(XS)=Station
BEGIN DESCRIPTION:
WILLOW CREEK
END DESCRIPTION:
DSS Export Rating Curves= 0
DSS Export Rating Curve Sorted= 0
DSS Export Volume Flow Curves= 0
DXF OffsetX= 0
DXF OffsetY= 0
DXF ScaleX= 1
DXF ScaleY= 10

--- WILLOW CREEK.p01 (plan) ---

Plan Title=Multiple Run
Short Identifier=Multiple
Geom File=g01
Flow File=f01
Subcritical Flow
K Sum by GR= 0
Std Step Tol= 0.01
Critical Tol= 0.01
Num of Std Step Trials= 20
Max Error Tol= 0.3
Flow Tol Ratio= 0.001
Split Flow NTrial= 30
Split Flow Tol= 0.02
Split Flow Ratio= 0.02
Log Output Level= 0
Friction Slope Method= 1
Unsteady Friction Slope Method= 2
Unsteady Bridges Friction Slope Method= 1
Parabolic Critical Depth
Global Vel Dist=  1 , 1 , 1
Global Log Level= 0
CheckData=True
Encroach Param= -1, 0, 0, 0
BEGIN DESCRIPTION:
Multiple Run
END DESCRIPTION:

--- WILLOW CREEK.f01 (steady flow) ---

Flow Title=Multiple
Program Version=4.10
Number of Profiles= 7
Profile Names=10-year,25-year,50-year,1pct_min,100-year,1pct_plu,500-year
River Rch & RM=WILLOW CREEK,Reach-1         ,71861
    1184    1741    2231    2090    2826    3822    4557
River Rch & RM=WILLOW CREEK,Reach-1         ,67707
    1565    2332    3015    2848    3852    5209    6313
River Rch & RM=WILLOW CREEK,Reach-1         ,66560
    1814    2709    3507    3313    4480    6059    7347
River Rch & RM=WILLOW CREEK,Reach-1         ,59755
    2602    3952    5172    4935    6674    9026   11169
River Rch & RM=WILLOW CREEK,Reach-1         ,55744
    2700    4084    5331    5070    6856    9272   11398
River Rch & RM=WILLOW CREEK,Reach-1         ,48591
    3996    6139    8098    7776   10516   14221   17820
River Rch & RM=WILLOW CREEK,Reach-1         ,47021
    4589    7059    9319    8951   12105   16370   20521
River Rch & RM=WILLOW CREEK,Reach-1         ,46909
    4589    7059    9319    8951   12105   16370   20521
River Rch & RM=WILLOW CREEK,Reach-1         ,37921
    4953    7635   10093    9706   13126   17752   22306
River Rch & RM=WILLOW CREEK,Reach-1         ,36345
    5167    7966   10533   10128   13696   18523   23271
River Rch & RM=WILLOW CREEK,Reach-1         ,32797
    5449    8402   11109   10680   14443   19533   24530
River Rch & RM=WILLOW CREEK,Reach-1         ,27349
    5436    8369   11054   10615   14355   19413   24323
River Rch & RM=WILLOW CREEK,Reach-1         ,23893
    5931    9147   12096   11628   15726   21267   26700
River Rch & RM=WILLOW CREEK,Reach-1         ,21022
    6224    9608   12713   12226   16534   22361   28097
River Rch & RM=WILLOW CREEK,Reach-1         ,16713
    6427    9926   13141   12643   17098   23123   29077
River Rch & RM=WILLOW CREEK,Reach-1         ,13957
    6499   10041   13295   12793   17302   23398   29432
River Rch & RM=WILLOW CREEK,Reach-1         ,12963
    6506   10048   13302   12796   17306   23404   29424
River Rch & RM=WILLOW CREEK,Reach-1         ,11379
    6480   10001   13232   12722   17205   23267   29219
River Rch & RM=WILLOW CREEK,Reach-1         ,10263
    6486   10007   13238   12724   17208   23272   29211
River Rch & RM=WILLOW CREEK,Reach-1         ,8925
    6605   10183   13465   12935   17494   23658   29662
River Rch & RM=WILLOW CREEK,Reach-1         ,1010
    6781   10462   13840   13301   17988   24327   30523
Boundary for River Rch & Prof#=WILLOW CREEK,Reach-1         , 1
Up Type= 0
Dn Type= 3
Dn Slope=0.0029
Boundary for River Rch & Prof#=WILLOW CREEK,Reach-1         , 2
Up Type= 0
Dn Type= 3
Dn Slope=0.0029
Boundary for River Rch & Prof#=WILLOW CREEK,Reach-1         , 3
Up Type= 0
Dn Type= 3
Dn Slope=0.0029
Boundary for River Rch & Prof#=WILLOW CREEK,Reach-1         , 4
Up Type= 0
Dn Type= 3
Dn Slope=0.0029
Boundary for River Rch & Prof#=WILLOW CREEK,Reach-1         , 5
Up Type= 0
Dn Type= 3
Dn Slope=0.0029
Boundary for River Rch & Prof#=WILLOW CREEK,Reach-1         , 6
Up Type= 0
Dn Type= 3
Dn Slope=0.0029
Boundary for River Rch & Prof#=WILLOW CREEK,Reach-1         , 7
Up Type= 0
Dn Type= 3
Dn Slope=0.0029
DSS Import GetInterval= 0
DSS Import GetPeak= 0
DSS Import FillOption= 0

--- WILLOW CREEK.g01 (geometry) ---

Geom Title=Existing Conditions
Program Version=4.10

River Reach=WILLOW CREEK    ,Reach-1
Reach XY= 30
      2785908.47     10102813.73      2788198.06     10106464.16
      2789561.19     10106828.75      2791689.95     10108789.55
      2793106.42     10112017.92      2795875.67     10112611.26
      2796404.12     10113480.65      2796818.49     10112913.57
      2799870.65     10113271.72      2801252.87     10114691.86
      2803784.85      10114598.6       2807848.6     10113005.42
      2808867.28     10112002.95      2808897.86     10110887.54
      2811503.14     10111672.99      2812989.67     10110626.72
      2815895.08     10110363.64      2816545.99      10109757.5
      2815645.82      10108693.7      2816012.28     10107768.22
      2816836.44     10107855.58      2818815.35      10106187.5
      2821966.79     10105480.04      2822417.31     10103905.18
      2825602.36     10102111.29       2826973.1     10104521.93
       2828562.7     10103556.16      2830349.04     10101054.64
        2833333.     10101851.56      2834088.47     10100603.73

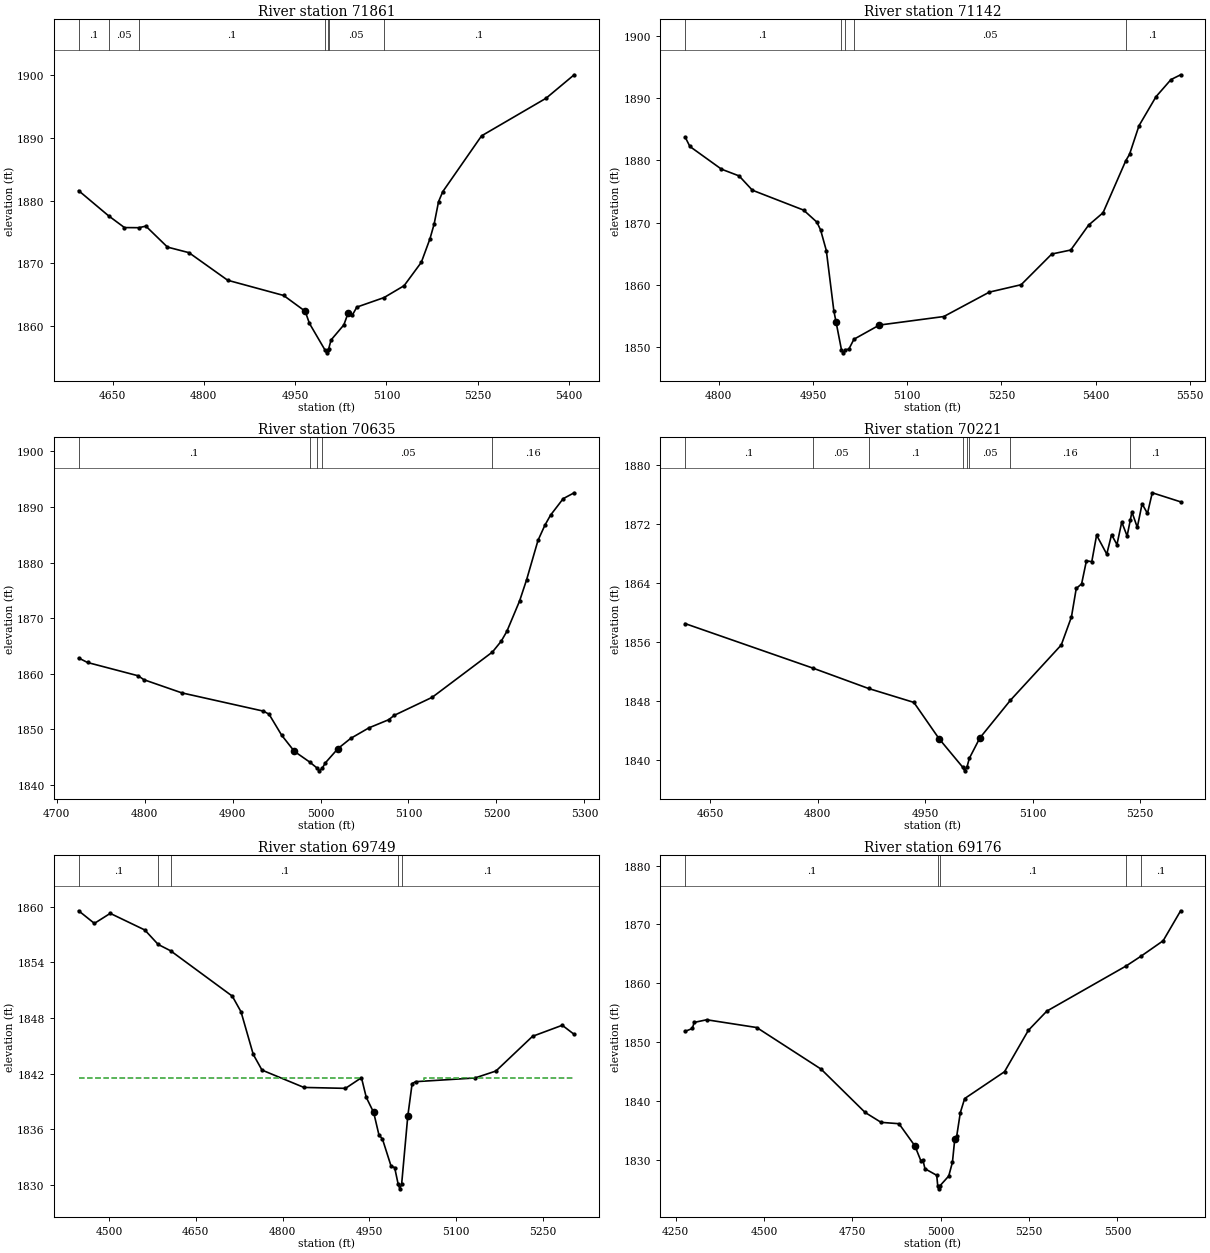
Type RM Length L Ch R = 1 ,71861   ,719,719,719
BEGIN DESCRIPTION:
WILLOW CREEK 120.0
END DESCRIPTION:
XS GIS Cut Line= 2
      2785660.86     10103142.53      2786244.35     10102574.39
#Sta/Elev= 30
  4594.2 1881.58  4643.3 1877.57  4669.5 1875.68  4693.1 1875.66  4704.7 1875.91
  4740.2 1872.56  4775.5 1871.67  4839.2 1867.26  4931.1 1864.83  4966.5 1862.31
  4973.5 1860.37  4998.8 1856.16  5001.6 1855.66  5004.8 1856.16  5005.2 1856.31
    5009 1857.71  5030.1 1860.13  5037.3 1862.08  5044.2 1861.72  5051.4 1862.97
  5096.1 1864.49  5129.1 1866.39  5157.4 1870.13  5171.6 1873.89  5178.5 1876.26
  5185.7 1879.82  5192.7 1881.43  5256.4 1890.34  5362.4 1896.35  5408.6  1900.1
#Mann= 7 ,-1 , 0
  4594.2      .1       0  4643.3     .05       0  4693.1      .1       0
  4998.8     .07       0  5004.8      .1       0  5005.2     .05       0
  5096.1      .1       0
Bank Sta=4966.5,5037.3
XS Rating Curve= 0 ,0
Exp/Cntr=0.3,0.1

Type RM Length L Ch R = 1 ,71142   ,507,507,507
BEGIN DESCRIPTION:
WILLOW CREEK 118.0
END DESCRIPTION:
XS GIS Cut Line= 2
      2785929.98     10103534.73      2786591.33     10103104.08
#Sta/Elev= 30
  4746.3 1883.74  4753.9 1882.22  4804.2 1878.58  4832.3  1877.5  4853.4 1875.21
    4935 1872.02  4956.1  1870.1  4962.1 1868.84  4971.2 1865.54  4983.2 1855.87
  4986.7 1854.09  4995.3 1849.64    4998 1849.14  5001.3 1849.64    5007 1849.72
  5015.2 1851.32  5055.6 1853.59  5158.3 1854.96  5230.8 1858.87  5281.5 1860.06
  5330.3 1864.98  5360.5 1865.62  5388.9 1869.61  5411.9 1871.59  5448.2 1879.95
  5454.1 1880.96  5469.2 1885.55  5496.3  1890.2  5520.1 1892.94  5535.5 1893.71
#Mann= 5 ,-1 , 0
  4746.3      .1       0  4995.3     .07       0  5001.3      .1       0
  5015.2     .05       0  5448.2      .1       0
Bank Sta=4986.7,5055.6
XS Rating Curve= 0 ,0
Exp/Cntr=0.3,0.1

Type RM Length L Ch R = 1 ,70635   ,414,414,414
BEGIN DESCRIPTION:
WILLOW CREEK 117.0
END DESCRIPTION:
XS GIS Cut Line= 2
      2786322.14     10103842.33      2786760.42     10103488.63
#Sta/Elev= 30
  4725.1 1862.85  4735.2 1862.04  4792.8 1859.65  4799.2 1858.95  4842.4 1856.58
  4935.1  1853.3  4941.5 1852.75  4955.9 1848.96  4970.3 1846.07  4987.7 1844.15
  4996.1 1843.07  4998.8 1842.57  5002.1 1843.07  5005.5    1844  5019.9 1846.58
  5034.3  1848.4  5055.1  1850.3  5077.4 1851.75  5083.9 1852.55    5127 1855.79
  5195.4 1863.92  5205.4 1865.87  5211.8 1867.64  5226.2 1873.07  5234.2 1876.89
  5247.2 1883.99    5255  1886.7  5261.4 1888.51  5275.8 1891.48  5288.3 1892.54
#Mann= 5 ,-1 , 0
  4725.1      .1       0  4987.7     .05       0  4996.1    .035       0
  5002.1     .05       0  5195.4     .16       0
Bank Sta=4970.3,5019.9
XS Rating Curve= 0 ,0
Exp/Cntr=0.3,0.1

Type RM Length L Ch R = 1 ,70221   ,472,472,472
BEGIN DESCRIPTION:
WILLOW CREEK 116.0
END DESCRIPTION:
XS GIS Cut Line= 2
      2786545.17     10104211.42      2787060.38     10103750.04
#Sta/Elev= 30
  4614.8 1858.56  4793.2 1852.52  4870.8 1849.76  4934.1 1847.87  4969.3 1842.94
  5002.2 1839.09  5004.9 1838.59  5008.2 1839.09  5011.4 1840.27  5026.1 1843.04
  5068.9 1848.17  5139.8 1855.66    5154 1859.46  5160.7 1863.32  5168.2 1863.95
  5174.9 1867.07  5182.4 1866.96  5189.1 1870.55  5203.3 1867.98    5210 1870.62
  5217.5 1869.27  5224.2 1872.33  5231.7 1870.44  5236.1 1872.58  5238.4  1873.7
  5245.9 1871.61  5252.6  1874.8  5260.1  1873.5  5266.8  1876.3  5306.4 1875.07
#Mann= 8 ,-1 , 0
  4614.8      .1       0  4793.2     .05       0  4870.8      .1       0
  5002.2     .07       0  5008.2      .1       0  5011.4     .05       0
  5068.9     .16       0  5236.1      .1       0
Bank Sta=4969.3,5026.1
XS Rating Curve= 0 ,0
Exp/Cntr=0.3,0.1

Type RM Length L Ch R = 1 ,69749   ,573,573,573
BEGIN DESCRIPTION:
WILLOW CREEK 115.0
END DESCRIPTION:
XS GIS Cut Line= 2
      2786682.82     10104605.03      2787398.95     10104136.29
#Sta/Elev= 30
  4447.7 1859.55  4474.9 1858.19  4502.3 1859.27    4562 1857.48  4585.1 1855.92
  4606.5 1855.24  4713.1 1850.35  4728.2 1848.66  4749.3 1844.07  4764.4 1842.38
  4836.8 1840.51  4908.6 1840.41  4936.2 1841.56  4944.5 1839.44  4957.3 1837.81
  4966.4 1835.39  4972.4 1834.96  4987.5    1832  4993.5 1831.88  4999.6 1830.08
  5002.4 1829.58  5005.6 1830.08  5016.2 1837.41  5023.7 1840.92  5029.7 1841.13
  5132.3 1841.53  5168.5 1842.28  5231.7 1846.02    5283 1847.21  5303.6 1846.23
#Mann= 5 ,-1 , 0
  4447.7      .1       0  4585.1     .05       0  4606.5      .1       0
  4999.6     .07       0  5005.6      .1       0
#XS Ineff= 2 , 0
         4935.58 1841.56 5044.26         1841.58
Permanent Ineff=
       F       F
Bank Sta=4957.3,5016.2
XS Rating Curve= 0 ,0
Exp/Cntr=0.3,0.1

Type RM Length L Ch R = 1 ,69176   ,434,434,434
BEGIN DESCRIPTION:
Mapping XS 02b2566a
END DESCRIPTION:
XS GIS Cut Line= 4
       2786747.9     10104852.42      2787190.65     10104787.31
      2787698.47     10104539.91      2787932.36     10104228.06
#Sta/Elev= 30
  4276.5 1851.82    4297 1852.31  4302.1 1853.34  4337.7 1853.79  4479.2 1852.47
  4661.2  1845.4    4786 1838.02  4831.1 1836.34  4881.7 1836.11  4926.8 1832.33
  4943.8 1829.78  4949.4 1829.95  4955.2 1828.45  4988.5 1827.33  4991.4 1825.53
  4994.2 1825.03  4997.4 1825.53  5022.5 1827.21    5033 1829.56  5039.5 1833.47
  5045.1    1834  5055.3    1838  5067.6 1840.39  5180.3 1844.95  5247.9    1852
    5300 1855.26  5524.4 1862.94  5567.2 1864.63  5629.2 1867.23  5678.7 1872.33
#Mann= 5 ,-1 , 0
  4276.5      .1       0  4991.4     .07       0  4997.4      .1       0
  5524.4     .16       0  5567.2      .1       0
Bank Sta=4926.8,5039.5
XS Rating Curve= 0 ,0
Exp/Cntr=0.3,0.1

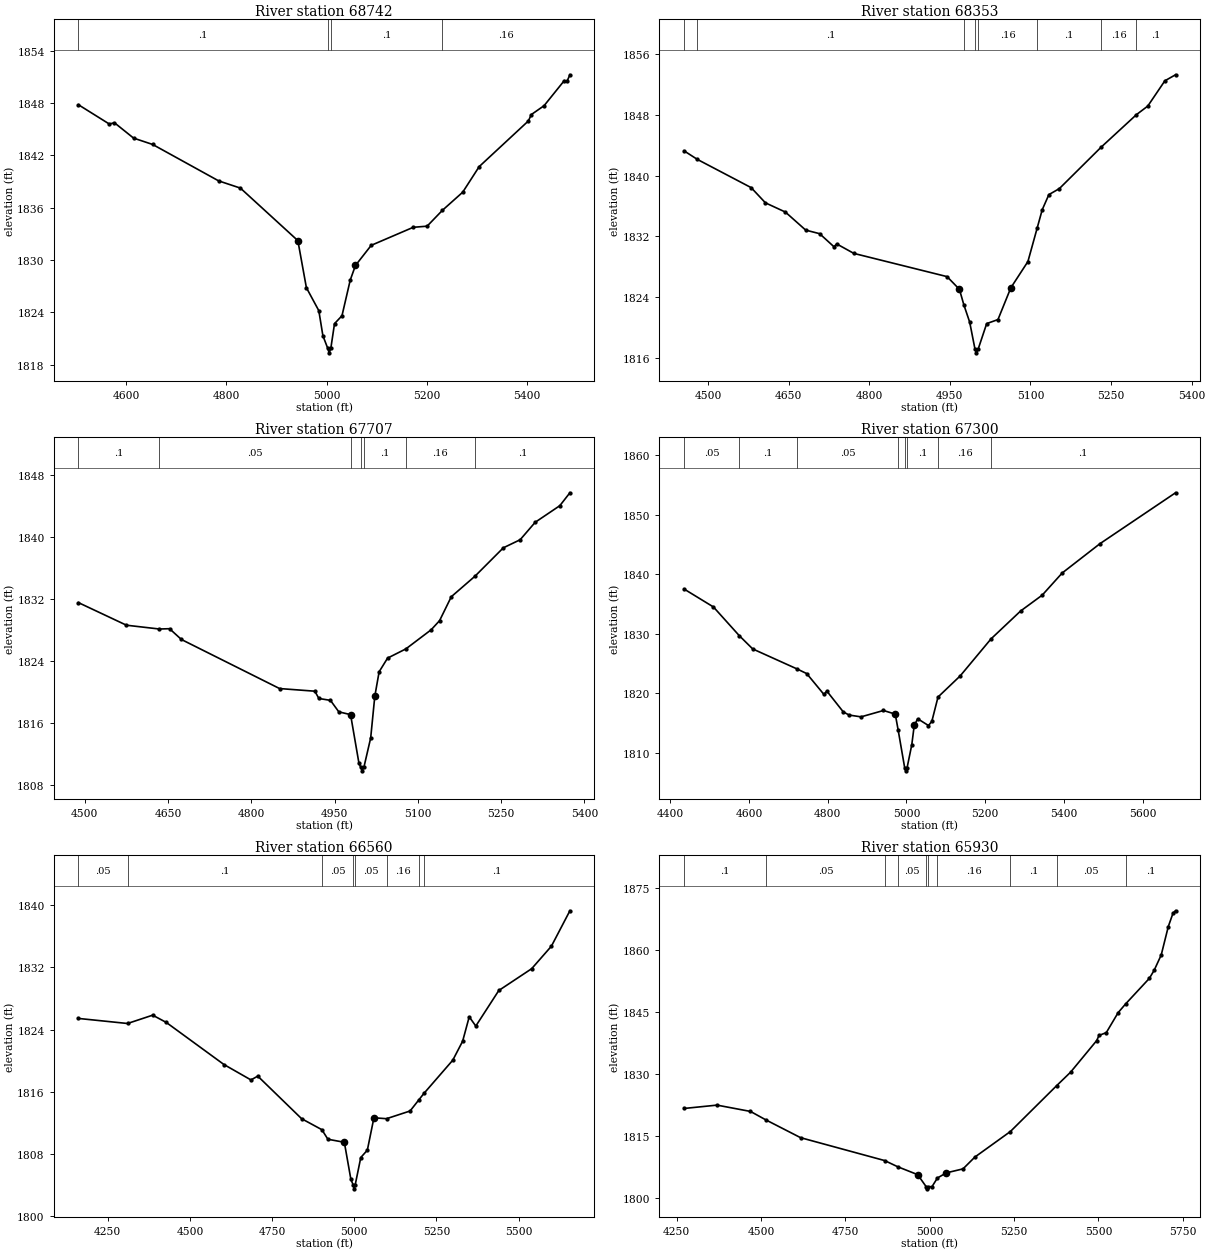
Type RM Length L Ch R = 1 ,68742   ,389,389,389
BEGIN DESCRIPTION:
WILLOW CREEK 114.0
END DESCRIPTION:
XS GIS Cut Line= 2
      2787029.64     10105211.09      2787967.75     10104926.58
#Sta/Elev= 30
  4505.1 1847.82  4566.6 1845.61    4577 1845.75  4615.1 1843.99  4653.2 1843.26
  4784.8 1839.08  4828.2 1838.25  4942.8 1832.22  4959.8 1826.82  4984.6 1824.18
  4992.7 1821.31  5002.5 1819.84  5005.2 1819.34  5008.5 1819.84  5015.9 1822.69
  5030.8  1823.6  5047.3  1827.7  5057.7 1829.37  5089.1 1831.68  5172.9 1833.75
  5200.6 1833.88  5231.1  1835.7  5271.6 1837.78  5304.5 1840.72  5402.6 1845.96
  5408.4 1846.69  5433.9 1847.71  5474.2 1850.59  5479.5 1850.49  5485.4 1851.26
#Mann= 4 ,-1 , 0
  4505.1      .1       0  5002.5     .07       0  5008.5      .1       0
  5231.1     .16       0
Bank Sta=4942.8,5057.7
XS Rating Curve= 0 ,0
Exp/Cntr=0.3,0.1

Type RM Length L Ch R = 1 ,68353   ,646,646,646
BEGIN DESCRIPTION:
WILLOW CREEK 112.0
END DESCRIPTION:
XS GIS Cut Line= 2
      2787183.44     10105557.12      2788052.35     10105272.61
#Sta/Elev= 30
  4455.6 1843.24  4480.5 1842.11  4580.4 1838.41    4607 1836.41  4644.1  1835.2
  4681.9 1832.83  4707.8 1832.36  4734.4 1830.65  4739.7 1831.01  4771.5 1829.77
  4944.9 1826.72  4967.9 1825.05  4976.1 1823.02    4987 1820.74  4996.8 1817.21
  4999.5 1816.71  5002.8 1817.21  5018.6 1820.55  5039.6 1821.08  5063.5 1825.25
  5095.3  1828.7  5112.5 1833.09  5121.9  1835.5  5134.3 1837.49  5153.8 1838.28
  5231.2  1843.7  5297.3    1848  5318.3 1849.12  5350.1 1852.44  5369.9 1853.23
#Mann= 8 ,-1 , 0
  4455.6     .05       0  4480.5      .1       0  4976.1     .16       0
  4996.8     .07       0  5002.8     .16       0  5112.5      .1       0
  5231.2     .16       0  5297.3      .1       0
Bank Sta=4967.9,5063.5
XS Rating Curve= 0 ,0
Exp/Cntr=0.3,0.1

Type RM Length L Ch R = 1 ,67707   ,407,407,407
BEGIN DESCRIPTION:
WILLOW CREEK 111.0
END DESCRIPTION:
XS GIS Cut Line= 3
      2787521.75     10106249.21      2787844.73     10105941.62
      2788213.66     10105703.35
#Sta/Elev= 30
  4488.7 1831.53  4575.2 1828.62  4634.4 1828.13  4652.8 1828.17  4674.2 1826.78
    4851 1820.46  4914.5 1820.12  4921.8 1819.18  4942.6 1818.94  4957.7 1817.46
  4978.9  1817.1  4979.1 1817.01    4994 1810.82    4997 1810.36  4999.7 1809.86
    5003 1810.36  5015.1  1814.1  5022.5 1819.46  5030.3 1822.62  5045.5 1824.38
  5078.5 1825.57    5124 1828.03  5139.2 1829.21  5160.3 1832.29  5202.9 1834.93
    5254 1838.59  5284.3 1839.63  5311.4 1841.88  5355.8 1844.02  5373.9 1845.68
#Mann= 7 ,-1 , 0
  4488.7      .1       0  4634.4     .05       0  4979.1      .1       0
    4997     .07       0    5003      .1       0  5078.5     .16       0
  5202.9      .1       0
Bank Sta=4978.9,5022.5
XS Rating Curve= 0 ,0
Exp/Cntr=0.3,0.1

Type RM Length L Ch R = 1 ,67300   ,740,740,740
BEGIN DESCRIPTION:
WILLOW CREEK 110.0
END DESCRIPTION:
XS GIS Cut Line= 3
      2787760.14     10106718.29      2788190.76     10106080.04
      2788398.39     10105649.42
#Sta/Elev= 30
  4435.2 1837.52  4509.9  1834.5  4575.3 1829.69  4609.6 1827.45  4722.5 1824.08
  4746.7 1823.31  4790.5  1819.8  4797.7 1820.38  4839.7 1816.86  4854.6 1816.34
  4884.6 1816.04  4941.6 1817.11  4971.5  1816.5  4978.8 1813.86  4995.5 1807.47
  4998.3 1806.97  5001.5 1807.47  5013.5 1811.36  5019.7  1814.6  5028.5 1815.72
  5055.9 1814.58  5064.4 1815.28  5080.1 1819.37  5136.4 1822.92  5214.7 1829.14
  5289.9 1833.83  5344.7 1836.49  5395.4 1840.21  5491.4 1845.14  5683.2 1853.69
#Mann= 8 ,-1 , 0
  4435.2     .05       0  4575.3      .1       0  4722.5     .05       0
  4978.8      .1       0  4995.5     .07       0  5001.5      .1       0
  5080.1     .16       0  5214.7      .1       0
#XS Ineff= 2 , 0
         4941.95  1817.1
Permanent Ineff=
       F       F
Bank Sta=4971.5,5019.7
XS Rating Curve= 0 ,0
Exp/Cntr=0.3,0.1

Type RM Length L Ch R = 1 ,66560   ,630,630,630
BEGIN DESCRIPTION:
WILLOW CREEK 108.0
END DESCRIPTION:
XS GIS Cut Line= 3
      2788506.04     10107302.73      2788667.53     10106664.46
      2788659.85     10105827.48
#Sta/Elev= 30
  4160.8 1825.44  4310.2 1824.79  4386.7 1825.86    4428 1824.93  4603.6 1819.52
  4685.8 1817.54  4706.5 1818.03  4839.9 1812.56  4901.5 1811.15  4919.9 1809.92
  4969.9 1809.53  4989.9 1804.75  4996.9 1804.05  4999.7 1803.55  5002.9 1804.05
  5019.9 1807.57  5039.9 1808.52  5059.9 1812.68  5098.2 1812.56  5169.9 1813.55
  5196.6 1814.98  5211.9  1815.8  5299.9 1820.08  5329.9 1822.52  5349.9 1825.65
  5369.9 1824.46  5439.9 1829.03  5539.9 1831.83  5599.9 1834.72  5656.2 1839.27
#Mann= 8 ,-1 , 0
  4160.8     .05       0  4310.2      .1       0  4901.5     .05       0
  4996.9     .07       0  5002.9     .05       0  5098.2     .16       0
  5196.6     .05       0  5211.9      .1       0
Bank Sta=4969.9,5059.9
XS Rating Curve= 0 ,0
Exp/Cntr=0.3,0.1

Type RM Length L Ch R = 1 ,65930   ,725,725,725
BEGIN DESCRIPTION:
WILLOW CREEK 107.0
END DESCRIPTION:
XS GIS Cut Line= 2
      2788721.38     10107195.02      2789712.16     10106127.44
#Sta/Elev= 30
    4272 1821.69  4369.7  1822.5  4468.9 1820.97  4515.1  1818.9  4617.4 1814.62
  4866.6 1809.08  4904.8  1807.6  4964.4 1805.67  4989.7 1802.74  4992.5 1802.24
  4995.7 1802.74  5006.9 1802.78  5022.9 1804.87  5049.4 1806.11  5098.7 1807.07
  5133.9 1809.93  5239.1 1816.11  5376.6 1827.24  5417.3 1830.45    5495 1838.13
  5501.8 1839.37  5523.3 1840.04  5558.5 1844.88  5580.7    1847  5650.9 1853.17
  5665.1 1855.11  5686.1 1858.83  5707.1 1865.71  5721.2 1868.98  5728.5 1869.53
#Mann= 10 ,-1 , 0
    4272      .1       0  4515.1     .05       0  4866.6     .16       0
  4904.8     .05       0  4989.7    .035       0  4995.7     .05       0
  5022.9     .16       0  5239.1      .1       0  5376.6     .05       0
  5580.7      .1       0
Bank Sta=4964.4,5049.4
XS Rating Curve= 0 ,0
Exp/Cntr=0.3,0.1

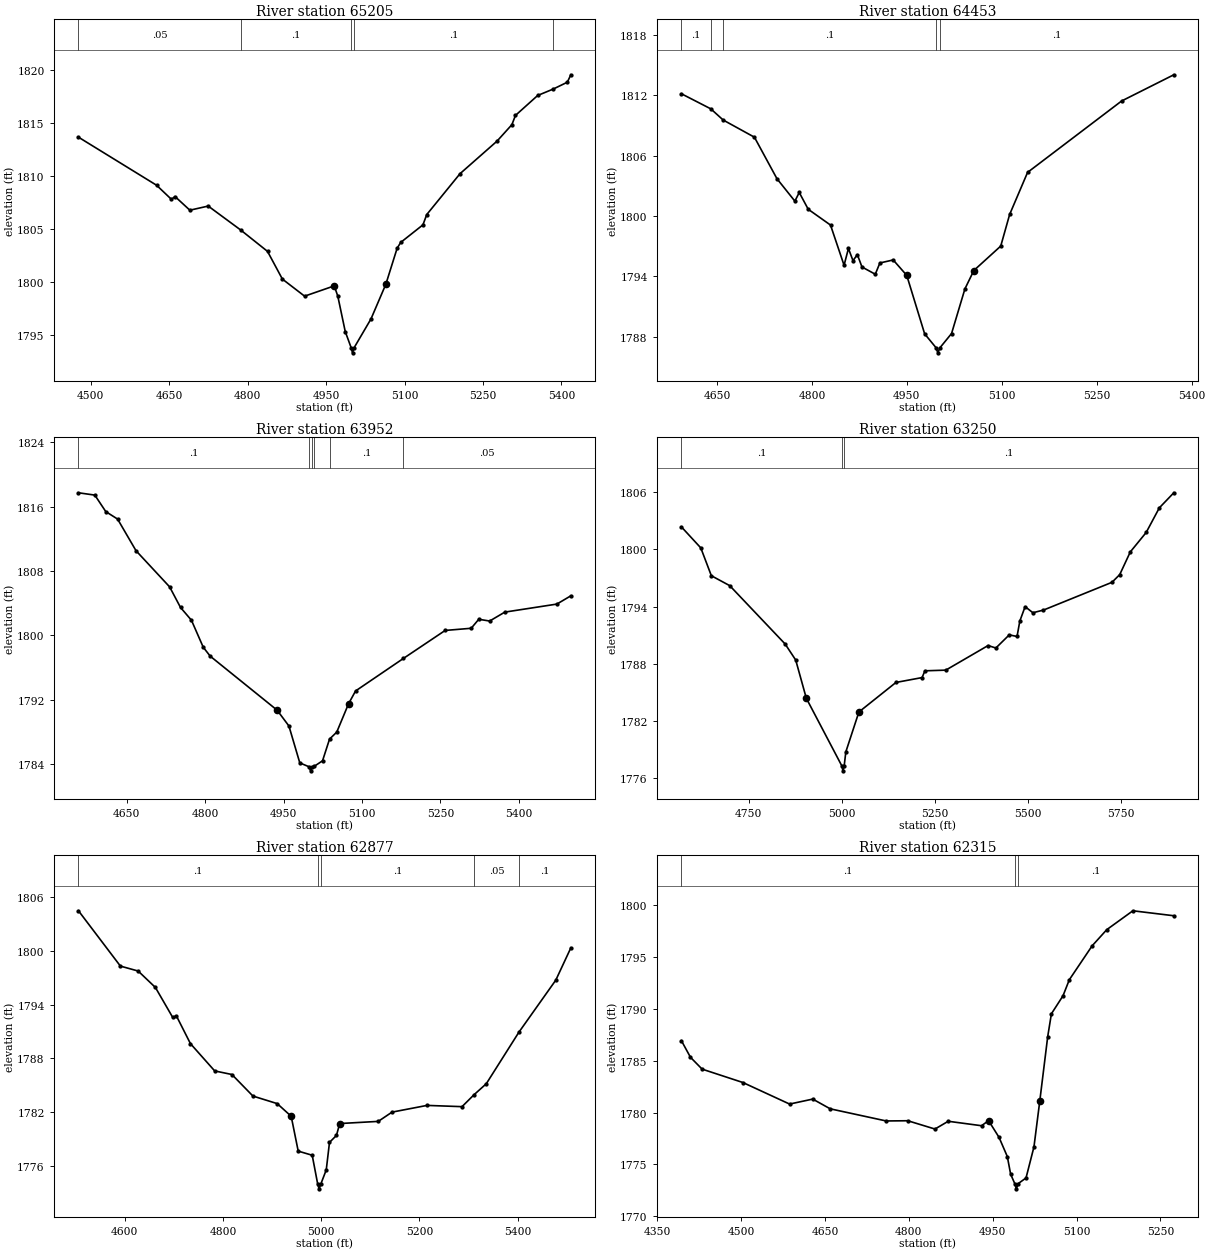
Type RM Length L Ch R = 1 ,65205   ,752,752,752
BEGIN DESCRIPTION:
WILLOW CREEK 105.0
END DESCRIPTION:
XS GIS Cut Line= 2
      2789367.28     10107433.44       2790059.4     10106795.16
#Sta/Elev= 30
  4476.5 1813.66  4625.9 1809.13  4654.3  1807.8  4661.1 1808.07  4689.5 1806.78
  4724.6 1807.17  4786.8 1804.91    4838  1802.9  4866.4 1800.29  4908.9 1798.68
  4965.6 1799.65  4972.4 1798.68  4986.6 1795.35  4997.8 1793.84  5000.5 1793.34
  5003.8 1793.84  5035.9 1796.54  5064.3 1799.81  5085.8 1803.19  5092.6 1803.74
  5135.2  1805.4  5142.5 1806.37  5206.1 1810.22  5276.9 1813.29  5305.3 1814.84
  5312.1 1815.71  5354.6 1817.59  5384.1 1818.19  5411.3 1818.84    5418 1819.54
#Mann= 5 ,-1 , 0
  4476.5     .05       0  4786.8      .1       0  4997.8     .07       0
  5003.8      .1       0  5384.1     .16       0
Bank Sta=4965.6,5064.3
XS Rating Curve= 0 ,0
Exp/Cntr=0.3,0.1

Type RM Length L Ch R = 1 ,64453   ,501,501,501
BEGIN DESCRIPTION:
WILLOW CREEK 104.0
END DESCRIPTION:
XS GIS Cut Line= 2
      2789674.86     10108033.26      2790213.19     10107471.86
#Sta/Elev= 30
  4593.9 1812.15  4640.3 1810.65  4659.8 1809.54  4709.2 1807.83  4744.8  1803.7
  4773.1 1801.47    4780 1802.33  4794.2 1800.66  4829.4 1799.09  4850.8 1795.09
  4857.7 1796.76  4864.9 1795.55  4871.8 1796.15  4879.1 1794.92  4900.1  1794.2
  4907.4 1795.32  4928.4 1795.62  4949.8 1794.09  4978.1 1788.27  4996.2 1786.88
  4998.9 1786.38  5002.2 1786.88  5020.6  1788.3  5041.7 1792.74  5055.8 1794.57
  5098.3    1797  5112.4 1800.15  5140.7 1804.33  5289.2 1811.43  5371.7 1814.04
#Mann= 5 ,-1 , 0
  4593.9      .1       0  4640.3     .05       0  4659.8      .1       0
  4996.2     .07       0  5002.2      .1       0
Bank Sta=4949.8,5055.8
XS Rating Curve= 0 ,0
Exp/Cntr=0.3,0.1

Type RM Length L Ch R = 1 ,63952   ,702,702,702
BEGIN DESCRIPTION:
WILLOW CREEK 102.0
END DESCRIPTION:
XS GIS Cut Line= 2
      2790043.98     10108433.12      2790620.12     10107687.97
#Sta/Elev= 30
  4557.5 1817.74  4588.8 1817.45  4609.7  1815.4  4632.3 1814.47  4667.6 1810.53
  4731.9 1806.03  4752.7 1803.47  4773.6 1801.88  4796.2 1798.52  4809.5 1797.41
  4937.5 1790.69  4960.1 1788.72  4980.9 1784.13  4998.8 1783.64  5001.5 1783.14
  5004.8 1783.64  5008.2 1783.69  5024.4 1784.39  5037.8 1787.09  5051.6 1787.96
  5074.2 1791.49  5087.6 1793.08  5179.2 1797.13    5259 1800.61  5308.8 1800.88
  5323.3    1802  5344.1 1801.78  5373.1 1802.89  5472.7 1803.89  5499.4 1804.92
#Mann= 6 ,-1 , 0
  4557.5      .1       0  4998.8     .07       0  5004.8      .1       0
  5008.2     .05       0  5037.8      .1       0  5179.2     .05       0
Bank Sta=4937.5,5074.2
XS Rating Curve= 0 ,0
Exp/Cntr=0.3,0.1

Type RM Length L Ch R = 1 ,63250   ,373,373,373
BEGIN DESCRIPTION:
WILLOW CREEK 101.0
END DESCRIPTION:
XS GIS Cut Line= 2
      2790597.64     10108756.09      2791473.86     10107764.58
#Sta/Elev= 30
  4569.3 1802.36  4621.3 1800.16  4649.7 1797.24  4699.1  1796.2    4848 1790.08
  4876.4  1788.4  4904.9 1784.39  5000.6 1777.28  5003.3 1776.78  5006.6 1777.28
  5011.1 1778.77  5046.2 1782.95  5145.8 1786.05    5216 1786.56  5223.6 1787.27
  5279.7 1787.34  5393.4 1789.92  5414.3 1789.66  5450.3 1791.04  5471.2 1790.87
  5478.7 1792.49  5492.9    1794  5513.8 1793.36  5542.3 1793.64  5726.3 1796.55
  5747.2 1797.36  5775.6 1799.74  5818.3 1801.78  5853.6 1804.36  5892.5 1805.94
#Mann= 3 ,-1 , 0
  4569.3      .1       0  5000.6     .07       0  5006.6      .1       0
Bank Sta=4904.9,5046.2
XS Rating Curve= 0 ,0
Exp/Cntr=0.3,0.1

Type RM Length L Ch R = 1 ,62877   ,562,562,562
BEGIN DESCRIPTION:
WILLOW CREEK 100.0
END DESCRIPTION:
XS GIS Cut Line= 2
      2790805.27     10108971.39      2791566.03     10108318.21
#Sta/Elev= 30
  4505.7 1804.44  4591.1 1798.28  4627.3 1797.73  4662.4  1795.9  4697.5 1792.58
  4705.2 1792.73  4733.7 1789.65  4783.1 1786.61  4818.2 1786.21    4861 1783.81
  4910.4 1782.97  4938.9 1781.56  4953.2 1777.68  4981.7 1777.22    4993 1773.98
  4995.8 1773.48    4999 1773.98  5010.3 1775.59  5016.9 1778.65  5031.1 1779.43
  5037.7 1780.75  5116.2 1780.99  5144.2 1782.02  5215.5 1782.77  5286.8 1782.63
  5311.5 1783.97  5336.2 1785.18  5402.5 1790.91  5477.8 1796.72  5508.4 1800.31
#Mann= 5 ,-1 , 0
  4505.7      .1       0    4993     .07       0    4999      .1       0
  5311.5     .05       0  5402.5      .1       0
Bank Sta=4938.9,5037.7
XS Rating Curve= 0 ,0
Exp/Cntr=0.3,0.1

Type RM Length L Ch R = 1 ,62315   ,347,347,347
BEGIN DESCRIPTION:
WILLOW CREEK 99.0
END DESCRIPTION:
XS GIS Cut Line= 2
       2791112.9     10108971.37      2791958.74     10108725.31
#Sta/Elev= 30
  4393.1 1786.94  4409.3 1785.34  4430.1  1784.2    4503 1782.91  4586.6 1780.83
    4628 1781.31  4659.3 1780.37  4759.4  1779.2  4798.1 1779.22  4846.7 1778.42
  4870.4 1779.17    4930 1778.74  4942.6 1779.23  4961.3 1777.62  4976.1 1775.77
  4982.1 1774.06  4989.5 1773.15  4992.3 1772.65  4995.5 1773.15  5009.6  1773.7
  5023.8  1776.7  5034.2 1781.12  5048.4 1787.34    5055 1789.54  5075.8 1791.28
  5087.1 1792.83  5127.9  1796.1  5154.1 1797.66  5200.8 1799.48    5274    1799
#Mann= 3 ,-1 , 0
  4393.1      .1       0  4989.5     .07       0  4995.5      .1       0
Bank Sta=4942.6,5034.2
XS Rating Curve= 0 ,0
Exp/Cntr=0.3,0.1

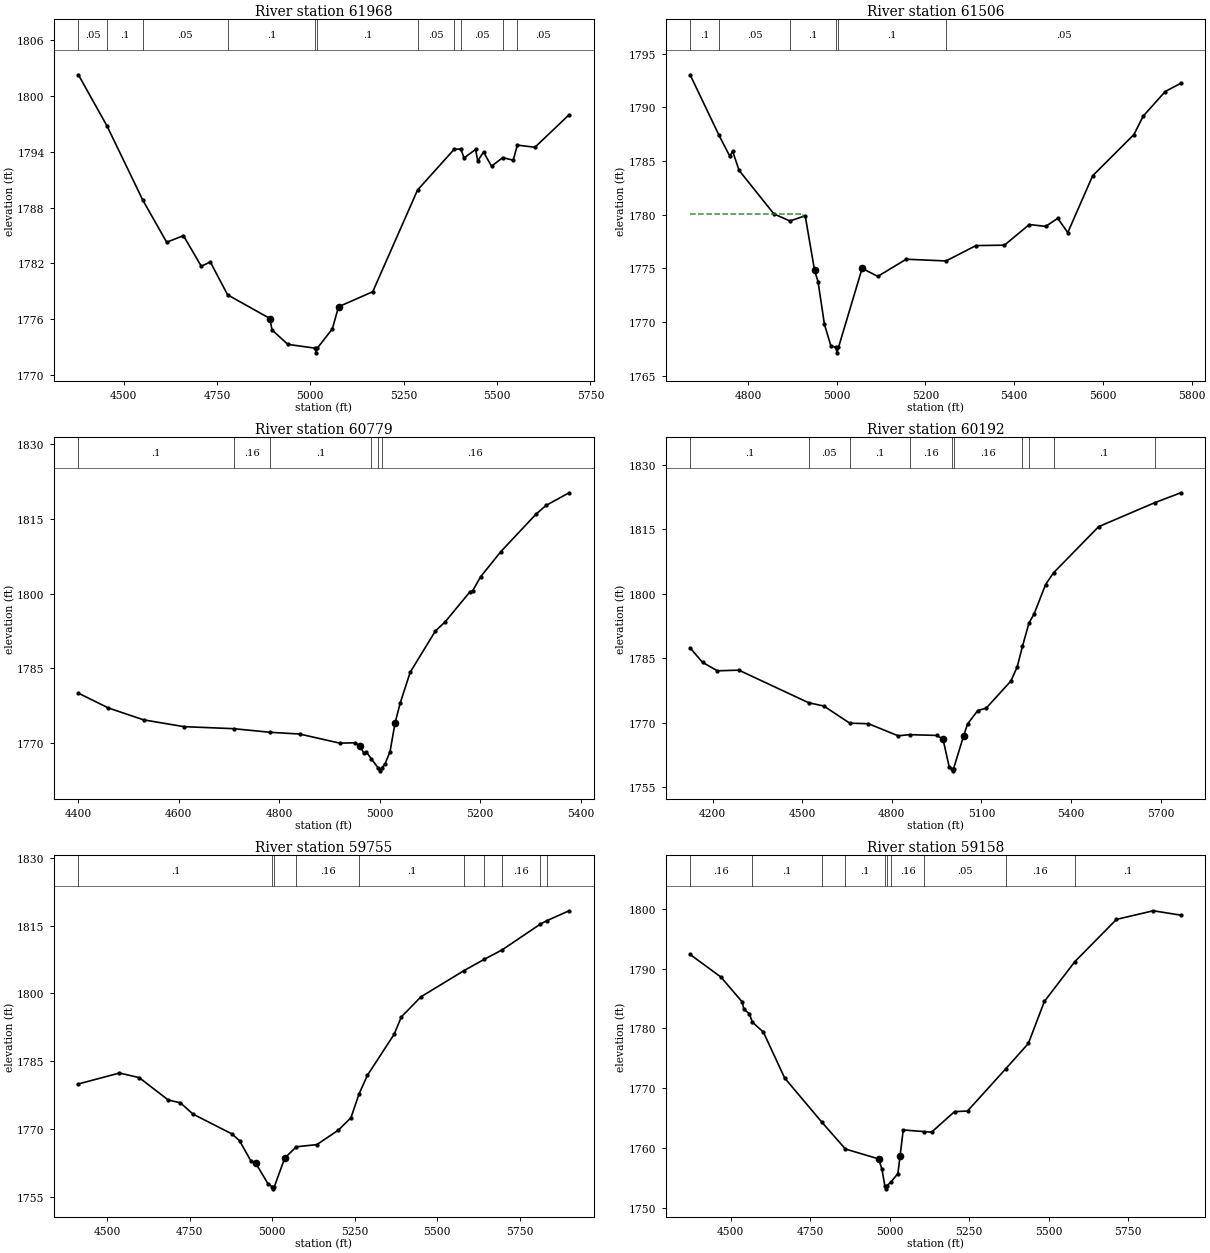
Type RM Length L Ch R = 1 ,61968   ,462,462,462
BEGIN DESCRIPTION:
WILLOW CREEK 98.0
END DESCRIPTION:
XS GIS Cut Line= 3
      2791109.93      10109344.6      2791930.24     10109006.06
      2792151.57      10108641.5
#Sta/Elev= 30
    4379 1802.23  4455.5 1796.75  4551.6 1788.78  4615.4 1784.28  4660.3 1784.98
  4708.1  1781.7  4732.1 1782.17  4778.5 1778.64  4891.8  1776.1  4897.3 1774.88
  4939.7 1773.33  5012.7 1772.92  5015.4 1772.42  5018.7 1772.92    5059 1774.99
  5075.5 1777.36  5167.1 1778.97    5287 1789.87  5385.5 1794.26  5403.2 1794.26
  5411.4 1793.31  5442.4 1794.22  5448.3 1792.99  5463.7 1793.95  5485.1 1792.43
  5515.3 1793.35  5543.2 1793.07  5554.2 1794.69  5601.4 1794.46  5692.9 1797.95
#Mann= 11 ,-1 , 0
    4379     .05       0  4455.5      .1       0  4551.6     .05       0
  4778.5      .1       0  5012.7     .07       0  5018.7      .1       0
    5287     .05       0  5385.5      .1       0  5403.2     .05       0
  5515.3      .1       0  5554.2     .05       0
Bank Sta=4891.8,5075.5
XS Rating Curve= 0 ,0
Exp/Cntr=0.3,0.1

Type RM Length L Ch R = 1 ,61506   ,727,727,727
BEGIN DESCRIPTION:
WILLOW CREEK 97.0
END DESCRIPTION:
XS GIS Cut Line= 2
      2791428.12     10109748.06      2792297.07     10109063.67
#Sta/Elev= 30
  4669.6 1793.03  4734.9 1787.38  4759.1 1785.44  4765.5 1785.91  4779.9 1784.13
  4858.5 1780.07  4894.7 1779.41    4929  1779.9  4950.1 1774.81  4957.9 1773.77
  4972.4 1769.78  4986.8 1767.79    4998 1767.63  5000.7 1767.13    5004 1767.63
  5057.3    1775  5092.6 1774.25  5156.7 1775.85  5246.5 1775.69  5313.9 1777.12
  5378.1 1777.16  5434.1 1779.08  5471.1 1778.91  5498.3 1779.66  5520.8 1778.33
  5576.9 1783.62  5669.9 1787.46  5690.7 1789.17  5740.4 1791.47  5775.7 1792.24
#Mann= 6 ,-1 , 0
  4669.6      .1       0  4734.9     .05       0  4894.7      .1       0
    4998     .07       0    5004      .1       0  5246.5     .05       0
#XS Ineff= 2 , 0
         4923.58 1780.06 5497.46         1779.61
Permanent Ineff=
       F       F
Bank Sta=4950.1,5057.3
XS Rating Curve= 0 ,0
Exp/Cntr=0.3,0.1

Type RM Length L Ch R = 1 ,60779   ,587,587,587
BEGIN DESCRIPTION:
WILLOW CREEK 96.0
END DESCRIPTION:
XS GIS Cut Line= 2
      2791658.83      10109855.7      2792634.44     10109809.61
#Sta/Elev= 30
  4400.1 1780.04  4459.8 1777.07  4529.9 1774.68    4610 1773.32  4709.1 1772.91
  4782.1 1772.18  4840.2 1771.84  4920.3 1770.01  4950.4 1770.08  4960.4 1769.51
  4968.5 1767.94  4973.5 1768.22  4983.3 1766.83  4997.4 1764.95  5000.2 1764.45
  5003.4 1764.95  5010.4 1765.81  5020.4 1768.32  5030.4 1774.09  5040.5 1778.01
  5060.5 1784.24  5110.5 1792.49  5130.6  1794.4  5179.6  1800.4  5184.6 1800.54
  5200.6 1803.39  5240.7 1808.42  5310.8 1815.95  5330.8 1817.71  5376.8 1820.25
#Mann= 6 ,-1 , 0
  4400.1      .1       0  4709.1     .16       0  4782.1      .1       0
  4983.3     .16       0  4997.4     .07       0  5003.4     .16       0
Bank Sta=4960.4,5030.4
XS Rating Curve= 0 ,0
Exp/Cntr=0.3,0.1

Type RM Length L Ch R = 1 ,60192   ,437,437,437
BEGIN DESCRIPTION:
WILLOW CREEK 95.0
END DESCRIPTION:
XS GIS Cut Line= 4
      2791489.63     10109894.12      2792112.54      10110378.6
      2792304.78     10110424.74      2792934.43     10110240.45
#Sta/Elev= 30
  4124.7 1787.38  4166.2 1784.03  4215.9 1782.05  4287.9  1782.2  4521.4 1774.61
  4572.5 1773.84    4659 1769.85  4721.8 1769.72  4821.3  1766.9  4859.2 1767.17
  4950.8 1766.99  4971.4 1766.11  4991.9 1759.71  5000.7 1759.24  5003.5 1758.74
  5006.7 1759.24  5040.6 1766.95  5053.6 1769.66  5087.7 1772.79  5116.1 1773.35
  5198.7 1779.68  5219.6 1782.93  5237.4 1787.76  5259.4 1793.23  5276.1 1795.25
  5314.7 1802.14  5341.5 1804.89  5492.3 1815.63  5680.1 1821.22  5767.6 1823.53
#Mann= 10 ,-1 , 0
  4124.7      .1       0  4521.4     .05       0    4659      .1       0
  4859.2     .16       0  5000.7     .07       0  5006.7     .16       0
  5237.4      .1       0  5259.4     .16       0  5341.5      .1       0
  5680.1     .16       0
Bank Sta=4971.4,5040.6
XS Rating Curve= 0 ,0
Exp/Cntr=0.3,0.1

Type RM Length L Ch R = 1 ,59755   ,597,597,597
BEGIN DESCRIPTION:
WILLOW CREEK 93.0
END DESCRIPTION:
XS GIS Cut Line= 2
      2791689.62     10111086.05      2792995.13     10110371.86
#Sta/Elev= 30
  4412.1 1779.97  4536.7 1782.39  4596.5 1781.37  4684.4 1776.43  4721.7 1775.78
  4759.6  1773.3  4878.1 1768.89  4900.9 1767.39  4935.1 1762.94  4950.2 1762.38
  4988.2 1757.74  5000.5 1757.25  5003.3 1756.75  5006.5 1757.25  5037.7 1763.55
    5073 1766.06  5135.2 1766.54  5200.6 1769.75  5238.6 1772.48  5262.9 1777.72
  5288.5 1781.88  5369.5 1790.96  5391.3  1794.8    5451 1799.27  5581.8 1805.08
  5642.7 1807.56    5697 1809.65  5812.2 1815.32  5832.6 1816.12  5900.2 1818.31
#Mann= 10 ,-1 , 0
  4412.1      .1       0  5000.5     .07       0  5006.5      .1       0
    5073     .16       0  5262.9      .1       0  5581.8     .16       0
  5642.7      .1       0    5697     .16       0  5812.2      .1       0
  5832.6     .16       0
Bank Sta=4950.2,5037.7
XS Rating Curve= 0 ,0
Exp/Cntr=0.3,0.1

Type RM Length L Ch R = 1 ,59158   ,732,732,732
BEGIN DESCRIPTION:
WILLOW CREEK 92.0
END DESCRIPTION:
XS GIS Cut Line= 3
       2791930.2      10111584.2      2792698.47     10111193.56
       2793374.5     10111115.56
#Sta/Elev= 30
  4372.8 1792.35  4469.7 1788.57  4536.4 1784.41    4542 1783.15  4558.7 1782.46
  4568.5 1781.02  4603.2 1779.35  4669.9 1771.68  4787.1 1764.27    4861 1759.79
  4965.4 1758.14  4975.8  1756.4  4984.9 1753.63  4987.6 1753.13  4990.9 1753.63
  5004.5  1754.3  5025.9 1755.69  5032.7 1758.61  5042.6 1762.98  5108.1 1762.71
  5131.6 1762.61  5203.9 1766.05  5244.7 1766.15  5364.7 1773.21    5436 1777.46
  5486.3 1784.49  5581.9 1791.14  5712.9 1798.22  5828.6 1799.66  5915.2 1798.93
#Mann= 10 ,-1 , 0
  4372.8     .16       0  4568.5      .1       0  4787.1     .16       0
    4861      .1       0  4984.9     .07       0  4990.9      .1       0
  5004.5     .16       0  5108.1     .05       0  5364.7     .16       0
  5581.9      .1       0
#XS Ineff= 2 , 0
                         5042.81         1762.96
Permanent Ineff=
       F       F
Bank Sta=4965.4,5032.7
XS Rating Curve= 0 ,0
Exp/Cntr=0.3,0.1