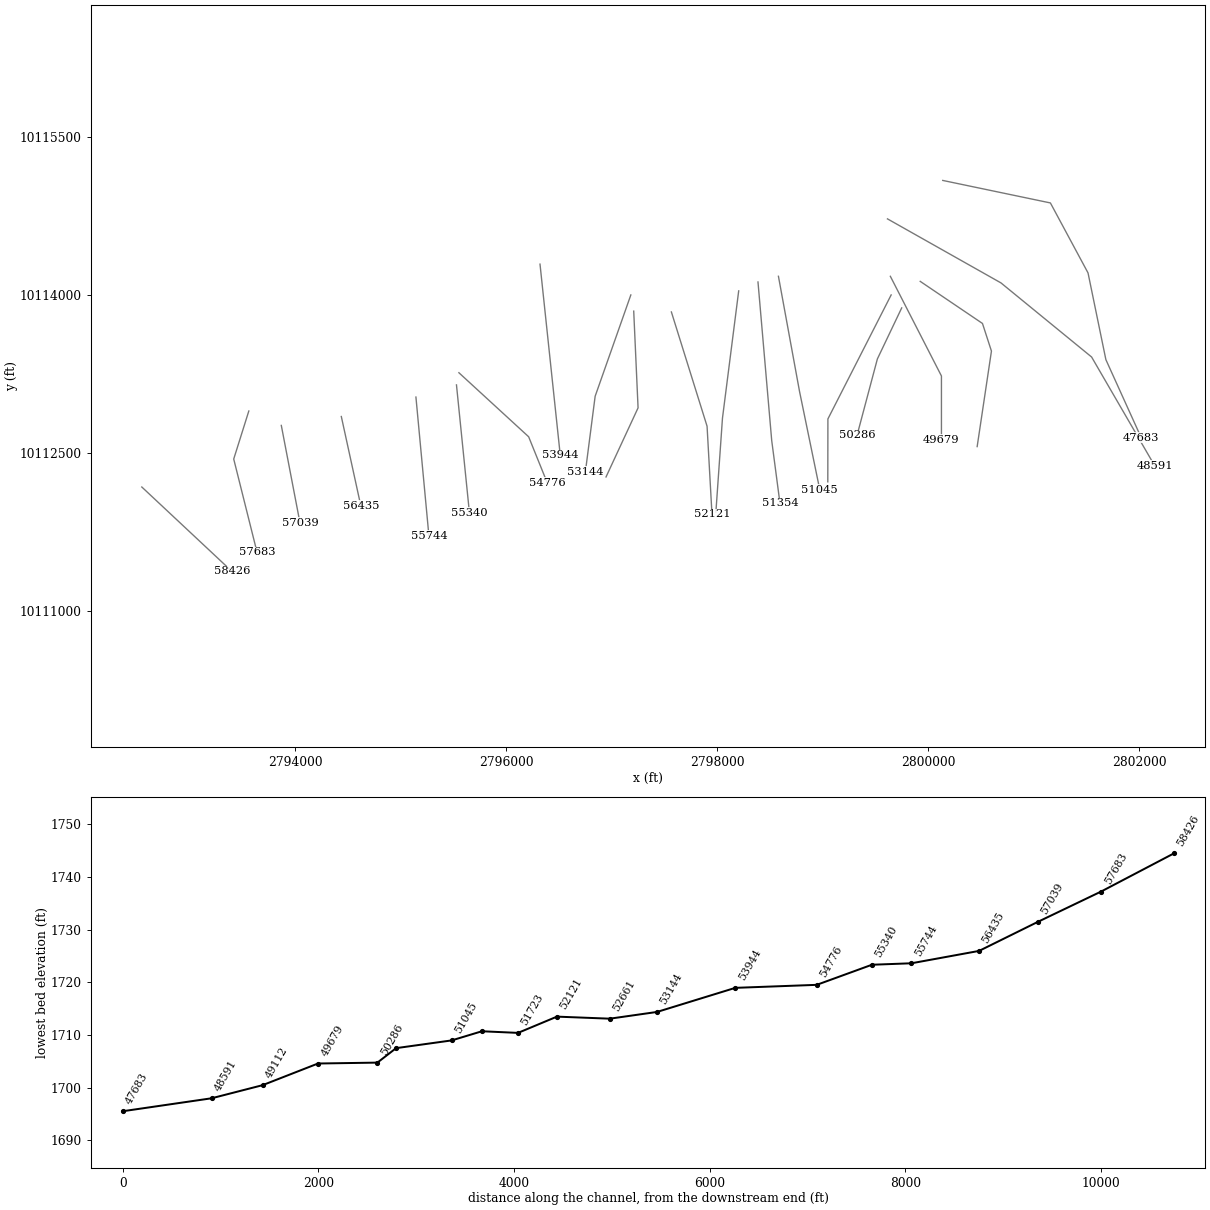
HEC-RAS study WILLOW CREEK.prj: WILLOW CREEK Base Level Engineering

--- WILLOW CREEK.g01 (geometry) --- (continued)

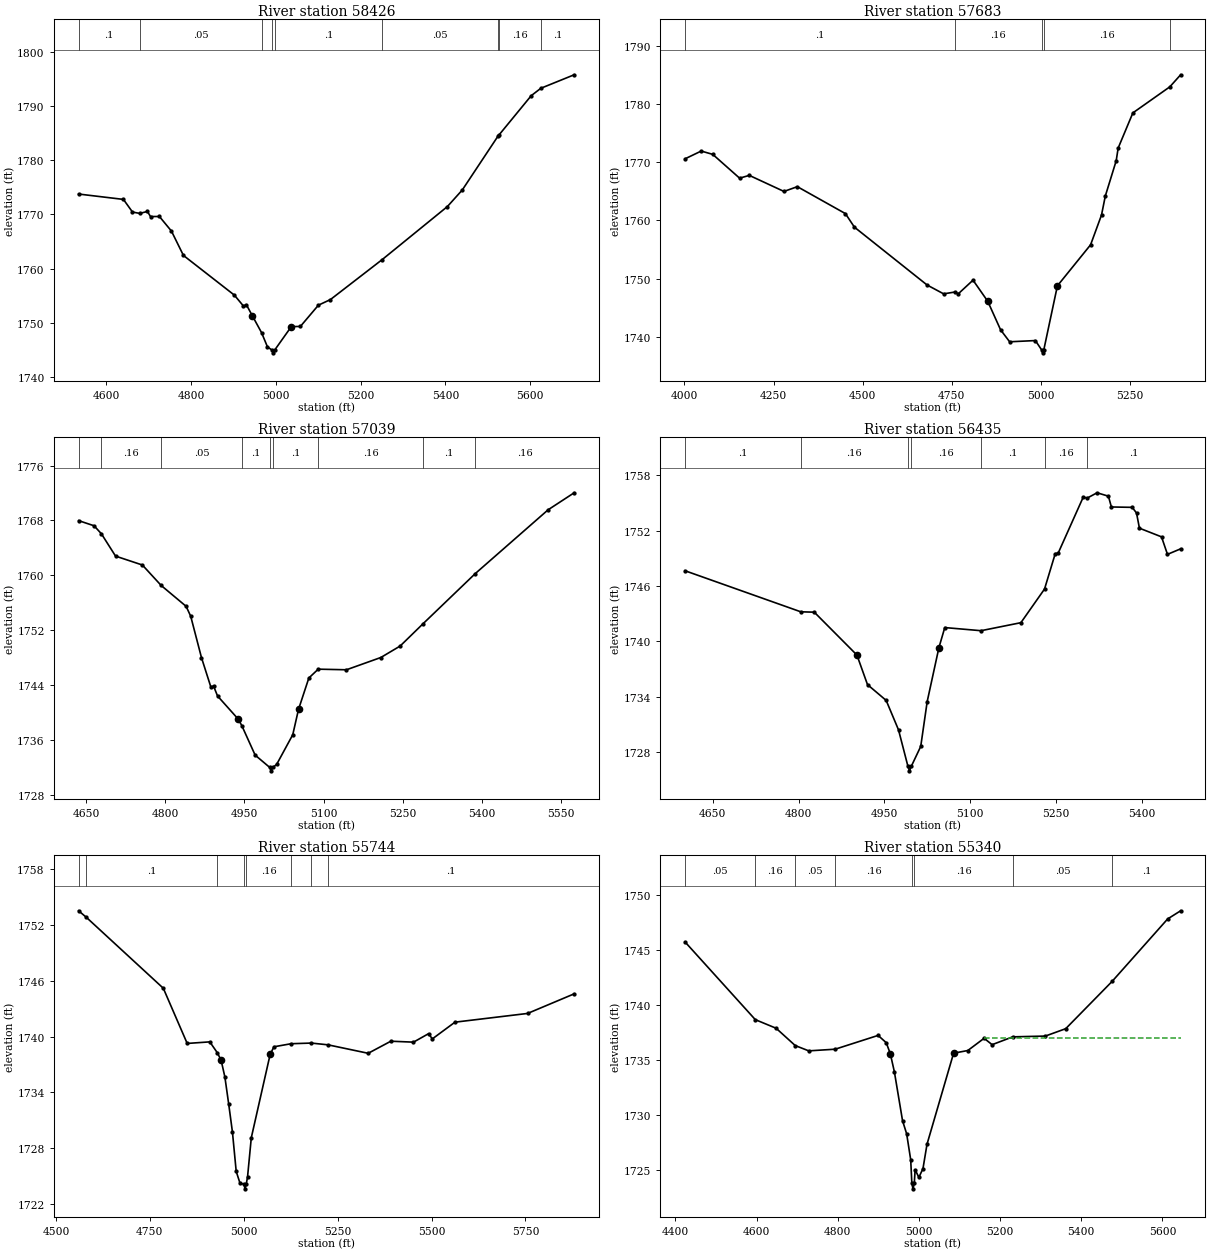
Type RM Length L Ch R = 1 ,58426   ,743,743,743
BEGIN DESCRIPTION:
WILLOW CREEK 90.0
END DESCRIPTION:
XS GIS Cut Line= 2
      2792543.18     10112177.99      2793396.47     10111378.51
#Sta/Elev= 30
  4534.6 1773.77  4640.3 1772.78  4661.7 1770.45  4678.8  1770.2  4696.9 1770.56
  4704.2 1769.62  4725.2 1769.63  4753.6 1766.94  4781.9 1762.45  4902.1 1755.13
  4923.5 1753.12  4930.4 1753.37  4944.6 1751.31  4966.2 1748.22  4980.2 1745.58
  4991.1 1744.99  4993.8 1744.49  4997.1 1744.99  5036.4 1749.32  5057.9 1749.36
  5100.4 1753.28  5128.7 1754.31    5251 1761.69  5404.7 1771.46  5439.9 1774.52
  5524.6  1784.5  5526.8 1784.69  5602.5  1791.9  5625.2 1793.27  5703.9 1795.76
#Mann= 9 ,-1 , 0
  4534.6      .1       0  4678.8     .05       0  4966.2      .1       0
  4991.1     .07       0  4997.1      .1       0    5251     .05       0
  5524.6      .1       0  5526.8     .16       0  5625.2      .1       0
Bank Sta=4944.6,5036.4
XS Rating Curve= 0 ,0
Exp/Cntr=0.3,0.1

Type RM Length L Ch R = 1 ,57683   ,644,644,644
BEGIN DESCRIPTION:
WILLOW CREEK 88.0
END DESCRIPTION:
XS GIS Cut Line= 3
      2793557.84     10112899.28      2793414.61     10112443.56
       2793635.9      10111558.4
#Sta/Elev= 30
  4001.7  1770.6  4046.9 1771.93  4079.3 1771.36  4154.6 1767.27  4181.8 1767.75
    4279 1764.99  4316.6 1765.81  4451.4 1761.18  4476.7 1758.85  4680.5 1748.91
  4726.9 1747.39  4758.5  1747.7  4768.1  1747.4  4809.4 1749.74  4850.6 1746.12
  4886.7 1741.21  4912.1 1739.15  4984.3 1739.36  5001.9 1737.75  5004.7 1737.25
  5007.9 1737.75  5046.1 1748.77  5139.2 1755.82  5169.8 1760.93  5180.5  1764.2
  5211.1 1770.28  5216.5 1772.44  5257.8 1778.49  5361.5 1782.97  5391.8 1785.04
#Mann= 5 ,-1 , 0
  4001.7      .1       0  4758.5     .16       0  5001.9     .07       0
  5007.9     .16       0  5361.5      .1       0
#XS Ineff= 2 , 0
         4809.46 1749.73
Permanent Ineff=
       F       F
Bank Sta=4850.6,5046.1
XS Rating Curve= 0 ,0
Exp/Cntr=0.3,0.1

Type RM Length L Ch R = 1 ,57039   ,604,604,604
BEGIN DESCRIPTION:
WILLOW CREEK 87.0
END DESCRIPTION:
XS GIS Cut Line= 2
      2793865.79     10112762.46      2794042.66     10111839.66
#Sta/Elev= 30
  4635.6 1767.98  4664.9 1767.23  4678.8 1766.06  4705.6 1762.81  4756.5 1761.51
  4792.1 1758.53  4839.4 1755.49  4848.1 1754.05  4868.5 1748.02  4886.3 1743.73
  4891.4 1743.87    4899 1742.42  4938.3 1739.04    4945  1738.1  4970.3  1733.8
  4997.9 1732.01  5000.6 1731.51  5003.9 1732.01    5011 1732.44  5041.6 1736.77
  5052.5 1740.46  5072.1 1745.04  5089.9 1746.33  5143.4 1746.24  5208.6 1748.03
  5245.2  1749.7  5288.5 1752.94  5387.8 1760.27  5525.8 1769.56  5575.2 1772.04
#Mann= 9 ,-1 , 0
  4635.6      .1       0  4678.8     .16       0  4792.1     .05       0
    4945      .1       0  4997.9     .07       0  5003.9      .1       0
  5089.9     .16       0  5288.5      .1       0  5387.8     .16       0
Bank Sta=4938.3,5052.5
XS Rating Curve= 0 ,0
Exp/Cntr=0.3,0.1

Type RM Length L Ch R = 1 ,56435   ,691,691,691
BEGIN DESCRIPTION:
WILLOW CREEK 86.0
END DESCRIPTION:
XS GIS Cut Line= 2
      2794434.84       10112847.       2794619.4      10112001.1
#Sta/Elev= 30
  4601.7 1747.66  4803.8 1743.21  4827.4 1743.17  4901.9 1738.52  4920.4 1735.31
    4953  1733.6  4974.6  1730.4    4991 1726.46  4993.7 1725.96    4997 1726.46
  5013.4 1728.61  5024.7 1733.48  5045.2 1739.33  5055.4  1741.5  5118.7 1741.16
  5188.4 1742.03  5229.7 1745.68  5248.4 1749.52  5253.5 1749.57  5297.4 1755.66
  5304.1 1755.54  5321.5 1756.12  5341.3 1755.75  5346.5 1754.58  5382.9 1754.54
  5390.4 1753.93  5395.5 1752.28  5434.1 1751.34  5444.5 1749.44  5467.5 1750.04
#Mann= 7 ,-1 , 0
  4601.7      .1       0  4803.8     .16       0    4991     .07       0
    4997     .16       0  5118.7      .1       0  5229.7     .16       0
  5304.1      .1       0
Bank Sta=4901.9,5045.2
XS Rating Curve= 0 ,0
Exp/Cntr=0.3,0.1

Type RM Length L Ch R = 1 ,55744   ,404,404,404
BEGIN DESCRIPTION:
WILLOW CREEK 84.0
END DESCRIPTION:
XS GIS Cut Line= 2
       2795142.3     10113031.53      2795265.23     10111717.66
#Sta/Elev= 30
  4560.3 1753.54  4581.2 1752.82  4785.8  1745.2  4849.4 1739.26  4909.6 1739.43
  4929.4 1738.27  4939.7 1737.46  4949.8 1735.64  4959.8 1732.77  4969.9 1729.72
  4979.9 1725.49    4990 1724.22  5000.6 1724.11  5003.4 1723.61  5006.6 1724.11
  5010.1 1724.89  5020.1 1729.11  5070.3 1738.08  5080.4  1738.9  5126.1 1739.23
    5180  1739.3  5224.5 1739.11  5331.4  1738.2  5391.7  1739.5    5452  1739.4
  5492.1 1740.31  5502.2 1739.75  5562.5 1741.55  5755.9 1742.49  5879.9  1744.6
#Mann= 8 ,-1 , 0
  4560.3     .05       0  4581.2      .1       0  4929.4     .16       0
  5000.6     .07       0  5006.6     .16       0  5126.1      .1       0
    5180     .16       0  5224.5      .1       0
Bank Sta=4939.7,5070.3
XS Rating Curve= 0 ,0
Exp/Cntr=0.3,0.1

Type RM Length L Ch R = 1 ,55340   ,564,564,564
BEGIN DESCRIPTION:
WILLOW CREEK 83.0
END DESCRIPTION:
XS GIS Cut Line= 2
      2795526.78     10113146.92      2795649.82     10111931.93
#Sta/Elev= 30
  4423.7 1745.71  4596.7 1738.67    4648 1737.89  4695.1 1736.32  4728.4 1735.84
  4793.5 1735.99  4899.3 1737.24  4919.4 1736.58  4929.5 1735.57  4939.5 1733.93
  4959.6  1729.5  4969.7 1728.32  4979.7 1725.96  4982.5 1723.83  4985.3 1723.33
  4988.5 1723.83  4990.6 1725.06  4999.8 1724.37  5009.9 1725.16  5019.9 1727.38
  5085.4 1735.63  5120.4 1735.87  5160.6 1736.98  5180.3  1736.4  5231.1 1737.11
  5311.4 1737.18  5361.7 1737.85  5476.1 1742.14  5612.9  1747.8  5644.9 1748.54
#Mann= 8 ,-1 , 0
  4423.7     .05       0  4596.7     .16       0  4695.1     .05       0
  4793.5     .16       0  4982.5     .07       0  4988.5     .16       0
  5231.1     .05       0  5476.1      .1       0
#XS Ineff= 2 , 0
         4894.32 1737.16  5160.1         1737.04
Permanent Ineff=
       F       F
Bank Sta=4929.5,5085.4
XS Rating Curve= 0 ,0
Exp/Cntr=0.3,0.1

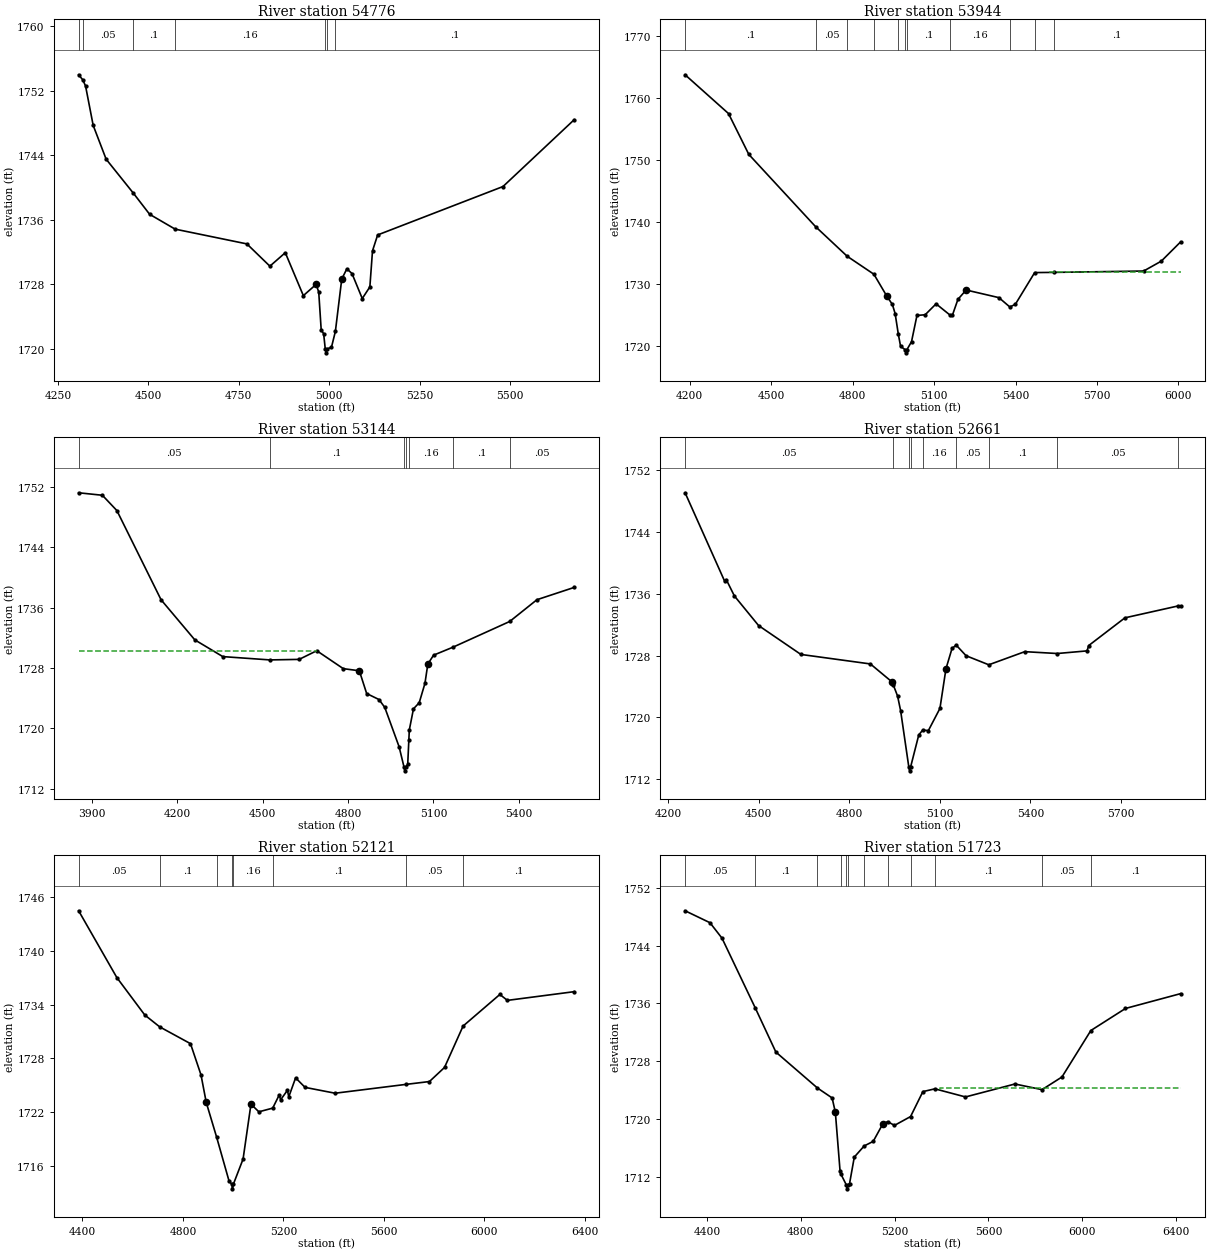
Type RM Length L Ch R = 1 ,54776   ,832,832,832
BEGIN DESCRIPTION:
WILLOW CREEK 82.0
END DESCRIPTION:
XS GIS Cut Line= 3
      2795549.85     10113262.26      2796211.17     10112654.77
      2796387.57     10112217.61
#Sta/Elev= 30
  4307.4 1753.97  4319.1 1753.33  4326.6 1752.57  4347.6  1747.7  4383.4 1743.51
  4458.6  1739.3  4503.6 1736.68  4574.1 1734.84  4772.4 1733.01  4835.9 1730.25
  4878.5 1731.92  4928.4  1726.6  4963.6 1727.99  4970.9 1727.05  4977.7 1722.36
  4984.5 1721.88  4988.9 1720.01  4991.7 1719.51  4994.9 1720.01  5006.1  1720.2
  5016.9 1722.16  5034.5 1728.65  5048.6 1729.92  5062.8 1729.34  5091.2 1726.24
  5112.2 1727.68  5119.5 1732.15  5133.7 1734.12  5480.1 1740.12  5676.8  1748.4
#Mann= 7 ,-1 , 0
  4307.4     .16       0  4319.1     .05       0  4458.6      .1       0
  4574.1     .16       0  4988.9     .07       0  4994.9     .16       0
  5016.9      .1       0
Bank Sta=4963.6,5034.5
XS Rating Curve= 0 ,0
Exp/Cntr=0.3,0.1

Type RM Length L Ch R = 1 ,53944   ,800,800,800
BEGIN DESCRIPTION:
WILLOW CREEK 81.0
END DESCRIPTION:
XS GIS Cut Line= 2
      2796318.83     10114292.68      2796511.03     10112478.33
#Sta/Elev= 30
  4183.5 1763.77  4343.3 1757.52  4418.1 1750.93    4664 1739.28  4780.3 1734.51
  4878.7 1731.61  4926.6 1728.05  4946.7 1726.74  4956.8 1725.27  4968.7 1721.91
  4976.9 1719.99    4994 1719.44  4996.7 1718.94    5000 1719.44  5017.1 1720.73
  5037.2 1724.97  5067.4 1725.08  5107.6 1726.84  5158.8 1725.03  5167.9 1725.03
    5188 1727.56  5218.2 1729.07  5338.9 1727.84    5379 1726.34  5399.2 1726.75
  5470.6 1731.88  5541.6 1731.91  5871.8 1732.13  5936.7 1733.72    6008 1736.83
#Mann= 11 ,-1 , 0
  4183.5      .1       0    4664     .05       0  4780.3      .1       0
  4878.7     .05       0  4968.7      .1       0    4994     .07       0
    5000      .1       0  5158.8     .16       0    5379      .1       0
  5470.6     .16       0  5541.6      .1       0
#XS Ineff= 2 , 0
                         5524.64         1732.04
Permanent Ineff=
       F       F
Bank Sta=4926.6,5218.2
XS Rating Curve= 0 ,0
Exp/Cntr=0.3,0.1

Type RM Length L Ch R = 1 ,53144   ,483,483,483
BEGIN DESCRIPTION:
WILLOW CREEK 80.0
END DESCRIPTION:
XS GIS Cut Line= 3
      2797180.07     10114000.44      2796841.73     10113039.26
      2796749.45     10112324.08
#Sta/Elev= 30
    3854 1751.26  3937.4 1750.93  3988.3  1748.9  4143.5 1737.06    4262 1731.74
  4360.2 1729.52  4525.7 1729.08  4628.3 1729.15  4690.2  1730.3  4783.4 1727.92
  4839.7 1727.64  4865.4 1724.62  4908.8 1723.82    4929 1722.78  4979.4 1717.55
  4996.6 1714.86  4999.3 1714.36  5002.6 1714.86  5009.6 1715.22  5013.6 1718.48
  5015.2 1719.79  5029.8 1722.59    5050  1723.4  5070.1 1725.97  5080.2 1728.53
  5100.4 1729.71  5168.6 1730.77  5367.7 1734.18  5463.4 1737.07  5594.1  1738.7
#Mann= 7 ,-1 , 0
    3854     .05       0  4525.7      .1       0  4996.6     .07       0
  5002.6      .1       0  5013.6     .16       0  5168.6      .1       0
  5367.7     .05       0
#XS Ineff= 2 , 0
         4690.21 1730.31
Permanent Ineff=
       F       F
Bank Sta=4839.7,5080.2
XS Rating Curve= 0 ,0
Exp/Cntr=0.3,0.1

Type RM Length L Ch R = 1 ,52661   ,540,540,540
BEGIN DESCRIPTION:
WILLOW CREEK 79.0
END DESCRIPTION:
XS GIS Cut Line= 3
      2797207.44     10113846.84      2797248.68      10112928.9
      2796944.88     10112273.56
#Sta/Elev= 30
  4256.5 1749.08  4387.7 1737.61  4392.7 1737.85  4419.8 1735.72  4499.9 1731.89
    4640 1728.15  4870.2 1726.92  4940.3 1724.64  4946.6 1724.15  4960.3 1722.75
  4970.3 1720.87  4997.4 1713.58  5000.1 1713.08  5003.4 1713.58  5030.4 1717.73
  5043.1 1718.34  5062.3  1718.3  5100.5 1721.16  5120.5  1726.3  5140.5 1728.92
  5154.3 1729.36  5187.2 1727.98  5262.3 1726.81  5381.5 1728.51  5488.9 1728.27
  5587.7 1728.61  5593.2  1729.3  5713.2 1732.89  5889.4 1734.43  5897.7 1734.44
#Mann= 9 ,-1 , 0
  4256.5     .05       0  4946.6      .1       0  4997.4     .07       0
  5003.4      .1       0  5043.1     .16       0  5154.3     .05       0
  5262.3      .1       0  5488.9     .05       0  5889.4      .1       0
Bank Sta=4940.3,5120.5
XS Rating Curve= 0 ,0
Exp/Cntr=0.3,0.1

Type RM Length L Ch R = 1 ,52121   ,398,398,398
BEGIN DESCRIPTION:
WILLOW CREEK 78.0
END DESCRIPTION:
XS GIS Cut Line= 3
      2797564.56     10113838.99      2797902.92     10112754.74
       2797949.6     10111918.16
#Sta/Elev= 30
  4384.6 1744.44  4536.8    1737  4648.1 1732.83  4707.5 1731.51  4830.1 1729.64
    4872 1726.16  4892.9 1723.09  4934.4 1719.21  4983.6 1714.35  4994.7 1713.97
  4997.4 1713.47  5000.7 1713.97  5039.6 1716.79    5071  1722.9  5102.5 1722.05
  5157.6 1722.46  5183.8 1723.94    5189 1723.38  5216.3 1724.45  5221.5 1723.71
  5248.8 1725.83  5286.5 1724.77  5406.2 1724.12  5687.3  1725.1  5781.8 1725.42
  5841.9 1726.99  5915.8  1731.6  6062.3 1735.12  6092.3 1734.46  6358.3 1735.43
#Mann= 8 ,-1 , 0
  4384.6     .05       0  4707.5      .1       0  4934.4     .16       0
  4994.7     .07       0  5000.7     .16       0  5157.6      .1       0
  5687.3     .05       0  5915.8      .1       0
#XS Ineff= 2 , 0
                            5250         1725.78
Permanent Ineff=
       F       F
Bank Sta=4892.9,5071
XS Rating Curve= 0 ,0
Exp/Cntr=0.3,0.1

Type RM Length L Ch R = 1 ,51723   ,369,369,369
BEGIN DESCRIPTION:
WILLOW CREEK 77.0
END DESCRIPTION:
XS GIS Cut Line= 3
      2798202.82     10114038.92      2798049.02     10112831.63
      2797986.52     10111939.27
#Sta/Elev= 30
  4307.3 1748.81  4413.3 1747.16  4464.6 1745.02  4605.6 1735.43  4694.2 1729.28
  4871.1 1724.32  4933.9 1722.94  4947.6 1720.95  4967.8 1712.78    4970  1712.5
    4995 1710.88  4997.8 1710.38    5001 1710.88  5008.1 1711.11  5028.3 1714.77
  5070.5 1716.31  5108.9 1716.94  5149.2 1719.32  5170.1 1719.67  5199.6 1719.15
  5268.1 1720.37  5320.6 1723.82  5371.8  1724.2  5502.1 1723.08  5712.7 1724.87
  5828.3 1724.09  5913.2 1725.84  6036.3 1732.26  6183.9 1735.31  6418.9 1737.36
#Mann= 12 ,-1 , 0
  4307.3     .05       0  4605.6      .1       0  4871.1     .05       0
    4970      .1       0    4995     .07       0    5001      .1       0
  5070.5     .16       0  5170.1      .1       0  5268.1     .16       0
  5371.8      .1       0  5828.3     .05       0  6036.3      .1       0
#XS Ineff= 2 , 0
                         5392.08         1724.32
Permanent Ineff=
       F       F
Bank Sta=4947.6,5149.2
XS Rating Curve= 0 ,0
Exp/Cntr=0.3,0.1

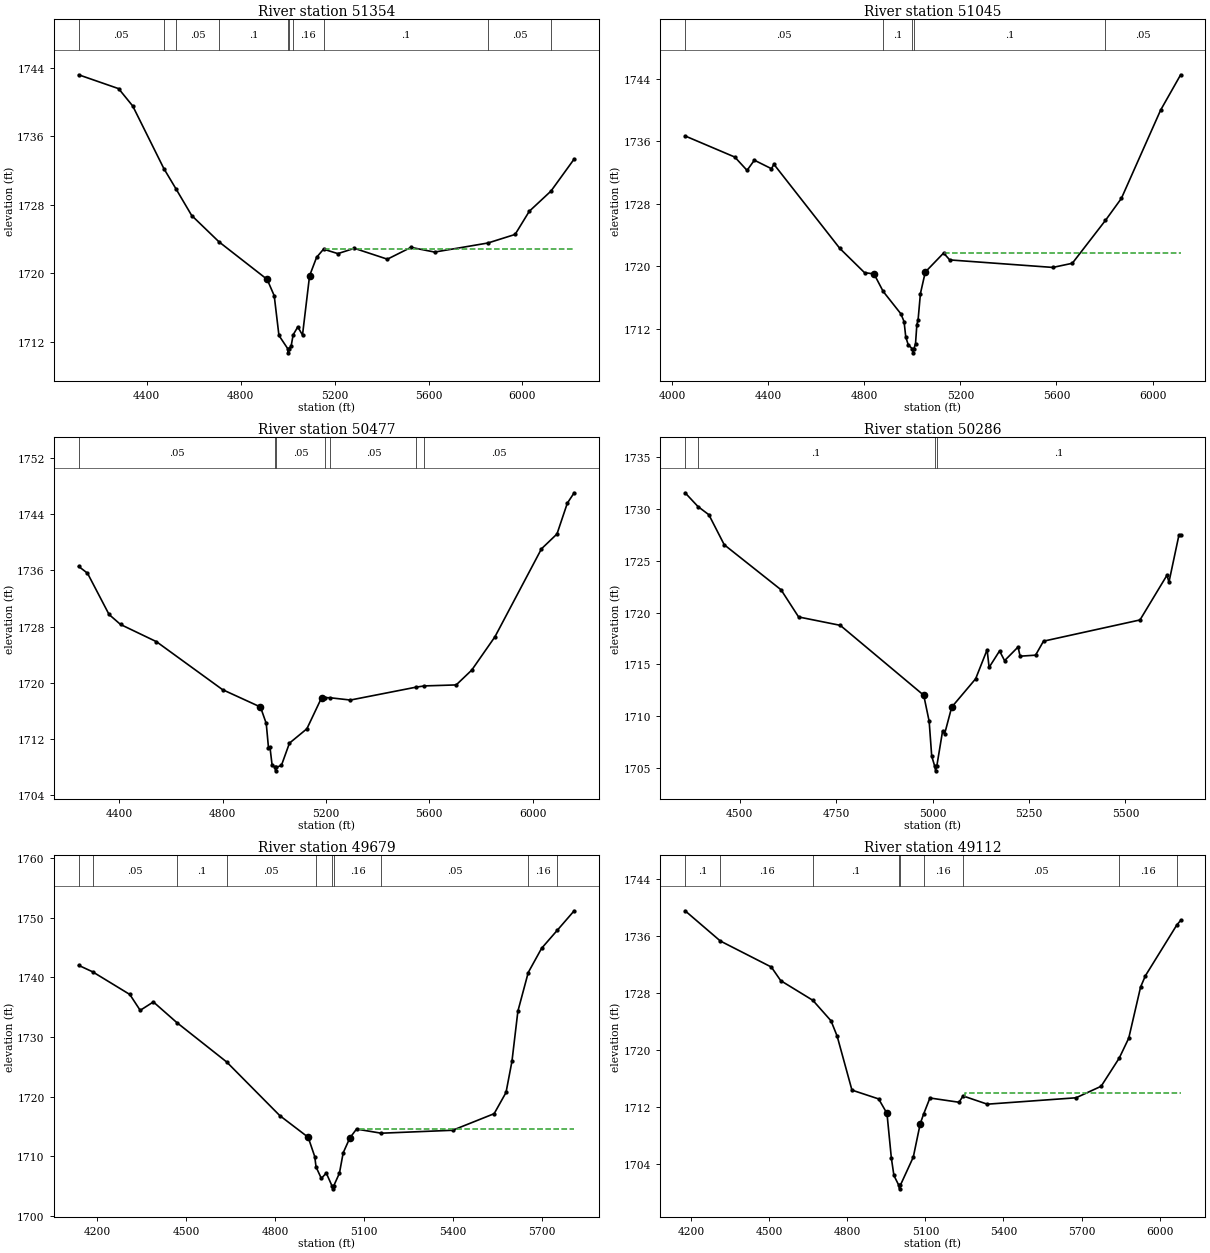
Type RM Length L Ch R = 1 ,51354   ,309,309,309
BEGIN DESCRIPTION:
Mapping XS 1cabbd97
END DESCRIPTION:
XS GIS Cut Line= 3
      2798385.75     10114123.32      2798515.96     10112618.12
      2798594.09     10112024.36
#Sta/Elev= 30
  4110.4 1743.17  4280.6 1741.55  4340.8 1739.52  4473.1 1732.22  4524.7 1729.85
  4591.8 1726.73  4708.2 1723.65    4913 1719.27  4943.1 1717.36  4963.2 1712.72
  5000.3 1711.19  5003.1 1710.69  5006.3 1711.19  5015.2 1711.49  5023.7  1712.8
  5043.5 1713.72  5063.5 1712.77  5093.6 1719.69  5123.4 1721.84    5153  1722.8
  5214.1 1722.28  5284.4  1722.9  5424.9 1721.63  5525.3 1723.01    5626 1722.46
  5852.9 1723.52  5968.6 1724.52  6029.1 1727.23  6121.2 1729.58  6220.1 1733.33
#Mann= 10 ,-1 , 0
  4110.4     .05       0  4473.1      .1       0  4524.7     .05       0
  4708.2      .1       0  5000.3     .07       0  5006.3      .1       0
  5023.7     .16       0    5153      .1       0  5852.9     .05       0
  6121.2      .1       0
#XS Ineff= 2 , 0
                         5154.78         1722.87
Permanent Ineff=
       F       F
Bank Sta=4913,5093.6
XS Rating Curve= 0 ,0
Exp/Cntr=0.3,0.1

Type RM Length L Ch R = 1 ,51045   ,568,568,568
BEGIN DESCRIPTION:
WILLOW CREEK 76.0
END DESCRIPTION:
XS GIS Cut Line= 3
      2798579.61     10114177.38      2798779.55     10113085.39
      2798971.76     10112152.02
#Sta/Elev= 30
    4054 1736.68    4261 1733.98  4311.9 1732.28  4342.4 1733.58  4413.6 1732.49
  4423.7 1733.06  4698.2  1722.3  4801.1  1719.2  4840.5 1719.04  4878.7  1716.8
  4952.3 1713.94  4965.7 1712.94  4972.7 1710.98  4982.8    1710  5000.2 1709.45
  5002.9 1708.95  5006.2 1709.45  5013.3  1710.1  5018.9 1712.56    5024 1713.16
  5033.7 1716.52    5054 1719.28  5130.3 1721.71  5155.7 1720.83  5584.9 1719.87
  5666.1  1720.4  5804.2 1725.89  5870.3 1728.69  6033.7 1739.98  6117.1  1744.5
#Mann= 5 ,-1 , 0
    4054     .05       0  4878.7      .1       0  5000.2     .07       0
  5006.2      .1       0  5804.2     .05       0
#XS Ineff= 2 , 0
                         5131.35         1721.72
Permanent Ineff=
       F       F
Bank Sta=4840.5,5054
XS Rating Curve= 0 ,0
Exp/Cntr=0.3,0.1

Type RM Length L Ch R = 1 ,50477   ,191,191,191
BEGIN DESCRIPTION:
WILLOW CREEK 75.0
END DESCRIPTION:
XS GIS Cut Line= 3
      2799648.49     10114000.47      2799048.69     10112823.94
      2799047.72     10112227.24
#Sta/Elev= 30
  4243.3 1736.56  4277.6 1735.59    4361 1729.72  4405.4  1728.3  4544.4 1725.85
    4800 1719.03  4946.8 1716.56  4969.2 1714.22  4977.9 1710.75  4983.5 1710.87
  4991.7 1708.34  5002.7 1707.98  5005.5 1707.48  5008.7 1707.98    5028 1708.26
    5059 1711.42  5126.4 1713.46  5183.6  1717.9  5198.2  1717.9  5217.5 1717.87
  5294.8 1717.55    5550 1719.39  5581.5 1719.56  5704.1  1719.7  5764.1  1721.8
  5854.1 1726.55  6034.1 1739.06  6094.1 1741.17  6134.1 1745.55  6160.6 1747.03
#Mann= 7 ,-1 , 0
  4243.3     .05       0  5002.7     .04       0  5008.7     .05       0
  5198.2     .16       0  5217.5     .05       0    5550      .1       0
  5581.5     .05       0
Bank Sta=4946.8,5183.6
XS Rating Curve= 0 ,0
Exp/Cntr=0.3,0.1

Type RM Length L Ch R = 1 ,50286   ,607,607,607
BEGIN DESCRIPTION:
Mapping XS 848fe3ee
END DESCRIPTION:
XS GIS Cut Line= 3
      2799748.47     10113877.48      2799517.76     10113392.98
      2799325.52     10112670.14
#Sta/Elev= 30
  4358.6 1731.58    4392 1730.25  4420.2 1729.46  4460.1 1726.56  4607.4 1722.21
  4652.8 1719.59  4760.8 1718.78  4977.2 1712.03  4991.3 1709.51  4997.9 1706.15
  5005.3 1705.23    5008 1704.73  5011.3 1705.23  5026.2  1708.6  5031.4  1708.3
  5049.7 1710.88  5111.8 1713.62  5141.5 1716.42  5146.7 1714.72  5173.8 1716.31
  5186.8 1715.37  5221.8 1716.69    5227  1715.8  5267.1  1715.9  5287.7 1717.25
  5537.8  1719.3  5607.8 1723.62  5612.9 1722.95  5638.7 1727.48  5643.2 1727.48
#Mann= 4 ,-1 , 0
  4358.6     .05       0    4392      .1       0  5005.3     .07       0
  5011.3      .1       0
Bank Sta=4977.2,5049.7
XS Rating Curve= 0 ,0
Exp/Cntr=0.3,0.1

Type RM Length L Ch R = 1 ,49679   ,567,567,567
BEGIN DESCRIPTION:
WILLOW CREEK 74.0
END DESCRIPTION:
XS GIS Cut Line= 3
      2799640.82     10114177.29      2800125.25      10113231.5
      2800125.25     10112624.04
#Sta/Elev= 30
  4137.3    1742  4184.3 1740.92  4309.8 1737.12  4344.8 1734.46  4389.2 1735.87
  4468.3 1732.41  4636.1 1725.82  4815.4 1716.82  4910.9  1713.2  4933.1 1709.96
  4937.4 1708.23  4955.3  1706.3  4971.9 1707.21  4991.1 1705.06  4993.8 1704.56
  4997.1 1705.06  5016.3 1707.19  5028.9 1710.59  5051.4 1713.09  5073.8 1714.57
  5157.1 1713.88  5397.7 1714.37  5537.7 1717.15  5577.7  1720.7  5597.7 1725.92
  5617.7 1734.32  5652.6  1740.8  5697.7 1744.86  5750.9  1747.9  5807.4 1751.14
#Mann= 10 ,-1 , 0
  4137.3      .1       0  4184.3     .05       0  4468.3      .1       0
  4636.1     .05       0  4937.4     .16       0  4991.1     .07       0
  4997.1     .16       0  5157.1     .05       0  5652.6     .16       0
  5750.9      .1       0
#XS Ineff= 2 , 0
                         5084.64         1714.65
Permanent Ineff=
       F       F
Bank Sta=4910.9,5051.4
XS Rating Curve= 0 ,0
Exp/Cntr=0.3,0.1

Type RM Length L Ch R = 1 ,49112   ,521,521,521
BEGIN DESCRIPTION:
Mapping XS a926c92f
END DESCRIPTION:
XS GIS Cut Line= 4
        2799924.     10114129.23      2800514.32     10113729.89
      2800599.39     10113467.74      2800463.98     10112561.51
#Sta/Elev= 30
  4176.3 1739.59  4311.9 1735.33  4507.7 1731.67  4543.9 1729.75  4667.4 1726.98
  4737.1  1724.1  4760.7 1721.94  4817.6 1714.34  4920.2  1713.1  4952.2 1711.06
  4969.1 1704.76  4978.9 1702.32  4997.6 1700.94  5000.4 1700.44  5003.6 1700.94
  5053.3  1704.9    5080 1709.61  5093.4    1711  5117.3 1713.23  5229.3 1712.63
  5244.5 1713.52  5337.8 1712.36  5678.8 1713.26  5775.3 1714.88  5844.9 1718.85
  5881.4 1721.65    5927 1728.86  5945.6 1730.45  6066.2 1737.59  6080.9 1738.23
#Mann= 9 ,-1 , 0
  4176.3      .1       0  4311.9     .16       0  4667.4      .1       0
  4997.6     .07       0  5003.6      .1       0  5093.4     .16       0
  5244.5     .05       0  5844.9     .16       0  6066.2      .1       0
#XS Ineff= 2 , 0
                         5253.02         1713.99
Permanent Ineff=
       F       F
Bank Sta=4952.2,5080
XS Rating Curve= 0 ,0
Exp/Cntr=0.3,0.1

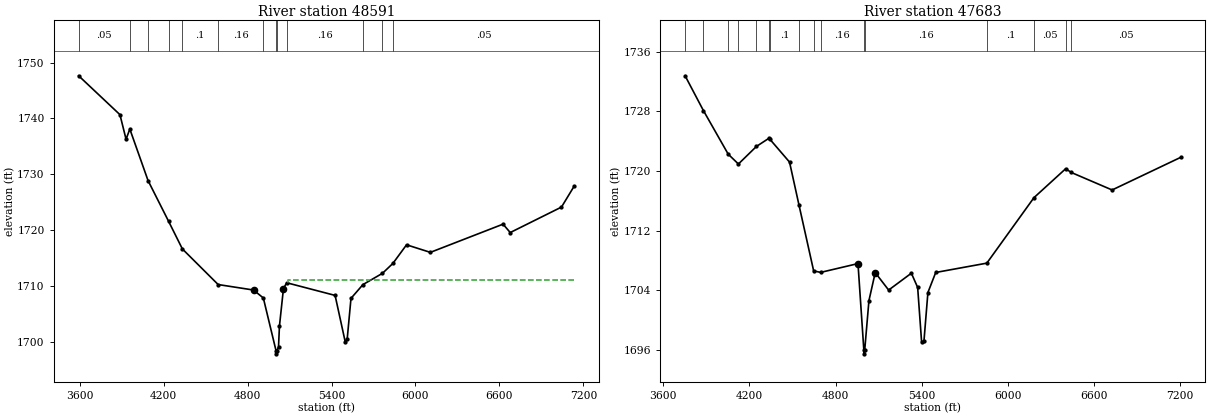
Type RM Length L Ch R = 1 ,48591   ,908,908,908
BEGIN DESCRIPTION:
WILLOW CREEK 73.0
END DESCRIPTION:
XS GIS Cut Line= 4
      2799613.42     10114722.19      2800689.79     10114114.57
      2801549.16     10113411.44      2802148.04      10112378.6
#Sta/Elev= 30
  3593.4 1747.63  3888.6 1740.68  3932.2 1736.29  3959.2 1738.11  4089.6 1728.89
  4236.5 1721.61  4334.6 1716.69  4590.2 1710.33  4842.9 1709.35    4913 1707.93
  5004.3 1698.45    5007 1697.95  5010.3 1698.45  5021.5 1699.22  5028.1 1702.91
  5056.8 1709.62    5080 1710.65  5425.7 1708.39  5497.5 1700.15  5511.9 1700.54
  5539.2 1707.86  5624.5 1710.32  5764.2 1712.34  5838.4  1714.1  5936.1 1717.43
  6106.3 1716.08  6625.6 1721.12  6676.9 1719.62    7043 1724.17  7133.7 1727.91
#Mann= 13 ,-1 , 0
  3593.4     .05       0  3959.2      .1       0  4089.6     .05       0
  4236.5     .16       0  4334.6      .1       0  4590.2     .16       0
    4913     .05       0  5004.3    .035       0  5010.3     .05       0
    5080     .16       0  5624.5      .1       0  5764.2     .16       0
  5838.4     .05       0
#XS Ineff= 2 , 0
                         5092.74         1711.06
Permanent Ineff=
       F       F
Bank Sta=4842.9,5056.8
XS Rating Curve= 0 ,0
Exp/Cntr=0.3,0.1

Type RM Length L Ch R = 1 ,47683   ,662,662,662
BEGIN DESCRIPTION:
Mapping XS 13b20352
END DESCRIPTION:
XS GIS Cut Line= 5
      2800137.69     10115086.86      2801158.49     10114873.33
      2801515.26     10114209.27      2801684.53     10113386.35
      2802020.45     10112644.21
#Sta/Elev= 30
  3751.6 1732.77  3879.3  1728.1  4051.9 1722.26  4122.9 1720.94  4248.7  1723.3
  4336.2  1724.4  4341.7 1724.27    4479  1721.2  4545.2 1715.41    4647 1706.61
  4695.8 1706.41  4955.8 1707.59  4996.6 1695.99  4999.4 1695.49  5002.6 1695.99
  5032.1 1702.63  5075.9 1706.38  5169.3 1704.04  5327.6  1706.3  5371.4 1704.39
    5399 1697.05  5415.2 1697.18  5442.8 1703.71  5497.2  1706.4  5853.2 1707.65
  6181.5 1716.43  6402.5 1720.31  6440.9 1719.81  6725.8 1717.46  7203.1 1721.83
#Mann= 16 ,-1 , 0
  3751.6      .1       0  3879.3     .05       0  4051.9      .1       0
  4122.9     .05       0  4248.7      .1       0  4336.2     .05       0
  4341.7      .1       0  4545.2     .05       0    4647      .1       0
  4695.8     .16       0  4996.6     .07       0  5002.6     .16       0
  5853.2      .1       0  6181.5     .05       0  6402.5      .1       0
  6440.9     .05       0
Bank Sta=4955.8,5075.9
XS Rating Curve= 0 ,0
Exp/Cntr=0.3,0.1