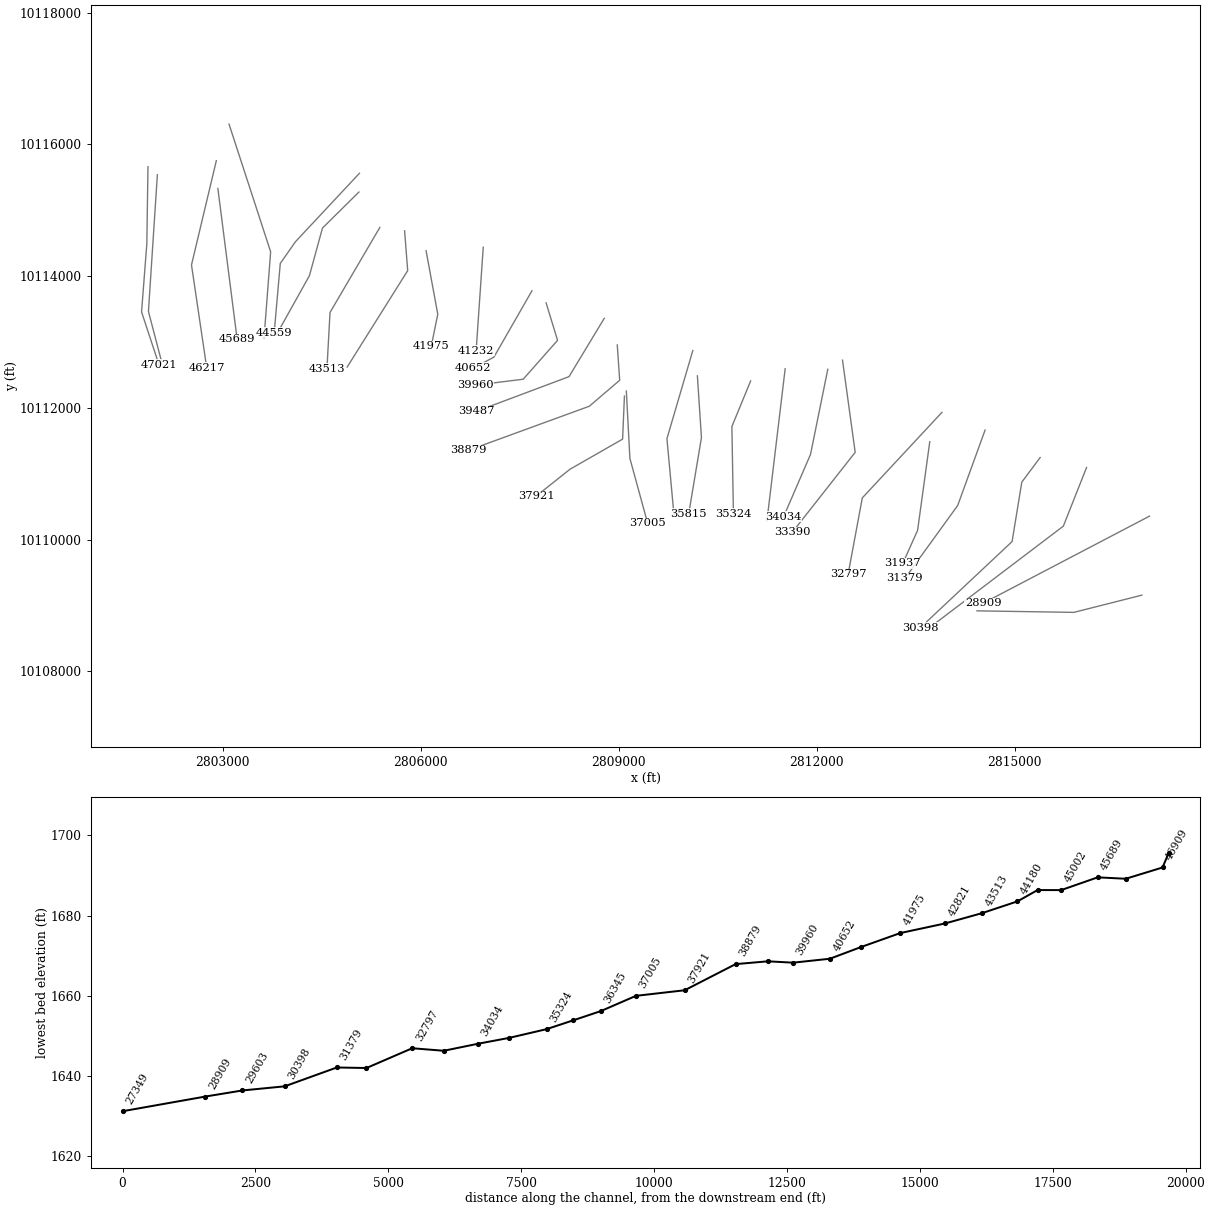
HEC-RAS study WILLOW CREEK.prj: WILLOW CREEK Base Level Engineering

--- WILLOW CREEK.g01 (geometry) --- (continued)

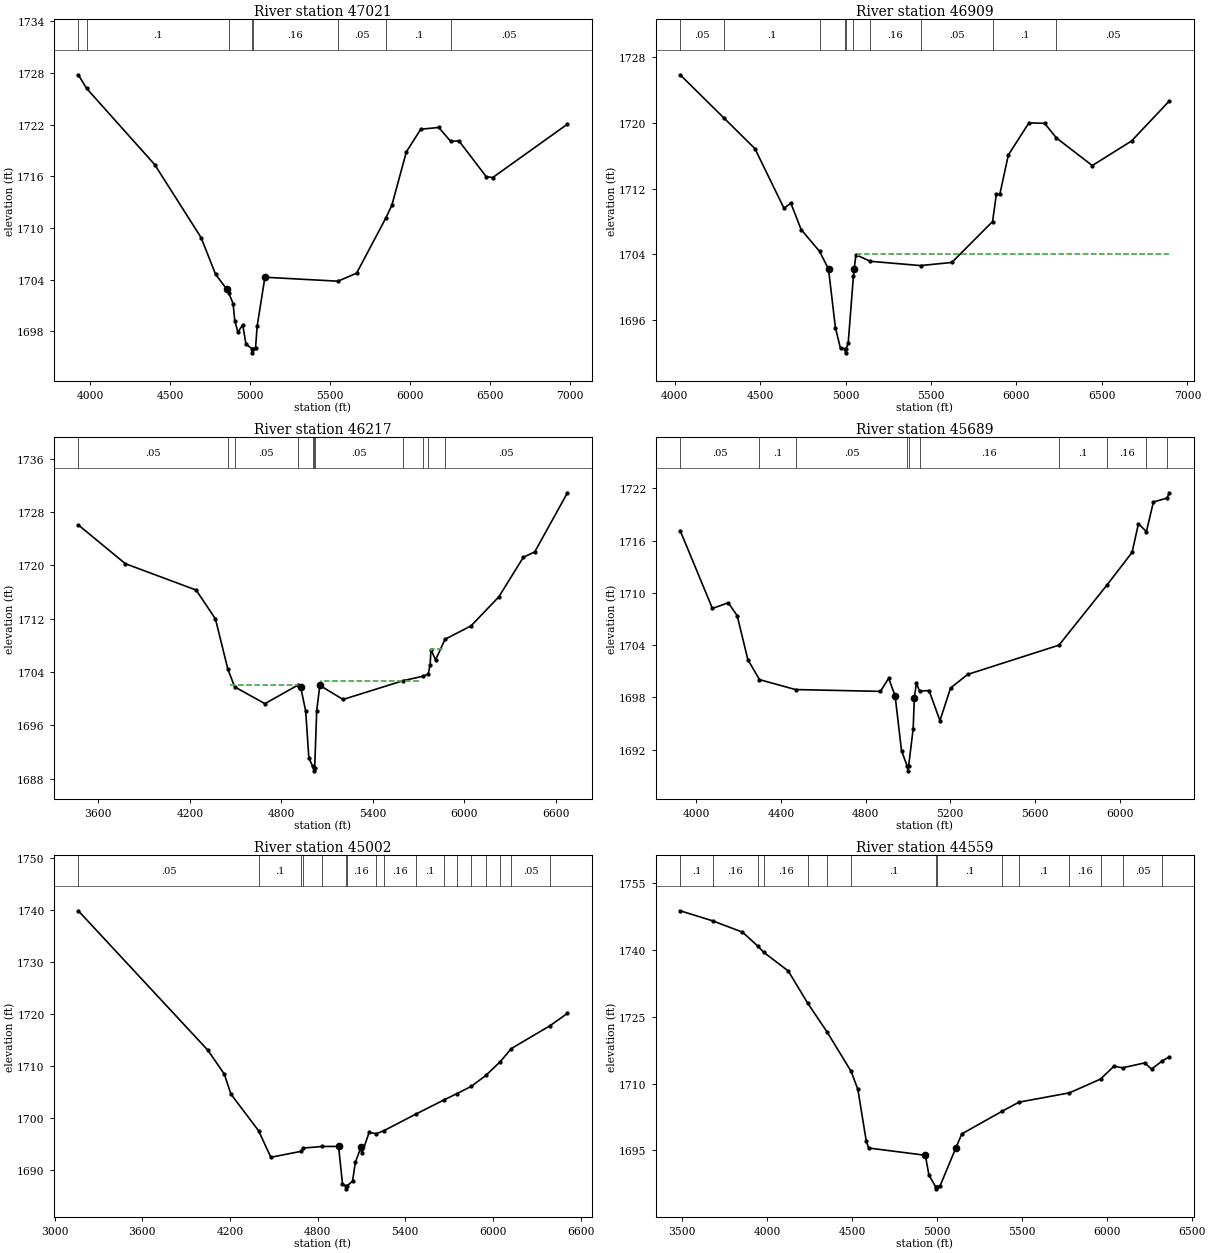
Type RM Length L Ch R = 1 ,47021   ,112,112,112
BEGIN DESCRIPTION:
WILLOW CREEK 72.0
END DESCRIPTION:
XS GIS Cut Line= 4
      2801865.09     10115661.56      2801847.73     10114491.39
      2801767.87     10113456.66      2802033.47     10112649.44
#Sta/Elev= 30
  3926.4 1727.81  3978.1 1726.23  4404.3 1717.37  4694.3 1708.89  4784.3 1704.65
  4854.3 1702.91  4866.7 1702.47  4894.3 1701.23  4904.3 1699.27  4924.3 1697.91
  4954.3 1698.79  4974.3 1696.53  5011.3 1696.02  5014.1 1695.52  5017.3 1696.02
  5034.3 1696.03  5044.3 1698.61    5093  1704.3  5549.4 1703.84    5666 1704.77
  5850.5 1711.23  5886.7 1712.67    5977 1718.85  6067.2 1721.49  6179.4 1721.69
  6254.3 1720.08    6306 1720.13    6476 1715.99  6516.6 1715.87  6984.3 1722.08
#Mann= 8 ,-1 , 0
  3926.4     .05       0  3978.1      .1       0  4866.7     .16       0
  5011.3     .07       0  5017.3     .16       0  5549.4     .05       0
  5850.5      .1       0  6254.3     .05       0
Bank Sta=4854.3,5093
XS Rating Curve= 0 ,0
Exp/Cntr=0.3,0.1

Type RM Length L Ch R = 1 ,46909   ,692,692,692
BEGIN DESCRIPTION:
WILLOW CREEK 71.0
END DESCRIPTION:
XS GIS Cut Line= 3
      2802007.45     10115539.96      2801872.03     10113463.61
      2802069.68     10112707.68
#Sta/Elev= 30
  4032.2 1725.88  4290.5 1720.57  4469.4 1716.89  4639.7 1709.62  4679.8 1710.24
  4739.9 1707.03  4848.1 1704.36  4900.3 1702.21  4940.4 1695.09  4970.4 1692.54
  4997.5 1692.51  5000.2 1692.01  5003.5 1692.51  5015.4 1693.19  5045.7 1701.31
  5050.6 1702.21  5060.6 1703.96  5144.5 1703.16  5438.8 1702.64  5621.8 1703.02
  5860.1    1708  5882.3 1711.32  5902.4  1711.3  5952.5 1716.12  6072.8 1720.02
  6164.5 1719.97  6233.5 1718.19  6443.6 1714.82  6674.1 1717.83  6894.3 1722.69
#Mann= 10 ,-1 , 0
  4032.2     .05       0  4290.5      .1       0  4848.1     .05       0
  4997.5    .035       0  5003.5     .05       0  5045.7      .1       0
  5144.5     .16       0  5438.8     .05       0  5860.1      .1       0
  6233.5     .05       0
#XS Ineff= 2 , 0
                         5075.57         1704.05
Permanent Ineff=
       F       F
Bank Sta=4900.3,5050.6
XS Rating Curve= 0 ,0
Exp/Cntr=0.3,0.1

Type RM Length L Ch R = 1 ,46217   ,528,528,528
BEGIN DESCRIPTION:
WILLOW CREEK 70.0
END DESCRIPTION:
XS GIS Cut Line= 3
      2802901.24     10115753.71      2802524.45     10114169.65
      2802755.14     10112608.66
#Sta/Elev= 30
  3469.1 1726.06  3777.5 1720.25  4241.2  1716.3  4367.7 1711.99  4448.9 1704.47
  4494.3 1701.78  4692.3 1699.27  4906.1 1702.02  4926.2  1701.8  4959.5 1698.15
  4980.1 1691.15  5004.9  1689.9  5012.6  1689.7  5015.4  1689.2  5018.6  1689.7
  5031.5 1698.12    5052 1702.01  5204.4  1699.9  5600.5 1702.73  5727.9 1703.38
  5762.2 1703.69  5775.1 1705.09  5780.6 1707.35  5810.9 1705.83  5872.7 1708.92
  6043.3 1710.93  6225.4 1715.28  6386.2 1721.21  6460.8 1722.02  6675.3 1730.88
#Mann= 11 ,-1 , 0
  3469.1     .05       0  4448.9      .1       0  4494.3     .05       0
  4906.1     .16       0  5004.9     .05       0  5012.6     .07       0
  5018.6     .05       0  5600.5      .1       0  5727.9     .05       0
  5762.2      .1       0  5872.7     .05       0
#XS Ineff= 3 ,-1
 4465.46 4910.89 1702.13 5060.23 5704.79 1702.61  5783.4 5865.93 1707.39
Permanent Ineff=
       F       F       F
Bank Sta=4926.2,5052
XS Rating Curve= 0 ,0
Exp/Cntr=0.3,0.1

Type RM Length L Ch R = 1 ,45689   ,687,687,687
BEGIN DESCRIPTION:
WILLOW CREEK 69.0
END DESCRIPTION:
XS GIS Cut Line= 2
      2802924.32     10115330.77      2803216.53     10113039.22
#Sta/Elev= 30
  3924.3 1717.16  4076.6 1708.21  4151.4 1708.86  4193.5 1707.39  4243.9 1702.33
  4298.9 1700.03    4469 1698.89  4870.1 1698.68  4909.2 1700.19  4939.5 1698.14
  4969.7 1691.87    4997 1690.05  4999.7 1689.55    5003 1690.05  5024.7 1694.38
  5030.2 1697.97  5040.3 1699.64  5054.7  1698.7  5099.6 1698.78  5151.2 1695.32
  5201.6 1699.08  5282.2 1700.63  5713.1 1703.99  5941.8 1710.96  6058.5 1714.65
  6088.7 1717.95  6126.1 1717.03  6159.3 1720.44  6223.4 1720.89  6234.4  1721.5
#Mann= 10 ,-1 , 0
  3924.3     .05       0  4298.9      .1       0    4469     .05       0
    4997    .035       0    5003     .05       0  5054.7     .16       0
  5713.1      .1       0  5941.8     .16       0  6126.1      .1       0
  6223.4     .16       0
#XS Ineff= 2 , 0
         4911.12 1699.98 5041.72         1699.43
Permanent Ineff=
       F       F
Bank Sta=4939.5,5030.2
XS Rating Curve= 0 ,0
Exp/Cntr=0.3,0.1

Type RM Length L Ch R = 1 ,45002   ,443,443,443
BEGIN DESCRIPTION:
WILLOW CREEK 68.0
END DESCRIPTION:
XS GIS Cut Line= 3
      2803093.51     10116307.36      2803724.05     10114369.58
      2803624.08     10113062.28
#Sta/Elev= 30
  3161.4 1739.86  4048.6 1713.03    4161 1708.44  4206.3 1704.59  4395.2 1697.56
  4479.7 1692.44  4689.1  1693.6    4699 1694.21  4832.8 1694.52  4943.2 1694.53
  4969.9 1687.39    4992 1686.87  4994.8 1686.37    4998 1686.87    5039 1687.84
  5058.1 1691.49  5097.6 1694.41  5102.9 1693.17  5152.8 1697.25  5201.2 1696.97
  5252.3 1697.54  5473.9 1700.77  5666.6  1703.5  5753.4 1704.68  5852.4 1706.09
  5951.3 1708.18  6050.3 1710.83  6126.4 1713.36  6390.3 1717.74  6510.3 1720.13
#Mann= 17 ,-1 , 0
  3161.4     .05       0  4395.2      .1       0  4689.1     .12       0
    4699      .1       0  4832.8     .16       0    4992     .07       0
    4998     .16       0  5201.2      .1       0  5252.3     .16       0
  5473.9      .1       0  5666.6     .16       0  5753.4     .05       0
  5852.4      .1       0  5951.3     .05       0  6050.3      .1       0
  6126.4     .05       0  6390.3      .1       0
Bank Sta=4943.2,5097.6
XS Rating Curve= 0 ,0
Exp/Cntr=0.3,0.1

Type RM Length L Ch R = 1 ,44559   ,379,379,379
BEGIN DESCRIPTION:
WILLOW CREEK 67.0
END DESCRIPTION:
XS GIS Cut Line= 4
      2805069.73     10115561.46      2804100.85     10114523.38
      2803870.16     10114192.72      2803777.88     10113139.21
#Sta/Elev= 30
  3487.7 1748.83  3678.4 1746.58  3854.7 1744.03  3945.7 1740.88  3979.3 1739.52
  4123.9 1735.32  4238.5  1728.1  4354.3 1721.53  4494.4 1712.76  4534.2 1708.72
  4583.6  1697.1  4597.7 1695.55  4931.6 1693.92  4952.7 1689.47  4991.6 1686.88
  4994.3 1686.38  4997.6 1686.88    5017 1686.92  5110.6 1695.51  5146.4 1698.72
  5384.1 1703.82  5483.2 1705.85  5780.4 1707.94  5963.3 1711.03  6042.6 1713.93
  6092.7 1713.56  6223.3 1714.66  6263.5 1713.28  6327.8 1715.13  6368.4 1716.02
#Mann= 15 ,-1 , 0
  3487.7      .1       0  3678.4     .16       0  3945.7      .1       0
  3979.3     .16       0  4238.5      .1       0  4354.3     .16       0
  4494.4      .1       0  4991.6     .07       0  4997.6      .1       0
  5384.1     .16       0  5483.2      .1       0  5780.4     .16       0
  5963.3      .1       0  6092.7     .05       0  6327.8      .1       0
Bank Sta=4931.6,5110.6
XS Rating Curve= 0 ,0
Exp/Cntr=0.3,0.1

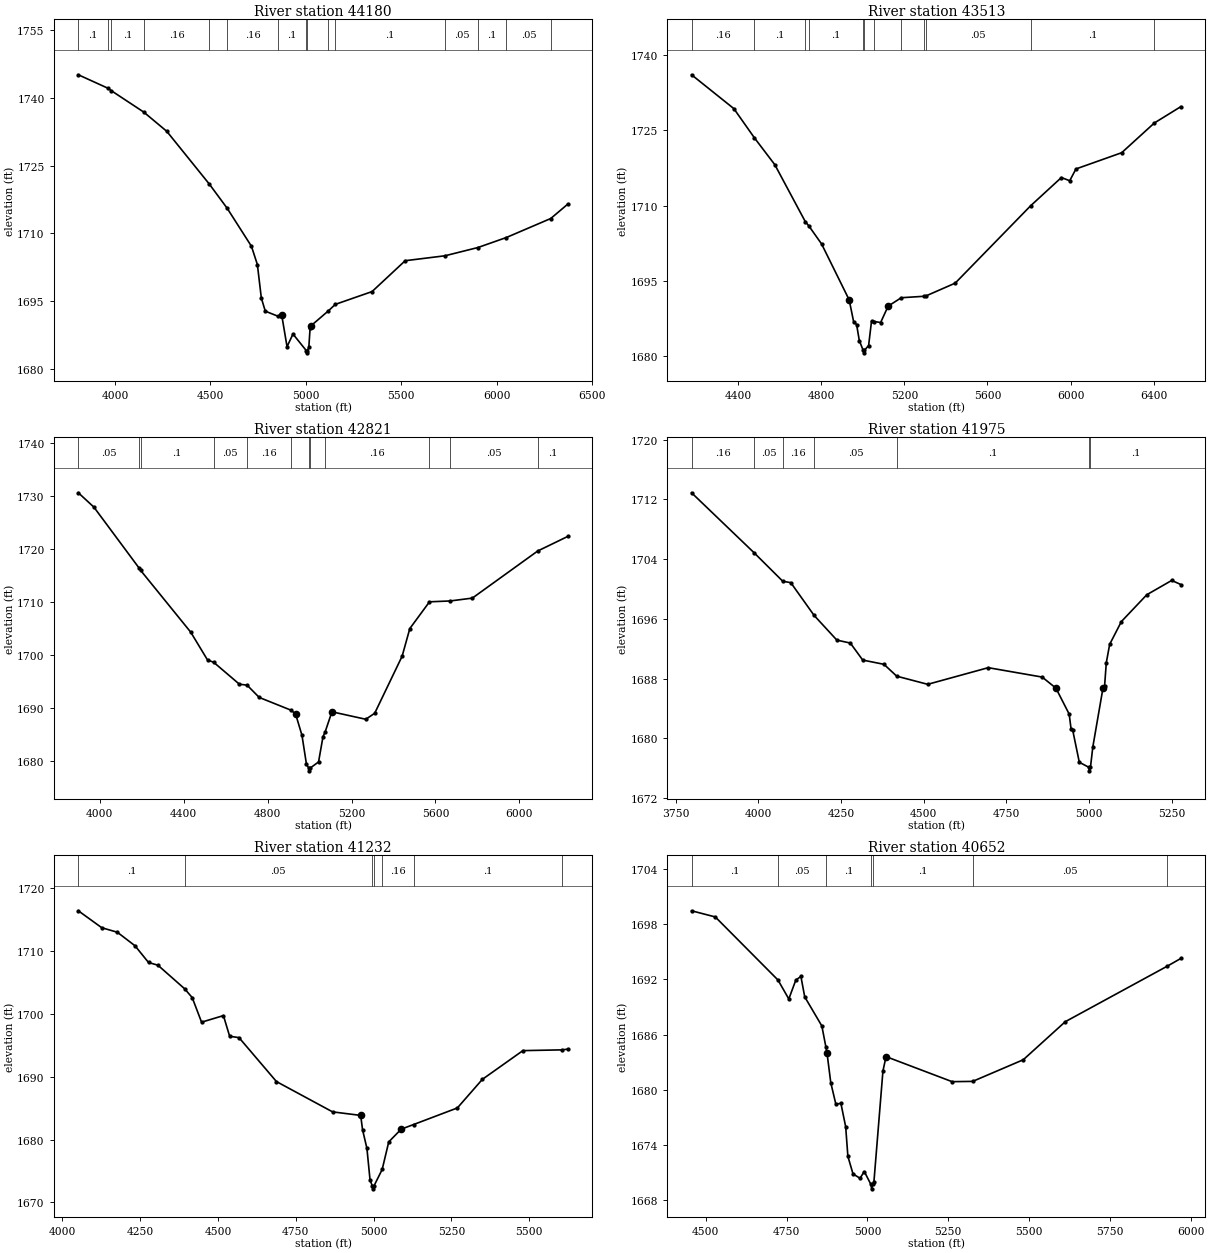
Type RM Length L Ch R = 1 ,44180   ,667,667,667
BEGIN DESCRIPTION:
WILLOW CREEK 66.0
END DESCRIPTION:
XS GIS Cut Line= 4
      2805061.37     10115276.32       2804509.3     10114729.46
      2804311.38     10114005.51       2803806.2      10113099.3
#Sta/Elev= 30
  3807.7 1745.16  3963.5 1742.17  3980.4 1741.64  4150.1 1736.91  4271.2 1732.64
  4494.8 1720.92  4587.7  1715.6  4715.1 1707.17  4746.2 1703.12  4766.9 1695.71
  4787.7 1692.79  4853.4 1691.68  4874.1 1691.86  4901.7 1684.92  4932.8 1687.73
  5002.4 1684.06  5005.1 1683.56  5008.4 1684.06  5015.8 1684.76  5022.5    1689
  5027.7 1689.57  5118.4 1692.86  5154.9  1694.3  5347.3 1697.13    5521 1703.97
  5729.3 1705.06  5902.2 1706.89  6051.4 1709.11  6283.9 1713.32  6372.8 1716.49
#Mann= 15 ,-1 , 0
  3807.7      .1       0  3963.5     .16       0  3980.4      .1       0
  4150.1     .16       0  4494.8      .1       0  4587.7     .16       0
  4853.4      .1       0  5002.4     .07       0  5008.4      .1       0
  5118.4     .16       0  5154.9      .1       0  5729.3     .05       0
  5902.2      .1       0  6051.4     .05       0  6283.9      .1       0
Bank Sta=4874.1,5027.7
XS Rating Curve= 0 ,0
Exp/Cntr=0.3,0.1

Type RM Length L Ch R = 1 ,43513   ,692,692,692
BEGIN DESCRIPTION:
WILLOW CREEK 65.0
END DESCRIPTION:
XS GIS Cut Line= 3
      2805379.08     10114739.86      2804623.88     10113448.21
      2804577.01     10112588.81
#Sta/Elev= 30
  4174.8 1736.07  4378.5 1729.32  4477.9 1723.47  4575.7 1718.14  4722.2 1706.81
  4739.4 1705.94  4800.9 1702.34  4933.9 1691.18  4955.4 1686.81  4969.6 1686.27
  4982.7 1683.06  5001.3 1681.12  5004.1 1680.62  5007.3 1681.12  5027.5 1682.08
  5041.4 1686.91  5055.7 1686.86  5085.4 1686.67  5121.5 1689.93  5184.7 1691.61
  5295.2  1691.9  5301.5 1691.93  5444.5 1694.52  5807.6 1709.94  5955.9 1715.58
    5996 1714.94    6026 1717.29  6246.4 1720.53  6403.4 1726.45  6531.7 1729.73
#Mann= 12 ,-1 , 0
  4174.8     .16       0  4477.9      .1       0  4722.2     .16       0
  4739.4      .1       0  5001.3     .07       0  5007.3      .1       0
  5055.7     .16       0  5184.7      .1       0  5295.2     .16       0
  5301.5     .05       0  5807.6      .1       0  6403.4     .05       0
Bank Sta=4933.9,5121.5
XS Rating Curve= 0 ,0
Exp/Cntr=0.3,0.1

Type RM Length L Ch R = 1 ,42821   ,846,846,846
BEGIN DESCRIPTION:
WILLOW CREEK 63.0
END DESCRIPTION:
XS GIS Cut Line= 3
      2805754.09     10114687.84      2805800.97     10114083.63
      2804884.32     10112620.12
#Sta/Elev= 30
  3897.4 1730.52  3971.7 1727.81  4185.9 1716.38    4194  1715.9  4433.1 1704.23
  4513.4 1698.97  4542.3 1698.55  4665.4  1694.4  4701.8 1694.23  4759.7 1691.91
  4910.8 1689.51    4933  1688.8  4963.5 1684.77  4984.9 1679.32  4995.9 1678.56
  4998.6 1678.06  5001.9 1678.56  5042.6 1679.74  5063.8 1684.51  5073.9 1685.39
  5106.3  1689.2  5267.7 1687.79  5310.2 1688.92    5441 1699.69  5477.6  1704.9
  5571.4 1709.95  5670.1 1710.11  5775.8 1710.65  6087.5 1719.54  6230.3 1722.28
#Mann= 12 ,-1 , 0
  3897.4     .05       0  4185.9     .16       0    4194      .1       0
  4542.3     .05       0  4701.8     .16       0  4910.8      .1       0
  4995.9     .07       0  5001.9      .1       0  5073.9     .16       0
  5571.4      .1       0  5670.1     .05       0  6087.5      .1       0
Bank Sta=4933,5106.3
XS Rating Curve= 0 ,0
Exp/Cntr=0.3,0.1

Type RM Length L Ch R = 1 ,41975   ,743,743,743
BEGIN DESCRIPTION:
WILLOW CREEK 62.0
END DESCRIPTION:
XS GIS Cut Line= 3
      2806079.62     10114385.67       2806256.7     10113422.17
      2806157.74      10112932.6
#Sta/Elev= 30
  3798.4  1712.9  3988.2 1704.83    4074 1701.05  4098.3 1700.86  4168.8 1696.47
  4237.6 1693.16  4278.2 1692.77  4315.7 1690.49  4379.9 1689.92  4418.5 1688.33
  4512.1 1687.24  4695.1 1689.47  4858.1 1688.21  4899.6 1686.73  4939.7 1683.25
  4945.3  1681.3  4950.4 1681.09  4970.3  1676.8  4998.1 1676.15  5000.9 1675.65
  5004.1 1676.15  5011.1 1678.84  5041.7  1686.7  5046.8 1687.07  5051.9 1690.14
  5062.1  1692.6  5097.5 1695.65  5174.3 1699.24  5249.7 1701.16  5277.5  1700.6
#Mann= 7 ,-1 , 0
  3798.4     .16       0  3988.2     .05       0    4074     .16       0
  4168.8     .05       0  4418.5      .1       0  4998.1     .07       0
  5004.1      .1       0
Bank Sta=4899.6,5041.7
XS Rating Curve= 0 ,0
Exp/Cntr=0.3,0.1

Type RM Length L Ch R = 1 ,41232   ,580,580,580
BEGIN DESCRIPTION:
WILLOW CREEK 61.0
END DESCRIPTION:
XS GIS Cut Line= 2
      2806946.06     10114438.81       2806838.4      10112870.1
#Sta/Elev= 30
  4051.1 1716.44  4126.4 1713.74  4176.5 1713.02  4233.3 1710.86  4276.7  1708.2
  4306.8 1707.77  4392.3 1704.03    4417 1702.61  4447.1 1698.69  4517.3 1699.74
  4537.3 1696.45  4567.4 1696.23  4687.7 1689.23  4868.1  1684.4  4958.3 1683.84
  4964.3 1681.57  4978.4 1678.58  4988.4 1673.55  4995.4 1672.64  4998.2 1672.14
  5001.4 1672.64  5027.4 1675.23  5048.5 1679.62  5088.6 1681.65  5128.1 1682.38
    5269 1685.03  5349.2 1689.58  5479.5 1694.16    5604 1694.28  5623.5 1694.39
#Mann= 7 ,-1 , 0
  4051.1      .1       0  4392.3     .05       0  4995.4    .035       0
  5001.4     .05       0  5027.4     .16       0  5128.1      .1       0
    5604     .05       0
Bank Sta=4958.3,5088.6
XS Rating Curve= 0 ,0
Exp/Cntr=0.3,0.1

Type RM Length L Ch R = 1 ,40652   ,692,692,692
BEGIN DESCRIPTION:
WILLOW CREEK 60.0
END DESCRIPTION:
XS GIS Cut Line= 3
      2807684.25     10113777.44      2807107.54     10112770.12
      2806796.15     10112603.91
#Sta/Elev= 30
  4455.9 1699.45  4529.3 1698.78  4723.2 1691.93  4756.7 1689.87  4778.3 1691.92
  4794.1 1692.32  4805.9  1690.1  4858.9 1686.94  4871.2 1684.69  4874.7 1684.05
  4886.5 1680.78    4902 1678.47  4917.9 1678.52  4932.6 1675.99  4939.4 1672.78
  4955.3 1670.87  4976.9  1670.4  4990.2 1671.13  5010.3 1669.75    5013 1669.25
  5016.3 1669.75    5020 1670.03  5047.8 1682.04  5057.4 1683.61  5261.8 1680.89
  5325.4 1680.92  5481.9 1683.27  5611.7  1687.4  5927.6 1693.44  5969.6 1694.28
#Mann= 7 ,-1 , 0
  4455.9      .1       0  4723.2     .05       0  4871.2      .1       0
  5010.3     .07       0  5016.3      .1       0  5325.4     .05       0
  5927.6      .1       0
Bank Sta=4874.7,5057.4
XS Rating Curve= 0 ,0
Exp/Cntr=0.3,0.1

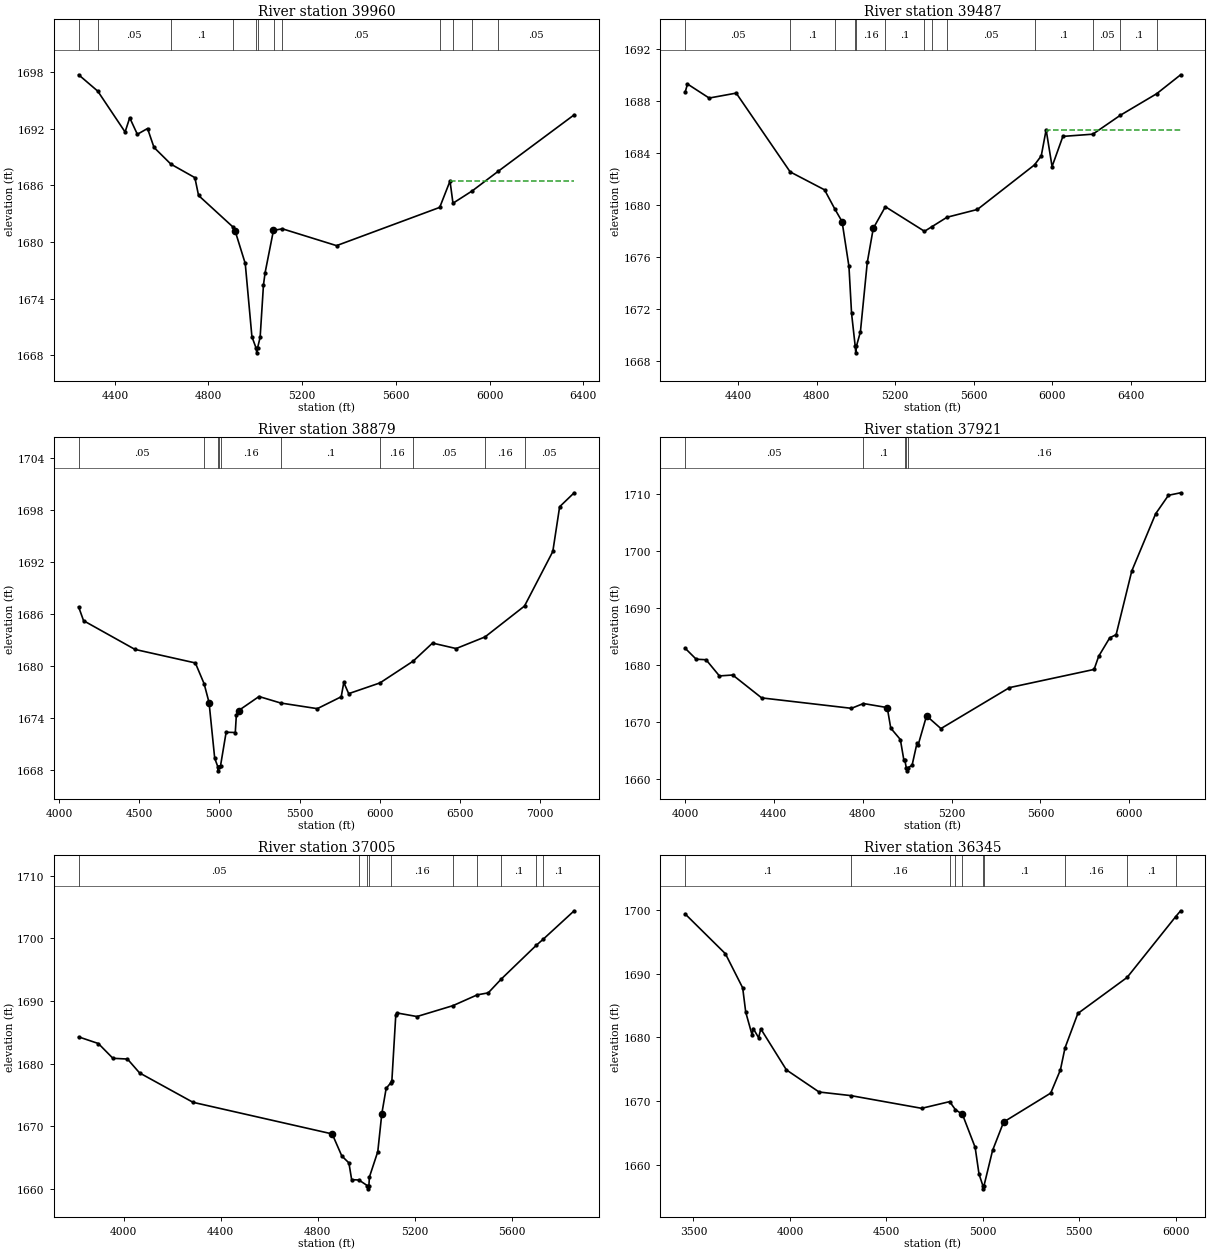
Type RM Length L Ch R = 1 ,39960   ,473,473,473
BEGIN DESCRIPTION:
WILLOW CREEK 59.0
END DESCRIPTION:
XS GIS Cut Line= 4
      2807898.58     10113593.46      2808072.18     10113024.91
      2807551.35     10112434.63       2806822.8     10112343.56
#Sta/Elev= 30
  4245.5 1697.71  4327.1 1695.98  4443.9 1691.65  4463.6 1693.16  4496.2 1691.41
  4539.7 1692.02  4567.3 1690.02  4639.4 1688.25  4741.8 1686.82  4757.6 1684.93
  4905.1 1681.58  4914.2 1681.14  4956.9 1677.73  4985.4 1669.98  5003.3 1668.77
    5006 1668.27  5009.3 1668.77  5020.5 1669.91  5034.7 1675.45  5041.6 1676.74
  5077.4 1681.24  5080.1 1681.25  5115.7  1681.4  5346.8 1679.62  5787.3 1683.67
  5831.3 1686.46  5843.9 1684.11  5926.3 1685.42    6038 1687.51  6361.4 1693.47
#Mann= 12 ,-1 , 0
  4245.5      .1       0  4327.1     .05       0  4639.4      .1       0
  4905.1     .16       0  5003.3     .07       0  5009.3     .16       0
  5080.1      .1       0  5115.7     .05       0  5787.3      .1       0
  5843.9     .05       0  5926.3      .1       0    6038     .05       0
#XS Ineff= 2 , 0
                         5830.66         1686.45
Permanent Ineff=
       F       F
Bank Sta=4914.2,5077.4
XS Rating Curve= 0 ,0
Exp/Cntr=0.3,0.1

Type RM Length L Ch R = 1 ,39487   ,608,608,608
BEGIN DESCRIPTION:
Mapping XS 2812b2f2
END DESCRIPTION:
XS GIS Cut Line= 3
      2808779.67     10113359.15      2808245.79     10112473.69
      2806848.54     10111948.64
#Sta/Elev= 30
  4128.7 1688.64  4140.8 1689.29  4251.4 1688.21  4389.3 1688.59  4664.4 1682.53
  4839.7 1681.15  4891.2  1679.7    4929 1678.71  4964.1 1675.26  4977.5 1671.64
  4996.1 1669.11  4998.9 1668.61  5002.1 1669.11  5022.5 1670.22  5057.5 1675.56
  5088.2 1678.19  5149.8 1679.85  5349.3 1677.96  5385.6  1678.3    5464 1679.04
  5619.2 1679.64  5910.3 1683.07  5944.6 1683.76  5969.5 1685.77  5999.8 1682.94
  6054.9 1685.26  6207.5 1685.43  6347.3 1686.88  6532.8 1688.54  6655.3    1690
#Mann= 13 ,-1 , 0
  4128.7     .05       0  4664.4      .1       0  4891.2     .16       0
  4996.1     .07       0  5002.1     .16       0  5149.8      .1       0
  5349.3     .16       0  5385.6      .1       0    5464     .05       0
  5910.3      .1       0  6207.5     .05       0  6347.3      .1       0
  6532.8     .05       0
#XS Ineff= 2 , 0
                         5971.58         1685.78
Permanent Ineff=
       F       F
Bank Sta=4929,5088.2
XS Rating Curve= 0 ,0
Exp/Cntr=0.3,0.1

Type RM Length L Ch R = 1 ,38879   ,958,958,958
BEGIN DESCRIPTION:
WILLOW CREEK 58.0
END DESCRIPTION:
XS GIS Cut Line= 4
      2808976.92      10112954.5      2809013.85     10112418.99
      2808553.21     10112024.21      2806723.28     10111355.28
#Sta/Elev= 30
  4121.9 1686.81  4152.7 1685.22  4473.5 1681.91  4850.1 1680.35  4904.9 1677.95
  4935.7 1675.78  4970.8 1669.37  4989.8 1668.41  4992.5 1667.91  4995.8 1668.41
  5007.3  1668.5  5042.2 1672.36  5099.3 1672.33  5105.8  1674.3  5120.1 1674.86
  5247.4 1676.48  5382.5 1675.73  5611.1 1675.08  5760.2 1676.45  5776.3  1678.1
  5806.8 1676.81  6002.3 1678.05  6209.2 1680.56  6329.8 1682.64  6477.2 1682.01
  6657.5 1683.35  6903.8 1686.91  7080.4  1693.2    7123 1698.36  7213.7 1699.97
#Mann= 10 ,-1 , 0
  4121.9     .05       0  4904.9      .1       0  4989.8     .07       0
  4995.8      .1       0  5007.3     .16       0  5382.5      .1       0
  6002.3     .16       0  6209.2     .05       0  6657.5     .16       0
  6903.8     .05       0
#XS Ineff= 2 , 0
                          6342.5         1682.52
Permanent Ineff=
       F       F
Bank Sta=4935.7,5120.1
XS Rating Curve= 0 ,0
Exp/Cntr=0.3,0.1

Type RM Length L Ch R = 1 ,37921   ,916,916,916
BEGIN DESCRIPTION:
Mapping XS 960314b0
END DESCRIPTION:
XS GIS Cut Line= 4
      2809085.62     10112177.94      2809057.84     10111525.16
      2808259.23     10111066.82      2807746.36     10110657.91
#Sta/Elev= 30
  4000.8 1682.89  4050.8 1680.96  4095.1 1680.87  4155.2 1678.03  4215.2 1678.19
  4345.3 1674.18  4749.5 1672.35  4803.3 1673.19  4910.5 1672.48  4926.3 1668.88
  4969.5 1666.88  4985.3 1663.28  4989.3 1663.34  4996.4 1661.89  4999.1 1661.39
  5002.4 1661.89  5022.4 1662.38  5044.3 1666.23    5050 1665.98  5087.4 1671.03
  5152.1  1668.8  5460.5 1675.98  5841.4 1679.17  5862.2 1681.49  5911.8 1684.71
  5940.6 1685.27  6011.1 1696.44  6118.4 1706.46  6176.1  1709.7  6230.9 1710.14
#Mann= 5 ,-1 , 0
  4000.8     .05       0  4803.3      .1       0  4989.3     .16       0
  4996.4     .07       0  5002.4     .16       0
Bank Sta=4910.5,5087.4
XS Rating Curve= 0 ,0
Exp/Cntr=0.3,0.1

Type RM Length L Ch R = 1 ,37005   ,660,660,660
BEGIN DESCRIPTION:
WILLOW CREEK 57.0
END DESCRIPTION:
XS GIS Cut Line= 3
      2809114.57     10112254.89      2809168.39     10111232.17
      2809437.41     10110248.32
#Sta/Elev= 30
  3814.4 1684.27  3895.7 1683.21  3955.8 1680.85  4015.8 1680.73  4065.9 1678.51
  4286.2 1673.82  4860.3 1668.77    4900 1665.25  4929.3 1664.14  4940.6 1661.47
  4970.6 1661.41  5005.7  1660.5  5008.5    1660  5011.7  1660.5  5013.9 1661.89
  5048.4 1665.94    5065    1672  5082.9 1676.04  5101.7 1676.92  5106.5 1677.25
  5122.6 1687.74  5127.8 1688.09  5210.1 1687.52  5358.6 1689.26  5458.5 1690.98
    5504  1691.3  5557.3 1693.49  5702.8 1698.92  5730.6 1699.86  5858.5 1704.41
#Mann= 10 ,-1 , 0
  3814.4     .05       0  4970.6      .1       0  5005.7     .07       0
  5011.7      .1       0  5101.7     .16       0  5358.6      .1       0
  5458.5     .16       0  5557.3      .1       0  5702.8     .16       0
  5730.6      .1       0
Bank Sta=4860.3,5065
XS Rating Curve= 0 ,0
Exp/Cntr=0.3,0.1

Type RM Length L Ch R = 1 ,36345   ,530,530,530
BEGIN DESCRIPTION:
WILLOW CREEK 56.0
END DESCRIPTION:
XS GIS Cut Line= 3
      2810121.93      10112870.1      2809729.75     10111532.07
       2809837.4     10110363.24
#Sta/Elev= 30
  3456.7 1699.36  3665.5 1693.11  3755.1 1687.75    3771 1683.92  3804.4  1680.3
  3809.6 1681.37  3837.8 1679.92  3848.9 1681.32  3981.8 1674.87  4151.1  1671.4
  4314.6 1670.84  4682.6 1668.84  4827.8 1669.89  4857.7 1668.62  4891.6 1667.95
  4893.1 1667.96  4959.8 1662.72  4979.9 1658.52  4999.8  1656.7  5002.6  1656.2
  5005.8  1656.7  5050.2 1662.23  5107.5 1666.69  5351.5 1671.23  5401.7 1674.87
  5425.5 1678.32  5492.1 1683.73  5747.5 1689.39  5999.1 1698.93  6024.8 1699.85
#Mann= 10 ,-1 , 0
  3456.7      .1       0  4314.6     .16       0  4827.8      .1       0
  4857.7     .16       0  4891.6      .1       0  4999.8     .07       0
  5005.8      .1       0  5425.5     .16       0  5747.5      .1       0
  5999.1     .05       0
Bank Sta=4893.1,5107.5
XS Rating Curve= 0 ,0
Exp/Cntr=0.3,0.1

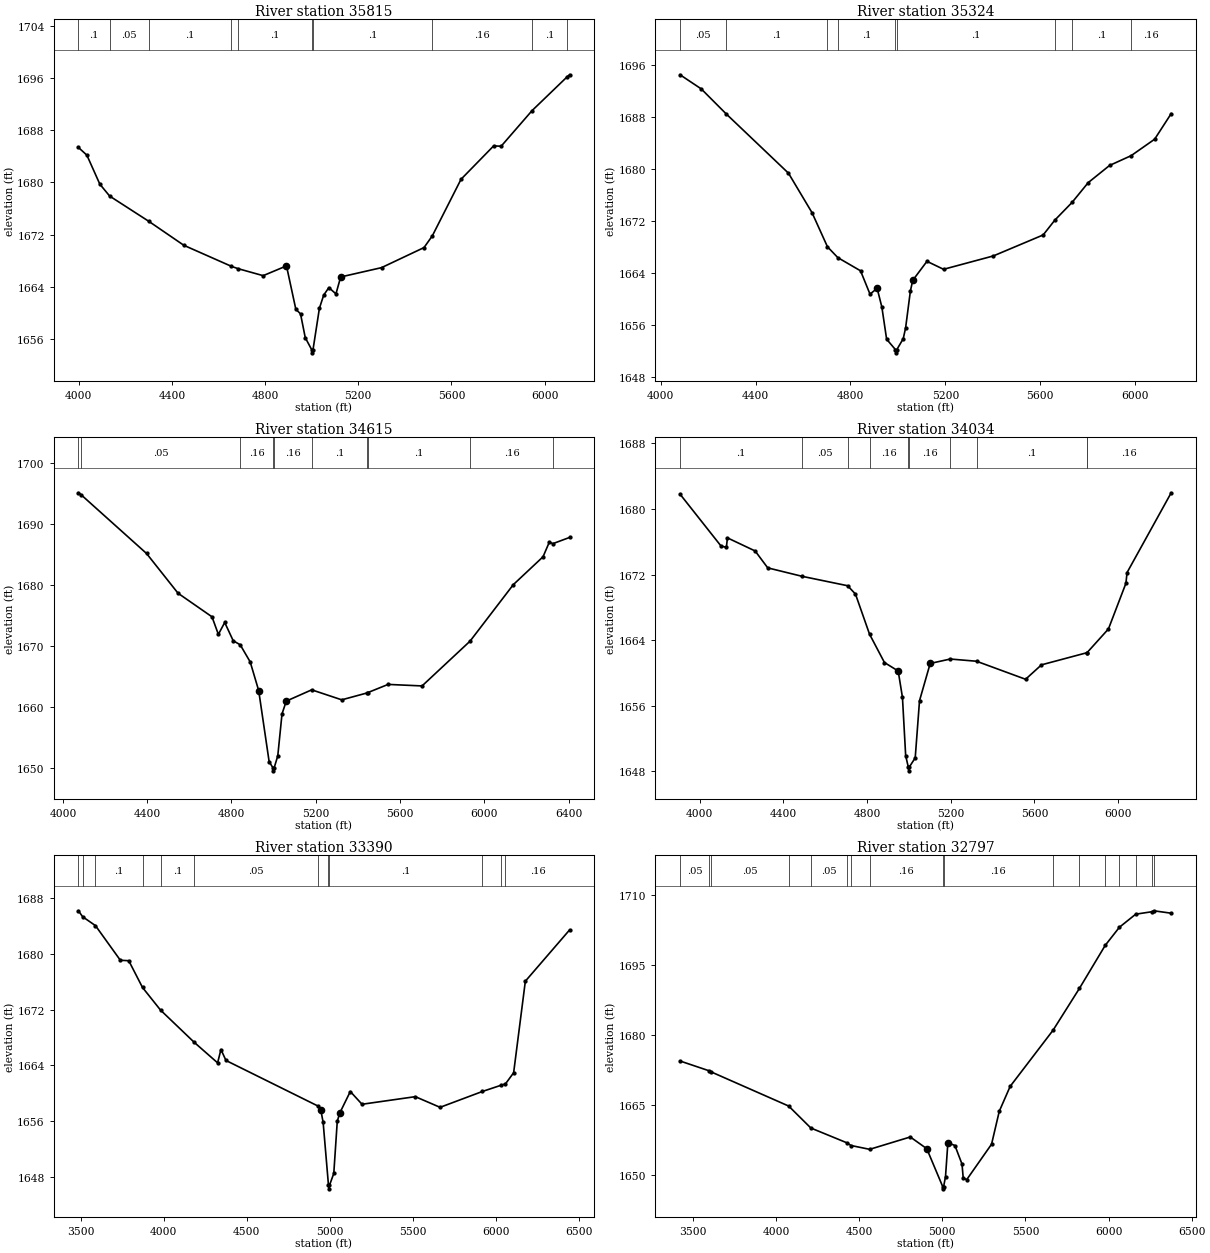
Type RM Length L Ch R = 1 ,35815   ,491,491,491
BEGIN DESCRIPTION:
WILLOW CREEK 55.0
END DESCRIPTION:
XS GIS Cut Line= 3
      2810191.13     10112485.55      2810252.65     10111547.45
       2810060.4     10110393.97
#Sta/Elev= 30
  3998.1 1685.36  4034.4 1684.18  4090.1 1679.73  4132.3  1677.9  4299.5 1674.05
  4450.9 1670.35  4654.8 1667.13  4683.2 1666.77  4791.6 1665.69  4891.8 1667.19
  4931.9 1660.54  4952.1 1659.83  4972.4 1656.18  4999.8 1654.35  5002.6 1653.85
  5005.8 1654.35  5033.2 1660.69  5051.7 1662.71  5073.8 1663.86  5104.2 1662.89
  5124.5 1665.49    5300 1666.92  5482.5    1670  5518.2  1671.8  5641.5 1680.48
  5781.6  1685.6  5813.8 1685.55  5946.5 1691.01  6098.2 1696.23  6107.6 1696.51
#Mann= 10 ,-1 , 0
  3998.1      .1       0  4132.3     .05       0  4299.5      .1       0
  4654.8     .05       0  4683.2      .1       0  4999.8     .07       0
  5005.8      .1       0  5518.2     .16       0  5946.5      .1       0
  6098.2     .05       0
Bank Sta=4891.8,5124.5
XS Rating Curve= 0 ,0
Exp/Cntr=0.3,0.1

Type RM Length L Ch R = 1 ,35324   ,709,709,709
BEGIN DESCRIPTION:
WILLOW CREEK 54.0
END DESCRIPTION:
XS GIS Cut Line= 3
      2810998.54     10112408.66      2810714.03     10111716.62
       2810737.1     10110393.96
#Sta/Elev= 30
  4081.4  1694.5  4170.7 1692.33  4276.2 1688.47  4538.6 1679.35  4638.1 1673.26
    4703 1668.02  4746.7 1666.35  4842.5 1664.32  4882.5 1660.72  4912.5 1661.63
  4932.5 1658.72  4952.5 1653.79  4989.6 1652.19  4992.3 1651.69  4995.6 1652.19
  5022.6 1653.87  5032.6 1655.54  5052.6 1661.18  5062.6 1662.85  5122.6 1665.78
  5192.6 1664.55  5402.6 1666.61  5612.6 1669.84  5662.3 1672.14  5734.3 1674.84
  5802.7  1677.9  5892.7 1680.54  5983.8 1682.05  6082.7 1684.58  6152.5 1688.52
#Mann= 9 ,-1 , 0
  4081.4     .05       0  4276.2      .1       0    4703     .05       0
  4746.7      .1       0  4989.6     .07       0  4995.6      .1       0
  5662.3     .16       0  5734.3      .1       0  5983.8     .16       0
Bank Sta=4912.5,5062.6
XS Rating Curve= 0 ,0
Exp/Cntr=0.3,0.1

Type RM Length L Ch R = 1 ,34615   ,581,581,581
BEGIN DESCRIPTION:
WILLOW CREEK 52.0
END DESCRIPTION:
XS GIS Cut Line= 2
      2811521.45     10112593.23      2811244.64     10110278.73
#Sta/Elev= 30
  4073.7 1695.12    4086 1694.81  4397.1 1685.16  4546.5 1678.64  4707.7 1674.77
  4737.9 1671.89  4768.1 1673.84  4808.4 1670.84  4841.6 1670.18    4889 1667.37
  4929.3 1662.67  4978.8 1651.02  4996.8    1650  4999.5  1649.5  5002.8    1650
  5019.9 1651.96    5040 1658.84  5060.2 1660.94  5180.9 1662.79  5323.5 1661.15
  5443.8 1662.28    5446 1662.32  5543.6 1663.68  5704.7 1663.43  5932.5 1670.78
  6137.8 1680.05  6278.8 1684.62    6309 1687.05  6325.2 1686.77  6404.7 1687.79
#Mann= 10 ,-1 , 0
  4073.7      .1       0    4086     .05       0  4841.6     .16       0
  4996.8     .07       0  5002.8     .16       0  5180.9      .1       0
  5443.8     .05       0    5446      .1       0  5932.5     .16       0
  6325.2      .1       0
Bank Sta=4929.3,5060.2
XS Rating Curve= 0 ,0
Exp/Cntr=0.3,0.1

Type RM Length L Ch R = 1 ,34034   ,644,644,644
BEGIN DESCRIPTION:
WILLOW CREEK 51.0
END DESCRIPTION:
XS GIS Cut Line= 3
       2812167.4     10112585.58      2811905.94     10111293.68
      2811498.59     10110348.31
#Sta/Elev= 30
  3906.4  1681.8  4102.1 1675.48  4127.8 1675.31  4132.9 1676.47  4265.4 1674.87
  4325.5 1672.81  4489.6 1671.78  4707.5 1670.63  4744.9 1669.61  4812.1 1664.72
  4883.4 1661.26    4949 1660.23  4969.4 1657.02  4984.8  1649.9    4997 1648.55
  4999.7 1648.05    5003 1648.55  5030.4 1649.63    5051 1656.61    5102 1661.15
    5198 1661.69  5323.4 1661.42  5557.9 1659.22  5633.9 1660.98  5849.6 1662.45
  5851.9 1662.47    5954 1665.36  6037.5 1670.93    6043 1672.24  6253.9 1681.97
#Mann= 10 ,-1 , 0
  3906.4      .1       0  4489.6     .05       0  4707.5      .1       0
  4812.1     .16       0    4997     .07       0    5003     .16       0
    5198     .05       0  5323.4      .1       0  5849.6     .05       0
  5851.9     .16       0
Bank Sta=4949,5102
XS Rating Curve= 0 ,0
Exp/Cntr=0.3,0.1

Type RM Length L Ch R = 1 ,33390   ,593,593,593
BEGIN DESCRIPTION:
WILLOW CREEK 50.0
END DESCRIPTION:
XS GIS Cut Line= 3
       2812390.4     10112723.99      2812582.64     10111324.44
      2811629.09     10110109.43
#Sta/Elev= 30
  3486.5 1686.18  3512.2 1685.32  3589.2 1684.05  3739.1 1679.08  3789.6 1679.02
  3872.4 1675.18  3980.8 1671.94  4184.4  1667.3  4324.6 1664.37  4344.7 1666.28
    4375 1664.71  4929.4 1658.17  4945.5 1657.66    4960 1655.84  4992.2  1646.8
    4995  1646.3  4998.2  1646.8  5024.1 1648.51    5045 1655.97  5059.4 1657.14
  5123.6 1660.26  5194.1 1658.43    5515 1659.52  5664.1 1657.99  5919.5 1660.27
  6031.7 1661.16  6057.4 1661.34    6107 1662.95  6177.5 1676.08  6443.7 1683.43
#Mann= 12 ,-1 , 0
  3486.5      .1       0  3512.2     .16       0  3589.2      .1       0
  3872.4     .16       0  3980.8      .1       0  4184.4     .05       0
  4929.4      .1       0  4992.2     .07       0  4998.2      .1       0
  5919.5     .05       0  6031.7      .1       0  6057.4     .16       0
#XS Ineff= 2 , 0
         4345.83  1666.2
Permanent Ineff=
       F       F
Bank Sta=4945.5,5059.4
XS Rating Curve= 0 ,0
Exp/Cntr=0.3,0.1

Type RM Length L Ch R = 1 ,32797   ,860,860,860
BEGIN DESCRIPTION:
WILLOW CREEK 49.0
END DESCRIPTION:
XS GIS Cut Line= 3
      2813897.59     10111931.94       2812690.3     10110632.37
      2812474.98     10109471.18
#Sta/Elev= 30
  3422.1 1674.34  3596.2 1672.25  3605.6 1672.06  4075.7 1664.68  4209.1 1659.97
  4424.4 1656.82  4450.7 1656.22  4562.9  1655.4  4807.2 1658.05  4906.4 1655.54
    5002 1647.43  5004.8 1646.93    5008 1647.43  5019.2 1649.56  5033.4 1656.84
  5075.9 1656.21  5118.4 1652.24  5125.7 1649.24  5146.7  1648.9  5296.2  1656.5
  5342.5 1663.55  5408.1  1668.9  5666.6 1680.96  5824.5 1689.89  5980.1 1699.14
  6065.4 1703.02  6163.5 1705.82  6263.5 1706.36  6271.5 1706.55  6376.9 1706.03
#Mann= 17 ,-1 , 0
  3422.1     .05       0  3596.2      .1       0  3605.6     .05       0
  4075.7      .1       0  4209.1     .05       0  4424.4     .16       0
  4450.7     .05       0  4562.9     .16       0    5002     .07       0
    5008     .16       0  5666.6      .1       0  5824.5     .16       0
  5980.1      .1       0  6065.4     .16       0  6163.5      .1       0
  6263.5     .05       0  6271.5      .1       0
Bank Sta=4906.4,5033.4
XS Rating Curve= 0 ,0
Exp/Cntr=0.3,0.1

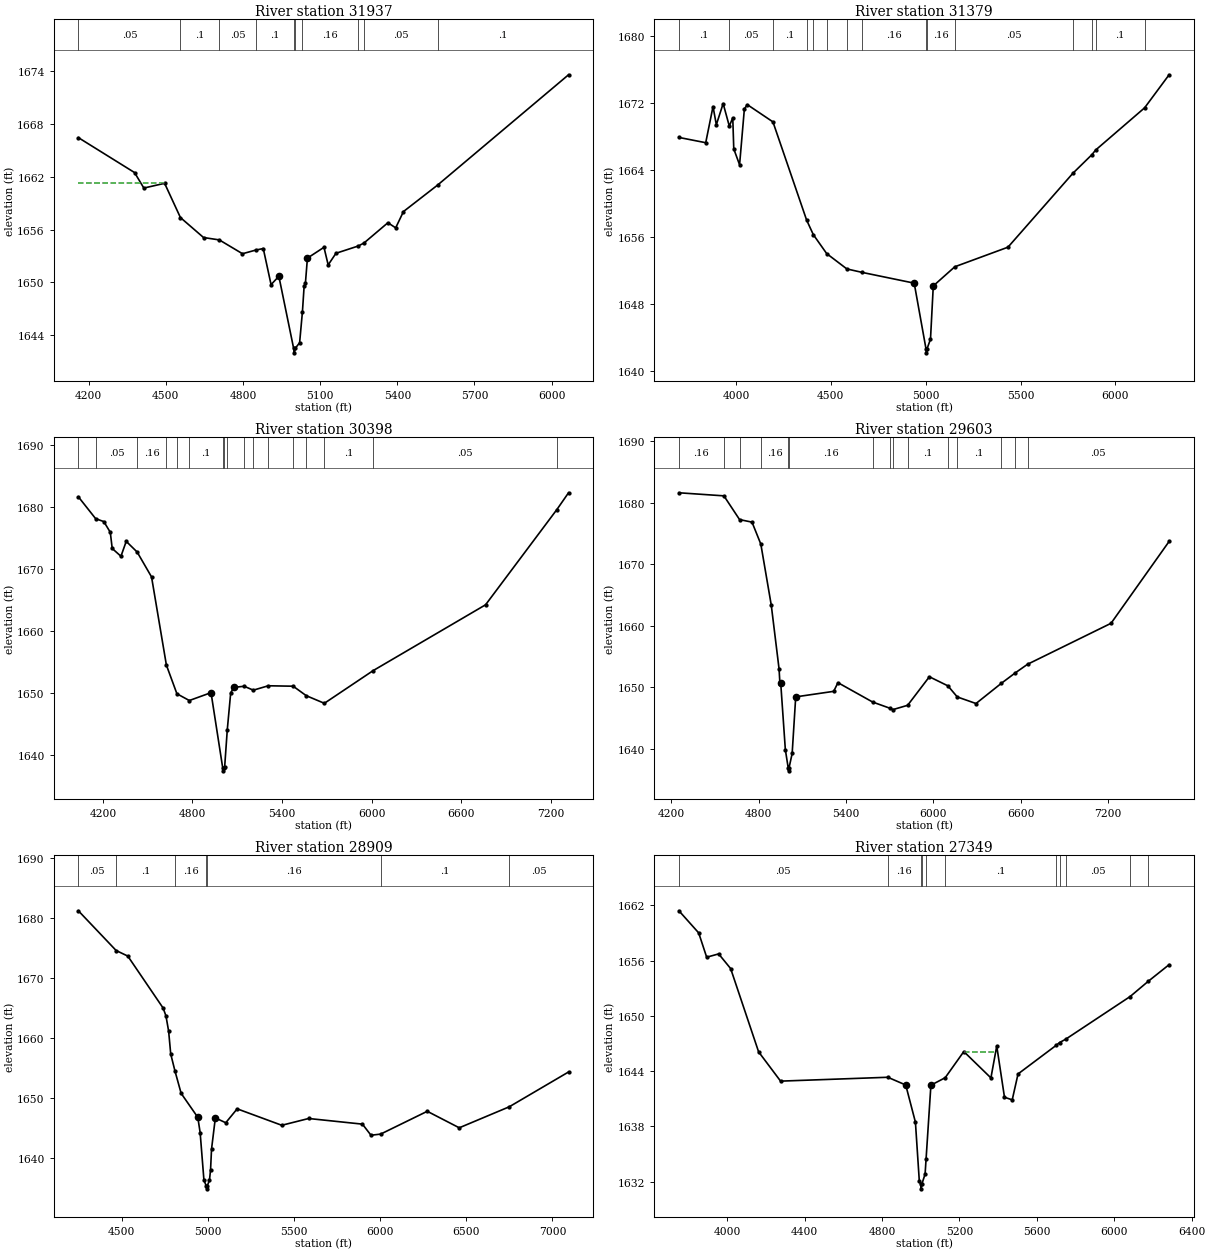
Type RM Length L Ch R = 1 ,31937   ,558,558,558
BEGIN DESCRIPTION:
WILLOW CREEK 48.0
END DESCRIPTION:
XS GIS Cut Line= 3
      2813713.04     10111485.96      2813528.48     10110140.22
      2813305.46     10109640.35
#Sta/Elev= 30
  4159.9 1666.45  4378.4 1662.48  4414.5 1660.72  4495.2 1661.26  4556.7 1657.37
  4646.6  1655.1  4707.9 1654.83    4798 1653.26  4849.1 1653.67  4878.8 1653.85
  4909.1 1649.75  4939.4  1650.7  4996.9  1642.5  4999.7    1642  5002.9  1642.5
  5020.1 1643.15  5031.1 1646.69  5037.6 1649.56  5042.6 1649.89  5050.4 1652.76
  5114.8 1653.99  5131.1 1651.99  5161.4 1653.31  5248.4 1654.14  5270.4 1654.48
  5363.3 1656.78  5393.6  1656.2  5423.8 1658.05  5556.6 1661.06  6065.6 1673.59
#Mann= 10 ,-1 , 0
  4159.9     .05       0  4556.7      .1       0  4707.9     .05       0
  4849.1      .1       0  4996.9     .07       0  5002.9      .1       0
  5031.1     .16       0  5248.4      .1       0  5270.4     .05       0
  5556.6      .1       0
#XS Ineff= 2 , 0
         4495.77 1661.32
Permanent Ineff=
       F       F
Bank Sta=4939.4,5050.4
XS Rating Curve= 0 ,0
Exp/Cntr=0.3,0.1

Type RM Length L Ch R = 1 ,31379   ,981,981,981
BEGIN DESCRIPTION:
WILLOW CREEK 47.0
END DESCRIPTION:
XS GIS Cut Line= 3
      2814551.21     10111662.77      2814135.97     10110517.02
      2813336.24      10109409.7
#Sta/Elev= 30
  3698.9 1667.88  3840.2 1667.25  3878.7 1671.57  3896.2  1669.4  3932.1 1671.93
  3964.6 1669.23  3982.8 1670.23  3988.1 1666.51  4018.7 1664.61    4044 1671.29
  4059.5  1671.8  4194.6 1669.74  4371.9 1658.02  4407.5 1656.26  4478.2 1653.99
  4584.4 1652.16  4666.3 1651.74  4939.5 1650.46  5001.5 1642.63  5004.3 1642.13
  5007.5 1642.63  5025.4 1643.77  5040.1 1650.13  5153.6 1652.42  5433.9 1654.76
  5776.8 1663.61  5876.5 1665.82    5896 1666.37  6154.4 1671.42  6283.5 1675.37
#Mann= 15 ,-1 , 0
  3698.9      .1       0  3964.6     .05       0  4194.6      .1       0
  4371.9     .05       0  4407.5      .1       0  4478.2     .16       0
  4584.4      .1       0  4666.3     .16       0  5001.5     .07       0
  5007.5     .16       0  5153.6     .05       0  5776.8      .1       0
  5876.5     .05       0    5896      .1       0  6154.4     .05       0
Bank Sta=4939.5,5040.1
XS Rating Curve= 0 ,0
Exp/Cntr=0.3,0.1

Type RM Length L Ch R = 1 ,30398   ,795,795,795
BEGIN DESCRIPTION:
Mapping XS 60996088
END DESCRIPTION:
XS GIS Cut Line= 4
      2815385.54     10111245.38      2815107.77     10110872.13
       2814960.2     10109969.35       2813572.4     10108663.95
#Sta/Elev= 30
  4035.1 1681.66    4151 1678.13  4205.8 1677.66  4249.1 1675.93    4262 1673.32
  4320.5 1672.06  4355.9 1674.47    4429 1672.75  4525.6 1668.73  4625.1  1654.5
  4695.6 1649.87  4778.8 1648.78  4924.3 1650.05  5002.4 1637.93  5005.1 1637.43
  5008.4 1637.93  5015.5 1638.02  5033.3 1644.09    5056 1649.99  5076.3  1650.9
  5146.4 1651.08  5207.8 1650.45  5308.1 1651.16  5474.8 1651.09  5562.6 1649.56
  5683.8 1648.33  6009.8 1653.59  6764.3 1664.23  7242.5 1679.61  7320.4 1682.31
#Mann= 17 ,-1 , 0
  4035.1      .1       0    4151     .05       0    4429     .16       0
  4625.1      .1       0  4695.6     .16       0  4778.8      .1       0
  5002.4     .07       0  5008.4      .1       0  5033.3     .16       0
  5146.4      .1       0  5207.8     .16       0  5308.1     .05       0
  5474.8      .1       0  5562.6     .05       0  5683.8      .1       0
  6009.8     .05       0  7242.5      .1       0
Bank Sta=4924.3,5076.3
XS Rating Curve= 0 ,0
Exp/Cntr=0.3,0.1

Type RM Length L Ch R = 1 ,29603   ,694,694,694
BEGIN DESCRIPTION:
WILLOW CREEK 46.0
END DESCRIPTION:
XS GIS Cut Line= 3
      2816088.69     10111093.53      2815737.11     10110203.73
      2813818.72      10108745.4
#Sta/Elev= 30
    4252 1681.59    4561 1681.09  4668.6 1677.23  4753.9 1676.82  4814.5 1673.25
  4886.2 1663.33  4939.9 1652.94  4945.9 1650.46  4951.3 1650.61  4982.9 1639.84
  5002.4  1636.9  5005.1  1636.4  5008.4  1636.9  5029.7 1639.22  5054.1 1648.42
    5315 1649.32  5344.1 1650.73  5582.6 1647.58  5702.7 1646.56  5721.5 1646.35
  5822.7 1647.05  5972.1 1651.69  6099.5 1650.21  6163.7 1648.41  6292.3 1647.34
  6466.1 1650.62  6561.5 1652.31  6646.4 1653.72  7219.8 1660.38  7618.5 1673.68
#Mann= 15 ,-1 , 0
    4252     .16       0    4561      .1       0  4668.6     .05       0
  4814.5     .16       0  5002.4     .07       0  5008.4     .16       0
  5582.6      .1       0  5702.7     .05       0  5721.5     .16       0
  5822.7      .1       0  6099.5     .05       0  6163.7      .1       0
  6466.1     .05       0  6561.5      .1       0  6646.4     .05       0
Bank Sta=4951.3,5054.1
XS Rating Curve= 0 ,0
Exp/Cntr=0.3,0.1

Type RM Length L Ch R = 1 ,28909   ,1560,1560,1560
BEGIN DESCRIPTION:
WILLOW CREEK 45.0
END DESCRIPTION:
XS GIS Cut Line= 2
      2817042.73     10110355.55      2814521.99      10109033.7
#Sta/Elev= 30
  4247.5 1681.22  4466.8  1674.6  4534.6 1673.67  4739.7 1665.01  4756.1 1663.71
  4771.7 1661.16  4783.8 1657.36  4808.3 1654.54  4844.3  1650.8  4941.1  1646.8
  4954.6 1644.27  4976.7 1636.32  4990.1 1635.39  4992.9 1634.89  4996.1 1635.39
  5008.8 1636.32  5015.2 1638.11  5020.8 1641.51  5042.9 1646.71  5103.4  1645.9
  5169.6 1648.22  5428.6 1645.48  5584.7 1646.61    5897 1645.67  5946.7 1643.82
  6002.7 1644.01  6273.5 1647.81  6459.2 1645.06  6749.5 1648.56  7093.8 1654.36
#Mann= 7 ,-1 , 0
  4247.5     .05       0  4466.8      .1       0  4808.3     .16       0
  4990.1     .07       0  4996.1     .16       0  6002.7      .1       0
  6749.5     .05       0
Bank Sta=4941.1,5042.9
XS Rating Curve= 0 ,0
Exp/Cntr=0.3,0.1

Type RM Length L Ch R = 1 ,27349   ,743,743,743
BEGIN DESCRIPTION:
WILLOW CREEK 44.0
END DESCRIPTION:
XS GIS Cut Line= 3
      2816927.39     10109155.95      2815896.92     10108894.48
      2814428.23     10108917.55
#Sta/Elev= 30
  3751.1  1661.4  3853.2    1659  3894.4 1656.36  3956.3 1656.72  4018.2 1655.13
  4162.7 1646.09  4276.2 1642.91  4830.1 1643.33  4922.7 1642.49  4972.7 1638.46
  4992.7  1632.1  4999.7 1631.72  5002.5 1631.22  5005.7 1631.72  5022.7 1632.82
  5027.7 1634.43  5052.7 1642.47  5126.5 1643.28  5222.7 1646.12  5362.7 1643.26
  5392.8 1646.72  5432.8 1641.16  5472.8 1640.88  5502.8 1643.69  5700.1  1646.8
  5717.5  1647.1  5748.9 1647.46  6081.7 1652.09  6176.2 1653.76  6283.1 1655.55
#Mann= 11 ,-1 , 0
  3751.1     .05       0  4830.1     .16       0  4999.7     .07       0
  5005.7     .16       0  5027.7     .05       0  5126.5      .1       0
  5700.1     .05       0  5717.5      .1       0  5748.9     .05       0
  6081.7      .1       0  6176.2     .05       0
#XS Ineff= 2 ,-1
 5225.38 5388.01 1646.08  5392.7 5717.96 1646.68
Permanent Ineff=
       F       F
Bank Sta=4922.7,5052.7
XS Rating Curve= 0 ,0
Exp/Cntr=0.3,0.1