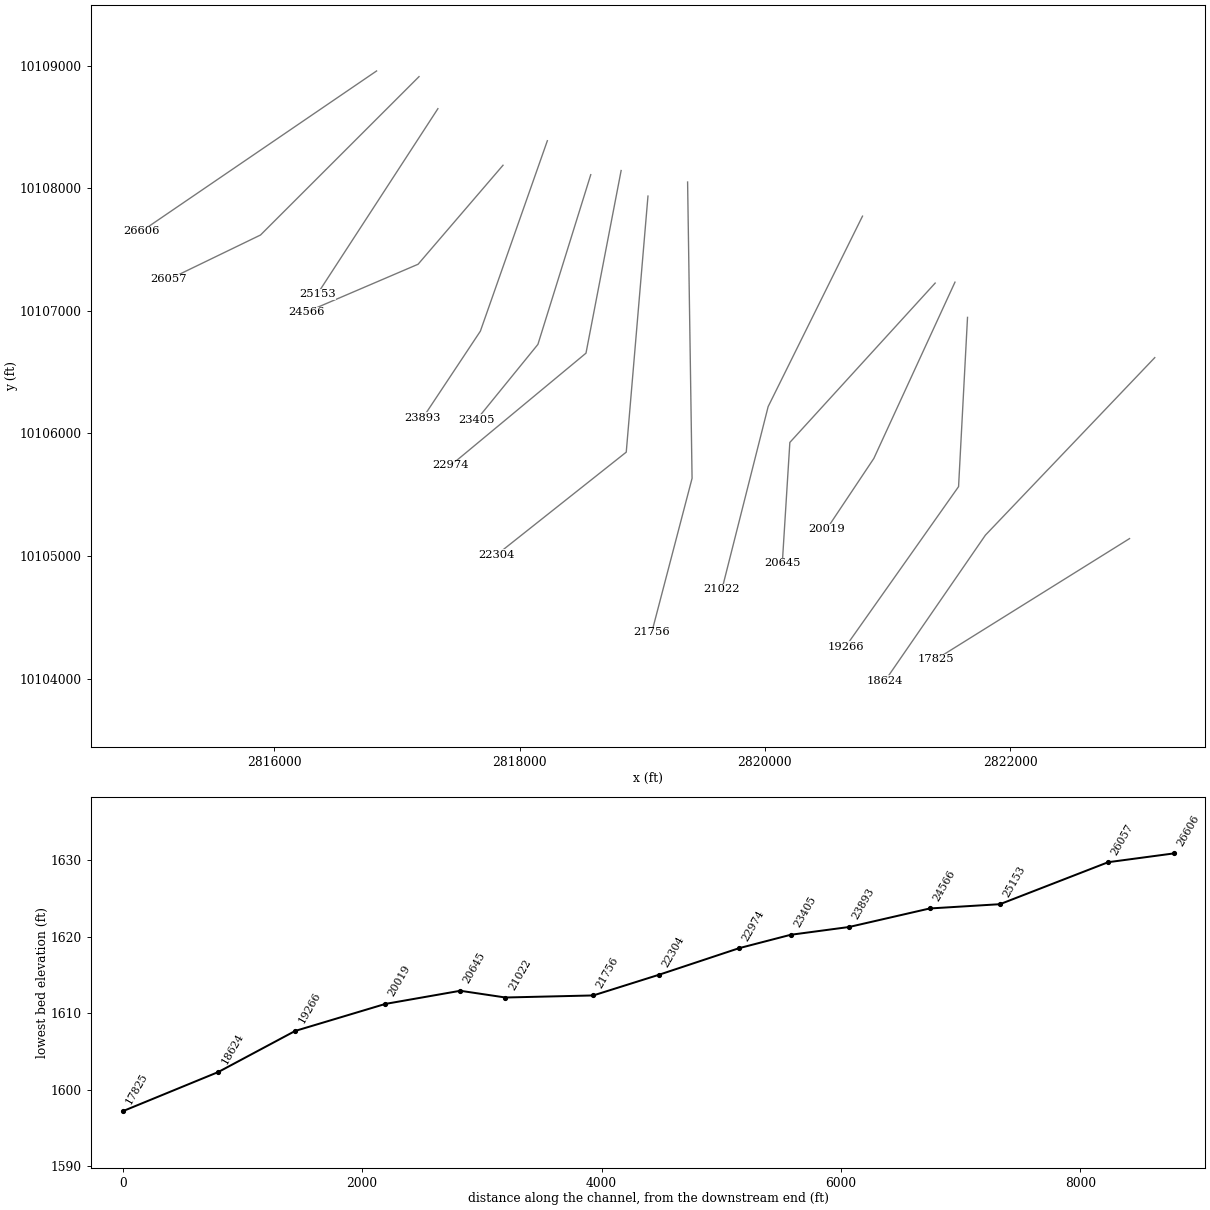
HEC-RAS study WILLOW CREEK.prj: WILLOW CREEK Base Level Engineering

--- WILLOW CREEK.g01 (geometry) --- (continued)

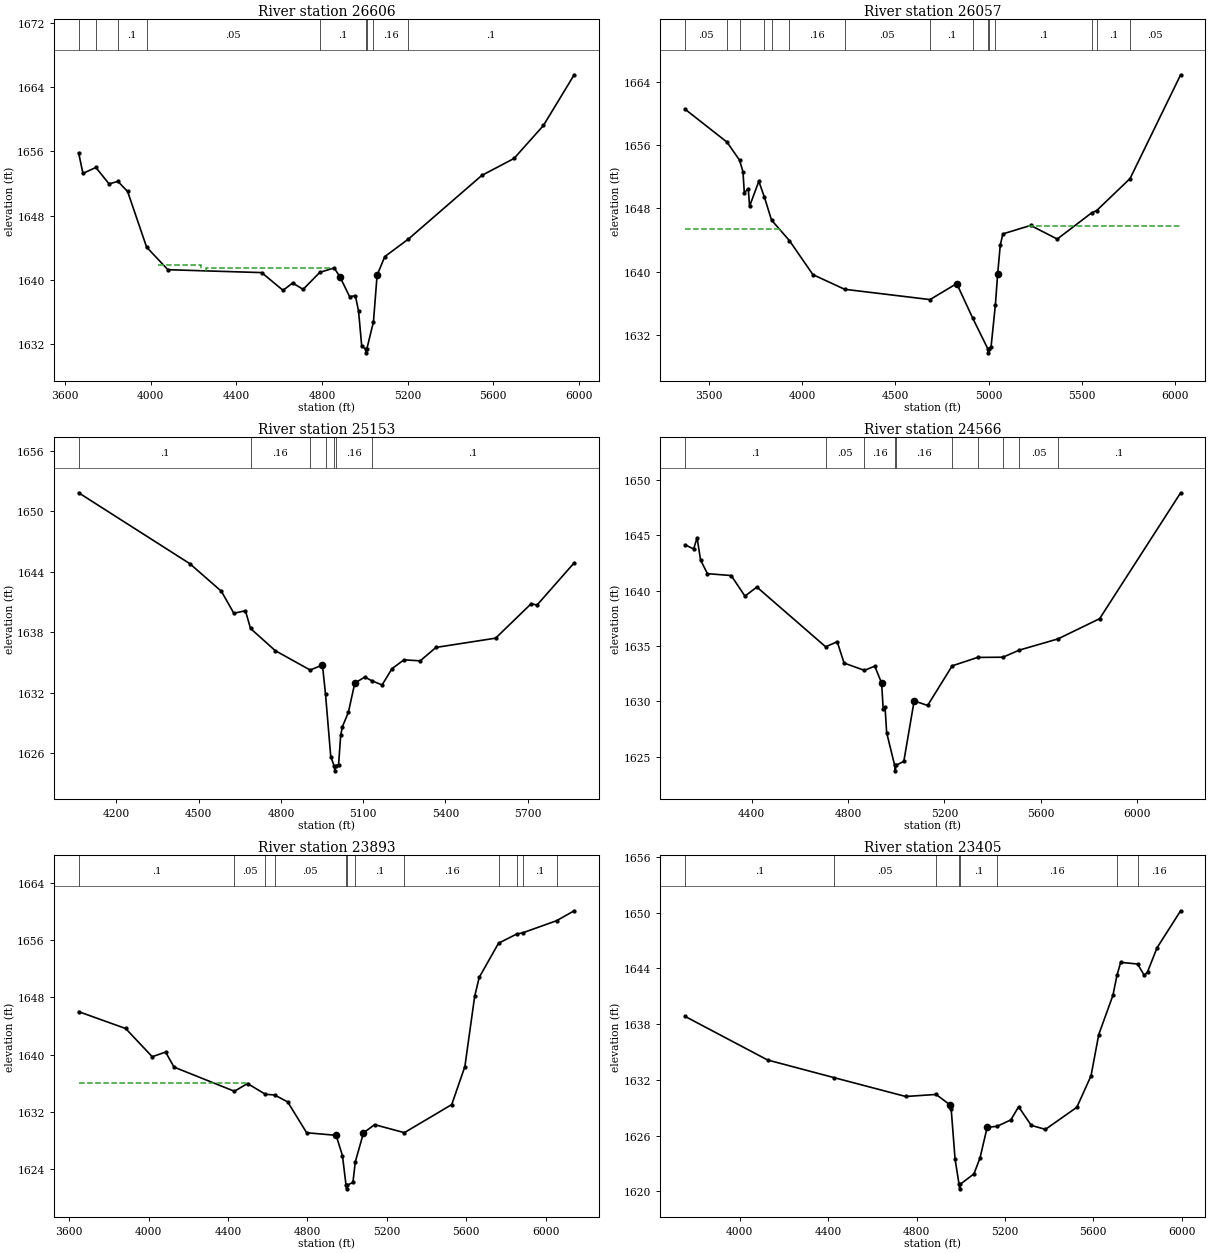
Type RM Length L Ch R = 1 ,26606   ,549,549,549
BEGIN DESCRIPTION:
WILLOW CREEK 43.0
END DESCRIPTION:
XS GIS Cut Line= 2
      2816835.08     10108956.01      2814921.86     10107649.79
#Sta/Elev= 30
  3662.4 1655.82  3682.5 1653.25  3742.9 1653.99  3804.6 1651.95  3846.1 1652.25
  3891.3    1651  3980.2 1644.07  4079.6 1641.26    4518  1640.9  4618.1 1638.69
  4662.9 1639.61  4711.7 1638.81    4790 1640.93    4857 1641.48  4884.3 1640.36
  4929.1 1637.91  4956.1 1638.02    4971 1636.12  4985.9 1631.72  5003.9 1631.41
  5006.7 1630.91  5009.9 1631.41  5040.7 1634.78  5057.7 1640.58  5093.6 1642.89
  5204.2 1645.08  5547.2    1653  5697.8 1655.11  5835.4 1659.22    5979 1665.53
#Mann= 9 ,-1 , 0
  3662.4      .1       0  3742.9     .05       0  3846.1      .1       0
  3980.2     .05       0    4790      .1       0  5003.9     .07       0
  5009.9      .1       0  5040.7     .16       0  5204.2      .1       0
#XS Ineff= 2 ,-1
  4031.4 4236.51  1641.9 4255.91 4846.27 1641.42
Permanent Ineff=
       F       F
Bank Sta=4884.3,5057.7
XS Rating Curve= 0 ,0
Exp/Cntr=0.3,0.1

Type RM Length L Ch R = 1 ,26057   ,904,904,904
BEGIN DESCRIPTION:
WILLOW CREEK 42.0
END DESCRIPTION:
XS GIS Cut Line= 3
      2817181.09     10108909.84      2815889.23     10107617.98
      2815143.43     10107256.62
#Sta/Elev= 30
  3373.1  1660.5  3597.7 1656.35  3664.7 1654.08  3683.3 1652.62  3690.4 1649.96
  3711.6 1650.48  3718.7 1648.26  3768.2 1651.41  3798.5 1649.38  3836.2 1646.52
  3932.3 1643.92  4058.1 1639.63  4228.1 1637.78  4685.8 1636.48  4828.8  1638.5
  4914.9 1634.12  4995.6 1630.26  4998.3 1629.76  5001.6 1630.26  5012.7 1630.47
  5036.2 1635.86    5048 1639.66  5062.2 1643.37  5076.3 1644.77    5225 1645.84
  5367.6 1644.12  5552.1 1647.43  5578.6 1647.71  5757.9 1651.76  6028.8 1664.85
#Mann= 15 ,-1 , 0
  3373.1     .05       0  3597.7      .1       0  3664.7     .05       0
  3798.5      .1       0  3836.2     .05       0  3932.3     .16       0
  4228.1     .05       0  4685.8      .1       0  4914.9     .05       0
  4995.6    .035       0  5001.6     .05       0  5036.2      .1       0
  5552.1     .05       0  5578.6      .1       0  5757.9     .05       0
#XS Ineff= 2 , 0
         3888.75 1645.41 5209.19         1645.74
Permanent Ineff=
       F       F
Bank Sta=4828.8,5048
XS Rating Curve= 0 ,0
Exp/Cntr=0.3,0.1

Type RM Length L Ch R = 1 ,25153   ,587,587,587
BEGIN DESCRIPTION:
WILLOW CREEK 40.0
END DESCRIPTION:
XS GIS Cut Line= 2
      2817334.89     10108648.39      2816350.64     10107133.57
#Sta/Elev= 30
  4062.6 1651.85  4468.3 1644.81    4583 1642.08  4628.4  1639.9  4670.6 1640.15
  4689.3 1638.39  4779.4 1636.19  4906.6 1634.27  4951.4 1634.77  4962.6 1631.88
  4981.7 1625.68  4993.8 1624.77  4996.6 1624.27  4999.8 1624.77  5010.3 1624.89
  5017.9 1627.78  5023.9 1628.63    5046 1630.08  5069.3 1632.97  5105.6 1633.57
  5133.2 1633.18  5168.9 1632.79  5205.1 1634.41  5248.8 1635.28  5307.9 1635.18
  5365.2 1636.51  5582.7 1637.43  5712.5 1640.85  5733.6 1640.71  5869.1  1644.9
#Mann= 7 ,-1 , 0
  4062.6      .1       0  4689.3     .16       0  4906.6     .05       0
  4962.6     .16       0  4993.8     .07       0  4999.8     .16       0
  5133.2      .1       0
Bank Sta=4951.4,5069.3
XS Rating Curve= 0 ,0
Exp/Cntr=0.3,0.1

Type RM Length L Ch R = 1 ,24566   ,673,673,673
BEGIN DESCRIPTION:
WILLOW CREEK 39.0
END DESCRIPTION:
XS GIS Cut Line= 3
      2817865.49     10108187.01      2817173.42      10107379.6
       2816259.9     10106988.09
#Sta/Elev= 30
  4123.1 1644.14  4158.6 1643.76  4172.9 1644.79  4187.2 1642.77  4215.7 1641.53
  4314.5 1641.36  4371.6  1639.5    4421 1640.32  4706.7 1634.92  4754.6 1635.38
  4783.2 1633.45  4867.5 1632.79  4910.5 1633.17    4939 1631.64  4945.6 1629.26
  4953.3 1629.46  4959.9 1627.16  4993.1 1624.21  4995.8 1623.71  4999.1 1624.21
  5031.2 1624.57    5074 1630.03    5130 1629.62    5232  1633.2  5337.5 1633.96
  5442.9 1633.98  5510.5 1634.62  5670.7 1635.63    5844 1637.46  6180.4 1648.84
#Mann= 10 ,-1 , 0
  4123.1      .1       0  4706.7     .05       0  4867.5     .16       0
  4993.1     .07       0  4999.1     .16       0    5232      .1       0
  5337.5     .05       0  5442.9      .1       0  5510.5     .05       0
  5670.7      .1       0
Bank Sta=4939,5074
XS Rating Curve= 0 ,0
Exp/Cntr=0.3,0.1

Type RM Length L Ch R = 1 ,23893   ,488,488,488
BEGIN DESCRIPTION:
WILLOW CREEK 38.0
END DESCRIPTION:
XS GIS Cut Line= 3
      2818226.93     10108386.99      2817680.94     10106833.63
      2817211.84     10106126.13
#Sta/Elev= 30
  3647.6 1646.02  3884.2 1643.67  4018.3 1639.73  4085.6 1640.38    4128 1638.28
    4432 1634.91  4498.1 1635.99  4587.8 1634.49  4634.4 1634.39  4700.4 1633.42
  4795.8 1629.12  4944.2 1628.76    4976 1625.94  4994.2 1621.79    4997 1621.29
  5000.2 1621.79    5029 1622.19  5040.7 1625.04    5082  1629.1    5138 1630.25
  5287.9 1629.13  5526.4 1633.05  5592.6 1638.35  5641.9 1648.15  5664.8  1650.8
    5762 1655.57  5853.3 1656.85  5883.5 1657.02  6054.1 1658.71    6143  1660.1
#Mann= 12 ,-1 , 0
  3647.6      .1       0    4432     .05       0  4587.8      .1       0
  4634.4     .05       0  4994.2    .035       0  5000.2     .05       0
  5040.7      .1       0  5287.9     .16       0    5762      .1       0
  5853.3     .16       0  5883.5      .1       0  6054.1     .05       0
#XS Ineff= 2 , 0
         4497.99 1636.01
Permanent Ineff=
       F       F
Bank Sta=4944.2,5082
XS Rating Curve= 0 ,0
Exp/Cntr=0.3,0.1

Type RM Length L Ch R = 1 ,23405   ,431,431,431
BEGIN DESCRIPTION:
WILLOW CREEK 37.0
END DESCRIPTION:
XS GIS Cut Line= 3
      2818580.64     10108110.11      2818150.02     10106725.97
      2817650.19      10106110.8
#Sta/Elev= 30
  3752.9 1638.83  4126.1 1634.14  4425.2 1632.25  4751.3 1630.21  4888.5 1630.43
  4951.7 1629.31    4957 1628.83  4974.4 1623.48  4992.4 1620.77  4995.1 1620.27
  4998.4 1620.77  5059.8 1621.88  5087.1 1623.58  5119.7 1626.89  5164.7    1627
  5226.7 1627.69  5261.9  1629.1  5319.4  1627.1  5383.3 1626.67  5525.5 1629.05
  5589.5 1632.43  5624.6 1636.88  5688.6 1641.09  5707.1 1643.26  5723.8 1644.65
  5800.2 1644.47  5830.8 1643.24  5845.2 1643.62  5888.2 1646.21  5995.1  1650.2
#Mann= 8 ,-1 , 0
  3752.9      .1       0  4425.2     .05       0  4888.5      .1       0
  4992.4     .07       0  4998.4      .1       0  5164.7     .16       0
  5707.1      .1       0  5800.2     .16       0
Bank Sta=4951.7,5119.7
XS Rating Curve= 0 ,0
Exp/Cntr=0.3,0.1

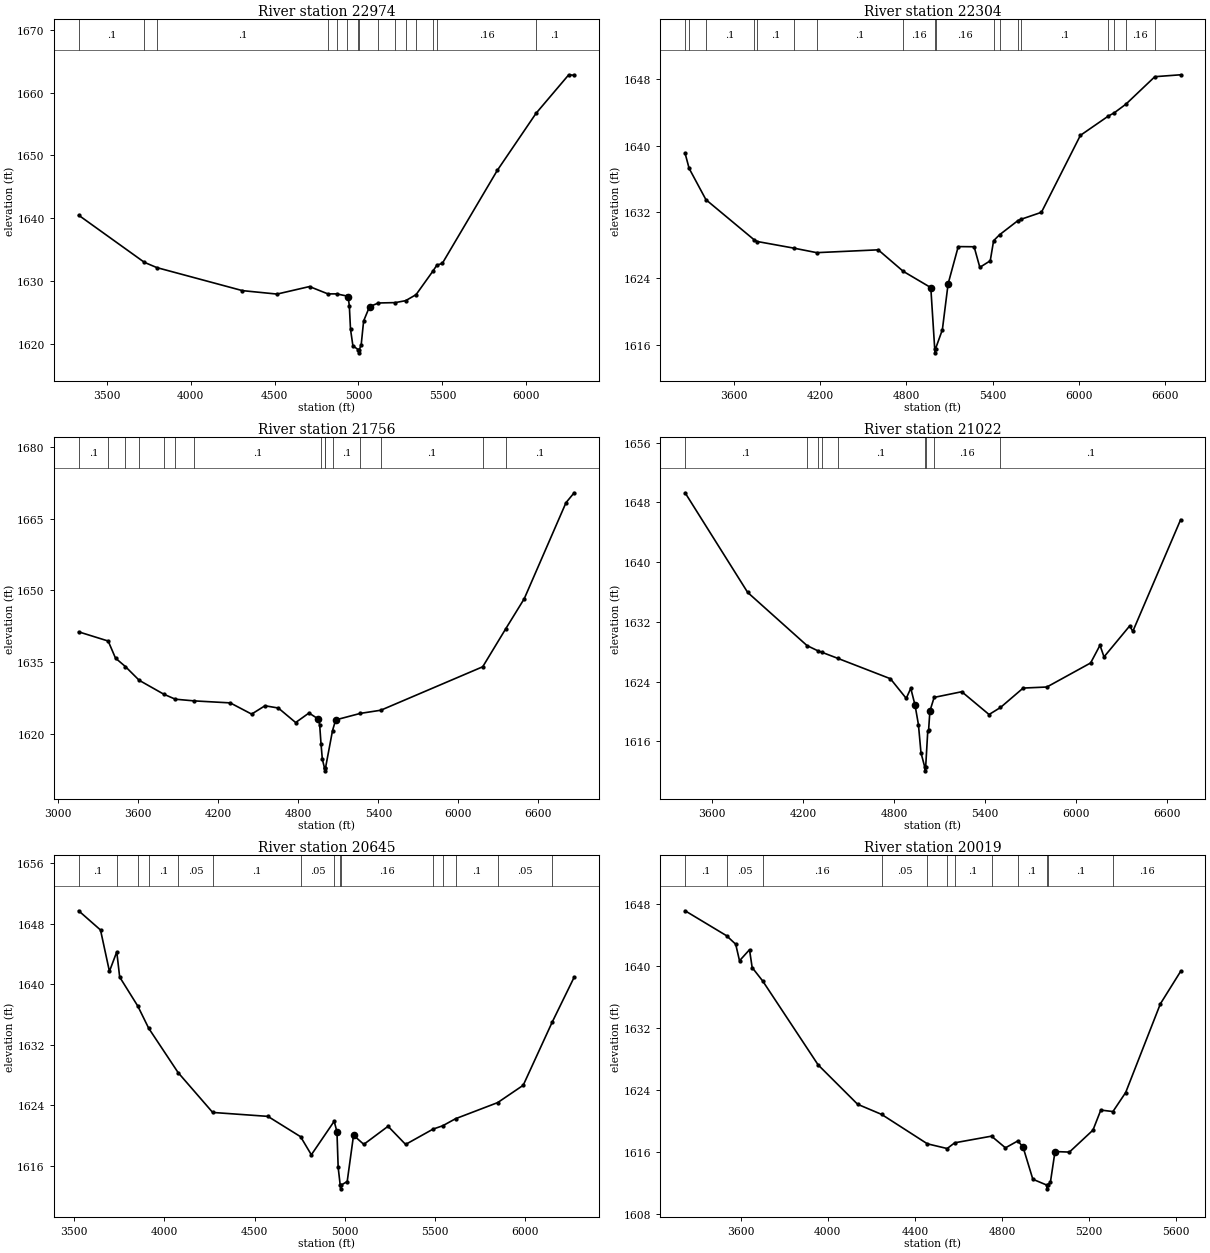
Type RM Length L Ch R = 1 ,22974   ,670,670,670
BEGIN DESCRIPTION:
WILLOW CREEK 36.0
END DESCRIPTION:
XS GIS Cut Line= 3
      2818828.19     10108143.93      2818541.74     10106654.35
      2817438.23     10105738.23
#Sta/Elev= 30
  3333.3 1640.47    3725 1632.95  3799.4 1632.11  4308.7 1628.44  4514.8 1627.89
  4708.2 1629.09  4817.9 1627.92  4870.3 1627.92  4930.6 1627.58  4938.1 1627.46
  4945.4 1626.04  4952.4 1622.29  4966.7 1619.64  4998.9 1619.02  5001.6 1618.52
  5004.9 1619.02  5016.2 1619.84  5030.5  1623.6  5065.7 1625.88  5118.6 1626.47
    5219 1626.53  5280.9 1626.84  5342.9  1627.8  5443.3 1631.56  5466.7  1632.5
  5499.3 1632.79  5826.2  1647.6  6057.5 1656.72    6252 1662.86  6284.4 1662.78
#Mann= 15 ,-1 , 0
  3333.3      .1       0    3725     .05       0  3799.4      .1       0
  4817.9     .16       0  4870.3      .1       0  4930.6     .16       0
  4998.9     .07       0  5004.9     .16       0  5118.6      .1       0
    5219     .16       0  5280.9      .1       0  5342.9     .16       0
  5443.3      .1       0  5466.7     .16       0  6057.5      .1       0
Bank Sta=4938.1,5065.7
XS Rating Curve= 0 ,0
Exp/Cntr=0.3,0.1

Type RM Length L Ch R = 1 ,22304   ,548,548,548
BEGIN DESCRIPTION:
WILLOW CREEK 35.0
END DESCRIPTION:
XS GIS Cut Line= 3
      2819046.94     10107935.61      2818869.86     10105847.06
      2817813.19     10105009.01
#Sta/Elev= 30
  3261.6 1639.08  3289.6 1637.26  3406.5 1633.49  3740.8 1628.67  3764.3 1628.45
  4018.9 1627.65  4176.6 1627.11    4604 1627.45    4778 1624.86  4969.6  1622.9
  4996.7 1615.54  4999.4 1615.04  5002.7 1615.54  5049.9 1617.82    5090 1623.36
  5160.3 1627.84  5270.7 1627.82  5310.4 1625.34  5382.8 1626.13  5406.2 1628.55
  5447.2 1629.26  5575.1 1630.97  5595.1 1631.12  5738.6 1631.97  6009.4 1641.24
  6204.1 1643.57  6244.3 1643.95  6325.9    1645    6527 1648.31  6706.3 1648.54
#Mann= 18 ,-1 , 0
  3261.6      .1       0  3289.6     .05       0  3406.5      .1       0
  3740.8     .05       0  3764.3      .1       0  4018.9     .05       0
  4176.6      .1       0    4778     .16       0  4996.7     .07       0
  5002.7     .16       0  5406.2     .16       0  5447.2      .1       0
  5575.1     .16       0  5595.1      .1       0  6204.1     .16       0
  6244.3      .1       0  6325.9     .16       0    6527      .1       0
Bank Sta=4969.6,5090
XS Rating Curve= 0 ,0
Exp/Cntr=0.3,0.1

Type RM Length L Ch R = 1 ,21756   ,734,734,734
BEGIN DESCRIPTION:
WILLOW CREEK 34.0
END DESCRIPTION:
XS GIS Cut Line= 3
      2819369.86     10108050.14      2819406.32     10105633.52
      2819078.24     10104378.48
#Sta/Elev= 30
  3153.4 1641.35  3374.8 1639.43  3429.8 1635.86  3503.6 1634.11  3607.5 1631.23
  3791.2 1628.34  3878.1 1627.29  4018.7 1626.94  4289.9 1626.52    4450 1624.18
    4550 1625.92    4650 1625.45    4780 1622.42    4880 1624.41    4950 1623.15
    4960 1621.95  4970.2 1617.92    4980 1614.77    4997 1612.84  4999.8 1612.34
    5003 1612.84  5056.4 1620.75    5080 1622.97    5265 1624.33  5418.3 1624.99
  6182.1 1634.06  6354.4 1641.98  6493.1 1648.25  6806.3 1668.31  6867.5 1670.37
#Mann= 15 ,-1 , 0
  3153.4      .1       0  3374.8     .05       0  3503.6      .1       0
  3607.5     .05       0  3791.2      .1       0  3878.1     .05       0
  4018.7      .1       0  4970.2     .16       0    4997     .07       0
    5003     .16       0  5056.4      .1       0    5265     .16       0
  5418.3      .1       0  6182.1     .05       0  6354.4      .1       0
Bank Sta=4950,5080
XS Rating Curve= 0 ,0
Exp/Cntr=0.3,0.1

Type RM Length L Ch R = 1 ,21022   ,377,377,377
BEGIN DESCRIPTION:
WILLOW CREEK 33.0
END DESCRIPTION:
XS GIS Cut Line= 3
       2820795.3     10107771.81      2820026.32     10106218.45
      2819649.77     10104727.65
#Sta/Elev= 30
  3420.9 1649.29    3834 1635.95  4225.5 1628.84    4301  1628.1  4325.1 1627.93
  4427.3 1627.14    4776  1624.4  4880.5 1621.77  4910.5 1623.12  4938.5 1620.88
    4961 1618.27  4977.8  1614.5  5002.8 1612.57  5005.6 1612.07  5008.8 1612.57
  5022.7  1617.4  5028.2 1617.52  5036.7 1620.07  5064.7  1621.9  5247.1 1622.66
  5427.2 1619.61  5502.7 1620.55  5652.4 1623.15  5808.8 1623.29  6097.6 1626.51
  6159.5 1628.88    6186 1627.32  6355.5 1631.47  6376.1 1630.74  6691.8 1645.69
#Mann= 9 ,-1 , 0
  3420.9      .1       0  4225.5     .16       0    4301      .1       0
  4325.1     .16       0  4427.3      .1       0  5002.8     .07       0
  5008.8      .1       0  5064.7     .16       0  5502.7      .1       0
Bank Sta=4938.5,5036.7
XS Rating Curve= 0 ,0
Exp/Cntr=0.3,0.1

Type RM Length L Ch R = 1 ,20645   ,626,626,626
BEGIN DESCRIPTION:
WILLOW CREEK 32.0
END DESCRIPTION:
XS GIS Cut Line= 3
      2821387.41     10107225.82      2820203.18     10105926.24
      2820141.66     10104941.97
#Sta/Elev= 30
  3525.5 1649.71  3646.7 1647.17  3696.1  1641.7  3736.7 1644.28  3752.8 1640.95
  3853.2 1637.11  3913.5 1634.18  4076.7 1628.31  4267.9 1623.05  4573.7 1622.53
  4754.8 1619.84  4814.3 1617.45  4940.7 1621.88  4956.1 1620.51  4962.9 1615.78
  4974.1 1613.45  4976.8 1612.95  4980.1 1613.45  5012.9 1613.92    5048 1620.03
  5104.8 1618.83  5239.2 1621.22  5336.3 1618.82  5488.7 1620.85  5542.1 1621.29
  5612.9 1622.22  5846.2 1624.35  5987.6 1626.64  6148.8 1635.02  6269.9 1640.93
#Mann= 15 ,-1 , 0
  3525.5      .1       0  3736.7     .05       0  3853.2     .16       0
  3913.5      .1       0  4076.7     .05       0  4267.9      .1       0
  4754.8     .05       0  4940.7     .16       0  4974.1     .07       0
  4980.1     .16       0  5488.7      .1       0  5542.1     .16       0
  5612.9      .1       0  5846.2     .05       0  6148.8      .1       0
Bank Sta=4956.1,5048
XS Rating Curve= 0 ,0
Exp/Cntr=0.3,0.1

Type RM Length L Ch R = 1 ,20019   ,753,753,753
BEGIN DESCRIPTION:
WILLOW CREEK 31.0
END DESCRIPTION:
XS GIS Cut Line= 3
       2821548.9     10107233.52      2820887.57     10105795.51
      2820503.26     10105219.06
#Sta/Elev= 30
  3344.7 1647.17  3534.9 1643.95  3577.1 1642.85  3594.6 1640.71  3640.5 1642.14
  3652.7 1639.83  3701.2 1638.09  3955.7 1627.25    4137 1622.16  4247.2 1620.85
  4457.2 1617.05  4548.1 1616.44  4582.8 1617.18  4751.8 1618.04  4815.8 1616.53
  4872.4 1617.42  4896.4 1616.65  4941.6 1612.47  5004.4 1611.73  5007.1 1611.23
  5010.4 1611.73  5022.4 1612.11  5043.4 1616.05  5109.5 1615.98  5217.7 1618.82
  5253.7 1621.41  5309.4 1621.22  5367.9 1623.68  5527.2 1635.14  5620.3 1639.34
#Mann= 12 ,-1 , 0
  3344.7      .1       0  3534.9     .05       0  3701.2     .16       0
  4247.2     .05       0  4457.2      .1       0  4548.1     .05       0
  4582.8      .1       0  4751.8     .16       0  4872.4      .1       0
  5004.4     .07       0  5010.4      .1       0  5309.4     .16       0
Bank Sta=4896.4,5043.4
XS Rating Curve= 0 ,0
Exp/Cntr=0.3,0.1

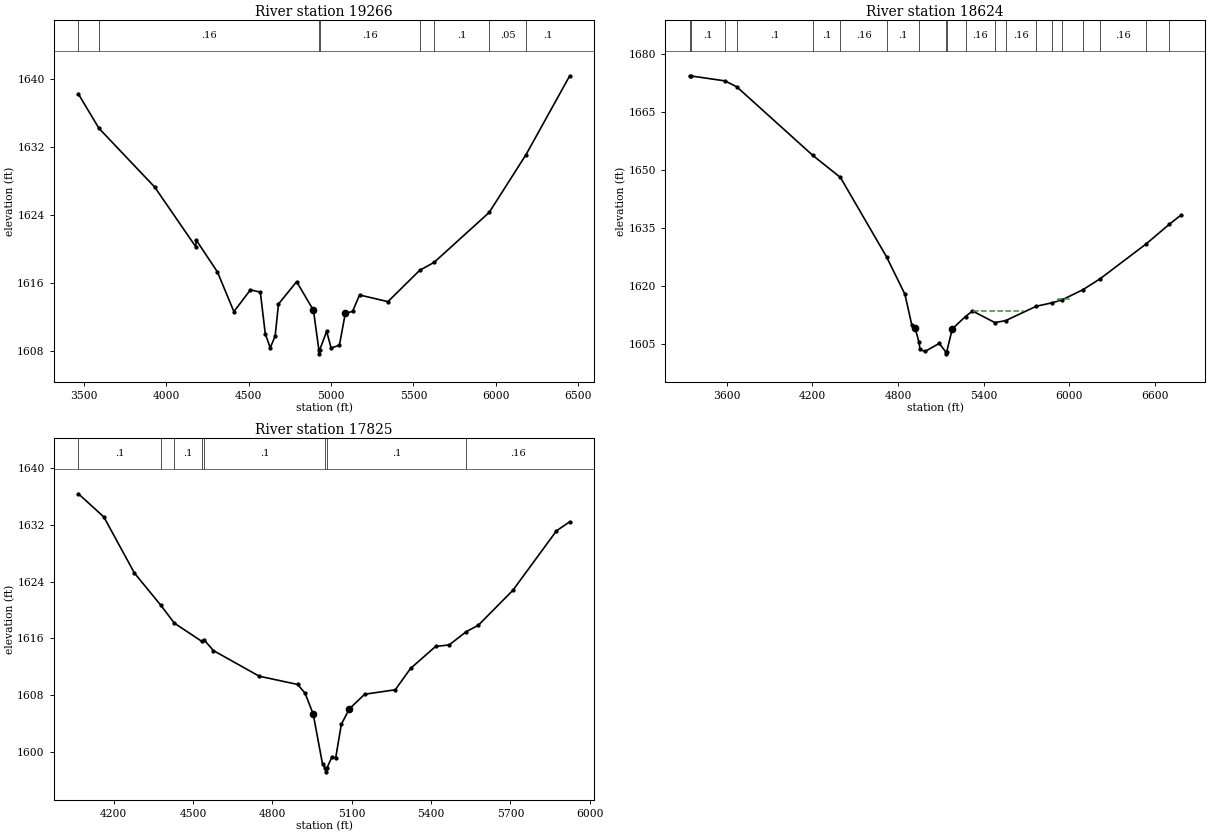
Type RM Length L Ch R = 1 ,19266   ,642,642,642
BEGIN DESCRIPTION:
WILLOW CREEK 30.0
END DESCRIPTION:
XS GIS Cut Line= 3
      2821651.11     10106946.06      2821578.19     10105565.81
      2820656.39     10104258.62
#Sta/Elev= 30
  3467.1 1638.27  3591.6 1634.24  3930.1 1627.32  4178.1 1620.33  4183.1 1621.06
  4310.6 1617.34  4410.7 1612.67  4510.9 1615.23    4571 1614.96    4601 1610.07
  4631.1 1608.41  4661.1 1609.79  4681.1 1613.56  4791.3 1616.19  4893.4 1612.83
  4926.1  1608.2  4928.9  1607.7  4932.1  1608.2  4973.5 1610.35  5000.5 1608.39
    5051 1608.71  5086.7 1612.47  5131.1 1612.69  5172.9 1614.63  5345.4 1613.84
  5538.2 1617.53  5625.5 1618.46  5959.9 1624.34  6183.7 1631.15  6448.8 1640.42
#Mann= 8 ,-1 , 0
  3467.1     .05       0  3591.6     .16       0  4926.1     .07       0
  4932.1     .16       0  5538.2     .05       0  5625.5      .1       0
  5959.9     .05       0  6183.7      .1       0
Bank Sta=4893.4,5086.7
XS Rating Curve= 0 ,0
Exp/Cntr=0.3,0.1

Type RM Length L Ch R = 1 ,18624   ,799,799,799
BEGIN DESCRIPTION:
WILLOW CREEK 28.0
END DESCRIPTION:
XS GIS Cut Line= 3
      2823177.16      10106617.9      2821796.94     10105169.98
      2820979.23     10103982.46
#Sta/Elev= 30
  3339.1 1674.34  3351.5 1674.28  3588.4 1673.01  3670.6 1671.47  4203.4  1653.7
  4396.2 1648.02  4719.2 1627.47  4847.8 1617.79  4897.2 1609.68  4918.6 1609.09
    4947 1605.34  4953.8 1603.48    4989 1602.94  5088.1 1605.03  5134.8 1602.83
  5137.5 1602.33  5140.8 1602.83  5180.3 1608.82  5272.6 1611.99  5321.5 1613.43
  5479.1 1610.41  5554.4 1610.94  5767.9 1614.65  5881.9 1615.57  5946.9 1616.28
  6094.2 1618.91  6217.2 1621.81  6536.9 1630.76  6700.6 1635.89  6781.3 1638.23
#Mann= 20 ,-1 , 0
  3339.1     .16       0  3351.5      .1       0  3588.4     .16       0
  3670.6      .1       0  4203.4      .1       0  4396.2     .16       0
  4719.2      .1       0    4947     .05       0  5134.8    .035       0
  5140.8     .05       0  5272.6     .16       0  5479.1     .05       0
  5554.4     .16       0  5767.9     .05       0  5881.9      .1       0
  5946.9     .05       0  6094.2     .16       0  6217.2     .16       0
  6536.9     .05       0  6700.6      .1       0
#XS Ineff= 2 ,-1
 5325.64 5675.49 1613.33 5917.92 6009.57 1616.46
Permanent Ineff=
       F       F
Bank Sta=4918.6,5180.3
XS Rating Curve= 0 ,0
Exp/Cntr=0.3,0.1

Type RM Length L Ch R = 1 ,17825   ,695,695,695
BEGIN DESCRIPTION:
WILLOW CREEK 27.0
END DESCRIPTION:
XS GIS Cut Line= 2
       2822971.5     10105141.89        2821396.     10104158.17
#Sta/Elev= 30
  4066.7  1636.4  4162.9 1633.13  4278.5 1625.22    4378 1620.69  4429.4 1618.16
  4532.4 1615.61  4542.7 1615.77  4576.9  1614.3  4750.3 1610.68  4895.5 1609.52
  4923.7 1608.27  4954.3 1605.34  4989.8 1598.24  4999.7  1597.7  5002.4  1597.2
  5005.7  1597.7  5025.2  1599.3  5039.3 1599.17  5060.6  1603.9  5091.2 1606.09
  5148.9 1608.14  5264.5 1608.77  5322.3 1611.78  5416.7 1614.87  5468.6  1615.1
  5532.9 1616.96  5578.3 1617.86    5709 1622.79    5874 1631.18  5924.1 1632.46
#Mann= 8 ,-1 , 0
  4066.7      .1       0    4378     .16       0  4429.4      .1       0
  4532.4     .16       0  4542.7      .1       0  4999.7     .07       0
  5005.7      .1       0  5532.9     .16       0
Bank Sta=4954.3,5091.2
XS Rating Curve= 0 ,0
Exp/Cntr=0.3,0.1