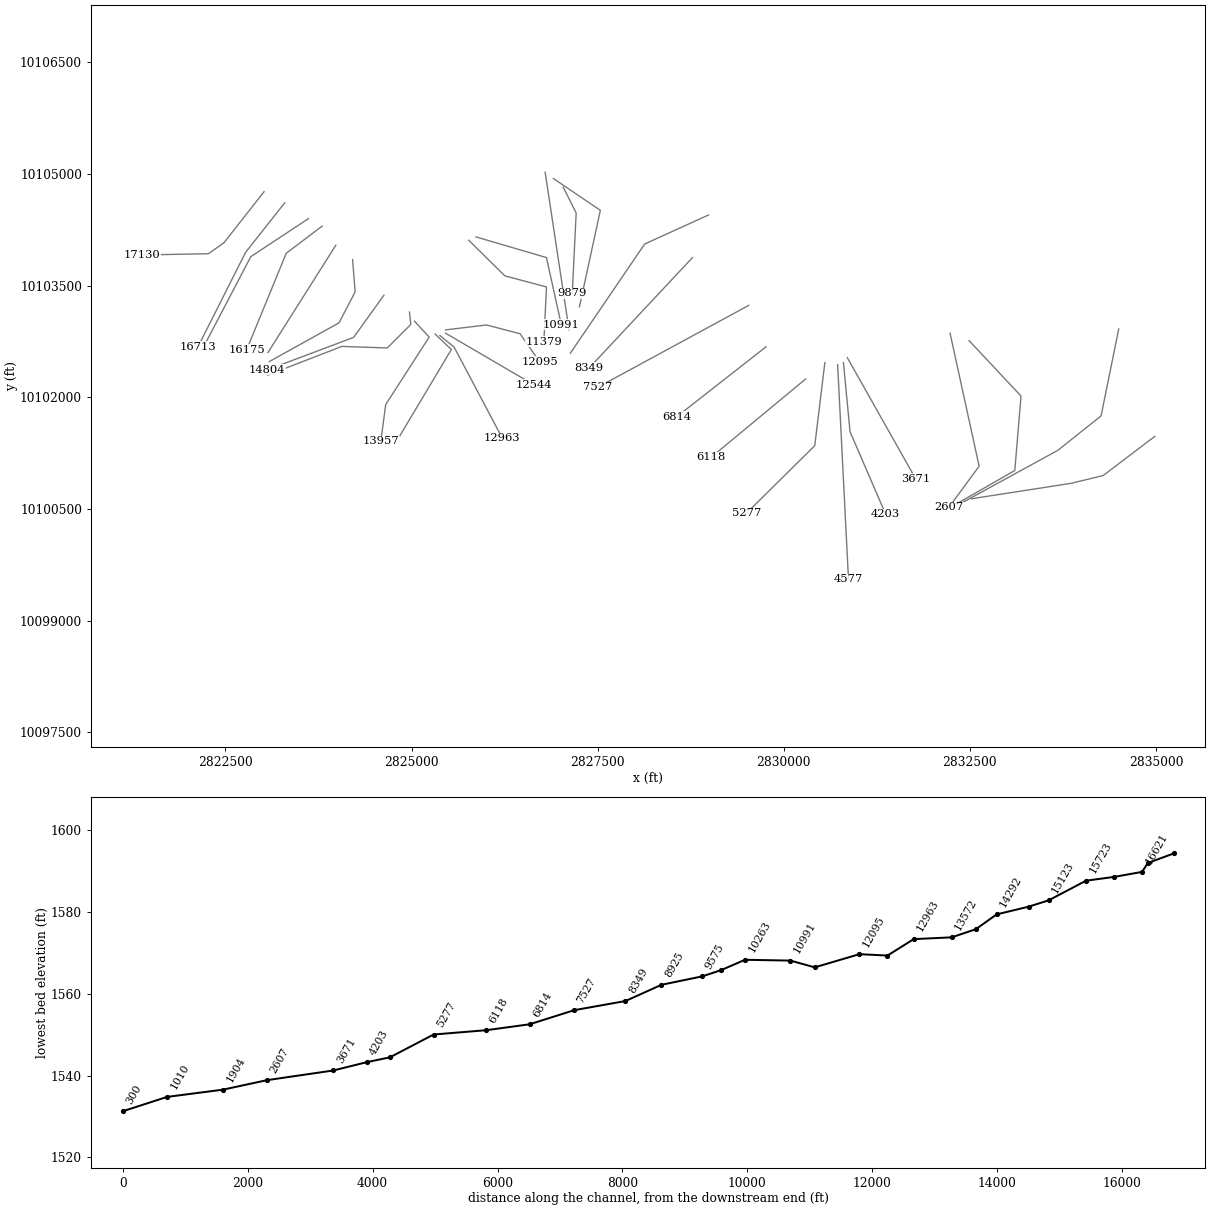
HEC-RAS study WILLOW CREEK.prj: WILLOW CREEK Base Level Engineering

--- WILLOW CREEK.g01 (geometry) --- (continued)

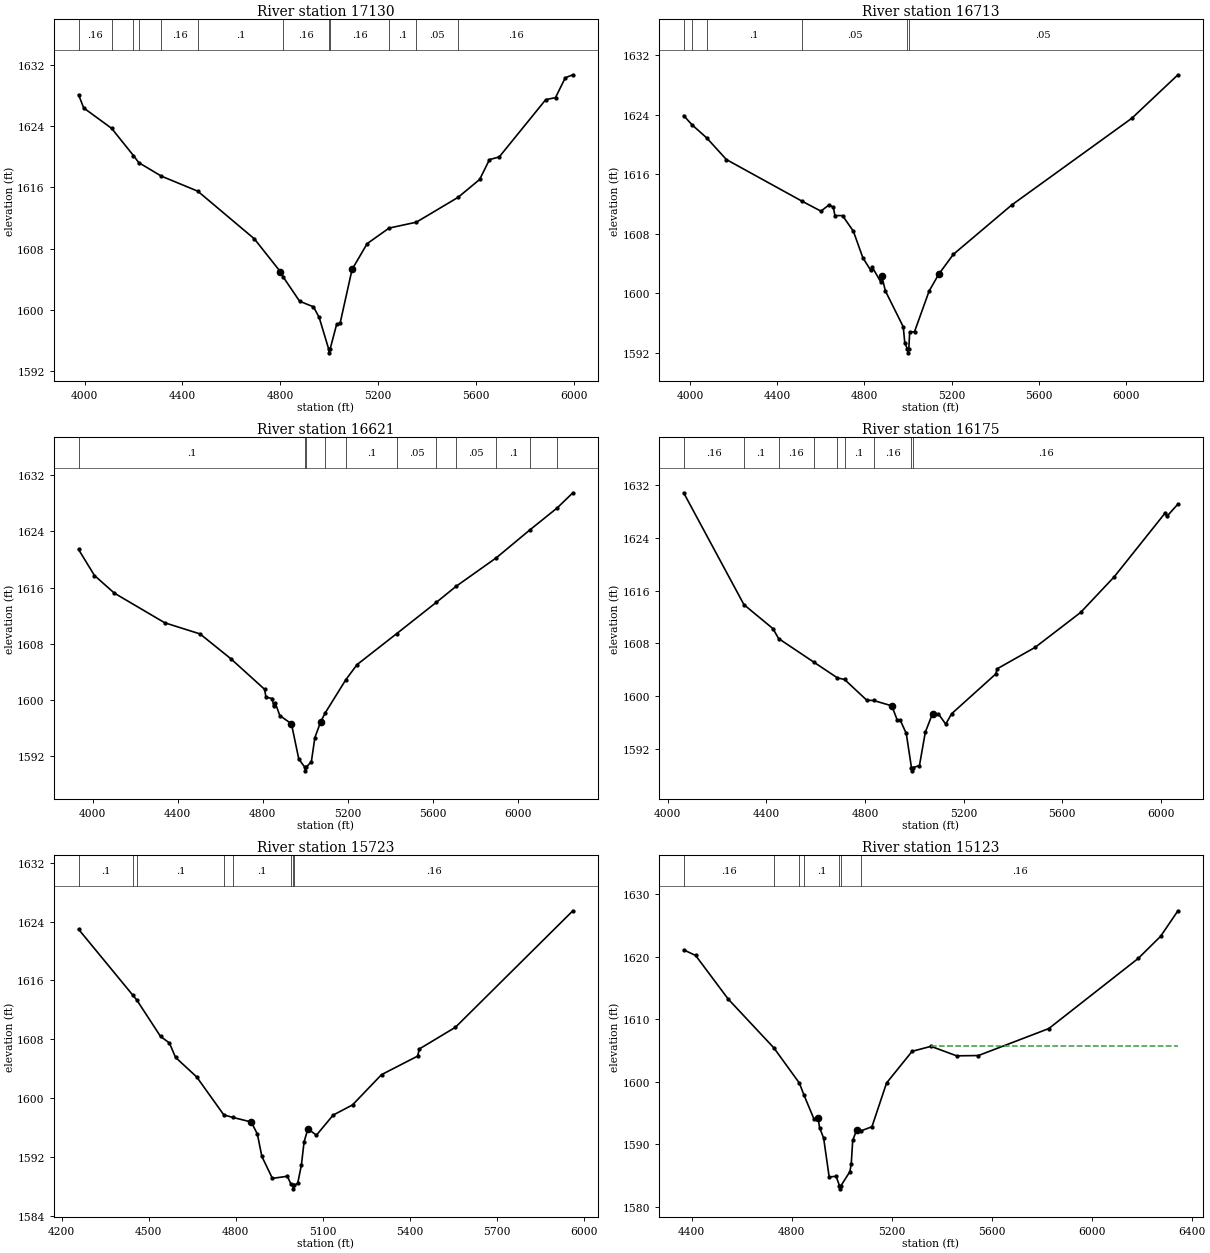
Type RM Length L Ch R = 1 ,17130   ,417,417,417
BEGIN DESCRIPTION:
WILLOW CREEK 26.0
END DESCRIPTION:
XS GIS Cut Line= 4
      2823018.07     10104762.93       2822479.9      10104077.2
      2822271.57     10103929.63      2821377.44     10103912.27
#Sta/Elev= 30
  3975.1 1628.09    3996 1626.36  4110.4 1623.69  4199.5 1620.14  4221.5 1619.21
    4314 1617.45  4462.5 1615.49  4693.8 1609.27  4800.4 1604.97  4810.7 1604.34
    4879 1601.12  4935.6 1600.39  4958.8 1599.02  4997.8 1594.88  5000.5 1594.38
  5003.8 1594.88  5030.4  1598.1  5044.6 1598.25  5093.6 1605.28  5155.2 1608.64
  5244.8 1610.67  5356.4 1611.44  5527.2 1614.69  5615.3 1617.02  5655.3 1619.61
  5695.3 1619.96  5885.4 1627.44  5925.4 1627.71  5965.4  1630.3  5996.4 1630.69
#Mann= 12 ,-1 , 0
  3975.1     .16       0  4110.4      .1       0  4199.5     .16       0
  4221.5      .1       0    4314     .16       0  4462.5      .1       0
  4810.7     .16       0  4997.8     .07       0  5003.8     .16       0
  5244.8      .1       0  5356.4     .05       0  5527.2     .16       0
Bank Sta=4800.4,5093.6
XS Rating Curve= 0 ,0
Exp/Cntr=0.3,0.1

Type RM Length L Ch R = 1 ,16713   ,92,92,92
BEGIN DESCRIPTION:
WILLOW CREEK 25.0
END DESCRIPTION:
XS GIS Cut Line= 3
      2823295.22     10104612.69       2822770.9     10103949.49
      2822129.43     10102676.95
#Sta/Elev= 30
  3969.4 1623.86  4007.1 1622.64  4074.8 1620.88  4165.7 1617.96  4512.3 1612.39
  4600.1 1611.04  4635.3 1611.84  4656.4 1611.61  4664.2 1610.45  4699.4 1610.44
  4749.1 1608.34  4792.4  1604.8  4829.1 1603.09  4834.7 1603.58  4873.7  1601.6
  4879.3 1602.33    4896 1600.34  4978.1 1595.53  4985.3 1593.33  4997.5 1592.54
  5000.2 1592.04  5003.5 1592.54  5007.6  1594.8  5029.9 1594.88  5096.8 1600.32
  5141.4  1602.6  5208.3 1605.25    5476 1611.86  6028.1  1623.5  6239.9 1629.33
#Mann= 6 ,-1 , 0
  3969.4      .1       0  4007.1     .16       0  4074.8      .1       0
  4512.3     .05       0  4997.5     .04       0  5003.5     .05       0
Bank Sta=4879.3,5141.4
XS Rating Curve= 0 ,0
Exp/Cntr=0.3,0.1

Type RM Length L Ch R = 1 ,16621   ,446,446,446
BEGIN DESCRIPTION:
Mapping XS 0ccc6c8c
END DESCRIPTION:
XS GIS Cut Line= 3
      2823614.64     10104400.87      2822840.35     10103890.46
      2822191.06      10102650.9
#Sta/Elev= 30
  3933.1 1621.43    4008 1617.72  4101.3 1615.21  4339.2 1610.97  4504.8 1609.39
  4649.4 1605.86    4809 1601.48    4815 1600.36  4845.1 1600.17  4851.1 1599.05
  4858.6 1599.58  4880.2 1597.75  4935.1 1596.57  4969.7 1591.55  4998.3 1590.36
    5001 1589.86  5004.3 1590.36    5029 1591.18  5045.4  1594.6  5073.1 1596.89
  5094.4 1598.14  5191.4 1602.87    5244 1605.01    5431 1609.44  5617.5  1613.9
  5710.3 1616.18  5900.1 1620.26  6059.3 1624.27  6185.3 1627.34  6259.8 1629.52
#Mann= 11 ,-1 , 0
  3933.1      .1       0  4998.3     .07       0  5004.3      .1       0
  5094.4     .05       0  5191.4      .1       0    5431     .05       0
  5617.5      .1       0  5710.3     .05       0  5900.1      .1       0
  6059.3     .05       0  6185.3      .1       0
Bank Sta=4935.1,5073.1
XS Rating Curve= 0 ,0
Exp/Cntr=0.3,0.1

Type RM Length L Ch R = 1 ,16175   ,452,452,452
BEGIN DESCRIPTION:
WILLOW CREEK 24.0
END DESCRIPTION:
XS GIS Cut Line= 3
      2823798.66     10104300.17      2823316.04      10103935.6
      2822784.79     10102640.46
#Sta/Elev= 30
  4064.2 1630.85  4308.8 1613.86  4426.6 1610.22  4449.2 1608.72  4590.9 1605.17
  4687.9 1602.75  4716.7 1602.51  4806.9 1599.36  4834.4 1599.32  4908.2 1598.51
  4930.5 1596.34    4943 1596.29    4967 1594.32    4988 1589.14  4990.7 1588.64
    4994 1589.14  5020.4 1589.43  5044.3 1594.51  5073.7 1597.34  5097.7 1597.27
  5127.1 1595.73  5151.1 1597.31  5329.8 1603.34  5335.2 1604.12  5489.9 1607.39
    5674 1612.68  5810.1 1618.08  6018.2 1627.84  6023.6 1627.25  6068.9 1629.14
#Mann= 9 ,-1 , 0
  4064.2     .16       0  4308.8      .1       0  4449.2     .16       0
  4590.9      .1       0  4687.9     .16       0  4716.7      .1       0
  4834.4     .16       0    4988     .07       0    4994     .16       0
Bank Sta=4908.2,5073.7
XS Rating Curve= 0 ,0
Exp/Cntr=0.3,0.1

Type RM Length L Ch R = 1 ,15723   ,600,600,600
BEGIN DESCRIPTION:
WILLOW CREEK 23.0
END DESCRIPTION:
XS GIS Cut Line= 2
      2823981.66     10104042.52      2823070.17      10102601.5
#Sta/Elev= 30
    4258 1622.96  4444.2 1614.05  4458.8 1613.35  4540.8  1608.4  4571.4 1607.51
  4592.6 1605.55  4665.5  1602.9  4759.3 1597.73  4790.4  1597.4  4853.7 1596.78
  4874.9 1595.13  4890.1 1592.12  4926.6 1589.12  4978.3 1589.41  4990.8 1588.32
  4996.5  1588.2  4999.2  1587.7  5002.5  1588.2  5013.8 1588.44  5026.6 1590.92
    5036  1594.1  5049.3 1595.87  5078.3 1594.98    5136 1597.71    5203  1599.1
    5303 1603.21  5427.6 1605.73  5433.5  1606.7  5558.1 1609.65  5963.1 1625.47
#Mann= 8 ,-1 , 0
    4258      .1       0  4444.2     .16       0  4458.8      .1       0
  4759.3     .16       0  4790.4      .1       0  4990.8     .16       0
  4996.5     .07       0  5002.5     .16       0
Bank Sta=4853.7,5049.3
XS Rating Curve= 0 ,0
Exp/Cntr=0.3,0.1

Type RM Length L Ch R = 1 ,15123   ,319,319,319
BEGIN DESCRIPTION:
WILLOW CREEK 22.0
END DESCRIPTION:
XS GIS Cut Line= 4
      2824207.33      10103851.5      2824242.06     10103417.48
      2824025.04     10103000.81      2823087.51     10102479.96
#Sta/Elev= 30
  4367.4 1621.13  4415.3 1620.23  4545.7 1613.25  4728.4 1605.44  4830.4 1599.81
  4849.4 1597.83    4889 1594.04  4905.4 1594.21  4911.1  1592.7  4927.5    1591
  4949.6 1584.79  4977.4  1584.9  4990.8 1583.39  4993.6 1582.89  4996.8 1583.39
  5032.4 1585.64    5038 1586.93  5043.8 1590.66  5060.1 1592.34  5078.6 1592.19
  5120.8 1592.83  5179.1 1599.82  5281.4 1604.89  5356.9 1605.69  5459.8 1604.17
  5546.8 1604.22  5828.2 1608.53  6186.2 1619.76  6275.4 1623.28  6345.1 1627.38
#Mann= 7 ,-1 , 0
  4367.4     .16       0  4728.4      .1       0  4830.4     .16       0
  4849.4      .1       0  4990.8     .07       0  4996.8      .1       0
  5078.6     .16       0
#XS Ineff= 2 , 0
                          5355.8         1605.72
Permanent Ineff=
       F       F
Bank Sta=4905.4,5060.1
XS Rating Curve= 0 ,0
Exp/Cntr=0.3,0.1

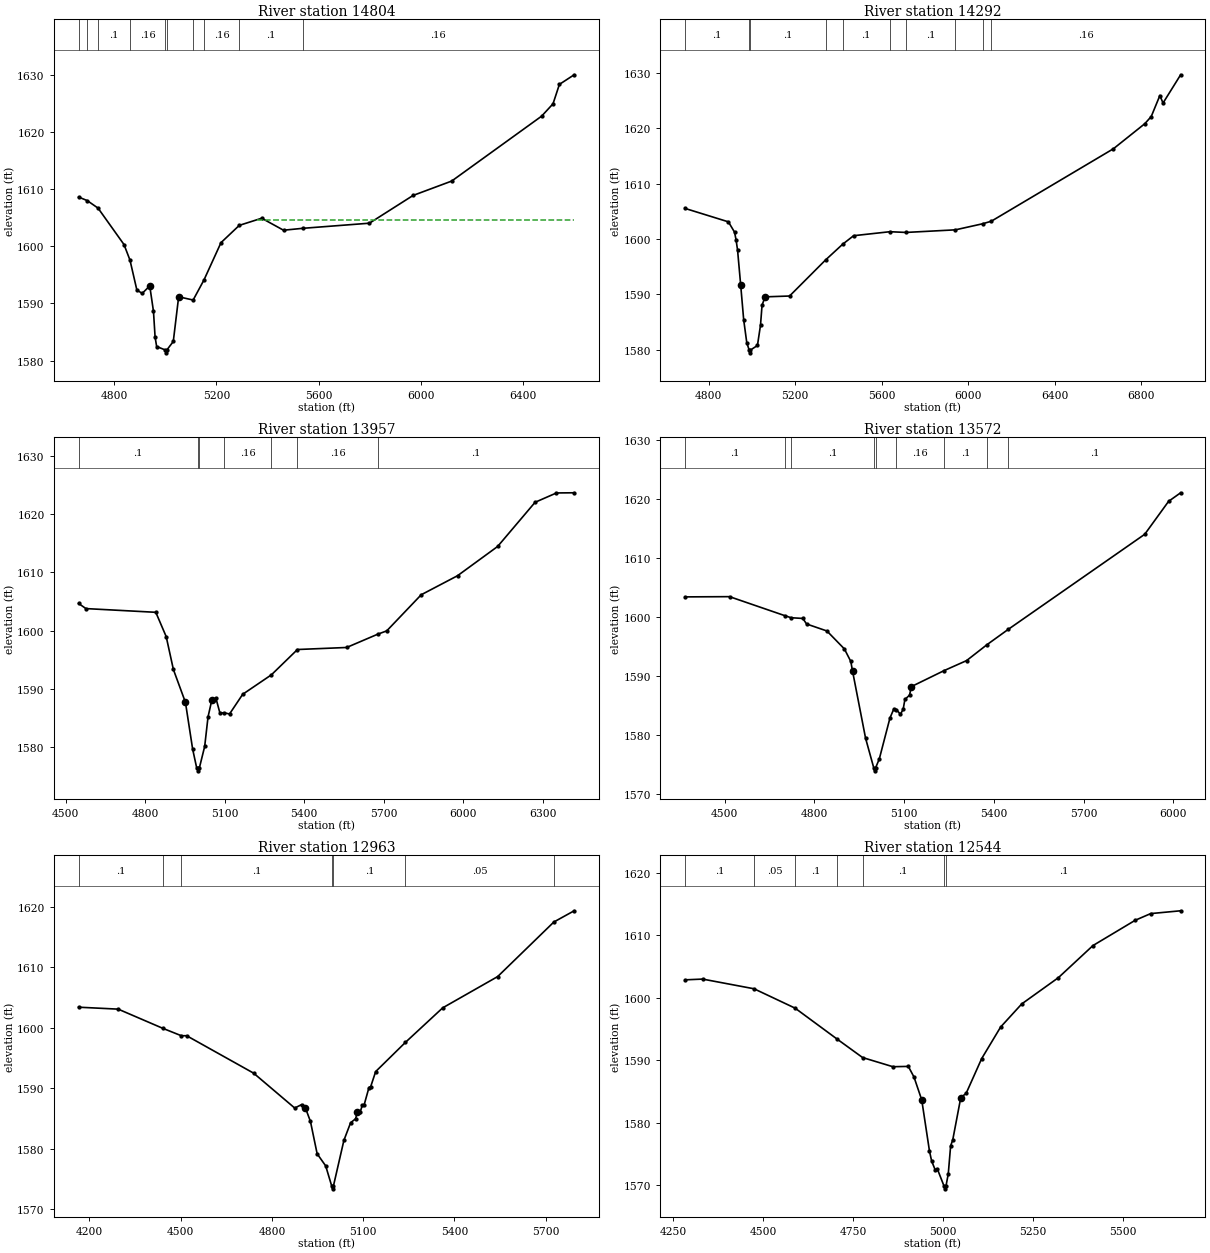
Type RM Length L Ch R = 1 ,14804   ,512,512,512
BEGIN DESCRIPTION:
WILLOW CREEK 21.0
END DESCRIPTION:
XS GIS Cut Line= 3
       2824627.9     10103371.61      2824221.65     10102805.65
      2823059.23     10102368.44
#Sta/Elev= 30
    4661 1608.64  4694.6 1608.02    4737  1606.7  4838.5 1600.32  4861.9 1597.59
  4888.8 1592.36  4909.7 1591.76  4939.2 1593.08  4953.8 1588.62  4960.1 1584.12
  4966.2 1582.46  5000.1 1581.85  5002.8 1581.35  5006.1 1581.85  5031.3 1583.34
  5052.3 1591.17    5109  1590.6  5151.6 1594.14  5217.9 1600.65  5289.5 1603.68
  5377.2 1604.93  5462.6 1602.83    5537 1603.16  5798.6 1604.06  5969.3 1608.92
  6120.4 1611.44  6472.2 1622.81  6516.9 1624.98  6541.8 1628.38  6599.6 1630.06
#Mann= 10 ,-1 , 0
    4661      .1       0  4694.6     .05       0    4737      .1       0
  4861.9     .16       0  5000.1     .07       0  5006.1     .16       0
    5109      .1       0  5151.6     .16       0  5289.5      .1       0
    5537     .16       0
#XS Ineff= 2 , 0
                         5360.04         1604.69
Permanent Ineff=
       F       F
Bank Sta=4939.2,5052.3
XS Rating Curve= 0 ,0
Exp/Cntr=0.3,0.1

Type RM Length L Ch R = 1 ,14292   ,335,335,335
BEGIN DESCRIPTION:
Mapping XS 6a8e70c6
END DESCRIPTION:
XS GIS Cut Line= 5
      2824971.65     10103145.98      2824989.02     10102979.26
      2824673.04     10102663.29      2824061.93     10102684.13
      2823068.93     10102298.73
#Sta/Elev= 30
    4691 1605.51  4891.2 1603.09  4919.5 1601.24  4926.6 1599.86  4933.6 1597.99
  4947.8 1591.78  4961.9 1585.41  4976.1 1581.31  4987.2 1579.96  4989.9 1579.46
  4993.2 1579.96  5025.5 1580.79  5039.7 1584.47  5046.8 1588.06  5060.9 1589.56
    5174 1589.71  5340.9 1596.23  5419.4 1599.05  5470.1 1600.59  5637.6 1601.31
  5712.5 1601.18  5940.9 1601.65  6066.3 1602.74  6106.6  1603.2  6671.5 1616.28
  6816.3 1620.79  6846.2 1622.09  6886.1 1625.88  6900.7 1624.52  6982.1 1629.62
#Mann= 10 ,-1 , 0
    4691      .1       0  4987.2     .07       0  4993.2      .1       0
  5340.9     .16       0  5419.4      .1       0  5637.6     .16       0
  5712.5      .1       0  5940.9     .16       0  6066.3      .1       0
  6106.6     .16       0
Bank Sta=4947.8,5060.9
XS Rating Curve= 0 ,0
Exp/Cntr=0.3,0.1

Type RM Length L Ch R = 1 ,13957   ,385,385,385
BEGIN DESCRIPTION:
WILLOW CREEK 20.0
END DESCRIPTION:
XS GIS Cut Line= 4
      2825038.72     10103023.15      2825236.23     10102809.36
      2824652.21     10101902.88      2824586.39     10101407.52
#Sta/Elev= 30
  4549.1 1604.66  4576.6 1603.78  4840.2 1603.14  4879.4 1598.95  4906.5 1593.29
    4952 1587.62  4979.1 1579.58  4994.3 1576.36  4998.5 1576.33  5001.2 1575.83
  5004.5 1576.33  5024.6 1580.05  5037.2 1585.13  5051.7 1588.06  5066.9 1588.35
  5082.1 1585.78  5096.6 1585.83  5118.4 1585.63    5168 1589.02  5276.2 1592.37
  5374.5 1596.73    5560 1597.08  5677.3 1599.37  5711.2 1599.94  5841.2 1606.16
  5978.2 1609.44  6129.5 1614.48  6270.7 1622.09  6351.4  1623.7  6418.2 1623.73
#Mann= 7 ,-1 , 0
  4549.1      .1       0  4998.5     .07       0  5004.5      .1       0
  5096.6     .16       0  5276.2      .1       0  5374.5     .16       0
  5677.3      .1       0
Bank Sta=4952,5051.7
XS Rating Curve= 0 ,0
Exp/Cntr=0.3,0.1

Type RM Length L Ch R = 1 ,13572   ,609,609,609
BEGIN DESCRIPTION:
WILLOW CREEK 19.0
END DESCRIPTION:
XS GIS Cut Line= 3
      2825315.43     10102850.76      2825534.15     10102642.46
      2824839.69     10101479.23
#Sta/Elev= 30
  4367.6 1603.39  4516.2 1603.43  4701.2  1600.2  4722.1 1599.85  4761.3 1599.73
  4773.7 1598.79  4841.8  1597.6  4900.2 1594.55  4921.6 1592.43  4927.4  1590.8
    4971 1579.39  4998.4 1574.35  5001.1 1573.85  5004.4 1574.35  5016.9 1575.87
  5052.5 1582.82  5065.6 1584.37  5074.3 1584.25  5087.4 1583.44  5096.7 1584.31
  5102.5 1585.97  5118.1 1586.71  5123.9 1588.15  5233.5 1590.87  5308.7 1592.57
  5377.1 1595.28  5447.6 1597.86  5904.3 1614.02  5984.2 1619.62  6024.4 1621.07
#Mann= 9 ,-1 , 0
  4367.6      .1       0  4701.2     .05       0  4722.1      .1       0
  4998.4     .07       0  5004.4      .1       0  5074.3     .16       0
  5233.5      .1       0  5377.1     .16       0  5447.6      .1       0
Bank Sta=4927.4,5123.9
XS Rating Curve= 0 ,0
Exp/Cntr=0.3,0.1

Type RM Length L Ch R = 1 ,12963   ,419,419,419
BEGIN DESCRIPTION:
WILLOW CREEK 18.0
END DESCRIPTION:
XS GIS Cut Line= 3
       2825381.4     10102829.94      2825572.35     10102673.71
      2826218.19     10101451.47
#Sta/Elev= 30
  4164.7  1603.4  4294.8 1603.08  4440.6 1599.93  4502.3 1598.69  4519.8 1598.69
    4740 1592.51  4875.1 1586.75  4897.7 1587.32  4910.4 1586.75  4926.8 1584.54
  4948.8  1579.2  4976.9  1577.2  4996.5 1573.91  4999.3 1573.41  5002.5 1573.91
  5036.8 1581.42  5058.8 1584.32  5075.2 1584.98  5080.9 1586.08    5090 1586.03
  5097.2  1587.2  5102.9  1587.2  5119.2 1590.14  5124.9 1590.29  5141.2 1592.77
  5239.2  1597.6  5361.5 1603.29  5542.4 1608.46  5727.1 1617.47  5793.8 1619.32
#Mann= 7 ,-1 , 0
  4164.7      .1       0  4440.6     .05       0  4502.3      .1       0
  4996.5     .07       0  5002.5      .1       0  5239.2     .05       0
  5727.1      .1       0
Bank Sta=4910.4,5080.9
XS Rating Curve= 0 ,0
Exp/Cntr=0.3,0.1

Type RM Length L Ch R = 1 ,12544   ,449,449,449
BEGIN DESCRIPTION:
WILLOW CREEK 17.0
END DESCRIPTION:
XS GIS Cut Line= 2
       2825457.8     10102861.19      2826645.26     10102166.77
#Sta/Elev= 30
  4283.9 1602.83  4332.6 1602.95  4475.3  1601.4  4589.3  1598.3  4706.6 1593.32
  4776.5  1590.4  4860.7 1588.93  4903.6 1588.98  4919.3 1587.28  4940.8 1583.62
  4962.3 1575.43  4968.2 1573.86    4978 1572.44  4983.8 1572.62  5002.3 1569.89
    5005 1569.39  5008.3 1569.89  5014.5 1571.81    5021 1576.27  5026.8  1577.2
  5049.2    1584    5064 1584.66  5107.2 1590.23  5159.8 1595.28  5218.5 1598.98
  5320.2 1603.18    5416 1608.31  5533.4 1612.36  5576.4 1613.43  5659.5 1613.88
#Mann= 7 ,-1 , 0
  4283.9      .1       0  4475.3     .05       0  4589.3      .1       0
  4706.6     .05       0  4776.5      .1       0  5002.3     .07       0
  5008.3      .1       0
Bank Sta=4940.8,5049.2
XS Rating Curve= 0 ,0
Exp/Cntr=0.3,0.1

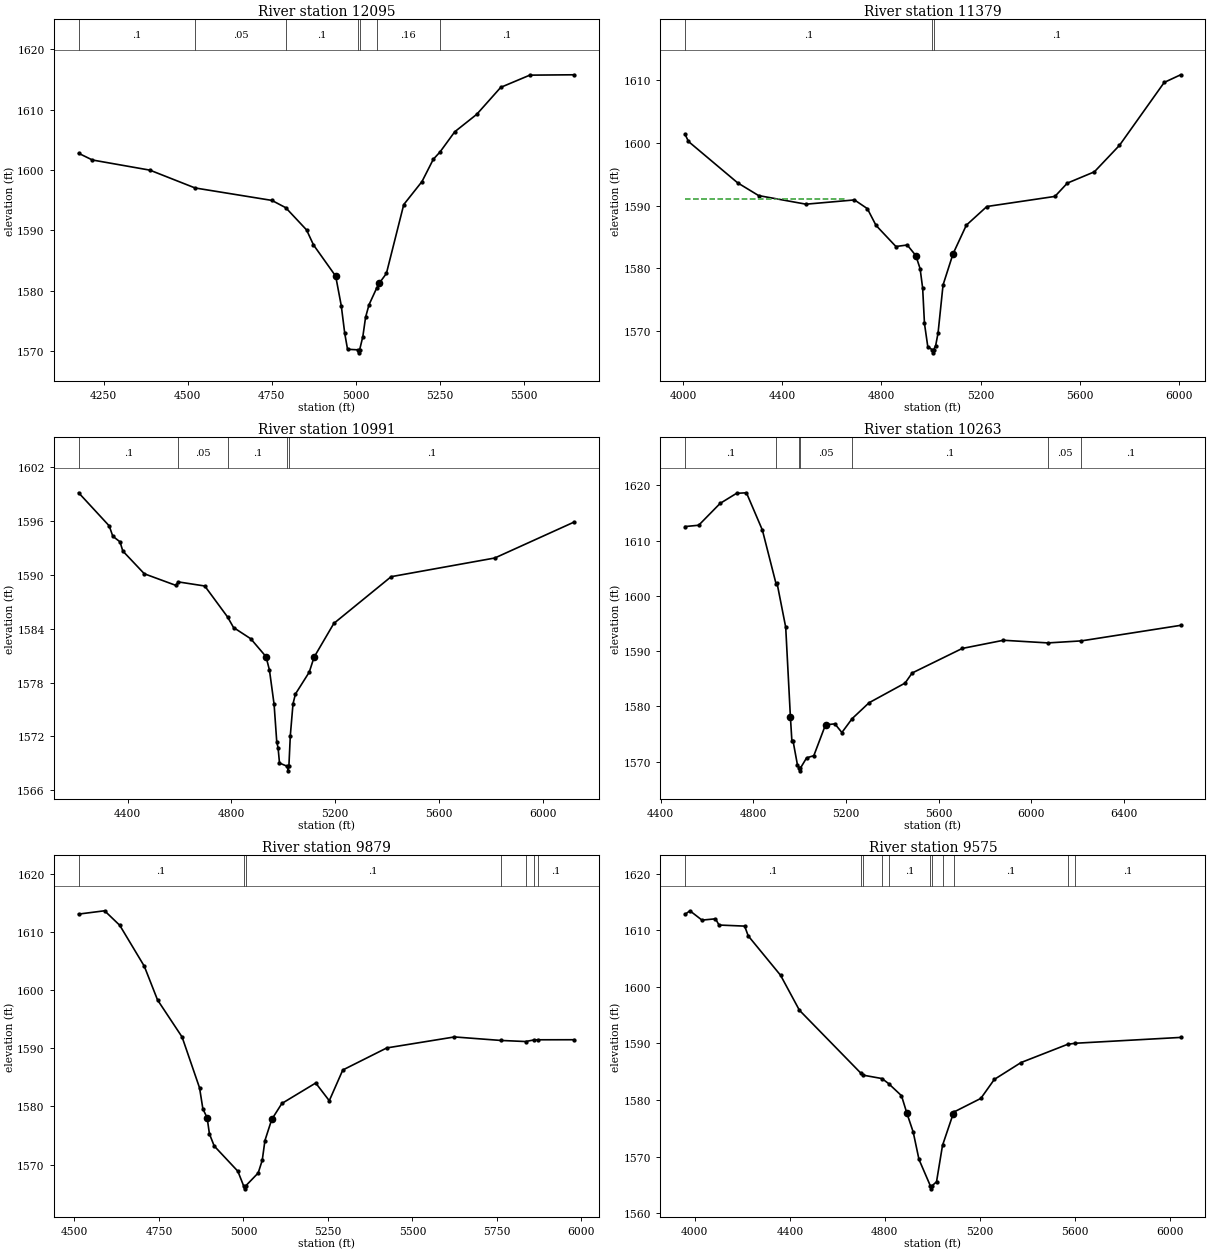
Type RM Length L Ch R = 1 ,12095   ,716,716,716
BEGIN DESCRIPTION:
WILLOW CREEK 16.0
END DESCRIPTION:
XS GIS Cut Line= 4
      2825457.76     10102906.35      2826006.38     10102972.32
      2826457.77     10102854.26      2826718.19     10102479.26
#Sta/Elev= 30
  4175.1 1602.77  4216.1 1601.66  4387.3 1599.98  4521.9 1597.03  4750.5 1594.97
  4791.9 1593.76  4853.9 1590.08  4874.5  1587.6  4940.6 1582.43  4957.2 1577.54
  4967.6 1572.94  4975.9 1570.32  5005.9 1570.23  5008.7 1569.73  5011.9 1570.23
  5021.5 1572.43  5029.6 1575.62  5039.9  1577.7  5062.5 1580.43  5070.9  1581.3
  5091.6 1582.87  5143.3 1594.28  5197.6 1598.09  5231.4 1601.79  5251.2 1602.98
  5295.1 1606.33  5360.6 1609.22  5432.2 1613.69  5518.7 1615.71  5650.8 1615.77
#Mann= 7 ,-1 , 0
  4175.1      .1       0  4521.9     .05       0  4791.9      .1       0
  5005.9     .07       0  5011.9      .1       0  5062.5     .16       0
  5251.2      .1       0
Bank Sta=4940.6,5070.9
XS Rating Curve= 0 ,0
Exp/Cntr=0.3,0.1

Type RM Length L Ch R = 1 ,11379   ,388,388,388
BEGIN DESCRIPTION:
Mapping XS 457a164c
END DESCRIPTION:
XS GIS Cut Line= 4
      2825766.79     10104111.21       2826252.9     10103632.04
      2826811.93     10103482.74      2826777.26     10102747.65
#Sta/Elev= 30
  4008.8 1601.35  4022.4 1600.22  4220.4 1593.63  4305.2 1591.59  4496.1 1590.22
  4691.4  1590.9  4743.3 1589.51  4778.2 1586.84  4858.4 1583.47  4904.1 1583.71
  4938.5 1582.03  4955.9 1579.94  4966.2 1576.83  4973.5 1571.19  4986.9 1567.49
  5004.6 1567.01  5007.4 1566.51  5010.6 1567.01  5018.7 1567.68  5028.3 1569.68
  5048.4 1577.34  5088.5 1582.29  5142.2 1586.87    5225 1589.85  5499.3 1591.46
  5549.3 1593.58  5658.2 1595.38  5759.5 1599.61  5939.7 1609.64  6005.9 1610.86
#Mann= 3 ,-1 , 0
  4008.8      .1       0  5004.6     .07       0  5010.6      .1       0
#XS Ineff= 2 , 0
         4648.43 1591.11
Permanent Ineff=
       F       F
Bank Sta=4938.5,5088.5
XS Rating Curve= 0 ,0
Exp/Cntr=0.3,0.1

Type RM Length L Ch R = 1 ,10991   ,728,728,728
BEGIN DESCRIPTION:
WILLOW CREEK 15.0
END DESCRIPTION:
XS GIS Cut Line= 3
      2825865.32     10104155.33       2826811.5     10103877.55
      2827011.15     10102974.78
#Sta/Elev= 30
  4211.4 1599.15  4329.3 1595.46  4343.1 1594.31    4371 1593.68  4381.7 1592.66
  4464.8 1590.12  4587.2 1588.82  4594.9 1589.22  4697.8 1588.76  4785.6 1585.31
  4808.7 1584.13  4875.1 1582.88  4933.8 1580.89  4947.1  1579.4  4965.1 1575.56
  4975.3  1571.4  4980.5 1570.71  4985.9 1569.03  5016.1 1568.66  5018.9 1568.16
  5022.1 1568.66  5027.6 1572.09    5038 1575.63  5047.3 1576.72  5100.6 1579.16
  5119.3 1580.83  5195.4 1584.59  5416.5  1589.8  5815.9 1591.88  6122.1 1595.89
#Mann= 5 ,-1 , 0
  4211.4      .1       0  4594.9     .05       0  4785.6      .1       0
  5016.1     .07       0  5022.1      .1       0
Bank Sta=4933.8,5119.3
XS Rating Curve= 0 ,0
Exp/Cntr=0.3,0.1

Type RM Length L Ch R = 1 ,10263   ,384,384,384
BEGIN DESCRIPTION:
WILLOW CREEK 14.0
END DESCRIPTION:
XS GIS Cut Line= 2
      2826794.13     10105023.42      2827115.06     10102907.01
#Sta/Elev= 30
  4505.1 1612.55  4563.9 1612.79  4656.5 1616.74  4727.3 1618.56  4770.1 1618.66
  4838.9 1611.92  4898.2 1602.17  4902.6 1602.25  4939.7 1594.34  4959.9 1578.18
  4966.3 1573.83  4971.3 1573.79  4990.3 1569.46  4997.4 1568.86  5000.1 1568.36
  5003.4 1568.86    5030 1570.71  5061.1  1571.1  5111.6 1576.68  5152.1 1576.86
  5182.4 1575.29  5226.8 1577.81  5299.9 1580.68  5455.5 1584.24  5485.9 1586.06
  5702.3  1590.5  5880.3 1591.98  6072.7  1591.5  6217.1 1591.87  6645.7 1594.68
#Mann= 7 ,-1 , 0
  4505.1      .1       0  4898.2     .05       0  4997.4    .035       0
  5003.4     .05       0  5226.8      .1       0  6072.7     .05       0
  6217.1      .1       0
Bank Sta=4959.9,5111.6
XS Rating Curve= 0 ,0
Exp/Cntr=0.3,0.1

Type RM Length L Ch R = 1 ,9879    ,304,304,304
BEGIN DESCRIPTION:
WILLOW CREEK 13.0
END DESCRIPTION:
XS GIS Cut Line= 3
      2827037.21     10104823.69      2827210.81     10104476.51
      2827158.72     10103400.13
#Sta/Elev= 30
  4512.6 1613.12  4589.4 1613.69  4634.2 1611.19  4706.8 1604.15    4746 1598.34
  4818.6 1591.96  4870.3  1583.2  4880.1 1579.59  4892.7 1578.06  4899.5 1575.28
  4913.6  1573.2  4983.6 1568.85  5000.7 1566.32  5003.4 1565.82  5006.7 1566.32
  5043.7 1568.55  5055.7 1570.73  5063.7 1574.14  5083.8 1577.77  5113.8 1580.52
  5213.9 1584.04    5254 1580.99    5294 1586.28  5424.2 1590.08  5624.4 1591.97
  5760.7 1591.37  5834.5 1591.18    5860 1591.46    5871 1591.48  5978.4 1591.49
#Mann= 7 ,-1 , 0
  4512.6      .1       0  5000.7     .07       0  5006.7      .1       0
  5760.7     .05       0  5834.5      .1       0    5860     .05       0
    5871      .1       0
Bank Sta=4892.7,5083.8
XS Rating Curve= 0 ,0
Exp/Cntr=0.3,0.1

Type RM Length L Ch R = 1 ,9575    ,650,650,650
BEGIN DESCRIPTION:
WILLOW CREEK 12.0
END DESCRIPTION:
XS GIS Cut Line= 3
      2826905.71     10104939.32      2827535.89     10104512.25
        2827255.     10103217.02
#Sta/Elev= 30
    3959  1612.8  3979.2 1613.43  4030.1 1611.78    4087 1612.01  4101.9 1610.91
  4209.8 1610.72  4224.7    1609    4361 1602.03  4440.4 1595.85  4700.3 1584.68
  4710.1 1584.37    4788 1583.78  4815.6  1582.9  4870.2 1580.75  4892.7 1577.68
  4919.4 1574.34  4943.9 1569.48    4992 1564.79  4994.8 1564.29    4998 1564.79
  5017.7 1565.54  5042.9 1571.97  5087.1 1577.46  5092.5  1577.9  5204.2 1580.27
  5261.1 1583.63  5373.6 1586.61  5569.7 1589.83  5602.3 1590.02  6045.6 1591.05
#Mann= 11 ,-1 , 0
    3959      .1       0  4700.3     .05       0  4710.1      .1       0
    4788     .05       0  4815.6      .1       0    4992     .07       0
    4998      .1       0  5042.9     .05       0  5092.5      .1       0
  5569.7     .05       0  5602.3      .1       0
Bank Sta=4892.7,5087.1
XS Rating Curve= 0 ,0
Exp/Cntr=0.3,0.1

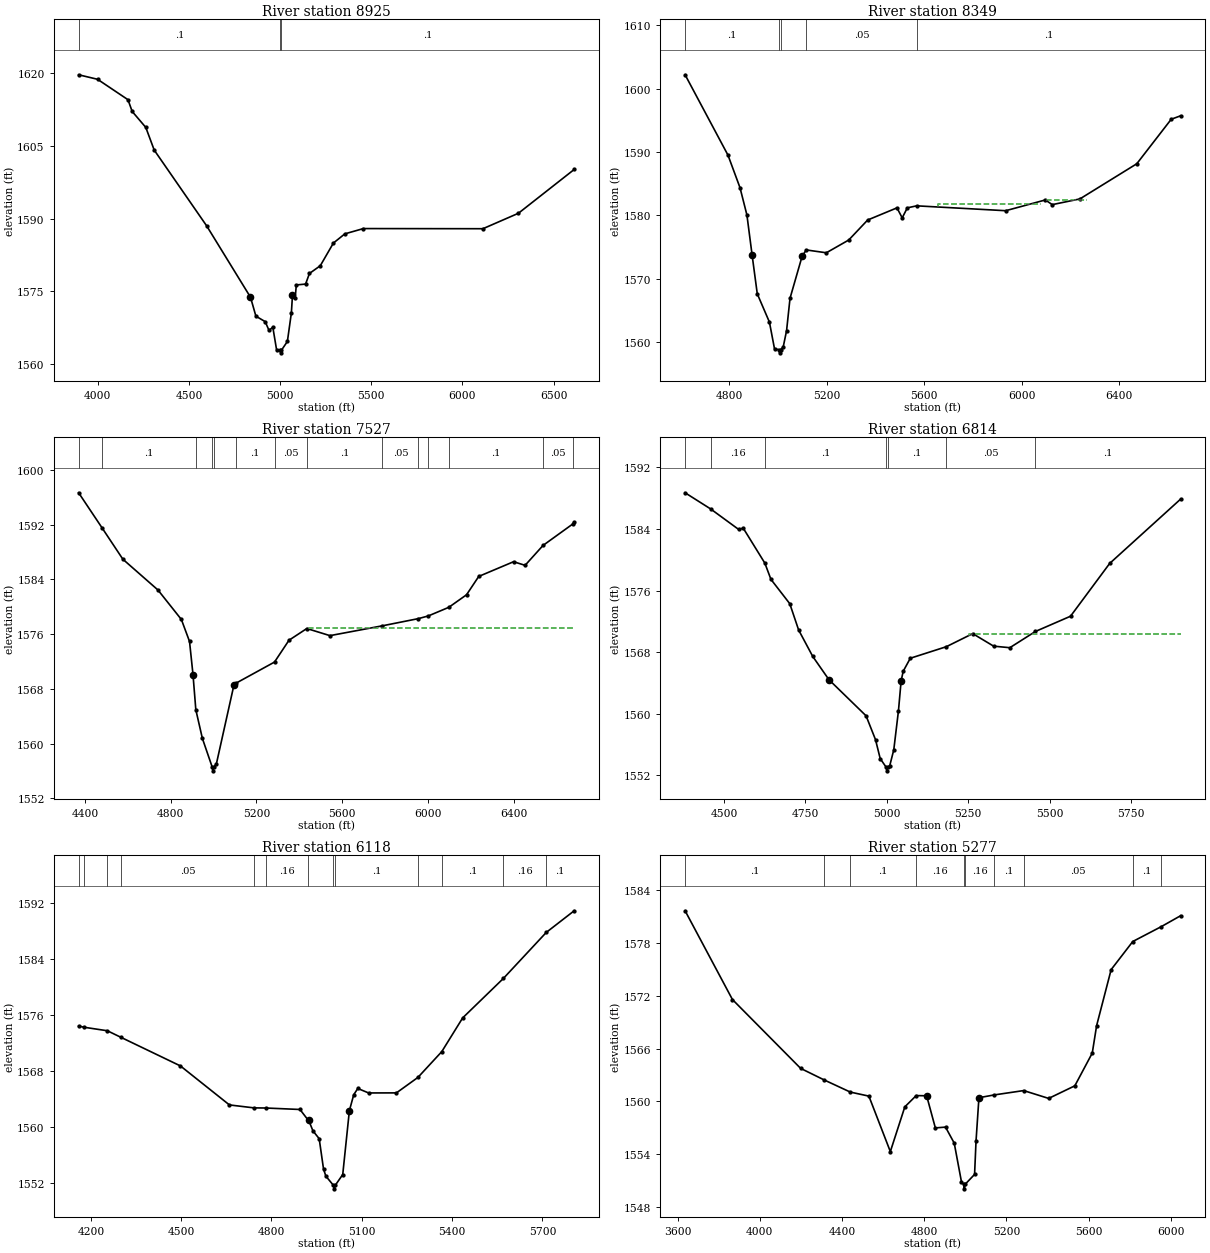
Type RM Length L Ch R = 1 ,8925    ,576,576,576
BEGIN DESCRIPTION:
WILLOW CREEK 11.0
END DESCRIPTION:
XS GIS Cut Line= 3
      2828990.34     10104450.47      2828130.95     10104059.84
      2827133.05     10102593.37
#Sta/Elev= 30
  3895.2  1619.7  3998.8 1618.77  4165.8 1614.55  4188.9 1612.12  4263.6 1608.82
  4309.7 1604.14  4597.5 1588.47  4837.8 1573.73  4867.5 1569.81  4918.4 1568.69
  4939.3 1566.88  4960.3 1567.53  4981.3 1562.78  5000.8 1562.74  5003.6 1562.24
  5006.8 1562.74  5040.1 1564.59    5062  1570.5  5068.1 1574.14    5083 1573.63
  5089.1 1576.27  5139.9 1576.45  5161.1 1578.64  5220.6 1580.24  5292.5 1584.93
  5355.4 1586.83  5457.1 1587.92  6112.6 1587.89  6307.1 1591.08    6613 1600.13
#Mann= 3 ,-1 , 0
  3895.2      .1       0  5000.8     .07       0  5006.8      .1       0
Bank Sta=4837.8,5068.1
XS Rating Curve= 0 ,0
Exp/Cntr=0.3,0.1

Type RM Length L Ch R = 1 ,8349    ,822,822,822
BEGIN DESCRIPTION:
WILLOW CREEK 10.0
END DESCRIPTION:
XS GIS Cut Line= 2
      2828773.32     10103877.57      2827384.45     10102393.21
#Sta/Elev= 30
  4619.2 1602.21  4795.1 1589.51  4844.5 1584.36  4872.8 1580.05  4894.3 1573.66
  4915.3 1567.59  4965.1 1563.13  4986.1 1558.88  5004.6 1558.77  5007.4 1558.27
  5010.6 1558.77  5021.6 1559.18  5035.5 1561.78  5049.6 1566.89  5099.5 1573.57
  5116.3 1574.53  5198.6 1574.08  5290.5  1576.1  5368.1 1579.26  5488.3 1581.18
  5509.8  1579.6  5530.8 1581.18  5569.1  1581.5  5934.3 1580.73    6097 1582.43
  6125.3 1581.69  6238.6 1582.59  6472.1 1588.15  6613.3 1595.18    6652 1595.73
#Mann= 5 ,-1 , 0
  4619.2      .1       0  5004.6     .07       0  5010.6      .1       0
  5116.3     .05       0  5569.1      .1       0
#XS Ineff= 2 ,-1
 5657.55 6080.65 1581.86 6097.67 6266.66 1582.48
Permanent Ineff=
       F       F
Bank Sta=4894.3,5099.5
XS Rating Curve= 0 ,0
Exp/Cntr=0.3,0.1

Type RM Length L Ch R = 1 ,7527    ,713,713,713
BEGIN DESCRIPTION:
WILLOW CREEK 9.0
END DESCRIPTION:
XS GIS Cut Line= 2
      2829528.51     10103235.19      2827497.29     10102132.77
#Sta/Elev= 30
  4370.7 1596.65    4479 1591.57  4577.1 1586.94  4740.6 1582.45  4849.9 1578.14
  4887.9 1574.93  4904.1 1570.09  4917.3 1564.95  4947.8 1560.77  4994.2 1556.53
    4997 1556.03  5000.2 1556.53  5013.4 1557.08  5095.1 1568.58  5103.2 1568.81
  5284.2 1571.92  5351.8 1575.11    5435 1576.82  5542.8 1575.78  5787.8 1577.22
  5955.7 1578.27  6001.6 1578.66  6097.3 1579.92  6179.8 1581.75  6236.7 1584.43
  6399.2 1586.58  6452.9 1586.05  6536.7 1588.96  6674.8 1592.08  6681.8 1592.32
#Mann= 14 ,-1 , 0
  4370.7     .16       0    4479      .1       0  4917.3     .16       0
  4994.2     .07       0  5000.2     .16       0  5103.2      .1       0
  5284.2     .05       0    5435      .1       0  5787.8     .05       0
  5955.7      .1       0  6001.6     .05       0  6097.3      .1       0
  6536.7     .05       0  6674.8      .1       0
#XS Ineff= 2 , 0
                         5443.66         1576.96
Permanent Ineff=
       F       F
Bank Sta=4904.1,5095.1
XS Rating Curve= 0 ,0
Exp/Cntr=0.3,0.1

Type RM Length L Ch R = 1 ,6814    ,696,696,696
BEGIN DESCRIPTION:
WILLOW CREEK 7.0
END DESCRIPTION:
XS GIS Cut Line= 2
      2829762.87     10102679.62        2828565.     10101742.15
#Sta/Elev= 30
  4380.7 1588.71  4459.1 1586.61  4544.7 1583.96  4559.2 1584.11  4625.5 1579.57
  4644.2 1577.46    4702  1574.3  4729.2 1570.88  4772.6 1567.44  4822.3 1564.42
  4936.2 1559.73  4965.2 1556.63  4979.6 1554.17  4997.4 1553.08  5000.2 1552.58
  5003.4 1553.08  5008.5 1553.19  5021.3 1555.32  5035.7 1560.41  5043.8 1564.27
  5050.2 1565.52    5072 1567.21  5182.6 1568.71  5263.6 1570.41  5327.8 1568.78
  5377.5 1568.58  5456.1 1570.69  5563.8 1572.67    5684 1579.53  5901.8 1587.89
#Mann= 7 ,-1 , 0
  4380.7      .1       0  4459.1     .16       0  4625.5      .1       0
  4997.4     .07       0  5003.4      .1       0  5182.6     .05       0
  5456.1      .1       0
#XS Ineff= 2 , 0
                         5251.27         1570.36
Permanent Ineff=
       F       F
Bank Sta=4822.3,5043.8
XS Rating Curve= 0 ,0
Exp/Cntr=0.3,0.1

Type RM Length L Ch R = 1 ,6118    ,841,841,841
BEGIN DESCRIPTION:
WILLOW CREEK 6.0
END DESCRIPTION:
XS GIS Cut Line= 2
      2830292.43     10102245.63      2829025.02     10101195.24
#Sta/Elev= 30
  4159.5 1574.38  4176.1 1574.21  4254.9  1573.7  4301.1 1572.74  4497.6 1568.68
  4660.4 1563.11  4741.8 1562.69    4781 1562.67  4894.8 1562.46  4920.7 1561.01
  4923.5 1560.94  4937.8 1559.41  4958.6 1558.29    4973 1553.96  4980.8 1552.94
  5005.9 1551.63  5008.6 1551.13  5011.9 1551.63  5036.8 1553.17  5058.9  1562.3
  5073.3 1564.56  5086.8 1565.46  5122.8 1564.82  5215.2 1564.83  5286.6 1567.04
  5365.8 1570.72  5435.3 1575.54  5570.7 1581.18  5712.9 1587.74  5805.6 1590.83
#Mann= 13 ,-1 , 0
  4159.5      .1       0  4176.1     .05       0  4254.9      .1       0
  4301.1     .05       0  4741.8      .1       0    4781     .16       0
  4920.7      .1       0  5005.9     .07       0  5011.9      .1       0
  5286.6     .05       0  5365.8      .1       0  5570.7     .16       0
  5712.9      .1       0
Bank Sta=4923.5,5058.9
XS Rating Curve= 0 ,0
Exp/Cntr=0.3,0.1

Type RM Length L Ch R = 1 ,5277    ,700,700,700
BEGIN DESCRIPTION:
WILLOW CREEK 4.0
END DESCRIPTION:
XS GIS Cut Line= 3
      2830551.51     10102465.34       2830416.1     10101350.79
      2829499.41     10100444.52
#Sta/Elev= 30
  3636.5 1581.66  3866.9 1571.58  4198.9 1563.76  4314.1 1562.44  4440.5 1561.07
    4531 1560.61  4635.4 1554.31  4705.9 1559.39  4761.2 1560.67  4812.1 1560.65
  4854.5    1557    4904 1557.09  4946.4 1555.27  4981.7 1550.86  4992.9 1550.58
  4995.6 1550.08  4998.9 1550.58  5045.4 1551.72  5052.5 1555.52  5066.6 1560.43
  5142.1 1560.75  5284.3 1561.24    5406 1560.35  5533.3 1561.78  5618.2  1565.5
  5639.4 1568.62  5710.1 1574.98  5815.4 1578.17  5954.1 1579.86  6048.3  1581.1
#Mann= 10 ,-1 , 0
  3636.5      .1       0  4314.1     .05       0  4440.5      .1       0
  4761.2     .16       0  4992.9     .07       0  4998.9     .16       0
  5142.1      .1       0  5284.3     .05       0  5815.4      .1       0
  5954.1     .05       0
Bank Sta=4812.1,5066.6
XS Rating Curve= 0 ,0
Exp/Cntr=0.3,0.1

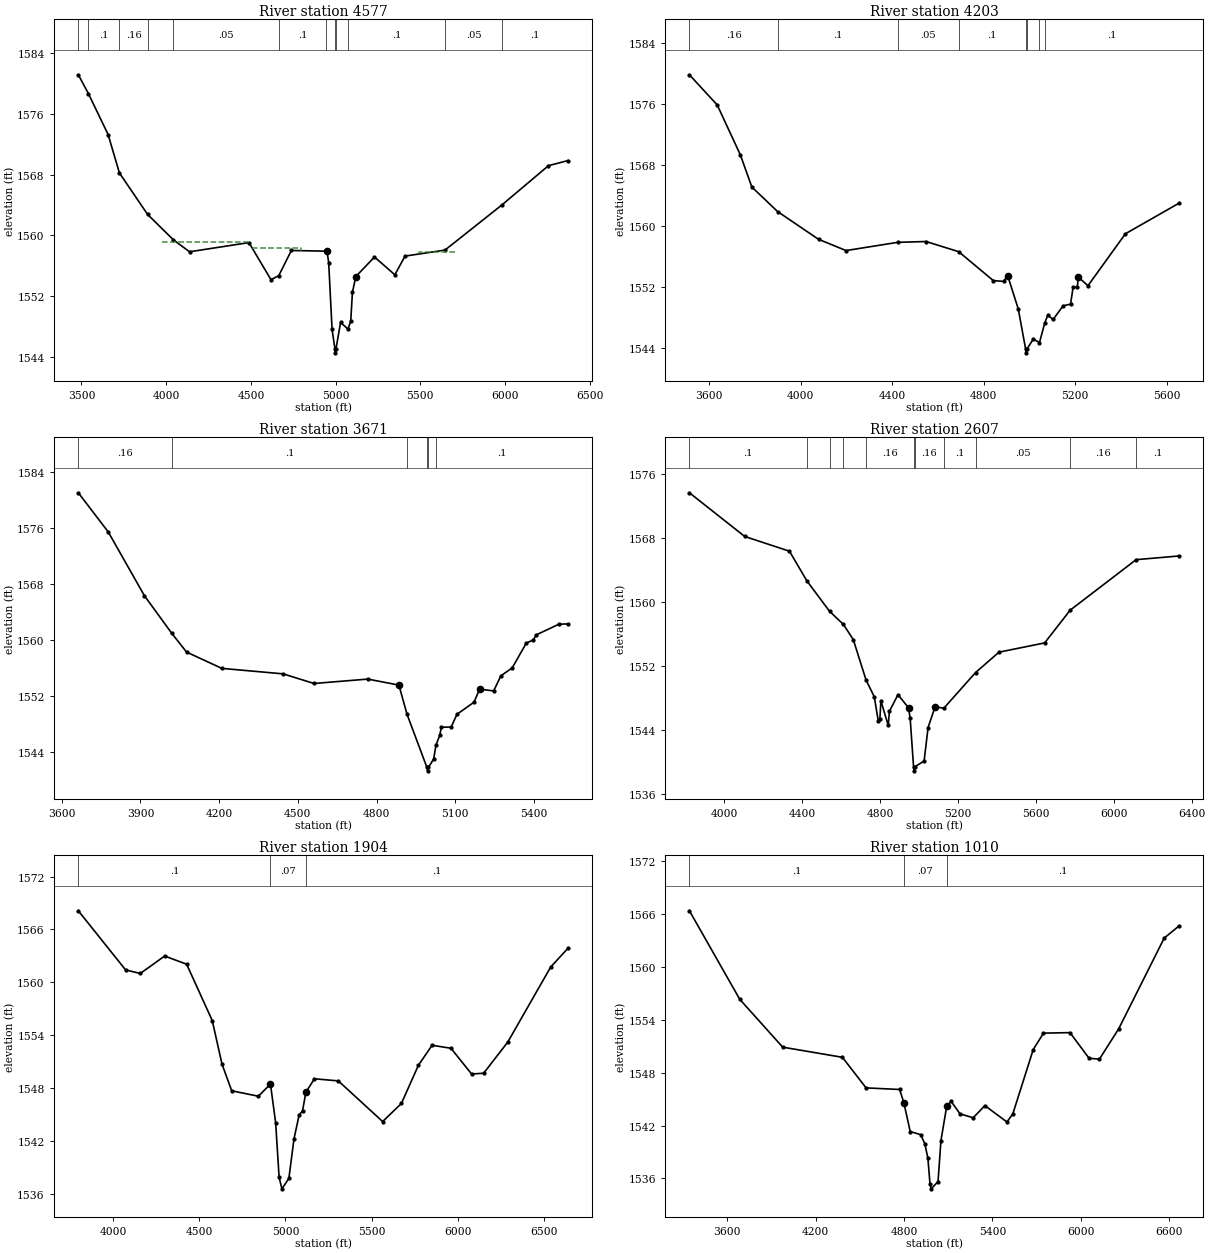
Type RM Length L Ch R = 1 ,4577    ,374,374,374
BEGIN DESCRIPTION:
Mapping XS 3aeda749
END DESCRIPTION:
XS GIS Cut Line= 2
      2830723.39     10102439.31      2830869.23     10099553.89
#Sta/Elev= 30
  3481.4 1581.15    3541 1578.66  3657.2 1573.27  3723.6 1568.22  3890.3 1562.74
  4042.7 1559.39  4137.8 1557.82  4488.3 1559.03  4618.4 1554.14  4664.5 1554.68
  4738.6 1557.99  4944.7  1557.9  4948.9  1557.9  4958.9 1556.39  4978.9 1547.58
  4995.9    1545  4998.7  1544.5  5001.9    1545    5029 1548.51  5072.6 1547.63
    5089 1548.66    5099 1552.47  5119.1 1554.56  5229.2 1557.13  5349.4 1554.79
  5409.4 1557.25  5645.2 1558.04  5983.2 1564.03    6256 1569.17  6370.5 1569.84
#Mann= 12 ,-1 , 0
  3481.4     .16       0    3541      .1       0  3723.6     .16       0
  3890.3      .1       0  4042.7     .05       0  4664.5      .1       0
  4944.7     .16       0  4995.9     .07       0  5001.9     .16       0
  5072.6      .1       0  5645.2     .05       0  5983.2      .1       0
#XS Ineff= 3 ,-1
 3974.22    4481 1559.05 4508.73 4793.69 1558.38 5491.48 5710.21 1557.73
Permanent Ineff=
       F       F       F
Bank Sta=4948.9,5119.1
XS Rating Curve= 0 ,0
Exp/Cntr=0.3,0.1

Type RM Length L Ch R = 1 ,4203    ,532,532,532
BEGIN DESCRIPTION:
Mapping XS 65699e62
END DESCRIPTION:
XS GIS Cut Line= 3
      2830801.52     10102465.34      2830890.06     10101538.29
      2831369.22     10100428.92
#Sta/Elev= 30
  3513.6 1579.84    3635 1575.88  3736.2 1569.32  3786.4 1565.09  3898.9 1561.87
  4077.8 1558.22  4198.3 1556.74  4423.8 1557.82  4547.9 1557.93  4690.6 1556.59
    4842 1552.79  4886.6 1552.69  4904.7 1553.44  4950.9 1549.07  4983.1  1543.8
  4985.8  1543.3  4989.1  1543.8  5016.3 1545.11  5043.7 1544.65  5067.1 1547.27
  5080.1 1548.24  5103.4 1547.69    5147 1549.48  5179.5  1549.7  5190.6 1551.93
  5208.5  1551.9  5213.9 1553.24  5255.5 1552.12  5419.3 1558.95  5653.3 1562.96
#Mann= 8 ,-1 , 0
  3513.6     .16       0  3898.9      .1       0  4423.8     .05       0
  4690.6      .1       0  4983.1     .07       0  4989.1      .1       0
  5043.7     .16       0  5067.1      .1       0
Bank Sta=4904.7,5213.9
XS Rating Curve= 0 ,0
Exp/Cntr=0.3,0.1

Type RM Length L Ch R = 1 ,3671    ,1064,1064,1064
BEGIN DESCRIPTION:
WILLOW CREEK 3.0
END DESCRIPTION:
XS GIS Cut Line= 2
       2830853.6     10102533.07      2831770.07     10100908.44
#Sta/Elev= 30
  3663.5 1581.07  3777.6 1575.46  3915.3 1566.34  4019.3 1560.97  4076.1 1558.27
  4210.4 1555.94  4443.5 1555.16  4561.4 1553.78  4766.5 1554.41    4885 1553.55
  4915.9 1549.38  4991.6 1541.78  4994.3 1541.28  4997.6 1541.78  5017.5 1542.98
  5026.1 1544.94  5040.5 1546.36  5046.7 1547.52  5084.3 1547.55    5106 1549.36
    5171  1551.1  5192.6 1552.96  5246.1 1552.72  5273.5 1554.87  5316.8 1556.02
  5370.3 1559.55  5397.7 1560.03  5407.9 1560.73  5494.5 1562.26  5528.8 1562.31
#Mann= 6 ,-1 , 0
  3663.5     .16       0  4019.3      .1       0  4915.9     .16       0
  4991.6     .07       0  4997.6     .16       0  5026.1      .1       0
Bank Sta=4885,5192.6
XS Rating Curve= 0 ,0
Exp/Cntr=0.3,0.1

Type RM Length L Ch R = 1 ,2607    ,703,703,703
BEGIN DESCRIPTION:
WILLOW CREEK 2.0
END DESCRIPTION:
XS GIS Cut Line= 3
      2832233.81     10102861.19      2832624.43     10101074.75
      2832218.18     10100522.66
#Sta/Elev= 30
  3820.5 1573.71  4104.7 1568.24  4334.3  1566.4  4423.3  1562.7    4540 1558.88
  4611.2 1557.24    4662 1555.34  4727.6 1550.28  4769.9 1548.17  4790.3 1545.17
  4798.7 1545.37  4803.8 1547.67  4841.5  1544.6  4847.7 1546.37  4891.6 1548.44
  4945.7  1546.8  4954.1 1545.51  4971.6 1539.41  4974.3 1538.91  4977.6 1539.41
  5025.8 1540.14  5046.2 1544.33  5082.5 1546.96  5126.4 1546.73    5290 1551.21
  5410.1 1553.76  5644.8 1554.92    5776 1559.02  6114.6 1565.34  6334.6  1565.8
#Mann= 11 ,-1 , 0
  3820.5      .1       0  4423.3     .05       0    4540      .1       0
  4611.2     .05       0  4727.6     .16       0  4971.6     .07       0
  4977.6     .16       0  5126.4      .1       0    5290     .05       0
    5776     .16       0  6114.6      .1       0
Bank Sta=4945.7,5082.5
XS Rating Curve= 0 ,0
Exp/Cntr=0.3,0.1

Type RM Length L Ch R = 1 ,1904    ,894,894,894
BEGIN DESCRIPTION:
WILLOW CREEK 1.0
END DESCRIPTION:
XS GIS Cut Line= 4
        2832489.     10102762.27      2833186.93     10102017.46
       2833103.6     10101017.46      2832322.89     10100569.85
#Sta/Elev= 30
  3798.7 1568.12  4073.1 1561.41    4158 1561.01  4299.7 1562.99  4427.1 1562.06
  4575.7 1555.67  4632.3 1550.73  4688.5 1547.71  4843.2 1547.09  4913.5 1548.47
  4943.6 1544.06  4963.6 1537.89  4979.9 1536.59 5020.28 1537.77 5049.96 1542.26
 5079.63 1544.95 5099.41 1545.43 5119.19 1547.56 5168.65 1549.07 5307.13 1548.83
  5564.3 1544.22  5673.1 1546.27 5772.02 1550.61 5851.15 1552.87  5960.7 1552.53
 6080.39 1549.61 6150.22  1549.7 6289.86 1553.22 6539.22 1561.74 6638.97 1563.86
#Mann= 3 , 0 , 0
  3798.7      .1       0  4913.5     .07       0 5119.19      .1       0
Bank Sta=4913.5,5119.19
XS Rating Curve= 0 ,0
Exp/Cntr=0.3,0.1

Type RM Length L Ch R = 1 ,1010    ,710,710,710
BEGIN DESCRIPTION:
NORTH GRAPE CREEK 98.0
END DESCRIPTION:
XS GIS Cut Line= 4
      2834499.43     10102918.48      2834262.67     10101750.95
      2833681.72     10101288.29      2832416.06     10100595.56
#Sta/Elev= 30
    3343 1566.36  3684.6 1556.32  3976.1 1550.89  4381.4 1549.74    4542 1546.27
  4769.8 1546.09  4798.2  1544.6  4841.5 1541.32  4911.9 1540.97  4940.8 1539.94
  4961.6 1538.28    4976 1535.33  4983.8 1534.82 5030.32 1535.65  5050.2  1540.3
 5089.96 1544.26 5119.78 1544.73 5179.43 1543.33  5268.9 1542.88 5348.43 1544.26
 5497.54 1542.41  5537.3 1543.29 5676.48 1550.62 5746.12 1552.48 5926.01 1552.54
 6055.93 1549.62 6125.88 1549.54  6255.8 1552.95 6565.61 1563.27 6665.55 1564.63
#Mann= 3 , 0 , 0
    3343      .1       0  4798.2     .07       0 5089.96      .1       0
#XS Ineff= 2 , 0
                         5812.58         1551.45
Permanent Ineff=
       F       F
Bank Sta=4798.2,5089.96
XS Rating Curve= 0 ,0
Exp/Cntr=0.3,0.1

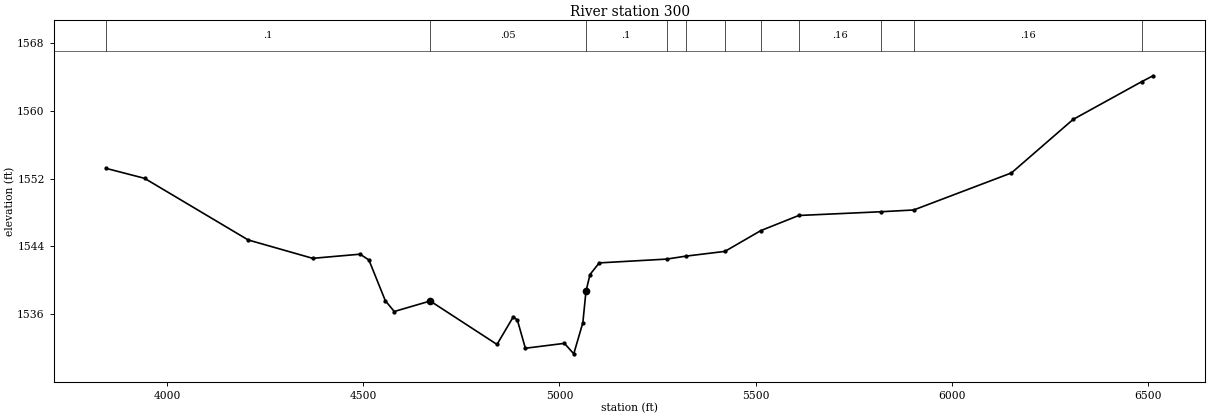
Type RM Length L Ch R = 1 ,300     ,0,0,0
BEGIN DESCRIPTION:
NORTH GRAPE CREEK 101.0
END DESCRIPTION:
XS GIS Cut Line= 4
      2834983.84     10101475.82       2834291.1     10100949.75
      2833864.02     10100845.58      2832521.91      10100637.5
#Sta/Elev= 30
    3845 1553.21  3942.7 1552.04  4206.8 1544.76  4371.1 1542.59  4492.1 1543.08
  4514.5 1542.39  4556.2 1537.59    4579 1536.31  4670.6 1537.55  4840.8 1532.42
  4882.3 1535.68  4892.8 1535.29  4913.1 1531.97  5012.7 1532.55  5036.4 1531.31
  5059.6 1534.99  5067.5 1538.68  5077.8 1540.68  5101.3 1542.05  5273.1  1542.5
  5322.4 1542.85  5421.6 1543.41  5512.9 1545.86  5609.6 1547.65  5818.4 1548.09
  5902.6  1548.3  6151.8 1552.68  6308.7 1558.99  6483.4 1563.45  6512.6 1564.15
#Mann= 11 ,-1 , 0
    3845      .1       0  4670.6     .05       0  5067.5      .1       0
  5273.1     .05       0  5322.4      .1       0  5421.6     .16       0
  5512.9      .1       0  5609.6     .16       0  5818.4      .1       0
  5902.6     .16       0  6483.4      .1       0
Bank Sta=4670.6,5067.5
XS Rating Curve= 0 ,0
Exp/Cntr=0.3,0.1

Chan Stop Cuts=-1
Use User Specified Reach Order=0
Composite Channel Slope=5