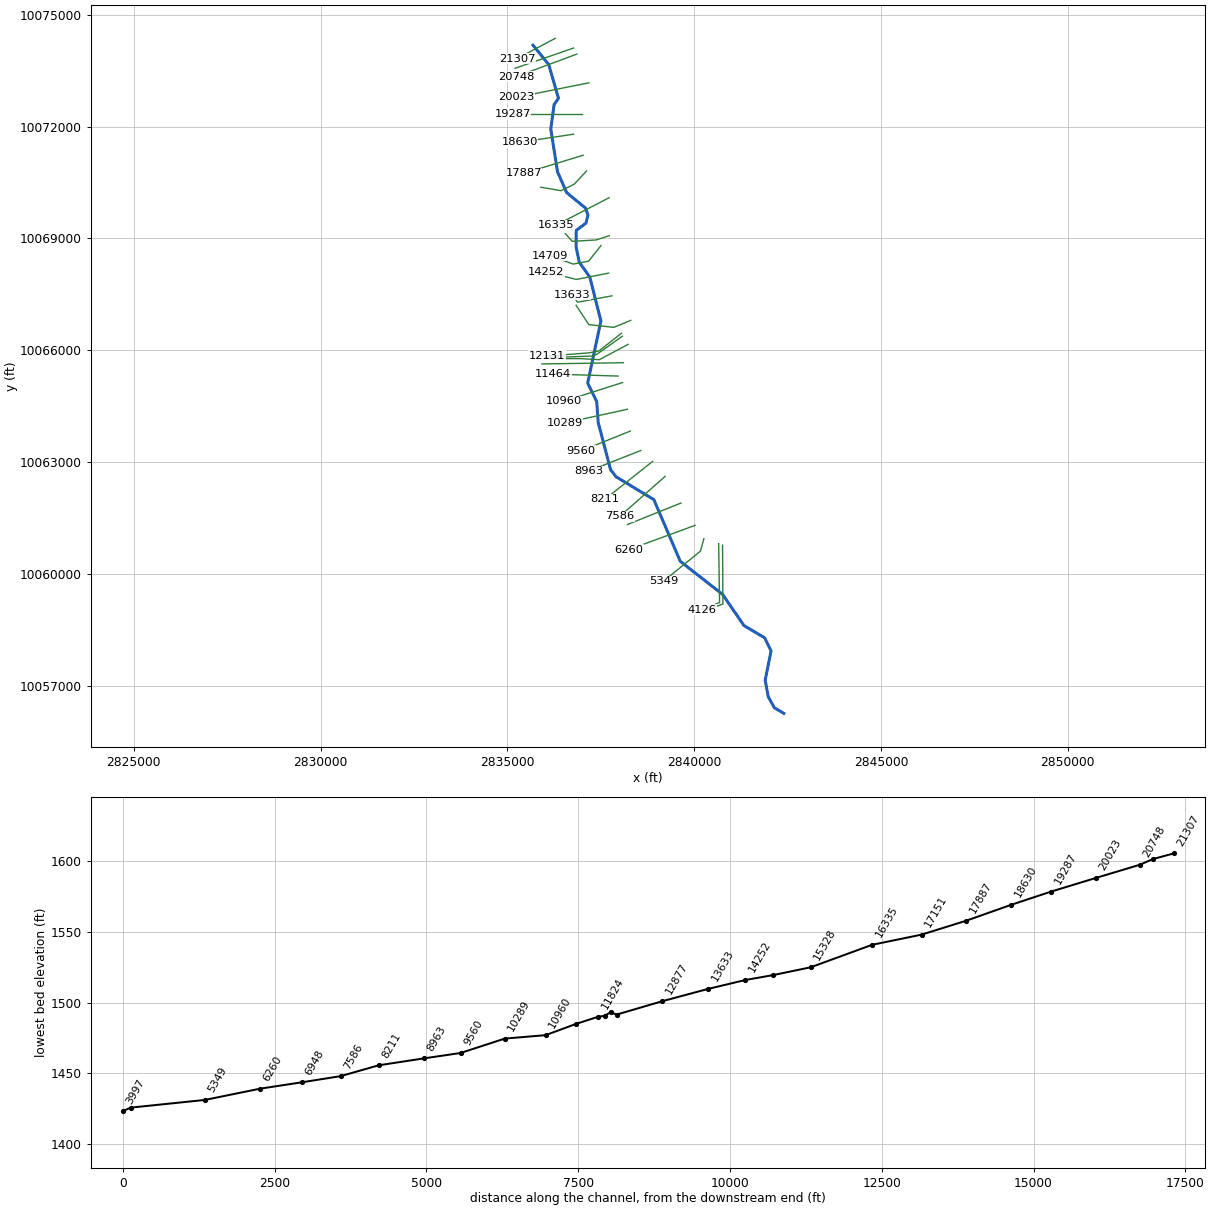
--- WITTINGTON CREEK.prj (project) ---

Proj Title=WITTINGTON CREEK Base Level Engineering
Current Plan=p01
Default Exp/Contr=0.3,0.1
English Units
Geom File=g01
Flow File=f01
Plan File=p01
BEGIN DESCRIPTION:
WITTINGTON CREEK
END DESCRIPTION:

--- WITTINGTON CREEK.p01 (plan) ---

Plan Title=Multiple Run
Short Identifier=Multiple
Geom File=g01
Flow File=f01
Subcritical Flow
K Sum by GR= 0
Std Step Tol= 0.01
Critical Tol= 0.01
Num of Std Step Trials= 20
Max Error Tol= 0.3
Flow Tol Ratio= 0.001
Split Flow NTrial= 30
Split Flow Tol= 0.02
Split Flow Ratio= 0.02
Log Output Level= 0
Friction Slope Method= 1
Unsteady Friction Slope Method= 2
Unsteady Bridges Friction Slope Method= 1
Parabolic Critical Depth
Global Vel Dist=  1 , 1 , 1
Global Log Level= 0
CheckData=True
Encroach Param= -1, 0, 0, 0
BEGIN DESCRIPTION:
Multiple Run
END DESCRIPTION:

--- WITTINGTON CREEK.f01 (steady flow) ---

Flow Title=Multiple
Number of Profiles=7
Profile Names=10-year,25-year,50-year,1pct_min,100-year,1pct_plu,500-year
River Rch & RM= WITTINGTON CREEK,Reach-1,21307
    1077    1588    2040    1920    2596    3511    4219
River Rch & RM= WITTINGTON CREEK,Reach-1,20748
    1475    2198    2842    2686    3632    4912    5960
River Rch & RM= WITTINGTON CREEK,Reach-1,11933
    2205    3336    4357    4153    5616    7595    9373
River Rch & RM= WITTINGTON CREEK,Reach-1,2231
    2628    4007    5261    5037    6812    9213   11478
Boundary for River Rch & Prof#=WITTINGTON CREEK,Reach-1,1
Up Type=0
Dn Type=3
Dn Slope=0.005
Boundary for River Rch & Prof#=WITTINGTON CREEK,Reach-1,2
Up Type=0
Dn Type=3
Dn Slope=0.005
Boundary for River Rch & Prof#=WITTINGTON CREEK,Reach-1,3
Up Type=0
Dn Type=3
Dn Slope=0.005
Boundary for River Rch & Prof#=WITTINGTON CREEK,Reach-1,4
Up Type=0
Dn Type=3
Dn Slope=0.005
Boundary for River Rch & Prof#=WITTINGTON CREEK,Reach-1,5
Up Type=0
Dn Type=3
Dn Slope=0.005
Boundary for River Rch & Prof#=WITTINGTON CREEK,Reach-1,6
Up Type=0
Dn Type=3
Dn Slope=0.005
Boundary for River Rch & Prof#=WITTINGTON CREEK,Reach-1,7
Up Type=0
Dn Type=3
Dn Slope=0.005

--- WITTINGTON CREEK.g01 (geometry) ---

Geom Title=Existing Conditions

River Reach=WITTINGTON CREEK,Reach-1
Reach XY= 30
      2835685.46     10074183.01      2836106.56     10073662.94
      2836366.92     10072757.86      2836249.73     10072588.21
      2836160.83     10071933.85      2836341.56     10070785.02
      2836583.38     10070230.98      2837088.71     10069813.68
      2837156.78     10069627.92      2837103.73     10069410.85
      2836841.47     10069212.26      2836839.31     10068768.67
      2836922.67     10068363.26      2837207.31     10067958.18
      2837502.23     10066783.96      2837148.76     10065118.87
      2837390.43     10064621.08      2837430.36     10064059.28
      2837762.83     10062790.86      2837912.28     10062601.83
      2838917.80     10061993.37      2839626.22     10060337.58
      2840759.60     10059448.07      2841332.59     10058611.60
      2841883.39     10058286.58      2842057.13     10057933.43
      2841899.00     10057148.45      2841981.32     10056704.92
      2842144.51     10056408.03      2842398.88     10056257.16

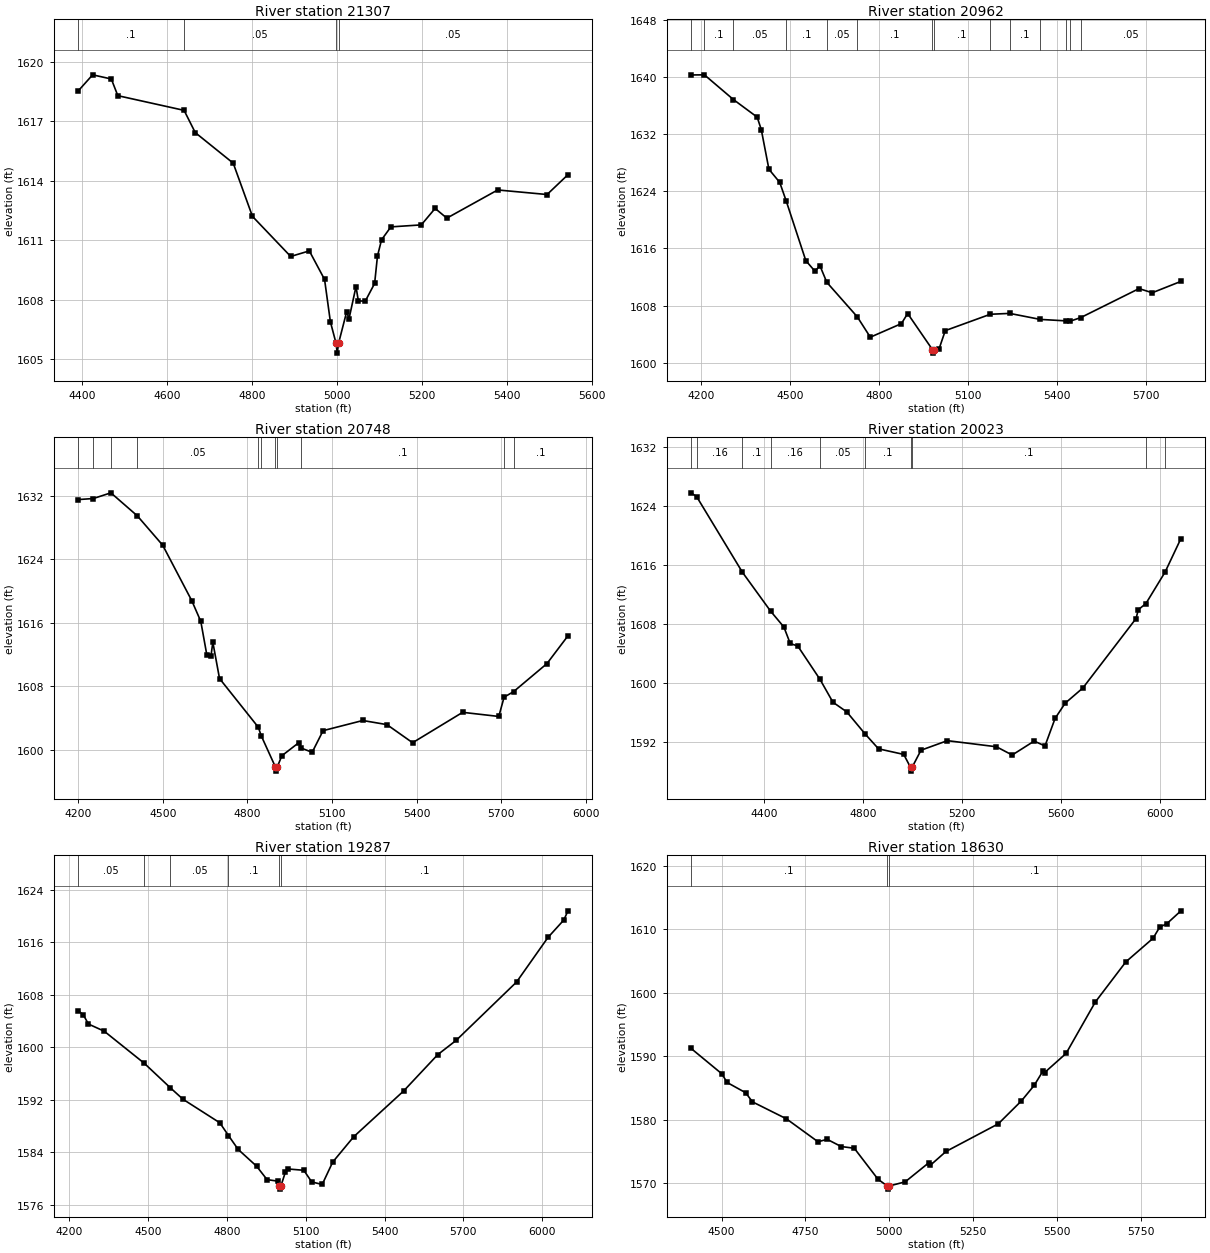
Type RM Length L Ch R = 1,21307,345,345,345
BEGIN DESCRIPTION:
WITTINGTON CREEK 43.0
END DESCRIPTION:
XS GIS Cut Line= 2
      2836281.19     10074366.32      2835262.35     10073824.39
#Sta/Elev= 30
  4390.1 1618.52  4424.5 1619.34  4468.5 1619.13  4483.8 1618.29  4639.9 1617.55
  4666.2 1616.43  4755.6 1614.89  4800.9 1612.21  4891.0 1610.19  4934.9 1610.47
  4970.8 1609.03  4984.5 1606.90  4997.8 1605.82  5000.6 1605.32  5003.8 1605.82
  5022.8 1607.40  5028.5 1607.06  5044.8 1608.67  5050.4 1607.95  5066.7 1607.94
  5088.7 1608.83  5095.4 1610.21  5105.0 1611.03  5127.0 1611.68  5198.6 1611.78
  5231.2 1612.61  5258.8 1612.12  5378.6 1613.54  5494.9 1613.31  5544.1 1614.31
#Mann=4,-1,0
  4390.1     0.1       0  4639.9    0.05       0  4997.8    0.04       0
  5003.8    0.05       0
Bank Sta=4997.8,5003.8
Exp/Cntr=0.3,0.1

Type RM Length L Ch R = 1,20962,214,214,214
BEGIN DESCRIPTION:
Mapping XS 73d24620
END DESCRIPTION:
XS GIS Cut Line= 2
      2836769.48     10074105.91      2835206.99     10073563.38
#Sta/Elev= 30
  4164.6 1640.28  4209.8 1640.30  4307.8 1636.84  4388.0 1634.38  4401.9 1632.63
  4427.7 1627.08  4464.1 1625.25  4486.4 1622.60  4552.2 1614.30  4583.3 1612.80
  4599.7 1613.60  4623.1 1611.26  4726.0 1606.43  4770.0 1603.58  4874.9 1605.48
  4896.1 1606.89  4979.6 1601.85  4982.4 1601.35  4985.6 1601.85  5001.9 1601.92
  5023.1 1604.50  5175.1 1606.79  5240.6 1606.91  5343.5 1606.07  5432.2 1605.86
  5443.9 1605.81  5480.2 1606.32  5677.2 1610.38  5721.8 1609.80  5818.6 1611.39
#Mann=14,-1,0
  4164.6    0.05       0  4209.8     0.1       0  4307.8    0.05       0
  4486.4     0.1       0  4623.1    0.05       0  4726.0     0.1       0
  4979.6    0.07       0  4985.6     0.1       0  5175.1    0.16       0
  5240.6     0.1       0  5343.5    0.16       0  5432.2    0.05       0
  5443.9     0.1       0  5480.2    0.05       0
Bank Sta=4979.6,4985.6
Exp/Cntr=0.3,0.1

Type RM Length L Ch R = 1,20748,725,725,725
BEGIN DESCRIPTION:
WITTINGTON CREEK 42.0
END DESCRIPTION:
XS GIS Cut Line= 2
      2836856.27     10073943.15      2835228.69     10073335.52
#Sta/Elev= 30
  4199.6 1631.55  4253.7 1631.68  4316.1 1632.40  4409.8 1629.50  4499.8 1625.80
  4602.9 1618.81  4634.9 1616.20  4656.2 1612.00  4671.0 1611.84  4677.6 1613.57
  4701.3 1609.00  4838.9 1602.86  4848.9 1601.81  4899.8 1597.83  4902.5 1597.33
  4905.8 1597.83  4922.4 1599.27  4983.0 1600.93  4990.8 1600.24  5029.8 1599.70
  5068.6 1602.43  5209.4 1603.71  5295.0 1603.19  5386.0 1600.91  5563.5 1604.74
  5691.6 1604.22  5710.4 1606.65  5744.2 1607.35  5862.4 1610.88  5936.9 1614.38
#Mann=11,-1,0
  4199.6     0.1       0  4253.7    0.05       0  4316.1     0.1       0
  4409.8    0.05       0  4838.9     0.1       0  4848.9    0.05       0
  4899.8    0.07       0  4905.8    0.05       0  4990.8     0.1       0
  5710.4    0.05       0  5744.2     0.1       0
Bank Sta=4899.8,4905.8
Exp/Cntr=0.3,0.1

Type RM Length L Ch R = 1,20023,736,736,736
BEGIN DESCRIPTION:
WITTINGTON CREEK 41.0
END DESCRIPTION:
XS GIS Cut Line= 2
      2837181.86     10073172.77      2835239.55     10072782.14
#Sta/Elev= 30
  4104.9 1625.81  4127.6 1625.30  4312.8 1615.02  4426.9 1609.73  4480.5 1607.58
  4506.2 1605.34  4536.8 1604.99  4626.5 1600.47  4678.9 1597.36  4734.8 1596.05
  4808.5 1593.07  4863.2 1591.03  4965.2 1590.27  4992.8 1588.50  4995.5 1588.00
  4998.8 1588.50  5034.9 1590.84  5141.7 1592.14  5340.0 1591.31  5403.8 1590.19
  5492.6 1592.08  5536.4 1591.42  5577.2 1595.16  5618.0 1597.23  5689.4 1599.29
  5904.6 1608.73  5913.8 1609.93  5944.6 1610.77  6022.0 1615.04  6086.1 1619.60
#Mann=10,-1,0
  4104.9     0.1       0  4127.6    0.16       0  4312.8     0.1       0
  4426.9    0.16       0  4626.5    0.05       0  4808.5     0.1       0
  4992.8    0.07       0  4998.8     0.1       0  5944.6    0.05       0
  6022.0     0.1       0
Bank Sta=4992.8,4998.8
Exp/Cntr=0.3,0.1

Type RM Length L Ch R = 1,19287,657,657,657
BEGIN DESCRIPTION:
WITTINGTON CREEK 39.0
END DESCRIPTION:
XS GIS Cut Line= 2
      2837008.18     10072337.25      2835142.68     10072337.25
#Sta/Elev= 30
  4232.6 1605.57  4252.3 1604.97  4272.3 1603.54  4332.3 1602.45  4484.9 1597.56
  4583.5 1593.85  4632.3 1592.08  4772.3 1588.50  4805.5 1586.55  4842.3 1584.44
  4912.3 1581.89  4952.3 1579.84  4992.3 1579.61  4999.3 1578.89  5002.1 1578.39
  5005.3 1578.89  5022.3 1581.01  5032.3 1581.46  5092.3 1581.26  5122.3 1579.49
  5162.3 1579.10  5202.3 1582.51  5282.3 1586.37  5472.3 1593.34  5602.3 1598.88
  5672.3 1601.05  5902.3 1609.94  6022.3 1616.75  6082.3 1619.39  6098.1 1620.79
#Mann=6,-1,0
  4232.6    0.05       0  4484.9     0.1       0  4583.5    0.05       0
  4805.5     0.1       0  4999.3    0.07       0  5005.3     0.1       0
Bank Sta=4999.3,5005.3
Exp/Cntr=0.3,0.1

Type RM Length L Ch R = 1,18630,743,743,743
BEGIN DESCRIPTION:
WITTINGTON CREEK 38.0
END DESCRIPTION:
XS GIS Cut Line= 2
      2836769.49     10071794.72      2835326.32     10071577.70
#Sta/Elev= 30
  4409.1 1591.24  4501.2 1587.22  4516.5 1585.87  4571.9 1584.25  4592.2 1582.81
  4693.3 1580.14  4787.5 1576.52  4814.6 1576.91  4856.5 1575.77  4895.5 1575.50
  4966.3 1570.61  4993.7 1569.56  4996.4 1569.06  4999.7 1569.56  5047.2 1570.21
  5117.4 1573.21  5122.5 1572.84  5168.6 1574.99  5324.5 1579.35  5393.5 1582.97
  5431.5 1585.41  5457.4 1587.66  5462.5 1587.43  5526.4 1590.44  5613.5 1598.54
  5704.5 1604.87  5785.4 1608.58  5805.7 1610.37  5825.9 1610.85  5868.5 1612.91
#Mann=3,-1,0
  4409.1     0.1       0  4993.7    0.07       0  4999.7     0.1       0
Bank Sta=4993.7,4999.7
Exp/Cntr=0.3,0.1

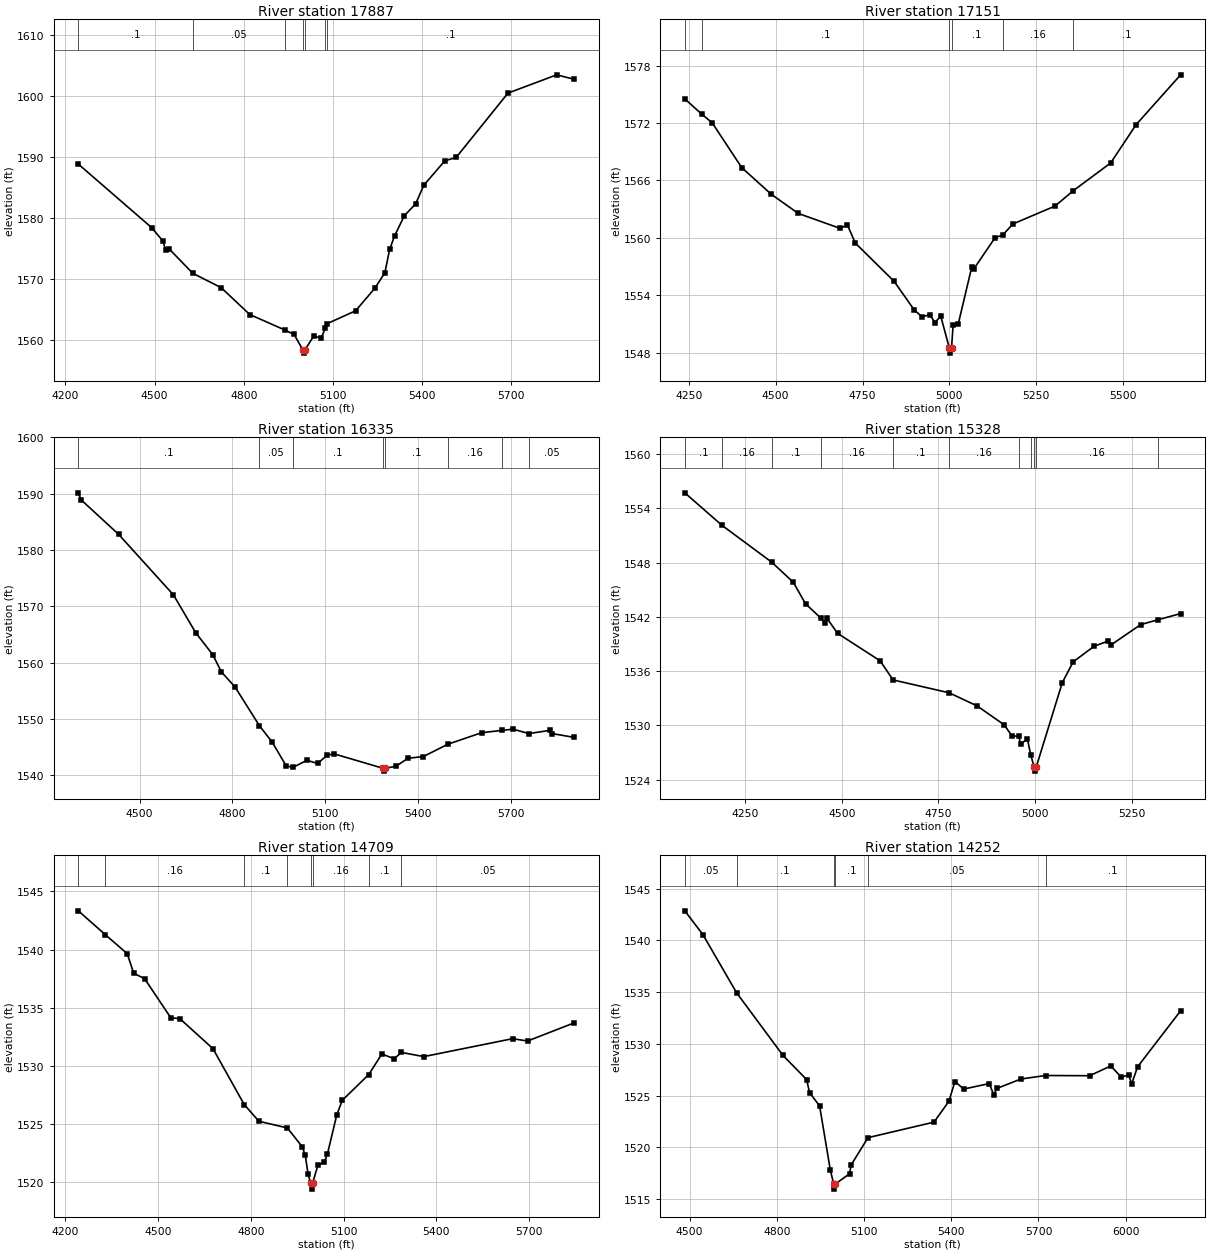
Type RM Length L Ch R = 1,17887,736,736,736
BEGIN DESCRIPTION:
WITTINGTON CREEK 36.0
END DESCRIPTION:
XS GIS Cut Line= 2
      2837029.93     10071230.49      2835434.89     10070742.21
#Sta/Elev= 30
  4243.2 1588.80  4489.4 1578.40  4527.4 1576.21  4537.6 1574.64  4548.0 1574.93
  4628.0 1570.90  4724.0 1568.53  4819.9 1564.13  4939.5 1561.56  4969.1 1560.86
  4998.9 1558.30  5001.6 1557.80  5004.9 1558.30  5034.6 1560.55  5060.5 1560.31
  5074.7 1561.92  5081.1 1562.65  5176.2 1564.75  5241.7 1568.50  5274.5 1570.99
  5290.5 1574.80  5307.2 1577.04  5340.0 1580.33  5378.0 1582.28  5405.5 1585.34
  5476.3 1589.34  5514.3 1589.89  5688.6 1600.44  5852.5 1603.44  5911.3 1602.71
#Mann=7,-1,0
  4243.2     0.1       0  4628.0    0.05       0  4939.5     0.1       0
  4998.9    0.07       0  5004.9     0.1       0  5074.7    0.05       0
  5081.1     0.1       0
Bank Sta=4998.9,5004.9
Exp/Cntr=0.3,0.1

Type RM Length L Ch R = 1,17151,816,816,816
BEGIN DESCRIPTION:
WITTINGTON CREEK 34.0
END DESCRIPTION:
XS GIS Cut Line= 4
      2837117.16     10070806.39      2836789.48     10070454.84
      2836437.92     10070279.06      2835892.25     10070372.17
#Sta/Elev= 30
  4238.4 1574.53  4287.4 1572.92  4317.2 1572.03  4402.2 1567.35  4487.2 1564.56
  4564.9 1562.56  4685.1 1561.00  4706.6 1561.34  4729.2 1559.46  4841.0 1555.46
  4899.0 1552.46  4921.4 1551.76  4943.7 1551.97  4958.4 1551.15  4975.1 1551.83
  5000.1 1548.46  5002.8 1547.96  5006.1 1548.46  5010.8 1550.93  5025.5 1551.00
  5064.6 1556.99  5070.2 1556.75  5131.8 1560.04  5153.4 1560.29  5182.5 1561.45
  5304.2 1563.33  5356.5 1564.93  5464.2 1567.83  5537.6 1571.84  5665.6 1577.04
#Mann=6,-1,0
  4238.4    0.05       0  4287.4     0.1       0  5000.1    0.07       0
  5006.1     0.1       0  5153.4    0.16       0  5356.5     0.1       0
Bank Sta=5000.1,5006.1
Exp/Cntr=0.3,0.1

Type RM Length L Ch R = 1,16335,1007,1007,1007
BEGIN DESCRIPTION:
WITTINGTON CREEK 33.0
END DESCRIPTION:
XS GIS Cut Line= 2
      2837724.33     10070091.15      2836303.19     10069353.46
#Sta/Elev= 30
  4302.2 1590.17  4310.9 1588.94  4432.4 1582.79  4609.4 1572.04  4681.4 1565.32
  4736.4 1561.42  4764.2 1558.37  4808.4 1555.68  4887.1 1548.81  4928.5 1545.87
  4973.6 1541.67  4995.9 1541.43  5040.5 1542.67  5075.0 1542.11  5106.8 1543.62
  5129.0 1543.80  5286.4 1541.25  5289.2 1540.75  5292.4 1541.25  5328.0 1541.61
  5366.6 1543.03  5416.5 1543.34  5495.2 1545.52  5604.3 1547.57  5669.3 1547.98
  5705.9 1548.20  5757.1 1547.42  5825.5 1547.99  5831.2 1547.43  5903.4 1546.74
#Mann=8,-1,0
  4302.2     0.1       0  4887.1    0.05       0  4995.9     0.1       0
  5286.4    0.07       0  5292.4     0.1       0  5495.2    0.16       0
  5669.3     0.1       0  5757.1    0.05       0
Bank Sta=5286.4,5292.4
Exp/Cntr=0.3,0.1

Type RM Length L Ch R = 1,15328,619,619,619
BEGIN DESCRIPTION:
WITTINGTON CREEK 31.0
END DESCRIPTION:
XS GIS Cut Line= 4
      2837724.82     10069072.46      2837375.42     10068957.44
      2836737.40     10068920.55      2836553.17     10069124.28
#Sta/Elev= 30
  4094.4 1555.73  4190.6 1552.13  4318.7 1548.07  4374.8 1545.84  4406.4 1543.46
  4445.5 1541.89  4455.9 1541.33  4462.2 1541.83  4489.2 1540.19  4599.4 1537.14
  4632.7 1535.03  4777.4 1533.61  4849.8 1532.16  4920.0 1530.06  4940.0 1528.84
  4957.9 1528.79  4962.3 1527.95  4980.1 1528.48  4988.7 1526.71  4997.1 1525.44
  4999.8 1524.94  5003.1 1525.44  5070.2 1534.74  5098.3 1537.03  5152.4 1538.76
  5187.5 1539.31  5195.0 1538.87  5272.7 1541.15  5318.4 1541.70  5376.0 1542.37
#Mann=11,-1,0
  4094.4     0.1       0  4190.6    0.16       0  4318.7     0.1       0
  4445.5    0.16       0  4632.7     0.1       0  4777.4    0.16       0
  4957.9     0.1       0  4988.7    0.16       0  4997.1    0.07       0
  5003.1    0.16       0  5318.4     0.1       0
Bank Sta=4997.1,5003.1
Exp/Cntr=0.3,0.1

Type RM Length L Ch R = 1,14709,457,457,457
BEGIN DESCRIPTION:
WITTINGTON CREEK 30.0
END DESCRIPTION:
XS GIS Cut Line= 4
      2837505.65     10068807.74      2837171.43     10068386.70
      2836761.27     10068310.74      2836150.94     10068529.34
#Sta/Elev= 30
  4242.7 1543.33  4329.9 1541.28  4400.8 1539.65  4421.7 1537.96  4456.9 1537.50
  4541.8 1534.13  4570.6 1534.07  4678.0 1531.48  4779.0 1526.68  4826.5 1525.24
  4918.5 1524.67  4966.3 1523.06  4976.5 1522.31  4985.2 1520.73  4993.9 1519.91
  4996.6 1519.41  4999.9 1519.91  5017.2 1521.46  5037.5 1521.70  5048.2 1522.45
  5078.2 1525.79  5096.0 1527.04  5181.6 1529.26  5224.0 1531.02  5264.1 1530.62
  5287.0 1531.16  5359.7 1530.80  5646.5 1532.34  5695.0 1532.14  5845.7 1533.70
#Mann=8,-1,0
  4242.7     0.1       0  4329.9    0.16       0  4779.0     0.1       0
  4918.5    0.16       0  4993.9    0.07       0  4999.9    0.16       0
  5181.6     0.1       0  5287.0    0.05       0
Bank Sta=4993.9,4999.9
Exp/Cntr=0.3,0.1

Type RM Length L Ch R = 1,14252,619,619,619
BEGIN DESCRIPTION:
WITTINGTON CREEK 28.0
END DESCRIPTION:
XS GIS Cut Line= 3
      2837709.65     10068067.69      2836845.91     10067898.42
      2836045.10     10068098.07
#Sta/Elev= 30
  4483.5 1542.87  4545.8 1540.57  4662.0 1534.93  4821.0 1528.89  4902.5 1526.55
  4912.7 1525.28  4947.2 1524.00  4984.0 1517.80  4995.7 1516.45  4998.4 1515.95
  5001.7 1516.45  5050.2 1517.44  5055.4 1518.28  5113.7 1520.93  5340.7 1522.43
  5392.0 1524.45  5412.6 1526.36  5443.0 1525.63  5530.7 1526.16  5546.5 1525.06
  5556.9 1525.69  5639.3 1526.60  5724.4 1526.94  5876.3 1526.92  5948.7 1527.87
  5984.8 1526.78  6010.3 1527.00  6020.6 1526.13  6041.2 1527.79  6189.0 1533.20
#Mann=6,-1,0
  4483.5    0.05       0  4662.0     0.1       0  4995.7    0.07       0
  5001.7     0.1       0  5113.7    0.05       0  5724.4     0.1       0
Bank Sta=4995.7,5001.7
Exp/Cntr=0.3,0.1

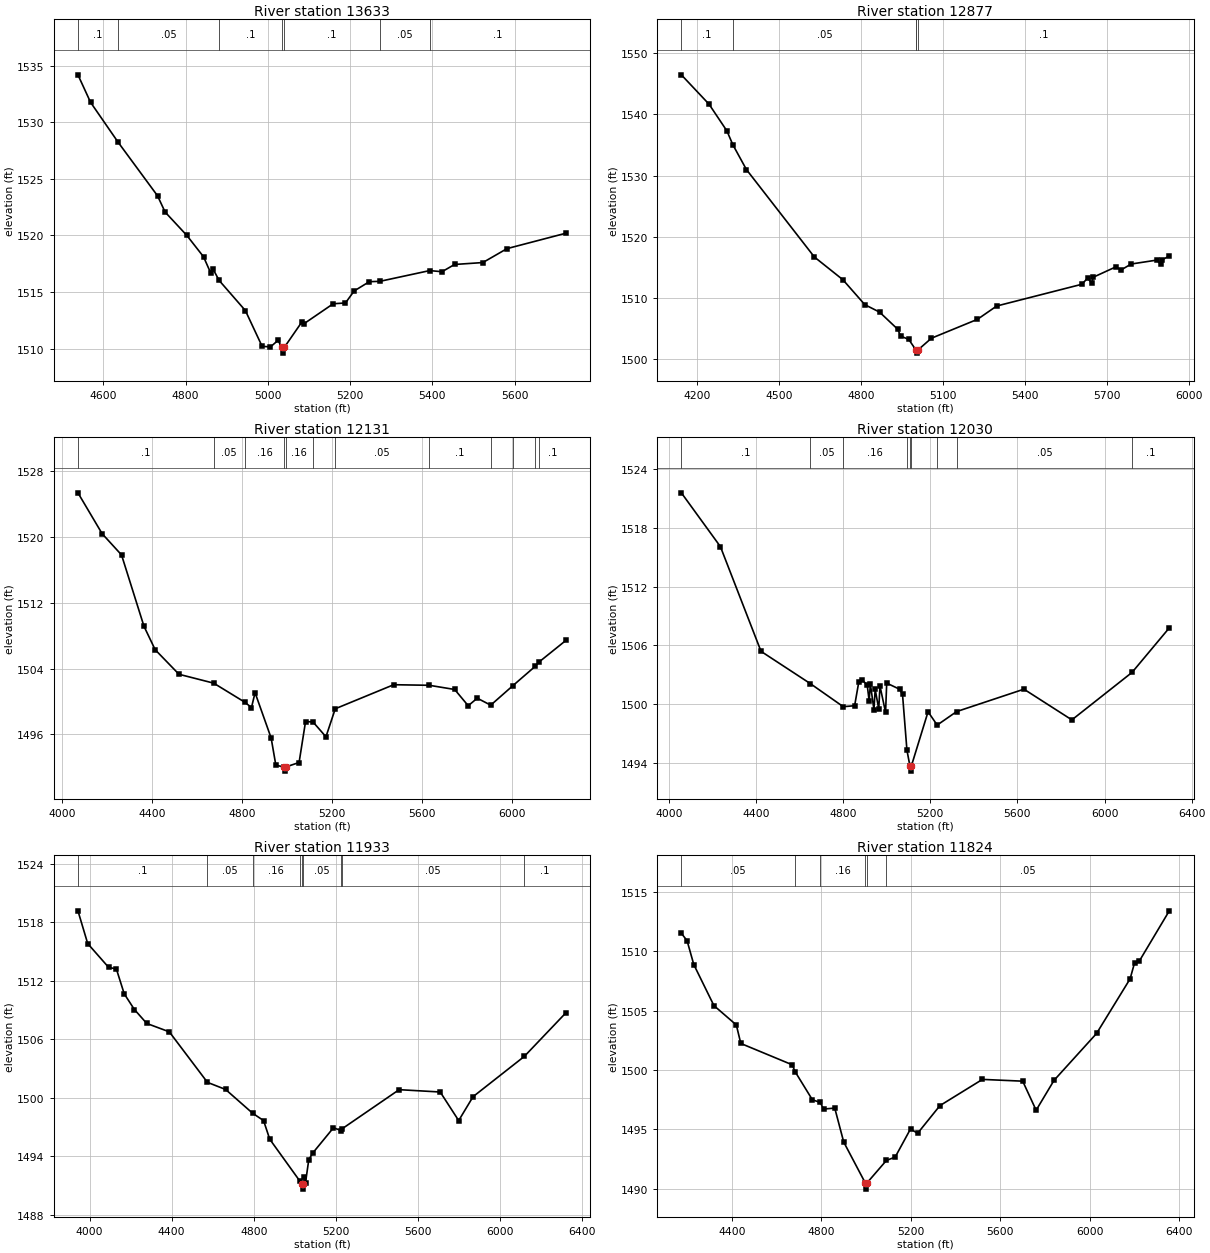
Type RM Length L Ch R = 1,13633,756,756,756
BEGIN DESCRIPTION:
WITTINGTON CREEK 27.0
END DESCRIPTION:
XS GIS Cut Line= 3
      2837798.65     10067457.89      2836874.98     10067286.89
      2836733.86     10067489.29
#Sta/Elev= 30
  4538.5 1534.19  4569.2 1531.76  4636.3 1528.23  4731.9 1523.51  4750.4 1522.07
  4803.1 1520.01  4843.8 1518.12  4861.2 1516.69  4866.3 1517.08  4881.5 1516.04
  4945.5 1513.37  4986.2 1510.21  5006.5 1510.16  5025.0 1510.74  5034.0 1510.11
  5036.8 1509.61  5040.0 1510.11  5083.0 1512.37  5088.1 1512.21  5159.0 1513.97
  5188.8 1514.04  5209.9 1515.10  5246.8 1515.92  5272.3 1515.95  5393.6 1516.90
  5423.5 1516.80  5454.0 1517.44  5522.8 1517.61  5581.5 1518.84  5724.6 1520.20
#Mann=7,-1,0
  4538.5     0.1       0  4636.3    0.05       0  4881.5     0.1       0
  5034.0    0.07       0  5040.0     0.1       0  5272.3    0.05       0
  5393.6     0.1       0
Bank Sta=5034,5040
Exp/Cntr=0.3,0.1

Type RM Length L Ch R = 1,12877,746,746,746
BEGIN DESCRIPTION:
WITTINGTON CREEK 25.0
END DESCRIPTION:
XS GIS Cut Line= 4
      2838302.11     10066800.34      2837850.68     10066613.69
      2837180.11     10066685.31      2836837.25     10067206.10
#Sta/Elev= 30
  4140.9 1546.50  4242.2 1541.69  4307.4 1537.33  4329.5 1535.04  4379.1 1530.98
  4627.9 1516.65  4732.2 1512.93  4812.6 1508.84  4866.6 1507.62  4933.3 1504.80
  4943.4 1503.70  4973.6 1503.14  4999.5 1501.42  5000.7 1501.40  5003.5 1500.90
  5006.7 1501.40  5056.3 1503.34  5225.0 1506.44  5295.4 1508.62  5607.0 1512.18
  5628.1 1513.18  5643.2 1512.40  5649.1 1513.34  5730.5 1515.01  5751.6 1514.55
  5787.7 1515.50  5881.1 1516.14  5896.2 1515.45  5902.2 1516.22  5927.3 1516.81
#Mann=5,-1,0
  4140.9     0.1       0  4329.5    0.05       0  4999.5     0.1       0
  5000.7    0.07       0  5006.7     0.1       0
Bank Sta=5000.7,5006.7
Exp/Cntr=0.3,0.1

Type RM Length L Ch R = 1,12131,101,101,101
BEGIN DESCRIPTION:
WITTINGTON CREEK 24.0
END DESCRIPTION:
XS GIS Cut Line= 4
      2838050.36     10066453.13      2837451.37     10065980.01
      2837184.45     10065927.93      2836055.98     10065843.29
#Sta/Elev= 30
  4072.1 1525.40  4179.4 1520.43  4265.7 1517.84  4365.4 1509.15  4415.1 1506.30
  4520.8 1503.31  4675.0 1502.23  4813.2 1499.91  4842.8 1499.26  4858.7 1501.07
  4930.1 1495.55  4951.0 1492.24  4988.2 1492.02  4990.9 1491.52  4994.2 1492.02
  5054.2 1492.57  5082.9 1497.56  5116.2 1497.50  5173.5 1495.70  5214.8 1499.11
  5474.4 1502.04  5632.2 1501.97  5745.1 1501.46  5805.3 1499.48  5845.4 1500.40
  5905.2 1499.55  6003.9 1501.93  6102.5 1504.27  6119.6 1504.80  6239.0 1507.43
#Mann=12,-1,0
  4072.1     0.1       0  4675.0    0.05       0  4813.2    0.16       0
  4988.2    0.07       0  4994.2    0.16       0  5116.2     0.1       0
  5214.8    0.05       0  5632.2     0.1       0  5905.2    0.05       0
  6003.9     0.1       0  6102.5    0.05       0  6119.6     0.1       0
Bank Sta=4988.2,4994.2
Exp/Cntr=0.3,0.1

Type RM Length L Ch R = 1,12030,97,97,97
BEGIN DESCRIPTION:
Mapping XS 7659b7e6
END DESCRIPTION:
XS GIS Cut Line= 6
      2838076.41     10066375.01      2837412.31     10065901.89
      2837321.17     10065854.14      2837273.42     10065841.12
      2837227.85     10065841.12      2836001.47     10065797.79
#Sta/Elev= 30
  4056.8 1521.60  4236.1 1516.10  4422.6 1505.39  4649.0 1502.09  4800.2 1499.73
  4852.4 1499.83  4871.5 1502.25  4887.8 1502.48  4910.4 1501.91  4919.1 1500.32
  4924.7 1502.05  4941.1 1499.42  4946.8 1501.49  4963.2 1499.50  4968.8 1501.84
  4994.5 1499.15  4999.7 1502.14  5059.5 1501.51  5072.3 1500.99  5092.6 1495.28
  5106.6 1493.64  5109.3 1493.14  5112.6 1493.64  5189.6 1499.21  5231.5 1497.85
  5320.8 1499.23  5629.9 1501.52  5850.0 1498.38  6126.5 1503.24  6297.3 1507.79
#Mann=9,-1,0
  4056.8     0.1       0  4649.0    0.05       0  4800.2    0.16       0
  5092.6    0.05       0  5106.6    0.07       0  5112.6    0.05       0
  5231.5     0.1       0  5320.8    0.05       0  6126.5     0.1       0
Bank Sta=5106.6,5112.6
Exp/Cntr=0.3,0.1

Type RM Length L Ch R = 1,11933,109,109,109
BEGIN DESCRIPTION:
Mapping XS 5826cba7
END DESCRIPTION:
XS GIS Cut Line= 4
      2838230.50     10066155.82      2837460.05     10065745.64
      2836954.41     10065773.85      2835956.17     10065773.85
#Sta/Elev= 30
  3943.3 1519.19  3990.9 1515.83  4092.9 1513.39  4130.6 1513.23  4168.8 1510.68
  4218.4 1509.07  4278.7 1507.64  4388.5 1506.78  4574.3 1501.60  4662.8 1500.87
  4794.6 1498.43  4847.8 1497.68  4877.8 1495.77  5024.8 1491.47  5035.1 1491.15
  5037.8 1490.65  5041.1 1491.15  5047.1 1491.91  5052.1 1491.31  5068.1 1493.67
  5088.1 1494.37  5188.3 1496.94  5226.0 1496.66  5230.0 1496.83  5508.5 1500.85
  5708.5 1500.61  5798.5 1497.68  5868.5 1500.13  6118.3 1504.26  6320.8 1508.73
#Mann=9,-1,0
  3943.3     0.1       0  4574.3    0.05       0  4794.6    0.16       0
  5024.8    0.05       0  5035.1    0.07       0  5041.1    0.05       0
  5226.0     0.1       0  5230.0    0.05       0  6118.3     0.1       0
Bank Sta=5035.1,5041.1
Exp/Cntr=0.3,0.1

Type RM Length L Ch R = 1,11824,360,360,360
BEGIN DESCRIPTION:
WITTINGTON CREEK 23.0
END DESCRIPTION:
XS GIS Cut Line= 2
      2838104.10     10065664.08      2835923.34     10065631.53
#Sta/Elev= 30
  4175.0 1511.52  4200.6 1510.89  4230.6 1508.88  4320.6 1505.42  4420.7 1503.79
  4440.7 1502.23  4670.7 1500.43  4683.2 1499.86  4760.7 1497.48  4795.8 1497.26
  4810.7 1496.70  4860.7 1496.78  4900.7 1493.92  4997.7 1490.45  5000.5 1489.95
  5003.7 1490.45  5091.6 1492.37  5130.7 1492.65  5199.5 1495.03  5230.8 1494.65
  5330.8 1496.99  5520.8 1499.20  5700.8 1499.05  5760.8 1496.60  5840.8 1499.12
  6030.8 1503.07  6180.9 1507.68  6200.9 1509.04  6220.9 1509.14  6356.0 1513.41
#Mann=6,-1,0
  4175.0    0.05       0  4683.2     0.1       0  4795.8    0.16       0
  4997.7    0.07       0  5003.7    0.16       0  5091.6    0.05       0
Bank Sta=4997.7,5003.7
Exp/Cntr=0.3,0.1

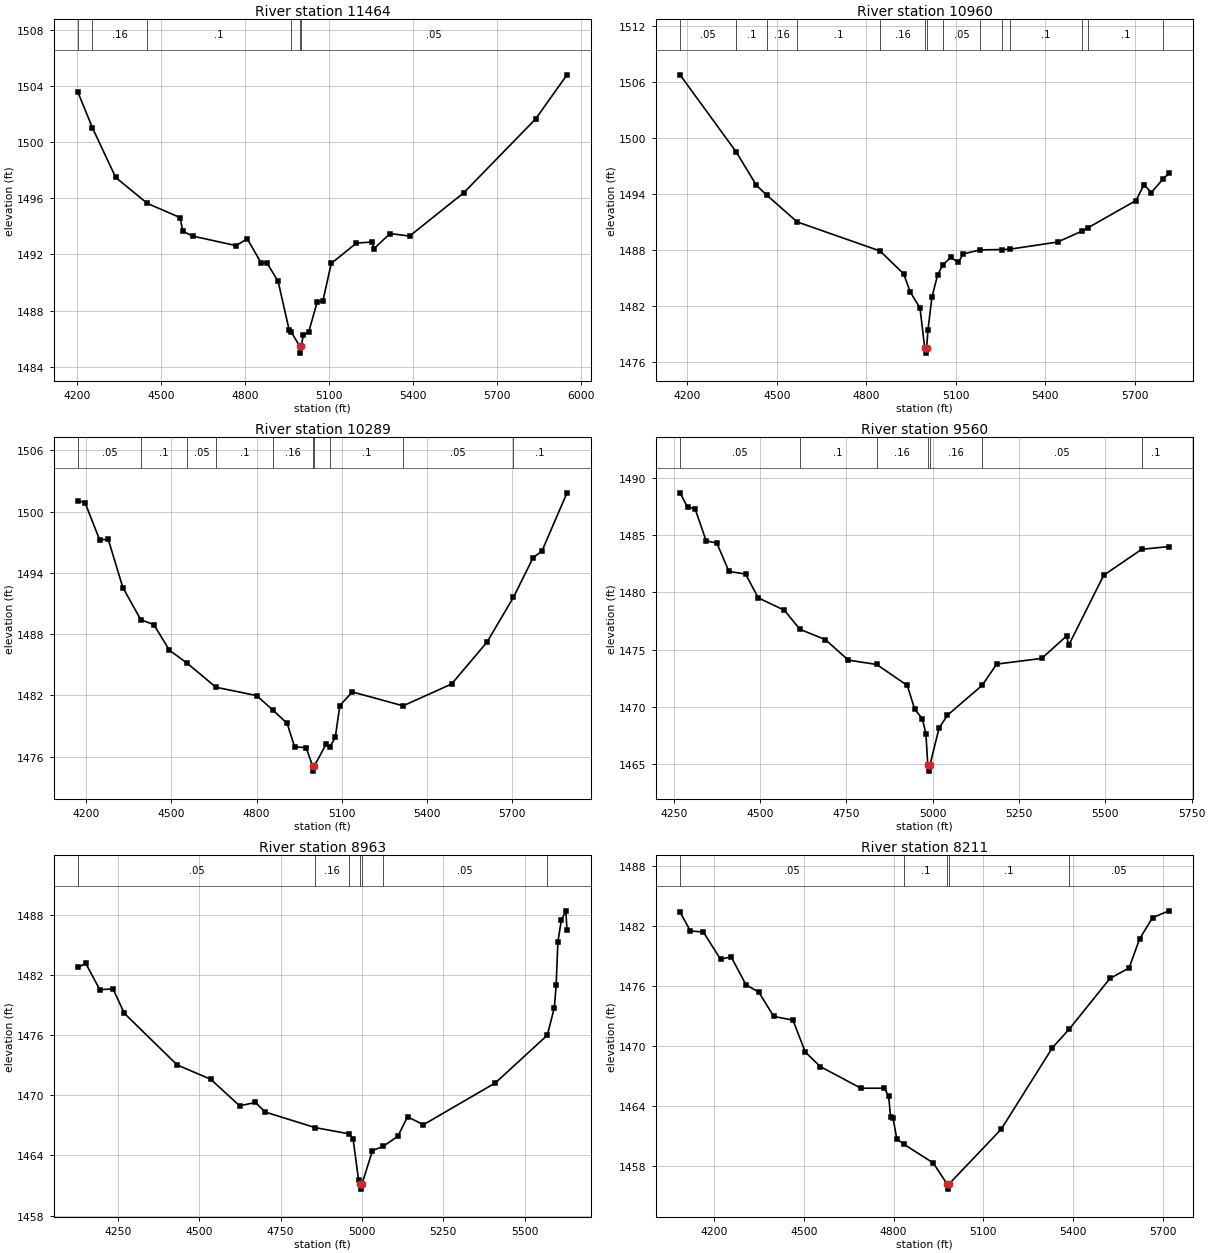
Type RM Length L Ch R = 1,11464,504,504,504
BEGIN DESCRIPTION:
WITTINGTON CREEK 22.0
END DESCRIPTION:
XS GIS Cut Line= 2
      2837963.10     10065306.00      2836216.15     10065360.26
#Sta/Elev= 30
  4203.1 1503.55  4254.8 1501.02  4337.8 1497.49  4450.7 1495.64  4567.9 1494.63
  4577.9 1493.65  4613.0 1493.31  4768.0 1492.63  4808.0 1493.12  4858.1 1491.38
  4878.1 1491.40  4918.1 1490.10  4958.1 1486.60  4965.2 1486.48  4995.1 1485.47
  4997.9 1484.97  5001.1 1485.47  5008.1 1486.23  5028.1 1486.51  5058.2 1488.62
  5078.2 1488.67  5108.2 1491.36  5198.2 1492.81  5255.4 1492.89  5260.4 1492.40
  5318.3 1493.49  5388.3 1493.31  5581.5 1496.39  5838.5 1501.65  5950.9 1504.80
#Mann=6,-1,0
  4203.1     0.1       0  4254.8    0.16       0  4450.7     0.1       0
  4965.2    0.05       0  4995.1    0.03       0  5001.1    0.05       0
Bank Sta=4995.1,5001.1
Exp/Cntr=0.3,0.1

Type RM Length L Ch R = 1,10960,671,671,671
BEGIN DESCRIPTION:
WITTINGTON CREEK 21.0
END DESCRIPTION:
XS GIS Cut Line= 2
      2838082.45     10065132.40      2836521.65     10064633.81
#Sta/Elev= 30
  4175.8 1506.75  4364.1 1498.50  4431.9 1494.93  4466.3 1493.89  4568.5 1491.02
  4846.2 1487.91  4925.3 1485.46  4947.6 1483.49  4979.8 1481.83  4995.8 1477.49
  4998.6 1476.99  5001.8 1477.49  5006.7 1479.50  5019.8 1482.97  5038.9 1485.36
  5055.7 1486.39  5082.8 1487.23  5108.5 1486.69  5124.8 1487.60  5181.5 1488.03
  5255.4 1488.07  5280.3 1488.10  5440.8 1488.87  5522.1 1490.03  5542.4 1490.39
  5703.5 1493.31  5730.4 1495.01  5754.7 1494.16  5794.6 1495.62  5814.3 1496.22
#Mann=14,-1,0
  4175.8    0.05       0  4364.1     0.1       0  4466.3    0.16       0
  4568.5     0.1       0  4846.2    0.16       0  4995.8    0.07       0
  5001.8    0.16       0  5055.7    0.05       0  5181.5     0.1       0
  5255.4    0.05       0  5280.3     0.1       0  5522.1    0.05       0
  5542.4     0.1       0  5794.6    0.05       0
Bank Sta=4995.8,5001.8
Exp/Cntr=0.3,0.1

Type RM Length L Ch R = 1,10289,729,729,729
BEGIN DESCRIPTION:
WITTINGTON CREEK 19.0
END DESCRIPTION:
XS GIS Cut Line= 2
      2838212.63     10064416.25      2836532.09     10064047.61
#Sta/Elev= 30
  4171.6 1501.08  4196.3 1500.88  4247.5 1497.25  4278.2 1497.27  4329.4 1492.56
  4392.4 1489.41  4438.5 1488.92  4493.2 1486.42  4556.8 1485.12  4656.9 1482.79
  4800.4 1481.97  4857.1 1480.55  4907.3 1479.26  4933.5 1476.96  4974.4 1476.86
  4997.1 1475.07  4999.8 1474.57  5003.1 1475.07  5043.9 1477.18  5058.4 1476.97
  5076.8 1477.88  5092.8 1480.99  5136.6 1482.33  5315.5 1480.97  5486.3 1483.11
  5610.6 1487.21  5703.6 1491.60  5773.0 1495.49  5803.7 1496.12  5892.1 1501.84
#Mann=10,-1,0
  4171.6    0.05       0  4392.4     0.1       0  4556.8    0.05       0
  4656.9     0.1       0  4857.1    0.16       0  4997.1    0.07       0
  5003.1    0.16       0  5058.4     0.1       0  5315.5    0.05       0
  5703.6     0.1       0
Bank Sta=4997.1,5003.1
Exp/Cntr=0.3,0.1

Type RM Length L Ch R = 1,9560,597,597,597
BEGIN DESCRIPTION:
WITTINGTON CREEK 18.0
END DESCRIPTION:
XS GIS Cut Line= 2
      2838288.59     10063830.31      2836975.75     10063298.67
#Sta/Elev= 30
  4268.1 1488.69  4289.8 1487.44  4311.4 1487.32  4343.8 1484.50  4374.8 1484.30
  4409.7 1481.83  4457.9 1481.60  4494.8 1479.52  4570.5 1478.44  4615.1 1476.78
  4689.0 1475.88  4755.5 1474.09  4837.5 1473.71  4926.3 1471.88  4947.9 1469.79
  4969.9 1468.97  4980.3 1467.67  4985.7 1464.90  4988.4 1464.40  4991.7 1464.90
  5018.2 1468.14  5042.3 1469.27  5143.2 1471.89  5185.3 1473.74  5315.7 1474.24
  5388.1 1476.20  5393.5 1475.37  5495.3 1481.50  5605.3 1483.76  5684.5 1484.00
#Mann=7,-1,0
  4268.1    0.05       0  4615.1     0.1       0  4837.5    0.16       0
  4985.7    0.07       0  4991.7    0.16       0  5143.2    0.05       0
  5605.3     0.1       0
Bank Sta=4985.7,4991.7
Exp/Cntr=0.3,0.1

Type RM Length L Ch R = 1,8963,752,752,752
BEGIN DESCRIPTION:
WITTINGTON CREEK 13.0
END DESCRIPTION:
XS GIS Cut Line= 2
      2838570.74     10063309.49      2837172.18     10062756.57
#Sta/Elev= 30
  4126.7 1482.74  4150.6 1483.14  4193.7 1480.52  4234.4 1480.59  4269.5 1478.15
  4431.8 1473.01  4534.6 1471.59  4623.8 1468.94  4672.5 1469.27  4702.2 1468.32
  4856.5 1466.76  4960.9 1466.14  4972.6 1465.67  4989.4 1461.57  4994.0 1461.13
  4996.7 1460.63  5000.0 1461.13  5032.4 1464.48  5065.2 1464.89  5110.5 1465.91
  5140.2 1467.85  5188.9 1467.05  5410.6 1471.23  5570.1 1475.98  5591.6 1478.73
  5597.2 1480.94  5602.6 1485.30  5613.1 1487.44  5627.0 1488.38  5630.6 1486.43
#Mann=7,-1,0
  4126.7    0.05       0  4856.5    0.16       0  4960.9     0.1       0
  4994.0    0.07       0  5000.0     0.1       0  5065.2    0.05       0
  5570.1     0.1       0
Bank Sta=4994,5000
Exp/Cntr=0.3,0.1

Type RM Length L Ch R = 1,8211,625,625,625
BEGIN DESCRIPTION:
WITTINGTON CREEK 12.0
END DESCRIPTION:
XS GIS Cut Line= 2
      2838885.33     10063016.48      2837606.35     10061997.62
#Sta/Elev= 30
  4085.6 1483.36  4120.2 1481.47  4163.5 1481.37  4221.1 1478.64  4256.4 1478.89
  4306.0 1476.11  4349.3 1475.36  4398.9 1472.94  4463.0 1472.58  4504.6 1469.38
  4554.6 1467.94  4690.4 1465.78  4768.9 1465.78  4783.3 1464.99  4789.7 1462.87
  4797.6 1462.85  4810.5 1460.72  4833.6 1460.20  4932.2 1458.32  4978.8 1456.21
  4981.6 1455.71  4984.8 1456.21  5159.6 1461.69  5331.0 1469.83  5386.9 1471.67
  5523.2 1476.73  5587.2 1477.78  5622.5 1480.69  5665.7 1482.80  5720.8 1483.48
#Mann=5,-1,0
  4085.6    0.05       0  4833.6     0.1       0  4978.8    0.07       0
  4984.8     0.1       0  5386.9    0.05       0
Bank Sta=4978.8,4984.8
Exp/Cntr=0.3,0.1

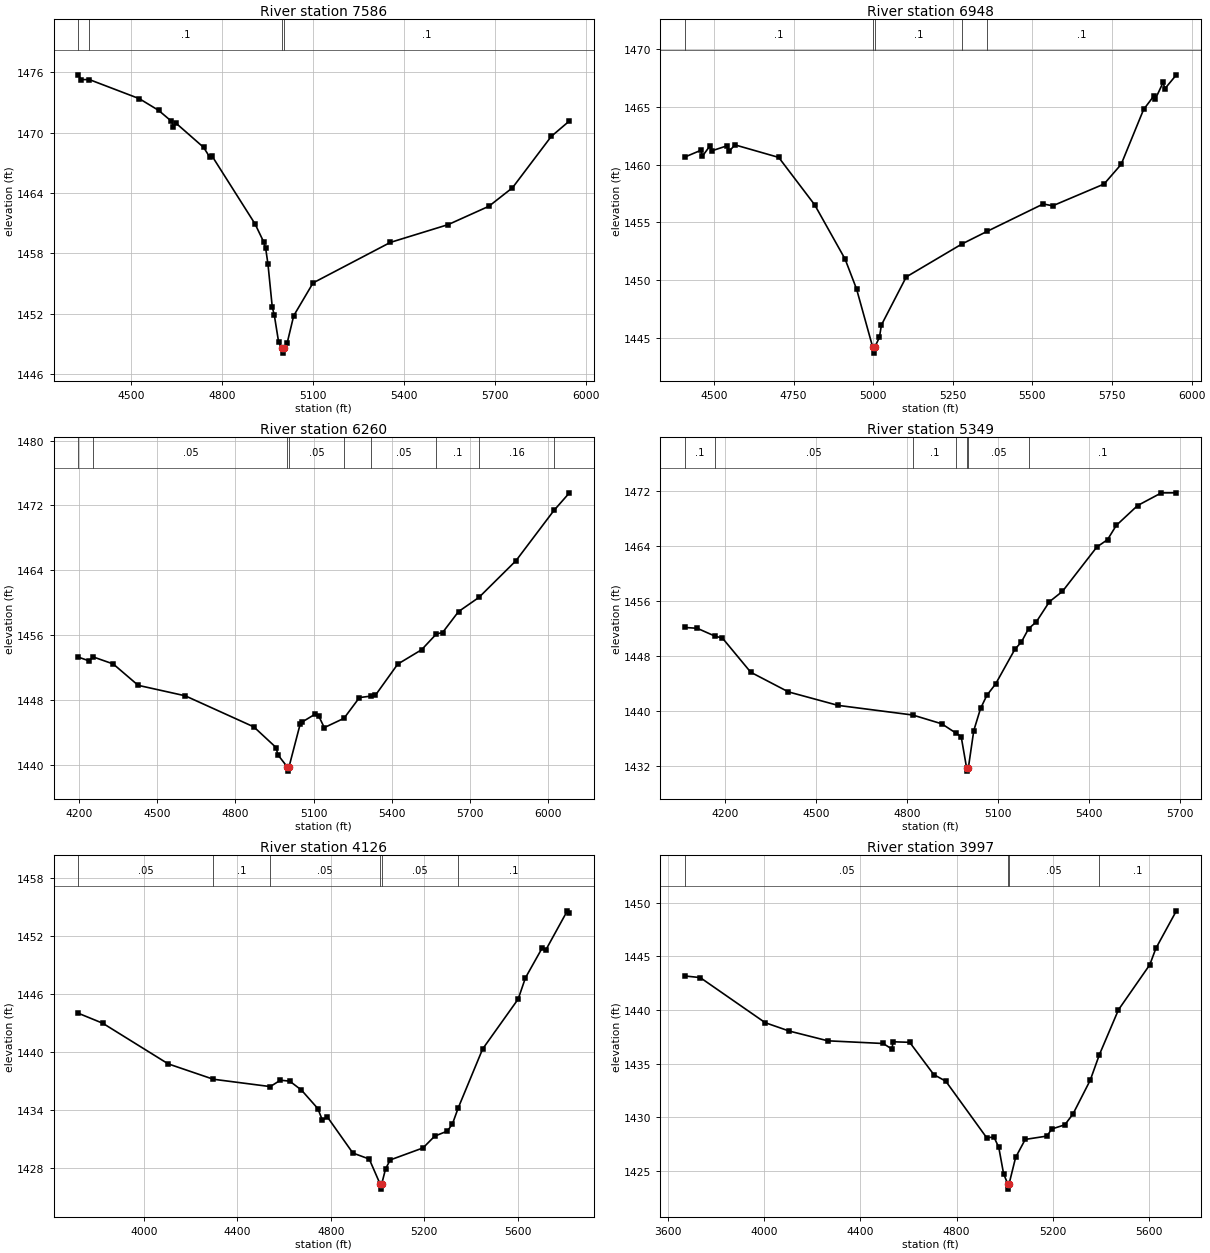
Type RM Length L Ch R = 1,7586,638,638,638
BEGIN DESCRIPTION:
WITTINGTON CREEK 11.0
END DESCRIPTION:
XS GIS Cut Line= 2
      2839221.73     10062615.02      2838006.44     10061540.79
#Sta/Elev= 30
  4324.5 1475.76  4334.8 1475.28  4361.3 1475.29  4526.3 1473.39  4589.9 1472.23
  4632.6 1471.14  4639.2 1470.61  4646.8 1470.97  4738.8 1468.54  4759.7 1467.54
  4767.2 1467.65  4908.6 1460.92  4937.0 1459.14  4943.7 1458.49  4951.3 1456.91
  4965.5 1452.63  4972.2 1451.84  4986.4 1449.17  4997.6 1448.56  5000.4 1448.06
  5003.6 1448.56  5014.8 1449.08  5036.2 1451.78  5100.2 1455.05  5355.3 1459.08
  5546.0 1460.85  5680.7 1462.68  5758.5 1464.52  5886.5 1469.63  5946.5 1471.17
#Mann=4,-1,0
  4324.5    0.05       0  4361.3     0.1       0  4997.6    0.07       0
  5003.6     0.1       0
Bank Sta=4997.6,5003.6
Exp/Cntr=0.3,0.1

Type RM Length L Ch R = 1,6948,688,688,688
BEGIN DESCRIPTION:
WITTINGTON CREEK 10.0
END DESCRIPTION:
XS GIS Cut Line= 2
      2839644.90     10061898.88      2838213.01     10061323.95
#Sta/Elev= 30
  4409.1 1460.66  4458.5 1461.23  4463.8 1460.73  4488.0 1461.64  4493.4 1461.19
  4541.8 1461.63  4547.2 1461.14  4566.0 1461.70  4703.2 1460.62  4816.1 1456.53
  4911.7 1451.84  4947.8 1449.25  4998.6 1444.22  5001.4 1443.72  5004.6 1444.22
  5019.5 1445.08  5025.8 1446.15  5103.8 1450.30  5279.0 1453.15  5358.9 1454.25
  5534.0 1456.60  5563.6 1456.44  5724.9 1458.32  5778.7 1460.02  5849.2 1464.76
  5880.9 1465.91  5886.3 1465.68  5910.5 1467.09  5915.9 1466.55  5952.1 1467.75
#Mann=5,-1,0
  4409.1     0.1       0  4998.6    0.07       0  5004.6     0.1       0
  5279.0    0.05       0  5358.9     0.1       0
Bank Sta=4998.6,5004.6
Exp/Cntr=0.3,0.1

Type RM Length L Ch R = 1,6260,911,911,911
BEGIN DESCRIPTION:
WITTINGTON CREEK 9.0
END DESCRIPTION:
XS GIS Cut Line= 2
      2840024.68     10061302.09      2838256.00     10060651.04
#Sta/Elev= 30
  4197.0 1453.29  4238.3 1452.83  4255.2 1453.30  4331.5 1452.44  4427.4 1449.80
  4607.6 1448.51  4871.1 1444.67  4957.1 1442.10  4962.5 1441.26  4999.8 1439.71
  5002.6 1439.21  5005.8 1439.71  5048.5 1444.98  5056.1 1445.27  5104.1 1446.20
  5120.0 1446.01  5141.3 1444.58  5216.9 1445.73  5276.2 1448.29  5320.5 1448.47
  5337.1 1448.56  5423.1 1452.42  5514.5 1454.19  5571.0 1456.13  5595.2 1456.32
  5656.2 1458.90  5734.5 1460.65  5876.6 1465.18  6022.1 1471.38  6081.7 1473.56
#Mann=9,-1,0
  4197.0     0.1       0  4255.2    0.05       0  4999.8    0.04       0
  5005.8    0.05       0  5216.9     0.1       0  5320.5    0.05       0
  5571.0     0.1       0  5734.5    0.16       0  6022.1     0.1       0
Bank Sta=4999.8,5005.8
Exp/Cntr=0.3,0.1

Type RM Length L Ch R = 1,5349,1223,1223,1223
BEGIN DESCRIPTION:
WITTINGTON CREEK 8.0
END DESCRIPTION:
XS GIS Cut Line= 3
      2840258.09     10060942.50      2840165.75     10060607.65
      2839178.36     10059804.72
#Sta/Elev= 30
  4068.8 1452.14  4109.0 1452.02  4168.1 1450.87  4192.0 1450.60  4285.4 1445.63
  4409.8 1442.77  4573.3 1440.81  4819.5 1439.41  4915.3 1438.13  4961.9 1436.78
  4979.2 1436.28  4997.0 1431.75  4999.7 1431.25  5003.0 1431.75  5020.8 1437.15
  5043.1 1440.36  5063.9 1442.27  5092.7 1443.92  5156.6 1448.99  5177.4 1450.00
  5201.6 1451.97  5226.9 1452.95  5270.1 1455.88  5313.2 1457.39  5426.6 1463.84
  5461.8 1464.91  5490.6 1466.98  5560.9 1469.87  5639.2 1471.71  5688.8 1471.72
#Mann=7,-1,0
  4068.8     0.1       0  4168.1    0.05       0  4819.5     0.1       0
  4961.9    0.05       0  4997.0    0.04       0  5003.0    0.05       0
  5201.6     0.1       0
Bank Sta=4997,5003
Exp/Cntr=0.3,0.1

Type RM Length L Ch R = 1,4126,129,129,129
BEGIN DESCRIPTION:
WITTINGTON CREEK 6.0
END DESCRIPTION:
XS GIS Cut Line= 3
      2840654.06     10060809.01      2840678.53     10059229.51
      2840193.60     10059035.99
#Sta/Elev= 30
  3719.3 1444.01  3824.6 1442.97  4104.6 1438.77  4297.7 1437.18  4541.3 1436.42
  4584.7 1437.08  4624.7 1436.98  4674.7 1436.06  4744.7 1434.15  4764.7 1432.92
  4784.7 1433.31  4894.7 1429.55  4964.7 1428.93  5011.7 1426.32  5014.5 1425.82
  5017.7 1426.32  5034.7 1427.93  5054.7 1428.84  5194.8 1430.08  5244.8 1431.30
  5299.0 1431.82  5320.6 1432.56  5345.1 1434.20  5449.8 1440.31  5601.9 1445.47
  5632.8 1447.66  5704.3 1450.74  5719.0 1450.50  5812.1 1454.59  5821.1 1454.41
#Mann=6,-1,0
  3719.3    0.05       0  4297.7     0.1       0  4541.3    0.05       0
  5011.7    0.04       0  5017.7    0.05       0  5345.1     0.1       0
Bank Sta=5011.7,5017.7
Exp/Cntr=0.3,0.1

Type RM Length L Ch R = 1,3997,558,558,558
BEGIN DESCRIPTION:
Mapping XS 403d51d1
END DESCRIPTION:
XS GIS Cut Line= 3
      2840758.61     10060766.69      2840767.51     10059189.47
      2840332.48     10059029.66
#Sta/Elev= 30
  3672.1 1443.17  3735.1 1443.02  4005.1 1438.81  4105.1 1438.03  4265.1 1437.12
  4495.1 1436.87  4531.2 1436.35  4536.2 1437.03  4605.1 1436.98  4705.1 1433.97
  4755.1 1433.35  4925.1 1428.07  4955.1 1428.14  4975.1 1427.18  4995.1 1424.72
  5012.1 1423.78  5014.8 1423.28  5018.1 1423.78  5045.1 1426.24  5085.1 1427.92
  5175.1 1428.23  5195.1 1428.89  5249.3 1429.28  5283.1 1430.28  5354.9 1433.44
  5392.9 1435.82  5472.1 1440.01  5602.4 1444.22  5627.5 1445.74  5712.8 1449.25
#Mann=4,-1,0
  3672.1    0.05       0  5012.1    0.04       0  5018.1    0.05       0
  5392.9     0.1       0
Bank Sta=5012.1,5018.1
Exp/Cntr=0.3,0.1