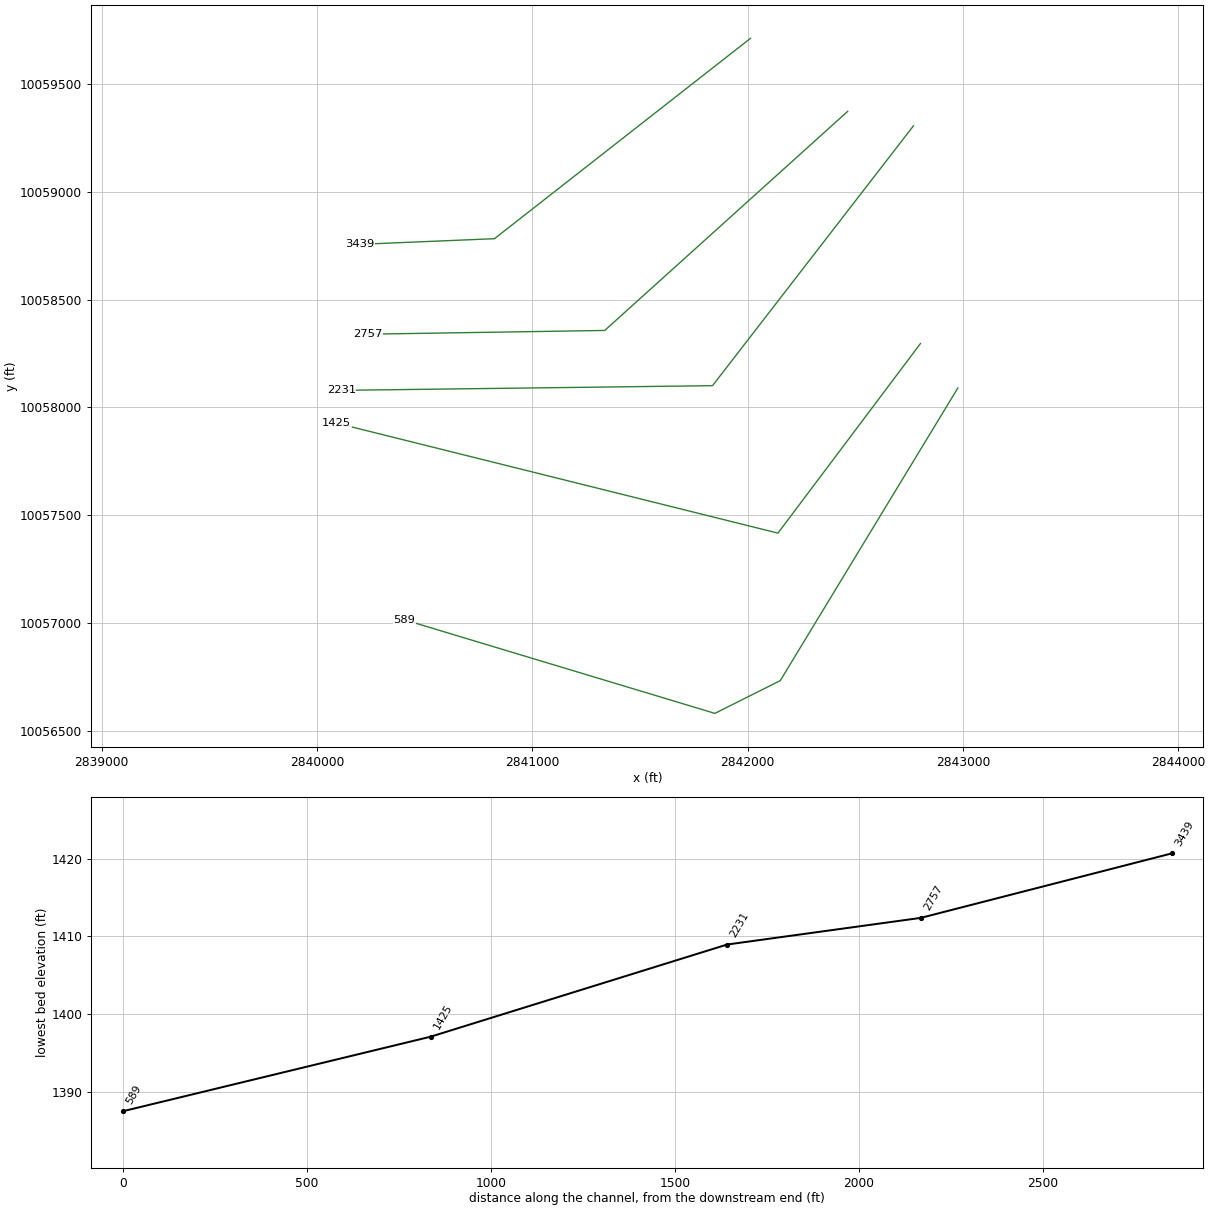
HEC-RAS study WITTINGTON CREEK.prj: WITTINGTON CREEK Base Level Engineering

--- WITTINGTON CREEK.g01 (geometry) --- (continued)

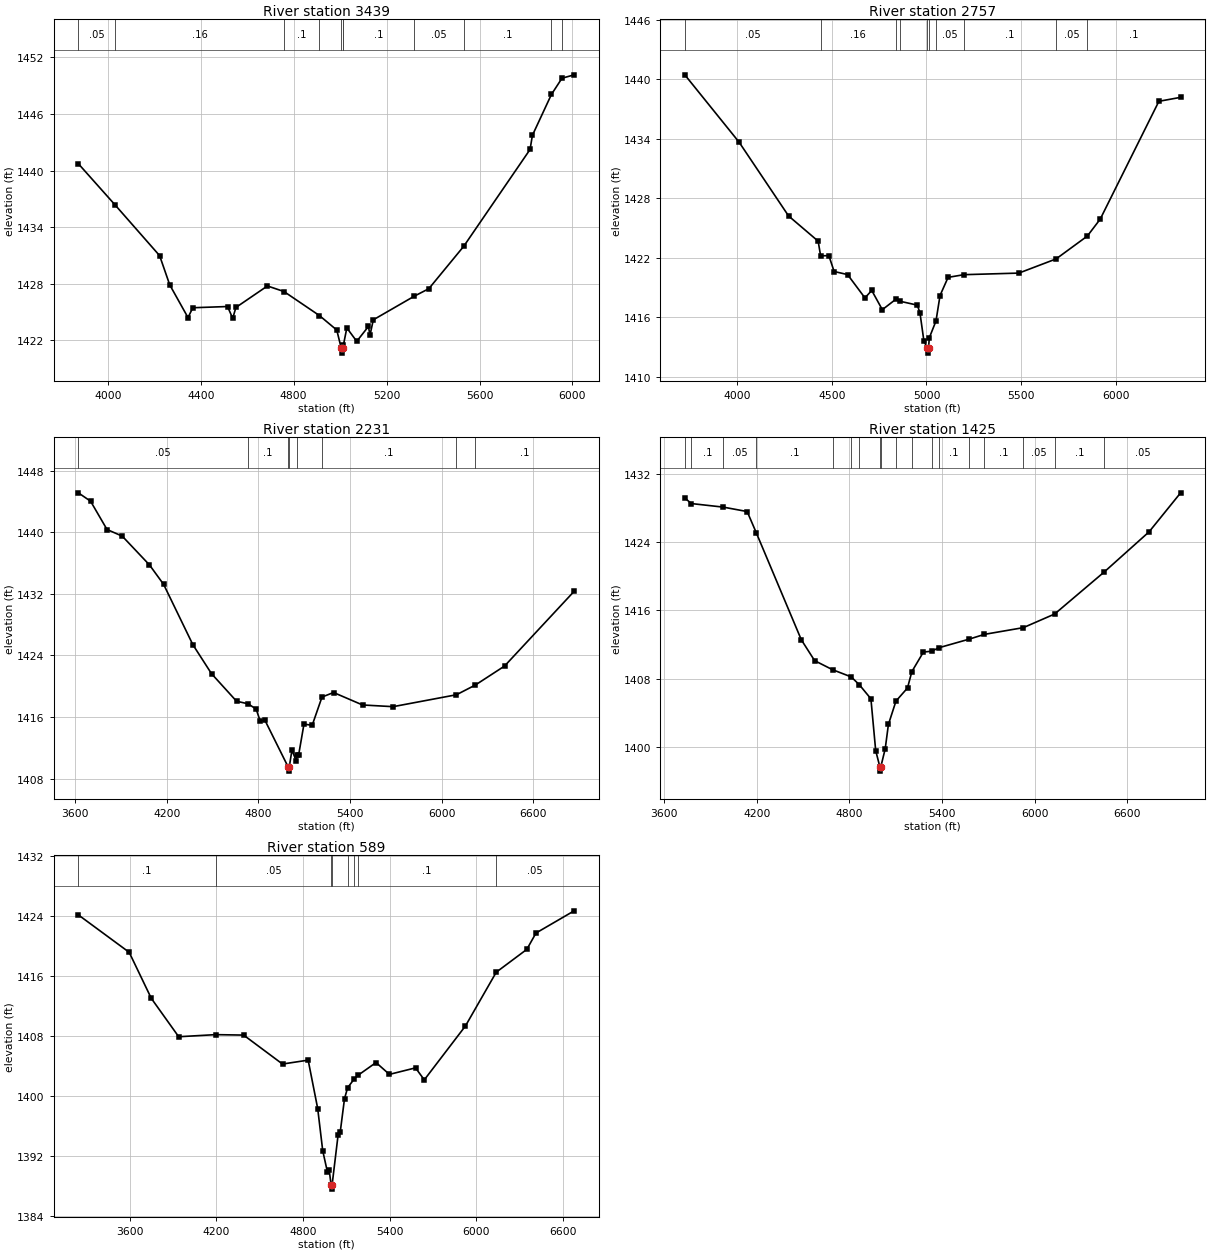
Type RM Length L Ch R = 1,3439,682,682,682
BEGIN DESCRIPTION:
WITTINGTON CREEK 4.0
END DESCRIPTION:
XS GIS Cut Line= 3
      2842013.04     10059711.28      2840823.82     10058782.47
      2840198.81     10058756.43
#Sta/Elev= 30
  3873.0 1440.74  4031.9 1436.35  4223.0 1430.99  4266.4 1427.90  4345.1 1424.43
  4365.9 1425.47  4515.2 1425.60  4537.7 1424.35  4551.3 1425.50  4687.0 1427.78
  4758.2 1427.19  4911.0 1424.64  4985.5 1423.11  5005.1 1421.16  5007.8 1420.66
  5011.1 1421.16  5013.9 1421.48  5028.9 1423.33  5071.5 1421.91  5122.0 1423.49
  5128.4 1422.54  5142.8 1424.19  5319.5 1426.70  5381.9 1427.49  5532.3 1431.99
  5817.7 1442.25  5827.7 1443.74  5909.6 1448.08  5955.1 1449.80  6007.5 1450.16
#Mann=11,-1,0
  3873.0    0.05       0  4031.9    0.16       0  4758.2     0.1       0
  4911.0    0.05       0  5005.1   0.035       0  5011.1    0.05       0
  5013.9     0.1       0  5319.5    0.05       0  5532.3     0.1       0
  5909.6    0.05       0  5955.1     0.1       0
Bank Sta=5005.1,5011.1
Exp/Cntr=0.3,0.1

Type RM Length L Ch R = 1,2757,526,526,526
BEGIN DESCRIPTION:
WITTINGTON CREEK 3.0
END DESCRIPTION:
XS GIS Cut Line= 3
      2842464.48     10059372.78      2841335.97     10058357.13
      2840233.56     10058339.77
#Sta/Elev= 30
  3722.7 1440.44  4009.7 1433.65  4271.3 1426.21  4427.5 1423.67  4440.7 1422.19
  4484.2 1422.21  4512.0 1420.61  4583.0 1420.30  4674.9 1417.95  4710.8 1418.70
  4766.8 1416.76  4839.5 1417.83  4862.6 1417.60  4951.4 1417.22  4965.6 1416.46
  4986.6 1413.59  5005.2 1412.88  5008.0 1412.38  5011.2 1412.88  5015.0 1413.92
  5050.4 1415.62  5071.8 1418.19  5114.4 1420.02  5198.4 1420.29  5488.5 1420.45
  5685.4 1421.88  5850.2 1424.18  5918.5 1425.89  6228.6 1437.77  6343.5 1438.17
#Mann=10,-1,0
  3722.7    0.05       0  4440.7    0.16       0  4839.5    0.05       0
  4862.6     0.1       0  5005.2    0.07       0  5011.2     0.1       0
  5050.4    0.05       0  5198.4     0.1       0  5685.4    0.05       0
  5850.2     0.1       0
Bank Sta=5005.2,5011.2
Exp/Cntr=0.3,0.1

Type RM Length L Ch R = 1,2231,806,806,806
BEGIN DESCRIPTION:
Mapping XS 58107f17
END DESCRIPTION:
XS GIS Cut Line= 3
      2842769.95     10059305.61      2841836.76     10058101.14
      2840112.47     10058079.45
#Sta/Elev= 30
  3620.8 1445.14  3701.0 1444.05  3808.8 1440.37  3908.4 1439.51  4086.7 1435.77
  4179.8 1433.23  4371.0 1425.40  4493.2 1421.63  4657.1 1418.05  4733.3 1417.71
  4785.7 1417.02  4812.8 1415.43  4841.8 1415.63  4996.3 1409.46  4999.1 1408.96
  5002.3 1409.46  5020.1 1411.69  5049.1 1410.25  5054.5 1411.09  5063.6 1411.02
  5098.9 1415.07  5152.8 1414.92  5217.0 1418.59  5292.8 1419.18  5482.8 1417.56
  5682.8 1417.34  6098.0 1418.89  6222.3 1420.16  6412.9 1422.62  6868.9 1432.34
#Mann=8,-1,0
  3620.8    0.05       0  4733.3     0.1       0  4996.3    0.07       0
  5002.3     0.1       0  5054.5    0.05       0  5217.0     0.1       0
  6098.0    0.05       0  6222.3     0.1       0
Bank Sta=4996.3,5002.3
Exp/Cntr=0.3,0.1

Type RM Length L Ch R = 1,1425,836,836,836
BEGIN DESCRIPTION:
WITTINGTON CREEK 2.0
END DESCRIPTION:
XS GIS Cut Line= 3
      2842802.46     10058296.44      2842140.58     10057417.55
      2840091.63     10057927.08
#Sta/Elev= 30
  3734.3 1429.22  3776.2 1428.56  3983.7 1428.14  4138.3 1427.62  4197.7 1425.11
  4488.8 1412.56  4575.3 1410.10  4691.0 1409.04  4812.4 1408.19  4865.7 1407.25
  4939.8 1405.62  4970.7 1399.54  4997.8 1397.62  5000.6 1397.12  5003.8 1397.62
  5032.5 1399.75  5053.1 1402.60  5102.1 1405.35  5176.8 1406.89  5204.9 1408.81
  5279.8 1411.11  5332.3 1411.21  5382.6 1411.63  5574.6 1412.62  5675.1 1413.19
  5927.3 1413.98  6129.8 1415.58  6452.3 1420.54  6741.7 1425.24  6945.9 1429.82
#Mann=18,-1,0
  3734.3    0.05       0  3776.2     0.1       0  3983.7    0.05       0
  4197.7     0.1       0  4691.0    0.05       0  4812.4     0.1       0
  4865.7    0.05       0  4997.8    0.04       0  5003.8    0.05       0
  5102.1    0.16       0  5204.9     0.1       0  5332.3    0.16       0
  5382.6     0.1       0  5574.6    0.16       0  5675.1     0.1       0
  5927.3    0.05       0  6129.8     0.1       0  6452.3    0.05       0
Bank Sta=4997.8,5003.8
Exp/Cntr=0.3,0.1

Type RM Length L Ch R = 1,589,0,0,0
BEGIN DESCRIPTION:
WITTINGTON CREEK 1.0
END DESCRIPTION:
XS GIS Cut Line= 4
      2842976.10     10058090.32      2842151.43     10056733.96
      2841847.61     10056582.05      2840404.43     10057016.09
#Sta/Elev= 30
  3244.5 1424.12  3596.7 1419.13  3749.8 1412.99  3939.7 1407.87  4194.6 1408.15
  4389.3 1408.09  4658.6 1404.23  4836.3 1404.75  4902.3 1398.30  4937.2 1392.67
  4969.4 1389.86  4981.9 1390.09  4995.7 1388.05  4998.5 1387.55  5001.7 1388.05
  5043.4 1394.74  5058.8 1395.22  5088.1 1399.62  5109.7 1401.07  5156.0 1402.26
  5180.2 1402.71  5306.4 1404.43  5399.1 1402.85  5579.9 1403.72  5640.6 1402.12
  5925.8 1409.31  6139.2 1416.48  6350.7 1419.52  6414.3 1421.70  6678.6 1424.66
#Mann=8,-1,0
  3244.5     0.1       0  4194.6    0.05       0  4995.7    0.04       0
  5001.7    0.05       0  5109.7     0.1       0  5156.0    0.05       0
  5180.2     0.1       0  6139.2    0.05       0
Bank Sta=4995.7,5001.7
Exp/Cntr=0.3,0.1

Chan Stop Cuts=-1