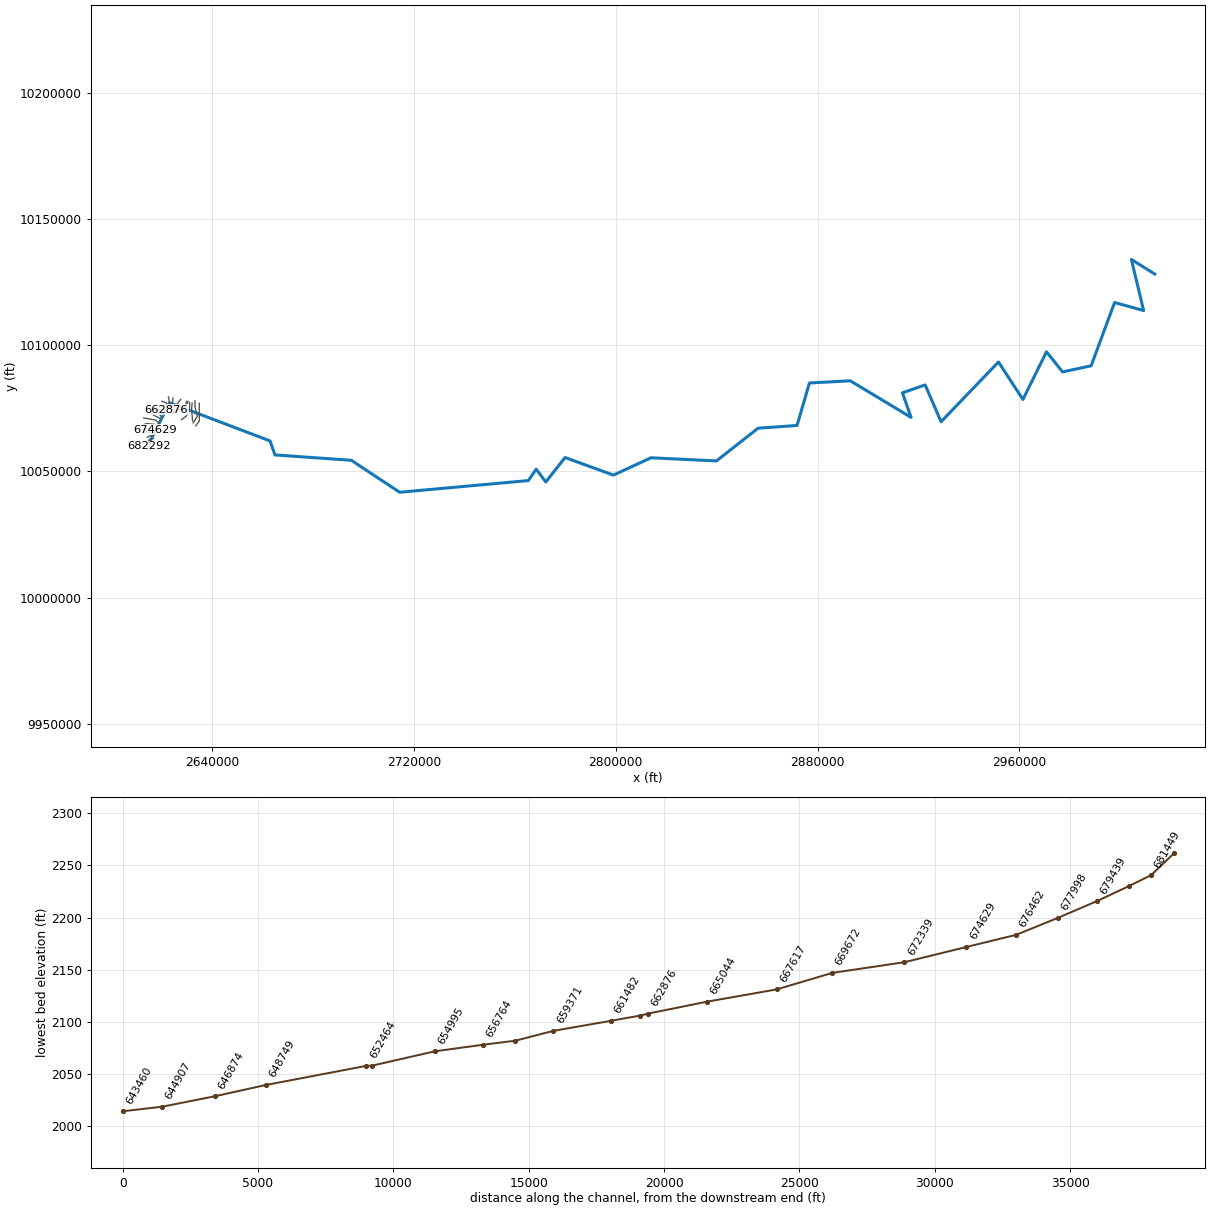
--- PEDERNALES RIVER.prj (project) ---

Proj Title=PEDERNALES RIVER Base Level Engineering
Current Plan=p01
Default Exp/Contr=0.3,0.1
English Units
Geom File=g01
Flow File=f01
Plan File=p01
Plan File=p02
Y Axis Title=Elevation
X Axis Title(PF)=Main Channel Distance
X Axis Title(XS)=Station
BEGIN DESCRIPTION:
PEDERNALES RIVER
END DESCRIPTION:
DSS Export Rating Curves= 0
DSS Export Rating Curve Sorted= 0
DSS Export Volume Flow Curves= 0
DXF OffsetX= 0
DXF OffsetY= 0
DXF ScaleX= 1
DXF ScaleY= 10

--- PEDERNALES RIVER.p01 (plan) ---

Plan Title=Multiple Run
Program Version=4.10
Short Identifier=Multiple
Geom File=g01
Flow File=f01
Subcritical Flow
K Sum by GR= 0
Std Step Tol= 0.01
Critical Tol= 0.01
Num of Std Step Trials= 20
Max Error Tol= 0.3
Flow Tol Ratio= 0.001
Split Flow NTrial= 30
Split Flow Tol= 0.02
Split Flow Ratio= 0.02
Log Output Level= 0
Friction Slope Method= 1
Unsteady Friction Slope Method= 2
Unsteady Bridges Friction Slope Method= 1
Parabolic Critical Depth
Global Vel Dist= 1 , 1 , 1
Global Log Level= 0
CheckData=True
Encroach Param=-1 ,0,0, 0
BEGIN DESCRIPTION:
Multiple Run
END DESCRIPTION:
Computation Interval=1HOUR
Output Interval=1HOUR
Run HTab= 0
Run UNet= 0
Run PostProcess= 0
Run WQNet= 0
UNET Theta= 1
UNET Theta Warmup= 1
UNET ZTol= 0.02
UNET ZSATol= 0.05
UNET MxIter= 20
UNET MaxInSteps= 0
UNET DtIC= 0
UNET DtMin= 0
UNET MaxCRTS= 20
UNET WFStab= 2
UNET SFStab= 1
UNET WFX= 1
UNET SFX= 1
UNET DSS MLevel= 4
UNET DZMax Abort= 100
UNET Convert EG Bridges= 0
UNET Use Existing IB Tables=-1
UNET Froude Reduction=False
UNET Froude Limit= 1
UNET Froude Power= 10
UNET Time Slicing=0,0, 5
UNET Junction Losses=0
Instantaneous Interval=1HOUR
Write IC File= 0
Write IC File at Sim End=0
Echo Input=False
Echo Parameters=False
Echo Output=False
Write Detailed= 0
WQ AD Non Conservative
WQ ULTIMATE=-1
WQ Max Comp Step=1HOUR
WQ Output Interval=15MIN
WQ Output Selected Increments= 0
WQ Output face flow=0
WQ Output face velocity=0
WQ Output face area=0
WQ Output face dispersion=0
WQ Output cell volume=0
WQ Output cell surface area=0
WQ Output cell continuity=0
WQ Output cumulative cell continuity=0
WQ Output face conc=0
WQ Output face dconc_dx=0
WQ Output face courant=0
WQ Output face peclet=0
WQ Output face adv mass=0
WQ Output face disp mass=0
WQ Output cell mass=0
WQ Output cell source sink temp=0
WQ Output cell source sink nsm=0
WQ Output MaxMinRange=-1
WQ Daily Max Min Mean=-1
WQ Daily Range=0
WQ Daily Time=0
WQ Create Restart=0
WQ Fixed Restart=0
WQ System Summary=0
WQ Use Fixed Temperature=0
Sorting and Armoring Iterations= 10
XS Update Threshold= 0.02
Hydraulics Update Threshold= 0.02
Energy Slope Method= 1
Volume Change Method= 0
XS Weighting Method= 0
Number of US Weighted Cross Sections= 1
Number of DS Weighted Cross Sections= 1
Upstream XS Weight=0.25
Main XS Weight=0.5
Downstream XS Weight=0.25
Number of DS XS's Weighted with US Boundary= 1
Upstream Boundary Weight= 1
Weight of XSs Associated with US Boundary= 0
Number of US XS's Weighted with DS Boundary= 1
Downstream Boundary Weight= 0.5
Weight of XSs Associated with DS Boundary= 0.5
Sediment Output Level= 4
Mass or Volume Output= 0
Output Increment Type= 1
Profile and TS Output Increment= 10
XS Output Flag= 0
XS Output Increment= 10
Disregard all LS=0
Disregard all Conn=0
Disregard all Breaches=0
Disregard all Pumps=0

--- PEDERNALES RIVER.p02 (plan) ---

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Plan Title=Delete
Short Identifier=GeorasImp
Geom File=.\_XsOutData\PEDERNALES RIVER.g02
Flow File=f01

--- PEDERNALES RIVER.f01 (steady flow) ---

Flow Title=Multiple
Program Version=4.10
Number of Profiles= 7
Profile Names=10-year,25-year,50-year,1pct_min,100-year,1pct_plu,500-year
River Rch & RM=PEDERNALES RIVER,Reach-1         ,682292
    3771    5733    7290    6621    8954   12110   12894
River Rch & RM=PEDERNALES RIVER,Reach-1         ,662576
    5059    7766    9939    9075   12273   16598   17866
River Rch & RM=PEDERNALES RIVER,Reach-1         ,652680
    6609   10252   13216   12147   16428   22217   24227
River Rch & RM=PEDERNALES RIVER,Reach-1         ,652464
    9617   15069   19561   18086   24459   33078   36492
River Rch & RM=PEDERNALES RIVER,Reach-1         ,636691
   11733   18473   24058   22307   30167   40798   45255
River Rch & RM=PEDERNALES RIVER,Reach-1         ,627323
   15785   24958   32601   30298   40975   55413   61730
River Rch & RM=PEDERNALES RIVER,Reach-1         ,595910
   24502   39092   51407   48068   65007   87914   99066
River Rch & RM=PEDERNALES RIVER,Reach-1         ,592191
   27587   44044   57954   54213   73317   99153  111801
River Rch & RM=PEDERNALES RIVER,Reach-1         ,580824
   30030   47762   62692   58486   79095  106967  119922
River Rch & RM=PEDERNALES RIVER,Reach-1         ,547814
   34298   54569   71660   66872   90436  122305  137155
River Rch & RM=PEDERNALES RIVER,Reach-1         ,538864
   40509   64549   84876   79301  107245  145036  162979
River Rch & RM=PEDERNALES RIVER,Reach-1         ,523821
   44707   71071   93336   87105  117800  159311  178588
River Rch & RM=PEDERNALES RIVER,Reach-1         ,503704
   46453   73699   96695   90202  121987  164974  184850
River Rch & RM=PEDERNALES RIVER,Reach-1         ,489895
   48679   77004  100863   93964  127076  171855  192089
River Rch & RM=PEDERNALES RIVER,Reach-1         ,470762
   48780   76985  100690   93674  126684  171325  190983
River Rch & RM=PEDERNALES RIVER,Reach-1         ,456247
   49754   78357  102358   95129  128651  173985  193575
River Rch & RM=PEDERNALES RIVER,Reach-1         ,442431
   51812   81318  106015   98363  133024  179900  199520
River Rch & RM=PEDERNALES RIVER,Reach-1         ,401731
   54889   86042  112116  103999  140647  190208  210862
River Rch & RM=PEDERNALES RIVER,Reach-1         ,390306
   55397   86541  112518  104151  140852  190486  210280
River Rch & RM=PEDERNALES RIVER,Reach-1         ,355975
   58291   91049  118397  109631  148263  200509  221492
River Rch & RM=PEDERNALES RIVER,Reach-1         ,331819
   61607   96321  125363  116201  157148  212525  235241
River Rch & RM=PEDERNALES RIVER,Reach-1         ,290001
   66400  103744  135007  125155  169257  228901  253426
River Rch & RM=PEDERNALES RIVER,Reach-1         ,254179
   68116  106288  138214  128041  173161  234180  258911
River Rch & RM=PEDERNALES RIVER,Reach-1         ,182551
   70460  109889  142868  132338  178972  242039  267529
River Rch & RM=PEDERNALES RIVER,Reach-1         ,175206
   74453  116063  150886  139776  189031  255643  282584
River Rch & RM=PEDERNALES RIVER,Reach-1         ,77429
   76999  119787  155538  143920  194636  263222  290272
River Rch & RM=PEDERNALES RIVER,Reach-1         ,62973
   79595  123660  160448  148368  200651  271357  298849
Boundary for River Rch & Prof#=PEDERNALES RIVER,Reach-1         , 1
Up Type= 0
Dn Type= 1
Dn Known WS=697
Boundary for River Rch & Prof#=PEDERNALES RIVER,Reach-1         , 2
Up Type= 0
Dn Type= 3
Dn Slope=0.000085
Boundary for River Rch & Prof#=PEDERNALES RIVER,Reach-1         , 3
Up Type= 0
Dn Type= 1
Dn Known WS=716
Boundary for River Rch & Prof#=PEDERNALES RIVER,Reach-1         , 4
Up Type= 0
Dn Type= 3
Dn Slope=0.000085
Boundary for River Rch & Prof#=PEDERNALES RIVER,Reach-1         , 5
Up Type= 0
Dn Type= 1
Dn Known WS=722
Boundary for River Rch & Prof#=PEDERNALES RIVER,Reach-1         , 6
Up Type= 0
Dn Type= 3
Dn Slope=0.000085
Boundary for River Rch & Prof#=PEDERNALES RIVER,Reach-1         , 7
Up Type= 0
Dn Type= 1
Dn Known WS=732
DSS Import GetInterval= 0
DSS Import GetPeak= 0
DSS Import FillOption= 0

--- PEDERNALES RIVER.g01 (geometry) ---

Geom Title=Existing Conditions
Program Version=4.10

River Reach=PEDERNALES RIVER,Reach-1
Reach XY= 30
      2614670.81     10060434.73      2623191.67     10077215.75
       2663031.4     10062079.44      2664958.47     10056533.73
      2695219.55     10054413.64      2714387.91      10041744.1
      2765377.96     10046374.96      2768482.73     10050893.81
      2772295.58     10045830.15      2779943.99     10055505.35
      2799096.35     10048543.55        2813999.     10055412.44
      2839934.14     10054161.17      2856443.11      10067130.4
      2871887.96     10068223.98      2876788.04     10085054.75
      2892981.25     10085916.12      2917091.06     10071406.93
      2913642.21     10081157.17      2922663.59     10084284.46
      2928960.79     10069699.21      2951715.61     10093370.74
      2961402.65     10078512.79      2970739.36     10097413.59
      2977106.86     10089436.75      2988444.56     10091869.41
      2997739.05     10116951.68      3009243.61     10113760.91
      3004395.61     10134012.67      3013659.67     10128223.23

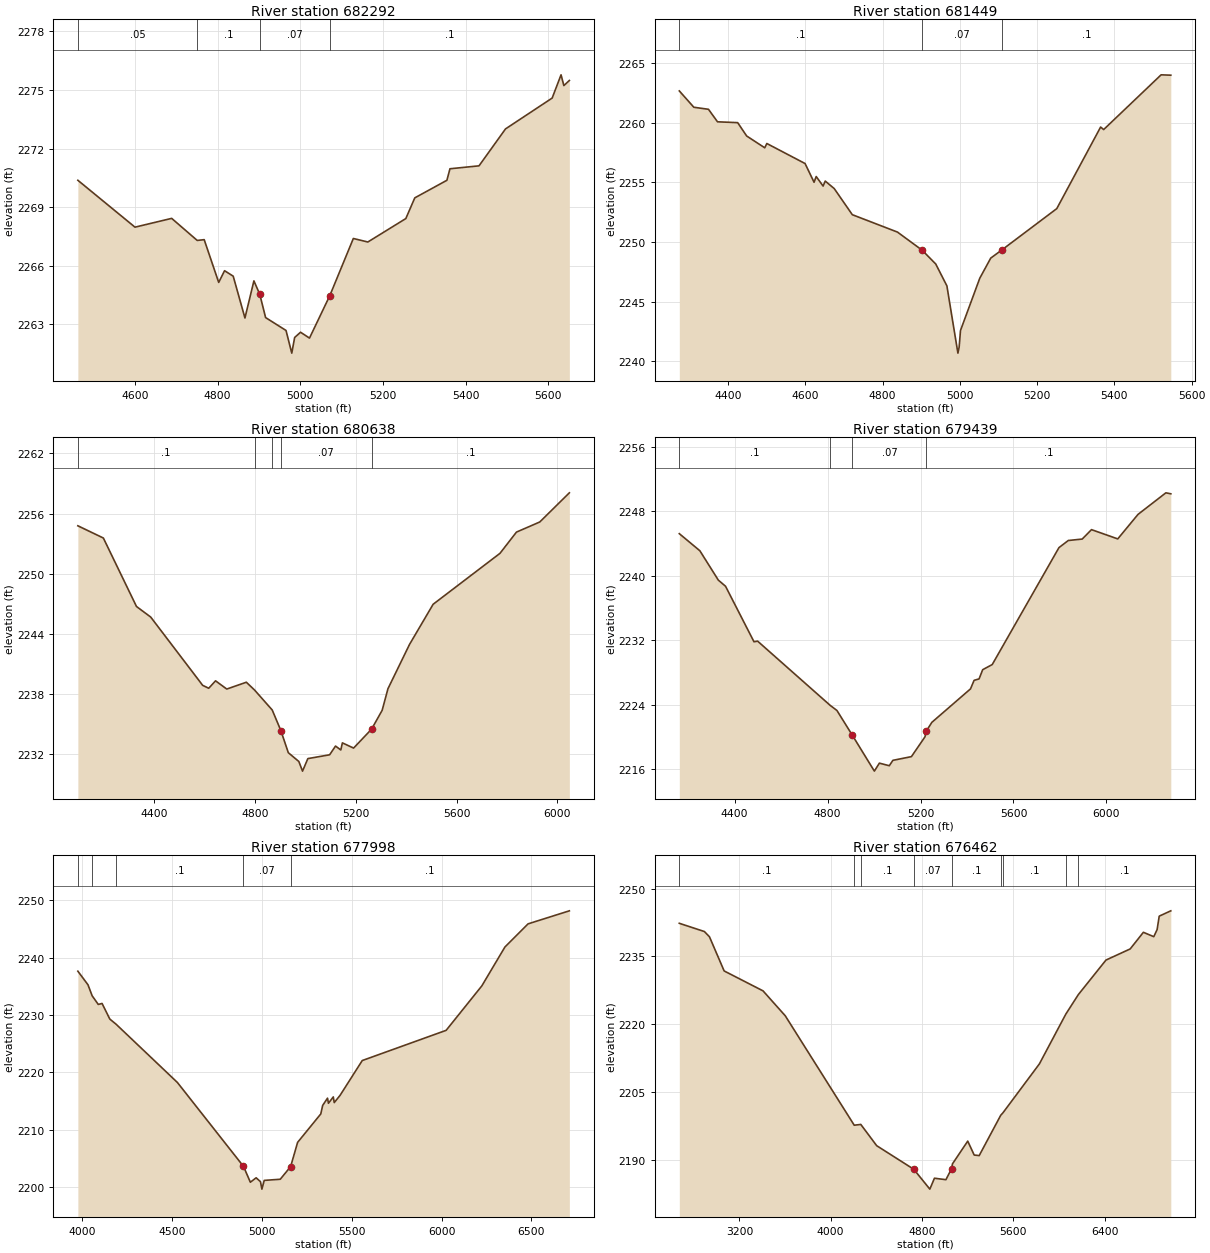
Type RM Length L Ch R = 1 ,682292  ,843,843,843
BEGIN DESCRIPTION:
PEDERNALES RIVER 1.0
END DESCRIPTION:
XS GIS Cut Line= 4
      2614488.46     10060927.43      2614507.29     10060671.57
      2614947.41     10060185.36      2615134.51     10059981.21
#Sta/Elev= 30
  4461.9 2270.38 4600.13 2267.98 4688.93 2268.43  4750.7  2267.3  4767.6 2267.34
  4802.7 2265.15  4816.9 2265.75  4837.8 2265.47  4866.2 2263.33  4887.9 2265.23
  4902.1 2264.54  4916.2 2263.35  4965.6 2262.69  4979.5 2261.53  4986.5 2262.33
  5000.7  2262.6  5022.4  2262.3  5071.7 2264.48  5128.5  2267.4  5163.6 2267.22
  5255.5 2268.42  5277.2 2269.48  5354.9 2270.38  5362.3 2270.97  5432.6 2271.12
  5496.7 2273.01  5609.6 2274.59  5631.1 2275.78  5637.9 2275.23  5651.2 2275.49
#Mann= 4 ,-1 , 0
  4461.9     .05       0  4750.7      .1       0  4902.1     .07       0
  5071.7      .1       0
Bank Sta=4902.1,5071.7
XS Rating Curve= 0 ,0
Exp/Cntr=0.3,0.1

Type RM Length L Ch R = 1 ,681449  ,811,811,811
BEGIN DESCRIPTION:
PEDERNALES RIVER 3.0
END DESCRIPTION:
XS GIS Cut Line= 3
      2614644.04     10061378.94      2615106.56     10061176.06
       2615702.6     10060692.64
#Sta/Elev= 30
  4273.5 2262.67  4311.1  2261.3    4349 2261.13  4372.4 2260.08  4424.6 2260.01
  4447.9 2258.89  4494.7  2257.9  4500.1 2258.26  4599.1 2256.58  4622.4 2255.01
  4627.9 2255.49  4645.8 2254.69  4651.3 2255.11  4674.6 2254.48  4721.4 2252.29
  4838.4 2250.83  4902.3 2249.31  4937.5 2248.15  4966.3 2246.32  4994.8 2240.68
    4998 2241.18  5001.5 2242.58  5051.4 2246.96  5079.8 2248.65  5108.5 2249.33
  5250.8  2252.8  5364.3 2259.64  5372.2 2259.43  5520.9 2264.02    5546 2263.99
#Mann= 3 ,-1 , 0
  4273.5      .1       0  4902.3     .07       0  5108.5      .1       0
Bank Sta=4902.3,5108.5
XS Rating Curve= 0 ,0
Exp/Cntr=0.3,0.1

Type RM Length L Ch R = 1 ,680638  ,1199,1199,1199
BEGIN DESCRIPTION:
PEDERNALES RIVER 4.0
END DESCRIPTION:
XS GIS Cut Line= 3
      2614839.28     10062044.18      2615340.51     10061945.93
      2616517.02     10061119.55
#Sta/Elev= 30
  4098.7 2254.78  4199.8 2253.56  4331.1 2246.73  4387.6 2245.67  4593.5 2238.86
  4617.5 2238.57  4644.6 2239.31    4689 2238.49  4766.6 2239.17  4799.3 2238.39
  4869.2  2236.4  4903.4 2234.35    4933 2232.14  4974.8 2231.26  4989.4  2230.3
  5010.5 2231.55  5096.8 2231.93  5120.2  2232.8  5141.2 2232.41  5147.4 2233.12
  5191.8  2232.6  5263.2 2234.49  5305.1 2236.37    5328 2238.52  5413.5 2242.94
  5507.2 2246.95  5772.1 2252.03  5837.5 2254.15  5929.9 2255.16  6047.2 2258.07
#Mann= 5 ,-1 , 0
  4098.7      .1       0  4799.3     .16       0  4869.2      .1       0
  4903.4     .07       0  5263.2      .1       0
Bank Sta=4903.4,5263.2
XS Rating Curve= 0 ,0
Exp/Cntr=0.3,0.1

Type RM Length L Ch R = 1 ,679439  ,1441,1441,1441
BEGIN DESCRIPTION:
PEDERNALES RIVER 5.0
END DESCRIPTION:
XS GIS Cut Line= 3
      2614877.48     10062343.26      2616028.99     10063037.46
      2616799.65     10063053.54
#Sta/Elev= 30
  4161.7 2245.21  4250.1 2243.09  4329.7 2239.44  4360.7 2238.68  4483.1 2231.79
  4498.6 2231.87  4811.2 2223.89  4840.1 2223.26  4906.3 2220.19  5001.2 2215.73
  5022.8 2216.72  5065.5  2216.4    5081 2217.07  5160.7 2217.53  5218.9 2219.98
  5225.4 2220.73  5248.8 2221.79    5415 2225.94  5430.5    2227  5451.9 2227.18
  5467.4 2228.32  5508.5 2228.96  5795.8 2243.48  5835.8 2244.36  5895.8 2244.54
  5935.8 2245.71  6048.8 2244.56  6135.9  2247.6  6255.9 2250.28  6277.1 2250.16
#Mann= 4 ,-1 , 0
  4161.7      .1       0  4811.2      .1       0  4906.3     .07       0
  5225.4      .1       0
Bank Sta=4906.3,5225.4
XS Rating Curve= 0 ,0
Exp/Cntr=0.3,0.1

Type RM Length L Ch R = 1 ,677998  ,1536,1536,1536
BEGIN DESCRIPTION:
PEDERNALES RIVER 6.0
END DESCRIPTION:
XS GIS Cut Line= 4
      2614350.08      10063482.9      2614838.44     10063877.56
      2616402.05     10064375.26      2616867.73     10064346.05
#Sta/Elev= 30
  3975.6 2237.63    4032 2235.26    4055 2233.35  4089.2 2231.84  4110.3 2232.01
  4153.5 2229.29  4188.5 2228.39  4529.3 2218.26  4897.4 2203.64  4935.6 2200.88
  4967.8 2201.65  4991.8 2200.98  4999.8 2199.68  5012.8  2201.2    5102  2201.4
  5159.7  2203.6  5198.6 2207.82  5327.5 2212.77  5338.1 2214.26    5365 2215.52
  5370.3 2214.63  5397.2 2215.74  5402.5 2214.75  5434.7    2216  5558.4 2222.07
  6025.3 2227.33  6223.9 2235.07  6352.4 2241.84  6481.3 2245.87    6711 2248.14
#Mann= 5 ,-1 , 0
  3975.6      .1       0    4055     .05       0  4188.5      .1       0
  4897.4     .07       0  5159.7      .1       0
Bank Sta=4897.4,5159.7
XS Rating Curve= 0 ,0
Exp/Cntr=0.3,0.1

Type RM Length L Ch R = 1 ,676462  ,1833,1833,1833
BEGIN DESCRIPTION:
PEDERNALES RIVER 7.0
END DESCRIPTION:
XS GIS Cut Line= 4
      2612954.87     10065181.69      2613665.97     10065537.34
      2616496.01     10065237.52      2617110.19     10064980.89
#Sta/Elev= 30
  2673.7 2242.33  2893.2 2240.51  2937.9 2239.35  3066.5 2231.79  3407.4 2227.38
    3602 2221.87  4206.4 2197.66    4264 2197.83  4403.1 2193.13  4728.3 2187.91
  4868.8 2183.52  4909.3 2185.93  5009.9 2185.61  5060.1 2188.08  5067.2 2189.11
  5200.9 2194.14  5257.6 2191.06  5301.5 2190.94  5490.3 2199.87  5509.1 2200.39
    5829 2211.23  6060.2 2222.23  6170.3 2226.56  6412.4  2234.2  6624.5 2236.66
    6740 2240.34  6831.2 2239.37  6860.4 2240.94  6878.8 2243.91  6980.3 2245.09
#Mann= 9 ,-1 , 0
  2673.7      .1       0  4206.4     .05       0    4264      .1       0
  4728.3     .07       0  5067.2      .1       0  5490.3     .16       0
  5509.1      .1       0  6060.2     .16       0  6170.3      .1       0
Bank Sta=4728.3,5060.1
XS Rating Curve= 0 ,0
Exp/Cntr=0.3,0.1

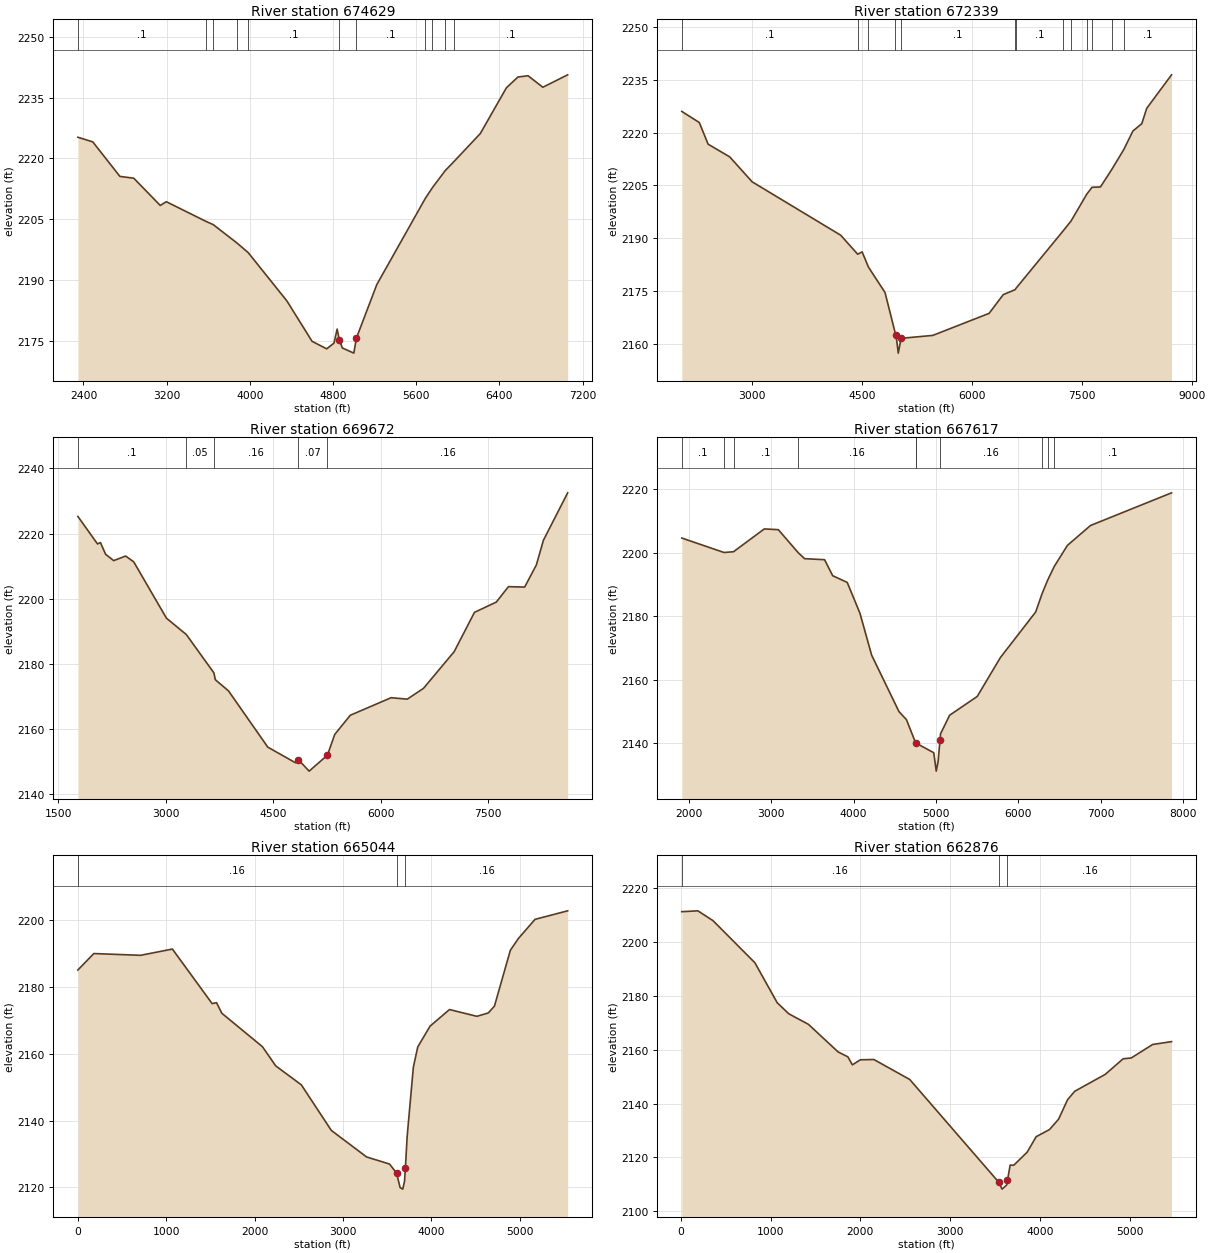
Type RM Length L Ch R = 1 ,674629  ,2290,2290,2290
BEGIN DESCRIPTION:
PEDERNALES RIVER 8.0
END DESCRIPTION:
XS GIS Cut Line= 4
      2613104.93     10066292.88      2614415.18     10067072.31
      2617152.85     10066800.91      2617535.72     10066597.92
#Sta/Elev= 30
  2346.8 2225.25  2489.9  2224.1  2750.9 2215.57  2883.4 2215.14  3138.5  2208.4
  3196.9 2209.32  3577.4 2204.47  3648.4 2203.65    3872 2199.21  3984.1 2196.75
    4357 2184.78  4598.2 2174.83  4738.9 2172.97  4809.2 2174.38  4839.4 2177.86
  4859.5 2175.25  4889.6 2173.18  4999.9 2171.91    5024 2175.58  5220.8 2188.85
    5688 2210.18  5755.7  2212.8  5877.7 2216.98    5959 2219.14  6216.1 2226.17
  6467.3 2237.48  6577.8 2240.13  6674.8 2240.44  6817.4  2237.6  7055.8 2240.67
#Mann= 11 ,-1 , 0
  2346.8      .1       0  3577.4     .16       0  3648.4      .1       0
    3872     .05       0  3984.1      .1       0  4859.5     .07       0
    5024      .1       0    5688     .16       0  5755.7      .1       0
  5877.7     .16       0    5959      .1       0
Bank Sta=4859.5,5024
XS Rating Curve= 0 ,0
Exp/Cntr=0.3,0.1

Type RM Length L Ch R = 1 ,672339  ,2667,2667,2667
BEGIN DESCRIPTION:
PEDERNALES RIVER 10.0
END DESCRIPTION:
XS GIS Cut Line= 4
       2612188.4     10068183.12      2614088.57     10068995.58
      2617548.29     10068593.84      2618501.66      10067988.8
#Sta/Elev= 30
  2046.3 2226.05  2284.9  2222.9  2405.3 2216.74  2700.4 2213.12  3005.3 2206.04
  4213.4 2190.85  4444.6 2185.45  4505.4 2186.11  4591.9 2181.78  4817.5 2174.57
  4958.4 2162.93  4968.5 2162.41  4998.4 2157.32  5036.6 2161.53  5469.8 2162.36
    6237 2168.63  6429.8 2173.95    6592 2175.37  6605.9  2175.8    7243 2191.99
  7353.7 2194.86  7568.3  2202.5  7640.6 2204.48  7755.3 2204.57  7908.8 2209.51
  8073.4  2215.2  8198.4 2220.49  8319.5 2222.58  8386.4 2226.93    8725 2236.46
#Mann= 13 ,-1 , 0
  2046.3      .1       0  4444.6     .05       0  4591.9      .1       0
  4958.4     .07       0  5036.6      .1       0    6592     .16       0
  6605.9      .1       0    7243     .16       0  7353.7      .1       0
  7568.3     .16       0  7640.6      .1       0  7908.8     .16       0
  8073.4      .1       0
Bank Sta=4968.5,5036.6
XS Rating Curve= 0 ,0
Exp/Cntr=0.3,0.1

Type RM Length L Ch R = 1 ,669672  ,2055,2055,2055
BEGIN DESCRIPTION:
PEDERNALES RIVER 11.0
END DESCRIPTION:
XS GIS Cut Line= 3
      2612968.69     10071195.93      2617718.47     10070349.38
      2619200.59      10068987.7
#Sta/Elev= 30
  1771.9 2225.27  2045.9 2216.83  2086.6 2217.26  2158.8 2213.66  2271.7 2211.71
  2438.4 2213.12  2551.3 2211.34  3007.8 2194.05  3286.1    2189  3671.1 2177.23
    3690 2175.15  3874.3 2171.72  4422.8 2154.45  4808.8 2149.65  4849.4 2150.59
  5000.3 2147.08  5255.7 2151.98  5357.3 2158.34    5575 2164.24  6144.4 2169.62
  6370.1 2169.18  6596.5  2172.5  7025.2 2183.77  7308.2 2195.83  7612.8 2198.98
  7782.3 2203.72  8008.8 2203.59  8171.8 2210.37  8270.7 2217.96  8609.2 2232.53
#Mann= 5 ,-1 , 0
  1771.9      .1       0  3286.1     .05       0  3671.1     .16       0
  4849.4     .07       0  5255.7     .16       0
Bank Sta=4849.4,5255.7
XS Rating Curve= 0 ,0
Exp/Cntr=0.3,0.1

Type RM Length L Ch R = 1 ,667617  ,2573,2573,2573
BEGIN DESCRIPTION:
PEDERNALES RIVER 12.0
END DESCRIPTION:
XS GIS Cut Line= 2
      2614546.53     10073575.76      2619804.36     10070799.91
#Sta/Elev= 30
  1913.3 2204.66  2425.5 2200.11  2541.5 2200.35  2914.9 2207.53  3085.4 2207.29
  3326.8 2200.04  3404.4 2198.16  3646.6 2197.84  3745.4 2192.79  3921.5 2190.69
  4075.6 2181.02  4218.4 2167.76  4550.3 2149.98  4640.7 2147.47  4751.9 2140.15
  4972.1 2137.05  5002.3 2131.25  5025.2 2134.36  5047.8 2140.99  5054.5    2143
  5164.6 2148.85  5499.9 2154.77  5780.5    2167  6209.5 2181.37    6285 2186.98
  6353.5 2191.32  6433.4 2195.64  6594.5 2202.34  6875.1 2208.61  7858.9  2218.9
#Mann= 10 ,-1 , 0
  1913.3      .1       0  2425.5     .05       0  2541.5      .1       0
  3326.8     .16       0  4751.9      .1       0  4751.9     .07       0
  5047.8     .16       0    6285      .1       0  6353.5     .16       0
  6433.4      .1       0
Bank Sta=4751.9,5047.8
XS Rating Curve= 0 ,0
Exp/Cntr=0.3,0.1

Type RM Length L Ch R = 1 ,665044  ,2168,2168,2168
XS GIS Cut Line= 3
     2616295.794    10075255.436     2618439.892    10073658.213
     2620193.364    10071366.547
#Sta/Elev= 30
       0 2185.01179.83722189.924 709.3582189.3951069.0332191.2651518.6262174.961
 1568.582175.2311628.5262172.078 2088.112162.0732237.9752156.3492527.7122150.685
2867.154 2137.063266.2352129.1253525.6372127.0113605.4542124.3113645.3622119.976
3675.2932119.5123695.2472121.8383705.2242125.8933725.1782135.2763795.017 2155.91
3844.902 2162.013984.5812168.2334204.0752173.1894513.3632171.1654643.0642172.166
4712.903 2174.234892.4892190.8924982.2832194.3815171.8462200.1445540.9962202.693
#Mann= 3 ,-1 , 0
       0     .16       03605.454     .07       03705.224     .16       0
Bank Sta=3605.454,3705.224
XS Rating Curve= 0 ,0
Exp/Cntr=0.3,0.1

Type RM Length L Ch R = 1 ,662876  ,300,300,300
XS GIS Cut Line= 3
     2617014.544    10075335.297     2617684.785    10074304.656
     2621852.218     10074517.01
#Sta/Elev= 30
9.9344122211.358188.75382211.677357.63882208.031824.55622192.3731072.9172177.522
1202.0642173.3861421.556 2169.46 1751.322159.2261861.2412157.3611911.2062154.394
2001.1412156.2762151.034 2156.372550.7482148.943 3540.042110.8373580.0112108.167
3629.9762109.6693639.9692111.4313669.9472117.1043709.918 2117.053859.8112121.921
 3959.742127.6624109.6322130.3584209.5612134.183 4309.492141.4094389.4322144.563
4729.189 2150.844929.0462156.6435018.9822156.945 5258.812161.975 5468.66 2163.03
#Mann= 3 , 0 , 0
9.934412     .16       0 3540.04     .07       03639.969     .16       0
Bank Sta=3540.04,3639.969
XS Rating Curve= 0 ,0
Exp/Cntr=0.3,0.1

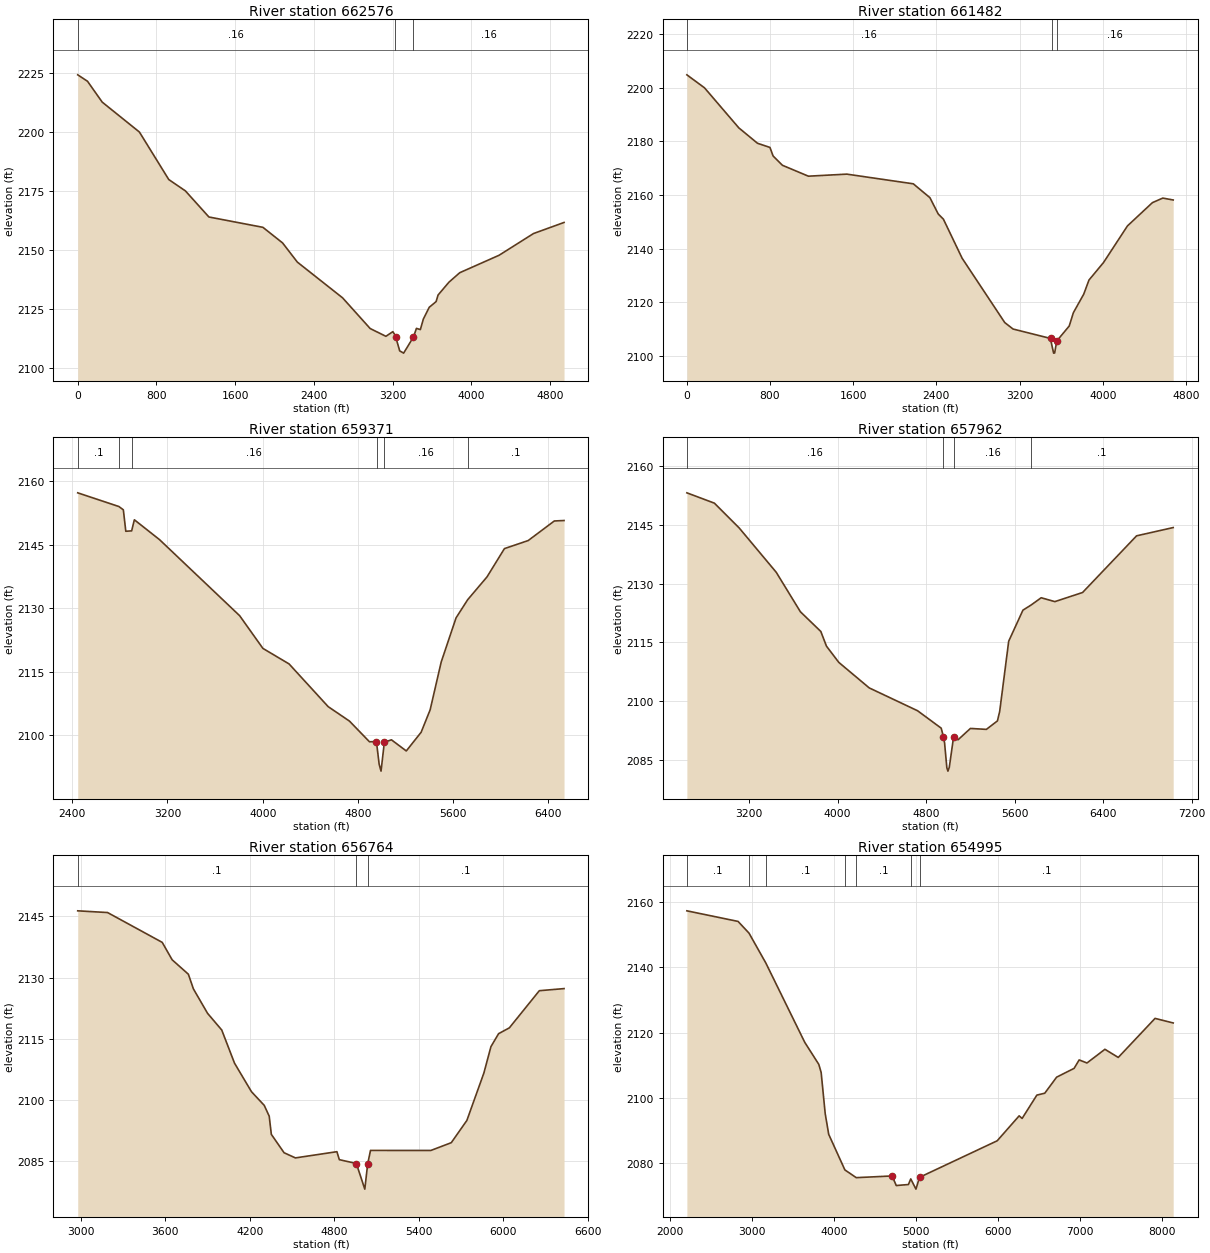
Type RM Length L Ch R = 1 ,662576  ,1094,1094,1094
XS GIS Cut Line= 3
     2617278.433    10075474.113      2618476.35    10074501.891
     2621887.808    10074658.141
#Sta/Elev= 30
       02224.26199.474672221.523248.68672212.681626.69042199.995925.11442179.835
1094.2212175.0221332.961 2163.951881.7482159.5672081.7462152.9432231.744 2144.81
2691.7392129.6372971.7352116.6253131.7332113.3343201.7322115.3023221.7322114.024
3231.7322112.9563271.7322107.1613311.7312106.199 3411.732113.0633441.7292116.691
3481.7292116.1973511.7292120.6123571.728 2125.643641.7272128.0633661.7272130.857
3771.7262136.2763881.7242140.3134281.7192147.7174631.7152156.9394941.7112161.632
#Mann= 3 ,-1 , 0
       0     .16       03221.732     .07       0 3411.73     .16       0
Bank Sta=3231.732,3411.73
XS Rating Curve= 0 ,0
Exp/Cntr=0.3,0.1

Type RM Length L Ch R = 1 ,661482  ,2111,2111,2111
XS GIS Cut Line= 3
     2617634.336    10076290.085     2620047.531    10075803.974
     2621983.294    10074901.197
#Sta/Elev= 30
       02204.813 169.8092199.961499.43832185.056679.2361 2179.31799.1013 2177.76
829.06762174.592918.96642171.1091168.6862167.047 1538.272167.8122177.5512164.205
2337.3712159.0462417.2812152.9672467.2252151.0342647.2012136.4793057.1972112.505
3137.1962110.0973497.1932106.5963507.1932104.6043527.193 2101.123537.1922101.164
3557.1922105.6333677.1912111.2153717.1912116.174 3817.192123.1223867.1892128.345
4007.1882134.8774237.1862148.5134477.1832157.1834577.1822158.8874677.1812158.181
#Mann= 3 ,-1 , 0
       0     .16       03507.193     .07       03557.192     .16       0
Bank Sta=3497.193,3557.192
XS Rating Curve= 0 ,0
Exp/Cntr=0.3,0.1

Type RM Length L Ch R = 1 ,659371  ,1409,1409,1409
BEGIN DESCRIPTION:
PEDERNALES RIVER 17.0
END DESCRIPTION:
XS GIS Cut Line= 4
      2620112.72     10077810.65      2621866.18     10077267.17
      2622719.98     10075725.62      2622628.15     10075247.92
#Sta/Elev= 30
  2446.6 2157.22  2792.1 2153.99  2829.7 2153.21  2850.4 2148.15  2899.5 2148.25
  2922.2 2150.86  3133.5 2146.18  3806.3 2128.24  4001.9 2120.52  4221.9 2116.85
    4550 2106.78  4728.6 2103.38  4896.9 2098.49  4949.3 2098.55  4956.4 2098.28
  4978.2 2093.19    4994 2091.57  5021.7 2098.36  5081.2 2098.96    5206 2096.33
  5330.8 2100.74  5406.4 2106.03  5499.1 2117.29  5623.9 2127.72  5721.2 2131.99
  5883.8 2137.38  6030.3 2144.06  6229.8 2145.96  6449.3 2150.58    6531 2150.69
#Mann= 6 ,-1 , 0
  2446.6      .1       0  2792.1     .05       0  2899.5     .16       0
  4956.4     .07       0  5021.7     .16       0  5721.2      .1       0
Bank Sta=4949.3,5021.7
XS Rating Curve= 0 ,0
Exp/Cntr=0.3,0.1

Type RM Length L Ch R = 1 ,657962  ,1198,1198,1198
BEGIN DESCRIPTION:
PEDERNALES RIVER 18.0
END DESCRIPTION:
XS GIS Cut Line= 3
      2622729.08     10079534.37       2623332.6     10076221.17
      2622996.87     10075251.47
#Sta/Elev= 30
  2638.7 2153.19  2887.4 2150.55  3110.8 2144.24  3445.9 2132.91  3664.2 2122.83
  3848.9 2117.79  3899.8 2114.05  4011.6 2109.89  4286.2 2103.38  4722.9 2097.55
  4936.5  2093.1  4956.9  2090.9    4967 2089.34  4987.4 2083.01  4997.3 2082.13
  5009.8 2083.12  5048.4 2090.85    5089 2090.14  5200.8 2093.03  5344.9 2092.79
  5444.8 2094.96  5465.1 2097.39  5546.4  2115.3    5675 2123.23  5749.7 2124.56
    5840  2126.4  5963.2 2125.41  6213.9 2127.74  6701.8 2142.21  7032.6 2144.32
#Mann= 4 ,-1 , 0
  2638.7     .16       0  4956.9     .07       0  5048.4     .16       0
  5749.7      .1       0
Bank Sta=4956.9,5048.4
XS Rating Curve= 0 ,0
Exp/Cntr=0.3,0.1

Type RM Length L Ch R = 1 ,656764  ,1769,1769,1769
BEGIN DESCRIPTION:
PEDERNALES RIVER 19.0
END DESCRIPTION:
XS GIS Cut Line= 2
      2624535.47      10079100.1      2624174.79      10075667.8
#Sta/Elev= 30
  2979.7 2146.33  3191.3 2145.91  3579.4 2138.61  3649.7 2134.35  3764.9 2130.82
  3800.6 2127.23  3901.1 2121.25  4001.7 2117.17  4092.2 2109.07  4212.8 2102.07
  4303.3 2098.73  4338.5 2096.09  4353.6 2091.64  4444.1 2087.14  4524.5 2085.88
    4819  2087.4  4836.2 2085.45  4956.9 2084.51    5017 2078.24  5037.3  2084.4
  5057.4 2087.71  5485.7  2087.7  5630.6  2089.6  5741.2 2095.04  5861.9 2106.64
  5912.1  2113.1  5966.3 2116.27  6042.8  2117.7  6255.6 2126.79  6430.9  2127.3
#Mann= 3 ,-1 , 0
  2979.7      .1       0  4956.9     .07       0  5037.3      .1       0
Bank Sta=4956.9,5037.3
XS Rating Curve= 0 ,0
Exp/Cntr=0.3,0.1

Type RM Length L Ch R = 1 ,654995  ,2315,2315,2315
BEGIN DESCRIPTION:
PEDERNALES RIVER 20.0
END DESCRIPTION:
XS GIS Cut Line= 4
      2627587.21     10078530.14      2626719.17     10077379.99
      2625330.28     10075752.39      2623225.22     10074710.71
#Sta/Elev= 30
  2207.4 2157.38  2831.7 2154.13  2965.1 2150.53  3169.7 2141.39  3644.8 2117.03
    3816 2110.27  3844.6 2107.79    3894 2095.14  3936.8 2088.81  4133.8  2077.9
  4272.2 2075.52  4709.8 2076.04  4760.3  2073.1  4908.5 2073.41  4937.1 2075.13
  5000.5    2072  5043.6 2075.62  5990.9 2086.83  6258.6 2094.48    6295 2093.69
  6474.4 2100.84    6571 2101.43  6715.6 2106.35  6928.6 2109.05  6990.3 2111.64
  7085.6  2110.7  7304.4  2114.9    7467  2112.4  7915.6 2124.38  8136.7 2122.98
#Mann= 7 ,-1 , 0
  2207.4      .1       0  2965.1     .16       0  3169.7      .1       0
  4133.8     .05       0  4272.2      .1       0  4937.1     .07       0
  5043.6      .1       0
Bank Sta=4709.8,5043.6
XS Rating Curve= 0 ,0
Exp/Cntr=0.3,0.1

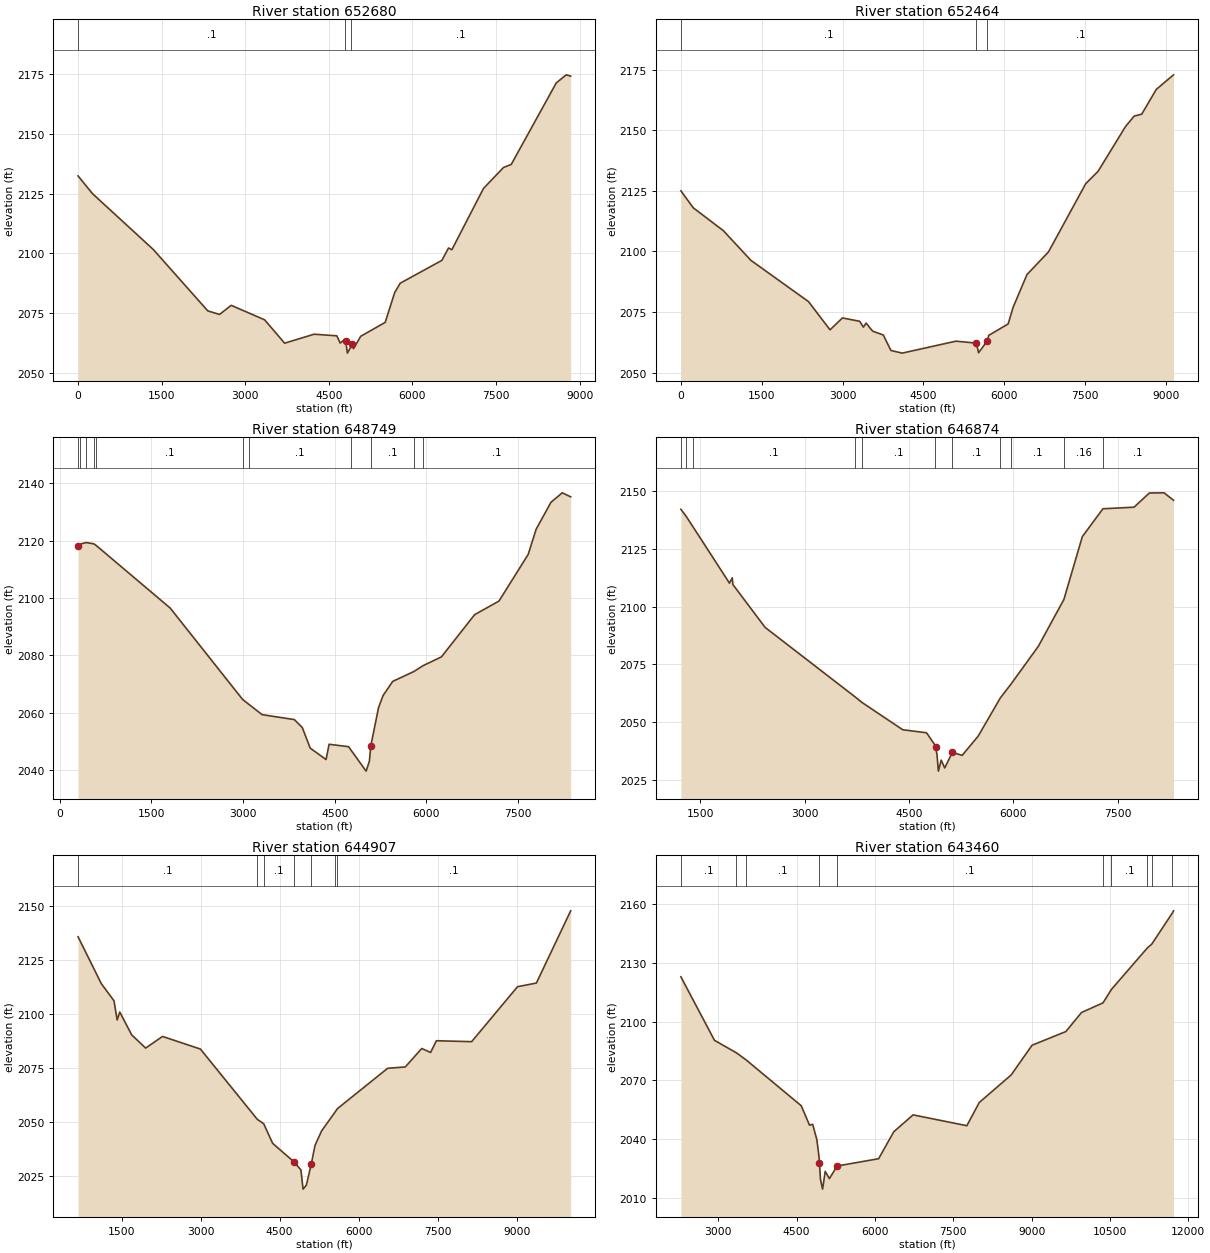
Type RM Length L Ch R = 1 ,652680  ,216,216,216
XS GIS Cut Line= 4
     2629932.438     10077714.73     2628929.834    10074693.897
     2625596.501    10074667.855     2624307.438    10072805.876
#Sta/Elev= 30
       02132.363259.86252124.9261349.2862101.6242328.7682075.9382538.6572074.457
2748.5462078.2623347.8962072.2073706.8512062.4414235.3122066.1874644.1212065.517
4703.9472062.4984783.7152063.9944803.6572063.2064833.5692058.2844903.3662061.255
4913.3372062.224 4943.25 2060.155072.8732065.3315511.5952071.1355681.1022083.544
5780.8112087.5036528.6332097.0536648.1872102.2216707.9642101.5067275.8452127.128
7634.5072135.8727773.9872137.1698580.9762171.2068760.3072174.6048840.0092174.045
#Mann= 3 ,-1 , 0
       0      .1       04783.715     .05       04903.366      .1       0
Bank Sta=4803.657,4913.337
XS Rating Curve= 0 ,0
Exp/Cntr=0.3,0.1

Type RM Length L Ch R = 1 ,652464  ,3715,3715,3715
XS GIS Cut Line= 4
     2630531.397    10077805.876     2629268.376    10074459.522
     2626039.209    10074472.543     2624515.772    10072662.647
#Sta/Elev= 30
       02125.021229.80882118.011789.34322108.5551298.9192096.347 2368.032079.327
2767.6972067.6852997.5062072.587 3317.24 2071.213387.1822068.796 3437.142070.482
3557.0312067.1453756.6852065.5463896.4432059.182 4106.082058.0715104.3492063.007
5483.6912062.1925523.6222058.2345683.3452063.0385713.2932065.412 6072.672070.105
6162.5152076.8616422.0652090.4856821.4162099.8417511.2082127.9467741.1392133.069
8250.9862151.5518410.9382155.8478550.8962156.6368820.8152166.8389140.7192172.859
#Mann= 3 , 0 , 0
       0      .1       05483.691     .07       05683.345      .1       0
Bank Sta=5483.691,5683.345
XS Rating Curve= 0 ,0
Exp/Cntr=0.3,0.1

Type RM Length L Ch R = 1 ,648749  ,1875,1875,1875
BEGIN DESCRIPTION:
PEDERNALES RIVER 26.0
END DESCRIPTION:
XS GIS Cut Line= 4
      2631142.64     10077340.16      2631055.83     10074388.82
      2629927.36     10072045.07      2627932.13     10070526.96
#Sta/Elev= 30
     299  2118.2   332.9 2118.76   431.4 2119.28     555 2118.86   597.6 2118.24
  1806.1  2096.5  2992.9 2064.64 3310.46 2059.38 3838.69 2057.65 3968.26  2054.9
 4097.82 2047.72 4356.96 2043.75 4406.79 2049.06 4725.72 2048.22  5012.4 2039.71
  5066.4 2043.18  5088.6 2048.41  5216.3 2061.84  5289.7    2066  5448.1 2070.95
  5794.6 2074.39  5942.9 2076.41  6245.3 2079.49  6787.9 2094.17  7187.1 2098.93
  7665.3 2115.18  7794.2 2123.89  8037.5 2133.32  8222.5  2136.6    8360 2135.21
#Mann= 11 ,-1 , 0
     299      .1       0   332.9     .16       0   431.4      .1       0
     555     .16       0   597.6      .1       0  2992.9     .05       0
  3091.4      .1       0  4758.3     .07       0  5088.6      .1       0
  5794.6     .05       0  5942.9      .1       0
Bank Sta=299,5088.6
XS Rating Curve= 0 ,0
Exp/Cntr=0.3,0.1

Type RM Length L Ch R = 1 ,646874  ,1967,1967,1967
BEGIN DESCRIPTION:
PEDERNALES RIVER 27.0
END DESCRIPTION:
XS GIS Cut Line= 3
      2632136.11     10077078.67      2631904.05     10074688.74
      2632328.26     10070028.28
#Sta/Elev= 30
  1221.2 2141.99  1295.1 2139.04  1398.8 2134.27  1919.4 2110.12  1959.6  2112.4
  1968.7 2109.52  2431.8 2091.02  3725.2 2061.03  3823.5 2058.64  4410.6 2046.83
    4752 2045.54  4872.5 2040.27  4882.6 2039.35  4902.6 2036.14  4922.5 2028.98
  4962.9 2033.73  5013.1 2030.34  5123.6  2037.1  5264.1 2035.77  5495.7 2044.14
    5813 2060.58  5963.5 2066.43  6358.6 2082.83  6726.4 2103.06  6991.2 2130.17
  7287.4 2142.21  7734.3 2142.89  7955.2 2149.02  8166.1 2149.09  8302.1 2145.89
#Mann= 11 ,-1 , 0
  1221.2      .1       0  1295.1     .05       0  1398.8      .1       0
  3725.2     .05       0  3823.5      .1       0  4872.5     .07       0
  5123.6      .1       0    5813     .16       0  5963.5      .1       0
  6726.4     .16       0  7287.4      .1       0
Bank Sta=4882.6,5123.6
XS Rating Curve= 0 ,0
Exp/Cntr=0.3,0.1

Type RM Length L Ch R = 1 ,644907  ,1447,1447,1447
BEGIN DESCRIPTION:
PEDERNALES RIVER 28.0
END DESCRIPTION:
XS GIS Cut Line= 4
      2633318.47     10078025.89      2633237.79     10075681.15
      2634194.21     10071894.68      2632576.24      10069249.5
#Sta/Elev= 30
   672.7 2135.97  1115.1 2114.17  1355.3 2106.25  1415.3 2097.36  1465.3 2101.03
  1690.5 2090.46  1955.6  2084.3  2276.5 2089.71  2996.2 2083.85  4076.3 2051.23
  4197.1 2049.21  4367.3 2040.11  4769.6 2031.55  4903.6 2027.77  4944.7 2018.86
    5007 2020.69  5099.6 2030.43  5171.8 2039.16  5295.6 2045.85    5547 2054.44
  5597.2 2056.21  6551.2 2074.94  6884.7 2075.54  7197.4 2084.11  7365.7 2082.27
  7475.9 2087.71  8144.5 2087.28  9016.2 2112.79  9374.1 2114.48   10025 2147.99
#Mann= 7 ,-1 , 0
   672.7      .1       0  4076.3     .05       0  4197.1      .1       0
  4769.6     .07       0  5099.6      .1       0    5547     .16       0
  5597.2      .1       0
Bank Sta=4769.6,5099.6
XS Rating Curve= 0 ,0
Exp/Cntr=0.3,0.1

Type RM Length L Ch R = 1 ,643460  ,2615,2615,2615
BEGIN DESCRIPTION:
PEDERNALES RIVER 29.0
END DESCRIPTION:
XS GIS Cut Line= 3
      2634957.72     10077047.05      2634976.86     10069950.79
      2633566.61     10068089.37
#Sta/Elev= 30
  2286.1 2122.86  2929.4 2090.46    3350 2084.07  3531.2 2080.55  4589.4 2057.13
  4749.4 2047.19  4809.4 2047.64  4889.4 2039.81  4931.6 2030.83  4939.4 2027.84
  4959.4 2019.46  4999.2 2014.58  5049.4 2023.64  5129.4 2019.96  5279.4 2026.38
 6072.05 2030.09  6361.9 2043.83 6731.71 2052.44 7761.16 2046.92  7999.4 2058.77
  8609.4  2072.8  9009.4 2087.95    9657 2094.94  9956.6 2104.65 10367.9 2109.56
 10527.8 2116.37 11219.1 2137.65 11300.5 2139.48   11696  2155.4 11717.7 2156.49
#Mann= 10 ,-1 , 0
  2286.1      .1       0    3350     .16       0  3531.2      .1       0
  4931.6     .07       0  5279.4      .1       0 10367.9     .16       0
 10527.8      .1       0 11219.1     .16       0 11300.5      .1       0
   11696     .16       0
Bank Sta=4939.4,5279.4
XS Rating Curve= 0 ,0
Exp/Cntr=0.3,0.1