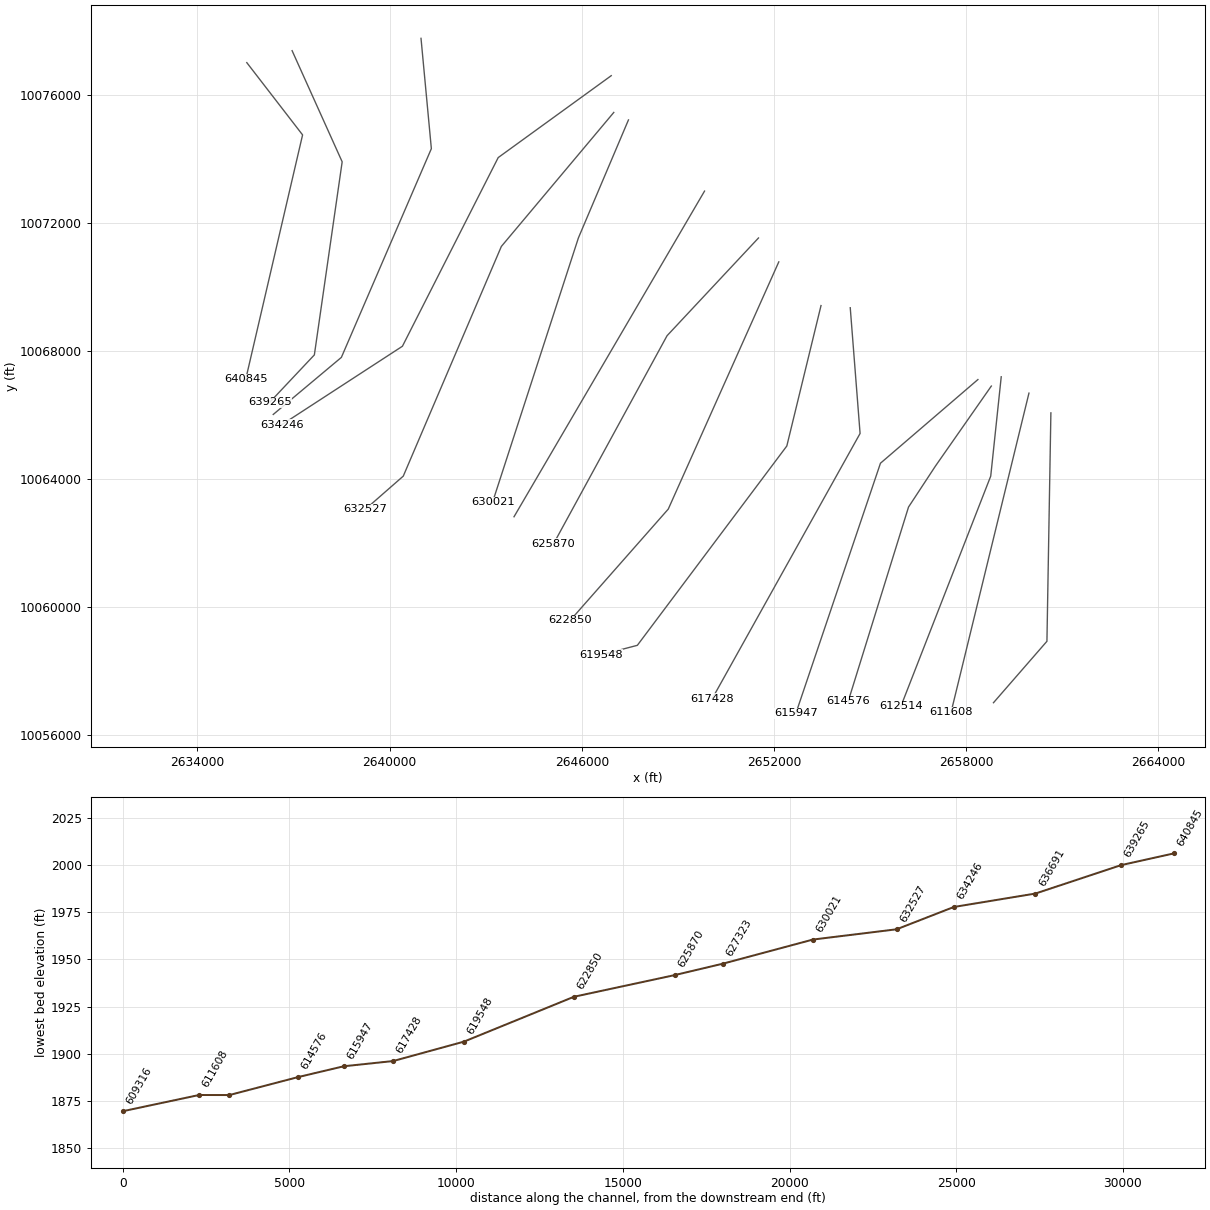
HEC-RAS study PEDERNALES RIVER.prj: PEDERNALES RIVER Base Level Engineering

--- PEDERNALES RIVER.g01 (geometry) --- (continued)

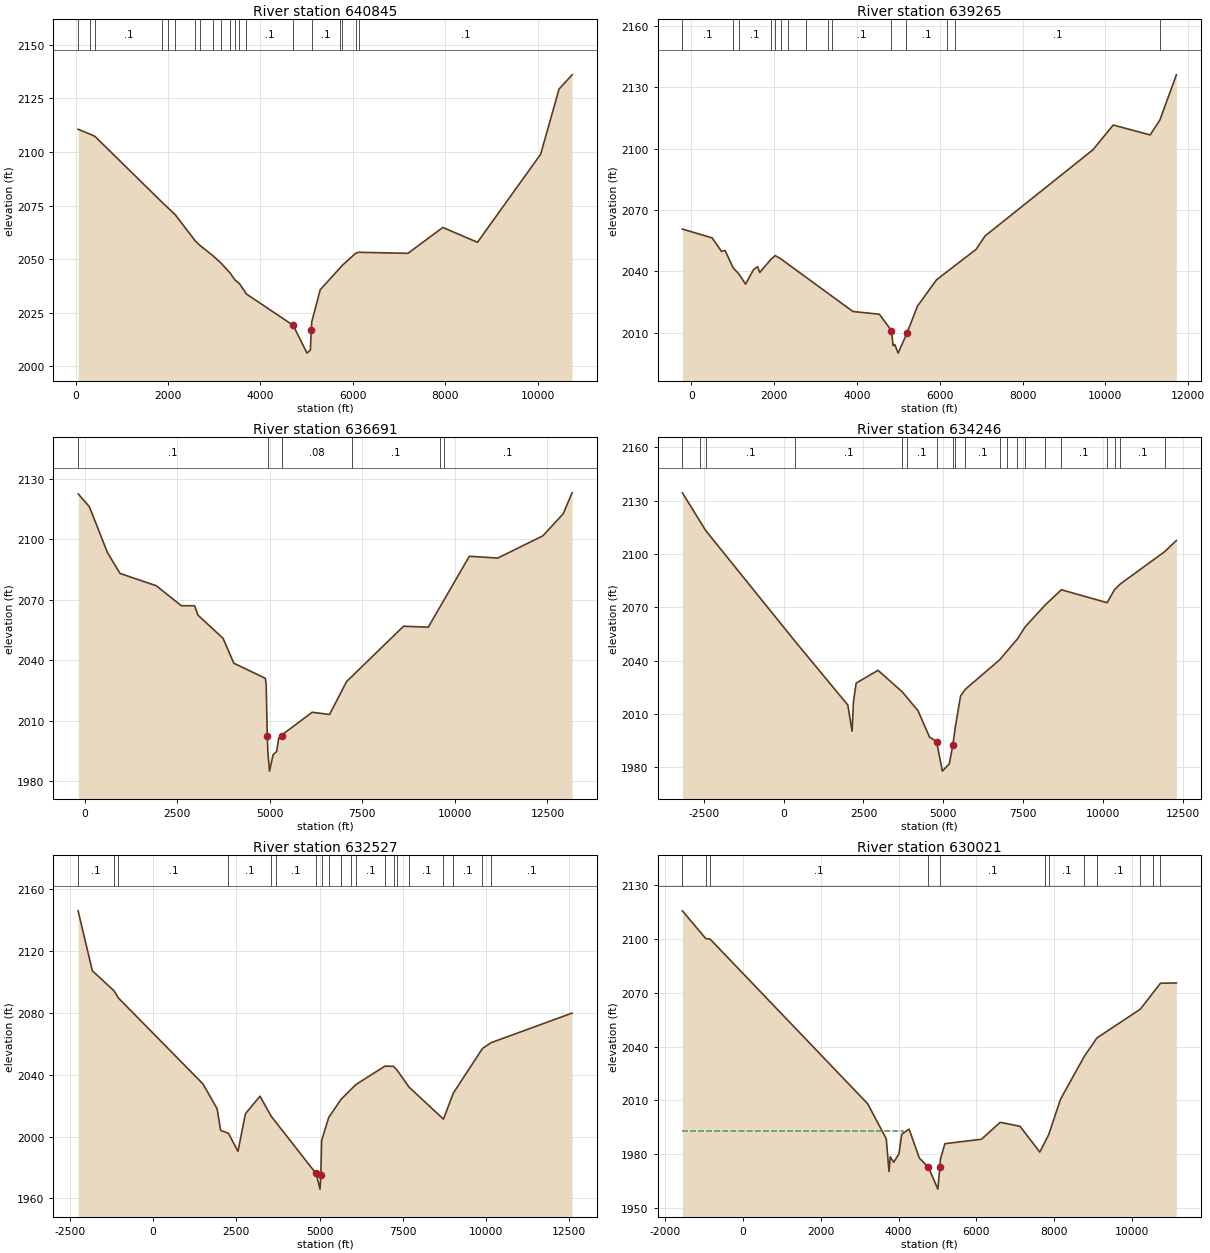
Type RM Length L Ch R = 1 ,640845  ,1580,1580,1580
BEGIN DESCRIPTION:
PEDERNALES RIVER 30.0
END DESCRIPTION:
XS GIS Cut Line= 3
      2635544.11     10077010.62      2637285.35     10074752.62
      2635509.69     10067114.19
#Sta/Elev= 30
    52.6 2110.62   300.9 2108.41   416.6  2107.3  1877.6 2076.42  1997.6 2073.97
  2157.5  2070.7  2589.4 2058.52  2698.7  2056.3  2972.6  2051.6    3138 2048.39
  3342.1 2043.61  3444.1 2040.45  3546.1 2038.59  3697.5 2033.77  4709.8 2019.16
  5007.3 2006.21  5080.5 2007.69  5099.9  2017.2  5110.2 2020.73  5293.5 2035.77
  5711.6  2045.7  5769.5 2047.11  6061.6 2052.78  6129.3 2053.24  7192.7 2052.75
    7948 2064.82  8698.1  2057.9 10065.4 2098.96 10464.3 2129.37 10746.1    2136
#Mann= 20 ,-1 , 0
    52.6      .1       0   300.9     .05       0   416.6      .1       0
  1877.6     .05       0  1997.6     .08       0  2157.5     .05       0
  2589.4     .08       0  2698.7     .05       0  2972.6     .08       0
    3138      .1       0  3342.1      .1       0  3444.1     .08       0
  3546.1     .05       0  3697.5      .1       0  4709.8     .07       0
  5110.2      .1       0  5711.6     .16       0  5769.5      .1       0
  6061.6     .16       0  6129.3      .1       0
Bank Sta=4709.8,5099.9
XS Rating Curve= 0 ,0
Exp/Cntr=0.3,0.1

Type RM Length L Ch R = 1 ,639265  ,2574,2574,2574
BEGIN DESCRIPTION:
PEDERNALES RIVER 31.0
END DESCRIPTION:
XS GIS Cut Line= 4
       2636958.6     10077383.63      2638521.11     10073911.39
      2637653.05      10067878.4      2636264.18     10066402.73
#Sta/Elev= 30
  -216.1 2060.69   502.3 2056.36   727.1 2049.77   814.2 2050.24  1013.3 2041.59
  1142.3 2038.85  1310.1 2033.74  1500.8 2040.83  1598.8 2042.29  1650.6 2039.46
  1919.4  2045.8  2025.2 2047.72  2169.5 2045.99  2342.4 2043.43 3901.33 2020.37
 4540.82 2019.03  4831.8 2011.03  4872.2 2003.65  4913.4 2004.21  4993.2 2000.01
 5210.28 2009.94 5460.08 2022.98 5919.71 2035.85  6876.4 2050.76  7094.9 2057.35
  9700.3 2099.49 10188.2 2111.56   11080 2106.72 11315.5 2114.02 11713.1 2136.11
#Mann= 15 ,-1 , 0
  -216.1      .1       0  1013.3     .05       0  1142.3      .1       0
  1919.4     .08       0  2025.2     .05       0  2169.5      .1       0
  2342.4     .05       0  2765.5      .1       0  3294.3     .05       0
  3399.2      .1       0  4831.8     .07       0  5191.2      .1       0
  6174.4     .16       0  6357.7      .1       0 11315.5     .16       0
#XS Ineff= 2 , 0
         3488.64 2024.71
Permanent Ineff=
       F       F
Bank Sta=4831.8,5210.28
XS Rating Curve= 0 ,0
Exp/Cntr=0.3,0.1

Type RM Length L Ch R = 1 ,636691  ,2445,2445,2445
BEGIN DESCRIPTION:
PEDERNALES RIVER 32.0
END DESCRIPTION:
XS GIS Cut Line= 4
      2640982.23     10077769.71       2641305.3     10074322.93
      2638496.42     10067800.68      2636369.76     10066018.11
#Sta/Elev= 30
    -174 2122.53   125.3  2116.2  614.15 2093.43  953.35 2083.07 1931.05 2076.98
 2609.45 2067.04 2968.61 2067.03  3058.4 2062.34 3737.31 2050.85 4026.96  2038.5
  4878.6    2031  4902.1 2027.75  4931.1 2002.46  4947.8 1994.19  4991.1 1984.91
  5089.3  1993.1  5182.7 1994.64  5241.7 2001.42    5318 2002.34  5328.8 2002.93
  6144.4 2014.14 6613.83 2013.03 7073.27 2029.38 8611.41 2056.84 9280.61 2056.39
10389.27  2091.611158.11 2090.7112376.25 2101.7612925.42 2112.6913165.05  2123.1
#Mann= 6 ,-1 , 0
  -179.1      .1       0  4947.8     .07       0  5328.8     .08       0
  7226.5      .1       0  9596.8     .16       0  9702.5      .1       0
Bank Sta=4931.1,5318
XS Rating Curve= 0 ,0
Exp/Cntr=0.3,0.1

Type RM Length L Ch R = 1 ,634246  ,1719,1719,1719
BEGIN DESCRIPTION:
PEDERNALES RIVER 33.0
END DESCRIPTION:
XS GIS Cut Line= 4
      2646920.71     10076603.28        2643392.      10074043.9
      2640402.06     10068148.84      2636633.42      10065695.2
#Sta/Elev= 30
 -3169.4 2134.47 -2629.5 2118.77 -2442.1  2113.3   363.6 2050.76  2009.3 2015.02
    2143  2000.3  2187.9 2017.14  2270.9 2027.36  2955.5 2034.54  3718.9 2022.33
 4208.11  2011.8 4568.11 1996.97  4786.8 1994.46  4970.3  1977.8  5187.6 1981.95
  5298.9 1992.68  5377.1 2002.75  5538.3 2020.02  5688.9 2023.87  6760.3 2040.42
  6983.1 2045.12  7321.5 2052.25  7563.1 2059.05  8191.4 2071.37    8695  2079.9
 10127.1 2072.63 10360.2 2079.96 10540.3 2083.14 11928.1 2101.34 12296.7 2107.61
#Mann= 20 ,-1 , 0
 -3169.4      .1       0 -2629.5     .05       0 -2442.1      .1       0
   363.6      .1       0  3718.9     .05       0  3866.7      .1       0
  4786.8     .07       0  5298.9      .1       0  5377.1     .16       0
  5688.9      .1       0  6760.3     .05       0  6983.1      .1       0
  7321.5     .05       0  7563.1      .1       0  8191.4      .1       0
    8695      .1       0 10127.1     .16       0 10360.2     .16       0
 10540.3      .1       0 11928.1      .1       0
Bank Sta=4786.8,5298.9
XS Rating Curve= 0 ,0
Exp/Cntr=0.3,0.1

Type RM Length L Ch R = 1 ,632527  ,2506,2506,2506
BEGIN DESCRIPTION:
PEDERNALES RIVER 34.0
END DESCRIPTION:
XS GIS Cut Line= 4
      2646999.48     10075454.03       2643490.1     10071267.22
      2640428.57     10064090.86      2639248.32     10063057.78
#Sta/Elev= 30
 -2250.9 2146.17 -1823.8 2107.36 -1172.3 2094.38   -1039 2089.68  1497.7  2034.1
  1924.4 2017.93  2029.8 2003.97  2264.6 2002.11  2548.9 1990.38  2775.3 2014.82
  3211.2 2026.13  3547.5 2013.14  4885.2 1976.29  4890.6 1976.57  5013.9 1965.95
  5037.7 1975.13  5061.4 1997.44  5273.9 2012.31  5640.8    2024  5946.2 2030.55
  6092.6 2033.67  6967.9 2045.67  7223.1 2045.41    7335 2042.79  7689.6 2031.94
  8719.2  2011.3  9019.6 2028.24  9892.6 2057.04 10152.4  2060.8 12582.8 2079.94
#Mann= 20 ,-1 , 0
 -2250.9      .1       0 -1172.3     .05       0   -1039      .1       0
  2264.6      .1       0  3547.5     .05       0  3687.7      .1       0
  4885.2     .07       0  5061.4      .1       0  5273.9     .16       0
  5640.8      .1       0  5946.2     .05       0  6092.6      .1       0
  6967.9      .1       0  7223.1     .05       0    7335      .1       0
  7689.6      .1       0  8719.2     .16       0  9019.6      .1       0
  9892.6     .05       0 10152.4      .1       0
Bank Sta=4890.6,5037.7
XS Rating Curve= 0 ,0
Exp/Cntr=0.3,0.1

Type RM Length L Ch R = 1 ,630021  ,2698,2698,2698
BEGIN DESCRIPTION:
PEDERNALES RIVER 36.0
END DESCRIPTION:
XS GIS Cut Line= 3
      2647457.98     10075220.77      2645895.84     10071534.53
      2643216.28     10063278.14
#Sta/Elev= 30
 -1548.7 2115.82  -947.9 2100.33    -839 2100.09  3207.5 2008.19  3685.8 1988.64
  3756.2 1970.35  3788.2  1978.6    3875 1975.49  4011.7 1980.19 4082.79 1991.14
 4272.59 1994.02    4534  1977.9  4768.7 1972.69  5010.2 1960.52  5063.1 1972.79
  5073.6 1977.02 5191.61 1985.88 6130.61 1988.36  6610.1  1997.8 7119.56  1995.6
  7628.3  1981.2  7764.8 1986.96  7859.5 1991.11  8161.6 2010.76  8770.9 2034.62
  9095.2 2044.89 10210.8 2060.96 10527.3 2069.84 10726.2 2075.41 11135.2 2075.56
#Mann= 12 ,-1 , 0
 -1548.7      .1       0  -947.9     .05       0    -839      .1       0
  4768.7     .07       0  5073.6      .1       0  7764.8     .16       0
  7859.5      .1       0  8770.9     .16       0  9095.2      .1       0
 10210.8     .16       0 10527.3      .1       0 10726.2     .16       0
#XS Ineff= 2 , 0
         4117.05 1992.84
Permanent Ineff=
       F       F
Bank Sta=4768.7,5063.1
XS Rating Curve= 0 ,0
Exp/Cntr=0.3,0.1

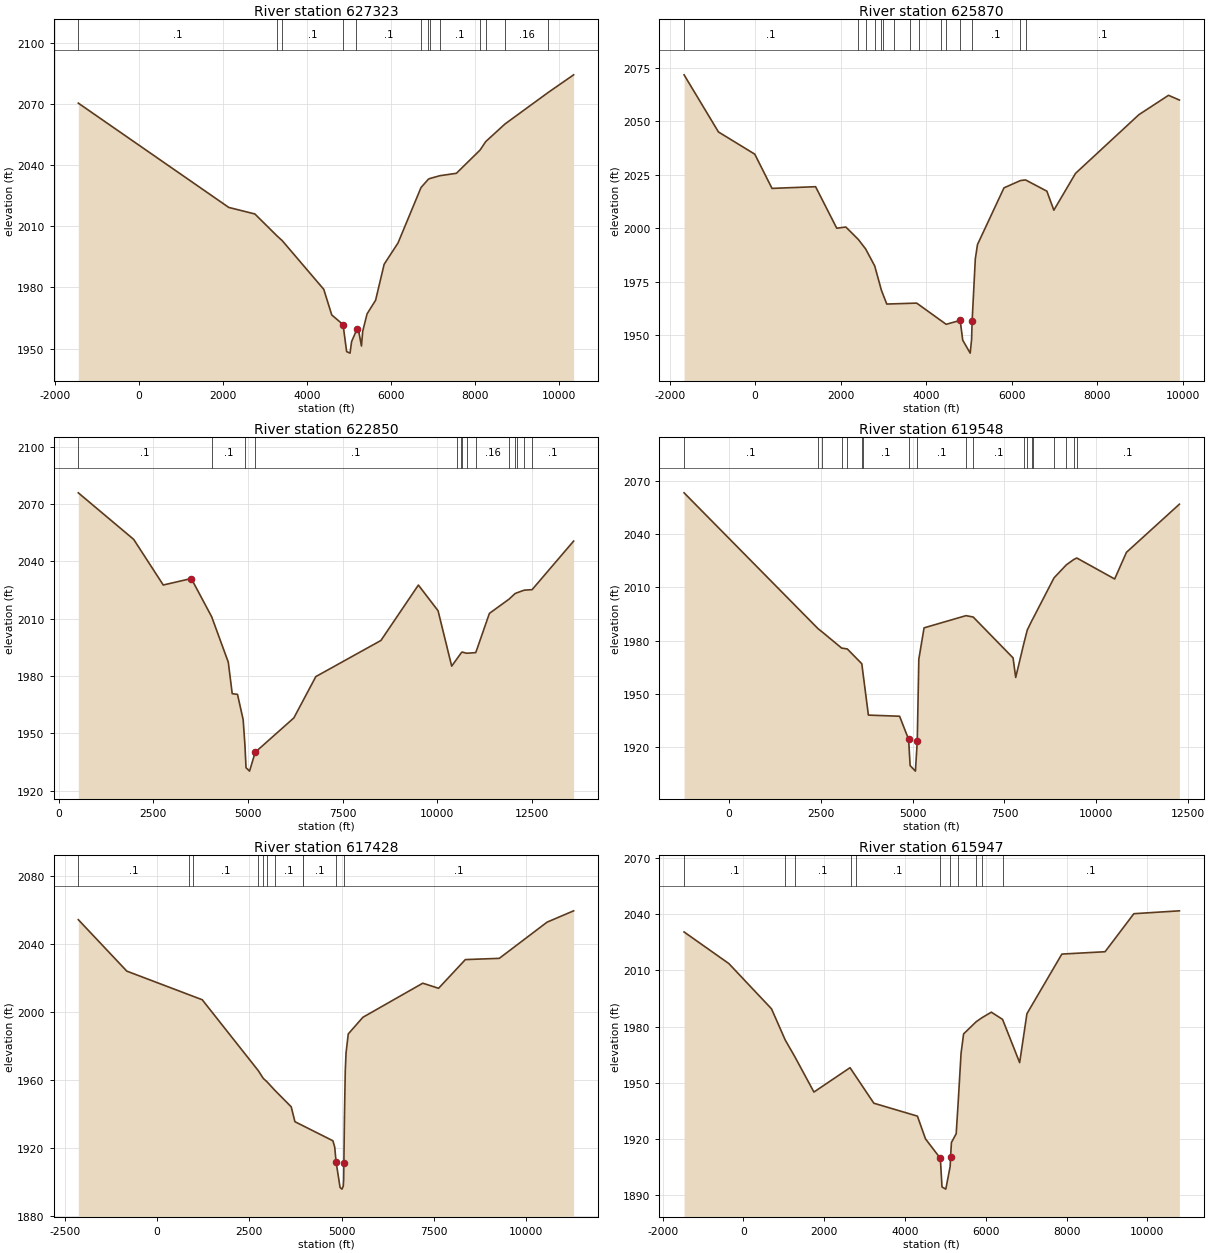
Type RM Length L Ch R = 1 ,627323  ,1453,1453,1453
BEGIN DESCRIPTION:
PEDERNALES RIVER 37.0
END DESCRIPTION:
XS GIS Cut Line= 2
      2649832.53     10072996.27      2643885.65     10062821.17
#Sta/Elev= 30
 -1436.8 2070.44  2143.9 2019.25  2763.8 2016.05  3295.1  2005.2  3416.6 2002.92
 4403.82 1979.05 4593.75 1966.49  4862.4 1961.75  4948.4 1948.48    5029 1947.74
  5065.7 1953.38  5168.3  1958.3  5183.1 1959.82  5220.3 1960.12  5300.5 1951.24
  5330.4 1958.44  5433.5 1966.99  5636.9 1973.69  5840.2 1991.34  6170.8 2001.83
  6718.1 2029.03  6893.8 2033.11  6929.2 2033.45  7167.3 2034.82  7559.4    2036
  8122.8 2047.41  8257.4 2051.57  8716.4 2060.21  9740.7 2075.63 10348.7 2084.33
#Mann= 13 ,-1 , 0
 -1436.8      .1       0  3295.1     .05       0  3416.6      .1       0
  4862.4     .07       0  5168.3      .1       0  6718.1     .16       0
  6893.8      .1       0  6929.2     .16       0  7167.3      .1       0
  8122.8     .16       0  8257.4      .1       0  8716.4     .16       0
  9740.7      .1       0
Bank Sta=4862.4,5183.1
XS Rating Curve= 0 ,0
Exp/Cntr=0.3,0.1

Type RM Length L Ch R = 1 ,625870  ,3020,3020,3020
BEGIN DESCRIPTION:
PEDERNALES RIVER 38.0
END DESCRIPTION:
XS GIS Cut Line= 3
      2651516.67     10071531.92       2648662.3     10068477.06
      2645120.32     10061977.59
#Sta/Elev= 30
 -1662.7 2071.79  -858.5 2045.07    -9.4 2034.69   393.6 2018.68  1412.6 2019.48
  1907.5 2000.06    2120 2000.62  2411.2 1994.83  2583.3 1990.36  2795.4 1982.41
  2951.5 1971.07 3077.36  1964.6 3776.73 1965.04 4466.12 1955.13  4793.8 1956.95
  4853.6 1947.71    5028 1941.65  5060.6 1948.06    5073 1956.48  5147.9 1985.74
  5198.3 1992.41  5818.3 2018.94  6204.2 2022.36  6323.3 2022.64  6820.9 2017.39
  6984.2  2008.5  7491.2 2025.71  8973.3 2053.16  9665.5 2062.21  9920.1    2060
#Mann= 15 ,-1 , 0
 -1662.7      .1       0  2411.2     .05       0  2583.3      .1       0
  2795.4     .16       0  2951.5      .1       0  2989.4     .16       0
  3249.8      .1       0  3619.2     .05       0  3830.5      .1       0
  4355.9     .05       0  4470.7      .1       0  4793.8     .07       0
  5060.6      .1       0  6204.2     .16       0  6323.3      .1       0
Bank Sta=4793.8,5073
XS Rating Curve= 0 ,0
Exp/Cntr=0.3,0.1

Type RM Length L Ch R = 1 ,622850  ,3302,3302,3302
BEGIN DESCRIPTION:
PEDERNALES RIVER 39.0
END DESCRIPTION:
XS GIS Cut Line= 3
      2652150.61     10070784.28      2648700.67     10063060.66
      2645644.09     10059588.04
#Sta/Elev= 30
   516.4 2075.77  1979.8 2051.41    2761 2027.54  3501.1 2030.93  4039.2 2010.96
  4478.9 1987.16  4582.7 1970.67    4722 1970.32  4872.2 1957.03  4918.6 1943.64
  4947.3 1931.96  5039.9 1930.16  5190.4 1940.04 6211.37 1958.01 6791.31 1979.62
 8511.13 1998.52 9500.86 2027.5110020.65 2014.08 10380.5  1985.1 10632.2 1992.02
 10655.8 1992.47 10774.5 1991.83 11016.7 1992.17 11376.9 2012.69 11894.3 2020.12
 12055.9 2023.07 12094.6 2023.39 12298.2 2024.85 12504.8 2025.11 13601.7 2050.52
#Mann= 14 ,-1 , 0
   516.4      .1       0  4039.2      .1       0  4918.6     .07       0
  5190.4      .1       0 10519.5     .16       0 10632.2      .1       0
 10655.8     .16       0 10774.5      .1       0 11016.7     .16       0
 11894.3      .1       0 12055.9     .16       0 12094.6      .1       0
 12298.2     .16       0 12504.8      .1       0
Bank Sta=3501.1,5190.4
XS Rating Curve= 0 ,0
Exp/Cntr=0.3,0.1

Type RM Length L Ch R = 1 ,619548  ,2120,2120,2120
BEGIN DESCRIPTION:
PEDERNALES RIVER 40.0
END DESCRIPTION:
XS GIS Cut Line= 4
      2653468.94     10069419.68      2652401.32     10065031.83
      2647735.61     10058804.22      2646593.33     10058504.18
#Sta/Elev= 30
 -1219.2 2063.29  2428.9 1986.62  2537.2 1984.87  3068.8 1975.74  3221.7 1975.25
 3616.53 1966.92 3796.33 1937.95 4645.41  1937.3  4890.8 1924.29  4932.5 1909.46
    5076 1906.35  5126.2 1923.22  5132.5 1929.91  5168.6  1969.5  5311.7 1987.15
  6451.8 1994.03  6647.8 1993.26  7732.9 1970.21    7805 1959.17  8020.9 1977.89
    8120 1985.93  8245.9 1991.28  8282.5 1992.69  8847.4 2015.33  9183.5  2022.7
    9386  2025.7  9467.2 2026.54 10497.9 2014.71 10818.8 2029.74 12259.2 2056.88
#Mann= 19 ,-1 , 0
 -1219.2      .1       0  2428.9     .16       0  2537.2      .1       0
  3068.8     .05       0  3221.7      .1       0  3623.8     .16       0
  3638.3      .1       0  4890.8     .07       0  5132.5      .1       0
  6451.8     .16       0  6647.8      .1       0  8020.9     .16       0
    8120      .1       0  8245.9     .16       0  8282.5      .1       0
  8847.4     .16       0  9183.5      .1       0    9386     .16       0
  9467.2      .1       0
Bank Sta=4890.8,5126.2
XS Rating Curve= 0 ,0
Exp/Cntr=0.3,0.1

Type RM Length L Ch R = 1 ,617428  ,1481,1481,1481
BEGIN DESCRIPTION:
PEDERNALES RIVER 41.0
END DESCRIPTION:
XS GIS Cut Line= 3
      2654381.23     10069352.38       2654688.4     10065423.64
      2650073.34     10057139.45
#Sta/Elev= 30
 -2133.9 2054.44  -819.3  2024.2   857.6  2010.4   966.7  2009.5    1225 2007.38
  2746.7 1965.62  2881.4 1961.08  2978.3 1959.21    3186  1954.3 3636.43 1944.46
 3736.35 1935.71  4765.6  1924.5 4815.57 1920.77  4851.6 1912.14  4960.6 1897.05
  5011.7 1896.07  5047.5 1897.82  5057.7 1901.82  5063.5 1911.41  5079.5 1939.05
  5101.2 1965.55  5122.9 1976.25  5182.4 1987.28  5577.9 1997.05  7202.3 2017.11
  7629.8 2014.11  8355.7 2030.98  9275.9 2031.71 10569.9 2052.98 11289.8 2059.64
#Mann= 11 ,-1 , 0
 -2133.9      .1       0   857.6     .16       0   966.7      .1       0
  2746.7     .05       0  2881.4      .1       0  2978.3     .16       0
    3186      .1       0  3947.6     .05       0  3957.3      .1       0
  4851.6     .07       0  5063.5      .1       0
Bank Sta=4851.6,5063.5
XS Rating Curve= 0 ,0
Exp/Cntr=0.3,0.1

Type RM Length L Ch R = 1 ,615947  ,1371,1371,1371
BEGIN DESCRIPTION:
PEDERNALES RIVER 42.0
END DESCRIPTION:
XS GIS Cut Line= 3
      2658366.42     10067108.11      2655324.49     10064493.67
      2652683.81     10056677.77
#Sta/Elev= 30
 -1470.1 2030.42  -362.5 2013.58   694.2 1989.44  1033.6 1972.82  1271.2 1963.92
  1744.4 1945.07 2637.96 1958.05 3227.41 1939.11 4306.41 1932.22 4506.22 1920.08
  4873.6 1909.74  4914.5 1894.46  5008.7  1893.3  5116.4  1905.4    5127 1910.52
  5148.1 1918.17  5265.8 1922.86  5314.4 1939.37  5386.4 1965.75  5449.3 1976.08
  5760.7 1982.55  5899.9 1984.65    6136 1987.65  6413.7 1983.81  6836.9 1960.76
  7016.7 1986.83  7881.5 2018.63    8951 2019.88  9663.9 2040.16 10790.9 2041.69
#Mann= 11 ,-1 , 0
 -1470.1      .1       0  1033.6     .16       0  1271.2      .1       0
    2665     .05       0  2781.5      .1       0  4873.6     .07       0
  5116.4      .1       0  5314.4     .16       0  5760.7      .1       0
  5899.9     .16       0  6413.7      .1       0
Bank Sta=4873.6,5127
XS Rating Curve= 0 ,0
Exp/Cntr=0.3,0.1

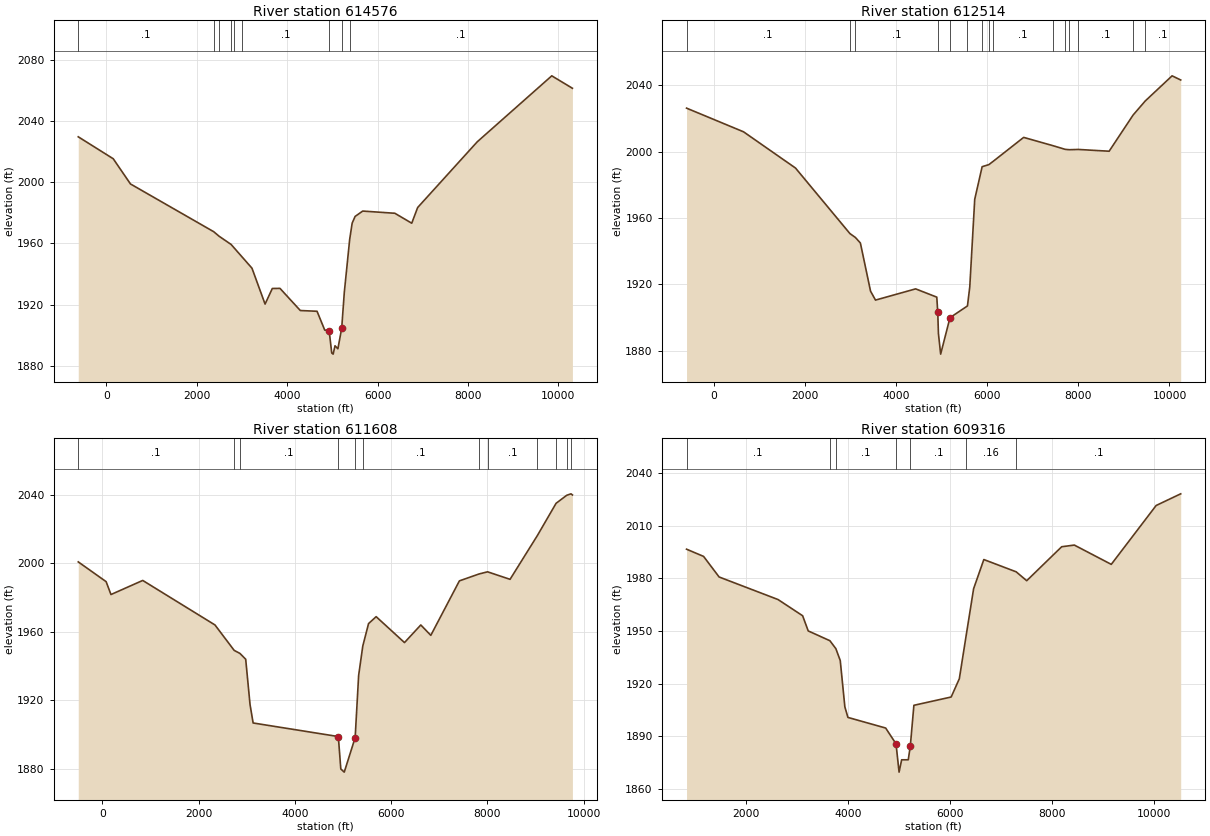
Type RM Length L Ch R = 1 ,614576  ,2062,2062,2062
BEGIN DESCRIPTION:
PEDERNALES RIVER 43.0
END DESCRIPTION:
XS GIS Cut Line= 4
      2658785.51     10066904.76       2657044.3     10064409.97
       2656200.2     10063123.84      2654319.15      10057059.5
#Sta/Elev= 30
  -619.3 2029.66   154.7 2015.31   535.9 1998.83  2378.4 1967.58  2493.9 1964.69
  2762.3 1959.26 3223.48 1943.74 3513.17 1920.28 3673.01 1930.48 3842.83 1930.55
 4292.67 1916.07 4662.62 1915.58 4832.61 1903.28  4929.6    1903  4987.6 1888.29
  5018.8 1887.56    5060 1893.02  5123.7 1891.06  5207.5 1904.39  5265.9  1928.1
  5384.6 1962.64  5439.3 1973.21  5504.5 1977.59  5672.6  1981.1    6383 1979.67
  6757.1 1973.16  6887.5  1983.4  8205.3 2026.37  9854.2 2069.53 10310.8  2061.4
#Mann= 9 ,-1 , 0
  -619.3      .1       0  2378.4     .16       0  2493.9      .1       0
  2762.3     .16       0  2826.8     .05       0  2991.7      .1       0
  4929.6     .07       0  5207.5     .16       0  5384.6      .1       0
Bank Sta=4929.6,5207.5
XS Rating Curve= 0 ,0
Exp/Cntr=0.3,0.1

Type RM Length L Ch R = 1 ,612514  ,906,906,906
BEGIN DESCRIPTION:
PEDERNALES RIVER 44.0
END DESCRIPTION:
XS GIS Cut Line= 3
      2659094.56     10067194.92       2658766.9     10064091.92
      2655962.18     10056897.77
#Sta/Elev= 30
  -595.3 2026.18   655.4 2011.92    1795 1990.11  2988.1 1950.67  3109.4 1948.28
    3219 1944.94  3441.8 1915.95  3550.5 1910.57  4431.1 1917.33    4895 1912.35
  4916.5 1903.12  4931.1 1890.46  4979.8 1878.03  5184.8 1899.99  5567.9 1907.05
  5618.7  1918.5  5727.4 1971.28  5890.1 1990.92  6037.3 1992.16  6128.5 1994.06
  6800.9 2008.56  7441.4 2003.59  7713.5 2001.35  7806.6 2001.14  8000.6  2001.3
  8676.1 2000.23  9202.9 2022.05    9468 2030.48 10057.6 2045.64 10246.5 2043.13
#Mann= 15 ,-1 , 0
  -595.3      .1       0  2988.1     .05       0  3109.4      .1       0
  4916.5     .07       0  5184.8      .1       0  5567.9     .16       0
  5890.1      .1       0  6037.3     .16       0  6128.5      .1       0
  7441.4     .16       0  7713.5      .1       0  7806.6     .16       0
  8000.6      .1       0  9202.9     .16       0    9468      .1       0
Bank Sta=4916.5,5184.8
XS Rating Curve= 0 ,0
Exp/Cntr=0.3,0.1

Type RM Length L Ch R = 1 ,611608  ,2292,2292,2292
BEGIN DESCRIPTION:
PEDERNALES RIVER 45.0
END DESCRIPTION:
XS GIS Cut Line= 2
      2659960.04     10066684.38      2657526.84     10056707.91
#Sta/Elev= 30
  -500.4 2000.71    78.9 1989.18   179.6 1981.66   839.6 1989.88  2341.2 1963.91
  2740.1 1949.07  2859.8  1947.3  2979.3 1943.92  3069.6 1917.47  3133.7 1906.73
  4904.2 1898.81  4955.6 1879.91  5027.4 1878.06  5254.1 1898.21  5326.2 1934.46
  5412.6 1951.63    5532  1964.7  5690.3 1968.75  6279.1 1953.63  6617.7 1963.91
  6826.2 1957.86  7420.1 1989.63  7828.8 1993.66  8005.7 1994.91  8472.6 1990.53
  9042.6 2016.17  9428.9 2034.87  9650.5 2039.57  9739.3 2040.41  9768.5 2039.75
#Mann= 12 ,-1 , 0
  -500.4      .1       0  2740.1     .05       0  2859.8      .1       0
  4904.2     .07       0  5254.1     .16       0  5412.6      .1       0
  7828.8     .16       0  8005.7      .1       0  9042.6     .16       0
  9428.9      .1       0  9650.5     .16       0  9739.3      .1       0
Bank Sta=4904.2,5254.1
XS Rating Curve= 0 ,0
Exp/Cntr=0.3,0.1

Type RM Length L Ch R = 1 ,609316  ,1236,1236,1236
BEGIN DESCRIPTION:
PEDERNALES RIVER 46.0
END DESCRIPTION:
XS GIS Cut Line= 3
      2660644.49     10066067.51      2660521.13     10058930.31
      2658852.35      10057010.6
#Sta/Elev= 30
   834.5 1996.63  1168.3 1992.51  1472.8 1980.77  2626.6 1967.91  3108.6 1958.67
  3218.6    1950  3643.7 1944.41  3759.9  1939.9 3846.26 1933.09 3936.24 1906.68
 3996.22 1900.66 4736.04  1894.6  4938.9 1885.58  4998.6 1869.45  5048.9 1876.48
  5178.9 1876.49  5218.9  1884.4  5288.9 1907.57    6019  1912.3  6179.1 1922.72
  6315.7 1947.88  6459.1 1974.09  6659.1 1990.72  7292.5 1983.72  7499.3 1978.65
  8184.7 1998.03  8432.5 1998.97  9156.1 1987.97 10035.2 2021.56 10516.4 2028.21
#Mann= 7 ,-1 , 0
   834.5      .1       0  3643.7     .05       0  3759.9      .1       0
  4938.9     .07       0  5218.9      .1       0  6315.7     .16       0
  7292.5      .1       0
Bank Sta=4938.9,5218.9
XS Rating Curve= 0 ,0
Exp/Cntr=0.3,0.1