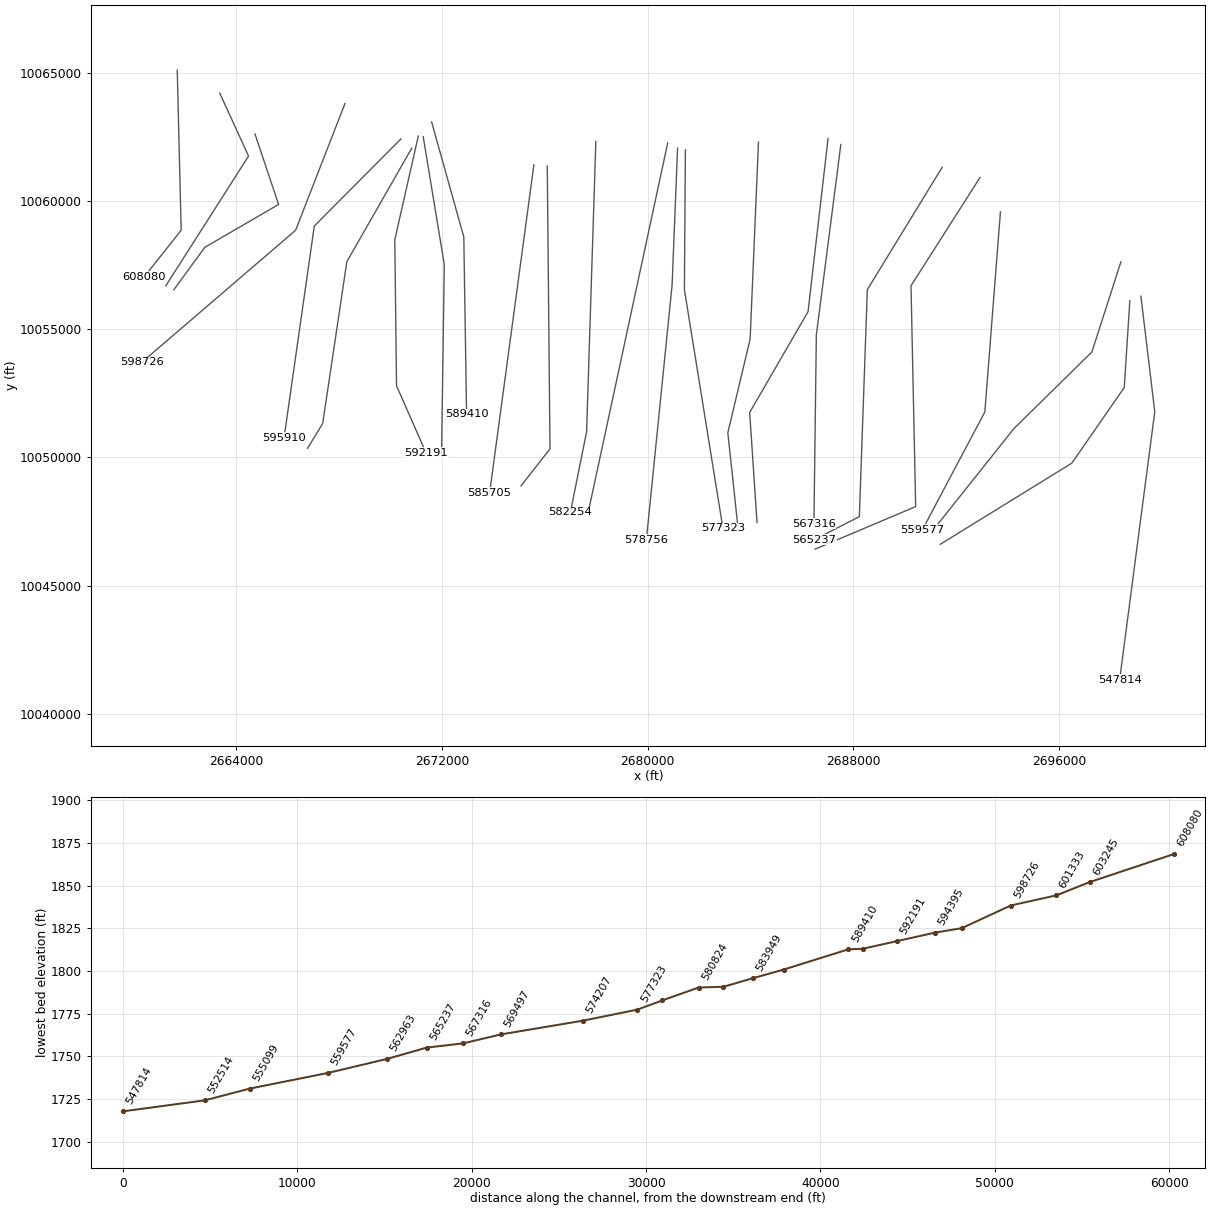
HEC-RAS study PEDERNALES RIVER.prj: PEDERNALES RIVER Base Level Engineering

--- PEDERNALES RIVER.g01 (geometry) --- (continued)

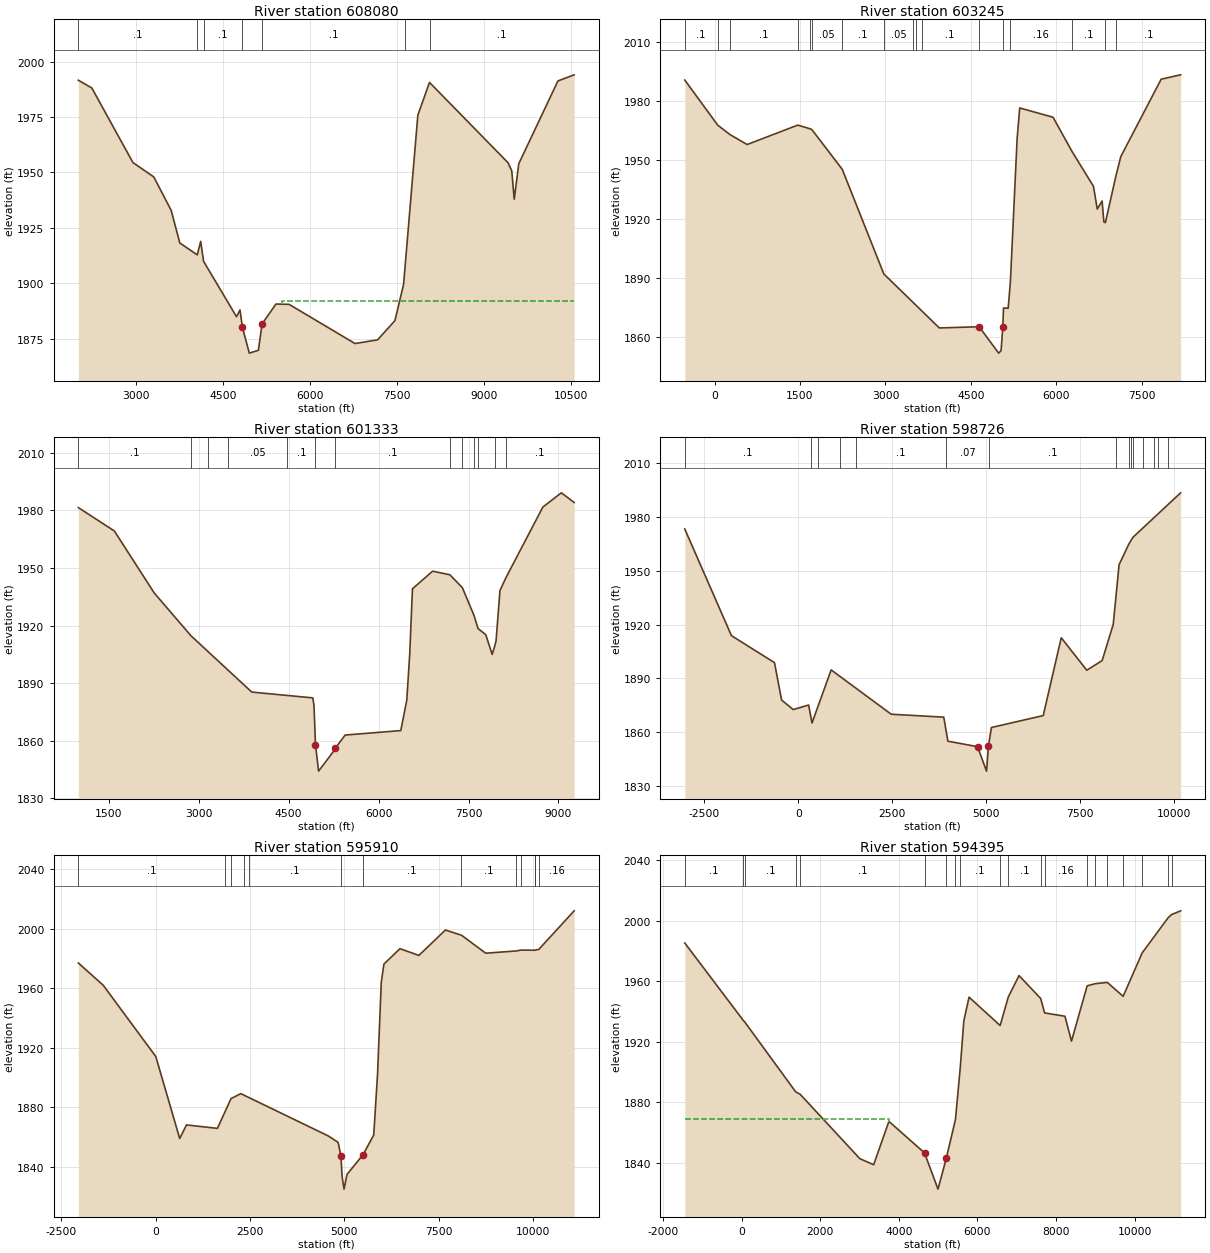
Type RM Length L Ch R = 1 ,608080  ,4835,4835,4835
BEGIN DESCRIPTION:
PEDERNALES RIVER 47.0
END DESCRIPTION:
XS GIS Cut Line= 3
      2661697.51     10065116.42      2661850.06       10058868.
      2660413.39     10057054.11
#Sta/Elev= 30
  1998.3 1991.61  2231.1 1988.12  2941.3 1954.45  3301.4 1947.95  3601.5 1932.89
  3751.5 1918.13  4052.7 1912.75 4111.72 1918.88 4161.64 1909.85 4730.76 1884.83
 4790.66  1887.9  4821.8 1882.05  4831.8 1880.09  4951.6  1868.4  5108.6 1869.67
  5171.9 1881.56    5412 1890.57 5639.35 1890.41 6777.58 1872.73 7166.97  1874.4
  7466.5 1883.07 7616.26 1899.43  7862.7 1975.86    8064 1990.62    9420 1954.38
  9484.2 1950.75  9527.4 1937.91    9606 1953.92 10282.3 1991.29 10562.5 1994.05
#Mann= 7 ,-1 , 0
  1998.3      .1       0  4052.7     .05       0  4173.4      .1       0
  4821.8     .07       0  5171.9      .1       0  7644.1     .16       0
    8064      .1       0
#XS Ineff= 2 , 0
                         5522.73         1891.71
Permanent Ineff=
       F       F
Bank Sta=4831.8,5171.9
XS Rating Curve= 0 ,0
Exp/Cntr=0.3,0.1

Type RM Length L Ch R = 1 ,603245  ,1912,1912,1912
BEGIN DESCRIPTION:
PEDERNALES RIVER 48.0
END DESCRIPTION:
XS GIS Cut Line= 3
      2663348.82      10064224.6      2664471.92     10061763.94
      2661250.85     10056699.31
#Sta/Elev= 30
  -523.1 1990.84    54.4 1967.95   266.6 1963.19   571.7 1958.06  1460.9 1967.94
  1670.8 1966.13  1708.3 1965.67  2242.2 1945.44  2971.9 1892.25 3946.55 1864.78
 4645.64  1865.4  4988.5 1851.98    5031 1853.23  5061.5 1865.39  5073.7 1874.92
  5155.5 1874.82  5194.5 1888.26    5313 1961.19  5358.1 1976.66  5943.8 1971.94
  6277.5  1954.5  6653.4 1936.81  6720.3 1925.27    6805 1929.34  6835.5 1918.74
  6862.7 1918.37  7049.7 1942.31  7132.7 1951.89  7842.3 1991.29  8183.9 1993.51
#Mann= 17 ,-1 , 0
  -523.1      .1       0    54.4     .16       0   266.6      .1       0
  1460.9     .05       0  1670.8      .1       0  1708.3     .05       0
  2242.2      .1       0  2971.9     .05       0  3485.2      .1       0
  3540.2     .05       0  3635.7      .1       0  4639.8     .07       0
  5061.5      .1       0  5194.5     .16       0  6277.5      .1       0
  6862.7     .16       0  7049.7      .1       0
Bank Sta=4645.64,5061.5
XS Rating Curve= 0 ,0
Exp/Cntr=0.3,0.1

Type RM Length L Ch R = 1 ,601333  ,2607,2607,2607
BEGIN DESCRIPTION:
PEDERNALES RIVER 49.0
END DESCRIPTION:
XS GIS Cut Line= 4
      2664722.07     10062626.34      2665640.29     10059876.74
      2662769.49     10058201.84      2661565.87     10056547.74
#Sta/Elev= 30
     993 1981.43  1594.3 1969.23  2257.9    1937  2872.2 1914.67 3884.86 1885.38
 4902.93 1882.35 4922.89 1878.29  4947.5 1858.05  4999.2 1844.22  5271.5 1855.44
  5277.2 1856.09  5441.9    1863 6370.13 1865.33 6469.94  1881.1 6519.85 1905.44
  6564.7 1939.14  6901.3 1948.33  7189.4 1946.43  7397.4 1939.72  7593.5 1925.11
  7657.7 1918.48  7787.5 1915.26  7894.1 1904.99  7938.1 1909.42    7959 1912.09
  8023.9 1938.21  8121.9 1944.82  8739.5 1981.71    9047 1989.11  9261.2 1984.11
#Mann= 13 ,-1 , 0
     993      .1       0  2872.2     .16       0  3149.1      .1       0
  3491.7     .05       0  4479.8      .1       0  4947.5     .07       0
  5271.5      .1       0  7189.4     .16       0  7397.4      .1       0
  7593.5     .16       0  7657.7      .1       0  7938.1     .16       0
  8121.9      .1       0
Bank Sta=4947.5,5277.2
XS Rating Curve= 0 ,0
Exp/Cntr=0.3,0.1

Type RM Length L Ch R = 1 ,598726  ,2816,2816,2816
BEGIN DESCRIPTION:
PEDERNALES RIVER 50.0
END DESCRIPTION:
XS GIS Cut Line= 3
      2668223.68     10063813.92      2666303.37     10058868.97
      2660323.12     10053719.69
#Sta/Elev= 30
 -3023.2 1973.31 -1781.7 1913.86 -636.37 1898.81 -446.55 1877.94 -136.86 1872.63
  272.74 1875.17362.6499 1865.14872.1399 1894.76 2470.56 1870.04 3869.17 1868.41
 3979.07 1855.01 4768.29 1851.94 5008.05 1838.31    5058 1852.33 5137.92 1862.63
 6516.57 1869.29  6996.1 1912.68 7675.44 1894.58 8085.04 1899.96  8379.8 1920.14
  8453.9    1936  8535.6 1953.41  8786.3 1964.55  8850.7 1966.89  8910.2 1968.82
  9166.3 1973.82  9464.5 1979.65  9579.7  1981.9  9830.6  1986.8 10173.2  1993.5
#Mann= 15 ,-1 , 0
 -3023.2      .1       0   335.5     .05       0   524.6      .1       0
    1114     .05       0  1532.9      .1       0    3934     .07       0
  5082.8      .1       0  8453.9     .16       0  8786.3      .1       0
  8850.7     .16       0  8910.2      .1       0  9166.3     .16       0
  9464.5      .1       0  9579.7     .16       0  9830.6      .1       0
Bank Sta=4768.29,5058
XS Rating Curve= 0 ,0
Exp/Cntr=0.3,0.1

Type RM Length L Ch R = 1 ,595910  ,1515,1515,1515
BEGIN DESCRIPTION:
PEDERNALES RIVER 51.0
END DESCRIPTION:
XS GIS Cut Line= 3
      2670401.72     10062433.62       2667030.6     10059033.89
      2665853.25     10050765.75
#Sta/Elev= 30
 -2047.6 1977.11 -1387.7 1962.12     5.3 1914.19  638.71 1859.05818.6201 1868.19
 1638.22 1865.87 1998.05 1885.87 2257.93 1889.24 4576.17 1860.78 4835.96 1856.48
    4912 1847.24  4942.3 1833.43  4993.5 1825.01  5073.6 1834.95  5497.8 1848.19
  5780.7 1861.41  5881.7 1902.34  5980.2 1964.07  6051.1 1976.38    6476 1986.73
  6976.8 1982.19  7679.6 1999.26  8103.9 1995.81  8747.3  1983.7  9552.9 1985.18
  9689.6 1985.79 10050.7 1985.67 10064.8 1985.86 10152.1 1986.17 11091.7 2012.18
#Mann= 13 ,-1 , 0
 -2047.6      .1       0  1847.5     .05       0  1992.6      .1       0
  2331.8     .05       0  2488.1      .1       0    4912     .07       0
  5497.8      .1       0  8103.9      .1       0  9552.9     .16       0
  9689.6      .1       0 10050.7     .16       0 10064.8      .1       0
 10152.1     .16       0
Bank Sta=4912,5497.8
XS Rating Curve= 0 ,0
Exp/Cntr=0.3,0.1

Type RM Length L Ch R = 1 ,594395  ,2204,2204,2204
BEGIN DESCRIPTION:
PEDERNALES RIVER 52.0
END DESCRIPTION:
XS GIS Cut Line= 4
      2670822.65       10062074.      2668297.24     10057642.67
       2667356.8     10051329.06      2666769.43     10050358.56
#Sta/Elev= 30
 -1445.5 1985.22    47.1 1933.91    87.2 1932.76  1375.7 1886.84    1489 1885.23
  3009.2 1842.62  3359.9 1838.61  3749.2 1867.29  4654.8 1846.43  4998.3 1822.48
  5210.8 1843.04  5442.7 1868.56    5566 1903.21  5655.7 1933.78  5788.4 1949.42
  6579.6 1930.67  6787.8 1949.57    7061 1963.69  7611.3 1948.55  7711.8 1938.98
  8228.5 1936.81  8395.6 1920.32  8793.6  1956.9  8998.2 1958.32  9307.2 1959.17
  9709.5 1949.97 10195.5 1978.73 10855.2 2001.97 10940.5    2004 11172.6 2006.51
#Mann= 20 ,-1 , 0
 -1445.5      .1       0    47.1     .16       0    87.2      .1       0
  1375.7     .05       0    1489      .1       0  4654.8     .07       0
  5210.8      .1       0  5442.7     .16       0    5566      .1       0
  6579.6     .16       0  6787.8      .1       0  7611.3     .16       0
  7711.8     .16       0  8793.6      .1       0  8998.2     .16       0
  9307.2      .1       0  9709.5     .16       0 10195.5     .16       0
 10855.2      .1       0 10940.5     .16       0
#XS Ineff= 2 , 0
         3759.09 1869.15
Permanent Ineff=
       F       F
Bank Sta=4654.8,5210.8
XS Rating Curve= 0 ,0
Exp/Cntr=0.3,0.1

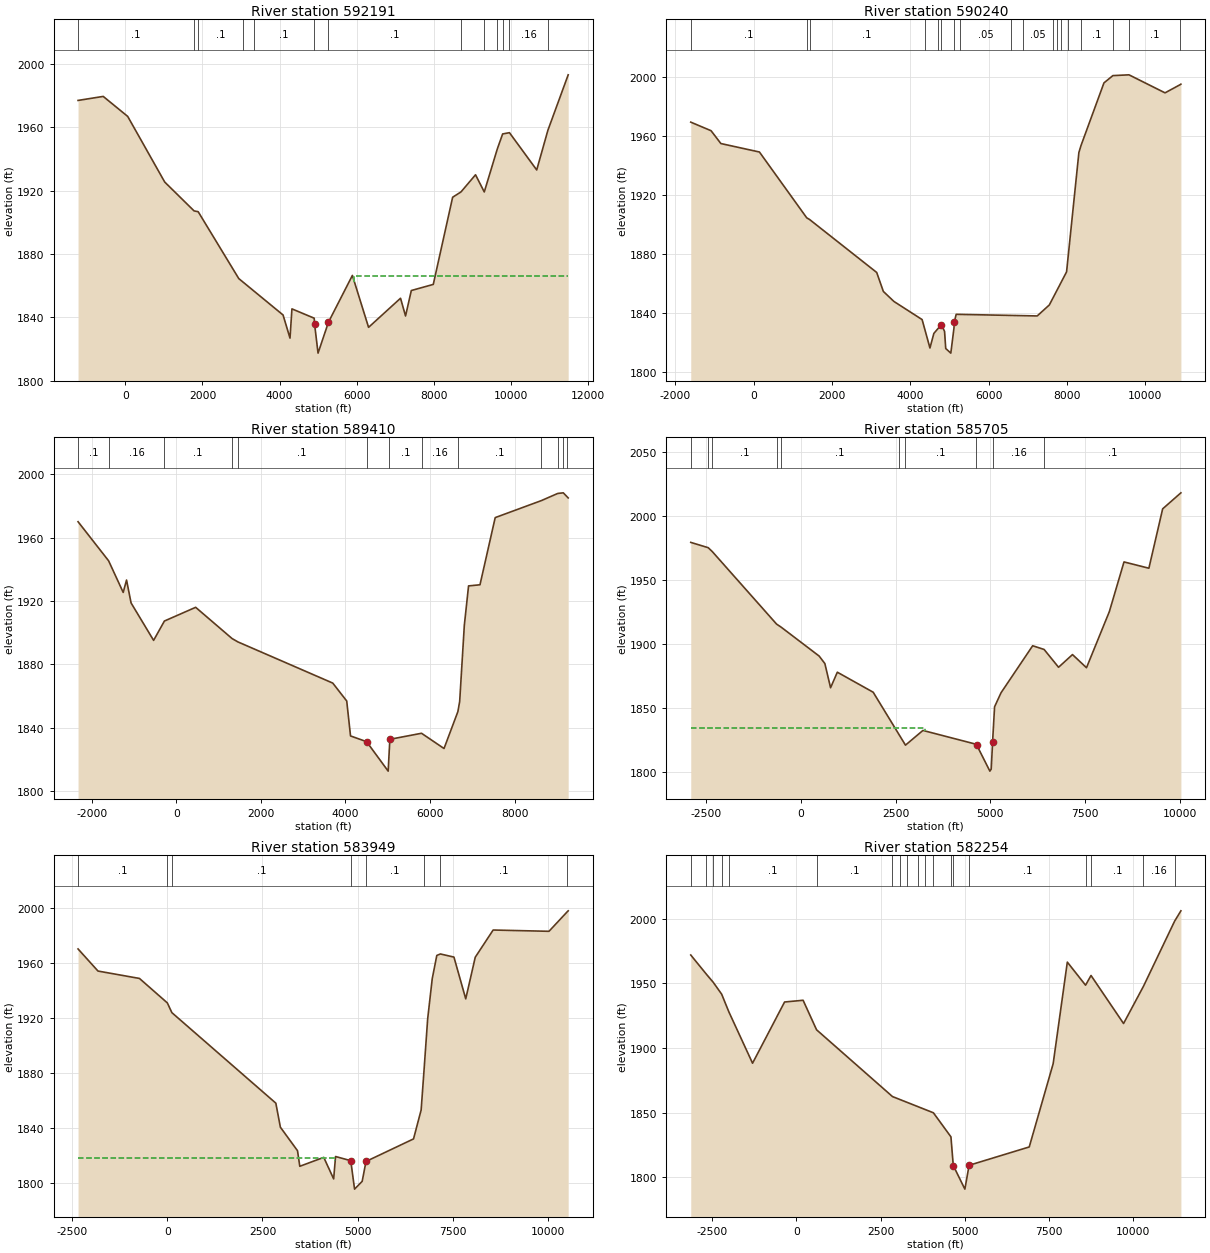
Type RM Length L Ch R = 1 ,592191  ,1951,1951,1951
BEGIN DESCRIPTION:
PEDERNALES RIVER 53.0
END DESCRIPTION:
XS GIS Cut Line= 4
      2671077.46     10062545.83      2670162.12     10058498.27
       2670230.1     10052795.68      2671381.16     10050179.03
#Sta/Elev= 30
 -1226.8 1976.95  -573.8 1979.48    61.4 1966.85  1020.7 1925.44  1782.5 1907.21
  1888.9  1906.7 2941.73 1864.48 4090.32  1841.5  4270.1  1826.9 4320.04 1845.37
  4897.7 1839.48  4907.7 1835.71  4997.4 1817.43  5267.7 1836.98 5888.12 1866.49
 6307.61 1833.71  7136.6 1852.08 7266.44 1840.88 7416.26 1856.95 7985.56 1860.81
  8487.9 1915.83  8705.5 1919.22  9081.4 1930.01  9308.4 1919.18  9646.5 1946.33
  9784.7 1955.79  9961.2 1956.59 10668.2 1933.06 10957.7 1958.07 11484.6 1993.11
#Mann= 13 ,-1 , 0
 -1226.8      .1       0  1782.5     .05       0  1888.9      .1       0
    3039     .05       0  3334.1      .1       0  4897.7     .07       0
  5267.7      .1       0  8705.5     .16       0  9308.4      .1       0
  9646.5     .16       0  9784.7      .1       0  9961.2     .16       0
 10957.7      .1       0
#XS Ineff= 2 , 0
                         5938.64         1866.33
Permanent Ineff=
       F       F
Bank Sta=4907.7,5267.7
XS Rating Curve= 0 ,0
Exp/Cntr=0.3,0.1

Type RM Length L Ch R = 1 ,590240  ,830,830,830
BEGIN DESCRIPTION:
PEDERNALES RIVER 54.0
END DESCRIPTION:
XS GIS Cut Line= 3
      2671268.77     10062517.68      2672087.75     10057535.94
      2671981.45     10050069.01
#Sta/Elev= 30
 -1609.4 1969.36 -1090.5 1963.55  -840.5 1954.87   144.2 1949.14  1351.3 1904.62
  1425.8 1903.43 3138.72 1867.61 3308.68 1854.76 3578.59 1847.98 4298.37 1835.71
  4498.3 1816.49 4598.27 1826.35  4791.6 1832.32  4871.6 1827.69  4901.6 1816.12
  5031.3    1813  5111.6 1829.91  5121.6 1834.13 5168.09 1839.27 7237.45 1838.17
 7547.36 1845.62 7987.23    1868  8301.9 1948.83  8357.9 1953.67    8942 1995.93
    9170 2000.86  9580.5 2001.39 10502.1 1989.19 10895.6 1994.85 10906.9 1995.09
#Mann= 18 ,-1 , 0
 -1609.4      .1       0  1351.3     .05       0  1425.8      .1       0
  4360.6     .16       0    4699      .1       0  4791.6     .07       0
  5111.6      .1       0  5276.1     .05       0  6569.9      .1       0
  6865.9     .05       0  7647.8     .16       0  7746.2      .1       0
  7844.6     .16       0  8014.4     .16       0  8357.9      .1       0
    9170     .16       0  9580.5      .1       0 10895.6     .16       0
Bank Sta=4791.6,5121.6
XS Rating Curve= 0 ,0
Exp/Cntr=0.3,0.1

Type RM Length L Ch R = 1 ,589410  ,3705,3705,3705
BEGIN DESCRIPTION:
PEDERNALES RIVER 55.0
END DESCRIPTION:
XS GIS Cut Line= 3
       2671596.1     10063094.58      2672847.61     10058604.08
      2672956.24     10051678.37
#Sta/Elev= 30
 -2320.7 1969.99 -1598.1 1945.33   -1253 1925.38 -1174.3 1933.19 -1066.5 1918.72
  -534.3 1895.13  -278.9 1907.33   460.1 1915.98  1320.3 1896.29  1457.9 1894.17
  3701.5 1868.18  4031.5 1856.88  4121.5 1834.84  4501.6 1831.22  5011.4 1812.64
  5031.6 1822.97  5051.6 1832.71  5800.1 1836.52  6331.8 1826.91  6659.2 1850.15
  6701.8 1856.55  6811.8 1904.59  6911.9 1929.49  7182.2  1930.2  7541.9 1972.58
  8632.8  1983.3  9020.5 1987.82  9151.4 1988.21  9249.7 1985.49  9267.5    1985
#Mann= 13 ,-1 , 0
 -2320.7      .1       0 -1598.1     .16       0  -278.9      .1       0
  1320.3     .05       0  1457.9      .1       0  4501.6     .07       0
  5031.6      .1       0  5800.1     .16       0  6659.2      .1       0
  8632.8     .16       0  9020.5      .1       0  9151.4     .16       0
  9249.7      .1       0
Bank Sta=4501.6,5051.6
XS Rating Curve= 0 ,0
Exp/Cntr=0.3,0.1

Type RM Length L Ch R = 1 ,585705  ,1756,1756,1756
BEGIN DESCRIPTION:
PEDERNALES RIVER 56.0
END DESCRIPTION:
XS GIS Cut Line= 2
      2675574.53     10061423.18      2673852.41     10048617.15
#Sta/Elev= 30
 -2898.7 1979.56 -2438.8 1975.42 -2333.9 1972.47  -636.4 1915.71    -518 1913.36
   485.8 1890.73   636.5 1884.86   787.2 1865.97   965.2 1878.11    1910 1862.48
 2761.89 1821.11 3221.64 1832.61  4627.9 1821.79    4638 1821.28  4986.6 1800.81
  5021.4  1802.4  5059.7 1823.89  5064.7 1827.18 5110.59 1851.09 5280.49 1862.03
  6114.6 1898.78    6416  1895.9  6797.2 1881.98  7164.5 1891.88  7533.7 1881.61
  8136.5 1925.49  8522.6 1964.29  9178.5 1959.37  9541.7 2005.77 10022.6 2018.29
#Mann= 10 ,-1 , 0
 -2898.7      .1       0 -2438.8     .16       0 -2333.9      .1       0
  -636.4     .05       0    -518      .1       0  2595.4     .05       0
  2760.8      .1       0  4627.9     .07       0  5064.7     .16       0
    6416      .1       0
#XS Ineff= 2 , 0
         3263.64 1834.42
Permanent Ineff=
       F       F
Bank Sta=4638,5059.7
XS Rating Curve= 0 ,0
Exp/Cntr=0.3,0.1

Type RM Length L Ch R = 1 ,583949  ,1695,1695,1695
BEGIN DESCRIPTION:
PEDERNALES RIVER 57.0
END DESCRIPTION:
XS GIS Cut Line= 3
      2676095.93     10061377.34      2676201.59     10050336.36
      2675073.18     10048890.83
#Sta/Elev= 30
 -2344.5 1970.44 -1820.9 1954.36  -730.8 1948.98       1  1931.2   120.6 1924.11
 2850.96  1858.3 2970.87  1840.8 3420.52 1823.72 3480.47  1812.4 4109.98 1818.88
 4369.78 1803.22 4419.74 1819.51  4819.4 1816.46  4919.2 1795.79  5119.4 1801.47
  5219.5 1815.91 6468.15 1832.31 6667.99 1853.35  6737.9 1879.86  6839.5 1919.59
  6959.5  1948.8  7079.5 1965.71  7173.7 1966.78  7529.6 1964.51  7839.6 1934.15
  8089.6 1964.42  8559.6 1984.19 10026.3 1983.26 10503.3 1997.39 10530.8 1998.15
#Mann= 8 ,-1 , 0
 -2344.5      .1       0       1     .05       0   120.6      .1       0
  4819.4     .07       0  5219.5      .1       0  6737.9     .16       0
  7173.7      .1       0 10503.3     .16       0
#XS Ineff= 2 , 0
         4409.09 1818.52
Permanent Ineff=
       F       F
Bank Sta=4819.4,5219.5
XS Rating Curve= 0 ,0
Exp/Cntr=0.3,0.1

Type RM Length L Ch R = 1 ,582254  ,1430,1430,1430
BEGIN DESCRIPTION:
PEDERNALES RIVER 58.0
END DESCRIPTION:
XS GIS Cut Line= 3
       2677985.6     10062337.44        2677626.     10051004.44
      2676995.14     10047854.39
#Sta/Elev= 30
 -3134.1 1972.02 -2677.1 1957.36 -2464.7  1950.8 -2216.4 1941.67 -2003.5 1928.03
 -1299.5 1888.23    -349 1935.63   201.3 1936.97   600.3 1914.12    2854 1862.42
  3070.3 1860.18  3281.1    1858    3611 1854.59  3825.7 1852.37  4069.3 1849.85
  4590.1 1831.21  4653.5 1810.81  4663.5 1808.81  5003.4 1790.74    5130 1809.27
    5135 1809.24  6914.7  1823.4    7625 1887.88  8045.2 1966.51  8586.6 1948.63
  8748.6 1956.16  9714.7 1918.97 10306.4 1947.83 11231.3 1998.26 11417.2 2006.22
#Mann= 19 ,-1 , 0
 -3134.1      .1       0 -2677.1     .16       0 -2464.7      .1       0
 -2216.4     .16       0 -2003.5      .1       0   600.3      .1       0
    2854      .1       0  3070.3     .05       0  3281.1     .05       0
    3611      .1       0  3825.7     .05       0  4069.3      .1       0
  4590.1     .16       0  4653.5     .07       0    5130      .1       0
  8586.6     .16       0  8748.6      .1       0 10306.4     .16       0
 11231.3      .1       0
Bank Sta=4663.5,5135
XS Rating Curve= 0 ,0
Exp/Cntr=0.3,0.1

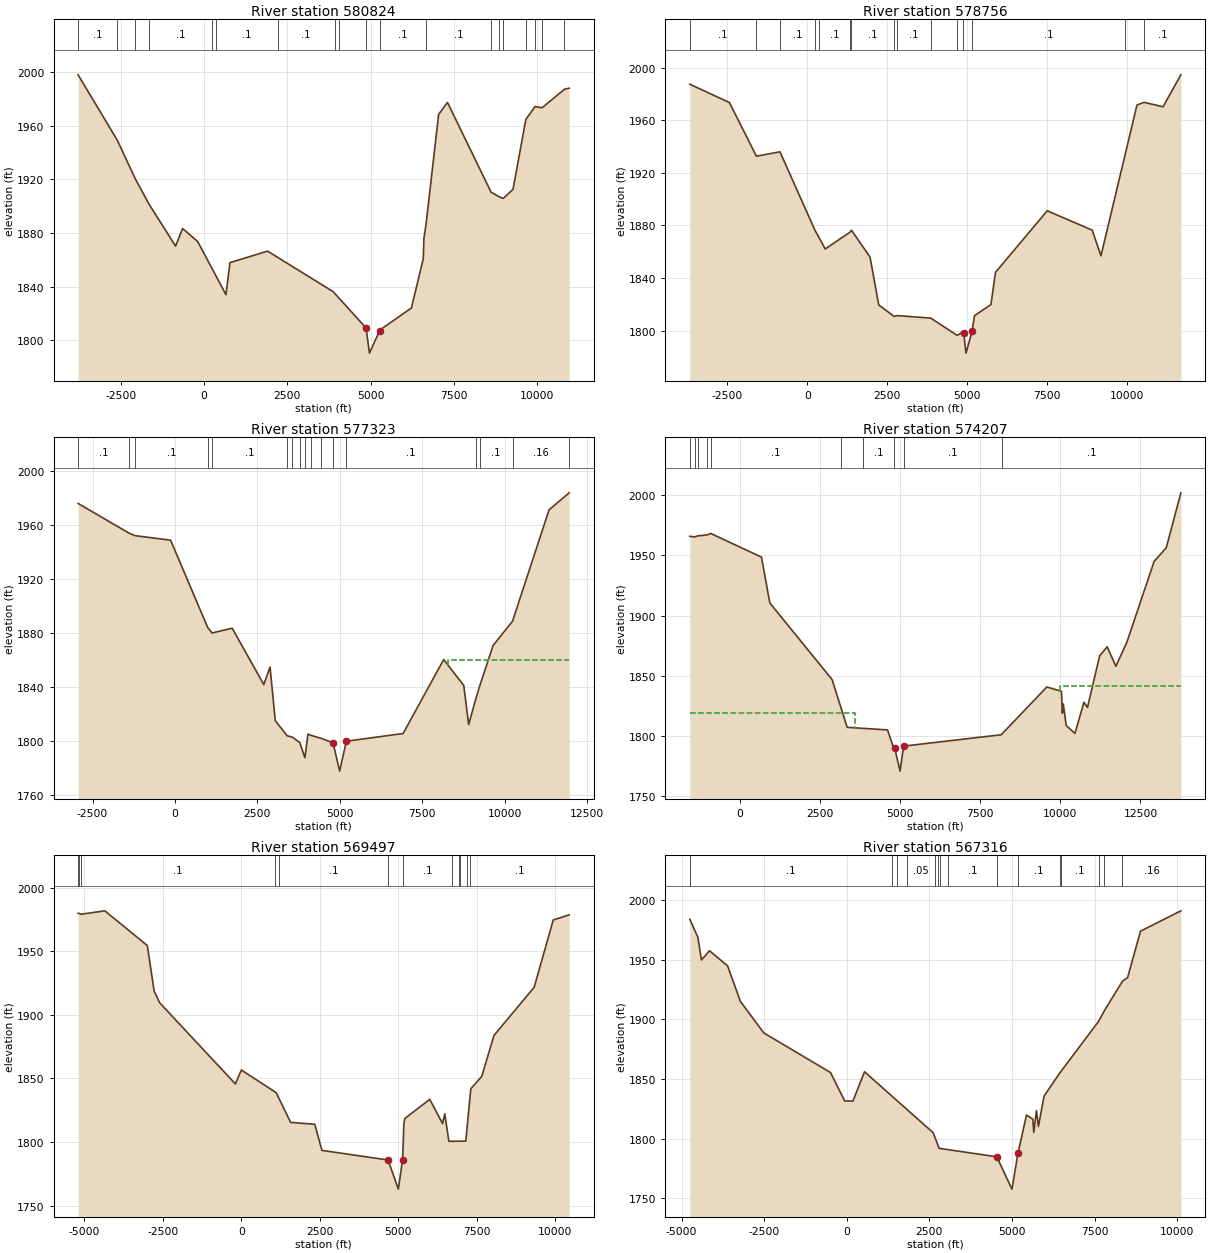
Type RM Length L Ch R = 1 ,580824  ,2068,2068,2068
BEGIN DESCRIPTION:
PEDERNALES RIVER 59.0
END DESCRIPTION:
XS GIS Cut Line= 2
      2680781.58     10062275.23      2677689.53     10047862.68
#Sta/Elev= 30
 -3778.5 1997.97 -2600.6 1949.13 -2055.5 1920.06   -1641 1901.13  -851.9 1870.15
  -641.7 1883.29  -189.3  1873.6660.1602 1833.92780.0801 1857.85 1909.35  1866.4
 3878.09 1836.16  4865.3  1809.1  4967.3  1790.3  5269.8  1806.9  5274.9 1807.47
  6226.6 1823.97  6583.5 1860.89    6602 1875.94  6662.3 1885.68  7043.8 1968.46
  7309.7 1977.39  8618.6 1910.37  8870.2 1906.83  8984.1  1905.8  9276.6 1912.47
  9661.9 1964.64  9938.8 1974.33 10148.2 1973.37 10820.6  1987.2   10962 1988.01
#Mann= 19 ,-1 , 0
 -3778.5      .1       0 -2600.6     .05       0 -2055.5      .1       0
   -1641      .1       0   241.9     .05       0   365.4      .1       0
  2208.4      .1       0  3920.1     .16       0  4064.4      .1       0
  4865.3     .07       0  5274.9      .1       0  6662.3      .1       0
  8618.6      .1       0  8870.2     .16       0  8984.1      .1       0
  9661.9      .1       0  9938.8     .16       0 10148.2     .16       0
 10820.6      .1       0
Bank Sta=4865.3,5269.8
XS Rating Curve= 0 ,0
Exp/Cntr=0.3,0.1

Type RM Length L Ch R = 1 ,578756  ,1433,1433,1433
BEGIN DESCRIPTION:
PEDERNALES RIVER 60.0
END DESCRIPTION:
XS GIS Cut Line= 3
      2681165.98     10062071.56      2680952.05      10056721.5
      2679950.88     10046778.61
#Sta/Elev= 30
 -3674.5 1987.31 -2435.7 1973.36 -1591.7 1932.54  -856.2 1935.88   241.9    1876
   359.4 1870.92   556.7 1862.02  1329.1 1874.72  1378.8 1876.27    1959 1855.83
  2230.4 1819.49  2711.8 1810.69  2806.8 1811.37  3857.6 1809.42  4684.7 1796.27
  4853.6 1798.95  4883.7 1798.47  4959.1 1782.81    5145 1799.31  5225.4 1811.37
    5738 1819.73  5878.7 1844.21  7496.9 1891.05  8903.9 1876.29  9175.3 1856.73
  9925.2 1933.13   10301 1971.45 10523.9 1973.52 11115.1 1970.12   11673 1994.43
#Mann= 15 ,-1 , 0
 -3674.5      .1       0 -1591.7     .16       0  -856.2      .1       0
   241.9     .05       0   359.4      .1       0  1329.1     .16       0
  1378.8      .1       0  2711.8     .16       0  2806.8      .1       0
  3857.6     .16       0  4684.7      .1       0  4853.6     .07       0
    5145      .1       0  9925.2     .16       0 10523.9      .1       0
Bank Sta=4883.7,5145
XS Rating Curve= 0 ,0
Exp/Cntr=0.3,0.1

Type RM Length L Ch R = 1 ,577323  ,3116,3116,3116
BEGIN DESCRIPTION:
PEDERNALES RIVER 61.0
END DESCRIPTION:
XS GIS Cut Line= 3
       2681470.6     10062005.67       2681431.5     10056553.61
      2682931.75     10047230.75
#Sta/Elev= 30
   -2937 1975.66-1399.19 1953.75-1219.44 1951.82 -130.99 1948.41997.4099 1883.58
 1127.22 1879.71 1736.36 1883.24 2695.11 1841.49 2884.96  1854.5 3044.84 1814.74
 3404.56 1803.57 3564.43 1802.56 3784.26 1798.58 3944.14 1787.35 4034.07 1804.76
 4133.99 1803.84 4443.75 1801.59  4796.5 1798.33  4996.5 1777.39  5199.4 1799.55
 6921.82 1805.24 8150.86 1860.02 8760.39 1840.87 8910.27 1811.88  9130.1 1831.34
 9240.01 1840.12  9649.7 1870.4310239.24 1888.4111348.37  1970.9 11957.9  1983.5
#Mann= 17 ,-1 , 0
   -2937      .1       0-1399.19     .05       0-1219.44      .1       0
997.4099     .05       0 1127.22      .1       0 3404.56     .16       0
 3564.43      .1       0 3784.26     .16       0 3944.14      .1       0
 4133.99     .05       0 4443.75      .1       0  4796.5     .07       0
  5199.4      .1       0  9130.1     .16       0 9240.01      .1       0
10239.24     .16       0 11957.9      .1       0
#XS Ineff= 2 , 0
         4036.36 1804.13 8272.73         1859.82
Permanent Ineff=
       F       F
Bank Sta=4796.5,5199.4
XS Rating Curve= 0 ,0
Exp/Cntr=0.3,0.1

Type RM Length L Ch R = 1 ,574207  ,4710,4710,4710
BEGIN DESCRIPTION:
PEDERNALES RIVER 62.0
END DESCRIPTION:
XS GIS Cut Line= 4
      2684314.31     10062308.73      2683989.41     10054622.24
      2683121.55     10050965.85        2683532.      10047117.5
#Sta/Elev= 30
 -1560.1 1965.71 -1403.6 1965.23 -1314.7 1966.03 -1015.2 1966.84    -909 1968.11
   676.9 1948.45   937.1 1910.44  2878.9 1846.91 3350.79 1807.27 4609.72 1805.11
  4810.6 1789.28  4830.6 1790.47  5000.5 1770.93  5110.9 1791.66 8157.29 1801.11
  9579.9 1840.75 10034.2 1837.18 10064.3 1819.01 10093.7  1826.6   10185 1808.78
 10456.5 1802.19 10738.1 1828.11 10847.9 1823.73 11227.6 1866.59 11462.2 1874.07
 11733.7 1857.94 12079.3 1878.07   12926 1944.81 13305.7  1956.2 13761.4 2001.77
#Mann= 10 ,-1 , 0
 -1560.1      .1       0 -1403.6     .16       0 -1314.7      .1       0
 -1015.2     .16       0    -909      .1       0  3143.3     .05       0
  3830.2      .1       0  4810.6     .07       0  5110.9      .1       0
  8187.3      .1       0
#XS Ineff= 2 , 0
         3581.82 1819.09   10000         1841.61
Permanent Ineff=
       F       F
Bank Sta=4830.6,5110.9
XS Rating Curve= 0 ,0
Exp/Cntr=0.3,0.1

Type RM Length L Ch R = 1 ,569497  ,2181,2181,2181
BEGIN DESCRIPTION:
PEDERNALES RIVER 63.0
END DESCRIPTION:
XS GIS Cut Line= 4
      2687021.13     10062445.25      2686242.39     10055690.86
      2683971.53     10051757.29      2684257.18     10047463.61
#Sta/Elev= 30
 -5200.5 1979.81 -5164.5 1979.76 -5105.7  1979.1 -4348.1 1981.78 -2994.5 1954.44
 -2777.2 1918.56 -2604.3 1909.53-189.629 1845.64.3398438 1856.57 1110.22 1838.76
 1570.16 1815.39 2338.84 1813.87 2568.44 1793.34  4674.6 1785.81  5001.8 1762.88
  5136.2 1785.92  5151.3 1794.76  5178.6 1814.61  5209.5 1818.45 6002.39 1833.48
 6411.73 1814.42 6481.62 1822.16 6611.41  1800.5 7150.57 1800.62 7310.32 1841.82
 7659.77  1851.6  8048.4 1883.77  9329.8 1921.69  9936.7 1974.59 10443.8  1978.6
#Mann= 12 ,-1 , 0
 -5200.5      .1       0 -5164.5     .16       0 -5105.7      .1       0
  1077.2     .05       0  1187.1      .1       0  4674.6     .07       0
  5151.3      .1       0    6715     .05       0  6929.4     .16       0
  6970.2     .05       0  7195.4     .16       0  7293.7      .1       0
Bank Sta=4674.6,5136.2
XS Rating Curve= 0 ,0
Exp/Cntr=0.3,0.1

Type RM Length L Ch R = 1 ,567316  ,2079,2079,2079
BEGIN DESCRIPTION:
PEDERNALES RIVER 64.0
END DESCRIPTION:
XS GIS Cut Line= 3
      2687518.67     10062216.83      2686565.74     10054783.22
      2686471.48     10047411.86
#Sta/Elev= 30
 -4753.5  1983.8 -4508.4 1968.69 -4400.3 1949.68 -4155.6 1957.36 -3608.8 1944.72
 -3220.6 1914.93 -2513.9 1888.55-493.169 1855.33-63.4902  1831.5186.3301 1831.44
536.0698 1855.98 2614.55 1804.88  2794.4 1791.83  4540.6 1784.69  5000.4 1757.61
  5180.6 1787.57  5440.6 1819.71  5630.7 1816.24  5660.7 1805.19  5740.7 1823.36
  5800.7  1810.1  5970.7 1835.49  6455.2 1855.31  6483.4 1856.28  7622.8 1898.24
  7788.7 1906.77  8345.7 1931.88  8500.9 1934.89  8890.9 1973.76 10112.9 1990.84
#Mann= 15 ,-1 , 0
 -4753.5      .1       0  1375.7     .05       0  1526.9      .1       0
  1835.2     .05       0  2675.4     .16       0    2759      .1       0
  2835.7     .16       0  3058.8      .1       0  4540.6     .07       0
  5180.6      .1       0  6455.2     .16       0  6483.4      .1       0
  7622.8     .05       0  7788.7      .1       0  8345.7     .16       0
Bank Sta=4540.6,5180.6
XS Rating Curve= 0 ,0
Exp/Cntr=0.3,0.1

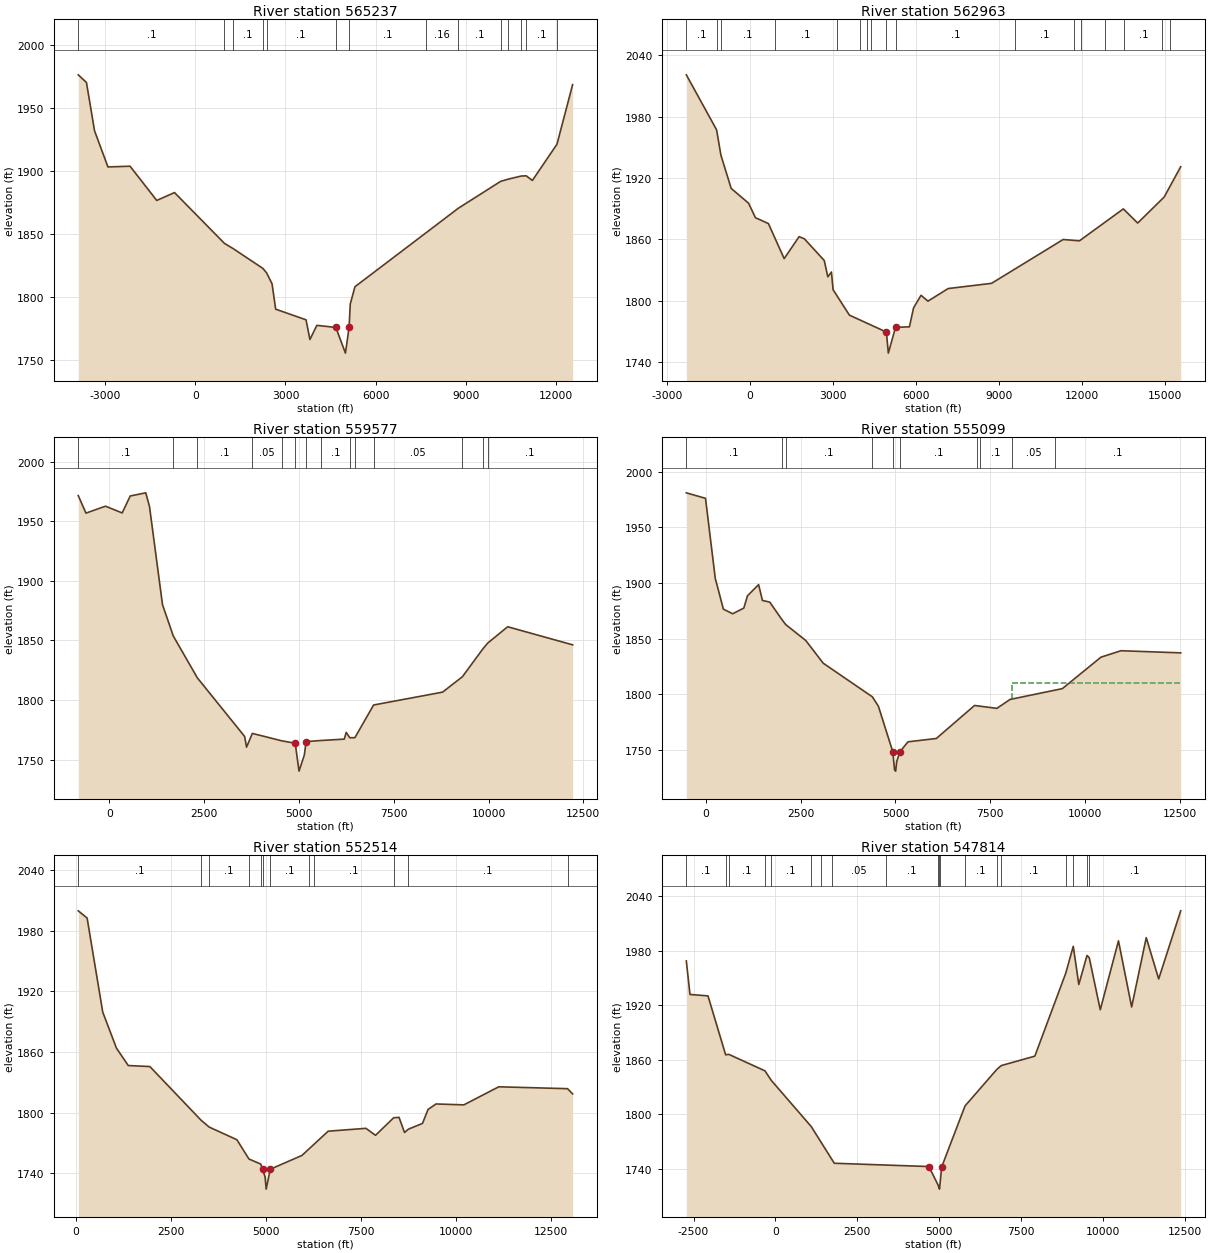
Type RM Length L Ch R = 1 ,565237  ,2274,2274,2274
BEGIN DESCRIPTION:
PEDERNALES RIVER 65.0
END DESCRIPTION:
XS GIS Cut Line= 4
      2691461.75     10061326.37      2688549.92      10056551.8
      2688239.06     10047693.44       2686480.7     10046787.85
#Sta/Elev= 30
 -3887.5 1976.39   -3615 1970.31 -3345.6 1931.85 -2900.5 1903.16 -2165.4 1903.74
 -1278.5 1876.52    -688 1882.79   973.5 1842.37    1253 1838.37  2248.7 1822.51
  2374.6 1818.92 2554.86 1810.29 2674.78  1790.1 3684.09 1781.64    3814 1765.98
 4043.84 1777.23  4674.8 1775.57  4994.8 1755.15  5115.1 1775.56  5155.1 1794.19
  5310.4 1807.93    7665 1850.65  8745.2  1870.3 10153.8  1891.7 10401.5 1893.42
 10839.5 1895.94 11005.7 1896.09 11208.7  1892.4 12026.9 1921.25 12546.6 1968.64
#Mann= 14 ,-1 , 0
 -3887.5      .1       0   973.5     .05       0    1253      .1       0
  2248.7     .05       0  2374.6      .1       0  4674.8     .07       0
  5115.1      .1       0    7665     .16       0  8745.2      .1       0
 10153.8     .16       0 10401.5      .1       0 10839.5     .05       0
 11005.7      .1       0 12026.9     .16       0
Bank Sta=4674.8,5115.1
XS Rating Curve= 0 ,0
Exp/Cntr=0.3,0.1

Type RM Length L Ch R = 1 ,562963  ,3386,3386,3386
BEGIN DESCRIPTION:
PEDERNALES RIVER 66.0
END DESCRIPTION:
XS GIS Cut Line= 4
       2692933.6     10060927.29       2690249.6     10056702.32
       2690430.7     10048084.23      2686518.05     10046422.82
#Sta/Elev= 30
 -2296.5 2020.94 -1202.6 1967.11 -1044.8 1942.19  -674.5 1909.74  -47.05 1895.33
  202.72  1881.1  672.28 1875.32 1241.76 1841.01 1781.26 1862.53 1971.08 1860.45
 2690.42 1839.24  2820.4 1823.22  2950.4 1827.93  3010.4 1810.59  3600.4 1785.72
    4938 1769.14  5007.8 1748.53    5268 1773.75  5770.4 1774.28  5920.4 1792.83
  6190.4 1805.13  6440.4 1799.41  7170.4 1811.74  8740.4 1816.85 11330.4 1859.75
11919.14 1858.4613505.72  1889.7 14024.6 1875.8614982.54 1901.33 15579.7 1930.97
#Mann= 17 ,-1 , 0
 -2296.5      .1       0 -1202.6     .16       0 -1044.8      .1       0
   914.5      .1       0  3137.5      .1       0  3983.2      .1       0
  4248.6     .05       0  4398.2      .1       0    4938     .07       0
    5268      .1       0  9597.2      .1       0 11723.1     .16       0
 11986.2     .16       0 12830.6      .1       0 13544.9      .1       0
 14910.7     .16       0 15208.5      .1       0
Bank Sta=4938,5268
XS Rating Curve= 0 ,0
Exp/Cntr=0.3,0.1

Type RM Length L Ch R = 1 ,559577  ,4478,4478,4478
BEGIN DESCRIPTION:
PEDERNALES RIVER 67.0
END DESCRIPTION:
XS GIS Cut Line= 3
      2693729.44     10059588.46       2693121.8     10051775.97
      2690692.16       10047177.
#Sta/Elev= 30
  -821.1 1971.54  -617.9 1956.83  -104.2 1962.65   337.1 1957.01   549.2 1971.21
     959 1973.87  1057.8 1962.39  1400.3 1880.06  1684.7 1853.75  2319.6  1818.6
  3566.8 1769.42    3617 1760.42  3770.2 1771.97  4545.5 1765.76  4900.9 1763.73
  5000.9 1740.32  5141.6 1753.89  5187.4  1765.1  5588.7 1766.04  6194.8 1767.18
  6244.9 1772.83  6339.3 1768.34  6474.9 1768.41  6967.4 1795.81  8787.9 1806.62
  9310.7 1819.57  9844.8 1842.71  9973.7 1847.68 10503.7 1861.48 12216.3 1846.31
#Mann= 14 ,-1 , 0
  -821.1      .1       0  1684.7     .16       0  2319.6      .1       0
  3770.2     .05       0  4545.5      .1       0  4900.9     .07       0
  5187.4     .16       0  5588.7      .1       0  6339.3     .05       0
  6474.9      .1       0  6967.4     .05       0  9310.7      .1       0
  9844.8     .16       0  9973.7      .1       0
Bank Sta=4900.9,5187.4
XS Rating Curve= 0 ,0
Exp/Cntr=0.3,0.1

Type RM Length L Ch R = 1 ,555099  ,2585,2585,2585
BEGIN DESCRIPTION:
PEDERNALES RIVER 69.0
END DESCRIPTION:
XS GIS Cut Line= 4
      2698416.95     10057635.36      2697288.47     10054119.72
      2694250.28     10051124.93      2691082.66     10047132.87
#Sta/Elev= 30
  -523.1 1981.08   -16.5 1976.13   240.4 1904.41   455.3 1876.63   700.5 1872.49
   994.8 1877.57  1091.2  1888.6  1385.4 1898.64    1487 1884.43  1679.7 1882.95
  1995.9 1867.49  2101.2  1862.8    2632 1848.45 3091.44  1828.1 4390.16 1797.89
 4550.01 1789.36  4927.1 1748.74  4976.6 1732.13  5004.7 1731.18  5033.2 1739.97
  5118.1 1748.53 5329.29 1757.49  6078.6 1760.49 7087.67 1790.12 7677.22 1787.55
 8027.05 1795.56 9406.37 1805.2610425.86 1833.51 10953.6 1839.29 12531.4 1837.38
#Mann= 10 ,-1 , 0
  -523.1      .1       0  1995.9     .05       0  2101.2      .1       0
    4379     .16       0  4927.1     .07       0  5118.1      .1       0
  7153.4     .05       0  7243.1      .1       0  8063.7     .05       0
  9223.6      .1       0
#XS Ineff= 2 , 0
                         8068.18         1810.01
Permanent Ineff=
       F       F
Bank Sta=4927.1,5118.1
XS Rating Curve= 0 ,0
Exp/Cntr=0.3,0.1

Type RM Length L Ch R = 1 ,552514  ,4700,4700,4700
BEGIN DESCRIPTION:
PEDERNALES RIVER 70.0
END DESCRIPTION:
XS GIS Cut Line= 4
      2698764.17     10056116.29      2698547.15     10052730.83
      2696507.22     10049779.44      2691385.72     10046611.05
#Sta/Elev= 30
    65.9 1999.47   298.9 1992.35   709.8 1899.33  1070.5 1863.69  1381.2 1846.49
    1950 1845.47  3296.6 1792.41  3510.1 1785.63  4238.7 1773.11  4555.5 1754.07
  4865.2 1749.06  4913.5 1743.88  4978.9 1736.48  5008.3 1724.28  5116.1 1743.95
 5949.81  1757.6 6639.38 1781.57  7631.7  1784.4  7884.6  1777.5  8360.6 1794.82
  8502.7 1795.27  8646.9 1780.26  8748.6 1783.55  9119.6 1789.24  9266.2 1803.08
  9476.6 1808.49 10208.1  1807.6 11124.9 1825.46 12934.6 1823.61 13068.4 1818.47
#Mann= 12 ,-1 , 0
    65.9      .1       0  3296.6     .05       0  3510.1      .1       0
  4555.5     .05       0  4865.2     .16       0  4913.5     .07       0
  5116.1      .1       0  6121.8     .05       0  6257.8      .1       0
  8360.6     .05       0  8748.6      .1       0 12934.6     .16       0
Bank Sta=4913.5,5116.1
XS Rating Curve= 0 ,0
Exp/Cntr=0.3,0.1

Type RM Length L Ch R = 1 ,547814  ,3313,3313,3313
BEGIN DESCRIPTION:
PEDERNALES RIVER 71.0
END DESCRIPTION:
XS GIS Cut Line= 3
      2699194.61     10056294.47      2699734.67     10051786.79
      2698366.75      10041318.6
#Sta/Elev= 30
 -2719.8 1968.78 -2608.3 1931.94 -2058.1 1930.34 -1519.3 1865.57 -1422.2 1866.05
  -317.6  1847.9  -130.1 1837.65  1094.7 1786.65  1798.9 1746.29  4688.7 1742.67
  4962.4  1722.8  5007.1 1718.34  5009.8 1717.84  5013.1 1718.34  5080.7 1742.51
  5791.4 1809.32  6759.7 1849.41  6897.9 1853.72    7923 1864.08  8866.3  1955.2
    9097 1984.92  9265.9 1942.89    9516  1974.8  9584.6 1972.35  9921.5  1915.1
 10477.2  1990.9 10879.5 1918.17 11325.3 1994.41 11704.8 1948.99 12377.3  2023.9
#Mann= 19 ,-1 , 0
 -2719.8      .1       0 -1519.3     .05       0 -1422.2      .1       0
  -317.6     .05       0  -130.1      .1       0  1094.7     .16       0
    1402      .1       0  1725.7     .05       0  3365.7      .1       0
  4962.4     .16       0  5007.1     .07       0  5013.1     .16       0
  5791.4      .1       0  6759.7     .05       0  6897.9      .1       0
  8866.3     .16       0    9097      .1       0    9516     .16       0
  9584.6      .1       0
Bank Sta=4688.7,5080.7
XS Rating Curve= 0 ,0
Exp/Cntr=0.3,0.1