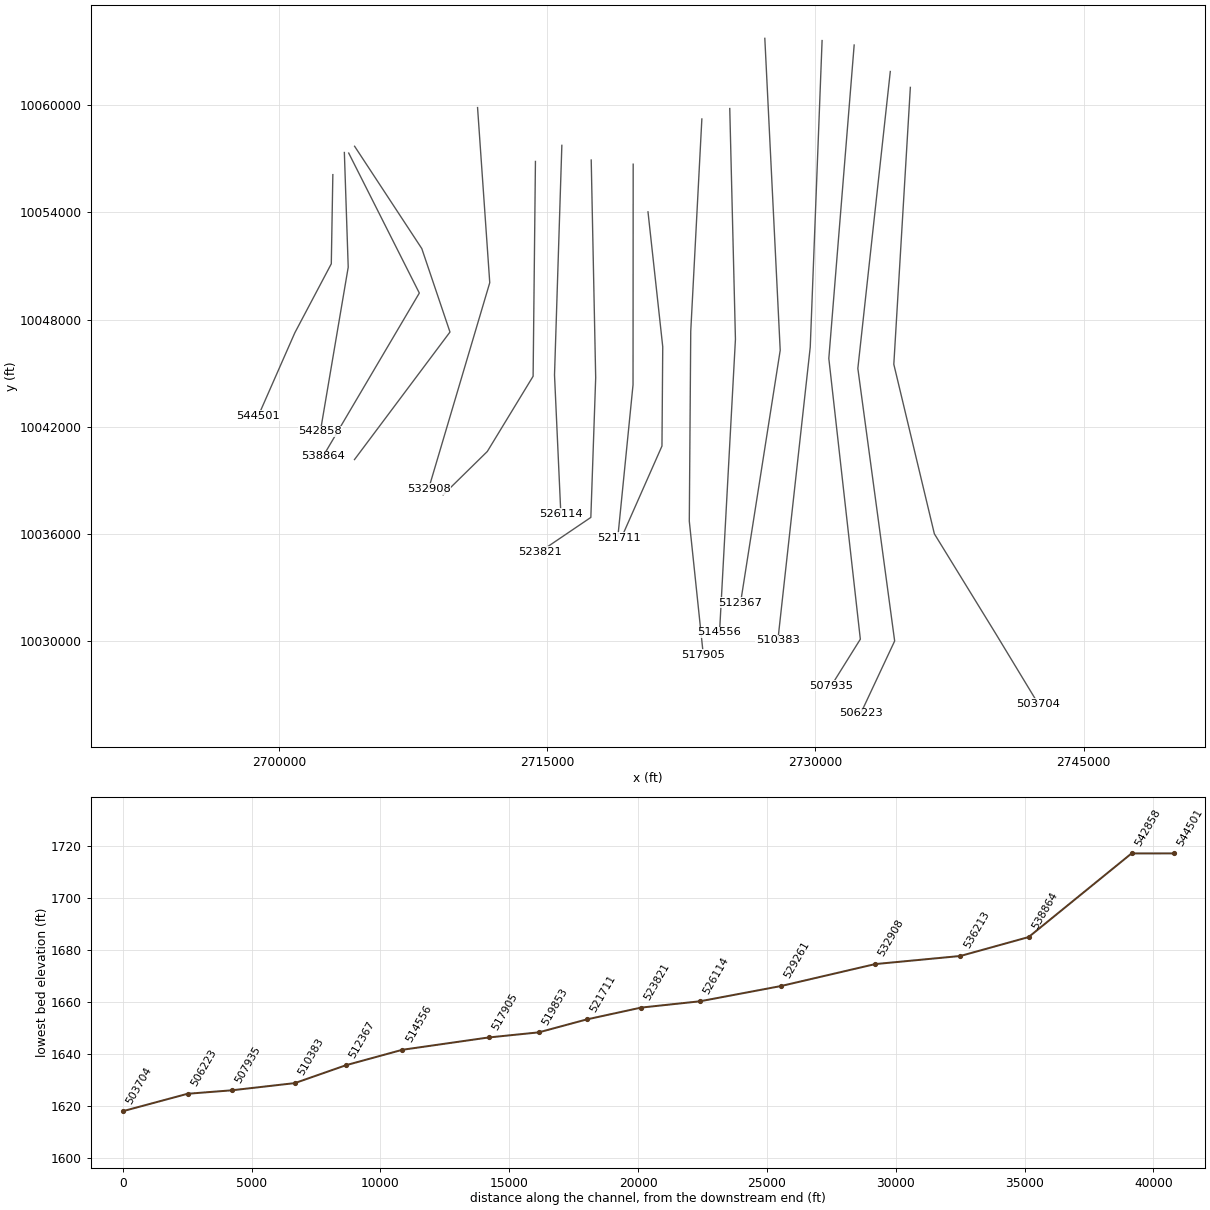
HEC-RAS study PEDERNALES RIVER.prj: PEDERNALES RIVER Base Level Engineering

--- PEDERNALES RIVER.g01 (geometry) --- (continued)

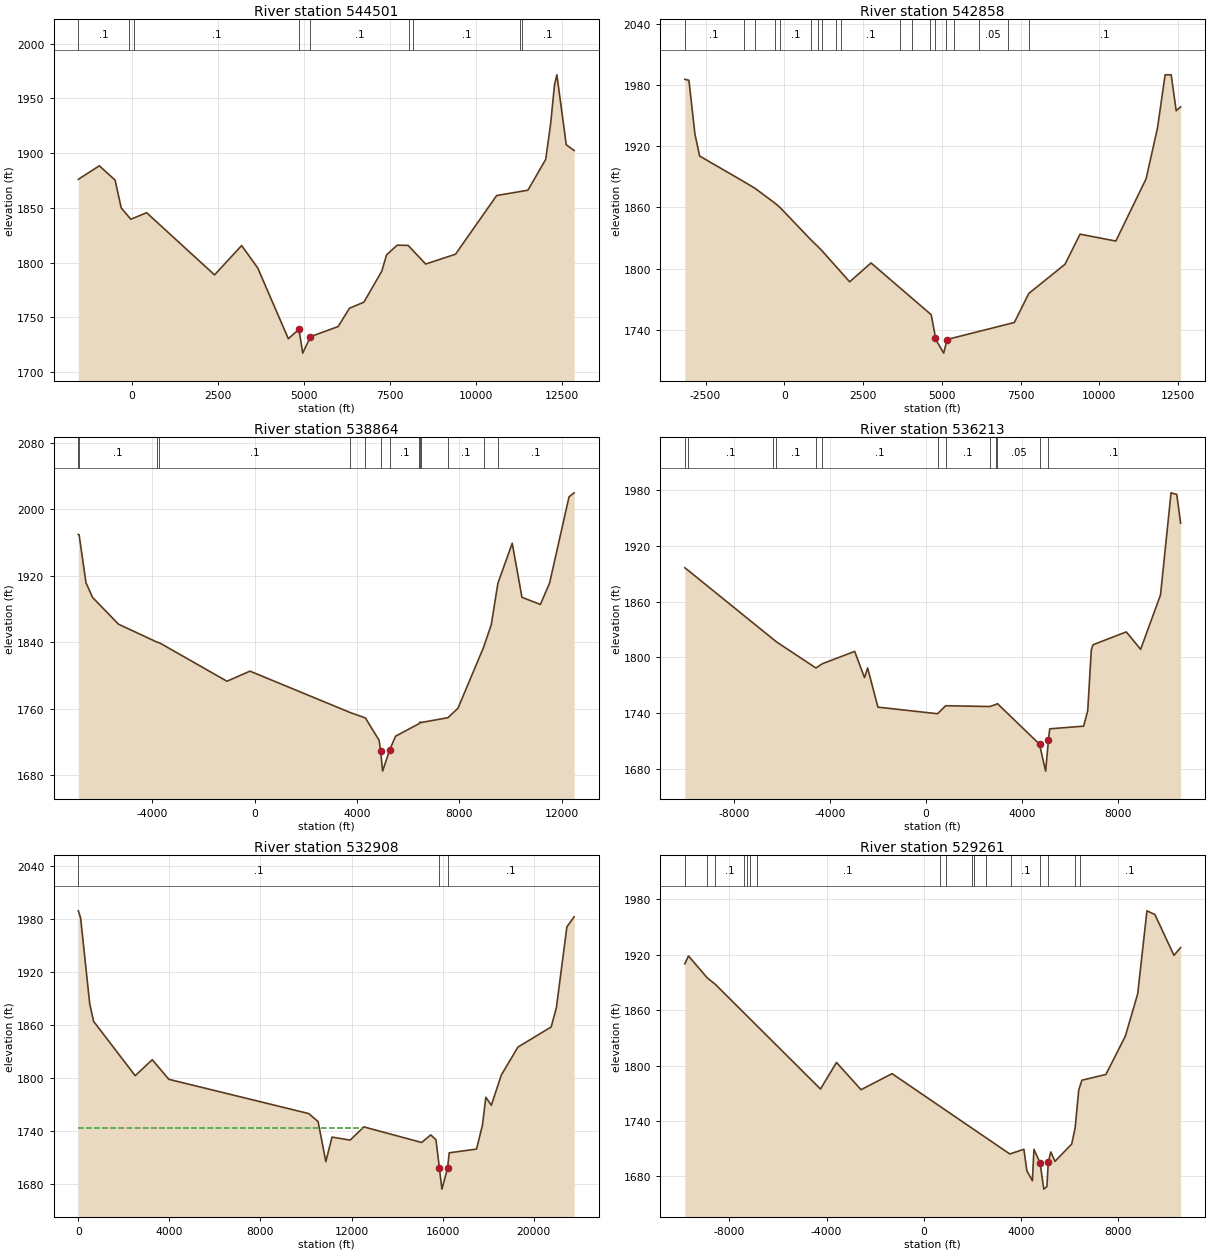
Type RM Length L Ch R = 1 ,544501  ,1643,1643,1643
BEGIN DESCRIPTION:
PEDERNALES RIVER 72.0
END DESCRIPTION:
XS GIS Cut Line= 4
      2703017.64     10056116.25      2702930.83     10051124.93
       2700890.9     10047262.08      2698851.15     10042618.39
#Sta/Elev= 30
 -1566.1 1876.08 -955.97 1888.42  -496.7 1875.41 -316.98 1849.91  -37.43 1839.61
  421.85 1845.56 2398.71 1788.74 3187.45 1815.56 3656.98 1795.01 4546.67 1730.42
  4856.5 1739.03  4966.3 1717.26  5191.5 1732.31 5996.15 1741.54 6326.04 1758.25
 6745.88 1763.83 7265.68 1792.08 7405.62 1806.98  7715.5 1815.91 8035.11 1815.69
 8544.35 1798.65 9413.04 1807.6410611.24 1861.2711519.88 1866.11 12037.9 1894.24
 12183.3 1927.19 12293.3 1962.18 12363.4 1971.54 12636.7 1907.64 12866.3 1902.38
#Mann= 9 ,-1 , 0
 -1566.1      .1       0   -84.2     .05       0    58.3      .1       0
  4856.5     .07       0  5191.5      .1       0  8060.4     .05       0
  8181.1      .1       0 11297.3     .16       0 11346.1      .1       0
Bank Sta=4856.5,5191.5
XS Rating Curve= 0 ,0
Exp/Cntr=0.3,0.1

Type RM Length L Ch R = 1 ,542858  ,3994,3994,3994
BEGIN DESCRIPTION:
PEDERNALES RIVER 77.0
END DESCRIPTION:
XS GIS Cut Line= 3
      2703661.31     10057354.89      2703877.05     10050933.53
      2702320.29     10041748.21
#Sta/Elev= 30
 -3158.7 1985.38 -3027.5 1984.48 -2837.4 1931.88 -2687.3 1910.29 -1289.3  1885.3
  -930.9 1878.69  -283.8 1863.85  -125.6  1859.6   845.2 1828.21  1058.4 1821.87
  1194.6  1817.6 2074.93 1787.11  2754.4 1805.56 4663.54 1754.89  4777.3 1736.37
  4783.1 1731.93  5061.1 1717.25  5145.2 1727.73  5162.8 1730.58 7302.62 1747.25
 7762.46 1775.69 8912.06 1804.27  9389.5 1833.74   10526 1827.02 11486.5    1888
 11848.6 1937.73 12090.2 1989.81 12282.9 1989.81   12442 1954.65 12582.6 1958.41
#Mann= 19 ,-1 , 0
 -3158.7      .1       0 -1289.3     .05       0  -930.9      .1       0
  -283.8     .05       0  -125.6      .1       0   845.2     .05       0
  1058.4      .1       0  1194.6     .05       0  1626.2     .05       0
  1794.3      .1       0  3687.7     .05       0  4067.6      .1       0
  4626.5      .1       0  4777.3     .07       0  5145.2      .1       0
  5396.5      .1       0  6174.6     .05       0  7090.7      .1       0
  7776.1      .1       0
Bank Sta=4783.1,5162.8
XS Rating Curve= 0 ,0
Exp/Cntr=0.3,0.1

Type RM Length L Ch R = 1 ,538864  ,2651,2651,2651
BEGIN DESCRIPTION:
PEDERNALES RIVER 78.0
END DESCRIPTION:
XS GIS Cut Line= 3
      2703904.78     10057323.04      2707852.92     10049487.98
       2702475.7     10040360.54
#Sta/Elev= 30
   -6885 1969.85-6855.02 1969.49-6585.22 1911.57-6325.41 1893.93-5316.14 1861.84
-3797.24 1840.06 -3717.3 1839.49-1079.23 1793.22-179.879 1805.36 3727.56 1755.66
  4327.2 1749.06  4862.3 1722.26  4926.7 1708.71  5000.7 1685.07  5278.1 1710.76
 5506.51 1727.07 6425.97 1742.23 6465.95 1744.27 6495.93 1743.48 7555.31 1749.39
 7945.08 1760.78  8944.5 1834.07 9244.32 1861.19 9504.17 1911.1510063.84 1959.21
10443.62  1894.2 11163.2 1885.5611522.99 1911.3512282.54 2015.0912482.42 2019.89
#Mann= 14 ,-1 , 0
   -6885      .1       0-6855.02      .1       0-3797.24     .05       0
 -3717.3      .1       0 3727.56     .05       0  4327.2      .1       0
  4926.7     .07       0  5278.1      .1       0 6425.97     .05       0
 6465.95      .1       0 6495.93     .05       0 7555.31      .1       0
  8944.5     .16       0 9504.17      .1       0
Bank Sta=4926.7,5278.1
XS Rating Curve= 0 ,0
Exp/Cntr=0.3,0.1

Type RM Length L Ch R = 1 ,536213  ,3305,3305,3305
BEGIN DESCRIPTION:
PEDERNALES RIVER 79.0
END DESCRIPTION:
XS GIS Cut Line= 4
      2704233.99      10057703.2      2707991.98     10051975.31
      2709567.07      10047306.4      2704227.35     10040168.04
#Sta/Elev= 30
  -10065 1896.26-9925.19 1893.47-6380.03 1819.61-6240.22 1816.69-4592.48 1788.61
-4322.85 1793.21 -2974.5 1806.44-2564.72  1778.2-2434.79 1788.65-2005.02 1746.54
483.7305 1739.44823.5596 1748.07 2662.65  1747.2 2922.52 1749.42 2982.49 1750.32
  4738.7 1706.77  4994.8 1677.79    5087 1704.01  5109.6 1711.03  5165.9 1723.24
6580.689 1726.12 6750.59  1742.6  6900.5 1808.026970.461 1813.53 8359.65 1827.38
8959.289 1808.649788.811 1867.0410228.55  1976.810468.41 1975.0610628.32 1944.24
#Mann= 13 ,-1 , 0
  -10065      .1       0-9925.19      .1       0-6380.03     .05       0
-6240.22      .1       0-4592.48     .05       0-4322.85      .1       0
483.7305     .05       0823.5596      .1       0 2662.65     .05       0
 2922.52      .1       0 2982.49     .05       0  4738.7     .07       0
    5087      .1       0
Bank Sta=4738.7,5109.6
XS Rating Curve= 0 ,0
Exp/Cntr=0.3,0.1

Type RM Length L Ch R = 1 ,532908  ,3647,3647,3647
BEGIN DESCRIPTION:
PEDERNALES RIVER 88.0
END DESCRIPTION:
XS GIS Cut Line= 3
      2711109.42     10059868.93      2711791.08     10050067.58
      2708370.05     10038524.07
#Sta/Elev= 30
       01988.999   99.911981.087  499.551884.169  669.391864.222 2497.731802.799
 3247.04 1820.82 3976.381798.69310120.891760.00710530.761750.97110870.651705.701
11140.571733.43311940.311730.06212540.121744.97615079.311727.35815479.181735.918
15709.111730.39315859.061698.11615969.021674.67616218.941698.48516288.921715.701
17488.541719.89617748.461746.83917898.411778.50518138.331769.32918578.19 1803.57
19307.961835.10920767.491857.79720997.421879.68121457.271970.83221777.171982.327
#Mann= 3 ,-1 , 0
       0      .1       015859.06     .07       016218.94      .1       0
#XS Ineff= 2 , 0
        12457.39 1743.66
Permanent Ineff=
       F       F
Bank Sta=15859.06,16218.94
XS Rating Curve= 0 ,0
Exp/Cntr=0.3,0.1

Type RM Length L Ch R = 1 ,529261  ,3147,3147,3147
BEGIN DESCRIPTION:
PEDERNALES RIVER 89.0
END DESCRIPTION:
XS GIS Cut Line= 4
      2714345.76     10056854.05      2714215.55     10044831.53
      2711654.79     10040621.46      2709182.17     10038192.22
#Sta/Elev= 30
 -9839.6  1910.1 -9689.3 1918.72 -8920.2 1895.11 -8579.8 1887.86-4252.14 1774.59
-3592.52  1803.4 -2583.1 1773.89-1303.83 1791.24 3543.54 1704.31    4124 1709.38
  4246.8  1686.1  4473.4 1675.35  4537.4 1709.38  4791.2 1694.56    4944 1666.25
  5070.2 1669.01  5128.3 1695.46 5232.72 1706.49 5402.63 1696.31  6092.3 1715.04
 6232.23 1732.12 6382.16 1773.45 6512.09 1784.157501.619 1790.39 8301.16 1831.84
8810.859 1877.749190.631 1967.51  9518.4 1963.56 10303.3 1919.26 10577.6  1927.8
#Mann= 17 ,-1 , 0
 -9839.6      .1       0 -8920.2     .05       0 -8579.8      .1       0
 -7401.7     .05       0 -7266.4      .1       0 -7140.4     .05       0
 -6876.6      .1       0     650     .05       0   896.7      .1       0
  1979.3     .05       0  2077.7      .1       0  2578.2     .05       0
    3573      .1       0  4791.2     .07       0  5128.3      .1       0
    6223     .16       0  6425.8      .1       0
Bank Sta=4791.2,5128.3
XS Rating Curve= 0 ,0
Exp/Cntr=0.3,0.1

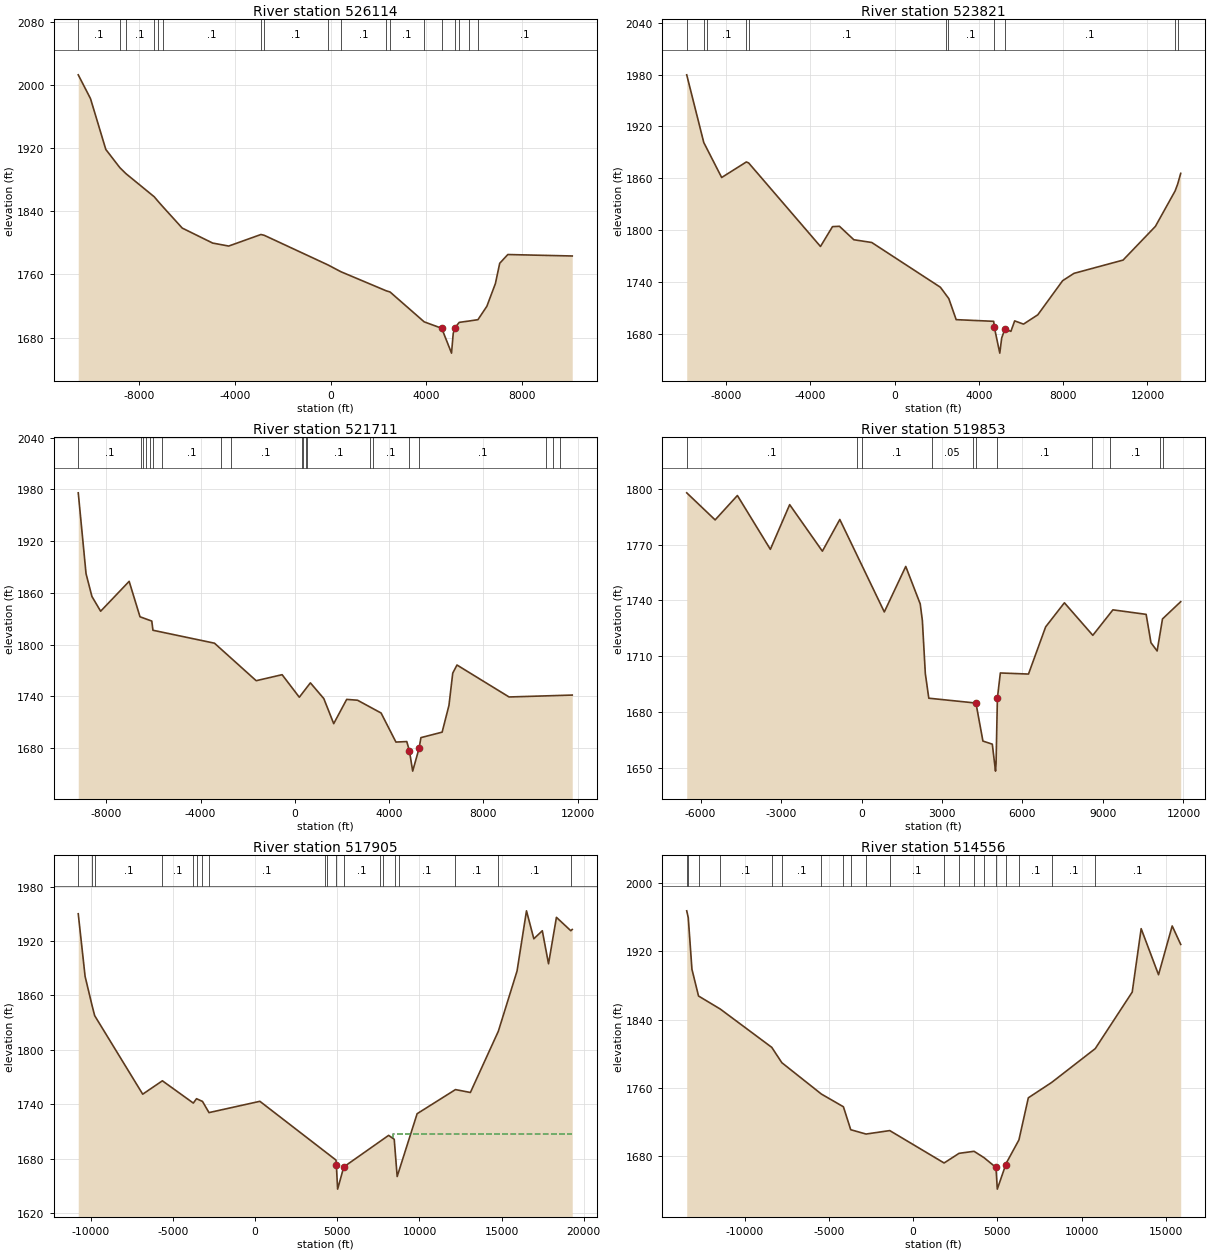
Type RM Length L Ch R = 1 ,526114  ,2293,2293,2293
BEGIN DESCRIPTION:
PEDERNALES RIVER 100.0
END DESCRIPTION:
XS GIS Cut Line= 3
      2715822.46     10057755.21      2715412.22     10044902.31
      2715765.67      10037137.8
#Sta/Elev= 30
-10540.7 2012.96  -10029 1982.84 -9388.6 1918.41 -8804.1  1895.4 -8548.1 1887.75
 -7363.7 1858.37 -7224.1 1853.34 -7001.9  1845.7   -6197 1818.79 -4925.7  1799.8
   -4256 1796.03 -2909.7 1810.66 -2770.3 1809.62  -105.6 1772.06   425.3 1763.56
  2318.3 1739.37  2480.7 1737.86  3907.5    1700  4640.1 1691.85  5049.9 1660.37
  5120.2 1685.16  5179.9 1691.95  5370.6 1699.34  5776.6 1701.03  6152.8 1702.76
  6525.5 1719.72    6882 1748.46  7062.2 1774.19  7400.8 1785.28 10091.3 1783.44
#Mann= 18 ,-1 , 0
-10540.7      .1       0 -8804.1     .05       0 -8548.1      .1       0
 -7363.7     .05       0 -7224.1      .1       0 -7001.9      .1       0
 -2909.7     .05       0 -2770.3      .1       0  -105.6     .05       0
   425.3      .1       0  2318.3     .05       0  2480.7      .1       0
  3907.5     .05       0  4640.1     .07       0  5179.9     .05       0
  5370.6      .1       0  5776.6     .05       0  6152.8      .1       0
Bank Sta=4640.1,5179.9
XS Rating Curve= 0 ,0
Exp/Cntr=0.3,0.1

Type RM Length L Ch R = 1 ,523821  ,2110,2110,2110
BEGIN DESCRIPTION:
PEDERNALES RIVER 101.0
END DESCRIPTION:
XS GIS Cut Line= 4
      2717464.34     10056932.82      2717714.57      10044747.6
      2717443.65     10036931.29      2714593.16     10034998.97
#Sta/Elev= 30
   -9875 1979.63 -9064.8 1901.35 -8905.1 1893.75 -8215.6 1860.95 -7044.7  1878.9
 -6934.5 1877.78 -3524.6 1781.22 -2954.5 1804.14 -2624.4 1804.56-1940.51    1789
-1090.67 1785.81 2168.69 1734.08 2568.36 1720.92 2917.95 1696.63  4698.1  1694.7
  4728.1 1687.93    4988 1657.93  5078.3 1675.44  5238.4 1686.16  5514.9 1683.08
 5694.69 1695.18  6114.2 1691.47  6793.4 1702.25 7972.02 1741.678511.391 1750.15
 10840.8 1765.48 12375.1 1804.42 13310.8 1845.37 13433.5 1853.35 13577.5 1865.73
#Mann= 11 ,-1 , 0
   -9875      .1       0 -9064.8     .05       0 -8905.1      .1       0
 -7044.7     .05       0 -6934.5      .1       0  2422.3     .05       0
  2528.5      .1       0  4728.1     .07       0  5238.4      .1       0
 13310.8     .05       0 13433.5      .1       0
Bank Sta=4728.1,5238.4
XS Rating Curve= 0 ,0
Exp/Cntr=0.3,0.1

Type RM Length L Ch R = 1 ,521711  ,1858,1858,1858
BEGIN DESCRIPTION:
PEDERNALES RIVER 102.0
END DESCRIPTION:
XS GIS Cut Line= 4
      2719810.99      10056700.5      2719802.73     10044355.93
      2718965.82     10035959.88      2719017.26     10035798.72
#Sta/Elev= 30
   -9185  1975.9-8855.15 1882.23-8605.26 1855.82-8235.42 1838.68-7025.95 1873.32
-6566.16 1832.25-6066.38 1827.28 -6016.4 1816.63-3407.56 1801.65-1638.34 1758.17
-538.809 1765.14190.8701 1739.02660.6699 1755.69 1230.43 1737.43 1650.25 1708.41
 2200.02 1736.52 2659.82 1735.55 3659.46 1720.73 4289.28 1687.06 4749.14 1687.65
  4859.5  1677.1  4999.9 1653.38  5272.6 1680.01 5348.97  1692.2  6248.7 1698.55
 6538.62 1729.65 6698.57 1766.96 6878.52 1776.359088.061 1739.31 11766.8 1741.52
#Mann= 20 ,-1 , 0
 -9185.7      .1       0 -6537.1     .05       0 -6420.2      .1       0
 -6321.8     .16       0   -6134      .1       0   -6022     .16       0
 -5627.3      .1       0 -3145.1     .05       0 -2718.9      .1       0
     290     .16       0   344.9      .1       0   489.4     .16       0
   531.8      .1       0    3198     .05       0  3313.9      .1       0
  4859.5     .07       0  5272.6      .1       0 10670.8     .05       0
 10930.8      .1       0 11249.6     .05       0
Bank Sta=4859.5,5272.6
XS Rating Curve= 0 ,0
Exp/Cntr=0.3,0.1

Type RM Length L Ch R = 1 ,519853  ,1948,1948,1948
BEGIN DESCRIPTION:
PEDERNALES RIVER 103.0
END DESCRIPTION:
XS GIS Cut Line= 4
      2720639.17     10054032.91      2721463.82     10046480.83
      2721420.42     10040925.28      2719293.93     10036108.15
#Sta/Elev= 30
   -6519 1797.76-5459.42 1783.23-4629.75 1796.32-3400.24 1767.43-2680.52 1791.41
   -1461 1766.44-811.259 1783.46848.0801 1733.84 1647.54 1758.25 2187.12 1738.15
 2267.06 1729.23 2376.97 1700.81 2506.87 1687.55  4264.9 1684.94  4524.9 1664.54
  4874.9 1662.88  4994.6 1648.41  5014.9  1652.5  5064.9 1687.67 5174.79 1701.09
 6223.97  1700.5 6863.49 1725.81 7563.01 1738.75 8622.29 1721.29 9371.77 1734.96
10610.86 1732.5410790.72 1717.3311020.55 1712.8811220.39 1730.0911899.87 1739.34
#Mann= 11 ,-1 , 0
 -6519.3      .1       0  -154.7     .05       0     4.5      .1       0
  2616.5     .05       0  4148.2      .1       0  4264.9     .07       0
  5064.9      .1       0  8597.6     .05       0  9279.6      .1       0
 11131.4      .1       0   11241     .05       0
#XS Ineff= 2 , 0
                            7625         1735.36
Permanent Ineff=
       F       F
Bank Sta=4264.9,5064.9
XS Rating Curve= 0 ,0
Exp/Cntr=0.3,0.1

Type RM Length L Ch R = 1 ,517905  ,3349,3349,3349
BEGIN DESCRIPTION:
PEDERNALES RIVER 104.0
END DESCRIPTION:
XS GIS Cut Line= 4
      2723651.26     10059231.27      2723029.86     10047348.16
      2722948.97     10036721.45      2723733.32     10029230.26
#Sta/Elev= 30
-10762.3  1950.1-10344.2 1880.98 -9916.1 1848.59 -9762.5 1837.75 -6839.4 1751.15
 -5641.9  1765.9   -3760 1741.34 -3564.8 1746.16   -3202 1743.15 -2805.5 1730.83
   290.3 1743.28  4921.6 1678.48  4941.6 1673.42  5021.3 1646.44 5395.08 1670.93
 8124.35 1705.73 8464.25 1701.418644.211 1660.36  9858.1 1729.61 12190.9 1756.21
   13099 1753.02 14799.2 1820.52   15938 1886.95 16512.7 1953.35   16960 1922.53
 17475.4 1931.37 17853.5 1894.93 18334.9 1946.15 19209.6  1931.4 19296.2 1932.81
#Mann= 19 ,-1 , 0
-10762.3      .1       0 -9916.1     .05       0 -9762.5      .1       0
 -5641.9      .1       0   -3760     .05       0 -3564.8      .1       0
   -3202     .16       0 -2805.5      .1       0    4259     .16       0
  4376.6      .1       0  4921.6     .07       0 5395.08      .1       0
  7577.6     .05       0  7790.2      .1       0  8508.2     .16       0
  8736.2      .1       0 12190.9      .1       0 14799.2      .1       0
 19209.6      .1       0
#XS Ineff= 2 , 0
                         8366.48         1707.13
Permanent Ineff=
       F       F
Bank Sta=4941.6,5395.08
XS Rating Curve= 0 ,0
Exp/Cntr=0.3,0.1

Type RM Length L Ch R = 1 ,514556  ,2189,2189,2189
BEGIN DESCRIPTION:
PEDERNALES RIVER 105.0
END DESCRIPTION:
XS GIS Cut Line= 3
      2725211.18     10059814.25      2725528.82     10046905.01
      2724640.38     10030508.61
#Sta/Elev= 30
  -13443 1967.07  -13352 1959.15-13132.4  1898.7-12741.6 1867.47-11450.1 1852.22
 -8392.3 1807.44 -7794.7 1789.52 -5443.9 1752.82   -4139 1738.01 -3703.9 1711.15
 -2795.8  1706.1 -1386.6 1710.14  1840.3 1672.27    2729 1683.55  3617.7 1685.92
  4203.5 1678.61  4919.4 1667.06  4926.7 1665.73  4999.3  1641.7  5490.2 1669.74
  5500.3 1670.92    6284 1699.25  6842.2 1748.46  8227.2 1766.42 10815.7 1805.97
 13011.3 1872.08   13542 1946.21 14573.5 1892.36 15384.7 1949.41 15890.6  1927.8
#Mann= 20 ,-1 , 0
  -13443      .1       0  -13352      .1       0-12741.6      .1       0
-11450.1      .1       0 -8392.3      .1       0 -7794.7      .1       0
 -5443.9      .1       0   -4139      .1       0 -3703.9     .05       0
 -2795.8     .05       0 -1386.6      .1       0  1840.3     .05       0
    2729     .05       0  3617.7     .05       0  4203.5      .1       0
  4926.7     .07       0  5500.3      .1       0    6284      .1       0
  8227.2      .1       0 10815.7      .1       0
Bank Sta=4919.4,5490.2
XS Rating Curve= 0 ,0
Exp/Cntr=0.3,0.1

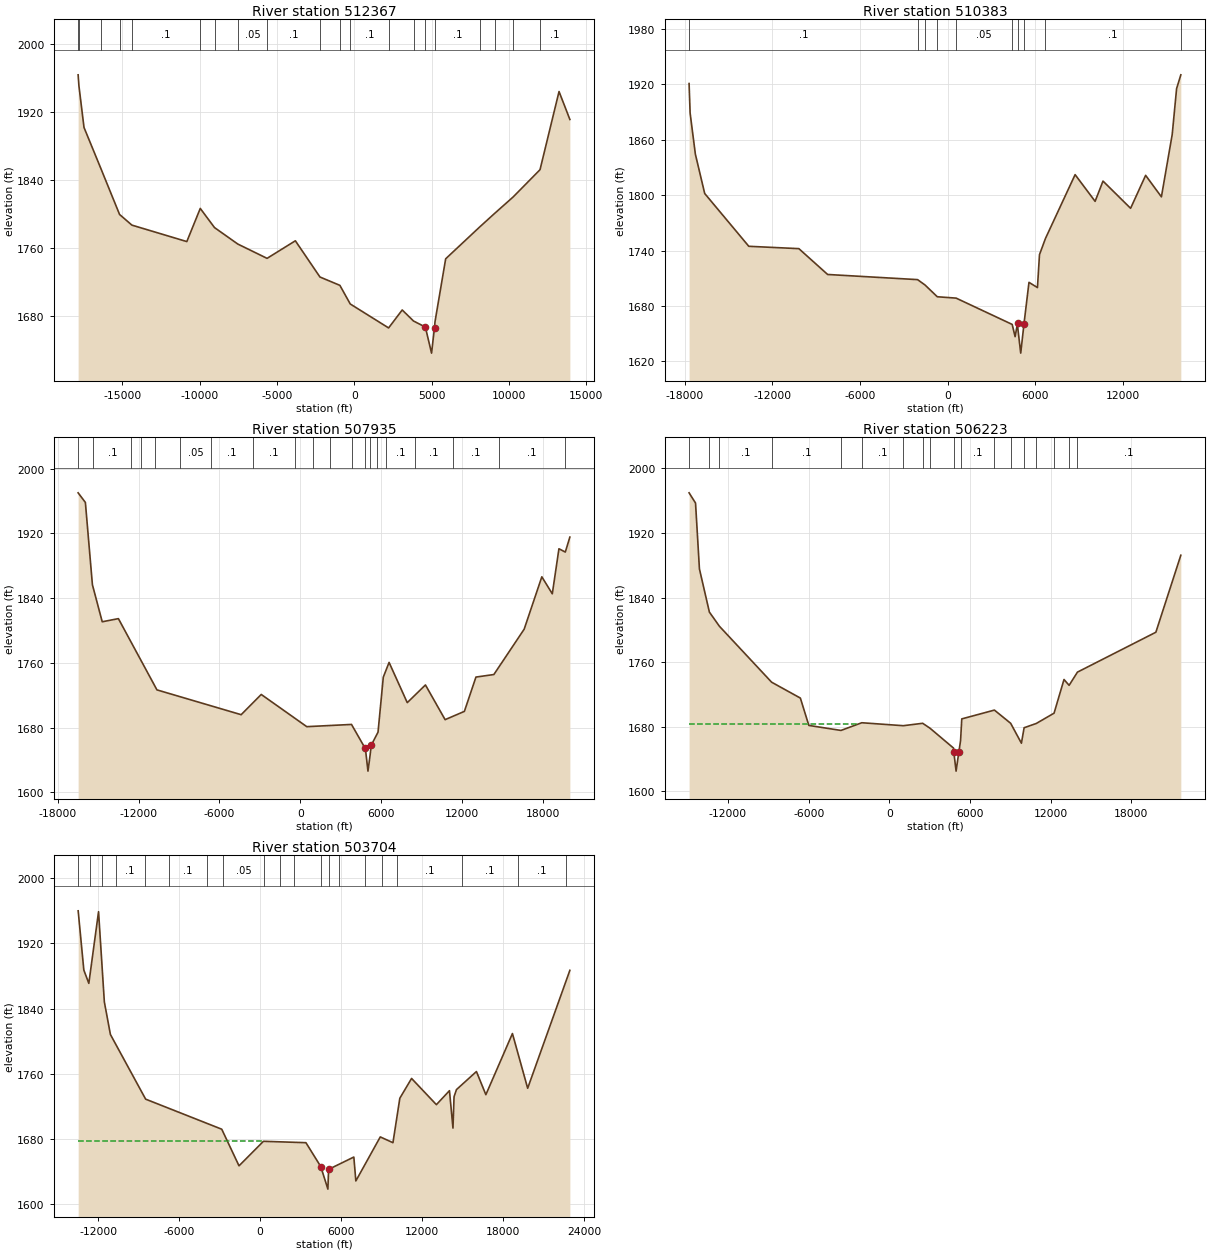
Type RM Length L Ch R = 1 ,512367  ,1984,1984,1984
BEGIN DESCRIPTION:
PEDERNALES RIVER 106.0
END DESCRIPTION:
XS GIS Cut Line= 3
      2727171.49     10063744.17      2728032.09     10046283.97
      2725814.36     10032150.41
#Sta/Elev= 30
  -17847  1963.7  -17797 1951.02-17467.1 1901.69-16357.7 1852.46-15168.3 1799.16
-14368.7 1786.58-10820.4 1767.21-9950.85 1806.27-9031.29 1783.72-7522.03 1764.26
-5632.95 1747.43-3803.85 1768.14-2214.62 1725.46-925.289 1715.62 -255.63 1693.68
2223.891 1665.453103.711 1686.62 3833.57 1673.62  4591.7 1666.56  4596.7 1666.79
  4999.7 1635.76  5192.3 1665.915223.301 1672.72 5913.17 1746.91 8112.74 1784.43
9092.539 1800.6410272.31 1819.7312011.97  1851.913241.73 1944.01 13941.6 1911.11
#Mann= 20 ,-1 , 0
  -17847     .16       0  -17797     .16       0-16357.7      .1       0
-15168.3      .1       0-14368.7      .1       0-9950.85      .1       0
-9031.29     .05       0-7522.03     .05       0-5632.95      .1       0
-2214.62      .1       0-925.289     .05       0 -255.63      .1       0
2223.891      .1       0 3833.57     .05       0  4596.7     .07       0
5223.301      .1       0 8112.74     .05       09092.539      .1       0
10272.31      .1       012011.97      .1       0
Bank Sta=4591.7,5192.3
XS Rating Curve= 0 ,0
Exp/Cntr=0.3,0.1

Type RM Length L Ch R = 1 ,510383  ,2448,2448,2448
BEGIN DESCRIPTION:
PEDERNALES RIVER 107.0
END DESCRIPTION:
XS GIS Cut Line= 3
      2730374.06     10063619.87      2729711.86      10046466.9
      2727901.25     10030059.35
#Sta/Elev= 30
  -17701 1921.04  -17631 1889.14-17271.1 1844.49-16631.2 1801.85  -13612 1744.65
-10182.9  1742.1-8213.36 1714.11 -2054.7 1708.53-1544.81 1702.71 -704.98 1689.97
584.7695 1688.49 4424.02 1659.99 4623.98  1646.7  4790.4 1661.37  4810.5 1655.65
  5008.9 1628.88    5233 1660.695573.789 1705.59 6153.68 1699.92 6293.65 1735.62
 6703.57 1753.16 8733.17  1822.310102.91 1793.36 10642.8 1815.3212532.43 1785.82
13562.23 1821.5314642.02 1798.2415381.92 1865.82 15681.9 1915.5215971.88 1930.47
#Mann= 10 ,-1 , 0
  -17701      .1       0 -2054.7      .1       0-1544.81     .05       0
 -704.98      .1       0584.7695     .05       0 4424.02      .1       0
  4810.5     .07       0    5233     .16       0 6703.57      .1       0
15971.88      .1       0
Bank Sta=4790.4,5233
XS Rating Curve= 0 ,0
Exp/Cntr=0.3,0.1

Type RM Length L Ch R = 1 ,507935  ,1712,1712,1712
BEGIN DESCRIPTION:
PEDERNALES RIVER 108.0
END DESCRIPTION:
XS GIS Cut Line= 4
      2732167.49     10063370.05      2730750.41     10045828.28
      2732512.53     10030114.74      2730882.99     10027503.19
#Sta/Elev= 30
-16489.5 1970.19-15951.4 1958.33-15429.7 1856.61-14701.1 1810.77-13501.1 1814.65
-10641.3 1726.56-4391.72 1695.89-2901.83  1720.9477.9707 1681.08  3796.4 1683.83
  4766.7 1655.56    4819 1655.15  5018.1 1626.11  5179.6 1646.26  5259.7  1658.1
 5765.24 1674.31 6155.01 1742.27 6584.76 1760.537933.971 1710.77 9283.18 1732.66
10742.32 1689.7512171.49 1699.9713030.98 1742.39 14360.2 1745.5416608.95 1801.61
 17919.8 1866.36   18696 1845.34 19189.1 1901.05 19660.9 1896.97 19999.7 1915.47
#Mann= 20 ,-1 , 0
-16489.5      .1       0-15364.6      .1       0-12541.9     .16       0
-11815.9      .1       0-10811.2      .1       0 -8895.2     .05       0
 -6638.9      .1       0 -3500.2      .1       0  -407.6      .1       0
   973.2     .05       0  2216.5     .05       0    3818      .1       0
  4766.7     .07       0  5179.6      .1       0  5659.1     .16       0
  6365.4      .1       0  8541.1      .1       0 11292.3      .1       0
 14747.8      .1       0 19660.9     .16       0
Bank Sta=4819,5259.7
XS Rating Curve= 0 ,0
Exp/Cntr=0.3,0.1

Type RM Length L Ch R = 1 ,506223  ,2519,2519,2519
BEGIN DESCRIPTION:
PEDERNALES RIVER 109.0
END DESCRIPTION:
XS GIS Cut Line= 4
      2734187.69     10061888.29      2732373.28     10045268.42
       2734431.6      10030014.2      2732535.63     10025963.32
#Sta/Elev= 30
  -14897 1969.82  -14417 1957.13  -14127 1875.41-13387.1 1821.98-12637.1 1804.32
-8757.48 1735.04-6617.62 1715.34-5987.69 1681.44-3597.92 1675.23-2048.07 1684.76
 1041.63  1681.1 2481.24 1684.09 3020.98 1678.054780.131 1653.31  4793.1 1649.02
  4966.6 1624.78  5176.5 1648.955299.881 1662.52 5389.84 1689.53 7818.67 1700.45
 9028.09 1684.079827.699 1659.3810027.61 1678.5710937.17 1683.8912256.53 1696.65
12996.18 1738.3813375.99 1731.1513995.69 1747.5119830.03 1796.9721687.12 1892.46
#Mann= 18 ,-1 , 0
  -14897     .16       0-13387.1     .16       0-12637.1      .1       0
-8757.48      .1       0-3597.92      .1       0-2048.07      .1       0
 1041.63      .1       0 2481.24     .05       0 3020.98      .1       0
4780.131     .07       05299.881      .1       0 7818.67     .05       0
 9028.09      .1       010027.61      .1       010937.17      .1       0
12256.53      .1       013375.99      .1       013995.69      .1       0
#XS Ineff= 2 , 0
        -2363.64  1683.1
Permanent Ineff=
       F       F
Bank Sta=4793.1,5176.5
XS Rating Curve= 0 ,0
Exp/Cntr=0.3,0.1

Type RM Length L Ch R = 1 ,503704  ,2528,2528,2528
BEGIN DESCRIPTION:
PEDERNALES RIVER 110.0
END DESCRIPTION:
XS GIS Cut Line= 5
      2735309.54     10060998.94      2734384.51     10045500.92
      2736651.39     10036013.58      2740122.38     10030360.37
      2742460.65     10026499.24
#Sta/Elev= 30
  -13477 1960.04-13057.1  1887.2-12687.2 1870.91-11967.4 1958.98-11537.5 1848.07
-11087.6 1808.06 -8478.4 1728.63-2839.99 1691.68-1560.37 1646.68249.0996 1676.84
3397.779 1675.124497.141 1645.75  5023.8 1618.06  5075.4 1642.326945.699 1657.49
7095.619 1628.138904.551 1682.21    9844 1675.1210353.71 1729.74 11223.2 1754.07
13061.62 1721.8614030.68 1739.0414290.42 1693.0514370.35 1731.5714550.17 1740.37
16028.72 1762.5616728.04  1734.118696.02 1809.2419824.57 1742.0222950.91 1886.93
#Mann= 20 ,-1 , 0
-13480.3     .16       0-12630.1     .16       0-11736.8      .1       0
  -10705      .1       0 -8543.5     .05       0 -6771.6      .1       0
 -3926.7     .05       0 -2754.3     .05       0   292.8     .05       0
  1502.6     .05       0  2532.6     .05       04497.141     .07       0
  5116.6     .16       0  5849.8      .1       0  7744.7      .1       0
  9004.1      .1       0 10174.3      .1       0 14967.7      .1       0
   19113      .1       0 22679.7     .16       0
#XS Ineff= 2 , 0
             250  1677.6
Permanent Ineff=
       F       F
Bank Sta=4497.141,5075.4
XS Rating Curve= 0 ,0
Exp/Cntr=0.3,0.1