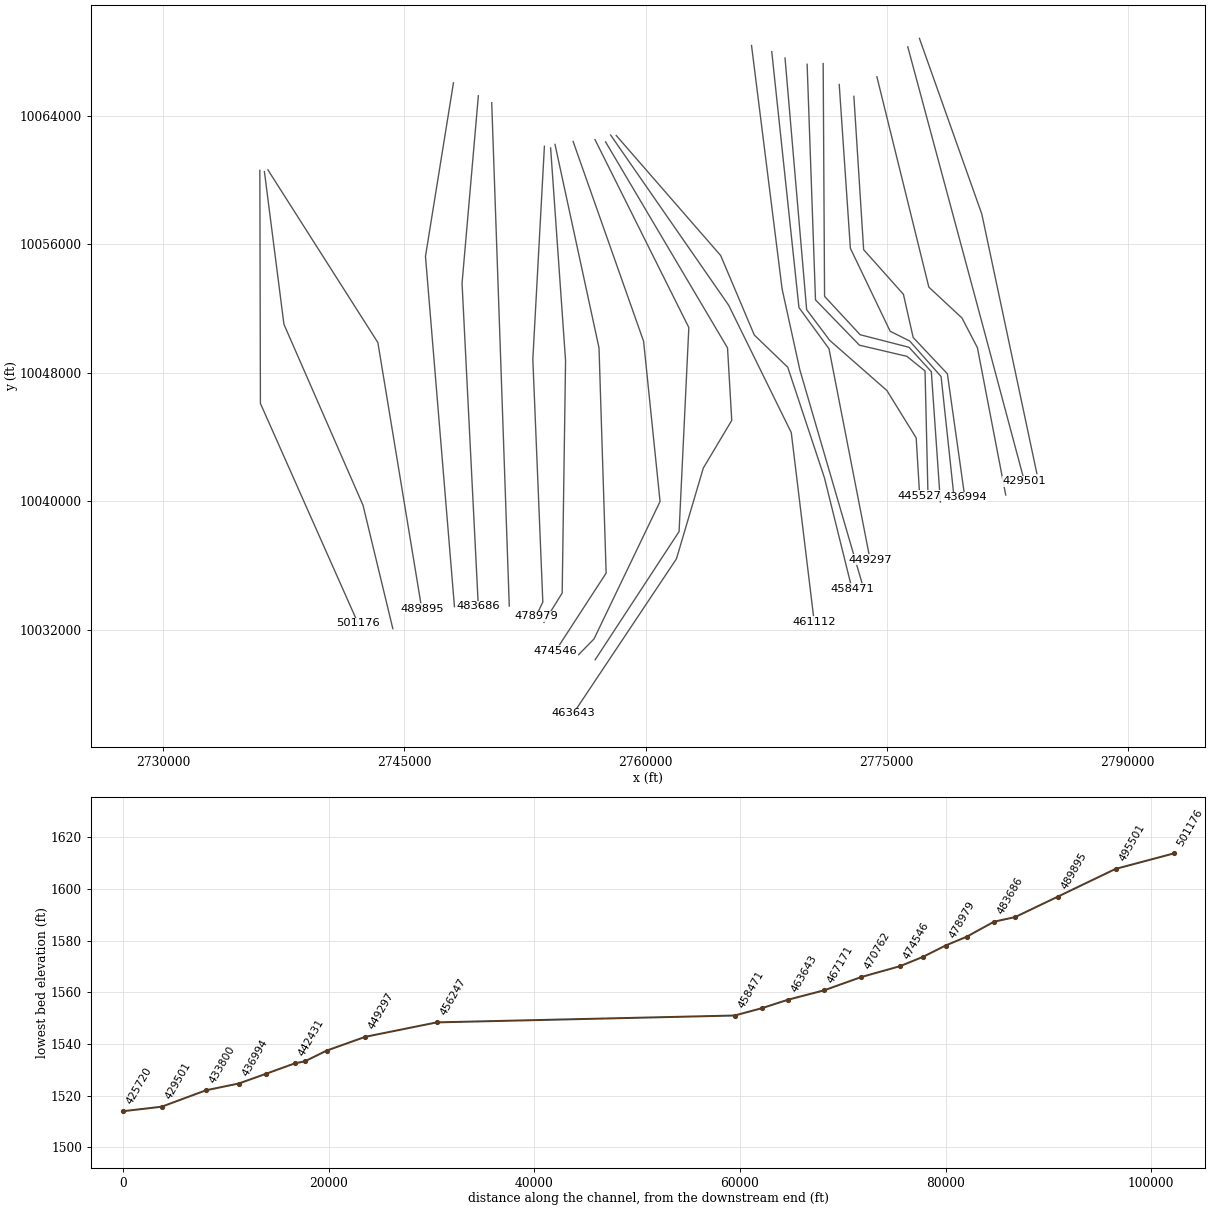
HEC-RAS study PEDERNALES RIVER.prj: PEDERNALES RIVER Base Level Engineering

--- PEDERNALES RIVER.g01 (geometry) --- (continued)

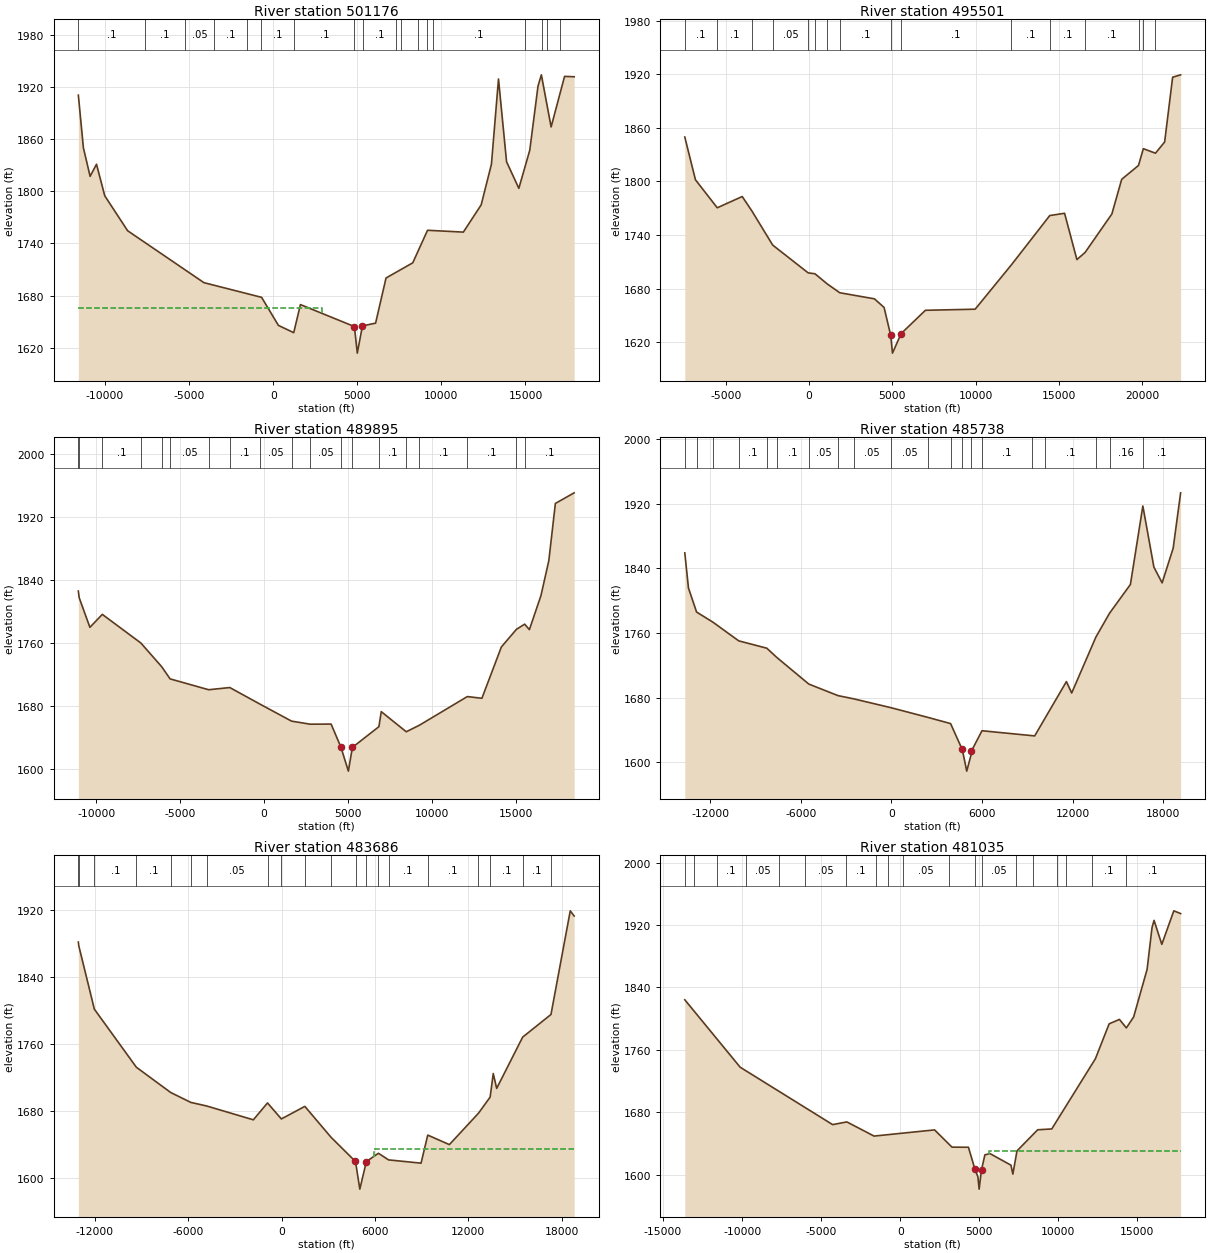
Type RM Length L Ch R = 1 ,501176  ,5675,5675,5675
BEGIN DESCRIPTION:
PEDERNALES RIVER 111.0
END DESCRIPTION:
XS GIS Cut Line= 3
      2736008.92     10060590.75      2736044.37     10046076.45
      2742111.85     10032398.55
#Sta/Elev= 30
  -11585 1910.47-11285.1 1849.95-10885.2 1817.06-10505.4 1830.99-10015.6 1794.74
-8656.15 1754.53-4117.92 1694.78-689.259 1677.89310.3496 1645.62 1219.99 1637.27
 1619.84 1669.56  4827.1 1644.28  5000.7 1613.73  5305.1 1645.056088.029  1648.2
6707.789 1700.13 8297.17  1717.6 9176.82 1755.0411305.99 1752.9312365.58 1784.28
12975.34 1831.0313395.17 1929.0513874.99 1833.85 14604.7 1803.2715254.45  1847.1
15744.26 1920.9115944.18 1933.8416523.95 1873.9117323.64 1932.0517893.42 1931.62
#Mann= 18 ,-1 , 0
-11586.1      .1       0 -7593.8      .1       0 -5263.9     .05       0
 -3491.5      .1       0   -1563     .05       0    -698      .1       0
  1265.7      .1       0  4827.1     .07       0  5314.4      .1       0
  7323.6     .05       0  7568.8      .1       0  8638.6      .1       0
  9130.1     .16       0  9478.8      .1       0   14958      .1       0
 15980.3     .16       0 16262.1      .1       0 17072.4      .1       0
#XS Ineff= 2 , 0
         2917.61 1666.15
Permanent Ineff=
       F       F
Bank Sta=4827.1,5305.1
XS Rating Curve= 0 ,0
Exp/Cntr=0.3,0.1

Type RM Length L Ch R = 1 ,495501  ,5606,5606,5606
BEGIN DESCRIPTION:
PEDERNALES RIVER 112.0
END DESCRIPTION:
XS GIS Cut Line= 4
      2736293.29     10060505.23      2737507.49     10051004.32
      2742428.26     10039732.72       2744280.7      10032054.4
#Sta/Elev= 30
   -7469 1849.62-6829.12 1801.78-5519.37 1770.44-4019.65 1783.03-3439.76 1766.87
   -2190 1728.67-60.4199 1697.59   349.5 1696.55 1079.36 1685.28 1839.21 1675.31
 3918.98 1668.52 4498.92 1658.86  4898.4  1627.5  5002.7 1607.73  5521.8 1629.59
 6978.68 1655.67 9968.42 1656.9212138.27 1706.4314448.11 1761.7315337.93 1764.28
16077.79 1712.4416567.69 1720.3818177.38 1763.4918767.26 1802.2919777.07 1817.82
20067.01 1836.5920796.87 1831.5521346.76 1844.0821826.67 1916.5822306.57 1919.27
#Mann= 16 ,-1 , 0
   -7469      .1       0-5519.37      .1       0-3439.76      .1       0
   -2190     .05       0-60.4199      .1       0   349.5     .16       0
 1079.36      .1       0 1839.21      .1       0  4898.4     .07       0
  5521.8      .1       012138.27      .1       014448.11      .1       0
16567.69      .1       019777.07     .05       020067.01      .1       0
20796.87      .1       0
Bank Sta=4898.4,5521.8
XS Rating Curve= 0 ,0
Exp/Cntr=0.3,0.1

Type RM Length L Ch R = 1 ,489895  ,4157,4157,4157
BEGIN DESCRIPTION:
PEDERNALES RIVER 113.0
END DESCRIPTION:
XS GIS Cut Line= 3
      2736511.93     10060617.89      2743351.53     10049864.49
      2746080.83     10033287.41
#Sta/Elev= 30
  -11071  1825.5  -11021 1817.11-10381.3 1779.47-9641.65  1795.9-7342.69 1759.55
-6103.26 1729.48-5603.49 1714.07-3304.54 1700.29-2045.15 1703.06 -226.04  1681.8
 1633.06 1660.47 2742.51 1656.57  3991.9 1656.72  4579.9 1627.21  5020.2 1597.02
    5258  1627.16840.381 1653.456980.301 1672.488469.439 1646.97 9248.99 1655.23
12107.34 1691.6112976.84 1689.4314136.17 1754.5415035.65 1776.9415525.37 1783.52
15805.21 1776.5216494.81 1819.6716964.54  1864.117354.31 1936.6518473.67 1950.12
#Mann= 19 ,-1 , 0
  -11071      .1       0  -11021      .1       0-9641.65      .1       0
-7342.69     .05       0-6103.26      .1       0-5603.49     .05       0
-3304.54     .05       0-2045.15      .1       0 -226.04     .05       0
 1633.06      .1       0 2742.51     .05       0  4579.9     .07       0
    5258     .16       06840.381      .1       08469.439     .05       0
 9248.99      .1       012107.34      .1       015035.65     .16       0
15525.37      .1       0
Bank Sta=4579.9,5258
XS Rating Curve= 0 ,0
Exp/Cntr=0.3,0.1

Type RM Length L Ch R = 1 ,485738  ,2052,2052,2052
BEGIN DESCRIPTION:
PEDERNALES RIVER 114.0
END DESCRIPTION:
XS GIS Cut Line= 3
      2748052.29     10066036.85      2746312.11     10055235.39
       2748114.6     10033420.56
#Sta/Elev= 30
-13684.2 1859.31-13441.6 1815.86-12903.3 1786.04-11820.9 1773.52  -10115 1750.41
 -8251.9 1741.29 -7609.9 1730.14 -5471.8 1696.88   -3541  1682.6 -2495.2 1678.59
   -62.4 1667.78  2429.4 1655.56  3914.4 1647.97  4679.6 1616.12  4684.6 1616.31
  4984.2  1589.1  5275.4 1609.62  5295.5 1613.99 5993.24  1639.1 9483.24  1632.7
11583.24 1699.9411933.24 1685.82 13531.4 1754.93 14436.7 1784.53 15821.2 1820.21
 16644.7 1917.39 17376.5 1841.71 17920.5 1822.18   18651 1865.02 19145.7 1933.67
#Mann= 20 ,-1 , 0
-13684.2      .1       0-12903.3      .1       0-11820.9      .1       0
  -10115      .1       0 -8251.9     .05       0 -7609.9      .1       0
 -5471.8     .05       0   -3541      .1       0 -2495.2     .05       0
   -62.4     .05       0  2429.4     .05       0  3914.4      .1       0
  4684.6     .07       0  5275.4      .1       0  6002.4      .1       0
  9286.3     .16       0 10178.1      .1       0 13531.4     .16       0
 14436.7     .16       0 16644.7      .1       0
Bank Sta=4679.6,5295.5
XS Rating Curve= 0 ,0
Exp/Cntr=0.3,0.1

Type RM Length L Ch R = 1 ,483686  ,2651,2651,2651
BEGIN DESCRIPTION:
PEDERNALES RIVER 115.0
END DESCRIPTION:
XS GIS Cut Line= 3
      2749602.04     10065230.41      2748587.41     10053557.66
       2749599.5     10033438.57
#Sta/Elev= 30
  -13059 1881.64  -13029 1877.14-12029.2 1801.69-9330.04 1732.53-7120.67  1702.4
-5831.04 1690.64-4811.33 1686.36-1812.21 1669.89 -902.48    1690-12.7402 1670.94
 1496.82  1685.9 3176.33 1649.17  4747.4 1620.29  4752.4 1620.31    5030 1587.32
  5400.7 1616.33  5410.7 1619.686225.721 1630.03 6875.59 1622.16 8965.18 1618.25
  9395.1 1651.6810784.83 1640.3612654.46 1677.7413404.32 1696.9413604.28 1725.01
13824.23  1707.315493.91 1768.3917313.55 1795.3718553.31 1918.8518803.26 1912.68
#Mann= 20 ,-1 , 0
  -13059      .1       0  -13029      .1       0-12029.2      .1       0
-9330.04      .1       0-7120.67      .1       0-5831.04      .1       0
-4811.33     .05       0 -902.48      .1       0-12.7402     .05       0
 1496.82      .1       0 3176.33      .1       0  4752.4     .07       0
  5400.7      .1       06225.721     .05       0 6875.59      .1       0
  9395.1      .1       012654.46      .1       013404.32      .1       0
15493.91      .1       017313.55      .1       0
#XS Ineff= 2 , 0
                         5920.45         1634.61
Permanent Ineff=
       F       F
Bank Sta=4747.4,5410.7
XS Rating Curve= 0 ,0
Exp/Cntr=0.3,0.1

Type RM Length L Ch R = 1 ,481035  ,2056,2056,2056
BEGIN DESCRIPTION:
PEDERNALES RIVER 116.0
END DESCRIPTION:
XS GIS Cut Line= 2
      2750432.81      10064799.2      2751524.95     10033460.52
#Sta/Elev= 30
  -13625 1824.15-10125.2 1737.77 -4275.7 1664.19-3375.79 1667.64-1655.96  1649.5
 2173.67 1657.423273.609 1635.314313.609 1635.18    4721 1607.35  4911.1 1597.27
  4990.9 1581.52  5141.3 1606.445353.609 1625.435673.609 1627.087003.609 1612.22
7123.609 1600.737383.609 1630.478693.609 1657.589583.609 1658.6412343.61  1748.6
13213.61 1793.3413863.61    179914303.61 1788.0714763.61 1802.2415613.61 1863.15
15923.61 1916.5316053.61  1925.916543.61  1895.217303.61 1938.1417733.61 1934.64
#Mann= 19 ,-1 , 0
-13625.6     .05       0-13041.4      .1       0-11614.1      .1       0
 -9776.5     .05       0 -7653.3      .1       0 -6031.7     .05       0
 -3428.5      .1       0 -1554.2     .16       0  -759.1      .1       0
   149.2     .05       0  3085.9      .1       0    4711     .07       0
  5151.3     .05       0  7352.3     .05       0  8383.1      .1       0
  9926.4     .05       0 10481.1      .1       0 12116.5      .1       0
 14254.6      .1       0
#XS Ineff= 2 , 0
                         5602.27          1630.1
Permanent Ineff=
       F       F
Bank Sta=4721,5141.3
XS Rating Curve= 0 ,0
Exp/Cntr=0.3,0.1

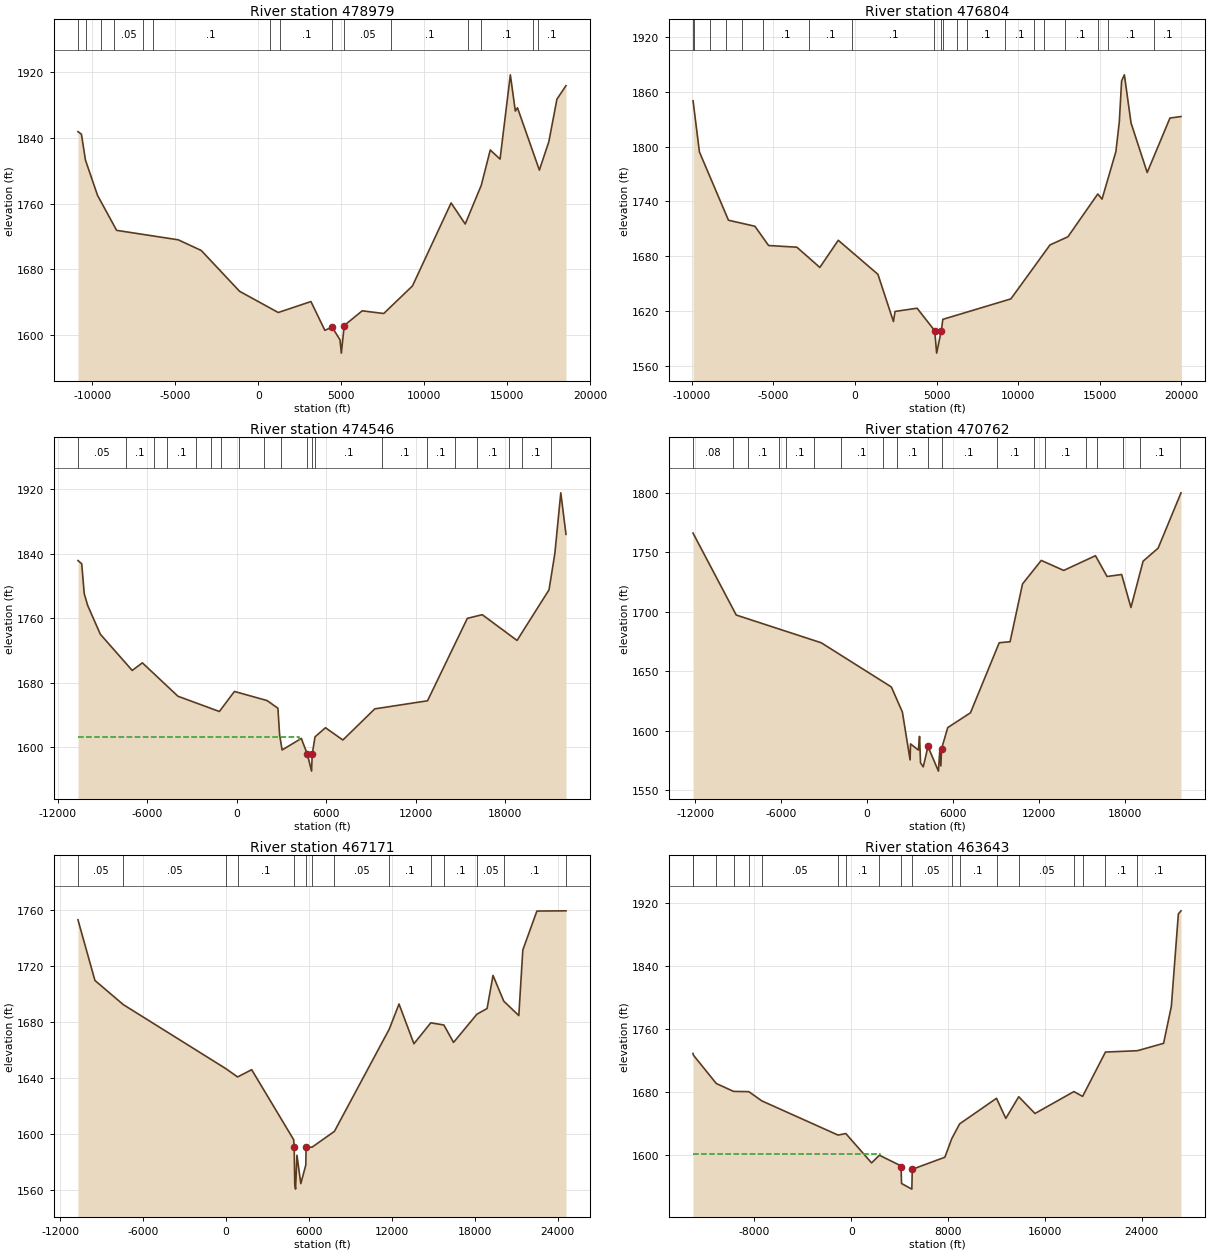
Type RM Length L Ch R = 1 ,478979  ,2175,2175,2175
BEGIN DESCRIPTION:
PEDERNALES RIVER 117.0
END DESCRIPTION:
XS GIS Cut Line= 4
      2753710.57     10062088.62      2752990.17     10048824.22
      2753612.17     10033705.62      2753183.15     10032821.11
#Sta/Elev= 30
  -10867 1847.92-10657.1  1844.8-10417.2  1813.4-9687.54  1770.3-8538.07 1727.67
 -4829.8 1716.17-3440.46 1703.17-1131.54 1653.45 1197.38 1627.59 3166.38 1640.95
 4005.88 1605.89  4442.7 1609.82  4918.6 1594.32  4998.4 1578.11  5172.9 1611.73
 6254.57 1629.647553.801 1626.389282.789 1659.9611611.43 1761.0512460.93 1735.43
13430.36 1782.6813970.04 1825.57 14559.7 1814.4815179.33 1917.1315479.16 1872.98
15609.08 1877.0116928.31 1801.0817497.97  1835.6 17985.2 1887.4718531.76 1903.92
#Mann= 15 ,-1 , 0
  -10868     .05       0  -10380      .1       0 -9491.4     .15       0
 -8701.6     .05       0 -6928.9     .05       0 -6369.5      .1       0
   678.3     .16       0  1329.3      .1       0  4442.7     .07       0
  5172.9     .05       0  8000.7      .1       0 12602.3     .16       0
 13402.2      .1       0 16544.6     .16       0 16845.3      .1       0
Bank Sta=4442.7,5172.9
XS Rating Curve= 0 ,0
Exp/Cntr=0.3,0.1

Type RM Length L Ch R = 1 ,476804  ,2258,2258,2258
BEGIN DESCRIPTION:
PEDERNALES RIVER 118.0
END DESCRIPTION:
XS GIS Cut Line= 4
      2754096.85     10061983.21      2755026.33     10048738.72
      2754815.48     10034270.15      2753682.94     10032442.24
#Sta/Elev= 30
   -9927 1850.28-9537.09 1794.25-7757.48 1719.41-6137.83  1712.8-5298.01 1691.69
-3568.38 1689.86-2158.69  1667.7-1028.91 1697.42 1400.61 1660.15 2350.43 1608.42
 2450.41 1619.45 3799.92    1623  4878.8 1598.42  4998.6 1573.77  5278.9 1597.83
  5288.9  1598.7 5378.84 1610.799546.199 1633.1911944.72 1692.3313044.04 1701.29
14872.91 1748.1815132.75 1742.5215982.22  1794.616192.09 1827.3516332.01 1871.97
 16501.9 1878.7316911.65 1825.8717900.76 1771.7119295.12 1831.3819972.38 1833.02
#Mann= 20 ,-1 , 0
 -9933.4      .1       0 -9864.5     .05       0 -8881.5     .05       0
 -7898.5     .05       0 -6915.5      .1       0 -5637.6      .1       0
 -2848.9      .1       0  -162.5      .1       0  4858.8     .07       0
  5288.9      .1       0  5397.3      .1       0  6272.8     .05       0
  6842.8      .1       0  9187.9      .1       0 10936.7     .05       0
 11576.8     .05       0 12846.9      .1       0 14861.4     .05       0
 15498.3      .1       0 18294.3      .1       0
Bank Sta=4878.8,5278.9
XS Rating Curve= 0 ,0
Exp/Cntr=0.3,0.1

Type RM Length L Ch R = 1 ,474546  ,3784,3784,3784
BEGIN DESCRIPTION:
PEDERNALES RIVER 119.0
END DESCRIPTION:
XS GIS Cut Line= 4
      2754369.17     10062206.53      2757106.88     10049533.81
      2757550.73     10035513.18      2754418.56      10030690.1
#Sta/Elev= 30
  -10659 1831.42-10409.1 1827.43-10239.1 1790.34-10009.2 1775.74-9159.57 1739.99
-7020.39 1695.04-6340.65 1704.52-3951.55 1663.05-1172.62 1644.12-163.009 1669.01
 2026.13  1657.7 2755.93 1648.18 2865.91 1615.67 3035.88 1596.37 4325.63 1610.69
  4725.9 1591.26  5013.8 1570.12    5054 1590.86 5245.45 1612.685945.311 1623.95
 7115.08 1608.76 9254.66 1647.3812793.97 1657.4315463.45 1759.6716463.08 1764.27
18799.42 1732.3120946.06 1795.1421335.45 1840.0821734.83 1915.4822084.28 1863.93
#Mann= 20 ,-1 , 0
-10662.5     .05       0 -7421.3      .1       0   -5593     .05       0
 -4655.5      .1       0 -2765.4      .1       0   -1734      .1       0
 -1033.6      .1       0   176.1      .1       0  1849.4      .1       0
    2940     .05       0  4693.8     .07       0    5054      .1       0
  5231.7      .1       0  9752.6      .1       0 12738.7      .1       0
 14633.8      .1       0 16126.5      .1       0 18256.6      .1       0
 19112.5      .1       0 21046.3      .1       0
#XS Ineff= 2 , 0
         4136.36 1612.58
Permanent Ineff=
       F       F
Bank Sta=4725.9,5054
XS Rating Curve= 0 ,0
Exp/Cntr=0.3,0.1

Type RM Length L Ch R = 1 ,470762  ,3591,3591,3591
BEGIN DESCRIPTION:
PEDERNALES RIVER 120.0
END DESCRIPTION:
XS GIS Cut Line= 5
      2755494.79     10062390.07      2759881.02     10049942.25
      2760903.97     10039971.26      2756796.62     10031414.17
      2755833.12     10030429.02
#Sta/Elev= 30
  -12153 1766.05-9133.46 1697.13-3194.35 1673.81 1704.45 1636.65 2473.92  1615.6
 3013.55 1575.34 3043.53 1588.78 3593.16 1583.64  3673.1  1595.1 3743.06 1572.83
 3932.93 1569.48  4263.8 1586.61 4992.23  1565.9 5082.18 1582.315162.119 1570.28
  5211.5 1584.69 5641.82 1602.497230.801 1614.94 9239.51 1673.82 9999.02 1674.71
10868.46 1723.2812177.43 1743.0513746.15 1734.6315964.34 1747.0216773.68 1729.54
17792.85  1731.218442.31 1703.4819291.62 1742.3820340.77 1753.3521940.57 1799.87
#Mann= 19 ,-1 , 0
-12156.8     .08       0 -9360.7     .05       0 -8334.4      .1       0
 -6171.2     .05       0 -5623.9      .1       0 -3711.1      .1       0
 -1842.9      .1       0    1117     .05       0  2098.1      .1       0
  4263.8     .07       0  5211.5      .1       0  9056.6      .1       0
 11658.1      .1       0 12419.1      .1       0 15333.4     .05       0
 16041.4      .1       0 17874.8      .1       0   19045      .1       0
 21838.8      .1       0
Bank Sta=4263.8,5211.5
XS Rating Curve= 0 ,0
Exp/Cntr=0.3,0.1

Type RM Length L Ch R = 1 ,467171  ,3528,3528,3528
BEGIN DESCRIPTION:
PEDERNALES RIVER 121.0
END DESCRIPTION:
XS GIS Cut Line= 4
      2756856.28     10062505.97      2762694.17     10050802.65
      2762087.63     10038099.17      2756866.51     10030114.61
#Sta/Elev= 30
  -10729  1752.9-9499.14  1709.6-7449.36  1692.4-40.1298 1646.83829.7803 1640.78
 1849.68 1645.96 4889.25 1596.05  4927.3 1590.62  4967.4 1564.58  5027.2 1560.79
  5127.5 1584.97  5407.9 1564.73  5768.3 1578.01  5788.3 1590.536229.029 1590.76
7838.711 1601.9611817.94 1675.03 12517.8  1692.813597.59 1664.4614817.35 1679.38
15766.61 1677.8316465.92 1665.4218154.25 1685.4918893.52  1689.6 19323.1 1713.18
20102.33 1694.8321191.25 1684.5621480.97  1731.322499.88 1759.09 24607.4 1759.25
#Mann= 14 ,-1 , 0
  -10729     .05       0-7449.36     .05       0-40.1298     .05       0
829.7803      .1       0 4889.25     .07       0  5768.3     .16       0
6229.029      .1       07838.711     .05       011817.94      .1       0
14817.35     .05       015766.61      .1       018154.25     .05       0
20102.33      .1       0 24607.4     .05       0
Bank Sta=4927.3,5788.3
XS Rating Curve= 0 ,0
Exp/Cntr=0.3,0.1

Type RM Length L Ch R = 1 ,463643  ,2531,2531,2531
BEGIN DESCRIPTION:
PEDERNALES RIVER 123.0
END DESCRIPTION:
XS GIS Cut Line= 6
      2757515.63     10062360.06       2765101.1      10049534.1
      2765363.81     10045023.09      2763593.96     10042050.17
      2761925.74     10036404.65      2755513.64     10026778.41
#Sta/Elev= 30
  -13081 1728.89  -13041 1726.76-11152.1 1690.89   -9723  1680.9-8463.75 1680.55
-7384.39 1668.86-1088.09 1625.58 -448.46 1627.53 1680.29 1590.37 2330.06 1600.04
4109.529 1586.61  4115.5 1585.63 4159.51 1564.25 5009.25 1557.13  5047.1 1582.27
 7738.85 1597.53 8308.85 1621.02 8958.85 1639.7612006.92 1672.1712776.24 1646.73
13843.28 1674.16 15188.8 1652.9318404.21 1680.6719123.43 1674.5621011.27 1730.71
23658.16 1732.4525817.26 1741.7826457.01 1788.5727036.79 1905.57 27256.7 1909.58
#Mann= 19 ,-1 , 0
  -13081     .05       0  -13041     .05       0-11152.1      .1       0
   -9723      .1       0-8463.75      .1       0-7384.39     .05       0
-1088.09     .05       0 -448.46      .1       0 2330.06     .05       0
4109.529     .07       0  5047.1     .05       0 8308.85     .05       0
 8958.85      .1       012006.92      .1       013843.28     .05       0
18404.21     .05       019123.43      .1       021011.27      .1       0
23658.16      .1       0
#XS Ineff= 2 , 0
         2357.95 1601.56
Permanent Ineff=
       F       F
Bank Sta=4115.5,5047.1
XS Rating Curve= 0 ,0
Exp/Cntr=0.3,0.1

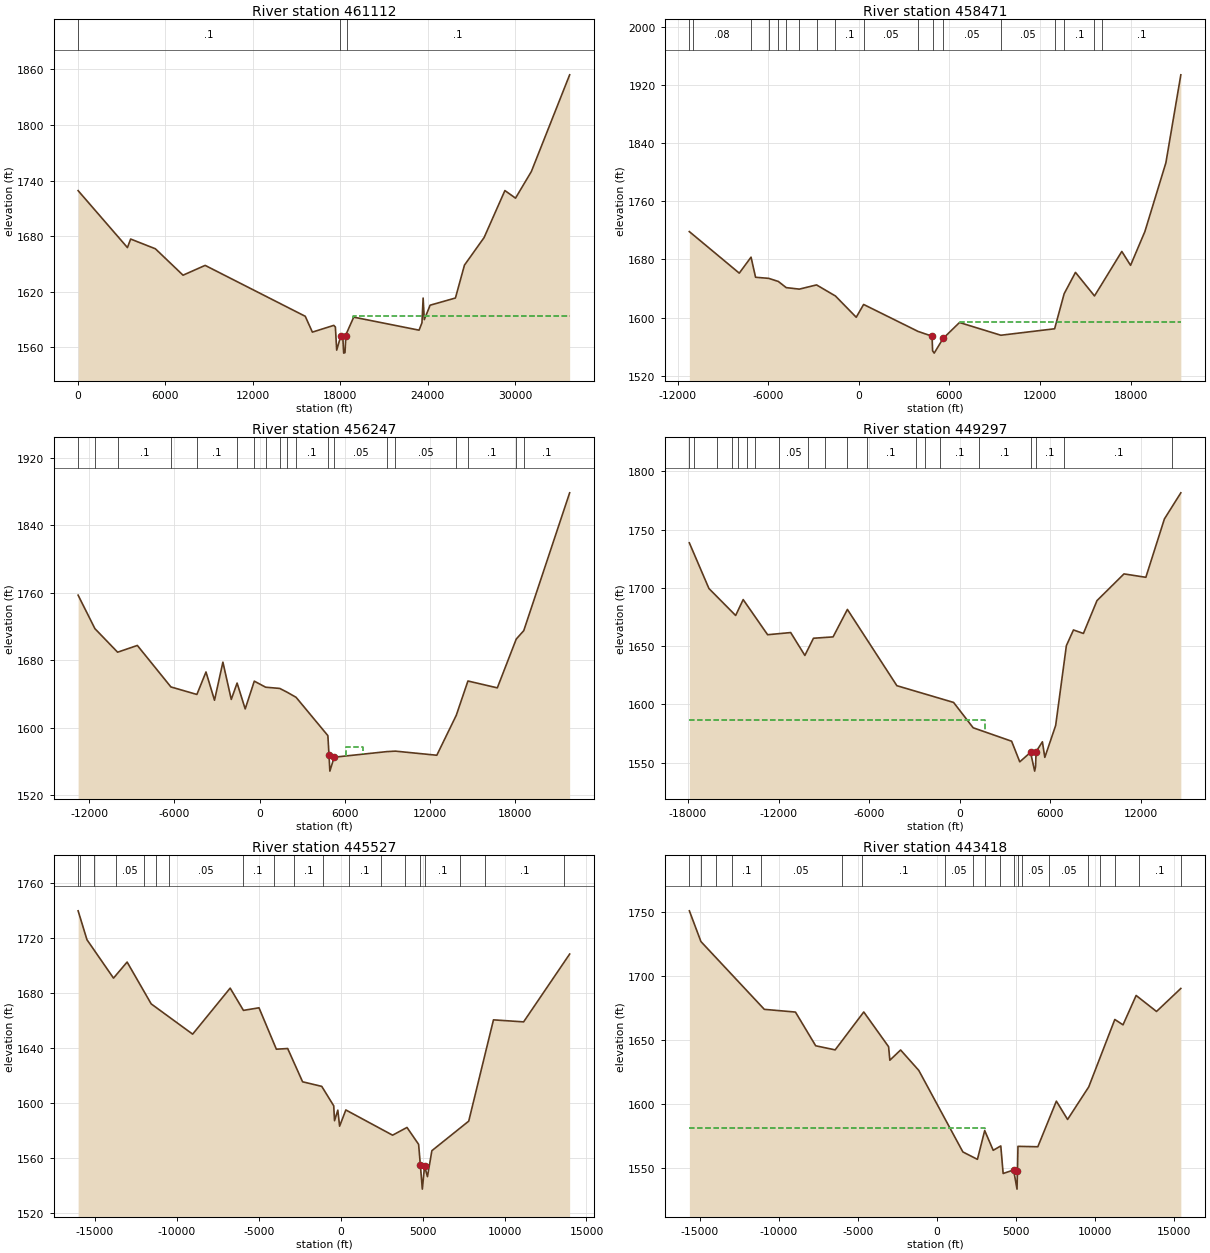
Type RM Length L Ch R = 1 ,461112  ,2641,2641,2641
BEGIN DESCRIPTION:
PEDERNALES RIVER 122.0
END DESCRIPTION:
XS GIS Cut Line= 4
      2757829.51     10062788.91      2765173.27     10052188.94
      2769066.84     10044260.12     2770493.466    10032478.732
#Sta/Elev= 30
       01729.1843387.4681667.7523607.3041676.9665306.0341666.4667204.615 1637.97
8723.4791648.53615598.661593.62216088.361576.54517557.461583.83217667.391582.025
17757.331557.12618037.161572.19918187.071568.38618237.041553.87718326.981554.409
18386.951572.21818436.921575.41818926.621592.69823413.621578.65123613.461586.589
 23693.41613.31223773.34 1590.0124173.021605.58925911.661613.33726531.181648.804
27880.12 1678.5729309.01 1729.2730038.441721.10531127.581749.86133755.531854.142
#Mann= 3 ,-1 , 0
       0      .1       017997.19     .05       018436.92      .1       0
#XS Ineff= 2 , 0
                        18892.04          1593.8
Permanent Ineff=
       F       F
Bank Sta=18037.16,18386.95
XS Rating Curve= 0 ,0
Exp/Cntr=0.3,0.1

Type RM Length L Ch R = 1 ,458471  ,28970,28970,28970
BEGIN DESCRIPTION:
PEDERNALES RIVER 124.0
END DESCRIPTION:
XS GIS Cut Line= 6
      2758179.21      10062758.9       2764675.8     10055284.73
      2766766.82      10050335.7      2768848.42     10048329.42
       2771132.2     10041438.09      2772843.23     10034531.14
#Sta/Elev= 30
  -11219 1718.38-10949.1 1713.77-7911.35 1661.18-7131.91 1683.21-6832.12 1655.52
-5962.73    1654-5323.18 1649.74-4803.55 1641.23-3934.16 1639.17-2794.95 1644.98
-1545.81 1629.75 -167.54 1600.44  321.79 1618.06 3926.86 1580.93  4852.7 1574.35
  4888.2 1554.28    4994 1551.04  5583.3 1571.22  6670.2  1593.29407.641 1575.66
12967.64 1584.5813597.64  1632.814347.56 1662.2415606.82  1629.816096.54  1646.3
17415.76 1691.0917995.42 1671.9518944.87 1718.5520334.05  1813.221323.47 1934.28
#Mann= 18 ,-1 , 0
  -11219     .08       0-10949.1     .08       0-7131.91      .1       0
-5962.73     .05       0-5323.18      .1       0-4803.55      .1       0
-3934.16      .1       0-2794.95     .05       0-1545.81      .1       0
  321.79     .05       0 3926.86      .1       0  4888.2     .07       0
  5583.3     .05       09407.641     .05       012967.64     .16       0
13597.64      .1       015606.82     .05       016096.54      .1       0
#XS Ineff= 2 , 0
                          6670.2         1593.66
Permanent Ineff=
       F       F
Bank Sta=4852.7,5583.3
XS Rating Curve= 0 ,0
Exp/Cntr=0.3,0.1

Type RM Length L Ch R = 1 ,456247  ,6950,6950,6950
BEGIN DESCRIPTION:
PEDERNALES RIVER 125.0
END DESCRIPTION:
XS GIS Cut Line= 4
      2766594.14     10068365.58      2768494.29     10053215.16
      2769600.21      10048168.2      2773558.87     10034576.89
#Sta/Elev= 30
  -12769 1757.01  -11589 1717.35-9989.17 1689.39-8599.25 1697.39-6239.38 1648.21
-4409.48 1639.28-3769.52 1665.95-3169.55 1632.43-2579.59 1677.59-1989.62  1633.4
-1579.65 1652.79-1009.68 1622.14-369.719 1655.07430.2305 1647.87 1420.17 1646.44
 1940.14 1641.96 2570.07 1635.934808.721 1590.46  4887.9 1567.59    4949 1548.38
  5252.5 1564.888956.789 1571.51 9556.68 1572.0812476.11 1567.2113845.84  1614.6
14665.68 1655.2416735.27 1647.1218065.01 1704.9318594.91 1714.9521824.64 1878.35
#Mann= 19 ,-1 , 0
  -12769      .1       0  -11589     .05       0-9989.17      .1       0
-6239.38      .1       0-4409.48      .1       0-1579.65     .16       0
-369.719      .1       0430.2305      .1       0 1420.17      .1       0
 1940.14     .08       0 2570.07      .1       04808.721     .07       0
  5252.5     .05       08956.789      .1       0 9556.68     .05       0
13845.84      .1       014665.68      .1       018065.01     .05       0
18594.91      .1       0
#XS Ineff= 1 ,-1
 6068.18 7295.45  1577.1
Permanent Ineff=
       F
Bank Sta=4887.9,5252.5
XS Rating Curve= 0 ,0
Exp/Cntr=0.3,0.1

Type RM Length L Ch R = 1 ,449297  ,3770,3770,3770
BEGIN DESCRIPTION:
Mapping XS 5a628749
END DESCRIPTION:
XS GIS Cut Line= 4
      2767852.82     10067974.92      2769545.53     10052046.15
      2771411.85     10049485.38      2773972.61     10036334.34
#Sta/Elev= 30
  -17915 1738.67-16615.1 1699.46-14845.2 1676.35-14345.3 1689.98-12725.4 1659.84
-11195.6 1661.69-10255.7 1642.07-9685.79 1656.81-8385.91 1657.97   -7436 1681.53
-4156.33  1616.1 -397.13 1601.74902.3594 1579.993451.789 1568.46 3991.68 1550.77
  4704.6 1558.93  4979.5  1542.8  5040.5  1546.8  5071.4 1559.445491.391 1567.97
5651.359 1554.586371.221 1581.98 7081.08 1650.46 7550.99 1663.928210.859 1660.92
 9110.68  1689.110900.33 1712.0212350.05 1709.0913579.81 1759.17 14669.6 1781.58
#Mann= 20 ,-1 , 0
-17917.5     .16       0-17610.8     .16       0-16071.5      .1       0
-15104.8     .05       0  -14711      .1       0-14064.6     .05       0
-13531.6      .1       0-11954.2     .05       0-10057.5     .05       0
 -8889.3      .1       0 -7463.6      .1       0 -6152.9      .1       0
 -2920.2      .1       0 -2285.1      .1       0 -1302.5      .1       0
  1265.4      .1       0  4704.6     .07       0  5040.5      .1       0
  6947.7      .1       0 14103.7     .05       0
#XS Ineff= 2 , 0
         1715.91 1586.36
Permanent Ineff=
       F       F
Bank Sta=4704.6,5071.4
XS Rating Curve= 0 ,0
Exp/Cntr=0.3,0.1

Type RM Length L Ch R = 1 ,445527  ,2109,2109,2109
BEGIN DESCRIPTION:
Mapping XS 92df53b8
END DESCRIPTION:
XS GIS Cut Line= 6
      2768677.47     10067584.39      2770022.96     10051915.94
      2771455.25     10050006.22      2775014.28     10046881.22
      2776837.19     10043929.83      2777054.17     10040328.07
#Sta/Elev= 30
  -16019 1739.89-15479.1 1718.87-13859.5 1690.94-13029.7 1702.63-11560.1 1672.19
-9030.77 1650.18-6741.33 1683.66-5931.51 1667.47-4981.72 1669.35-3921.96 1639.23
-3232.12 1639.73-2322.32 1615.53-1152.58 1612.19 -422.75 1598.06-372.759 1587.21
-172.919 1594.89-63.0498 1583.25316.5098 1595.043170.199 1576.694048.141 1582.32
 4757.59 1570.02  4864.7 1554.96  4984.7 1537.45  5120.1  1554.2 5297.16 1546.53
5566.949 1565.41 7815.59 1586.919325.051 1660.5811164.43 1659.1113973.56 1708.44
#Mann= 19 ,-1 , 0
-16019.5     .16       0-15916.1      .1       0-15058.1      .1       0
  -13690     .05       0-12016.6      .1       0-11245.3     .05       0
-10488.7     .05       0 -5965.8      .1       0 -4097.3     .05       0
 -2856.1      .1       0 -1083.6      .1       0   536.5      .1       0
  2463.5      .1       0  3902.2      .1       0  4843.7     .07       0
    5162      .1       0  7307.1     .05       0  8836.5      .1       0
 13642.4     .05       0
Bank Sta=4864.7,5120.1
XS Rating Curve= 0 ,0
Exp/Cntr=0.3,0.1

Type RM Length L Ch R = 1 ,443418  ,987,987,987
BEGIN DESCRIPTION:
Mapping XS 0066b6b8
END DESCRIPTION:
XS GIS Cut Line= 6
       2770052.8     10067194.58      2770573.63     10052524.48
        2773308.      10049703.3      2776259.39     10049008.86
      2777387.87      10048097.4      2777577.37     10040107.81
#Sta/Elev= 30
  -15669 1750.77  -14939 1726.77-10929.2 1673.79-8959.29 1671.66-7679.36 1645.32
-6449.41 1642.12-4639.48 1671.74-3069.54 1644.59-2989.55 1634.03-2309.57 1642.03
-1159.62 1626.08 1629.59 1562.362549.301 1556.58 3008.99 1579.09 3547.58 1563.64
 4026.33 1567.07 4175.93 1545.52  4836.5 1548.27  5053.3 1533.31 5081.69 1547.66
 5113.48 1566.74 6368.65 1566.427541.699 1602.06 8251.01 1587.759589.699  1613.2
11238.09 1665.8611757.58 1661.6812586.77 1684.6313875.51 1672.1315414.01 1690.12
#Mann= 20 ,-1 , 0
-15673.4      .1       0-14909.6      .1       0  -13976     .05       0
-12955.2      .1       0-11155.5     .05       0 -6043.5      .1       0
   -4773      .1       0   489.7     .05       0  2243.6     .16       0
  3028.5      .1       0  3973.9      .1       0  4831.4     .07       0
  5113.2      .1       0  5359.7     .05       0  7105.5     .05       0
  9563.7      .1       0 10307.3      .1       0 11222.8     .16       0
 12773.1      .1       0 15403.9      .1       0
#XS Ineff= 2 , 0
         3022.73 1580.73
Permanent Ineff=
       F       F
Bank Sta=4836.5,5081.69
XS Rating Curve= 0 ,0
Exp/Cntr=0.3,0.1

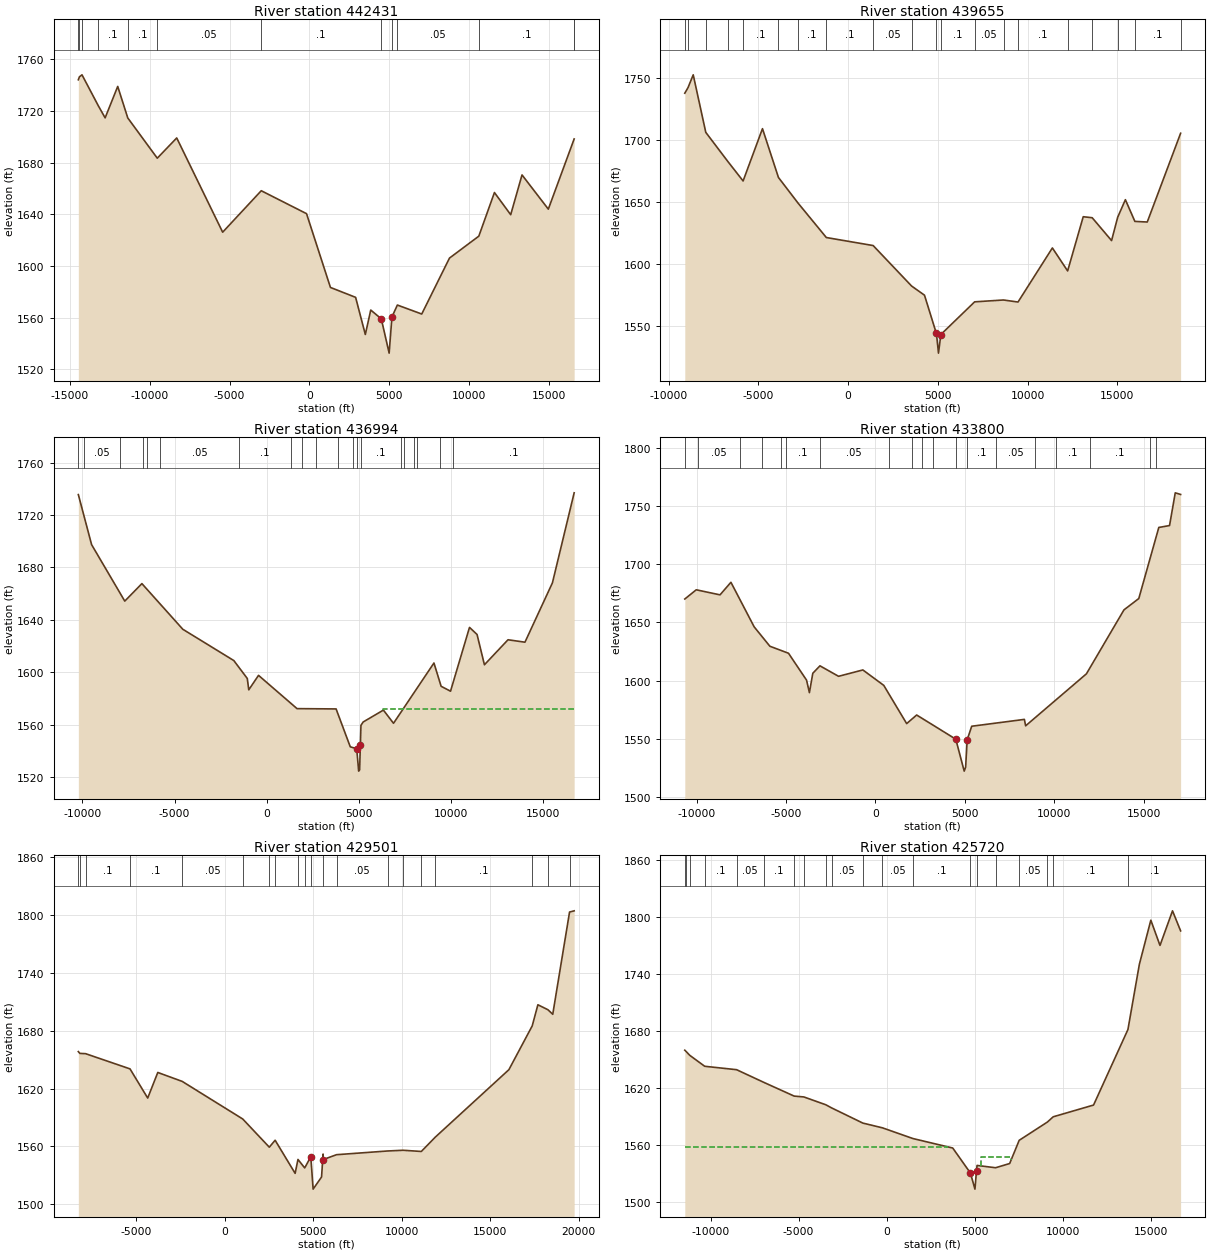
Type RM Length L Ch R = 1 ,442431  ,2776,2776,2776
BEGIN DESCRIPTION:
Mapping XS 1fc5da43
END DESCRIPTION:
XS GIS Cut Line= 6
      2771051.06     10067238.02      2771137.87      10052741.5
      2773351.41     10050354.34       2776389.6     10049573.09
      2777778.49       10048054.      2778342.69     10039938.21
#Sta/Elev= 30
  -14483 1744.05  -14413 1746.32  -14253 1747.86-13233.2    1724-12803.3 1714.56
-12013.5 1738.88-11383.6  1714.5 -9534.1 1683.36-8314.35 1699.02-5434.95 1626.09
-3015.48 1658.18-176.099 1640.42 1322.06 1583.34  2899.9 1575.69 3509.16 1546.93
 3848.83 1565.86  4494.8 1559.21    4500  1559.6  5002.3 1532.52  5157.5 1557.36
  5167.8 1560.215517.199 1569.73 7045.83 1562.788784.561 1606.0610623.62 1623.02
11603.12 1656.79 12622.6 1639.6213332.24 1670.41 14981.4 1643.9416600.57 1698.25
#Mann= 13 ,-1 , 0
  -14483      .1       0  -14413      .1       0  -14253     .05       0
-13233.2      .1       0-11383.6      .1       0 -9534.1     .05       0
-3015.48      .1       0    4500     .07       0  5157.5      .1       0
5517.199     .05       010623.62      .1       016600.57     .16       0
16600.57      .1       0
Bank Sta=4494.8,5167.8
XS Rating Curve= 0 ,0
Exp/Cntr=0.3,0.1

Type RM Length L Ch R = 1 ,439655  ,2661,2661,2661
BEGIN DESCRIPTION:
Mapping XS c24b0705
END DESCRIPTION:
XS GIS Cut Line= 6
      2772049.32     10065935.95      2772743.77     10055736.29
      2775217.73     10050571.36        2776433.     10049963.72
      2778386.13     10047750.18      2779167.37      10040458.6
#Sta/Elev= 30
   -9099 1737.45-8919.12 1741.96-8629.31 1752.23-7929.77 1705.98-6690.59 1682.38
-5851.13 1666.91-4771.84 1708.96-3882.42 1669.73-2793.13 1649.18-1214.16 1621.44
 1393.33 1614.99  3536.1 1582.45 4254.34 1575.08    4916 1544.33  4922.1 1543.86
  5033.4 1528.52  5164.8 1543.47 7047.75 1569.758655.439 1571.23 9463.23 1569.59
11378.32 1613.0812227.55 1594.5913096.76 1638.1713596.31 1637.3514675.33 1618.99
15015.02  1637.715444.63 1651.8615974.15  1634.416663.52 1633.9118521.83 1705.27
#Mann= 20 ,-1 , 0
   -9099      .1       0-8919.12      .1       0-7929.77     .05       0
-6690.59      .1       0-5851.13      .1       0-3882.42     .05       0
-2793.13      .1       0-1214.16      .1       0 1393.33     .05       0
  3536.1     .05       0  4922.1     .07       0  5164.8      .1       0
 7047.75     .05       08655.439      .1       0 9463.23      .1       0
12227.55      .1       013596.31      .1       015015.02      .1       0
15974.15      .1       018521.83      .1       0
Bank Sta=4916,5164.8
XS Rating Curve= 0 ,0
Exp/Cntr=0.3,0.1

Type RM Length L Ch R = 1 ,436994  ,3194,3194,3194
BEGIN DESCRIPTION:
Mapping XS b71ae863
END DESCRIPTION:
XS GIS Cut Line= 6
      2772960.78     10065198.08      2773568.42     10055649.48
      2776042.38      10052871.7      2776650.02     10050180.73
      2778776.75     10047923.79      2779861.82     10040241.52
#Sta/Elev= 30
  -10219 1735.58-9499.16 1697.42-7699.55 1654.36-6769.75 1667.71-4550.21 1632.91
-1780.76 1609.03-1050.91 1595.37-970.919 1586.73-441.009 1597.76 1648.79 1572.39
 3768.31 1572.16 4537.93 1543.28  4887.4  1541.8  4993.2 1524.74  5044.7 1525.65
  5085.7 1544.99 5117.65 1559.66 5237.59  1562.2 6335.83 1571.276884.221 1561.22
9078.189 1607.189468.109 1589.41 9978.01 1585.6911007.81 1634.3311417.73 1628.92
11817.65 1605.83 13097.4  1624.914017.22 1623.0515506.93 1668.27 16686.7 1736.93
#Mann= 20 ,-1 , 0
-10219.5     .05       0 -9904.1     .05       0 -7962.7      .1       0
 -6731.7     .05       0 -6484.9      .1       0 -5787.9     .05       0
 -1488.6      .1       0  1313.5     .05       0  1932.4      .1       0
  2656.3     .05       0  3877.5      .1       0  4692.2      .1       0
  4880.6     .07       0  5095.9      .1       0  7299.6     .05       0
    7454      .1       0  7989.6     .05       0  8140.4      .1       0
  9432.5     .05       0 10103.9      .1       0
#XS Ineff= 2 , 0
                         6318.18         1572.28
Permanent Ineff=
       F       F
Bank Sta=4887.4,5085.7
XS Rating Curve= 0 ,0
Exp/Cntr=0.3,0.1

Type RM Length L Ch R = 1 ,433800  ,4299,4299,4299
BEGIN DESCRIPTION:
PEDERNALES RIVER 133.0
END DESCRIPTION:
XS GIS Cut Line= 5
      2774393.07     10066413.39      2777624.14     10053317.94
      2779685.67     10051396.17      2780646.55     10049544.29
      2782406.93     10040374.18
#Sta/Elev= 30
  -10657 1670.13  -10017 1678.05-8687.27  1673.7-8077.35 1684.52-6777.53 1646.18
-5897.64  1629.5-4857.79 1623.49-3847.92 1600.39-3687.94 1589.61-3497.96 1606.27
-3098.02 1612.67-2058.16 1603.66 -698.36 1609.13471.4805 1595.86 1751.29 1562.98
 2311.22 1570.38  4499.5 1549.58 4969.89 1522.12 5049.84 1525.53  5136.1 1549.02
 5389.64 1560.728335.699 1566.618405.689 1561.0811805.02 1605.7913904.61 1660.77
14734.45 1670.5415854.23 1731.6716454.11 1733.2916774.05 1761.4417073.99 1760.04
#Mann= 19 ,-1 , 0
-10657.5      .1       0 -9946.2     .05       0 -7587.3      .1       0
 -6324.7     .05       0 -5287.1     .05       0 -4971.1      .1       0
 -3114.3     .05       0   741.1      .1       0  2064.1     .05       0
  2598.1      .1       0  3215.4     .05       0  4520.5     .07       0
  5150.2      .1       0  6722.6     .05       0  8943.3     .05       0
 10076.6      .1       0 12026.1      .1       0 15334.3     .05       0
 15676.6      .1       0
Bank Sta=4499.5,5136.1
XS Rating Curve= 0 ,0
Exp/Cntr=0.3,0.1

Type RM Length L Ch R = 1 ,429501  ,3781,3781,3781
BEGIN DESCRIPTION:
PEDERNALES RIVER 134.0
END DESCRIPTION:
XS GIS Cut Line= 3
      2776314.54     10068279.53      2781004.48     10050835.36
      2783568.56     10041230.24
#Sta/Elev= 30
   -8264 1658.27-8174.03  1656.4-7854.14 1656.14-5345.03 1640.37-4345.38 1610.14
-3775.58 1636.66-2396.05 1627.39 1022.77 1588.44 2522.25 1559.24 2852.13 1566.43
 3981.74  1532.1 4141.69 1546.53 4521.55 1537.73  4866.9 1549.34  4996.8 1515.77
  5473.4 1528.33  5560.4 1552.15  5566.6 1546.42 6320.93 1551.459199.881 1555.29
10079.42 1556.0311108.58  1554.811897.93 1569.65 16054.5 1639.5217373.41 1684.95
17693.15 1706.8318262.68 1701.6418532.46 1696.9519481.67 1802.8919741.46 1804.16
#Mann= 20 ,-1 , 0
   -8264     .05       0-8174.03     .05       0-7854.14      .1       0
-5345.03      .1       0-2396.05     .05       0 1022.77      .1       0
 2522.25     .05       0 2852.13      .1       0 4141.69      .1       0
 4521.55     .05       0  4866.9     .07       0  5560.4      .1       0
 6320.93     .05       09199.881      .1       010079.42     .05       0
11108.58      .1       011897.93      .1       017373.41      .1       0
18262.68      .1       019481.67      .1       0
Bank Sta=4866.9,5566.6
XS Rating Curve= 0 ,0
Exp/Cntr=0.3,0.1

Type RM Length L Ch R = 1 ,425720  ,1712,1712,1712
BEGIN DESCRIPTION:
PEDERNALES RIVER 135.0
END DESCRIPTION:
XS GIS Cut Line= 3
      2777037.31     10068809.18      2780919.59     10057865.96
      2784343.75     10041710.01
#Sta/Elev= 30
  -11458 1659.93  -11388 1658.66-11178.2 1654.55-10328.8 1643.03-8520.17 1639.44
-6971.32  1626.1-5252.59 1611.71   -4703 1610.82-3463.92 1602.65-3124.17 1599.27
 -1355.5 1583.36 -246.33 1578.39 1483.11 1567.14 3742.67 1557.18    4747 1530.88
  5002.3 1514.02  5091.3  1533.4  5122.4 1538.896172.189 1536.486972.039  1540.9
 7511.93 1565.279111.619 1584.459441.551 1589.9711731.11 1602.3113680.73 1681.59
 14330.6  1750.214980.47 1796.4215500.37 1769.9316210.23 1806.2716670.14 1785.22
#Mann= 20 ,-1 , 0
  -11458      .1       0  -11388      .1       0-11178.2      .1       0
-10328.8      .1       0-8520.17     .05       0-6971.32      .1       0
-5252.59      .1       0   -4703      .1       0-3463.92      .1       0
-3124.17     .05       0 -1355.5      .1       0 -246.33     .05       0
 1483.11      .1       0    4747     .07       0  5122.4      .1       0
6172.189      .1       0 7511.93     .05       09111.619      .1       0
9441.551      .1       013680.73      .1       0
#XS Ineff= 2 ,-1
  -11458 3498.43 1558.42 5339.35 7051.84 1548.16
Permanent Ineff=
       F       F
Bank Sta=4747,5091.3
XS Rating Curve= 0 ,0
Exp/Cntr=0.3,0.1