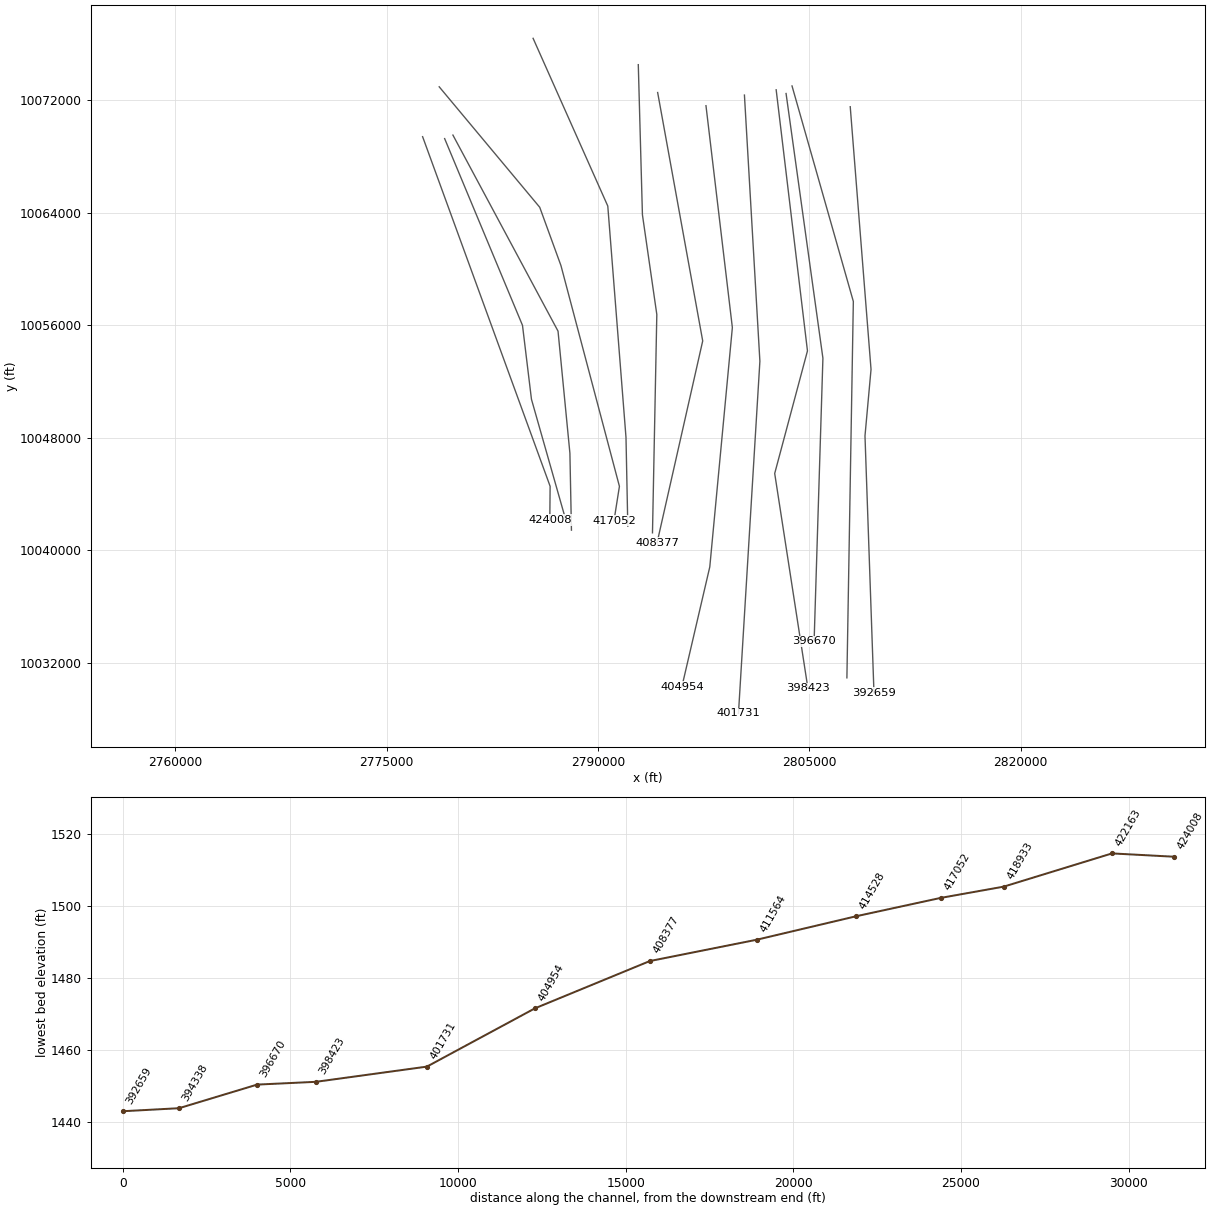
HEC-RAS study PEDERNALES RIVER.prj: PEDERNALES RIVER Base Level Engineering

--- PEDERNALES RIVER.g01 (geometry) --- (continued)

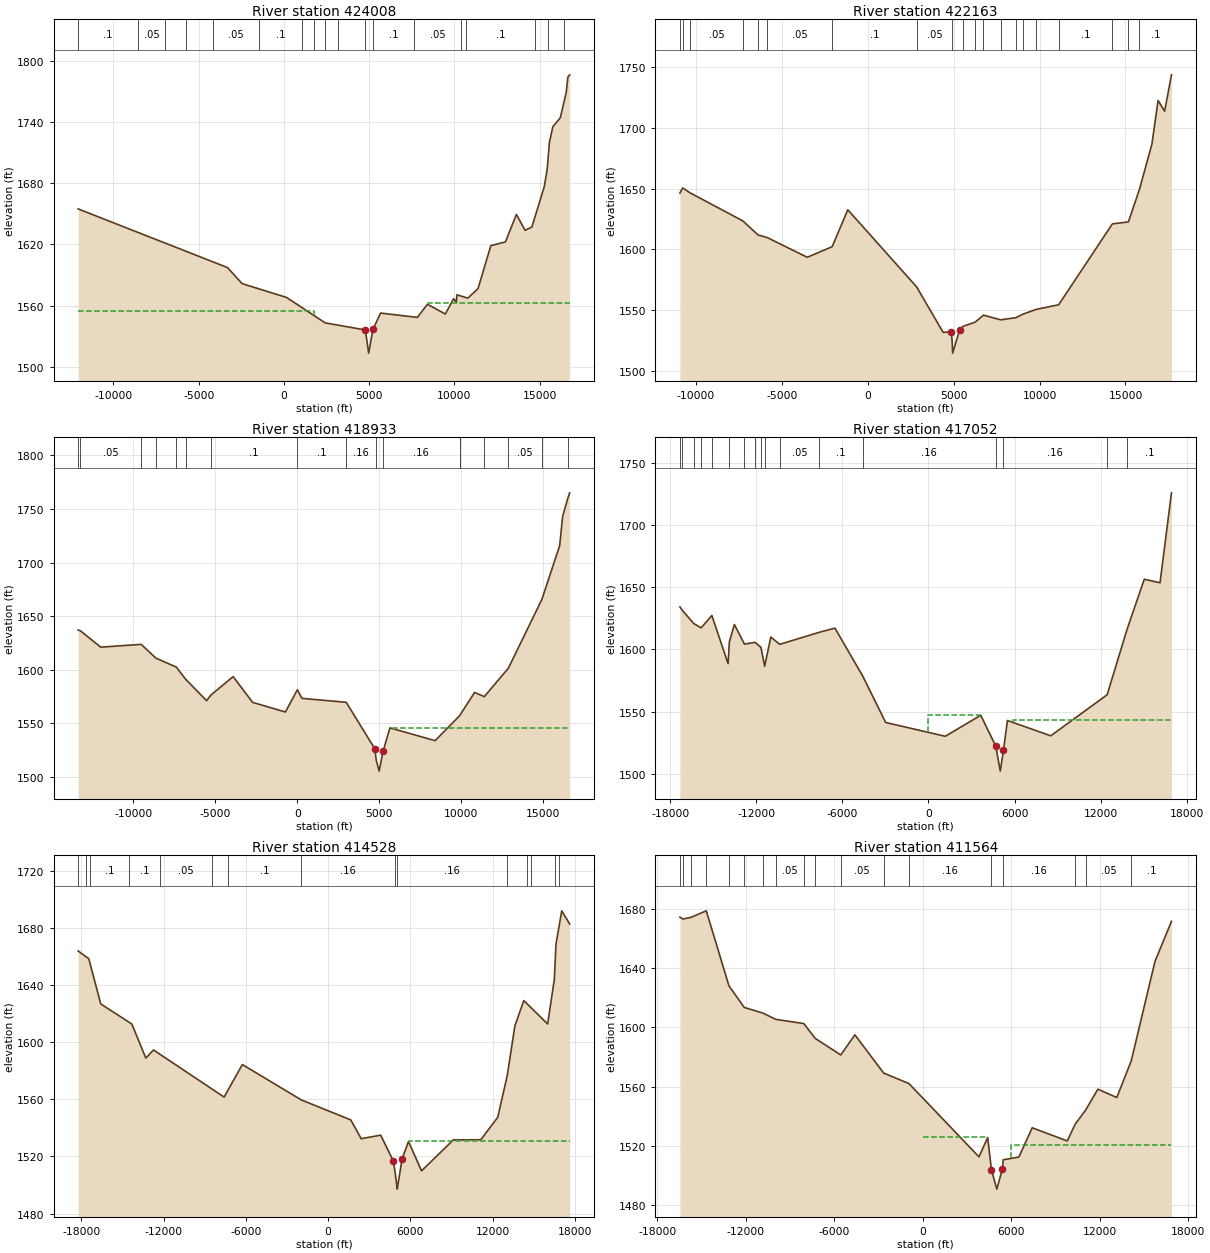
Type RM Length L Ch R = 1 ,424008  ,1845,1845,1845
BEGIN DESCRIPTION:
PEDERNALES RIVER 136.0
END DESCRIPTION:
XS GIS Cut Line= 3
      2777551.19     10069388.29      2786601.61     10044548.39
      2786578.47      10042152.1
#Sta/Elev= 30
  -12070 1654.76-3310.88 1597.36-2450.96 1581.65  158.79 1568.08 2418.56 1543.25
  4778.8  1536.3  4970.2 1513.63  5223.1 1536.87 5668.23 1552.83    7828  1548.6
8417.939 1561.48 9467.83 1551.919957.779 1566.9110117.76 1563.3710147.76 1570.74
10787.69 1567.4611387.62 1576.8212137.55 1618.7912997.46 1622.5213637.39 1649.34
14147.33 1633.8414547.03 1637.0815275.89 1676.7815445.62 1693.8615575.42 1720.13
15775.11 1735.1816214.42 1744.0116563.87 1769.1116653.73 1783.7116763.56    1786
#Mann= 18 ,-1 , 0
  -12074      .1       0 -8576.9     .05       0 -6957.6      .1       0
 -5735.4      .1       0 -4176.8     .05       0 -1462.3      .1       0
  1052.2     .05       0  1735.9      .1       0    2424     .05       0
  3191.7      .1       0  4746.9     .07       0  5253.7      .1       0
  7602.2     .05       0   10408     .05       0   10708      .1       0
 14746.6     .16       0 15499.9      .1       0 16424.2     .05       0
#XS Ineff= 2 , 0
         1784.09 1554.44 8426.14         1562.33
Permanent Ineff=
       F       F
Bank Sta=4778.8,5223.1
XS Rating Curve= 0 ,0
Exp/Cntr=0.3,0.1

Type RM Length L Ch R = 1 ,422163  ,3230,3230,3230
BEGIN DESCRIPTION:
PEDERNALES RIVER 137.0
END DESCRIPTION:
XS GIS Cut Line= 4
       2779115.4      10069250.9      2784640.43     10055983.72
      2785276.84      10050730.7      2787724.85     10042113.86
#Sta/Elev= 30
  -10942 1646.26  -10782 1650.52-10362.3 1646.57-7274.13 1623.33-6384.64 1611.74
-5874.93 1609.77-3526.27 1593.43-2077.11 1602.15-1167.65 1632.54    2840  1569.1
 4388.07 1531.55  4863.6 1532.32 4917.19 1522.29 4937.15 1514.55    5337 1533.31
 5536.17 1536.576245.061 1540.026734.289 1545.81 7732.73 1541.95 8621.34 1543.73
9021.119 1546.549810.971 1550.5811110.71 1554.35 14240.1 1620.9415169.92 1622.52
 15809.8 1649.0716539.65 1686.4816899.58 1722.4917279.51 1713.6217679.43 1743.59
#Mann= 20 ,-1 , 0
  -10942      .1       0  -10782      .1       0-10362.3     .05       0
-7274.13      .1       0-6384.64      .1       0-5874.93     .05       0
-2077.11      .1       0    2840     .05       0 4917.19     .07       0
 5536.17     .05       06245.061      .1       06734.289     .05       0
 7732.73      .1       0 8621.34     .05       09021.119      .1       0
9810.971      .1       011110.71      .1       0 14240.1      .1       0
15169.92     .05       0 15809.8      .1       0
Bank Sta=4863.6,5337
XS Rating Curve= 0 ,0
Exp/Cntr=0.3,0.1

Type RM Length L Ch R = 1 ,418933  ,1881,1881,1881
BEGIN DESCRIPTION:
PEDERNALES RIVER 144.0
END DESCRIPTION:
XS GIS Cut Line= 4
      2779702.67     10069501.08       2787162.9     10055571.46
      2788005.57     10046900.58      2788115.05     10041432.77
#Sta/Elev= 30
  -13372 1637.02  -13242 1636.39-11992.7 1621.02-9524.05 1623.64-8634.52 1610.84
-7385.21 1602.42-6815.51 1591.11-5536.21 1571.06-5266.35 1576.41-3917.08 1593.53
-2727.73 1569.48-728.799 1560.51.7998047 1581.22280.6504 1573.22 2978.97 1569.55
  4728.6 1526.06  4808.8 1515.64  4989.5 1505.32  5226.6 1523.755646.359 1545.69
 8403.67 1533.739892.211 1556.9910811.31 1578.7411400.94 1574.8312870.65  1601.4
14910.25 1665.4416000.04  1715.816180.01 1743.1216479.95  1759.216609.92 1765.04
#Mann= 17 ,-1 , 0
  -13372     .05       0  -13242     .05       0-9524.05      .1       0
-8634.52      .1       0-7385.21      .1       0-6815.51     .05       0
-5266.35      .1       0.7998047      .1       0 2978.97     .16       0
  4808.8     .07       0  5226.6     .16       09892.211     .05       0
9892.211      .1       011400.94     .05       012870.65     .05       0
14910.25      .1       016479.95     .05       0
#XS Ineff= 2 , 0
       0                 5825.73       0 1545.49
Permanent Ineff=
       F       T
Bank Sta=4728.6,5226.6
XS Rating Curve= 0 ,0
Exp/Cntr=0.3,0.1

Type RM Length L Ch R = 1 ,417052  ,2524,2524,2524
BEGIN DESCRIPTION:
PEDERNALES RIVER 145.0
END DESCRIPTION:
XS GIS Cut Line= 5
      2778728.75     10072932.39      2785863.63     10064372.41
      2787372.15     10060223.79      2791520.23     10044543.86
      2791133.32       10042092.
#Sta/Elev= 30
  -17322 1634.22-17152.1 1631.47-16362.5 1620.89-15842.8 1617.35-15093.2 1627.28
-13963.9 1588.53  -13874 1606.21-13524.2 1620.04-12824.6 1604.31  -12085  1605.7
-11675.2 1601.72-11415.4 1586.53-10985.6 1609.99  -10366  1604.1-7607.67 1613.78
-6518.31 1617.17-4580.54 1578.61-2982.57 1541.291175.881  1530.23645.881 1547.09
4695.881 1522.16  5006.4 1502.19  5229.4 1519.015505.881  1542.98525.881 1530.58
12455.88 1563.5813855.88 1616.5915044.26 1656.4616141.25 1653.5916939.07  1725.9
#Mann= 17 ,-1 , 0
  -17322     .05       0-17152.1     .05       0-16362.5     .05       0
-15842.8      .1       0-15093.2      .1       0  -13874      .1       0
-12824.6     .05       0  -12085      .1       0-11675.2     .16       0
-11415.4      .1       0  -10366     .05       0-7607.67      .1       0
-4580.54     .16       04695.881     .07       0  5229.4     .16       0
12455.88      .1       013855.88      .1       0
#XS Ineff= 2 , 0
       0 3568.46 1547.02 5892.12       0 1543.67
Permanent Ineff=
       T       T
Bank Sta=4695.881,5229.4
XS Rating Curve= 0 ,0
Exp/Cntr=0.3,0.1

Type RM Length L Ch R = 1 ,414528  ,2964,2964,2964
BEGIN DESCRIPTION:
PEDERNALES RIVER 148.0
END DESCRIPTION:
XS GIS Cut Line= 4
      2785393.64     10076375.74      2790694.06     10064460.21
      2791986.66     10048016.65      2792114.89      10041717.2
#Sta/Elev= 30
  -18228 1663.89-17448.5 1658.41-16579.1  1626.8-14310.6  1612.7-13291.3 1588.88
-12731.7 1594.54 -7585.2 1561.55-6256.11 1584.34-1957.87 1559.561650.721 1545.56
 2410.43 1532.393829.869 1534.91 4759.51 1516.64  4900.5 1507.46  5040.6 1497.09
  5043.9 1497.59 5389.26 1518.16 5859.08 1530.456808.711 1509.919127.801 1531.57
11127.02 1531.6612365.71 1547.42 13054.9  1576.513614.24  1611.414263.48 1629.13
16001.44 1612.7316490.87 1643.9416610.73 1668.6717030.23 1691.9817609.55 1682.73
#Mann= 15 ,-1 , 0
-18228.3      .1       0-17619.8     .16       0-17379.9      .1       0
-14483.6      .1       0-12275.6     .05       0 -8482.7     .16       0
 -7333.2      .1       0-1957.87     .16       0  4900.5     .07       0
  5043.9     .16       0 13054.9      .1       0 14504.3     .05       0
 14821.7      .1       0 16529.2     .16       0 16859.1      .1       0
#XS Ineff= 2 , 0
       0                 5892.12       0 1531.09
Permanent Ineff=
       F       T
Bank Sta=4759.51,5389.26
XS Rating Curve= 0 ,0
Exp/Cntr=0.3,0.1

Type RM Length L Ch R = 1 ,411564  ,3187,3187,3187
BEGIN DESCRIPTION:
PEDERNALES RIVER 150.0
END DESCRIPTION:
XS GIS Cut Line= 4
      2792859.27     10074505.42      2793153.26     10063838.61
      2794173.95     10056755.62      2793866.53     10041240.98
#Sta/Elev= 30
  -16478 1674.68-16268.1 1673.39-15718.6 1674.56-14689.5 1678.95-13150.8 1628.17
-12111.7 1613.55-10842.8 1609.71-9983.57 1605.51-8075.22 1602.64 -7295.9 1592.58
-5567.35  1581.4-4607.89 1595.01-2658.99 1569.15 -939.96 1562.01 3808.24 1512.43
4398.119 1525.51  4653.5 1503.65    5018 1490.57  5403.6 1504.43 5447.92 1510.43
6517.711 1512.327417.529  1532.1 9797.07 1523.1910336.96 1534.5811036.83 1543.99
11876.66 1558.2313156.41 1552.5814136.22 1577.3615745.91 1644.65 16865.8 1671.86
#Mann= 18 ,-1 , 0
  -16478      .1       0-16268.1      .1       0-15718.6      .1       0
-14689.5      .1       0-13150.8      .1       0-12111.7     .05       0
-10842.8      .1       0-9983.57     .05       0-8075.22      .1       0
 -7295.9      .1       0-5567.35     .05       0-2658.99      .1       0
 -939.96     .16       0  4653.5     .07       0 5447.92     .16       0
10336.96     .05       011036.83     .05       014136.22      .1       0
#XS Ineff= 2 , 0
       0  4379.5 1525.69 5959.06       0 1520.22
Permanent Ineff=
       T       T
Bank Sta=4653.5,5403.6
XS Rating Curve= 0 ,0
Exp/Cntr=0.3,0.1

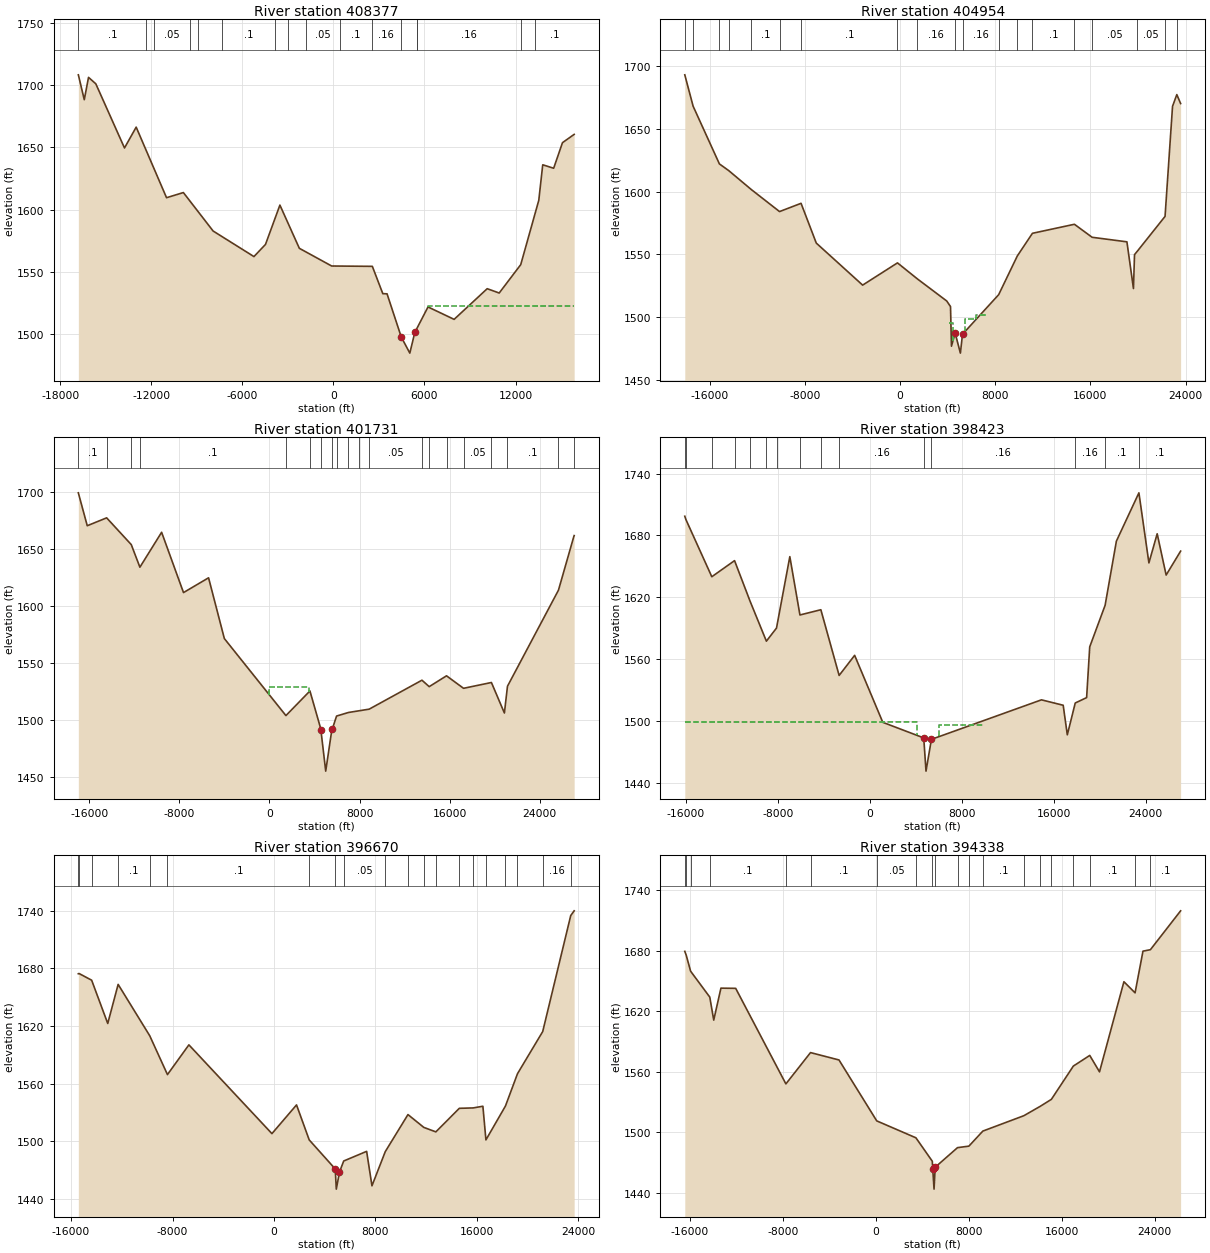
Type RM Length L Ch R = 1 ,408377  ,3423,3423,3423
BEGIN DESCRIPTION:
PEDERNALES RIVER 152.0
END DESCRIPTION:
XS GIS Cut Line= 3
      2794233.74     10072525.04      2797431.27     10054876.37
      2794186.79     10040513.25
#Sta/Elev= 30
  -16800 1708.19  -16410  1688.2-16130.1 1706.14-15650.2 1700.99-13760.6 1649.44
-12990.8 1666.17-10991.3 1609.49-9881.57 1613.62   -7922 1582.73-5232.53  1562.2
-4472.68 1571.96-3522.86 1603.56-2243.11 1568.85-113.529 1554.63 2565.67 1554.35
  3255.4 1532.423535.289 1532.28  4470.8 1497.625034.711 1484.65 5364.58 1501.27
 6234.24 1521.747953.561 1511.7710132.71  1536.4 10922.4 1532.9312341.85 1555.73
13531.38 1607.4513791.28 1635.93   14511 1633.1515090.78 1653.6915860.47 1660.35
#Mann= 16 ,-1 , 0
-16801.7      .1       0-12313.7      .1       0-11796.3     .05       0
 -9437.5      .1       0 -8926.3     .05       0 -7336.6      .1       0
 -3876.7      .1       0 -2990.8      .1       0 -1807.1     .05       0
   423.2      .1       0  2538.8     .16       0  4440.3     .07       0
  5523.8      .1       0  5523.8     .16       012341.85      .1       0
 13291.9      .1       0
#XS Ineff= 2 , 0
       0                 6241.01       0 1522.11
Permanent Ineff=
       F       T
Bank Sta=4470.8,5364.58
XS Rating Curve= 0 ,0
Exp/Cntr=0.3,0.1

Type RM Length L Ch R = 1 ,404954  ,3223,3223,3223
BEGIN DESCRIPTION:
PEDERNALES RIVER 154.0
END DESCRIPTION:
XS GIS Cut Line= 4
      2797663.12     10071589.93       2799535.8     10055824.19
      2797933.69      10038820.2      2795953.64     10030307.92
#Sta/Elev= 30
  -18114 1692.83-17414.1 1667.88-15204.6    1622-14424.7 1616.71-12505.1 1601.49
-10145.6 1584.09-8336.03 1590.65-7056.28 1559.04-3157.04 1525.61 -227.25 1543.29
 1432.75 1530.66 3912.75    1513 4232.75 1508.57 4312.75 1477.02 4622.75 1487.55
 5062.75 1471.53 5242.75 1486.54 8282.75 1518.01 9852.75 1548.8211122.75 1566.81
14652.75 1573.9916141.63 1563.6519069.13 1560.0319618.66 1522.8919708.58 1549.85
19948.38 1552.6322276.39 1580.2622905.85 1667.8123265.54 1677.1123585.27    1670
#Mann= 19 ,-1 , 0
  -18114      .1       0-17414.1     .05       0-15204.6      .1       0
-14424.7      .1       0-12505.1      .1       0-10145.6      .1       0
-8336.03      .1       0 -227.25     .05       0 1432.75     .16       0
 4622.75     .07       0 5242.75     .16       0 8282.75      .1       0
 9852.75      .1       011122.75      .1       014652.75     .05       0
16141.63     .05       019948.38     .05       022276.39     .16       0
23265.54      .1       0
#XS Ineff= 3 ,-1
 4072.93 4430.54  1495.4 5417.95 6261.26 1498.74 6394.69 7275.36 1502.19
Permanent Ineff=
       T       T       T
Bank Sta=4622.75,5242.75
XS Rating Curve= 0 ,0
Exp/Cntr=0.3,0.1

Type RM Length L Ch R = 1 ,401731  ,3308,3308,3308
BEGIN DESCRIPTION:
PEDERNALES RIVER 156.0
END DESCRIPTION:
XS GIS Cut Line= 3
      2800392.65     10072344.35      2801489.62     10053433.16
      2799969.35     10028412.88
#Sta/Elev= 30
-16957.7 1699.31-16165.8 1670.46-14445.3 1677.38-12258.6 1653.92-11492.8 1634.11
 -9564.7 1664.73 -7622.5 1611.86 -5397.7 1624.81 -3996.3 1571.53  1468.2 1504.03
  3598.9 1525.62  4589.5 1491.46  4609.5 1488.31    5000 1455.34  5547.7 1491.86
  5552.7 1491.19  5961.8 1503.61  7020.1 1506.75  7915.2 1508.17  8856.7 1509.66
 13541.3 1535.05 14185.2 1529.39 15722.7  1538.9 17233.1 1527.94 19707.9 1533.03
 20859.5  1506.3 21134.8 1529.78 25659.2 1613.98   27018 1660.86 27051.7 1661.82
#Mann= 20 ,-1 , 0
-16957.7      .1       0-14445.3      .1       0-12258.6      .1       0
-11492.8      .1       0  1468.2      .1       0  3598.9     .16       0
  4609.5     .07       0  5552.7     .16       0  5961.8      .1       0
  7020.1     .05       0  7915.2     .05       0  8856.7     .05       0
 13541.3      .1       0 14185.2     .05       0 15722.7     .05       0
 17233.1     .05       0 19707.9     .05       0 21134.8      .1       0
 25659.2      .1       0   27018     .16       0
#XS Ineff= 2 , 0
       0 3511.48 1529.02               0
Permanent Ineff=
       T       F
Bank Sta=4589.5,5547.7
XS Rating Curve= 0 ,0
Exp/Cntr=0.3,0.1

Type RM Length L Ch R = 1 ,398423  ,1753,1753,1753
BEGIN DESCRIPTION:
PEDERNALES RIVER 157.0
END DESCRIPTION:
XS GIS Cut Line= 4
      2802645.14     10072718.76      2804866.32     10054168.52
      2802541.05     10045459.28      2804895.98     10030208.79
#Sta/Elev= 30
  -16090 1698.65  -16000 1695.61-13740.9 1639.89-11761.6 1655.53-10422.1 1616.43
-8992.72 1577.33-8113.05 1590.04 -6953.5  1659.4-6073.85 1602.76-4254.56 1607.86
-2665.18 1544.03-1315.71 1563.56 1133.34 1498.51  4696.4 1483.36  4891.4 1451.12
  5343.7 1480.74  5357.2 1481.9514935.53 1520.3516824.45 1515.0917184.29 1486.39
17873.99 1517.2918863.57 1522.5119133.45  1571.820472.88  1612.221452.46 1674.46
23411.61 1721.3824281.24 1653.3225000.93 1681.61 25780.6 1641.5227040.05 1664.76
#Mann= 15 ,-1 , 0
  -16090      .1       0  -16000      .1       0-13740.9      .1       0
-11761.6      .1       0-10422.1     .05       0-8992.72      .1       0
-8113.05      .1       0-6073.85      .1       0-4254.56      .1       0
-2665.18     .16       0  4696.4     .07       0  5343.7     .16       0
17873.99     .16       020472.88      .1       023411.61      .1       0
#XS Ineff= 3 ,-1
  -16090 4107.88 1498.94 6063.26 9947.49 1496.1114933.63 18900.5 1519.76
Permanent Ineff=
       T       T       T
Bank Sta=4696.4,5357.2
XS Rating Curve= 0 ,0
Exp/Cntr=0.3,0.1

Type RM Length L Ch R = 1 ,396670  ,2332,2332,2332
BEGIN DESCRIPTION:
PEDERNALES RIVER 163.0
END DESCRIPTION:
XS GIS Cut Line= 3
      2803347.99     10072454.89      2805962.94     10053648.94
      2805338.26     10033544.53
#Sta/Elev= 30
  -15427  1674.3  -15367 1674.51-14377.1 1667.57-13107.3 1622.58-12287.5 1663.21
-9797.92 1609.85-8398.14 1569.44-6708.44 1600.35-159.719 1508.05 1779.91  1537.9
2779.711 1501.54  4831.6 1471.34  4916.3 1450.35  5166.7 1468.01    5499 1479.58
 7308.48 1489.627728.359 1453.828778.051 1489.3410567.54 1527.8611817.18 1514.53
 12766.9 1509.8714616.37 1534.3615706.06 1534.7816475.84 1536.5116715.77 1501.54
18255.23 1536.7519204.86 1570.3621194.08 1614.1823403.22 1734.7923673.11  1739.7
#Mann= 20 ,-1 , 0
  -15427      .1       0  -15367      .1       0-14377.1     .16       0
-12287.5      .1       0-9797.92     .05       0-8398.14      .1       0
2779.711     .05       0  4831.6     .07       0    5499     .05       0
8778.051      .1       010567.54     .05       011817.18      .1       0
 12766.9      .1       014616.37      .1       015706.06      .1       0
16715.77     .16       018255.23      .1       019204.86      .1       0
21194.08     .16       023403.22      .1       0
Bank Sta=4831.6,5166.7
XS Rating Curve= 0 ,0
Exp/Cntr=0.3,0.1

Type RM Length L Ch R = 1 ,394338  ,1679,1679,1679
BEGIN DESCRIPTION:
PEDERNALES RIVER 158.0
END DESCRIPTION:
XS GIS Cut Line= 3
      2803770.31     10072992.87      2808122.58     10057680.36
       2807665.2      10030937.8
#Sta/Elev= 30
  -16427 1679.18  -16307 1675.47  -15927 1659.56-14277.1  1633.9-13937.1 1611.13
-13317.1 1642.76-12047.2 1642.56-7727.51 1547.96-5607.72 1578.96-3157.96 1571.66
91.73047 1511.34 3461.51 1494.61 4871.42  1471.4  4911.6 1463.78  5021.4 1443.79
  5121.7 1465.487041.279 1484.868021.211 1486.359221.131 1501.25 12750.9 1516.48
14150.81 1525.7115120.74 1532.6917010.66 1565.6318420.66 1576.1519260.66 1559.89
21360.66 1649.1122320.66 1638.1223000.66 1679.3823640.66 1680.8426240.66 1719.31
#Mann= 20 ,-1 , 0
  -16427     .16       0  -16307     .16       0  -15927     .16       0
-14277.1      .1       0-7727.51      .1       0-5607.72      .1       0
91.73047     .05       0 3461.51      .1       0 4871.42     .07       0
  5121.7     .05       07041.279     .05       08021.211      .1       0
9221.131      .1       0 12750.9     .05       014150.81      .1       0
15120.74     .05       017010.66     .05       018420.66      .1       0
22320.66     .16       023640.66      .1       0
Bank Sta=4911.6,5121.7
XS Rating Curve= 0 ,0
Exp/Cntr=0.3,0.1

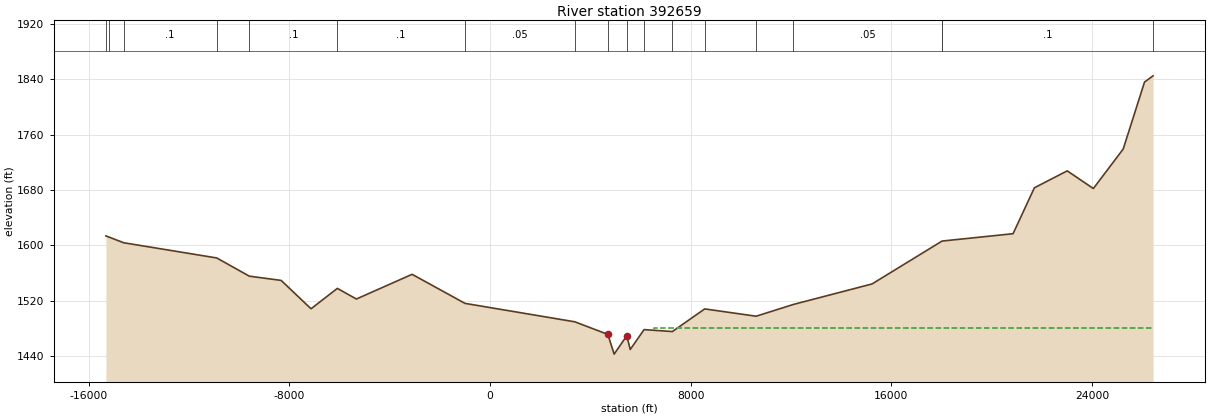
Type RM Length L Ch R = 1 ,392659  ,2353,2353,2353
BEGIN DESCRIPTION:
PEDERNALES RIVER 173.0
END DESCRIPTION:
XS GIS Cut Line= 4
      2807901.95     10071518.02      2809378.08     10052854.51
      2808949.21     10048126.81      2809587.08     10029869.25
#Sta/Elev= 30
  -15307 1613.79  -15197 1612.28-14597.3 1603.89-10888.9 1581.92-9589.52  1555.6
 -8320.1 1549.46-7130.63 1508.49-6081.06 1537.94-5321.36 1522.59-3102.26 1558.28
 -993.12 1516.293385.141 1489.65    4701 1471.45  4951.8 1442.95  5453.8  1469.5
5593.859 1449.686143.529 1478.377272.869 1475.57 8562.35 1508.2810612.35 1497.73
12092.35 1514.6915232.35 1544.3818022.35 1606.3420852.35 1616.9521702.35 1683.31
23012.35 1707.7724052.35 1682.2225242.35  1739.326092.35 1836.0926432.35 1845.11
#Mann= 18 ,-1 , 0
  -15307      .1       0  -15197      .1       0-14597.3      .1       0
-10888.9     .05       0-9589.52      .1       0-6081.06      .1       0
 -993.12     .05       03385.141     .05       0    4701     .07       0
  5453.8     .05       06143.529      .1       07272.869      .1       0
 8562.35     .05       010612.35      .1       012092.35     .05       0
18022.35     .05       018022.35      .1       026432.35      .1       0
#XS Ineff= 2 , 0
                         6530.99         1481.02
Permanent Ineff=
       F       F
Bank Sta=4701,5453.8
XS Rating Curve= 0 ,0
Exp/Cntr=0.3,0.1