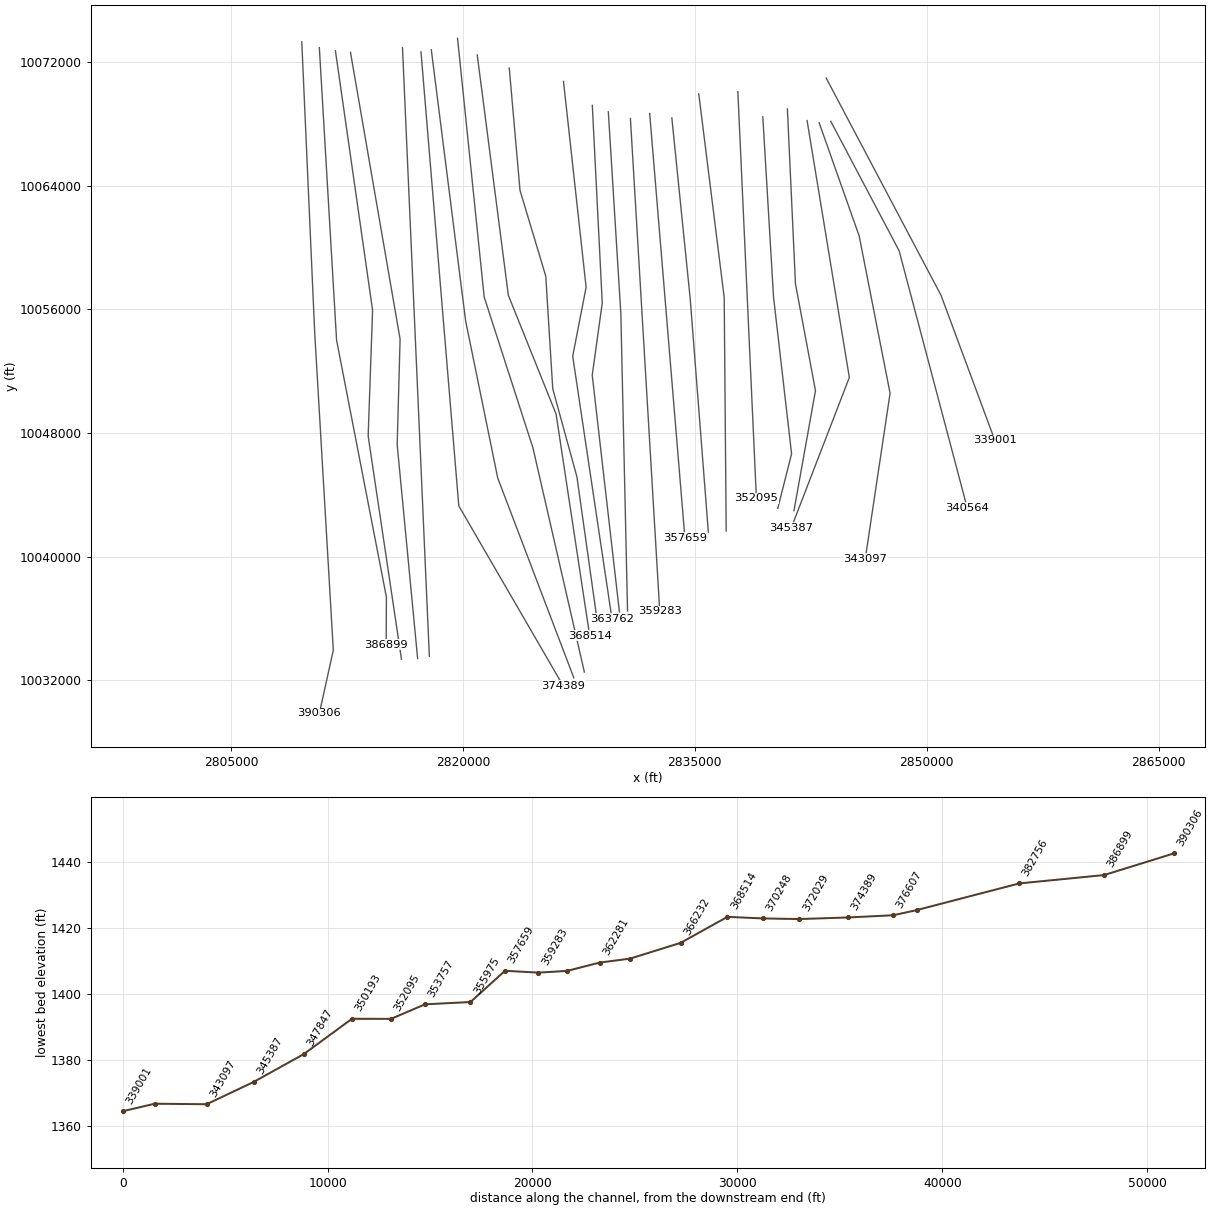
HEC-RAS study PEDERNALES RIVER.prj: PEDERNALES RIVER Base Level Engineering

--- PEDERNALES RIVER.g01 (geometry) --- (continued)

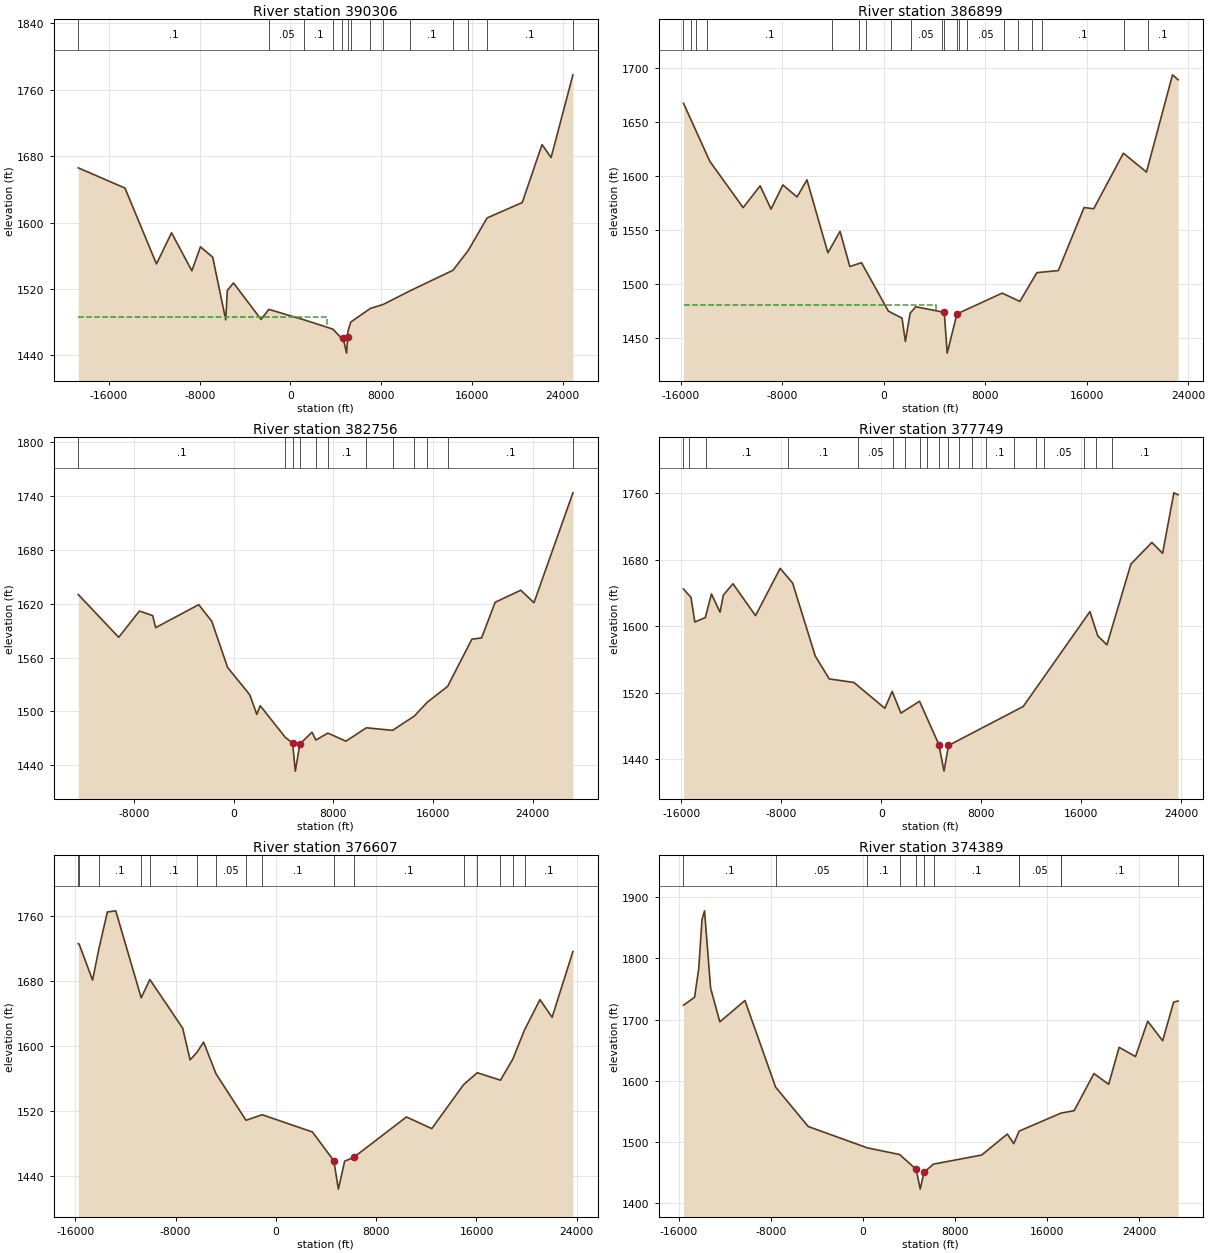
Type RM Length L Ch R = 1 ,390306  ,3407,3407,3407
BEGIN DESCRIPTION:
PEDERNALES RIVER 161.0
END DESCRIPTION:
XS GIS Cut Line= 4
      2809582.46     10073323.63      2810418.22     10054496.19
      2811622.25     10033936.43      2810717.27     10029847.03
#Sta/Elev= 30
  -18718 1665.97-14598.8 1641.63-11819.4 1550.18-10489.7 1587.72-8700.09 1541.88
-7940.24 1570.79-6860.45 1558.35-5710.67 1482.79 -5570.7 1518.17-5030.81 1527.34
-2591.28 1483.33-1911.42 1495.451217.971 1482.76 3737.48 1471.68 4537.32 1460.18
  4639.4 1461.18 4947.24 1442.72  5050.1 1462.735067.221 1469.01 5317.17 1480.13
 7036.84 1496.538186.609 1501.4310556.15 1517.8914335.36 1542.5715664.84 1566.12
17344.18 1605.6220442.97 1624.1822189.41 1694.0122987.54  1678.424913.02 1778.08
#Mann= 14 ,-1 , 0
  -18718      .1       0-1911.42     .05       01217.971      .1       0
 3737.48      .1       0 4537.32     .07       05067.221      .1       0
 5317.17      .1       0 7036.84     .05       08186.609     .05       0
10556.15      .1       014335.36      .1       015664.84     .05       0
17344.18      .1       024913.02      .1       0
#XS Ineff= 2 , 0
         3218.88 1485.69
Permanent Ineff=
       F       F
Bank Sta=4639.4,5050.1
XS Rating Curve= 0 ,0
Exp/Cntr=0.3,0.1

Type RM Length L Ch R = 1 ,386899  ,4143,4143,4143
BEGIN DESCRIPTION:
PEDERNALES RIVER 167.0
END DESCRIPTION:
XS GIS Cut Line= 4
      2810718.33     10072952.21      2811833.35     10054006.53
      2815055.92     10037377.79      2815041.08     10034304.41
#Sta/Elev= 30
  -15788 1666.98-13718.1 1613.43-11088.3 1570.59-9748.52 1590.74 -8888.6 1569.21
 -7958.7 1591.58-6838.81 1580.45-6058.88 1596.27-4409.04 1528.84-3449.14 1548.66
-2679.21 1516.19 -1759.3 1519.71360.4902 1474.961440.449 1468.421700.439 1446.87
 2070.43 1472.95 2520.42 1478.98  4765.2 1473.86  4998.8 1436.15  5763.6 1472.35
9329.221 1491.5910728.95 1483.9412068.69 1510.5313758.36 1512.4315787.97 1570.65
16547.82 1569.5618887.74  1620.920706.43 1603.4722761.78 1693.3123200.79 1688.74
#Mann= 20 ,-1 , 0
-15795.4      .1       0-15212.6      .1       0-14766.6     .05       0
-13939.7      .1       0 -4063.9      .1       0   -1943     .16       0
 -1380.6      .1       0   580.3      .1       0  2127.6     .05       0
  4560.1      .1       0  4765.2     .07       0  5763.6      .1       0
  5894.9      .1       0  6570.7     .05       0  9466.3     .05       0
 10562.2      .1       0 11672.7     .05       0 12471.4      .1       0
 18930.1      .1       0 20788.7      .1       0
#XS Ineff= 2 , 0
         4118.35 1480.55
Permanent Ineff=
       F       F
Bank Sta=4765.2,5763.6
XS Rating Curve= 0 ,0
Exp/Cntr=0.3,0.1

Type RM Length L Ch R = 1 ,382756  ,5007,5007,5007
BEGIN DESCRIPTION:
PEDERNALES RIVER 169.0
END DESCRIPTION:
XS GIS Cut Line= 4
      2811758.52     10072750.07      2814162.23      10055948.5
      2813875.92     10047804.55      2816029.78     10033351.08
#Sta/Elev= 30
  -12495 1630.16 -9246.4 1582.56-7587.13 1611.78 -6517.6 1606.75 -6277.7 1593.32
-2819.18 1618.91-1769.62 1600.37-500.139 1549.03 1279.12 1518.65 1848.89 1496.74
 2118.78 1506.444147.949 1470.99  4724.9 1464.83 4937.73 1433.61  5305.4  1463.7
6277.461 1476.93  6597.4 1468.217557.211 1475.95 9006.93 1466.9310646.61 1481.83
12756.17 1479.0114505.41 1494.9615544.97  1510.417174.26 1527.8819123.42 1580.47
19903.09 1581.8820992.64 1621.5623051.84 1634.9724111.43 1621.06 27240.2 1743.38
#Mann= 12 ,-1 , 0
  -12495      .1       04147.949     .05       0  4724.9     .07       0
  5305.4      .1       0  6597.4      .1       07557.211      .1       0
10646.61     .05       012756.17      .1       014505.41     .05       0
15544.97     .05       017174.26      .1       0 27240.2      .1       0
Bank Sta=4724.9,5305.4
XS Rating Curve= 0 ,0
Exp/Cntr=0.3,0.1

Type RM Length L Ch R = 1 ,377749  ,1142,1142,1142
BEGIN DESCRIPTION:
PEDERNALES RIVER 171.0
END DESCRIPTION:
XS GIS Cut Line= 4
      2812732.11     10072647.22      2815941.29     10054076.34
      2815752.91      10047237.7      2817075.75     10033398.34
#Sta/Elev= 30
  -15836 1644.85-15236.1 1634.79-14926.1 1605.09-14086.3 1610.42-13596.4 1638.83
-12906.6 1616.95-12646.6 1637.39-11876.8 1651.21-10067.1 1612.74-8097.61 1669.65
-7097.81 1651.99-5288.17 1564.15-4168.38 1536.57-2188.77 1532.28  280.75 1501.15
870.6309 1521.47 1570.49  1495.4 3060.15 1509.67 4608.18 1457.45 5017.66 1425.52
5377.211 1456.4211360.68 1503.39 16697.7 1617.5817327.41 1588.3618057.13 1577.63
19976.38 1674.8421655.72 1700.8722515.39 1687.8723415.04 1760.65 23754.9 1758.29
#Mann= 20 ,-1 , 0
  -15837     .05       0-15426.1      .1       0-14037.7      .1       0
 -7429.9      .1       0 -1828.2     .05       0     927     .05       0
  1898.1      .1       0  3104.5      .1       0  3629.5     .05       0
 4608.18     .07       05377.211      .1       0  6198.3     .05       0
  7220.3      .1       0  8398.7      .1       0 10584.3      .1       0
 12382.4      .1       0 13014.3     .05       0 16229.1      .1       0
 17222.8     .05       0 18456.2      .1       0
Bank Sta=4608.18,5377.211
XS Rating Curve= 0 ,0
Exp/Cntr=0.3,0.1

Type RM Length L Ch R = 1 ,376607  ,2218,2218,2218
BEGIN DESCRIPTION:
PEDERNALES RIVER 175.0
END DESCRIPTION:
XS GIS Cut Line= 2
      2816096.61     10072954.17      2817833.24     10033538.01
#Sta/Elev= 30
  -15762  1726.3  -15692 1725.77-14622.1 1681.45-14112.2 1720.31-13442.2 1765.37
-12772.3  1766.8-10742.6 1659.69-10052.6 1682.15-7432.96 1622.27-6843.03 1583.25
-6313.09 1592.09-5763.15 1605.05-4773.27    1566-2383.54 1508.75-1093.69  1515.6
 2915.67 1494.35    4622 1458.95 4985.26 1423.96 5485.16 1458.38  6212.9 1463.14
 10414.2 1512.8612433.81 1498.5114973.31 1552.68 16063.1 1567.3717912.91 1558.15
18892.91 1583.9319832.91 1620.0721062.91 1657.3622032.91 1635.6723692.91 1716.69
#Mann= 16 ,-1 , 0
  -15762     .16       0  -15692     .16       0-14112.2      .1       0
-10742.6     .16       0-10052.6      .1       0-6313.09      .1       0
-4773.27     .05       0-2383.54      .1       0-1093.69      .1       0
    4622     .07       0  6212.9      .1       014973.31      .1       0
 16063.1      .1       017912.91      .1       018892.91      .1       0
19832.91      .1       0
Bank Sta=4622,6212.9
XS Rating Curve= 0 ,0
Exp/Cntr=0.3,0.1

Type RM Length L Ch R = 1 ,374389  ,2360,2360,2360
BEGIN DESCRIPTION:
PEDERNALES RIVER 177.0
END DESCRIPTION:
XS GIS Cut Line= 3
      2817292.23     10072676.26      2819738.83      10043279.4
      2826480.51     10031645.27
#Sta/Elev= 30
  -15578 1723.23  -14608 1736.42  -14248 1783.55  -13968 1862.85  -13748 1877.31
-13218.1  1751.1-12418.1 1696.16-10238.2 1731.01 -7578.4 1589.75-4748.55 1525.47
371.1797 1490.71 3191.15  1479.7  4624.9 1455.63 4981.15 1423.29  5299.2 1450.76
 6131.15 1464.1110311.15 1478.9312541.15 1513.1413101.15 1497.4313561.15 1517.89
17200.51 1547.3218340.06 1551.2720059.39 1611.8221338.89 1594.3622248.54 1654.64
23667.98 1639.5824727.57 1697.2326027.06 1665.3526976.69 1728.3127366.54  1730.2
#Mann= 12 ,-1 , 0
  -15578      .1       0 -7578.4     .05       0371.1797      .1       0
 3191.15      .1       0  4624.9     .07       0  5299.2      .1       0
 6131.15      .1       013561.15      .1       013561.15     .05       0
17200.51     .05       017200.51      .1       027366.54      .1       0
Bank Sta=4624.9,5299.2
XS Rating Curve= 0 ,0
Exp/Cntr=0.3,0.1

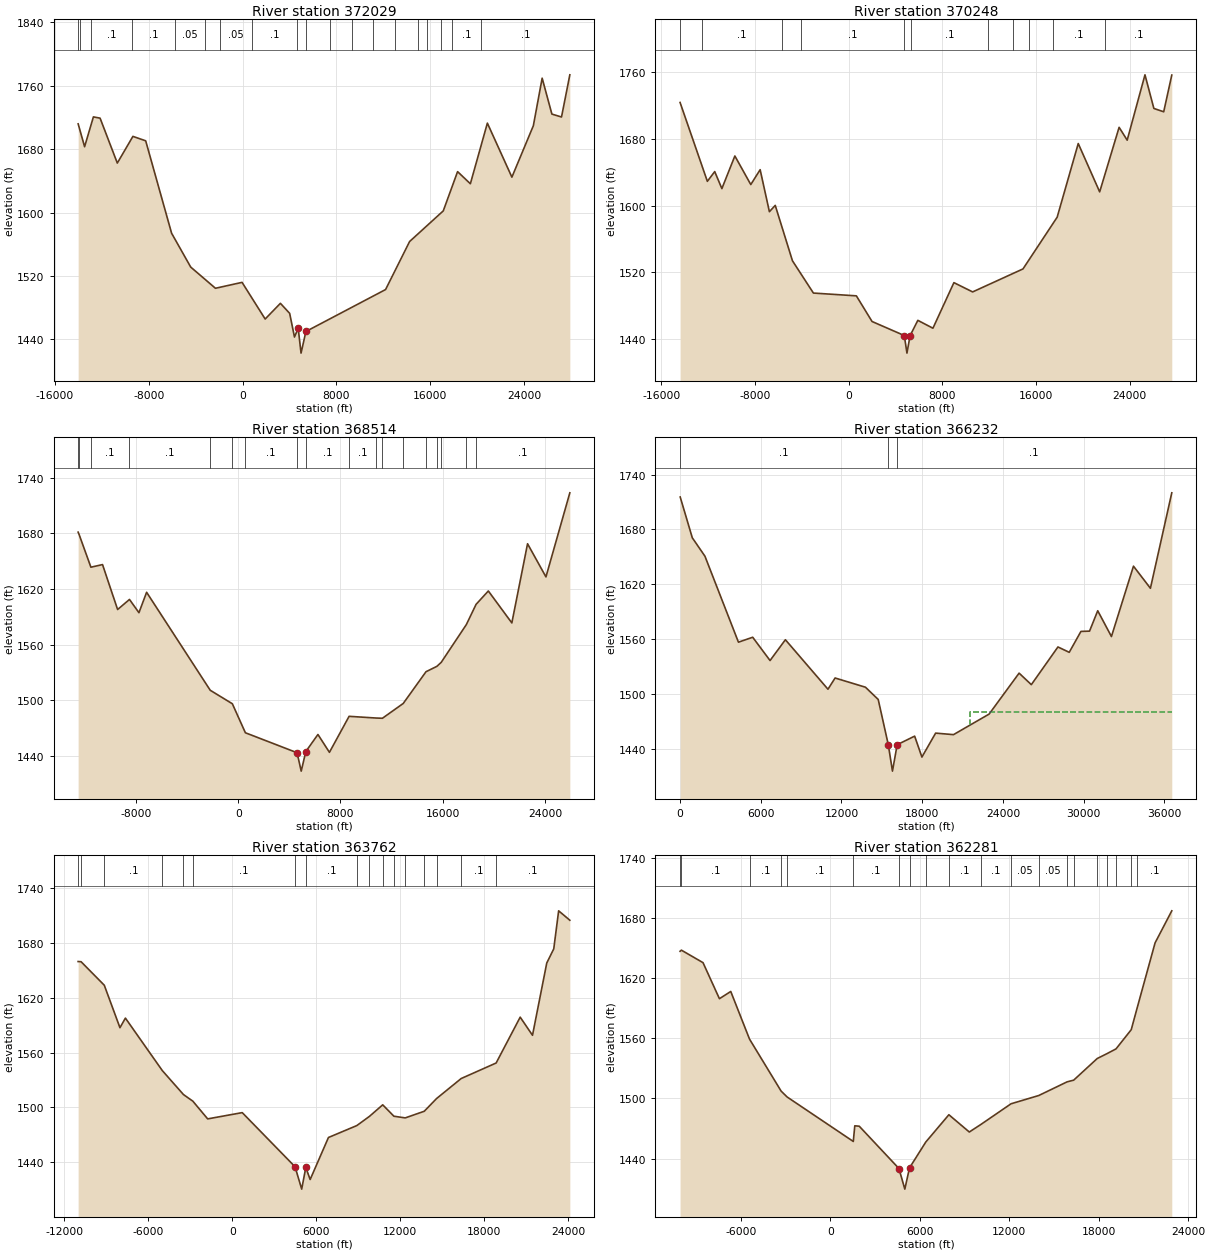
Type RM Length L Ch R = 1 ,372029  ,1781,1781,1781
BEGIN DESCRIPTION:
PEDERNALES RIVER 179.0
END DESCRIPTION:
XS GIS Cut Line= 4
      2817959.75      10072809.1      2820180.08      10055257.2
      2822256.75      10045082.1      2827177.43     10032148.46
#Sta/Elev= 30
  -14018 1711.97-13468.2 1683.13-12718.6 1720.75-12148.8 1719.19-10679.5 1662.51
-9350.16 1696.18-8260.66  1690.6-6051.68 1574.03-4422.45 1531.35-2313.46 1504.61
-44.5498 1512.06 1924.51 1465.823223.961 1485.624013.631 1472.964423.439 1443.11
  4739.8 1454.26 4983.18 1422.81  5399.6 1450.11 12189.8 1502.99 14238.9 1563.58
17108.37 1602.2318328.15 1651.7219418.07 1636.4320868.07 1712.8922958.07 1644.76
24788.07 1709.6325538.07 1769.6226368.07  1724.327188.07 1720.6227898.07 1773.82
#Mann= 19 ,-1 , 0
-14020.6     .16       0-13881.5      .1       0-12890.3      .1       0
 -9451.6      .1       0 -5736.9     .05       0   -3199      .1       0
 -1917.2     .05       0   767.9      .1       0  4638.7     .07       0
  5379.1      .1       0  7445.6     .05       0  9337.8      .1       0
 11083.3     .05       0 13008.5      .1       0 14970.1     .05       0
   15745      .1       0 16897.5     .05       0 17847.2      .1       0
 20307.1      .1       0
Bank Sta=4739.8,5399.6
XS Rating Curve= 0 ,0
Exp/Cntr=0.3,0.1

Type RM Length L Ch R = 1 ,370248  ,1734,1734,1734
BEGIN DESCRIPTION:
PEDERNALES RIVER 182.0
END DESCRIPTION:
XS GIS Cut Line= 4
      2819657.08     10073550.56      2821379.34     10056806.47
       2824536.4     10047024.31      2827859.34      10032523.6
#Sta/Elev= 30
  -14394 1723.63  -12065 1629.04-11435.3 1640.75-10825.6 1620.31 -9716.1 1659.47
-8356.73 1625.19-7557.09 1643.04-6767.46 1592.63-6267.68 1600.19-4798.33 1533.75
-3009.11 1495.04659.2803  1491.71998.689 1460.93  4751.6 1444.09 4978.33    1423
  5245.4 1443.88 5908.26 1462.31 7198.17 1452.888988.039 1507.5410587.92 1496.42
14887.34 1523.9917806.77 1586.0619606.18  1674.421435.46  1616.423094.81 1693.83
23784.54 1678.4525303.95  1756.826063.65 1716.4726903.32 1712.4627593.05  1756.5
#Mann= 11 ,-1 , 0
-14395.4      .1       0  -12537      .1       0   -5679      .1       0
 -4104.4      .1       0  4751.6     .07       0  5314.7      .1       0
 11886.5      .1       0 14040.2     .05       0 15376.3      .1       0
 17430.7      .1       0 21884.7      .1       0
Bank Sta=4751.6,5245.4
XS Rating Curve= 0 ,0
Exp/Cntr=0.3,0.1

Type RM Length L Ch R = 1 ,368514  ,2282,2282,2282
BEGIN DESCRIPTION:
PEDERNALES RIVER 183.0
END DESCRIPTION:
XS GIS Cut Line= 4
      2820931.04     10072473.22      2822942.77     10056915.43
      2826031.04     10049226.76      2828201.57     10034887.24
#Sta/Elev= 30
  -12530 1681.26  -12460    1679-11530.1 1643.45-10620.3 1646.27-9440.52  1597.8
-8510.67 1608.66 -7770.8 1594.38-7170.91 1616.39-2191.77 1510.69-462.049 1496.15
557.7803 1464.86  4603.2 1443.31  4926.4 1423.47 5288.87 1444.64 6235.66    1463
7135.141 1443.75 8674.27 1482.5910803.05 1480.7311282.78  1480.512912.12 1496.49
14691.42  1530.715541.09 1536.4815880.96 1540.7817850.19 1581.5718609.89 1603.37
19569.51  1617.8 21408.8 1583.3322638.32 1668.7424077.75    163325947.02 1723.68
#Mann= 18 ,-1 , 0
  -12530      .1       0  -12460      .1       0-11530.1      .1       0
-8510.67      .1       0-2191.77     .05       0-462.049     .05       0
557.7803      .1       0  4603.2     .07       0 5288.87      .1       0
 8674.27      .1       010803.05     .16       011282.78      .1       0
12912.12     .05       014691.42      .1       015541.09     .05       0
15880.96      .1       017850.19     .16       018609.89      .1       0
Bank Sta=4603.2,5288.87
XS Rating Curve= 0 ,0
Exp/Cntr=0.3,0.1

Type RM Length L Ch R = 1 ,366232  ,2470,2470,2470
XS GIS Cut Line= 6
     2823002.312    10071624.522     2823696.757    10063707.855
     2825363.423      10058152.3     2825814.812    10050860.633
     2827379.283    10045156.833     2828693.718    10035814.626
#Sta/Elev= 30
9.9998461715.512909.98591670.8781849.9711650.7224339.9331556.6675399.9171562.065
6689.8961536.5867829.8791559.35710995.681505.195 11524.91517.47613781.561507.409
14731.09 1493.9915480.751444.48115790.61 1415.5916140.451444.49417439.871453.871
17979.621430.97618999.16 1457.1820328.56 1455.5122977.01 1478.0125205.541522.797
26114.931510.19728093.461551.44228932.771545.56829802.061568.44530441.541568.755
31051.041591.06332070.211562.84133708.871639.83334967.841615.64636556.541720.079
#Mann= 3 ,-1 , 0
       0      .1       015440.77     .05       016090.48      .1       0
#XS Ineff= 2 , 0
                        21590.91         1480.16
Permanent Ineff=
       F       F
Bank Sta=15480.75,16140.45
XS Rating Curve= 0 ,0
Exp/Cntr=0.3,0.1

Type RM Length L Ch R = 1 ,363762  ,1481,1481,1481
BEGIN DESCRIPTION:
PEDERNALES RIVER 185.0
END DESCRIPTION:
XS GIS Cut Line= 4
       2826509.8     10070763.35      2827973.74     10057434.22
      2827105.52     10052974.65      2829645.04      10035968.7
#Sta/Elev= 30
  -11017 1659.47  -10807 1659.28 -9147.1 1633.58-8027.15 1587.17-7637.17 1597.66
 -4997.3 1540.27-3487.38 1514.12-2817.41 1506.91-1757.48 1487.54712.3496 1494.39
  4488.1 1435.24  4962.8  1410.8    5257 1434.44 5567.57 1421.28 6875.59 1467.21
 8904.75 1480.25 9804.41 1490.2810754.04 1502.9111553.74 1490.4612363.43 1488.62
13722.91 1495.8814602.58 1509.7516361.91 1531.6418860.95  1548.6 20580.3 1598.69
21459.96 1578.8922479.57 1657.8622979.38 1673.3123329.24 1714.8724128.93  1704.6
#Mann= 17 ,-1 , 0
  -11017      .1       0  -10807      .1       0 -9147.1      .1       0
 -4997.3      .1       0-3487.38     .05       0-2817.41      .1       0
  4488.1     .07       0    5257      .1       0 8904.75      .1       0
 9804.41      .1       010754.04     .05       011553.74      .1       0
12363.43     .05       013722.91     .05       014602.58     .05       0
16361.91      .1       018860.95      .1       0
Bank Sta=4488.1,5257
XS Rating Curve= 0 ,0
Exp/Cntr=0.3,0.1

Type RM Length L Ch R = 1 ,362281  ,1580,1580,1580
BEGIN DESCRIPTION:
PEDERNALES RIVER 195.0
END DESCRIPTION:
XS GIS Cut Line= 4
       2828373.3     10069212.63      2829016.97     10056416.02
      2828368.38     10051742.08      2830128.02     10036408.63
#Sta/Elev= 30
  -10071 1646.63-9981.05 1647.75-8531.87 1635.29-7432.49 1599.38-6672.93 1606.59
-5413.64 1559.07-3294.85 1507.28-2895.07 1501.45 1542.34 1457.12 1642.29  1472.7
 1942.11 1472.31  4601.1 1430.17  4603.7 1430.14  4997.2 1409.61  5310.4 1430.77
 6400.58 1456.51 7950.18 1483.749319.641 1466.5310119.33 1474.2912118.55 1494.67
13977.82 1502.9115877.08 1516.5216316.91  1518.217896.29 1539.7718566.03 1544.75
 19155.8 1549.36 20175.4 1568.4720575.25 1590.3221774.78 1655.0222894.34 1686.95
#Mann= 20 ,-1 , 0
  -10071      .1       0-9981.05      .1       0-5413.64      .1       0
-3294.85      .1       0-2895.07      .1       0 1542.34      .1       0
  4601.1     .07       0  5310.4      .1       0 6400.58      .1       0
 7950.18      .1       010119.33      .1       012118.55     .05       0
13977.82     .05       015877.08     .16       016316.91      .1       0
17896.29      .1       018566.03     .16       0 19155.8      .1       0
 20175.4     .16       020575.25      .1       0
Bank Sta=4603.7,5310.4
XS Rating Curve= 0 ,0
Exp/Cntr=0.3,0.1

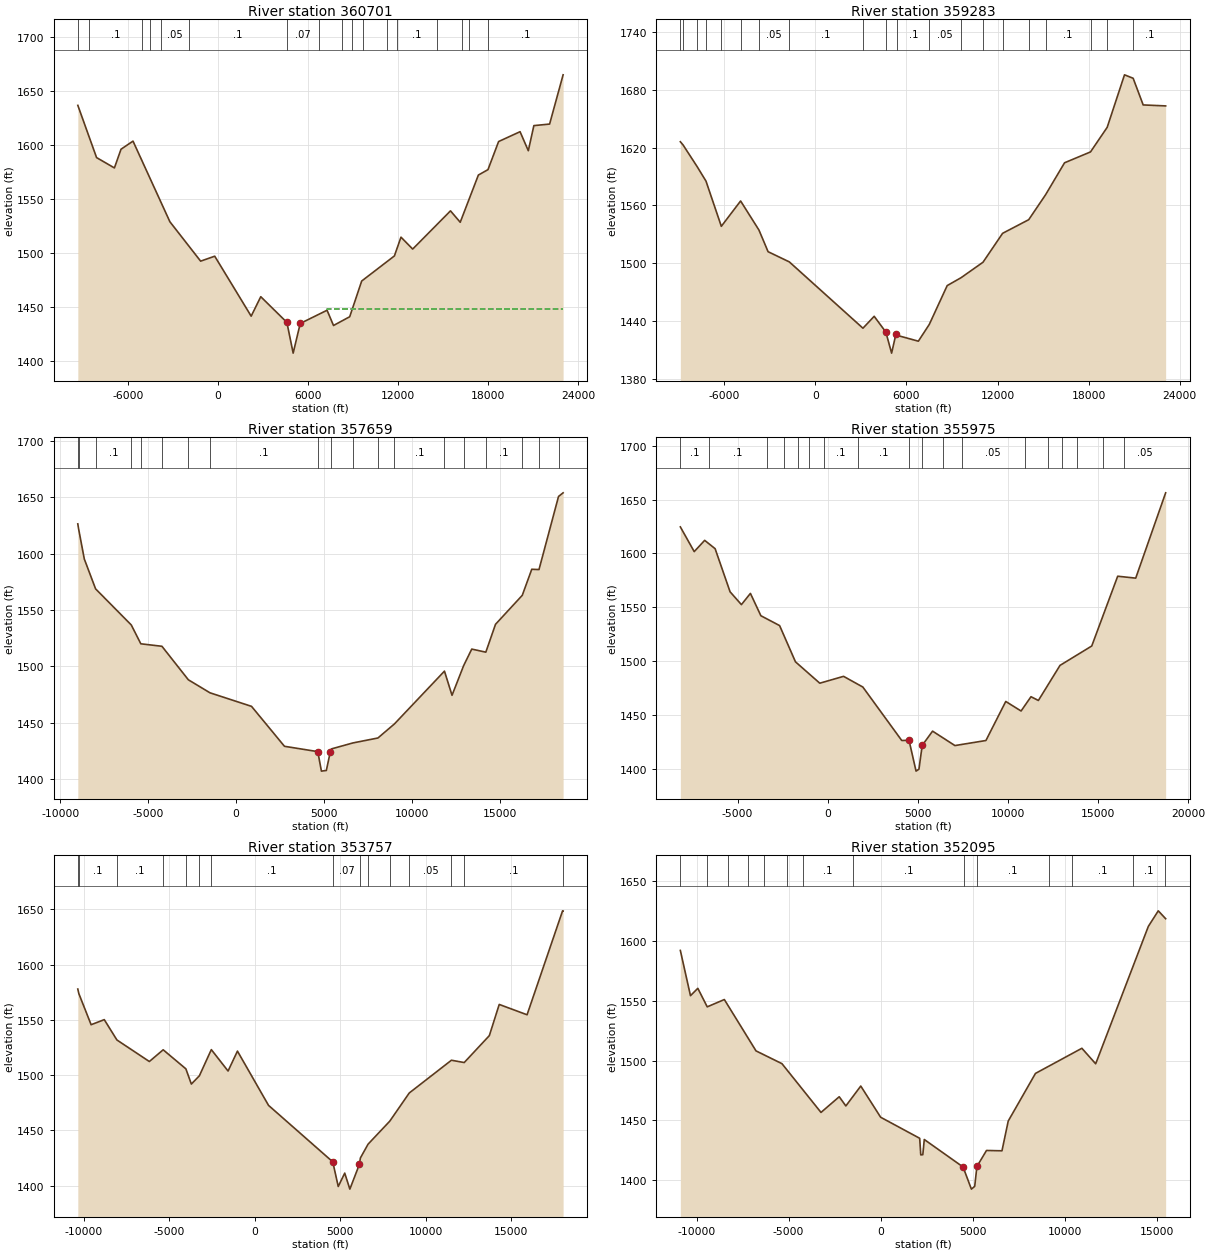
Type RM Length L Ch R = 1 ,360701  ,1418,1418,1418
BEGIN DESCRIPTION:
PEDERNALES RIVER 197.0
END DESCRIPTION:
XS GIS Cut Line= 3
      2829409.28     10068791.11        2830219.     10055725.28
      2830652.37     10036480.06
#Sta/Elev= 30
   -9324 1637.02-8074.87 1588.55-6885.69 1578.95   -6446 1596.31-5646.55 1603.83
-3188.28    1529-1139.72 1492.44 -200.36 1497.04 2227.98  1441.4 2867.54 1459.45
  4607.1 1435.64  5026.9 1407.09  5497.3 1434.61 7285.18 1446.88 7714.93 1432.73
8794.301 1440.86 9593.83    147411772.55 1497.2812212.29 1514.7212991.84 1503.65
15510.36 1539.1116159.98 1528.5317369.27 1572.34 18008.9 1577.3618718.48 1603.44
20147.64 1612.5820697.32 1594.91 21067.1 1618.2122116.49 1619.6623015.96 1665.35
#Mann= 17 ,-1 , 0
 -9325.6      .1       0 -8562.6      .1       0 -5023.5     .16       0
   -4520      .1       0   -3788     .05       0 -1902.7      .1       0
  4607.1     .07       0  6775.7      .1       0  8271.5     .16       0
  8945.1     .05       0  9674.9      .1       0 11304.1     .05       0
 11923.9      .1       0 14626.6      .1       0   16310      .1       0
 16771.4      .1       0   18031      .1       0
#XS Ineff= 2 , 0
                         7281.25         1447.68
Permanent Ineff=
       F       F
Bank Sta=4607.1,5497.3
XS Rating Curve= 0 ,0
Exp/Cntr=0.3,0.1

Type RM Length L Ch R = 1 ,359283  ,1624,1624,1624
BEGIN DESCRIPTION:
PEDERNALES RIVER 198.0
END DESCRIPTION:
XS GIS Cut Line= 2
      2830838.18     10068359.27      2832736.19     10036453.37
#Sta/Elev= 30
   -8894 1626.01-8714.04 1622.68-7794.26 1600.35-7204.41 1585.13-6194.66 1538.22
-4924.97 1564.53-3715.26 1534.31-3115.41 1511.86-1715.76 1501.27 3133.23 1432.42
 3873.08 1444.79  4640.5 1428.43  5020.9 1406.56  5301.7 1426.05 5402.78 1424.93
 6782.51 1418.957502.359 1436.358682.131 1476.679591.961 1484.8211041.67 1500.94
12331.42 1530.9414051.08 1545.0915160.87 1570.9516410.62 1604.1618120.29 1615.44
19220.07 1640.9820359.85 1695.4820929.74 1691.8921589.61 1664.2223069.32 1663.21
#Mann= 20 ,-1 , 0
   -8894      .1       0-8714.04      .1       0-7794.26      .1       0
-7204.41     .16       0-6194.66      .1       0-4924.97     .16       0
-3715.26     .05       0-1715.76      .1       0 3133.23      .1       0
  4640.5     .07       0 5402.78      .1       07502.359     .05       0
9591.961      .1       011041.67     .05       012331.42      .1       0
14051.08     .16       015160.87      .1       018120.29      .1       0
19220.07      .1       020929.74      .1       0
Bank Sta=4640.5,5301.7
XS Rating Curve= 0 ,0
Exp/Cntr=0.3,0.1

Type RM Length L Ch R = 1 ,357659  ,1684,1684,1684
BEGIN DESCRIPTION:
PEDERNALES RIVER 202.0
END DESCRIPTION:
XS GIS Cut Line= 2
      2832084.25     10068686.92      2834362.54     10041213.02
#Sta/Elev= 30
   -8994 1626.28   -8954 1622.29-8624.02 1595.12-7984.07  1568.7 -5954.2 1536.64
-5414.24 1519.98-4214.31 1517.78 -2714.4 1488.09-1484.48 1476.54875.3203 1464.53
 2745.14 1429.14  4639.4  1424.4 4844.93 1407.12  5124.9  1407.7  5351.8 1424.38
 5414.88 1426.82 6634.76 1432.11 8054.68 1436.49 8994.68 1448.9811834.68 1495.76
12264.68 1474.3412924.68 1500.6413384.68  1515.314184.68 1512.5714734.68 1537.26
16254.68 1562.9516794.68 1586.0517204.68 1585.7918314.68 1650.5818574.68 1653.81
#Mann= 19 ,-1 , 0
   -8994      .1       0   -8954      .1       0-7984.07      .1       0
 -5954.2     .05       0-5414.24      .1       0-4214.31     .05       0
 -2714.4      .1       0-1484.48      .1       0  4639.4     .07       0
 5414.88      .1       0 6634.76      .1       0 8054.68     .05       0
 8994.68      .1       011834.68     .16       012924.68      .1       0
14184.68      .1       016254.68      .1       017204.68      .1       0
18314.68      .1       0
Bank Sta=4639.4,5351.8
XS Rating Curve= 0 ,0
Exp/Cntr=0.3,0.1

Type RM Length L Ch R = 1 ,355975  ,2218,2218,2218
BEGIN DESCRIPTION:
PEDERNALES RIVER 204.0
END DESCRIPTION:
XS GIS Cut Line= 3
      2833517.66     10068394.58      2834704.87     10056693.43
      2835878.53     10041581.77
#Sta/Elev= 30
   -8174 1624.65-7404.58 1601.68-6825.01 1612.15-6245.45  1604.4-5416.07 1564.34
-4786.54  1552.4-4286.91 1562.84-3707.34 1542.08-2668.12 1532.92-1788.78 1499.24
 -439.79 1479.37879.1904 1485.74 1948.35 1475.81 4106.97  1426.1  4509.3 1426.31
  4900.2 1397.64    5061  1399.5  5241.5  1421.6 5816.64  1434.8 7056.39  1421.4
8776.061  1426.1 9875.84 1462.3910725.68 1453.5311275.57 1466.8211685.49 1463.31
12885.26 1495.9214644.91 1513.9416084.63 1578.8117084.44 1577.0218744.11 1656.32
#Mann= 18 ,-1 , 0
 -8174.4      .1       0 -6568.4      .1       0 -3368.7      .1       0
 -2448.9     .05       0 -1620.6      .1       0 -1028.8     .05       0
  -192.2      .1       0  1655.7      .1       0  4509.3     .07       0
  5241.5      .1       0  6386.1      .1       0  7426.3     .05       0
 10927.8     .05       0 12244.4      .1       0 12996.2     .05       0
   13838      .1       0 15280.1      .1       0 16459.8     .05       0
Bank Sta=4509.3,5241.5
XS Rating Curve= 0 ,0
Exp/Cntr=0.3,0.1

Type RM Length L Ch R = 1 ,353757  ,1662,1662,1662
BEGIN DESCRIPTION:
PEDERNALES RIVER 208.0
END DESCRIPTION:
XS GIS Cut Line= 3
      2835258.77     10069955.71      2836903.99     10056775.16
      2837032.78     10041650.74
#Sta/Elev= 30
  -10354 1577.84  -10294 1573.75-9574.42 1545.59-8804.83 1550.18-8065.23 1531.81
-6166.24 1512.32-5356.67 1522.92-4027.38 1505.69-3707.54 1491.93-3237.79 1499.43
-2538.17 1523.09-1558.71 1503.71-1009.03 1521.73809.9297 1472.68  4570.5  1421.6
  4890.5 1399.34  5270.5 1411.43  5570.3 1396.956127.699 1419.27 6187.68 1425.12
  6637.5 1437.61 7907.01 1458.399046.561 1483.86 11515.6 1513.48 12265.3 1511.39
13734.73 1535.73 14314.5 1563.9315943.87 1554.5818023.05 1648.5618053.04 1648.42
#Mann= 15 ,-1 , 0
  -10354      .1       0  -10294      .1       0-8065.23      .1       0
-5356.67      .1       0-4027.38      .1       0-3237.79      .1       0
-2538.17      .1       0  4570.5     .07       0 6187.68     .16       0
  6637.5      .1       0 7907.01      .1       09046.561     .05       0
 11515.6      .1       0 12265.3      .1       018023.05     .05       0
Bank Sta=4570.5,6127.699
XS Rating Curve= 0 ,0
Exp/Cntr=0.3,0.1

Type RM Length L Ch R = 1 ,352095  ,1902,1902,1902
BEGIN DESCRIPTION:
PEDERNALES RIVER 210.0
END DESCRIPTION:
XS GIS Cut Line= 2
      2837787.14     10070096.44      2838987.24     10043764.67
#Sta/Elev= 30
  -10881  1592.2  -10331 1554.36-9931.03 1560.51-9421.05 1545.02-8491.08 1551.14
-6771.14 1508.18-5361.18 1497.48-3241.23  1456.7-2251.25 1469.81-1891.25 1462.12
-1081.25 1478.77   -1.25 1452.66 2118.75 1435.06 2178.75 1421.17 2288.75 1421.33
 2368.75 1434.04  4487.2 1410.93  4537.3 1408.51  4927.4 1392.53  5107.9 1394.85
    5228 1411.47 5748.75 1424.87 6588.75 1424.59 6928.75  1449.5 8408.75 1489.34
10928.75 1510.3611678.75 1497.3614538.75 1612.3215078.75 1625.3515478.75 1618.77
#Mann= 14 ,-1 , 0
-10881.4      .1       0 -9436.1      .1       0 -8307.3      .1       0
 -7221.9     .05       0   -6311      .1       0   -5106     .05       0
 -4240.2      .1       0 -1516.7      .1       0  4537.3     .07       0
    5238      .1       0  9135.7     .05       0   10376      .1       0
 13707.2      .1       0 15422.7     .16       0
Bank Sta=4487.2,5228
XS Rating Curve= 0 ,0
Exp/Cntr=0.3,0.1

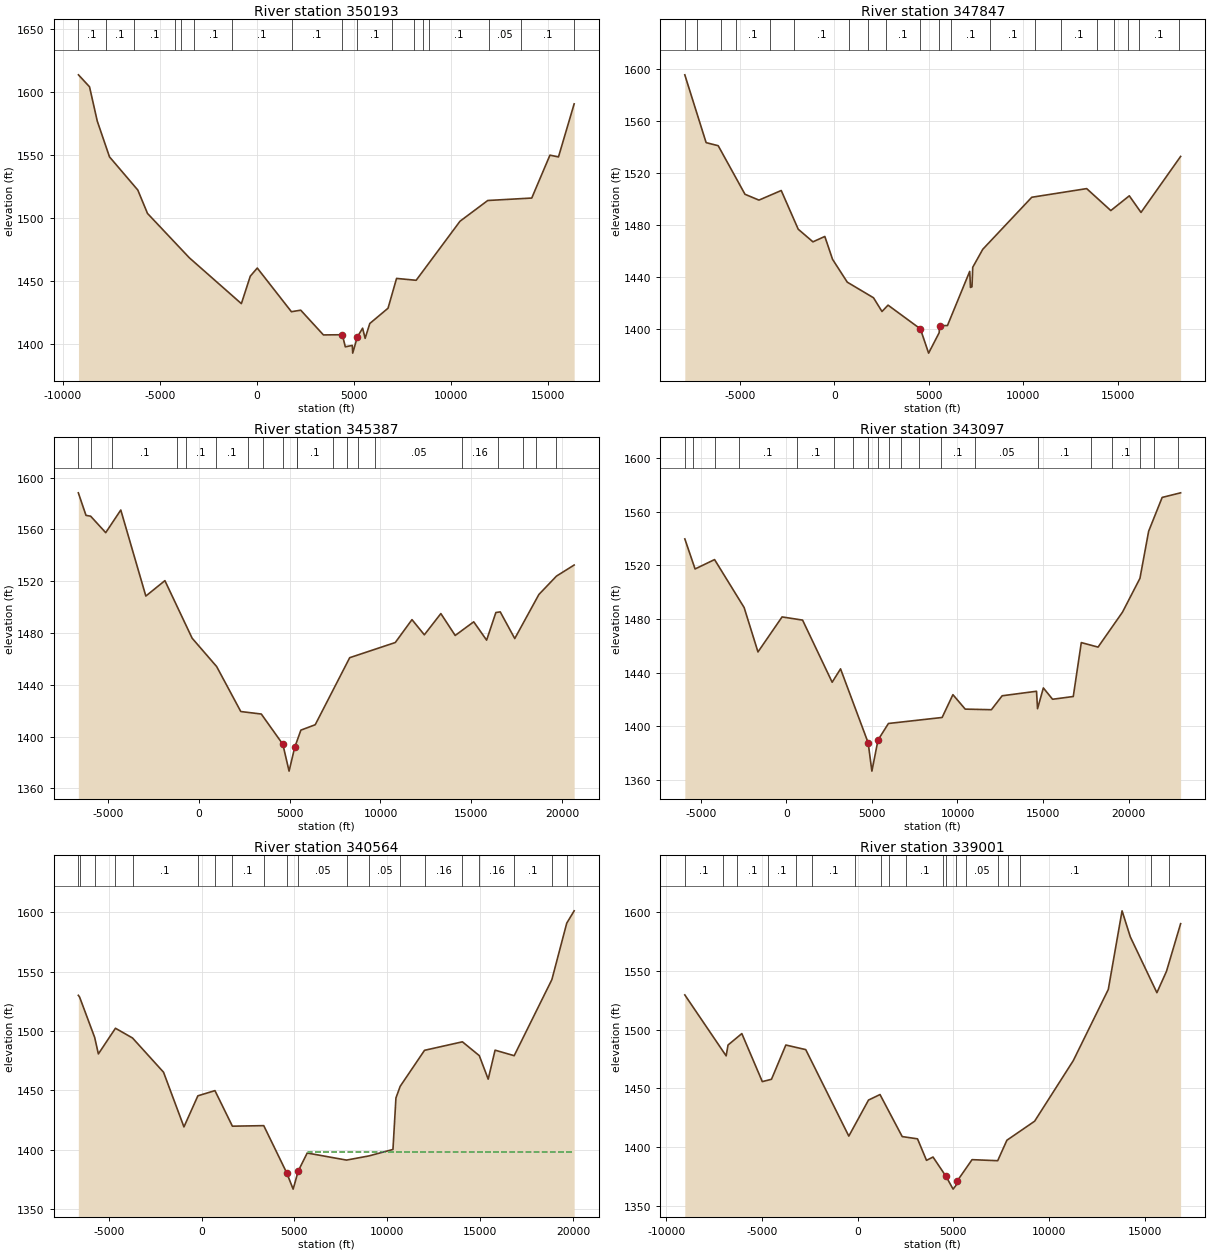
Type RM Length L Ch R = 1 ,350193  ,2346,2346,2346
BEGIN DESCRIPTION:
PEDERNALES RIVER 212.0
END DESCRIPTION:
XS GIS Cut Line= 4
      2839402.01     10068466.09      2840093.69     10056813.93
      2841262.29     10046652.52      2840370.16     10043121.44
#Sta/Elev= 30
   -9201 1613.89-8631.36 1604.37-8231.61 1577.08-7602.01 1548.66-6142.93 1522.26
-5643.25 1503.65-3484.59 1468.34-806.259 1431.92-346.559 1453.7813.20996 1460.24
 1772.05  1425.5 2251.74 1426.73 3421.41 1407.05  4397.7 1407.19  4548.7 1397.59
  4909.9 1398.69    4931 1392.57    5172 1405.51 5441.02  1412.4 5570.99 1404.31
 5810.94 1416.12 6750.76 1428.28 7190.67 1451.98 8200.48  1450.510460.04 1497.46
11889.76 1513.9514156.46  1515.915094.44 1550.02 15533.5 1548.5916341.76 1590.79
#Mann= 17 ,-1 , 0
 -9207.8      .1       0 -7794.2      .1       0 -6335.1      .1       0
 -4244.9      .1       0 -3921.8     .05       0 -3229.7      .1       0
 -1272.3      .1       0    1793      .1       0  4377.6     .07       0
    5172      .1       0  6978.2     .16       0  8102.6      .1       0
  8533.5     .05       0  8854.2      .1       0 11975.6     .05       0
 13590.1      .1       0 16330.9      .1       0
Bank Sta=4397.7,5172
XS Rating Curve= 0 ,0
Exp/Cntr=0.3,0.1

Type RM Length L Ch R = 1 ,347847  ,2460,2460,2460
BEGIN DESCRIPTION:
PEDERNALES RIVER 214.0
END DESCRIPTION:
XS GIS Cut Line= 4
      2840990.82     10068980.41      2841513.52     10057656.23
      2842807.67     10050741.57      2841417.08     10042969.15
#Sta/Elev= 30
   -7927 1595.26-6797.38 1543.27-6157.59 1540.91-4738.07 1503.67-3998.31  1499.2
-2818.69 1506.56-1918.98 1476.89-1139.23 1467.21 -509.43 1471.33  -99.56 1453.79
680.1699 1436.29 2069.69 1424.32 2519.54  1413.8 2839.42 1418.67    4553 1400.47
  4988.9 1381.88  5547.8 1397.52  5568.2 1402.93 5987.31 1403.03 7166.43 1444.56
  7206.4 1432.24 7286.34 1432.73 7326.31 1447.69 7855.92 1461.4610453.91 1501.39
13362.21 1508.0214641.46 1491.1815620.88  1502.516240.52 1489.7518339.29 1532.69
#Mann= 20 ,-1 , 0
 -7927.4      .1       0 -7289.1      .1       0 -6035.3     .05       0
 -5208.9      .1       0 -3437.9     .05       0 -2141.6      .1       0
   772.3      .1       0  1761.9      .1       0  2716.7      .1       0
    4553     .07       0  5547.8      .1       0  6163.9      .1       0
  8244.7      .1       0   10636     .05       0 11987.7      .1       0
 13890.2     .05       0 14835.4      .1       0 15575.8     .05       0
 16136.8      .1       0 18265.9     .05       0
Bank Sta=4553,5568.2
XS Rating Curve= 0 ,0
Exp/Cntr=0.3,0.1

Type RM Length L Ch R = 1 ,345387  ,2290,2290,2290
BEGIN DESCRIPTION:
PEDERNALES RIVER 218.0
END DESCRIPTION:
XS GIS Cut Line= 3
      2842265.04     10068225.88      2844997.45     10051593.26
      2841237.13     10041844.08
#Sta/Elev= 30
 -6639.7 1588.19 -6217.3 1570.79   -5961 1570.15 -5131.4 1557.45-4301.62 1574.92
-2921.99 1508.52-1872.26 1520.41-372.629 1475.98  977.04 1454.11 2306.67 1419.38
 3436.34 1417.45 4622.76 1394.11  4965.7 1373.38  5275.8 1391.67  5615.7 1405.01
 6405.47 1409.19 8304.91 1460.9410814.38 1472.6411734.36 1490.3212414.35  1478.6
13324.33 1494.9914114.31  1478.115134.29 1488.6315844.27 1474.4816354.26  1495.8
16594.25  1496.317394.23 1475.7318724.21 1509.75 19691.9 1523.92 20665.1 1532.46
#Mann= 20 ,-1 , 0
 -6639.7      .1       0   -5961     .05       0   -4809      .1       0
 -1187.7      .1       0  -700.5      .1       0   935.8      .1       0
  2679.9     .05       0  3509.2      .1       0    4638     .07       0
  5410.4     .05       0  5410.4      .1       0  7369.4      .1       0
  8161.2      .1       0  8735.8     .05       0  9713.1     .05       0
 14475.9     .16       0 16459.3     .05       0 17854.4      .1       0
 18577.3      .1       0 19691.9     .05       0
Bank Sta=4622.76,5275.8
XS Rating Curve= 0 ,0
Exp/Cntr=0.3,0.1

Type RM Length L Ch R = 1 ,343097  ,2533,2533,2533
BEGIN DESCRIPTION:
PEDERNALES RIVER 221.0
END DESCRIPTION:
XS GIS Cut Line= 4
      2843044.93     10068084.66      2845634.17     10060754.77
      2847633.18      10050570.2      2846027.55     10039857.12
#Sta/Elev= 30
   -5940 1539.59-5340.48 1517.21-4201.38 1524.19-2472.75 1488.47-1663.39  1455.4
-254.509 1481.49  944.54 1479.12 2673.76 1432.84 3163.71 1442.81  4778.1 1387.74
    4996 1366.64  5356.3 1389.86 5963.44 1402.12 9103.13  1406.6 9733.07 1423.59
   10453 1412.8211982.76 1412.3812612.49 1422.7614621.32 1426.1214681.28 1413.12
15021.08  1428.615560.77 1420.1616770.06 1422.2217239.78 1462.3718219.21 1459.01
19648.37 1485.0620667.77 1510.2121177.47 1545.3121967.01 1570.4923046.38 1573.91
#Mann= 20 ,-1 , 0
 -5941.9      .1       0 -5491.4      .1       0 -4197.6     .05       0
 -2792.9      .1       0   637.7      .1       0  2800.2      .1       0
  3920.6      .1       0  4778.1     .07       0  5356.3      .1       0
  6017.4      .1       0  6710.3      .1       0  7771.8      .1       0
  9032.4      .1       0 11008.8     .05       0 14723.5      .1       0
   17805      .1       0 19010.6      .1       0 20652.2      .1       0
   21486     .16       0 22912.5     .16       0
Bank Sta=4778.1,5356.3
XS Rating Curve= 0 ,0
Exp/Cntr=0.3,0.1

Type RM Length L Ch R = 1 ,340564  ,1563,1563,1563
BEGIN DESCRIPTION:
PEDERNALES RIVER 225.0
END DESCRIPTION:
XS GIS Cut Line= 3
      2843796.82     10068178.51      2848217.89     10059796.16
      2852624.96     10043143.76
#Sta/Elev= 30
   -6636 1530.14-6566.02 1528.61 -5756.3 1494.68-5556.37 1480.75-4636.68 1502.38
-3716.99 1494.18-2047.56 1465.35-947.939 1419.24  -198.2 1445.43  721.48 1449.82
 1661.16 1419.85 3350.61  1420.3  4593.4 1380.29  4932.6  1366.8  5209.3 1382.17
 5689.99 1397.23 7809.43 1391.27 9019.11  1394.810308.81 1400.2410468.78 1443.65
10698.73 1453.4812008.47 1483.7914048.08 1490.95 14957.9  1479.3 15437.8 1459.49
15807.73 1483.9116837.53 1479.2618867.13 1543.3919666.98 1590.94 20066.9 1601.35
#Mann= 20 ,-1 , 0
   -6636      .1       0-6566.02      .1       0 -5756.3      .1       0
-4636.68     .05       0-3716.99      .1       0  -198.2     .05       0
  721.48      .1       0 1661.16      .1       0 3350.61     .05       0
  4593.4     .07       0  5209.3     .05       0 7809.43     .05       0
 9019.11     .05       010698.73      .1       012008.47     .16       0
14048.08     .05       0 14957.9     .16       016837.53      .1       0
18867.13      .1       019666.98      .1       0
#XS Ineff= 2 , 0
                         5759.11         1397.89
Permanent Ineff=
       F       F
Bank Sta=4593.4,5209.3
XS Rating Curve= 0 ,0
Exp/Cntr=0.3,0.1

Type RM Length L Ch R = 1 ,339001  ,2618,2618,2618
BEGIN DESCRIPTION:
PEDERNALES RIVER 234.0
END DESCRIPTION:
XS GIS Cut Line= 3
      2843504.49     10070971.85      2850928.73     10056912.15
      2854406.52     10047528.08
#Sta/Elev= 30
   -9024 1529.41-6864.06 1477.66-6764.06 1486.86-6044.09 1496.57-4974.12 1455.79
-4494.14 1457.77-3744.16 1486.85 -2704.2 1482.95-454.259 1409.53575.7402 1440.13
 1175.74 1444.81 2335.74 1409.13 3135.74 1407.21 3605.74 1388.95 3945.74 1391.76
  4616.4 1375.57  4995.5 1364.52  5165.9  1368.1  5199.9  1371.2 5985.74 1389.54
 7325.65 1388.657805.561 1406.019255.279 1422.1811274.88  1473.613104.53 1534.02
13824.38 1600.77 14254.3 1578.6915644.03 1531.2816143.93 1549.3716883.79 1589.86
#Mann= 20 ,-1 , 0
 -9024.2      .1       0 -7020.5      .1       0 -6320.3      .1       0
   -4670      .1       0 -3211.9      .1       0 -2398.6      .1       0
  -119.6      .1       0  1218.9     .05       0  1664.8     .05       0
  2545.1      .1       0  4453.5      .1       0  4616.4     .07       0
  5165.9     .05       0  5645.6     .05       0  7348.6      .1       0
  7880.4      .1       0  8512.4      .1       0 14147.6      .1       0
 15357.8     .16       0 16274.5      .1       0
Bank Sta=4616.4,5199.9
XS Rating Curve= 0 ,0
Exp/Cntr=0.3,0.1