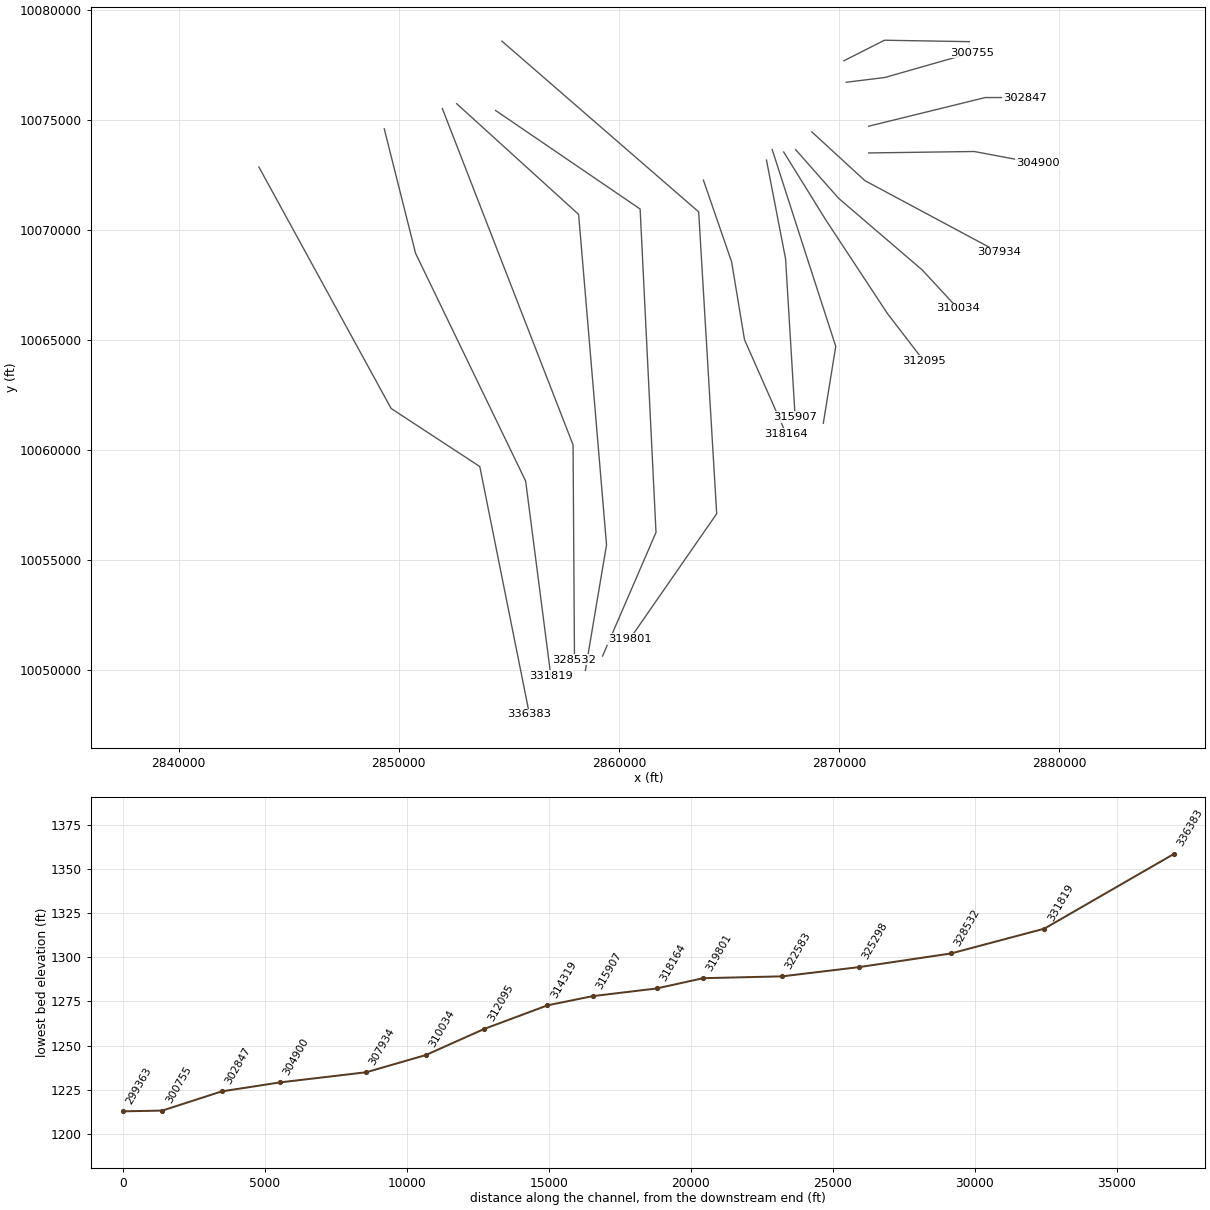
HEC-RAS study PEDERNALES RIVER.prj: PEDERNALES RIVER Base Level Engineering

--- PEDERNALES RIVER.g01 (geometry) --- (continued)

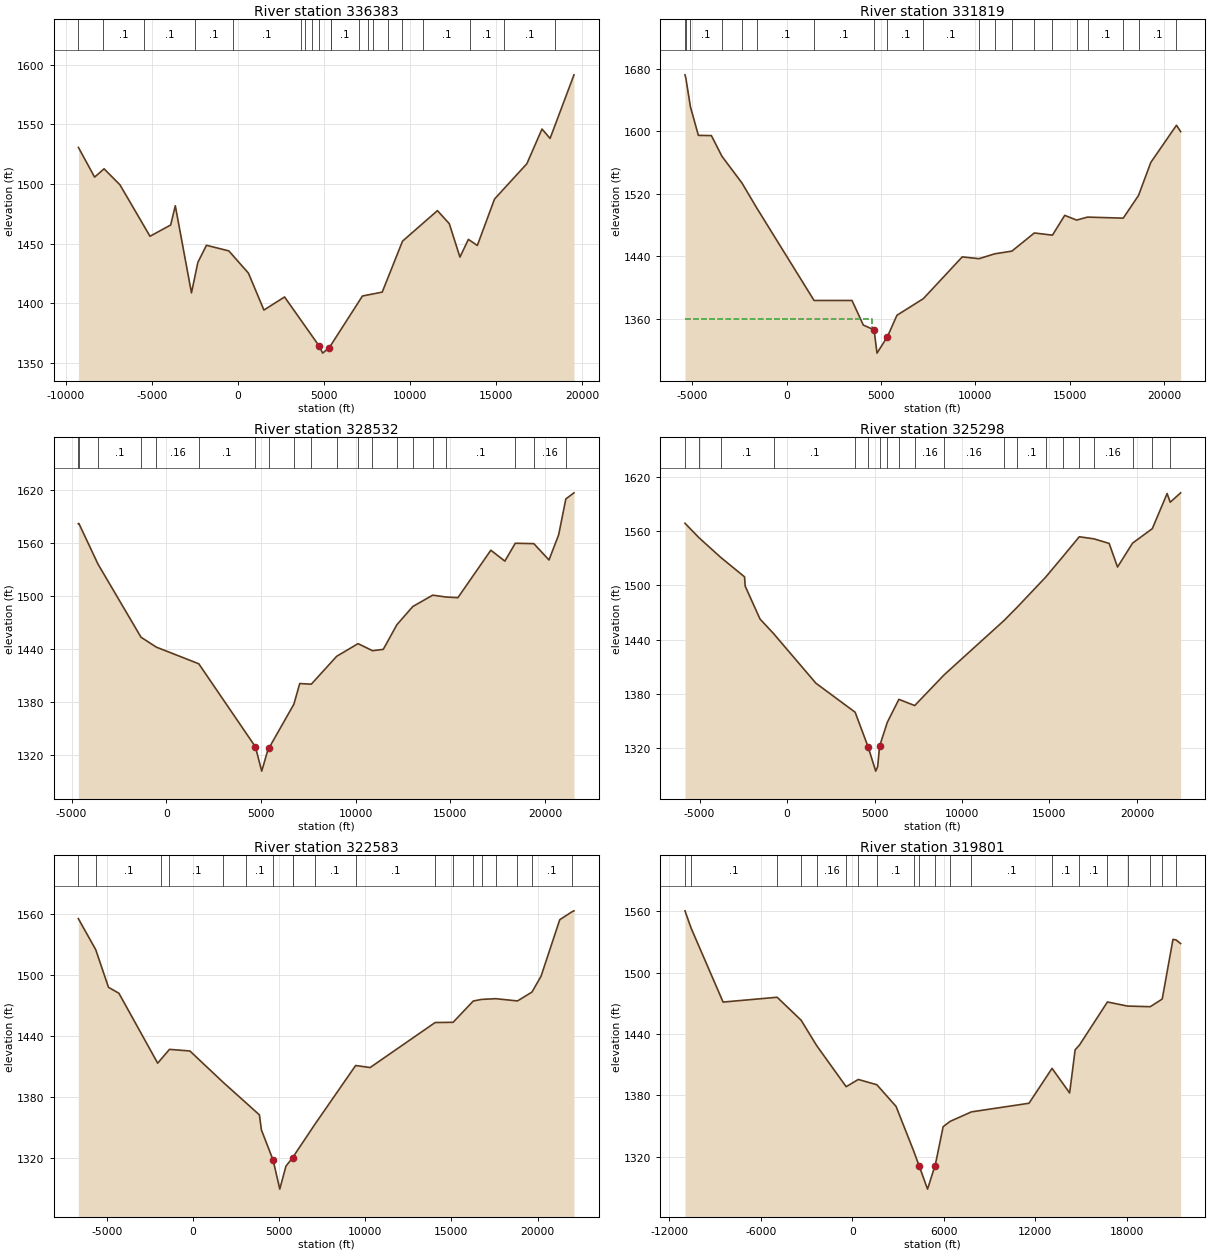
Type RM Length L Ch R = 1 ,336383  ,4564,4564,4564
BEGIN DESCRIPTION:
PEDERNALES RIVER 236.0
END DESCRIPTION:
XS GIS Cut Line= 4
      2843643.37     10072846.87      2849650.31     10061874.66
      2853678.09     10059235.77      2855932.12     10047987.05
#Sta/Elev= 30
   -9260 1530.68-8320.08 1505.84-7770.13 1512.78-6850.21 1499.45-5100.36 1456.31
-3900.47 1465.71-3630.49 1481.85-2690.58 1408.89-2320.61 1434.37-1820.65 1448.75
-520.769 1444.05619.1201 1425.41 1519.03 1394.52 2718.91 1405.45  4730.1 1364.37
  4931.9 1358.43    5321 1363.097244.949 1406.278393.961 1409.53 9573.27 1452.21
11602.08 1477.7512291.67 1466.8412911.31 1438.8513401.02  1453.713920.72 1448.59
14920.13 1487.4616799.03 1517.0417678.52 1546.1118148.24 1538.2419537.43 1591.49
#Mann= 20 ,-1 , 0
 -9266.3      .1       0   -7826      .1       0 -5440.2      .1       0
   -2486      .1       0  -298.7      .1       0  3649.5     .16       0
  3932.3      .1       0  4292.9     .16       0    4715     .07       0
  5389.6      .1       0  5389.6      .1       0  7064.2     .05       0
  7593.7     .16       0  7849.8      .1       0  8722.1     .16       0
  9533.6      .1       0 10759.2      .1       0 13469.7      .1       0
 15442.8      .1       0 18454.8      .1       0
Bank Sta=4730.1,5321
XS Rating Curve= 0 ,0
Exp/Cntr=0.3,0.1

Type RM Length L Ch R = 1 ,331819  ,3287,3287,3287
BEGIN DESCRIPTION:
PEDERNALES RIVER 245.0
END DESCRIPTION:
XS GIS Cut Line= 4
      2849337.81     10074582.98      2850761.42     10068923.27
      2855761.42     10058576.05      2856903.69     10049736.41
#Sta/Elev= 30
   -5377 1672.47-5327.03 1667.83 -5087.2 1631.46-4667.48 1594.98-3977.95 1594.67
-3418.33 1568.15-2359.05 1533.96 -1559.6 1501.37 1458.34 1383.58 3466.94 1383.59
 4066.53 1352.09  4635.5 1345.97  4790.8 1316.18  5344.1 1337.34 5845.31 1364.63
 7244.36 1385.92 9302.95 1439.3910192.34 1437.0911031.76 1443.3711931.09 1446.77
13120.38 1469.9914079.82 1467.2314729.44 1492.5615359.07 1486.5215938.73 1490.32
17827.62 1488.9918637.15 1518.0919286.77 1560.3220645.97 1607.9220865.84 1599.77
#Mann= 20 ,-1 , 0
   -5377     .16       0-5327.03     .16       0 -5087.2      .1       0
-3418.33      .1       0-2359.05      .1       0 -1559.6      .1       0
 1458.34      .1       0  4635.5     .07       0  5344.1      .1       0
 7244.36      .1       010192.34     .16       011031.76      .1       0
11931.09      .1       013120.38     .16       014079.82      .1       0
15359.07     .16       015938.73      .1       017827.62      .1       0
18637.15      .1       020645.97     .16       0
#XS Ineff= 2 , 0
         4536.93 1359.57
Permanent Ineff=
       F       F
Bank Sta=4635.5,5344.1
XS Rating Curve= 0 ,0
Exp/Cntr=0.3,0.1

Type RM Length L Ch R = 1 ,328532  ,3234,3234,3234
BEGIN DESCRIPTION:
PEDERNALES RIVER 246.0
END DESCRIPTION:
XS GIS Cut Line= 3
      2851978.42     10075500.48       2857915.6     10060218.48
      2857980.31      10050453.1
#Sta/Elev= 30
   -4640  1582.1-4610.01 1582.33-3600.33  1536.3-1331.04 1453.65 -521.29 1442.43
 1718.01  1423.6    4707 1329.68  5038.7 1302.17  5400.8 1328.75 5426.89 1328.47
 6736.51 1377.84 7046.42 1401.26 7656.24 1400.51 8995.85 1432.0610125.51 1446.38
10885.29 1438.4111455.12 1439.9112174.87 1467.8213014.54 1488.3814064.13 1501.22
14773.86 1499.1115393.61 1498.3717132.93 1552.0817872.64 1539.7418422.43 1559.94
19402.05  1559.520201.73 1541.0220711.54 1569.4321091.39 1610.0621521.22 1616.98
#Mann= 20 ,-1 , 0
   -4640      .1       0-4610.01      .1       0-3600.33      .1       0
-1331.04     .16       0 -521.29     .16       0 1718.01      .1       0
    4707     .07       0 5426.89     .16       0 6736.51      .1       0
 7656.24      .1       0 8995.85     .16       010125.51      .1       0
10885.29     .16       012174.87      .1       013014.54     .05       0
14064.13      .1       014773.86      .1       018422.43     .16       0
19402.05     .16       021091.39     .16       0
Bank Sta=4707,5400.8
XS Rating Curve= 0 ,0
Exp/Cntr=0.3,0.1

Type RM Length L Ch R = 1 ,325298  ,2715,2715,2715
BEGIN DESCRIPTION:
PEDERNALES RIVER 252.0
END DESCRIPTION:
XS GIS Cut Line= 4
      2852626.77     10075725.39      2858167.79     10070692.91
      2859435.82     10055679.47      2858474.49     10049970.78
#Sta/Elev= 30
 -5839.4 1568.74 -5040.3 1552.78 -3794.2 1530.96 -2432.2 1509.41 -2396.4 1499.18
   -1547 1462.72  -775.5 1446.69  1645.8 1391.77    3891 1359.62 4636.36 1321.09
  5066.9 1294.45  5177.5 1299.37  5287.9 1322.05  5730.6  1348.5  6392.6 1373.89
  7296.5 1367.01  8983.5 1401.08 12407.3 1461.16 13173.9 1476.18 14794.6 1509.33
 15770.8 1531.88 16705.1 1553.77   17535 1551.53 18415.1 1546.43 18894.3 1520.28
   19752 1546.72 20882.2 1562.76 21729.1 1601.63 21905.8 1592.01 22501.8  1602.4
#Mann= 20 ,-1 , 0
 -5839.4      .1       0 -5040.3     .16       0 -3794.2      .1       0
  -775.5      .1       0    3891      .1       0 4636.36     .07       0
  5287.9      .1       0  5730.6     .16       0  6392.6     .16       0
  7296.5     .16       0  8983.5     .16       0 12407.3      .1       0
 13173.9      .1       0 14794.6      .1       0 15770.8      .1       0
 16705.1      .1       0   17535     .16       0   19752     .16       0
 20882.2      .1       0 21905.8     .16       0
Bank Sta=4636.36,5287.9
XS Rating Curve= 0 ,0
Exp/Cntr=0.3,0.1

Type RM Length L Ch R = 1 ,322583  ,2782,2782,2782
BEGIN DESCRIPTION:
PEDERNALES RIVER 253.0
END DESCRIPTION:
XS GIS Cut Line= 4
      2854396.59     10075415.54      2860961.79     10070938.05
      2861683.43      10056243.5      2859256.76     10050627.06
#Sta/Elev= 30
 -6661.3 1555.06 -5651.7 1524.56 -4909.9 1487.55 -4305.6 1481.72 -2052.9 1412.96
 -1857.8 1416.89   -1369 1426.57  -183.1 1424.96  1741.9 1394.28  3068.6 1374.11
  3852.8 1362.18  3968.9 1347.43  4653.8 1317.45    5034 1289.22  5393.3 1311.82
  5777.9 1320.09  7061.1 1352.61  9438.6 1410.68 10280.5 1408.71 14056.9 1452.94
 15095.3 1453.14 16270.5 1474.07 16748.9 1475.64 17570.6 1476.37 18834.3 1474.14
 19675.5 1482.85 20202.3 1498.38 21289.2 1553.92 21991.2 1561.69 22115.9 1562.69
#Mann= 19 ,-1 , 0
 -6661.3      .1       0 -5651.7      .1       0 -1857.8     .16       0
   -1369      .1       0  1741.9      .1       0  3068.6      .1       0
  4653.8     .07       0  5777.9     .05       0  5777.9      .1       0
  7061.1      .1       0  9438.6      .1       0 14056.9      .1       0
 15095.3      .1       0 16270.5      .1       0 16748.9     .16       0
 17570.6      .1       0 18834.3      .1       0 19675.5      .1       0
 21991.2     .16       0
Bank Sta=4653.8,5777.9
XS Rating Curve= 0 ,0
Exp/Cntr=0.3,0.1

Type RM Length L Ch R = 1 ,319801  ,1637,1637,1637
BEGIN DESCRIPTION:
PEDERNALES RIVER 254.0
END DESCRIPTION:
XS GIS Cut Line= 4
       2854683.8     10078565.79      2863621.89     10070807.71
      2864440.18     10057090.95      2860494.53     10051400.15
#Sta/Elev= 30
-10970.2 1560.56-10562.2 1543.46 -8470.4 1471.26   -4927 1475.98 -3354.2 1453.52
 -2336.4 1428.71  -399.6 1388.43   396.7 1395.52  1612.5 1390.35  2872.8 1369.11
  4028.2 1325.42 4386.36 1310.89  4936.2 1288.18    5424 1311.15    5429 1310.76
  5958.2 1349.26  6407.3 1354.42  7812.6 1363.79 11588.2 1372.23 13099.7 1406.37
   14253 1382.31 14613.6 1424.53 14896.9 1429.18 16731.6 1471.35   18052 1467.34
 19538.5 1466.74 20324.6 1474.22 21029.1 1532.61 21226.4 1532.13 21531.2 1528.55
#Mann= 20 ,-1 , 0
-10970.2      .1       0-10562.2      .1       0   -4927      .1       0
 -3354.2      .1       0 -2336.4     .16       0  -399.6     .16       0
   396.7      .1       0  1612.5      .1       0  4028.2      .1       0
 4386.36     .07       0    5429     .05       0  6407.3      .1       0
  7812.6      .1       0 13099.7      .1       0 14896.9      .1       0
 16731.6      .1       0   18052      .1       0 19538.5     .16       0
 20324.6      .1       0 21226.4      .1       0
Bank Sta=4386.36,5424
XS Rating Curve= 0 ,0
Exp/Cntr=0.3,0.1

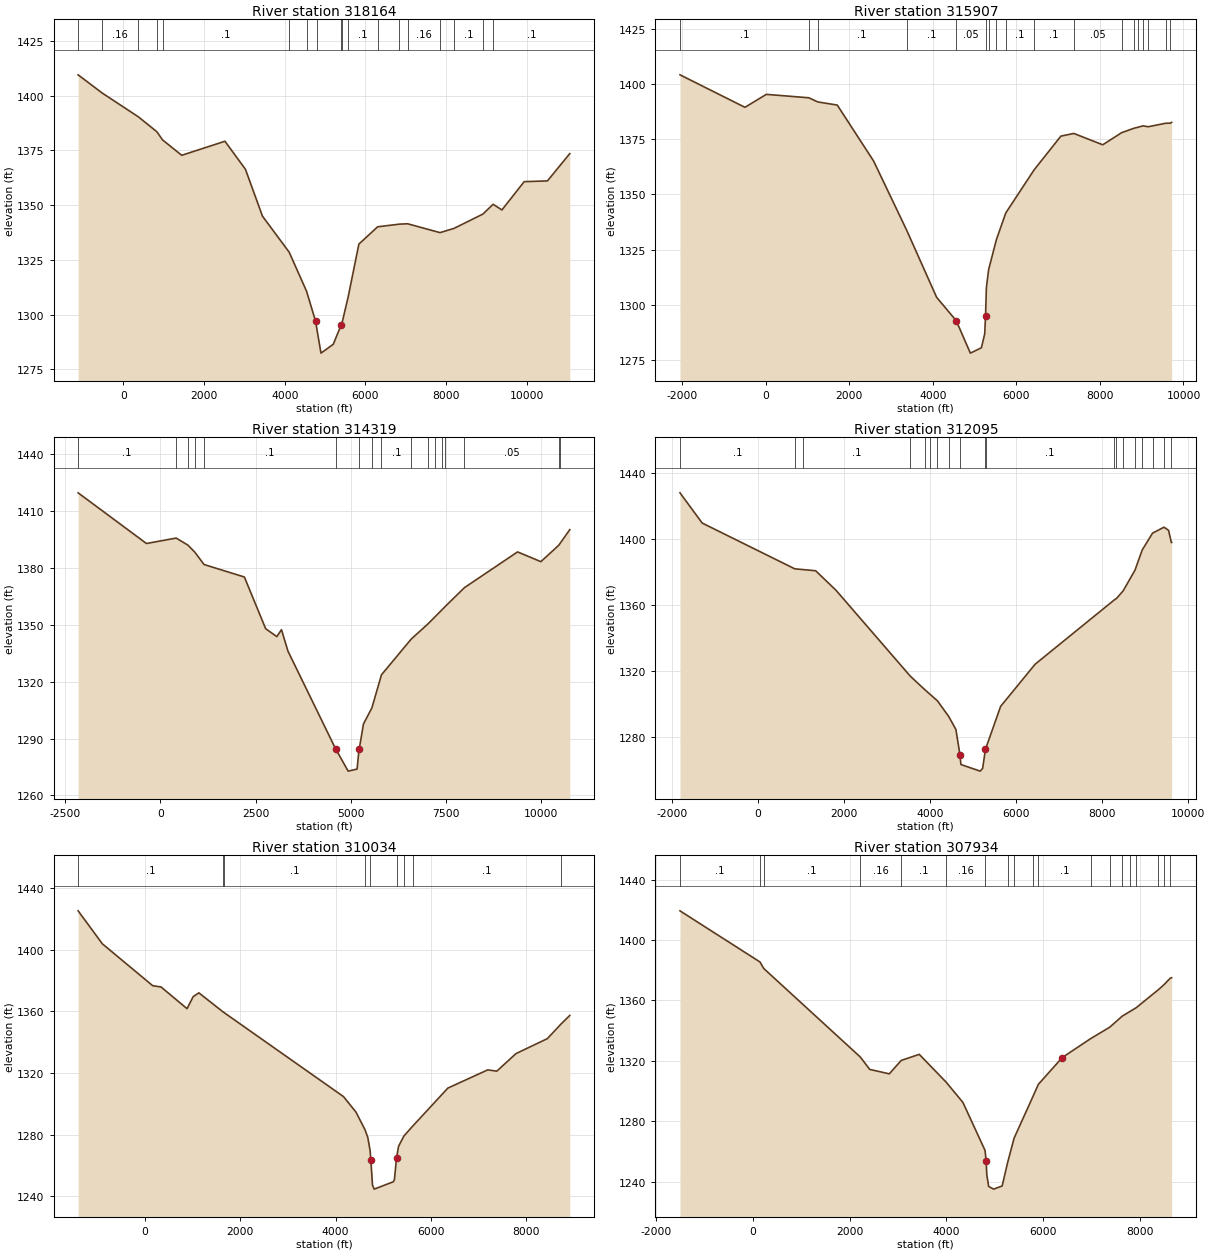
Type RM Length L Ch R = 1 ,318164  ,2257,2257,2257
BEGIN DESCRIPTION:
PEDERNALES RIVER 257.0
END DESCRIPTION:
XS GIS Cut Line= 4
      2863837.32     10072249.41      2865117.71     10068538.46
      2865703.64     10065001.13      2867591.07      10060727.3
#Sta/Elev= 30
 -1120.7 1409.49  -521.4 1401.14   373.8 1390.29   830.8 1383.49   971.3 1379.77
  1446.7 1372.73  2517.5 1379.15  3025.7 1366.35  3447.7 1344.93    4110 1328.46
  4539.9 1310.65    4766 1296.82  4806.6 1292.18  4897.5 1282.37  5201.9 1286.42
  5394.5 1295.09  5428.7 1296.87    5570 1307.96    5837 1332.18  6301.4 1340.07
  6842.7 1341.29  7044.1 1341.46  7847.7 1337.41  8195.6 1339.36  8909.2 1345.88
  9163.3 1350.37  9381.3 1347.77  9932.4 1360.69 10508.9 1361.03 11062.5 1373.49
#Mann= 18 ,-1 , 0
 -1120.7      .1       0  -521.4     .16       0   373.8      .1       0
   830.8     .05       0   971.3      .1       0    4110     .16       0
  4539.9      .1       0  4806.6     .05       0  5394.5      .1       0
  5428.7     .16       0    5570      .1       0  6301.4     .16       0
  6842.7      .1       0  7044.1     .16       0  7847.7     .16       0
  8195.6      .1       0  8909.2     .05       0  9163.3      .1       0
Bank Sta=4766,5394.5
XS Rating Curve= 0 ,0
Exp/Cntr=0.3,0.1

Type RM Length L Ch R = 1 ,315907  ,1588,1588,1588
BEGIN DESCRIPTION:
PEDERNALES RIVER 256.0
END DESCRIPTION:
XS GIS Cut Line= 3
      2866701.92     10073160.81      2867569.96     10068668.67
      2868003.89     10061487.11
#Sta/Elev= 30
 -2053.2  1404.2  -497.9 1389.47    13.5 1395.34  1031.8 1393.79  1243.9 1391.92
  1712.3 1390.48  2581.1 1365.16  3374.1 1333.73  4089.8 1303.36  4560.7 1292.71
  4898.6 1278.02  5161.8 1280.44  5241.9 1286.73    5262 1295.05    5282 1307.69
  5335.5 1315.89  5522.3 1329.53    5747  1341.6  6421.3 1361.03  7065.2 1376.41
  7375.5 1377.62  8067.1 1372.48  8518.6 1377.96  8814.2 1379.97  8921.6  1380.5
  9031.3 1381.05  9158.1 1380.67  9579.7 1382.26  9685.9 1382.28  9716.7 1382.65
#Mann= 18 ,-1 , 0
 -2053.2      .1       0  1031.8     .05       0  1243.9      .1       0
  3374.1      .1       0  4560.7     .05       0    5262     .16       0
  5335.5      .1       0  5522.3      .1       0    5747      .1       0
  6421.3      .1       0  7375.5     .05       0  8518.6      .1       0
  8814.2     .05       0  8921.6      .1       0  9031.3     .05       0
  9158.1      .1       0  9579.7     .05       0  9685.9      .1       0
Bank Sta=4560.7,5262
XS Rating Curve= 0 ,0
Exp/Cntr=0.3,0.1

Type RM Length L Ch R = 1 ,314319  ,2224,2224,2224
BEGIN DESCRIPTION:
PEDERNALES RIVER 260.0
END DESCRIPTION:
XS GIS Cut Line= 4
      2866962.33     10073638.28      2868372.92      10069254.6
      2869848.61     10064697.31      2869284.37     10061203.37
#Sta/Elev= 30
   -2167 1419.57  -369.4 1392.85   411.8 1395.71   719.4 1392.03   904.4 1388.26
  1146.3 1381.76    2207 1375.18  2767.2 1347.92  3060.5 1343.76  3183.2 1347.41
  3353.7 1336.09  4604.3 1284.68  4937.1 1272.82  5171.9  1273.9  5213.9 1282.46
  5230.6 1284.68    5340 1297.69  5561.6 1306.16  5812.9 1323.59  6597.1 1342.47
  7038.4 1350.48    7221 1354.16  7394.2 1357.65  7494.6 1359.71  7996.2 1369.56
  9393.9 1388.42 10007.4 1383.28 10476.5 1391.89 10500.6 1392.57 10767.5 1400.15
#Mann= 17 ,-1 , 0
   -2167      .1       0   411.8     .05       0   719.4      .1       0
   904.4     .05       0  1146.3      .1       0  4604.3     .07       0
  5213.9     .16       0  5561.6     .16       0  5812.9      .1       0
  6597.1     .05       0  7038.4      .1       0    7221     .05       0
  7394.2      .1       0  7494.6     .05       0  7996.2     .05       0
 10476.5      .1       0 10500.6     .05       0
Bank Sta=4604.3,5230.6
XS Rating Curve= 0 ,0
Exp/Cntr=0.3,0.1

Type RM Length L Ch R = 1 ,312095  ,2061,2061,2061
BEGIN DESCRIPTION:
PEDERNALES RIVER 262.0
END DESCRIPTION:
XS GIS Cut Line= 4
      2867483.15     10073529.78      2869392.88     10070448.18
      2872192.36     10066194.71      2873840.73     10064047.49
#Sta/Elev= 30
 -1809.7 1427.96 -1293.7 1409.66   857.3 1381.96  1044.8 1381.51  1343.3 1380.79
  1815.4 1368.99  3542.8 1316.96  3879.3  1308.8  4001.6 1305.99  4173.2 1302.04
  4435.3 1292.56    4602 1284.69  4695.4 1269.52  4718.1  1263.5  5165.1  1259.5
  5222.5 1261.11  5288.8 1272.75  5295.8 1273.24  5641.2  1298.7  6442.4 1324.21
  8285.9 1363.21  8331.6 1363.99  8487.9 1368.62  8762.7 1381.11  8931.9 1393.41
    9172 1403.56  9437.3 1407.16  9543.8 1405.25  9609.1 1397.84  9614.7 1397.91
#Mann= 19 ,-1 , 0
 -1809.7      .1       0   857.3     .05       0  1044.8      .1       0
  3542.8     .16       0  3879.3      .1       0  4001.6     .16       0
  4173.2      .1       0  4435.3      .1       0  4695.4    .033       0
  5288.8     .05       0  5295.8      .1       0  8285.9     .05       0
  8331.6      .1       0  8487.9     .05       0  8762.7      .1       0
  8931.9     .16       0    9172      .1       0  9437.3     .16       0
  9609.1      .1       0
Bank Sta=4695.4,5288.8
XS Rating Curve= 0 ,0
Exp/Cntr=0.3,0.1

Type RM Length L Ch R = 1 ,310034  ,2100,2100,2100
BEGIN DESCRIPTION:
PEDERNALES RIVER 264.0
END DESCRIPTION:
XS GIS Cut Line= 4
       2868025.7     10073638.27      2869978.82     10071424.74
      2873776.56     10068169.53      2875382.47     10066433.42
#Sta/Elev= 30
 -1402.7 1425.21  -894.4 1403.83   161.4 1376.68   337.9 1375.82   883.9 1361.75
  1011.4 1369.52  1131.9 1372.01  1636.6 1359.73  1661.8 1359.18    4167 1304.73
  4429.3 1294.66    4617 1283.33  4677.4 1278.23  4726.8 1269.49    4741 1263.71
  4776.2 1247.26  4812.1 1244.71  5216.3 1249.53  5237.1 1251.13  5279.9  1264.8
  5322.7 1272.46  5435.9 1279.19  5622.4 1285.66  6357.7 1310.24  7193.6 1322.04
  7384.7 1321.23  7787.8 1332.62  8446.1 1342.32    8735 1351.87  8916.2 1357.34
#Mann= 9 ,-1 , 0
 -1402.7      .1       0  1636.6     .16       0  1661.8      .1       0
    4617     .16       0  4726.8     .05       0  5279.9      .1       0
  5435.9     .16       0  5622.4      .1       0    8735     .05       0
Bank Sta=4741,5279.9
XS Rating Curve= 0 ,0
Exp/Cntr=0.3,0.1

Type RM Length L Ch R = 1 ,307934  ,3034,3034,3034
BEGIN DESCRIPTION:
PEDERNALES RIVER 266.0
END DESCRIPTION:
XS GIS Cut Line= 3
      2868763.56     10074441.21      2871172.39     10072227.69
      2877248.78     10068972.49
#Sta/Elev= 30
 -1509.7 1419.38   145.1 1385.47   221.8 1381.18  2218.4 1322.52  2412.8 1314.31
  2818.2 1311.37  3063.5 1320.24  3437.2 1324.29  3995.1 1305.79  4340.6  1292.4
  4797.6  1260.6  4820.3 1253.53  4833.7 1244.52  4871.9 1236.78  4975.6 1234.98
  5151.4 1237.09  5262.7 1252.42  5398.6  1268.8  5795.2 1296.87    5900 1304.43
  6394.3 1322.18  6983.8 1334.76    7377 1342.31  7634.4 1349.62  7799.3  1352.8
  7921.5 1355.15  8383.1 1367.18  8505.8 1370.72  8623.8 1374.66  8655.1 1375.05
#Mann= 19 ,-1 , 0
 -1509.7      .1       0   145.1     .16       0   221.8      .1       0
  2218.4     .16       0  3063.5      .1       0  3995.1     .16       0
  4797.6     .07       0  5262.7     .16       0  5398.6      .1       0
  5795.2     .16       0    5900      .1       0  6983.8     .05       0
    7377      .1       0  7634.4     .16       0  7799.3      .1       0
  7921.5     .05       0  8383.1      .1       0  8505.8     .05       0
  8623.8     .05       0
Bank Sta=4820.3,6394.3
XS Rating Curve= 0 ,0
Exp/Cntr=0.3,0.1

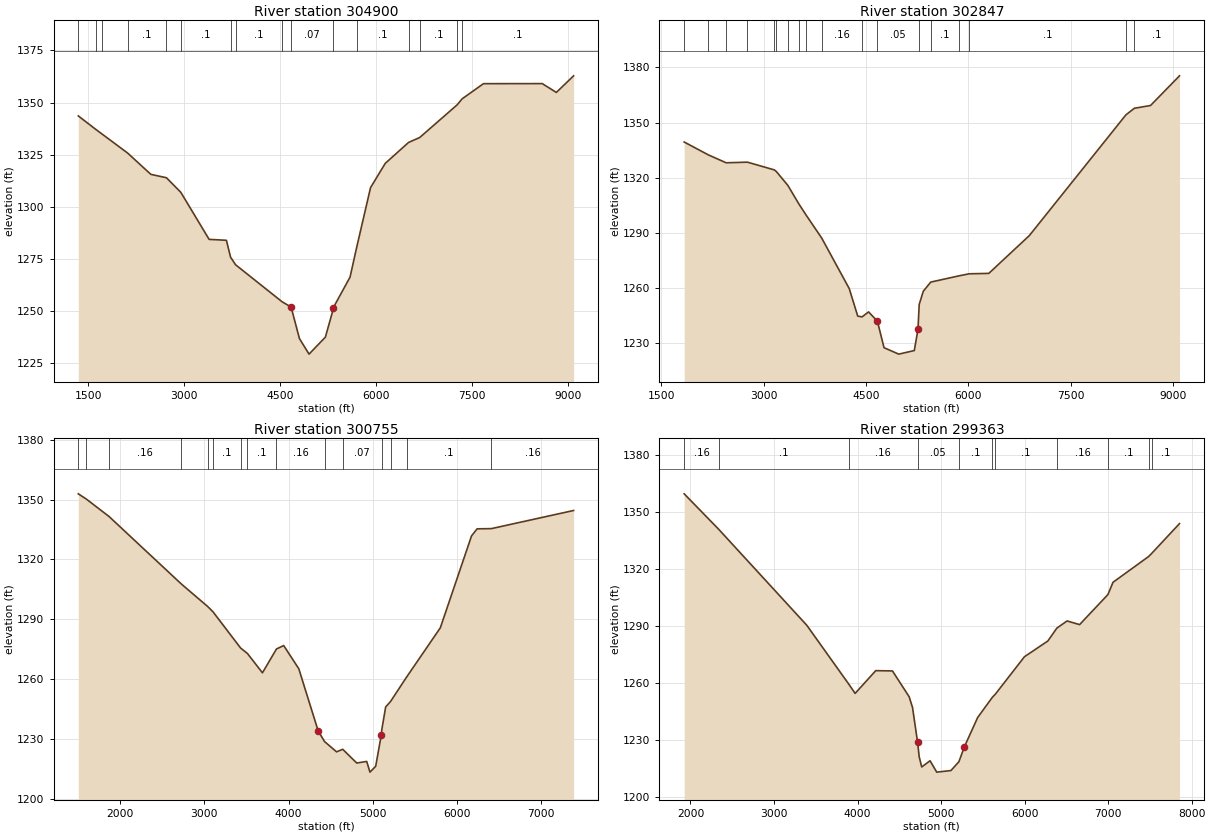
Type RM Length L Ch R = 1 ,304900  ,2053,2053,2053
BEGIN DESCRIPTION:
PEDERNALES RIVER 268.0
END DESCRIPTION:
XS GIS Cut Line= 3
      2871346.04     10073486.37      2876142.01     10073551.48
      2879028.25     10073008.95
#Sta/Elev= 30
  1346.9 1343.59  1620.9  1337.1  1715.5 1334.94    2116 1325.79  2479.4 1315.54
  2723.2 1313.91  2947.6 1306.91  3389.5 1284.33  3659.5 1283.89  3724.2 1275.79
  3801.9 1272.16  4529.7 1254.36  4669.6 1251.83  4799.6 1236.72  4949.4 1229.25
  5204.5  1237.4  5317.8 1249.79  5329.7 1251.62  5589.7 1266.22    5696 1280.87
  5909.7 1309.16    6139  1320.8  6503.5 1330.86  6677.3 1333.22  7263.3 1348.94
  7338.1 1351.75  7672.5 1359.06  8590.5  1359.1  8810.7 1354.86  9080.1 1362.83
#Mann= 16 ,-1 , 0
  1346.9      .1       0  1620.9     .16       0  1715.5      .1       0
    2116      .1       0  2723.2     .16       0  2947.6      .1       0
  3724.2     .16       0  3801.9      .1       0  4529.7      .1       0
  4669.6     .07       0  5317.8      .1       0    5696      .1       0
  6503.5     .16       0  6677.3      .1       0  7263.3     .16       0
  7338.1      .1       0
Bank Sta=4669.6,5329.7
XS Rating Curve= 0 ,0
Exp/Cntr=0.3,0.1

Type RM Length L Ch R = 1 ,302847  ,2092,2092,2092
BEGIN DESCRIPTION:
PEDERNALES RIVER 269.0
END DESCRIPTION:
XS GIS Cut Line= 3
      2871346.01     10074701.65      2876641.14     10076003.74
      2878442.36     10076003.74
#Sta/Elev= 30
  1836.4 1339.42  2188.6 1332.46  2451.3 1328.13    2762 1328.47    3157 1324.27
  3187.8 1323.32  3354.5 1315.86  3517.1 1305.71  3621.7 1299.75  3849.9 1287.27
  4253.4 1259.81  4378.1 1244.83  4441.5 1244.41    4537 1247.12  4665.7 1242.09
  4763.5 1227.66  4979.5 1224.17  5206.3 1226.11  5260.6 1237.62  5278.4 1251.16
  5338.5 1258.34    5447  1263.3  5856.4 1266.67  6010.1 1267.81  6297.9 1268.04
  6890.7 1288.55  8305.4 1354.15  8429.4 1357.75  8666.6 1359.26  9090.5 1375.38
#Mann= 18 ,-1 , 0
  1836.4      .1       0  2188.6     .16       0  2451.3      .1       0
    2762     .16       0    3157      .1       0  3187.8     .16       0
  3354.5      .1       0  3517.1     .16       0  3621.7      .1       0
  3849.9     .16       0  4441.5      .1       0  4665.7     .05       0
  5278.4     .16       0    5447      .1       0  5856.4     .16       0
  6010.1      .1       0  8305.4     .16       0  8429.4      .1       0
Bank Sta=4665.7,5260.6
XS Rating Curve= 0 ,0
Exp/Cntr=0.3,0.1

Type RM Length L Ch R = 1 ,300755  ,1392,1392,1392
BEGIN DESCRIPTION:
Mapping XS 468fd7d0
END DESCRIPTION:
XS GIS Cut Line= 3
        2870326.     10076698.18      2872083.85     10076915.19
      2876033.51     10078043.67
#Sta/Elev= 30
  1503.9 1352.93  1599.2  1350.3    1869 1341.55  2727.9 1307.66  3040.4 1296.37
    3102 1293.79  3429.9  1275.6  3511.7 1272.83  3689.5 1263.14    3856 1275.09
  3941.7 1276.83  4121.1 1265.18  4351.1    1234  4426.9 1228.65  4569.5 1223.49
  4642.3 1224.78  4808.7 1217.89  4927.2 1218.69  4965.9 1213.32  5033.8 1216.26
  5099.9 1231.86  5106.6 1234.68  5151.9    1246  5210.4 1248.78  5399.4 1260.93
  5800.8 1285.71  6171.1  1331.8  6237.6 1335.37  6406.6 1335.47  7382.8 1344.57
#Mann= 15 ,-1 , 0
  1503.9     .16       0  1599.2      .1       0    1869     .16       0
  2727.9      .1       0  3040.4     .16       0    3102      .1       0
  3429.9     .16       0  3511.7      .1       0    3856     .16       0
  4426.9      .1       0  4642.3     .07       0  5106.6      .1       0
  5210.4     .16       0  5399.4      .1       0  6406.6     .16       0
Bank Sta=4351.1,5099.9
XS Rating Curve= 0 ,0
Exp/Cntr=0.3,0.1

Type RM Length L Ch R = 1 ,299363  ,1626,1626,1626
BEGIN DESCRIPTION:
Mapping XS b7bac6b9
END DESCRIPTION:
XS GIS Cut Line= 3
      2870217.56     10077674.76      2872062.15      10078607.9
      2875924.21     10078542.81
#Sta/Elev= 30
  1924.8 1359.52  2338.1 1340.83    3392  1290.3  3897.9 1259.09  3971.4 1254.37
  4218.3 1266.36  4418.4  1266.2  4618.4 1252.59  4658.4 1246.96  4718.4 1228.84
  4738.4 1220.99  4768.4  1215.6  4868.4 1218.88  4948.2 1212.89  5118.5 1213.72
    5214 1218.39  5278.5 1226.17  5438.5 1241.68  5613.9  1252.3  5650.2 1253.97
  5998.6 1273.69  6278.6 1281.98    6386 1288.74  6508.7 1292.54  6658.7 1290.61
    6998 1306.46  7058.7 1312.91  7485.7 1326.51  7527.4 1328.38  7854.6 1343.83
#Mann= 11 ,-1 , 0
  1924.8     .16       0  2338.1      .1       0  3897.9     .16       0
  4718.4     .05       0    5214      .1       0  5613.9     .16       0
  5650.2      .1       0    6386     .16       0    6998      .1       0
  7485.7     .16       0  7527.4      .1       0
Bank Sta=4718.4,5278.5
XS Rating Curve= 0 ,0
Exp/Cntr=0.3,0.1