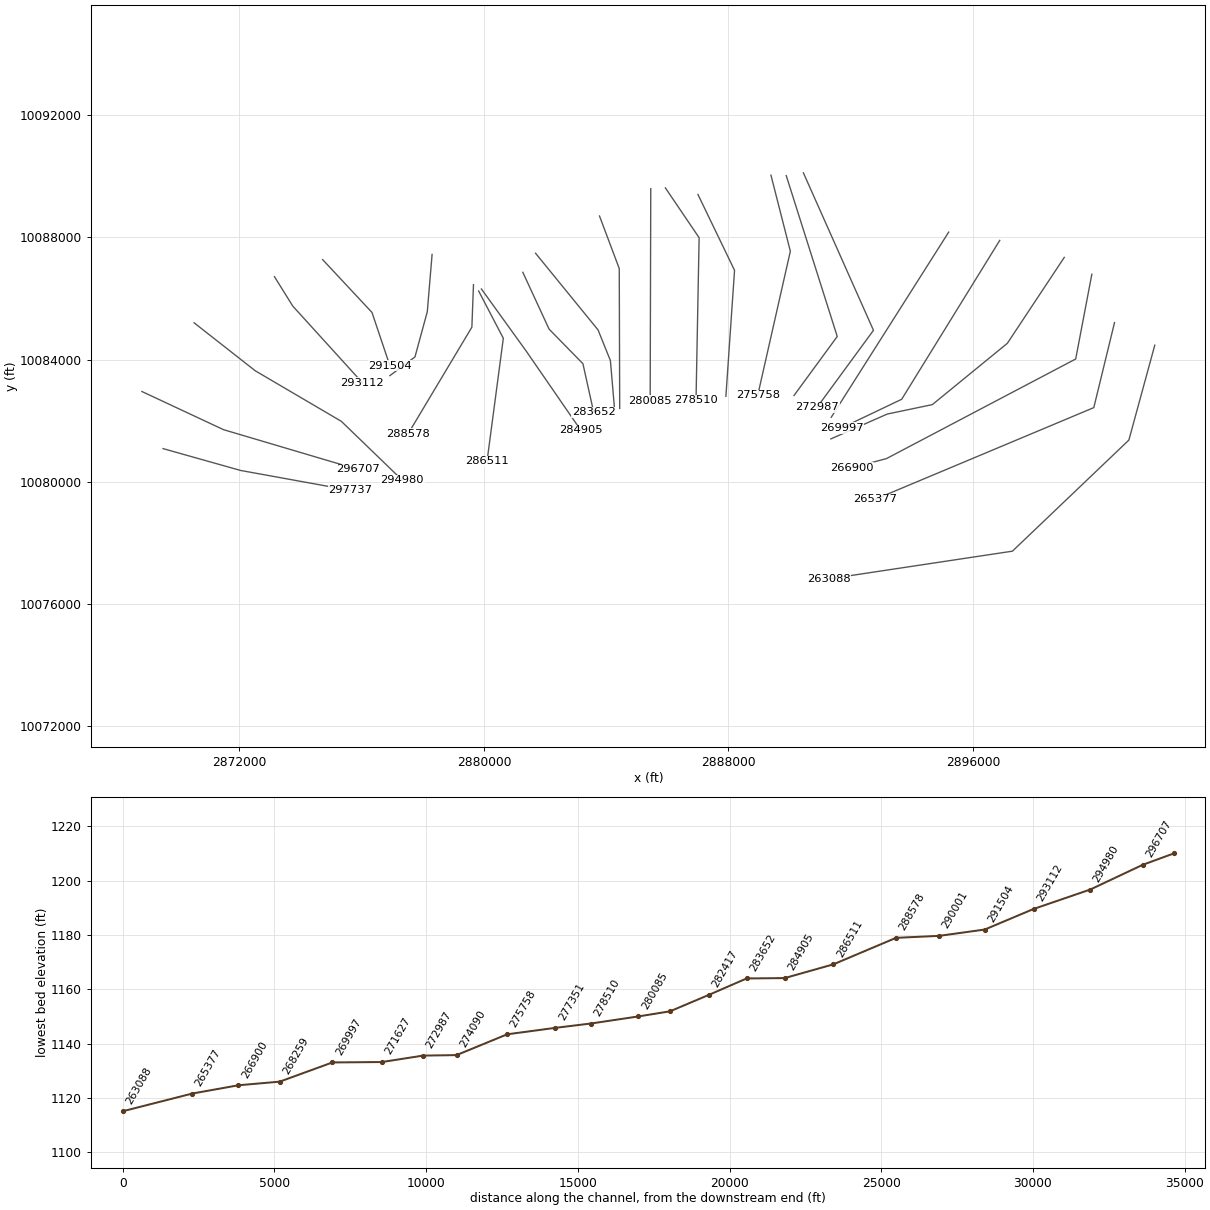
HEC-RAS study PEDERNALES RIVER.prj: PEDERNALES RIVER Base Level Engineering

--- PEDERNALES RIVER.g01 (geometry) --- (continued)

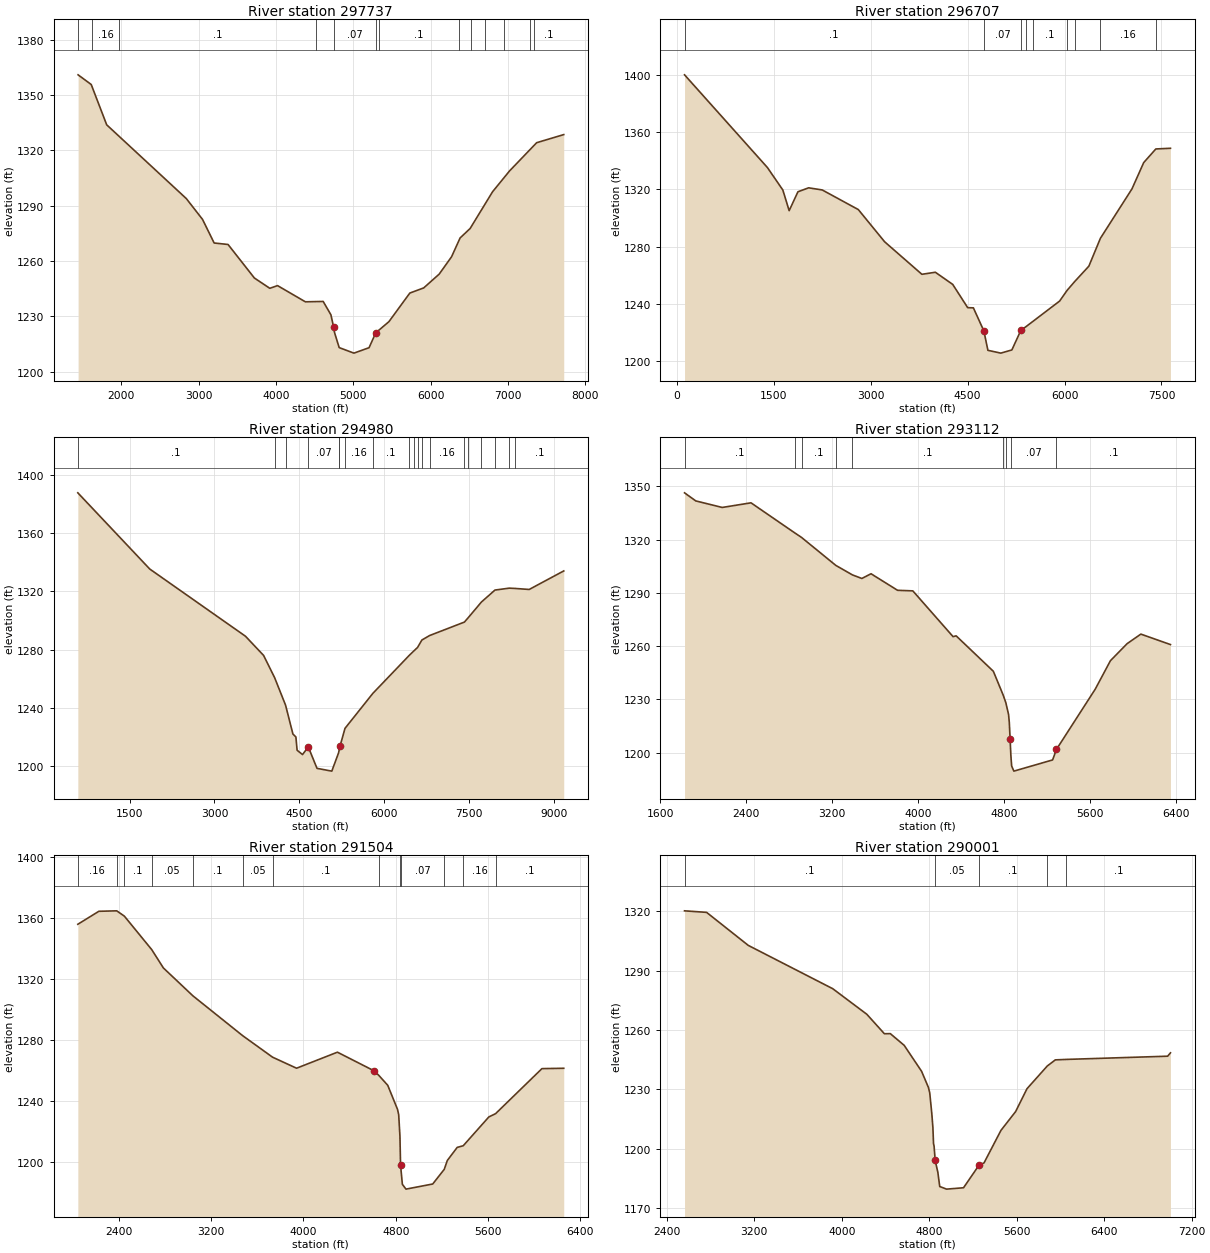
Type RM Length L Ch R = 1 ,297737  ,1030,1030,1030
BEGIN DESCRIPTION:
Mapping XS 5d83a6b7
END DESCRIPTION:
XS GIS Cut Line= 3
      2869501.41     10081081.85      2872040.45     10080365.71
      2875621.14     10079714.68
#Sta/Elev= 30
    1442 1360.99 1611.88 1355.74 1811.74 1333.87 2841.01 1293.85 3050.86 1282.54
 3200.75 1269.75 3380.62 1268.94 3720.38 1250.77 3920.24 1245.17 4020.17 1246.63
 4380.08 1237.84 4610.04 1238.04 4710.02  1230.8  4745.7 1224.04  4755.9 1221.29
  4816.9    1213  5007.4    1210  5203.1 1212.94  5289.7 1221.01 5459.91 1227.07
 5729.87 1242.58 5909.84 1245.39 6109.81 1252.88 6269.78 1262.29 6379.76 1272.48
 6509.74 1277.63  6799.7 1297.56 7019.66 1308.88 7369.61 1324.17 7719.55 1328.56
#Mann= 13 ,-1 , 0
  1438.8      .1       0  1628.2     .16       0  1976.1      .1       0
  4514.7     .16       0  4755.9     .07       0  5289.7     .16       0
    5331      .1       0  6371.9     .16       0  6525.7      .1       0
  6698.2     .16       0    6942      .1       0  7278.5     .16       0
    7335      .1       0
Bank Sta=4745.7,5289.7
XS Rating Curve= 0 ,0
Exp/Cntr=0.3,0.1

Type RM Length L Ch R = 1 ,296707  ,1727,1727,1727
BEGIN DESCRIPTION:
Mapping XS 632ee251
END DESCRIPTION:
XS GIS Cut Line= 3
      2868811.25     10082952.53      2871480.55     10081702.52
      2875868.55     10080400.44
#Sta/Elev= 30
   115.4 1399.82  1398.2 1335.21  1637.6 1319.51  1735.5 1305.11  1871.4 1318.28
  2036.8 1321.04  2247.8 1319.55  2806.6 1305.87  3214.4  1283.4  3790.9 1260.75
  3999.5 1262.17  4268.4  1253.7  4500.2 1237.48  4588.3 1237.36  4750.5  1221.3
  4813.1 1207.75  5012.8 1205.79  5184.4 1208.01  5322.5 1221.59  5408.6 1224.44
  5512.8 1228.01  5923.8 1242.09  6040.9 1249.62  6156.2 1255.64  6376.5 1266.42
  6555.4 1285.85  7044.3 1320.32    7226 1338.64  7413.6 1348.13    7640 1348.62
#Mann= 9 ,-1 , 0
   115.4      .1       0  4750.5     .07       0  5322.5      .1       0
  5408.6     .16       0  5512.8      .1       0  6040.9     .16       0
  6156.2      .1       0  6555.4     .16       0  7413.6      .1       0
Bank Sta=4750.5,5322.5
XS Rating Curve= 0 ,0
Exp/Cntr=0.3,0.1

Type RM Length L Ch R = 1 ,294980  ,1868,1868,1868
BEGIN DESCRIPTION:
Mapping XS 9e6836ef
END DESCRIPTION:
XS GIS Cut Line= 4
      2870516.98     10085205.15      2872522.22      10083629.6
      2875334.72     10081975.96       2877326.9     10080048.89
#Sta/Elev= 30
   586.5 1387.63  1856.6 1335.37  3548.4 1289.24  3868.7 1276.06  4062.6 1260.88
  4256.7 1241.94  4386.2 1222.17    4439 1220.14  4460.4 1211.03  4556.2 1208.07
  4657.7 1213.31    4812  1198.6  5073.4  1196.7  5192.4 1209.17  5220.4 1214.13
  5306.9 1226.06  5798.3 1250.03  6445.4 1276.27  6529.4 1279.39  6588.7 1281.56
  6664.9 1286.65  6800.4 1289.71  7415.3 1298.94  7472.9 1301.49  7717.9 1312.76
  7955.9 1320.92  8208.3 1322.23  8308.5 1322.04  8560.6 1321.33    9171 1334.04
#Mann= 19 ,-1 , 0
   586.5      .1       0  4062.6     .05       0  4256.7      .1       0
  4657.7     .07       0  5192.4     .05       0  5192.4      .1       0
  5306.9     .16       0  5798.3      .1       0  6445.4     .16       0
  6529.4      .1       0  6588.7     .16       0  6664.9      .1       0
  6800.4     .16       0  7415.3      .1       0  7472.9     .16       0
  7717.9      .1       0  7955.9      .1       0  8208.3     .16       0
  8308.5      .1       0
Bank Sta=4657.7,5220.4
XS Rating Curve= 0 ,0
Exp/Cntr=0.3,0.1

Type RM Length L Ch R = 1 ,293112  ,1608,1608,1608
BEGIN DESCRIPTION:
Mapping XS cafbb9bf
END DESCRIPTION:
XS GIS Cut Line= 3
      2873147.22     10086715.55      2873746.18       10085752.
      2876024.14     10083239.73
#Sta/Elev= 30
  1825.2 1346.29  1929.6 1341.74  2176.3 1338.05  2444.3 1340.66  2852.4  1323.7
  2915.2 1321.16  3233.9 1305.43  3388.1 1300.09  3476.8 1298.05  3562.1 1300.71
  3809.4 1291.39  3951.4 1291.07  4326.4 1265.28  4354.8 1265.75  4701.5 1245.78
  4793.9 1232.24  4817.6  1228.1  4843.4 1221.41  4850.2 1216.79  4857.6 1207.63
  4864.4 1198.63  4871.8 1192.47  4892.5 1189.55  5253.6 1195.86  5289.5 1201.82
  5650.3  1235.7  5792.1 1251.75  5947.7 1261.36  6075.4 1266.72    6351 1260.83
#Mann= 9 ,-1 , 0
  1825.2      .1       0  2852.4     .16       0  2915.2      .1       0
  3233.9     .16       0  3388.1      .1       0  4793.9     .05       0
  4817.6      .1       0  4864.4     .07       0  5289.5      .1       0
Bank Sta=4857.6,5289.5
XS Rating Curve= 0 ,0
Exp/Cntr=0.3,0.1

Type RM Length L Ch R = 1 ,291504  ,1503,1503,1503
BEGIN DESCRIPTION:
Mapping XS 4bb0072c
END DESCRIPTION:
XS GIS Cut Line= 3
      2874722.72     10087275.46      2876337.32     10085543.67
      2876923.28     10083798.83
#Sta/Elev= 30
  2046.7 1355.82  2228.7 1364.33  2383.4 1364.64  2449.6 1361.16  2686.8 1339.16
  2787.6 1327.15  3042.8 1308.88  3474.4 1282.69  3733.6 1268.56  3941.1 1261.34
  4294.8 1271.86  4614.8 1259.53  4653.2 1256.66  4730.8 1250.12  4815.6 1234.31
  4825.7 1230.76  4836.3 1216.71  4839.6 1205.26  4841.8 1197.63  4857.4 1185.13
  4888.8 1181.98  5120.3 1185.35  5220.2 1194.98  5246.4 1200.74  5332.1 1209.36
  5384.4 1210.45  5606.4 1229.36  5664.6  1231.5  6066.2 1261.07    6255  1261.3
#Mann= 13 ,-1 , 0
  2046.7     .16       0  2383.4     .05       0  2449.6      .1       0
  2686.8     .05       0  3042.8      .1       0  3474.4     .05       0
  3733.6      .1       0  4653.2     .16       0  4839.6      .1       0
  4841.8     .07       0  5220.2      .1       0  5384.4     .16       0
  5664.6      .1       0
Bank Sta=4614.8,4841.8
XS Rating Curve= 0 ,0
Exp/Cntr=0.3,0.1

Type RM Length L Ch R = 1 ,290001  ,1423,1423,1423
BEGIN DESCRIPTION:
Mapping XS 0e9bef21
END DESCRIPTION:
XS GIS Cut Line= 4
      2878303.47      10087444.7      2878147.22     10085569.71
      2877743.57     10084085.33      2876923.35     10083473.42
#Sta/Elev= 30
  2562.4 1320.15  2764.1 1319.37  3145.4 1302.69    3918 1280.82  4229.1 1267.93
  4389.7  1258.1  4443.9 1258.15  4570.9 1252.24    4730 1239.12  4792.1 1231.04
  4804.4 1228.26  4823.2 1217.84  4833.5 1210.65    4839 1202.62  4844.2 1201.36
  4854.2 1194.13  4878.8  1188.1  4895.7 1180.98  4958.1 1179.65  5113.3 1180.34
  5255.9 1191.81  5300.8 1192.88  5455.3 1209.28    5590 1218.82  5693.7 1230.34
  5878.9 1241.79  5952.7  1244.9  6051.7 1245.13  6980.1 1246.76  7005.5 1248.45
#Mann= 5 ,-1 , 0
  2562.4      .1       0  4854.2     .05       0  5255.9      .1       0
  5878.9     .16       0  6051.7      .1       0
Bank Sta=4854.2,5255.9
XS Rating Curve= 0 ,0
Exp/Cntr=0.3,0.1

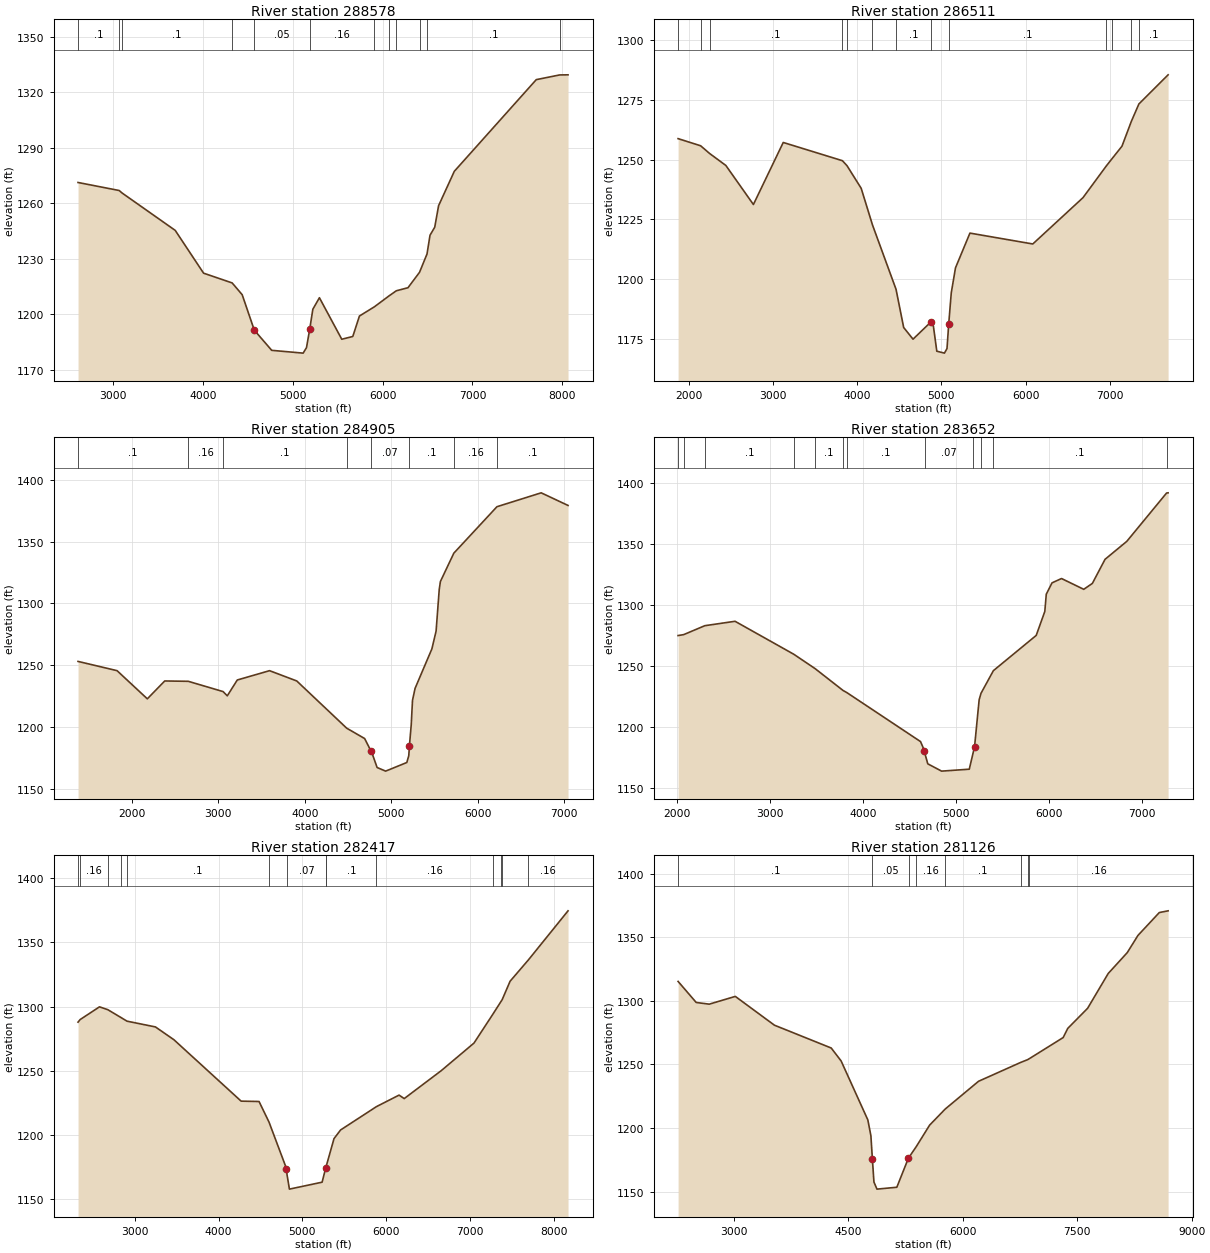
Type RM Length L Ch R = 1 ,288578  ,2067,2067,2067
BEGIN DESCRIPTION:
Mapping XS 5d15e5cf
END DESCRIPTION:
XS GIS Cut Line= 3
      2879657.64     10086455.14      2879605.55     10085061.89
      2877522.83     10081573.33
#Sta/Elev= 30
  2607.5 1271.28  3065.2 1266.94  3096.9 1265.63  3689.7 1245.36  4005.6  1222.2
  4323.7 1216.92  4435.6 1210.55  4570.5 1191.35  4764.5 1180.43  5114.5 1178.92
  5151.8 1181.89  5187.5 1191.78  5222.5 1202.68  5295.7  1208.9  5544.8 1186.43
  5667.4 1187.93  5741.4 1198.99  5908.1    1204    6074    1210  6152.1 1212.66
  6282.3 1214.33  6410.7 1222.66  6494.2 1232.61  6527.5 1242.74  6580.1 1247.07
  6622.9  1258.7    6798 1277.32  7710.7 1326.94    7971 1329.49  8064.7 1329.55
#Mann= 12 ,-1 , 0
  2607.5      .1       0  3065.2     .16       0  3096.9      .1       0
  4323.7     .16       0  4570.5     .05       0  5187.5     .16       0
  5908.1      .1       0    6074     .16       0  6152.1      .1       0
  6410.7     .16       0  6494.2      .1       0    7971     .16       0
Bank Sta=4570.5,5187.5
XS Rating Curve= 0 ,0
Exp/Cntr=0.3,0.1

Type RM Length L Ch R = 1 ,286511  ,1606,1606,1606
BEGIN DESCRIPTION:
Mapping XS 2efcf93c
END DESCRIPTION:
XS GIS Cut Line= 3
      2879826.91     10086246.78       2880634.2     10084697.31
      2880100.34     10080660.82
#Sta/Elev= 30
  1874.6 1258.75  2142.6 1255.76  2247.6 1252.58  2441.8 1247.54  2768.8 1231.23
  3123.2 1257.15  3825.9 1249.53  3880.2 1247.46    4049 1237.98  4182.8 1222.72
  4462.6 1195.82  4553.4 1179.86  4664.3 1174.99  4876.2 1182.15  4906.4 1180.41
  4946.8 1169.96  5037.3 1169.16  5067.8 1171.08    5088 1181.25  5118.3  1194.3
  5168.7 1204.78  5340.2 1219.29  6086.6 1214.75  6682.4 1234.08  6959.9 1247.35
  7030.9 1250.52  7145.8  1255.6    7257 1265.97  7346.6 1273.23  7693.4  1285.4
#Mann= 13 ,-1 , 0
  1874.6      .1       0  2142.6     .16       0  2247.6      .1       0
  3825.9     .16       0  3880.2      .1       0  4182.8     .16       0
  4462.6      .1       0  4876.2     .05       0    5088      .1       0
  6959.9     .16       0  7030.9      .1       0    7257     .16       0
  7346.6      .1       0
Bank Sta=4876.2,5088
XS Rating Curve= 0 ,0
Exp/Cntr=0.3,0.1

Type RM Length L Ch R = 1 ,284905  ,1253,1253,1253
BEGIN DESCRIPTION:
Mapping XS 5be24633
END DESCRIPTION:
XS GIS Cut Line= 3
      2879918.03     10086311.92      2881389.41     10084267.62
      2883172.49      10081677.6
#Sta/Elev= 30
  1379.2 1252.96  1830.1 1245.47    2180 1222.65  2381.2 1237.12  2653.4 1236.84
  3055.2 1228.53  3104.2 1225.08  3219.5  1237.9  3592.7 1245.46  3906.9 1237.13
  4484.2 1198.89  4691.8 1190.48  4763.9 1180.51    4770 1180.08  4835.6 1167.03
  4934.4  1164.1  5179.2 1171.09  5201.7 1176.66  5208.9 1184.38  5229.9 1201.48
  5244.8 1221.44  5274.6 1231.14  5468.7  1263.1  5517.4  1277.5  5553.8 1311.32
  5567.4  1317.7  5722.4 1340.63  6220.7 1378.25  6732.1  1389.5  7042.4 1379.28
#Mann= 8 ,-1 , 0
  1379.2      .1       0  2653.4     .16       0  3055.2      .1       0
  4484.2     .16       0  4763.9     .07       0  5201.7      .1       0
  5722.4     .16       0  6220.7      .1       0
Bank Sta=4770,5208.9
XS Rating Curve= 0 ,0
Exp/Cntr=0.3,0.1

Type RM Length L Ch R = 1 ,283652  ,1235,1235,1235
BEGIN DESCRIPTION:
Mapping XS a3bec1fe
END DESCRIPTION:
XS GIS Cut Line= 4
      2881272.21     10086858.79       2882131.6     10084996.79
      2883238.37     10083863.98      2883589.57     10082277.06
#Sta/Elev= 30
  2016.4  1274.9  2076.6 1275.67  2303.7 1282.97  2627.7 1286.57  3258.3  1259.6
  3487.3 1247.83  3786.7 1229.99  3827.4 1228.25  4618.6 1188.15  4661.1 1180.65
  4668.2 1177.65  4696.5 1169.95  4844.7 1163.97    5142 1165.55  5184.4 1179.31
  5198.6 1183.95    5248 1222.37  5268.1 1227.68  5400.8 1246.18  5860.4    1275
  5952.7  1294.6  5968.6 1308.74  6030.1 1318.02  6132.3 1321.55  6370.9 1312.73
  6463.3 1317.57  6599.3 1337.27  6832.8 1351.97    7260 1391.52  7276.2 1391.68
#Mann= 12 ,-1 , 0
  2016.4      .1       0  2076.6     .16       0  2303.7      .1       0
  3258.3     .05       0  3487.3      .1       0  3786.7     .05       0
  3827.4      .1       0  4668.2     .07       0  5184.4     .05       0
  5268.1     .16       0  5400.8      .1       0    7260     .16       0
Bank Sta=4661.1,5198.6
XS Rating Curve= 0 ,0
Exp/Cntr=0.3,0.1

Type RM Length L Ch R = 1 ,282417  ,1291,1291,1291
BEGIN DESCRIPTION:
Mapping XS a81cf08a
END DESCRIPTION:
XS GIS Cut Line= 4
       2881688.9     10087483.76      2883733.16     10084970.75
       2884136.8     10083968.14      2884267.01     10082444.69
#Sta/Elev= 30
  2323.3 1287.85  2348.9 1289.89  2579.4 1299.76  2678.7 1297.55    2839 1291.33
  2907.2 1288.63  3247.3 1284.14  3467.8 1274.18  4270.1 1226.41  4484.1 1226.13
  4602.9 1210.14  4811.3 1174.01  4818.1 1169.24  4846.6 1157.97  5236.8 1163.37
  5279.9  1174.4  5289.2 1176.56    5379 1197.27  5457.3 1203.98  5885.7 1222.15
  6155.3  1231.1  6217.1  1228.4  6658.1 1250.07  7049.5 1271.55  7272.7 1293.78
    7371 1303.79  7386.4 1305.35    7481 1319.69  7699.5 1336.28  8172.6 1374.45
#Mann= 14 ,-1 , 0
  2323.3      .1       0  2348.9     .16       0  2678.7      .1       0
    2839     .16       0  2907.2      .1       0  4602.9     .16       0
  4818.1     .07       0  5289.2     .16       0  5289.2      .1       0
  5885.7     .16       0  7272.7      .1       0    7371     .16       0
  7386.4      .1       0  7699.5     .16       0
Bank Sta=4811.3,5279.9
XS Rating Curve= 0 ,0
Exp/Cntr=0.3,0.1

Type RM Length L Ch R = 1 ,281126  ,1041,1041,1041
BEGIN DESCRIPTION:
Mapping XS 92669579
END DESCRIPTION:
XS GIS Cut Line= 3
      2883780.87     10088703.06      2884426.92     10086981.74
      2884441.25     10082398.63
#Sta/Elev= 30
  2268.7 1315.32    2506 1298.76  2676.9 1297.43  3018.5 1303.54    3531 1280.89
  4275.3 1262.92  4405.3 1252.73  4755.3 1206.34  4795.3 1193.92  4815.3  1175.2
  4835.3 1157.45    4875 1151.87  5135.3 1153.35  5285.3 1175.98  5295.3 1176.96
  5390.5 1185.38  5565.3 1202.25  5769.9 1214.93  6205.9 1236.73  6756.7 1251.53
  6847.8 1253.71  6866.4 1254.34  7315.3 1271.15  7375.3 1278.35  7635.3 1294.16
  7905.3 1321.54  8155.3 1338.01  8295.3 1351.51  8575.3 1369.53  8690.4 1370.88
#Mann= 8 ,-1 , 0
  2268.7      .1       0  4815.3     .05       0  5295.3      .1       0
  5390.5     .16       0  5769.9      .1       0  6756.7     .16       0
  6847.8      .1       0  6866.4     .16       0
Bank Sta=4815.3,5285.3
XS Rating Curve= 0 ,0
Exp/Cntr=0.3,0.1

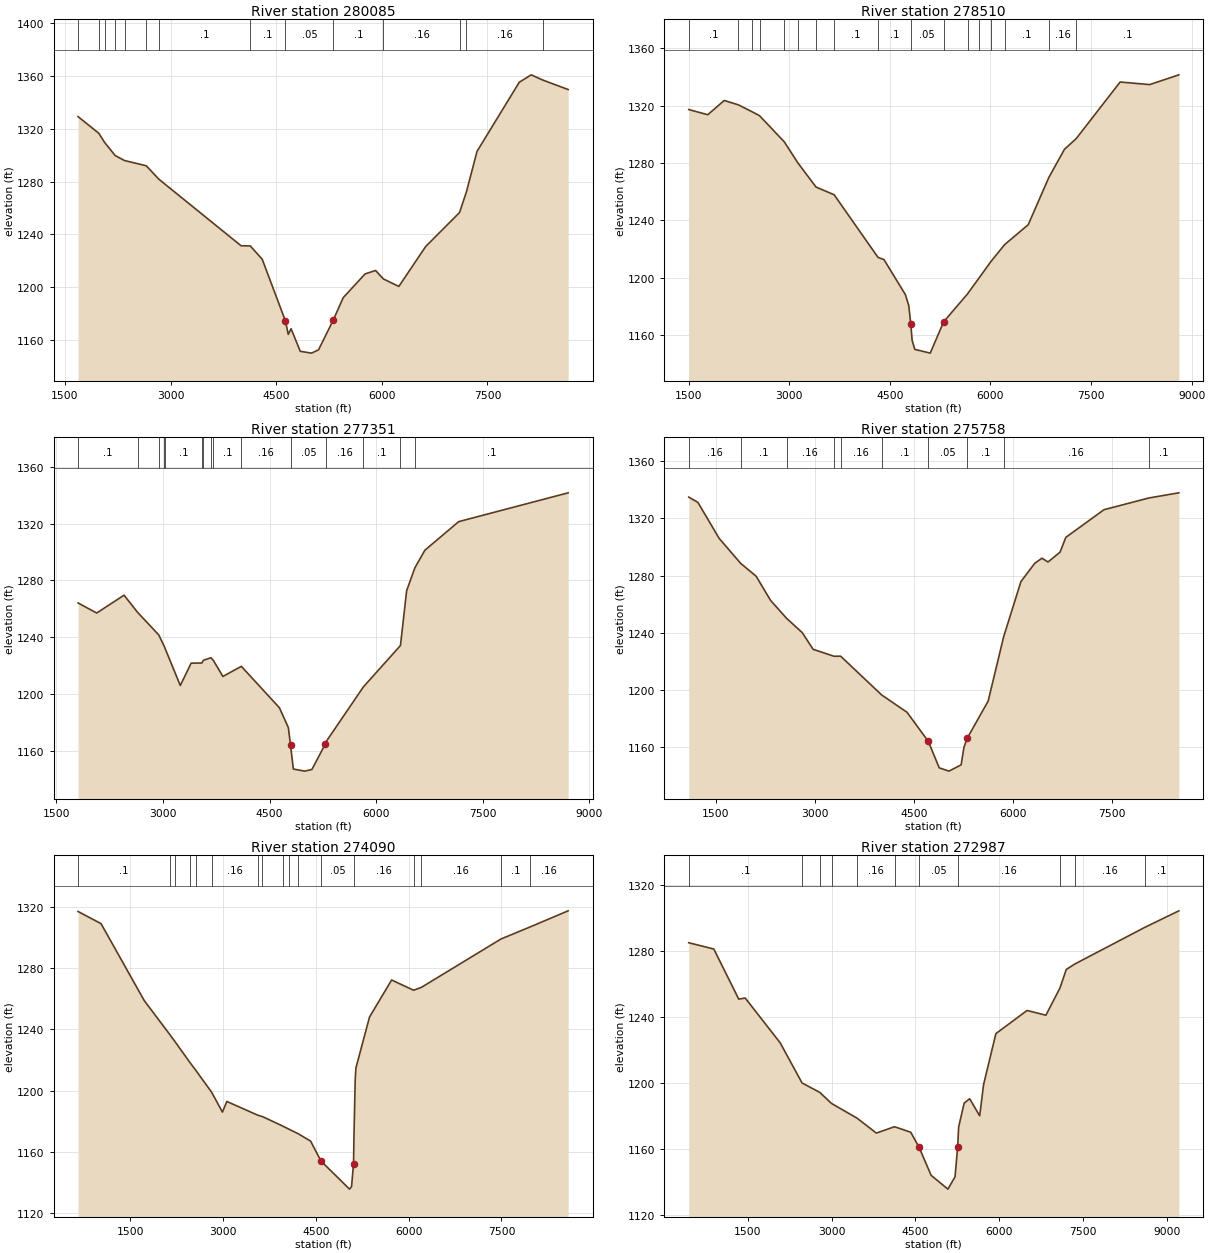
Type RM Length L Ch R = 1 ,280085  ,1575,1575,1575
BEGIN DESCRIPTION:
Mapping XS c240b7b2
END DESCRIPTION:
XS GIS Cut Line= 2
      2885457.45     10089598.56      2885438.32     10082639.88
#Sta/Elev= 30
    1687 1329.34  1981.1 1316.73  2067.3 1309.55  2214.9 1299.77  2346.8 1296.04
  2655.6 1292.05  2835.5 1281.83  4001.8  1231.4  4131.8 1231.28  4301.8 1221.22
  4631.8 1174.36  4671.8 1164.22  4711.8  1168.5  4841.8 1151.39  5001.6 1149.99
  5101.8  1152.5  5311.8 1175.19  5451.8 1192.03  5761.8 1210.03  5911.8 1212.66
  6021.8 1206.25  6241.8 1200.57  6621.8 1230.76  7104.1 1256.62  7202.4 1272.48
  7351.8 1302.95  7951.8  1355.4  8121.8 1361.02  8282.9 1357.11  8645.7 1349.87
#Mann= 14 ,-1 , 0
    1687      .1       0  1981.1     .16       0  2067.3      .1       0
  2214.9     .16       0  2346.8      .1       0  2655.6     .16       0
  2835.5      .1       0  4131.8      .1       0  4631.8     .05       0
  5311.8      .1       0  6021.8     .16       0  7104.1     .05       0
  7202.4     .16       0  8282.9      .1       0
Bank Sta=4631.8,5311.8
XS Rating Curve= 0 ,0
Exp/Cntr=0.3,0.1

Type RM Length L Ch R = 1 ,278510  ,1159,1159,1159
BEGIN DESCRIPTION:
Mapping XS 6115e061
END DESCRIPTION:
XS GIS Cut Line= 3
      2885936.27     10089625.26      2887039.59     10087992.85
      2886938.13     10082658.51
#Sta/Elev= 30
  1503.1 1317.33  1786.2 1313.72  2031.9 1323.66  2243.6  1320.6  2442.5 1315.89
  2557.9 1313.05  2926.8 1294.83  3130.1  1280.1  3399.7 1263.27  3670.5 1257.87
  4324.5 1214.16  4412.7 1212.65  4732.7 1188.18  4782.8 1180.43  4812.8 1167.57
  4832.8 1156.33  4872.8    1150  5102.6 1147.37  5302.8 1169.22  5659.3 1188.76
  5833.7 1200.02  6011.7 1211.55  6213.5 1223.18  6563.1 1236.96  6873.2 1270.19
  7103.2 1289.58  7279.6 1297.11  7933.3 1336.55  8373.4 1334.74  8808.7 1341.56
#Mann= 17 ,-1 , 0
  1503.1      .1       0  2243.6     .16       0  2442.5      .1       0
  2557.9      .1       0  2926.8     .16       0  3130.1     .16       0
  3399.7      .1       0  3670.5      .1       0  4324.5      .1       0
  4812.8     .05       0  5302.8     .16       0  5659.3      .1       0
  5833.7     .16       0  6011.7      .1       0  6213.5      .1       0
  6873.2     .16       0  7279.6      .1       0
Bank Sta=4812.8,5302.8
XS Rating Curve= 0 ,0
Exp/Cntr=0.3,0.1

Type RM Length L Ch R = 1 ,277351  ,1593,1593,1593
BEGIN DESCRIPTION:
Mapping XS 9b352956
END DESCRIPTION:
XS GIS Cut Line= 3
      2887001.43      10089409.1      2888198.51     10086923.67
      2887915.76     10082796.93
#Sta/Elev= 30
  1804.6 1264.18  2067.1 1257.07  2451.7 1269.64  2641.5 1257.61  2939.1 1241.72
  3019.4 1233.48  3031.5  1231.9    3243 1206.07  3395.8 1221.79    3546 1221.89
  3567.4 1223.79  3674.4 1225.61  3708.7 1223.69  3842.3 1212.45  4102.2 1219.54
  4637.7 1190.39  4763.7 1176.36  4793.8 1163.95  4833.9 1147.26    4994 1145.79
  5094.5 1146.95  5284.9 1164.99  5294.9 1166.56  5817.7    1205  6340.4 1234.21
  6427.6  1272.8  6542.8 1288.85  6684.2 1301.29  7159.3  1321.4  8699.7 1341.69
#Mann= 15 ,-1 , 0
  1804.6      .1       0  2641.5     .16       0  2939.1      .1       0
  3019.4     .16       0  3031.5      .1       0    3546     .16       0
  3567.4      .1       0  3674.4     .16       0  3708.7      .1       0
  4102.2     .16       0  4793.8     .05       0  5294.9     .16       0
  5817.7      .1       0  6340.4     .16       0  6542.8      .1       0
Bank Sta=4793.8,5284.9
XS Rating Curve= 0 ,0
Exp/Cntr=0.3,0.1

Type RM Length L Ch R = 1 ,275758  ,1668,1668,1668
BEGIN DESCRIPTION:
Mapping XS fc4d8844
END DESCRIPTION:
XS GIS Cut Line= 3
      2889389.57     10090042.42      2890024.21     10087550.17
      2888956.91     10082828.68
#Sta/Elev= 30
  1094.4 1334.89  1232.1 1331.24  1554.1 1306.07  1879.4 1288.62  2114.6 1279.55
  2331.3 1262.75  2574.6 1250.17  2811.7 1240.15  2975.3 1228.56  3291.5 1223.68
  3391.9 1223.73  4011.1 1196.68  4395.4 1184.54  4718.5 1164.14  4882.6 1145.71
  5030.4 1143.41  5213.7 1147.81  5256.8 1160.05  5305.2 1166.33  5622.8 1192.37
  5856.5 1237.23  6118.3 1275.87  6328.1 1288.68    6436 1292.22  6527.4 1289.53
  6710.4 1296.45  6796.8 1306.74  7373.9 1326.08  8052.9 1334.29  8506.8 1337.89
#Mann= 10 ,-1 , 0
  1094.4     .16       0  1879.4      .1       0  2574.6     .16       0
  3291.5      .1       0  3391.9     .16       0  4011.1      .1       0
  4718.5     .05       0  5305.2      .1       0  5856.5     .16       0
  8052.9      .1       0
Bank Sta=4718.5,5305.2
XS Rating Curve= 0 ,0
Exp/Cntr=0.3,0.1

Type RM Length L Ch R = 1 ,274090  ,1103,1103,1103
BEGIN DESCRIPTION:
Mapping XS 962afba4
END DESCRIPTION:
XS GIS Cut Line= 3
      2889889.74     10090027.74      2891558.39     10084756.39
      2890144.49     10082822.36
#Sta/Elev= 30
   652.9 1317.04  1024.2 1309.11  1723.7 1258.84  2145.9  1236.2  2225.7 1231.77
  2456.1 1218.77    2554 1213.49  2811.7 1199.11  2987.8 1186.06  3059.1 1192.99
  3555.5 1184.08  3634.4 1183.12  3962.6 1176.93  4064.4 1174.85  4213.1 1171.92
  4413.5  1167.1  4580.2 1154.14  5042.7 1135.75  5075.3 1137.36  5107.6 1152.35
    5115 1171.22  5134.6 1207.29  5146.4 1214.92    5366  1248.1  5723.3  1272.3
  6078.9  1265.6  6206.3 1267.52  7491.8 1299.07  7966.6    1307  8577.8 1317.46
#Mann= 17 ,-1 , 0
   652.9      .1       0  2145.9     .16       0  2225.7      .1       0
  2456.1     .16       0    2554      .1       0  2811.7     .16       0
  3555.5      .1       0  3634.4     .16       0  3962.6     .16       0
  4064.4      .1       0  4213.1     .16       0  4580.2     .05       0
    5115     .16       0  6078.9      .1       0  6206.3     .16       0
  7491.8      .1       0  7966.6     .16       0
Bank Sta=4580.2,5107.6
XS Rating Curve= 0 ,0
Exp/Cntr=0.3,0.1

Type RM Length L Ch R = 1 ,272987  ,1360,1360,1360
BEGIN DESCRIPTION:
Mapping XS 21b6a98a
END DESCRIPTION:
XS GIS Cut Line= 3
      2890451.14     10090117.94      2892743.44     10084958.38
       2890900.3     10082437.22
#Sta/Elev= 30
   445.8 1284.87   894.2 1281.06  1340.2 1250.72  1456.5 1251.35  2081.7 1224.22
  2472.8 1199.91  2789.6  1194.2  3000.8 1187.47  3455.2 1178.61  3802.7 1169.53
  4127.1 1173.39    4417 1170.05  4567.5 1160.89  4782.3 1143.94    5083 1135.57
  5210.5 1143.07    5257 1161.17  5274.8 1173.24  5373.3 1187.67  5471.8 1190.34
    5651 1179.99  5720.8 1198.92    5941 1229.81  6499.1 1243.83  6835.8 1240.96
  7086.6  1257.4  7199.9 1268.66  7351.3 1271.95  8605.8  1294.2  9214.7 1304.21
#Mann= 11 ,-1 , 0
   445.8      .1       0  2472.8     .16       0  2789.6      .1       0
  3000.8     .16       0  3455.2     .16       0  4127.1      .1       0
  4567.5     .05       0    5257     .16       0  7086.6      .1       0
  7351.3     .16       0  8605.8      .1       0
Bank Sta=4567.5,5257
XS Rating Curve= 0 ,0
Exp/Cntr=0.3,0.1

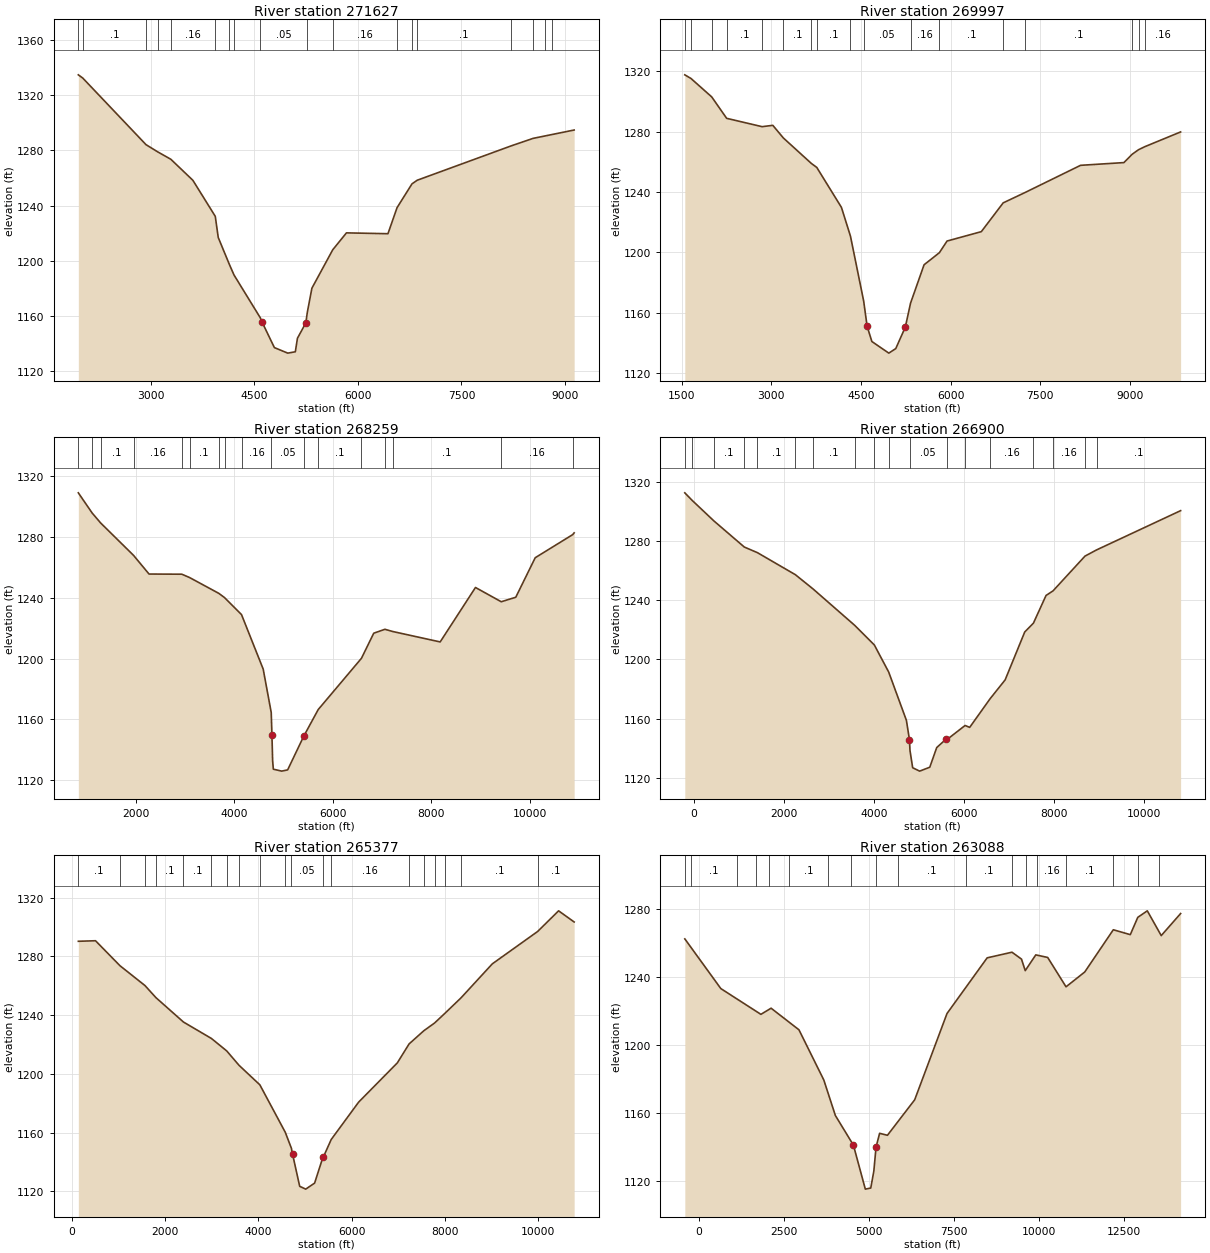
Type RM Length L Ch R = 1 ,271627  ,1630,1630,1630
BEGIN DESCRIPTION:
Mapping XS 20aac99c
END DESCRIPTION:
XS GIS Cut Line= 2
      2895204.11     10088176.03      2891361.63     10082108.13
#Sta/Elev= 30
    1950 1334.71    2014 1332.38  2930.1 1284.16  3097.3 1279.01  3290.3 1273.56
  3609.3 1258.33  3933.7 1232.25  3976.7 1216.93  4137.1 1197.53  4205.4 1189.75
  4586.5 1158.74  4607.7 1156.09  4789.9  1137.2  4983.7  1133.2  5093.3 1134.18
  5123.9 1143.97    5245 1155.05  5266.9 1162.69  5333.2 1180.21  5635.5 1208.06
  5834.1 1220.28    6435 1219.66  6566.5  1238.5  6783.1 1255.76    6859 1258.39
  8216.9 1283.21  8536.9 1288.69  8702.9 1290.38    8809 1291.46  9132.2 1294.75
#Mann= 18 ,-1 , 0
    1950     .16       0    2014      .1       0  2930.1     .16       0
  3097.3      .1       0  3290.3     .16       0  3933.7      .1       0
  4137.1     .16       0  4205.4      .1       0  4586.5     .05       0
  5266.9      .1       0  5635.5     .16       0  6566.5      .1       0
  6783.1     .16       0    6859      .1       0  8216.9     .16       0
  8536.9      .1       0  8702.9     .16       0    8809      .1       0
Bank Sta=4607.7,5245
XS Rating Curve= 0 ,0
Exp/Cntr=0.3,0.1

Type RM Length L Ch R = 1 ,269997  ,1738,1738,1738
BEGIN DESCRIPTION:
Mapping XS 833a2dfa
END DESCRIPTION:
XS GIS Cut Line= 3
      2896874.13     10087904.81      2893666.93      10082698.8
       2891699.9     10081758.38
#Sta/Elev= 30
  1554.1 1317.71    1658 1315.27  2004.4 1303.07  2254.4 1288.85  2847.5 1283.31
  3026.4  1284.2  3203.4  1275.8  3672.4 1258.88  3762.3 1256.26  4174.6 1229.76
  4325.8 1210.64  4546.6  1167.6  4604.5 1150.82  4683.8 1140.75  4967.5 1133.05
  5083.6 1136.07  5243.4 1150.32  5330.9 1166.22  5556.9 1191.67    5813 1199.68
  5941.3 1207.42  6515.1 1213.66  6880.5 1232.75  7243.2 1239.56  8175.1 1257.66
  8900.3 1259.48  9038.5 1265.01  9144.3 1268.01  9251.5 1270.06    9849 1279.82
#Mann= 17 ,-1 , 0
  1554.1      .1       0    1658     .16       0  2004.4     .16       0
  2254.4      .1       0  2847.5     .16       0  3203.4      .1       0
  3672.4     .16       0  3762.3      .1       0  4325.8      .1       0
  4546.6     .05       0  5330.9     .16       0    5813      .1       0
  6880.5     .16       0  7243.2      .1       0  9038.5     .16       0
  9144.3      .1       0  9251.5     .16       0
Bank Sta=4604.5,5243.4
XS Rating Curve= 0 ,0
Exp/Cntr=0.3,0.1

Type RM Length L Ch R = 1 ,268259  ,1359,1359,1359
BEGIN DESCRIPTION:
Mapping XS 9c8e1187
END DESCRIPTION:
XS GIS Cut Line= 5
      2898985.12     10087347.26      2897123.72     10084532.79
      2894669.09     10082523.56      2893193.68     10082213.84
      2891349.42     10081399.59
#Sta/Elev= 30
     834 1309.06  1115.5 1295.75  1287.1 1289.24  1955.7 1267.91    2270 1255.63
  2935.2 1255.53  3092.2 1253.35    3688 1242.91  3803.8 1240.12  4148.4 1228.94
  4588.5  1193.1  4751.5 1164.57 4765.91 1150.06  4780.2 1132.82  4794.5 1127.26
  4964.4 1125.98  5085.2  1126.8  5412.5 1148.99  5705.9 1166.48  6584.2  1200.2
  6833.7 1216.71  7060.7 1219.29    7216 1217.85  8182.9 1210.97  8899.9 1246.79
  9423.2 1237.41  9718.3 1240.36 10113.2 1266.37 10874.1 1281.56   10904 1282.73
#Mann= 17 ,-1 , 0
     834      .1       0  1115.5     .05       0  1287.1      .1       0
  1955.7     .16       0  2935.2      .1       0  3092.2      .1       0
    3688     .16       0  3803.8     .16       0  4148.4     .16       0
  4751.5     .05       0  5412.5     .16       0  5705.9      .1       0
  6584.2     .16       0  7060.7     .16       0    7216      .1       0
  9423.2     .16       0 10874.1      .1       0
Bank Sta=4765.91,5412.5
XS Rating Curve= 0 ,0
Exp/Cntr=0.3,0.1

Type RM Length L Ch R = 1 ,266900  ,1523,1523,1523
BEGIN DESCRIPTION:
Mapping XS be875100
END DESCRIPTION:
XS GIS Cut Line= 4
      2899887.73      10086795.8      2899359.22     10084018.48
      2893169.86     10080755.18      2892027.75     10080449.55
#Sta/Elev= 30
  -200.3 1312.42   -32.6 1307.19   448.6 1293.39  1120.7 1275.85  1411.9 1272.05
  2254.2 1257.19  2646.7 1247.57  3567.7 1223.11  4007.5 1209.76  4326.1 1191.49
  4719.1  1158.9  4786.6  1145.9  4798.2 1138.64  4858.3 1126.93  5012.8 1124.65
  5237.8 1127.28    5392 1140.55  5606.6 1146.42  5612.2 1145.78    6022 1155.45
  6123.9 1154.18  6576.6 1173.48  6910.6 1186.21  7345.4 1218.52  7538.6 1224.49
  7818.7 1243.17  7974.2 1246.28  8683.5 1269.73  8940.3  1273.9 10806.1 1300.39
#Mann= 18 ,-1 , 0
  -200.3      .1       0   -32.6     .05       0   448.6      .1       0
  1120.7      .1       0  1411.9      .1       0  2254.2     .16       0
  2646.7      .1       0  3567.7      .1       0  4007.5      .1       0
  4326.1     .16       0  4798.2     .05       0  5612.2     .16       0
    6022     .16       0  6576.6     .16       0  7538.6      .1       0
  7974.2     .16       0  8683.5     .16       0  8940.3      .1       0
Bank Sta=4786.6,5606.6
XS Rating Curve= 0 ,0
Exp/Cntr=0.3,0.1

Type RM Length L Ch R = 1 ,265377  ,2289,2289,2289
BEGIN DESCRIPTION:
Mapping XS 5a0b3115
END DESCRIPTION:
XS GIS Cut Line= 3
      2900629.37     10085211.14      2899951.65       10082425.
      2892802.15     10079421.36
#Sta/Elev= 30
   146.2  1290.3   514.4 1290.67    1039 1273.65  1574.6 1260.15    1808 1251.96
  2398.3 1235.34    2998 1224.14  3325.2 1215.67  3588.7 1205.89  4034.8  1192.6
  4579.6  1160.3  4711.2 1149.38    4735 1145.53  4888.4 1123.52  5017.8  1121.6
  5208.1  1125.7  5383.1 1143.01  5392.5 1143.24  5563.5 1155.37    6150 1180.77
  6980.7 1207.55  7232.2 1220.44    7548 1229.41  7779.1  1234.7  8004.2 1241.41
  8344.4 1251.78  9014.7 1274.93    9986 1296.97 10435.1 1311.03 10768.4 1303.44
#Mann= 19 ,-1 , 0
   146.2      .1       0    1039      .1       0  1574.6     .16       0
    1808      .1       0  2398.3      .1       0    2998     .05       0
  3325.2      .1       0  3588.7     .16       0  4034.8      .1       0
  4579.6     .16       0  4711.2     .05       0  5383.1      .1       0
  5563.5     .16       0  7232.2      .1       0    7548     .16       0
  7779.1     .16       0  8004.2      .1       0  8344.4      .1       0
    9986      .1       0
Bank Sta=4735,5392.5
XS Rating Curve= 0 ,0
Exp/Cntr=0.3,0.1

Type RM Length L Ch R = 1 ,263088  ,2551,2551,2551
BEGIN DESCRIPTION:
Mapping XS a36af871
END DESCRIPTION:
XS GIS Cut Line= 4
      2901946.32     10084470.57      2901098.96     10081361.19
      2897289.25     10077720.73      2891284.54     10076813.91
#Sta/Elev= 30
    -402  1262.4  655.63 1233.15    1833 1217.98 2132.33  1221.6 2950.78 1208.89
  3680.7 1179.35 4020.67 1158.43 4550.62 1140.99 4900.58 1115.09 5060.57 1115.74
 5150.56 1125.73  5216.1 1139.88 5320.54 1147.95 5550.52 1146.79 6350.44 1167.67
 7300.35 1218.47 8479.81 1251.24 9208.96 1254.56 9488.63 1250.49  9598.5 1243.72
 9908.14 1252.9810257.73 1251.4810797.09 1234.1911346.45 1242.9112185.47 1267.77
12684.88  1264.912904.62 1275.0813184.29 1278.9213593.81 1264.3314163.15 1277.33
#Mann= 18 ,-1 , 0
  -402.8     .16       0  -218.8      .1       0  1121.8     .05       0
  1685.2     .05       0    2060      .1       0  2668.7      .1       0
  3802.4     .16       0 4494.32     .05       0  5216.1     .16       0
    5865      .1       0  7845.8      .1       0  9207.9     .05       0
  9608.1      .1       0  9956.2     .16       0 10785.3      .1       0
 12186.1      .1       0   12905      .1       0 13529.4      .1       0
Bank Sta=4550.62,5216.1
XS Rating Curve= 0 ,0
Exp/Cntr=0.3,0.1