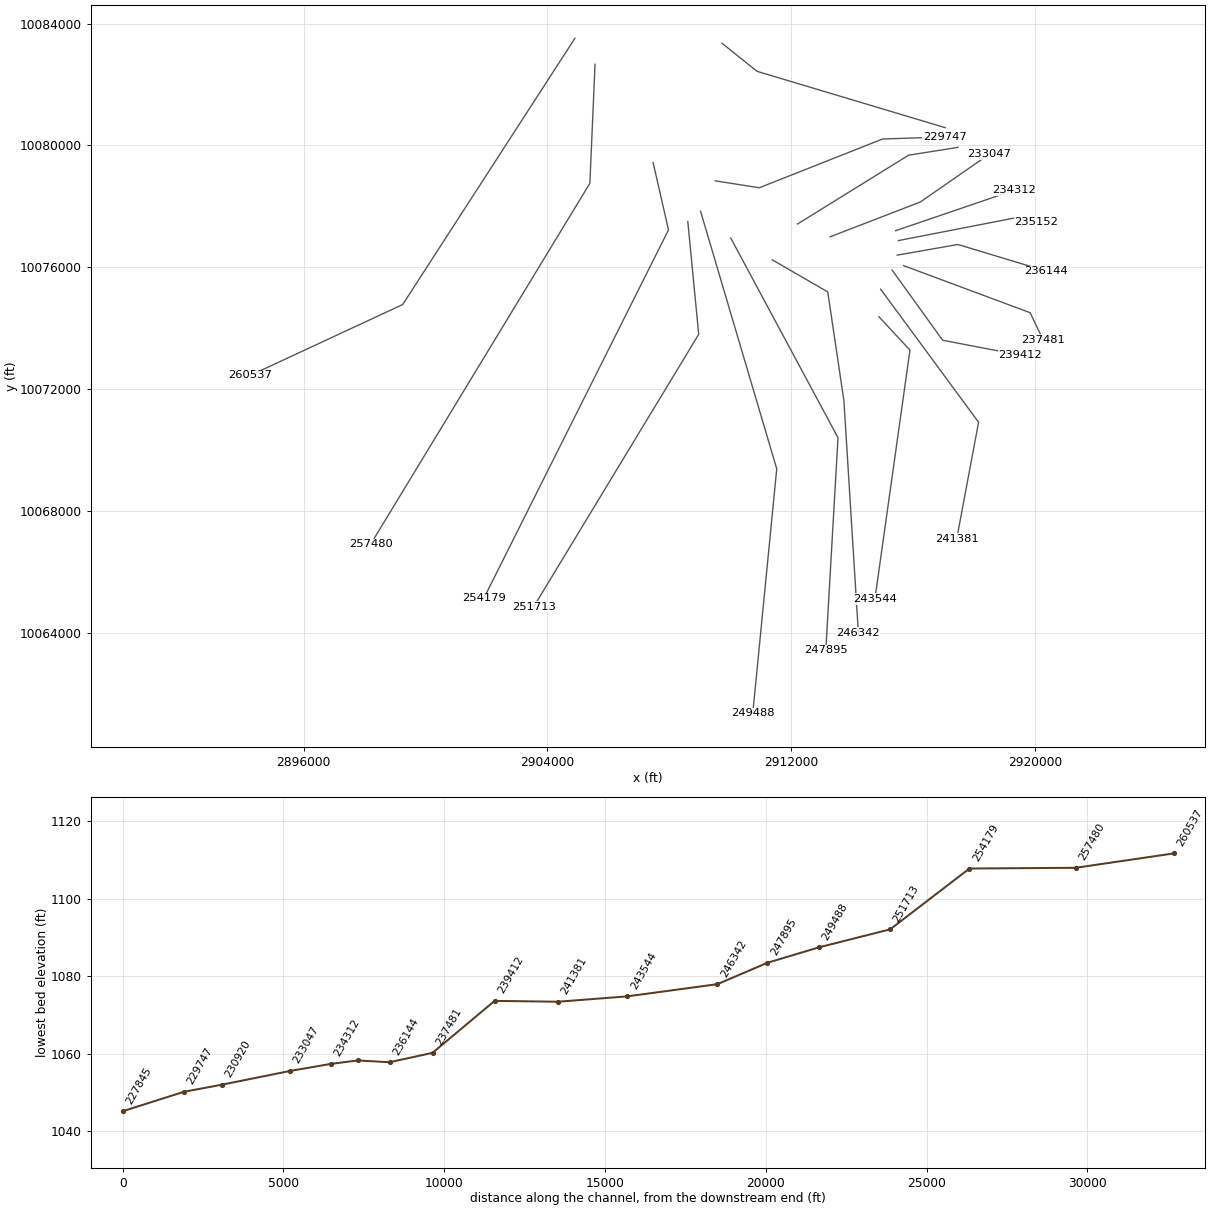
HEC-RAS study PEDERNALES RIVER.prj: PEDERNALES RIVER Base Level Engineering

--- PEDERNALES RIVER.g01 (geometry) --- (continued)

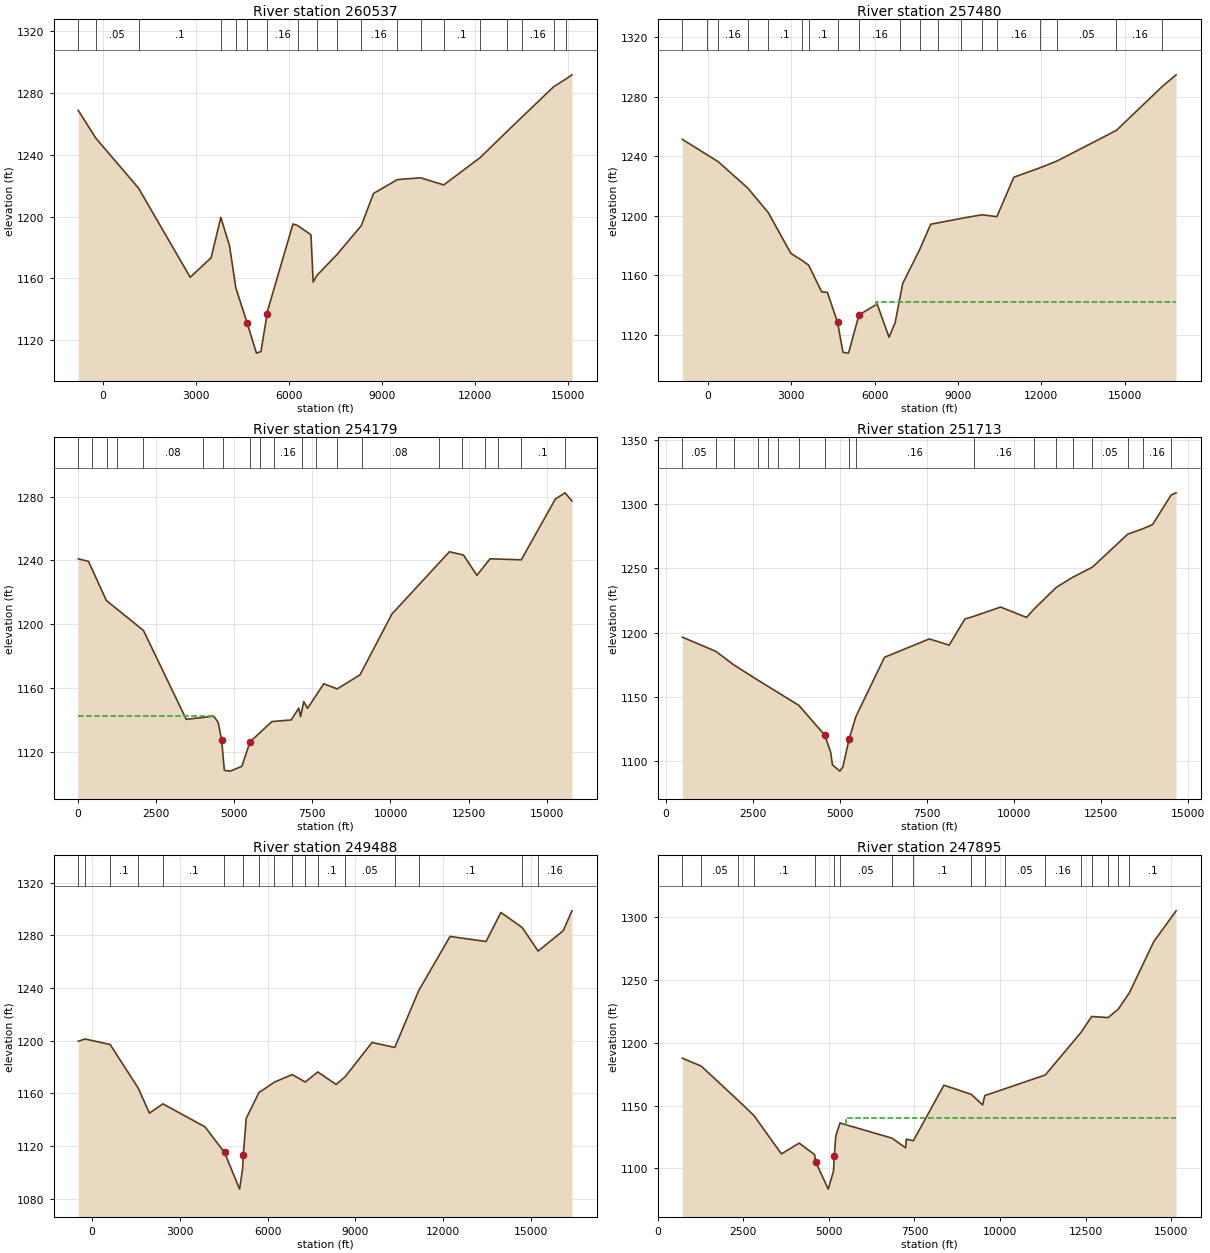
Type RM Length L Ch R = 1 ,260537  ,3057,3057,3057
BEGIN DESCRIPTION:
Mapping XS 648c867f
END DESCRIPTION:
XS GIS Cut Line= 3
      2904900.77     10083517.17      2899252.43     10074775.92
      2894254.72     10072449.07
#Sta/Elev= 30
  -783.4 1268.94  -216.9 1250.94  1161.1 1218.53  2828.6 1160.78  3502.8 1173.45
  3814.8 1199.59  4095.3 1181.26  4298.4 1153.97  4666.6 1131.05  4962.6 1111.65
    5108 1112.64  5305.4 1136.75  5316.6 1138.65  6141.8 1195.32    6291 1194.34
  6721.5 1188.32  6792.9 1157.64  6910.3 1161.92  7566.4 1175.63  8344.2 1194.22
  8738.6 1215.06    9508 1224.07 10257.3 1225.23   11005 1220.62 12181.1 1238.36
 13053.4 1255.44 13541.5 1264.84 14544.8 1284.16 14952.9 1289.38 15136.8 1291.93
#Mann= 19 ,-1 , 0
  -783.4      .1       0  -216.9     .05       0  1161.1      .1       0
  3814.8      .1       0  4298.4     .16       0  4666.6     .05       0
  5316.6     .16       0    6291      .1       0  6910.3     .16       0
  7566.4      .1       0  8344.2     .16       0    9508      .1       0
 10257.3     .05       0   11005      .1       0 12181.1      .1       0
 13053.4     .05       0 13541.5     .16       0 14544.8      .1       0
 14952.9     .05       0
Bank Sta=4666.6,5305.4
XS Rating Curve= 0 ,0
Exp/Cntr=0.3,0.1

Type RM Length L Ch R = 1 ,257480  ,3301,3301,3301
BEGIN DESCRIPTION:
Mapping XS 02f041a1
END DESCRIPTION:
XS GIS Cut Line= 3
      2905562.24     10082665.92      2905393.09     10078757.46
       2898203.7     10066908.27
#Sta/Elev= 30
    -923 1251.28   -48.5 1241.12   374.7 1236.21  1428.1 1218.68  2171.1 1202.14
  2984.2  1174.8  3366.6 1170.33  3621.9 1166.95    4093 1149.04  4298.5 1148.64
  4662.9 1128.65 4858.89 1108.48 5058.77 1107.94  5434.5 1133.53 6088.13 1140.85
 6517.86 1118.64 6737.72 1128.41 7007.55 1154.58  7617.6 1177.29  8018.6 1194.38
  8272.2 1195.28  9123.1  1198.3  9861.2  1200.7 10399.2 1199.45 11009.8 1225.89
 11962.4 1232.28 12565.5 1236.78 14702.8  1257.3 16356.1 1286.79 16848.8 1294.54
#Mann= 19 ,-1 , 0
    -923     .16       0   -48.5      .1       0   374.7     .16       0
  1428.1     .16       0  2171.1      .1       0  3366.6     .16       0
  3621.9      .1       0  4662.9     .05       0  5434.5     .16       0
  6909.1      .1       0  7617.6     .16       0  8272.2     .16       0
  9123.1      .1       0  9861.2      .1       0 10399.2     .16       0
 11962.4     .16       0 12565.5     .05       0 14702.8     .16       0
 16356.1     .16       0
#XS Ineff= 2 , 0
                         6036.93         1142.05
Permanent Ineff=
       F       F
Bank Sta=4662.9,5434.5
XS Rating Curve= 0 ,0
Exp/Cntr=0.3,0.1

Type RM Length L Ch R = 1 ,254179  ,2466,2466,2466
BEGIN DESCRIPTION:
Mapping XS a5f67f4f
END DESCRIPTION:
XS GIS Cut Line= 3
      2907468.19     10079433.95      2907972.68     10077226.52
      2901914.03     10065129.34
#Sta/Elev= 30
      12 1240.95  341.18 1239.28  909.75  1214.8 2096.78 1196.01 3466.31 1140.24
 4346.28 1142.21 4486.28 1138.42  4597.1 1127.52 4686.27 1108.26 4876.27 1107.75
 5246.25  1110.8 5506.24 1126.07 6206.22 1138.84  6826.2 1139.87 7066.19 1147.29
 7126.19 1141.94 7226.18 1151.41 7346.18 1147.14 7866.16 1162.55 8296.15 1159.33
 9026.14 1168.1410046.12 1206.28 11886.1 1245.3712336.09 1243.3212766.09 1230.57
13186.08 1240.9514186.07 1240.3115276.06 1278.4415586.05 1282.3315806.05 1277.25
#Mann= 20 ,-1 , 0
    10.5      .1       0   439.6     .05       0   927.4     .16       0
  1258.6      .1       0    2074     .08       0  4018.3     .08       0
    4649     .05       0 5506.24     .05       0  5821.9     .16       0
  6288.4     .16       0  7165.1     .05       0  7614.7     .05       0
    8289     .08       0  9075.8     .08       0 11548.4      .1       0
 12297.7     .16       0 13009.5     .16       0 13452.4     .05       0
 14180.2      .1       0 15579.7     .16       0
#XS Ineff= 2 , 0
         4318.18 1142.58
Permanent Ineff=
       F       F
Bank Sta=4597.1,5506.24
XS Rating Curve= 0 ,0
Exp/Cntr=0.3,0.1

Type RM Length L Ch R = 1 ,251713  ,2225,2225,2225
BEGIN DESCRIPTION:
Mapping XS 12a5855c
END DESCRIPTION:
XS GIS Cut Line= 3
      2908605.46     10077499.87      2908963.35     10073795.85
      2903552.63     10064855.53
#Sta/Elev= 30
   479.9 1196.44  1444.2 1185.37  1949.2 1175.02  2658.5 1162.82  2951.1 1157.92
  3223.5 1153.36  3827.3 1143.26  4569.9 1120.04  4738.6 1106.62  4788.1 1097.02
  4998.3 1092.07  5087.8 1095.38  5268.2 1117.18    5463 1134.69  6282.6 1180.78
    7570  1195.1  8138.9 1190.26    8589  1210.6  8851.7 1212.75  9615.5 1219.92
 10359.9 1211.85 10576.9 1218.43 11215.7 1235.29 11690.3  1243.2 12248.7 1250.97
 13265.5 1276.74 13698.4 1280.92 13977.5  1284.2 14511.5  1307.3 14651.3 1308.93
#Mann= 18 ,-1 , 0
   479.9     .05       0  1444.2      .1       0  1949.2     .05       0
  2658.5      .1       0  2951.1     .05       0  3223.5      .1       0
  3827.3     .16       0  4569.9     .05       0  5268.2      .1       0
    5463     .16       0  8851.7     .16       0 10576.9     .05       0
 11215.7      .1       0 11690.3      .1       0 12248.7     .05       0
 13265.5      .1       0 13698.4     .16       0 14511.5     .05       0
Bank Sta=4569.9,5268.2
XS Rating Curve= 0 ,0
Exp/Cntr=0.3,0.1

Type RM Length L Ch R = 1 ,249488  ,1593,1593,1593
BEGIN DESCRIPTION:
Mapping XS 34fc0573
END DESCRIPTION:
XS GIS Cut Line= 3
      2909024.23     10077838.41      2911523.82     10069379.15
      2910736.81     10061348.55
#Sta/Elev= 30
  -476.6 1199.66  -239.3 1201.35   614.1  1197.2  1577.2 1164.06  1959.4 1145.09
  2421.7 1152.12  3861.1 1134.66    4523 1115.39    4530 1115.21  5044.1  1087.4
  5148.7 1103.15  5170.9 1113.68  5270.7 1141.08  5702.3  1160.6  6235.9  1168.6
  6843.6 1174.35  7292.3  1168.7  7718.6 1176.35  8346.2 1166.87  8660.1 1172.83
  9574.3 1198.71 10354.1 1194.96 11170.8 1238.03 12243.6 1279.21 13476.7 1275.35
 13984.2 1297.42 14713.5 1285.93 15257.2  1268.1 16116.7 1283.54 16413.3 1298.64
#Mann= 17 ,-1 , 0
  -476.6     .05       0  -239.3     .05       0   614.1      .1       0
  1577.2     .16       0  2421.7      .1       0    4523     .05       0
  5148.7     .16       0  5702.3      .1       0  6235.9      .1       0
  6843.6     .05       0  7292.3      .1       0  7718.6      .1       0
  8660.1     .05       0 10354.1      .1       0 11170.8      .1       0
 14713.5      .1       0 15257.2     .16       0
Bank Sta=4530,5170.9
XS Rating Curve= 0 ,0
Exp/Cntr=0.3,0.1

Type RM Length L Ch R = 1 ,247895  ,1553,1553,1553
BEGIN DESCRIPTION:
Mapping XS 123fdf3d
END DESCRIPTION:
XS GIS Cut Line= 3
      2910015.82     10076955.53      2913533.76     10070401.22
      2913133.41     10063419.73
#Sta/Elev= 30
   714.7  1187.7  1265.6  1181.4  2345.7 1154.08  2801.2 1142.24  3611.6  1111.5
  4131.2 1120.07  4580.2 1110.91  4609.6 1105.25  4979.5 1083.44  5133.2 1097.85
  5155.1 1109.78  5199.7 1125.79  5323.4 1136.08  6845.2    1124  7240.3 1116.35
  7262.2 1123.26  7466.6 1121.97  8361.3 1166.21  9161.9 1158.88  9493.1 1150.48
  9554.9 1157.91 10147.3 1163.38 11325.7 1174.34 12370.6  1208.3 12679.9 1220.89
 13160.8 1220.03   13457 1226.71 13781.1 1239.68 14491.3  1280.3 15146.4 1305.02
#Mann= 18 ,-1 , 0
   714.7     .05       0  1265.6     .05       0  2345.7      .1       0
  2801.2      .1       0  4580.2     .05       0  5133.2     .16       0
  5323.4     .05       0  6845.2     .05       0  7466.6      .1       0
  9161.9     .16       0  9554.9      .1       0 10147.3     .05       0
 11325.7     .16       0 12370.6     .16       0 12679.9      .1       0
 13160.8     .16       0   13457      .1       0 13781.1      .1       0
#XS Ineff= 2 , 0
                         5490.91         1139.74
Permanent Ineff=
       F       F
Bank Sta=4609.6,5155.1
XS Rating Curve= 0 ,0
Exp/Cntr=0.3,0.1

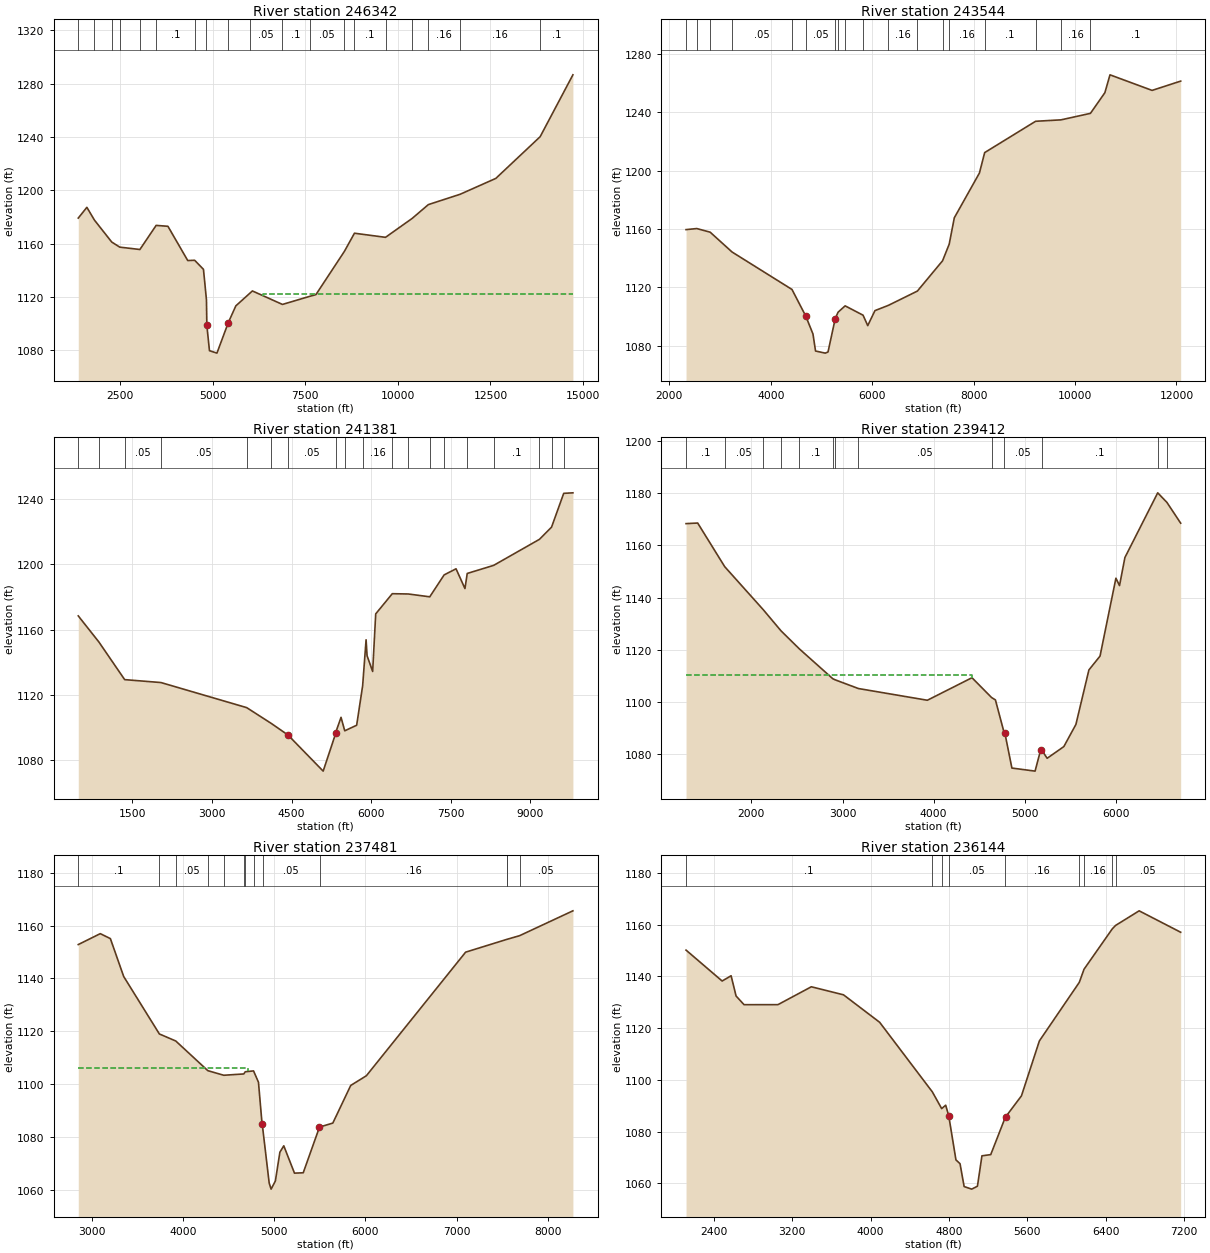
Type RM Length L Ch R = 1 ,246342  ,2798,2798,2798
BEGIN DESCRIPTION:
Mapping XS c0ef7d5f
END DESCRIPTION:
XS GIS Cut Line= 4
      2911378.73     10076243.07      2913197.28     10075188.92
      2913727.17     10071618.91      2914202.62     10063987.11
#Sta/Elev= 30
  1369.1 1179.16  1601.4 1187.21  1806.1 1177.63  2273.5 1161.17  2490.1 1157.38
  3033.3 1155.61  3471.9 1173.67  3790.2 1173.01  4325.5 1147.32  4511.8 1147.53
  4750.1 1140.74    4831 1117.78  4841.1 1098.79  4911.9 1079.76  5113.8 1077.93
  5421.4 1100.87  5624.6 1113.37 6071.32 1124.54    6883 1114.43  7624.1 1120.53
  7786.8 1121.78  8555.1 1154.17  8827.5 1167.81  9666.4 1164.73 10386.6 1178.92
 10822.9 1189.26 11679.7 1196.99 12645.4 1208.91 13841.7 1240.14 14726.8 1286.54
#Mann= 19 ,-1 , 0
  1369.1      .1       0  1806.1     .05       0  2273.5      .1       0
  2490.1     .05       0  3033.3      .1       0  3471.9      .1       0
  4511.8     .16       0    4831     .05       0  5421.4      .1       0
  5993.8     .05       0    6883      .1       0  7624.1     .05       0
  8555.1     .16       0  8827.5      .1       0  9666.4      .1       0
 10386.6      .1       0 10822.9     .16       0 11679.7     .16       0
 13841.7      .1       0
#XS Ineff= 2 , 0
                         6363.64         1122.59
Permanent Ineff=
       F       F
Bank Sta=4841.1,5421.4
XS Rating Curve= 0 ,0
Exp/Cntr=0.3,0.1

Type RM Length L Ch R = 1 ,243544  ,2163,2163,2163
BEGIN DESCRIPTION:
Mapping XS 426d073e
END DESCRIPTION:
XS GIS Cut Line= 3
      2914873.94     10074376.15      2915894.41     10073277.49
      2914744.59     10065103.33
#Sta/Elev= 30
  2329.9 1159.49  2541.7 1160.22  2805.4 1157.74  3236.8 1144.15    4419 1118.45
  4691.5 1100.13  4832.9 1087.91  4883.4 1076.24    5075 1074.79  5129.6 1075.57
  5272.1 1098.49  5328.3 1102.88  5467.3  1107.2  5820.7  1100.8  5913.2 1093.66
  6054.8 1103.94  6320.3 1107.55  6892.1 1117.35  7388.5 1138.12  7519.3 1149.52
  7620.1  1167.6  8114.9 1198.27  8218.7 1212.31    9223 1233.78    9724 1234.76
 10304.6 1239.22 10589.3 1253.41   10690 1265.64 11520.4 1254.96   12084 1261.33
#Mann= 18 ,-1 , 0
  2329.9     .16       0  2541.7      .1       0  2805.4     .16       0
  3236.8     .05       0    4419     .16       0  4691.5     .05       0
  5272.1     .16       0  5328.3     .05       0  5467.3      .1       0
  5820.7     .16       0  6320.3     .16       0  6892.1     .16       0
  7388.5     .05       0  7519.3     .16       0  8218.7      .1       0
    9223      .1       0    9724     .16       0 10304.6      .1       0
Bank Sta=4691.5,5272.1
XS Rating Curve= 0 ,0
Exp/Cntr=0.3,0.1

Type RM Length L Ch R = 1 ,241381  ,1969,1969,1969
BEGIN DESCRIPTION:
Mapping XS 1c78f884
END DESCRIPTION:
XS GIS Cut Line= 3
      2914932.32     10075279.66      2918145.76     10070909.18
       2917428.8     10067080.82
#Sta/Elev= 30
   479.8 1168.49   868.5  1152.5  1354.1 1129.45    2038 1127.66  3653.1  1112.3
  4114.3 1102.66    4430 1095.56    5094  1073.4  5330.4 1096.57  5338.8 1097.88
  5430.7 1106.35  5500.5  1098.1  5725.1 1101.51  5837.7 1125.68  5902.6 1153.86
  5921.1 1144.09  6026.3 1134.45    6084 1169.73  6396.3 1182.09  6698.9 1181.91
  7102.3 1180.18    7373  1193.6  7597.4 1197.34  7765.4 1185.25  7808.4 1194.49
  8306.8 1199.45  9169.3  1215.4  9396.9 1222.86  9626.1 1243.56  9799.4 1243.88
#Mann= 19 ,-1 , 0
   479.8     .05       0   868.5      .1       0  1354.1     .05       0
    2038     .05       0  3653.1     .05       0  4114.3     .16       0
    4430     .05       0  5338.8     .05       0  5500.5     .05       0
  5837.7     .16       0  6396.3      .1       0  6698.9      .1       0
  7102.3     .16       0    7373      .1       0  7808.4      .1       0
  8306.8      .1       0  9169.3     .16       0  9396.9      .1       0
  9626.1     .16       0
Bank Sta=4430,5330.4
XS Rating Curve= 0 ,0
Exp/Cntr=0.3,0.1

Type RM Length L Ch R = 1 ,239412  ,1931,1931,1931
BEGIN DESCRIPTION:
Mapping XS c23ee2bb
END DESCRIPTION:
XS GIS Cut Line= 3
      2915306.55     10075909.28      2916966.84     10073603.15
      2919507.66     10073113.46
#Sta/Elev= 30
  1282.5 1168.29  1410.3 1168.51    1707 1151.82  2131.1 1135.32  2324.7 1127.29
  2526.5 1120.37  2893.3 1108.96  2920.1 1108.53  3174.7 1105.21  3931.2 1100.73
  4421.1 1109.35  4635.9 1101.77  4678.3 1100.86    4777 1087.91  4782.1 1088.16
    4859  1074.8  5113.4 1073.62  5174.7  1081.7  5184.9 1081.78    5246 1078.53
  5429.3 1083.01  5561.7 1091.48  5704.3 1112.32  5826.5 1117.62  6000.8 1147.41
  6040.4  1144.6  6099.5 1155.32  6459.7 1180.07    6561 1176.39  6711.7 1168.46
#Mann= 13 ,-1 , 0
  1282.5      .1       0    1707     .05       0  2131.1      .1       0
  2324.7     .05       0  2526.5      .1       0  2893.3     .05       0
  2920.1      .1       0  3174.7     .05       0  4635.9      .1       0
    4777     .05       0  5184.9      .1       0  6459.7     .05       0
    6561      .1       0
#XS Ineff= 2 , 0
         4426.14 1110.29
Permanent Ineff=
       F       F
Bank Sta=4782.1,5174.7
XS Rating Curve= 0 ,0
Exp/Cntr=0.3,0.1

Type RM Length L Ch R = 1 ,237481  ,1337,1337,1337
BEGIN DESCRIPTION:
Mapping XS cc62e269
END DESCRIPTION:
XS GIS Cut Line= 3
      2915686.76     10076052.81       2919837.8     10074506.45
      2920265.51     10073608.86
#Sta/Elev= 30
  2850.6 1152.82    3092 1156.95  3202.6 1155.07  3348.9 1140.71  3739.9 1118.97
  3919.5 1116.31  4271.1 1105.08  4446.3 1103.33  4665.7 1103.83  4681.5 1104.65
  4772.7 1104.98  4826.6 1100.68  4865.7 1085.01  4871.1  1083.9    4944 1062.54
  4965.1 1060.22    5012 1063.31  5061.4 1074.19  5104.1 1076.62  5221.5 1066.27
  5317.5 1066.41  5495.6  1083.7    5501 1083.76    5642 1085.23  5838.3 1099.48
  6009.6 1103.14  7098.1 1149.94  7550.9 1154.79    7690 1156.18  8274.6 1165.59
#Mann= 13 ,-1 , 0
  2850.6      .1       0  3739.9     .05       0  3919.5     .05       0
  4271.1      .1       0  4446.3     .05       0  4665.7     .16       0
  4681.5      .1       0  4772.7     .16       0  4871.1     .05       0
    5501     .16       0  7550.9     .05       0  7550.9     .16       0
    7690     .05       0
#XS Ineff= 2 , 0
          4712.5 1106.26
Permanent Ineff=
       F       F
Bank Sta=4865.7,5495.6
XS Rating Curve= 0 ,0
Exp/Cntr=0.3,0.1

Type RM Length L Ch R = 1 ,236144  ,992,992,992
BEGIN DESCRIPTION:
Mapping XS 55091ab8
END DESCRIPTION:
XS GIS Cut Line= 3
      2915475.51     10076397.16      2917467.78     10076747.12
      2920364.21     10075871.38
#Sta/Elev= 30
  2116.3 1150.17  2484.8 1138.22  2576.2 1140.26    2627 1132.43  2708.3 1129.08
  3054.3 1129.09  3395.2    1136  3723.5 1132.89  4092.3 1122.28  4630.8 1095.35
  4725.4 1088.92  4766.6 1090.24    4798 1086.07  4871.1  1069.1  4912.9 1067.62
  4954.7 1058.79  5032.2  1057.8  5090.5 1058.93  5136.5 1070.67  5226.3 1071.14
  5372.4 1085.31  5377.6 1085.68  5539.7 1093.84  5722.7 1115.07  6130.4 1137.72
  6178.2 1142.76  6467.5 1158.41  6500.8 1159.71  6741.1 1165.35    7165 1157.07
#Mann= 9 ,-1 , 0
  2116.3      .1       0  4630.8     .16       0  4725.4      .1       0
    4798     .05       0  5372.4     .16       0  6130.4      .1       0
  6178.2     .16       0  6467.5      .1       0  6500.8     .05       0
Bank Sta=4798,5377.6
XS Rating Curve= 0 ,0
Exp/Cntr=0.3,0.1

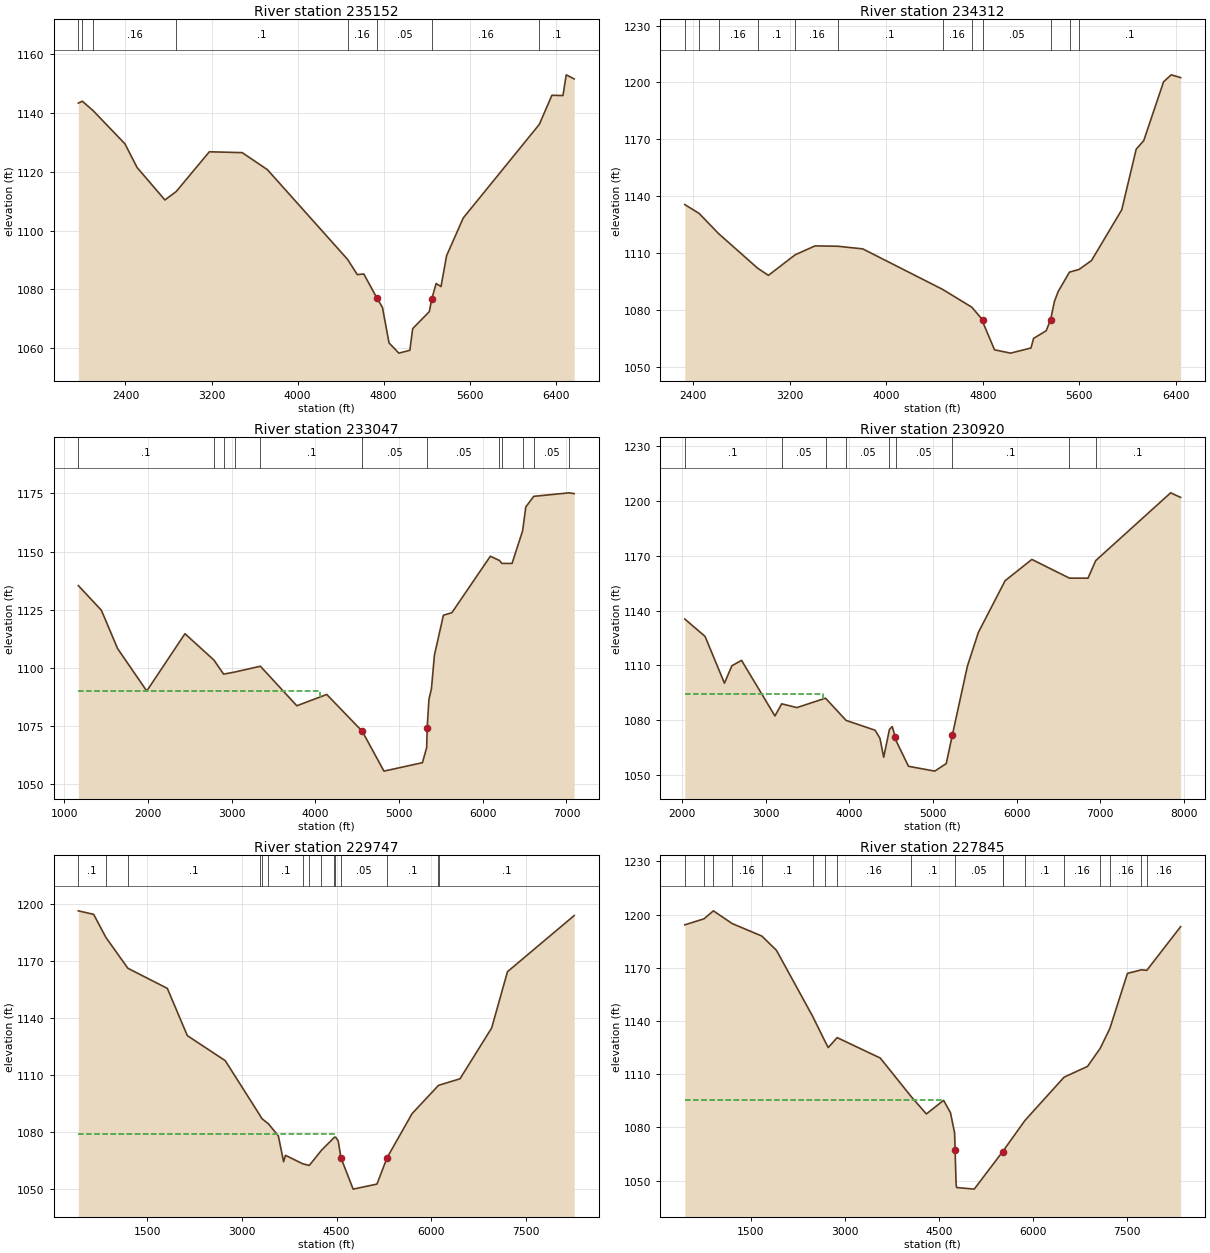
Type RM Length L Ch R = 1 ,235152  ,840,840,840
BEGIN DESCRIPTION:
Mapping XS bed8fc4b
END DESCRIPTION:
XS GIS Cut Line= 3
      2915513.01     10076875.06      2919323.49     10077616.26
       2920041.1     10077494.86
#Sta/Elev= 30
  1961.6  1143.4  1998.3 1144.06    2098 1140.88  2394.9 1129.54  2508.4 1121.45
  2766.6 1110.42  2872.3 1113.32  3179.5 1126.83  3485.1 1126.54  3719.4 1120.74
  4465.8 1090.14  4554.8    1085  4615.9 1085.21  4738.1 1076.97  4789.1 1073.83
  4850.2 1061.73  4941.6 1058.25  5043.8 1059.21    5070  1066.6    5225  1072.4
  5247.5  1076.7  5288.3 1081.97  5333.4 1080.92  5385.1 1091.42    5540 1104.27
  6247.6 1136.18  6364.5 1146.08  6467.2 1145.98  6497.6 1153.04  6571.3 1151.65
#Mann= 8 ,-1 , 0
  1961.6     .16       0  1998.3     .05       0    2098     .16       0
  2872.3      .1       0  4465.8     .16       0  4738.1     .05       0
  5247.5     .16       0  6247.6      .1       0
Bank Sta=4738.1,5247.5
XS Rating Curve= 0 ,0
Exp/Cntr=0.3,0.1

Type RM Length L Ch R = 1 ,234312  ,1265,1265,1265
BEGIN DESCRIPTION:
Mapping XS 32d64fca
END DESCRIPTION:
XS GIS Cut Line= 2
      2915422.27     10077199.49       2919312.3      10078527.6
#Sta/Elev= 30
  2328.9 1135.65  2446.9 1131.02  2609.8  1120.3  2933.7 1102.07  3022.3 1098.35
  3244.3  1109.2  3408.9 1113.87  3598.5 1113.68  3804.2  1112.3  4465.4 1090.98
  4707.8 1081.59  4797.4 1074.94  4802.7 1073.22  4896.6 1059.11  5029.7 1057.36
    5199 1060.07  5220.2 1065.12  5324.6 1069.12  5361.2 1074.91  5392.6 1084.46
  5423.9 1089.79  5518.2 1100.06  5597.2 1101.46  5700.5 1106.15  5951.1 1132.86
  6071.1 1164.82  6133.8 1169.37    6298 1200.34  6361.4 1204.02  6439.4 1202.56
#Mann= 12 ,-1 , 0
  2328.9     .16       0  2446.9      .1       0  2609.8     .16       0
  2933.7      .1       0  3244.3     .16       0  3598.5      .1       0
  4465.4     .16       0  4707.8      .1       0  4802.7     .05       0
  5361.2      .1       0  5518.2     .05       0  5597.2      .1       0
Bank Sta=4797.4,5361.2
XS Rating Curve= 0 ,0
Exp/Cntr=0.3,0.1

Type RM Length L Ch R = 1 ,233047  ,2127,2127,2127
BEGIN DESCRIPTION:
Mapping XS 1c776ee1
END DESCRIPTION:
XS GIS Cut Line= 3
       2913276.2     10076999.55      2916235.35     10078142.64
      2918494.15     10079710.73
#Sta/Elev= 30
  1169.8 1135.37  1445.3 1124.73  1638.9 1108.26    1987 1090.01  2443.3 1114.65
  2789.4 1103.32  2904.9 1097.27  3037.5 1098.16  3344.2 1100.66  3779.4 1083.66
  4136.7 1088.52    4561 1072.68  4820.1 1055.54  5279.6 1059.17  5330.3  1065.7
  5336.4 1074.22  5357.3 1086.44    5387 1090.91  5422.8 1105.44  5530.2 1122.59
  5631.5  1123.7  6090.8 1147.99    6200 1146.14  6228.1 1144.89  6350.1 1144.89
  6476.4 1158.95  6514.2 1169.19  6609.6 1173.75  7031.5 1175.26  7091.8 1174.91
#Mann= 12 ,-1 , 0
  1169.8      .1       0  2789.4     .05       0  2904.9      .1       0
  3037.5     .16       0  3344.2      .1       0    4561     .05       0
  5336.4     .05       0    6200      .1       0  6228.1     .05       0
  6476.4      .1       0  6609.6     .05       0  7031.5      .1       0
#XS Ineff= 2 , 0
         4050.57 1089.94
Permanent Ineff=
       F       F
Bank Sta=4561,5336.4
XS Rating Curve= 0 ,0
Exp/Cntr=0.3,0.1

Type RM Length L Ch R = 1 ,230920  ,1173,1173,1173
BEGIN DESCRIPTION:
Mapping XS 7631730a
END DESCRIPTION:
XS GIS Cut Line= 3
      2912207.63     10077420.49      2915847.58     10079678.72
      2917472.07     10079937.36
#Sta/Elev= 30
  2033.1 1135.37  2275.8 1125.83  2507.3 1100.19  2595.9 1109.75  2711.7 1112.71
  3110.9 1082.25  3191.7 1088.88  3373.2 1086.82  3715.6 1091.98  3961.7  1079.8
  4308.6 1074.41  4366.5 1069.98  4411.3 1059.61    4480 1074.85    4513 1076.41
  4549.6 1070.94  4555.5 1069.02  4707.8 1054.65  5021.8 1051.99  5159.1 1056.12
  5232.3 1071.81  5411.8 1109.48  5542.9    1128    5863 1156.37  6183.1 1168.04
  6631.6 1157.79  6854.2 1157.76  6946.4  1167.4  7842.3 1204.55  7961.6 1202.05
#Mann= 9 ,-1 , 0
  2033.1      .1       0  3191.7     .05       0  3715.6      .1       0
  3961.7     .05       0    4480     .16       0  4555.5     .05       0
  5232.3      .1       0  6631.6     .05       0  6946.4      .1       0
#XS Ineff= 2 , 0
         3684.09 1094.52
Permanent Ineff=
       F       F
Bank Sta=4549.6,5232.3
XS Rating Curve= 0 ,0
Exp/Cntr=0.3,0.1

Type RM Length L Ch R = 1 ,229747  ,1902,1902,1902
BEGIN DESCRIPTION:
Mapping XS e6b95da8
END DESCRIPTION:
XS GIS Cut Line= 4
      2909507.91      10078837.1      2910952.38     10078609.97
      2914994.68     10080210.81      2917033.67     10080279.21
#Sta/Elev= 30
   411.7 1196.17   654.4 1194.31   846.6  1182.3  1195.9 1166.04  1820.9 1155.48
  2137.7 1130.69  2737.6 1117.57  3283.1 1089.11  3317.9 1087.16  3422.3 1084.39
    3578 1078.12  3661.8 1064.56  3691.5  1067.9  3965.2 1063.46  4067.6 1062.59
  4261.5 1070.56  4464.4  1077.3    4480 1077.67  4526.3 1075.47  4569.4 1066.62
  4762.7 1050.17  5139.4 1052.81  5300.7 1066.71  5696.7 1089.82  6112.6 1104.55
  6114.8 1104.61  6454.3 1108.05  6955.9 1134.72    7206 1164.23  8261.8 1193.68
#Mann= 15 ,-1 , 0
   411.7      .1       0   846.6     .05       0  1195.9      .1       0
  3283.1     .05       0  3317.9     .16       0  3422.3      .1       0
  3965.2     .05       0  4067.6      .1       0  4261.5     .05       0
  4464.4      .1       0    4480     .05       0  4569.4     .05       0
  5300.7      .1       0  6112.6     .05       0  6114.8      .1       0
#XS Ineff= 2 , 0
         4477.27 1078.85
Permanent Ineff=
       F       F
Bank Sta=4569.4,5300.7
XS Rating Curve= 0 ,0
Exp/Cntr=0.3,0.1

Type RM Length L Ch R = 1 ,227845  ,1435,1435,1435
BEGIN DESCRIPTION:
Mapping XS ffaed9bf
END DESCRIPTION:
XS GIS Cut Line= 3
      2909730.33     10083353.82      2910877.68     10082433.77
      2917051.75     10080583.28
#Sta/Elev= 30
   444.9 1194.25   752.1 1197.66   901.4 1202.16    1200    1195  1675.5 1187.92
  1908.9 1179.85  2485.8 1142.68  2676.4 1129.03  2735.1 1125.01  2877.2 1130.63
  3565.4 1119.12  4064.2 1097.15  4301.7 1087.59  4576.8 1095.24  4686.4 1088.28
  4752.6 1076.88 4760.42 1067.18  4776.8 1047.45  4785.7 1046.07  5065.7 1045.16
  5520.7 1066.37  5875.1 1083.88  6500.5 1108.33  6874.5 1114.38  7076.6 1124.56
  7230.9 1135.77    7512 1166.86  7735.7 1168.88  7820.8 1168.58    8361 1193.22
#Mann= 19 ,-1 , 0
   444.9      .1       0   752.1     .05       0   901.4      .1       0
    1200     .16       0  1675.5      .1       0  2485.8     .05       0
  2676.4      .1       0  2877.2     .16       0  4064.2      .1       0
  4752.6     .05       0  5520.7     .05       0  5520.7      .1       0
  5520.7     .16       0  5875.1      .1       0  6500.5     .16       0
  7076.6      .1       0  7230.9     .16       0  7735.7      .1       0
  7820.8     .16       0
#XS Ineff= 2 , 0
         4585.23 1095.64
Permanent Ineff=
       F       F
Bank Sta=4760.42,5520.7
XS Rating Curve= 0 ,0
Exp/Cntr=0.3,0.1