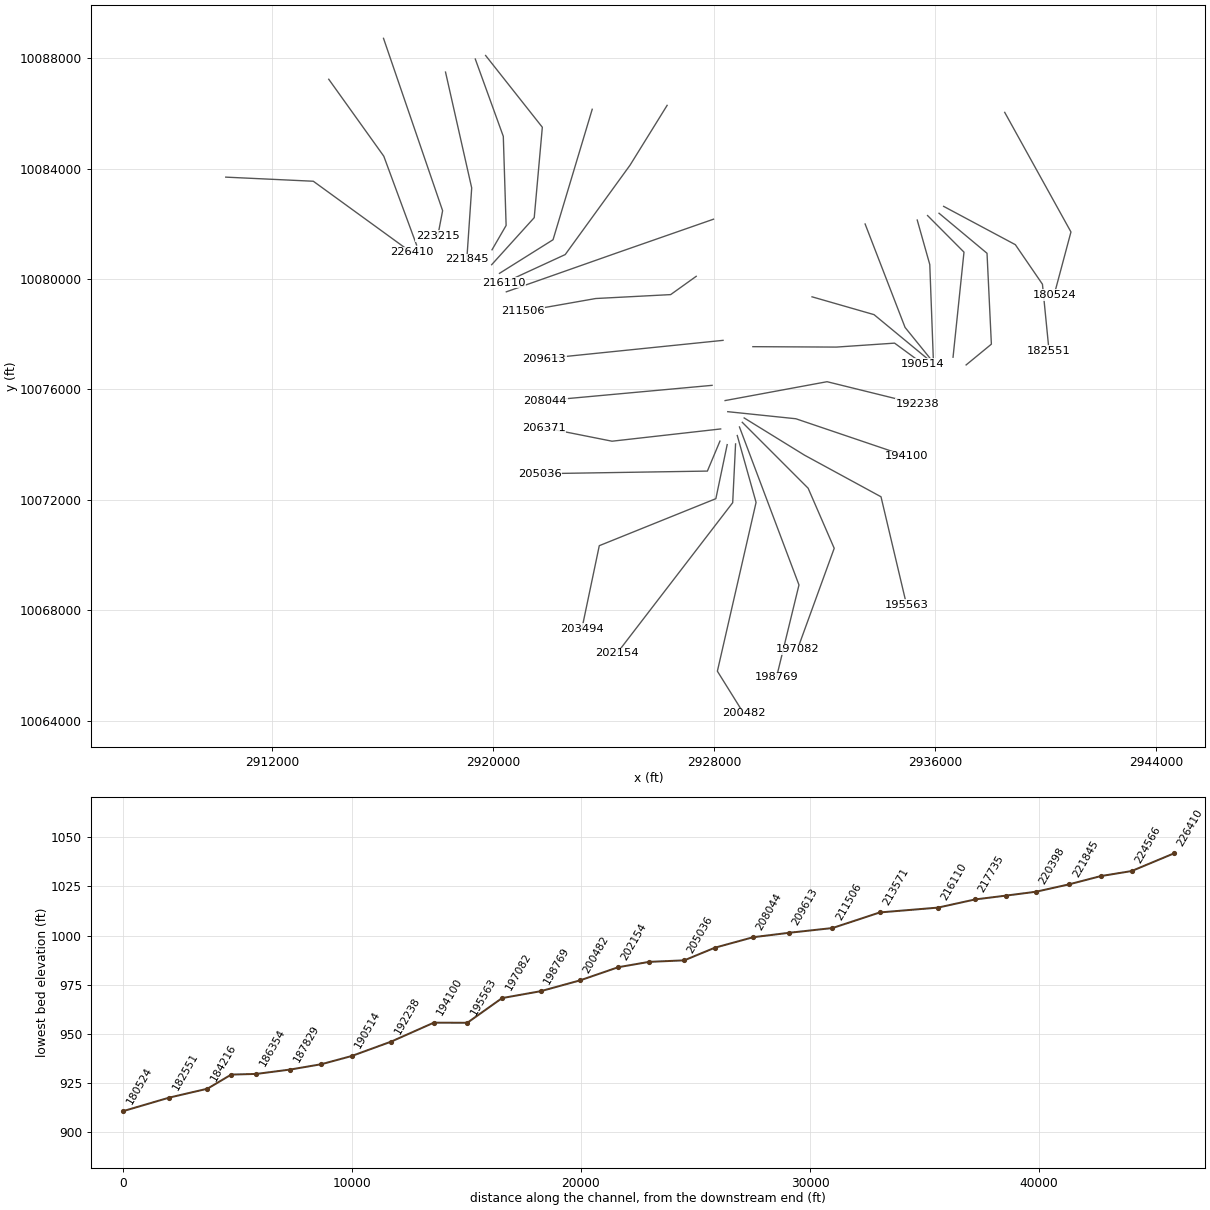
HEC-RAS study PEDERNALES RIVER.prj: PEDERNALES RIVER Base Level Engineering

--- PEDERNALES RIVER.g01 (geometry) --- (continued)

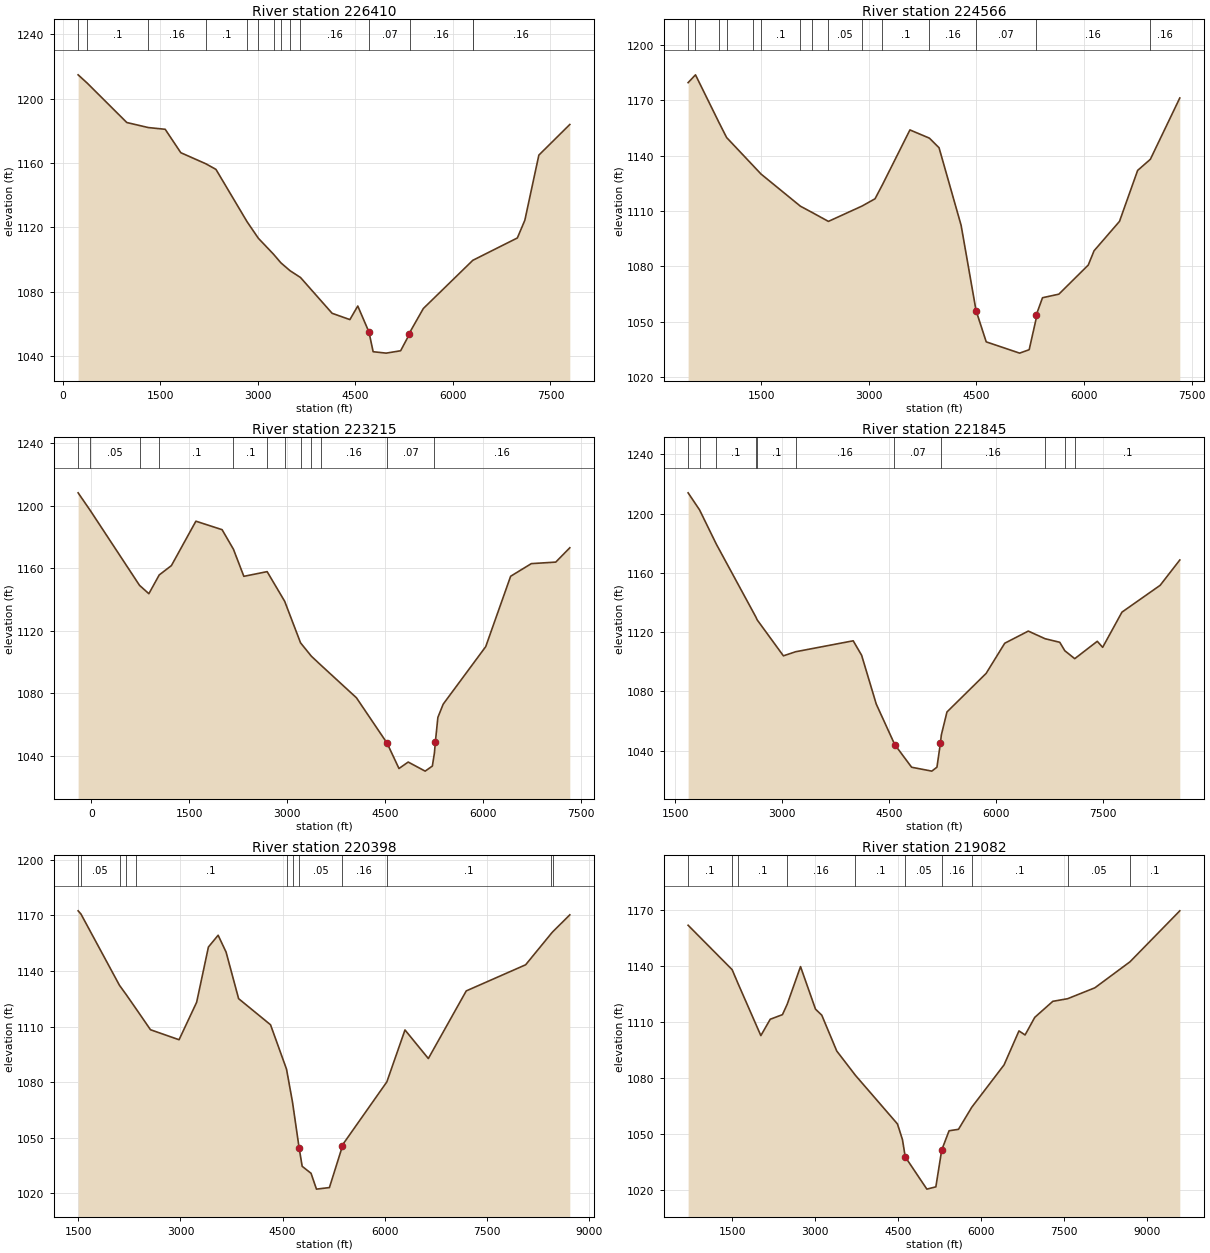
Type RM Length L Ch R = 1 ,226410  ,1844,1844,1844
BEGIN DESCRIPTION:
Mapping XS 5c696f8a
END DESCRIPTION:
XS GIS Cut Line= 3
      2910330.36     10083691.03      2913498.94     10083542.37
      2917051.49     10080960.88
#Sta/Elev= 30
   233.7 1214.73   372.5 1209.62   982.6  1185.1  1312.9 1181.97  1573.3 1180.89
  1813.5 1166.34  2200.1 1159.44  2354.1 1155.97  2832.5 1123.48  3006.5 1113.18
  3239.6 1103.28  3353.8 1097.89  3494.3 1093.01  3654.4 1088.82  4140.7 1066.58
  4414.1 1062.66  4535.5  1071.1  4707.1 1054.99  4715.5 1053.42    4772  1042.7
  4972.7 1041.83  5194.8  1043.3  5330.8 1053.67    5337 1054.83  5544.1 1069.55
    6305 1099.49  6990.2 1113.38  7105.4 1124.38    7321 1164.84  7797.2 1183.88
#Mann= 14 ,-1 , 0
   233.7     .16       0   372.5      .1       0  1312.9     .16       0
  2200.1      .1       0  2832.5     .05       0  3006.5      .1       0
  3239.6     .05       0  3353.8      .1       0  3494.3     .05       0
  3654.4     .16       0  4715.5     .07       0    5337     .16       0
    6305      .1       0    6305     .16       0
Bank Sta=4707.1,5330.8
XS Rating Curve= 0 ,0
Exp/Cntr=0.3,0.1

Type RM Length L Ch R = 1 ,224566  ,1351,1351,1351
BEGIN DESCRIPTION:
Mapping XS da71cbba
END DESCRIPTION:
XS GIS Cut Line= 3
      2914057.84     10087236.76      2916050.38     10084448.67
      2917235.64     10081234.01
#Sta/Elev= 30
   482.2 1179.64   584.9 1183.88   912.8 1157.98  1018.9 1149.85    1382 1134.85
  1498.6 1130.03  2047.2 1112.59  2203.2 1109.34  2437.8 1104.34    2907 1112.68
  3087.2  1116.6  3190.3 1124.21  3573.8 1153.98  3845.1 1149.52  3979.7 1144.31
  4287.4 1102.19  4495.7 1055.93  4637.2 1038.96  5102.7 1032.85    5236 1034.71
  5330.5 1051.09  5335.8 1053.69  5421.8 1062.92  5649.4 1064.84  6059.5 1080.65
  6140.2 1088.39  6494.8 1104.35  6747.5    1132  6924.8 1138.04  7335.3 1171.32
#Mann= 15 ,-1 , 0
   482.2      .1       0   584.9     .16       0   912.8     .05       0
  1018.9      .1       0    1382     .16       0  1498.6      .1       0
  2047.2      .1       0  2203.2     .16       0  2437.8     .05       0
    2907     .16       0  3190.3      .1       0  3845.1     .16       0
  4495.7     .07       0  5330.5     .16       0  6924.8     .16       0
Bank Sta=4495.7,5335.8
XS Rating Curve= 0 ,0
Exp/Cntr=0.3,0.1

Type RM Length L Ch R = 1 ,223215  ,1370,1370,1370
BEGIN DESCRIPTION:
Mapping XS 223380d4
END DESCRIPTION:
XS GIS Cut Line= 3
      2916039.69     10088719.39      2918178.79     10082474.73
      2918002.84     10081557.32
#Sta/Elev= 30
  -202.3 1208.22   -14.8 1196.84   738.5 1149.07   881.9 1143.72  1040.4 1155.71
  1227.1 1161.68  1602.5 1190.08  2003.9 1184.66  2177.9 1172.15  2337.5 1154.82
  2694.3 1157.83  2963.3 1138.86  3206.5 1112.29  3372.4 1103.74  3514.5 1098.19
    4063 1077.17  4532.3 1048.17  4714.7 1031.95  4856.3 1036.07  5115.9 1030.27
  5226.3 1033.51    5258 1041.87  5272.6 1049.06  5310.9 1064.61  5392.4  1073.1
  6044.1 1109.87  6425.9 1154.87    6743 1162.95  7117.2 1163.92  7332.7 1173.09
#Mann= 12 ,-1 , 0
  -202.3     .05       0   -14.8     .05       0   738.5      .1       0
  1040.4      .1       0  2177.9      .1       0  2694.3     .16       0
  2963.3      .1       0  3206.5      .1       0  3372.4     .05       0
  3514.5     .16       0  4532.3     .07       0    5258     .16       0
Bank Sta=4532.3,5272.6
XS Rating Curve= 0 ,0
Exp/Cntr=0.3,0.1

Type RM Length L Ch R = 1 ,221845  ,1447,1447,1447
BEGIN DESCRIPTION:
Mapping XS c9dd96ed
END DESCRIPTION:
XS GIS Cut Line= 3
      2918283.86     10087496.93      2919231.19     10083300.16
      2919054.57     10080714.64
#Sta/Elev= 30
  1683.1 1214.09  1843.4 1202.58  2078.3 1179.46  2631.2 1130.37  2651.7 1128.26
  3019.1 1103.98  3190.1 1106.74  3997.8 1114.14    4116 1104.35    4321  1071.4
  4567.1 1045.44  4585.2 1043.75  4816.6 1028.74  5099.9 1026.11  5171.9 1028.77
  5220.9 1045.06  5233.4 1050.53  5312.4 1066.07  5861.7 1092.13  6122.2 1112.49
    6453  1120.7  6687.1 1115.56    6894 1113.13  6964.4 1107.44  7104.1 1102.07
  7419.8  1113.8  7495.4 1109.73    7766  1133.5    8301  1151.6    8577 1168.72
#Mann= 11 ,-1 , 0
  1683.1      .1       0  1843.4     .16       0  2078.3      .1       0
  2631.2     .16       0  2651.7      .1       0  3190.1     .16       0
  4567.1     .07       0  5233.4     .16       0  6687.1      .1       0
  6964.4     .05       0  7104.1      .1       0
Bank Sta=4585.2,5220.9
XS Rating Curve= 0 ,0
Exp/Cntr=0.3,0.1

Type RM Length L Ch R = 1 ,220398  ,1316,1316,1316
BEGIN DESCRIPTION:
Mapping XS 1c4b74cc
END DESCRIPTION:
XS GIS Cut Line= 4
      2919361.42     10087968.52      2920374.96     10085168.39
      2920477.06     10081940.42      2919967.05     10081059.17
#Sta/Elev= 30
  1495.7 1172.47  1537.5 1170.73  2103.8 1132.26    2198  1127.5  2340.4 1119.99
  2559.2 1108.32    2979 1102.92  3237.4 1123.13  3410.6 1152.94  3553.2  1159.3
  3670.3 1150.19  3854.3 1125.08  4323.3    1111  4558.5 1087.03  4646.3 1069.25
  4743.1 1044.68  4788.4 1034.63  4918.5 1030.88  4998.3 1022.33  5188.6 1023.17
  5368.7 1044.21  5374.5 1045.85  6032.6 1080.19  6299.2  1108.2  6642.4 1092.78
  7199.6 1129.27  8072.3 1143.36  8449.1 1160.26  8474.2 1161.29  8721.4 1170.31
#Mann= 12 ,-1 , 0
  1495.7      .1       0  1537.5     .05       0  2103.8      .1       0
    2198     .05       0  2340.4      .1       0  4558.5     .16       0
  4646.3      .1       0  4743.1     .05       0  5368.7     .16       0
  6032.6      .1       0  8449.1     .05       0  8474.2      .1       0
Bank Sta=4743.1,5374.5
XS Rating Curve= 0 ,0
Exp/Cntr=0.3,0.1

Type RM Length L Ch R = 1 ,219082  ,1347,1347,1347
BEGIN DESCRIPTION:
Mapping XS 2165a8ca
END DESCRIPTION:
XS GIS Cut Line= 4
      2919734.85     10088098.07       2921787.6     10085498.23
      2921494.44     10082223.74      2919953.79     10080518.33
#Sta/Elev= 30
   698.1 1161.96  1494.6 1138.13  1604.4 1130.48  2014.4 1102.74  2184.2 1111.51
  2405.5 1113.98  2491.4 1119.58  2732.5 1139.76  3003.5 1116.95  3117.3 1113.67
  3388.2 1094.46  3725.7 1081.43    4487 1055.31  4577.4  1046.9  4627.6 1037.65
  5018.9 1020.34  5181.6 1021.57  5287.9 1041.34  5420.8 1051.66  5591.4 1052.44
  5831.6 1064.29  6415.9 1087.01  6685.8 1105.25  6796.2 1103.08  6972.3 1112.55
  7298.2 1121.13  7565.6 1122.53  8060.1  1128.4  8695.6 1142.36  9596.5  1169.7
#Mann= 10 ,-1 , 0
   698.1      .1       0  1494.6     .05       0  1604.4      .1       0
  2491.4     .16       0  3725.7      .1       0  4627.6     .05       0
  5287.9     .16       0  5831.6      .1       0  7565.6     .05       0
  8695.6      .1       0
Bank Sta=4627.6,5287.9
XS Rating Curve= 0 ,0
Exp/Cntr=0.3,0.1

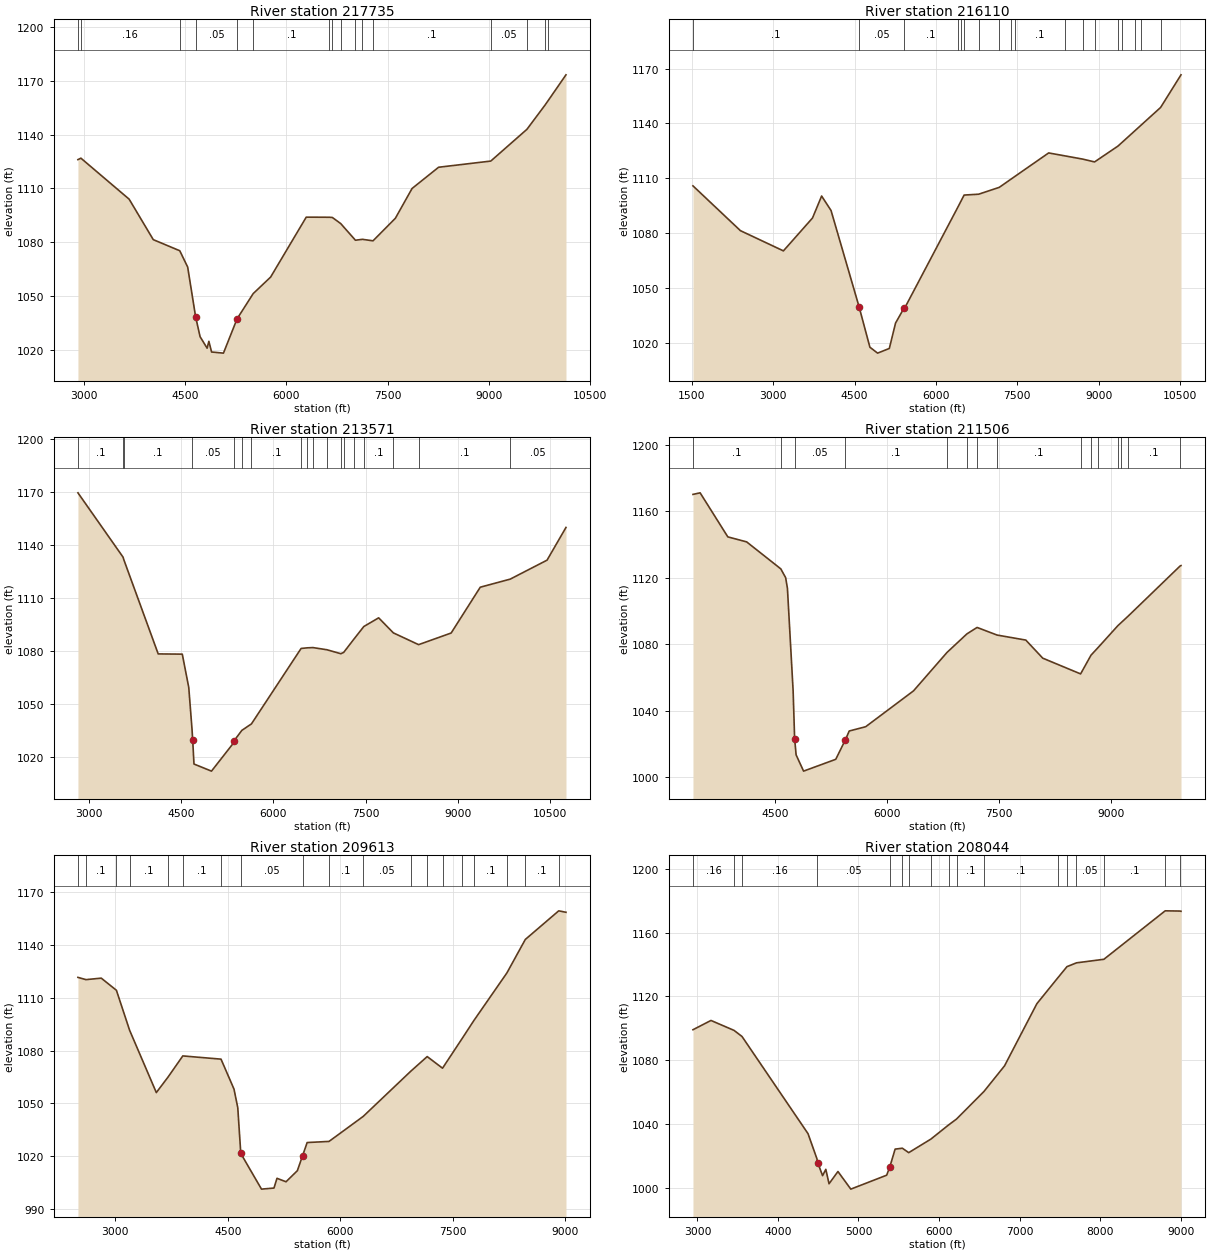
Type RM Length L Ch R = 1 ,217735  ,1625,1625,1625
BEGIN DESCRIPTION:
Mapping XS 593ce54a
END DESCRIPTION:
XS GIS Cut Line= 3
      2923592.99     10086149.69      2922175.29     10081423.05
      2920237.07     10080205.67
#Sta/Elev= 30
  2916.1 1126.06  2960.3 1126.86    3674 1104.05  4031.2 1081.53  4423.4 1075.36
  4540.5 1066.26  4657.7 1038.65  4723.8 1027.56  4828.3 1021.15  4853.7 1024.98
  4894.4 1019.02  5069.9  1018.4  5271.4 1037.48  5510.4 1051.53    5768 1060.71
  6295.2 1094.05  6637.2 1093.99  6682.1 1093.86  6805.5 1090.47  7023.3 1081.21
  7127.3 1081.71  7283.6 1080.88  7614.3 1093.42  7861.8 1110.01  8254.1 1121.81
  9026.6 1125.25  9561.7 1142.92  9827.3 1156.28    9876  1158.9 10139.6 1173.23
#Mann= 16 ,-1 , 0
  2916.1      .1       0  2960.3     .16       0  4423.4      .1       0
  4657.7     .05       0  5271.4     .16       0  5510.4      .1       0
  6637.2     .05       0  6682.1      .1       0  6805.5     .05       0
  7023.3      .1       0  7127.3     .05       0  7283.6      .1       0
  9026.6     .05       0  9561.7      .1       0  9827.3     .05       0
    9876      .1       0
Bank Sta=4657.7,5271.4
XS Rating Curve= 0 ,0
Exp/Cntr=0.3,0.1

Type RM Length L Ch R = 1 ,216110  ,2539,2539,2539
BEGIN DESCRIPTION:
Mapping XS 788ab93b
END DESCRIPTION:
XS GIS Cut Line= 4
      2926303.98     10086291.52      2924963.35     10084126.59
      2922615.92     10080885.91      2920393.36     10079860.42
#Sta/Elev= 30
  1520.4 1105.82  2394.6  1081.3  3187.5 1070.22  3723.9 1088.23  3891.8 1100.25
  4065.4 1092.32 4581.82 1039.65  4781.5 1017.47  4923.5 1014.23  5139.5 1016.79
  5254.7 1030.71  5411.7 1038.94  5417.9 1038.63  6403.7  1094.2  6467.8 1097.88
  6518.2 1100.78  6785.1 1101.25  7165.8    1105  7381.7 1109.48  7452.8 1110.96
  8076.6 1123.85  8374.6 1122.25  8706.4 1120.46    8923 1118.93  9354.9 1127.62
  9419.2 1129.35  9675.3 1136.24  9782.9 1139.14 10140.3 1148.76 10516.1 1166.62
#Mann= 18 ,-1 , 0
  1520.4      .1       0 4581.82     .05       0  5417.9      .1       0
  6403.7     .16       0  6467.8      .1       0  6518.2     .16       0
  6785.1      .1       0  7165.8     .16       0  7381.7     .16       0
  7452.8      .1       0  8374.6      .1       0  8706.4      .1       0
    8923      .1       0  9354.9     .05       0  9419.2      .1       0
  9675.3     .05       0  9782.9      .1       0 10140.3     .05       0
Bank Sta=4581.82,5411.7
XS Rating Curve= 0 ,0
Exp/Cntr=0.3,0.1

Type RM Length L Ch R = 1 ,213571  ,2065,2065,2065
BEGIN DESCRIPTION:
Mapping XS b80bdd74
END DESCRIPTION:
XS GIS Cut Line= 3
      2927982.25     10082167.09      2924503.17     10080952.47
        2920484.     10079535.93
#Sta/Elev= 30
  2816.4  1169.3  3551.3 1132.88  3564.7 1131.32  4123.2 1078.12  4515.4 1077.99
    4621  1059.1    4674 1035.37  4684.6 1029.55  4705.8 1015.79  4990.9 1011.77
  5351.9  1027.8  5358.5 1028.95  5485.2 1034.83  5641.7 1038.52  6450.1 1081.21
  6553.1 1081.56  6642.8  1081.7  6871.1 1080.47  7096.1 1078.24    7143 1078.96
  7311.2 1086.54  7470.7 1093.61  7712.9 1098.54  7952.3 1090.02  8363.5 1083.36
  8893.3 1089.95  9367.3 1115.88    9855 1120.45 10454.8 1131.19 10762.9 1149.71
#Mann= 18 ,-1 , 0
  2816.4      .1       0  3551.3     .16       0  3564.7      .1       0
    4674     .05       0  5351.9      .1       0  5485.2     .05       0
  5641.7      .1       0  6450.1     .05       0  6553.1      .1       0
  6642.8     .05       0  6871.1      .1       0  7096.1     .05       0
    7143      .1       0  7311.2     .05       0  7470.7      .1       0
  7952.3     .05       0  8363.5      .1       0    9855     .05       0
Bank Sta=4684.6,5358.5
XS Rating Curve= 0 ,0
Exp/Cntr=0.3,0.1

Type RM Length L Ch R = 1 ,211506  ,1893,1893,1893
BEGIN DESCRIPTION:
Mapping XS 70bcdf49
END DESCRIPTION:
XS GIS Cut Line= 4
      2927356.64     10080097.75      2926431.56     10079435.31
      2923720.56     10079293.52      2921078.63     10078827.06
#Sta/Elev= 30
  3404.3 1170.23    3500 1171.18    3871 1144.69  4122.8 1141.69  4580.4 1125.45
  4645.3 1120.17  4669.2 1113.75  4745.5    1052  4765.5 1023.35  4785.5  1013.6
  4885.4 1003.83  5316.3 1010.94  5446.4 1022.78  5496.5 1027.95  5716.8 1030.53
  6357.7  1052.1    6806  1075.2  7072.3 1086.35    7209 1090.23    7476 1085.66
  7861.3 1082.63    8088 1071.76    8595 1062.29  8734.1 1073.53  8833.5 1078.36
  9093.9 1091.29  9139.4 1093.18  9228.5 1096.89  9927.5 1127.19  9939.6 1127.43
#Mann= 15 ,-1 , 0
  3404.3      .1       0  4580.4     .16       0  4765.5     .05       0
  5446.4      .1       0    6806     .05       0  7072.3      .1       0
    7209     .05       0    7476      .1       0    8595     .05       0
  8734.1      .1       0  8833.5     .05       0  9093.9      .1       0
  9139.4     .05       0  9228.5      .1       0  9927.5     .05       0
Bank Sta=4765.5,5446.4
XS Rating Curve= 0 ,0
Exp/Cntr=0.3,0.1

Type RM Length L Ch R = 1 ,209613  ,1569,1569,1569
BEGIN DESCRIPTION:
Mapping XS c5e8d5e5
END DESCRIPTION:
XS GIS Cut Line= 2
      2928327.79     10077777.99      2921856.64     10077115.21
#Sta/Elev= 30
  2503.5 1121.47  2610.5 1120.19  2814.4 1121.04  3016.3 1114.15  3192.2 1091.49
  3548.3 1056.16  3706.8  1065.1  3901.1 1076.94  4410.7 1075.11  4583.6 1058.13
  4633.9 1047.58  4674.1 1021.64    4950 1001.42  5116.4 1002.03  5156.6 1007.55
  5277.3  1005.6    5428 1011.87  5498.4 1020.45  5558.7 1027.83  5850.4 1028.47
  6306.2 1042.66  6936.8 1068.14  7158.7 1076.57  7363.1 1069.98  7628.1 1087.05
  7781.8 1097.06  8220.7 1123.97  8466.5 1142.97    8912  1159.2  9008.5 1158.38
#Mann= 19 ,-1 , 0
  2503.5      .1       0  2610.5      .1       0  3016.3     .16       0
  3192.2      .1       0  3706.8     .05       0  3901.1      .1       0
  4410.7     .16       0  4674.1     .05       0  5498.4      .1       0
  5850.4      .1       0  6306.2     .05       0  6936.8      .1       0
  7158.7     .16       0  7363.1      .1       0  7628.1     .05       0
  7781.8      .1       0  8220.7     .05       0  8466.5      .1       0
    8912      .1       0
Bank Sta=4674.1,5498.4
XS Rating Curve= 0 ,0
Exp/Cntr=0.3,0.1

Type RM Length L Ch R = 1 ,208044  ,1673,1673,1673
BEGIN DESCRIPTION:
Mapping XS f7433aed
END DESCRIPTION:
XS GIS Cut Line= 2
      2927931.13     10076148.07      2921896.13     10075594.82
#Sta/Elev= 30
  2944.8 1099.09  3168.4  1104.9  3454.6 1098.68  3553.3 1094.88  4373.4 1033.94
  4483.9 1018.22  4493.9 1015.78  4554.2 1007.59  4594.3 1011.57  4634.5 1002.52
    4745 1010.21  4904.7  999.16    5350 1007.89  5389.6 1013.21    5455 1024.24
  5544.6 1024.81  5623.9 1022.03  5899.9 1030.55  6119.6 1039.42  6218.3 1043.13
  6557.9 1060.37  6813.6 1076.44  7215.3 1115.42  7480.1 1131.92  7589.1 1138.64
  7706.9 1141.02  8047.4 1143.25  8808.5 1173.63  8992.8 1173.49  9005.1 1173.34
#Mann= 17 ,-1 , 0
  2944.8     .16       0  3454.6      .1       0  3553.3     .16       0
  4483.9     .05       0  5389.6     .05       0  5544.6      .1       0
  5623.9     .05       0  5899.9     .16       0  6119.6     .05       0
  6218.3      .1       0  6557.9      .1       0  7480.1     .05       0
  7589.1      .1       0  7706.9     .05       0  8047.4      .1       0
  8808.5     .05       0  8992.8      .1       0
Bank Sta=4493.9,5389.6
XS Rating Curve= 0 ,0
Exp/Cntr=0.3,0.1

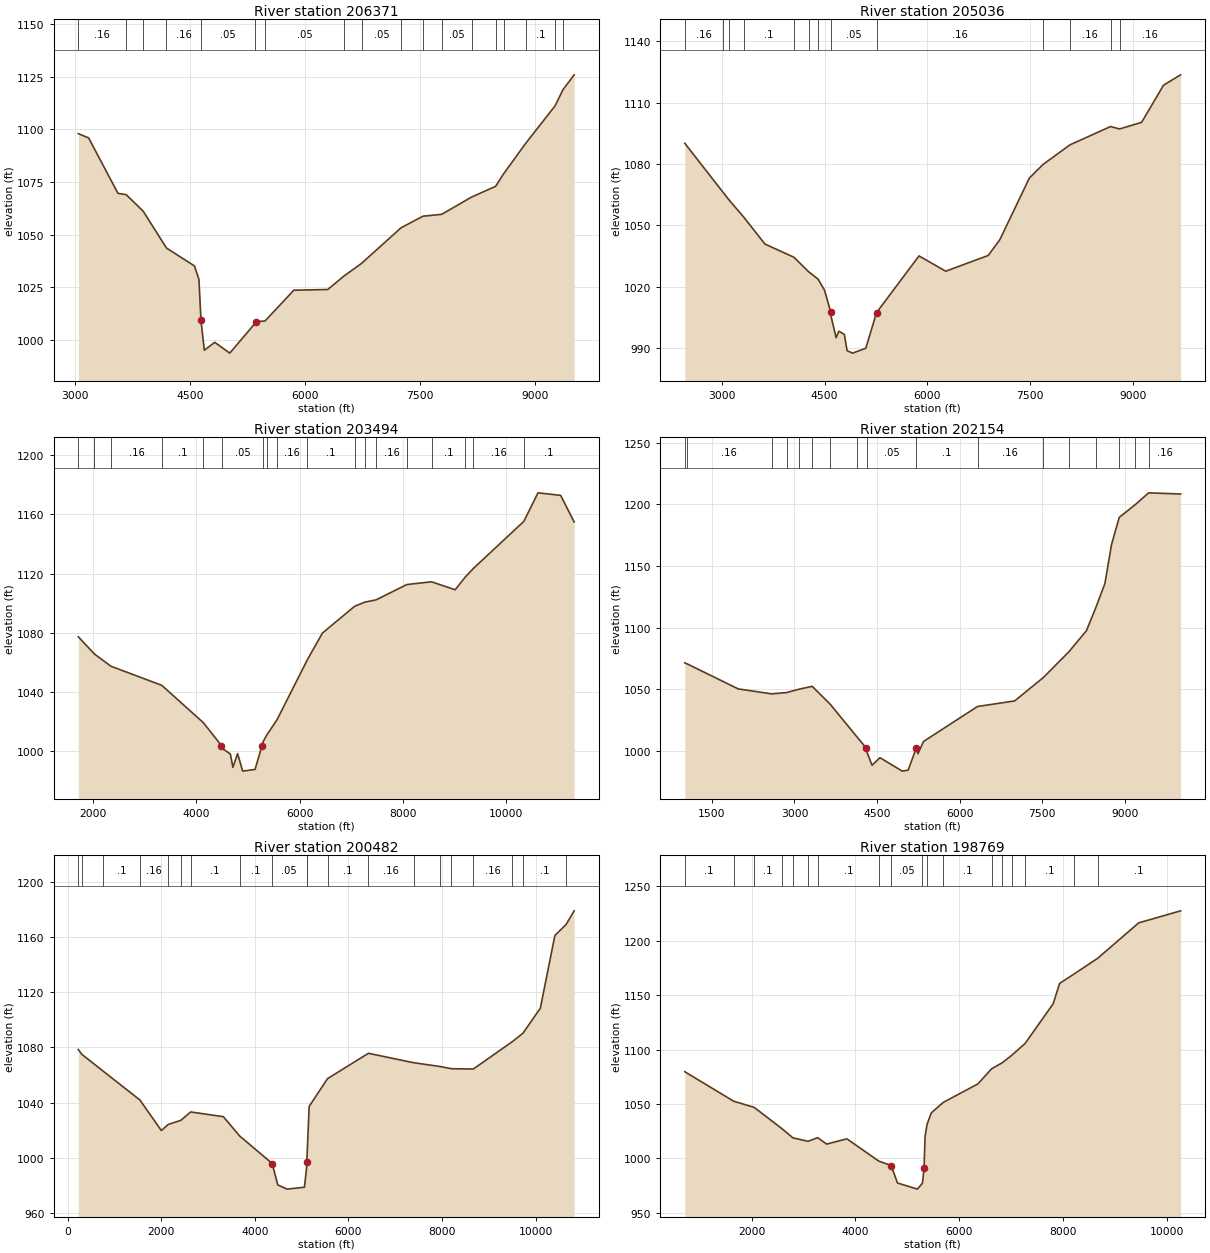
Type RM Length L Ch R = 1 ,206371  ,1335,1335,1335
BEGIN DESCRIPTION:
Mapping XS 1342c581
END DESCRIPTION:
XS GIS Cut Line= 3
       2928242.2     10074568.51      2924310.06     10074124.39
      2921845.66     10074614.99
#Sta/Elev= 30
  3043.4 1098.02    3178 1095.96  3560.4 1069.67  3668.1 1069.04  3889.8  1061.2
  4193.2 1043.73  4558.9  1035.2  4617.1 1028.83  4643.7 1009.41  4648.8 1007.78
  4687.5  995.19  4823.4  998.96  5019.4  993.82  5351.7 1008.05  5357.4 1008.67
  5480.4  1009.1  5854.9 1023.68  6297.7 1024.02  6511.6 1030.47  6738.9 1036.42
  7255.2 1053.34  7540.6 1058.82  7784.8 1059.71  8176.7 1067.94  8487.8 1072.98
  8591.6 1078.88  8887.2  1093.7  9264.6 1111.22  9366.1 1118.81  9513.3 1125.93
#Mann= 18 ,-1 , 0
  3043.4     .16       0  3668.1      .1       0  3889.8     .16       0
  4193.2     .16       0  4648.8     .05       0  5351.7      .1       0
  5480.4     .05       0  6511.6      .1       0  6738.9     .05       0
  7255.2      .1       0  7540.6     .05       0  7784.8     .05       0
  8176.7      .1       0  8487.8      .1       0  8591.6     .05       0
  8887.2      .1       0  9264.6     .05       0  9366.1      .1       0
Bank Sta=4643.7,5357.4
XS Rating Curve= 0 ,0
Exp/Cntr=0.3,0.1

Type RM Length L Ch R = 1 ,205036  ,1542,1542,1542
BEGIN DESCRIPTION:
Mapping XS e914ae97
END DESCRIPTION:
XS GIS Cut Line= 3
      2928215.52     10074127.17      2927760.97     10073041.72
       2921699.4     10072946.48
#Sta/Elev= 30
    2460 1090.14  3020.1 1066.07  3110.1 1062.23  3324.5 1053.84  3629.7 1040.81
  4053.1 1034.34  4269.2 1027.21  4405.3 1023.65  4499.4 1018.24  4589.4 1007.68
  4599.4 1004.85  4669.4  994.95  4709.4  998.12  4789.4  996.57  4829.4  988.59
  4909.2  987.39  5102.3  989.77  5259.5 1007.23  5879.6 1034.99  6269.6  1027.5
  6889.7  1035.2  7059.7 1042.92  7489.8 1073.07  7689.9 1079.76  8084.3 1089.39
  8676.1 1098.34  8808.1 1097.15    9130 1100.41    9450  1118.6  9699.1 1123.66
#Mann= 13 ,-1 , 0
    2460     .16       0  3020.1      .1       0  3110.1     .16       0
  3324.5      .1       0  4053.1     .16       0  4269.2      .1       0
  4405.3     .16       0  4599.4     .05       0  5259.5     .16       0
  7689.9      .1       0  8084.3     .16       0  8676.1      .1       0
  8808.1     .16       0
Bank Sta=4589.4,5259.5
XS Rating Curve= 0 ,0
Exp/Cntr=0.3,0.1

Type RM Length L Ch R = 1 ,203494  ,1340,1340,1340
BEGIN DESCRIPTION:
Mapping XS 6b68cf6f
END DESCRIPTION:
XS GIS Cut Line= 4
      2928477.51     10074000.17      2928067.52     10072041.98
      2923848.71     10070339.14      2923220.61     10067338.44
#Sta/Elev= 30
  1708.7 1077.35  2021.9  1065.7    2342 1057.44  3326.9 1044.57  4133.2 1019.33
  4484.8 1003.87  4492.6 1002.13  4657.9  998.14  4706.2  989.16  4797.5   998.4
  4896.5   986.6  5135.6  987.76  5267.1 1003.24  5291.3 1006.33  5359.3 1010.78
  5560.5 1021.22  6151.4 1061.89  6442.6 1079.87  7068.4    1098  7264.8 1100.76
  7482.7 1102.29  8079.1 1112.64  8558.5 1114.51    9016 1109.13  9212.9 1117.69
    9368 1123.45 10348.9 1155.35 10623.3 1174.61 11062.6 1172.89 11324.6 1154.92
#Mann= 18 ,-1 , 0
  1708.7     .16       0  2021.9      .1       0    2342     .16       0
  3326.9      .1       0  4133.2     .16       0  4492.6     .05       0
  5291.3     .05       0  5359.3      .1       0  5560.5     .16       0
  6151.4      .1       0  7068.4     .16       0  7264.8      .1       0
  7482.7     .16       0  8079.1     .16       0  8558.5      .1       0
  9212.9     .05       0    9368     .16       0 10348.9      .1       0
Bank Sta=4484.8,5267.1
XS Rating Curve= 0 ,0
Exp/Cntr=0.3,0.1

Type RM Length L Ch R = 1 ,202154  ,1672,1672,1672
BEGIN DESCRIPTION:
Mapping XS b487ee41
END DESCRIPTION:
XS GIS Cut Line= 3
      2928781.04      10074025.6      2928676.96     10071897.55
      2924490.31     10066442.31
#Sta/Elev= 30
  1007.8  1071.6  1039.9 1070.99  1978.7 1050.47  2583.4 1046.49  2856.6  1047.5
  3076.8 1050.16  3322.1 1052.59  3653.1 1037.86    4133 1011.77  4302.9 1002.61
  4324.3   998.4  4409.5  988.63  4552.7  994.78  4958.1  983.89  5065.7  984.72
  5215.3 1002.91  5244.3  998.03    5344  1007.9  6325.2 1036.23  6999.1 1040.73
    7519  1059.6  7986.2  1080.6  8303.4 1097.58  8474.4 1116.29  8639.2 1135.76
  8760.2 1167.46  8900.8 1189.45  9185.6 1199.51  9434.7 1209.28   10015 1208.32
#Mann= 17 ,-1 , 0
  1007.8      .1       0  1039.9     .16       0  2583.4      .1       0
  2856.6     .16       0  3076.8      .1       0  3322.1     .16       0
  3653.1      .1       0    4133      .1       0  4324.3     .05       0
  5215.3      .1       0  6325.2     .16       0    7519     .05       0
  7986.2      .1       0  8474.4      .1       0  8900.8      .1       0
  9185.6      .1       0  9434.7     .16       0
Bank Sta=4302.9,5215.3
XS Rating Curve= 0 ,0
Exp/Cntr=0.3,0.1

Type RM Length L Ch R = 1 ,200482  ,1713,1713,1713
BEGIN DESCRIPTION:
Mapping XS cfa8be4a
END DESCRIPTION:
XS GIS Cut Line= 4
      2928842.39     10074330.25      2929523.22     10071907.94
      2928122.56      10065792.4      2929073.99     10064264.11
#Sta/Elev= 30
   230.3 1078.51   304.3 1075.04   766.2 1062.66  1546.7 1041.84  2002.9  1019.7
  2152.4 1024.15  2419.2 1027.08  2628.8 1033.19    3329 1029.75  3675.2 1015.78
  4357.1   996.2  4371.7  995.62    4491   980.2  4689.5  977.18    5059  978.56
  5105.7   992.5  5110.3   996.9  5160.3 1037.19  5552.8 1057.37  6426.1 1075.76
  7392.1 1068.92  7954.5 1066.19  8199.9 1064.56  8667.7 1064.37  9495.3  1084.1
    9729 1090.37 10098.6 1108.54   10409 1161.28 10647.4  1169.2 10820.6 1179.16
#Mann= 20 ,-1 , 0
   230.3      .1       0   304.3      .1       0   766.2      .1       0
  1546.7     .16       0  2152.4      .1       0  2419.2     .16       0
  2628.8      .1       0  3675.2      .1       0  4357.1     .05       0
  5105.7      .1       0  5105.7     .16       0  5552.8      .1       0
  6426.1     .16       0  7392.1      .1       0  7954.5      .1       0
  8199.9     .16       0  8667.7     .16       0  9495.3     .05       0
    9729      .1       0 10647.4      .1       0
Bank Sta=4371.7,5110.3
XS Rating Curve= 0 ,0
Exp/Cntr=0.3,0.1

Type RM Length L Ch R = 1 ,198769  ,1687,1687,1687
BEGIN DESCRIPTION:
Mapping XS 6c0cd8b1
END DESCRIPTION:
XS GIS Cut Line= 3
      2928921.95     10074640.19      2931075.64     10068916.48
      2930262.51     10065573.03
#Sta/Elev= 30
   713.6 1079.65    1655 1052.54  2051.1 1046.84  2578.3  1027.6  2798.4 1018.82
  3089.4 1015.68  3275.5 1019.03  3447.1  1013.1  3838.2 1017.93  4453.2  997.43
  4691.5  993.36  4812.7  977.32  5197.1  971.68  5294.2   977.2  5325.5  991.27
    5344 1019.95    5384 1031.37  5464.9 1041.82  5697.3  1051.5  6361.9 1068.42
  6625.2 1082.28    6832 1087.89  7015.1 1094.73  7270.6 1105.55  7813.2 1142.13
  7938.4 1160.92  8217.7 1169.56  8672.9 1184.03  9461.7 1216.54   10270 1227.62
#Mann= 18 ,-1 , 0
   713.6      .1       0    1655     .16       0  2051.1      .1       0
  2578.3      .1       0  2798.4      .1       0  3089.4     .16       0
  3275.5      .1       0  4453.2      .1       0  4691.5     .05       0
  5294.2      .1       0    5384     .16       0  5697.3      .1       0
  6625.2     .16       0    6832      .1       0  7015.1     .16       0
  7270.6      .1       0  8217.7     .16       0  8672.9      .1       0
Bank Sta=4691.5,5325.5
XS Rating Curve= 0 ,0
Exp/Cntr=0.3,0.1

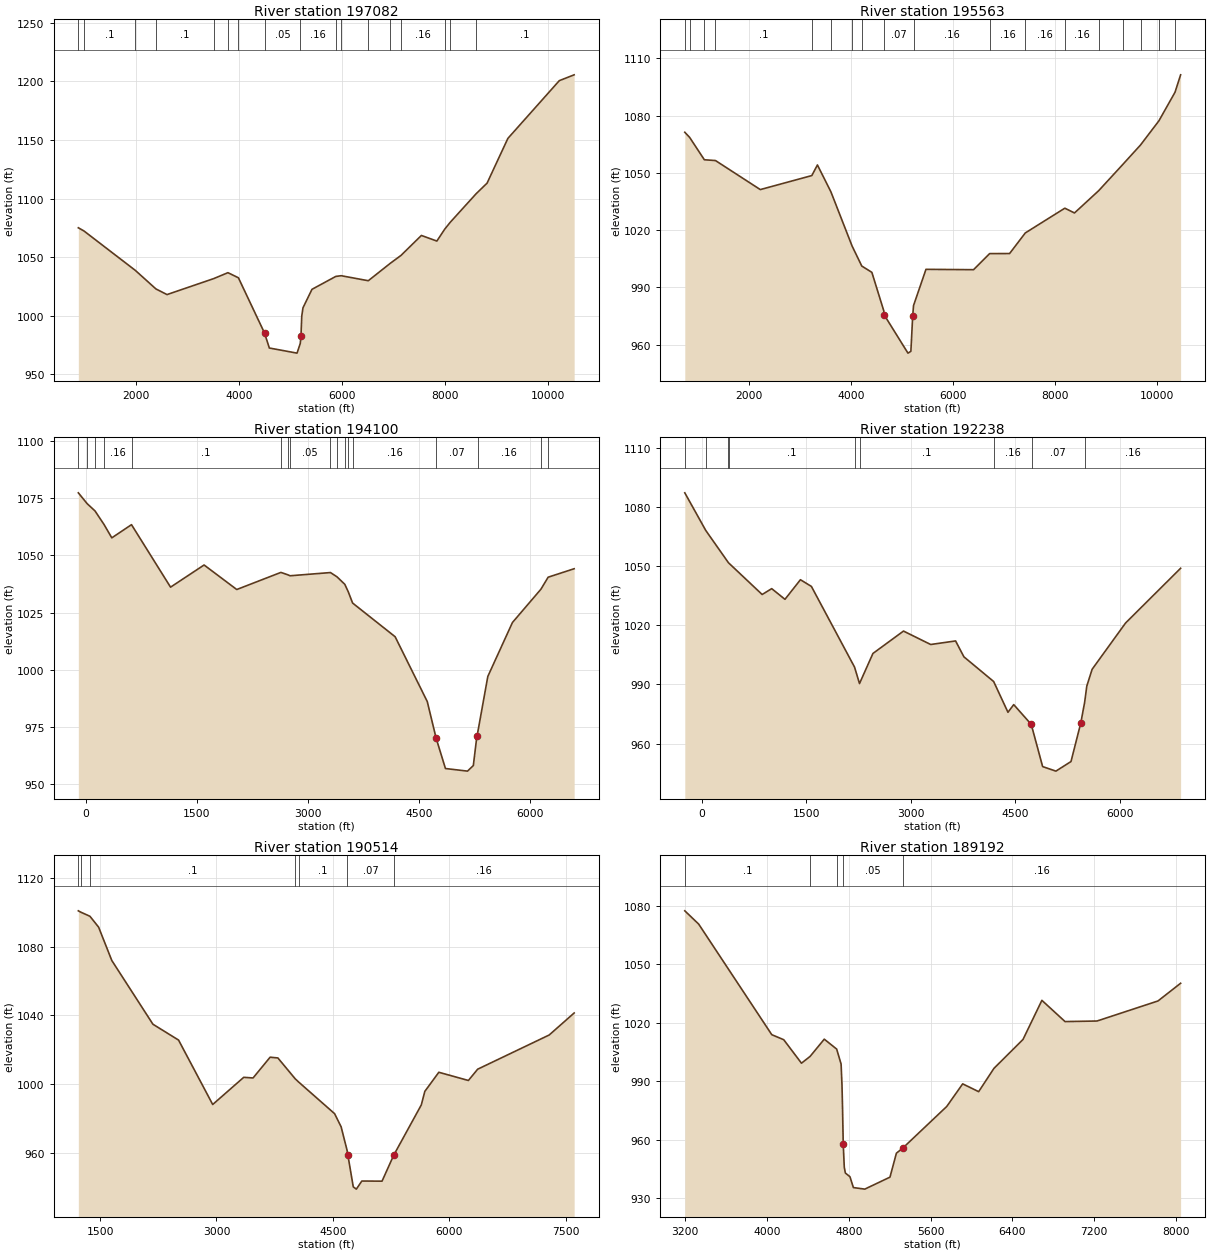
Type RM Length L Ch R = 1 ,197082  ,1519,1519,1519
BEGIN DESCRIPTION:
Mapping XS 52befbc8
END DESCRIPTION:
XS GIS Cut Line= 4
      2929024.06     10074808.13      2931407.61     10072420.69
      2932351.04     10070244.69      2931020.97     10066582.35
#Sta/Elev= 30
   875.3 1075.13   984.7 1072.41  1983.4 1038.78  2383.5 1022.97  2599.8 1018.13
    3508 1031.76  3784.4 1036.82  3988.3 1032.46  4496.3  985.28  4589.7  972.53
  5128.2  968.17  5191.1  976.44  5204.7  982.82    5220  999.77  5243.5  1006.8
  5418.6 1022.61    5882 1033.62  5987.3 1034.23  6513.5 1029.94  6942.7 1044.85
  7150.1 1051.56  7546.4 1068.58  7847.2 1063.79  8000.3 1073.97  8106.6 1079.78
  8610.4 1104.16  8823.9 1113.23  9228.2 1151.39 10228.3 1200.67   10517 1205.64
#Mann= 17 ,-1 , 0
   875.3     .16       0   984.7      .1       0  1983.4     .16       0
  2383.5      .1       0    3508     .16       0  3784.4      .1       0
  3988.3     .16       0  4496.3     .05       0  5191.1     .16       0
    5882      .1       0  5987.3      .1       0  6513.5      .1       0
  6942.7     .05       0  7150.1     .16       0  8000.3      .1       0
  8106.6     .16       0  8610.4      .1       0
Bank Sta=4496.3,5204.7
XS Rating Curve= 0 ,0
Exp/Cntr=0.3,0.1

Type RM Length L Ch R = 1 ,195563  ,1463,1463,1463
BEGIN DESCRIPTION:
Mapping XS 1cf03ccc
END DESCRIPTION:
XS GIS Cut Line= 4
      2929092.45     10074967.01      2931275.77     10073618.76
      2934044.39     10072111.05      2934967.04     10068207.19
#Sta/Elev= 30
   733.6 1071.26   827.7 1068.61  1117.4 1056.86    1336 1056.44  2215.3 1041.24
  3226.2 1048.58  3336.4 1054.14  3601.2 1040.05  4015.9 1011.72  4206.7  1001.2
  4404.7  997.89  4639.3  977.68  4646.4  975.61  5112.9  955.59  5170.1  956.53
  5206.2  975.21  5222.4  980.51  5466.2  999.47    6400  999.29  6715.6 1007.71
  7107.1 1007.74  7415.3 1018.53  8191.1 1031.49  8381.2    1029  8856.8 1040.69
    9341 1054.75  9676.8  1064.6   10038 1077.27 10353.4 1092.21 10463.6 1101.34
#Mann= 18 ,-1 , 0
   733.6     .16       0   827.7      .1       0  1117.4     .16       0
    1336      .1       0  3226.2     .16       0  3601.2     .16       0
  4015.9      .1       0  4206.7     .16       0  4639.3     .07       0
  5222.4     .16       0  6715.6     .16       0  7415.3     .16       0
  8191.1     .16       0  8856.8      .1       0    9341     .05       0
  9676.8     .05       0   10038     .16       0 10353.4      .1       0
Bank Sta=4646.4,5206.2
XS Rating Curve= 0 ,0
Exp/Cntr=0.3,0.1

Type RM Length L Ch R = 1 ,194100  ,1862,1862,1862
BEGIN DESCRIPTION:
Mapping XS aee10ab1
END DESCRIPTION:
XS GIS Cut Line= 3
      2928498.48     10075194.08      2930962.68     10074937.87
      2934963.62     10073580.82
#Sta/Elev= 30
  -102.2  1077.4    18.3 1072.62   123.1 1069.49   246.3 1063.49   350.2  1057.7
   616.5 1063.47  1144.5 1036.13  1597.7 1045.83  2039.3  1035.1  2635.6 1042.58
  2729.8 1041.54  2759.6 1041.11  3305.8 1042.52    3394 1040.66  3499.7 1037.38
  3546.1 1034.14  3605.4 1029.18    4180 1014.45  4614.4   986.1  4734.8  970.01
  4860.4  956.79  5158.3  955.65  5237.3  958.09  5285.3  970.97  5294.8  972.25
  5433.1  997.08  5765.9 1020.66  6151.2 1035.25  6248.5 1040.49  6600.1 1044.19
#Mann= 17 ,-1 , 0
  -102.2      .1       0    18.3     .16       0   123.1      .1       0
   246.3     .16       0   616.5      .1       0  2635.6     .05       0
  2729.8      .1       0  2759.6     .05       0  3305.8      .1       0
    3394     .05       0  3499.7      .1       0  3546.1     .05       0
  3605.4     .16       0  4734.8     .07       0  5294.8     .16       0
  6151.2      .1       0  6248.5     .16       0
Bank Sta=4734.8,5285.3
XS Rating Curve= 0 ,0
Exp/Cntr=0.3,0.1

Type RM Length L Ch R = 1 ,192238  ,1724,1724,1724
BEGIN DESCRIPTION:
Mapping XS 31e63607
END DESCRIPTION:
XS GIS Cut Line= 3
      2928402.46     10075596.56      2932092.07     10076279.91
       2935355.4     10075474.12
#Sta/Elev= 30
  -240.6 1087.15      61 1068.03   385.8 1051.69   386.4 1051.67   869.3 1035.58
  1006.3 1038.55  1196.7 1033.14  1418.4 1043.08  1575.8 1039.68  2194.8  998.76
    2266  990.41  2458.7 1005.68    2897 1017.03  3287.5 1010.22  3644.5 1012.03
  3763.7 1003.98  4190.8  991.44  4395.9  975.85  4478.8  979.73  4727.5  969.81
  4733.8   969.2  4893.4   948.3  5083.8     946  5300.3  950.86  5440.9  970.44
    5496   980.9  5526.9  989.11  5603.3  997.65  6083.1 1021.12  6873.1 1048.89
#Mann= 9 ,-1 , 0
  -240.6     .16       0      61      .1       0   385.8     .16       0
   386.4      .1       0  2194.8     .05       0    2266      .1       0
  4190.8     .16       0  4733.8     .07       0    5496     .16       0
Bank Sta=4727.5,5440.9
XS Rating Curve= 0 ,0
Exp/Cntr=0.3,0.1

Type RM Length L Ch R = 1 ,190514  ,1322,1322,1322
BEGIN DESCRIPTION:
Mapping XS 2c89a7d6
END DESCRIPTION:
XS GIS Cut Line= 4
      2929407.12     10077549.06      2932428.23     10077534.08
      2934535.91     10077677.17      2935547.64     10076934.39
#Sta/Elev= 30
  1220.4 1100.86  1250.1 1100.12  1369.8 1097.69  1481.8 1091.34  1651.8 1071.91
  2181.8 1034.76  2511.8 1025.54  2951.8  987.99  3351.8 1003.83  3471.8 1003.45
  3691.8 1015.56  3791.8 1015.11  4015.7 1002.93    4065 1000.85  4522.4  982.65
  4606.6  974.99  4682.8  961.36  4692.8  958.75    4763     940  4802.8  938.67
  4873.2  943.39  5133.8  943.31  5284.2  958.44  5639.5  987.73  5685.1  995.64
  5865.5 1006.77  6246.4 1001.99  6365.9 1008.56  7287.7  1028.5  7609.2 1041.33
#Mann= 7 ,-1 , 0
  1220.4      .1       0  1250.1     .16       0  1369.8      .1       0
  4015.7     .05       0    4065      .1       0  4682.8     .07       0
  5284.2     .16       0
Bank Sta=4692.8,5284.2
XS Rating Curve= 0 ,0
Exp/Cntr=0.3,0.1

Type RM Length L Ch R = 1 ,189192  ,1363,1363,1363
BEGIN DESCRIPTION:
Mapping XS 21c20cbf
END DESCRIPTION:
XS GIS Cut Line= 3
      2931548.63     10079354.92      2933791.86     10078709.72
      2935732.17     10077105.94
#Sta/Elev= 30
  3195.3 1077.55  3330.9 1070.75  4046.5 1013.88  4163.2 1011.31  4336.9  999.23
  4421.5 1002.73  4559.9 1011.58  4681.3 1006.48  4724.7  998.79  4733.5  987.75
  4738.7  976.49  4745.5  957.71  4755.9  945.73  4766.3  942.78  4811.3  940.87
    4845   935.3  4956.3   934.5  5202.8  940.65  5265.8  952.97  5328.2  955.59
  5758.6     977  5914.3  988.61  6070.6   984.6  6220.4  996.58  6504.4 1011.42
  6689.4 1031.54    6916 1020.62  7228.7 1020.91  7825.3 1031.22  8046.8 1040.32
#Mann= 5 ,-1 , 0
  3195.3      .1       0  4421.5     .16       0  4681.3      .1       0
  4738.7     .05       0  5328.2     .16       0
Bank Sta=4745.5,5328.2
XS Rating Curve= 0 ,0
Exp/Cntr=0.3,0.1

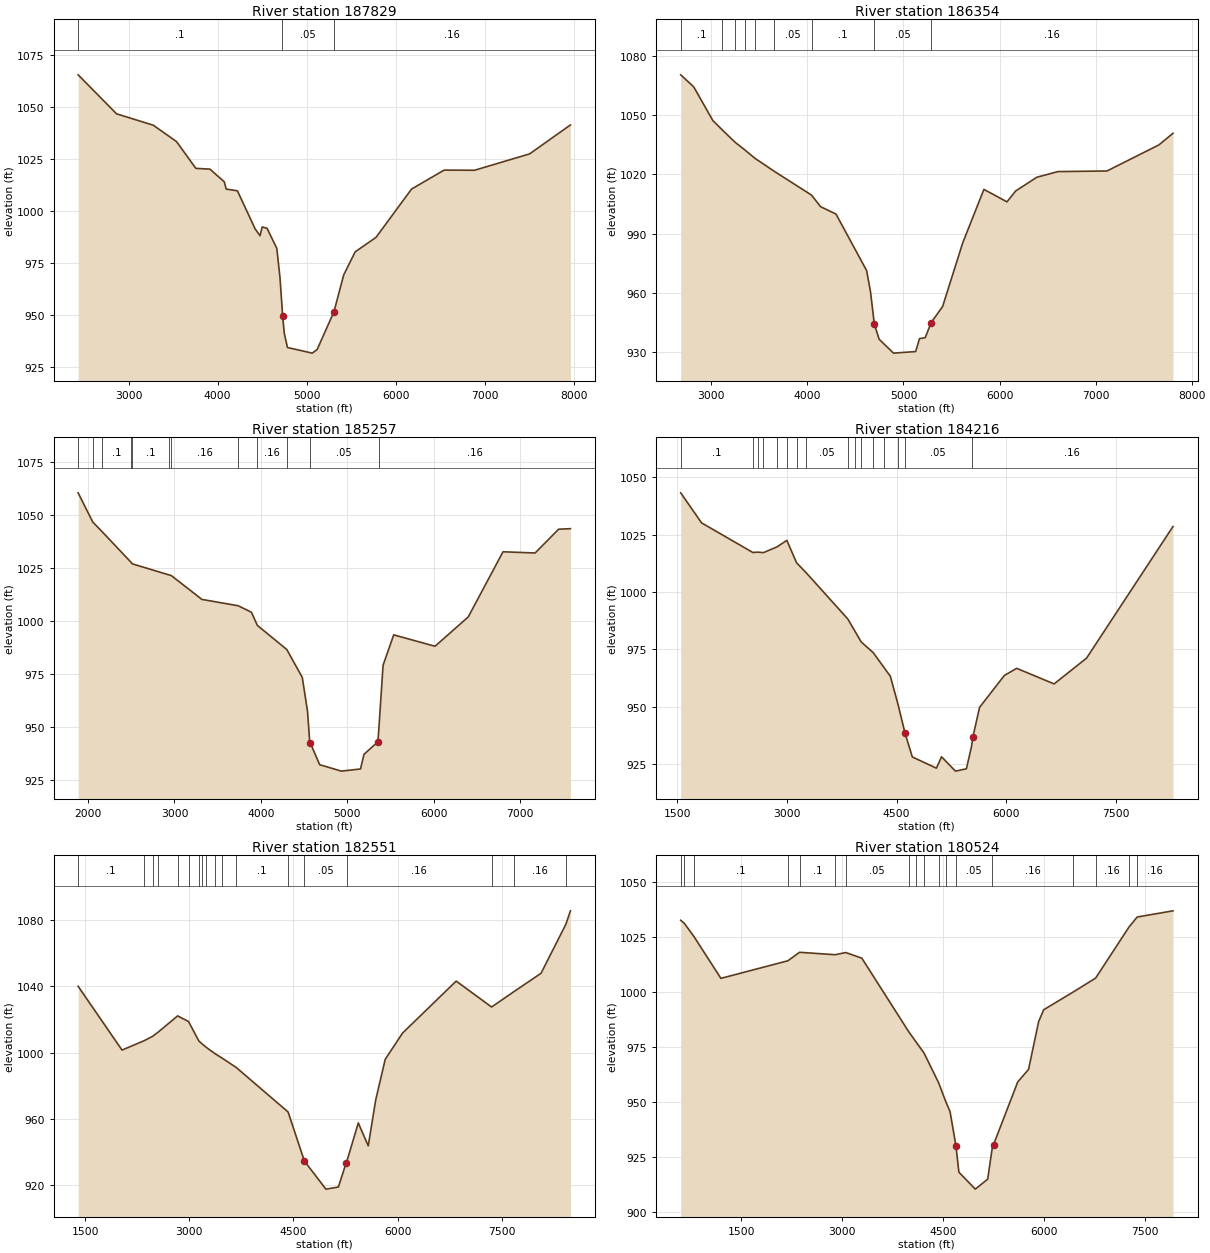
Type RM Length L Ch R = 1 ,187829  ,1475,1475,1475
BEGIN DESCRIPTION:
Mapping XS b890d0d6
END DESCRIPTION:
XS GIS Cut Line= 3
      2933469.39     10081993.58      2934915.21     10078246.08
       2935862.8     10077074.96
#Sta/Elev= 30
  2434.6 1065.61  2865.6 1046.86  3277.6 1041.38  3538.4 1033.51  3754.9 1020.63
  3913.3 1020.26  4074.4 1014.15  4095.8 1010.67  4221.5 1009.84  4420.6  991.51
  4475.1  988.25  4499.7  992.45  4554.3  991.81  4663.5  982.14  4698.8  968.29
  4723.4  953.21  4728.8  949.49    4748  941.15  4783.4  934.48  5061.4  931.78
  5116.2  933.54  5304.5  951.64  5413.7  969.35  5542.8  980.49  5776.5  987.44
  6175.2 1010.67    6541  1019.8  6881.5 1019.71  7500.3  1027.6  7957.8 1041.51
#Mann= 3 ,-1 , 0
  2434.6      .1       0  4723.4     .05       0  5304.5     .16       0
Bank Sta=4728.8,5304.5
XS Rating Curve= 0 ,0
Exp/Cntr=0.3,0.1

Type RM Length L Ch R = 1 ,186354  ,1097,1097,1097
BEGIN DESCRIPTION:
Mapping XS 67e10a41
END DESCRIPTION:
XS GIS Cut Line= 3
       2935355.7     10082136.13      2935809.54     10080524.93
      2935938.68     10077077.35
#Sta/Elev= 30
  2681.6 1070.29  2817.4  1064.2  3016.5 1047.15  3113.6 1042.47  3247.2 1036.22
  3348.1 1032.36  3454.2 1028.09    3651 1021.65  4043.2 1009.47  4138.6 1003.59
  4297.9  999.89  4616.9  971.29  4656.9  960.73  4696.9  944.34    4747  936.59
  4896.8  929.56  5127.2  930.36  5167.3  936.87  5227.3  937.41  5287.4  944.94
  5407.4  953.09  5617.6  985.39  5837.7 1012.37  6077.9 1006.05    6168 1011.55
  6388.1 1018.49  6608.3 1021.36  7118.6 1021.66    7659 1034.85  7805.5 1040.73
#Mann= 9 ,-1 , 0
  2681.6      .1       0  3113.6     .05       0  3247.2      .1       0
  3348.1     .05       0  3454.2      .1       0    3651     .05       0
  4043.2      .1       0  4696.9     .05       0  5287.4     .16       0
Bank Sta=4696.9,5287.4
XS Rating Curve= 0 ,0
Exp/Cntr=0.3,0.1

Type RM Length L Ch R = 1 ,185257  ,1041,1041,1041
BEGIN DESCRIPTION:
Mapping XS 67f809a9
END DESCRIPTION:
XS GIS Cut Line= 3
      2935729.15     10082299.14      2937047.54     10080974.18
       2936651.7     10077167.94
#Sta/Elev= 30
  1885.7 1060.64  2054.1 1046.91    2165  1042.2  2491.5  1028.1    2514 1027.09
  2931.1 1021.95  2963.7 1021.57  3317.4 1010.31  3737.9 1007.31  3890.9 1004.24
  3959.1  998.05  4300.2  986.64  4479.2  973.48  4539.5  957.49  4566.1  942.52
  4571.1  942.61  4680.2  932.26  4931.3  929.22  5152.8  930.24    5193  937.14
  5353.9  943.06  5363.9  948.61  5414.2  979.27  5537.1  993.57    6015  988.18
  6399.4 1002.04  6801.6  1032.8  7173.2 1032.23  7445.1 1043.46  7581.6 1043.72
#Mann= 12 ,-1 , 0
  1885.7      .1       0  2054.1     .05       0    2165      .1       0
  2491.5     .05       0    2514      .1       0  2931.1     .05       0
  2963.7     .16       0  3737.9      .1       0  3959.1     .16       0
  4300.2      .1       0  4566.1     .05       0  5363.9     .16       0
Bank Sta=4571.1,5353.9
XS Rating Curve= 0 ,0
Exp/Cntr=0.3,0.1

Type RM Length L Ch R = 1 ,184216  ,1665,1665,1665
BEGIN DESCRIPTION:
Mapping XS 5781f7d6
END DESCRIPTION:
XS GIS Cut Line= 4
      2936144.78      10082382.4       2937881.4     10080932.35
      2938039.07     10077639.93      2937125.21     10076887.61
#Sta/Elev= 30
  1544.2 1043.22  1829.9 1030.14  2532.1 1017.24  2597.8 1017.38  2678.1 1017.18
  2864.4  1019.7  2997.7 1022.51    3131 1012.77  3262.2 1008.44  3833.3  988.27
  3931.5  982.91  4015.7  978.31  4180.7  973.63  4327.1  967.21  4415.9  963.32
  4521.1  951.03  4616.2  938.63  4716.3   928.2  5046.6  923.31  5116.7  928.28
  5306.7  922.02  5457.1  923.04  5527.2  932.74  5547.2  936.98  5637.3  949.79
  5977.7   963.7  6146.2  966.79  6658.5     960  7102.8  971.23  8286.5 1028.54
#Mann= 16 ,-1 , 0
  1544.2      .1       0  2532.1     .05       0  2597.8      .1       0
  2678.1     .05       0  2864.4     .16       0  2997.7      .1       0
    3131      .1       0  3262.2     .05       0  3833.3      .1       0
  3931.5     .16       0  4015.7      .1       0  4180.7     .16       0
  4327.1      .1       0  4521.1     .05       0  4616.2     .05       0
  5527.2     .16       0
Bank Sta=4616.2,5547.2
XS Rating Curve= 0 ,0
Exp/Cntr=0.3,0.1

Type RM Length L Ch R = 1 ,182551  ,2027,2027,2027
BEGIN DESCRIPTION:
Mapping XS f110a0e2
END DESCRIPTION:
XS GIS Cut Line= 4
      2936310.98     10082631.84      2938906.24     10081244.43
      2939887.42     10079811.15      2940125.17     10077406.97
#Sta/Elev= 30
  1396.4 1040.12  2028.6 1001.55  2347.3 1007.21  2468.2 1009.84  2554.3 1012.56
  2830.3 1022.22    2987 1018.84  3136.8 1007.03  3180.2 1005.41  3241.3 1003.26
  3373.5  999.27  3470.3  996.73  3673.8  991.08  4422.8  964.13  4657.1  934.51
  4967.7   917.5  5147.3  918.78  5261.1  933.57  5269.9  934.38  5434.4  957.51
  5577.9  943.67  5685.5  971.45    5823     996  6072.7 1011.85  6845.6 1043.25
    7356 1027.59  7681.4 1036.98  8068.3 1047.97  8426.3 1077.58  8492.1 1085.73
#Mann= 18 ,-1 , 0
  1396.4      .1       0  2347.3     .16       0  2468.2      .1       0
  2554.3     .05       0  2830.3     .16       0    2987      .1       0
  3136.8     .05       0  3180.2      .1       0  3241.3     .05       0
  3373.5     .16       0  3470.3     .05       0  3673.8      .1       0
  4422.8      .1       0  4657.1     .05       0  5269.9     .16       0
    7356      .1       0  7681.4     .16       0  8426.3      .1       0
Bank Sta=4657.1,5261.1
XS Rating Curve= 0 ,0
Exp/Cntr=0.3,0.1

Type RM Length L Ch R = 1 ,180524  ,1991,1991,1991
BEGIN DESCRIPTION:
Mapping XS 3410d31a
END DESCRIPTION:
XS GIS Cut Line= 3
      2938521.78     10086037.34      2940918.85     10081704.74
      2940308.95      10079418.6
#Sta/Elev= 30
   601.5 1032.44   654.1  1031.1   793.5 1025.31  1199.1 1006.11    2194 1014.08
  2368.2 1017.93  2897.2 1016.83  3054.2 1017.82  3293.7 1015.28    3993  981.84
  4105.2  977.07  4218.8  972.25  4434.6  958.84  4544.4  950.05  4605.6  945.67
  4693.1   930.2  4736.6  918.25  4980.3  910.56    5165  915.08  5230.2  928.75
    5252  930.74  5611.8  959.17  5772.2  964.83  5922.3  986.51  5997.3  991.88
  6433.6  999.88  6769.3 1006.23  7264.2 1029.33    7387 1033.92  7919.1 1036.73
#Mann= 18 ,-1 , 0
   601.5      .1       0   654.1     .05       0   793.5      .1       0
    2194     .16       0  2368.2      .1       0  2897.2     .05       0
  3054.2     .05       0    3993     .05       0  4105.2      .1       0
  4218.8      .1       0  4434.6     .05       0  4544.4      .1       0
  4693.1     .05       0  5230.2     .16       0  6433.6      .1       0
  6769.3     .16       0  7264.2      .1       0    7387     .16       0
Bank Sta=4693.1,5252
XS Rating Curve= 0 ,0
Exp/Cntr=0.3,0.1