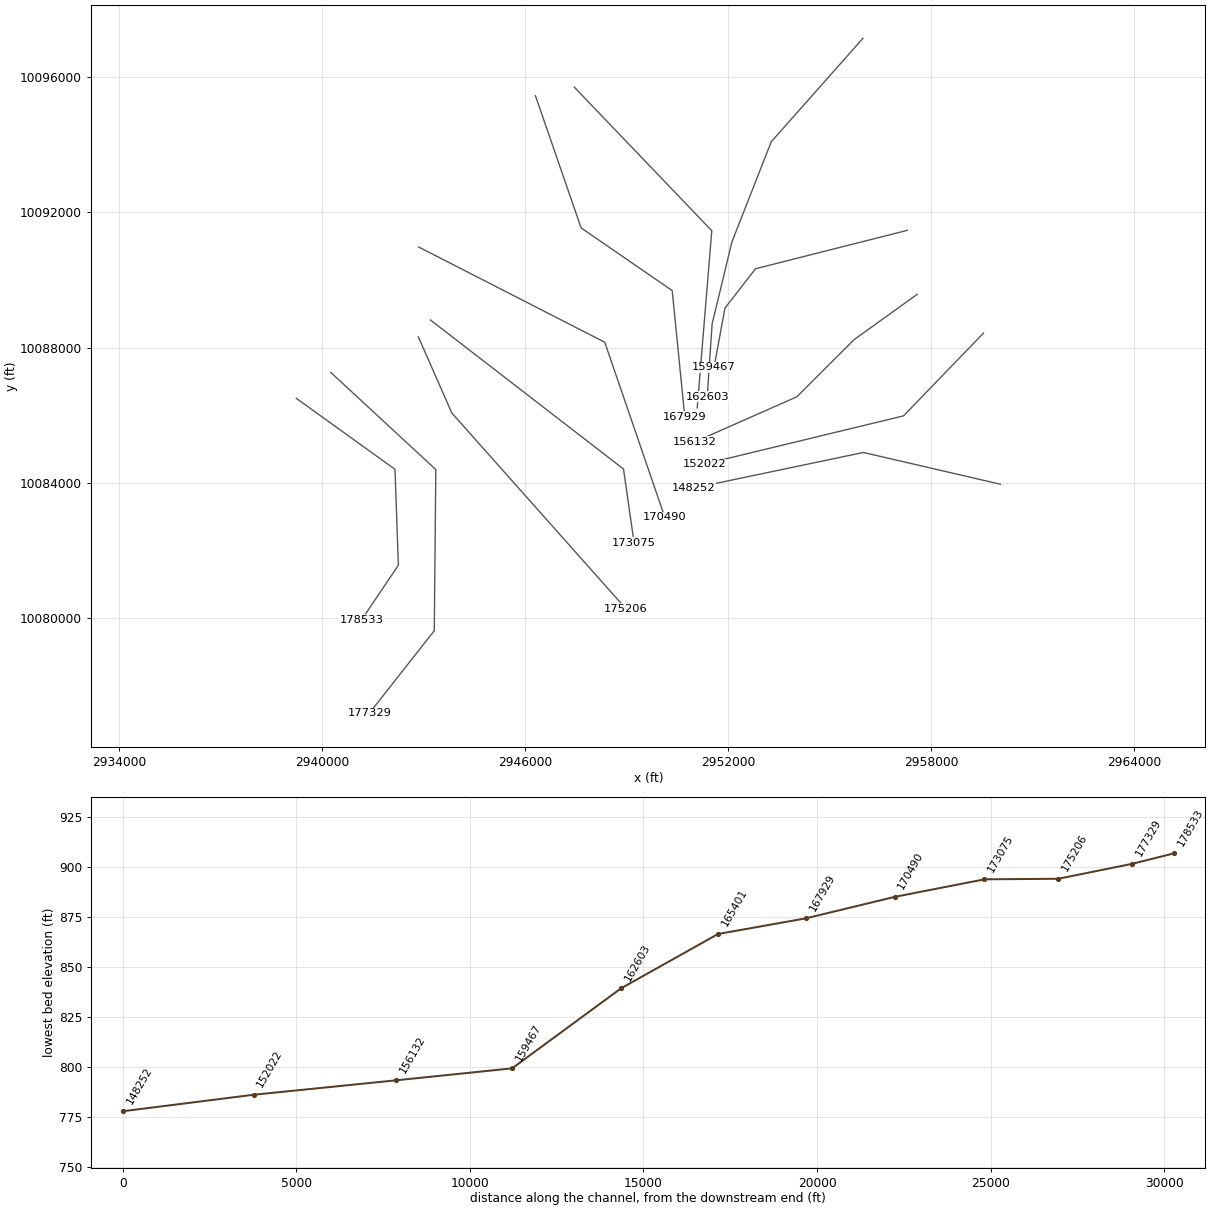
HEC-RAS study PEDERNALES RIVER.prj: PEDERNALES RIVER Base Level Engineering

--- PEDERNALES RIVER.g01 (geometry) --- (continued)

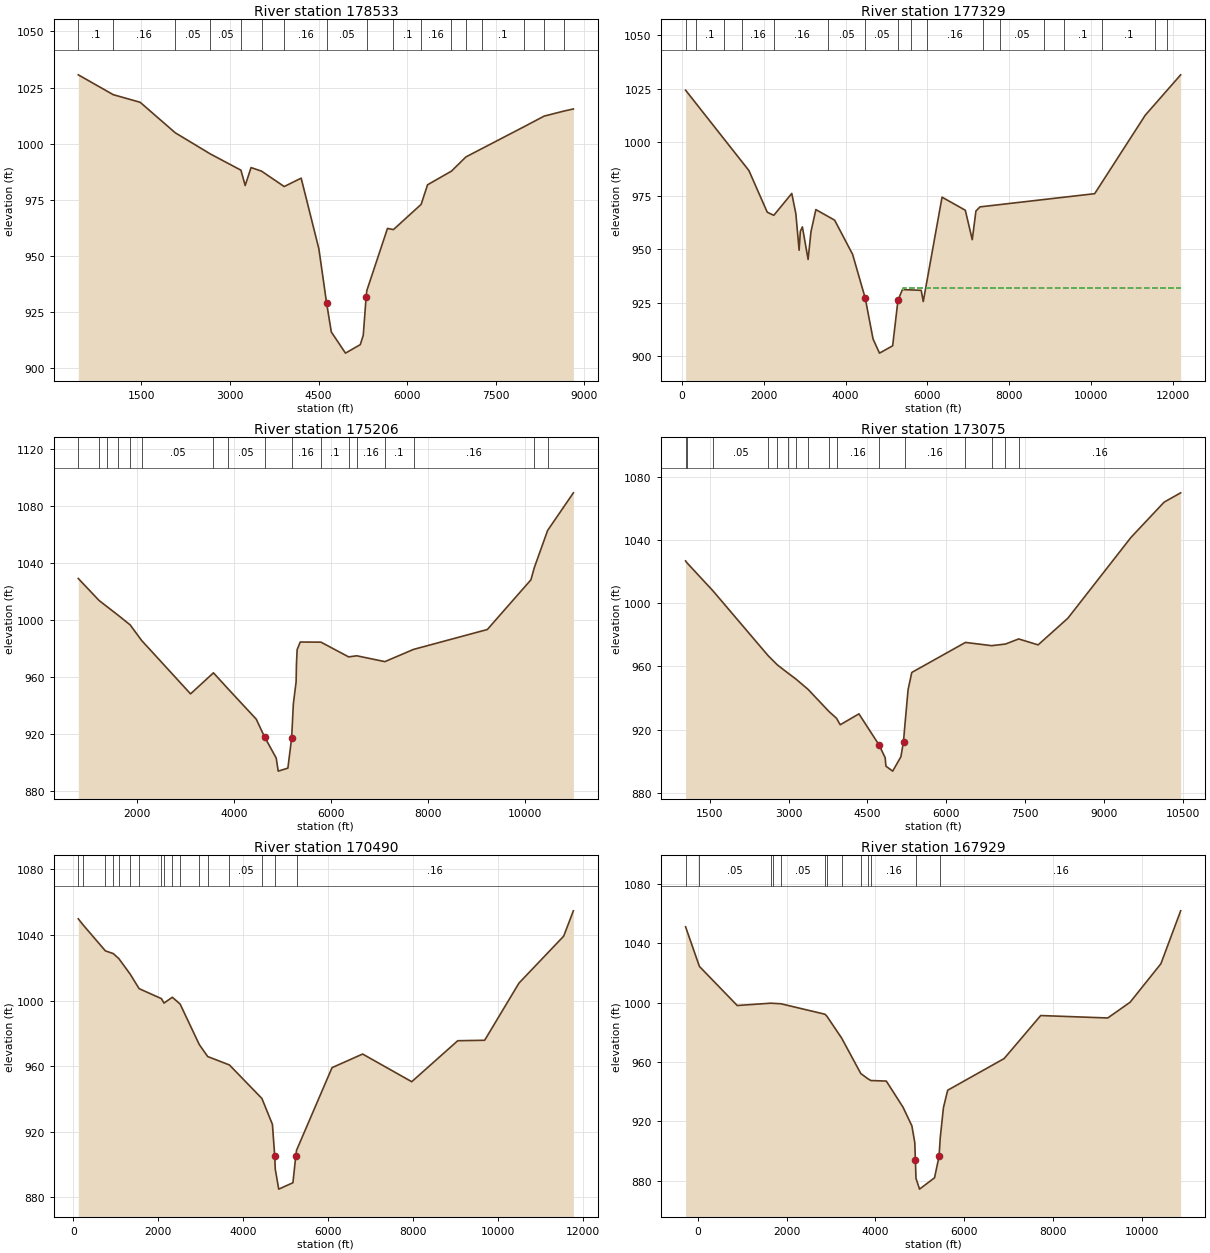
Type RM Length L Ch R = 1 ,178533  ,1204,1204,1204
BEGIN DESCRIPTION:
Mapping XS 3a03abcc
END DESCRIPTION:
XS GIS Cut Line= 4
      2939245.24     10086501.97      2942161.74     10084402.37
      2942261.75       10081565.      2941174.79       10079950.
#Sta/Elev= 30
   433.9 1030.66  1024.3 1021.83  1481.3 1018.42  2074.2 1004.85  2667.9  995.42
  3186.8  988.17  3258.5  981.35  3358.1  989.33  3534.8  987.75  3919.3  980.88
  4206.3  984.62  4506.5  953.03  4636.6  928.97  4716.6  916.06  4956.5  906.64
  5206.9  910.43  5256.9  914.61  5305.5  931.52    5317  934.48  5667.2  962.22
  5767.7  961.69  6236.6  972.93  6345.1  981.65  6750.3  987.75  6994.4  994.07
  7261.6  997.73  7970.6 1007.43  8318.1 1012.26  8650.5 1014.49  8813.4 1015.45
#Mann= 17 ,-1 , 0
   433.9      .1       0  1024.3     .16       0  2074.2     .05       0
  2667.9     .05       0  3186.8     .16       0  3534.8      .1       0
  3919.3     .16       0  4636.6     .05       0    5317     .16       0
  5767.7      .1       0  6236.6     .16       0  6750.3     .05       0
  6994.4     .16       0  7261.6      .1       0  7970.6     .05       0
  8318.1      .1       0  8650.5     .05       0
Bank Sta=4636.6,5305.5
XS Rating Curve= 0 ,0
Exp/Cntr=0.3,0.1

Type RM Length L Ch R = 1 ,177329  ,2123,2123,2123
BEGIN DESCRIPTION:
Mapping XS 7138c78d
END DESCRIPTION:
XS GIS Cut Line= 4
      2940260.01      10087272.9      2943368.36     10084394.43
      2943322.82     10079628.14      2941399.72     10077182.54
#Sta/Elev= 30
      84 1024.35 1632.71   986.8 2082.33   967.3  2242.2  965.87 2681.83  976.09
 2781.74  966.61 2861.68  949.55 2891.65  958.38 2941.61  960.45 3081.49  945.24
 3151.43  958.18 3271.33  968.54 3730.95   963.6 4170.58  947.62  4480.3  927.08
  4670.4  908.09  4828.3  901.44  5150.4  904.87  5280.4  926.14 5389.67  931.15
 5849.33  930.79  5899.3  925.56 6358.96  974.35 6928.54  968.24 7098.42  954.47
 7188.35  967.88 7288.28  969.8110094.09  975.9811330.58 1012.6312198.12 1031.54
#Mann= 17 ,-1 , 0
    83.2     .05       0   343.2      .1       0  1013.4     .16       0
  1452.9     .16       0  2258.9     .16       0  3575.9     .05       0
  4480.3     .05       0  5280.4     .16       0  5610.4      .1       0
    6003     .16       0  7358.6      .1       0  7773.9     .05       0
  8856.2     .16       0  9335.9      .1       0 10275.8      .1       0
 11582.3     .05       0 11858.2     .05       0
#XS Ineff= 2 , 0
                         5393.18          931.71
Permanent Ineff=
       F       F
Bank Sta=4480.3,5280.4
XS Rating Curve= 0 ,0
Exp/Cntr=0.3,0.1

Type RM Length L Ch R = 1 ,175206  ,2131,2131,2131
BEGIN DESCRIPTION:
Mapping XS 95bb0334
END DESCRIPTION:
XS GIS Cut Line= 3
      2942851.32     10088320.41      2943842.58     10086066.96
      2948992.14     10080270.83
#Sta/Elev= 30
   782.9 1029.24  1211.7  1013.8  1384.3 1009.25  1602.8  1003.5    1854  996.63
  2087.3  985.82  3099.3  948.23  3571.8  963.01  3862.7  952.15  4455.1  930.46
  4625.7  918.04  4866.5  903.17  4908.1  893.99  5107.4  896.11  5185.1  917.22
  5220.3  941.23  5277.1  956.64  5283.8  968.79    5298  979.26  5362.4  984.63
  5789.3  984.55  6360.6  974.21  6529.8  974.96  7108.6  970.87  7699.3  979.44
  9222.5  993.41 10122.3 1028.31 10191.6 1036.83 10466.2 1062.94   10998 1089.38
#Mann= 17 ,-1 , 0
   782.9      .1       0  1211.7     .05       0  1384.3      .1       0
  1602.8     .05       0    1854     .05       0  2087.3     .05       0
  3571.8      .1       0  3862.7     .05       0  4625.7     .05       0
  5185.1     .16       0  5789.3      .1       0  6360.6      .1       0
  6529.8     .16       0  7108.6      .1       0  7699.3     .16       0
 10191.6      .1       0 10466.2     .16       0
Bank Sta=4625.7,5185.1
XS Rating Curve= 0 ,0
Exp/Cntr=0.3,0.1

Type RM Length L Ch R = 1 ,173075  ,2585,2585,2585
BEGIN DESCRIPTION:
Mapping XS 212ea356
END DESCRIPTION:
XS GIS Cut Line= 3
      2943209.75     10088819.64      2948915.14      10084410.6
      2949228.35     10082227.84
#Sta/Elev= 30
  1041.5 1026.69  1060.5 1025.77  1563.4 1007.71  2609.6  966.81  2787.7  960.87
  2985.4  955.81  3138.6  951.99  3372.2  945.39  3766.6  931.47  3912.1  927.14
  3982.4  923.02  4338.4  929.92  4716.9  910.49  4837.3  902.22  4851.8  896.82
  4980.2  893.69  5136.2  902.76    5186  912.43  5208.7  921.39    5273  945.22
  5343.6  956.12  6364.2  975.11  6862.1  973.07  7125.8  974.09  7376.3  977.32
  7746.2  973.57  8312.5  990.45  9512.1 1041.55 10142.1 1063.85 10457.1 1069.76
#Mann= 16 ,-1 , 0
  1041.5     .05       0  1060.5      .1       0  1563.4     .05       0
  2609.6     .05       0  2787.7     .16       0  2985.4     .05       0
  3138.6      .1       0  3372.2     .16       0  3766.6      .1       0
  3912.1     .16       0  4716.9     .05       0  5208.7     .16       0
  6364.2     .16       0  6862.1      .1       0  7125.8      .1       0
  7376.3     .16       0
Bank Sta=4716.9,5186
XS Rating Curve= 0 ,0
Exp/Cntr=0.3,0.1

Type RM Length L Ch R = 1 ,170490  ,2561,2561,2561
BEGIN DESCRIPTION:
PEDERNALES RIVER 24.0
END DESCRIPTION:
XS GIS Cut Line= 3
      2942857.68     10090980.16      2948361.22     10088161.54
      2950138.87     10082976.85
#Sta/Elev= 30
   118.5 1049.82   232.6  1046.1   757.2 1030.29   940.8 1028.64  1072.1 1025.62
  1339.8 1016.15  1551.5 1007.24  2077.3 1001.14  2137.6  998.44    2334 1001.97
  2517.7  997.84  2968.9  973.14  3166.9  965.82  3679.1  960.69  4444.4  940.25
  4692.1  924.47  4746.5  905.18  4759.5  897.09  4840.7  884.94  5175.2  888.84
  5242.6  905.14  5260.4  908.63  6096.5  959.03  6817.5  967.35  7974.4  950.47
  9058.7  975.47  9692.9  975.75 10501.8 1010.64 11554.6 1039.27 11782.8 1054.71
#Mann= 17 ,-1 , 0
   118.5     .05       0   232.6      .1       0   757.2     .16       0
   940.8      .1       0  1072.1     .16       0  1339.8     .16       0
  1551.5      .1       0  2077.3     .05       0  2137.6      .1       0
    2334     .05       0  2517.7      .1       0  2968.9     .05       0
  3166.9     .16       0  3679.1     .05       0  4444.4     .16       0
  4759.5     .05       0  5260.4     .16       0
Bank Sta=4746.5,5242.6
XS Rating Curve= 0 ,0
Exp/Cntr=0.3,0.1

Type RM Length L Ch R = 1 ,167929  ,2528,2528,2528
BEGIN DESCRIPTION:
PEDERNALES RIVER 23.0
END DESCRIPTION:
XS GIS Cut Line= 4
      2946312.21       10095455.      2947662.45     10091543.61
      2950354.58     10089688.71        2950726.     10085960.63
#Sta/Elev= 30
  -278.2 1051.23    33.4 1024.49   885.9   998.1  1637.2  999.68  1702.4  999.57
  1871.2  999.28  2862.1  992.23  2904.1  990.95  3238.5   976.1  3669.5   952.2
  3836.4  948.53  3897.3  947.49    4244  947.12  4619.9  929.55  4820.2   916.9
  4885.8  905.64  4899.2  893.88  4912.8  881.45    4993  874.21  5330.7  881.86
  5432.2  896.28  5459.2  908.82  5530.9  929.17  5626.3  940.93  6898.3   962.3
  7722.4  991.34  9232.7   989.7  9736.1  1000.3 10430.2 1026.29 10875.5    1062
#Mann= 13 ,-1 , 0
  -278.2     .16       0    33.4     .05       0  1637.2      .1       0
  1702.4     .16       0  1871.2     .05       0  2862.1      .1       0
  2904.1     .05       0  3238.5      .1       0  3669.5     .16       0
  3836.4      .1       0  3897.3     .16       0  4912.8     .05       0
  5459.2     .16       0
Bank Sta=4899.2,5432.2
XS Rating Curve= 0 ,0
Exp/Cntr=0.3,0.1

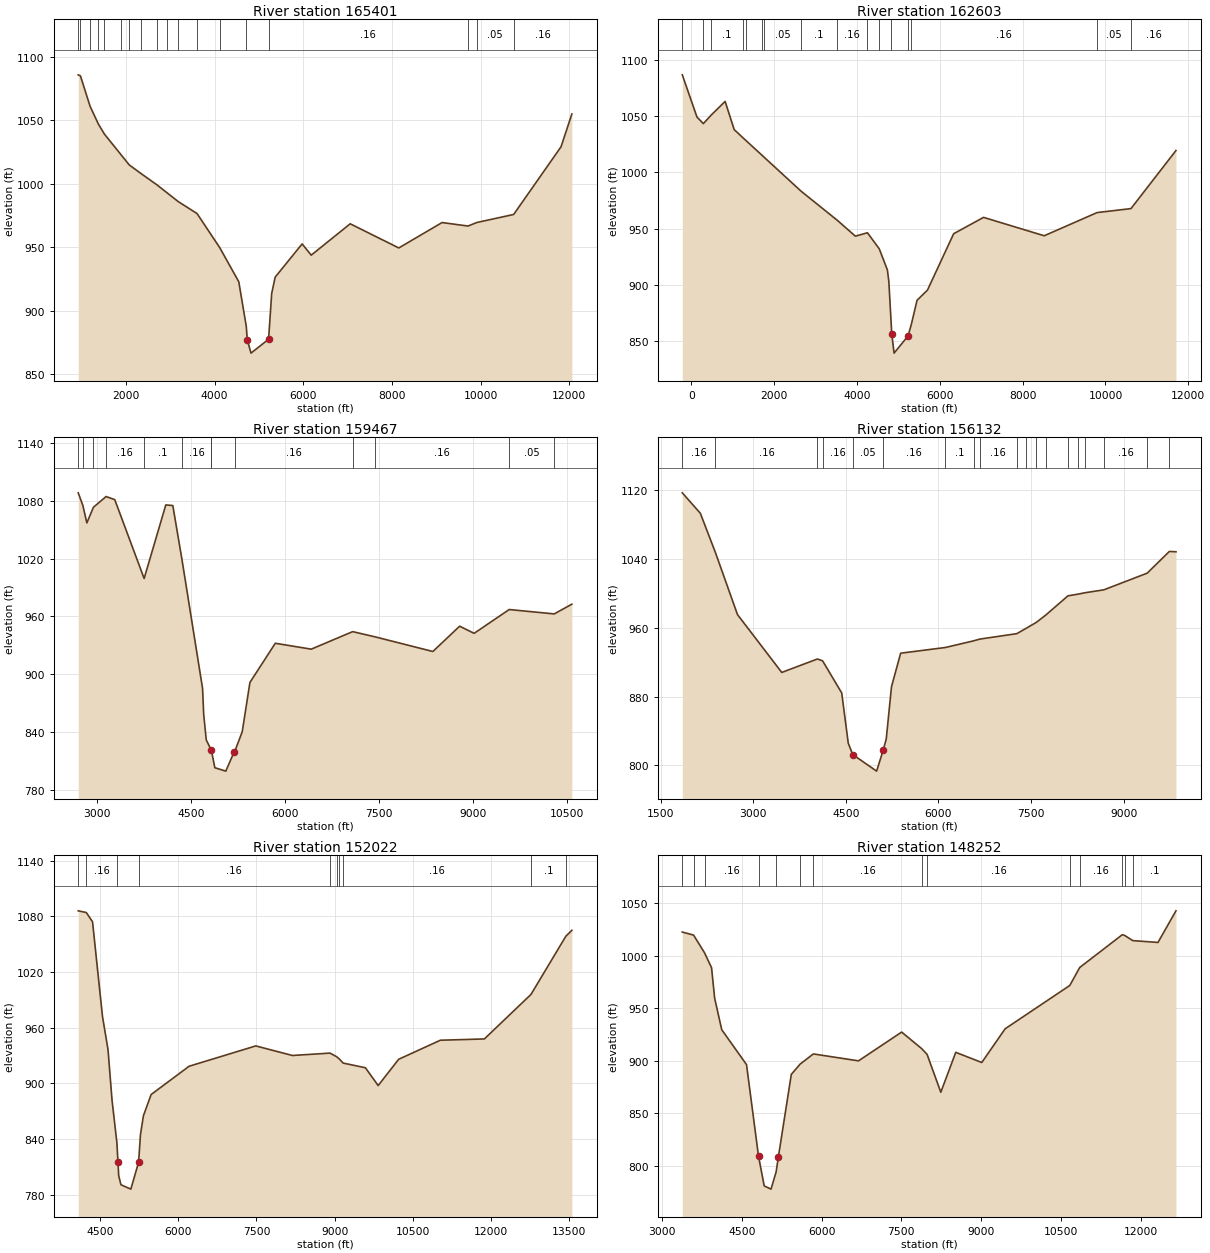
Type RM Length L Ch R = 1 ,165401  ,2798,2798,2798
BEGIN DESCRIPTION:
PEDERNALES RIVER 270.0
END DESCRIPTION:
XS GIS Cut Line= 3
       2947461.4     10095706.95      2951524.09      10091460.1
       2951093.8     10086220.31
#Sta/Elev= 30
   925.6 1085.75   975.9  1084.9  1192.6 1061.01  1381.1  1046.9  1517.4 1039.01
  1893.4 1022.69  2077.2 1014.72  2351.7 1007.71  2701.2  999.04  2939.2   992.5
  3179.6   985.9  3605.7  976.42  4114.7  949.72    4547  922.68  4716.9  887.39
  4737.9  877.07  4822.6  866.41  5219.1  877.33  5289.6  913.42  5367.6  926.29
  5975.8  952.49  6180.9  943.62    7060  968.35  8156.6   949.3  9131.9  969.32
  9718.3  966.57  9916.3  969.36 10746.8  975.69 11815.4 1029.03 12060.2 1054.88
#Mann= 18 ,-1 , 0
   925.6     .05       0   975.9      .1       0  1192.6     .05       0
  1381.1     .05       0  1517.4      .1       0  1893.4      .1       0
  2077.2     .05       0  2351.7     .05       0  2701.2     .05       0
  2939.2      .1       0  3179.6     .16       0  3605.7     .05       0
  4114.7     .16       0  4716.9     .05       0  5219.1     .16       0
  9718.3      .1       0  9916.3     .05       0 10746.8     .16       0
Bank Sta=4737.9,5219.1
XS Rating Curve= 0 ,0
Exp/Cntr=0.3,0.1

Type RM Length L Ch R = 1 ,162603  ,3136,3136,3136
BEGIN DESCRIPTION:
PEDERNALES RIVER 271.0
END DESCRIPTION:
XS GIS Cut Line= 5
      2955991.18     10097151.27      2953282.11     10094092.64
      2952116.93     10091121.43      2951534.34     10088703.68
      2951388.71     10086548.42
#Sta/Elev= 30
  -221.6 1086.68     133  1049.1   286.8  1043.3   480.3 1051.04     813 1063.05
  1032.1 1037.96  1236.2 1030.97  1310.9 1028.44    1707 1015.04  1743.5 1013.81
  2650.2  983.15  3517.7  957.48  3959.8  943.22    4250  946.26  4535.5  932.01
  4732.4  913.22  4767.6  902.91  4829.8  861.75  4838.6  856.08    4894  839.24
  5231.4  854.52  5310.1  864.69  5448.3  886.19  5700.5  895.28  6333.6  945.42
  7055.8  959.94  8520.6  943.58  9797.9   964.2 10616.2  967.74 11702.9 1019.37
#Mann= 16 ,-1 , 0
  -221.6      .1       0   286.8     .16       0   480.3      .1       0
  1236.2     .16       0  1310.9      .1       0    1707     .16       0
  1743.5     .05       0  2650.2      .1       0  3517.7     .16       0
    4250     .05       0  4535.5     .16       0  4829.8     .05       0
  5231.4      .1       0  5310.1     .16       0  9797.9     .05       0
 10616.2     .16       0
Bank Sta=4838.6,5231.4
XS Rating Curve= 0 ,0
Exp/Cntr=0.3,0.1

Type RM Length L Ch R = 1 ,159467  ,3335,3335,3335
BEGIN DESCRIPTION:
PEDERNALES RIVER 272.0
END DESCRIPTION:
XS GIS Cut Line= 4
      2957302.03       10091471.      2952816.03     10090334.94
      2951913.02     10089169.75       2951592.6     10087422.03
#Sta/Elev= 30
  2697.4 1088.26  2772.1 1075.02  2835.2 1057.03  2940.8 1073.31  3142.2  1084.4
  3280.4 1081.22  3749.4  999.33  4095.2 1075.69  4207.2 1075.05  4354.5 1018.49
  4681.7  885.25  4699.9  858.25  4740.9  831.69  4822.9  820.87  4877.7  802.86
  5052.8  799.32  5186.7  819.32  5191.9  819.07  5314.8  840.19  5437.8  891.38
  5842.7  932.07  6416.6  925.95  7077.4  944.15  7441.8  938.62  8357.6  923.53
  8784.9   949.8  9016.1  942.38  9575.6  967.09   10295  962.55   10576  972.67
#Mann= 13 ,-1 , 0
  2697.4      .1       0  2772.1     .16       0  2940.8      .1       0
  3142.2     .16       0  3749.4      .1       0  4354.5     .16       0
  4822.9    .033       0  4822.9     .05       0  5191.9     .16       0
  7077.4      .1       0  7441.8     .16       0  9575.6     .05       0
   10295     .16       0
Bank Sta=4822.9,5186.7
XS Rating Curve= 0 ,0
Exp/Cntr=0.3,0.1

Type RM Length L Ch R = 1 ,156132  ,4110,4110,4110
BEGIN DESCRIPTION:
PEDERNALES RIVER 273.0
END DESCRIPTION:
XS GIS Cut Line= 4
      2957593.31     10089577.59      2955728.99     10088237.61
      2954039.47      10086548.1      2951012.41     10085209.21
#Sta/Elev= 30
  1852.4 1116.65  2144.7  1092.9  2389.3  1047.2  2746.3  975.19  3463.3  907.99
  4040.2  923.62  4124.3  921.51  4434.3   884.2  4540.3  825.81  4610.7  812.93
  4618.1  812.33  4999.7  793.36    5106  817.78  5155.5  830.68  5240.4  891.38
  5388.9  930.35  6112.8  936.97    6574  944.77  6668.4   946.7  7270.1  953.06
  7423.9  959.36  7584.6  966.08  7739.8  974.71  8098.8  996.98  8257.1  998.91
  8377.9 1000.61  8680.7 1003.98  9382.1 1023.34  9740.7 1048.57  9847.6 1048.17
#Mann= 19 ,-1 , 0
  1852.4     .16       0  2389.3     .16       0  4040.2      .1       0
  4124.3     .16       0  4610.7     .05       0    5106     .16       0
  6112.8      .1       0    6574     .16       0  6668.4     .16       0
  7270.1      .1       0  7423.9     .16       0  7584.6      .1       0
  7739.8     .16       0  8098.8      .1       0  8257.1     .16       0
  8377.9      .1       0  8680.7     .16       0  9382.1      .1       0
  9740.7     .16       0
#XS Ineff= 2 , 0
         4172.73  887.11
Permanent Ineff=
       F       F
Bank Sta=4618.1,5106
XS Rating Curve= 0 ,0
Exp/Cntr=0.3,0.1

Type RM Length L Ch R = 1 ,152022  ,3770,3770,3770
BEGIN DESCRIPTION:
PEDERNALES RIVER 274.0
END DESCRIPTION:
XS GIS Cut Line= 3
      2959556.26     10088434.01      2957190.58     10085982.94
      2951296.61     10084556.16
#Sta/Elev= 30
  4080.1 1086.07  4234.5 1084.26  4354.6 1074.28  4545.5  972.29  4651.5  936.61
  4729.4  881.65  4821.3   836.6  4842.6  815.48  4856.8  800.67  4899.2  790.86
  5089.8  786.14  5238.5  815.17    5274  844.79  5330.6  865.18  5479.1  888.09
  6207.3  918.57  7486.6  940.48    8189  930.17  8911.2  932.73  9036.6  928.87
  9086.9  926.52  9162.6     922    9590  916.94  9834.6  897.77 10227.7  926.07
 11027.6  946.61 11871.8  947.99 12766.2  995.97   13436 1058.74 13550.8 1065.09
#Mann= 10 ,-1 , 0
  4080.1      .1       0  4234.5     .16       0  4821.3     .05       0
  5238.5     .16       0  8911.2      .1       0  9036.6     .16       0
  9086.9      .1       0  9162.6     .16       0 12766.2      .1       0
   13436     .16       0
Bank Sta=4842.6,5238.5
XS Rating Curve= 0 ,0
Exp/Cntr=0.3,0.1

Type RM Length L Ch R = 1 ,148252  ,3978,3978,3978
BEGIN DESCRIPTION:
PEDERNALES RIVER 275.0
END DESCRIPTION:
XS GIS Cut Line= 3
      2960054.12     10083960.89      2956005.98     10084900.61
      2950993.11     10083849.34
#Sta/Elev= 30
  3383.4 1022.31  3595.4 1019.43  3800.9 1002.61  3933.3  988.43  3991.4  959.45
  4124.4  929.49  4590.3  896.31  4816.2  809.06  4922.8  780.98  5050.5  777.91
  5146.3   794.2  5188.9  808.46  5432.1  887.02  5598.7  896.81  5846.2  906.43
  6695.3  899.87  7505.8  927.24  7884.3  911.39  7984.2  905.98  8241.7  870.03
  8522.7  907.96  9011.5   898.3  9450.5  930.33 10665.6  971.53 10852.6  988.63
 11652.4 1019.79 11696.1 1019.13 11848.9 1014.18 12323.3 1012.45 12661.1  1042.5
#Mann= 14 ,-1 , 0
  3383.4     .16       0  3595.4      .1       0  3800.9     .16       0
  4816.2     .05       0  5146.3     .16       0  5598.7      .1       0
  5846.2     .16       0  7884.3      .1       0  7984.2     .16       0
 10665.6      .1       0 10852.6     .16       0 11652.4      .1       0
 11696.1     .16       0 11848.9      .1       0
Bank Sta=4816.2,5188.9
XS Rating Curve= 0 ,0
Exp/Cntr=0.3,0.1