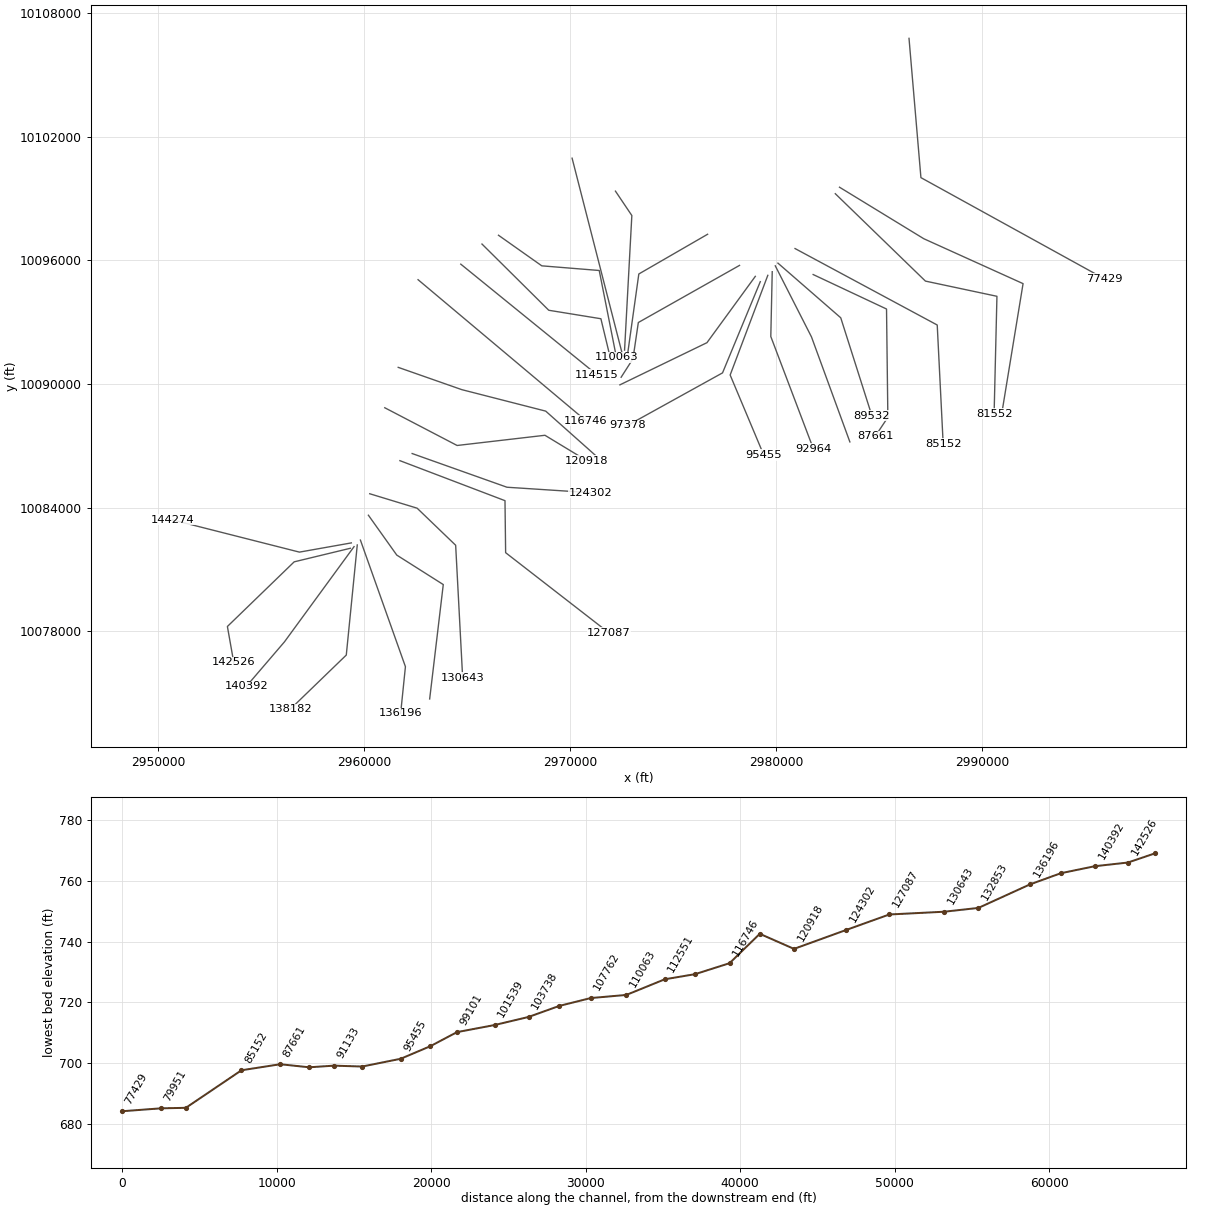
HEC-RAS study PEDERNALES RIVER.prj: PEDERNALES RIVER Base Level Engineering

--- PEDERNALES RIVER.g01 (geometry) --- (continued)

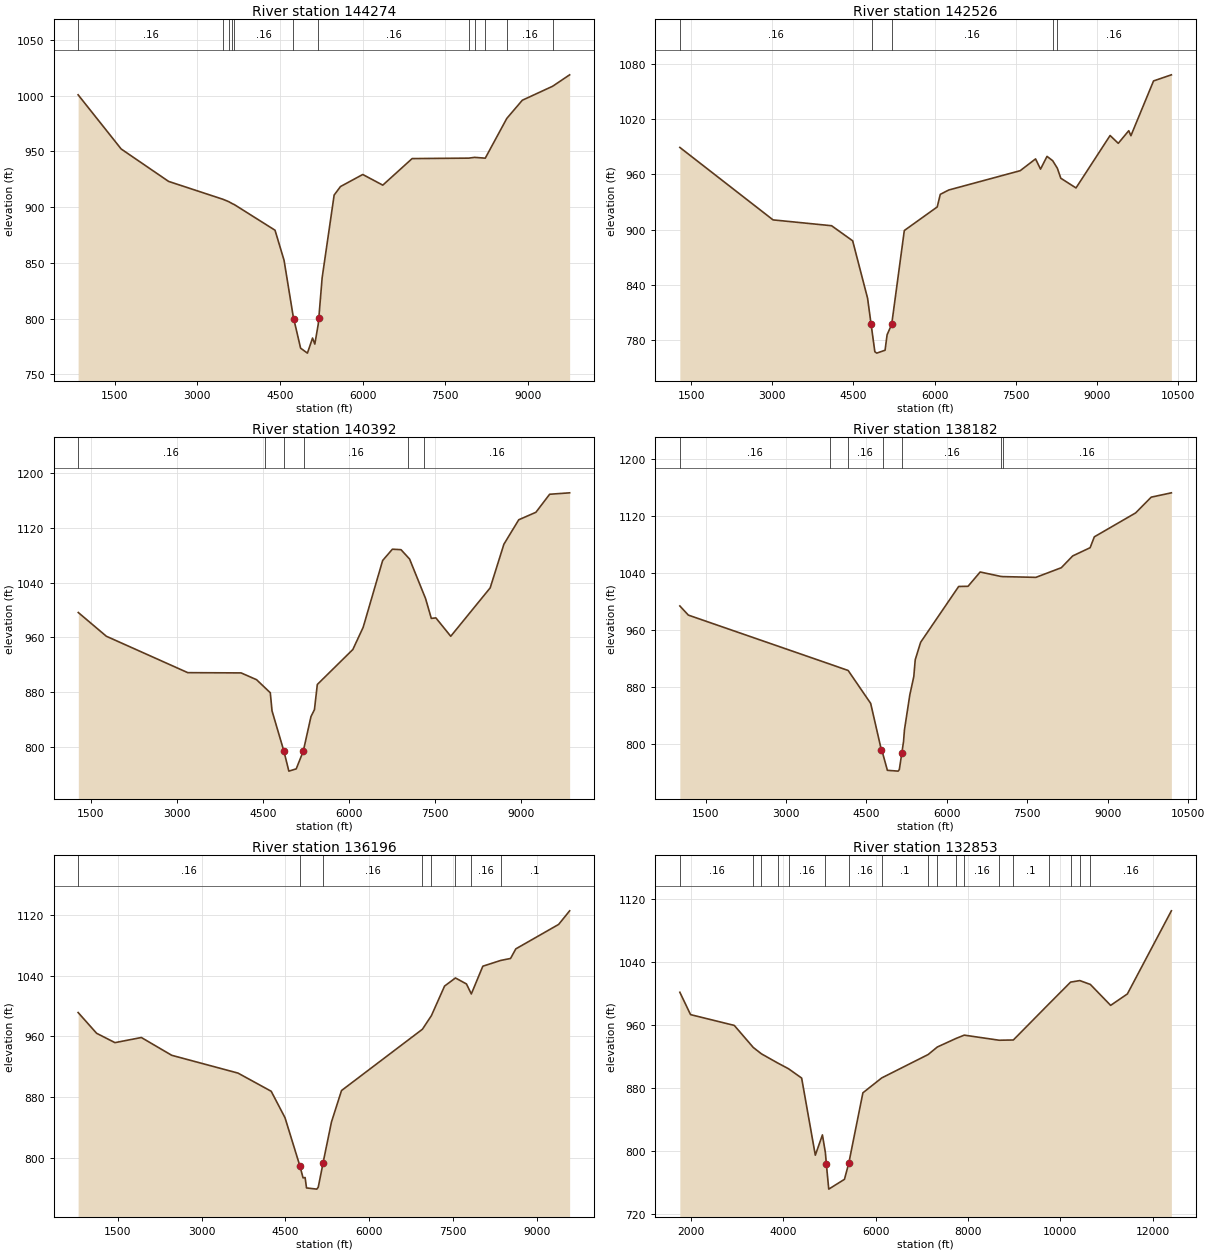
Type RM Length L Ch R = 1 ,144274  ,1748,1748,1748
BEGIN DESCRIPTION:
PEDERNALES RIVER 276.0
END DESCRIPTION:
XS GIS Cut Line= 3
      2959371.63     10082285.78      2956851.02     10081838.04
      2950685.76     10083402.78
#Sta/Elev= 30
   837.9 1000.88  1619.8  952.24  2480.3  923.15  3469.8  907.06  3572.7  904.94
  3635.7   903.2  3675.6  902.27  4411.7  879.34  4575.6  852.35  4739.4  802.66
  4752.5  799.69  4875.9  773.49  4999.5  769.03  5092.6  782.56  5133.9  777.15
  5195.8   794.9  5206.1  800.26  5266.8  836.63  5484.6  910.88  5599.6  918.53
    6004  929.36  6367.5   919.8    6900  943.64  7928.6  944.04  8033.6  944.73
  8227.3  944.01  8618.5   979.7  8899.6     996  9449.8 1008.55  9758.7 1018.81
#Mann= 12 ,-1 , 0
   837.9     .16       0  3469.8      .1       0  3572.7     .16       0
  3635.7      .1       0  3675.6     .16       0  4739.4     .05       0
  5195.8     .16       0  7928.6      .1       0  8033.6     .16       0
  8227.3      .1       0  8618.5     .16       0  9449.8      .1       0
Bank Sta=4752.5,5206.1
XS Rating Curve= 0 ,0
Exp/Cntr=0.3,0.1

Type RM Length L Ch R = 1 ,142526  ,2134,2134,2134
BEGIN DESCRIPTION:
PEDERNALES RIVER 277.0
END DESCRIPTION:
XS GIS Cut Line= 4
      2959322.71     10082024.75      2956596.41     10081366.15
      2953353.73     10078227.17      2953661.42     10076487.39
#Sta/Elev= 30
  1291.4  989.27  3013.8  910.63  4096.1  904.29  4485.3  887.92  4761.3  825.56
  4824.8  798.01    4839  791.88  4895.5  767.55  4930.5  766.02  5084.5  769.18
  5121.9  785.95  5206.7  797.16  5440.1  899.08  6048.2  924.66  6104.8  938.34
  6260.5  943.04  7582.9  964.04  7865.7  976.81  7957.7  965.73  8077.9  979.55
  8182.6  974.83  8268.7  966.67  8332.5  955.83  8613.5  945.29  9243.4 1002.21
  9394.7  993.71  9588.3 1007.44  9628.2 1001.96 10046.5 1061.43   10376 1068.06
#Mann= 5 ,-1 , 0
  1291.4     .16       0    4839     .05       0  5206.7     .16       0
  8182.6      .1       0  8268.7     .16       0
Bank Sta=4824.8,5206.7
XS Rating Curve= 0 ,0
Exp/Cntr=0.3,0.1

Type RM Length L Ch R = 1 ,140392  ,2210,2210,2210
BEGIN DESCRIPTION:
PEDERNALES RIVER 278.0
END DESCRIPTION:
XS GIS Cut Line= 3
      2959504.06     10082105.15      2956123.43     10077480.01
      2954274.93     10075321.73
#Sta/Elev= 30
    1280  996.34  1769.9  961.69 3189.63  908.57 4119.45   908.2  4389.4   898.3
 4629.35  879.19 4659.35  852.79  4867.5  793.68    4953  764.82  5081.3   768.1
  5204.2   793.9 5339.22  844.58 5399.21  854.54  5449.2  891.29 6069.07  942.38
 6249.04  974.77 6588.97 1072.31 6758.93 1088.78 6908.91 1088.09 7058.74 1074.46
 7337.92 1016.64 7437.62  987.78 7517.39  988.52 7776.63  961.68  8464.6 1032.33
  8703.9 1096.088963.141 1131.76 9262.26 1142.68 9501.55 1168.99 9850.53 1171.08
#Mann= 6 ,-1 , 0
  1276.9     .16       0    4530      .1       0  4867.5     .05       0
  5210.4     .16       0  7035.5      .1       0  7303.1     .16       0
Bank Sta=4867.5,5204.2
XS Rating Curve= 0 ,0
Exp/Cntr=0.3,0.1

Type RM Length L Ch R = 1 ,138182  ,1986,1986,1986
BEGIN DESCRIPTION:
PEDERNALES RIVER 279.0
END DESCRIPTION:
XS GIS Cut Line= 3
      2959659.31     10082185.19       2959126.2      10076839.9
      2956398.19     10074202.03
#Sta/Elev= 30
  1019.2  994.17  1177.6  981.33  3824.4  912.42  4158.2  903.65  4578.2  857.48
  4779.2  791.54  4799.3  788.25  4889.8  763.64  5090.5   762.5  5112.3  764.68
  5159.9  788.26  5191.3  804.24  5207.9  820.32  5308.5  869.63  5382.2  895.09
  5409.1  918.75  5509.8  943.21  6219.2 1021.48  6393.8 1021.72  6620.1 1041.78
  7008.2 1035.53  7051.4  1035.3  7659.7 1034.27  8133.5 1047.79  8345.7 1064.33
  8670.9 1075.85  8748.8 1091.08  9519.5 1124.66  9809.7 1146.75 10185.8 1152.82
#Mann= 7 ,-1 , 0
  1019.2     .16       0  3824.4      .1       0  4158.2     .16       0
  4799.3     .05       0  5159.9     .16       0  7008.2      .1       0
  7051.4     .16       0
Bank Sta=4779.2,5159.9
XS Rating Curve= 0 ,0
Exp/Cntr=0.3,0.1

Type RM Length L Ch R = 1 ,136196  ,3343,3343,3343
BEGIN DESCRIPTION:
PEDERNALES RIVER 280.0
END DESCRIPTION:
XS GIS Cut Line= 3
      2959812.65     10082421.41      2961997.82     10076276.32
      2961765.41     10074008.25
#Sta/Elev= 30
   786.6  991.37  1117.9  964.01  1446.6  951.72  1918.8  958.46  2463.4  935.03
  3649.4  911.63  4244.1   887.7  4491.8  852.84  4758.8  789.16  4815.2  773.63
  4851.3  774.12  4876.8   760.4  5061.7  758.84  5087.4  761.52  5174.7   793.8
    5180     796  5323.6  847.23  5503.3  888.62  6952.5  969.37  7112.8  987.21
  7348.9 1026.19  7543.9 1036.88  7741.1 1028.98    7828 1015.83    8034 1052.34
  8354.8 1059.95  8530.6 1062.55  8624.9 1075.18  9392.1  1107.4  9588.6 1125.26
#Mann= 8 ,-1 , 0
   786.6     .16       0  4758.8     .05       0    5180     .16       0
  6952.5      .1       0  7112.8     .16       0  7543.9      .1       0
    7828     .16       0  8354.8      .1       0
Bank Sta=4758.8,5174.7
XS Rating Curve= 0 ,0
Exp/Cntr=0.3,0.1

Type RM Length L Ch R = 1 ,132853  ,2210,2210,2210
BEGIN DESCRIPTION:
PEDERNALES RIVER 281.0
END DESCRIPTION:
XS GIS Cut Line= 4
      2960200.13     10083629.46      2961578.22     10081693.24
      2963835.49     10080262.69      2963174.86     10074708.11
#Sta/Elev= 30
  1762.7  1001.6  1994.7  973.15  2941.5  959.41  3352.1  931.39  3529.8  923.23
  3881.4  911.59  4115.7  904.27    4400  892.43    4696  794.27  4849.9  820.09
  4914.3  797.48  4935.5  782.58  4986.9  751.09    5327  763.56    5421  784.24
    5726  873.62    6133  892.57  7138.3  922.35  7337.3  931.92  7735.5  942.65
  7920.5  947.04  8676.8  940.56  8983.7  940.87  9745.6  986.28 10223.9 1014.53
   10423 1016.46 10650.9 1011.58 11090.6  984.91 11453.1  999.48 12405.4 1105.23
#Mann= 18 ,-1 , 0
  1762.7     .16       0  3352.1      .1       0  3529.8     .16       0
  3881.4      .1       0  4115.7     .16       0  4914.3     .05       0
    5421     .16       0    6133      .1       0  7138.3     .16       0
  7337.3     .16       0  7735.5      .1       0  7920.5     .16       0
  8676.8     .05       0  8983.7      .1       0  9745.6     .16       0
 10223.9     .08       0   10423      .1       0 10650.9     .16       0
Bank Sta=4935.5,5421
XS Rating Curve= 0 ,0
Exp/Cntr=0.3,0.1

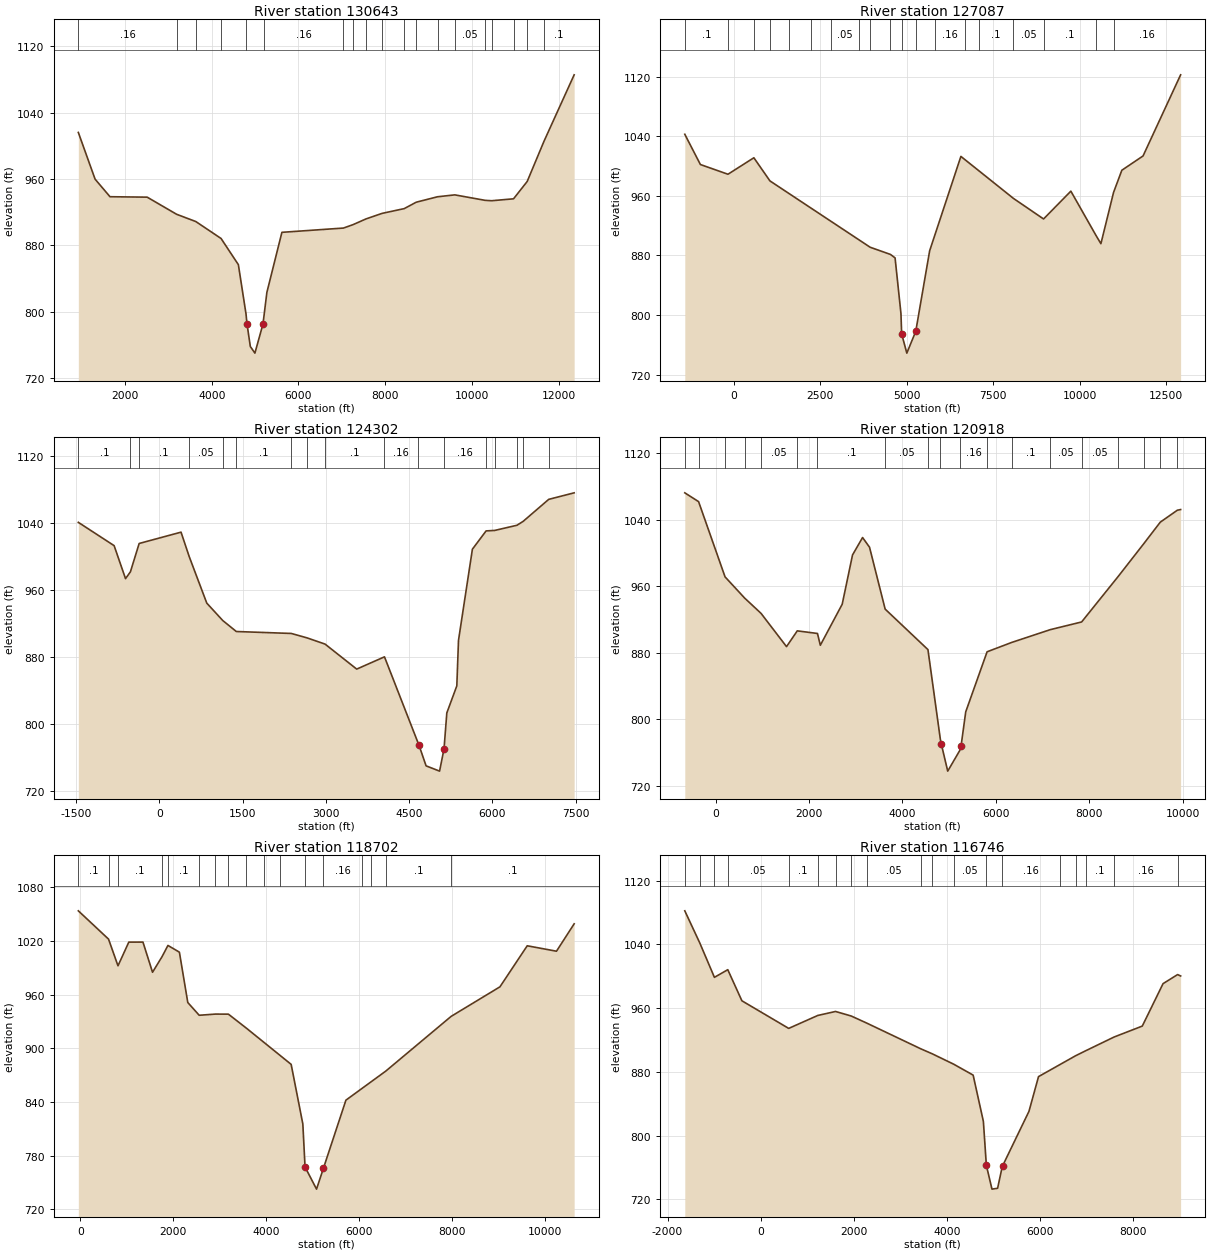
Type RM Length L Ch R = 1 ,130643  ,3556,3556,3556
BEGIN DESCRIPTION:
PEDERNALES RIVER 282.0
END DESCRIPTION:
XS GIS Cut Line= 4
      2960265.41     10084671.92      2962565.79     10083971.09
      2964436.97      10082171.2      2964776.66     10075742.96
#Sta/Elev= 30
     922 1016.11  1308.6  959.75  1652.6  938.56  2510.1  938.04  3189.6  917.37
  3632.5  908.61    4215  888.16    4614  856.59  4790.7  796.99  4812.1  785.54
  4889.8  757.85  4995.5  749.84  5179.7  784.59  5201.1  793.13  5271.8  823.17
  5618.4   895.6  7038.1  900.75  7260.1  904.88  7557.5  911.76  7929.5  918.47
  8440.3  924.21  8716.6  931.94  9207.9   938.5  9607.1  940.79 10305.3  934.21
 10455.4  933.72 10961.6  936.03 11276.9  956.96 11664.4 1005.46 12360.3 1085.64
#Mann= 19 ,-1 , 0
     922     .16       0  3189.6      .1       0  3632.5      .1       0
    4215     .16       0  4790.7     .07       0  5201.1     .16       0
  7038.1     .05       0  7260.1     .16       0  7557.5     .16       0
  7929.5     .05       0  8440.3      .1       0  8716.6     .05       0
  9207.9     .05       0  9607.1     .05       0 10305.3      .1       0
 10455.4     .05       0 10961.6     .16       0 11276.9     .16       0
 11664.4      .1       0
Bank Sta=4812.1,5179.7
XS Rating Curve= 0 ,0
Exp/Cntr=0.3,0.1

Type RM Length L Ch R = 1 ,127087  ,2785,2785,2785
BEGIN DESCRIPTION:
PEDERNALES RIVER 283.0
END DESCRIPTION:
XS GIS Cut Line= 4
      2961730.06     10086278.53       2966832.2      10084336.2
      2966863.35     10081810.49      2971884.47     10077914.82
#Sta/Elev= 30
 -1420.7 1042.77  -969.6 1002.14  -172.1  989.09   576.8 1011.21    1042  980.15
  1584.3  963.48  2217.9  944.01  2808.6  925.86  3630.1  900.62  3941.1  891.06
  4526.4  881.46  4661.2   876.8  4831.2  802.02  4851.2  774.85  5000.9  748.93
    5259  778.16  5661.2  886.35  5816.5  908.13  6564.6 1013.04  6674.1 1008.98
  7082.7  993.82  8085.8  956.61  8955.8  929.05    9745  966.39 10477.2  906.52
   10614  895.86 10980.2  964.71 11219.6  994.46 11833.3 1013.66 12919.7 1122.56
#Mann= 19 ,-1 , 0
 -1420.7      .1       0  -172.1     .16       0   576.8     .05       0
    1042      .1       0  1584.3      .1       0  2217.9     .05       0
  2808.6     .05       0  3630.1     .16       0  3941.1      .1       0
  4526.4     .16       0  4851.2     .07       0    5259     .16       0
  5816.5     .16       0  6674.1      .1       0  7082.7      .1       0
  8085.8     .05       0  8955.8      .1       0 10477.2     .16       0
 10980.2     .16       0
Bank Sta=4851.2,5259
XS Rating Curve= 0 ,0
Exp/Cntr=0.3,0.1

Type RM Length L Ch R = 1 ,124302  ,3384,3384,3384
BEGIN DESCRIPTION:
PEDERNALES RIVER 284.0
END DESCRIPTION:
XS GIS Cut Line= 3
      2962324.77      10086624.4      2966928.33     10084988.44
      2970968.09     10084725.77
#Sta/Elev= 30
 -1458.7 1040.41  -813.7 1012.63  -608.3  973.29  -520.2  981.45  -362.7 1015.22
   391.8 1028.72   538.7  999.66   855.6  944.14  1142.9  923.42    1388  910.28
  2378.7  907.96  2663.8  902.67    2987  895.28  3557.3  865.47  4057.6  880.09
    4660  777.99  4679.7  774.67  4807.2  750.14  5050.2  743.85  5130.6  770.42
  5180.7  813.19  5361.1  845.51  5391.2  899.71  5641.7 1008.41  5888.4 1030.19
  6043.5 1030.78  6444.9 1036.94  6556.2 1041.58  7016.8 1067.81  7475.2  1075.6
#Mann= 17 ,-1 , 0
 -1458.7      .1       0  -520.2     .16       0  -362.7      .1       0
   538.7     .05       0  1142.9     .05       0    1388      .1       0
  2378.7      .1       0  2663.8     .05       0    2987      .1       0
  4057.6     .16       0    4660     .07       0  5130.6     .16       0
  5888.4      .1       0  6043.5     .16       0  6444.9      .1       0
  6556.2     .16       0  7016.8      .1       0
Bank Sta=4679.7,5130.6
XS Rating Curve= 0 ,0
Exp/Cntr=0.3,0.1

Type RM Length L Ch R = 1 ,120918  ,2216,2216,2216
BEGIN DESCRIPTION:
PEDERNALES RIVER 285.0
END DESCRIPTION:
XS GIS Cut Line= 4
      2960995.19     10088847.66      2964507.45     10087015.91
      2968772.24     10087511.23      2970792.64     10086286.11
#Sta/Elev= 30
  -657.7 1072.56  -362.5 1061.98   204.4  971.41   622.8  945.96   975.5  927.46
  1520.6  887.45    1751  906.43  2183.5  903.28  2244.5  889.11    2713  938.47
    2934  997.79  3149.2 1018.76  3298.2 1007.06  3632.7  932.61  4549.1  883.87
  4814.6  775.97  4834.8  770.31  4972.5  737.61  5229.6  762.39  5257.6  767.67
  5358.3     809  5815.6  881.24  6343.2  892.51  7168.5  907.88    7840  917.14
  8627.5  972.23    9182 1012.17  9523.8 1037.23    9889 1051.62  9959.8 1052.44
#Mann= 19 ,-1 , 0
  -657.7      .1       0  -362.5     .05       0   204.4     .05       0
   622.8     .05       0   975.5     .05       0    1751      .1       0
  2183.5      .1       0  3632.7     .05       0  4549.1     .16       0
  4814.6     .07       0  5229.6     .16       0  5815.6     .05       0
  6343.2      .1       0  7168.5     .05       0    7840     .05       0
  8627.5      .1       0    9182     .16       0  9523.8     .16       0
    9889     .16       0
Bank Sta=4834.8,5257.6
XS Rating Curve= 0 ,0
Exp/Cntr=0.3,0.1

Type RM Length L Ch R = 1 ,118702  ,1956,1956,1956
BEGIN DESCRIPTION:
PEDERNALES RIVER 286.0
END DESCRIPTION:
XS GIS Cut Line= 4
      2961648.17     10090808.83      2964734.44     10089727.09
      2968809.86     10088683.59      2971204.71      10086552.8
#Sta/Elev= 30
   -45.3 1053.73   605.6  1022.1   809.3  992.26  1042.3 1018.73  1347.1 1018.77
  1553.5  985.04    1759 1002.52  1885.5 1015.03  2132.2  1007.5  2312.9  951.23
  2558.9  936.96  2908.4  938.27    3188  938.21  3575.2  922.55  3952.2  906.73
  4292.4  892.45  4540.2  882.05  4791.9  815.39  4839.5  767.33    5087  742.57
  5235.6  765.92    5720  842.04  6072.5  855.38  6260.5  862.49  6579.9  874.57
  7986.5   935.7  9038.5  968.75  9626.3 1014.65 10256.8 1008.58 10637.5  1039.2
#Mann= 17 ,-1 , 0
   -45.3      .1       0   605.6     .05       0   809.3      .1       0
    1759     .16       0  1885.5      .1       0  2558.9     .05       0
  2908.4      .1       0    3188     .05       0  3575.2      .1       0
  3952.2      .1       0  4292.4     .16       0  4839.5     .07       0
  5235.6     .16       0  6072.5      .1       0  6260.5     .16       0
  6579.9      .1       0  7986.5      .1       0
Bank Sta=4839.5,5235.6
XS Rating Curve= 0 ,0
Exp/Cntr=0.3,0.1

Type RM Length L Ch R = 1 ,116746  ,2231,2231,2231
BEGIN DESCRIPTION:
PEDERNALES RIVER 287.0
END DESCRIPTION:
XS GIS Cut Line= 2
      2962611.33     10095065.52      2970768.79     10088212.98
#Sta/Elev= 30
 -1629.5 1082.13 -1306.6 1041.71  -993.1  998.66  -705.7 1008.27  -402.7  969.25
   603.1  934.59  1228.1  950.84  1609.4  955.84  1945.7  950.15  2282.2  941.19
  3440.9  908.99    3686  902.75  4148.6  889.66  4566.3  875.97  4786.1  817.87
  4849.9  762.79  4970.6   732.9  5091.8  733.98  5184.1  759.14  5197.2  761.85
  5765.6  830.51  5971.1  874.09  6425.3  889.02  6767.7  900.28  6996.7  906.88
  7594.1  923.76  8200.6  937.51  8646.8  990.75  8959.7 1002.14  9024.2 1000.38
#Mann= 19 ,-1 , 0
 -1629.5      .1       0 -1306.6      .1       0  -993.1      .1       0
  -705.7     .05       0   603.1      .1       0  1228.1     .16       0
  1609.4      .1       0  1945.7     .05       0  2282.2     .05       0
  3440.9      .1       0    3686     .05       0  4148.6     .05       0
  4849.9     .05       0  5184.1     .16       0  6425.3      .1       0
  6767.7     .16       0  6996.7      .1       0  7594.1     .16       0
  8959.7     .16       0
Bank Sta=4849.9,5197.2
XS Rating Curve= 0 ,0
Exp/Cntr=0.3,0.1

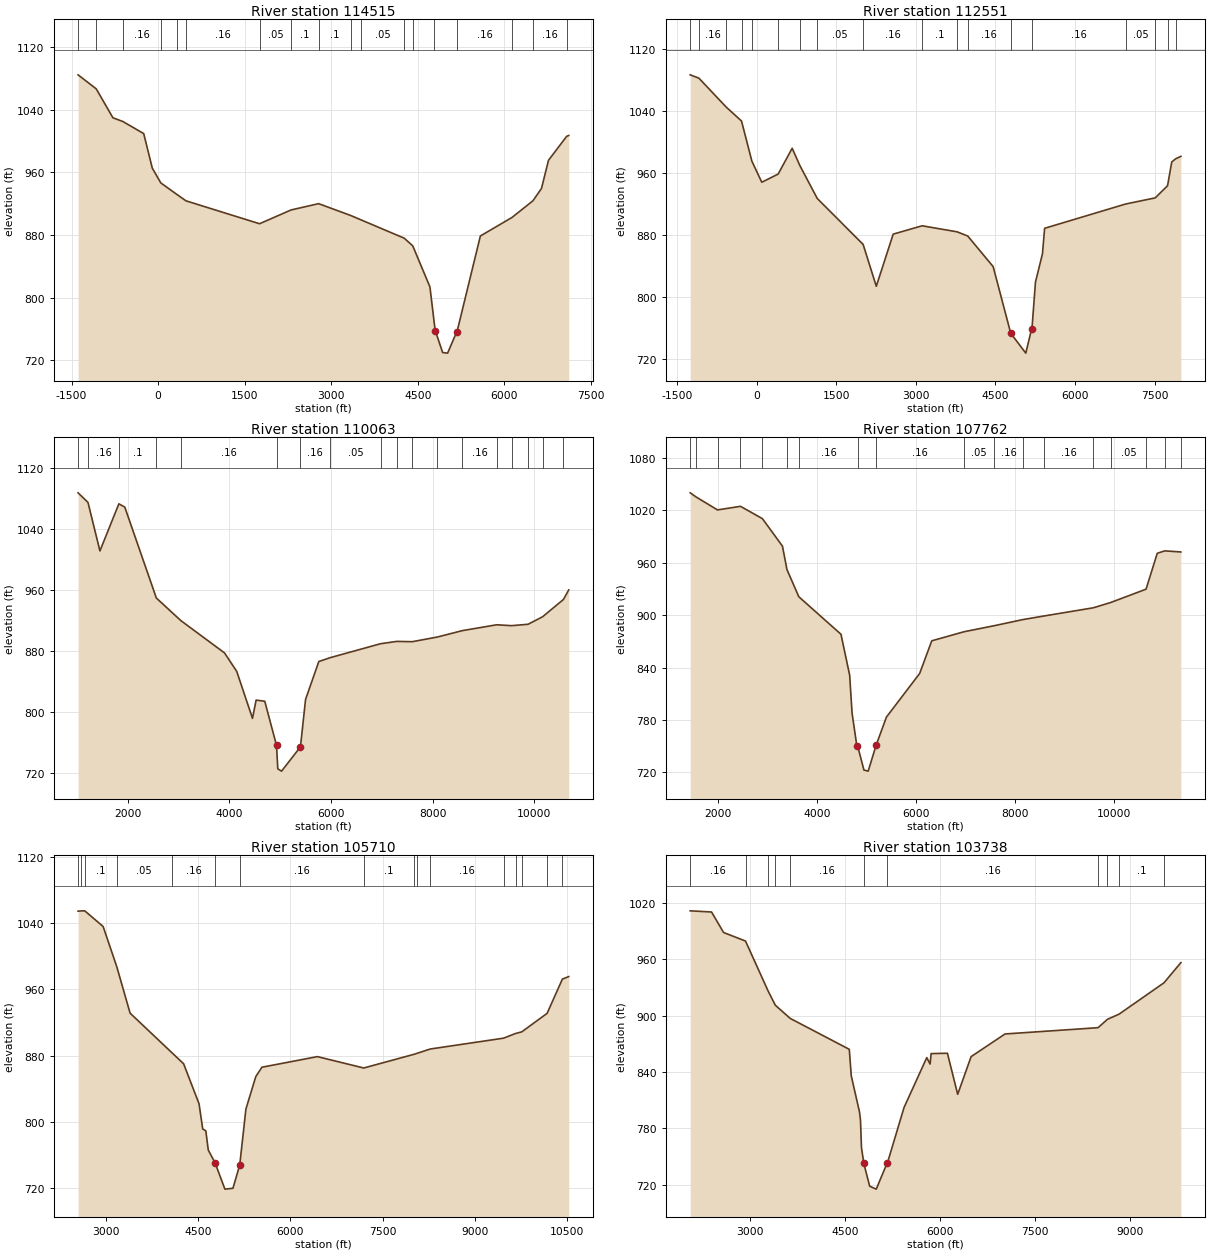
Type RM Length L Ch R = 1 ,114515  ,1964,1964,1964
BEGIN DESCRIPTION:
PEDERNALES RIVER 288.0
END DESCRIPTION:
XS GIS Cut Line= 2
      2964685.32      10095820.3      2971287.96       10090459.
#Sta/Elev= 30
 -1388.3 1084.25 -1073.6 1066.36  -784.1 1029.45  -612.4 1024.73  -250.7 1009.33
  -101.7  965.24    45.9  946.38   324.7  931.67   482.4  923.53  1757.4  894.32
  2304.7  911.92  2781.6  919.93  3337.3  904.84  3522.9  899.05  4264.3  875.93
  4412.6  866.16  4710.6  813.81  4788.9  765.69  4803.2  758.02  4931.1  730.04
  5017.1  729.29  5172.5  755.96  5180.4  756.61  5584.8  878.69  6131.1  902.24
  6495.9  923.58  6644.4  939.33  6765.8  975.24  7080.2 1005.76  7116.9 1006.93
#Mann= 18 ,-1 , 0
 -1388.3      .1       0 -1073.6      .1       0  -612.4     .16       0
    45.9     .05       0   324.7      .1       0   482.4     .16       0
  1757.4     .05       0  2304.7      .1       0  2781.6      .1       0
  3337.3      .1       0  3522.9     .05       0  4264.3      .1       0
  4412.6     .16       0  4788.9     .05       0  5180.4     .16       0
  6131.1      .1       0  6495.9     .16       0  7080.2      .1       0
Bank Sta=4803.2,5172.5
XS Rating Curve= 0 ,0
Exp/Cntr=0.3,0.1

Type RM Length L Ch R = 1 ,112551  ,2488,2488,2488
BEGIN DESCRIPTION:
PEDERNALES RIVER 289.0
END DESCRIPTION:
XS GIS Cut Line= 4
      2965714.96     10096796.53      2968957.78      10093581.3
      2971488.91     10093169.82      2971982.96     10091118.72
#Sta/Elev= 30
 -1249.2  1086.9 -1085.6 1082.62  -569.6 1045.16  -282.8 1027.27   -87.6  975.44
    98.8  948.23   406.8  958.74   671.5  992.11   816.3  969.72  1143.5   927.3
  2007.5  867.94  2255.5   813.9  2573.6  881.22  3118.6  892.01  3776.6  884.22
  3977.9  878.77  4456.5  839.26  4787.1  753.28  5070.5   727.6  5182.2  759.23
  5192.4  764.05  5253.1  819.34  5384.9  855.84  5425.4  888.75  6950.3   920.1
  7508.1  928.04  7740.4   943.7  7819.7  974.42  7893.3  978.52  7991.5  981.65
#Mann= 18 ,-1 , 0
 -1249.2     .16       0 -1085.6     .16       0  -569.6      .1       0
  -282.8     .16       0   -87.6      .1       0   406.8      .1       0
   816.3     .05       0  1143.5     .05       0  2007.5     .16       0
  3118.6      .1       0  3776.6      .1       0  3977.9     .16       0
  4787.1    .035       0  5192.4     .16       0  6950.3     .05       0
  7508.1      .1       0  7740.4     .16       0  7893.3      .1       0
Bank Sta=4787.1,5182.2
XS Rating Curve= 0 ,0
Exp/Cntr=0.3,0.1

Type RM Length L Ch R = 1 ,110063  ,2301,2301,2301
BEGIN DESCRIPTION:
PEDERNALES RIVER 290.0
END DESCRIPTION:
XS GIS Cut Line= 4
      2966517.02     10097223.08      2968618.66     10095738.59
      2971407.92     10095512.58      2972241.11     10091304.12
#Sta/Elev= 30
  1020.8 1087.54  1216.1 1074.96  1451.1  1011.3  1824.1 1073.13  1940.8 1068.79
    2562  949.53  3043.2  919.99  3904.7  877.52  4145.5  853.22  4455.1  791.64
  4526.7  815.63  4697.3   814.1    4928  756.23  4953.6   725.4  5028.1  722.45
  5399.6   754.3  5499.9  816.44  5760.7  866.21  5985.2  871.29    6976  889.58
  7297.2  892.63  7599.9  892.24  8092.4  898.33  8589.4  906.79  9263.2  914.44
  9555.4  913.27  9881.8  915.13 10167.9  924.99 10577.7  947.64 10682.4  960.17
#Mann= 18 ,-1 , 0
  1020.8      .1       0  1216.1     .16       0  1824.1      .1       0
    2562     .16       0  3043.2     .16       0    4928    .035       0
  5399.6     .16       0  5985.2     .05       0    6976     .16       0
  7297.2     .05       0  7599.9      .1       0  8092.4     .16       0
  8589.4     .16       0  9263.2     .05       0  9555.4     .05       0
  9881.8      .1       0 10167.9     .16       0 10577.7     .16       0
Bank Sta=4928,5399.6
XS Rating Curve= 0 ,0
Exp/Cntr=0.3,0.1

Type RM Length L Ch R = 1 ,107762  ,2052,2052,2052
BEGIN DESCRIPTION:
PEDERNALES RIVER 291.0
END DESCRIPTION:
XS GIS Cut Line= 2
      2970090.64     10100965.07      2972552.92     10091360.05
#Sta/Elev= 30
  1435.6 1039.93  1552.1 1035.28  1987.5 1020.37  2451.8 1024.49  2895.1 1010.38
  3299.9  978.93    3391  952.13  3630.6  920.98  4482.4  878.09  4657.9  831.28
  4706.6  787.88  4803.7  750.03  4828.9  748.13  4946.1  722.68  5032.6  721.43
  5190.8  750.78  5401.1  783.27  6072.2  833.17  6317.2  870.56  6970.8  880.98
  7573.4  887.78  8159.5  894.88  8578.4  898.91  9581.9  908.36  9936.3  914.47
 10647.5  929.68 10873.9  970.74 11025.4   973.5 11344.9  972.29 11351.2  972.15
#Mann= 18 ,-1 , 0
  1435.6      .1       0  1552.1     .16       0  1987.5     .16       0
  2451.8      .1       0  2895.1     .16       0    3391      .1       0
  3630.6     .16       0  4828.9    .035       0  5190.8     .16       0
  6970.8     .05       0  7573.4     .16       0  8159.5      .1       0
  8578.4     .16       0  9581.9     .16       0  9936.3     .05       0
 10647.5     .16       0 11025.4      .1       0 11344.9     .16       0
Bank Sta=4803.7,5190.8
XS Rating Curve= 0 ,0
Exp/Cntr=0.3,0.1

Type RM Length L Ch R = 1 ,105710  ,1972,1972,1972
BEGIN DESCRIPTION:
PEDERNALES RIVER 292.0
END DESCRIPTION:
XS GIS Cut Line= 3
      2972195.43     10099365.22      2972991.31     10098181.44
      2972638.06     10091646.83
#Sta/Elev= 30
  2550.7 1054.36    2601 1054.68  2659.5 1054.79  2957.8 1035.84    3179  987.42
    3396  931.26  4071.4  883.75  4265.3  870.15  4515.6  821.88  4575.7  791.41
  4625.8  789.18  4665.9  765.92    4776   750.6    4936  718.82  5066.4  719.83
  5176.6  747.88  5276.8  815.38    5437  854.56  5537.1  865.98  6438.4  878.79
  7191.2  865.05  8009.3  881.61  8049.2  882.58  8272.1  887.98  9461.4  901.04
  9658.8  906.74  9757.5  908.64 10169.6  931.02   10418  972.39 10521.3  975.42
#Mann= 16 ,-1 , 0
  2550.7      .1       0    2601     .05       0  2659.5      .1       0
    3179     .05       0  4071.4     .16       0    4776    .035       0
  5176.6     .16       0  7191.2      .1       0  8009.3     .16       0
  8049.2      .1       0  8272.1     .16       0  9461.4     .05       0
  9658.8     .16       0  9757.5      .1       0 10169.6     .16       0
   10418      .1       0
Bank Sta=4776,5176.6
XS Rating Curve= 0 ,0
Exp/Cntr=0.3,0.1

Type RM Length L Ch R = 1 ,103738  ,2199,2199,2199
BEGIN DESCRIPTION:
PEDERNALES RIVER 293.0
END DESCRIPTION:
XS GIS Cut Line= 3
      2976670.08     10097271.99      2973330.17     10095342.73
      2972791.98     10091496.78
#Sta/Elev= 30
  2054.5 1011.85  2391.3  1010.6  2581.3  988.73  2927.1  979.66  3282.4  926.58
  3397.8  911.22  3631.5  897.21  4564.1  864.22  4595.7  835.87  4724.9  797.56
  4740.7  788.98  4756.5   759.5  4793.3  742.71  4885.7  718.34  4989.4  715.21
  5158.5  742.56  5164.3  742.77  5428.5  802.33  5786.5  855.39    5839  848.53
  5854.8  859.68  6112.5  860.03  6274.1  816.26  6486.1  856.45  7021.3  880.59
  8487.9  887.29  8637.1  896.24  8819.1  901.68  9528.5  935.14    9795  956.63
#Mann= 11 ,-1 , 0
  2054.5     .16       0  2927.1      .1       0  3282.4     .05       0
  3397.8      .1       0  3631.5     .16       0  4793.3    .035       0
  5164.3     .16       0  8487.9      .1       0  8637.1     .16       0
  8819.1      .1       0  9528.5     .16       0
Bank Sta=4793.3,5158.5
XS Rating Curve= 0 ,0
Exp/Cntr=0.3,0.1

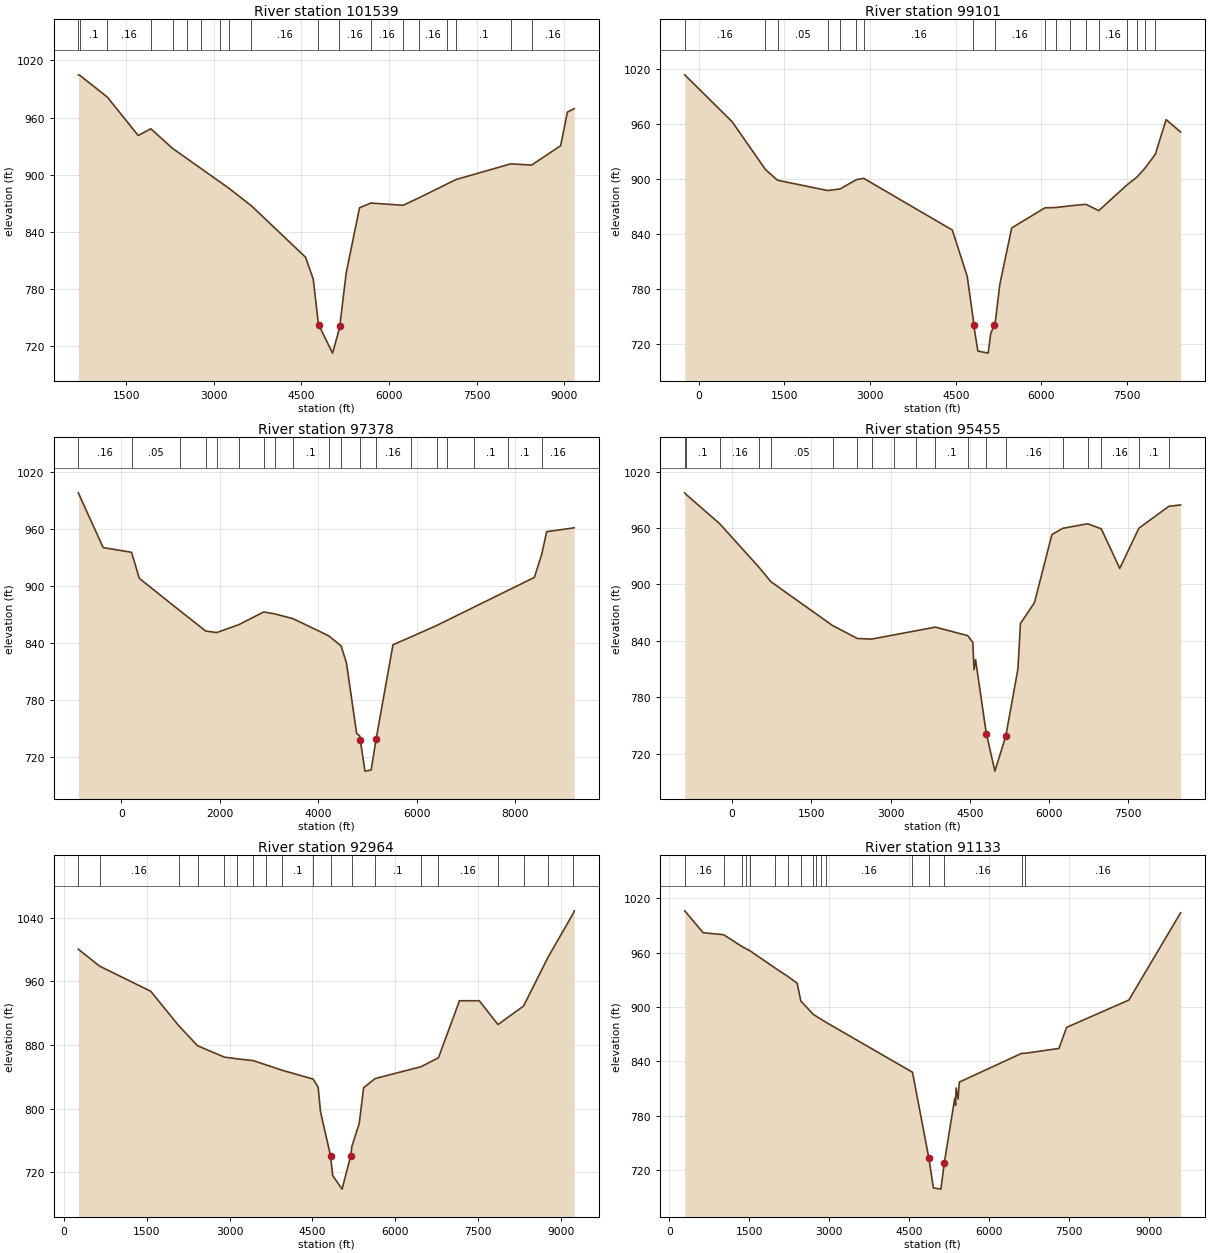
Type RM Length L Ch R = 1 ,101539  ,2438,2438,2438
BEGIN DESCRIPTION:
PEDERNALES RIVER 294.0
END DESCRIPTION:
XS GIS Cut Line= 4
      2978220.18     10095759.74      2973306.44     10092986.37
      2973046.06     10091225.33      2972471.27     10090328.59
#Sta/Elev= 30
   680.3 1004.91   706.3 1004.35  1177.5  981.49  1704.8  941.17    1921  948.26
  2294.4  927.57  2537.5  917.02  2783.7  906.34  3103.3  892.47  3251.7  886.03
  3640.5  867.45  4568.7  813.38  4701.3  790.24  4789.7  743.12  4795.4  742.06
  5032.1  712.55  5149.1  738.57  5156.5  741.16  5264.8  796.69  5493.6  865.23
  5686.3  870.19  6239.7  867.88    6503  875.45  6983.4  890.03    7143  894.87
  8082.8   911.4    8439  910.11  8935.9  930.45  9050.9  965.76    9168  969.35
#Mann= 19 ,-1 , 0
   680.3     .16       0   706.3      .1       0  1177.5     .16       0
    1921      .1       0  2294.4     .16       0  2537.5     .05       0
  2783.7      .1       0  3103.3     .16       0  3251.7     .05       0
  3640.5     .16       0  4789.7    .035       0  5149.1     .16       0
  5686.3     .16       0  6239.7      .1       0    6503     .16       0
  6983.4     .16       0    7143      .1       0  8082.8     .05       0
    8439     .16       0
Bank Sta=4795.4,5156.5
XS Rating Curve= 0 ,0
Exp/Cntr=0.3,0.1

Type RM Length L Ch R = 1 ,99101   ,1723,1723,1723
BEGIN DESCRIPTION:
PEDERNALES RIVER 295.0
END DESCRIPTION:
XS GIS Cut Line= 3
      2978986.28     10095226.64      2976638.87     10092007.54
      2972412.01     10089959.45
#Sta/Elev= 30
  -244.2  1013.2   587.3  962.04  1169.5  910.05  1380.6  898.43  2258.8  887.23
  2475.1  888.95  2761.8   899.1  2890.1  900.51  4440.4  844.18  4700.9  793.81
  4807.1  746.57  4813.8  741.07  4887.1  712.49  5067.5  710.21  5112.9  731.62
  5173.8  740.65    5196  745.51    5271  784.79  5479.7  846.51  6060.6  868.37
  6262.5  868.77  6500.5   870.6  6778.1  872.22  7003.7  865.34  7497.8  893.33
  7672.3  901.87  7817.5   911.9  7994.7  926.79  8182.9  964.46  8436.8  950.89
#Mann= 18 ,-1 , 0
  -244.2     .16       0  1169.5     .05       0  1380.6     .05       0
  2258.8      .1       0  2475.1     .05       0  2761.8     .05       0
  2890.1     .16       0  4807.1    .033       0    5196     .16       0
  6060.6      .1       0  6262.5     .16       0  6500.5     .16       0
  6778.1      .1       0  7003.7     .16       0  7497.8     .05       0
  7672.3      .1       0  7817.5     .16       0  7994.7     .16       0
Bank Sta=4813.8,5173.8
XS Rating Curve= 0 ,0
Exp/Cntr=0.3,0.1

Type RM Length L Ch R = 1 ,97378   ,1923,1923,1923
BEGIN DESCRIPTION:
PEDERNALES RIVER 296.0
END DESCRIPTION:
XS GIS Cut Line= 3
      2979228.19     10094969.25      2977394.83     10090541.16
      2972783.04       10087989.
#Sta/Elev= 30
  -869.8  997.71  -366.1  940.26   209.7  935.28   367.9  907.96  1183.5  874.29
  1717.3  852.59  1938.2  851.05  2388.9  859.35  2892.2  872.67  3112.6  870.69
  3486.7  865.63  4212.6  847.58  4462.3   837.1    4572     819  4778.1  745.21
  4837.6  742.75  4853.7  737.98    4947  705.58    5073  706.83 5172.73  739.05
  5515.6  838.24  5873.5   846.3  6400.4  858.39  6620.5     864  7168.7  877.96
  7849.1  895.29  8385.3  908.95  8534.5  933.18  8634.9  956.93  9193.7  960.98
#Mann= 19 ,-1 , 0
  -869.8     .16       0   209.7     .05       0  1183.5      .1       0
  1717.3     .05       0  1938.2      .1       0  2388.9     .05       0
  2892.2     .16       0  3112.6     .05       0  3486.7      .1       0
  4212.6     .05       0  4462.3     .16       0  4837.6    .033       0
 5172.73     .16       0  5873.5     .16       0  6400.4     .05       0
  6620.5     .16       0  7168.7      .1       0  7849.1      .1       0
  8534.5     .16       0
Bank Sta=4853.7,5172.73
XS Rating Curve= 0 ,0
Exp/Cntr=0.3,0.1

Type RM Length L Ch R = 1 ,95455   ,2491,2491,2491
BEGIN DESCRIPTION:
PEDERNALES RIVER 297.0
END DESCRIPTION:
XS GIS Cut Line= 3
       2979593.3     10095277.54      2977765.04     10090437.22
      2979397.27     10086551.07
#Sta/Elev= 30
  -896.6  997.42  -865.9  995.48  -234.7  964.58     513     918   735.9  902.86
  1901.6  856.32  2372.1  842.49  2639.6  841.85  3063.1  846.31  3474.2  850.64
  3848.9  854.59  4461.7  845.53  4557.7  838.28  4581.4   809.3  4610.6  819.87
  4811.5  742.06  4816.9  740.88  4975.5  701.44  5182.1  738.66  5412.2  810.11
  5459.7  858.45  5724.4  880.47  6054.9  952.96  6257.7  959.62  6733.1  964.55
  6991.1  959.09  7339.9  917.05  7702.9  959.85  8268.8  983.06  8492.5  984.56
#Mann= 19 ,-1 , 0
  -896.6     .16       0  -865.9      .1       0  -234.7     .16       0
     513      .1       0   735.9     .05       0  1901.6     .05       0
  2372.1     .16       0  2639.6     .05       0  3063.1      .1       0
  3474.2      .1       0  3848.9      .1       0  4461.7      .1       0
  4811.5    .035       0  5182.1     .16       0  6257.7      .1       0
  6733.1     .16       0  6991.1     .16       0  7702.9      .1       0
  8268.8      .1       0
Bank Sta=4816.9,5182.1
XS Rating Curve= 0 ,0
Exp/Cntr=0.3,0.1

Type RM Length L Ch R = 1 ,92964   ,1831,1831,1831
BEGIN DESCRIPTION:
PEDERNALES RIVER 298.0
END DESCRIPTION:
XS GIS Cut Line= 3
      2979808.14     10095453.83      2979738.51     10092306.24
      2981802.31     10086862.91
#Sta/Elev= 30
   265.2 1000.22     650  978.98  1575.6  947.36  2077.2  904.52  2420.9  879.03
  2906.3   864.7  3143.9  862.52  3429.3  860.28  3661.5  854.91  3954.3  848.14
  4512.1  837.11  4603.3  826.81  4646.1  795.94  4827.9  740.57  4865.7     716
  5035.7  698.89  5191.5  740.52  5212.9   752.4  5346.1  781.33  5425.9  826.25
  5632.9  837.73  6465.6   852.7  6779.6  863.92  7159.4  935.48  7517.6   935.5
  7855.9  905.59  8319.4  928.91  8764.6  990.54  9220.5 1045.56    9235 1048.43
#Mann= 19 ,-1 , 0
   265.2     .16       0     650     .16       0  2077.2     .16       0
  2420.9     .05       0  2906.3      .1       0  3143.9     .05       0
  3429.3     .16       0  3661.5     .05       0  3954.3      .1       0
  4512.1     .16       0  4827.9    .035       0  5212.9     .16       0
  5632.9      .1       0  6465.6     .05       0  6779.6     .16       0
  7855.9     .16       0  8319.4      .1       0  8764.6      .1       0
  9220.5      .1       0
Bank Sta=4827.9,5191.5
XS Rating Curve= 0 ,0
Exp/Cntr=0.3,0.1

Type RM Length L Ch R = 1 ,91133   ,1601,1601,1601
BEGIN DESCRIPTION:
PEDERNALES RIVER 299.0
END DESCRIPTION:
XS GIS Cut Line= 3
      2979956.55     10095737.77      2981713.59     10092287.23
      2983577.82     10087188.69
#Sta/Elev= 30
   290.9 1006.08   637.2  981.92  1021.1  979.74  1356.9  966.97  1441.3  964.25
  1519.5  961.83  1991.1  942.83  2221.8  933.86  2399.6  926.27  2468.4  906.61
  2705.6  891.69  2745.3  890.25  2853.3  886.33  2942.8  883.08  4562.7  828.07
  4869.5  733.34  4954.7  700.51  5096.2  699.18  5157.5  727.74  5355.3  799.27
  5369.9   791.7  5380.5  810.75  5416.3  798.61  5441.5  817.23  6608.7  848.87
  6667.5  848.94  7310.4  854.33  7452.4  877.54  8620.4  907.66  9591.7 1003.94
#Mann= 17 ,-1 , 0
   290.9     .16       0  1021.1      .1       0  1356.9     .16       0
  1441.3      .1       0  1519.5     .16       0  1991.1      .1       0
  2221.8      .1       0  2468.4     .05       0  2705.6      .1       0
  2745.3     .05       0  2853.3      .1       0  2942.8     .16       0
  4562.7     .05       0  4869.5    .035       0  5157.5     .16       0
  6608.7      .1       0  6667.5     .16       0
Bank Sta=4869.5,5157.5
XS Rating Curve= 0 ,0
Exp/Cntr=0.3,0.1

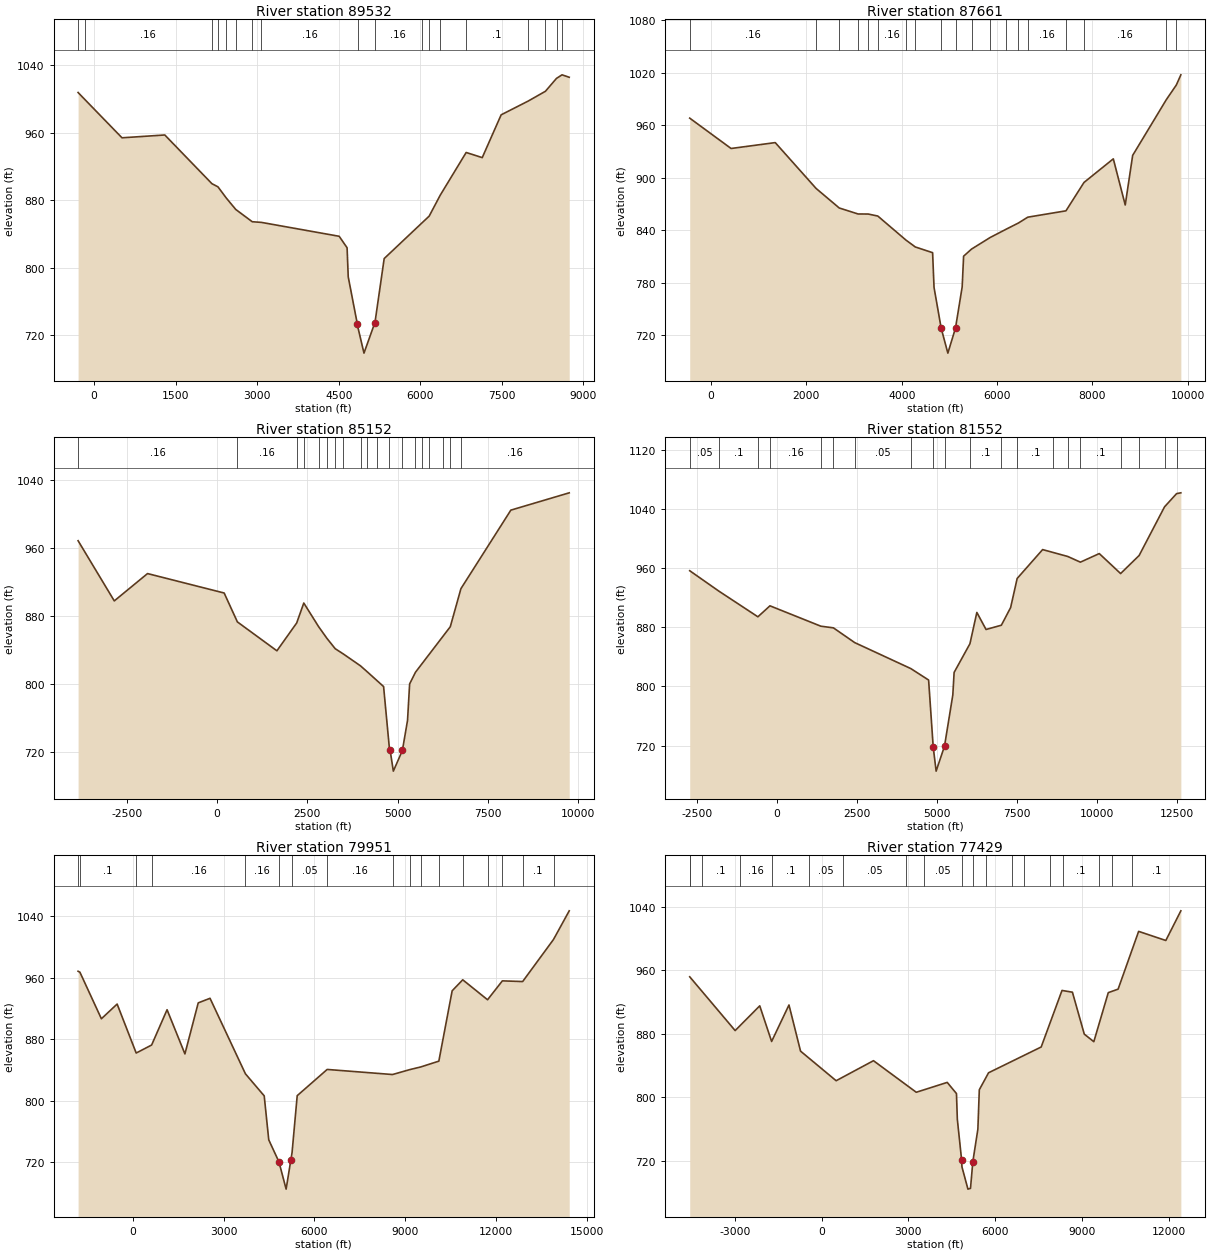
Type RM Length L Ch R = 1 ,89532   ,1871,1871,1871
BEGIN DESCRIPTION:
PEDERNALES RIVER 300.0
END DESCRIPTION:
XS GIS Cut Line= 3
      2980085.16     10095869.54      2983134.42     10093216.25
       2984647.2     10088460.59
#Sta/Elev= 30
  -292.9  1007.9  -171.7  999.78   514.6  954.15  1301.7   957.5  2168.5   899.7
  2279.5  895.97  2435.8   882.4  2608.1  869.04  2910.2  854.54  3076.1   853.8
  4508.6  837.29  4654.2  823.65  4675.2  789.13  4843.1  733.01  4853.6  729.12
  4964.9  698.64  5163.8   734.6  5166.1  734.57  5336.3  810.85  6024.6  852.76
  6163.7  861.21  6367.4  886.07  6844.2  936.74  7139.9  930.64  7487.5  981.41
  7985.3  997.76    8302 1009.36  8505.7 1024.69  8607.5 1028.88  8739.6 1025.98
#Mann= 18 ,-1 , 0
  -292.9      .1       0  -171.7     .16       0  2168.5      .1       0
  2279.5      .1       0  2435.8     .16       0  2608.1     .05       0
  2910.2     .16       0  3076.1     .16       0  4853.6    .035       0
  5166.1     .16       0  6024.6     .16       0  6163.7      .1       0
  6367.4     .16       0  6844.2      .1       0  7985.3     .16       0
    8302      .1       0  8505.7     .16       0  8607.5      .1       0
Bank Sta=4843.1,5163.8
XS Rating Curve= 0 ,0
Exp/Cntr=0.3,0.1

Type RM Length L Ch R = 1 ,87661   ,2509,2509,2509
BEGIN DESCRIPTION:
PEDERNALES RIVER 320.0
END DESCRIPTION:
XS GIS Cut Line= 4
      2981795.05      10095316.6      2985357.45     10093641.85
      2985422.46     10088382.18       2984808.8     10087463.12
#Sta/Elev= 30
  -446.8  967.96   421.1   933.3  1347.1  940.02  2203.7   887.7  2689.2  865.38
  3084.1  858.53  3296.2  858.46  3498.3  856.17    4088  828.75  4284.6  820.87
  4647.8  814.34  4677.8  774.62  4827.8  728.09  4967.6  699.65  5127.9   728.3
  5267.9  775.26  5297.9  810.33  5464.1  818.44  5856.3  831.71  6193.1  841.21
    6447   848.2  6643.6  854.87    7445  862.13  7823.1  894.52  8438.1  921.48
  8688.1  868.81    8844  925.44  9549.4  989.02    9761 1005.88  9854.8 1017.41
#Mann= 19 ,-1 , 0
  -446.8     .16       0  2203.7     .05       0  2689.2     .16       0
  3084.1     .05       0  3296.2     .16       0  3498.3     .16       0
    4088     .05       0  4284.6     .16       0  4827.8    .033       0
  5127.9     .16       0  5464.1      .1       0  5856.3     .05       0
  6193.1      .1       0    6447     .05       0  6643.6     .16       0
    7445      .1       0  7823.1     .16       0  9549.4      .1       0
    9761     .16       0
Bank Sta=4827.8,5127.9
XS Rating Curve= 0 ,0
Exp/Cntr=0.3,0.1

Type RM Length L Ch R = 1 ,85152   ,3600,3600,3600
BEGIN DESCRIPTION:
PEDERNALES RIVER 301.0
END DESCRIPTION:
XS GIS Cut Line= 3
      2980915.77     10096577.44      2987819.33     10092864.99
      2988107.51     10087108.96
#Sta/Elev= 30
   -3847   968.9 -2844.8  898.07 -1923.9  930.25   198.2  907.36   564.3  873.34
  1659.1  839.32    2207  872.11  2403.5  895.58  2814.5  867.72  3043.8  854.01
  3273.1  841.81  3502.4   835.5  3974.1   821.6  4161.7  814.56  4431.6   804.2
  4613.5  797.21  4773.7  724.77  4793.7  722.46  4883.6  697.66  5134.1  721.96
  5276.7  757.44  5334.4  800.29  5496.8   814.1  5667.4  823.58  5871.1   834.9
  6264.1  856.74  6460.6  867.65  6755.4  912.49  8137.9 1004.93  9754.7 1025.31
#Mann= 19 ,-1 , 0
   -3847     .16       0   564.3     .16       0    2207      .1       0
  2403.5     .16       0  2814.5     .16       0  3043.8     .05       0
  3273.1     .05       0  3502.4     .16       0  3974.1     .05       0
  4161.7     .05       0  4431.6     .16       0  4773.7    .033       0
  5134.1     .16       0  5496.8      .1       0  5667.4     .05       0
  5871.1     .16       0  6264.1     .05       0  6460.6      .1       0
  6755.4     .16       0
Bank Sta=4793.7,5134.1
XS Rating Curve= 0 ,0
Exp/Cntr=0.3,0.1

Type RM Length L Ch R = 1 ,81552   ,1601,1601,1601
BEGIN DESCRIPTION:
PEDERNALES RIVER 302.0
END DESCRIPTION:
XS GIS Cut Line= 4
      2982870.73     10099240.47      2987246.08     10094997.67
      2990718.78     10094259.36        2990581.     10088554.41
#Sta/Elev= 30
 -2730.4  956.69 -1816.2  928.95  -599.4  894.28  -222.3  909.15  1367.3  881.57
  1761.7   879.3  2425.6  859.36  4179.3  824.19  4736.7  808.65  4879.8  718.32
  4971.6   685.3  5233.5  719.12  5493.2  788.42  5534.1  818.96  6028.6  857.83
  6244.5  900.19  6531.9   877.1  7010.8  882.89  7300.3  906.76  7504.5  946.18
  8300.6   985.3  8636.7   981.3  9087.4  975.95  9481.3  968.28 10071.1   979.9
   10738  952.85 11316.9  977.29 12111.3 1043.19 12488.1  1061.1 12621.2 1062.16
#Mann= 20 ,-1 , 0
 -2730.4     .05       0 -1816.2      .1       0  -599.4      .1       0
  -222.3     .16       0  1367.3     .16       0  1761.7     .16       0
  2425.6     .05       0  4179.3     .16       0  4879.8    .035       0
  5233.5      .1       0  6028.6      .1       0  7010.8     .16       0
  7504.5      .1       0  8636.7     .05       0  9087.4     .16       0
  9481.3      .1       0   10738     .16       0 11316.9     .16       0
 12111.3     .16       0 12488.1      .1       0
Bank Sta=4879.8,5233.5
XS Rating Curve= 0 ,0
Exp/Cntr=0.3,0.1

Type RM Length L Ch R = 1 ,79951   ,2522,2522,2522
BEGIN DESCRIPTION:
PEDERNALES RIVER 303.0
END DESCRIPTION:
XS GIS Cut Line= 4
      2983075.13     10099555.52      2987168.58     10097054.02
      2991987.23     10094874.01      2990994.39     10088819.99
#Sta/Elev= 30
   -1804   968.2-1744.03  966.97-1034.44  906.46 -514.74   925.6   114.9  861.95
624.6101  872.37 1134.32  918.21 1723.99  860.82 2163.74  927.12 2553.51  933.06
 3723.09  834.93 4342.94   806.3 4492.91  749.17  4830.2  720.49  5066.5  685.14
  5222.8  723.14 5262.73   732.6 5432.69  806.57 6422.46  840.63 8581.84  834.03
 9161.34  840.52 9511.04  843.8510110.52  851.4110550.15   942.810899.84  957.11
11719.14  931.1712208.72  955.7212878.14  954.8213897.27 1009.4914416.82 1046.71
#Mann= 17 ,-1 , 0
   -1804      .1       0-1744.03      .1       0   114.9      .1       0
624.6101     .16       0 3723.09     .16       0  4830.2    .035       0
 5262.73     .05       0 6422.46     .16       0 8581.84      .1       0
 9161.34      .1       0 9511.04     .05       010110.52     .16       0
10899.84      .1       011719.14      .1       012208.72     .05       0
12878.14      .1       013897.27     .16       0
Bank Sta=4830.2,5222.8
XS Rating Curve= 0 ,0
Exp/Cntr=0.3,0.1

Type RM Length L Ch R = 1 ,77429   ,2072,2072,2072
BEGIN DESCRIPTION:
PEDERNALES RIVER 304.0
END DESCRIPTION:
XS GIS Cut Line= 3
      2986449.34     10106784.64      2987027.73     10100021.03
      2995942.75     10095105.22
#Sta/Elev= 30
   -4554  951.61-2984.39  883.87 -2134.6  915.04 -1724.7  870.16-1124.85  916.12
 -724.95  857.99504.7402  820.71 1794.41  845.93 3273.33  806.17 4342.32   818.6
 4662.02  804.54 4691.99  772.15  4838.7  721.25  4852.1   712.1  5058.2  684.18
    5147   685.2  5226.9  718.56 5401.32  759.68 5451.27  809.32 5770.97  830.73
 7589.24  863.21 8308.56  934.41 8668.22   932.2 9077.83   879.4 9407.52  869.88
 9907.04  931.6410246.72  936.0510956.05 1008.8111895.15  997.3312414.65 1034.69
#Mann= 19 ,-1 , 0
 -4554.1      .1       0 -4533.8     .16       0 -4133.3      .1       0
 -2805.4     .16       0 -1706.7      .1       0  -423.2     .05       0
   749.8     .05       0  2918.8     .05       0  3529.6     .05       0
  4852.1    .035       0  5226.9     .16       0  5685.6     .16       0
  6582.6     .05       0  6984.3     .05       0  7902.2      .1       0
  8349.6      .1       0  9582.6     .16       0 10036.7      .1       0
 10736.5      .1       0
Bank Sta=4838.7,5226.9
XS Rating Curve= 0 ,0
Exp/Cntr=0.3,0.1