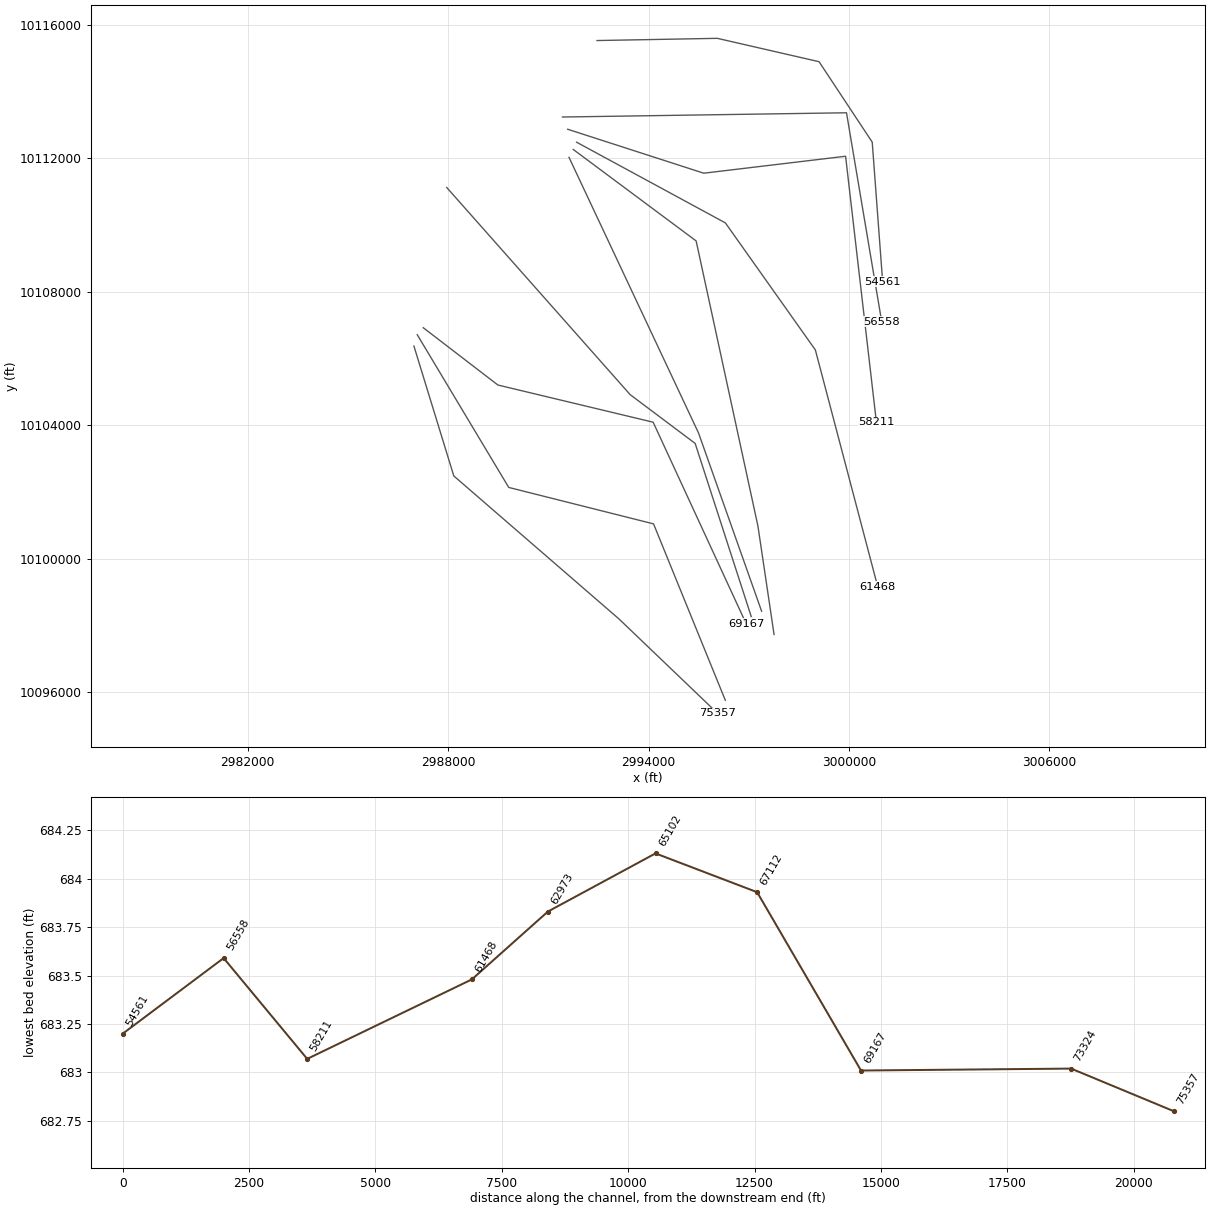
HEC-RAS study PEDERNALES RIVER.prj: PEDERNALES RIVER Base Level Engineering

--- PEDERNALES RIVER.g01 (geometry) --- (continued)

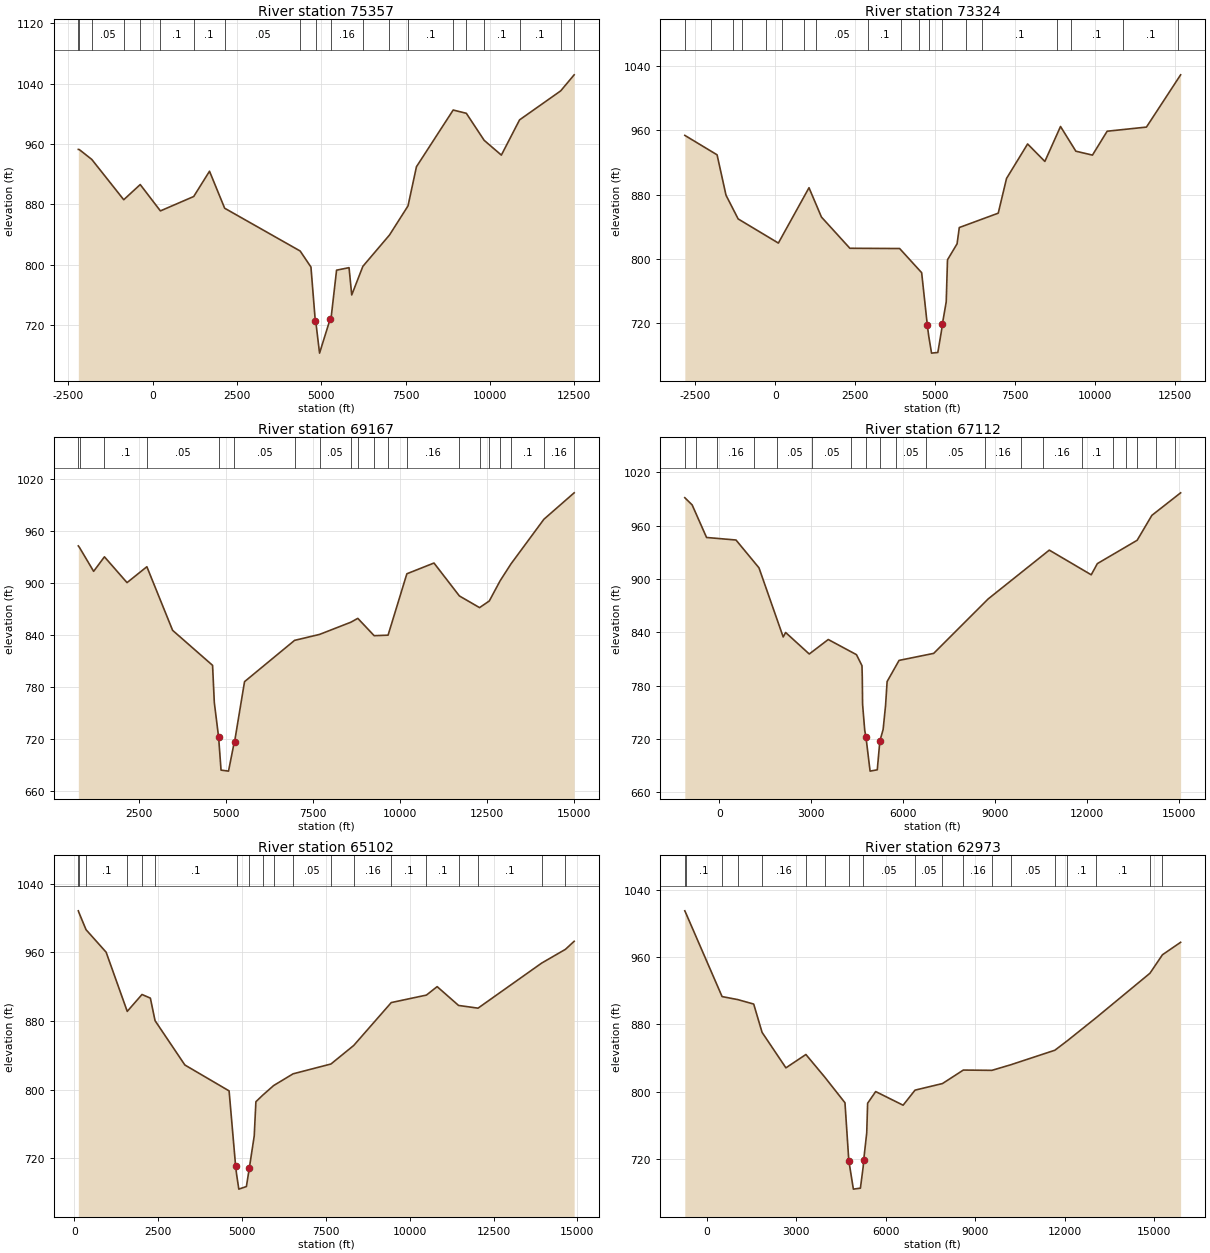
Type RM Length L Ch R = 1 ,75357   ,2033,2033,2033
BEGIN DESCRIPTION:
PEDERNALES RIVER 305.0
END DESCRIPTION:
XS GIS Cut Line= 4
      2986975.23     10106374.53      2988169.17     10102483.05
      2993118.02      10098195.3      2996068.88       10095368.
#Sta/Elev= 30
   -2206  952.69-2176.07  952.42-1806.93  939.43 -859.14  886.03 -370.29  906.14
228.3201  871.23 1216.01  890.29 1684.92  923.79 2134.41  874.77 4373.74  818.09
 4693.65  796.85    4822  725.72  4850.5  719.49    4949   682.8  5261.8  727.74
 5293.47  730.35 5453.42   792.7 5823.31  796.04 5903.28  759.89 6233.19  797.76
 7022.95  839.27 7572.79  877.87 7822.72  929.73 8912.29 1004.87 9302.08 1000.55
  9831.8  964.7110341.54  945.1610881.26  991.8412100.62 1030.2312500.41 1051.51
#Mann= 20 ,-1 , 0
   -2206     .16       0-2176.07     .16       0-1806.93     .05       0
 -859.14      .1       0 -370.29      .1       0228.3201      .1       0
 1216.01      .1       0 2134.41     .05       0 4373.74     .05       0
  4850.5    .033       0 5293.47     .16       0 6233.19      .1       0
 7022.95     .05       0 7572.79      .1       0 8912.29     .05       0
 9302.08      .1       0  9831.8      .1       010881.26      .1       0
12100.62      .1       012500.41      .1       0
Bank Sta=4822,5261.8
XS Rating Curve= 0 ,0
Exp/Cntr=0.3,0.1

Type RM Length L Ch R = 1 ,73324   ,4157,4157,4157
BEGIN DESCRIPTION:
PEDERNALES RIVER 306.0
END DESCRIPTION:
XS GIS Cut Line= 4
      2987075.22     10106714.25      2989814.04     10102138.81
      2994150.46     10101046.62      2996299.19     10095760.73
#Sta/Elev= 30
   -2830  953.53 -1821.4  929.39-1541.79  879.22-1162.32  849.7695.92993  819.75
  1054.6  888.49 1444.05  852.06 2332.81  813.28 3890.05  812.97 4578.79  782.95
  4756.3   717.7  4797.4  704.95  4887.8  683.02  5085.1  683.83  5203.2  711.79
  5228.3  719.38  5347.4  746.76 5387.33  798.96 5686.77   818.8 5756.65  839.05
  6974.4  856.89 7234.22  900.04 7893.77  942.87  8433.4  921.17 8923.07  964.59
 9402.74  933.89 9922.38  929.0310382.07   958.711611.23  963.83 12680.5 1028.76
#Mann= 19 ,-1 , 0
 -2831.2     .16       0 -2015.9     .05       0 -1323.5      .1       0
 -1044.3      .1       0  -291.8     .05       0     195     .05       0
   890.4      .1       0  1280.6     .05       0  2907.7      .1       0
  3924.6     .05       0  4507.4     .05       0  4797.4    .033       0
  5203.2     .16       0  5951.7     .05       0    6452      .1       0
    8812     .05       0    9250      .1       0 10889.7      .1       0
 12592.9     .16       0
Bank Sta=4756.3,5228.3
XS Rating Curve= 0 ,0
Exp/Cntr=0.3,0.1

Type RM Length L Ch R = 1 ,69167   ,2055,2055,2055
BEGIN DESCRIPTION:
PEDERNALES RIVER 307.0
END DESCRIPTION:
XS GIS Cut Line= 4
      2987254.86     10106924.86      2989489.64      10105207.7
       2994138.8     10104093.33      2996921.81     10098060.04
#Sta/Elev= 30
     770  942.62  809.98  940.35 1209.73   913.3 1519.54  930.06 2169.15  900.31
  2738.8  918.62 3478.36  845.31 4626.31  804.95 4676.21  762.14  4800.6  721.86
  4869.3  684.19  5084.2  683.01  5252.6  717.14  5257.7  716.63 5544.55  786.15
  6981.8  833.74 7700.43  840.61 8598.95  854.67 8798.77   859.1 9268.36  839.13
 9668.01  839.7510207.54   910.510986.85   922.911716.21  884.96 12295.7  871.49
12575.45  879.1512885.18  902.3313194.91  921.6814144.07  973.3415013.31 1003.82
#Mann= 20 ,-1 , 0
     770      .1       0  809.98      .1       0 1519.54      .1       0
  2738.8     .05       0  4800.6    .033       0  5252.6     .05       0
  6981.8     .05       0 7700.43     .05       0 8598.95      .1       0
 8798.77     .05       0 9268.36     .05       0 9668.01     .16       0
10207.54     .16       011716.21      .1       0 12295.7     .16       0
12575.45      .1       012885.18     .16       013194.91      .1       0
14144.07     .16       015013.31      .1       0
Bank Sta=4800.6,5257.7
XS Rating Curve= 0 ,0
Exp/Cntr=0.3,0.1

Type RM Length L Ch R = 1 ,67112   ,2010,2010,2010
BEGIN DESCRIPTION:
PEDERNALES RIVER 308.0
END DESCRIPTION:
XS GIS Cut Line= 4
      2987958.15     10111126.17      2993451.52     10104918.16
      2995396.66     10103457.86      2997075.45     10098270.27
#Sta/Elev= 30
   -1130  991.45 -890.01  983.34 -420.04  946.72  539.91  943.87 1289.87   912.6
 2079.83  834.81 2159.83  839.84 2929.79  815.67 3549.76  831.96 4469.71  814.93
 4649.71  802.48  4659.7  789.75  4669.7  759.06  4739.7  729.75    4780  722.18
  4914.4  683.93  5148.9  685.42  5233.3  717.86 5339.67  730.71 5419.67   757.9
 5469.67  784.65 5859.65  808.46 6989.59  816.37 8764.53  877.5510760.32   932.5
12128.45  904.7512328.18  917.33 13626.4  943.5814105.74  971.5715044.46  996.94
#Mann= 20 ,-1 , 0
 -1130.1     .16       0  -759.3      .1       0   -95.3     .16       0
  1136.7      .1       0  1880.7     .05       0    3018     .05       0
  4285.5     .16       0  4765.8    .033       0  5233.3     .05       0
    5767     .05       0  6728.4     .05       0  8667.8     .16       0
  9843.6      .1       0 10540.9     .16       0 11813.9      .1       0
 12832.8      .1       0 13258.7     .16       0 13618.5      .1       0
 14232.9     .16       0 14874.2      .1       0
Bank Sta=4780,5233.3
XS Rating Curve= 0 ,0
Exp/Cntr=0.3,0.1

Type RM Length L Ch R = 1 ,65102   ,2129,2129,2129
BEGIN DESCRIPTION:
PEDERNALES RIVER 309.0
END DESCRIPTION:
XS GIS Cut Line= 3
      2991618.75     10112030.85      2995496.94      10103771.6
      2997385.97     10098430.36
#Sta/Elev= 30
     116 1008.23  125.99 1006.98  345.86  986.27  945.49  960.03 1575.11  891.13
 2014.84   910.8 2264.69  906.56  2404.6  880.32 3294.06   828.7 4613.25  798.52
  4806.5  711.51  4834.8  701.88    4903  684.13  5129.1  687.14  5217.5  708.94
 5362.77  745.99 5412.74  785.94 5622.61  793.76 5942.41  804.76 6522.04  818.41
 7651.33  829.85 8330.91  851.44 9450.21  901.3810499.37  910.1110819.12  919.94
11458.61  898.0312038.15  894.8813936.64  947.3714646.07  963.3914905.86  972.76
#Mann= 19 ,-1 , 0
     116     .05       0  125.99     .05       0  345.86      .1       0
 1575.11     .16       0 2014.84      .1       0  2404.6      .1       0
  4834.8    .033       0  5217.5     .16       0 5622.61     .05       0
 5942.41     .16       0 6522.04     .05       0 7651.33     .05       0
 8330.91     .16       0 9450.21      .1       010499.37      .1       0
11458.61     .16       012038.15      .1       013936.64      .1       0
14646.07     .16       0
Bank Sta=4806.5,5217.5
XS Rating Curve= 0 ,0
Exp/Cntr=0.3,0.1

Type RM Length L Ch R = 1 ,62973   ,1505,1505,1505
BEGIN DESCRIPTION:
PEDERNALES RIVER 310.0
END DESCRIPTION:
XS GIS Cut Line= 4
      2991746.05     10112266.76      2995425.74     10109525.87
      2997276.26     10100981.13      2997759.19     10097731.86
#Sta/Elev= 30
    -738 1015.16 -708.01 1012.87  511.54  913.08 1041.35  909.44 1571.15  904.16
 1851.05  870.52 2650.76  828.22 3320.52  844.12 3950.23   817.3 4629.67  786.67
  4758.2  717.83  4911.4  683.83    5147  684.98  5239.1  710.08  5258.3  718.76
 5359.06  750.86 5389.04  786.07 5658.81  799.98 6578.05  783.75 6977.72  801.68
 7896.98  809.52 8596.44  825.58 9555.69  825.2510185.19  831.8811664.04   849.2
12083.71  860.5313052.59  888.0714849.78  940.8315269.12  962.8615878.17  977.68
#Mann= 19 ,-1 , 0
    -738      .1       0 -708.01      .1       0  511.54      .1       0
 1041.35      .1       0 1851.05     .16       0 3320.52     .05       0
 3950.23      .1       0  4758.2    .033       0  5239.1     .05       0
 6977.72     .05       0 7896.98      .1       0 8596.44     .16       0
 9555.69     .05       010185.19     .05       011664.04      .1       0
12083.71      .1       013052.59      .1       014849.78      .1       0
15269.12      .1       0
Bank Sta=4758.2,5258.3
XS Rating Curve= 0 ,0
Exp/Cntr=0.3,0.1

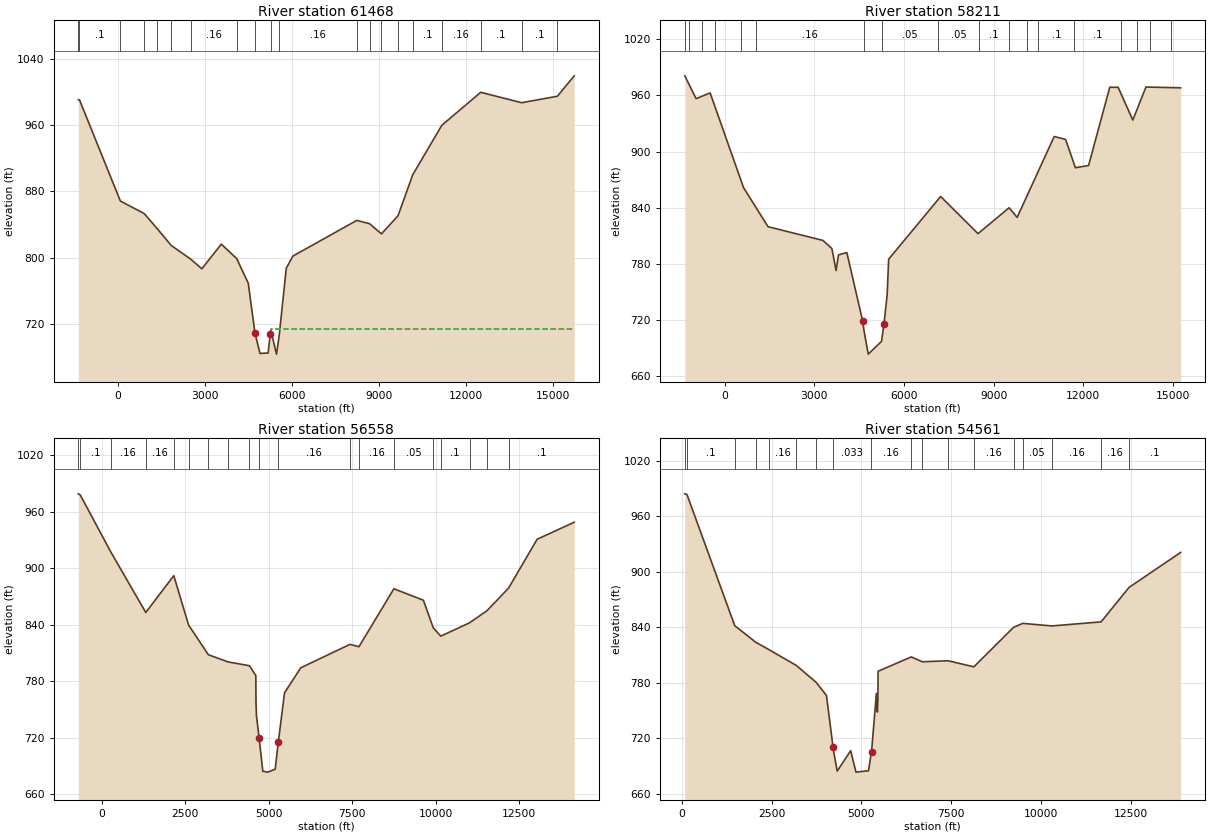
Type RM Length L Ch R = 1 ,61468   ,3257,3257,3257
BEGIN DESCRIPTION:
PEDERNALES RIVER 311.0
END DESCRIPTION:
XS GIS Cut Line= 4
      2991844.61       10112485.      2996301.56     10110066.22
      2998996.23     10106258.47      3000863.52     10099163.76
#Sta/Elev= 30
   -1354  990.36-1314.07  990.1793.42004  868.08  911.97  853.07  1341.2  835.65
  1850.3  814.34 2509.13  798.22 2898.44  786.39 3567.25  816.13 4096.56   798.8
 4496.11  769.05  4729.1  708.45  4901.4  684.33  5180.8  684.84    5253  707.91
  5275.6  711.68  5468.6  683.48  5561.1  705.82 5804.65  787.12  6034.4  801.75
 8231.96  844.75 8671.65   840.8 9081.45  828.52 9651.17  850.2810160.92  899.93
11160.43  959.4712499.78  999.2613909.09  986.69 15138.5   994.515718.27 1019.12
#Mann= 20 ,-1 , 0
   -1354      .1       0-1314.07      .1       093.42004     .16       0
  911.97      .1       0  1341.2     .05       0  1850.3     .16       0
 2509.13     .16       0 4096.56     .16       0  4729.1    .033       0
  5275.6     .07       0  5561.1     .16       0 8231.96      .1       0
 8671.65     .05       0 9081.45     .16       0 9651.17      .1       0
10160.92      .1       011160.43     .16       012499.78      .1       0
13909.09      .1       0 15138.5     .16       0
#XS Ineff= 2 , 0
                         5292.05          714.08
Permanent Ineff=
       F       F
Bank Sta=4729.1,5253
XS Rating Curve= 0 ,0
Exp/Cntr=0.3,0.1

Type RM Length L Ch R = 1 ,58211   ,1653,1653,1653
BEGIN DESCRIPTION:
PEDERNALES RIVER 312.0
END DESCRIPTION:
XS GIS Cut Line= 4
      2991579.46     10112872.32       2995653.8     10111555.57
      2999900.91     10112063.86      3000824.29      10104089.3
#Sta/Elev= 30
   -1334  981.05 -954.72   956.6 -485.61  962.75  632.27  861.31 1450.71  819.52
 3287.66  804.83 3587.48  796.13 3727.39  772.52 3807.35  789.25 4087.18  791.84
  4613.3  718.99  4663.7  707.79  4804.4  683.07  5249.2  696.78  5331.6  715.79
 5436.38  746.52 5486.35  784.68 7225.32  851.87 8474.95  812.05 9514.65   839.8
 9784.57  829.44 11024.2  916.0911404.09  912.96   11734  882.6412173.87  885.03
12883.66  968.8313163.58  968.7413653.43  933.69 14093.3  969.0615252.98  968.22
#Mann= 18 ,-1 , 0
   -1335      .1       0 -1198.6     .16       0  -771.1     .16       0
  -324.5      .1       0   556.7     .05       0  1047.1     .16       0
  4663.7    .033       0  5249.2     .05       0  7133.1     .05       0
  8519.1      .1       0  9509.9     .16       0 10100.9     .16       0
 10494.9      .1       0 11692.1      .1       0 13272.5     .16       0
 13780.1     .16       0   14238     .05       0 14944.9     .16       0
Bank Sta=4613.3,5331.6
XS Rating Curve= 0 ,0
Exp/Cntr=0.3,0.1

Type RM Length L Ch R = 1 ,56558   ,1997,1997,1997
BEGIN DESCRIPTION:
PEDERNALES RIVER 313.0
END DESCRIPTION:
XS GIS Cut Line= 3
      2991422.98     10113239.31      2999928.19     10113366.26
      3000982.13     10107108.25
#Sta/Elev= 30
  -701.9  979.02  -643.8  977.79   263.6  917.78  1318.1  853.06  2156.9  892.13
  2600.4  839.76  3192.3  808.24  3783.5  800.59  4423.8  796.53  4614.2  786.07
  4619.4  757.35  4634.2  743.04  4714.2  719.49  4824.2  684.44    4974  683.59
  5194.2  686.67  5289.5   716.1  5474.3  767.75  5959.5  794.33  7433.8  819.22
  7703.2  816.72  8749.2  878.23  9632.2  866.14  9926.9  836.92 10152.5  827.92
 11015.9  842.09 11538.1  854.95 12185.8  879.03 13039.5  930.79 14150.4  948.87
#Mann= 19 ,-1 , 0
  -701.9     .16       0  -643.8      .1       0   263.6     .16       0
  1318.1     .16       0  2156.9     .05       0  2600.4     .05       0
  3192.3     .16       0  3783.5      .1       0  4423.8     .16       0
  4714.2    .033       0  5289.5     .16       0  7433.8      .1       0
  7703.2     .16       0  8749.2     .05       0  9926.9     .05       0
 10152.5      .1       0 11015.9     .16       0 11538.1      .1       0
 12185.8      .1       0
Bank Sta=4714.2,5289.5
XS Rating Curve= 0 ,0
Exp/Cntr=0.3,0.1

Type RM Length L Ch R = 1 ,54561   ,1876,1876,1876
BEGIN DESCRIPTION:
PEDERNALES RIVER 314.0
END DESCRIPTION:
XS GIS Cut Line= 5
      2992458.01     10115530.71      2996059.51     10115596.97
      2999106.31     10114896.85      3000698.62     10112486.06
      3001010.85     10108301.59
#Sta/Elev= 30
    79.2  984.54   140.4   983.9  1472.1  841.79  2052.7  823.96  2421.2  815.92
  3185.8  798.76  3734.5  780.62  4027.3  766.19    4209   710.8  4214.1  708.29
  4326.7  684.32  4700.8   706.4  4849.7   683.2  5198.8  684.67  5278.4  704.93
  5283.5  705.28  5417.2  768.41  5445.1  748.21    5460  760.97  5465.6  792.39
  6389.9  807.97  6696.7  802.69    7414  803.79  8133.1   797.2  9239.9  839.99
  9495.3  844.27 10301.9  841.49 11677.9   845.9 12456.1   883.2 13892.8  921.06
#Mann= 18 ,-1 , 0
    79.2     .16       0   140.4      .1       0  1472.1     .05       0
  2052.7      .1       0  2421.2     .16       0  3185.8     .05       0
  3734.5     .16       0  4214.1    .033       0  5278.4     .16       0
  6389.9     .16       0  6696.7     .05       0    7414     .16       0
  8133.1     .16       0  9239.9      .1       0  9495.3     .05       0
 10301.9     .16       0 11677.9     .16       0 12456.1      .1       0
Bank Sta=4209,5283.5
XS Rating Curve= 0 ,0
Exp/Cntr=0.3,0.1