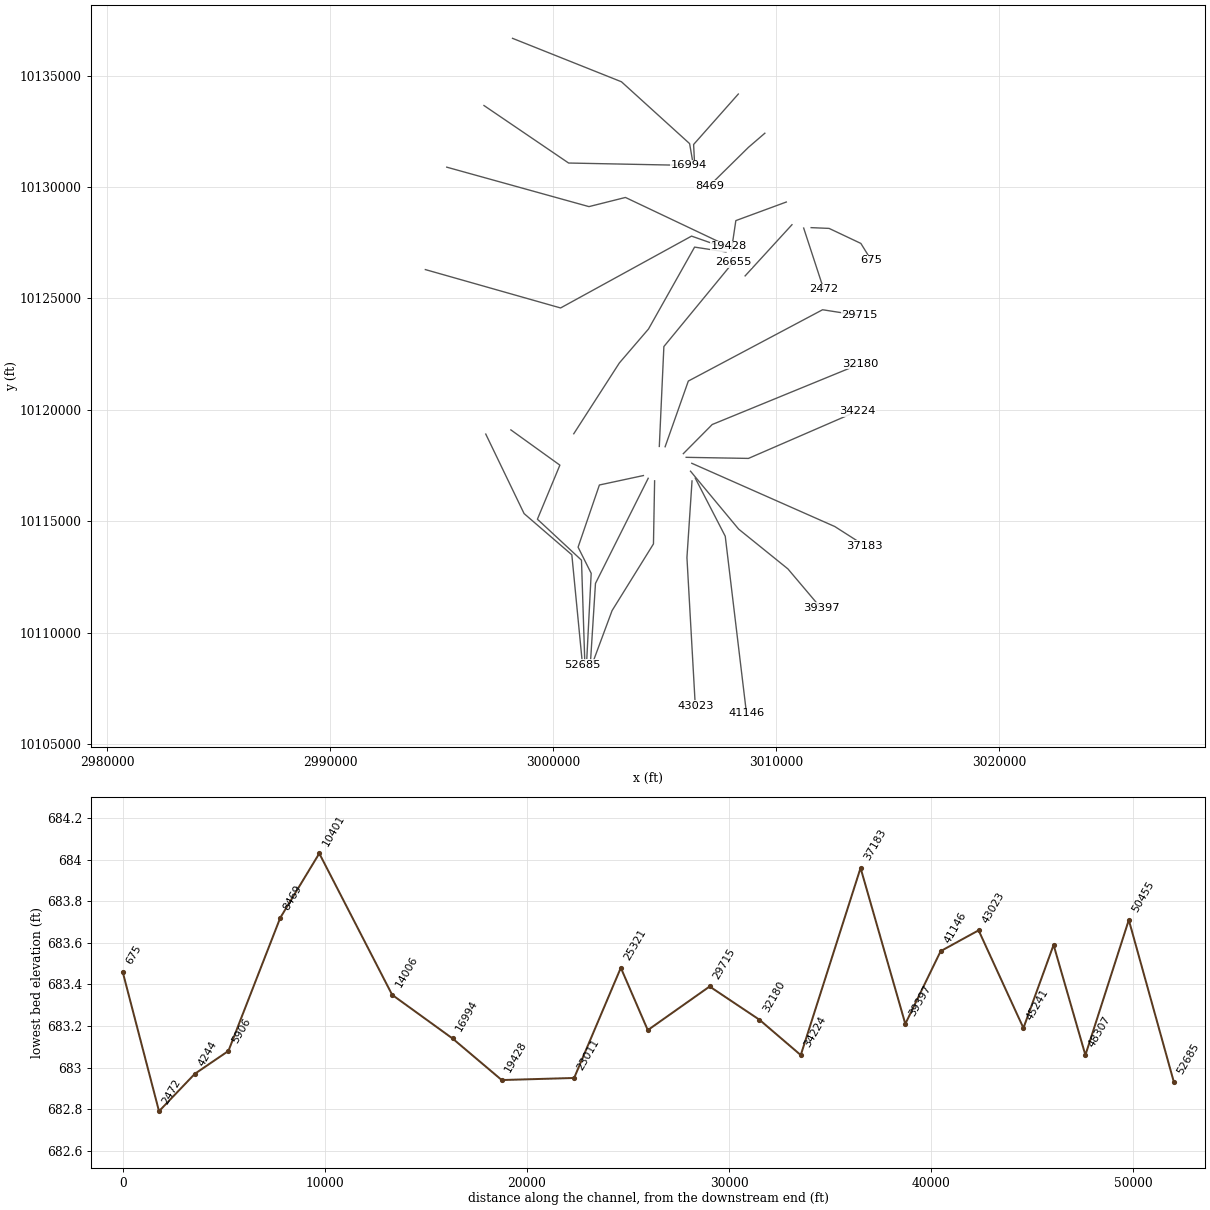
HEC-RAS study PEDERNALES RIVER.prj: PEDERNALES RIVER Base Level Engineering

--- PEDERNALES RIVER.g01 (geometry) --- (continued)

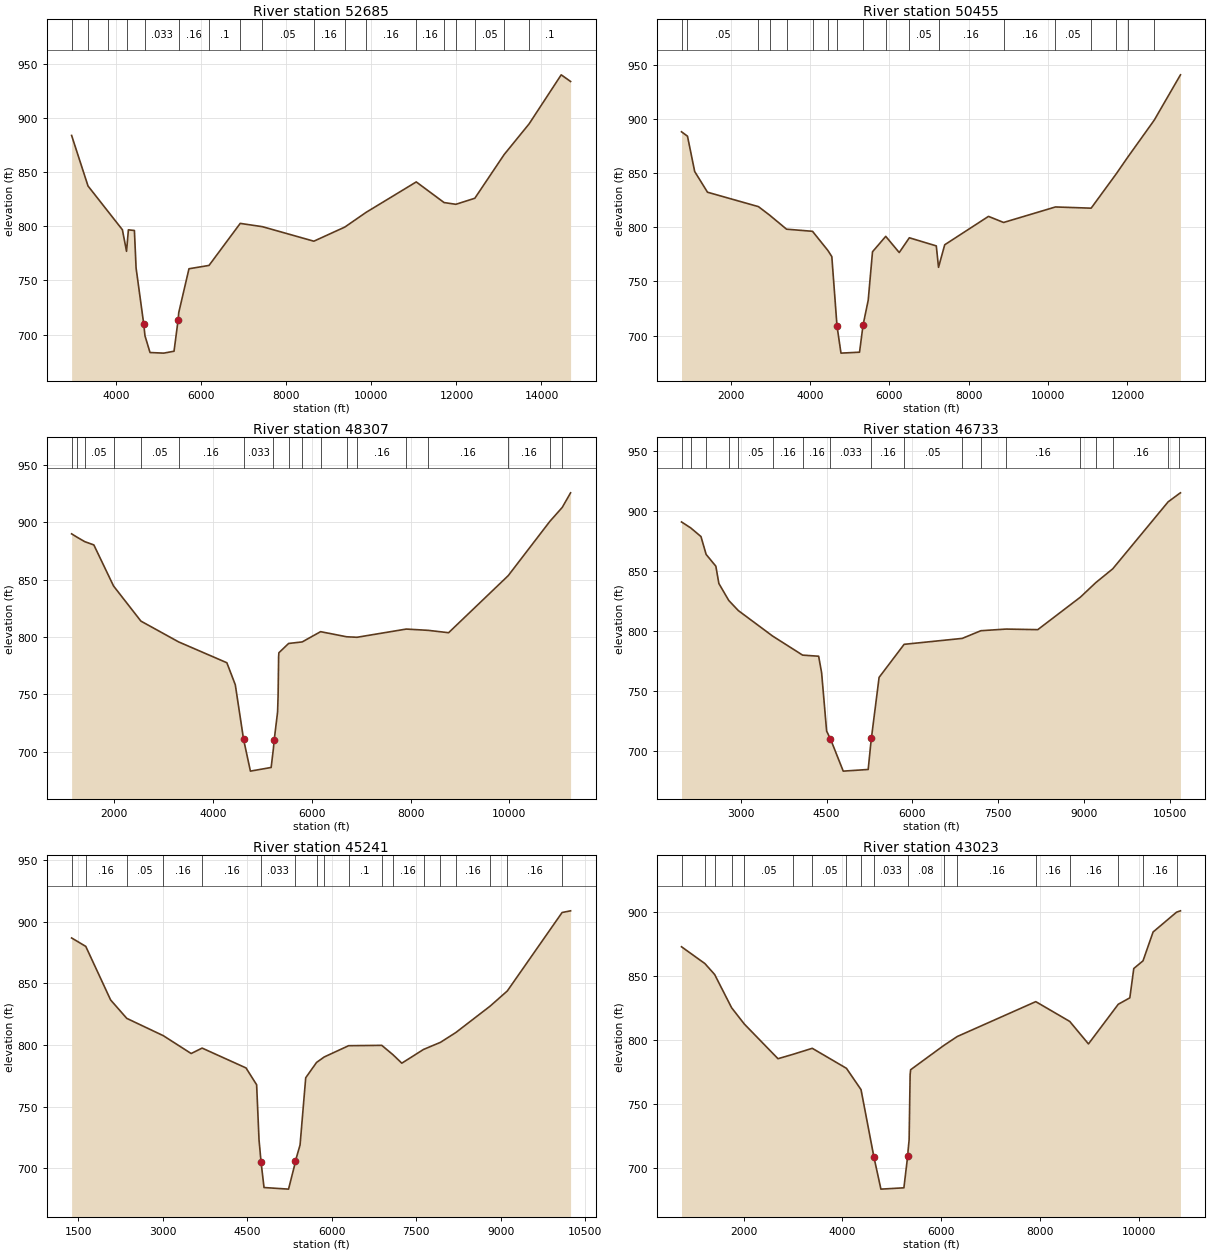
Type RM Length L Ch R = 1 ,52685   ,2230,2230,2230
BEGIN DESCRIPTION:
PEDERNALES RIVER 315.0
END DESCRIPTION:
XS GIS Cut Line= 4
      2996974.94     10118913.86      2998692.75     10115347.45
      3000833.65       10113499.      3001311.29     10108574.43
#Sta/Elev= 30
  2949.3  883.69  3334.8   837.1  3793.8  814.17  4143.4  796.75  4241.1  776.82
  4284.7  796.63    4426  796.02  4465.7  761.41  4646.7  709.39  4674.4  698.95
  4793.5  683.48  5115.5  682.93    5358  684.68  5455.1  713.93    5469  720.28
  5709.4  760.73    6181  763.81  6914.9  802.58  7437.5  799.53  8646.3  786.16
  9375.3   799.2  9874.2  812.73 11054.8  840.82   11709  821.79 11986.2  820.18
 12432.1  825.76 13120.8  866.01 13708.2  894.34 14463.7  939.59   14684  933.47
#Mann= 18 ,-1 , 0
  2949.3      .1       0  3334.8     .05       0  3793.8     .05       0
  4241.1     .16       0  4674.4    .033       0    5469     .16       0
    6181      .1       0  6914.9     .16       0  7437.5     .05       0
  8646.3     .16       0  9375.3     .05       0  9874.2     .16       0
 11054.8     .16       0   11709     .05       0 11986.2     .16       0
 12432.1     .05       0 13120.8     .16       0 13708.2      .1       0
Bank Sta=4646.7,5455.1
XS Rating Curve= 0 ,0
Exp/Cntr=0.3,0.1

Type RM Length L Ch R = 1 ,50455   ,2148,2148,2148
BEGIN DESCRIPTION:
PEDERNALES RIVER 316.0
END DESCRIPTION:
XS GIS Cut Line= 5
      2998101.07     10119101.42      3000297.76     10117520.05
      2999290.49     10115094.44      3001266.33     10113256.96
      3001413.72     10108714.58
#Sta/Elev= 30
   759.6  888.26   910.7  884.19  1092.3  851.51  1415.1  832.41  2699.2  819.09
    2980  811.25  3407.3  798.25  4061.8  796.29  4450.6  778.52  4548.5  772.87
  4678.7  708.86  4779.3  683.71    5247  684.57  5335.5  709.61  5465.5  732.59
  5573.8  777.38  5907.4  791.63  6247.5  776.67    6502  790.31  7181.7   782.8
  7237.7  762.99  7393.7  783.84  8497.4  810.09  8877.7  804.46   10185  818.79
 11084.5  817.67   11714  849.26 12008.7  864.88 12674.2  899.01 13335.7   940.9
#Mann= 18 ,-1 , 0
   759.6      .1       0   910.7     .05       0  2699.2     .16       0
    2980     .05       0  3407.3     .16       0  4061.8     .05       0
  4450.6     .16       0  4678.7    .033       0  5335.5     .16       0
  5907.4     .05       0    6502     .05       0  7237.7     .16       0
  8877.7     .16       0   10185     .05       0 11084.5     .16       0
   11714      .1       0 12008.7     .16       0 12674.2      .1       0
Bank Sta=4678.7,5335.5
XS Rating Curve= 0 ,0
Exp/Cntr=0.3,0.1

Type RM Length L Ch R = 1 ,48307   ,1574,1574,1574
BEGIN DESCRIPTION:
PEDERNALES RIVER 317.0
END DESCRIPTION:
XS GIS Cut Line= 5
      3004042.89     10117053.53      3002069.05     10116629.79
      3001114.03     10113840.24      3001701.47     10112666.98
      3001505.83      10108846.9
#Sta/Elev= 30
  1133.6  890.04  1236.4   887.3  1400.6  883.22  1584.1  880.36    1983  844.54
  2536.8  813.93  3301.2  795.77  4277.5   777.6  4448.3  758.41  4616.4  710.68
  4754.6  683.06  5174.4  686.25  5219.9  702.66    5237  710.47  5304.9   734.7
  5315.1  748.72  5325.6  782.76  5330.9   786.3  5528.1  794.42  5802.8  795.76
  6175.5  804.71  6703.4  800.25  6913.3  799.82  7910.8  806.98    8357  805.85
    8768   803.8  9975.2  853.57   10818   900.9 11068.8  913.08 11238.1  925.82
#Mann= 18 ,-1 , 0
  1133.6     .16       0  1236.4      .1       0  1400.6     .05       0
    1983     .05       0  2536.8     .05       0  3301.2     .16       0
  4616.4    .033       0  5219.9     .16       0  5528.1     .05       0
  5802.8     .05       0  6175.5     .16       0  6703.4     .05       0
  6913.3     .16       0  7910.8     .05       0    8357     .16       0
  9975.2     .16       0   10818     .16       0 11068.8      .1       0
Bank Sta=4616.4,5237
XS Rating Curve= 0 ,0
Exp/Cntr=0.3,0.1

Type RM Length L Ch R = 1 ,46733   ,1492,1492,1492
BEGIN DESCRIPTION:
PEDERNALES RIVER 318.0
END DESCRIPTION:
XS GIS Cut Line= 3
       3004257.1     10116930.28      3001893.71     10112213.64
      3001675.87     10108778.27
#Sta/Elev= 30
  1964.5  891.13  2124.7  886.19  2304.6  878.96  2395.3  864.05  2564.6  854.28
  2617.5  839.86  2790.2  825.75    2957  817.32  3557.9  796.04  4080.4  780.21
  4360.5  779.29 4412.73  765.52  4500.1  716.92  4567.2   710.4  4790.4  683.59
  5226.4  684.97  5271.1   706.2  5282.6   711.1  5416.9  761.66  5854.1  789.19
  6869.9  794.14  7194.8  800.53  7634.9   801.9  8189.5  801.43  8934.3  828.51
  9203.4  840.61  9499.8  852.11 10466.3  907.84 10661.7  914.73 10682.4  915.38
#Mann= 18 ,-1 , 0
  1964.5     .16       0  2124.7     .16       0  2395.3     .05       0
  2790.2      .1       0    2957     .05       0  3557.9     .16       0
  4080.4     .16       0  4567.2    .033       0  5271.1     .16       0
  5854.1     .05       0  6869.9     .05       0  7194.8     .05       0
  7634.9     .16       0  8934.3     .05       0  9203.4     .16       0
  9499.8     .16       0 10466.3      .1       0 10661.7     .05       0
Bank Sta=4567.2,5282.6
XS Rating Curve= 0 ,0
Exp/Cntr=0.3,0.1

Type RM Length L Ch R = 1 ,45241   ,2218,2218,2218
BEGIN DESCRIPTION:
PEDERNALES RIVER 319.0
END DESCRIPTION:
XS GIS Cut Line= 4
      3004544.98     10116816.71      3004493.23     10113986.26
      3002637.96     10110994.58      3001764.34     10108640.01
#Sta/Elev= 30
  1378.4  886.86  1629.9  880.03  2071.5  836.58  2358.5  821.65  3007.3  807.62
  3501.7  793.16  3696.6  797.55  4475.8  781.48  4664.8   767.8  4707.3  723.16
  4743.9  704.89  4795.9  684.48  5231.6  683.19  5347.6  704.11  5353.7  706.02
  5436.1  718.99  5536.6   773.5  5728.7  785.91    5865  790.35  6298.9   799.5
  6887.5  799.78  7089.4  792.06  7243.5  785.32  7629.5  796.48  7929.8  802.22
  8203.4   810.2  8811.7  831.57  9117.8  843.92 10090.2  907.51   10241  908.87
#Mann= 18 ,-1 , 0
  1378.4     .05       0  1629.9     .16       0  2358.5     .05       0
  3007.3     .16       0  3696.6     .16       0  4743.9    .033       0
  5347.6     .16       0  5728.7     .16       0    5865     .05       0
  6298.9      .1       0  6887.5     .05       0  7089.4     .16       0
  7629.5     .16       0  7929.8     .05       0  8203.4     .16       0
  8811.7     .05       0  9117.8     .16       0 10090.2      .1       0
Bank Sta=4743.9,5353.7
XS Rating Curve= 0 ,0
Exp/Cntr=0.3,0.1

Type RM Length L Ch R = 1 ,43023   ,1877,1877,1877
BEGIN DESCRIPTION:
PEDERNALES RIVER 329.0
END DESCRIPTION:
XS GIS Cut Line= 3
      3006222.49     10116811.77      3005994.28      10113371.5
      3006368.23     10106730.35
#Sta/Elev= 30
   742.9  872.89    1216  859.79  1413.6  851.26  1757.3  825.27  2015.9  812.49
  2696.2  785.49  2994.6  788.85  3389.8  793.61  4081.5  777.99  4376.9  761.33
  4639.2  708.41  4779.2  683.66  5244.3  684.68  5320.3  709.22  5330.3  714.21
  5350.3  722.21  5370.4  773.02  5380.4  776.87  6047.1  795.69  6323.6   802.8
  7913.7  830.05  8601.5  814.59    8980  797.04  9583.9  828.02  9817.4     833
  9897.5  855.93 10084.2  861.89 10288.1  884.41 10762.9  899.89 10842.4  900.95
#Mann= 18 ,-1 , 0
   742.9      .1       0    1216     .16       0  1413.6     .05       0
  1757.3     .16       0  2015.9     .05       0  2994.6     .16       0
  3389.8     .05       0  4081.5     .05       0  4376.9      .1       0
  4639.2    .033       0  5330.3     .08       0  6047.1     .16       0
  6323.6     .16       0  7913.7     .16       0  8601.5     .16       0
  9583.9     .05       0 10084.2     .16       0 10762.9      .1       0
Bank Sta=4639.2,5320.3
XS Rating Curve= 0 ,0
Exp/Cntr=0.3,0.1

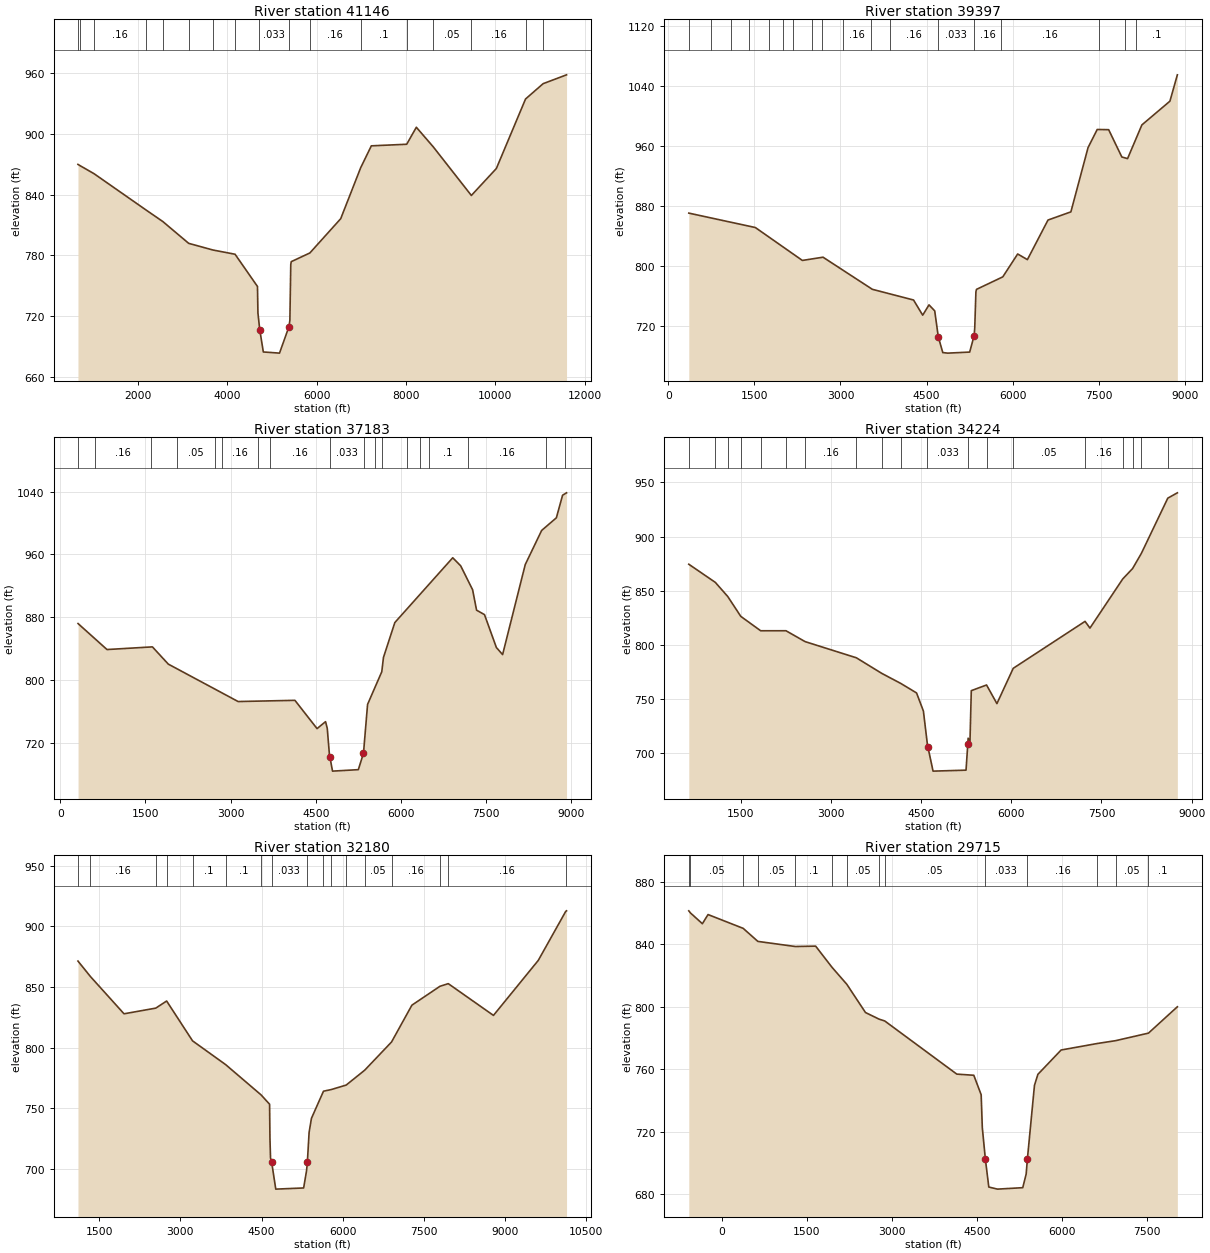
Type RM Length L Ch R = 1 ,41146   ,1749,1749,1749
BEGIN DESCRIPTION:
PEDERNALES RIVER 330.0
END DESCRIPTION:
XS GIS Cut Line= 3
      3006366.74     10116938.56      3007711.54     10114330.26
      3008664.16     10106383.83
#Sta/Elev= 30
   657.2  869.99   702.4  868.79  1018.7  860.76  2176.3   825.1  2556.7  813.54
  3135.7  792.01  3681.5  785.39  4174.2  781.24    4676   749.4  4686.1  723.23
  4716.3  710.98  4726.4  706.82  4806.9  684.71  5169.3  683.56    5381  709.72
  5401.2  716.04  5421.3  771.05  5431.4   773.9  5849.2  782.53  6539.3  816.35
  6986.2  866.68  7224.9  888.32  8016.8  889.89  8232.5  906.67    8608  887.49
  9464.1   839.3   10024  865.95 10677.2  934.59 11071.3  949.74 11595.1  958.47
#Mann= 17 ,-1 , 0
   657.2      .1       0   702.4     .05       0  1018.7     .16       0
  2176.3     .16       0  2556.7      .1       0  3135.7     .16       0
  3681.5     .05       0  4174.2     .16       0  4716.3    .033       0
    5381     .16       0  5849.2     .16       0  6986.2      .1       0
  8016.8      .1       0    8608     .05       0  9464.1     .16       0
 10677.2     .16       0 11071.3     .16       0
Bank Sta=4726.4,5381
XS Rating Curve= 0 ,0
Exp/Cntr=0.3,0.1

Type RM Length L Ch R = 1 ,39397   ,2214,2214,2214
BEGIN DESCRIPTION:
PEDERNALES RIVER 321.0
END DESCRIPTION:
XS GIS Cut Line= 4
      3006154.57     10117248.42      3008311.73     10114650.19
      3010521.31     10112865.11      3012001.36     10111112.63
#Sta/Elev= 30
     358   870.3 1516.96  851.04 2336.23  807.06 2695.91   811.4 3555.15  768.49
  4273.2  754.18 4432.67  733.91  4542.3  747.69 4641.97  739.68  4704.1  705.07
  4782.4  683.97    4867  683.21    5251   684.6  5329.4  706.75 5339.65  717.59
 5359.58  765.03 5369.55   768.4 5828.02  785.12 6087.16   815.7 6256.59  808.14
 6615.42  861.03 7014.35  871.98 7313.54  957.88 7473.11  982.08 7672.57  981.79
 7901.95   945.3 8001.69  943.13 8251.01  988.14  8739.7  1019.9 8869.35  1055.1
#Mann= 18 ,-1 , 0
   357.4      .1       0   736.5     .05       0  1088.8     .16       0
  1414.3     .05       0  1747.4     .16       0  1994.4     .05       0
  2169.1     .16       0  2502.8     .16       0  2683.4      .1       0
  3042.2     .16       0  3530.5      .1       0  3869.5     .16       0
  4704.1    .033       0  5329.4     .16       0    5803     .16       0
  7504.4      .1       0  7952.9     .16       0  8150.1      .1       0
Bank Sta=4704.1,5329.4
XS Rating Curve= 0 ,0
Exp/Cntr=0.3,0.1

Type RM Length L Ch R = 1 ,37183   ,2959,2959,2959
BEGIN DESCRIPTION:
PEDERNALES RIVER 322.0
END DESCRIPTION:
XS GIS Cut Line= 3
      3006212.64      10117603.3       3012622.7     10114766.13
      3013964.35     10113909.28
#Sta/Elev= 30
     312  871.93  821.99  838.82 1621.97  842.22 1901.96  820.25 3131.94  772.59
 4131.92  774.13 4521.91  738.11 4671.91  746.99 4701.91  738.28  4742.6  702.52
    4757  698.52  4794.4  683.96  5249.1  685.83  5339.8  706.77 5411.89  768.98
 5661.89  810.49 5691.88  828.81 5891.88  873.19 6911.85  955.72 7051.85  945.45
 7261.84  914.97 7331.81  888.96 7471.34  883.29 7680.63   841.4 7790.26  832.39
 8188.92  947.02 8477.95  990.51 8737.08  1006.6 8846.72 1035.39 8916.49 1038.43
#Mann= 18 ,-1 , 0
   310.7      .1       0   614.8     .16       0    1604     .05       0
  2050.4     .05       0  2715.8      .1       0    2845     .16       0
    3473     .05       0    3693     .16       0    4757    .033       0
  5347.5     .16       0  5545.9     .08       0  5672.7     .16       0
  6112.6      .1       0  6332.6      .1       0  6487.1      .1       0
  7176.3     .16       0  8561.9     .05       0  8897.4     .16       0
Bank Sta=4742.6,5339.8
XS Rating Curve= 0 ,0
Exp/Cntr=0.3,0.1

Type RM Length L Ch R = 1 ,34224   ,2044,2044,2044
BEGIN DESCRIPTION:
PEDERNALES RIVER 323.0
END DESCRIPTION:
XS GIS Cut Line= 3
      3005959.42     10117870.97      3008751.57     10117822.24
      3013641.82     10119945.32
#Sta/Elev= 30
   637.9  874.37  1079.5  857.57  1286.2  844.49  1502.7  826.16  1833.3  812.84
  2254.2  812.86  2571.5  802.82  3424.6  787.85    3846  773.47    4163  764.14
  4425.3  755.35  4539.1  738.59  4605.9  707.48  4615.4  704.98  4699.5  683.06
  5247.7  683.95  5277.4  708.33  5282.9   713.5  5313.1  709.78  5335.2  757.47
    5589  762.71  5761.2  745.49  6032.8  778.14    7227  821.54  7308.1  815.31
  7853.8  860.77  8017.4  870.39  8162.9  884.38  8602.7  935.47  8761.7  940.39
#Mann= 19 ,-1 , 0
   637.9     .05       0  1079.5     .16       0  1286.2      .1       0
  1502.7      .1       0  1833.3     .16       0  2254.2      .1       0
  2571.5     .16       0  3424.6     .16       0    3846      .1       0
    4163     .05       0  4605.9    .033       0  5282.9     .05       0
    5589     .16       0  6032.8     .05       0    7227     .16       0
  7853.8     .05       0  8017.4     .08       0  8162.9     .05       0
  8602.7     .08       0
Bank Sta=4615.4,5277.4
XS Rating Curve= 0 ,0
Exp/Cntr=0.3,0.1

Type RM Length L Ch R = 1 ,32180   ,2465,2465,2465
BEGIN DESCRIPTION:
PEDERNALES RIVER 324.0
END DESCRIPTION:
XS GIS Cut Line= 3
      3005832.31     10118036.04      3007128.59     10119343.76
      3013782.04     10122071.97
#Sta/Elev= 30
  1106.1  871.28  1336.3  858.54  1957.4   827.8  2544.3  832.48  2745.5  838.34
  3224.5  805.49    3836  785.91  4491.5  760.93  4648.5  753.24    4655  725.55
  4665.8     709  4687.4  705.34  4762.8  683.23  5278.2  684.19  5331.6  698.33
  5346.7  705.24  5379.1  730.04  5422.3  741.58  5644.9  763.97  5791.2  765.36
  6064.3  769.03  6406.4  781.27  6903.2  804.56  7279.6  834.92  7797.8  850.47
  7951.7  852.67  8787.4  826.48  9615.8  871.84 10122.7   912.2 10138.5  912.71
#Mann= 17 ,-1 , 0
  1106.1     .05       0  1336.3     .16       0  2544.3      .1       0
  2745.5      .1       0  3224.5      .1       0    3836      .1       0
  4491.5      .1       0  4687.4    .033       0  5331.6     .16       0
  5644.9     .08       0  5791.2     .16       0  6064.3     .05       0
  6406.4     .05       0  6903.2     .16       0  7797.8     .05       0
  7951.7     .16       0 10122.7      .1       0
Bank Sta=4687.4,5346.7
XS Rating Curve= 0 ,0
Exp/Cntr=0.3,0.1

Type RM Length L Ch R = 1 ,29715   ,3060,3060,3060
BEGIN DESCRIPTION:
PEDERNALES RIVER 325.0
END DESCRIPTION:
XS GIS Cut Line= 4
      3005016.01     10118345.37      3006055.87     10121292.22
      3012075.05     10124491.72      3013727.52     10124234.43
#Sta/Elev= 30
    -580  861.31 -550.05  859.94 -340.39  853.07 -240.55  858.93  378.44  850.11
  638.02  841.76 1296.95   838.5 1656.36  838.74 1945.89  825.15 2205.46  814.36
 2534.93  796.29 2774.82  792.06 2874.78  790.89 4144.29  756.92 4444.17  756.18
 4574.12  743.73 4594.11  722.79  4648.5  702.44  4708.8  684.72  4862.4  683.39
  5307.2  684.32  5367.4  693.02  5389.4  702.83 5513.74  749.74 5573.72  756.75
 5983.56  772.33  6623.3   776.5 6943.17  778.29 7522.94  783.12 8032.74  799.96
#Mann= 14 ,-1 , 0
    -580     .05       0 -550.05     .05       0  378.44      .1       0
  638.02     .05       0 1296.95      .1       0 1945.89     .05       0
 2205.46     .05       0 2774.82      .1       0 2874.78     .05       0
  4648.5    .033       0  5389.4     .16       0  6623.3     .05       0
 6943.17     .05       0 7522.94      .1       0
Bank Sta=4648.5,5389.4
XS Rating Curve= 0 ,0
Exp/Cntr=0.3,0.1

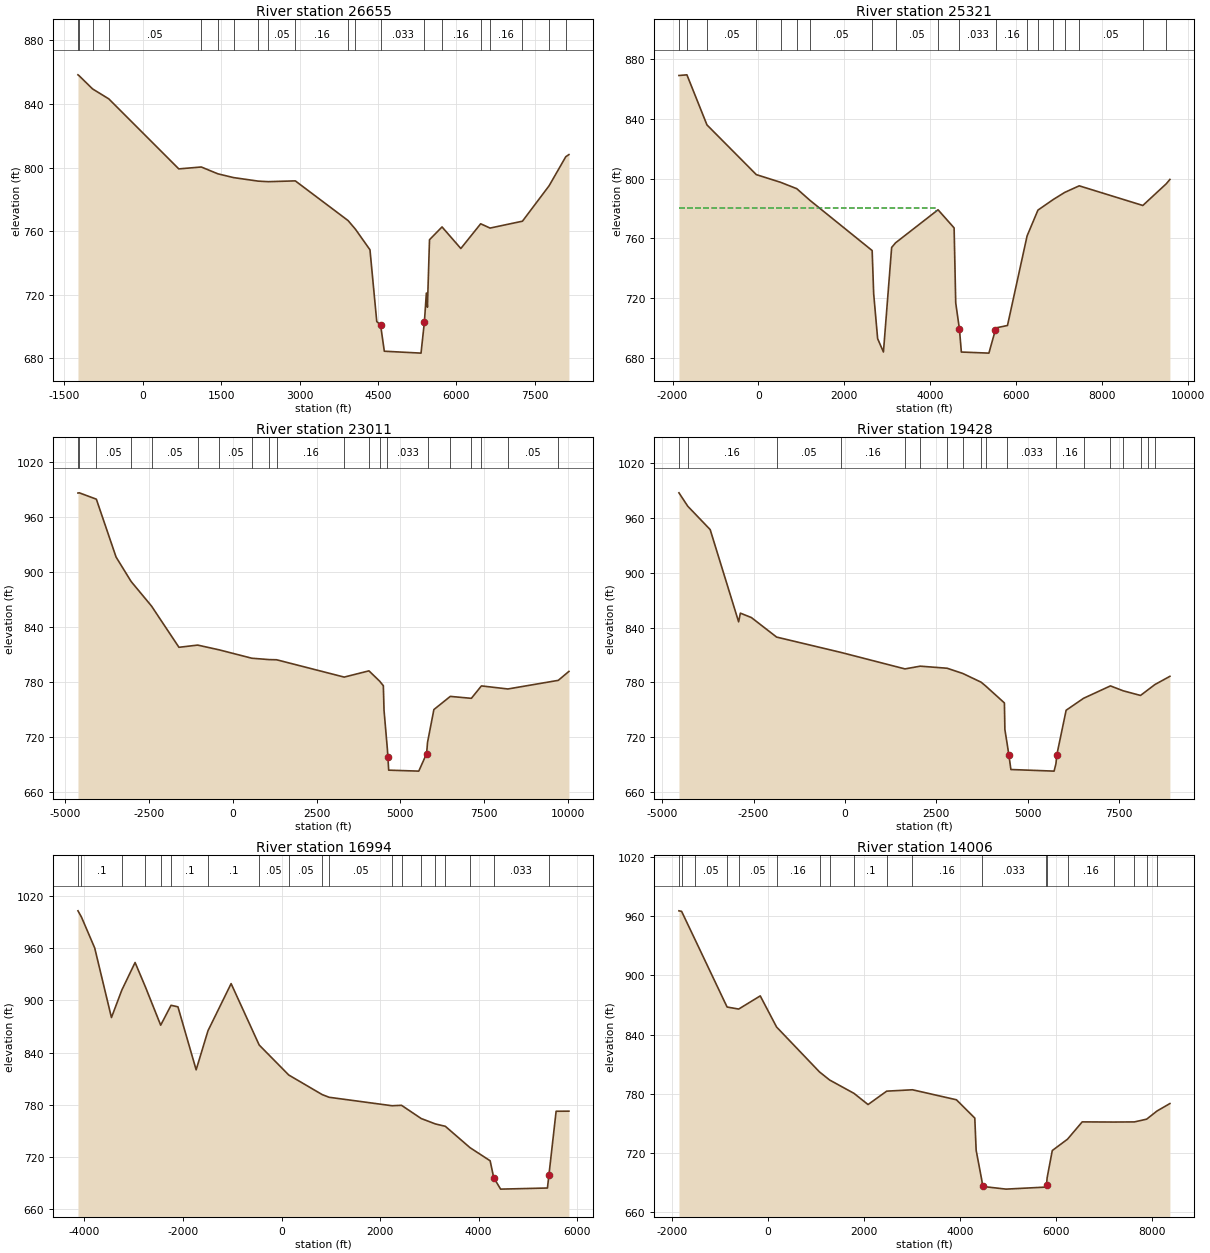
Type RM Length L Ch R = 1 ,26655   ,1334,1334,1334
BEGIN DESCRIPTION:
PEDERNALES RIVER 326.0
END DESCRIPTION:
XS GIS Cut Line= 3
      3004755.43     10118359.49      3004960.33      10122841.1
      3008072.65     10126629.11
#Sta/Elev= 30
   -1238  858.34-1218.02  857.84 -958.23  849.46 -648.49  843.21  690.39  799.13
 1120.03  800.33 1439.77  796.01 1739.52  793.65 2209.12  791.44 2398.97  791.09
 2918.53  791.59 3927.31  766.63 4067.12  761.24 4346.73  748.22 4476.54  703.03
  4549.2  700.93  4620.9  684.38  5323.1  683.18  5387.7  702.88 5425.22     721
 5445.19  712.09 5485.14  754.55  5724.8  762.61  6084.3  749.02 6463.77  764.59
 6643.52  761.89 7262.66  766.22 7771.96  788.49 8091.52   806.8 8151.44  808.13
#Mann= 20 ,-1 , 0
   -1238     .16       0-1218.02     .16       0 -958.23     .16       0
 -648.49     .05       0 1120.03      .1       0 1439.77      .1       0
 1739.52     .05       0 2209.12      .1       0 2398.97     .05       0
 2918.53     .16       0 3927.31     .05       0 4067.12     .16       0
  4549.2    .033       0  5387.7     .16       0  5724.8     .16       0
 6463.77      .1       0 6643.52     .16       0 7262.66     .05       0
 7771.96      .1       0 8091.52     .05       0
Bank Sta=4549.2,5387.7
XS Rating Curve= 0 ,0
Exp/Cntr=0.3,0.1

Type RM Length L Ch R = 1 ,25321   ,2310,2310,2310
BEGIN DESCRIPTION:
PEDERNALES RIVER 327.0
END DESCRIPTION:
XS GIS Cut Line= 5
      3000920.34     10118928.29       3002964.3     10122104.59
      3004273.48     10123631.17       3006337.3     10127302.45
      3007744.82     10127085.75
#Sta/Elev= 30
 -1849.9  868.74 -1664.5  869.19 -1198.1  835.77     -49  802.59   513.2  797.49
   891.6  793.22  1197.8  785.45  2645.7  751.93  2681.1  723.13  2773.3  693.15
  2908.3  684.23  3099.3  753.99  3189.8  757.08  4178.8  779.14  4552.7  767.04
  4590.3  717.03    4677  699.39  4721.3  684.21  5362.1  683.48  5514.1  699.04
    5530  700.34  5794.6  701.92  6250.7  761.68  6503.6  778.92  6862.2  786.04
  7129.1  790.77  7463.7  795.12  8944.1  782.01  9490.4  796.52    9574  799.39
#Mann= 19 ,-1 , 0
 -1849.9     .08       0 -1664.5     .05       0 -1198.1     .05       0
     -49     .05       0   513.2     .16       0   891.6      .1       0
  1197.8     .05       0  2645.7     .16       0  3189.8     .05       0
  4178.8     .16       0    4677    .033       0    5530     .16       0
  6250.7     .08       0  6503.6     .05       0  6862.2     .05       0
  7129.1     .08       0  7463.7     .05       0  8944.1      .1       0
  9490.4      .1       0
#XS Ineff= 2 , 0
         4122.73  780.16
Permanent Ineff=
       F       F
Bank Sta=4677,5514.1
XS Rating Curve= 0 ,0
Exp/Cntr=0.3,0.1

Type RM Length L Ch R = 1 ,23011   ,3583,3583,3583
BEGIN DESCRIPTION:
PEDERNALES RIVER 328.0
END DESCRIPTION:
XS GIS Cut Line= 4
      2994266.93     10126293.65      3000329.67     10124571.88
      3006200.98     10127795.53      3007770.29     10127242.08
#Sta/Elev= 30
   -4626  985.87-4586.05   986.1-4076.65  979.18-3487.35  916.13-3037.89  889.51
-2428.61  862.75-1609.58  817.83-1050.25  820.23    -411  815.09567.8398  805.93
 1087.22  804.43 1306.96  804.26 3326.06  785.38 4065.84  792.18 4385.75  780.91
 4495.71  775.99 4515.71  749.37 4615.68  707.05  4631.9  698.64  4654.7  684.01
  5553.6  682.95    5788  702.04 5815.33  714.28 6005.27  750.01 6495.13  764.35
 7124.94  762.25 7424.86  775.79 8214.62  772.43 9719.71  781.8210038.56  791.57
#Mann= 20 ,-1 , 0
   -4626     .05       0-4586.05     .05       0-4076.65     .05       0
-3037.89     .16       0-2428.61     .05       0-1050.25     .16       0
    -411     .05       0567.8398     .16       0 1087.22     .05       0
 1306.96     .16       0 3326.06     .16       0 4065.84     .16       0
 4385.75      .1       0 4615.68    .033       0 5815.33      .1       0
 6495.13     .08       0 7124.94      .1       0 7424.86      .1       0
 8214.62     .05       0 9719.71      .1       0
Bank Sta=4631.9,5788
XS Rating Curve= 0 ,0
Exp/Cntr=0.3,0.1

Type RM Length L Ch R = 1 ,19428   ,2434,2434,2434
BEGIN DESCRIPTION:
PEDERNALES RIVER 331.0
END DESCRIPTION:
XS GIS Cut Line= 4
      2995225.64     10130888.67      3001601.44     10129118.71
      3003236.91     10129529.57      3007868.09     10127331.85
#Sta/Elev= 30
 -4540.9  987.28 -4298.8   972.6   -3687   947.1 -2908.6  846.21 -2860.4   855.7
 -2560.3  850.91 -1869.5  829.53   -98.1  812.64  1640.4  794.73  2059.7  797.72
  2794.8  795.45  3219.8  789.79  3724.5  780.21  3854.4  775.86  4361.7  757.51
  4374.5  728.46  4437.2  712.68  4482.7  700.68  4539.2   684.7  5720.4  682.94
  5771.6  691.11  5794.4  700.56  6049.9  749.51  6526.7  762.59  7261.2  776.14
  7609.9  770.79  8084.7   765.7  8300.8  772.25  8478.8  777.64  8888.5  786.61
#Mann= 18 ,-1 , 0
 -4540.9      .1       0 -4298.8     .16       0 -1869.5     .05       0
   -98.1     .16       0  1640.4     .05       0  2059.7     .16       0
  2794.8     .05       0  3219.8     .16       0  3724.5     .05       0
  3854.4     .05       0  4437.2    .033       0  5771.6     .16       0
  6526.7     .05       0  7261.2      .1       0  7609.9     .05       0
  8084.7      .1       0  8300.8     .05       0  8478.8      .1       0
Bank Sta=4482.7,5794.4
XS Rating Curve= 0 ,0
Exp/Cntr=0.3,0.1

Type RM Length L Ch R = 1 ,16994   ,2988,2988,2988
BEGIN DESCRIPTION:
PEDERNALES RIVER 332.0
END DESCRIPTION:
XS GIS Cut Line= 3
      2996894.49     10133653.97      3000688.72     10131074.13
      3006064.14     10130967.13
#Sta/Elev= 30
   -4132 1002.81-4062.03  995.78-3792.13  960.13-3452.26  880.23-3242.34  911.68
-2972.44  943.46-2762.52  915.34-2452.64  871.45-2242.72  894.31-2102.77  892.54
-1732.91  820.19   -1493  865.04-1023.17   919.2-453.389  848.67146.3799  814.23
826.0601  791.71965.9902  788.64  2245.3  778.91  2435.2  779.43 2834.98  764.24
 3124.83  757.99 3324.72  755.31 3824.45  730.84 4234.24   715.7  4307.3   696.3
  4447.1  683.14  5397.5  684.42  5427.5  699.26 5573.58  772.58 5833.45  772.69
#Mann= 19 ,-1 , 0
   -4132      .1       0-4062.03      .1       0-3242.34      .1       0
-2762.52      .1       0-2452.64     .16       0-2242.72      .1       0
   -1493      .1       0-453.389     .05       0146.3799     .05       0
826.0601      .1       0965.9902     .05       0  2245.3     .05       0
  2435.2      .1       0 2834.98     .05       0 3124.83     .08       0
 3324.72     .05       0 3824.45     .08       0  4307.3    .033       0
  5427.5     .05       0
Bank Sta=4307.3,5427.5
XS Rating Curve= 0 ,0
Exp/Cntr=0.3,0.1

Type RM Length L Ch R = 1 ,14006   ,3605,3605,3605
BEGIN DESCRIPTION:
PEDERNALES RIVER 333.0
END DESCRIPTION:
XS GIS Cut Line= 4
      2998175.45     10136668.19      3003058.75     10134719.06
      3006113.82     10131944.53      3006256.69     10131117.62
#Sta/Elev= 30
 -1855.3  965.42 -1800.1  964.89   -1529  937.18  -852.8  867.92  -611.5  865.86
  -162.1  879.19   177.9  847.65  1072.1  802.12  1281.5  793.98  1791.7  780.36
  2082.5  769.07  2470.6  782.65  3008.1  784.05    3923  773.91  4305.5  755.38
  4333.9  722.74  4454.2  691.69  4468.4  686.07    4956  683.35  5792.2  685.44
  5798.9  687.59  5812.2  694.89  5919.2  722.46  6237.5  734.02  6542.3   751.5
  7198.7  751.34  7630.2  751.48  7884.5  754.26  8099.5  762.52  8368.7  770.09
#Mann= 19 ,-1 , 0
 -1855.3     .05       0 -1800.1     .08       0   -1529     .05       0
  -852.8      .1       0  -611.5     .05       0   177.9     .16       0
  1072.1      .1       0  1281.5     .16       0  1791.7      .1       0
  2470.6     .16       0  3008.1     .16       0  4454.2    .033       0
  5792.2     .05       0  5812.2     .16       0  6237.5     .16       0
  7198.7     .05       0  7630.2     .08       0  7884.5     .05       0
  8099.5     .08       0
Bank Sta=4468.4,5798.9
XS Rating Curve= 0 ,0
Exp/Cntr=0.3,0.1

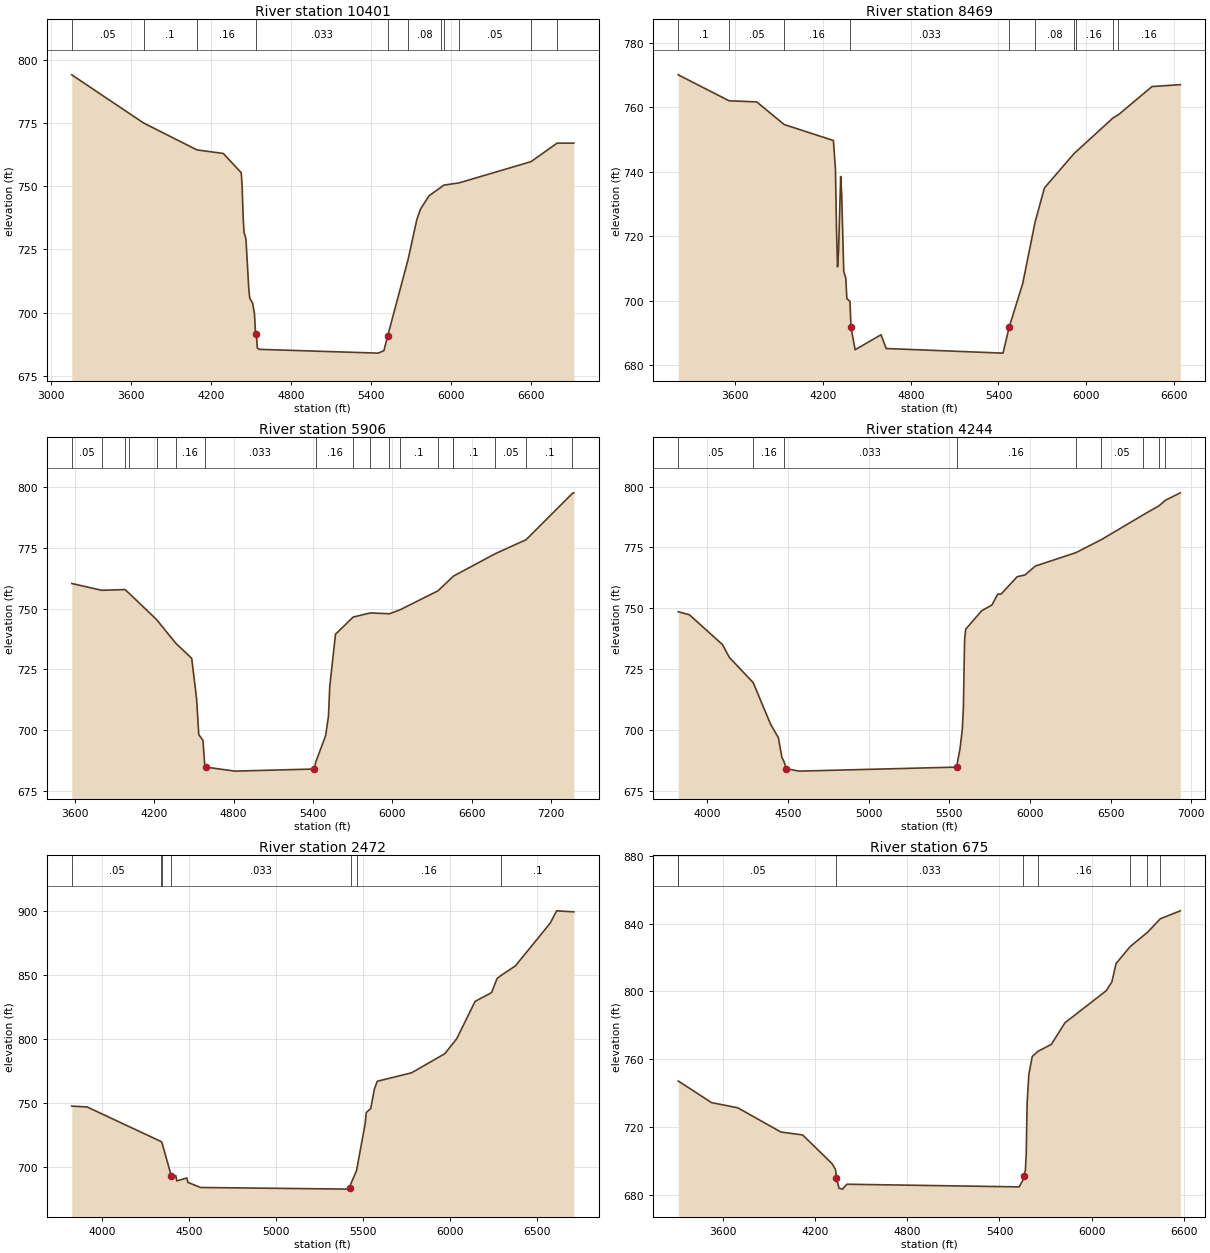
Type RM Length L Ch R = 1 ,10401   ,1932,1932,1932
BEGIN DESCRIPTION:
PEDERNALES RIVER 334.0
END DESCRIPTION:
XS GIS Cut Line= 3
      3008297.28     10134169.31      3006293.14      10131906.1
      3006330.97     10131164.39
#Sta/Elev= 30
  3154.6  794.02  3693.5  774.98  4092.9  764.36  4291.2  762.94  4425.9  755.32
  4432.5  749.84  4440.1  737.65  4446.8  731.77    4461  729.17  4482.7  709.11
  4489.4  705.75  4511.1  703.78  4524.5  699.74  4532.1  692.87  4538.8  691.68
  4546.3  686.05  4560.5  685.53  5452.7  684.03  5495.6  684.99  5524.1  690.83
  5676.7  720.95  5743.2  736.93  5771.6  741.09  5835.2  746.28  5926.9  749.68
    5944  750.41  6062.1  751.35  6598.7   759.7  6795.2  767.03  6920.3  767.03
#Mann= 11 ,-1 , 0
  3154.6     .05       0  3693.5      .1       0  4092.9     .16       0
  4538.8    .033       0  5524.1     .05       0  5676.7     .08       0
  5926.9     .05       0    5944      .1       0  6062.1     .05       0
  6598.7     .16       0  6795.2     .05       0
Bank Sta=4538.8,5524.1
XS Rating Curve= 0 ,0
Exp/Cntr=0.3,0.1

Type RM Length L Ch R = 1 ,8469    ,2563,2563,2563
BEGIN DESCRIPTION:
PEDERNALES RIVER 335.0
END DESCRIPTION:
XS GIS Cut Line= 3
      3009487.17     10132411.43      3008756.15     10131782.18
       3006998.2     10130050.43
#Sta/Elev= 30
  3210.9  770.02  3558.2  761.98  3747.5  761.62  3935.2  754.61  4271.7  749.65
  4285.8  740.63  4292.9   721.9  4299.9  710.47  4307.1  715.63  4321.2  738.48
  4328.2  732.98  4342.4  709.07  4356.5  706.95  4363.6  700.62  4384.8  699.77
  4391.9  691.73  4420.2  684.76    4597  689.42  4632.4  685.15  5431.2  683.72
  5473.8  691.88  5565.7  705.29  5650.3  724.35  5714.3  734.95  5916.3  745.58
  5927.5  746.04  6182.3  756.62  6220.1  757.65  6449.6  766.38  6643.1  766.98
#Mann= 10 ,-1 , 0
  3210.9      .1       0  3558.2     .05       0  3935.2     .16       0
  4384.8    .033       0  5473.8     .16       0  5650.3     .08       0
  5916.3     .05       0  5927.5     .16       0  6182.3     .05       0
  6220.1     .16       0
Bank Sta=4391.9,5473.8
XS Rating Curve= 0 ,0
Exp/Cntr=0.3,0.1

Type RM Length L Ch R = 1 ,5906    ,1662,1662,1662
BEGIN DESCRIPTION:
PEDERNALES RIVER 336.0
END DESCRIPTION:
XS GIS Cut Line= 3
      3010449.46     10129325.09      3008186.72     10128490.97
      3007982.35     10127121.32
#Sta/Elev= 30
  3576.9  760.33    3804  757.53  3979.5  757.83  4011.2  756.25  4218.3  745.48
  4363.5  735.71  4483.9  729.52  4520.8  712.84  4537.2  698.12  4569.1  695.71
  4581.7   686.1  4590.4  684.75    4809  683.08  5411.1  683.95  5421.9  686.81
  5496.4   697.7  5517.7  705.59  5527.7  717.93    5571  739.44  5704.8  746.52
  5834.7  748.21  5979.2  747.87  6062.4  749.58  6346.1  757.32  6462.5  763.34
  6462.9  763.37  6777.4  772.55    7012  778.36  7362.8  797.45  7373.3  797.66
#Mann= 18 ,-1 , 0
  3576.9     .05       0    3804     .16       0  3979.5      .1       0
  4011.2     .16       0  4218.3     .05       0  4363.5     .16       0
  4581.7    .033       0  5421.9     .16       0  5704.8      .1       0
  5834.7     .05       0  5979.2     .16       0  6062.4      .1       0
  6346.1     .05       0  6462.5     .16       0  6462.9      .1       0
  6777.4     .05       0    7012      .1       0  7362.8     .16       0
Bank Sta=4590.4,5411.1
XS Rating Curve= 0 ,0
Exp/Cntr=0.3,0.1

Type RM Length L Ch R = 1 ,4244    ,1772,1772,1772
BEGIN DESCRIPTION:
PEDERNALES RIVER 337.0
END DESCRIPTION:
XS GIS Cut Line= 2
      3010702.98     10128306.65      3008602.54     10126010.28
#Sta/Elev= 30
  3820.1  748.52  3889.2  747.26  4094.6  734.99  4136.5  729.77    4285  719.33
  4391.8  702.37  4441.2  696.66  4462.1  688.76  4476.3  686.76  4490.5  683.97
  4568.6  682.97  5545.2  684.62  5566.6  692.13  5580.8  700.08  5587.6  709.03
    5595  736.97  5601.8  741.31  5701.1  748.93  5764.6  751.28  5800.3  755.71
  5821.3  755.77  5920.6  762.89  5969.9  763.65  6033.4  767.28  6284.9   772.8
  6441.5  778.11  6700.6  788.28    6801   792.1  6839.1  794.31  6932.2   797.4
#Mann= 9 ,-1 , 0
  3820.1     .05       0    4285     .16       0  4476.3    .033       0
  5545.2     .16       0  6284.9      .1       0  6441.5     .05       0
  6700.6     .16       0    6801      .1       0  6839.1     .05       0
Bank Sta=4490.5,5545.2
XS Rating Curve= 0 ,0
Exp/Cntr=0.3,0.1

Type RM Length L Ch R = 1 ,2472    ,1797,1797,1797
BEGIN DESCRIPTION:
PEDERNALES RIVER 338.0
END DESCRIPTION:
XS GIS Cut Line= 2
      3011227.61     10128156.88      3012123.98     10125414.25
#Sta/Elev= 30
  3825.1  747.54  3913.1  746.91  4339.3  719.86  4344.3  718.69  4396.5  693.37
  4423.1  693.32  4428.4  689.23  4486.8  691.48  4492.1  688.07  4564.9  684.08
  5421.5  682.79  5424.8  683.29  5427.5  686.51  5461.6  697.19  5511.7  734.26
  5517.4   742.5  5543.3   745.7  5564.3  760.99  5581.1  766.95  5777.7  773.51
  5968.9  788.43  6037.9  800.24  6142.9  829.23  6237.6  836.09  6269.2  847.07
  6291.1  849.38  6374.4  856.91  6574.3  890.22  6611.7  899.89  6710.5   899.1
#Mann= 7 ,-1 , 0
  3825.1     .05       0  4339.3     .16       0  4344.3     .08       0
  4396.5    .033       0  5427.5     .05       0  5461.6     .16       0
  6291.1      .1       0
Bank Sta=4396.5,5424.8
XS Rating Curve= 0 ,0
Exp/Cntr=0.3,0.1

Type RM Length L Ch R = 1 ,675     ,0,0,0
BEGIN DESCRIPTION:
Mapping XS 2bef7eef
END DESCRIPTION:
XS GIS Cut Line= 4
      3011562.05     10128175.69      3012367.63     10128140.97
      3013791.24     10127467.36      3014256.11     10126718.01
#Sta/Elev= 30
  3312.1  747.19  3313.2  747.17  3528.7  734.47  3698.9  731.43  3979.1  717.15
    4121  715.39  4311.8   698.5  4334.6  695.03  4340.6  689.77  4357.3     684
  4379.8  683.46  4408.4  686.35  5528.2  684.78  5550.9  688.59  5557.5  691.31
  5568.2  694.44  5573.7  704.21  5579.7   734.5  5590.7  751.03  5612.9   761.7
  5650.7  764.75  5737.2  768.85  5825.8  781.59  6093.9  800.46  6130.5  805.68
  6157.7  816.48  6249.2   826.5  6361.9   834.9  6445.4  842.89  6575.2  847.57
#Mann= 8 ,-1 , 0
  3312.1     .08       0  3313.2     .05       0  4340.6    .033       0
  5550.9     .05       0  5650.7     .16       0  6249.2     .08       0
  6361.9      .1       0  6445.4     .05       0
Bank Sta=4340.6,5557.5
XS Rating Curve= 0 ,0
Exp/Cntr=0.3,0.1

Chan Stop Cuts=-1
Use User Specified Reach Order=0
Composite Channel Slope=5

--- PEDERNALES RIVER.g02 (geometry) ---

Geom Title=del
Program Version=4.10

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
River Reach=PEDERNALES RIVER,Reach-1

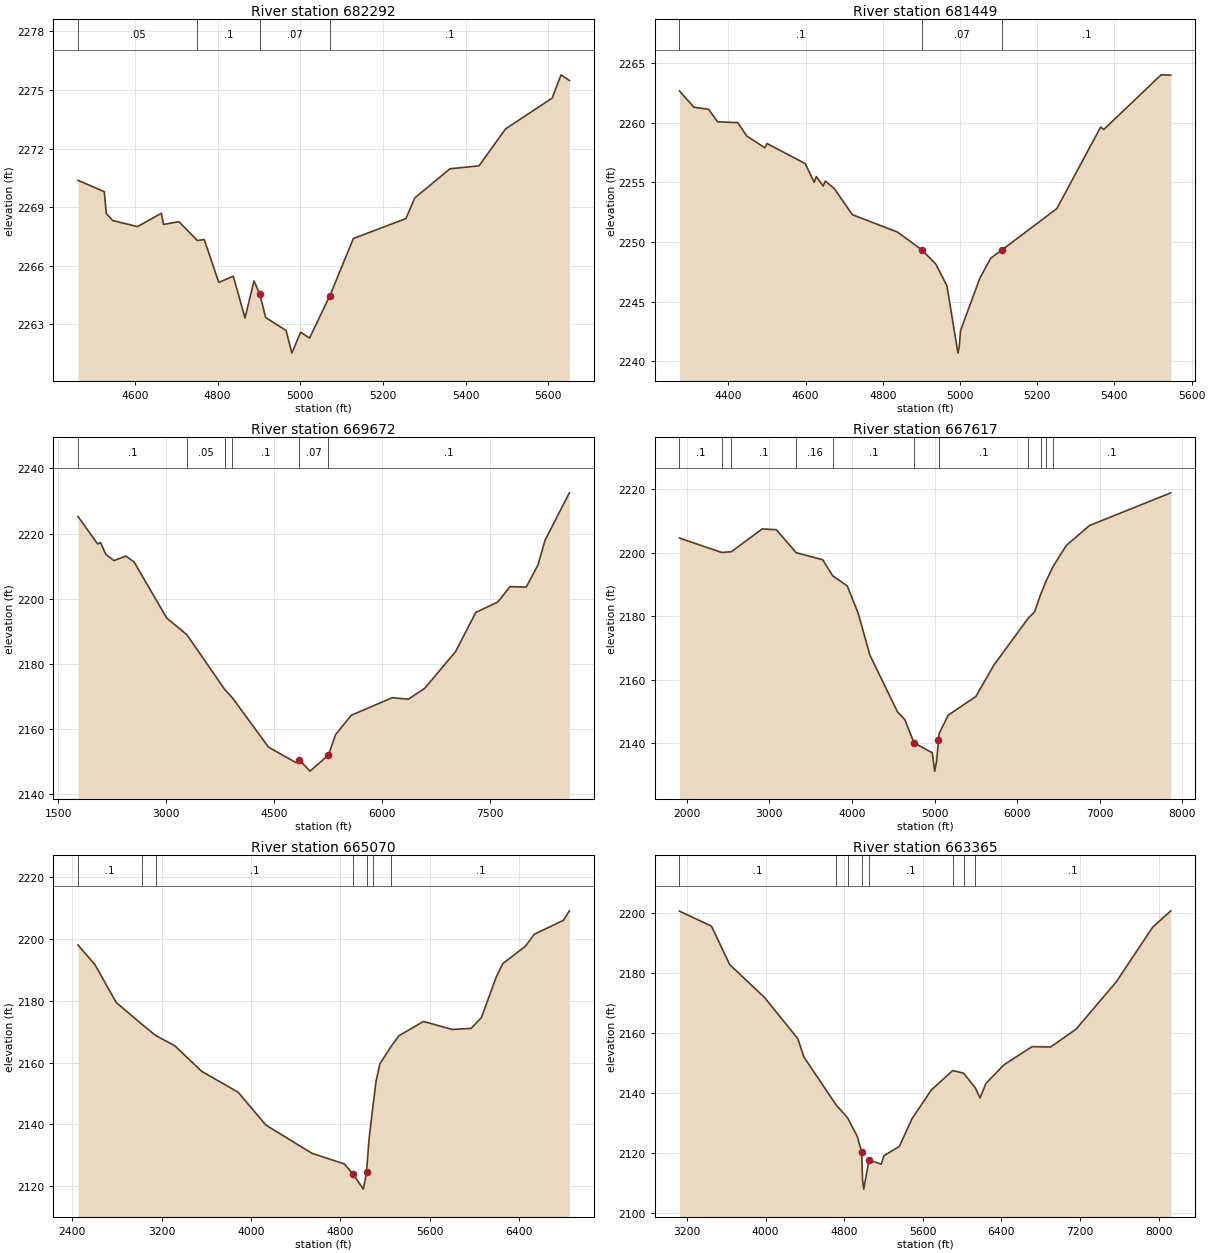
Type RM Length L Ch R = 1 ,682292  ,843,843,843
BEGIN DESCRIPTION:
PEDERNALES RIVER 1.0
END DESCRIPTION:
XS GIS Cut Line= 4
      2614488.46     10060927.43      2614507.29     10060671.57
      2614947.41     10060185.36      2615134.51     10059981.21
#Sta/Elev= 30
  4461.9 2270.38  4525.5  2269.8  4530.5 2268.68  4545.8 2268.32    4606 2268.01
  4663.8 2268.69  4668.8 2268.12  4706.3 2268.26  4750.7  2267.3  4767.6 2267.34
  4802.7 2265.15  4837.8 2265.47  4866.2 2263.33  4887.9 2265.23  4902.1 2264.54
  4916.2 2263.35  4965.6 2262.69  4979.5 2261.53  5000.7  2262.6  5022.4  2262.3
  5071.7 2264.48  5128.5  2267.4  5255.5 2268.42  5277.2 2269.48  5362.3 2270.97
  5432.6 2271.12  5496.7 2273.01  5609.6 2274.59  5631.1 2275.78  5651.2 2275.49
#Mann= 4 ,-1 , 0
  4461.9     .05       0  4750.7      .1       0  4902.1     .07       0
  5071.7      .1       0
Bank Sta=4902.1,5071.7
XS Rating Curve= 0 ,0
Exp/Cntr=0.3,0.1

Type RM Length L Ch R = 1 ,681449  ,811,811,811
BEGIN DESCRIPTION:
PEDERNALES RIVER 3.0
END DESCRIPTION:
XS GIS Cut Line= 3
      2614644.04     10061378.94      2615106.56     10061176.06
       2615702.6     10060692.64
#Sta/Elev= 30
  4273.5 2262.67  4311.1  2261.3    4349 2261.13  4372.4 2260.08  4424.6 2260.01
  4447.9 2258.89  4494.7  2257.9  4500.1 2258.26  4599.1 2256.58  4622.4 2255.01
  4627.9 2255.49  4645.8 2254.69  4651.3 2255.11  4674.6 2254.48  4721.4 2252.29
  4838.4 2250.83  4902.3 2249.31  4937.5 2248.15  4966.3 2246.32  4994.8 2240.68
    4998 2241.18  5001.5 2242.58  5051.4 2246.96  5079.8 2248.65  5108.5 2249.33
  5250.8  2252.8  5364.3 2259.64  5372.2 2259.43  5520.9 2264.02    5546 2263.99
#Mann= 3 , 0 , 0
  4273.5      .1       0  4902.3     .07       0  5108.5      .1       0
Bank Sta=4902.3,5108.5
XS Rating Curve= 0 ,0
Exp/Cntr=0.3,0.1

Type RM Length L Ch R = 1 ,669672  ,2055,2055,2055
BEGIN DESCRIPTION:
PEDERNALES RIVER 11.0
END DESCRIPTION:
XS GIS Cut Line= 3
      2612968.69     10071195.93      2617718.47     10070349.38
      2619200.59      10068987.7
#Sta/Elev= 30
  1771.9 2225.27  2045.9 2216.83  2086.6 2217.26  2158.8 2213.66  2271.7 2211.71
  2438.4 2213.12  2551.3 2211.34  3007.8 2194.05  3286.1    2189  3816.6 2172.06
  3822.6 2171.96  3921.4 2169.57  4422.8 2154.45  4808.8 2149.65  4849.4 2150.59
  5000.3 2147.08  5255.7 2151.98  5357.3 2158.34    5575 2164.24  6144.4 2169.62
  6370.1 2169.18  6596.5  2172.5  7025.2 2183.77  7308.2 2195.83  7612.8 2198.98
  7782.3 2203.72  8008.8 2203.59  8171.8 2210.37  8270.7 2217.96  8609.2 2232.53
#Mann= 7 ,-1 , 0
  1771.9      .1       0  3286.1     .05       0  3816.6      .1       0
  3822.6     .05       0  3921.4      .1       0  4849.4     .07       0
  5255.7      .1       0
Bank Sta=4849.4,5255.7
XS Rating Curve= 0 ,0
Exp/Cntr=0.3,0.1

Type RM Length L Ch R = 1 ,667617  ,2547,2547,2547
BEGIN DESCRIPTION:
PEDERNALES RIVER 12.0
END DESCRIPTION:
XS GIS Cut Line= 2
      2614546.53     10073575.76      2619804.36     10070799.91
#Sta/Elev= 30
  1913.3 2204.66  2425.5 2200.11  2541.5 2200.35  2914.9 2207.53  3085.4 2207.29
  3326.8 2200.04  3646.6 2197.84    3768 2192.76  3943.5 2189.61  4075.6 2181.02
  4218.4 2167.76  4550.3 2149.98  4640.7 2147.47  4751.9 2140.15  4972.1 2137.05
  5002.3 2131.25  5025.2 2134.36  5047.8 2140.99  5054.5    2143  5164.6 2148.85
  5499.9 2154.77  5720.1 2164.72  6135.7 2179.49  6209.5 2181.37    6285 2186.98
  6353.5 2191.32  6433.4 2195.64  6594.5 2202.34  6875.1 2208.61  7858.9  2218.9
#Mann= 11 ,-1 , 0
  1913.3      .1       0  2425.5     .05       0  2541.5      .1       0
  3326.8     .16       0    3768      .1       0  4751.9     .07       0
  5054.5      .1       0  6135.7     .16       0    6285      .1       0
  6353.5     .16       0  6433.4      .1       0
Bank Sta=4751.9,5047.8
XS Rating Curve= 0 ,0
Exp/Cntr=0.3,0.1

Type RM Length L Ch R = 1 ,665070  ,1705,1705,1705
BEGIN DESCRIPTION:
PEDERNALES RIVER 13.0
END DESCRIPTION:
XS GIS Cut Line= 3
      2617362.05     10074789.69      2619870.67     10071867.98
      2620023.97     10071342.09
#Sta/Elev= 30
  2450.2 2198.02  2601.2 2191.72  2792.1 2179.45  3020.4 2172.44  3145.3 2168.77
  3316.7 2165.44  3558.1 2157.16  3884.1 2150.41  4132.1  2139.8  4543.6 2130.68
  4834.4 2127.23  4912.3 2123.97  5004.3 2119.08  5033.1 2124.51  5054.6 2134.84
  5090.8 2145.91  5118.7 2154.03  5153.8 2159.66  5254.2 2165.28  5323.9  2168.7
  5543.4 2173.31  5799.1 2170.72  5969.2 2171.05  6061.3 2174.54  6196.3 2187.85
  6253.4    2192  6455.3 2197.62  6534.7  2201.5  6795.1 2205.98  6848.9 2209.07
#Mann= 7 ,-1 , 0
  2450.2      .1       0  3020.4     .05       0  3145.3      .1       0
  4912.3     .07       0  5033.1      .1       0  5090.8     .16       0
  5254.2      .1       0
Bank Sta=4912.3,5033.1
XS Rating Curve= 0 ,0
Exp/Cntr=0.3,0.1

Type RM Length L Ch R = 1 ,663365  ,997,997,997
BEGIN DESCRIPTION:
PEDERNALES RIVER 14.0
END DESCRIPTION:
XS GIS Cut Line= 3
      2618187.04     10075493.94      2619263.36     10074768.83
      2621072.56       10071535.
#Sta/Elev= 30
  3121.8  2200.8  3448.2 2195.76  3634.1 2182.89  3987.9 2171.93  4326.8 2158.16
  4389.8 2151.98  4719.5 2135.88  4833.2  2131.7  4933.6  2125.4    4977 2120.25
  4986.9 2110.64  4998.4 2107.82  5052.3 2117.56  5176.8 2116.17  5204.6 2119.02
  5360.6 2122.09  5491.1 2131.43  5684.9 2140.92  5904.8 2147.49  6014.8  2146.6
  6132.8 2141.77  6182.8  2138.3  6242.1 2143.15    6426 2149.39  6712.6 2155.47
  6902.1 2155.37  7161.3 2161.34  7572.4 2177.24  7940.1 2195.41  8125.1 2200.89
#Mann= 8 ,-1 , 0
  3121.8      .1       0  4719.5     .05       0  4833.2      .1       0
    4977     .07       0  5052.3      .1       0  5904.8     .16       0
  6014.8     .05       0  6132.8      .1       0
Bank Sta=4977,5052.3
XS Rating Curve= 0 ,0
Exp/Cntr=0.3,0.1